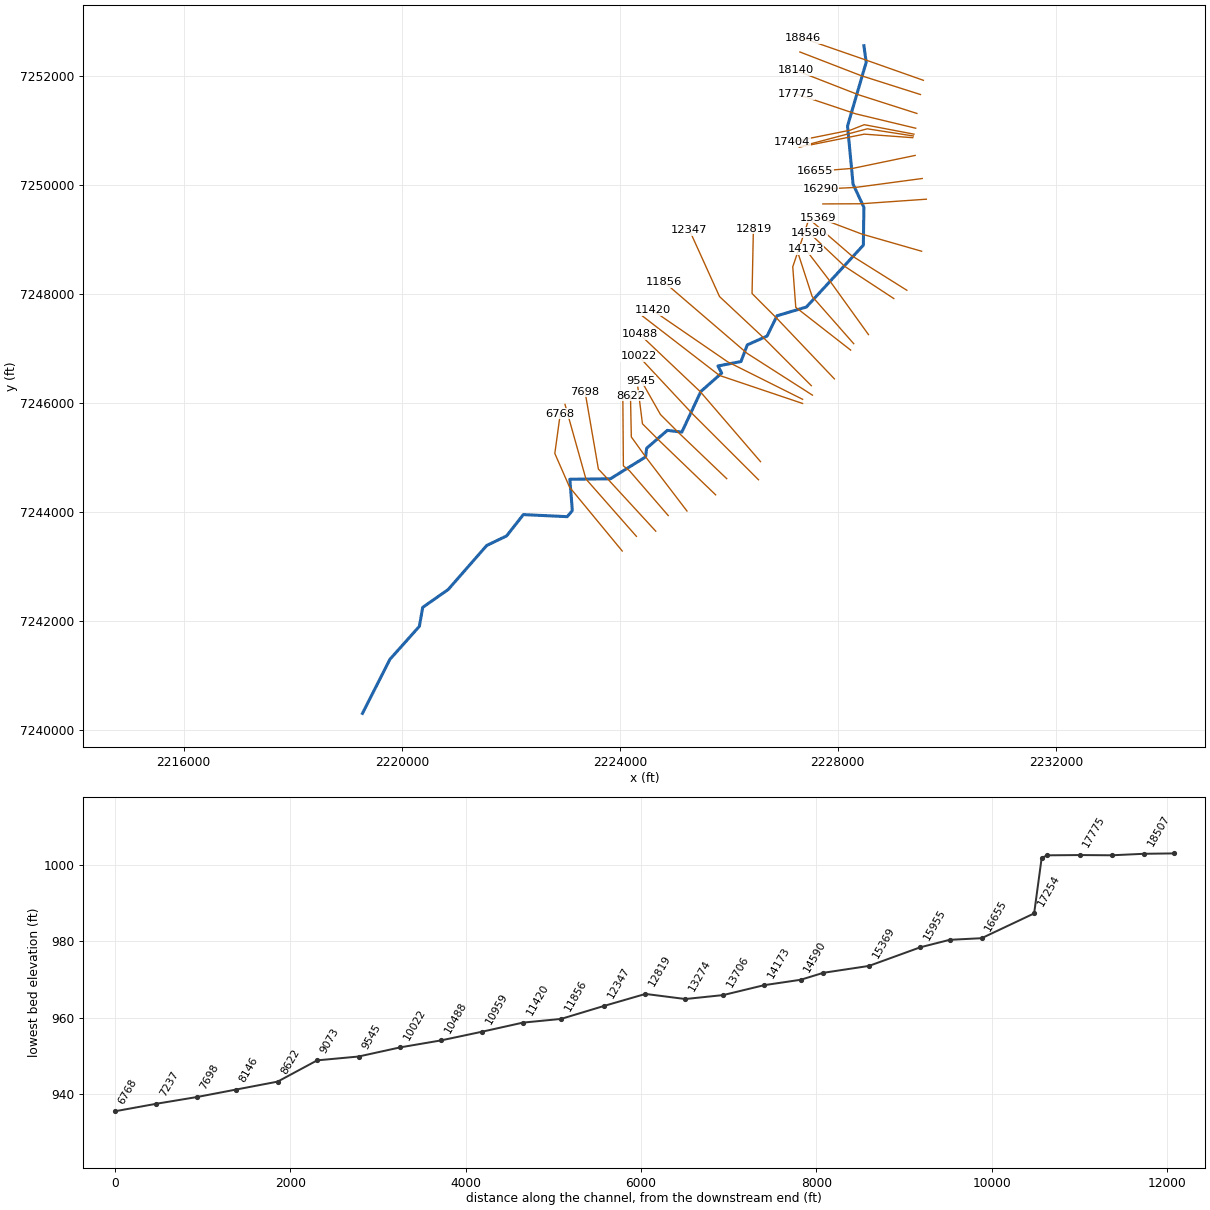
--- BEECHMAN BRANCH.prj (project) ---

Proj Title=BEECHMAN BRANCH Base Level Engineering
Current Plan=p01
Default Exp/Contr=0.3,0.1
English Units
Geom File=g01
Flow File=f01
Plan File=p01
Y Axis Title=Elevation
X Axis Title(PF)=Main Channel Distance
X Axis Title(XS)=Station
BEGIN DESCRIPTION:
BEECHMAN BRANCH
END DESCRIPTION:
DSS Export Rating Curves= 0
DSS Export Rating Curve Sorted= 0
DSS Export Volume Flow Curves= 0
DXF OffsetX= 0
DXF OffsetY= 0
DXF ScaleX= 1
DXF ScaleY= 10

--- BEECHMAN BRANCH.p01 (plan) ---

Plan Title=Multiple Run
Short Identifier=Multiple
Geom File=g01
Flow File=f01
Subcritical Flow
K Sum by GR= 0
Std Step Tol= 0.01
Critical Tol= 0.01
Num of Std Step Trials= 20
Max Error Tol= 0.3
Flow Tol Ratio= 0.001
Split Flow NTrial= 30
Split Flow Tol= 0.02
Split Flow Ratio= 0.02
Log Output Level= 0
Friction Slope Method= 1
Unsteady Friction Slope Method= 2
Unsteady Bridges Friction Slope Method= 1
Parabolic Critical Depth
Global Vel Dist=  1 , 1 , 1
Global Log Level= 0
CheckData=True
Encroach Param= -1, 0, 0, 0
BEGIN DESCRIPTION:
Multiple Run
END DESCRIPTION:

--- BEECHMAN BRANCH.f01 (steady flow) ---

Flow Title=Multiple
Program Version=4.10
Number of Profiles= 7
Profile Names=10-year,25-year,50-year,1pct_min,100-year,1pct_plu,500-year
River Rch & RM=BEECHMAN BRANCH,Reach-1         ,18846
     678     946    1171     720    1436    2865    2166
River Rch & RM=BEECHMAN BRANCH,Reach-1         ,15369
     981    1388    1734    1074    2143    4275    3283
River Rch & RM=BEECHMAN BRANCH,Reach-1         ,7237
    1264    1808    2275    1417    2828    5642    4385
River Rch & RM=BEECHMAN BRANCH,Reach-1         ,496
    1310    1879    2368    1478    2949    5884    4591
Boundary for River Rch & Prof#=BEECHMAN BRANCH,Reach-1         , 1
Up Type= 0
Dn Type= 3
Dn Slope=0.004
Boundary for River Rch & Prof#=BEECHMAN BRANCH,Reach-1         , 2
Up Type= 0
Dn Type= 3
Dn Slope=0.004
Boundary for River Rch & Prof#=BEECHMAN BRANCH,Reach-1         , 3
Up Type= 0
Dn Type= 3
Dn Slope=0.004
Boundary for River Rch & Prof#=BEECHMAN BRANCH,Reach-1         , 4
Up Type= 0
Dn Type= 3
Dn Slope=0.004
Boundary for River Rch & Prof#=BEECHMAN BRANCH,Reach-1         , 5
Up Type= 0
Dn Type= 3
Dn Slope=0.004
Boundary for River Rch & Prof#=BEECHMAN BRANCH,Reach-1         , 6
Up Type= 0
Dn Type= 3
Dn Slope=0.004
Boundary for River Rch & Prof#=BEECHMAN BRANCH,Reach-1         , 7
Up Type= 0
Dn Type= 3
Dn Slope=0.004
DSS Import GetInterval= 0
DSS Import GetPeak= 0
DSS Import FillOption= 0

--- BEECHMAN BRANCH.g01 (geometry) ---

Geom Title=Existing Conditions
Program Version=4.10

River Reach=BEECHMAN BRANCH ,Reach-1
Reach XY= 30
        2228479.        7252560.      2228520.95      7252256.71
      2228178.52      7251085.03       2228280.2       7250020.5
      2228478.61      7249594.84      2228468.81      7248900.32
      2227423.59      7247765.17      2226884.45      7247604.81
       2226702.9      7247232.72      2226339.33      7247070.17
      2226223.56      7246765.18      2225801.44      7246683.81
      2225870.09      7246553.48      2225487.14      7246216.06
       2225138.8      7245470.47      2224872.93      7245502.53
       2224492.2      7245173.73      2224473.82      7245015.41
       2223827.5      7244613.62      2223084.18       7244605.4
      2223129.33      7244030.15      2223035.76      7243919.12
      2222230.64      7243956.85      2221923.39      7243565.59
      2221558.82      7243390.38      2220852.51        7242583.
      2220384.19      7242254.56      2220323.52      7241907.56
      2219782.54      7241301.51        2219279.        7240310.

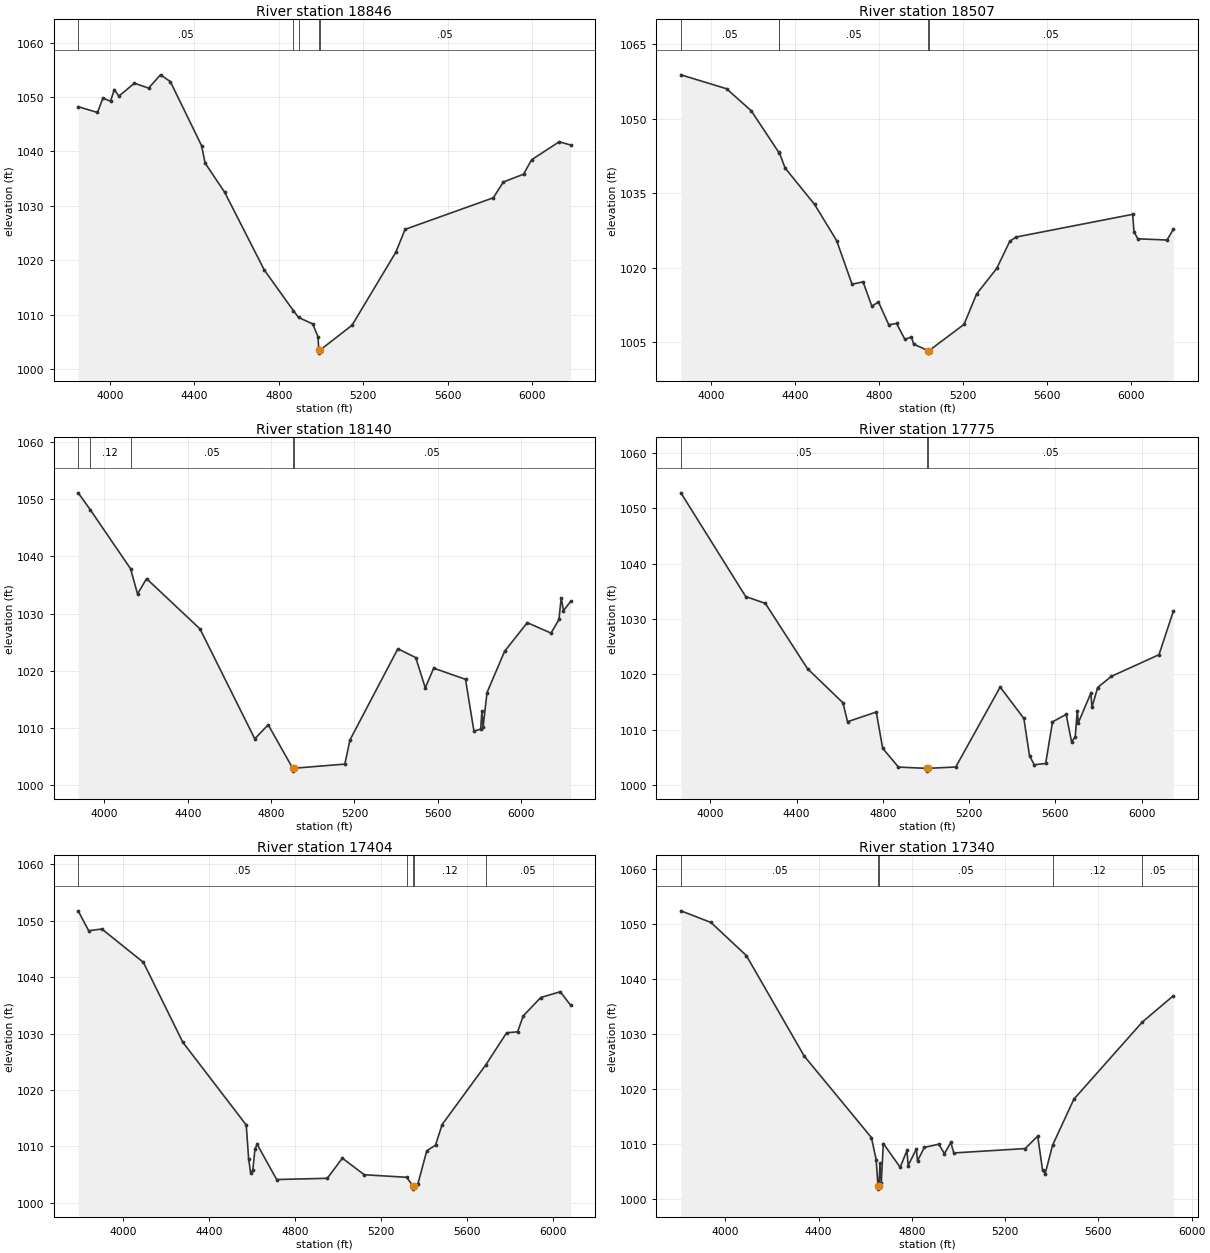
Type RM Length L Ch R = 1 ,18846   ,339,339,339
BEGIN DESCRIPTION:
BEECHMAN BRANCH 41.0
END DESCRIPTION:
XS GIS Cut Line= 3
      2229570.75      7251924.68        2228479.        7252310.
      2227368.19      7252695.03
#Sta/Elev= 30
    3849 1048.24  3940.5 1047.17  3966.2  1049.8  4002.4 1049.25  4020.5 1051.39
  4041.7 1050.17  4115.5 1052.55  4182.7 1051.65  4239.2 1054.09  4285.6 1052.86
  4434.1 1041.05  4450.4 1037.88  4543.2 1032.51    4731 1018.22  4868.6 1010.76
  4893.1 1009.51  4960.4  1008.3  4985.5 1005.95  4989.3 1003.44  4989.5 1002.94
  4993.3 1003.44  5146.9 1008.07  5354.3 1021.49  5398.3 1025.69  5816.1 1031.49
    5864  1034.4  5959.3 1035.82  5997.7 1038.48  6128.6 1041.79  6182.4 1041.19
#Mann= 5 ,-1 , 0
    3849     .05       0  4868.6     .12       0  4893.1     .05       0
  4989.3    .033       0  4993.3     .05       0
Bank Sta=4989.3,4993.3
XS Rating Curve= 0 ,0
Exp/Cntr=0.3,0.1

Type RM Length L Ch R = 1 ,18507   ,367,367,367
BEGIN DESCRIPTION:
BEECHMAN BRANCH 40.0
END DESCRIPTION:
XS GIS Cut Line= 3
      2229516.52      7251664.26        2228429.        7252010.
      2227304.16      7252445.05
#Sta/Elev= 30
  3854.3 1058.82  4072.1 1056.02  4189.8 1051.58  4322.3 1043.14  4322.9 1043.26
    4351 1040.08  4491.8 1032.74  4596.7 1025.48  4670.2  1016.7  4722.6 1017.18
  4764.6 1012.28  4796.1 1013.12  4845.1 1008.56  4882.6  1008.8    4922 1005.61
  4953.5 1006.09    4964 1004.64    5033 1003.34  5033.3 1002.84    5037 1003.34
    5204 1008.62  5263.8 1014.73    5360 1019.89  5422.1 1025.35    5452 1026.19
    6008 1030.76    6014 1027.23  6032.6 1025.84  6171.6 1025.59  6201.5 1027.75
#Mann= 5 ,-1 , 0
  3854.3     .05       0  4322.3     .12       0  4322.9     .05       0
    5033    .033       0    5037     .05       0
Bank Sta=5033,5037
XS Rating Curve= 0 ,0
Exp/Cntr=0.3,0.1

Type RM Length L Ch R = 1 ,18140   ,365,365,365
BEGIN DESCRIPTION:
BEECHMAN BRANCH 39.0
END DESCRIPTION:
XS GIS Cut Line= 3
       2229451.4      7251317.04        2228379.        7251660.
      2227226.97      7252109.15
#Sta/Elev= 30
  3874.5  1051.1    3932 1048.18  4125.8 1037.83  4159.3 1033.42  4202.5  1036.1
  4459.2  1027.3  4721.8  1008.1  4786.1 1010.55  4903.9 1002.95  4904.2 1002.45
  4907.9 1002.95  5153.9 1003.68  5178.4  1007.9  5408.3 1023.84  5494.1 1022.29
  5539.8 1017.01    5580 1020.45  5732.8  1018.5  5773.2 1009.45  5805.4 1009.77
  5811.6 1012.99    5817 1010.12  5836.1 1016.19  5920.4  1023.4  6029.1  1028.4
  6143.2 1026.58  6181.1 1028.96  6191.8 1032.71  6202.9 1030.51  6236.9 1032.11
#Mann= 5 ,-1 , 0
  3874.5     .05       0    3932     .12       0  4125.8     .05       0
  4903.9    .033       0  4907.9     .05       0
Bank Sta=4903.9,4907.9
XS Rating Curve= 0 ,0
Exp/Cntr=0.3,0.1

Type RM Length L Ch R = 1 ,17775   ,371,371,371
BEGIN DESCRIPTION:
BEECHMAN BRANCH 38.0
END DESCRIPTION:
XS GIS Cut Line= 3
      2229429.64      7251045.79        2228329.        7251310.
      2227237.97      7251675.07
#Sta/Elev= 30
    3864 1052.83  4164.3 1034.08  4255.5 1032.84  4450.9 1021.03  4615.4 1014.86
  4636.4 1011.44  4769.7  1013.2  4799.2 1006.65  4872.5 1003.24  5004.4 1003.01
  5004.7 1002.51  5008.4 1003.01    5138 1003.26  5343.9 1017.71  5453.7 1012.04
    5480 1005.27  5502.1 1003.66  5554.8 1003.89  5586.4 1011.41  5649.7 1012.77
  5674.8 1007.81  5691.9 1008.71  5701.1  1013.4  5706.3 1011.27  5764.2 1016.61
  5769.5 1014.08  5795.8 1017.63  5858.9 1019.64    6080 1023.56  6146.4  1031.4
#Mann= 3 ,-1 , 0
    3864     .05       0  5004.4    .033       0  5008.4     .05       0
Bank Sta=5004.4,5008.4
XS Rating Curve= 0 ,0
Exp/Cntr=0.3,0.1

Type RM Length L Ch R = 1 ,17404   ,64,64,64
BEGIN DESCRIPTION:
BEECHMAN BRANCH 37.0
END DESCRIPTION:
XS GIS Cut Line= 4
      2229397.13      7250937.27      2228485.66      7251110.88
        2228229.        7251010.      2227162.92      7250796.42
#Sta/Elev= 30
  3792.4 1051.77  3841.4 1048.24  3902.5 1048.55  4095.9 1042.64  4279.1 1028.49
  4574.3 1013.81  4585.8  1007.7  4594.7 1005.35  4604.9 1005.82  4615.1 1009.58
  4625.2 1010.37    4716 1004.14  4951.4 1004.36  5021.5 1007.93  5123.4 1004.99
  5320.6 1004.54    5351 1002.94  5351.2 1002.44    5355 1002.94  5373.1 1003.38
  5414.2 1009.23    5455 1010.24  5485.6 1013.88  5689.3 1024.49  5785.8 1030.16
  5836.7 1030.32  5862.9 1033.14  5944.5  1036.4  6035.4 1037.43  6083.3 1035.04
#Mann= 5 ,-1 , 0
  3792.4     .05       0  5320.6     .12       0    5351    .033       0
    5355     .12       0  5689.3     .05       0
Bank Sta=5351,5355
XS Rating Curve= 0 ,0
Exp/Cntr=0.3,0.1

Type RM Length L Ch R = 1 ,17340   ,86,86,86
BEGIN DESCRIPTION:
BEECHMAN BRANCH 36.5
END DESCRIPTION:
XS GIS Cut Line= 3
      2229386.47      7250903.62      2228541.34      7251035.11
      2227326.82      7250713.01
#Sta/Elev= 30
  3809.5 1052.47  3938.5 1050.35  4090.3 1044.32  4338.5 1026.01  4626.7 1011.17
  4646.9 1007.16    4655 1002.28  4655.3 1001.78    4659 1002.28  4663.1  1006.5
  4668.8 1002.85  4677.6 1010.09    4750 1005.76  4779.1 1008.84  4784.2 1006.08
  4819.3 1009.08  4824.4 1006.92  4853.4 1009.38  4915.5 1009.96  4939.8 1008.24
  4967.2  1010.3    4980 1008.37  5286.1 1009.17  5339.7 1011.44  5360.4 1005.31
  5371.7 1004.57  5403.6 1009.79  5494.9 1018.17  5788.5 1032.22  5921.3 1036.99
#Mann= 5 ,-1 , 0
  3809.5     .05       0    4655    .033       0    4659     .05       0
  5403.6     .12       0  5788.5     .05       0
Bank Sta=4655,4659
XS Rating Curve= 0 ,0
Exp/Cntr=0.3,0.1

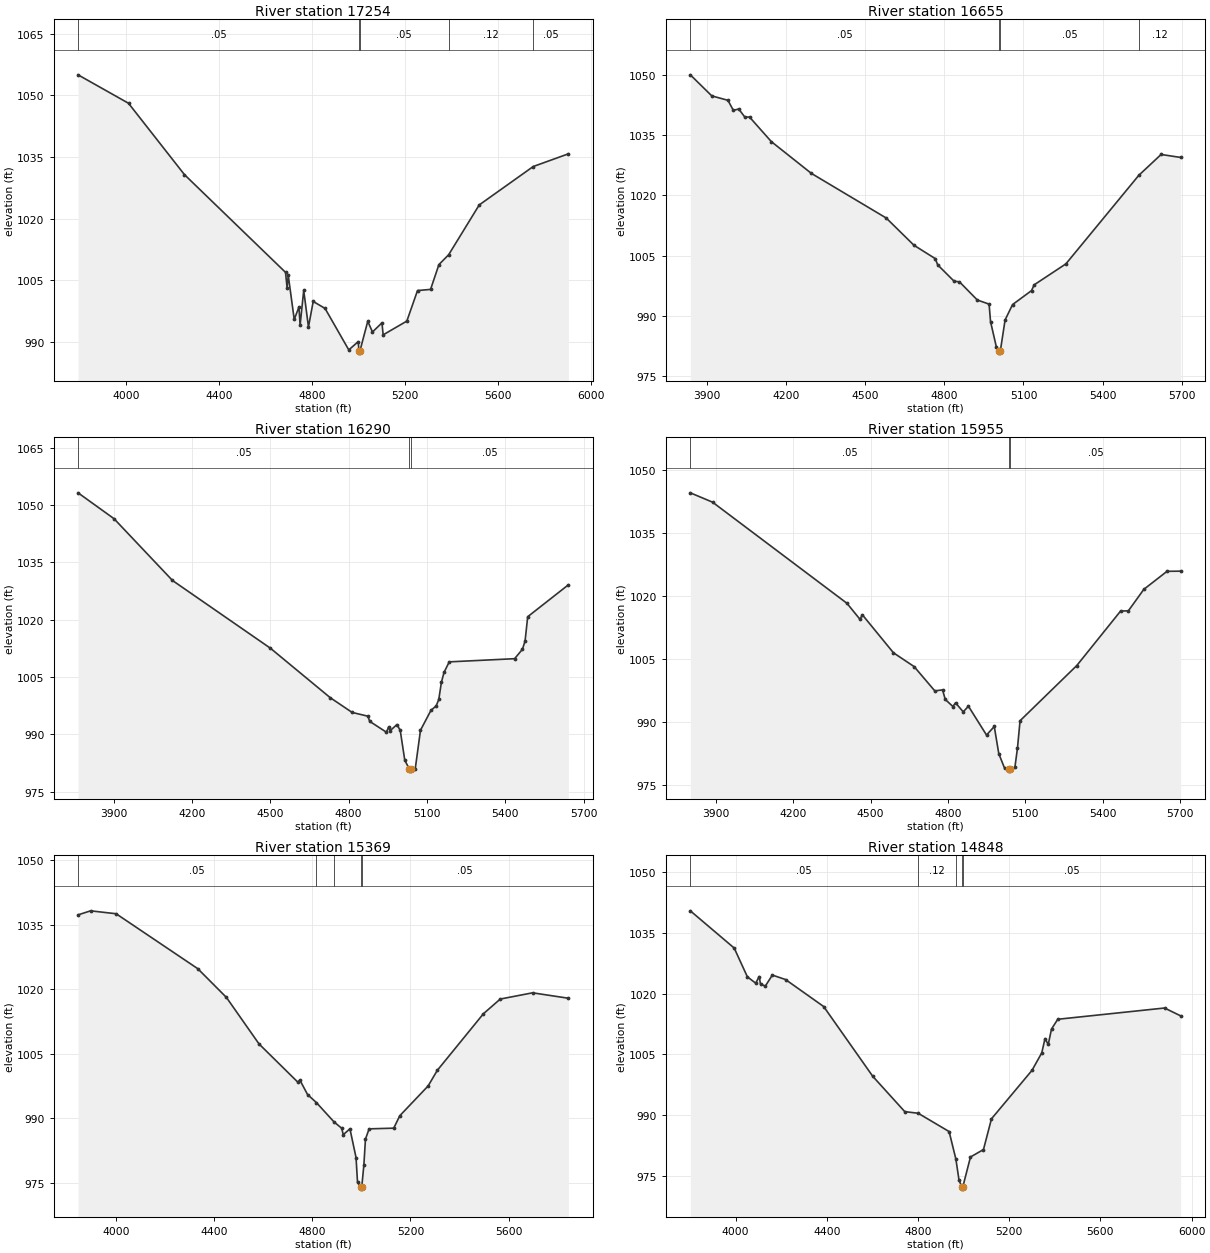
Type RM Length L Ch R = 1 ,17254   ,599,599,599
BEGIN DESCRIPTION:
BEECHMAN BRANCH 36.0
END DESCRIPTION:
XS GIS Cut Line= 3
      2229375.37      7250872.17      2228485.66      7250937.27
      2227293.07      7250698.75
#Sta/Elev= 30
  3794.5    1055  4011.4 1048.08  4252.1  1030.7  4686.6 1006.92  4693.2 1003.18
  4698.3 1006.19    4724  995.45  4744.2  998.47  4749.3   994.1  4764.8 1002.52
  4785.2  993.63  4805.6  999.84  4856.5  998.14  4958.5  988.05  4999.2  990.05
  5002.3  987.76  5002.5  987.26  5006.3  987.76  5040.1     995  5060.5  992.41
  5101.2  994.63  5106.3  991.71  5208.2  995.06  5254.1 1002.49  5310.2 1002.77
  5346.1 1008.81    5388 1011.21  5519.4 1023.33  5751.6 1032.68  5902.8 1035.77
#Mann= 5 ,-1 , 0
  3794.5     .05       0  5002.3    .033       0  5006.3     .05       0
    5388     .12       0  5751.6     .05       0
Bank Sta=5002.3,5006.3
XS Rating Curve= 0 ,0
Exp/Cntr=0.3,0.1

Type RM Length L Ch R = 1 ,16655   ,365,365,365
BEGIN DESCRIPTION:
BEECHMAN BRANCH 35.0
END DESCRIPTION:
XS GIS Cut Line= 3
      2229418.79      7250546.64        2228279.        7250310.
      2227585.07      7250253.68
#Sta/Elev= 30
    3836    1050  3917.5 1044.76  3978.8 1043.66  3999.2 1041.16  4019.6  1041.5
    4043 1039.47  4060.5 1039.51  4143.3 1033.39  4295.4 1025.48  4579.1 1014.39
  4684.5 1007.61  4765.2 1004.29  4774.5 1002.73  4836.7  998.67  4857.1  998.51
  4924.9  993.99  4969.5  992.97    4975  988.62  4997.5   982.2  5008.1  981.28
  5008.4  980.78  5012.1  981.28  5030.2  989.04  5058.6  992.86  5130.5  996.33
  5140.6  997.77  5260.9 1002.98  5537.7 1025.02  5622.1 1030.19  5696.3 1029.45
#Mann= 4 ,-1 , 0
    3836     .05       0  5008.1    .033       0  5012.1     .05       0
  5537.7     .12       0
Bank Sta=5008.1,5012.1
XS Rating Curve= 0 ,0
Exp/Cntr=0.3,0.1

Type RM Length L Ch R = 1 ,16290   ,335,335,335
BEGIN DESCRIPTION:
BEECHMAN BRANCH 34.0
END DESCRIPTION:
XS GIS Cut Line= 3
      2229549.07      7250123.48        2228329.        7249960.
      2227683.35      7249928.19
#Sta/Elev= 30
  3764.1 1053.17  3901.8  1046.4  4125.7 1030.23  4500.6 1012.51  4729.6  999.57
  4813.5  995.71    4874  994.72  4880.6  993.38  4944.6  990.54  4953.5  991.92
  4958.6  990.91    4985  992.52  4997.6  991.03  5015.1  983.18  5033.1  980.85
  5033.4  980.35  5037.1  980.85  5055.1  980.94  5075.2  991.05  5115.2  996.24
  5135.2  997.41  5145.3  999.11  5155.3  1003.6  5165.3 1006.18  5185.3 1008.94
  5435.6 1009.77  5465.6 1012.24  5475.7 1014.41  5485.7 1020.75  5641.5  1029.1
#Mann= 3 ,-1 , 0
  3764.1     .05       0  5033.1    .033       0  5037.1     .05       0
Bank Sta=5033.1,5037.1
XS Rating Curve= 0 ,0
Exp/Cntr=0.3,0.1

Type RM Length L Ch R = 1 ,15955   ,586,586,586
BEGIN DESCRIPTION:
BEECHMAN BRANCH 33.0
END DESCRIPTION:
XS GIS Cut Line= 3
      2229624.98       7249743.7        2228429.        7249660.
      2227726.12      7249656.89
#Sta/Elev= 30
  3801.1 1044.56  3887.3 1042.34  4408.6  1018.3  4458.7 1014.52  4468.7 1015.54
    4589 1006.53  4669.2 1003.25  4749.4  997.47  4779.5  997.72  4789.8  995.44
  4819.6  993.76  4829.6  994.64  4859.7  992.49  4879.7  993.84  4949.9  986.98
    4980  989.01  4997.5  982.55    5020  979.09    5038   978.9  5038.3   978.4
    5042   978.9    5060  979.31    5070  983.89    5080  990.38    5300  1003.5
    5470 1016.46    5500  1016.5    5560 1021.61    5650  1025.9  5702.9 1025.94
#Mann= 3 ,-1 , 0
  3801.1     .05       0    5038    .033       0    5042     .05       0
Bank Sta=5038,5042
XS Rating Curve= 0 ,0
Exp/Cntr=0.3,0.1

Type RM Length L Ch R = 1 ,15369   ,521,521,521
BEGIN DESCRIPTION:
BEECHMAN BRANCH 32.0
END DESCRIPTION:
XS GIS Cut Line= 3
      2229538.13      7248788.85      2228442.26      7249103.51
      2227639.27      7249407.34
#Sta/Elev= 30
  3845.2 1037.32  3896.3 1038.26  4000.4 1037.58  4333.3  1024.8  4450.1 1018.11
    4583 1007.29  4740.7  998.43  4749.4  998.89  4780.7  995.53  4817.1  993.64
  4888.9  989.14  4919.7   987.7  4926.3   986.2  4953.4  987.56  4978.3  980.88
  4984.4  975.09  4997.5  974.03  4997.8  973.53  5001.6  974.03  5010.2   979.1
  5016.7  985.15  5031.6  987.55    5132  987.71  5156.8  990.61  5272.2  997.53
  5309.6 1001.16  5497.5 1014.32  5566.2 1017.74  5697.9 1019.19  5843.9 1017.93
#Mann= 5 ,-1 , 0
  3845.2     .05       0  4817.1     .12       0  4888.9     .05       0
  4997.5    .033       0  5001.6     .05       0
Bank Sta=4997.5,5001.6
XS Rating Curve= 0 ,0
Exp/Cntr=0.3,0.1

Type RM Length L Ch R = 1 ,14848   ,258,258,258
BEGIN DESCRIPTION:
BEECHMAN BRANCH 31.0
END DESCRIPTION:
XS GIS Cut Line= 3
      2229266.94      7248072.67      2228246.94      7248712.88
      2227530.81      7249331.36
#Sta/Elev= 30
  3801.4 1040.43  3993.8 1031.24  4051.6 1024.14  4088.1 1022.57  4103.4 1024.21
  4109.3 1022.31  4130.5 1021.87  4161.1 1024.57  4218.9 1023.47  4386.1 1016.81
  4601.8  999.56  4741.9  990.86  4800.6  990.46  4936.4  985.94  4966.2  979.11
  4979.6  974.03    4992  972.23  4992.3  971.73  4996.2  972.23  5030.1  979.66
  5087.1   981.5  5122.2  989.09  5299.9 1001.05  5342.7 1005.36  5356.9 1008.88
  5371.2 1007.46  5385.5 1011.25  5412.9 1013.66  5881.3 1016.44  5951.9  1014.5
#Mann= 5 ,-1 , 0
  3801.4     .05       0  4800.6     .12       0  4966.2     .05       0
    4992    .033       0  4996.2     .05       0
Bank Sta=4992,4996.2
XS Rating Curve= 0 ,0
Exp/Cntr=0.3,0.1

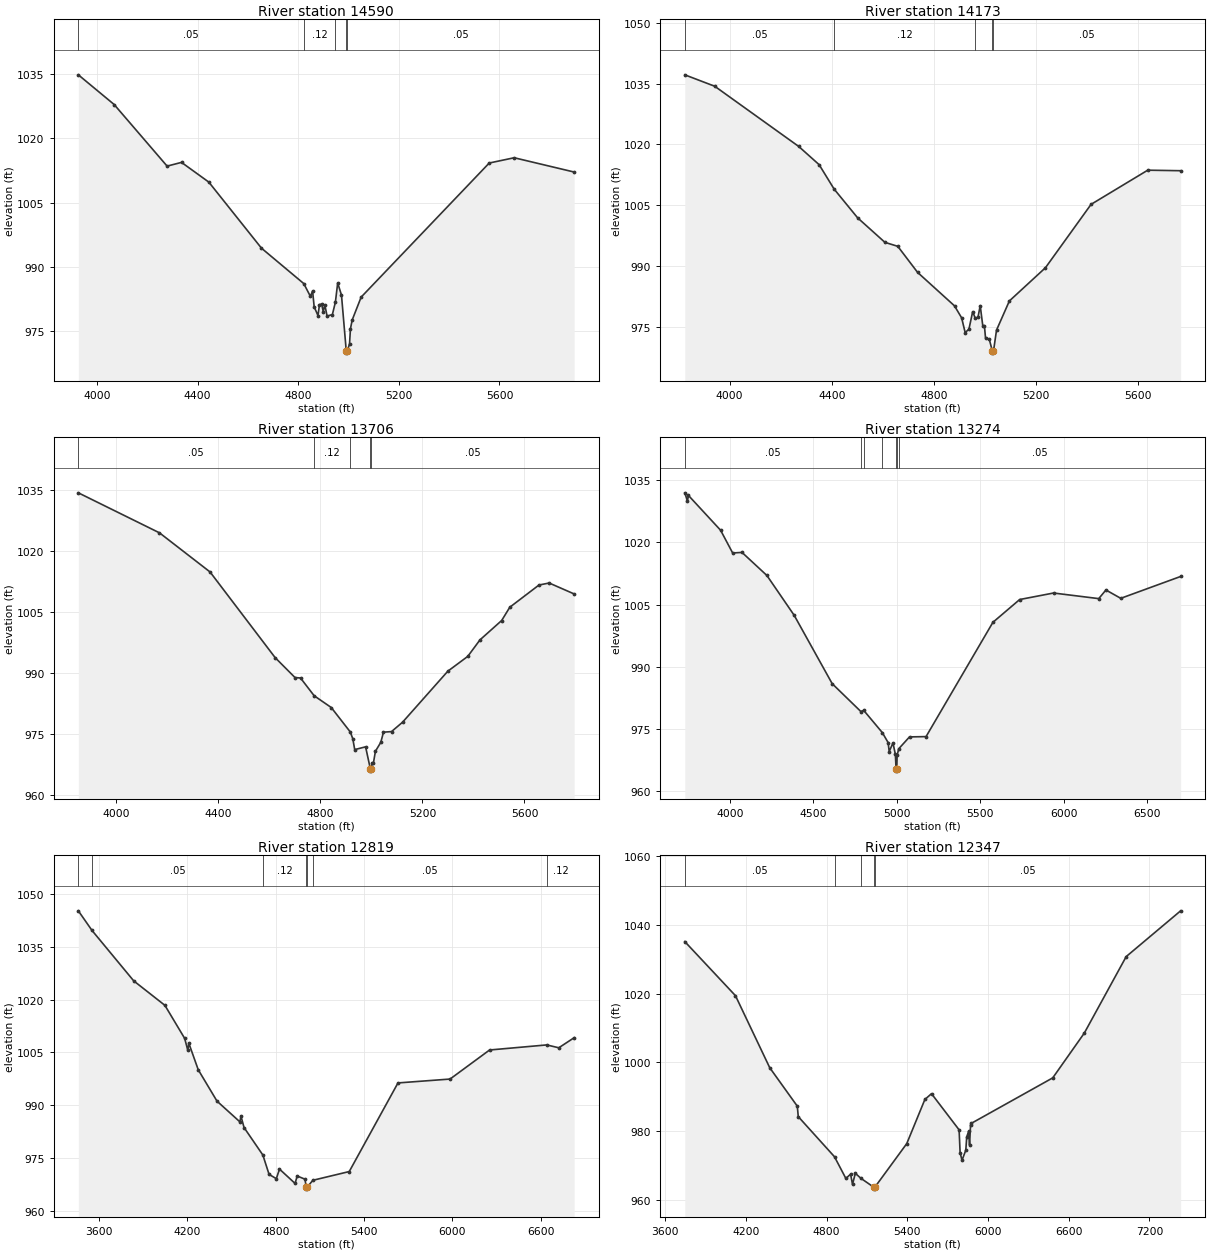
Type RM Length L Ch R = 1 ,14590   ,417,417,417
BEGIN DESCRIPTION:
BEECHMAN BRANCH 30.0
END DESCRIPTION:
XS GIS Cut Line= 3
      2229028.16       7247920.8        2228129.        7248510.
      2227476.67      7249125.09
#Sta/Elev= 30
  3925.5 1034.75    4068 1027.83  4278.5 1013.48  4335.8 1014.35  4444.3 1009.76
  4653.8  994.36    4822  986.11  4848.2  983.14    4857  984.38  4863.3  980.69
  4878.4  978.67  4884.4  981.21  4892.9  981.35  4899.5  979.55  4905.5  981.19
  4914.6  978.54  4935.7   978.9  4947.7  981.79  4956.8  986.26  4971.9  983.42
  4990.9  970.41  4991.2  969.91  4995.1  970.41  5003.9  972.08  5007.6   975.6
  5014.5  977.64  5050.1  982.96  5559.4  1014.2  5658.6 1015.43  5897.1  1012.1
#Mann= 5 ,-1 , 0
  3925.5     .05       0    4822     .12       0  4947.7     .05       0
  4990.9    .033       0  4995.1     .05       0
Bank Sta=4990.9,4995.1
XS Rating Curve= 0 ,0
Exp/Cntr=0.3,0.1

Type RM Length L Ch R = 1 ,14173   ,467,467,467
BEGIN DESCRIPTION:
BEECHMAN BRANCH 29.0
END DESCRIPTION:
XS GIS Cut Line= 3
      2228562.48      7247259.76        2227879.        7248210.
      2227409.73      7248822.23
#Sta/Elev= 30
  3824.3 1037.14  3941.6 1034.32  4270.6 1019.47  4350.4 1014.98  4409.1 1008.96
  4501.3 1001.86  4608.1  995.82  4658.5  994.84  4736.1  988.41  4880.6  980.16
  4908.6  977.19  4922.4  973.56  4937.1  974.41  4951.8  978.73  4962.1  977.08
  4972.7   977.4  4981.3  980.21  4991.7  975.08    4998  975.08  5002.1  972.22
  5016.6  971.94    5029     969  5029.3   968.5  5033.3     969  5045.2  974.18
  5095.5  981.37  5236.8  989.56  5415.4 1005.19  5637.4 1013.62  5766.2 1013.49
#Mann= 5 ,-1 , 0
  3824.3     .05       0  4409.1     .12       0  4962.1     .05       0
    5029    .033       0  5033.3     .05       0
Bank Sta=5029,5033.3
XS Rating Curve= 0 ,0
Exp/Cntr=0.3,0.1

Type RM Length L Ch R = 1 ,13706   ,432,432,432
BEGIN DESCRIPTION:
BEECHMAN BRANCH 28.0
END DESCRIPTION:
XS GIS Cut Line= 3
      2228291.65      7247093.09        2227529.        7247960.
       2227284.7      7248711.15
#Sta/Elev= 30
  3850.4 1034.41  4168.7 1024.56    4367 1014.93  4622.2  993.85    4700  988.95
  4721.8  988.83  4775.3  984.46  4842.3  981.57  4916.8  975.56  4926.8  973.88
  4934.3  971.21    4977  971.89  4995.8  966.41  4996.1  965.91  5000.1  966.41
  5001.7  967.92  5007.7  967.92  5015.5   970.8  5036.6     973  5047.1   975.5
  5078.6  975.64  5122.1  977.96  5299.5  990.51  5377.6  994.15  5425.6  998.22
  5510.6 1002.98  5542.5 1006.25    5657 1011.72    5697 1012.21  5794.9 1009.52
#Mann= 5 ,-1 , 0
  3850.4     .05       0  4775.3     .12       0  4916.8     .05       0
  4995.8    .033       0  5000.1     .05       0
Bank Sta=4995.8,5000.1
XS Rating Curve= 0 ,0
Exp/Cntr=0.3,0.1

Type RM Length L Ch R = 1 ,13274   ,455,455,455
BEGIN DESCRIPTION:
BEECHMAN BRANCH 27.0
END DESCRIPTION:
XS GIS Cut Line= 4
      2228236.06      7246975.06        2227229.        7247760.
      2227173.59      7248502.81      2227479.06      7249405.31
#Sta/Elev= 30
    3728 1031.96  3743.7 1030.01  3750.1 1031.32  3942.8 1022.94  4015.1 1017.46
  4071.2  1017.6  4220.5 1012.04  4384.2 1002.44  4612.2  985.96  4784.1  979.25
  4801.2  979.53  4912.9  974.17  4947.8  971.76  4954.2   969.6  4976.8  971.68
  4991.3  968.91  4995.4  965.38  4995.8  964.88  4999.7  965.38  5001.7  968.66
  5011.4  970.27    5076  973.13  5175.3   973.2  5576.4 1000.75  5736.9 1006.24
  5940.1 1007.81  6211.3 1006.46  6254.4 1008.54  6343.4 1006.53  6702.5  1011.8
#Mann= 7 ,-1 , 0
    3728     .05       0  4784.1     .12       0  4801.2     .05       0
  4912.9     .12       0  4995.4     .07       0  4999.7     .12       0
  5011.4     .05       0
Bank Sta=4995.4,4999.7
XS Rating Curve= 0 ,0
Exp/Cntr=0.3,0.1

Type RM Length L Ch R = 1 ,12819   ,472,472,472
BEGIN DESCRIPTION:
BEECHMAN BRANCH 26.0
END DESCRIPTION:
XS GIS Cut Line= 4
      2227937.52      7246447.22        2226879.        7247560.
       2226426.9      7248013.06      2226451.37      7249204.25
#Sta/Elev= 30
    3459 1045.22  3551.5 1039.67    3835 1025.34  4046.9 1018.39  4181.2    1009
  4202.6  1005.6  4209.5 1007.62  4273.4 1000.09  4400.8  991.19  4556.2  985.31
  4563.4  986.93  4584.5  983.69  4712.2  975.89  4754.4  970.39  4803.7  969.18
  4825.1   971.9  4931.1  967.82  4945.3  969.94  4998.3  969.03  5006.7  966.71
  5007.1  966.21  5011.3  966.71    5052  968.72  5298.9   971.2  5629.8  996.36
  5983.6  997.46  6251.9 1005.71  6639.9 1007.15    6722 1006.34  6826.3  1009.2
#Mann= 7 ,-1 , 0
    3459     .12       0  3551.5     .05       0  4712.2     .12       0
  5006.7     .07       0  5011.3     .12       0    5052     .05       0
  6639.9     .12       0
Bank Sta=5006.7,5011.3
XS Rating Curve= 0 ,0
Exp/Cntr=0.3,0.1

Type RM Length L Ch R = 1 ,12347   ,491,491,491
BEGIN DESCRIPTION:
BEECHMAN BRANCH 25.0
END DESCRIPTION:
XS GIS Cut Line= 4
      2227513.87      7246322.26        2226629.        7247210.
      2225829.89      7247957.48      2225278.09       7249175.7
#Sta/Elev= 30
  3746.6 1035.13  4123.2 1019.38  4377.8  998.42  4582.8  987.22  4589.9  984.18
  4859.2   972.5  4943.5   966.2  4978.8  967.42    4993  964.47    5014   967.7
  5054.5  966.25  5153.2  963.58  5153.8  963.08    5158  963.58  5396.4  976.34
  5530.8  989.17  5580.1  990.86  5785.3  980.33  5792.6  973.74  5806.8  971.47
  5835.1  974.43  5841.9  978.28  5856.1  979.91    5863   975.9  5870.3  981.72
  5877.1  982.25  6481.2  995.46  6715.8  1008.5  7027.1 1030.76  7431.6 1044.08
#Mann= 5 ,-1 , 0
  3746.6     .05       0  4859.2     .12       0  5054.5     .05       0
  5153.2     .07       0    5158     .05       0
Bank Sta=5153.2,5158
XS Rating Curve= 0 ,0
Exp/Cntr=0.3,0.1

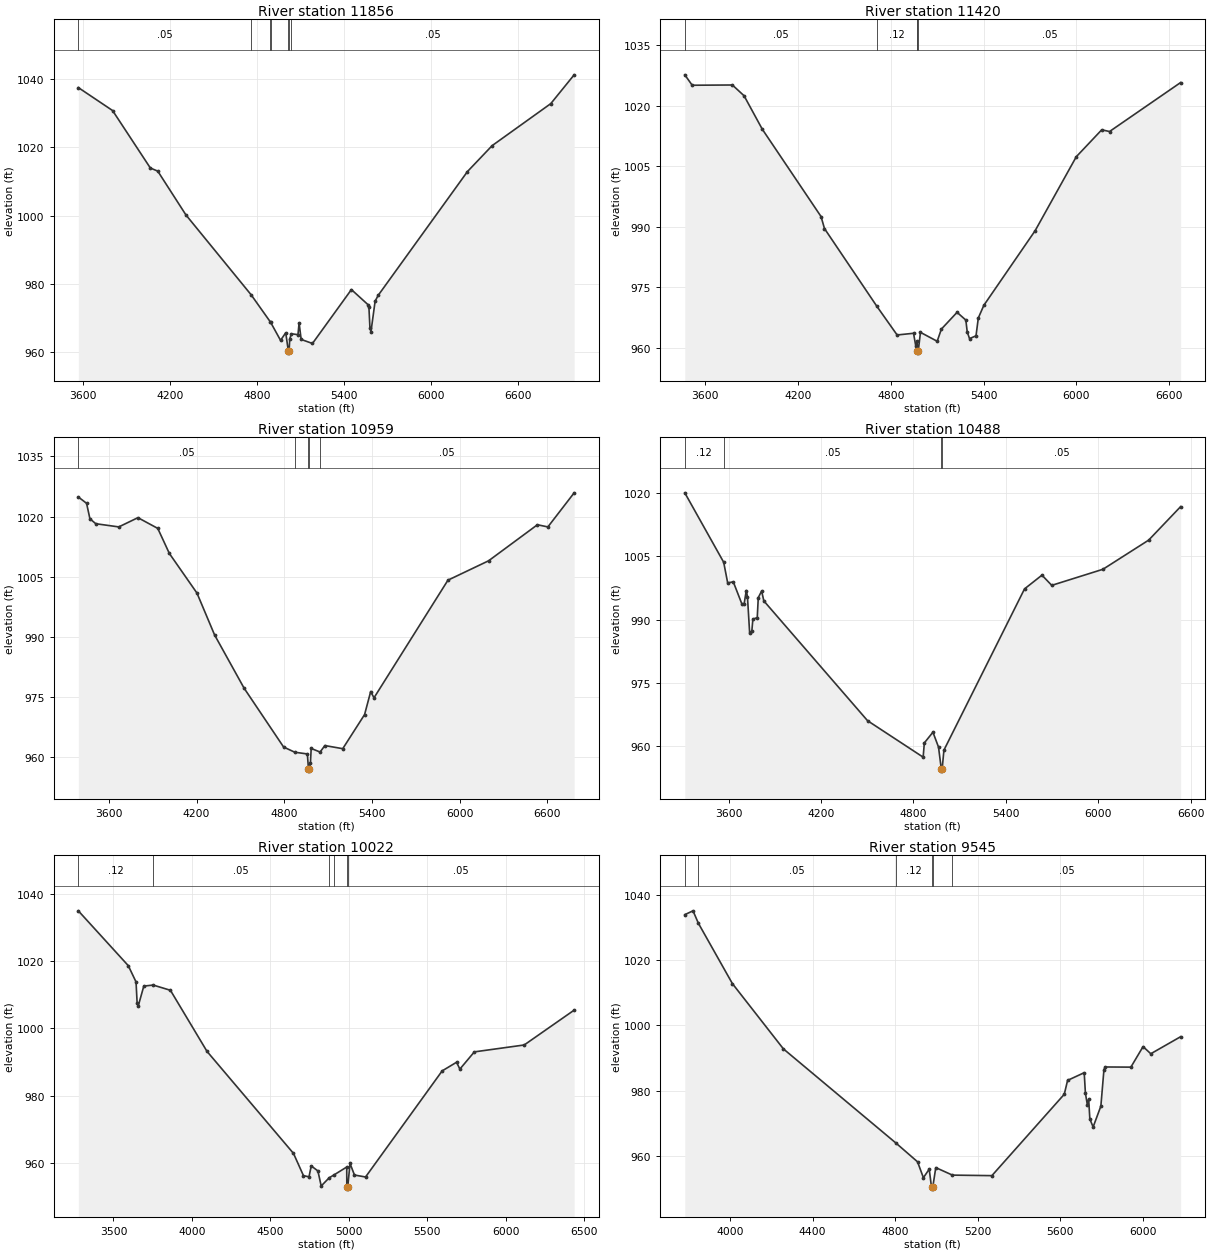
Type RM Length L Ch R = 1 ,11856   ,436,436,436
BEGIN DESCRIPTION:
BEECHMAN BRANCH 24.0
END DESCRIPTION:
XS GIS Cut Line= 3
      2227534.68      7246148.66      2226340.26      7246912.53
      2224819.46      7248218.06
#Sta/Elev= 30
  3566.4 1037.57  3802.8 1030.83  4063.2 1013.99  4114.8 1013.05  4309.1 1000.21
  4759.2  976.78  4892.4  968.79  4892.8  968.78    4962  963.43  4997.9  965.65
  5016.3  960.18  5016.9  959.68  5021.1  960.18  5025.4  963.85  5037.1  965.35
  5082.4   965.1  5090.1  968.56  5104.3   963.7  5182.3  962.51  5451.1  978.32
  5565.3  973.91  5571.9  973.23  5578.9  967.19  5586.1  965.96  5614.7   974.9
  5635.5   976.6  6252.3 1012.95  6422.4 1020.54  6827.3 1032.87  6988.5 1041.31
#Mann= 7 ,-1 , 0
  3566.4     .05       0  4759.2     .12       0  4892.4     .05       0
  4892.8     .12       0  5016.3     .07       0  5021.1     .12       0
  5037.1     .05       0
Bank Sta=5016.3,5021.1
XS Rating Curve= 0 ,0
Exp/Cntr=0.3,0.1

Type RM Length L Ch R = 1 ,11420   ,461,461,461
BEGIN DESCRIPTION:
BEECHMAN BRANCH 23.0
END DESCRIPTION:
XS GIS Cut Line= 3
      2227354.12      7246072.27        2225979.        7246760.
      2224604.11      7247704.23
#Sta/Elev= 30
  3468.2 1027.69    3516 1025.11  3775.8 1025.17  3851.4  1022.5  3968.8 1014.23
  4348.9  992.57  4371.3  989.58  4710.3  970.29  4840.8  963.21    4947  963.63
    4961  960.56  4970.2  961.64  4972.5  959.21  4973.1  958.71  4977.4  959.21
  4991.7  963.86  5099.8  961.65    5127  964.67  5228.3  968.82  5285.1   966.9
    5294  963.97  5308.9  962.31  5350.8     963  5365.7  967.42  5401.6  970.57
  5733.1  989.06  5999.1 1007.39  6163.5 1014.06  6214.2 1013.64  6673.6 1025.78
#Mann= 5 ,-1 , 0
  3468.2     .05       0  4710.3     .12       0  4970.2     .05       0
  4972.5    .033       0  4977.4     .05       0
Bank Sta=4972.5,4977.4
XS Rating Curve= 0 ,0
Exp/Cntr=0.3,0.1

Type RM Length L Ch R = 1 ,10959   ,471,471,471
BEGIN DESCRIPTION:
BEECHMAN BRANCH 22.0
END DESCRIPTION:
XS GIS Cut Line= 3
      2227354.18      7245995.86        2225829.        7246510.
      2224416.63      7247600.04
#Sta/Elev= 30
  3390.9 1024.88  3447.3  1023.3  3470.2 1019.44  3510.3  1018.2  3667.7  1017.4
  3798.9 1019.71  3934.6 1017.03    4014 1010.76  4202.9 1000.86  4323.6  990.39
  4525.5  977.09  4795.8  962.39  4871.9  961.09  4958.5  960.65  4966.1  956.86
  4966.9  956.36  4971.4  956.86  4979.3  958.27  4984.7  962.03  5045.6  961.13
  5078.3  962.75  5200.6  961.97    5350  970.49    5392  976.26  5414.4  974.68
  5920.7 1004.09  6198.8 1008.93    6533 1017.94  6604.7  1017.4  6784.5 1025.92
#Mann= 5 ,-1 , 0
  3390.9     .05       0  4871.9     .12       0  4966.1     .07       0
  4971.4     .12       0  5045.6     .05       0
Bank Sta=4966.1,4971.4
XS Rating Curve= 0 ,0
Exp/Cntr=0.3,0.1

Type RM Length L Ch R = 1 ,10488   ,466,466,466
BEGIN DESCRIPTION:
BEECHMAN BRANCH 21.0
END DESCRIPTION:
XS GIS Cut Line= 3
       2226581.6        7244929.        2225479.        7246210.
      2224368.06      7247262.34
#Sta/Elev= 30
  3314.8 1020.03  3567.4 1003.57  3593.4  998.67  3629.6  998.94  3685.6  993.69
  3699.8   993.6  3714.1  996.88  3721.8  995.42    3736  986.83  3750.3  987.32
  3756.9  990.08  3785.4  990.45    3792   995.2  3813.9  996.75  3828.2  994.41
  4501.9  966.02  4862.9  957.38  4870.6  960.76  4926.5   963.3  4962.7  959.77
  4980.8  954.57  4981.6  954.07  4986.3  954.57  4997.8  959.04  5521.3  997.26
  5634.6 1000.52  5698.1   998.1  6030.6 1001.91  6327.6 1008.82  6535.2 1016.76
#Mann= 4 ,-1 , 0
  3314.8     .12       0  3567.4     .05       0  4980.8    .033       0
  4986.3     .05       0
Bank Sta=4980.8,4986.3
XS Rating Curve= 0 ,0
Exp/Cntr=0.3,0.1

Type RM Length L Ch R = 1 ,10022   ,477,477,477
BEGIN DESCRIPTION:
BEECHMAN BRANCH 20.0
END DESCRIPTION:
XS GIS Cut Line= 3
      2226545.09      7244595.72        2225329.        7245810.
      2224343.74      7246864.66
#Sta/Elev= 30
    3276 1034.98  3594.5 1018.68    3644 1013.84    3651 1007.51  3658.1  1006.7
  3693.5 1012.61  3753.4 1012.91  3863.2 1011.36  4096.5   993.2    4648  962.87
  4711.7  956.25    4747  955.91  4761.2  959.15  4803.6  957.66  4824.8  953.19
  4875.7  955.62  4908.9  956.55  4987.5  958.82  4988.2  952.75    4989  952.25
  4993.7  952.75  5008.5  959.89  5036.8  956.44  5107.6  955.86  5596.1   987.4
    5688  989.97    5709  987.93  5801.3  993.05  6119.3   995.1  6437.8 1005.46
#Mann= 6 ,-1 , 0
    3276     .12       0  3753.4     .05       0  4875.7     .12       0
  4908.9     .05       0  4988.2    .033       0  4993.7     .05       0
Bank Sta=4988.2,4993.7
XS Rating Curve= 0 ,0
Exp/Cntr=0.3,0.1

Type RM Length L Ch R = 1 ,9545    ,472,472,472
BEGIN DESCRIPTION:
BEECHMAN BRANCH 19.0
END DESCRIPTION:
XS GIS Cut Line= 4
      2225961.82       7244616.5        2225079.        7245460.
      2224746.82      7245792.18      2224394.06      7246413.44
#Sta/Elev= 30
  3779.7 1033.91  3819.6 1035.08  3845.5 1031.28  4010.5  1012.8    4258   992.8
  4805.1   963.9  4908.7  958.22    4937  953.35  4965.3  955.96  4976.7  950.35
  4977.5  949.85  4982.3  950.35  4997.2  956.44    5078  954.14  5269.4  953.98
  5620.6  978.91  5636.5  983.15  5717.2  985.51    5723  979.27  5732.5  975.64
  5738.8  977.35  5744.6  971.31  5760.5  968.88    5798  975.27    5813  986.48
  5819.6  987.26  5943.6  987.21  6002.7   993.5  6040.2  991.31  6184.9  996.53
#Mann= 6 ,-1 , 0
  3779.7     .12       0  3845.5     .05       0  4805.1     .12       0
  4976.7     .07       0  4982.3     .12       0    5078     .05       0
Bank Sta=4976.7,4982.3
XS Rating Curve= 0 ,0
Exp/Cntr=0.3,0.1

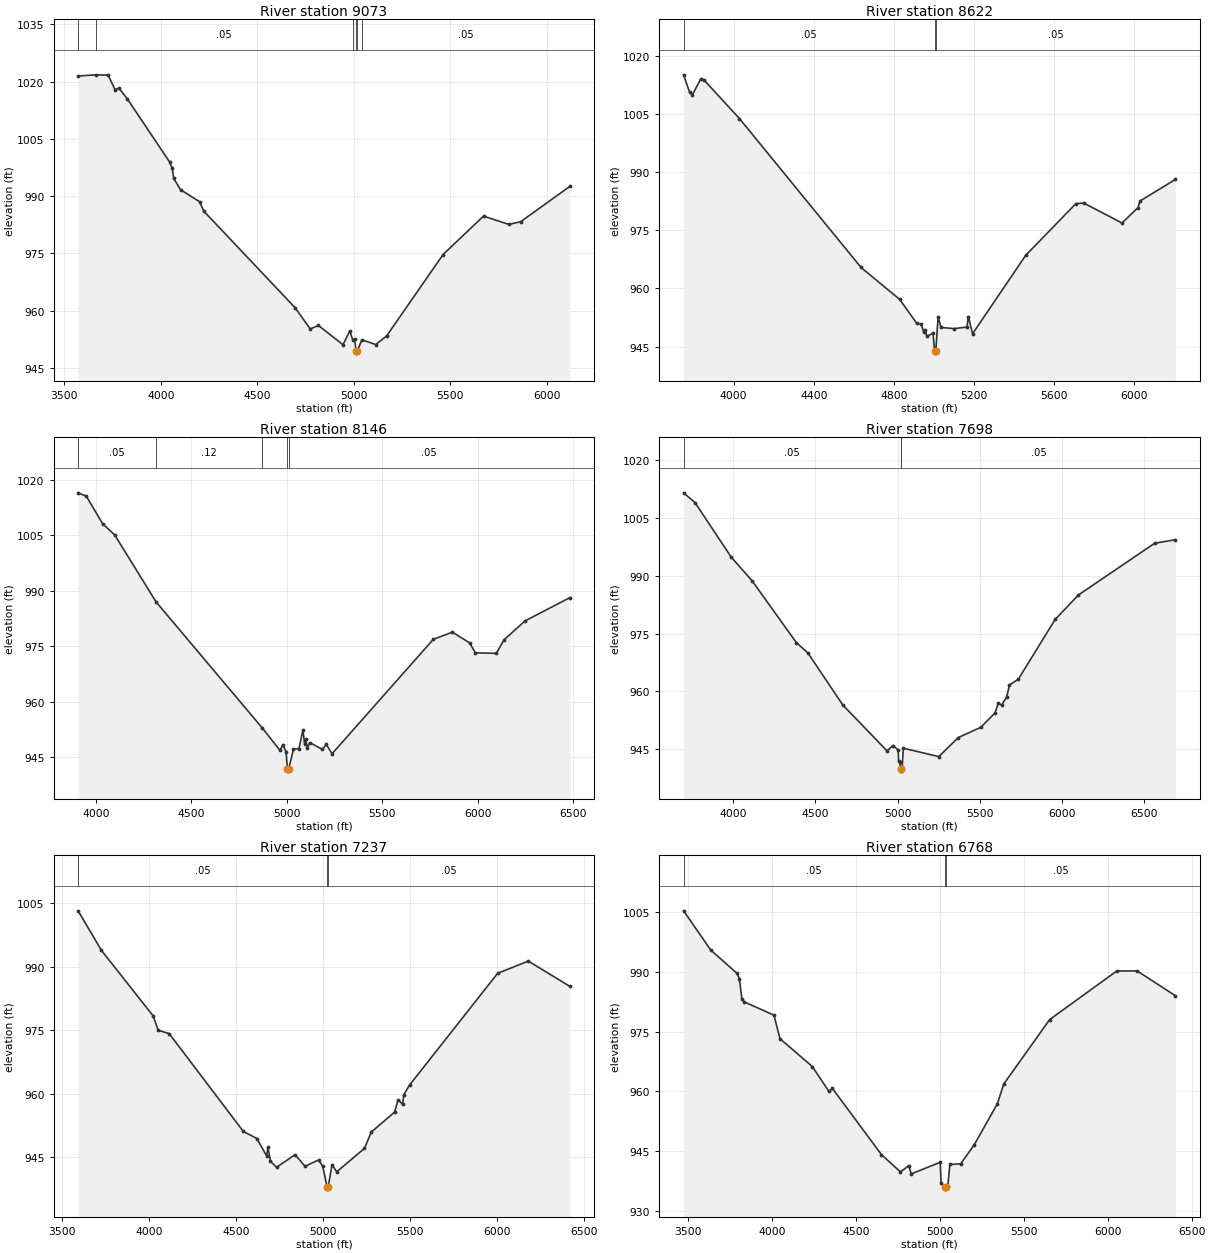
Type RM Length L Ch R = 1 ,9073    ,451,451,451
BEGIN DESCRIPTION:
BEECHMAN BRANCH 18.0
END DESCRIPTION:
XS GIS Cut Line= 4
      2225758.66      7244319.65        2224729.        7245310.
      2224416.09      7245622.91      2224331.57      7246293.65
#Sta/Elev= 30
  3571.6 1021.48  3663.5 1021.79  3727.1  1021.7  3762.6 1017.93  3783.7 1018.26
  3826.2 1015.51  4045.4  998.96  4059.5  997.26  4066.7  994.63    4102  991.69
    4201  988.53  4222.4  986.07    4696  960.73    4774  955.18  4816.4   956.1
  4943.8  951.05    4979  954.69  4993.6  952.38  5003.8   952.5  5011.5  949.35
  5012.4  948.85  5017.3  949.35  5041.7  952.35  5113.4   951.1  5169.9  953.37
  5462.2  974.69  5671.6  984.76  5802.7  982.59  5863.8  983.28  6118.8  992.55
#Mann= 6 ,-1 , 0
  3571.6     .12       0  3663.5     .05       0  4993.6     .12       0
  5011.5     .07       0  5017.3     .12       0  5041.7     .05       0
Bank Sta=5011.5,5017.3
XS Rating Curve= 0 ,0
Exp/Cntr=0.3,0.1

Type RM Length L Ch R = 1 ,8622    ,476,476,476
BEGIN DESCRIPTION:
BEECHMAN BRANCH 17.0
END DESCRIPTION:
XS GIS Cut Line= 4
      2225232.65      7244022.74        2224479.        7245010.
      2224211.79      7245382.15      2224196.19       7246136.2
#Sta/Elev= 30
  3750.2 1015.17  3779.6 1010.75  3794.1 1010.03  3835.7  1014.1  3850.3 1013.93
    4029 1003.87  4635.8  965.42  4828.7  957.16  4914.3  950.97  4935.1  950.75
  4949.6  948.71  4955.9  949.34  4964.2  947.59  4995.3  948.48  5002.9  943.79
  5003.8  943.29  5008.7  943.79  5020.5  952.59  5035.2  949.92  5100.3  949.63
  5164.6  950.02  5171.5  952.73  5192.4  948.29  5458.2  968.57  5708.3  981.91
  5748.3  982.03  5938.3   976.9  6018.4  980.88  6028.4  982.58  6204.6  988.14
#Mann= 3 ,-1 , 0
  3750.2     .05       0  5002.9    .033       0  5008.7     .05       0
Bank Sta=5002.9,5008.7
XS Rating Curve= 0 ,0
Exp/Cntr=0.3,0.1

Type RM Length L Ch R = 1 ,8146    ,448,448,448
BEGIN DESCRIPTION:
BEECHMAN BRANCH 16.0
END DESCRIPTION:
XS GIS Cut Line= 4
       2224888.9      7243939.41        2224179.        7244760.
      2224065.95       7244850.9      2224055.54      7246194.66
#Sta/Elev= 30
  3907.7 1016.43  3950.3 1015.54  4035.8 1008.09  4099.4 1005.03  4315.8  986.94
  4871.4  952.89  4964.8  946.79    4979  948.36    4996  946.48  5003.4  941.71
  5004.4  941.21  5009.3  941.71  5035.1  947.15  5063.9  947.32  5084.7  952.39
  5092.7  948.57  5099.1  949.87  5107.1  947.57  5121.1   948.9  5186.9  947.07
  5206.9  948.44  5236.9   945.9  5766.9  976.83  5866.9  978.77  5956.9  975.88
  5986.9  973.18  6096.9  973.04  6136.9  976.69  6246.9   981.8  6481.6   988.1
#Mann= 5 ,-1 , 0
  3907.7     .05       0  4315.8     .12       0  4871.4     .05       0
  5003.4    .033       0  5009.3     .05       0
Bank Sta=5003.4,5009.3
XS Rating Curve= 0 ,0
Exp/Cntr=0.3,0.1

Type RM Length L Ch R = 1 ,7698    ,461,461,461
BEGIN DESCRIPTION:
BEECHMAN BRANCH 15.0
END DESCRIPTION:
XS GIS Cut Line= 4
      2224659.68      7243653.01        2223779.        7244610.
      2223607.38      7244793.06      2223362.84      7246210.24
#Sta/Elev= 30
  3699.5 1011.59  3768.6 1009.07    3988  994.93  4115.6  988.74  4384.5  972.68
  4455.3  969.96  4667.4  956.44  4936.2  944.51    4972  945.89  5003.5  944.78
  5007.1  941.88    5014  941.55  5018.3  939.75  5019.3  939.25  5024.2  939.75
  5028.2  940.24  5035.5  945.21    5251  943.03  5369.6  947.98  5506.4  950.64
  5592.9  954.38  5613.2  956.92  5633.5  956.42  5663.9  958.58  5680.8  961.64
    5735  963.17  5958.2  978.67  6100.3  985.05  6563.3  998.48  6689.1   999.4
#Mann= 3 ,-1 , 0
  3699.5     .05       0  5018.3    .033       0  5024.2     .05       0
Bank Sta=5018.3,5024.2
XS Rating Curve= 0 ,0
Exp/Cntr=0.3,0.1

Type RM Length L Ch R = 1 ,7237    ,469,469,469
BEGIN DESCRIPTION:
BEECHMAN BRANCH 14.0
END DESCRIPTION:
XS GIS Cut Line= 3
      2224305.54       7243557.5        2223379.        7244610.
      2222994.77      7245979.39
#Sta/Elev= 30
    3593 1003.22  3727.2  993.86  4024.2  978.39  4052.7  975.03  4116.2  974.22
  4542.2  951.12    4620  949.45    4676  945.33  4683.6   947.4  4697.8  944.08
  4732.9  942.65  4839.2  945.64  4896.1   942.9  4973.9  944.38  4997.8  942.92
  5023.3     938  5024.3   937.5  5029.4     938  5051.5  943.26  5078.3  941.59
  5237.6  947.11  5276.8  950.96  5410.7  955.68  5431.4  958.63  5457.7  957.49
  5462.9  959.74  5496.9  962.08  6002.7  988.46  6179.2  991.35  6417.5  985.38
#Mann= 3 ,-1 , 0
    3593     .05       0  5023.3    .033       0  5029.4     .05       0
Bank Sta=5023.3,5029.4
XS Rating Curve= 0 ,0
Exp/Cntr=0.3,0.1

Type RM Length L Ch R = 1 ,6768    ,869,869,869
BEGIN DESCRIPTION:
BEECHMAN BRANCH 13.0
END DESCRIPTION:
XS GIS Cut Line= 4
      2224045.15      7243288.37        2223079.        7244460.
      2222808.14       7245078.5      2222907.91      7245805.37
#Sta/Elev= 30
  3475.4 1005.21    3637  995.38  3793.3  989.55  3807.7  988.25    3822  983.18
  3836.3  982.42  4013.5  979.08  4048.7  973.22  4241.6  966.24  4340.6  959.99
  4361.4  960.75  4653.3  944.19  4766.6  939.85  4816.1  941.44  4830.5  939.36
    5003  942.27  5008.4  937.05  5028.8  936.05  5029.8  935.55  5034.9  936.05
  5048.6  936.45  5060.6  941.72    5125  941.89  5206.4   946.7  5343.3  956.91
    5381  961.84  5654.5  977.98  6054.3  990.15  6175.4  990.17  6402.9  983.97
#Mann= 3 ,-1 , 0
  3475.4     .05       0  5028.8    .033       0  5034.9     .05       0
Bank Sta=5028.8,5034.9
XS Rating Curve= 0 ,0
Exp/Cntr=0.3,0.1