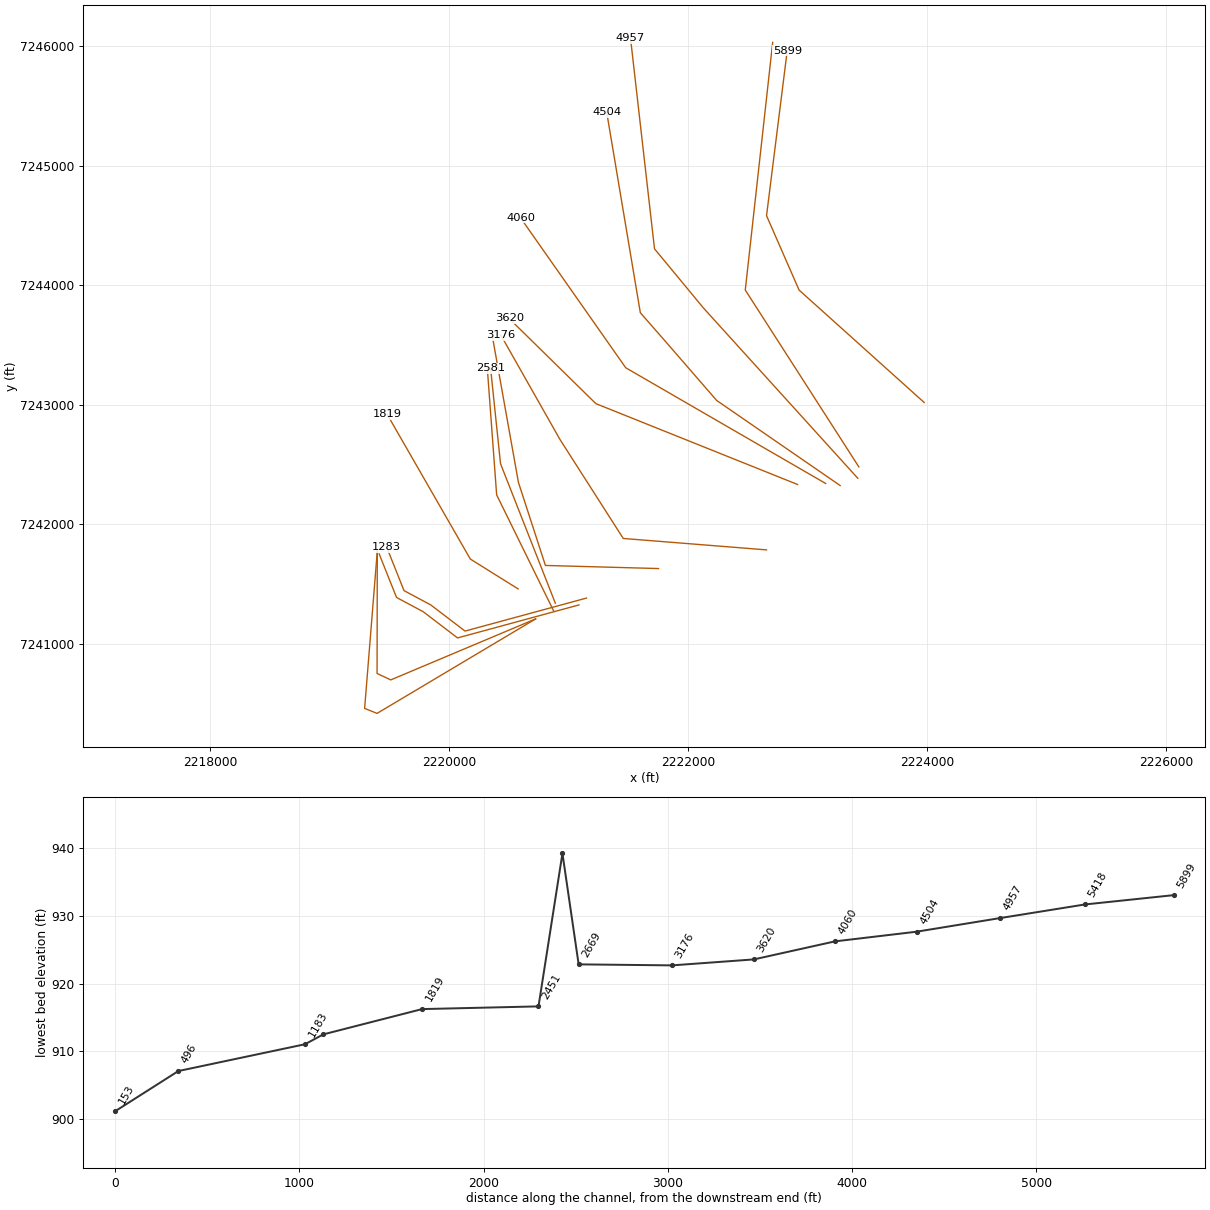
HEC-RAS study BEECHMAN BRANCH.prj: BEECHMAN BRANCH Base Level Engineering

--- BEECHMAN BRANCH.g01 (geometry) --- (continued)

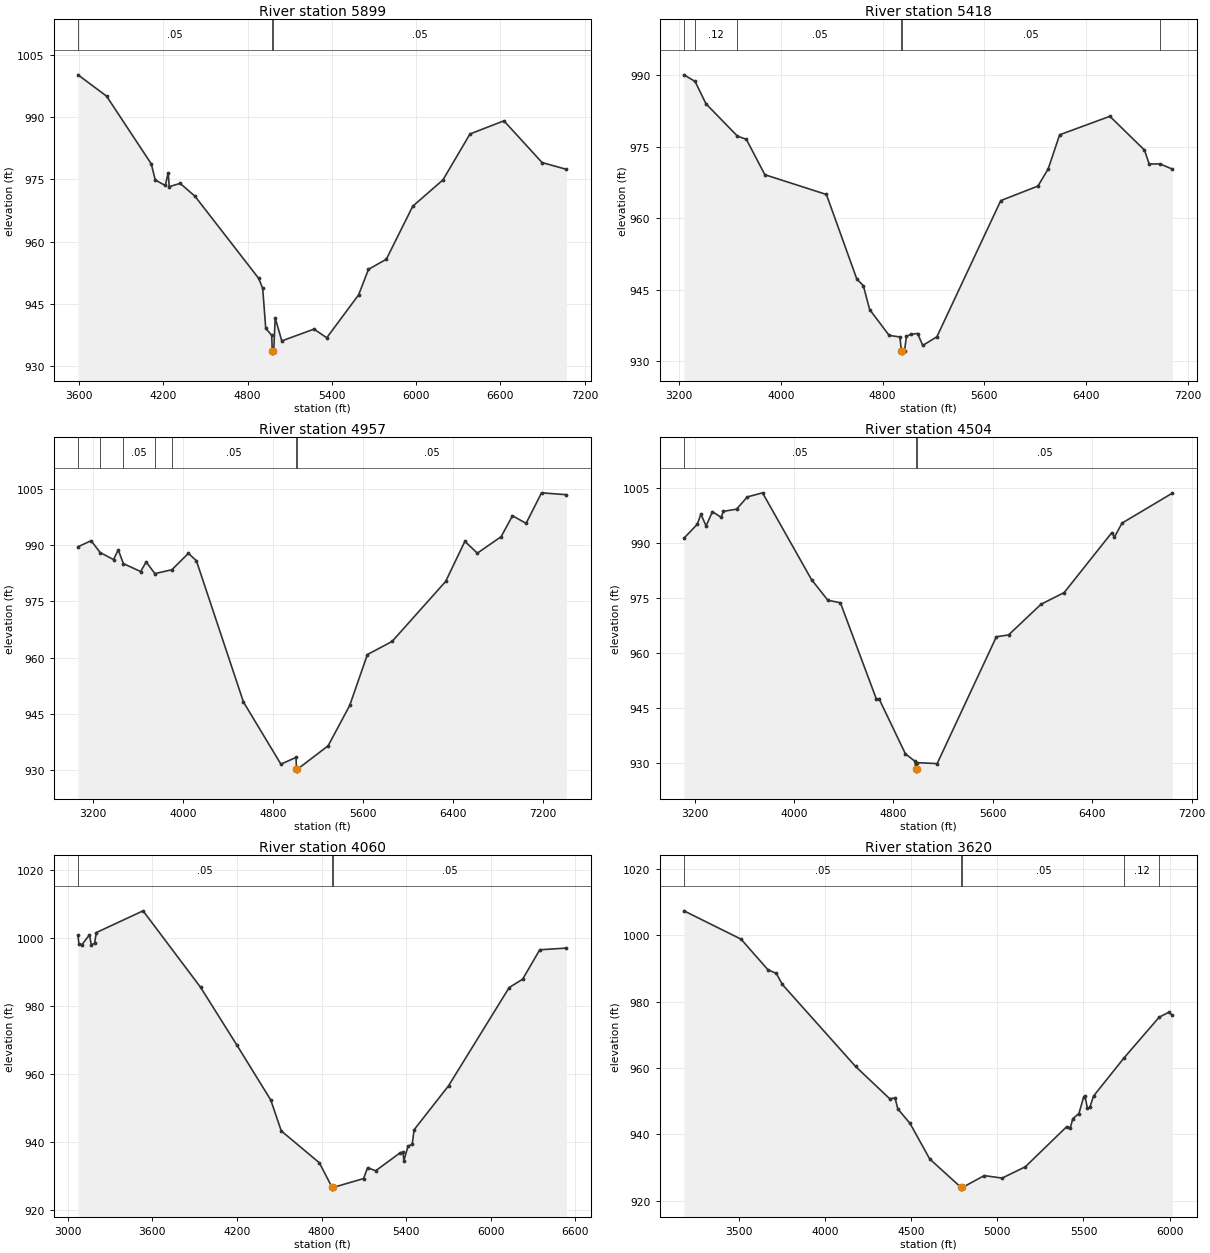
Type RM Length L Ch R = 1 ,5899    ,481,481,481
BEGIN DESCRIPTION:
BEECHMAN BRANCH 12.0
END DESCRIPTION:
XS GIS Cut Line= 4
      2223975.69      7243019.29        2222929.        7243960.
      2222656.84      7244582.07      2222829.84      7245961.97
#Sta/Elev= 30
  3592.3 1000.26  3795.8  995.12  4114.2  978.75  4142.6  974.86  4213.6  973.53
  4234.6  976.62    4242  973.25  4319.8  974.04  4425.9  970.91  4878.9  951.09
  4907.3  948.69    4929  939.02  4971.6  937.34  4975.2  933.54  4976.2  933.04
  4981.4  933.54  4985.8  933.63  4996.2  941.54  5043.3  935.99  5272.5  938.84
  5363.3  936.75  5590.2  947.12  5660.4  953.28  5787.4  955.72  5975.6  968.53
  6190.5  974.88  6383.1  985.98  6624.7  989.15    6896  979.07  7069.3  977.43
#Mann= 3 ,-1 , 0
  3592.3     .05       0  4975.2    .033       0  4981.4     .05       0
Bank Sta=4975.2,4981.4
XS Rating Curve= 0 ,0
Exp/Cntr=0.3,0.1

Type RM Length L Ch R = 1 ,5418    ,461,461,461
BEGIN DESCRIPTION:
BEECHMAN BRANCH 11.0
END DESCRIPTION:
XS GIS Cut Line= 3
      2223428.81      7242481.09        2222479.        7243960.
      2222708.32       7246031.5
#Sta/Elev= 30
  3237.4  990.05  3325.1  988.66  3410.6  983.98  3658.2  977.19  3728.4  976.52
  3873.7   969.1  4357.9  964.95    4597  947.22  4648.6  945.81  4697.9  940.82
  4851.4  935.39  4935.9  935.06  4947.9  932.17    4949  931.67  4954.3  932.17
  4972.3  932.18  4987.4  935.18  5025.2  935.65  5075.5  935.78  5115.8  933.28
  5226.9   935.1  5729.5  963.67  6021.3  966.71  6101.8  970.28  6192.3  977.47
  6587.6  981.35  6859.8  974.26  6896.6  971.34  6982.4  971.36  7079.2  970.27
#Mann= 6 ,-1 , 0
  3237.4     .05       0  3325.1     .12       0  3658.2     .05       0
  4947.9    .033       0  4954.3     .05       0  6982.4     .12       0
Bank Sta=4947.9,4954.3
XS Rating Curve= 0 ,0
Exp/Cntr=0.3,0.1

Type RM Length L Ch R = 1 ,4957    ,453,453,453
BEGIN DESCRIPTION:
BEECHMAN BRANCH 10.0
END DESCRIPTION:
XS GIS Cut Line= 4
      2223420.15      7242385.59        2222129.        7243810.
      2221719.74      7244304.86      2221519.15       7246065.6
#Sta/Elev= 30
    3069  989.57    3186   991.2    3266  988.04  3384.7  986.16  3426.6  988.75
  3472.3  985.08  3625.3  982.96  3674.7  985.52  3752.2  982.41  3902.5  983.44
  4049.7  987.82  4120.7  985.84  4538.4  948.12  4870.9  931.52  5005.2  933.33
  5009.2  930.16  5010.4  929.66  5016.9  930.16    5290  936.42  5481.9  947.21
  5638.8  960.79  5858.1  964.29  6333.3   980.3  6504.4  991.02  6615.1  987.87
  6826.5  992.28  6927.1  997.86  7047.9  995.83    7185 1003.98  7405.8 1003.48
#Mann= 7 ,-1 , 0
    3069     .05       0    3266     .12       0  3472.3     .05       0
  3752.2     .12       0  3902.5     .05       0  5009.2    .033       0
  5016.9     .05       0
Bank Sta=5009.2,5016.9
XS Rating Curve= 0 ,0
Exp/Cntr=0.3,0.1

Type RM Length L Ch R = 1 ,4504    ,444,444,444
BEGIN DESCRIPTION:
BEECHMAN BRANCH 9.0
END DESCRIPTION:
XS GIS Cut Line= 5
      2223272.53      7242324.87      2222239.57      7243036.67
        2221829.        7243510.      2221601.17      7243770.38
      2221319.42      7245449.88
#Sta/Elev= 30
  3114.5  991.28  3221.2  995.07    3251  997.82  3292.9  994.63  3343.6  998.53
  3415.3  996.96  3430.2  998.61  3537.7  999.22  3624.3 1002.56  3746.7 1003.68
  4140.9  979.98  4272.2  974.34  4373.2  973.65  4662.7  947.35  4683.6  947.46
  4896.3  932.38  4974.2  930.32    4978  928.15  4979.1  927.65  4985.7  928.15
  4992.2  929.97  5151.7   929.7  5628.4  964.36  5726.5  964.86  5987.2  973.23
  6174.1  976.44  6557.9  992.84  6578.2  991.58    6639   995.4  7044.5  1003.6
#Mann= 3 ,-1 , 0
  3114.5     .05       0    4978    .033       0  4985.7     .05       0
Bank Sta=4978,4985.7
XS Rating Curve= 0 ,0
Exp/Cntr=0.3,0.1

Type RM Length L Ch R = 1 ,4060    ,440,440,440
BEGIN DESCRIPTION:
BEECHMAN BRANCH 8.0
END DESCRIPTION:
XS GIS Cut Line= 3
      2223151.04      7242342.21        2221479.        7243310.
      2220598.93      7244564.45
#Sta/Elev= 30
  3072.1 1000.65    3079  998.16  3100.5  997.98  3153.5 1000.85  3166.9  997.93
    3190  998.35  3202.4 1001.51  3533.8 1007.89  3941.4  985.47  4198.3  968.55
  4439.4  952.38    4514  943.31  4784.5  933.94  4874.5  926.72  4875.7  926.22
  4882.4  926.72  5097.7  929.32  5126.2   932.5    5184  931.62  5356.6  936.86
  5377.5  937.09  5383.6  934.54  5413.2  938.84  5442.9  939.36    5456  943.64
  5700.3  956.54  6130.5  985.38  6225.5  987.81  6347.5  996.46  6536.4  996.96
#Mann= 3 ,-1 , 0
  3072.1     .05       0  4874.5    .033       0  4882.4     .05       0
Bank Sta=4874.5,4882.4
XS Rating Curve= 0 ,0
Exp/Cntr=0.3,0.1

Type RM Length L Ch R = 1 ,3620    ,444,444,444
BEGIN DESCRIPTION:
BEECHMAN BRANCH 7.0
END DESCRIPTION:
XS GIS Cut Line= 3
      2222916.63      7242333.55        2221229.        7243010.
      2220503.74      7243722.15
#Sta/Elev= 30
  3181.6  1007.3  3513.2  998.77  3669.3  989.55  3717.7  988.47  3752.7  985.14
  4177.8  960.46  4374.9   950.8  4407.2  950.95  4422.6  947.71  4493.4  943.35
  4608.3  932.61  4789.9  924.06  4791.1  923.56  4797.9  924.06  4924.3  927.63
    5028  926.88  5162.4  930.27  5402.9  942.36    5424  942.03  5438.1  944.76
  5473.6   946.3  5501.9  951.38  5508.9  951.53    5523  947.93  5537.2  948.17
  5558.4  951.56  5736.7  963.12  5939.5   975.3  5996.8  976.81  6016.2  975.83
#Mann= 5 ,-1 , 0
  3181.6     .05       0  4789.9    .033       0  4797.9     .05       0
  5736.7     .12       0  5939.5     .05       0
Bank Sta=4789.9,4797.9
XS Rating Curve= 0 ,0
Exp/Cntr=0.3,0.1

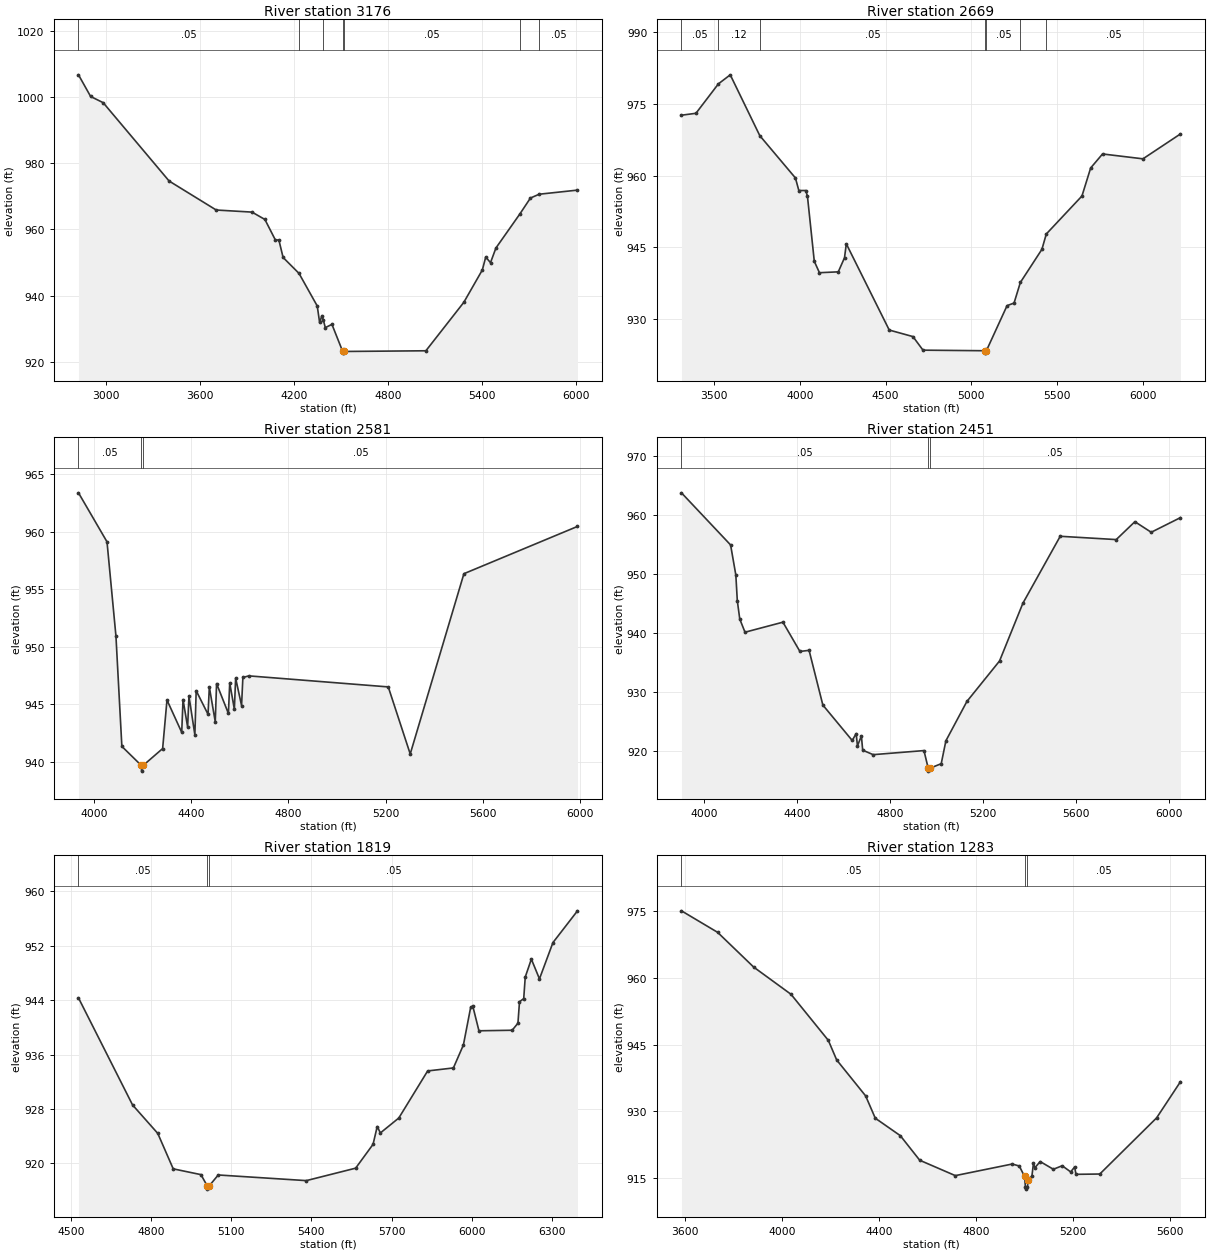
Type RM Length L Ch R = 1 ,3176    ,507,507,507
BEGIN DESCRIPTION:
BEECHMAN BRANCH 6.0
END DESCRIPTION:
XS GIS Cut Line= 4
      2222656.26      7241786.66      2221458.32      7241882.15
        2220929.        7242710.        2220434.      7243583.56
#Sta/Elev= 30
  2824.1 1006.69  2901.6 1000.16  2981.9  998.28  3403.2  974.63  3704.1  965.88
  3932.8  965.25  4015.1  963.03  4082.6  956.79  4104.3  956.87  4131.4  951.56
  4233.1  946.75  4349.6  936.91  4364.8  931.93  4379.4  933.98  4387.9   932.8
  4401.1  930.38  4443.5  931.36  4512.2  923.18  4513.4  922.68  4520.2  923.18
  5043.8  923.39  5286.2  938.02  5404.5  947.79  5426.1  951.68  5456.7  949.99
  5491.2  954.41    5645  964.74  5711.8   969.5  5767.8  970.65  6012.5  971.89
#Mann= 7 ,-1 , 0
  2824.1     .05       0  4233.1     .12       0  4387.9     .05       0
  4512.2    .033       0  4520.2     .05       0    5645     .12       0
  5767.8     .05       0
Bank Sta=4512.2,4520.2
XS Rating Curve= 0 ,0
Exp/Cntr=0.3,0.1

Type RM Length L Ch R = 1 ,2669    ,88,88,88
BEGIN DESCRIPTION:
BEECHMAN BRANCH 5.0
END DESCRIPTION:
XS GIS Cut Line= 4
      2221753.49      7241630.41      2220807.27      7241656.46
      2220581.58       7242350.9      2220364.67      7243565.61
#Sta/Elev= 30
  3309.1  972.62  3393.6  973.02  3524.6  979.18  3593.7  981.07    3766  968.34
  3973.8  959.49  3993.8  956.86  4033.9  956.86  4043.9  955.69  4083.9  942.05
  4113.9  939.66  4223.9  939.84  4260.2  942.79  4270.7   945.7  4521.1  927.66
  4659.4  926.29    4718  923.45  5079.6  923.33  5080.9  922.83  5087.7  923.33
  5208.4  932.77  5249.1  933.31  5285.9  937.62  5411.6  944.55  5437.2  947.76
  5645.2  955.71    5696  961.58  5765.3  964.51    6001  963.49  6219.8   968.7
#Mann= 7 ,-1 , 0
  3309.1     .05       0  3524.6     .12       0    3766     .05       0
  5079.6    .033       0  5087.7     .05       0  5285.9     .12       0
  5437.2     .05       0
Bank Sta=5079.6,5087.7
XS Rating Curve= 0 ,0
Exp/Cntr=0.3,0.1

Type RM Length L Ch R = 1 ,2581    ,130,130,130
BEGIN DESCRIPTION:
BEECHMAN BRANCH 4.5
END DESCRIPTION:
XS GIS Cut Line= 3
       2220890.1       7241340.6      2220431.75      7242507.31
      2220348.46      7243305.47
#Sta/Elev= 30
  3934.8  963.39  4052.3  959.13  4089.1  950.94  4113.5  941.35  4193.4   939.7
  4194.6   939.2  4201.5   939.7  4281.5  941.16  4299.4  945.38  4360.1  942.57
  4365.5  945.42  4384.5  943.03  4389.9  945.73  4414.3  942.35  4419.7  946.19
  4468.5  944.14  4473.9  946.51  4498.3  943.49  4503.7  946.81  4552.5  944.21
  4557.9  946.87    4577  944.58  4582.3  947.28  4606.7   944.9  4612.1  947.34
  4636.5  947.48  5211.1  946.52  5301.6  940.69  5522.8  956.36  5990.8  960.47
#Mann= 3 ,-1 , 0
  3934.8     .05       0  4193.4    .033       0  4201.5     .05       0
Bank Sta=4193.4,4201.5
XS Rating Curve= 0 ,0
Exp/Cntr=0.3,0.1

Type RM Length L Ch R = 1 ,2451    ,632,632,632
BEGIN DESCRIPTION:
BEECHMAN BRANCH 4.0
END DESCRIPTION:
XS GIS Cut Line= 3
       2220876.7      7241274.54      2220399.29      7242246.73
      2220321.19      7243305.37
#Sta/Elev= 30
  3904.1  963.77  4115.3  954.94  4137.8  949.85  4144.1  945.51  4154.7  942.39
  4177.2  940.16  4340.2  941.86  4413.2   936.9  4452.6  937.09  4511.8  927.82
    4638  921.82    4655  922.99  4660.5   920.9  4677.4  922.59    4683  920.18
    4728  919.42  4946.3  920.11  4964.5  917.13  4965.7  916.63  4972.6  917.13
  5020.5  917.89  5040.6  921.77  5130.8  928.43  5271.2  935.29  5371.5  945.07
  5531.9  956.41  5772.6  955.85  5852.8  958.88    5923  957.09  6048.7  959.57
#Mann= 3 ,-1 , 0
  3904.1     .05       0  4964.5    .033       0  4972.6     .05       0
Bank Sta=4964.5,4972.6
XS Rating Curve= 0 ,0
Exp/Cntr=0.3,0.1

Type RM Length L Ch R = 1 ,1819    ,536,536,536
BEGIN DESCRIPTION:
BEECHMAN BRANCH 3.0
END DESCRIPTION:
XS GIS Cut Line= 3
      2220579.03      7241459.98        2220179.        7241710.
      2219483.85      7242919.66
#Sta/Elev= 30
  4528.5  944.33  4730.8   928.6  4825.1  924.42  4882.9  919.21  4986.7  918.36
  5009.7  916.73  5010.9  916.23    5018  916.73  5051.3  918.31  5380.8  917.48
  5565.4  919.31  5630.6  922.82  5646.1  925.43    5658  924.49  5726.8  926.68
  5834.8   933.6  5931.1  934.04  5968.5  937.41  5995.8  942.96  6003.7  943.12
  6026.7   939.5    6151  939.58  6172.6  940.62  6178.4  943.77  6194.2  944.23
  6199.9   947.4  6222.8  950.03  6253.1  947.13  6303.5  952.46  6395.4  957.13
#Mann= 3 ,-1 , 0
  4528.5     .05       0  5009.7     .04       0    5018     .05       0
Bank Sta=5009.7,5018
XS Rating Curve= 0 ,0
Exp/Cntr=0.3,0.1

Type RM Length L Ch R = 1 ,1283    ,100,100,100
BEGIN DESCRIPTION:
BEECHMAN BRANCH 2.5
END DESCRIPTION:
XS GIS Cut Line= 5
       2221150.4      7241383.46      2220134.75      7241107.41
      2219848.29      7241326.16      2219624.33      7241445.95
        2219479.        7241810.
#Sta/Elev= 30
    3585  975.12  3734.2  970.28    3883  962.46    4037  956.34  4190.9  945.98
  4225.5  941.56  4344.9  933.48  4384.7  928.46    4488  924.53  4568.1     919
  4714.9  915.54  4949.8  918.15  4978.9   917.7  5000.4  915.38  5004.3     913
  5005.5   912.5  5012.6     913  5015.4   914.5  5031.1  915.46  5037.3  918.33
    5043  917.31  5065.2   918.7  5119.4  916.97  5155.9  917.76  5190.9  916.38
  5207.2  917.47  5212.9  915.83  5311.1   915.9  5545.6  928.54  5643.9  936.67
#Mann= 3 ,-1 , 0
    3585     .05       0  5004.3     .04       0  5012.6     .05       0
Bank Sta=5000.4,5015.4
XS Rating Curve= 0 ,0
Exp/Cntr=0.3,0.1

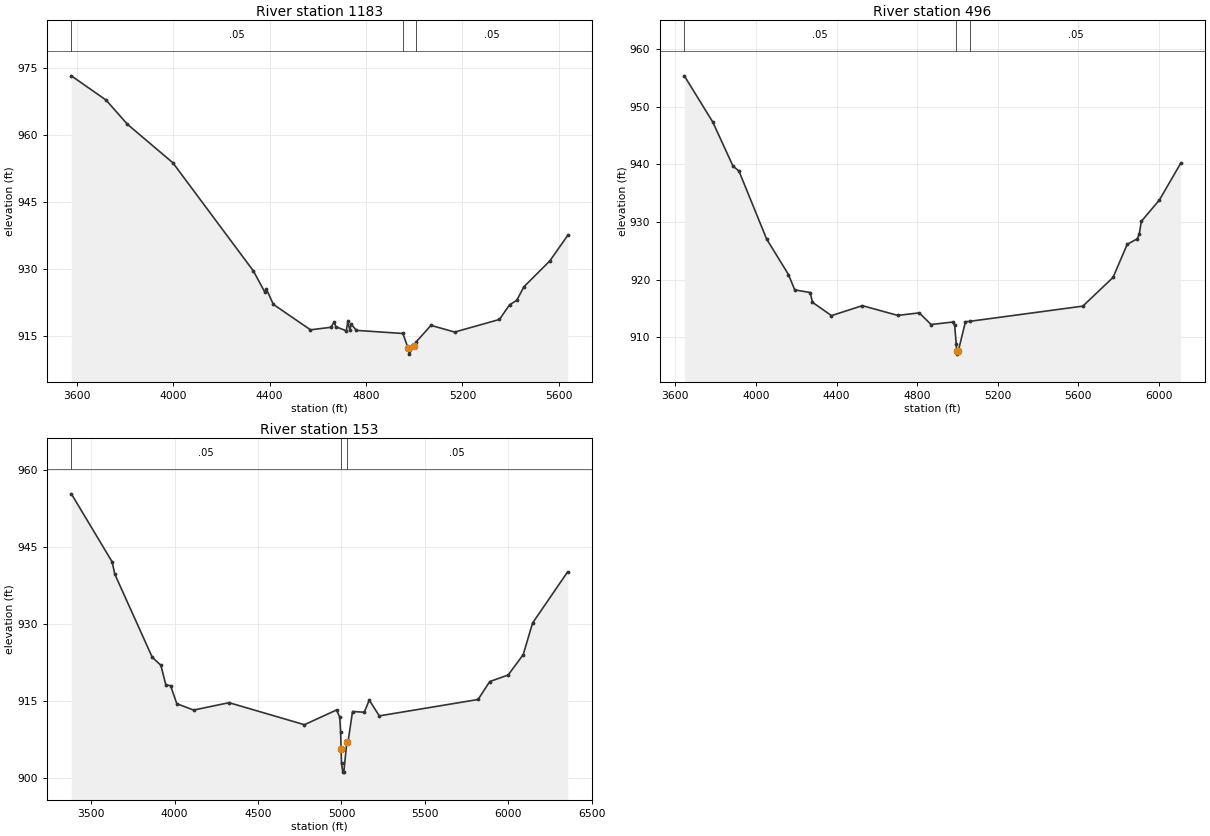
Type RM Length L Ch R = 1 ,1183    ,687,687,687
BEGIN DESCRIPTION:
BEECHMAN BRANCH 2.0
END DESCRIPTION:
XS GIS Cut Line= 5
      2221087.86      7241326.16      2220072.25      7241050.12
      2219785.79      7241268.87      2219561.83      7241388.66
      2219416.48      7241752.75
#Sta/Elev= 30
  3577.7  973.32  3721.6   967.9  3810.3  962.48  3998.9  953.86    4333  929.65
  4381.2  924.84  4386.4  925.64  4415.8  922.17  4569.8  916.48  4653.9  917.04
  4668.4  918.21  4674.7  917.19  4718.3  916.25  4724.6  918.36  4732.8  916.48
  4739.1  917.74  4760.1  916.36  4953.2  915.66    4974  912.47  4979.3  911.04
  4998.1   912.8  5009.6  913.86  5069.6  917.48    5168  915.98  5353.7   918.8
    5396   922.1  5425.6  923.08  5455.2  926.11    5563  931.92  5636.6  937.59
#Mann= 3 ,-1 , 0
  3577.7     .05       0  4953.2    .033       0  5009.6     .05       0
Bank Sta=4974,4998.1
XS Rating Curve= 0 ,0
Exp/Cntr=0.3,0.1

Type RM Length L Ch R = 1 ,496     ,343,343,343
BEGIN DESCRIPTION:
BEECHMAN BRANCH 1.0
END DESCRIPTION:
XS GIS Cut Line= 4
      2220725.45       7241209.4      2219513.65      7240698.99
      2219399.07      7240752.81      2219400.81      7241775.21
#Sta/Elev= 30
  3644.3  955.38  3785.7  947.35    3886  939.71  3915.2  938.88  4052.8  927.07
  4161.3   920.9  4192.5  918.24  4269.1  917.78  4280.6  916.08  4374.9  913.77
  4528.2   915.5  4703.8  913.81  4810.9  914.25  4869.2  912.23  4977.1  912.66
  4986.4  912.12  4994.4  908.77  4995.7  907.59  4996.9  907.09  5004.2  907.59
    5040  912.71  5062.8  912.79    5623  915.42    5773  920.41    5843  926.14
    5893   927.1    5903  927.92    5913  930.12    6003  933.84  6108.2  940.18
#Mann= 3 ,-1 , 0
  3644.3     .05       0  4994.4    .033       0  5062.8     .05       0
Bank Sta=4995.7,5004.2
XS Rating Curve= 0 ,0
Exp/Cntr=0.3,0.1

Type RM Length L Ch R = 1 ,153     ,0,0,0
BEGIN DESCRIPTION:
BEECHMAN BRANCH 0.5
END DESCRIPTION:
XS GIS Cut Line= 4
      2220725.46      7241209.41      2219399.12      7240419.01
      2219294.95      7240460.68       2219400.8      7241775.24
#Sta/Elev= 30
  3380.6  955.38  3625.2  942.12  3640.8  939.75  3865.4  923.55  3917.2  921.98
  3946.9  918.17  3975.6     918  4012.6  914.49  4113.8  913.25    4326  914.69
  4777.7   910.4  4970.4  913.27  4989.3   911.9  4994.7  909.06 4997.66  905.66
  5000.1  902.87  5007.9  901.16  5013.9  901.16  5031.9  907.02    5039  907.02
  5066.2  912.97  5136.4  912.83  5166.5  915.19  5226.7  912.12  5818.6  915.31
  5888.9  918.81  5999.2  920.08  6089.5  924.06  6145.5  930.21  6355.6  940.18
#Mann= 3 , 0 , 0
  3380.6     .05       0 4997.66    .033       0  5031.9     .05       0
Bank Sta=4997.66,5031.9
XS Rating Curve= 0 ,0
Exp/Cntr=0.3,0.1

Chan Stop Cuts=-1
Use User Specified Reach Order=0
Composite Channel Slope=5