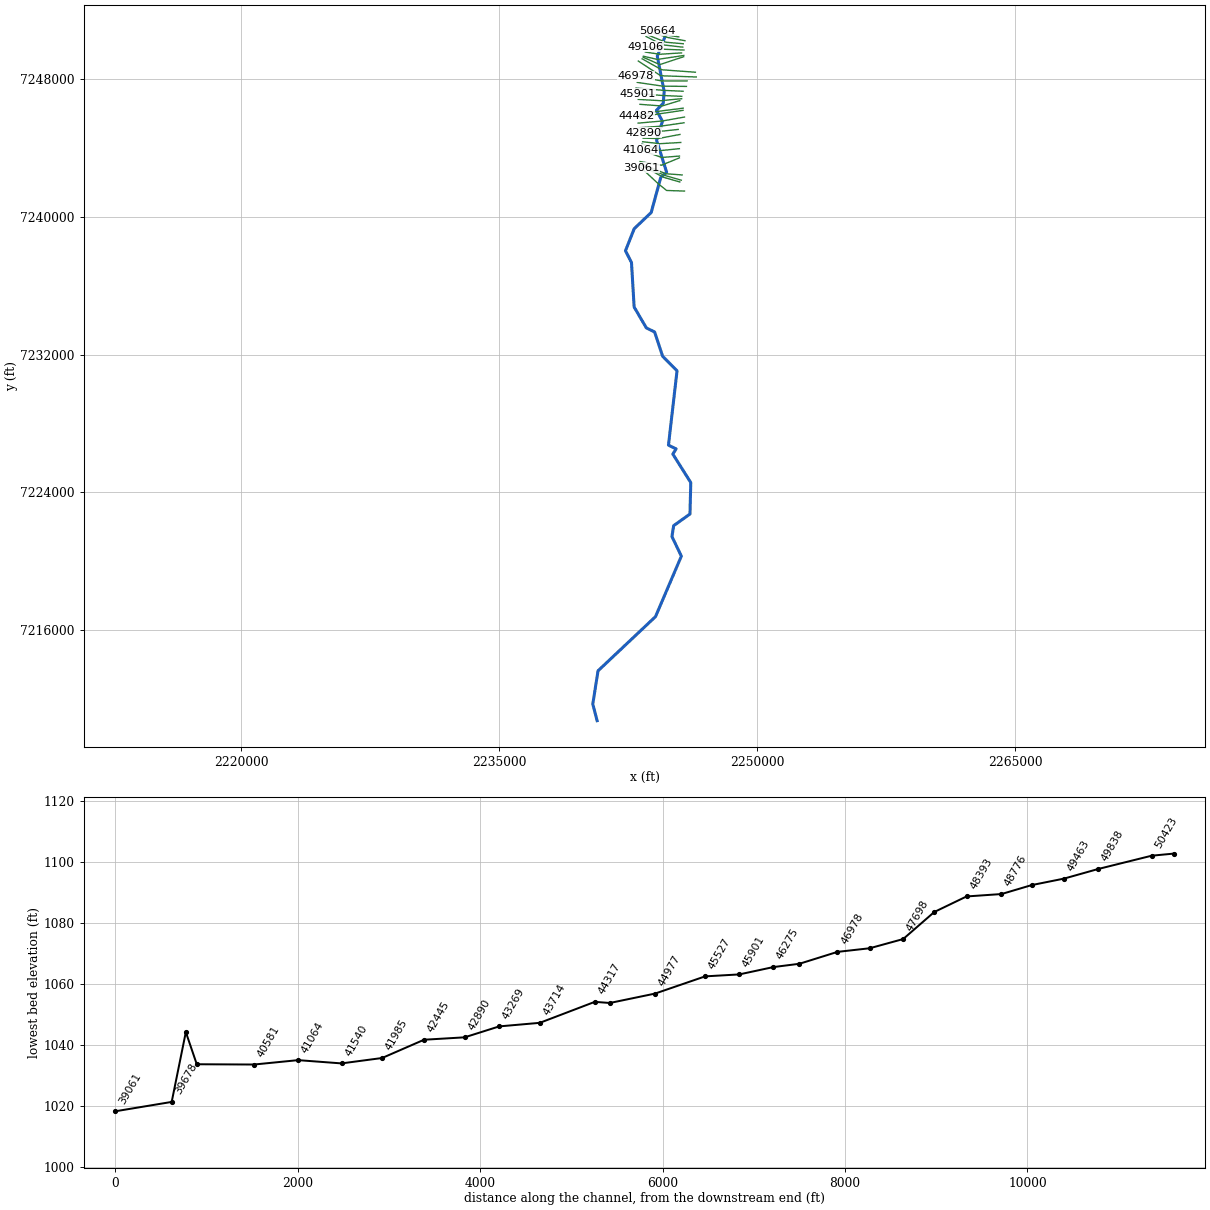
--- BRADEN BRANCH.prj (project) ---

Proj Title=BRADEN BRANCH Base Level Engineering
Current Plan=p01
Default Exp/Contr=0.3,0.1
English Units
Geom File=g01
Flow File=f01
Plan File=p01
Y Axis Title=Elevation
X Axis Title(PF)=Main Channel Distance
X Axis Title(XS)=Station
BEGIN DESCRIPTION:
BRADEN BRANCH
END DESCRIPTION:
DSS Export Rating Curves= 0
DSS Export Rating Curve Sorted= 0
DSS Export Volume Flow Curves= 0
DXF OffsetX= 0
DXF OffsetY= 0
DXF ScaleX= 1
DXF ScaleY= 10

--- BRADEN BRANCH.p01 (plan) ---

Plan Title=Multiple Run
Short Identifier=Multiple
Geom File=g01
Flow File=f01
Subcritical Flow
K Sum by GR= 0
Std Step Tol= 0.01
Critical Tol= 0.01
Num of Std Step Trials= 20
Max Error Tol= 0.3
Flow Tol Ratio= 0.001
Split Flow NTrial= 30
Split Flow Tol= 0.02
Split Flow Ratio= 0.02
Log Output Level= 0
Friction Slope Method= 1
Unsteady Friction Slope Method= 2
Unsteady Bridges Friction Slope Method= 1
Parabolic Critical Depth
Global Vel Dist=  1 , 1 , 1
Global Log Level= 0
CheckData=True
Encroach Param= -1, 0, 0, 0
BEGIN DESCRIPTION:
Multiple Run
END DESCRIPTION:

--- BRADEN BRANCH.f01 (steady flow) ---

Flow Title=Multiple
Program Version=4.10
Number of Profiles= 7
Profile Names=10-year,25-year,50-year,1pct_min,100-year,1pct_plu,500-year
River Rch & RM=BRADEN BRANCH,Reach-1         ,50664
     751    1056    1314     812    1620    3233    2471
River Rch & RM=BRADEN BRANCH,Reach-1         ,44482
    1105    1580    1988    1240    2474    4935    3843
River Rch & RM=BRADEN BRANCH,Reach-1         ,35051
    1124    1608    2024    1263    2519    5026    3918
River Rch & RM=BRADEN BRANCH,Reach-1         ,33670
    1786    2611    3335    2108    4205    8390    6714
River Rch & RM=BRADEN BRANCH,Reach-1         ,26407
    1820    2660    3396    2146    4281    8542    6832
River Rch & RM=BRADEN BRANCH,Reach-1         ,22673
    3174    4743    6147    3936    7854   15670   12872
River Rch & RM=BRADEN BRANCH,Reach-1         ,16412
    4080    6144    8004    5147   10270   20492   16979
River Rch & RM=BRADEN BRANCH,Reach-1         ,11156
    4353    6557    8543    5494   10962   21872   18119
River Rch & RM=BRADEN BRANCH,Reach-1         ,5560
    4301    6464    8408    5397   10769   21486   17735
Boundary for River Rch & Prof#=BRADEN BRANCH,Reach-1         , 1
Up Type= 0
Dn Type= 3
Dn Slope=0.002
Boundary for River Rch & Prof#=BRADEN BRANCH,Reach-1         , 2
Up Type= 0
Dn Type= 3
Dn Slope=0.002
Boundary for River Rch & Prof#=BRADEN BRANCH,Reach-1         , 3
Up Type= 0
Dn Type= 3
Dn Slope=0.002
Boundary for River Rch & Prof#=BRADEN BRANCH,Reach-1         , 4
Up Type= 0
Dn Type= 3
Dn Slope=0.002
Boundary for River Rch & Prof#=BRADEN BRANCH,Reach-1         , 5
Up Type= 0
Dn Type= 3
Dn Slope=0.002
Boundary for River Rch & Prof#=BRADEN BRANCH,Reach-1         , 6
Up Type= 0
Dn Type= 3
Dn Slope=0.002
Boundary for River Rch & Prof#=BRADEN BRANCH,Reach-1         , 7
Up Type= 0
Dn Type= 3
Dn Slope=0.002
DSS Import GetInterval= 0
DSS Import GetPeak= 0
DSS Import FillOption= 0

--- BRADEN BRANCH.g01 (geometry) ---

Geom Title=Existing Conditions
Program Version=4.10

River Reach=BRADEN BRANCH   ,Reach-1
Reach XY= 30
        2244679.        7250610.      2244179.33      7249344.97
      2244579.51      7247294.74      2244525.66      7246611.36
      2244129.53      7246199.55      2244480.03      7245565.42
      2244136.01      7244460.19       2244721.4      7242606.67
      2244380.48      7242298.52      2243823.54      7240257.55
      2242836.81      7239316.19      2242328.77      7238034.93
      2242678.41      7237349.38      2242832.75      7234761.55
      2243542.36      7233546.65      2244023.54      7233312.46
      2244487.02      7231903.66      2245326.86      7231054.03
      2244828.78      7226730.05      2245274.05      7226512.51
      2245082.34      7226211.72      2246126.74      7224554.06
      2246078.68      7222725.02      2245130.64      7222048.17
      2245030.97      7221415.65      2245578.46       7220275.9
      2244073.48      7216757.57      2240732.62       7213608.5
      2240428.29      7211675.06        2240679.        7210710.

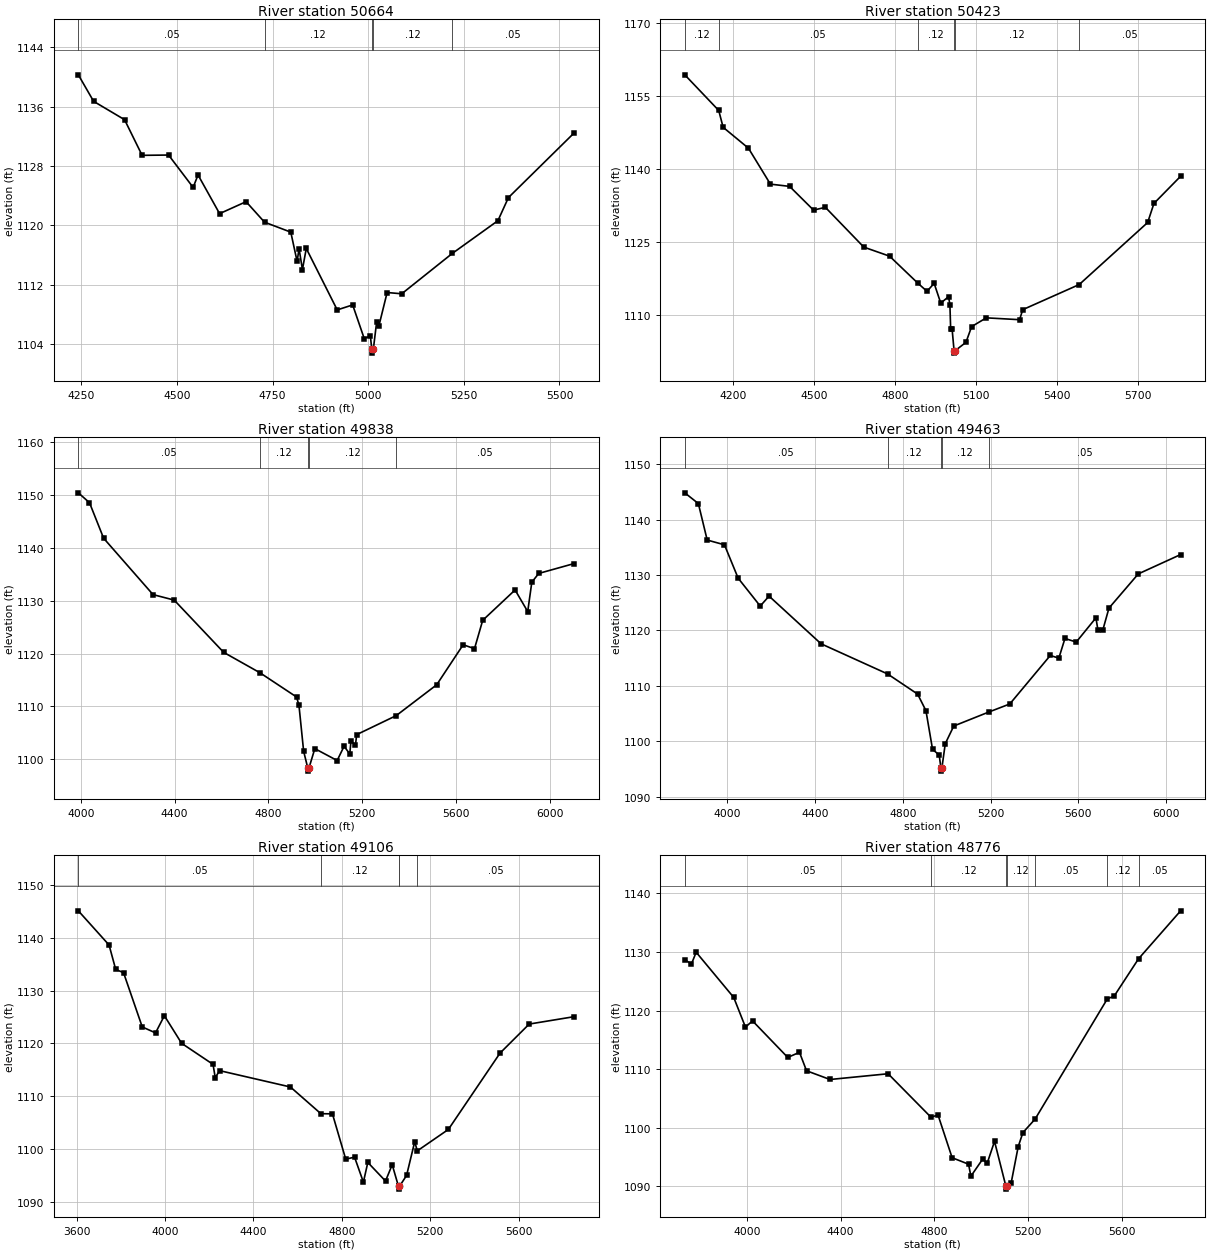
Type RM Length L Ch R = 1 ,50664   ,241,241,241
BEGIN DESCRIPTION:
BRADEN BRANCH 101.5
END DESCRIPTION:
XS GIS Cut Line= 3
      2245428.53      7250470.32      2244678.58      7250582.29
      2244204.59      7250837.51
#Sta/Elev= 30
  4241.8 1140.27  4281.8  1136.7  4362.7 1134.23  4408.6 1129.43  4477.8 1129.47
    4542 1125.11  4554.8 1126.79  4611.2 1121.58  4680.5 1123.19  4728.7 1120.43
  4797.4 1119.09  4813.9 1115.15    4819 1116.87  4827.8 1114.05  4837.9 1116.89
  4918.8 1108.62  4959.2 1109.29  4989.5 1104.75  5005.5 1105.13  5009.2  1103.3
  5009.5  1102.8  5013.2  1103.3  5021.8 1106.95  5027.4 1106.39  5049.3 1110.96
  5087.5 1110.79  5219.9 1116.23    5339 1120.63  5366.5 1123.74  5538.4 1132.45
#Mann= 5 ,-1 , 0
  4241.8     .05       0  4728.7     .12       0  5009.2     .07       0
  5013.2     .12       0  5219.9     .05       0
Bank Sta=5009.2,5013.2
XS Rating Curve= 0 ,0
Exp/Cntr=0.3,0.1

Type RM Length L Ch R = 1 ,50423   ,585,585,585
BEGIN DESCRIPTION:
BRADEN BRANCH 101.0
END DESCRIPTION:
XS GIS Cut Line= 3
      2245790.51      7250248.96      2244821.81      7250426.04
      2244012.95      7250686.12
#Sta/Elev= 30
  4022.1 1159.29  4147.6 1151.97  4163.9 1148.51  4257.5 1144.22  4338.8 1136.83
  4409.9 1136.37  4498.5 1131.49  4542.1 1132.07  4684.4 1123.89  4779.8 1122.03
  4884.5 1116.47  4918.2 1114.81  4944.6 1116.45    4969 1112.39  4997.8  1113.7
  5002.9  1112.1  5005.7 1107.09    5011 1107.09  5018.3 1102.61  5018.6 1102.11
  5022.3 1102.61  5062.3 1104.33  5083.3 1107.56  5137.6 1109.36  5260.7 1108.98
  5272.4 1111.04  5481.3  1116.2  5734.6 1128.95  5757.8 1132.87  5856.5 1138.45
#Mann= 6 ,-1 , 0
  4022.1     .12       0  4147.6     .05       0  4884.5     .12       0
  5018.3     .07       0  5022.3     .12       0  5481.3     .05       0
Bank Sta=5018.3,5022.3
XS Rating Curve= 0 ,0
Exp/Cntr=0.3,0.1

Type RM Length L Ch R = 1 ,49838   ,375,375,375
BEGIN DESCRIPTION:
BRADEN BRANCH 100.0
END DESCRIPTION:
XS GIS Cut Line= 3
      2245686.39      7250071.87        2244679.        7250160.
      2243655.18      7250571.86
#Sta/Elev= 30
  3989.8 1150.45  4037.4 1148.58  4097.6 1141.86  4308.4 1131.18  4398.7 1130.14
  4609.6 1120.25  4764.2 1116.39  4920.7 1111.79  4930.8 1110.22  4950.8 1101.52
  4968.9 1098.26  4969.2 1097.76  4972.9 1098.26  4998.5 1102.02  5093.7 1099.77
  5123.3 1102.47  5147.5 1101.01  5152.9 1103.49  5171.7 1102.64    5177 1104.67
  5345.7 1108.27  5518.3 1114.11  5631.2 1121.69  5679.5 1120.94  5714.5 1126.31
  5852.6 1132.06  5906.5 1127.97    5924 1133.53  5953.6 1135.19  6104.6 1137.06
#Mann= 5 ,-1 , 0
  3989.8     .05       0  4764.2     .12       0  4968.9     .07       0
  4972.9     .12       0  5345.7     .05       0
Bank Sta=4968.9,4972.9
XS Rating Curve= 0 ,0
Exp/Cntr=0.3,0.1

Type RM Length L Ch R = 1 ,49463   ,357,357,357
BEGIN DESCRIPTION:
BRADEN BRANCH 99.0
END DESCRIPTION:
XS GIS Cut Line= 3
      2245660.36      7249873.95        2244479.        7250010.
       2243524.9      7250493.76
#Sta/Elev= 30
    3807 1144.82  3868.8 1142.88    3909  1136.3  3987.7 1135.44    4050 1129.42
  4150.6 1124.39  4190.9 1126.18  4427.7 1117.58  4730.7 1112.14  4867.7  1108.5
  4905.6 1105.51  4935.8 1098.51    4966 1097.52    4974  1095.1  4974.3  1094.6
    4978  1095.1  4993.7 1099.56  5032.4 1102.74  5191.1 1105.25  5287.7 1106.72
  5472.1 1115.47  5511.1 1114.99  5538.9 1118.54  5590.4 1117.89  5680.1 1122.26
  5689.2 1120.04  5711.5 1120.07  5739.4 1124.02    5873 1130.19  6065.9 1133.68
#Mann= 5 ,-1 , 0
    3807     .05       0  4730.7     .12       0    4974     .07       0
    4978     .12       0  5191.1     .05       0
Bank Sta=4974,4978
XS Rating Curve= 0 ,0
Exp/Cntr=0.3,0.1

Type RM Length L Ch R = 1 ,49106   ,330,330,330
BEGIN DESCRIPTION:
BRADEN BRANCH 98.0
END DESCRIPTION:
XS GIS Cut Line= 3
      2245728.02      7249707.29        2244329.        7249760.
      2243498.93      7249910.41
#Sta/Elev= 30
  3607.4 1145.09  3746.5 1138.62  3776.5    1134  3811.9  1133.4  3896.6 1123.13
  3956.7    1122  3996.7 1125.25  4074.8 1120.03  4216.9 1116.05  4226.9 1113.55
  4246.9 1114.86  4567.1 1111.77  4704.9 1106.72  4757.2 1106.69  4817.3 1098.12
  4857.3  1098.5  4897.3 1093.77  4917.3  1097.5  4997.4 1093.98  5027.7 1097.07
  5056.2 1092.95  5056.5 1092.45  5060.2 1092.95  5092.7 1095.04  5129.4  1101.4
  5141.3 1099.69  5281.8 1103.74  5515.6 1118.18  5647.5 1123.67    5851 1125.07
#Mann= 5 ,-1 , 0
  3607.4     .05       0  4704.9     .12       0  5056.2     .07       0
  5060.2     .12       0  5141.3     .05       0
Bank Sta=5056.2,5060.2
XS Rating Curve= 0 ,0
Exp/Cntr=0.3,0.1

Type RM Length L Ch R = 1 ,48776   ,383,383,383
BEGIN DESCRIPTION:
BRADEN BRANCH 97.0
END DESCRIPTION:
XS GIS Cut Line= 3
      2245587.42      7249540.62        2244329.        7249460.
      2243483.65      7249587.44
#Sta/Elev= 30
  3735.1 1128.68  3763.6 1127.97  3783.6 1129.97  3943.9 1122.25    3994 1117.18
  4024.1 1118.25  4174.4 1112.01  4224.5 1112.88  4254.6 1109.73  4354.8 1108.24
  4602.7 1109.22  4785.6  1101.8  4815.7 1102.18  4875.9 1094.88    4946 1093.78
    4956 1091.73  5006.2 1094.64  5025.5 1093.93  5056.8 1097.68  5105.3 1090.02
  5105.6 1089.52  5109.3 1090.02  5127.6 1090.53  5157.9 1096.78  5178.1 1099.18
  5229.8 1101.47  5538.6 1122.03  5566.9 1122.45  5671.4 1128.85    5851 1137.04
#Mann= 7 ,-1 , 0
  3735.1     .05       0  4785.6     .12       0  5105.3     .07       0
  5109.3     .12       0  5229.8     .05       0  5538.6     .12       0
  5671.4     .05       0
Bank Sta=5105.3,5109.3
XS Rating Curve= 0 ,0
Exp/Cntr=0.3,0.1

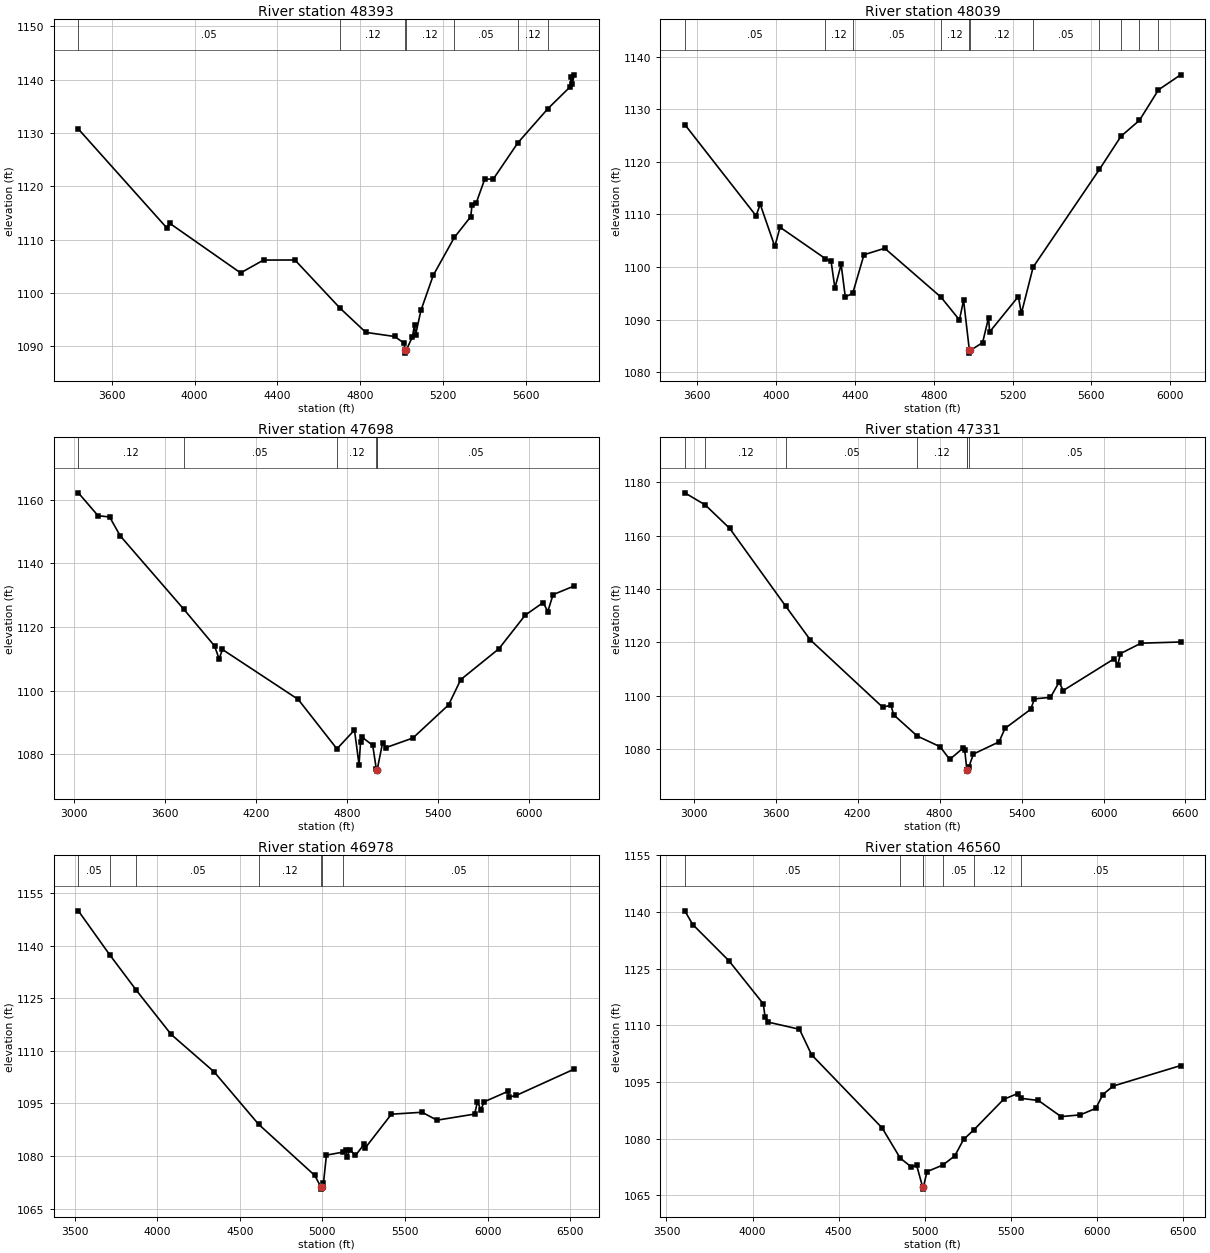
Type RM Length L Ch R = 1 ,48393   ,354,354,354
BEGIN DESCRIPTION:
BRADEN BRANCH 96.0
END DESCRIPTION:
XS GIS Cut Line= 3
      2245722.89      7249389.59        2244179.        7249160.
      2243368.67      7249347.92
#Sta/Elev= 30
  3439.1 1130.75  3867.7 1112.13  3880.5 1113.06  4222.3 1103.77  4332.7 1106.18
  4484.4 1106.19  4702.8 1097.13  4826.5 1092.62  4965.3 1091.85  5010.2 1090.63
  5016.7 1089.23    5017 1088.73  5020.7 1089.23  5051.3 1091.77  5061.4 1094.05
  5066.5 1092.15  5092.4 1096.74  5151.9 1103.33  5253.6 1110.42  5332.8 1114.32
  5338.7 1116.43  5359.3  1116.9  5400.3 1121.36  5441.4 1121.36  5560.7 1128.19
  5704.9 1134.56  5810.9  1138.6  5817.5 1140.46  5822.6 1139.13  5831.8 1140.91
#Mann= 7 ,-1 , 0
  3439.1     .05       0  4702.8     .12       0  5016.7     .07       0
  5020.7     .12       0  5253.6     .05       0  5560.7     .12       0
  5704.9     .05       0
Bank Sta=5016.7,5020.7
XS Rating Curve= 0 ,0
Exp/Cntr=0.3,0.1

Type RM Length L Ch R = 1 ,48039   ,341,341,341
BEGIN DESCRIPTION:
BRADEN BRANCH 95.0
END DESCRIPTION:
XS GIS Cut Line= 3
      2245712.43      7249316.66        2244329.        7248860.
      2243358.73      7249285.21
#Sta/Elev= 30
  3536.5 1127.07  3898.2 1109.72  3919.2 1111.92  3993.3  1103.9  4019.8 1107.55
  4249.1  1101.6    4279 1101.04  4298.3 1095.97  4329.9 1100.49    4351 1094.29
  4388.8    1095  4445.8 1102.32  4551.1 1103.55  4836.6 1094.26  4930.2 1089.93
  4951.2 1093.67  4980.8 1084.12  4981.1 1083.62  4984.8 1084.12  5047.9 1085.62
  5077.9 1090.36  5083.4 1087.65  5229.1 1094.38  5244.5 1091.17  5304.4 1099.98
  5640.6 1118.54  5750.1 1124.84  5843.7 1127.87  5940.4 1133.67  6052.7 1136.52
#Mann= 11 ,-1 , 0
  3536.5     .05       0  4249.1     .12       0  4388.8     .05       0
  4836.6     .12       0  4980.8     .07       0  4984.8     .12       0
  5304.4     .05       0  5640.6     .12       0  5750.1     .05       0
  5843.7     .12       0  5940.4     .05       0
Bank Sta=4980.8,4984.8
XS Rating Curve= 0 ,0
Exp/Cntr=0.3,0.1

Type RM Length L Ch R = 1 ,47698   ,367,367,367
BEGIN DESCRIPTION:
BRADEN BRANCH 94.0
END DESCRIPTION:
XS GIS Cut Line= 3
      2246394.73      7248415.62        2244429.        7248560.
      2243297.47      7249195.91
#Sta/Elev= 30
    3029  1162.1  3158.6 1154.93  3235.3 1154.51  3305.5 1148.58  3723.1 1125.63
  3927.1 1114.03  3957.2 1109.97  3979.2 1112.92  4478.6 1097.25    4734 1081.73
  4849.6 1087.64  4879.7 1076.77  4889.7 1083.91  4899.8 1085.39  4969.9 1082.84
  4993.9 1075.28  4995.5 1075.24  4995.8 1074.74  4999.5 1075.24  5035.4 1083.71
  5057.4 1082.13    5235 1085.14  5470.3 1095.55  5550.6 1103.48  5801.8 1113.15
  5975.2 1123.69  6093.8 1127.66  6124.2 1124.84  6158.8 1130.13    6298 1132.86
#Mann= 6 ,-1 , 0
    3029     .12       0  3723.1     .05       0    4734     .12       0
  4993.9     .05       0  4995.5    .033       0  4999.5     .05       0
Bank Sta=4995.5,4999.5
XS Rating Curve= 0 ,0
Exp/Cntr=0.3,0.1

Type RM Length L Ch R = 1 ,47331   ,353,353,353
BEGIN DESCRIPTION:
BRADEN BRANCH 93.0
END DESCRIPTION:
XS GIS Cut Line= 3
      2246446.79      7248139.58        2244379.        7248210.
      2243074.13      7249065.14
#Sta/Elev= 30
  2935.3 1175.99  3084.3 1171.48  3263.3  1162.7  3674.4 1133.48  3853.6 1120.91
  4383.9 1095.65    4444 1096.44    4464 1092.82  4636.5 1084.87  4804.2 1080.87
  4874.2 1076.08  4974.3 1080.45  4984.3 1079.49  4999.8 1072.22    5000 1071.72
  5003.8 1072.22  5013.9 1073.23    5048 1078.14  5234.9 1082.66  5279.3 1087.74
  5467.1 1094.88  5494.5  1098.8  5611.8 1099.35    5675 1105.06  5705.2 1101.92
  6080.3 1113.89  6103.2 1111.34  6124.2 1115.76  6274.9 1119.66  6564.4  1120.1
#Mann= 7 ,-1 , 0
  2935.3     .05       0  3084.3     .12       0  3674.4     .05       0
  4636.5     .12       0  4999.8     .07       0  5003.8     .12       0
  5013.9     .05       0
Bank Sta=4999.8,5003.8
XS Rating Curve= 0 ,0
Exp/Cntr=0.3,0.1

Type RM Length L Ch R = 1 ,46978   ,418,418,418
BEGIN DESCRIPTION:
BRADEN BRANCH 92.0
END DESCRIPTION:
XS GIS Cut Line= 3
      2245911.33      7247908.24        2244429.        7247910.
      2242933.04      7248184.12
#Sta/Elev= 30
  3521.6 1149.89  3710.6 1137.42  3873.6  1127.2  4083.9 1114.64  4343.9 1103.98
  4613.1 1089.04  4953.9 1074.42  4991.9 1071.03  4992.2 1070.53  4995.9 1071.03
  5006.5 1072.28  5024.3 1080.23  5125.5 1081.09  5141.9 1081.71    5147 1079.58
  5166.6 1081.73  5200.2 1080.13  5253.3 1083.36  5258.4 1082.21  5417.9  1091.9
  5603.8 1092.45  5693.8 1090.19  5921.7 1091.93  5939.3 1095.44  5959.6 1093.16
  5979.9 1095.43  6122.3 1098.38  6132.4 1096.82  6173.1 1097.23  6524.8 1104.75
#Mann= 7 ,-1 , 0
  3521.6     .05       0  3710.6     .12       0  3873.6     .05       0
  4613.1     .12       0  4991.9     .07       0  4995.9     .12       0
  5125.5     .05       0
Bank Sta=4991.9,4995.9
XS Rating Curve= 0 ,0
Exp/Cntr=0.3,0.1

Type RM Length L Ch R = 1 ,46560   ,285,285,285
BEGIN DESCRIPTION:
BRADEN BRANCH 91.0
END DESCRIPTION:
XS GIS Cut Line= 3
      2245874.87      7247590.53      2244489.45      7247606.16
      2243012.13      7247824.64
#Sta/Elev= 30
  3606.7 1140.28  3652.6 1136.66  3862.6 1127.08  4062.6 1115.65  4072.6 1112.25
  4092.6  1110.8  4272.6 1108.93  4342.6  1102.2  4752.6 1082.81  4857.3 1074.84
  4922.7 1072.46  4952.7 1072.96  4987.9 1067.12  4988.2 1066.62  4991.9 1067.12
  5012.9 1071.25  5104.8 1072.99  5174.6 1075.43  5225.2 1079.76  5286.4 1082.37
  5457.7 1090.38  5538.5  1091.9  5557.5 1090.66  5659.8 1090.08  5791.3 1085.82
  5902.5 1086.27  5993.4    1088  6033.9 1091.66  6094.5 1093.91  6485.6 1099.32
#Mann= 7 ,-1 , 0
  3606.7     .05       0  4857.3     .12       0  4987.9     .07       0
  4991.9     .12       0  5104.8     .05       0  5286.4     .12       0
  5557.5     .05       0
Bank Sta=4987.9,4991.9
XS Rating Curve= 0 ,0
Exp/Cntr=0.3,0.1

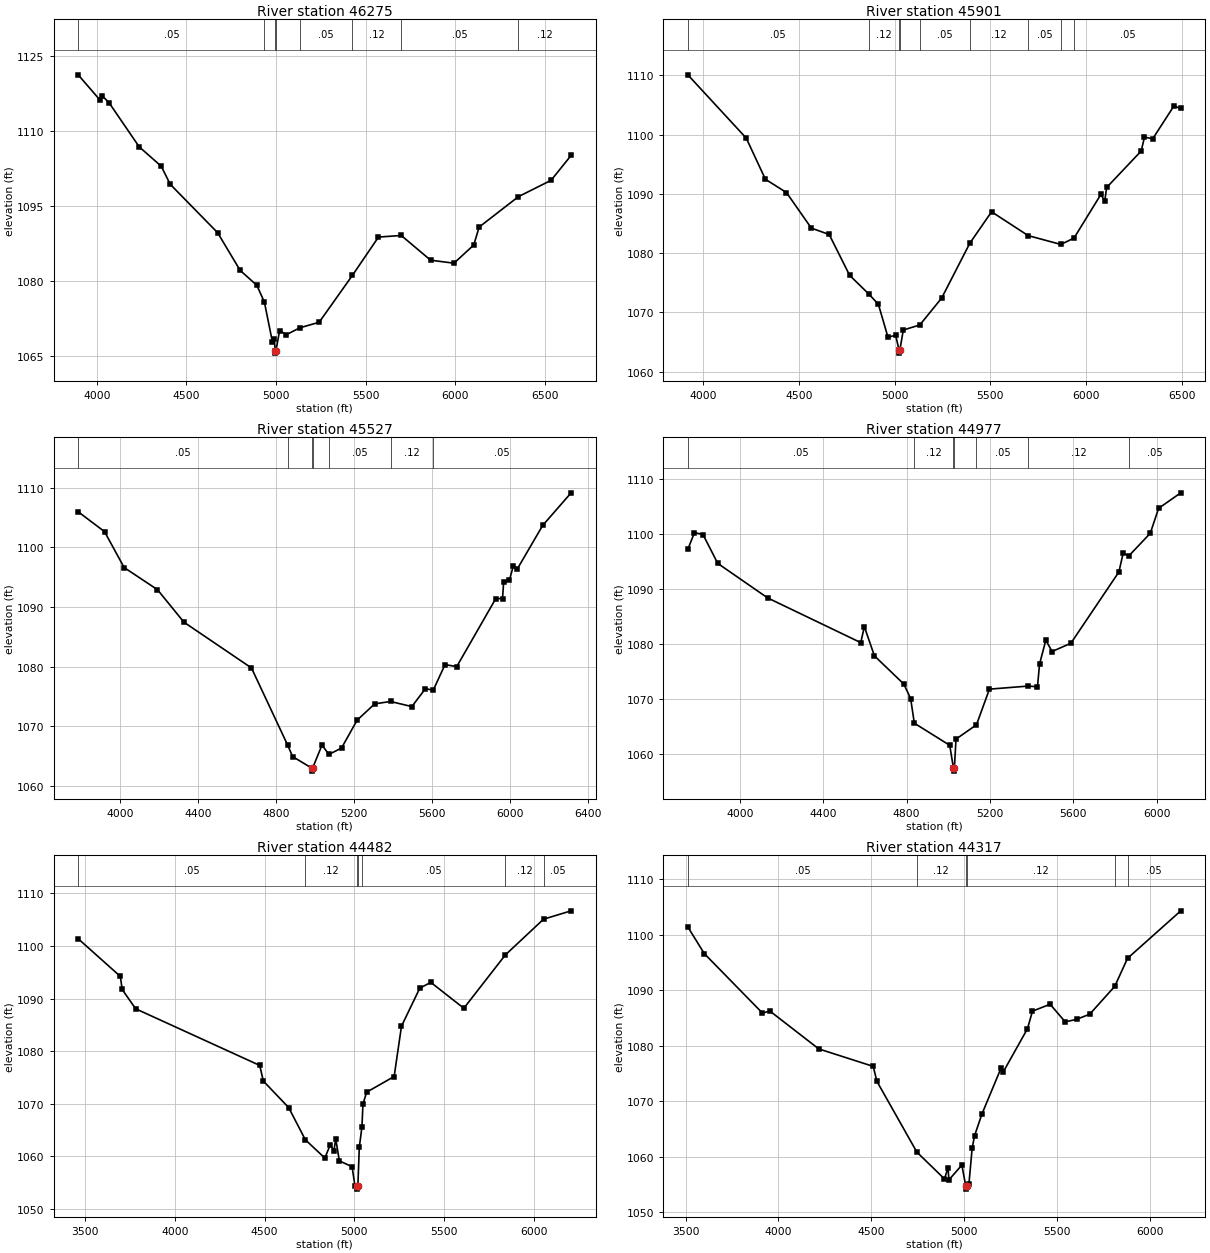
Type RM Length L Ch R = 1 ,46275   ,374,374,374
BEGIN DESCRIPTION:
BRADEN BRANCH 90.0
END DESCRIPTION:
XS GIS Cut Line= 3
      2245682.19      7247309.28        2244579.        7247360.
      2242937.35      7247496.79
#Sta/Elev= 30
  3895.8 1121.15  4017.2 1116.12  4029.1 1116.99  4069.2 1115.52  4236.2 1106.77
  4359.5 1102.88  4409.5 1099.28  4674.2  1089.6  4799.9 1082.07  4893.2 1079.09
  4935.5  1075.7  4980.1 1067.76  4990.1 1068.41  4995.7 1066.04  4995.9 1065.54
  4999.7 1066.04  5020.2 1070.06  5057.9 1069.23  5133.2  1070.6    5241 1071.71
  5426.4 1081.07  5572.1 1088.73  5699.2 1089.05  5863.1 1084.11  5993.6 1083.51
    6104 1087.15  6134.1 1090.73  6353.3 1096.81  6535.5 1100.07  6647.5 1105.05
#Mann= 8 ,-1 , 0
  3895.8     .05       0  4935.5     .12       0  4995.7     .07       0
  4999.7     .12       0  5133.2     .05       0  5426.4     .12       0
  5699.2     .05       0  6353.3     .12       0
Bank Sta=4995.7,4999.7
XS Rating Curve= 0 ,0
Exp/Cntr=0.3,0.1

Type RM Length L Ch R = 1 ,45901   ,374,374,374
BEGIN DESCRIPTION:
BRADEN BRANCH 89.0
END DESCRIPTION:
XS GIS Cut Line= 3
      2245604.01      7247012.41        2244529.        7247060.
       2243032.6      7247168.55
#Sta/Elev= 30
  3919.5 1110.09  4224.8 1099.41  4324.9 1092.47  4435.2 1090.22  4565.1 1084.22
  4658.3 1083.15  4765.3 1076.25  4865.3 1073.11  4915.5 1071.37  4965.5 1065.82
  5005.6 1066.14  5023.6 1063.63  5023.9 1063.13  5027.6 1063.63  5045.7 1067.03
  5131.8 1067.88  5246.2 1072.42  5393.3 1081.67  5506.9 1086.98  5698.3 1082.96
  5869.2 1081.47  5938.1 1082.55  6078.4 1089.91  6098.5 1088.78  6108.5 1091.08
    6289 1097.23  6306.3 1099.59  6349.1 1099.29  6459.4  1104.8  6495.9 1104.45
#Mann= 9 ,-1 , 0
  3919.5     .05       0  4865.3     .12       0  5023.6     .07       0
  5027.6     .12       0  5131.8     .05       0  5393.3     .12       0
  5698.3     .05       0  5869.2     .12       0  5938.1     .05       0
Bank Sta=5023.6,5027.6
XS Rating Curve= 0 ,0
Exp/Cntr=0.3,0.1

Type RM Length L Ch R = 1 ,45527   ,550,550,550
BEGIN DESCRIPTION:
BRADEN BRANCH 88.0
END DESCRIPTION:
XS GIS Cut Line= 3
      2245593.59      7246876.99        2244379.        7246760.
      2243073.38      7246835.29
#Sta/Elev= 30
  3783.6 1105.98  3918.8 1102.65  4019.3 1096.63  4190.1 1092.92  4325.8 1087.47
  4672.3 1079.79    4858 1066.84  4883.3 1064.93  4981.7 1062.99    4982 1062.49
  4985.7 1062.99  5033.9 1066.86  5069.4 1065.29    5134 1066.36  5214.2 1071.04
  5304.3 1073.77  5385.4 1074.17  5494.6 1073.31  5564.7 1076.33  5604.2 1076.05
  5664.9 1080.35    5725 1080.02  5925.3 1091.43  5959.8 1091.43  5965.4 1094.14
  5995.5 1094.54  6015.5 1096.96  6035.5 1096.39  6165.7 1103.69  6311.6 1109.16
#Mann= 7 ,-1 , 0
  3783.6     .05       0    4858     .12       0  4981.7     .07       0
  4985.7     .12       0  5069.4     .05       0  5385.4     .12       0
  5604.2     .05       0
Bank Sta=4981.7,4985.7
XS Rating Curve= 0 ,0
Exp/Cntr=0.3,0.1

Type RM Length L Ch R = 1 ,44977   ,495,495,495
BEGIN DESCRIPTION:
BRADEN BRANCH 87.0
END DESCRIPTION:
XS GIS Cut Line= 4
      2245489.43      7246767.61      2244468.62      7246455.12
      2244213.41      7246470.74      2243172.89      7246548.78
#Sta/Elev= 30
  3749.8 1097.22  3781.6 1100.26  3822.6 1099.92  3893.4 1094.66  4133.2 1088.37
  4580.1 1080.23  4597.3 1083.14  4645.7 1077.82  4787.2 1072.67  4819.7 1070.03
  4837.2 1065.56  5007.3 1061.53  5025.3 1057.33  5025.6 1056.83  5029.5 1057.33
  5037.4 1062.66  5135.7 1065.27  5197.8 1071.76  5384.7 1072.32  5428.5 1072.19
  5438.5 1076.33  5468.6 1080.67  5498.7 1078.61  5588.9 1080.12  5819.6 1093.11
  5839.6 1096.49  5868.2 1096.07    5970 1100.14  6010.1 1104.69  6116.5 1107.51
#Mann= 7 ,-1 , 0
  3749.8     .05       0  4837.2     .12       0  5025.3     .07       0
  5029.5     .12       0  5135.7     .05       0  5384.7     .12       0
  5868.2     .05       0
Bank Sta=5025.3,5029.5
XS Rating Curve= 0 ,0
Exp/Cntr=0.3,0.1

Type RM Length L Ch R = 1 ,44482   ,165,165,165
BEGIN DESCRIPTION:
BRADEN BRANCH 86.5
END DESCRIPTION:
XS GIS Cut Line= 3
      2245682.16      7246324.91      2244150.91       7246132.2
      2242973.92      7245887.43
#Sta/Elev= 30
  3461.8 1101.37  3696.5 1094.21  3706.9 1091.72  3781.9 1088.05  4472.9 1077.28
    4493 1074.31  4634.1 1069.26  4727.2 1063.13  4835.7 1059.66  4865.9  1062.2
  4886.1 1060.99  4896.2 1063.34  4916.3 1059.13  4987.3 1058.01  5003.6 1054.29
  5015.2 1054.25  5015.5 1053.75  5019.4 1054.25  5027.5 1061.72  5042.1 1065.55
  5047.9 1069.94  5068.4 1072.19  5221.6 1075.17  5262.4 1084.74  5364.6 1091.98
  5425.9 1093.07  5609.7 1088.15  5840.9 1098.29  6053.7 1105.09  6207.3 1106.68
#Mann= 7 ,-1 , 0
  3461.8     .05       0  4727.2     .12       0  5015.2     .07       0
  5019.4     .12       0  5042.1     .05       0  5840.9     .12       0
  6053.7     .05       0
Bank Sta=5015.2,5019.4
XS Rating Curve= 0 ,0
Exp/Cntr=0.3,0.1

Type RM Length L Ch R = 1 ,44317   ,603,603,603
BEGIN DESCRIPTION:
BRADEN BRANCH 86.0
END DESCRIPTION:
XS GIS Cut Line= 3
      2245676.95      7246199.91      2244192.58      7245981.16
      2243057.19      7245767.62
#Sta/Elev= 30
  3512.3 1101.41  3601.2  1096.6  3914.5 1085.87  3953.7 1086.26  4217.8 1079.41
  4511.1 1076.26  4531.1 1073.55  4746.2  1060.8    4895 1055.96    4914 1057.99
    4919 1055.79  4988.7 1058.46  5009.9 1054.62  5010.2 1054.12  5014.1 1054.62
  5026.5 1054.98  5043.9 1061.45    5057 1063.74  5096.4 1067.64  5199.5 1075.93
  5211.5 1075.25    5342 1083.05    5369 1086.22  5464.1 1087.47  5545.5 1084.29
  5606.5 1084.74  5677.7 1085.68  5812.3  1090.7  5881.2 1095.75    6168 1104.32
#Mann= 6 ,-1 , 0
  3512.3     .05       0  4746.2     .12       0  5009.9     .07       0
  5014.1     .12       0  5812.3     .12       0  5881.2     .05       0
Bank Sta=5009.9,5014.1
XS Rating Curve= 0 ,0
Exp/Cntr=0.3,0.1

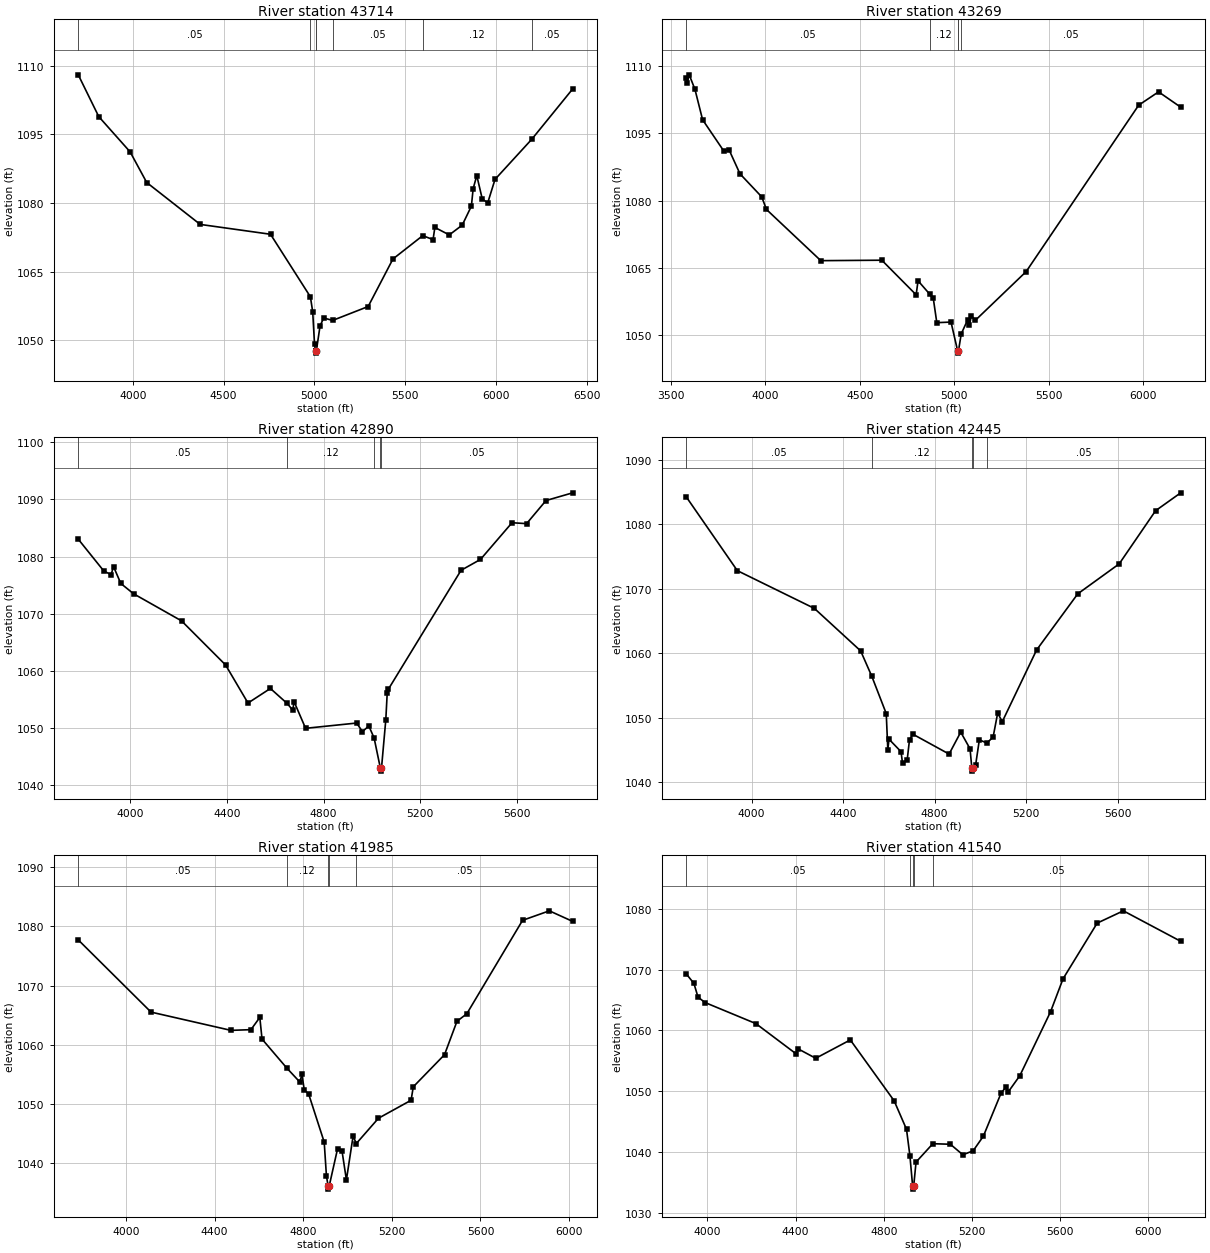
Type RM Length L Ch R = 1 ,43714   ,445,445,445
BEGIN DESCRIPTION:
BRADEN BRANCH 85.0
END DESCRIPTION:
XS GIS Cut Line= 3
       2245760.3      7245809.29      2244468.62      7245580.12
      2243063.22      7245455.19
#Sta/Elev= 30
  3699.4 1108.01  3812.4 1098.88  3985.1 1091.18  4076.5 1084.49    4371 1075.34
  4758.2 1073.19  4977.9 1059.53  4990.6 1056.26  5000.7 1049.14  5006.3 1047.73
  5006.7 1047.23  5010.7 1047.73    5031 1053.16    5051  1054.9  5100.7 1054.38
    5296 1057.41  5432.5 1067.79  5596.6 1072.89  5653.4 1072.02  5663.4 1074.68
  5742.7 1073.05    5814 1075.18  5864.5 1079.33  5874.3 1083.16  5894.3    1086
  5924.5 1080.89  5954.6 1080.06  5994.7 1085.18  6197.6 1093.96  6422.2 1104.92
#Mann= 7 ,-1 , 0
  3699.4     .05       0  4977.9     .12       0  5006.3     .07       0
  5010.7     .12       0  5100.7     .05       0  5596.6     .12       0
  6197.6     .05       0
Bank Sta=5006.3,5010.7
XS Rating Curve= 0 ,0
Exp/Cntr=0.3,0.1

Type RM Length L Ch R = 1 ,43269   ,379,379,379
BEGIN DESCRIPTION:
BRADEN BRANCH 84.0
END DESCRIPTION:
XS GIS Cut Line= 3
      2245734.29      7245475.96       2244333.2      7245272.83
      2243132.02      7245189.63
#Sta/Elev= 30
  3580.6 1107.37  3584.1 1106.13    3596    1108  3626.4 1104.76  3666.8 1098.01
  3777.9 1091.12  3808.2 1091.21  3864.9 1085.97    3980 1080.85  4005.4 1078.03
  4293.3 1066.64  4616.6 1066.74  4798.5 1059.04  4808.6 1062.16  4870.5 1059.18
  4889.4 1058.23    4908 1052.84  4983.3 1052.97  5018.4 1046.56  5018.8 1046.06
  5022.8 1046.56  5037.4 1050.34  5070.7  1053.4  5080.7 1052.24  5090.8 1054.36
  5112.7 1053.38  5381.5 1064.21  5977.9 1101.25  6083.1 1104.21  6200.4  1100.8
#Mann= 5 ,-1 , 0
  3580.6     .05       0  4870.5     .12       0  5018.4     .07       0
  5022.8     .12       0  5037.4     .05       0
Bank Sta=5018.4,5022.8
XS Rating Curve= 0 ,0
Exp/Cntr=0.3,0.1

Type RM Length L Ch R = 1 ,42890   ,445,445,445
BEGIN DESCRIPTION:
BRADEN BRANCH 83.0
END DESCRIPTION:
XS GIS Cut Line= 3
      2245393.96       7245088.8        2244179.        7244960.
      2243359.28      7244887.41
#Sta/Elev= 30
  3785.7 1083.04  3891.3 1077.48  3921.5 1076.83  3931.5 1078.25  3961.6  1075.3
  4014.2  1073.5    4213 1068.75    4395 1061.04  4487.7 1054.38  4580.3 1056.93
  4649.3 1054.32    4673 1053.14  4678.1 1054.64  4725.9 1049.96  4937.1 1050.88
  4961.1 1049.38  4987.4 1050.37  5009.3 1048.27  5035.3 1042.97  5035.8 1042.47
  5039.8 1042.97  5057.7 1051.48  5063.4 1056.06  5068.4 1056.81  5368.9  1077.6
  5449.2  1079.5  5579.7 1085.92  5639.9 1085.76  5720.2  1089.8  5830.4 1091.15
#Mann= 5 ,-1 , 0
  3785.7     .05       0  4649.3     .12       0  5009.3     .05       0
  5035.3     .07       0  5039.8     .05       0
Bank Sta=5035.3,5039.8
XS Rating Curve= 0 ,0
Exp/Cntr=0.3,0.1

Type RM Length L Ch R = 1 ,42445   ,460,460,460
BEGIN DESCRIPTION:
BRADEN BRANCH 82.0
END DESCRIPTION:
XS GIS Cut Line= 3
      2245498.16      7244797.14        2244229.        7244560.
       2243359.2      7244581.85
#Sta/Elev= 30
  3714.9 1084.28  3937.9 1072.83  4274.8 1066.96    4477 1060.36  4525.6 1056.43
  4588.9 1050.62  4595.8    1045  4600.9 1046.64  4653.6  1044.7  4660.1 1042.89
  4680.5 1043.44  4690.7 1046.59  4706.2  1047.4  4863.6 1044.33  4914.5 1047.74
  4955.2 1045.15    4963 1042.18  4963.5 1041.68  4967.6 1042.18  4979.7 1042.65
  4995.9 1046.54  5028.5 1046.05    5056 1046.96    5076  1050.7  5096.1 1049.36
  5246.1  1060.5  5426.2 1069.23  5607.2 1073.88  5766.3 1082.14  5876.1 1084.92
#Mann= 5 ,-1 , 0
  3714.9     .05       0  4525.6     .12       0    4963     .07       0
  4967.6     .12       0  5028.5     .05       0
Bank Sta=4963,4967.6
XS Rating Curve= 0 ,0
Exp/Cntr=0.3,0.1

Type RM Length L Ch R = 1 ,41985   ,445,445,445
BEGIN DESCRIPTION:
BRADEN BRANCH 81.0
END DESCRIPTION:
XS GIS Cut Line= 3
      2245546.75      7244331.85        2244329.        7244260.
      2243324.56      7244373.52
#Sta/Elev= 30
  3785.1 1077.69  4113.4 1065.52    4474 1062.44  4564.2 1062.56  4604.3 1064.62
  4614.3 1060.97  4725.3 1056.12  4784.6 1053.74  4794.6 1055.03  4804.6 1052.45
  4824.7 1051.71  4894.8 1043.61  4904.8 1037.96  4912.4 1036.18    4913 1035.68
  4917.2 1036.18  4954.9 1042.45  4974.9 1042.18    4995 1037.24  5025.1  1044.6
  5039.8 1043.37  5139.7 1047.63  5286.8 1050.66  5296.8 1052.93  5437.7 1058.34
  5493.9 1063.97  5538.3 1065.24  5789.9 1080.99  5910.7 1082.59  6015.8 1080.81
#Mann= 5 ,-1 , 0
  3785.1     .05       0  4725.3     .12       0  4912.4     .07       0
  4917.2     .12       0  5039.8     .05       0
Bank Sta=4912.4,4917.2
XS Rating Curve= 0 ,0
Exp/Cntr=0.3,0.1

Type RM Length L Ch R = 1 ,41540   ,476,476,476
BEGIN DESCRIPTION:
BRADEN BRANCH 80.0
END DESCRIPTION:
XS GIS Cut Line= 3
      2245463.37      7243970.74        2244379.        7243860.
      2243289.81      7244241.57
#Sta/Elev= 30
  3903.9  1069.3  3938.4 1067.74    3957 1065.49  3988.7  1064.6  4219.9 1061.13
  4400.8  1056.2  4410.9 1056.99  4491.3 1055.43  4648.3 1058.45  4847.2 1048.44
  4903.4 1043.75  4918.9 1039.38  4931.2 1034.41  4931.7 1033.91    4936 1034.41
  4946.7 1038.36  5022.9 1041.38  5102.5 1041.29  5159.2 1039.56  5205.8 1040.21
  5252.3 1042.62    5333 1049.73  5354.2 1050.65  5364.8 1049.88  5417.7 1052.56
  5557.1 1063.07  5613.9  1068.5  5768.9 1077.66  5887.7 1079.68    6148 1074.67
#Mann= 5 ,-1 , 0
  3903.9     .05       0  4918.9     .12       0  4931.2     .07       0
    4936     .12       0  5022.9     .05       0
Bank Sta=4931.2,4936
XS Rating Curve= 0 ,0
Exp/Cntr=0.3,0.1

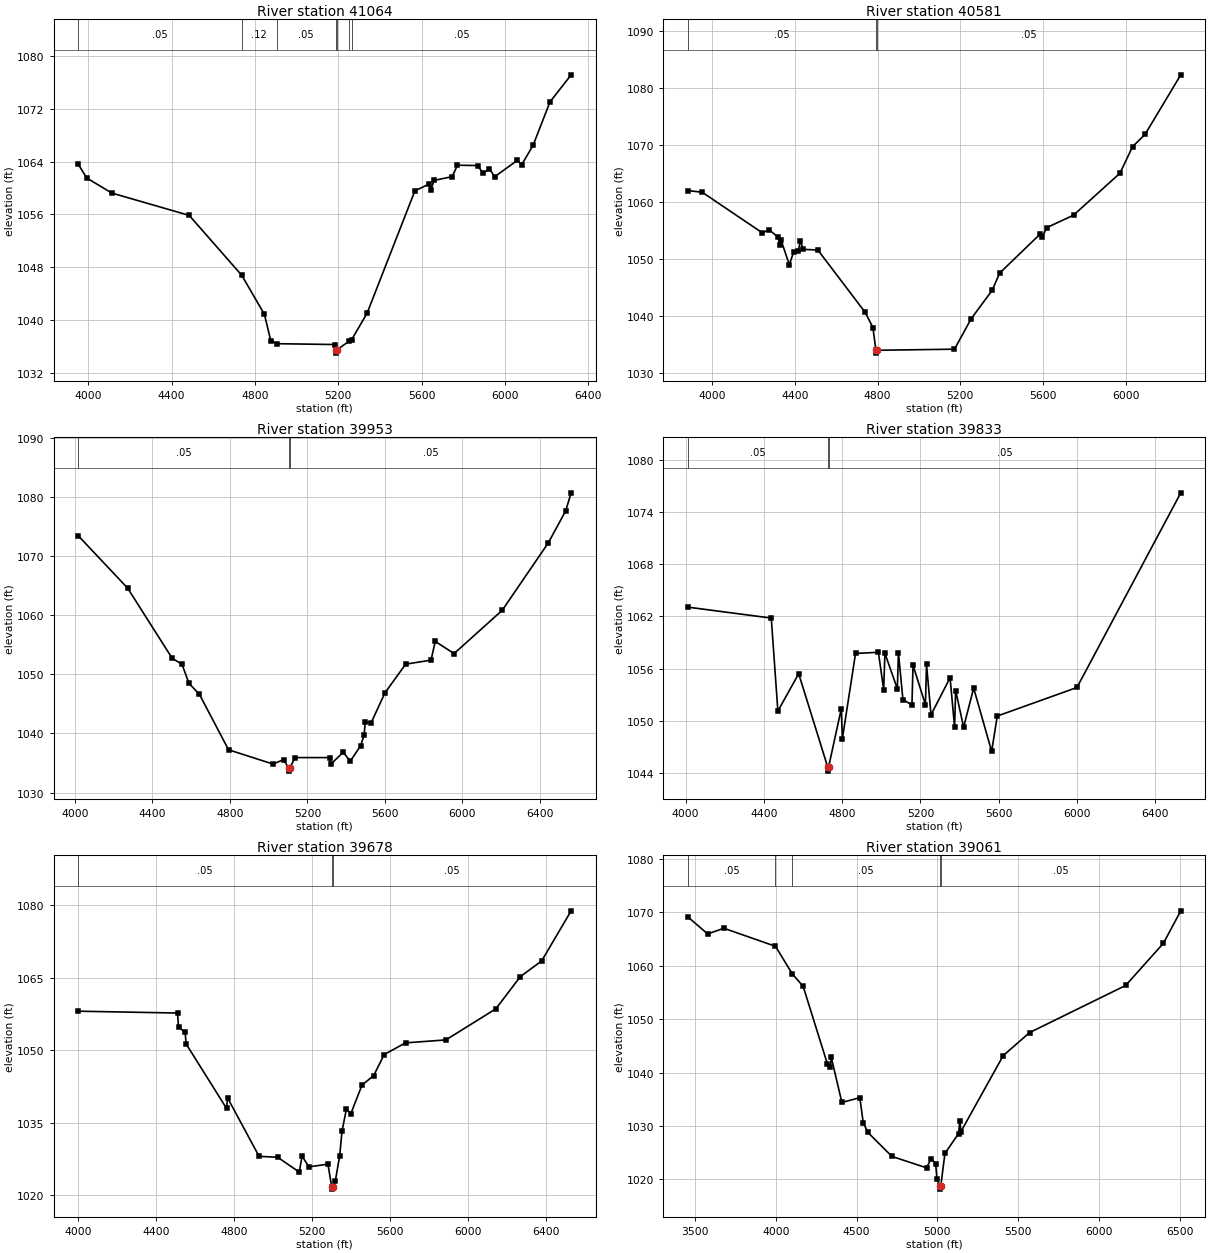
Type RM Length L Ch R = 1 ,41064   ,483,483,483
BEGIN DESCRIPTION:
BRADEN BRANCH 79.0
END DESCRIPTION:
XS GIS Cut Line= 3
      2245470.32      7243540.18        2244429.        7243460.
      2243185.64      7243908.24
#Sta/Elev= 30
  3951.4 1063.59  3992.8 1061.49  4113.2 1059.22  4484.3 1055.84  4736.6 1046.76
  4845.4 1040.84  4875.5 1036.89  4904.4 1036.41  5184.6 1036.28  5187.6 1035.48
  5188.1 1034.98  5192.4 1035.48  5252.6 1036.79  5264.3 1037.04  5338.1 1041.03
  5567.6 1059.57  5634.3 1060.56  5644.2 1059.75  5659.7 1061.14  5746.5 1061.71
  5771.8 1063.44  5869.2 1063.39  5894.6  1062.2  5925.3 1062.88  5950.6  1061.7
  6058.8 1064.17  6080.1 1063.52  6134.8 1066.46  6216.2 1073.04  6317.5 1077.13
#Mann= 7 ,-1 , 0
  3951.4     .05       0  4736.6     .12       0  4904.4     .05       0
  5187.6    .033       0  5192.4     .05       0  5252.6     .12       0
  5264.3     .05       0
Bank Sta=5187.6,5192.4
XS Rating Curve= 0 ,0
Exp/Cntr=0.3,0.1

Type RM Length L Ch R = 1 ,40581   ,628,628,628
BEGIN DESCRIPTION:
BRADEN BRANCH 78.0
END DESCRIPTION:
XS GIS Cut Line= 3
       2245463.4      7243436.01        2244429.        7243010.
      2243178.72      7243220.74
#Sta/Elev= 30
  3880.9 1062.01  3950.5 1061.72  4242.5 1054.59  4273.5 1055.18  4318.3 1053.82
  4326.8 1052.53  4332.2 1053.35  4372.3 1049.03    4394 1051.31  4415.6 1051.46
  4426.4 1053.25  4438.8 1051.72  4510.7 1051.59    4740 1040.66  4777.1 1038.02
  4791.6 1034.04  4792.2 1033.54  4796.7 1034.04    5172 1034.23  5253.1 1039.58
  5354.5 1044.54  5390.3 1047.54  5587.8 1054.43  5597.9 1053.91  5618.2 1055.51
  5748.3  1057.7  5973.1 1065.05    6034 1069.69  6094.8 1071.86  6267.5 1082.28
#Mann= 3 ,-1 , 0
  3880.9     .05       0  4791.6    .033       0  4796.7     .05       0
Bank Sta=4791.6,4796.7
XS Rating Curve= 0 ,0
Exp/Cntr=0.3,0.1

Type RM Length L Ch R = 1 ,39953   ,120,120,120
BEGIN DESCRIPTION:
BRADEN BRANCH 77.0
END DESCRIPTION:
XS GIS Cut Line= 3
      2245623.16      7242442.96      2244678.69      7242512.41
      2243199.53      7243116.57
#Sta/Elev= 30
  4016.6 1073.47  4271.4 1064.61  4502.1 1052.71  4552.2 1051.73  4588.6 1048.48
  4642.4 1046.62  4792.8 1037.24    5023 1034.82  5076.5 1035.58  5103.3 1034.13
    5104 1033.63  5108.6 1034.13  5136.1 1035.92  5314.3 1035.92  5319.7 1034.77
  5384.6 1036.83  5421.2  1035.3  5474.7 1037.94  5492.6  1039.7  5498.7 1041.99
  5528.1 1041.76  5600.2 1046.87  5707.1 1051.73    5838 1052.41  5859.8 1055.58
  5957.1 1053.52  6205.5 1060.84  6443.2 1072.24  6532.9 1077.65  6561.4 1080.72
#Mann= 3 ,-1 , 0
  4016.6     .05       0  5103.3    .033       0  5108.6     .05       0
Bank Sta=5103.3,5108.6
XS Rating Curve= 0 ,0
Exp/Cntr=0.3,0.1

Type RM Length L Ch R = 1 ,39833   ,155,155,155
BEGIN DESCRIPTION:
BRADEN BRANCH 76.5
END DESCRIPTION:
XS GIS Cut Line= 3
      2245574.51      7242137.41      2244612.33      7242414.17
      2243234.23      7243047.14
#Sta/Elev= 30
  4011.7 1063.07    4438 1061.81  4471.7  1051.1    4578 1055.41  4725.7 1044.69
  4726.4 1044.19    4731 1044.69  4795.7 1051.39  4800.9 1047.89  4868.3 1057.74
  4985.1 1057.87    5012 1053.58  5018.5 1057.75  5081.9 1053.66  5087.4 1057.84
  5110.4 1052.43  5156.4  1051.8  5161.9 1056.38  5225.3 1051.84  5230.8  1056.5
  5253.8 1050.67  5351.2 1054.94  5374.2 1049.27  5379.7 1053.47  5420.2 1049.25
  5471.7 1053.75  5563.6 1046.46  5592.1 1050.53  5999.3 1053.82  6529.4 1076.23
#Mann= 3 ,-1 , 0
  4011.7     .05       0  4725.7    .033       0    4731     .05       0
Bank Sta=4725.7,4731
XS Rating Curve= 0 ,0
Exp/Cntr=0.3,0.1

Type RM Length L Ch R = 1 ,39678   ,617,617,617
BEGIN DESCRIPTION:
BRADEN BRANCH 76.0
END DESCRIPTION:
XS GIS Cut Line= 3
      2245491.22      7242033.23        2244529.        7242310.
      2243185.66      7243040.17
#Sta/Elev= 30
  4000.9 1058.06  4510.8 1057.68    4516 1054.77  4549.7 1053.69  4554.9 1051.29
  4762.3 1037.96  4767.5 1040.14  4929.3 1028.04  5024.9 1027.85  5135.6 1024.78
  5150.1 1028.09    5185 1025.87  5282.9 1026.42  5302.1 1021.76  5302.9 1021.26
  5307.4 1021.76  5320.8 1022.99  5342.8 1028.08    5355 1033.24  5377.7 1037.85
  5400.5 1036.88  5457.7 1042.79  5517.6 1044.74  5571.2 1049.09    5681 1051.51
  5888.1 1052.12  6144.7 1058.55  6270.1 1065.21  6379.4 1068.44  6531.1 1078.82
#Mann= 3 ,-1 , 0
  4000.9     .05       0  5302.1    .033       0  5307.4     .05       0
Bank Sta=5302.1,5307.4
XS Rating Curve= 0 ,0
Exp/Cntr=0.3,0.1

Type RM Length L Ch R = 1 ,39061   ,201,201,201
BEGIN DESCRIPTION:
BRADEN BRANCH 75.0
END DESCRIPTION:
XS GIS Cut Line= 4
      2245761.99      7241505.47      2244720.35      7241540.19
      2244262.02      7241908.24      2243220.34      7242873.53
#Sta/Elev= 30
    3456 1069.12  3579.1 1065.93  3679.1 1066.99  3998.6 1063.61  4102.8 1058.44
  4169.4 1056.15  4319.5 1041.64  4338.5 1041.11  4343.5 1042.85  4409.5  1034.4
  4520.5  1035.3  4541.3 1030.64  4570.1  1028.8    4719 1024.31  4933.4 1022.17
  4961.7 1023.91  4989.4 1022.96  4997.4 1020.16  5015.5 1018.69  5016.3 1018.19
  5020.9 1018.69    5047 1024.88  5131.6 1028.58    5139 1030.96  5145.8 1028.95
  5407.7 1043.17  5570.5 1047.47  6165.2 1056.29  6398.8 1064.18  6506.2 1070.25
#Mann= 5 ,-1 , 0
    3456     .05       0  3998.6     .12       0  4102.8     .05       0
  5015.5    .033       0  5020.9     .05       0
Bank Sta=5015.5,5020.9
XS Rating Curve= 0 ,0
Exp/Cntr=0.3,0.1