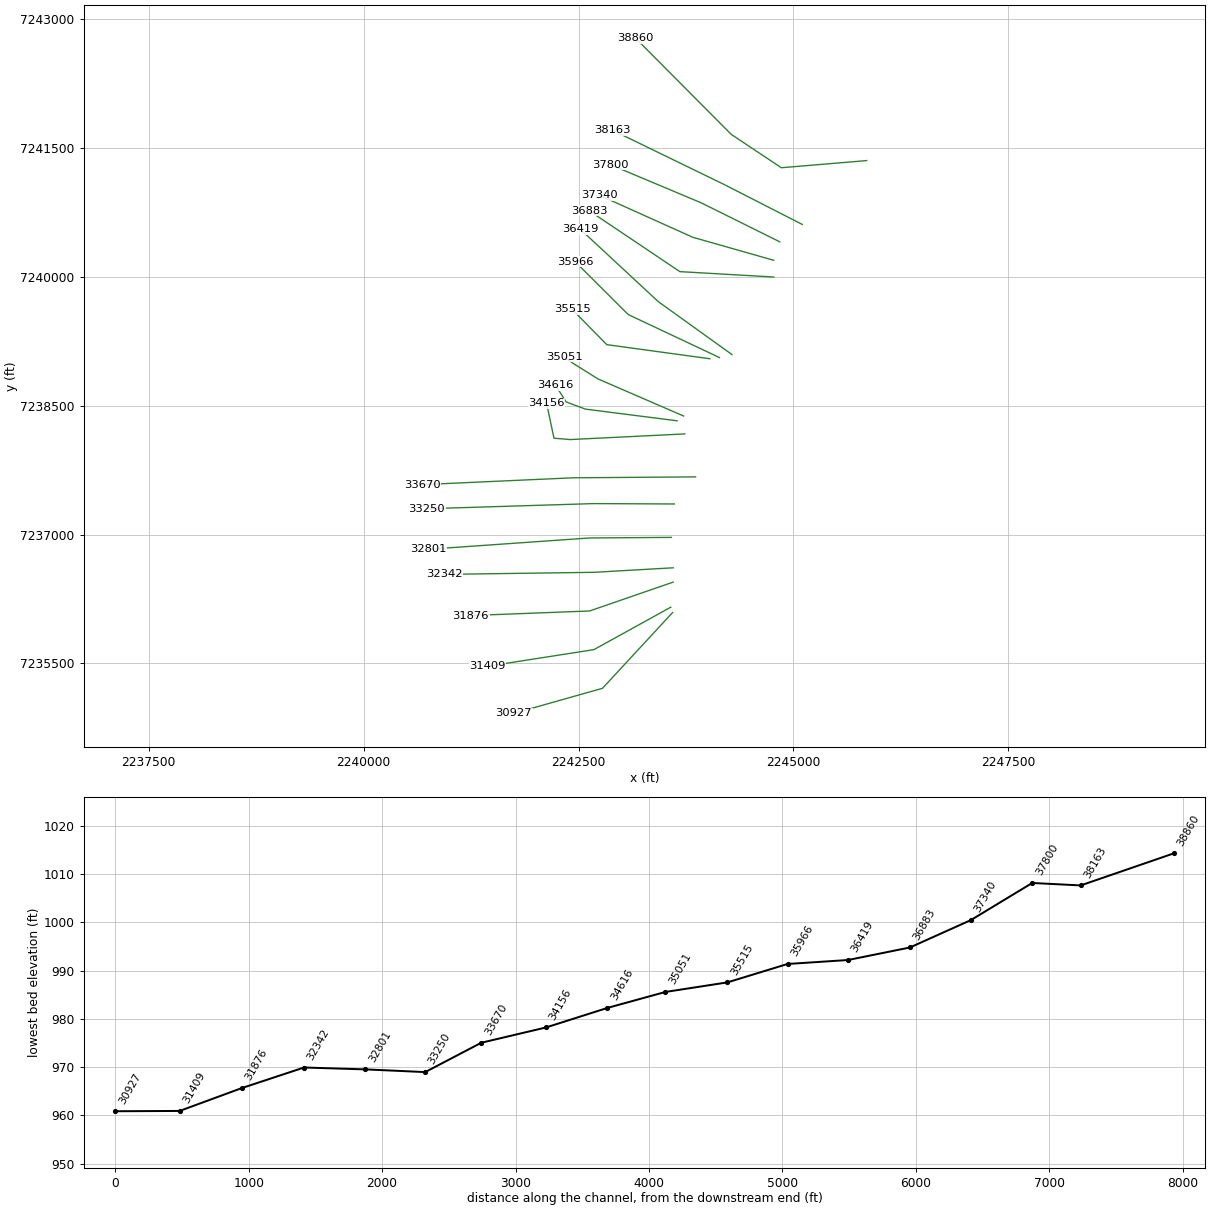
HEC-RAS study BRADEN BRANCH.prj: BRADEN BRANCH Base Level Engineering

--- BRADEN BRANCH.g01 (geometry) --- (continued)

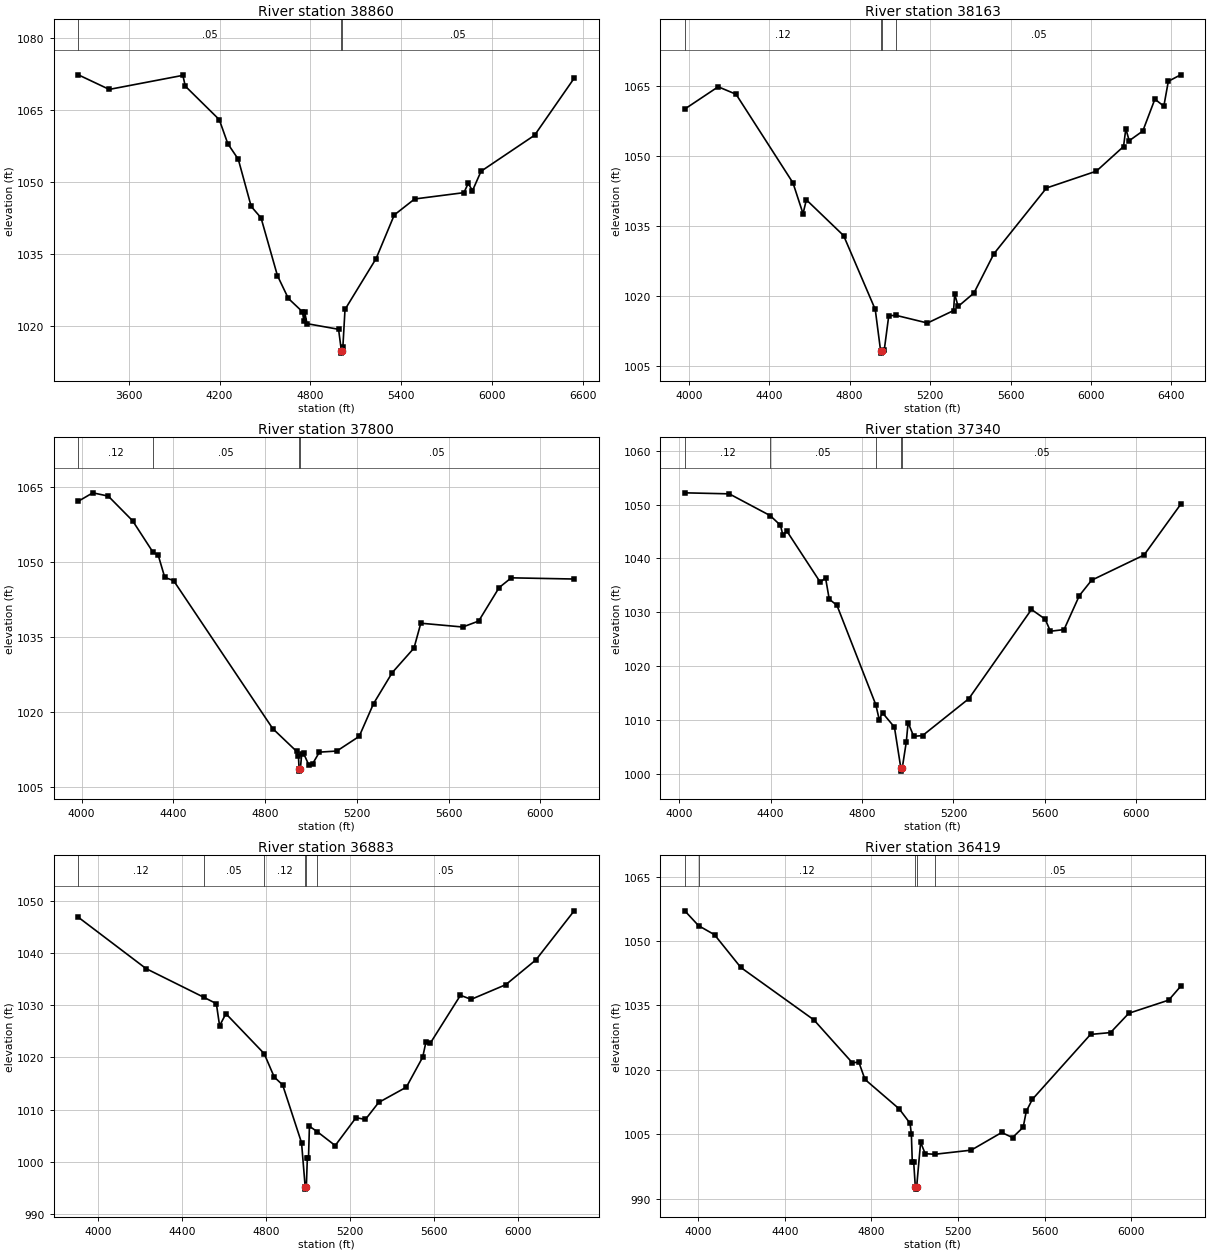
Type RM Length L Ch R = 1 ,38860   ,697,697,697
BEGIN DESCRIPTION:
BRADEN BRANCH 74.0
END DESCRIPTION:
XS GIS Cut Line= 4
      2245852.26      7241352.68      2244859.24      7241269.35
      2244275.91      7241658.24      2243165.47      7242775.62
#Sta/Elev= 30
  3267.6 1072.32  3471.6 1069.28  3957.8 1072.21  3973.3 1069.97  4197.9 1062.98
  4254.3 1057.96  4323.4 1054.72  4408.6 1044.89  4473.7  1042.5  4581.8 1030.47
  4653.9 1025.71  4747.1 1022.93  4756.1 1021.05  4762.1  1022.8  4777.1 1020.45
  4985.4 1019.28  5003.9 1014.81  5004.7 1014.31  5009.4 1014.81  5013.7 1015.53
  5027.9 1023.41    5233 1034.01  5353.1 1043.11  5487.5 1046.44  5812.8 1047.76
  5841.1 1049.69  5869.4 1048.17  5925.9 1052.22  6279.4 1059.73  6540.5 1071.61
#Mann= 3 ,-1 , 0
  3267.6     .05       0  5003.9    .033       0  5009.4     .05       0
Bank Sta=5003.9,5009.4
XS Rating Curve= 0 ,0
Exp/Cntr=0.3,0.1

Type RM Length L Ch R = 1 ,38163   ,363,363,363
BEGIN DESCRIPTION:
BRADEN BRANCH 73.0
END DESCRIPTION:
XS GIS Cut Line= 3
      2245102.26      7240609.65      2244192.58      7241074.91
      2242893.94      7241706.87
#Sta/Elev= 30
  3980.1 1059.97  4146.1 1064.74    4235 1063.14  4518.1 1044.15  4568.1 1037.55
  4584.7 1040.52    4770 1032.85  4927.3 1017.02  4953.9 1008.17  4954.8 1007.67
  4959.5 1008.17  4972.2 1008.38  4994.6 1015.71  5032.9 1015.74  5187.1 1014.12
  5316.8 1016.79  5322.4 1020.34  5339.4 1017.67  5418.2 1020.55  5517.4 1028.96
  5778.9 1043.05    6027 1046.66  6162.2 1051.94  6173.6 1055.75  6190.3 1053.18
    6258 1055.26  6318.1 1062.09  6362.6 1060.58  6384.9 1065.91  6446.1  1067.3
#Mann= 4 ,-1 , 0
  3980.1     .12       0  4953.9     .07       0  4959.5     .12       0
  5032.9     .05       0
Bank Sta=4953.9,4959.5
XS Rating Curve= 0 ,0
Exp/Cntr=0.3,0.1

Type RM Length L Ch R = 1 ,37800   ,460,460,460
BEGIN DESCRIPTION:
BRADEN BRANCH 72.0
END DESCRIPTION:
XS GIS Cut Line= 3
      2244840.72      7240407.09        2243929.        7240860.
      2242875.44      7241302.92
#Sta/Elev= 30
  3986.1 1062.06  4049.1 1063.74  4116.4 1063.09  4222.5 1058.17  4311.4 1051.89
  4334.2  1051.3  4362.8 1046.85  4401.2 1046.22  4833.3 1016.67  4937.1 1012.14
  4945.3 1011.26  4948.1 1008.68    4949 1008.18  4953.8 1008.68  4959.5 1011.53
  4967.7 1011.75  4990.1 1009.45  5006.8 1009.62  5036.7 1011.97  5112.6 1012.19
  5210.2 1015.12  5272.5 1021.64  5354.6 1027.87  5448.9 1032.74  5478.7 1037.71
  5661.3 1036.95  5730.9 1038.14    5820 1044.82    5873 1046.77    6147 1046.53
#Mann= 4 ,-1 , 0
  3986.1     .12       0  4311.4     .05       0  4948.1    .033       0
  4953.8     .05       0
Bank Sta=4948.1,4953.8
XS Rating Curve= 0 ,0
Exp/Cntr=0.3,0.1

Type RM Length L Ch R = 1 ,37340   ,457,457,457
BEGIN DESCRIPTION:
BRADEN BRANCH 71.0
END DESCRIPTION:
XS GIS Cut Line= 3
      2244771.33      7240191.79        2243829.        7240460.
      2242743.78      7240948.63
#Sta/Elev= 30
  4024.4 1052.19    4219    1052  4397.9 1047.96  4442.9 1046.17  4453.1 1044.44
  4471.6 1045.04  4617.4 1035.57  4640.3  1036.4  4656.5 1032.44  4690.3 1031.28
  4860.5  1012.8  4875.2 1010.06  4889.8  1011.3  4941.8 1008.65  4970.1 1000.98
    4971 1000.48  4975.8 1000.98  4993.8 1005.92  5001.6  1009.5  5026.1 1006.95
  5064.8 1007.08  5267.4 1013.94  5541.5 1030.52  5601.4 1028.72  5624.5 1026.47
  5684.1 1026.78  5751.2  1033.1  5804.7 1035.95  6034.4 1040.64  6194.3 1050.04
#Mann= 5 ,-1 , 0
  4024.4     .12       0  4397.9     .05       0  4860.5     .12       0
  4970.1    .033       0  4975.8     .05       0
Bank Sta=4970.1,4975.8
XS Rating Curve= 0 ,0
Exp/Cntr=0.3,0.1

Type RM Length L Ch R = 1 ,36883   ,464,464,464
BEGIN DESCRIPTION:
BRADEN BRANCH 70.0
END DESCRIPTION:
XS GIS Cut Line= 3
      2244771.26      7239997.36        2243679.        7240060.
      2242625.46      7240768.19
#Sta/Elev= 30
  3905.9 1046.85  4228.7 1037.02  4505.4  1031.5  4563.8 1030.31  4579.3 1026.07
  4609.3 1028.39  4791.8 1020.74  4839.7 1016.26  4879.8 1014.75  4969.9 1003.69
  4987.1   995.3    4988   994.8  4992.8   995.3  4997.5  1000.7    5003  1000.7
  5007.5 1006.84  5045.4 1005.78  5130.4 1003.14  5229.5 1008.48  5274.4 1008.14
  5337.5 1011.39  5469.4 1014.32  5547.4 1020.06  5562.4 1022.88  5583.4 1022.72
  5727.4 1031.91  5778.4 1031.13  5943.4 1033.94  6087.4  1038.7  6269.4 1048.08
#Mann= 6 ,-1 , 0
  3905.9     .12       0  4505.4     .05       0  4791.8     .12       0
  4987.1     .07       0  4992.8     .12       0  5045.4     .05       0
Bank Sta=4987.1,4992.8
XS Rating Curve= 0 ,0
Exp/Cntr=0.3,0.1

Type RM Length L Ch R = 1 ,36419   ,453,453,453
BEGIN DESCRIPTION:
BRADEN BRANCH 69.0
END DESCRIPTION:
XS GIS Cut Line= 3
      2244285.17      7239094.58        2243429.        7239710.
      2242522.63      7240551.67
#Sta/Elev= 30
  3937.6 1057.05  4001.2 1053.59  4074.9 1051.48  4196.5 1043.85  4534.1 1031.64
  4712.1 1021.62  4741.6 1021.81  4770.3 1017.76  4928.2 1010.91  4978.5 1007.54
  4984.6 1005.01  4988.9  998.46  4995.4  998.46  5002.9   992.7  5003.9   992.2
    5009   992.7  5027.4 1003.13  5048.4 1000.46  5092.3 1000.32    5261 1001.28
  5402.2  1005.4    5452 1004.21  5501.4 1006.62  5515.6 1010.33  5543.9 1013.14
  5812.6 1028.25    5905 1028.68  5989.5 1033.18  6173.7 1036.24  6228.9 1039.45
#Mann= 5 ,-1 , 0
  3937.6     .05       0  4001.2     .12       0  5002.9     .07       0
    5009     .12       0  5092.3     .05       0
Bank Sta=5002.9,5009
XS Rating Curve= 0 ,0
Exp/Cntr=0.3,0.1

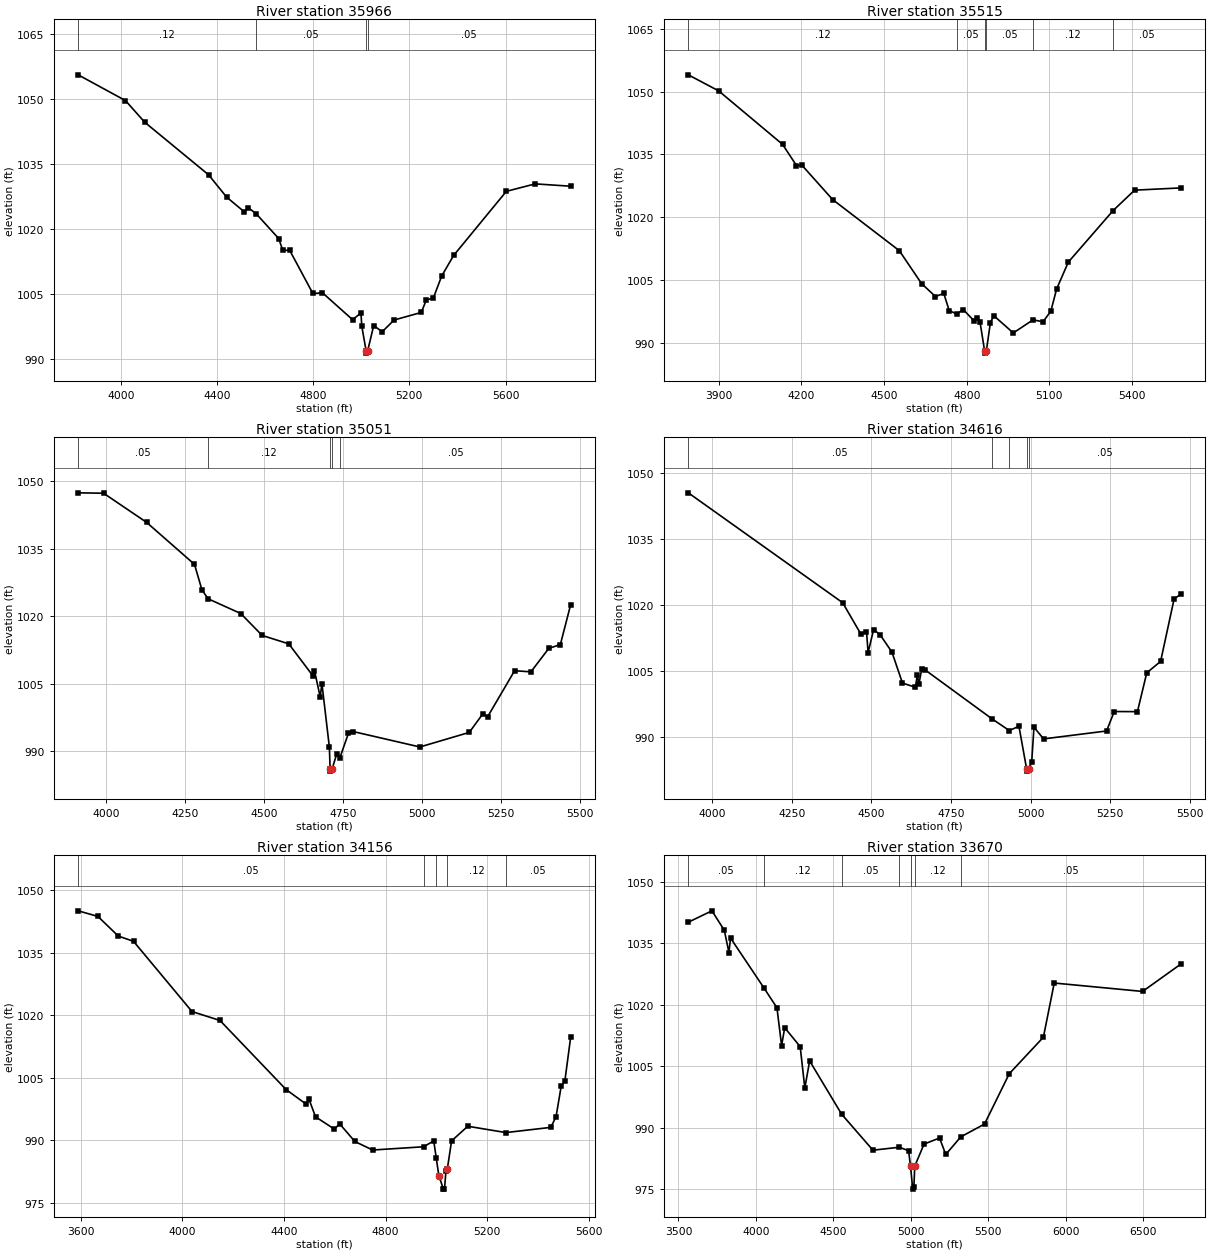
Type RM Length L Ch R = 1 ,35966   ,451,451,451
BEGIN DESCRIPTION:
BRADEN BRANCH 68.0
END DESCRIPTION:
XS GIS Cut Line= 3
      2244139.34      7239059.86        2243079.        7239560.
      2242458.76      7240177.94
#Sta/Elev= 30
  3822.8 1055.59  4019.5 1049.65  4099.6 1044.65  4364.9 1032.53  4440.6 1027.35
  4514.4 1023.95  4530.8  1024.9  4562.4 1023.58  4656.6 1017.82  4673.9 1015.08
  4702.2 1015.12  4798.8 1005.14  4838.8  1005.3  4963.8   999.1  4998.7 1000.63
  5002.2   997.6  5020.3  991.88  5021.3  991.38  5026.5  991.88  5051.7  997.74
  5087.1  996.31  5136.6  999.02  5249.7 1000.77  5270.9 1003.71  5299.2 1004.01
  5334.6 1009.19  5384.1 1013.91  5603.3 1028.71  5723.5 1030.43  5870.7 1029.89
#Mann= 4 ,-1 , 0
  3822.8     .12       0  4562.4     .05       0  5020.3    .033       0
  5026.5     .05       0
Bank Sta=5020.3,5026.5
XS Rating Curve= 0 ,0
Exp/Cntr=0.3,0.1

Type RM Length L Ch R = 1 ,35515   ,464,464,464
BEGIN DESCRIPTION:
BRADEN BRANCH 67.0
END DESCRIPTION:
XS GIS Cut Line= 3
      2244028.18      7239045.98        2242829.        7239210.
      2242424.05      7239622.37
#Sta/Elev= 30
    3789 1054.01  3899.2 1050.18  4131.3  1037.4  4181.8 1032.35    4202  1032.4
    4313 1024.23  4555.3 1012.02    4636 1004.16  4686.5 1001.08  4716.7 1001.81
  4736.5  997.68  4763.9  996.93  4787.4  997.97  4827.8  995.17  4837.9  996.06
    4848   995.1    4865  988.06    4866  987.56  4871.2  988.06    4886  994.87
  4898.4  996.49  4969.1  992.38  5040.9  995.51  5077.1  995.04  5105.4  997.59
  5126.6 1002.91    5169  1009.3  5331.4 1021.59  5409.5 1026.47  5577.3 1027.01
#Mann= 6 ,-1 , 0
    3789     .12       0  4763.9     .05       0    4865    .033       0
  4871.2     .05       0  5040.9     .12       0  5331.4     .05       0
Bank Sta=4865,4871.2
XS Rating Curve= 0 ,0
Exp/Cntr=0.3,0.1

Type RM Length L Ch R = 1 ,35051   ,435,435,435
BEGIN DESCRIPTION:
BRADEN BRANCH 66.0
END DESCRIPTION:
XS GIS Cut Line= 4
      2243722.63      7238379.32        2242729.        7238810.
      2242438.62      7238991.49      2242332.87      7239069.33
#Sta/Elev= 30
  3912.8 1047.46  3993.1 1047.37  4128.8 1040.91  4280.5 1031.55    4304 1025.89
  4323.5  1023.9  4426.8 1020.62  4494.4 1015.75  4578.5 1013.88  4654.4 1006.81
  4659.8 1007.93  4677.8 1002.09  4683.3 1005.04  4706.8  990.95  4709.2  986.08
  4710.2  985.58  4715.5  986.08  4730.2   989.4  4740.4  988.61  4766.9  993.95
  4782.6  994.37    4993  990.95  5149.1  994.19  5192.1  998.34  5207.4  997.71
  5292.3  1007.9    5344 1007.66  5400.4 1012.87    5437 1013.72  5469.5 1022.59
#Mann= 5 ,-1 , 0
  3912.8     .05       0  4323.5     .12       0  4709.2    .033       0
  4715.5     .12       0  4740.4     .05       0
Bank Sta=4709.2,4715.5
XS Rating Curve= 0 ,0
Exp/Cntr=0.3,0.1

Type RM Length L Ch R = 1 ,34616   ,460,460,460
BEGIN DESCRIPTION:
BRADEN BRANCH 65.0
END DESCRIPTION:
XS GIS Cut Line= 4
      2243646.32      7238323.75        2242579.        7238460.
       2242356.3      7238543.51      2242231.12      7238740.23
#Sta/Elev= 30
  3924.7 1045.49  4409.7 1020.52  4466.4 1013.44  4484.4 1013.98  4489.5  1009.2
  4506.7 1014.41  4526.9 1013.28  4564.3 1009.31  4597.4 1002.28  4637.8 1001.32
  4644.1 1004.02  4649.1 1002.05  4657.9 1005.47    4668 1005.29  4878.3  994.17
  4932.9  991.49  4963.3  992.46  4987.4  982.77  4988.5  982.27  4993.8  982.77
  5003.4  984.42  5010.5  992.25  5040.7  989.59  5238.5  991.39  5262.7  995.81
  5335.5  995.78  5364.8  1004.6  5408.3  1007.2  5450.7 1021.38  5471.7 1022.46
#Mann= 5 ,-1 , 0
  3924.7     .05       0  4878.3     .12       0  4932.9     .05       0
  4987.4    .033       0  4993.8     .05       0
Bank Sta=4987.4,4993.8
XS Rating Curve= 0 ,0
Exp/Cntr=0.3,0.1

Type RM Length L Ch R = 1 ,34156   ,486,486,486
BEGIN DESCRIPTION:
BRADEN BRANCH 64.0
END DESCRIPTION:
XS GIS Cut Line= 4
      2243736.54      7238170.97      2242404.83      7238105.38
      2242214.72      7238121.01      2242129.01      7238526.17
#Sta/Elev= 30
  3590.1 1045.05  3667.7 1043.71  3747.8    1039  3807.9 1037.73  4038.2 1020.86
  4148.3 1018.72  4408.6 1002.12  4488.7  998.57  4498.7  999.79  4524.2  995.59
  4598.9  992.61  4618.9  993.92    4679  989.66    4749  987.61  4949.4  988.39
  4989.5  989.79  4999.5  985.66  5009.5  981.48  5027.5  978.22  5031.8  978.22
  5037.7  982.64  5042.7  982.96  5059.7   989.8  5123.4  993.32  5273.4   991.8
  5450.4  993.05  5470.9  995.64  5491.3    1003  5505.4 1004.14  5528.3 1014.66
#Mann= 5 ,-1 , 0
  3590.1     .05       0  4949.4     .12       0  4999.5     .07       0
  5042.7     .12       0  5273.4     .05       0
Bank Sta=5009.5,5042.7
XS Rating Curve= 0 ,0
Exp/Cntr=0.3,0.1

Type RM Length L Ch R = 1 ,33670   ,420,420,420
BEGIN DESCRIPTION:
BRADEN BRANCH 63.0
END DESCRIPTION:
XS GIS Cut Line= 3
      2243861.51      7237670.97        2242429.        7237660.
      2240682.45      7237580.76
#Sta/Elev= 30
  3563.4 1040.11  3715.9 1042.88  3795.9 1038.14  3825.9 1032.69  3835.9 1036.26
  4050.2 1024.18  4135.9 1019.25  4165.9 1010.02  4185.9 1014.38  4285.9 1009.78
  4315.9  999.69  4347.1 1006.29  4553.8   993.3  4755.9  984.53  4926.4  985.25
    4986  984.41  4998.5  980.75  5012.8  975.04  5020.4  975.54    5026  980.65
    5086  986.02  5186.2   987.5  5226.2  983.49  5323.4  987.78  5476.5   990.9
  5636.6 1003.18  5856.8 1012.07  5926.9 1025.28  6497.5 1023.23  6744.3 1029.89
#Mann= 7 ,-1 , 0
  3563.4     .05       0  4050.2     .12       0  4553.8     .05       0
  4926.4     .12       0  4998.5     .07       0    5026     .12       0
  5323.4     .05       0
Bank Sta=4998.5,5026
XS Rating Curve= 0 ,0
Exp/Cntr=0.3,0.1

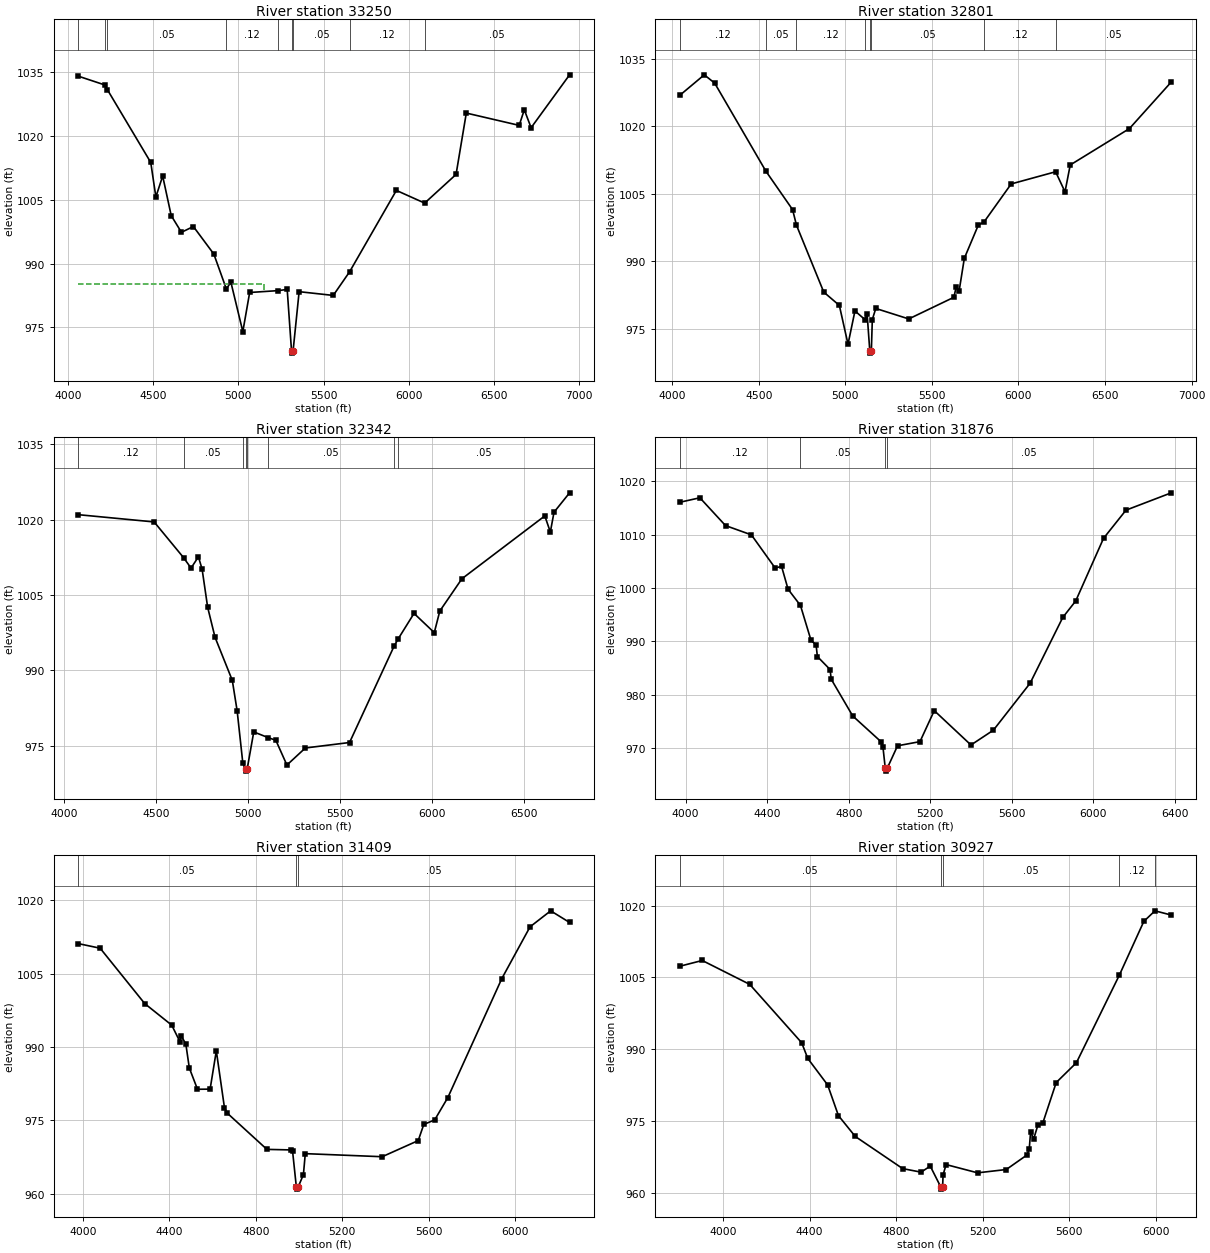
Type RM Length L Ch R = 1 ,33250   ,449,449,449
BEGIN DESCRIPTION:
BRADEN BRANCH 62.0
END DESCRIPTION:
XS GIS Cut Line= 3
      2243615.01      7237355.58        2242679.        7237360.
      2240733.54      7237300.04
#Sta/Elev= 30
  4060.1 1034.01  4215.3 1031.95  4232.1  1030.8  4486.1 1013.74  4516.1 1005.64
  4556.1 1010.54  4606.1 1001.25  4666.1  997.33  4736.1  998.69  4856.1  992.22
  4929.4  984.04  4956.1  985.62  5026.1  974.01  5066.2   983.2  5234.5  983.64
  5286.3  983.92  5311.8  969.46  5313.1  968.96  5320.8  969.46  5356.3  983.39
  5556.4  982.51  5652.5  988.07  5926.6 1007.17  6092.5 1004.19  6276.7 1010.92
  6336.8 1025.33  6646.9 1022.44  6676.9  1026.1  6716.9 1021.89  6942.5 1034.31
#Mann= 9 ,-1 , 0
  4060.1     .05       0  4215.3     .12       0  4232.1     .05       0
  4929.4     .12       0  5234.5     .05       0  5311.8     .07       0
  5320.8     .05       0  5652.5     .12       0  6092.5     .05       0
#XS Ineff= 2 , 0
         5148.34  985.13
Permanent Ineff=
       F       F
Bank Sta=5311.8,5320.8
XS Rating Curve= 0 ,0
Exp/Cntr=0.3,0.1

Type RM Length L Ch R = 1 ,32801   ,459,459,459
BEGIN DESCRIPTION:
BRADEN BRANCH 61.0
END DESCRIPTION:
XS GIS Cut Line= 3
      2243580.36      7236966.69        2242629.        7236960.
      2240747.02      7236827.81
#Sta/Elev= 30
  4044.2 1026.89  4185.6 1031.45  4245.6 1029.61  4541.4 1010.01  4695.6 1001.45
    4718  997.99  4875.6   983.1  4965.6  980.14  5015.6   971.5  5055.7  978.91
  5112.9     977  5125.9  978.25  5141.4  970.02  5142.7  969.52  5150.4  970.02
    5156     977    5176  979.46  5366.5  977.13  5627.1  981.95    5640  984.22
  5657.2  983.34  5687.3  990.62  5767.5  997.96  5802.6  998.79  5957.9 1007.17
  6214.5 1009.88  6268.7 1005.41  6298.8 1011.39  6640.7 1019.49  6882.2 1029.85
#Mann= 8 ,-1 , 0
  4044.2     .12       0  4541.4     .05       0    4718     .12       0
  5112.9     .05       0  5141.4     .07       0  5150.4     .05       0
  5802.6     .12       0  6214.5     .05       0
Bank Sta=5141.4,5150.4
XS Rating Curve= 0 ,0
Exp/Cntr=0.3,0.1

Type RM Length L Ch R = 1 ,32342   ,466,466,466
BEGIN DESCRIPTION:
BRADEN BRANCH 60.0
END DESCRIPTION:
XS GIS Cut Line= 3
      2243601.13      7236612.52        2242679.        7236560.
      2240934.49      7236536.14
#Sta/Elev= 30
  4076.5    1021  4489.3 1019.55    4649 1012.44  4689.6 1010.36  4729.7  1012.6
  4749.7 1010.14  4779.8 1002.55  4819.8  996.58  4913.6  987.99    4940   981.9
    4971  971.43  4985.6  970.41  4986.9  969.91  4994.7  970.41  5030.1  977.72
  5107.3   976.6  5150.1  976.05  5210.1  971.12  5310.2  974.52  5550.2  975.61
  5792.8  994.87  5814.9   996.3  5900.2 1001.33  6010.2   997.5  6040.2  1001.8
  6160.2 1008.23  6610.3 1020.75  6640.3 1017.54  6660.3 1021.49  6744.8 1025.35
#Mann= 8 ,-1 , 0
  4076.5     .12       0    4649     .05       0    4971     .12       0
  4985.6     .07       0  4994.7     .12       0  5107.3     .05       0
  5792.8     .12       0  5814.9     .05       0
Bank Sta=4985.6,4994.7
XS Rating Curve= 0 ,0
Exp/Cntr=0.3,0.1

Type RM Length L Ch R = 1 ,31876   ,467,467,467
BEGIN DESCRIPTION:
BRADEN BRANCH 59.0
END DESCRIPTION:
XS GIS Cut Line= 3
      2243601.13      7236445.86        2242629.        7236110.
      2241246.93      7236056.97
#Sta/Elev= 30
  3971.1 1016.05  4069.7 1016.89  4195.5 1011.68  4322.5 1009.94  4438.9 1003.73
  4470.6 1004.02  4502.4  999.75  4563.2  996.71  4615.1  990.16  4639.9  989.31
  4646.3  987.13  4708.7  984.69    4714  982.89  4819.8  975.99  4958.1  971.18
  4967.9  970.21  4979.5  966.15  4980.8  965.65  4988.6  966.15  5039.6   970.4
  5149.7  971.18  5219.8  976.99  5399.9  970.55    5510  973.33  5690.1  982.13
  5850.2  994.45  5913.9  997.55  6050.4 1009.29  6160.5 1014.57  6382.7 1017.82
#Mann= 4 ,-1 , 0
  3971.1     .12       0  4563.2     .05       0  4979.5    .033       0
  4988.6     .05       0
Bank Sta=4979.5,4988.6
XS Rating Curve= 0 ,0
Exp/Cntr=0.3,0.1

Type RM Length L Ch R = 1 ,31409   ,482,482,482
BEGIN DESCRIPTION:
BRADEN BRANCH 58.0
END DESCRIPTION:
XS GIS Cut Line= 3
      2243573.35      7236154.19        2242679.        7235660.
       2241442.7      7235466.89
#Sta/Elev= 30
  3977.8 1011.14  4079.7 1010.19  4285.9  998.86  4410.8  994.45  4448.6  991.07
  4454.3  992.31  4476.1  990.57  4492.1  985.69  4529.9  981.33  4588.3  981.36
    4617  989.19  4654.8  977.52  4668.3  976.42  4851.1  969.03  4964.1  968.92
  4969.8  968.63    4987   961.4  4988.3   960.9  4996.2   961.4  5019.8  963.87
  5028.5  968.16  5384.2  967.53  5550.8  970.83  5576.5  974.13  5627.1  975.07
  5687.9  979.64  5937.5 1003.98  6068.1 1014.57  6163.5 1017.84  6250.9 1015.46
#Mann= 3 ,-1 , 0
  3977.8     .05       0    4987    .033       0  4996.2     .05       0
Bank Sta=4987,4996.2
XS Rating Curve= 0 ,0
Exp/Cntr=0.3,0.1

Type RM Length L Ch R = 1 ,30927   ,465,465,465
BEGIN DESCRIPTION:
BRADEN BRANCH 57.0
END DESCRIPTION:
XS GIS Cut Line= 3
       2243594.2      7236091.69        2242779.        7235210.
        2241747.      7234918.09
#Sta/Elev= 30
  3799.3 1007.34  3903.2 1008.54  4122.7 1003.56  4363.1  991.38  4391.4   988.1
  4483.3  982.57  4533.2  976.17  4610.9  971.83  4830.3  965.12  4915.3  964.38
  4957.9  965.64  5005.9  961.34  5007.2  960.84  5015.1  961.34  5017.1  963.83
  5031.3  965.96  5176.8  964.24  5309.5  964.93  5405.4  967.97  5415.8  969.22
  5421.8  972.71  5436.6  971.37  5455.8  974.21  5478.2   974.6  5540.5  983.08
    5634  987.22  5832.6 1005.49  5945.8  1016.7  5997.2  1018.9  6072.6 1018.02
#Mann= 5 ,-1 , 0
  3799.3     .05       0  5005.9    .033       0  5015.1     .05       0
  5832.6     .12       0  5997.2     .05       0
Bank Sta=5005.9,5015.1
XS Rating Curve= 0 ,0
Exp/Cntr=0.3,0.1