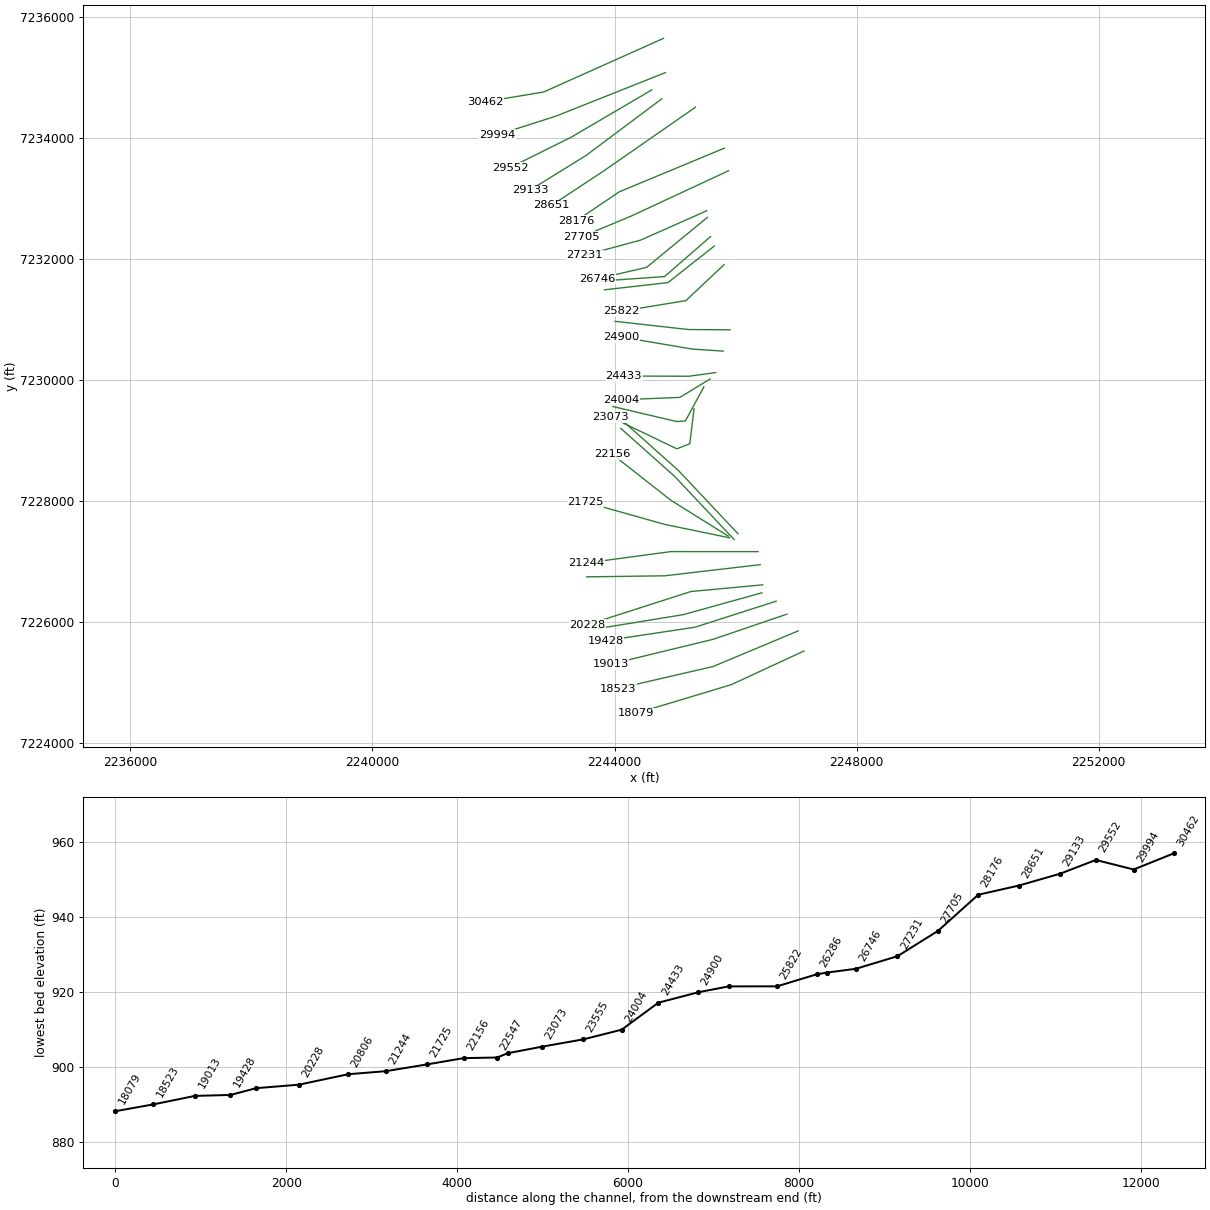
HEC-RAS study BRADEN BRANCH.prj: BRADEN BRANCH Base Level Engineering

--- BRADEN BRANCH.g01 (geometry) --- (continued)

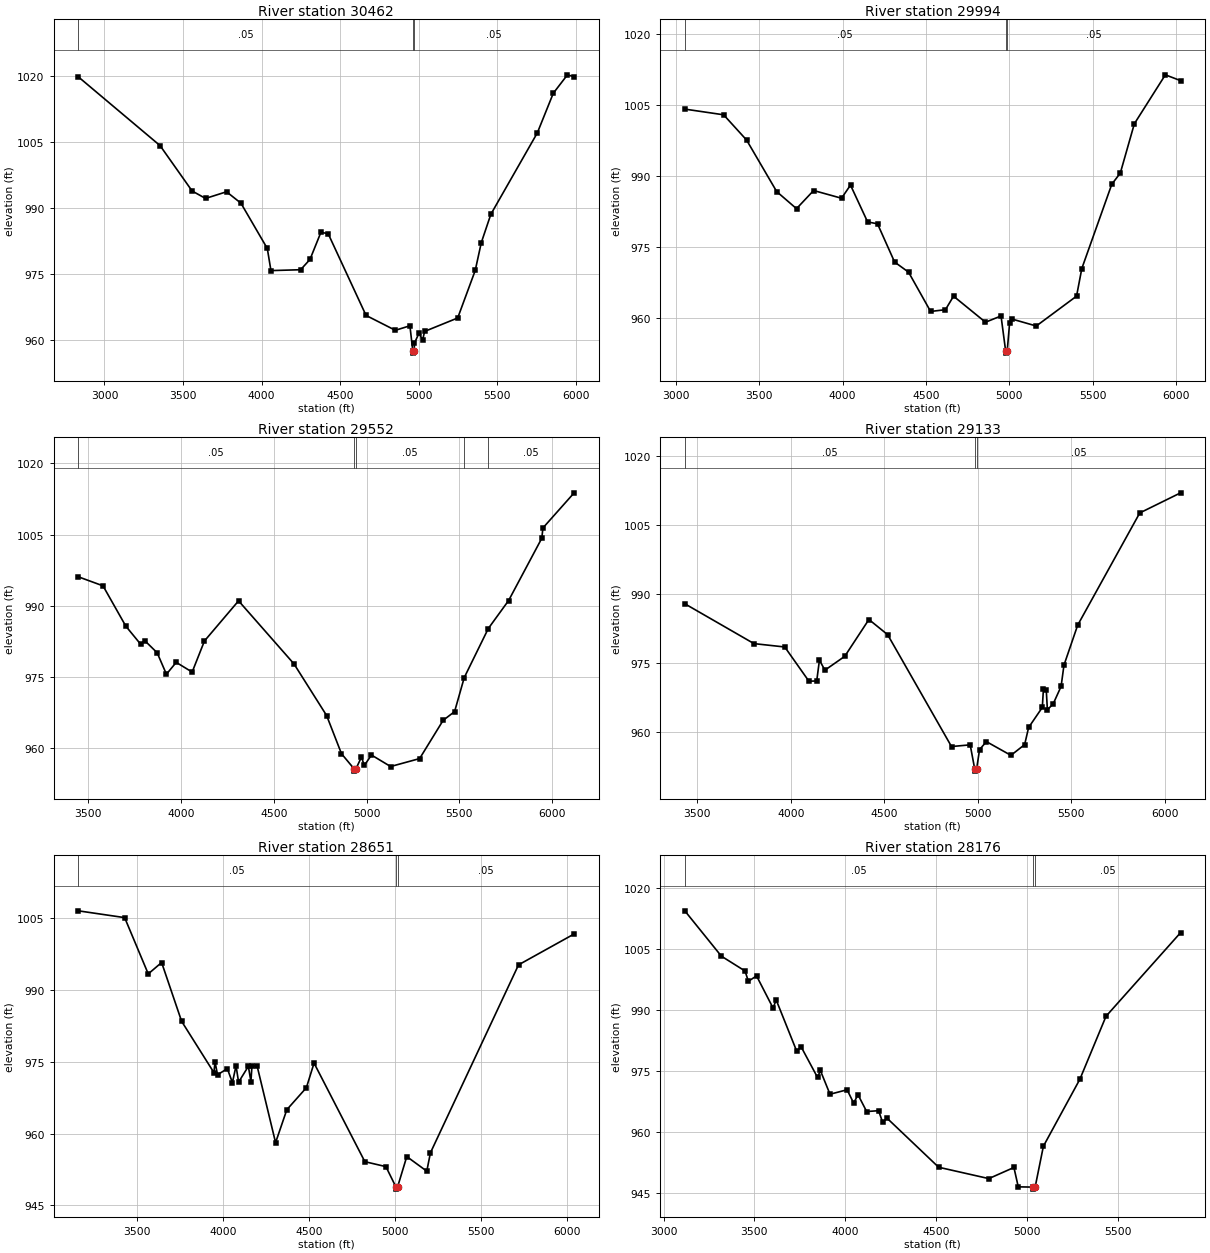
Type RM Length L Ch R = 1 ,30462   ,468,468,468
BEGIN DESCRIPTION:
BRADEN BRANCH 56.0
END DESCRIPTION:
XS GIS Cut Line= 3
       2244809.5      7235647.26        2242829.        7234760.
      2241858.09      7234598.64
#Sta/Elev= 30
  2833.9 1019.92    3354 1004.25  3557.7  993.92  3643.2  992.22  3776.8  993.74
  3868.3  991.14  4036.1  980.82  4059.3  975.78    4248  975.98  4307.6  978.32
  4377.2  984.51  4423.3  984.19  4664.4  965.57  4850.7  962.18  4943.4  963.21
  4961.7  957.48  4963.1  956.98  4971.3  957.48    4972  959.25  5001.3  961.52
  5024.3  959.99  5037.1  961.93  5247.4  964.99  5358.9  975.81  5397.4  982.14
  5458.3  988.61  5754.2 1007.17  5855.6 1016.19  5945.6 1020.38  5988.3 1019.95
#Mann= 3 ,-1 , 0
  2833.9     .05       0  4961.7    .033       0  4971.3     .05       0
Bank Sta=4961.7,4971.3
XS Rating Curve= 0 ,0
Exp/Cntr=0.3,0.1

Type RM Length L Ch R = 1 ,29994   ,442,442,442
BEGIN DESCRIPTION:
BRADEN BRANCH 55.0
END DESCRIPTION:
XS GIS Cut Line= 3
      2244841.19      7235080.71        2243029.        7234360.
      2242054.67       7234047.7
#Sta/Elev= 30
  3053.9 1004.15  3286.7 1002.95  3424.3  997.63  3605.1  986.75  3723.8  983.15
  3826.4  986.98  3993.7  985.35  4047.6  988.12  4150.2  980.35  4209.5  979.96
  4312.1  971.89  4395.7  969.76  4527.9  961.47  4616.9  961.84  4665.5  964.69
  4857.1   959.2  4950.3  960.52  4977.8  953.18  4979.2  952.68  4987.5  953.18
  5001.5  958.95  5014.6  959.88  5161.7   958.4  5403.2   964.7  5434.7  970.52
  5614.4  988.29  5665.7  990.67  5749.7 1001.05  5935.7 1011.38  6027.3 1010.15
#Mann= 3 ,-1 , 0
  3053.9     .05       0  4977.8    .033       0  4987.5     .05       0
Bank Sta=4977.8,4987.5
XS Rating Curve= 0 ,0
Exp/Cntr=0.3,0.1

Type RM Length L Ch R = 1 ,29552   ,419,419,419
BEGIN DESCRIPTION:
BRADEN BRANCH 54.0
END DESCRIPTION:
XS GIS Cut Line= 3
      2244615.43      7234794.22        2243279.        7234010.
      2242272.88       7233510.1
#Sta/Elev= 30
  3445.9  996.14  3578.9  994.24  3701.9  985.75    3782  981.94  3803.5  982.72
  3870.8  980.15  3920.8  975.63  3973.6  978.13  4059.5  976.08  4125.8  982.63
  4309.7  991.08  4608.6   977.8  4784.5  966.93  4864.5   958.9  4932.2  955.73
  4933.7  955.23  4942.7  955.73  4972.2  958.19  4987.6  956.42  5026.2  958.62
  5129.4   956.2  5285.8  957.87  5412.7  965.93  5474.3  967.76  5526.3  974.92
    5656  985.25  5765.6  991.15  5944.6 1004.27  5950.4 1006.42  6118.9 1013.82
#Mann= 5 ,-1 , 0
  3445.9     .05       0  4932.2    .033       0  4942.7     .05       0
  5526.3     .12       0    5656     .05       0
Bank Sta=4932.2,4942.7
XS Rating Curve= 0 ,0
Exp/Cntr=0.3,0.1

Type RM Length L Ch R = 1 ,29133   ,482,482,482
BEGIN DESCRIPTION:
BRADEN BRANCH 53.0
END DESCRIPTION:
XS GIS Cut Line= 3
       2244780.4      7234646.67        2243529.        7233710.
      2242602.83      7233137.03
#Sta/Elev= 30
  3433.1  987.91  3803.2  979.25  3967.8  978.52  4096.9  971.09  4138.7  971.13
  4153.3  975.66  4182.5  973.48  4288.7  976.49  4417.9  984.49    4518   981.2
  4859.7  956.89  4959.7  957.26  4983.7  952.05  4985.1  951.55  4994.2  952.05
  5009.8  956.23  5046.4  957.96  5177.6  954.98  5250.9  957.31  5272.2  961.03
  5345.5  965.39  5351.4  969.39  5366.7  969.09  5372.6  964.89  5403.4  966.14
  5445.9  969.95  5461.3  974.57  5534.6  983.26  5866.7 1007.64  6085.3 1012.01
#Mann= 3 ,-1 , 0
  3433.1     .05       0  4983.7    .033       0  4994.2     .05       0
Bank Sta=4983.7,4994.2
XS Rating Curve= 0 ,0
Exp/Cntr=0.3,0.1

Type RM Length L Ch R = 1 ,28651   ,475,475,475
BEGIN DESCRIPTION:
BRADEN BRANCH 52.0
END DESCRIPTION:
XS GIS Cut Line= 3
      2245335.93      7234507.77        2243829.        7233460.
      2242957.87      7232884.78
#Sta/Elev= 30
  3159.5  1006.5  3428.5 1005.08  3565.5  993.33  3643.2  995.71  3759.3  983.43
    3947  972.71  3953.1  974.98  3967.9  972.27  4024.7  973.55  4054.3  970.64
  4075.3  974.15  4090.1  970.73  4146.9  974.03  4161.7  970.85  4167.8  974.13
  4197.5  974.13  4304.9   958.1  4370.3  964.98  4483.8  969.57  4528.3  974.71
  4823.4  954.12  4945.6  953.09  5003.1  948.89  5004.6  948.39  5013.8  948.89
  5066.8  955.19    5183  952.14  5204.1  955.97  5715.8  995.22  6038.8 1001.67
#Mann= 3 ,-1 , 0
  3159.5     .05       0  5003.1    .033       0  5013.8     .05       0
Bank Sta=5003.1,5013.8
XS Rating Curve= 0 ,0
Exp/Cntr=0.3,0.1

Type RM Length L Ch R = 1 ,28176   ,471,471,471
BEGIN DESCRIPTION:
BRADEN BRANCH 51.0
END DESCRIPTION:
XS GIS Cut Line= 3
      2245813.39       7233830.7        2244079.        7233110.
      2243375.79      7232633.89
#Sta/Elev= 30
  3117.1 1014.45  3318.3 1003.29  3448.4  999.64  3466.9   997.1  3511.7  998.44
  3602.4  990.54    3620  992.49  3732.5  979.92  3756.4  981.02  3847.4  973.42
  3862.6  975.17  3915.8   969.3  4009.8   970.4  4045.9  967.12  4069.8  969.18
  4117.5  965.04  4183.1  965.25  4205.3  962.39  4229.2  963.42  4513.3  951.33
  4789.5  948.53  4927.5  951.27  4951.4   946.5  5033.2  946.44  5034.7  945.94
  5044.2  946.44  5089.6   956.5  5290.4     973  5434.2   988.5  5844.5 1009.09
#Mann= 3 ,-1 , 0
  3117.1     .05       0  5033.2    .033       0  5044.2     .05       0
Bank Sta=5033.2,5044.2
XS Rating Curve= 0 ,0
Exp/Cntr=0.3,0.1

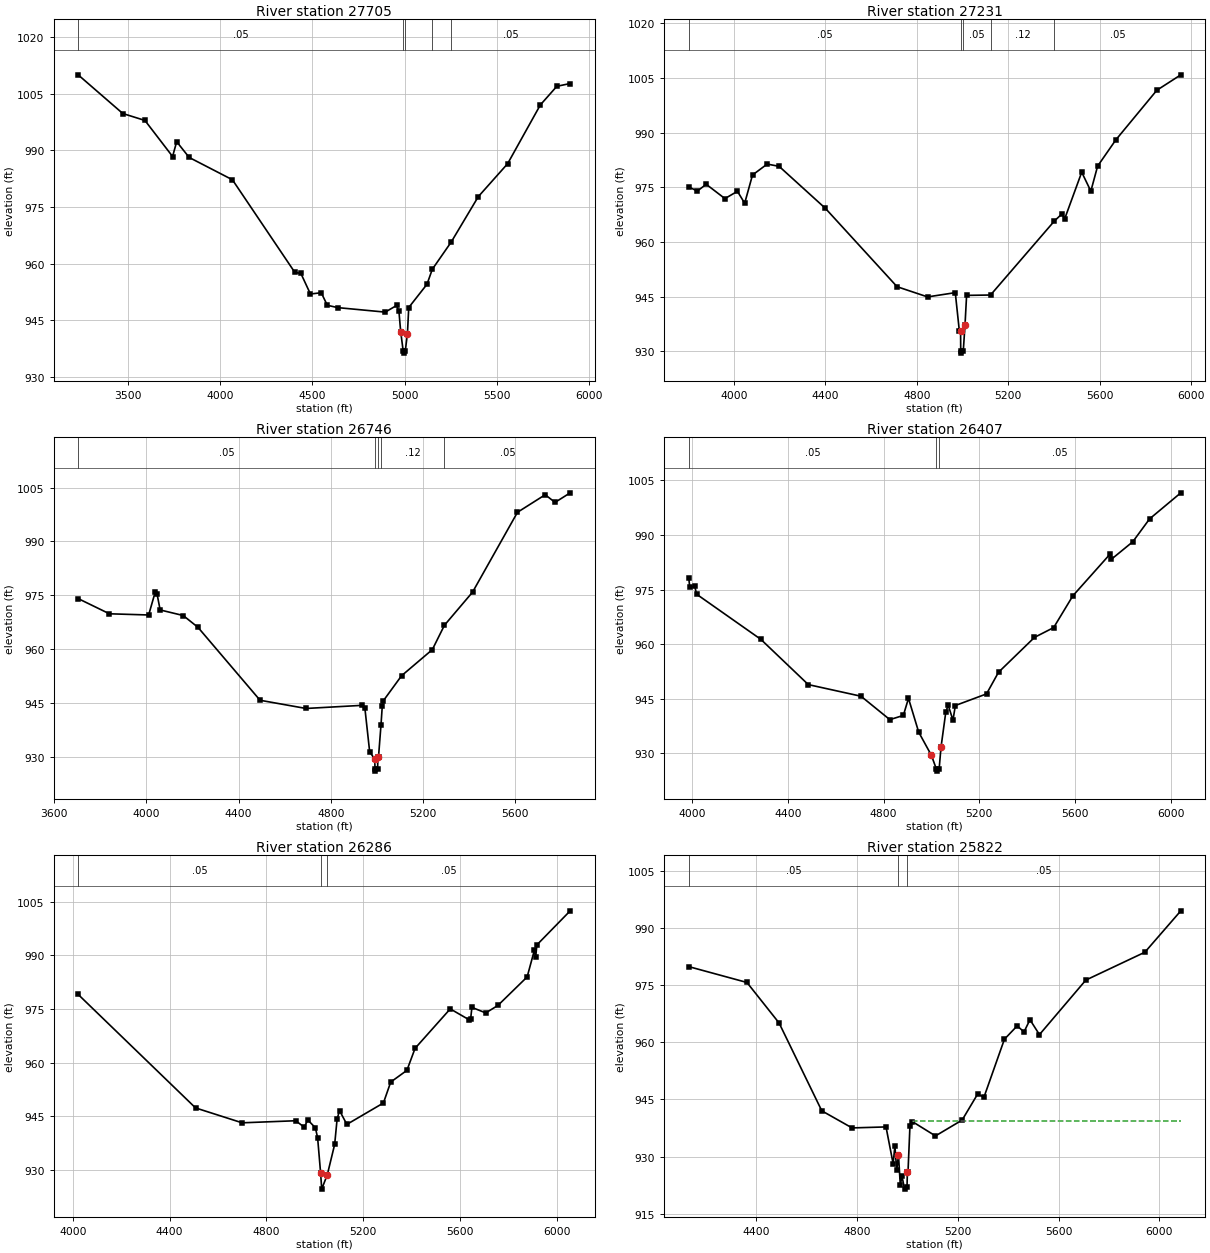
Type RM Length L Ch R = 1 ,27705   ,474,474,474
BEGIN DESCRIPTION:
BRADEN BRANCH 50.0
END DESCRIPTION:
XS GIS Cut Line= 3
      2245882.83      7233457.44        2244279.        7232710.
      2243452.25      7232363.68
#Sta/Elev= 30
  3230.5 1009.98  3472.5  999.73  3592.3   997.9  3742.2  988.35  3764.3  992.27
  3832.1   988.1  4066.3  982.19  4404.2  957.68  4437.3  957.38  4488.9  951.94
  4547.6  952.27  4580.4  948.95  4637.2  948.33  4894.3  947.14  4955.8   948.9
  4968.4  947.38  4977.9  941.99  4991.7  936.78  4993.2  936.28  5002.7  936.78
  5014.5  941.44  5021.6  948.36  5120.5  954.52  5149.3  958.49  5251.8  965.71
  5398.4  977.72  5557.4  986.45  5734.7 1002.02  5823.9 1006.94  5896.3 1007.68
#Mann= 5 ,-1 , 0
  3230.5     .05       0  4991.7    .033       0  5002.7     .05       0
  5149.3     .12       0  5251.8     .05       0
Bank Sta=4977.9,5014.5
XS Rating Curve= 0 ,0
Exp/Cntr=0.3,0.1

Type RM Length L Ch R = 1 ,27231   ,485,485,485
BEGIN DESCRIPTION:
BRADEN BRANCH 49.0
END DESCRIPTION:
XS GIS Cut Line= 3
      2245523.48      7232795.99        2244429.        7232310.
      2243507.83       7232061.6
#Sta/Elev= 30
  3802.5   975.1  3840.2  973.98  3878.7  975.84  3960.6  971.91  4015.3  973.91
    4047  970.63  4081.2  978.38  4145.5  981.38  4197.5  980.76    4400  969.23
  4713.4  947.74  4846.8  944.94  4967.9  946.11  4985.7  935.59  4991.1   935.6
  4991.7  930.02  4993.3  929.52  5002.8  930.02  5010.4   937.2  5017.4  945.36
  5122.1  945.46  5401.4  965.77    5435  967.75  5446.1  966.32  5520.8  979.15
  5560.7  973.95  5590.3  980.82  5670.1  988.03  5849.3 1001.63  5954.1 1005.86
#Mann= 5 ,-1 , 0
  3802.5     .05       0  4991.7    .033       0  5002.8     .05       0
  5122.1     .12       0  5401.4     .05       0
Bank Sta=4991.1,5010.4
XS Rating Curve= 0 ,0
Exp/Cntr=0.3,0.1

Type RM Length L Ch R = 1 ,26746   ,339,339,339
BEGIN DESCRIPTION:
BRADEN BRANCH 48.0
END DESCRIPTION:
XS GIS Cut Line= 3
      2245533.88      7232686.61        2244529.        7231860.
      2243716.17      7231670.98
#Sta/Elev= 30
  3703.7  974.13  3839.5   969.9  4009.8  969.57  4038.5  976.02  4046.4  975.35
  4059.6  970.97  4159.7  969.42  4223.6  966.15  4493.3  945.86  4692.8  943.58
  4933.9  944.44  4948.2  943.72    4969  931.55  4991.2  929.46  4992.2  926.66
  4993.7  926.16  5003.3  926.66  5004.9   930.1  5007.4   930.1  5018.1   938.9
  5023.6  944.13  5028.7  945.75  5107.5  952.68    5241  959.94  5293.6  966.72
  5415.6  975.92  5610.6  998.12    5731    1003  5773.6 1000.87  5839.4 1003.53
#Mann= 5 ,-1 , 0
  3703.7     .05       0  4992.2    .033       0  5003.3     .05       0
  5018.1     .12       0  5293.6     .05       0
Bank Sta=4991.2,5004.9
XS Rating Curve= 0 ,0
Exp/Cntr=0.3,0.1

Type RM Length L Ch R = 1 ,26407   ,121,121,121
BEGIN DESCRIPTION:
BRADEN BRANCH 47.5
END DESCRIPTION:
XS GIS Cut Line= 3
      2245585.93      7232368.87      2244825.53      7231707.43
      2243778.69      7231634.52
#Sta/Elev= 30
  3985.8  978.16    3990   975.6  4010.9  975.89  4018.5  973.74  4287.2  961.34
  4485.6  948.91  4705.9  945.72  4826.5  939.29    4883  940.45  4904.4  945.14
  4947.1  935.86  5000.2  929.49  5021.4  925.65  5022.9  925.15  5032.5  925.65
  5040.3  931.66  5060.3   941.3  5070.3  943.31  5090.4  939.13  5100.4  943.17
  5230.7  946.36  5280.8   952.3  5431.2  961.88  5511.4  964.57  5591.6  973.29
  5747.6  984.78  5752.6  983.33  5842.2  988.14  5912.4  994.42    6043 1001.58
#Mann= 3 ,-1 , 0
  3985.8     .05       0  5021.4    .033       0  5032.5     .05       0
Bank Sta=5000.2,5040.3
XS Rating Curve= 0 ,0
Exp/Cntr=0.3,0.1

Type RM Length L Ch R = 1 ,26286   ,464,464,464
BEGIN DESCRIPTION:
BRADEN BRANCH 47.0
END DESCRIPTION:
XS GIS Cut Line= 3
      2245648.47      7232212.65      2244882.83      7231608.47
      2243832.33      7231488.86
#Sta/Elev= 30
  4022.1  979.09  4507.2  947.37  4699.6  943.21  4920.9  943.79  4956.2  941.98
  4970.6  944.02  5001.9  941.84  5011.3  939.08 5023.53  929.31  5028.3  924.68
  5051.6  928.76  5081.8  937.19  5091.8  944.25  5101.9  946.63  5132.1  942.77
  5283.1  948.75  5313.3   954.6  5380.2  957.87  5413.9  964.02  5559.2  975.05
  5635.3  972.08  5643.6  972.34  5648.7  975.47  5705.8  973.92  5756.1  976.01
  5876.9  983.98  5907.1  991.53  5912.1  989.55  5917.1  992.93  6054.7 1002.45
#Mann= 3 , 0 , 0
  4022.1     .05       0 5023.53    .033       0  5051.6     .05       0
Bank Sta=5023.53,5051.6
XS Rating Curve= 0 ,0
Exp/Cntr=0.3,0.1

Type RM Length L Ch R = 1 ,25822   ,567,567,567
BEGIN DESCRIPTION:
BRADEN BRANCH 46.0
END DESCRIPTION:
XS GIS Cut Line= 3
       2245809.9      7231905.34        2245179.        7231310.
       2244108.3      7231134.76
#Sta/Elev= 30
  4132.5  979.85  4363.4  975.69  4490.8  965.07  4660.3  942.02  4780.5  937.53
  4915.2  937.79  4943.5  928.11  4950.4  932.86  4957.7  926.38  4964.6  930.48
  4971.8  922.59  4978.7  924.79  4988.8  921.47  4998.5  921.97    5000  926.07
  5002.5  926.07  5010.1  937.97  5020.2  939.17  5111.4  935.43  5217.2  939.59
  5278.6   946.4  5303.9  945.61    5385   960.8  5435.7  964.31  5462.7  962.71
  5486.3  965.92    5524  962.01  5708.1  976.32  5942.3  983.63  6084.9  994.49
#Mann= 3 , 0 , 0
  4132.5     .05       0  4964.6    .033       0    5000     .05       0
#XS Ineff= 2 , 0
                          5020.3          939.28
Permanent Ineff=
       F       F
Bank Sta=4964.6,5000
XS Rating Curve= 0 ,0
Exp/Cntr=0.3,0.1

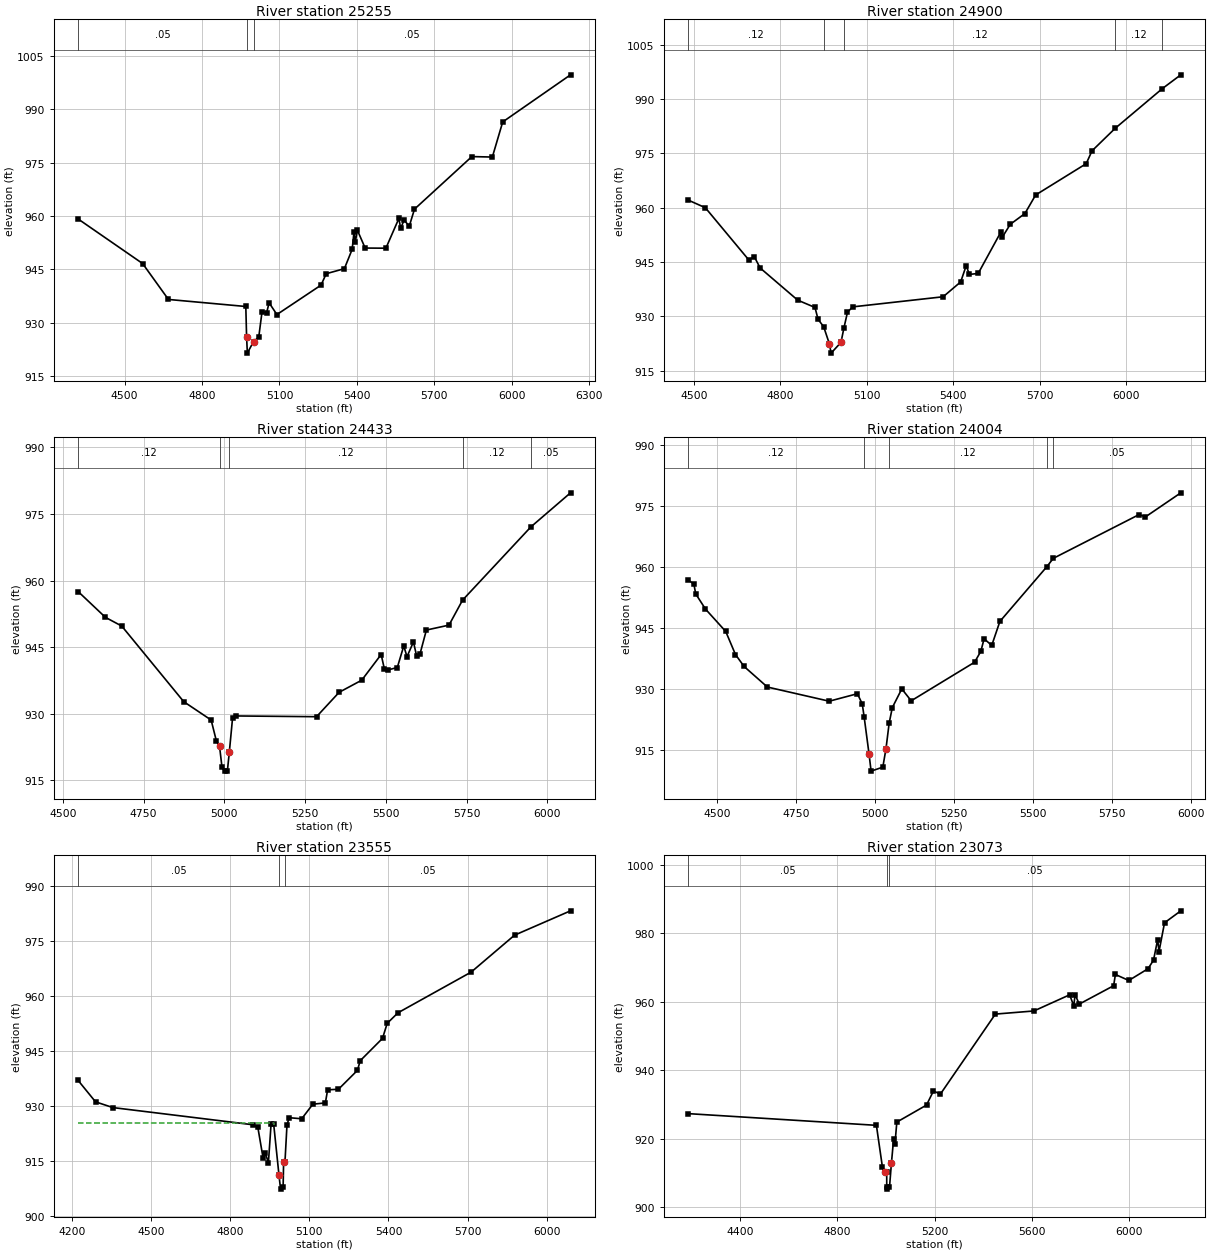
Type RM Length L Ch R = 1 ,25255   ,355,355,355
BEGIN DESCRIPTION:
BRADEN BRANCH 45.0
END DESCRIPTION:
XS GIS Cut Line= 3
       2245908.9      7230827.22      2245221.37      7230832.43
      2244007.85      7230967.85
#Sta/Elev= 30
  4319.7  959.18  4569.6  946.65  4669.6  936.55  4969.6  934.57 4972.62  926.06
  4975.6  921.45  4999.6  924.72  5019.7  925.92  5032.6  933.15  5049.9  932.68
  5059.9  935.61  5090.1   932.3  5261.2  940.58  5281.3  943.79  5351.7  945.21
  5381.9  950.65    5389  955.54  5394.1  952.72  5402.1  956.04  5432.2  951.01
  5512.7  950.97    5563  959.34  5569.8  956.55  5583.2  958.88  5603.3  957.17
  5623.4  961.95  5845.9  976.74  5925.3  976.61  5965.5  986.49  6228.3  999.74
#Mann= 3 , 0 , 0
  4319.7     .05       0 4972.62    .033       0  4999.6     .05       0
Bank Sta=4972.62,4999.6
XS Rating Curve= 0 ,0
Exp/Cntr=0.3,0.1

Type RM Length L Ch R = 1 ,24900   ,467,467,467
BEGIN DESCRIPTION:
BRADEN BRANCH 44.0
END DESCRIPTION:
XS GIS Cut Line= 3
       2245797.6      7230474.58        2245279.        7230510.
      2244104.95      7230708.95
#Sta/Elev= 30
  4480.2   962.1  4538.9  960.02  4689.3  945.66  4709.3  946.45  4729.4  943.38
  4859.7  934.51  4919.8  932.49  4930.7  929.18  4949.9  927.19  4969.9  922.43
  4975.9  919.88  5010.2  922.85  5020.3  926.81  5032.7  931.17  5050.7  932.65
  5365.1  935.44    5426  939.54  5445.1     944  5456.4  941.61  5486.9  941.88
  5565.8  953.33  5570.8  951.91  5598.4  955.45  5649.1  958.41  5686.5  963.54
  5862.1  972.18  5882.4  975.73  5962.5  981.92  6126.6   992.9  6190.8  996.71
#Mann= 5 ,-1 , 0
  4480.2     .12       0  4949.9     .03       0  5020.3     .12       0
  5962.5     .12       0  6126.6     .05       0
Bank Sta=4969.9,5010.2
XS Rating Curve= 0 ,0
Exp/Cntr=0.3,0.1

Type RM Length L Ch R = 1 ,24433   ,429,429,429
BEGIN DESCRIPTION:
BRADEN BRANCH 43.0
END DESCRIPTION:
XS GIS Cut Line= 3
      2245672.67      7230120.42        2245229.        7230060.
      2244152.87      7230063.12
#Sta/Elev= 30
  4547.7  957.54  4632.1  951.73  4682.6  949.77  4874.4  932.74  4959.3   928.6
  4975.3  923.95  4985.4  922.64  4992.9  917.95  5001.4  917.09  5009.5  917.09
  5015.5  921.31  5025.5  928.97  5035.5  929.52  5285.5  929.35  5355.5  934.85
  5425.5  937.58  5485.5  943.36  5495.5  940.11  5505.5  939.87  5535.5  940.43
  5555.5  945.29  5565.5  942.87  5585.5  946.19  5595.5  942.97  5605.5  943.41
  5625.5  948.87  5695.5  949.98  5737.5  955.61  5948.9   972.1  6071.6  979.78
#Mann= 5 ,-1 , 0
  4547.7     .12       0  4985.4    .033       0  5015.5     .12       0
  5737.5     .12       0  5948.9     .05       0
Bank Sta=4985.4,5015.5
XS Rating Curve= 0 ,0
Exp/Cntr=0.3,0.1

Type RM Length L Ch R = 1 ,24004   ,449,449,449
BEGIN DESCRIPTION:
BRADEN BRANCH 42.0
END DESCRIPTION:
XS GIS Cut Line= 3
      2245578.61      7230013.88        2245079.        7229710.
      2244107.25      7229670.98
#Sta/Elev= 30
  4410.6  956.75  4427.7  955.85  4433.6   953.4  4464.5  949.67  4528.5  944.18
  4559.4   938.5  4586.6  935.58  4660.2  930.53  4855.9  927.05    4945  928.89
  4960.3   926.4  4966.3  923.21  4981.8   914.1  4988.3  909.88  5025.4  910.86
  5035.4  915.38  5045.4  921.65  5055.4  925.48  5085.4  930.07  5115.2  927.15
  5315.6  936.62  5335.6  939.33  5345.7  942.39  5369.9  940.75  5395.7  946.64
  5544.4   960.1  5564.6  962.13    5836  972.88  5856.1  972.31  5967.9  978.22
#Mann= 5 ,-1 , 0
  4410.6     .12       0  4966.3    .033       0  5045.4     .12       0
  5544.4     .12       0  5564.6     .05       0
Bank Sta=4981.8,5035.4
XS Rating Curve= 0 ,0
Exp/Cntr=0.3,0.1

Type RM Length L Ch R = 1 ,23555   ,482,482,482
BEGIN DESCRIPTION:
BRADEN BRANCH 41.0
END DESCRIPTION:
XS GIS Cut Line= 4
       2245475.4      7229882.92      2245170.72      7229320.44
        2245029.        7229310.      2243972.27      7229559.12
#Sta/Elev= 30
  4223.1   936.9    4289  931.08  4354.6  929.52  4884.6  924.85  4904.6  924.16
  4924.7  915.71  4933.3  917.02  4944.7  914.49  4954.8  924.99  4964.8  924.95
  4984.8  911.14  4990.8   907.3  5000.5   907.8  5002.4  914.66  5007.5  914.66
  5015.2  924.81  5023.5  926.76    5071  926.47  5113.3  930.44  5160.8  930.79
  5169.3  934.35  5210.4  934.51  5282.3  939.65    5293  942.29  5377.6  948.38
  5395.3  952.47  5436.4  955.35  5713.8  966.43  5878.2  976.48  6090.6  983.12
#Mann= 3 ,-1 , 0
  4223.1     .05       0  4984.8    .033       0  5007.5     .05       0
#XS Ineff= 2 , 0
         4965.17   925.2
Permanent Ineff=
       F       F
Bank Sta=4984.8,5002.4
XS Rating Curve= 0 ,0
Exp/Cntr=0.3,0.1

Type RM Length L Ch R = 1 ,23073   ,400,400,400
BEGIN DESCRIPTION:
BRADEN BRANCH 40.0
END DESCRIPTION:
XS GIS Cut Line= 4
      2245313.96      7229520.99      2245243.64      7228942.83
        2245029.        7228860.      2243936.71      7229385.47
#Sta/Elev= 30
  4187.5  927.38  4960.4  923.97    4985  911.85  4997.3  910.27  5002.8  910.27
  5002.9  905.85  5004.4  905.35  5014.2  905.85  5022.2  912.95  5031.2  919.98
  5036.7  918.58  5044.4  924.92  5166.4  929.88  5195.1  934.02  5223.3  933.06
  5449.6  956.44    5608  957.35  5754.9  962.06    5772  958.88  5777.5  962.12
  5794.6  959.36  5935.9  964.72  5943.2     968  5998.3  966.25  6077.3  969.68
  6099.9  972.18    6117  978.21  6122.5  974.69  6145.2  983.09  6212.1  986.58
#Mann= 3 ,-1 , 0
  4187.5     .05       0  5002.9    .033       0  5014.2     .05       0
Bank Sta=4997.3,5022.2
XS Rating Curve= 0 ,0
Exp/Cntr=0.3,0.1

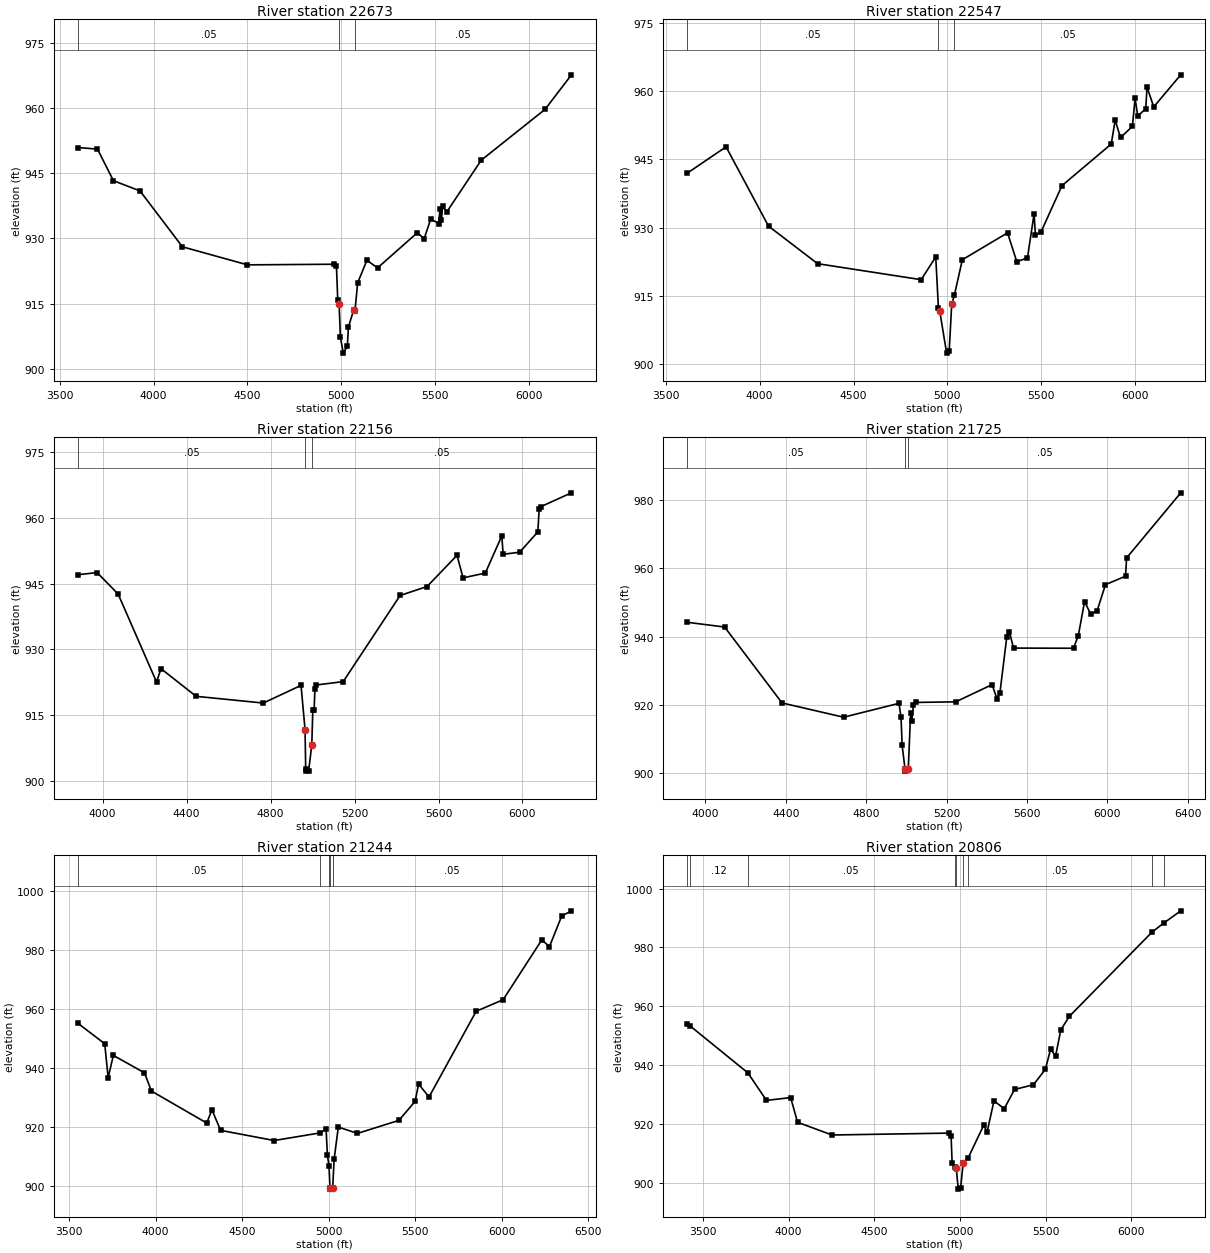
Type RM Length L Ch R = 1 ,22673   ,126,126,126
BEGIN DESCRIPTION:
BRADEN BRANCH 39.0
END DESCRIPTION:
XS GIS Cut Line= 3
      2246039.96      7227455.36      2245056.78      7228500.28
      2244165.34      7229295.29
#Sta/Elev= 30
  3597.7  950.93  3700.5  950.57  3785.5   943.3  3927.1  940.95  4153.3  928.08
    4500  923.93    4960  924.07  4974.2  923.62  4981.1  915.87  4988.4  915.03
  4995.2  907.31  5010.8  903.61  5032.4  905.25  5037.9  909.62  5066.3  913.55
    5073   913.3  5087.2  919.79  5136.7  924.98  5193.4  923.23  5405.7  931.34
  5441.7  929.93  5476.8  934.49  5519.4  933.44  5526.1  936.72  5533.6  934.18
  5540.3  937.44  5562.1   936.1    5746  948.02  6086.3  959.73  6226.9  967.67
#Mann= 3 ,-1 , 0
  3597.7     .05       0  4988.4    .033       0    5073     .05       0
Bank Sta=4988.4,5066.3
XS Rating Curve= 0 ,0
Exp/Cntr=0.3,0.1

Type RM Length L Ch R = 1 ,22547   ,391,391,391
BEGIN DESCRIPTION:
BRADEN BRANCH 38.5
END DESCRIPTION:
XS GIS Cut Line= 3
      2245977.46      7227358.13      2244994.28      7228403.06
      2244103.22      7229197.73
#Sta/Elev= 30
  3615.3  941.98  3820.8  947.73    4047  930.33  4308.7  922.08  4860.6  918.57
  4938.3  923.57  4952.5  912.39  4959.8  911.61  4996.3  902.45  5010.1  902.95
  5023.3  913.16  5037.4  915.15  5080.1  922.95  5320.9  928.85  5370.2  922.52
  5427.1  923.35  5462.2  932.99  5469.7  928.34  5498.2  928.94    5611  939.21
  5873.5  948.34  5894.5  953.56  5922.9  949.78  5986.4   952.2  6000.6  958.35
  6014.8   954.5  6057.5  956.08  6064.2  960.82  6100.1   956.5    6244  963.53
#Mann= 3 ,-1 , 0
  3615.3     .05       0  4952.5    .033       0  5037.4     .05       0
Bank Sta=4959.8,5023.3
XS Rating Curve= 0 ,0
Exp/Cntr=0.3,0.1

Type RM Length L Ch R = 1 ,22156   ,431,431,431
BEGIN DESCRIPTION:
BRADEN BRANCH 38.0
END DESCRIPTION:
XS GIS Cut Line= 3
      2245879.19      7227416.54        2244929.        7228010.
      2243963.26      7228770.13
#Sta/Elev= 30
  3883.9  947.01    3974  947.49  4074.2  942.59    4257  922.58  4278.3  925.61
  4445.7  919.32  4765.4  917.79  4945.2  921.81 4964.32  911.73  4967.4  902.79
  4969.4  902.29  4981.2  902.29  4996.5  908.25  5001.2  916.13  5007.4  916.13
  5011.4  920.97  5017.8   921.9  5146.1  922.67  5417.1  942.28  5545.4  944.32
  5688.2  951.42  5716.9  946.29  5822.9  947.38  5901.5  955.86  5907.8  951.67
  5986.4  952.12  6073.1  956.76  6079.5  962.05  6085.9  962.47  6233.2  965.65
#Mann= 3 , 0 , 0
  3883.9     .05       0 4964.32    .033       0  4996.5     .05       0
Bank Sta=4964.32,4996.5
XS Rating Curve= 0 ,0
Exp/Cntr=0.3,0.1

Type RM Length L Ch R = 1 ,21725   ,481,481,481
BEGIN DESCRIPTION:
BRADEN BRANCH 37.0
END DESCRIPTION:
XS GIS Cut Line= 3
      2245900.02      7227388.77        2244829.        7227610.
      2243518.08      7227979.05
#Sta/Elev= 30
  3910.6  944.21  4095.4  942.83  4381.3  920.58  4687.8   916.4  4963.4  920.47
  4973.6  916.41  4979.1  908.17  4993.7   901.1  4995.7   900.6  5009.6   901.1
  5021.2  917.52  5026.4  915.22  5035.4  919.88  5045.8  920.73  5246.2  920.91
  5426.8  925.95  5450.9  921.88    5466  923.58  5500.1  939.95  5513.3  941.27
  5534.1  936.66  5832.3  936.61  5856.1  940.31  5887.3  950.27  5918.4  946.59
    5950  947.65  5991.2  955.24  6091.3  957.74  6096.5  963.08  6366.1  982.16
#Mann= 3 ,-1 , 0
  3910.6     .05       0  4993.7    .033       0  5009.6     .05       0
Bank Sta=4993.7,5009.6
XS Rating Curve= 0 ,0
Exp/Cntr=0.3,0.1

Type RM Length L Ch R = 1 ,21244   ,438,438,438
BEGIN DESCRIPTION:
BRADEN BRANCH 36.0
END DESCRIPTION:
XS GIS Cut Line= 3
      2246372.22      7227159.61        2244929.        7227160.
      2243532.99      7226972.24
#Sta/Elev= 30
  3552.5     955  3705.7  948.13  3725.7  936.64  3755.7  944.17  3935.7  938.26
  3975.7  932.08  4295.7  921.22  4325.7  925.71  4375.7  918.74  4685.7  915.29
  4950.8  917.88  4985.7   919.2  4993.2  910.32  5002.6  906.71  5007.9   899.3
  5009.9   898.8  5023.8   899.3  5032.1  908.89  5056.3  919.86  5167.2  917.71
  5406.4  922.12  5500.2  928.55  5520.4  934.44  5580.9  930.07  5853.4  959.14
  6009.1  963.06  6232.7  983.35  6277.2  981.08  6347.8  991.46  6404.3  993.22
#Mann= 5 ,-1 , 0
  3552.5     .05       0  4950.8     .12       0  5002.6     .05       0
  5007.9     .07       0  5023.8     .05       0
Bank Sta=5007.9,5023.8
XS Rating Curve= 0 ,0
Exp/Cntr=0.3,0.1

Type RM Length L Ch R = 1 ,20806   ,578,578,578
BEGIN DESCRIPTION:
BRADEN BRANCH 35.0
END DESCRIPTION:
XS GIS Cut Line= 3
      2246406.91      7226944.32        2244829.        7226760.
      2243538.95      7226742.94
#Sta/Elev= 30
  3410.5   954.1    3426  953.36  3762.6  937.46  3871.5   928.1  4012.7  929.05
  4052.7  920.68  4254.1  916.36  4938.7     917  4948.8  916.12  4954.9   906.9
  4968.9   905.6    4979  905.17  4990.7  897.99  5004.6  898.49  5019.1  906.72
  5048.5  908.57  5139.2  919.67  5159.2  917.39  5199.2  927.94  5259.2  925.29
  5319.2  931.81  5429.2   933.4  5499.2  938.62  5529.2  945.39  5559.2  943.26
  5589.2  952.02  5639.2  956.62  6121.7  985.22    6190  988.27  6289.3  992.43
#Mann= 9 ,-1 , 0
  3410.5     .05       0    3426     .12       0  3762.6     .05       0
  4968.9     .12       0    4979     .07       0  5019.1     .12       0
  5048.5     .05       0  6121.7     .12       0    6190     .05       0
Bank Sta=4979,5019.1
XS Rating Curve= 0 ,0
Exp/Cntr=0.3,0.1

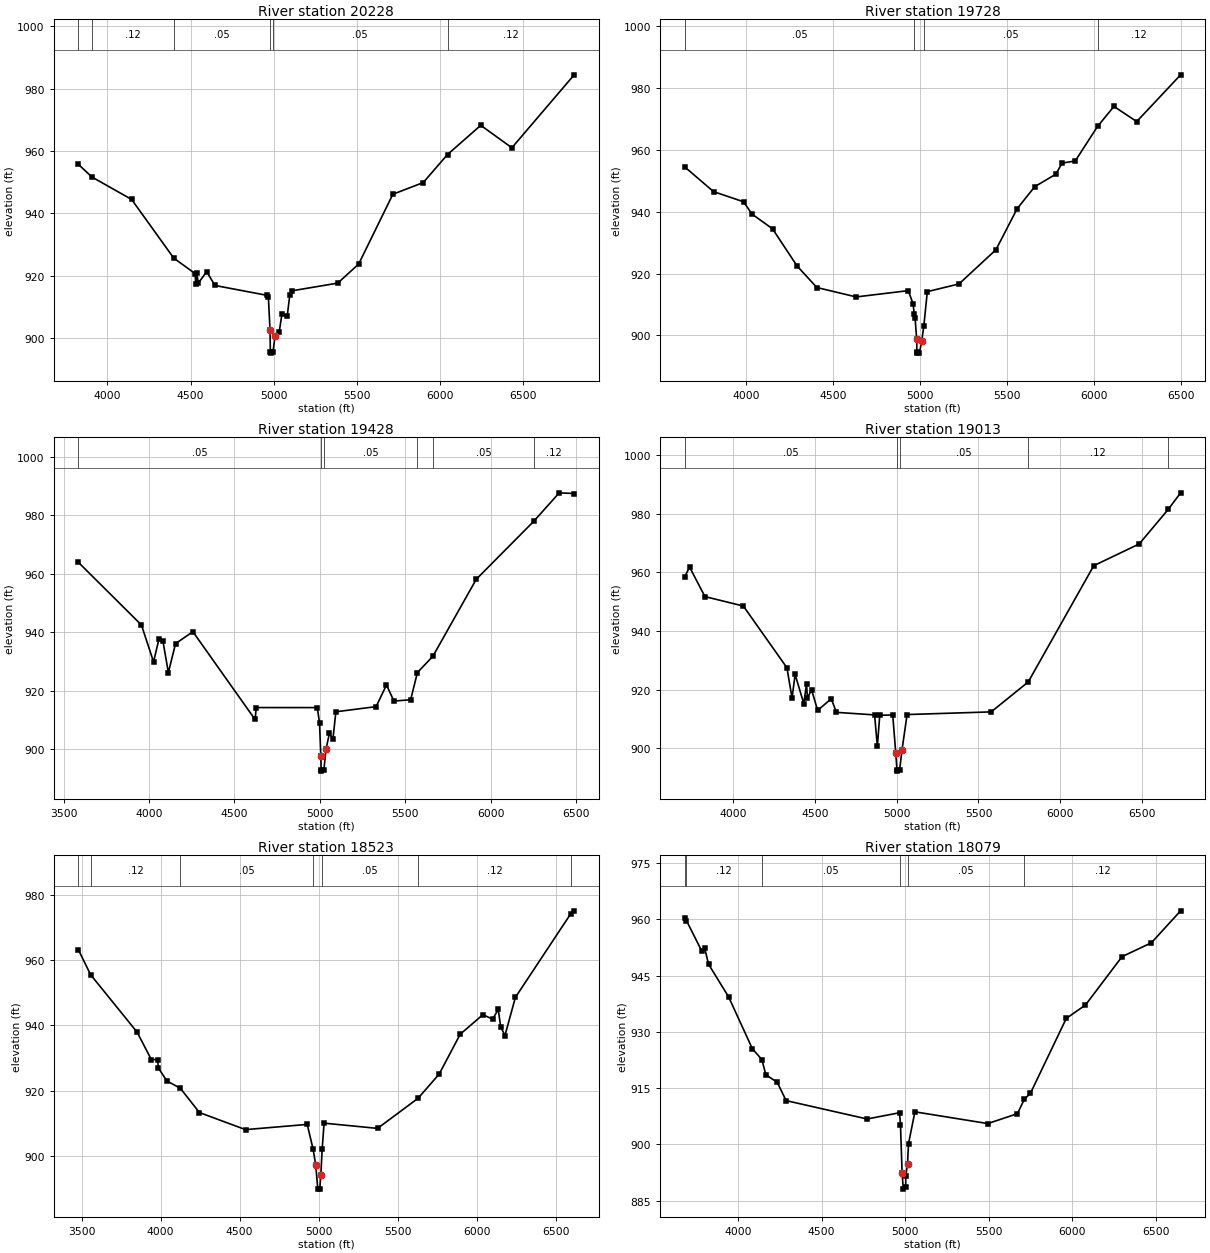
Type RM Length L Ch R = 1 ,20228   ,500,500,500
BEGIN DESCRIPTION:
BRADEN BRANCH 34.0
END DESCRIPTION:
XS GIS Cut Line= 3
      2246448.58      7226610.99      2245261.12      7226499.88
      2243553.37      7225951.46
#Sta/Elev= 30
  3824.4  955.73  3906.1  951.66  4145.4  944.46    4399  925.66    4527  920.72
  4532.4  917.28  4537.4  920.75  4547.1  917.64  4597.3   921.3  4647.6  916.88
    4963   913.7    4969  913.24    4979  902.51  4980.9  895.69  4982.9  895.19
  4997.1  895.69  5009.1   900.7    5034  901.91  5050.8  907.76  5082.3  906.94
  5098.2  913.94  5113.8   915.2  5386.9  917.64  5512.9  923.76  5718.8  946.13
  5901.5  949.87    6048  958.87  6248.2  968.23  6435.6  961.03  6810.7  984.42
#Mann= 6 ,-1 , 0
  3824.4     .05       0  3906.1     .12       0    4399     .05       0
  4980.9    .033       0  4997.1     .05       0    6048     .12       0
Bank Sta=4979,5009.1
XS Rating Curve= 0 ,0
Exp/Cntr=0.3,0.1

Type RM Length L Ch R = 1 ,19728   ,300,300,300
BEGIN DESCRIPTION:
BRADEN BRANCH 33.0
END DESCRIPTION:
XS GIS Cut Line= 3
      2246434.71      7226479.04      2245136.12      7226117.94
      2243650.32      7225874.93
#Sta/Elev= 30
  3647.2  954.44  3812.8  946.47  3985.3   943.2  4033.8  939.22    4152  934.45
  4294.1  922.39  4407.2  915.47  4633.4  912.43  4933.2  914.46  4960.9  910.24
  4967.4  907.02  4972.6  905.51  4981.7  898.69  4982.8  894.76  4984.8  894.26
  4997.1  894.26  5010.3  898.03  5022.5  902.88  5042.8  914.14  5225.2  916.63
    5438   927.7  5559.6  940.94  5660.9  948.07  5782.5  952.12  5818.3   955.7
    5894  956.38  6023.3  967.61  6116.9  974.02    6248  969.13  6500.6  984.24
#Mann= 4 ,-1 , 0
  3647.2     .05       0  4967.4    .033       0  5022.5     .05       0
  6023.3     .12       0
Bank Sta=4981.7,5010.3
XS Rating Curve= 0 ,0
Exp/Cntr=0.3,0.1

Type RM Length L Ch R = 1 ,19428   ,415,415,415
BEGIN DESCRIPTION:
BRADEN BRANCH 32.0
END DESCRIPTION:
XS GIS Cut Line= 3
      2246670.89      7226340.18        2245329.        7225910.
      2243852.72      7225687.58
#Sta/Elev= 30
  3586.1  963.89  3955.6  942.42  4026.4  929.81  4058.5  937.75  4081.6  936.83
  4113.1  926.15  4154.9  936.05  4256.6  940.14  4620.5  910.11  4627.7  914.19
  4984.8  914.18  4997.8  908.99  5005.4  897.54  5007.3  892.95  5009.3  892.45
  5023.6  892.95  5035.7  899.96  5055.9   905.4  5076.2  903.42  5093.6  912.75
    5329  914.51  5389.7  921.93  5433.4  916.41  5531.2  916.86  5570.8  926.18
  5661.1  931.72  5915.5  958.09  6252.3  977.94  6400.9  987.64  6488.2   987.4
#Mann= 6 ,-1 , 0
  3586.1     .05       0  5007.3    .033       0  5023.6     .05       0
  5570.8     .12       0  5661.1     .05       0  6252.3     .12       0
Bank Sta=5005.4,5035.7
XS Rating Curve= 0 ,0
Exp/Cntr=0.3,0.1

Type RM Length L Ch R = 1 ,19013   ,490,490,490
BEGIN DESCRIPTION:
BRADEN BRANCH 31.0
END DESCRIPTION:
XS GIS Cut Line= 3
      2246847.96      7226125.76        2245629.        7225710.
      2243932.64      7225297.96
#Sta/Elev= 30
  3703.2  958.53  3732.5  961.75  3826.5  951.71  4061.3  948.49  4327.9  927.46
  4359.3  917.17  4378.3  925.16  4431.1  915.23    4448   921.9  4453.3  917.23
  4479.3  919.86    4516  912.91  4599.4  916.89  4630.7  912.24  4864.3  911.37
  4881.4  900.68    4896  911.26  4975.4  911.34  4993.7  898.47  5001.3   892.7
  5003.3   892.2  5017.6   892.7  5032.3  899.47  5063.2  911.49  5577.7   912.4
  5804.4  922.61  6205.4  962.25  6483.3  969.65    6661  981.44  6736.8  987.09
#Mann= 5 ,-1 , 0
  3703.2     .05       0  5001.3    .033       0  5017.6     .05       0
  5804.4     .12       0    6661     .05       0
Bank Sta=4993.7,5032.3
XS Rating Curve= 0 ,0
Exp/Cntr=0.3,0.1

Type RM Length L Ch R = 1 ,18523   ,444,444,444
BEGIN DESCRIPTION:
BRADEN BRANCH 30.0
END DESCRIPTION:
XS GIS Cut Line= 3
      2247035.39      7225849.69        2245629.        7225260.
      2244056.26      7224896.58
#Sta/Elev= 30
  3478.8  963.17  3556.8  955.49    3851  937.93  3941.2  929.54  3980.7  929.56
  3986.1  926.93  4039.1  923.03  4124.8  920.76  4245.6  913.34  4537.5  908.12
  4927.9  909.72  4965.4   902.1  4982.1  897.15    4995  889.92  5007.3  889.92
  5014.1  894.24  5022.6  902.09  5034.6   910.1  5373.3   908.5  5629.5   917.7
  5763.3  925.11  5896.7  937.31  6040.4  943.29    6102   941.9  6137.2   944.9
  6153.3  939.49  6179.9  936.91  6245.7  948.55  6597.4  974.23    6618  975.05
#Mann= 7 ,-1 , 0
  3478.8     .05       0  3556.8     .12       0  4124.8     .05       0
  4965.4    .033       0  5022.6     .05       0  5629.5     .12       0
  6597.4     .05       0
Bank Sta=4982.1,5014.1
XS Rating Curve= 0 ,0
Exp/Cntr=0.3,0.1

Type RM Length L Ch R = 1 ,18079   ,470,470,470
BEGIN DESCRIPTION:
BRADEN BRANCH 29.0
END DESCRIPTION:
XS GIS Cut Line= 3
      2247129.15      7225516.36        2245929.        7224960.
      2244353.61      7224485.27
#Sta/Elev= 30
  3681.5  960.51  3691.4  959.69  3783.1  951.57  3800.5  952.39  3823.4  948.08
  3943.5  939.38  4086.5  925.48  4142.9  922.66  4166.6  918.59  4234.9  916.58
  4287.9   911.7  4772.9   906.8  4967.2  908.47  4972.7  905.19  4982.3  892.47
  4989.5   888.1  5003.8   888.6  5004.3  891.53  5014.8  894.87  5020.8  900.24
    5059  908.71  5495.2  905.58  5672.8  908.21  5714.2  912.08  5750.3  913.62
  5965.2  933.62  6080.1  937.19  6299.1  950.09  6474.5  953.77  6649.7   962.3
#Mann= 6 ,-1 , 0
  3681.5     .05       0  3691.4     .12       0  4142.9     .05       0
  4967.2    .033       0  5014.8     .05       0  5714.2     .12       0
Bank Sta=4982.3,5014.8
XS Rating Curve= 0 ,0
Exp/Cntr=0.3,0.1