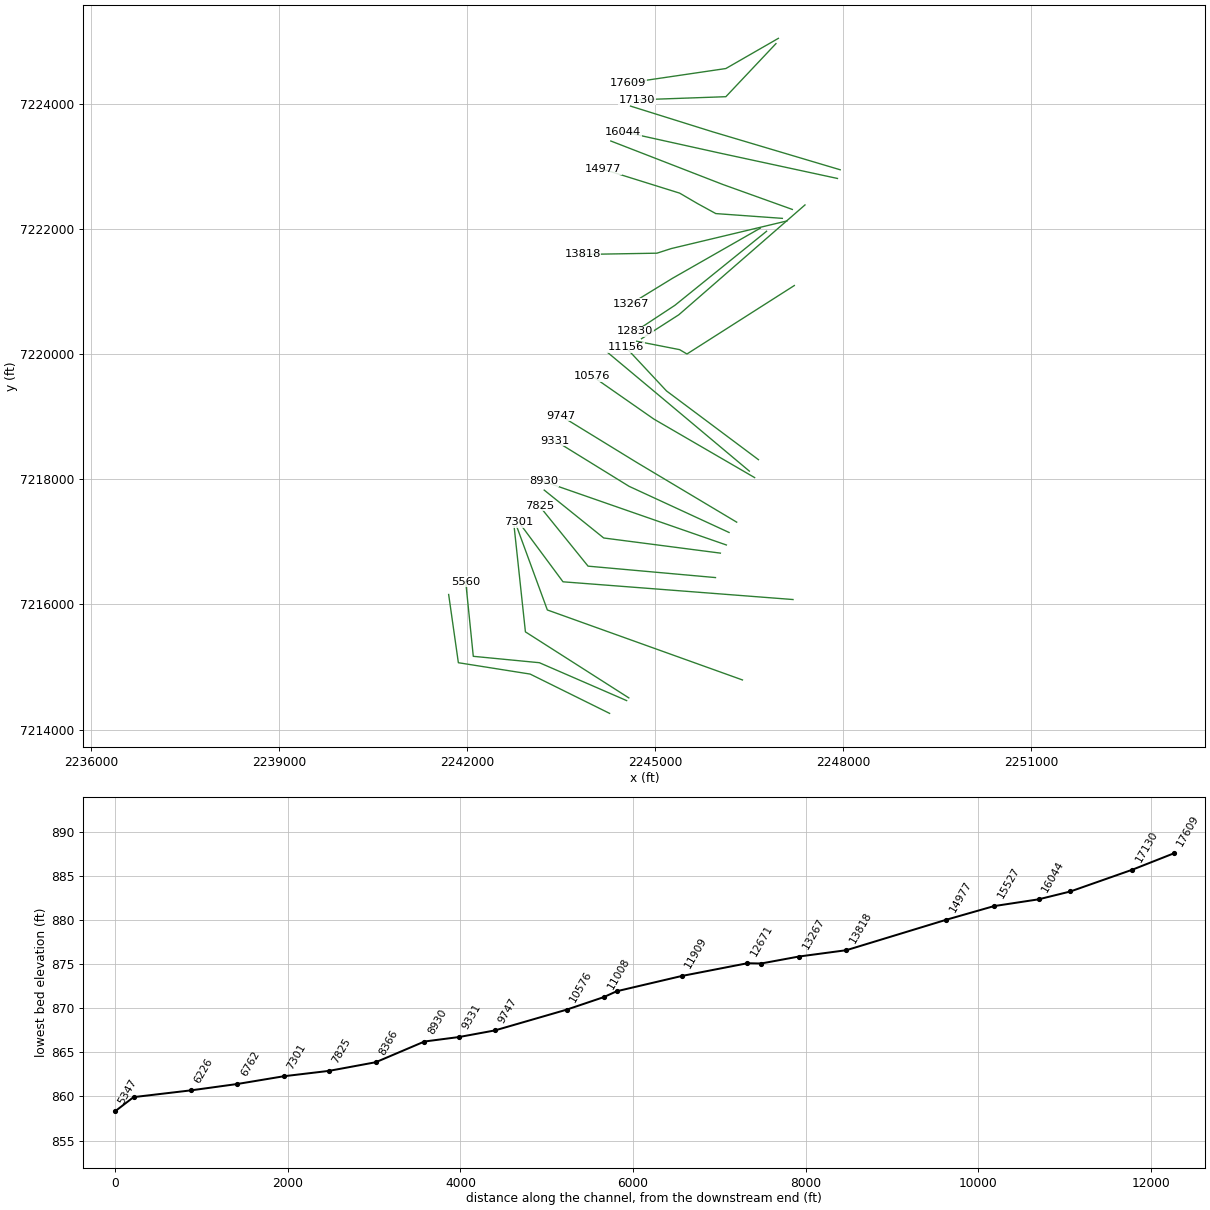
HEC-RAS study BRADEN BRANCH.prj: BRADEN BRANCH Base Level Engineering

--- BRADEN BRANCH.g01 (geometry) --- (continued)

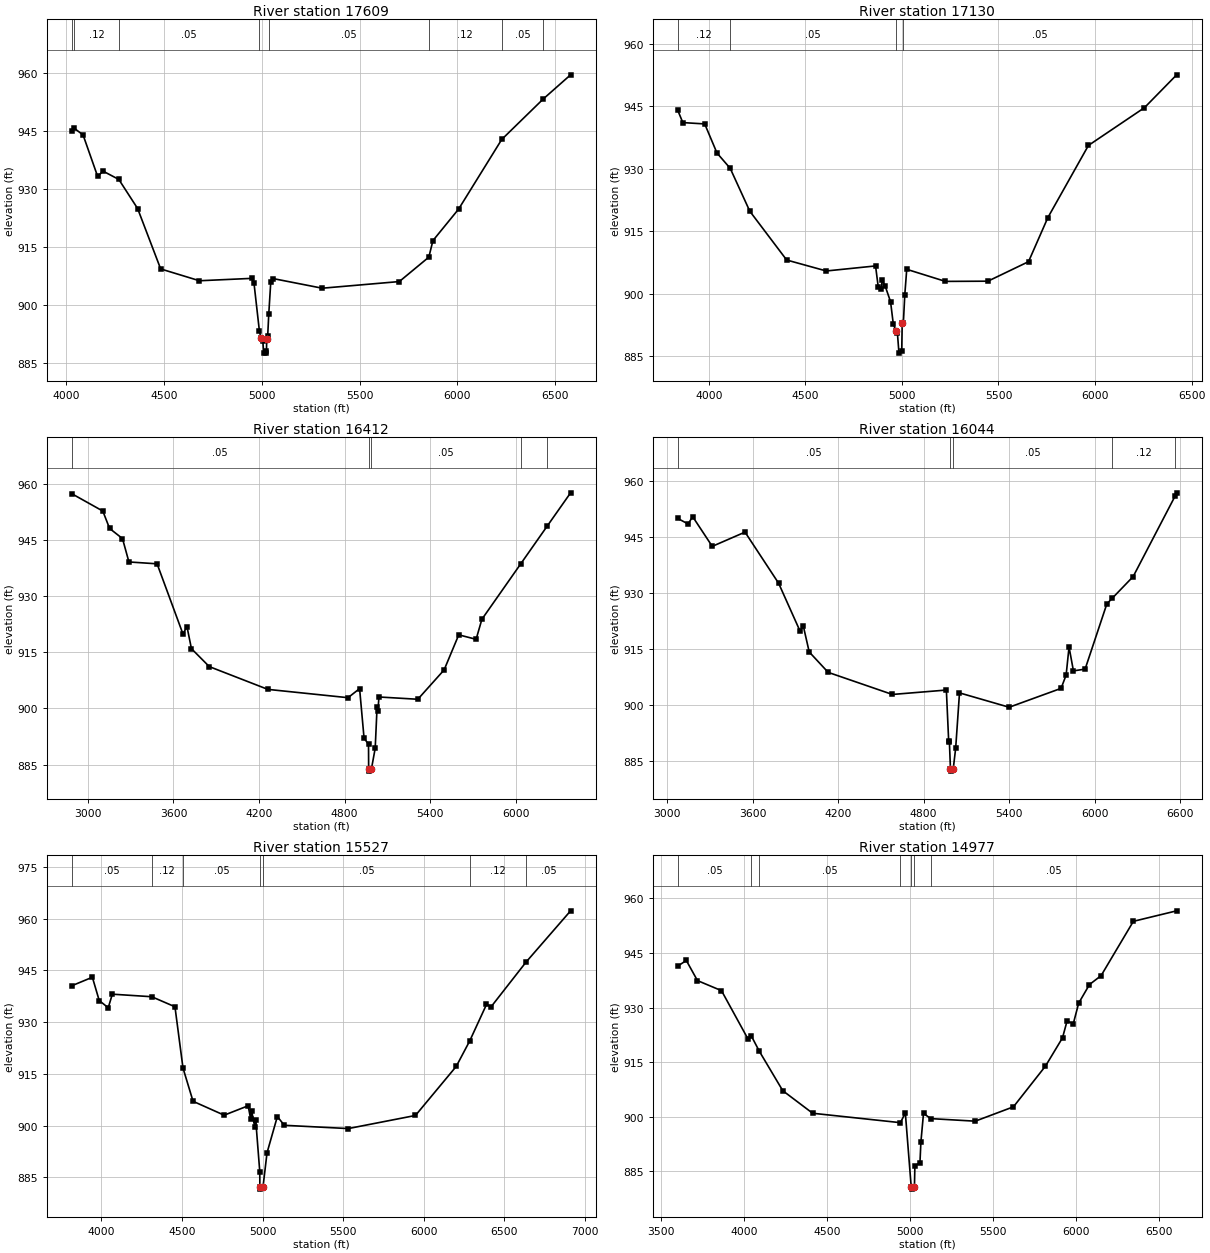
Type RM Length L Ch R = 1 ,17609   ,479,479,479
BEGIN DESCRIPTION:
BRADEN BRANCH 28.0
END DESCRIPTION:
XS GIS Cut Line= 3
      2246967.76      7225042.44        2246129.        7224560.
      2244562.74      7224329.06
#Sta/Elev= 30
  4028.1  945.18  4042.5  945.72  4086.6  944.04  4161.3  933.28  4188.7  934.67
  4269.4  932.52  4365.5  924.99  4483.3  909.36  4681.6   906.3  4950.4  906.92
  4960.5  905.64  4987.8  893.41  4995.7   891.5  5005.8  890.64  5009.8  887.57
  5022.1  887.57  5024.1  888.07  5025.5  891.31  5030.5  892.07  5036.1  897.82
  5046.2  906.01  5056.4  906.88  5309.2  904.37  5703.3  906.09  5854.2  912.41
  5875.1  916.69  6006.5  924.85  6227.1  942.88  6439.3  953.35  6578.9  959.59
#Mann= 8 ,-1 , 0
  4028.1     .05       0  4042.5     .12       0  4269.4     .05       0
  4987.8    .033       0  5036.1     .05       0  5854.2     .12       0
  6227.1     .05       0  6439.3     .12       0
Bank Sta=4995.7,5025.5
XS Rating Curve= 0 ,0
Exp/Cntr=0.3,0.1

Type RM Length L Ch R = 1 ,17130   ,718,718,718
BEGIN DESCRIPTION:
BRADEN BRANCH 27.0
END DESCRIPTION:
XS GIS Cut Line= 3
      2246928.89      7224958.02        2246129.        7224110.
      2244712.54      7224059.62
#Sta/Elev= 30
  3839.4  944.02  3866.1  941.03  3979.4  940.71  4042.9  933.73  4111.3  930.06
  4212.8  919.77  4403.7  908.06  4608.9  905.43  4863.8  906.64  4877.9  901.52
  4892.1  901.13  4898.9  903.26  4913.1  901.87  4941.4  898.07  4955.6  892.72
  4969.7  890.99    4977  890.48    4985  885.72  4999.3  886.22  5001.7  892.88
  5007.6  892.88  5015.2  899.75  5025.2  905.83  5225.3  902.93  5445.4  902.98
  5655.6  907.66  5755.6  918.22  5965.8  935.55  6255.9  944.61  6422.5  952.49
#Mann= 4 ,-1 , 0
  3839.4     .12       0  4111.3     .05       0  4969.7    .033       0
  5007.6     .05       0
Bank Sta=4969.7,5001.7
XS Rating Curve= 0 ,0
Exp/Cntr=0.3,0.1

Type RM Length L Ch R = 1 ,16412   ,368,368,368
BEGIN DESCRIPTION:
BRADEN BRANCH 26.0
END DESCRIPTION:
XS GIS Cut Line= 3
      2247954.09      7222942.64      2245914.16      7223550.28
      2244606.79      7223959.75
#Sta/Elev= 30
  2886.1  957.36  3104.9   952.7  3152.3  948.06  3242.8  945.35  3287.9  939.11
  3485.4  938.61  3666.9  919.86  3694.8  921.87  3726.1  915.96  3851.4  911.16
    4262  905.08    4824  902.86  4905.2  905.28  4936.5  892.05  4967.8  890.41
  4968.7  883.75  4970.7  883.25  4987.8  883.75  5014.6  889.36  5027.8  900.39
  5033.1   899.2    5041  903.05  5313.4  902.44  5497.8  910.28  5600.4  919.65
  5722.1  918.45  5762.6   923.8  6035.4  938.63  6219.7  948.64  6384.6  957.57
#Mann= 5 ,-1 , 0
  2886.1     .05       0  4968.7    .033       0  4987.8     .05       0
  6035.4     .12       0  6219.7     .05       0
Bank Sta=4968.7,4987.8
XS Rating Curve= 0 ,0
Exp/Cntr=0.3,0.1

Type RM Length L Ch R = 1 ,16044   ,517,517,517
BEGIN DESCRIPTION:
BRADEN BRANCH 25.0
END DESCRIPTION:
XS GIS Cut Line= 3
      2247910.66      7222803.76        2246029.        7223210.
      2244492.26       7223549.9
#Sta/Elev= 30
    3075  949.97  3148.3  948.47  3179.9  950.45  3317.5  942.49  3547.3   946.3
  3782.6  932.64  3932.4  919.88  3956.5  921.09  3997.4  914.24  4130.4  908.78
  4580.6  902.87  4959.1  904.05  4975.4  890.32  4980.5  890.06  4987.9  882.86
  4989.9  882.36    5007  882.86  5024.4  888.51  5051.2  903.29  5399.4  899.45
  5763.5   904.5  5798.9  908.06  5819.3  915.56  5850.1  909.18    5932  909.65
  6084.3  927.09    6124  928.68  6269.1  934.42    6563  955.94  6573.9  956.81
#Mann= 5 ,-1 , 0
    3075     .05       0  4987.9    .033       0    5007     .05       0
    6124     .12       0    6563     .05       0
Bank Sta=4987.9,5007
XS Rating Curve= 0 ,0
Exp/Cntr=0.3,0.1

Type RM Length L Ch R = 1 ,15527   ,550,550,550
BEGIN DESCRIPTION:
BRADEN BRANCH 24.0
END DESCRIPTION:
XS GIS Cut Line= 3
      2247190.24      7222308.94      2246079.09      7222708.26
      2244292.42      7223402.12
#Sta/Elev= 30
  3814.8  940.54  3943.6  943.03  3986.1  936.28  4042.1  934.18  4067.5  938.12
  4312.2  937.38  4456.3  934.47  4506.1  916.72  4568.6  907.06  4761.8  903.03
  4910.6  905.76  4926.6  901.82    4932  904.32  4952.1  899.54  4957.4  901.73
  4982.8  886.64  4983.3  882.09  4985.3  881.59  5002.5  882.09  5027.8  892.12
  5091.9  902.64  5135.1   900.1    5532  899.15  5949.2  902.95  6202.2  917.17
  6285.8  924.55  6390.1  935.13    6420  934.54  6635.6  947.42  6912.2  962.29
#Mann= 7 ,-1 , 0
  3814.8     .05       0  4312.2     .12       0  4506.1     .05       0
  4983.3    .033       0  5002.5     .05       0  6285.8     .12       0
  6635.6     .05       0
Bank Sta=4983.3,5002.5
XS Rating Curve= 0 ,0
Exp/Cntr=0.3,0.1

Type RM Length L Ch R = 1 ,14977   ,1159,1159,1159
BEGIN DESCRIPTION:
BRADEN BRANCH 23.0
END DESCRIPTION:
XS GIS Cut Line= 5
      2247031.03      7222166.31      2245968.56       7222242.7
      2245676.89      7222402.42      2245392.17      7222569.09
      2244169.93      7222951.04
#Sta/Elev= 30
  3598.7  941.39  3650.9  942.94    3718  937.41  3862.9  934.64  4021.8  921.42
  4041.6  922.28    4091  917.97  4232.4  907.12  4412.5  900.92  4941.7  898.33
  4971.2  901.03  5006.8  880.55  5008.8  880.05    5026  880.55  5028.8  886.47
  5059.3  887.28  5065.1  893.04  5080.8  900.91  5123.4  899.45  5392.5  898.74
    5623  902.69  5816.2   913.9  5918.9  921.68  5946.1  926.29  5983.8  925.56
  6016.3  931.21  6081.3  936.32  6151.5  938.78  6345.9  953.71  6606.9   956.6
#Mann= 7 ,-1 , 0
  3598.7     .05       0  4041.6     .12       0    4091     .05       0
  4941.7     .12       0  5006.8     .07       0    5026     .12       0
  5123.4     .05       0
Bank Sta=5006.8,5026
XS Rating Curve= 0 ,0
Exp/Cntr=0.3,0.1

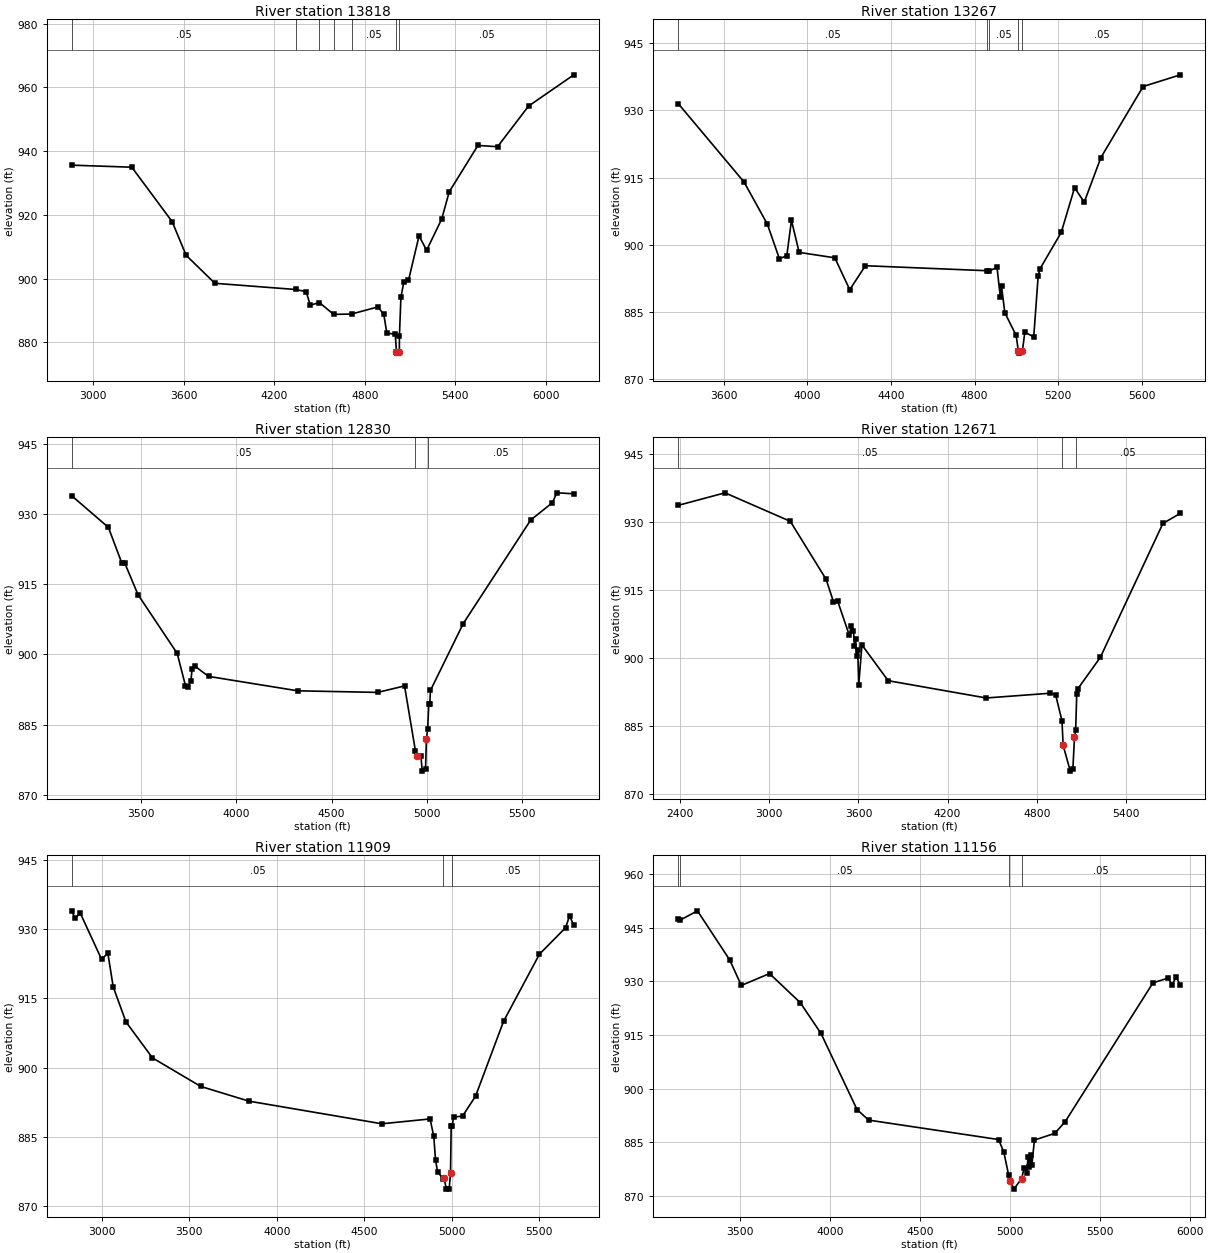
Type RM Length L Ch R = 1 ,13818   ,551,551,551
BEGIN DESCRIPTION:
BRADEN BRANCH 22.0
END DESCRIPTION:
XS GIS Cut Line= 4
       2247105.7      7222125.51      2245258.08       7221683.9
        2245029.        7221610.      2243843.74      7221589.92
#Sta/Elev= 30
  2859.6   935.6  3257.2  934.96  3524.5  917.87  3617.1   907.3  3807.7  898.51
  4341.8  896.57  4412.1  895.88  4439.6  891.64  4499.9  892.47  4593.8  888.76
  4713.2  888.86  4887.8  891.11  4926.4  888.73  4946.6  882.92  5002.5  882.49
  5010.3  877.09  5012.3  876.59  5029.6  877.09    5030  881.98    5040  894.25
    5060  899.05    5090  899.41    5160  913.41    5210  908.87    5310  918.67
    5360  927.25    5550  941.79  5680.1  941.39  5885.4  954.15  6185.4  963.96
#Mann= 7 ,-1 , 0
  2859.6     .05       0  4341.8     .12       0  4499.9     .05       0
  4593.8     .12       0  4713.2     .05       0  5010.3    .033       0
  5029.6     .05       0
Bank Sta=5010.3,5029.6
XS Rating Curve= 0 ,0
Exp/Cntr=0.3,0.1

Type RM Length L Ch R = 1 ,13267   ,437,437,437
BEGIN DESCRIPTION:
BRADEN BRANCH 21.0
END DESCRIPTION:
XS GIS Cut Line= 3
      2246678.99        7222010.        2245279.        7221210.
      2244607.43      7220798.24
#Sta/Elev= 30
  3383.4   931.5    3698  914.02  3809.5  904.62  3867.1  896.91  3902.4  897.59
  3924.7  905.47  3961.4  898.33    4132  897.12  4203.3  890.02  4278.2  895.36
  4860.3  894.24  4870.3  894.16  4907.3  895.04  4923.1  888.37  4928.9  890.76
  4944.7  884.86  4998.8  879.83  5009.2  876.37  5011.2  875.87  5028.7  876.37
  5040.3  880.55  5082.9  879.48  5104.2  893.17  5113.1  894.69  5214.4  902.79
  5278.2  912.76  5324.3  909.52  5403.8  919.46  5605.8  935.31  5783.6  937.92
#Mann= 5 ,-1 , 0
  3383.4     .05       0  4860.3     .12       0  4870.3     .05       0
  5009.2    .033       0  5028.7     .05       0
Bank Sta=5009.2,5028.7
XS Rating Curve= 0 ,0
Exp/Cntr=0.3,0.1

Type RM Length L Ch R = 1 ,12830   ,159,159,159
BEGIN DESCRIPTION:
BRADEN BRANCH 20.0
END DESCRIPTION:
XS GIS Cut Line= 3
      2246778.97      7221959.97      2245315.78      7220777.42
      2244683.89      7220360.79
#Sta/Elev= 30
  3135.2   933.9  3327.8  927.15  3398.2  919.52  3412.6  919.64    3483   912.8
  3689.2  900.23  3732.4  893.37  3746.8  893.15  3761.2  894.44  3767.6  896.88
    3782  897.51  3853.9  895.32  4322.4  892.24  4742.4   891.9  4883.8  893.28
  4941.2  879.35  4948.1  878.32    4970  878.31  4976.6  875.08  4994.1  875.58
  4998.8  881.99  5005.2  884.07  5011.2  889.41  5016.5  889.41  5019.8  892.31
  5192.3  906.61  5546.7  928.73  5661.1  932.44  5683.4  934.54  5773.4  934.34
#Mann= 3 ,-1 , 0
  3135.2     .05       0  4941.2    .033       0  5005.2     .05       0
Bank Sta=4948.1,4998.8
XS Rating Curve= 0 ,0
Exp/Cntr=0.3,0.1

Type RM Length L Ch R = 1 ,12671   ,762,762,762
BEGIN DESCRIPTION:
BRADEN BRANCH 19.5
END DESCRIPTION:
XS GIS Cut Line= 3
       2247392.2      7222380.75        2245379.      7220626.67
      2244782.55      7220243.66
#Sta/Elev= 30
  2387.2  933.72  2701.8  936.48  3141.3   930.2  3382.5   917.4  3431.8  912.47
  3460.3  912.59  3538.2  905.11  3552.4  907.17  3566.7     906  3573.3  902.65
  3580.9  904.14  3587.5  900.39  3595.2  901.91  3601.8  894.12  3623.6  902.93
  3800.2  895.05  4460.1  891.24    4892  892.29  4927.1  891.94  4969.9  886.19
  4977.5  880.81  5025.7  875.11  5043.2  875.61    5054  882.57  5061.9  884.16
  5069.2  892.13  5077.1  893.29  5228.3  900.22  5649.2  929.74  5766.2  931.95
#Mann= 3 ,-1 , 0
  2387.2     .05       0  4969.9    .033       0  5061.9     .05       0
Bank Sta=4977.5,5054
XS Rating Curve= 0 ,0
Exp/Cntr=0.3,0.1

Type RM Length L Ch R = 1 ,11909   ,753,753,753
BEGIN DESCRIPTION:
BRADEN BRANCH 19.0
END DESCRIPTION:
XS GIS Cut Line= 4
      2247222.26      7221093.23      2245507.88       7219999.5
      2245390.69      7220068.94      2244704.94      7220203.49
#Sta/Elev= 30
  2828.6  934.01  2847.1  932.39  2877.5  933.48  2998.6  923.51  3034.9   924.8
  3065.4  917.51  3138.2  909.93  3289.6  902.12  3565.5  895.93  3840.7  892.74
  4599.9  887.83  4875.6  888.88  4897.1  885.08  4906.9  879.98    4919  877.35
  4949.7  875.94  4955.5  875.99  4969.3  873.66  4984.8  873.66  4992.6  877.15
  4996.5  887.39  5001.8  887.39  5010.3  889.29  5061.2  889.49  5135.7  893.83
  5295.6  910.05  5500.9  924.62  5650.2  930.35  5672.7  932.93  5697.2  930.83
#Mann= 3 ,-1 , 0
  2828.6     .05       0  4949.7     .04       0  5001.8     .05       0
Bank Sta=4955.5,4992.6
XS Rating Curve= 0 ,0
Exp/Cntr=0.3,0.1

Type RM Length L Ch R = 1 ,11156   ,148,148,148
BEGIN DESCRIPTION:
BRADEN BRANCH 18.0
END DESCRIPTION:
XS GIS Cut Line= 3
      2246649.36      7218311.13      2245180.75      7219409.79
      2244530.95      7220106.38
#Sta/Elev= 30
  3156.8  947.36  3167.8  947.17  3263.4  949.76  3442.6  936.02  3506.9  928.89
  3663.6  932.21  3834.4  924.06  3949.1  915.47  4149.1  894.19  4213.8  891.23
  4934.8   885.8    4964  882.29  4990.9  875.78  4999.4  874.28  5019.6  871.93
  5062.9  874.88  5077.1  877.95  5091.2  876.45  5098.6  881.03  5105.4  878.04
  5112.7  881.52  5119.6  878.74  5133.7  885.64  5247.1  887.54  5303.8  890.75
  5791.8  929.62  5876.8  930.97  5897.8  928.98  5919.3  931.22  5943.5  929.13
#Mann= 4 ,-1 , 0
  3156.8     .12       0  3167.8     .05       0  4990.9     .04       0
  5062.9     .05       0
Bank Sta=4999.4,5062.9
XS Rating Curve= 0 ,0
Exp/Cntr=0.3,0.1

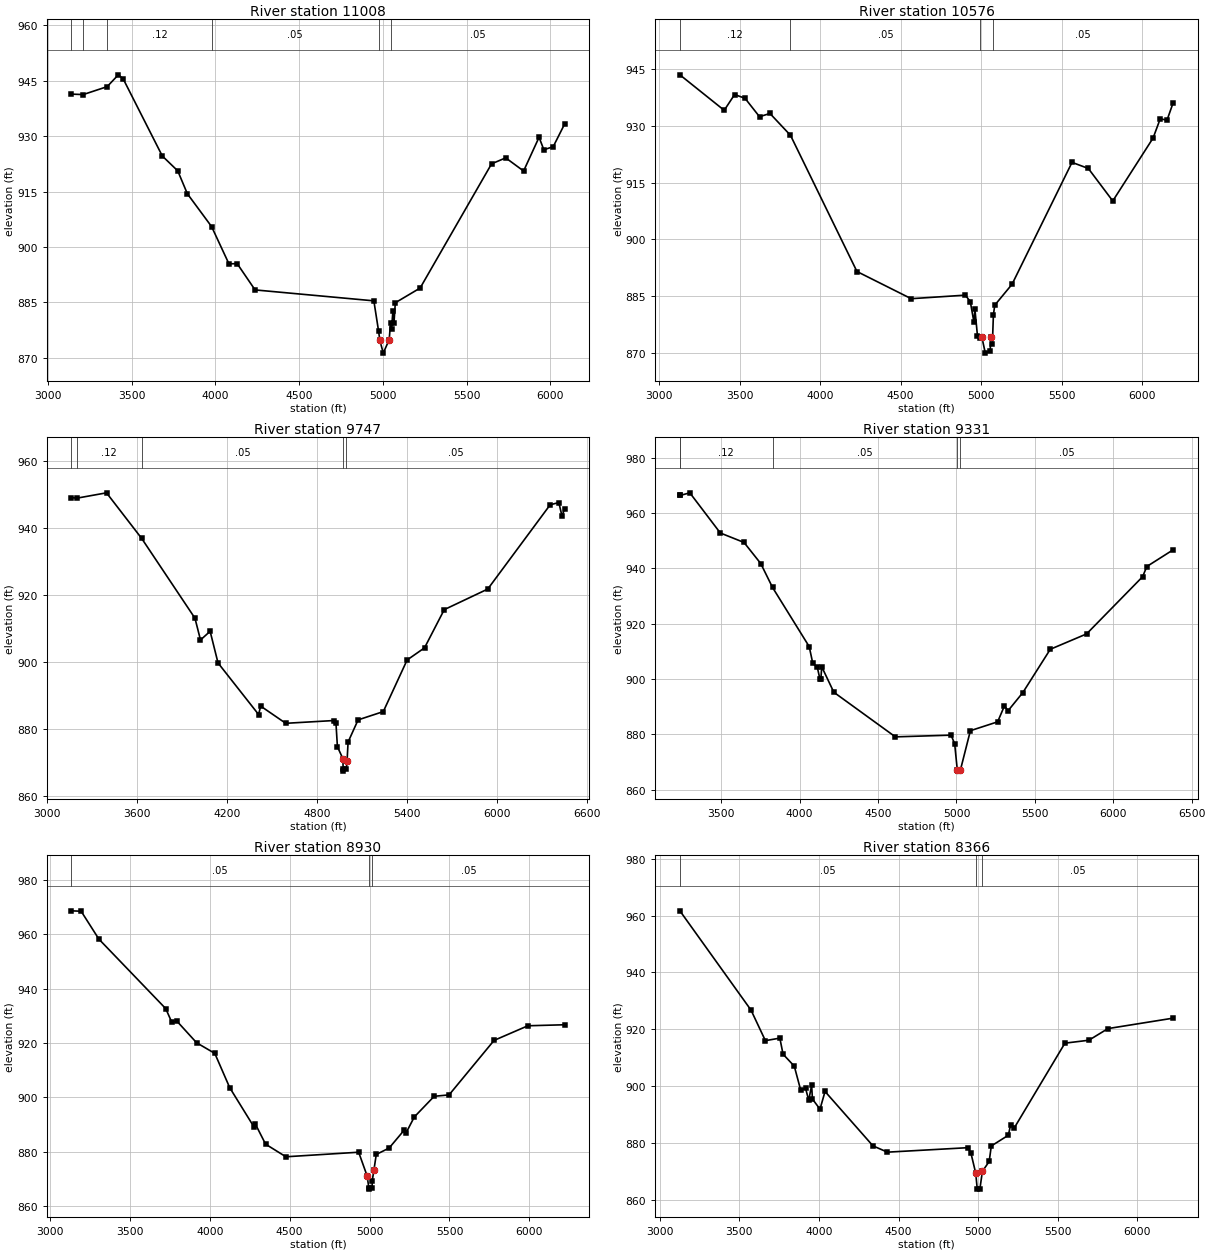
Type RM Length L Ch R = 1 ,11008   ,432,432,432
BEGIN DESCRIPTION:
BRADEN BRANCH 17.0
END DESCRIPTION:
XS GIS Cut Line= 3
       2246503.7      7218128.51      2245081.79      7219321.25
      2244244.64      7220021.14
#Sta/Elev= 30
  3139.1  941.42  3209.8  941.29  3353.2  943.44  3419.8  946.64  3448.4  945.59
  3682.6  924.66  3774.9  920.63  3832.2  914.44  3977.2  905.53  4080.6  895.46
  4130.1  895.49  4236.8  888.39  4946.5  885.43  4974.4  877.33  4982.2  874.76
  5002.7  871.27  5038.2  874.93    5046  879.31  5052.5   877.9  5060.3  882.72
  5066.8  879.47  5074.6  884.91    5223   888.9  5649.8  922.54  5734.4  924.15
  5841.1  920.59  5933.5  929.73  5962.1  926.34  6018.1  927.19  6086.2  933.32
#Mann= 6 ,-1 , 0
  3139.1     .12       0  3209.8     .05       0  3353.2     .12       0
  3977.2     .05       0  4974.4    .033       0    5046     .05       0
Bank Sta=4982.2,5038.2
XS Rating Curve= 0 ,0
Exp/Cntr=0.3,0.1

Type RM Length L Ch R = 1 ,10576   ,829,829,829
BEGIN DESCRIPTION:
BRADEN BRANCH 16.0
END DESCRIPTION:
XS GIS Cut Line= 3
      2246588.42       7218024.6        2244979.        7218960.
      2243993.42      7219647.52
#Sta/Elev= 30
  3129.1  943.56  3404.4  934.16  3468.9  938.34  3533.5  937.35  3623.7  932.46
  3688.3  933.33  3815.9  927.54  4228.7  891.46  4565.6  884.26  4902.5   885.2
  4932.8  883.42  4955.4  877.98  4961.2  881.44    4977  874.42  4993.7  873.76
  5004.1  874.13  5025.7  869.84  5054.7  870.38  5063.5     874  5069.6  872.22
    5076  879.97  5084.4  882.54  5191.7  888.08  5564.2  920.37  5665.4  918.76
  5817.2  910.15  6067.6  926.82  6112.1  931.93    6154  931.54  6192.3  936.17
#Mann= 4 ,-1 , 0
  3129.1     .12       0  3815.9     .05       0  4993.7    .033       0
    5076     .05       0
Bank Sta=5004.1,5063.5
XS Rating Curve= 0 ,0
Exp/Cntr=0.3,0.1

Type RM Length L Ch R = 1 ,9747    ,416,416,416
BEGIN DESCRIPTION:
BRADEN BRANCH 15.0
END DESCRIPTION:
XS GIS Cut Line= 3
      2246301.93      7217312.81       2244704.7      7218267.68
      2243489.46      7219014.18
#Sta/Elev= 30
  3161.9  949.01    3199  948.83  3396.3  950.42  3630.2  936.86  3985.7  913.06
  4022.6  906.57  4086.8  909.16  4139.4  899.73  4409.8  884.36  4423.6  886.87
  4590.7  881.74  4912.9  882.57  4925.3  881.79    4935  874.76  4971.2  871.22
  4973.4  867.99  4975.5  867.49  4993.8  867.99  4999.2  870.39  5006.1  876.16
  5072.8  882.76  5240.7  885.23  5399.5  900.61  5515.5  904.23  5646.9  915.61
  5936.9  921.75  6352.4  946.84  6410.4  947.53  6431.7  943.47    6449  945.69
#Mann= 5 ,-1 , 0
  3161.9     .05       0    3199     .12       0  3630.2     .05       0
  4973.4    .033       0  4993.8     .05       0
Bank Sta=4971.2,4999.2
XS Rating Curve= 0 ,0
Exp/Cntr=0.3,0.1

Type RM Length L Ch R = 1 ,9331    ,401,401,401
BEGIN DESCRIPTION:
BRADEN BRANCH 14.0
END DESCRIPTION:
XS GIS Cut Line= 3
      2246180.37       7217147.9      2244583.17      7217885.73
      2243403.27       7218614.5
#Sta/Elev= 30
  3235.9  966.34    3237  966.34  3299.3  967.29  3493.8  952.78    3645  949.36
  3751.6  941.75  3826.9   933.1  4060.8  911.73  4083.8  905.63  4112.2  904.31
  4129.6  899.87  4135.1  900.09  4140.7  904.44  4217.8  895.24  4610.4  879.12
  4965.5  879.74  4988.4  876.66  5005.1  867.24  5007.2  866.74  5025.6  867.24
  5088.7  881.35  5262.5  884.55  5305.8  890.29  5329.3  888.58  5423.3  895.12
  5598.3  910.76    5830  916.32  6187.1  936.98  6214.2  940.67  6382.1  946.71
#Mann= 5 ,-1 , 0
  3235.9     .05       0    3237     .12       0  3826.9     .05       0
  5005.1    .033       0  5025.6     .05       0
Bank Sta=5005.1,5025.6
XS Rating Curve= 0 ,0
Exp/Cntr=0.3,0.1

Type RM Length L Ch R = 1 ,8930    ,564,564,564
BEGIN DESCRIPTION:
BRADEN BRANCH 13.0
END DESCRIPTION:
XS GIS Cut Line= 3
      2246136.97      7216948.24        2244379.        7217560.
      2243222.13      7217963.23
#Sta/Elev= 30
  3134.1   968.7  3195.5  968.55  3306.7  958.27  3724.9  932.68  3762.6  927.68
  3793.7  928.14    3918  920.12  4031.8  916.21  4125.1  903.59  4275.3  889.28
  4286.1  890.13  4349.6  882.79  4476.7  878.14  4931.9  879.82  4985.2  871.04
  4995.5  866.73  4997.5  866.23    5016  866.73  5016.7  869.24  5027.2  873.19
  5042.1     879  5122.6  881.36  5217.9  888.03  5228.5  886.94  5280.1   892.8
  5404.4  900.41  5497.6  900.93  5779.1  920.99  5990.9  926.38  6220.6  926.75
#Mann= 3 ,-1 , 0
  3134.1     .05       0  4995.5    .033       0    5016     .05       0
Bank Sta=4985.2,5027.2
XS Rating Curve= 0 ,0
Exp/Cntr=0.3,0.1

Type RM Length L Ch R = 1 ,8366    ,541,541,541
BEGIN DESCRIPTION:
BRADEN BRANCH 12.0
END DESCRIPTION:
XS GIS Cut Line= 3
      2246041.53      7216818.02        2244179.        7217060.
      2243228.99      7217824.98
#Sta/Elev= 30
  3126.6  961.67  3573.4  926.78  3663.6  916.05  3754.4  916.94  3774.5   911.3
  3845.1  907.08  3885.5  898.62  3915.7  899.35  3935.9  895.09    3954  900.43
    3959  895.54  4006.5  891.97  4038.2  898.19  4339.2  879.08    4430  876.87
  4934.2  878.44  4954.4  876.54  4984.6  869.47  4994.1  863.88  5010.5  863.88
  5026.4  870.12    5069  873.61  5082.4  879.05  5189.5  882.82  5203.9  886.57
  5224.7  885.21  5544.7  915.17    5695   916.2    5815  920.29  6224.5  923.96
#Mann= 3 , 0 , 0
  3126.6     .05       0  4984.6     .04       0  5026.4     .05       0
Bank Sta=4984.6,5026.4
XS Rating Curve= 0 ,0
Exp/Cntr=0.3,0.1

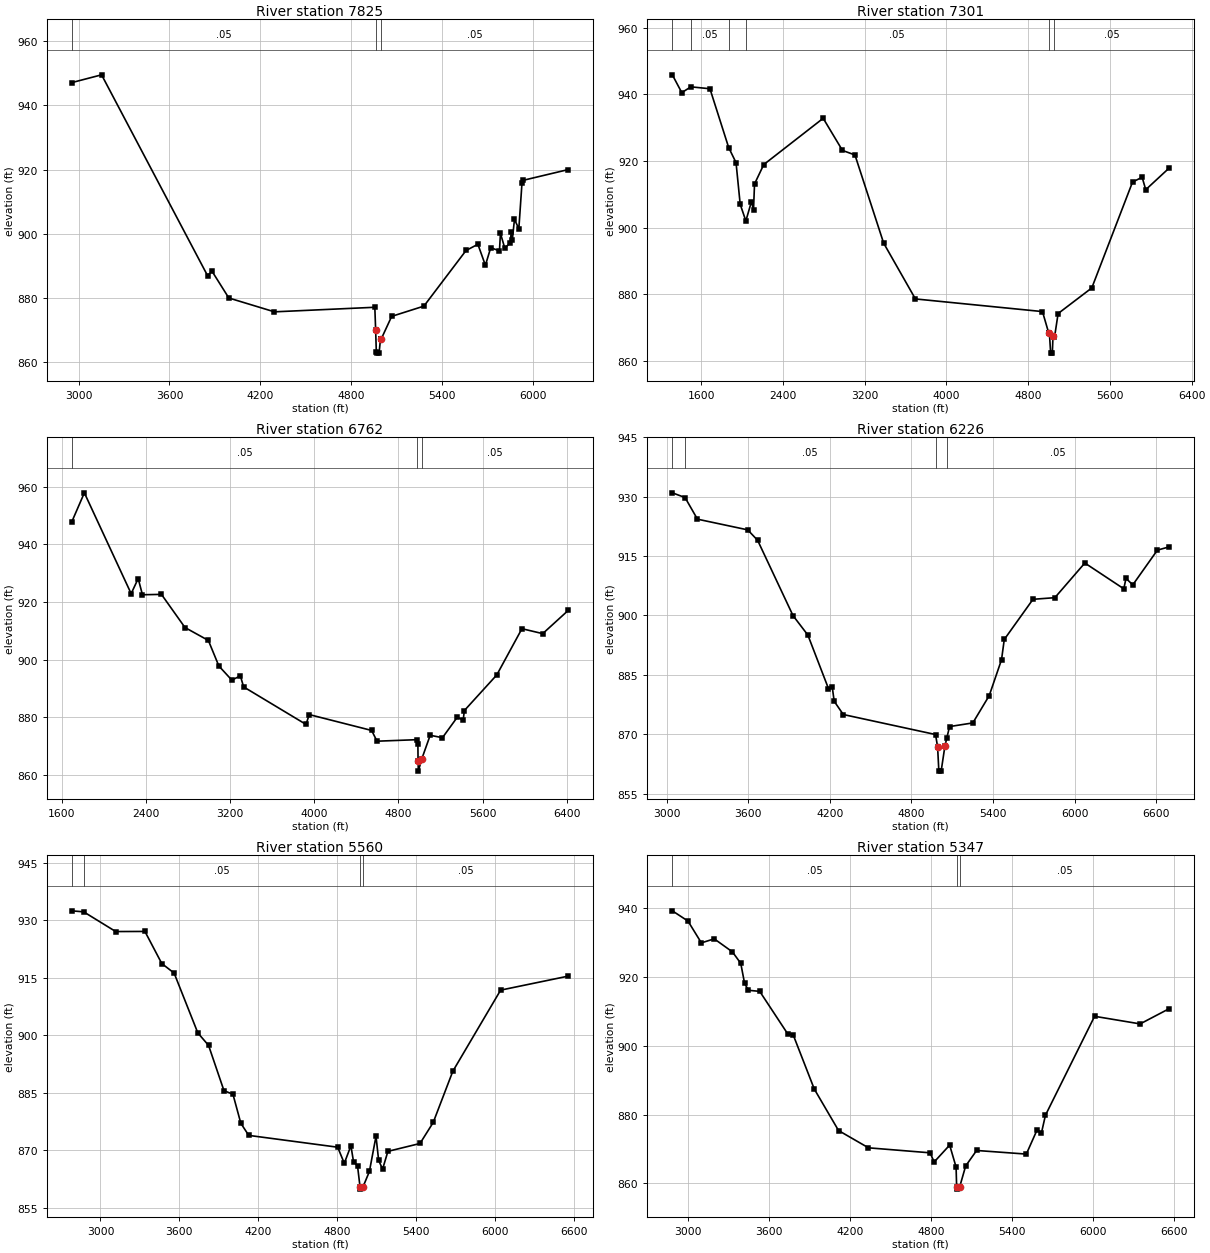
Type RM Length L Ch R = 1 ,7825    ,524,524,524
BEGIN DESCRIPTION:
BRADEN BRANCH 11.0
END DESCRIPTION:
XS GIS Cut Line= 3
      2245963.35       7216427.4        2243929.        7216610.
      2243150.87      7217573.24
#Sta/Elev= 30
  2953.4  947.07  3151.9  949.51  3851.3  887.04  3881.5  888.35  3991.9  880.06
  4293.1  875.75  4955.8  877.17 4961.36     870  4965.6   863.4  4967.6   862.9
    4984   862.9  4993.4   867.4  4999.1   867.4  5067.1  874.34  5279.8  877.53
    5558  894.84  5636.3  896.77  5685.9  890.23  5721.1  895.73  5778.7   894.7
  5785.1  900.18  5813.9  895.56  5849.1  897.19    5857   900.7  5863.4   898.1
  5877.8  904.54  5906.6  901.59  5927.4  915.86  5934.4  916.67  6234.2  920.04
#Mann= 3 ,-1 , 0
  2953.4     .05       0  4965.6     .04       0  4999.1     .05       0
Bank Sta=4961.36,4993.4
XS Rating Curve= 0 ,0
Exp/Cntr=0.3,0.1

Type RM Length L Ch R = 1 ,7301    ,539,539,539
BEGIN DESCRIPTION:
BRADEN BRANCH 10.0
END DESCRIPTION:
XS GIS Cut Line= 3
      2247201.26       7216076.7        2243529.        7216360.
      2242826.25      7217309.32
#Sta/Elev= 30
  1316.6   945.9  1409.1  940.55  1498.1  942.29  1684.7  941.72    1868  924.06
  1940.1  919.52  1980.8  907.01  2036.2  902.01  2091.2  907.83  2111.2  905.37
  2121.2  913.12  2211.5  918.94  2793.2  932.84  2981.7  923.19  3104.2  921.82
    3385  895.34  3695.9  878.57  4939.7  874.77  4999.8  868.43  5007.1  868.48
  5019.7  862.29  5036.2  862.29  5042.6  867.32  5057.2  866.99  5092.6  874.18
  5422.5  881.88    5821  913.67    5915  915.14  5950.5  911.39  6180.9  917.93
#Mann= 6 ,-1 , 0
  1316.6     .12       0  1498.1     .05       0    1868     .12       0
  2036.2     .05       0  4999.8    .033       0  5057.2     .05       0
Bank Sta=5007.1,5042.6
XS Rating Curve= 0 ,0
Exp/Cntr=0.3,0.1

Type RM Length L Ch R = 1 ,6762    ,536,536,536
BEGIN DESCRIPTION:
BRADEN BRANCH 9.0
END DESCRIPTION:
XS GIS Cut Line= 3
      2246393.94      7214791.98        2243279.        7215910.
      2242791.52      7217239.86
#Sta/Elev= 30
    1691  947.55  1813.1  957.82  2258.2  922.89    2325  928.12  2365.6  922.51
  2546.2  922.64  2770.1  911.16  2992.5  906.68  3092.3  897.83  3215.6  892.94
  3296.8  894.42  3327.6  890.59  3921.1  877.59  3951.8     881  4545.3   875.5
  4596.2  871.78  4979.3  872.31  4985.1  870.72 4986.57  865.03  4989.4  861.41
  5021.8  865.62  5101.9  873.83  5218.6  872.99  5360.5  880.13  5415.9  879.07
  5426.8  882.39  5735.4  894.74  5974.5  910.75    6172  909.04  6416.9  917.16
#Mann= 3 ,-1 , 0
    1691     .05       0  4979.3     .04       0  5021.8     .05       0
Bank Sta=4986.57,5021.8
XS Rating Curve= 0 ,0
Exp/Cntr=0.3,0.1

Type RM Length L Ch R = 1 ,6226    ,666,666,666
BEGIN DESCRIPTION:
BRADEN BRANCH 8.0
END DESCRIPTION:
XS GIS Cut Line= 3
      2244579.68      7214505.54        2242929.        7215560.
      2242748.29      7217246.82
#Sta/Elev= 30
  3041.3  930.95  3134.8  929.76    3226   924.3  3595.7   921.6  3668.5  918.97
    3929  899.95  4038.2  895.04  4189.6  881.54  4216.9  882.05  4231.9  878.32
  4298.7  874.98  4977.2  869.93  4992.4  866.83  5001.6  860.69  5018.5  860.69
  5046.1  866.99  5060.4  869.11  5080.5  871.94  5251.5  872.86  5372.1  879.75
  5462.7  888.83  5482.8  893.93    5694  904.07  5854.9  904.48  6075.4  913.23
    6362  906.72  6377.9  909.35  6428.2  907.72  6609.2  916.49  6696.5  917.31
#Mann= 4 ,-1 , 0
  3041.3     .12       0  3134.8     .05       0  4977.2    .033       0
  5060.4     .05       0
Bank Sta=4992.4,5046.1
XS Rating Curve= 0 ,0
Exp/Cntr=0.3,0.1

Type RM Length L Ch R = 1 ,5560    ,213,213,213
BEGIN DESCRIPTION:
BRADEN BRANCH 7.0
END DESCRIPTION:
XS GIS Cut Line= 4
      2244544.94      7214462.14      2243151.98      7215067.27
      2242096.71      7215169.39      2241975.54      7216363.14
#Sta/Elev= 30
  2779.8  932.42  2872.1  932.16    3116  927.02    3338  927.05  3466.2  918.69
    3560   916.2  3740.5   900.6    3822  897.36    3939  885.58  4007.4  884.63
  4067.2  877.08  4127.3  873.92  4803.8  870.84  4854.1  866.65  4904.3  871.22
  4924.4  867.04  4954.6     866    4974  860.42  4976.1  859.92  4995.3  860.42
    5045  864.52  5095.2   873.7  5115.3   867.4  5145.4  865.14  5185.6  869.76
  5429.7  871.81  5530.2  877.29  5679.3  890.63  6042.8  911.76  6558.6  915.42
#Mann= 4 ,-1 , 0
  2779.8     .12       0  2872.1     .05       0    4974     .05       0
  4995.3     .05       0
Bank Sta=4974,4995.3
XS Rating Curve= 0 ,0
Exp/Cntr=0.3,0.1

Type RM Length L Ch R = 1 ,5347    ,1068,1068,1068
BEGIN DESCRIPTION:
BRADEN BRANCH 6.5
END DESCRIPTION:
XS GIS Cut Line= 4
      2244272.64      7214257.88      2243004.47      7214885.72
      2241858.42      7215067.27      2241703.48      7216156.99
#Sta/Elev= 30
  2886.4  939.17    3002   936.2  3101.1  929.86  3196.4  931.03    3331  927.24
  3392.6  923.91  3420.7  918.13  3448.7  916.09  3532.8  915.77  3740.2   903.4
  3779.5  903.23  3936.5  887.39  4115.9  875.34  4337.4  870.32    4793  868.87
  4823.4  866.21  4937.9  871.11  4985.4  864.72  4989.6  858.82  4991.7  858.32
  5010.9  858.82  5056.2  865.04  5137.2  869.55    5505   868.5  5585.8  875.63
  5616.1  874.51  5646.4  879.78    6010  908.53    6347  906.32  6562.5  910.76
#Mann= 3 ,-1 , 0
  2886.4     .05       0  4989.6    .035       0  5010.9     .05       0
Bank Sta=4989.6,5010.9
XS Rating Curve= 0 ,0
Exp/Cntr=0.3,0.1