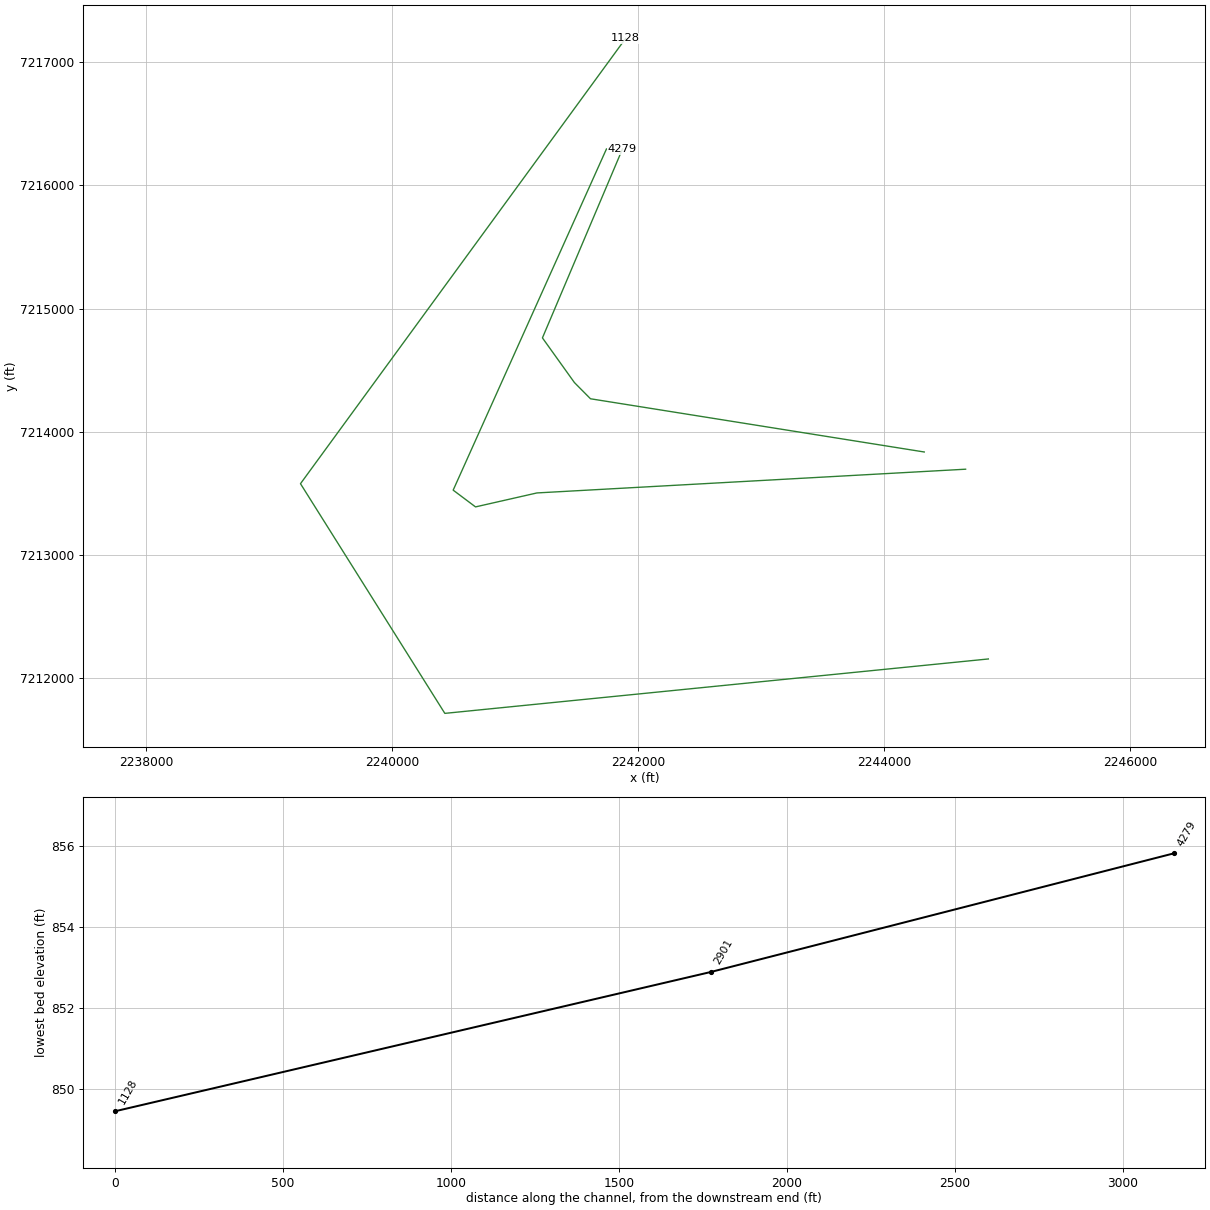
HEC-RAS study BRADEN BRANCH.prj: BRADEN BRANCH Base Level Engineering

--- BRADEN BRANCH.g01 (geometry) --- (continued)

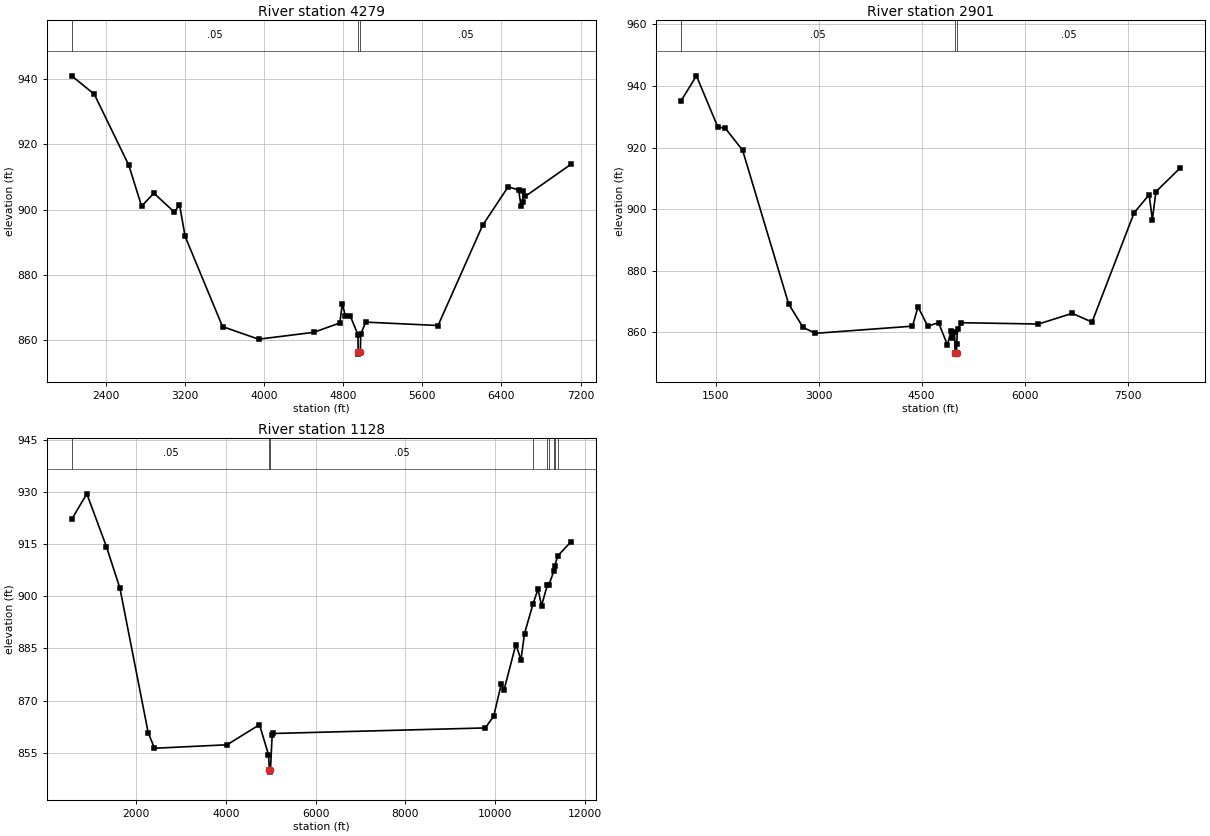
Type RM Length L Ch R = 1 ,4279    ,1378,1378,1378
BEGIN DESCRIPTION:
BRADEN BRANCH 6.0
END DESCRIPTION:
XS GIS Cut Line= 5
      2244324.91      7213834.09      2241612.75      7214266.58
      2241482.04      7214398.32      2241222.12      7214761.37
      2241872.58      7216296.44
#Sta/Elev= 30
  2057.4  940.97  2286.2  935.35  2635.1  913.61  2764.4  901.08  2888.7  905.07
  3096.3  899.24  3147.3  901.59  3204.4  891.82  3582.3  864.23  3946.9  860.38
  4503.8  862.48  4767.1  865.34  4793.1  871.25    4823  867.49  4872.5  867.54
  4950.3  861.76  4953.8  856.31  4955.9  855.81  4975.1  856.31  4978.6  861.86
  5028.4   865.6  5760.2  864.57  6210.3  895.22  6468.8  907.04  6574.8  906.02
    6598   901.1  6616.3  902.24  6621.7  905.72    6640  904.06  7103.1   913.9
#Mann= 3 ,-1 , 0
  2057.4     .05       0  4953.8     .04       0  4975.1     .05       0
Bank Sta=4953.8,4975.1
XS Rating Curve= 0 ,0
Exp/Cntr=0.3,0.1

Type RM Length L Ch R = 1 ,2901    ,1773,1773,1773
BEGIN DESCRIPTION:
BRADEN BRANCH 5.0
END DESCRIPTION:
XS GIS Cut Line= 5
      2244661.11      7213694.27       2241177.6      7213501.38
      2240678.32      7213387.91      2240496.77      7213524.07
      2241742.32      7216296.42
#Sta/Elev= 30
   999.6  935.21  1222.1  943.31  1533.3  926.69  1642.7  926.27  1894.4  919.12
  2564.1  869.21  2774.4  861.55  2954.7  859.64  4366.9  861.97    4447  868.26
  4589.6  861.95  4745.7   863.1  4874.9  855.91  4928.2   860.5  4948.5  858.17
  4979.3  859.97  4986.8  853.38    4989  852.88  5008.2  853.38  5009.1  856.28
  5023.7  861.08  5079.9  863.09  6200.4  862.66    6692  866.13    6980  863.29
    7592  898.79  7811.4   904.7  7857.7  896.53  7909.5  905.66  8266.7  913.46
#Mann= 3 ,-1 , 0
   999.6     .05       0  4986.8    .033       0  5008.2     .05       0
Bank Sta=4986.8,5008.2
XS Rating Curve= 0 ,0
Exp/Cntr=0.3,0.1

Type RM Length L Ch R = 1 ,1128    ,0,0,0
BEGIN DESCRIPTION:
BRADEN BRANCH 2.0
END DESCRIPTION:
XS GIS Cut Line= 4
       2244845.8      7212152.23        2240429.        7211710.
      2239255.98      7213576.48      2241898.74      7217195.63
#Sta/Elev= 30
   565.9  922.06   904.4  929.41  1341.3  914.23  1642.6  902.24  2271.2   860.8
  2411.9   856.3  4029.9   857.3  4751.2  863.07    4952  854.45    4974  849.94
  4976.1  849.44  4995.4  849.94  5033.6  860.12  5048.9  860.54  9783.2  862.14
  9969.3  865.54 10140.8  874.87 10197.8  872.93 10462.8  886.11 10577.9  881.75
 10655.9  889.26 10845.2  897.75 10956.3  902.04 11035.9  897.27 11162.6  903.12
   11196   903.1 11313.4  907.34 11332.3  908.77 11395.4  911.58 11690.6  915.61
#Mann= 9 ,-1 , 0
   565.9     .05       0    4974    .033       0  4995.4     .05       0
 10845.2     .12       0 11162.6     .05       0   11196     .12       0
 11313.4     .05       0 11332.3     .12       0 11395.4     .05       0
Bank Sta=4974,4995.4
XS Rating Curve= 0 ,0
Exp/Cntr=0.3,0.1

Chan Stop Cuts=-1
Use User Specified Reach Order=0
Composite Channel Slope=5