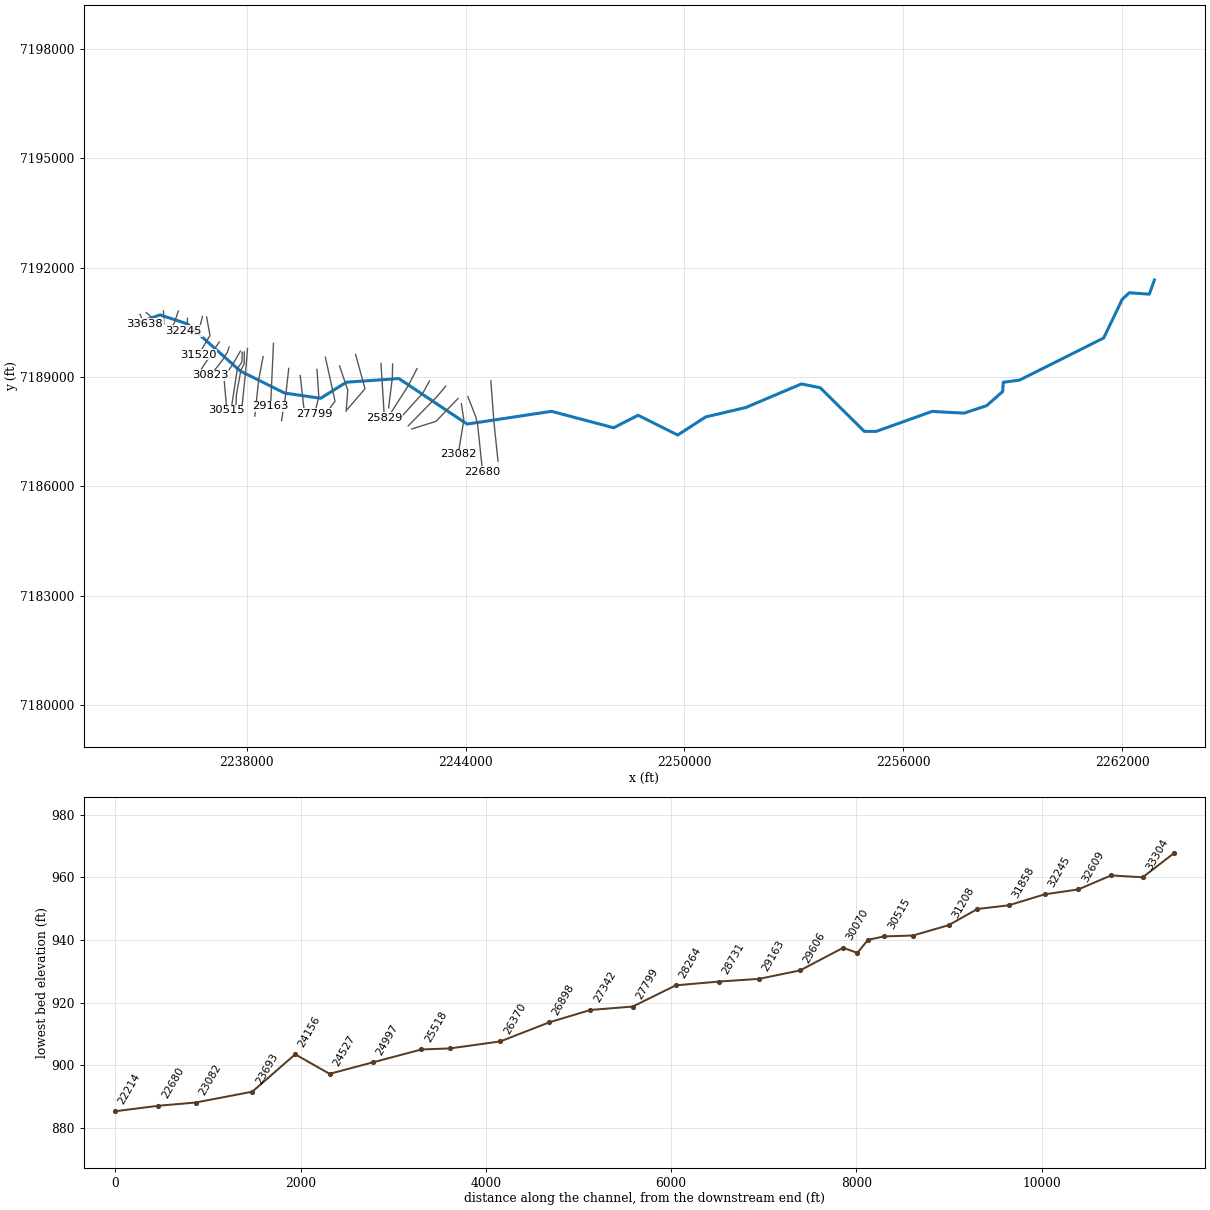
--- Cottonwood Creek.prj (project) ---

Proj Title=Cottonwood Creek Base Level Engineering
Current Plan=p01
Default Exp/Contr=0.3,0.1
English Units
Geom File=g01
Flow File=f01
Plan File=p01
Y Axis Title=Elevation
X Axis Title(PF)=Main Channel Distance
X Axis Title(XS)=Station
BEGIN DESCRIPTION:
Cottonwood Creek
END DESCRIPTION:
DSS Export Rating Curves= 0
DSS Export Rating Curve Sorted= 0
DSS Export Volume Flow Curves= 0
DXF OffsetX= 0
DXF OffsetY= 0
DXF ScaleX= 1
DXF ScaleY= 10

--- Cottonwood Creek.p01 (plan) ---

Plan Title=Multiple Run
Short Identifier=Multiple
Geom File=g01
Flow File=f01
Subcritical Flow
K Sum by GR= 0
Std Step Tol= 0.01
Critical Tol= 0.01
Num of Std Step Trials= 20
Max Error Tol= 0.3
Flow Tol Ratio= 0.001
Split Flow NTrial= 30
Split Flow Tol= 0.02
Split Flow Ratio= 0.02
Log Output Level= 0
Friction Slope Method= 1
Unsteady Friction Slope Method= 2
Unsteady Bridges Friction Slope Method= 1
Parabolic Critical Depth
Global Vel Dist=  1 , 1 , 1
Global Log Level= 0
CheckData=True
Encroach Param= -1, 0, 0, 0
BEGIN DESCRIPTION:
Multiple Run
END DESCRIPTION:

--- Cottonwood Creek.f01 (steady flow) ---

Flow Title=Multiple
Program Version=4.10
Number of Profiles= 7
Profile Names=10-year,25-year,50-year,1pct_min,100-year,1pct_plu,500-year
River Rch & RM=Cottonwood Creek,Reach-1         ,33638
     483     660     805     489     976    1947    1436
River Rch & RM=Cottonwood Creek,Reach-1         ,31520
     990    1419    1789    1120    2235    4459    3498
River Rch & RM=Cottonwood Creek,Reach-1         ,30515
    1380    2011    2564    1621    3234    6453    5165
River Rch & RM=Cottonwood Creek,Reach-1         ,26370
    1425    2081    2656    1680    3352    6689    5362
River Rch & RM=Cottonwood Creek,Reach-1         ,25829
    1861    2750    3537    2253    4496    8971    7294
River Rch & RM=Cottonwood Creek,Reach-1         ,23082
    2213    3293    4256    2723    5433   10841    8889
River Rch & RM=Cottonwood Creek,Reach-1         ,21777
    2357    3513    4547    2912    5809   11591    9522
River Rch & RM=Cottonwood Creek,Reach-1         ,20423
    2448    3649    4723    3024    6034   12039    9888
River Rch & RM=Cottonwood Creek,Reach-1         ,18562
    3019    4529    5885    3781    7544   15052   12447
River Rch & RM=Cottonwood Creek,Reach-1         ,13873
    3027    4535    5888    3778    7539   15042   12410
River Rch & RM=Cottonwood Creek,Reach-1         ,10858
    3410    5101    6617    4241    8462   16885   13891
River Rch & RM=Cottonwood Creek,Reach-1         ,4413
    4124    6211    8093    5208   10391   20732   17190
Boundary for River Rch & Prof#=Cottonwood Creek,Reach-1         , 1
Up Type= 0
Dn Type= 3
Dn Slope=0.003
Boundary for River Rch & Prof#=Cottonwood Creek,Reach-1         , 2
Up Type= 0
Dn Type= 3
Dn Slope=0.003
Boundary for River Rch & Prof#=Cottonwood Creek,Reach-1         , 3
Up Type= 0
Dn Type= 3
Dn Slope=0.003
Boundary for River Rch & Prof#=Cottonwood Creek,Reach-1         , 4
Up Type= 0
Dn Type= 3
Dn Slope=0.003
Boundary for River Rch & Prof#=Cottonwood Creek,Reach-1         , 5
Up Type= 0
Dn Type= 3
Dn Slope=0.003
Boundary for River Rch & Prof#=Cottonwood Creek,Reach-1         , 6
Up Type= 0
Dn Type= 3
Dn Slope=0.003
Boundary for River Rch & Prof#=Cottonwood Creek,Reach-1         , 7
Up Type= 0
Dn Type= 3
Dn Slope=0.003
DSS Import GetInterval= 0
DSS Import GetPeak= 0
DSS Import FillOption= 0

--- Cottonwood Creek.g01 (geometry) ---

Geom Title=Existing Conditions
Program Version=4.10

River Reach=Cottonwood Creek,Reach-1
Reach XY= 30
        2234929.        7190460.      2235628.99      7190702.47
       2236377.5      7190456.39      2237822.83      7189167.76
      2239038.66      7188561.38        2240029.      7188417.56
      2240734.86      7188857.95      2242173.48      7188957.64
      2244042.92      7187710.68      2246356.16       7188060.3
      2248059.02      7187609.94      2248728.99      7187952.47
      2249814.96      7187410.09      2250580.58      7187906.17
      2251678.01      7188163.53        2253204.      7188810.42
      2253720.66      7188706.84        2254929.        7187510.
      2255254.08       7187509.8      2256784.94      7188057.74
      2257660.73      7188010.21      2258281.42      7188215.54
      2258721.19      7188603.81      2258736.61      7188856.93
       2259177.5      7188913.62        2261489.      7190070.65
      2261995.65      7191126.67      2262189.44      7191308.96
      2262739.43      7191270.96        2262879.        7191660.

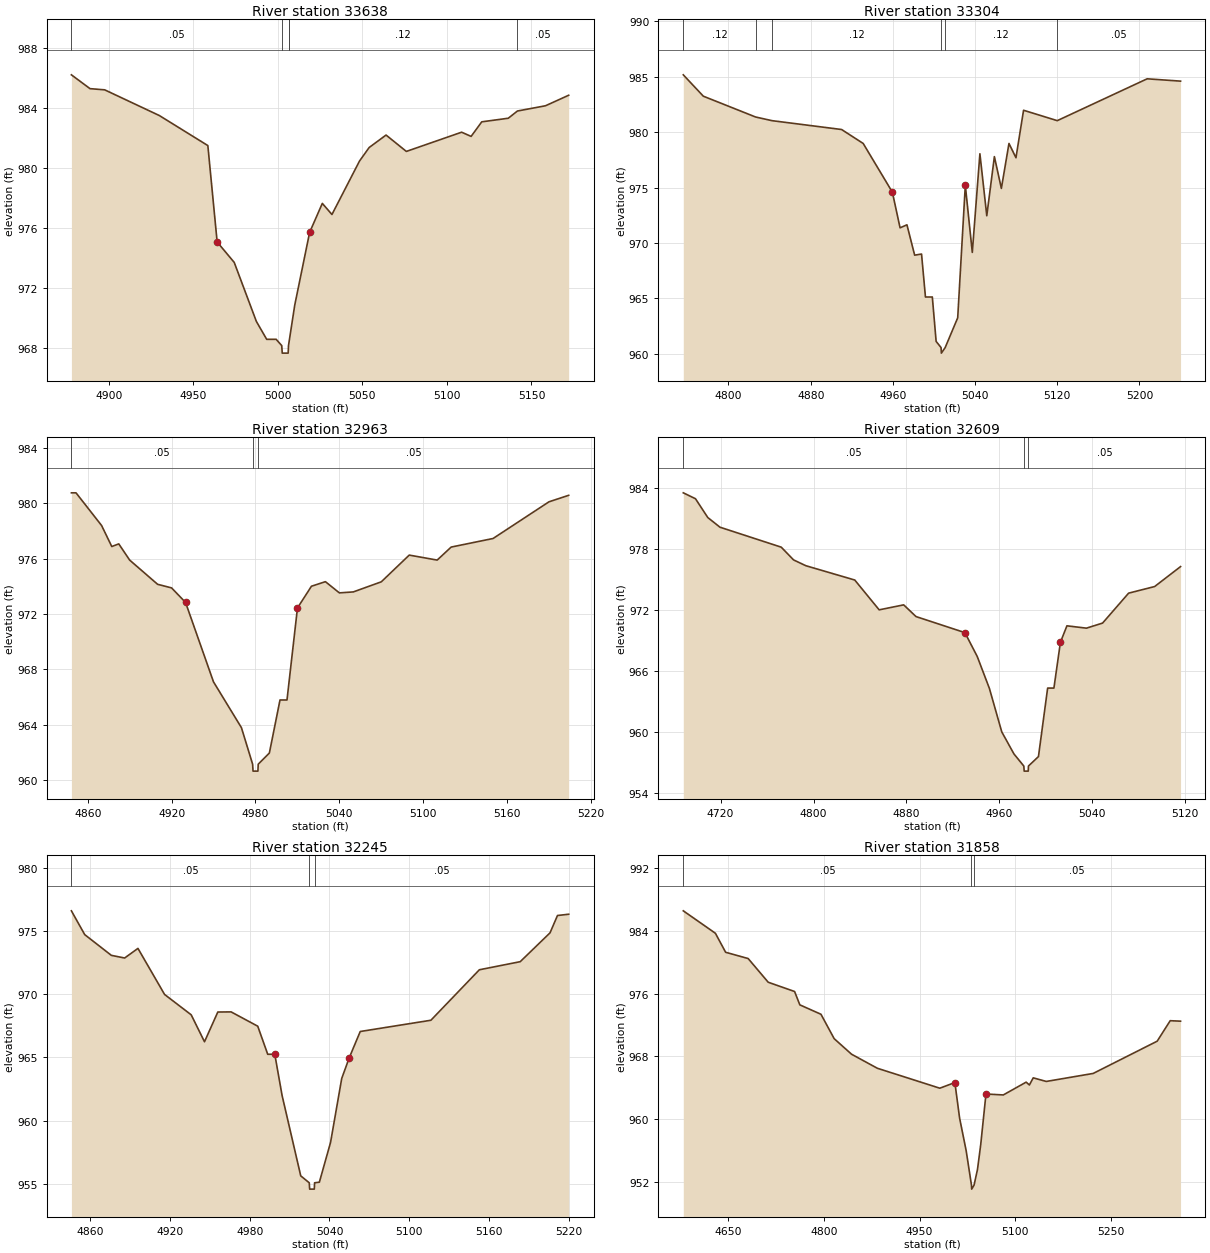
Type RM Length L Ch R = 1 ,33638   ,334,334,334
BEGIN DESCRIPTION:
Cottonwood Creek 68.0
END DESCRIPTION:
XS GIS Cut Line= 3
      2235080.78      7190717.96        2235129.        7190610.
      2235211.28      7190454.57
#Sta/Elev= 30
  4877.9  986.19  4888.9  985.27  4897.6  985.19  4929.9  983.48  4958.6  981.48
  4964.1  975.06  4974.2   973.7  4987.3  969.77  4993.4  968.58    4999  968.58
  5002.3  968.16  5002.6  967.66  5006.1  967.66  5006.3  968.16  5006.7  968.45
    5010  970.86  5018.8   975.7  5026.3  977.63    5032  976.89  5048.3  980.45
    5054  981.35    5064  982.18    5076  981.09  5108.7  982.37  5114.3  982.09
  5120.6  983.06  5136.3   983.3  5141.7  983.78  5158.3  984.13    5172  984.83
#Mann= 5 ,-1 , 0
  4877.9     .05       0  5002.3    .033       0  5006.3     .05       0
  5006.7     .12       0  5141.7     .05       0
Bank Sta=4964.1,5018.8
XS Rating Curve= 0 ,0
Exp/Cntr=0.3,0.1

Type RM Length L Ch R = 1 ,33304   ,341,341,341
BEGIN DESCRIPTION:
Cottonwood Creek 67.0
END DESCRIPTION:
XS GIS Cut Line= 3
       2235250.3      7190768.74        2235429.        7190610.
      2235594.56      7190429.45
#Sta/Elev= 30
    4756  985.18  4775.5  983.25  4826.4  981.37  4842.3  981.04  4910.1  980.24
  4931.1  978.98  4959.5  974.58    4967  971.36  4973.7  971.63  4981.2  968.89
  4987.9  968.99  4991.7  965.11  4998.4  965.11  5002.1   961.1  5006.9  960.54
  5007.2  960.04  5010.9  960.54  5023.1  963.23  5030.5   975.2  5037.3  969.14
  5044.7  978.05  5051.4  972.45  5058.8  977.79  5065.6  974.92    5073  978.98
  5079.8  977.69  5087.2  981.98    5120  981.04  5207.5  984.82    5240  984.61
#Mann= 6 ,-1 , 0
    4756     .12       0  4826.4     .05       0  4842.3     .12       0
  5006.9     .07       0  5010.9     .12       0    5120     .05       0
Bank Sta=4959.5,5030.5
XS Rating Curve= 0 ,0
Exp/Cntr=0.3,0.1

Type RM Length L Ch R = 1 ,32963   ,354,354,354
BEGIN DESCRIPTION:
Cottonwood Creek 66.0
END DESCRIPTION:
XS GIS Cut Line= 3
      2235722.71      7190811.62        2235729.        7190660.
      2235730.04      7190455.86
#Sta/Elev= 30
  4848.3  980.75  4851.6  980.75  4869.9  978.39  4877.2  976.87  4882.2  977.06
    4890  975.89    4910  974.14    4920  973.88    4930  972.83    4950  967.09
    4970  963.78    4978  961.14  4978.3  960.64  4981.8  960.64    4982  961.14
    4990  961.95  4997.6  965.78  5002.6  965.78  5010.1  972.43  5020.1     974
  5030.1  974.33  5040.1  973.52  5050.1  973.59  5070.1  974.32  5090.1  976.25
  5110.1  975.89  5120.1  976.83  5150.1  977.45  5190.1   980.1  5204.2  980.57
#Mann= 3 ,-1 , 0
  4848.3     .05       0    4978    .033       0    4982     .05       0
Bank Sta=4930,5010.1
XS Rating Curve= 0 ,0
Exp/Cntr=0.3,0.1

Type RM Length L Ch R = 1 ,32609   ,364,364,364
BEGIN DESCRIPTION:
Cottonwood Creek 65.0
END DESCRIPTION:
XS GIS Cut Line= 3
        2236129.      7190809.99        2236029.        7190510.
      2235979.01      7190410.02
#Sta/Elev= 30
  4687.9  983.52  4698.4  982.94    4709  981.09  4719.5  980.14  4772.2  978.18
  4782.8  976.93  4793.3  976.36  4835.5  974.95  4856.5  972.02  4877.6  972.51
  4888.2  971.36  4930.3  969.78  4940.9  967.44  4951.4  964.29    4962  960.03
  4972.5  957.86    4981  956.67  4981.3  956.17  4984.8  956.17    4985  956.67
  4993.6   957.6  5001.5  964.33  5006.9  964.33  5012.5  968.83  5018.1  970.45
  5034.9  970.22  5048.8  970.72  5071.2  973.66  5093.6  974.31  5115.9  976.27
#Mann= 3 ,-1 , 0
  4687.9     .05       0    4981    .033       0    4985     .05       0
Bank Sta=4930.3,5012.5
XS Rating Curve= 0 ,0
Exp/Cntr=0.3,0.1

Type RM Length L Ch R = 1 ,32245   ,387,387,387
BEGIN DESCRIPTION:
Cottonwood Creek 64.0
END DESCRIPTION:
XS GIS Cut Line= 3
        2236379.      7190609.96        2236379.        7190460.
      2236278.99      7190259.97
#Sta/Elev= 30
  4846.1  976.59  4856.1  974.71  4876.1  973.07  4886.1  972.86  4896.1  973.62
  4916.1  969.98  4936.1  968.37  4946.1  966.24  4956.1  968.59  4966.1   968.6
  4986.1  967.47  4993.6  965.25  4998.9  965.25  5004.4  961.99  5018.4  955.64
  5024.8  955.09  5025.1  954.59  5028.6  954.59  5028.8  955.09  5032.4  955.14
  5040.8  958.28  5049.2  963.34  5054.8  964.96  5063.1  967.05  5116.2  967.94
  5152.6  971.93  5183.3  972.57  5205.7  974.85  5211.3  976.22  5219.7  976.32
#Mann= 3 ,-1 , 0
  4846.1     .05       0  5024.8    .033       0  5028.8     .05       0
Bank Sta=4998.9,5054.8
XS Rating Curve= 0 ,0
Exp/Cntr=0.3,0.1

Type RM Length L Ch R = 1 ,31858   ,338,338,338
BEGIN DESCRIPTION:
Cottonwood Creek 63.0
END DESCRIPTION:
XS GIS Cut Line= 3
      2236790.85      7190658.65      2236660.67      7190159.76
      2236403.16      7190213.71
#Sta/Elev= 30
  4580.1  986.56  4630.4   983.7  4646.4  981.28  4681.7  980.48  4713.1  977.46
  4754.4  976.28  4762.6  974.58  4795.7  973.38  4816.4  970.27  4843.6  968.29
    4884   966.5  4981.8  963.96  5005.4  964.68  5012.8  960.15  5023.1  955.99
  5031.4   951.6  5031.7   951.1  5035.4   951.6  5040.8   953.6  5045.9  956.79
  5054.1  963.22  5081.2   963.1    5117  964.73  5122.1  964.37  5128.1  965.28
  5148.5  964.82    5222  965.84  5322.2  969.95  5342.6  972.56  5358.8   972.5
#Mann= 3 ,-1 , 0
  4580.1     .05       0  5031.4    .033       0  5035.4     .05       0
Bank Sta=5005.4,5054.1
XS Rating Curve= 0 ,0
Exp/Cntr=0.3,0.1

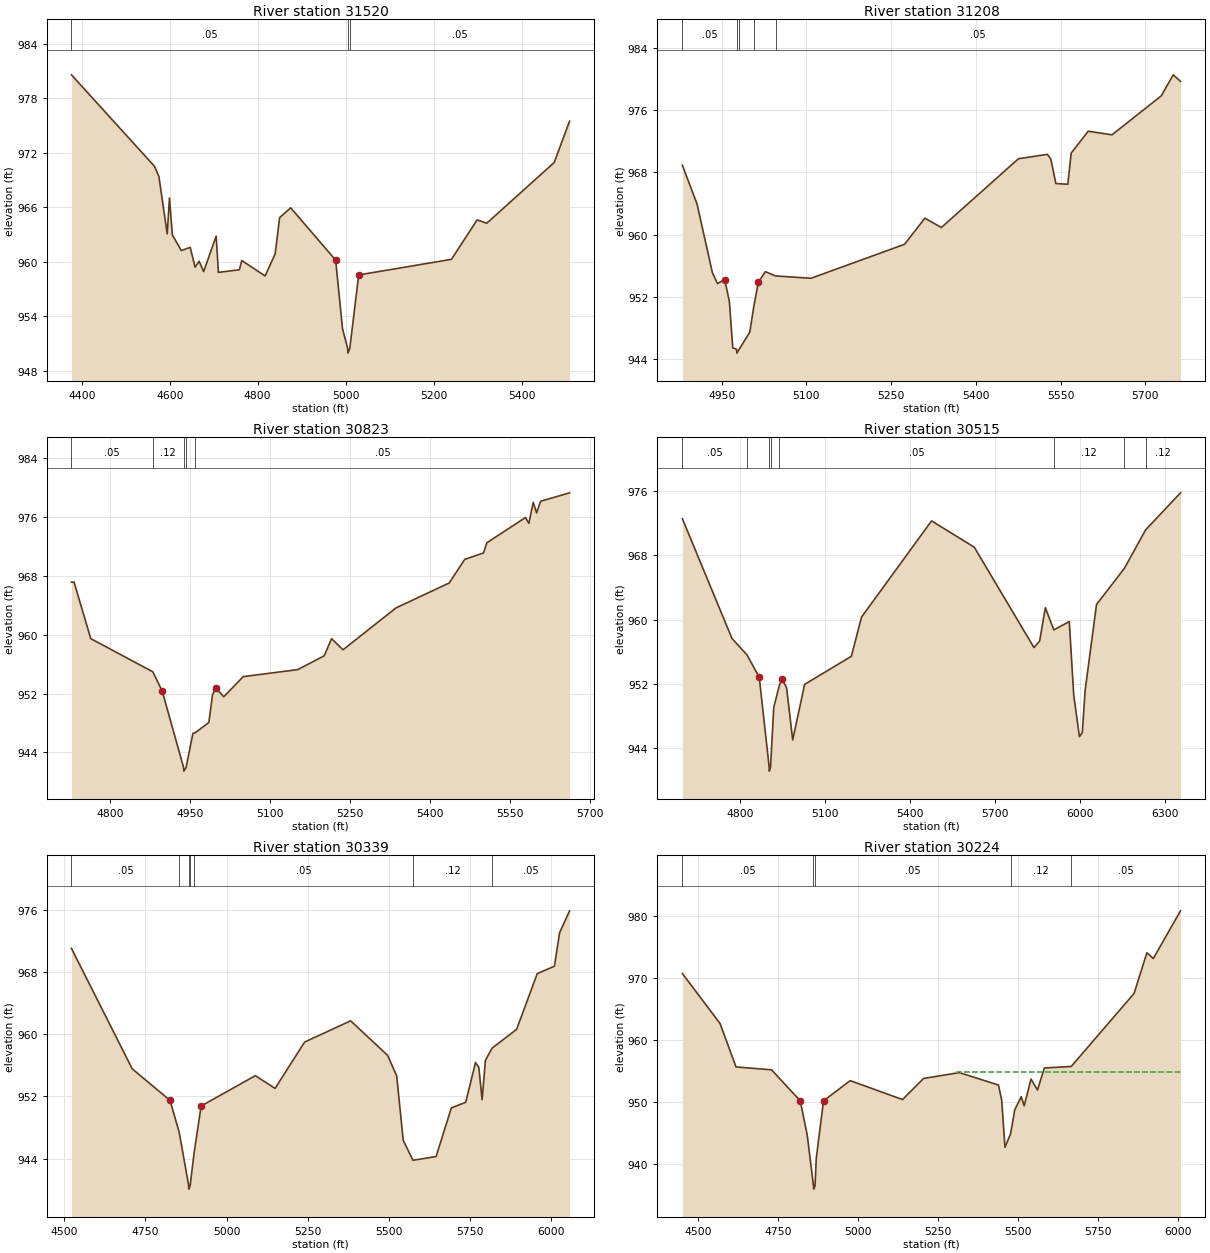
Type RM Length L Ch R = 1 ,31520   ,312,312,312
BEGIN DESCRIPTION:
Cottonwood Creek 62.0
END DESCRIPTION:
XS GIS Cut Line= 3
      2236904.04      7190645.67      2236997.26      7190137.78
      2236678.99      7189609.99
#Sta/Elev= 30
  4376.6   980.6  4565.4  970.52  4575.5  969.39  4594.4  963.07  4599.5  967.03
    4606  962.96  4626.4  961.23  4646.7  961.58  4657.7   959.4    4667  960.05
  4677.2  958.91  4705.7  962.82  4710.8  958.82  4758.5  959.11  4763.9  960.13
    4817  958.43  4839.9  960.87    4850  964.86  4875.2  965.94  4977.4  960.17
  4992.9  952.64  5004.8  950.42  5005.3  949.92  5009.5  950.42  5029.8  958.54
  5240.7  960.26  5299.1  964.61    5321  964.24  5474.3  970.93  5509.3  975.49
#Mann= 3 ,-1 , 0
  4376.6     .05       0  5004.8    .033       0  5009.5     .05       0
Bank Sta=4977.4,5029.8
XS Rating Curve= 0 ,0
Exp/Cntr=0.3,0.1

Type RM Length L Ch R = 1 ,31208   ,385,385,385
BEGIN DESCRIPTION:
Cottonwood Creek 61.1
END DESCRIPTION:
XS GIS Cut Line= 2
      2237251.13      7189962.46       2236765.2      7189226.75
#Sta/Elev= 30
  4880.5  968.91  4906.5  963.91  4933.6  955.09  4942.6  953.69  4955.4   954.2
  4963.7  951.37  4969.7  945.41  4976.4  945.24  4976.9  944.74  4981.1  945.24
  4999.8  947.44  5006.8   950.7  5014.9  953.85  5027.3  955.22  5045.5  954.67
  5108.2  954.37  5273.7  958.74  5309.8   962.1  5338.9   960.9  5475.4  969.75
  5526.6  970.31  5532.6   969.7  5541.6  966.56  5562.7  966.46  5568.7  970.47
  5598.8  973.29  5640.9  972.82  5728.2  977.84  5749.3  980.54  5762.2   979.7
#Mann= 5 ,-1 , 0
  4880.5     .05       0  4976.4    .033       0  4981.1     .05       0
  5006.8     .12       0  5045.5     .05       0
Bank Sta=4955.4,5014.9
XS Rating Curve= 0 ,0
Exp/Cntr=0.3,0.1

Type RM Length L Ch R = 1 ,30823   ,308,308,308
BEGIN DESCRIPTION:
Cottonwood Creek 61.0
END DESCRIPTION:
XS GIS Cut Line= 4
      2237520.92      7189824.38      2237470.92      7189674.39
      2237344.19      7189471.87      2237015.45      7189047.01
#Sta/Elev= 30
  4728.1  967.17    4733  967.17  4764.3  959.48  4880.6  954.97  4898.3  952.36
  4938.4  941.95  4938.9  941.45  4943.1  941.95    4956   946.6  4960.3  946.68
  4985.8  948.07  4992.6  951.81  4998.5  952.77  5013.8  951.57  5050.3  954.31
  5152.3  955.26  5202.1  957.14    5216  959.48  5237.4  957.96    5337  963.67
  5436.6  967.05  5465.6  970.26  5500.9  971.14  5507.2  972.52  5579.6  975.96
    5586  975.16  5594.1  978.03  5600.5  976.59  5607.9  978.17  5662.3  979.32
#Mann= 5 ,-1 , 0
  4728.1     .05       0  4880.6     .12       0  4938.4    .033       0
  4943.1     .12       0  4960.3     .05       0
Bank Sta=4898.3,4998.5
XS Rating Curve= 0 ,0
Exp/Cntr=0.3,0.1

Type RM Length L Ch R = 1 ,30515   ,176,176,176
BEGIN DESCRIPTION:
Cottonwood Creek 60.0
END DESCRIPTION:
XS GIS Cut Line= 4
      2237828.99      7189709.98        2237629.        7189360.
       2237378.6      7188988.31      2237458.78      7188084.62
#Sta/Elev= 30
  4596.9  972.56  4771.8  957.68  4825.3  955.61  4868.3  952.83  4903.3  941.67
  4903.8  941.17  4908.1  941.67  4919.4  949.09  4939.6  951.89  4948.9   952.6
  4964.7  951.55  4986.3  945.05  5028.5  951.96  5193.4  955.45  5229.4  960.33
  5476.6  972.29  5627.3  969.02    5838  956.54  5858.1  957.35  5878.2   961.5
  5908.1  958.73  5962.7  959.77  5978.5   950.6  5998.6  945.45  6008.7  945.96
  6018.7  951.21  6058.9  961.89  6157.3  966.39    6232  971.16  6355.4  975.78
#Mann= 8 ,-1 , 0
  4596.9     .05       0  4825.3     .12       0  4903.3    .033       0
  4908.1     .12       0  4939.6     .05       0  5908.1     .12       0
  6157.3     .05       0    6232     .12       0
#XS Ineff= 2 , 0
       0                  5476.6       0  972.29
Permanent Ineff=
       F       F
Bank Sta=4868.3,4948.9
XS Rating Curve= 0 ,0
Exp/Cntr=0.3,0.1

Type RM Length L Ch R = 1 ,30339   ,115,115,115
BEGIN DESCRIPTION:
Cottonwood Creek 59.2
END DESCRIPTION:
XS GIS Cut Line= 4
      2237880.11      7189676.91      2237871.07      7189410.64
      2237746.26      7189225.18      2237589.51      7188193.89
#Sta/Elev= 30
  4522.6  971.03  4709.6  955.55    4826  951.49  4854.3  947.38  4883.3  940.58
  4883.9  940.08  4888.1  940.58  4900.1  944.73  4921.7  950.76  5088.6  954.67
  5149.3  953.03  5240.3  958.99  5381.9  961.72  5495.8  957.27  5523.6  954.65
  5543.8  946.34  5573.8  943.79  5644.9  944.27  5691.8  950.52    5736  951.24
  5766.3  956.36  5776.4  955.73  5786.5  951.58  5796.7  956.64  5817.3  958.21
  5892.7  960.62  5956.3  967.79  6009.1  968.74    6025  973.04  6055.7  975.86
#Mann= 7 ,-1 , 0
  4522.6     .05       0  4854.3     .12       0  4883.3    .033       0
  4888.1     .12       0  4900.1     .05       0  5573.8     .12       0
  5817.3     .05       0
#XS Ineff= 2 , 0
       0                  5381.9       0  961.72
Permanent Ineff=
       F       F
Bank Sta=4826,4921.7
XS Rating Curve= 0 ,0
Exp/Cntr=0.3,0.1

Type RM Length L Ch R = 1 ,30224   ,154,154,154
BEGIN DESCRIPTION:
Cottonwood Creek 59.1
END DESCRIPTION:
XS GIS Cut Line= 5
      2237936.12      7189687.58      2237933.59      7189360.52
      2237845.65      7189194.85      2237721.62      7188526.29
      2237705.04      7188165.07
#Sta/Elev= 30
  4450.9  970.71  4568.5  962.65  4618.5  955.63  4729.4  955.17    4819  950.18
    4841  944.61  4860.5  936.41  4861.1  935.91  4865.3  936.41  4869.1  940.84
  4891.8  950.16  4975.1  953.42  5138.7  950.37  5204.4  953.77  5316.3  954.72
  5438.3  952.71  5448.5  950.27  5458.7  942.67  5476.2  944.83  5489.2  948.71
  5509.5  950.84  5518.7  949.36    5540  953.67  5560.4  951.91  5581.7  955.46
  5665.7  955.71    5862  967.49  5902.1  974.07  5922.1  973.13  6007.1  980.83
#Mann= 5 ,-1 , 0
  4450.9     .05       0  4860.5    .033       0  4865.3     .05       0
  5476.2     .12       0  5665.7     .05       0
#XS Ineff= 2 , 0
       0                  5307.4       0  954.78
Permanent Ineff=
       F       F
Bank Sta=4819,4891.8
XS Rating Curve= 0 ,0
Exp/Cntr=0.3,0.1

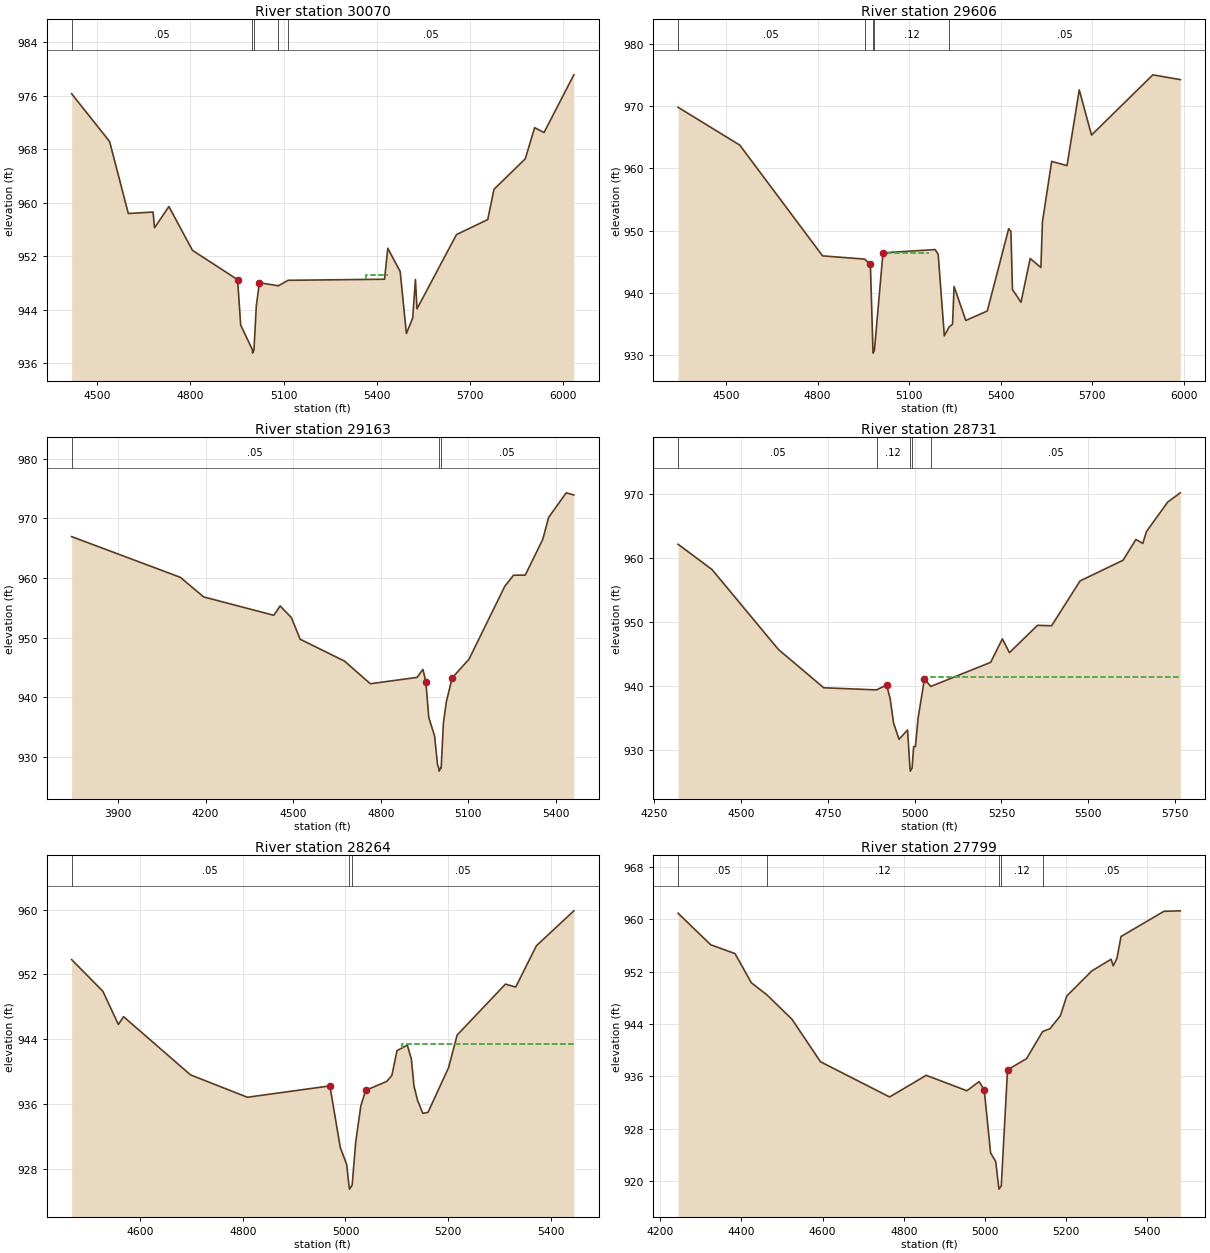
Type RM Length L Ch R = 1 ,30070   ,464,464,464
BEGIN DESCRIPTION:
Cottonwood Creek 59.0
END DESCRIPTION:
XS GIS Cut Line= 3
      2238025.59      7189781.59        2237979.        7189210.
      2237872.09      7188174.69
#Sta/Elev= 30
    4419  976.32    4541  969.18  4601.2  958.41  4680.6  958.63  4685.6  956.28
  4731.6  959.46  4807.4   952.9  4952.4  948.52  4962.4  941.73  5000.1  938.03
  5000.7  937.53    5005  938.03  5012.6  944.59  5022.6  948.06  5083.6   947.6
  5114.8  948.42  5424.8  948.58  5435.2  953.21    5475  949.74  5495.1  940.46
  5515.2  942.76  5524.1  948.54  5529.1  944.15    5656  955.26  5756.5   957.5
  5776.6  962.03  5877.2  966.59  5907.3  971.25  5937.5  970.52  6033.3  979.15
#Mann= 5 ,-1 , 0
    4419     .05       0  5000.1    .033       0    5005     .05       0
  5083.6     .12       0  5114.8     .05       0
#XS Ineff= 3 ,-1
                          5364.5  5435.2  949.26  5435.2    5700  953.21
Permanent Ineff=
       F       F       F
Bank Sta=4952.4,5022.6
XS Rating Curve= 0 ,0
Exp/Cntr=0.3,0.1

Type RM Length L Ch R = 1 ,29606   ,443,443,443
BEGIN DESCRIPTION:
Cottonwood Creek 58.0
END DESCRIPTION:
XS GIS Cut Line= 3
      2238452.32      7189560.05        2238329.        7188910.
      2238226.36      7187930.51
#Sta/Elev= 30
  4342.8  969.82  4544.9  963.75  4816.4  945.95  4953.9  945.43  4973.2  944.59
  4981.6  930.82  4982.2  930.32  4986.5  930.82  5014.5  946.44  5185.4  946.96
  5195.5  946.19  5215.6   933.1  5231.5  934.54  5242.5  934.95  5247.6  941.03
    5286  935.57  5356.4  937.09  5426.7  950.32    5434  949.87    5439  940.55
    5467   938.5  5497.1  945.53  5532.2  944.08  5537.3   951.4  5567.5  961.13
  5617.8  960.45    5658  972.63  5698.2  965.36  5899.3  975.04  5989.3  974.27
#Mann= 5 ,-1 , 0
  4342.8     .05       0  4953.9     .12       0  4981.6     .07       0
  4986.5     .12       0  5231.5     .05       0
#XS Ineff= 2 ,-1
  5024.6  5165.3  946.48  5165.3    5700  946.77
Permanent Ineff=
       F       F
Bank Sta=4973.2,5014.5
XS Rating Curve= 0 ,0
Exp/Cntr=0.3,0.1

Type RM Length L Ch R = 1 ,29163   ,432,432,432
BEGIN DESCRIPTION:
Cottonwood Creek 57.0
END DESCRIPTION:
XS GIS Cut Line= 3
      2238736.15      7189921.73        2238679.        7188660.
      2238656.29      7188203.79
#Sta/Elev= 30
  3741.4  966.93  4113.5  960.11  4193.6  956.82  4433.8  953.74  4455.4  955.31
  4493.9  953.35  4523.9  949.73    4676  946.06  4764.2  942.27  4924.3  943.33
  4944.4  944.67  4954.4  942.63  4964.4  936.62  4984.4  933.51  4994.4  928.68
  4998.9  928.12  4999.9  927.62    5005  928.12  5006.9  928.12  5014.4  935.62
  5024.5  939.23  5044.5  943.25  5102.3  946.39  5224.7   958.6  5254.7  960.46
  5294.8  960.48  5354.9  966.48  5374.9  970.15    5435  974.27  5461.2  973.91
#Mann= 3 ,-1 , 0
  3741.4     .05       0  4998.9    .033       0    5005     .05       0
Bank Sta=4954.4,5044.5
XS Rating Curve= 0 ,0
Exp/Cntr=0.3,0.1

Type RM Length L Ch R = 1 ,28731   ,467,467,467
BEGIN DESCRIPTION:
Cottonwood Creek 56.0
END DESCRIPTION:
XS GIS Cut Line= 3
      2239155.91      7189237.07        2239079.        7188560.
      2238957.58      7187803.71
#Sta/Elev= 30
  4318.2  962.17  4415.9  958.23  4607.1  945.76    4738  939.77    4890  939.44
  4919.1   940.2  4929.2  938.11  4939.2  934.27  4954.8  931.73  4979.5  933.18
  4986.5  927.26  4987.5  926.76  4992.6  927.26  4997.1  930.59  5002.2  930.59
  5009.8  935.01  5028.1  941.12  5046.5  939.98  5218.9  943.74  5252.8   947.4
  5273.1  945.26  5354.1  949.52  5394.6  949.45  5476.7  956.45  5600.6  959.68
  5637.7  962.92  5657.5   962.3  5668.1  964.16  5729.5  968.77  5765.6   970.2
#Mann= 5 ,-1 , 0
  4318.2     .05       0    4890     .12       0  4986.5     .07       0
  4992.6     .12       0  5046.5     .05       0
#XS Ineff= 2 , 0
       0                  5033.1       0   941.5
Permanent Ineff=
       F       F
Bank Sta=4919.1,5028.1
XS Rating Curve= 0 ,0
Exp/Cntr=0.3,0.1

Type RM Length L Ch R = 1 ,28264   ,465,465,465
BEGIN DESCRIPTION:
Cottonwood Creek 55.0
END DESCRIPTION:
XS GIS Cut Line= 3
      2239469.87      7189040.54        2239529.        7188510.
      2239579.78      7188067.43
#Sta/Elev= 30
  4466.1  953.83    4527  949.93  4557.2  945.84  4567.3   946.8  4698.1  939.62
  4808.8  936.87  4969.7  938.27  4989.9   930.7  5002.4  928.59  5006.8  926.05
  5007.9  925.55  5013.1  926.05  5020.1   931.4  5030.1  935.83  5039.5  937.72
  5080.5  938.82  5090.5  939.55  5100.6  942.62  5120.7  943.29  5128.6  941.57
  5133.7  938.24  5140.8  936.47  5150.9  934.89    5161  935.01  5201.2  940.53
  5217.8  944.53    5312  950.81  5332.1  950.45  5372.4  955.54  5445.4  959.84
#Mann= 3 ,-1 , 0
  4466.1     .05       0  5006.8    .033       0  5013.1     .05       0
#XS Ineff= 2 , 0
       0                  5110.6       0  943.49
Permanent Ineff=
       F       F
Bank Sta=4969.7,5039.5
XS Rating Curve= 0 ,0
Exp/Cntr=0.3,0.1

Type RM Length L Ch R = 1 ,27799   ,457,457,457
BEGIN DESCRIPTION:
Cottonwood Creek 54.0
END DESCRIPTION:
XS GIS Cut Line= 3
        2239929.      7189209.97        2239979.        7188460.
      2239863.85      7187988.19
#Sta/Elev= 30
    4244  960.93  4324.2  956.12  4384.3  954.76  4424.4  950.31    4463  948.45
  4524.6  944.73  4594.8  938.24  4765.1  932.86  4855.3  936.17  4955.5  933.81
  4985.6  935.21  4998.2  933.95  5013.9  924.31  5026.5  923.01  5033.5  919.28
  5034.6  918.78  5040.2  919.28  5055.6  937.01  5102.4  938.71  5142.1  942.86
  5160.3   943.3  5185.8  945.27  5201.5  948.28  5263.3  952.12  5310.8   953.9
  5315.9   952.9    5325     954  5335.3  957.38    5441  961.23  5481.3   961.3
#Mann= 5 ,-1 , 0
    4244     .05       0    4463     .12       0  5033.5     .07       0
  5040.2     .12       0  5142.1     .05       0
Bank Sta=4998.2,5055.6
XS Rating Curve= 0 ,0
Exp/Cntr=0.3,0.1

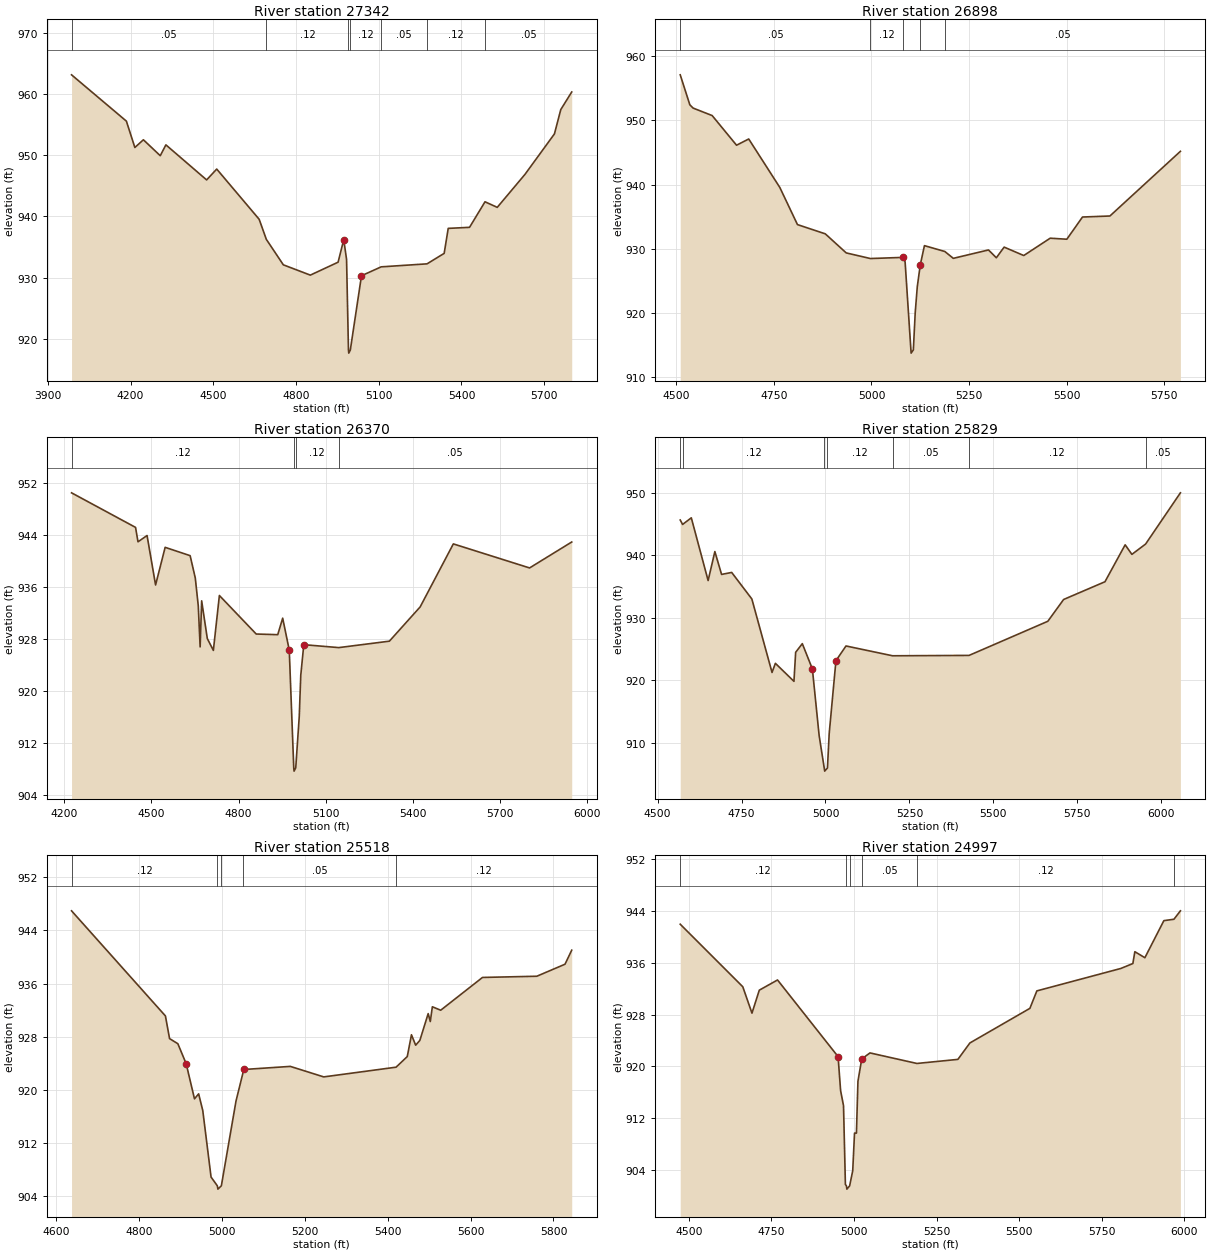
Type RM Length L Ch R = 1 ,27342   ,444,444,444
BEGIN DESCRIPTION:
Cottonwood Creek 53.0
END DESCRIPTION:
XS GIS Cut Line= 3
       2240159.2      7189544.23      2240423.63      7188338.68
      2240083.34      7187869.26
#Sta/Elev= 30
  3985.9  963.11  4184.8  955.55  4215.5  951.25  4246.5  952.51  4307.6  949.91
  4328.1  951.68  4475.8  945.96  4512.4  947.73  4666.4  939.53  4692.3  936.26
    4754   932.1  4851.9  930.42  4952.6  932.53  4973.1  936.22  4983.3  932.98
  4990.2  918.19  4991.3  917.69  4996.9  918.19  5037.4  930.32  5108.8  931.77
  5275.1  932.26  5337.3  933.97    5352  938.05  5429.3  938.22  5485.4  942.39
  5529.8  941.48  5630.3  946.86  5737.2  953.47  5760.2  957.44  5799.9  960.31
#Mann= 7 ,-1 , 0
  3985.9     .05       0  4692.3     .12       0  4990.2     .07       0
  4996.9     .12       0  5108.8     .05       0  5275.1     .12       0
  5485.4     .05       0
Bank Sta=4973.1,5037.4
XS Rating Curve= 0 ,0
Exp/Cntr=0.3,0.1

Type RM Length L Ch R = 1 ,26898   ,528,528,528
BEGIN DESCRIPTION:
Cottonwood Creek 52.0
END DESCRIPTION:
XS GIS Cut Line= 3
      2240546.94      7189301.12      2240773.29      7188644.67
        2240729.      7188060.02
#Sta/Elev= 30
  4510.3  957.11  4534.9  952.44  4543.2  951.93  4592.1  950.76  4654.5  946.14
  4685.7  947.11  4765.3  939.56  4810.5  933.77  4881.7  932.33  4935.3  929.36
  4997.3  928.48  5080.8  928.66  5086.1  927.95  5101.5  913.74  5107.2  914.24
    5112  920.05  5117.3   924.1    5125  927.52  5135.6  930.49  5187.8  929.58
  5209.5  928.51  5299.6  929.82  5319.7   928.6  5339.7  930.26  5389.9  928.95
  5457.6  931.65  5500.2  931.49  5540.3  934.95  5610.5  935.11    5791  945.19
#Mann= 5 ,-1 , 0
  4510.3     .05       0  4997.3     .12       0  5080.8     .07       0
    5125     .12       0  5187.8     .05       0
Bank Sta=5080.8,5125
XS Rating Curve= 0 ,0
Exp/Cntr=0.3,0.1

Type RM Length L Ch R = 1 ,26370   ,541,541,541
BEGIN DESCRIPTION:
Cottonwood Creek 51.0
END DESCRIPTION:
XS GIS Cut Line= 3
      2240986.53      7189620.46       2241245.1      7188678.99
      2240760.87      7188113.52
#Sta/Elev= 30
  4225.3  950.49  4445.5  945.17  4453.9  942.95  4485.1  943.92  4514.4  936.31
  4547.3   942.1  4633.3  940.82    4651  937.39  4661.3  933.09  4667.7  926.78
  4672.9  933.87  4692.4  928.06  4713.2  926.24  4733.9  934.69  4860.6  928.76
  4934.7  928.66  4951.7   931.2  4974.3  926.29  4989.8  908.16  4990.8  907.66
  4996.6  908.16  5008.7  916.07  5013.9  922.41  5024.3  927.12  5144.8  926.67
  5318.8  927.66  5424.6  932.93  5538.8  942.63  5801.1  938.93  5946.1  942.92
#Mann= 4 ,-1 , 0
  4225.3     .12       0  4989.8     .07       0  4996.6     .12       0
  5144.8     .05       0
Bank Sta=4974.3,5024.3
XS Rating Curve= 0 ,0
Exp/Cntr=0.3,0.1

Type RM Length L Ch R = 1 ,25829   ,311,311,311
BEGIN DESCRIPTION:
Cottonwood Creek 50.1
END DESCRIPTION:
XS GIS Cut Line= 2
      2241682.94      7189372.96      2241775.48      7187885.74
#Sta/Elev= 30
  4567.3  945.62  4574.4  944.91  4600.3  945.97  4650.4  935.93  4670.5  940.57
  4690.5  936.91  4720.6  937.23  4780.7  932.98  4840.8  921.22  4850.8  922.68
  4906.1   919.8  4911.2  924.45    4931  925.83    4961  921.79  4981.1  911.14
  4996.3  905.93  4997.6  905.43  5005.9  905.93  5011.1  911.44  5031.2  923.11
  5061.2  925.46  5199.9  923.89  5427.8  923.95  5662.4  929.41  5709.5   932.9
  5832.7  935.74  5892.8  941.65  5912.9  940.12  5953.7  941.77  6057.4  949.97
#Mann= 7 ,-1 , 0
  4567.3     .05       0  4574.4     .12       0  4996.3     .07       0
  5005.9     .12       0  5199.9     .05       0  5427.8     .12       0
  5953.7     .05       0
Bank Sta=4961,5031.2
XS Rating Curve= 0 ,0
Exp/Cntr=0.3,0.1

Type RM Length L Ch R = 1 ,25518   ,521,521,521
BEGIN DESCRIPTION:
Cottonwood Creek 50.0
END DESCRIPTION:
XS GIS Cut Line= 3
      2242001.93      7189356.39      2241994.21      7188984.06
      2241892.33      7188156.42
#Sta/Elev= 30
  4637.7  946.94  4864.1  931.13  4874.1  927.72  4894.1  926.95  4914.1  923.95
  4934.2  918.66  4944.2  919.41  4954.2  916.89  4974.2  906.89  4989.3  905.58
  4990.7  905.08    4999  905.58  5034.4  918.35    5051  922.53  5054.5  923.08
  5165.3  923.54  5245.9  921.96  5420.3  923.42  5447.4  925.02  5457.5   928.3
  5467.6  926.73  5477.7  927.45  5497.8  931.48  5502.9  930.29  5507.9  932.51
    5528  931.99  5628.8  936.92  5759.8   937.1  5827.8  938.91    5844  941.02
#Mann= 5 ,-1 , 0
  4637.7     .12       0  4989.3     .07       0    4999     .12       0
    5051     .05       0  5420.3     .12       0
Bank Sta=4914.1,5054.5
XS Rating Curve= 0 ,0
Exp/Cntr=0.3,0.1

Type RM Length L Ch R = 1 ,24997   ,470,470,470
BEGIN DESCRIPTION:
Cottonwood Creek 49.0
END DESCRIPTION:
XS GIS Cut Line= 3
      2242671.18      7189232.27        2242429.        7188760.
      2241897.89      7187931.34
#Sta/Elev= 30
  4473.6  941.96  4663.1  932.29  4690.9  928.21  4713.1  931.76  4768.3  933.34
  4951.7  921.49  4959.4  916.22  4968.2   913.9  4973.9  901.73    4977   901.5
  4978.4     901  4986.7   901.5  4996.1  903.85  5001.5  909.66  5007.3  909.66
  5011.9  917.68  5023.4  921.13  5048.3  922.06  5190.5  920.43  5314.6  921.06
    5351   923.6  5532.7  928.95  5553.8  931.65  5808.3  935.12  5844.6  935.88
  5850.6  937.71    5881  936.78  5938.5  942.51  5969.1  942.73  5988.6  944.03
#Mann= 6 ,-1 , 0
  4473.6     .12       0    4977     .07       0  4986.7     .12       0
  5023.4     .05       0  5190.5     .12       0  5969.1     .05       0
Bank Sta=4951.7,5023.4
XS Rating Curve= 0 ,0
Exp/Cntr=0.3,0.1

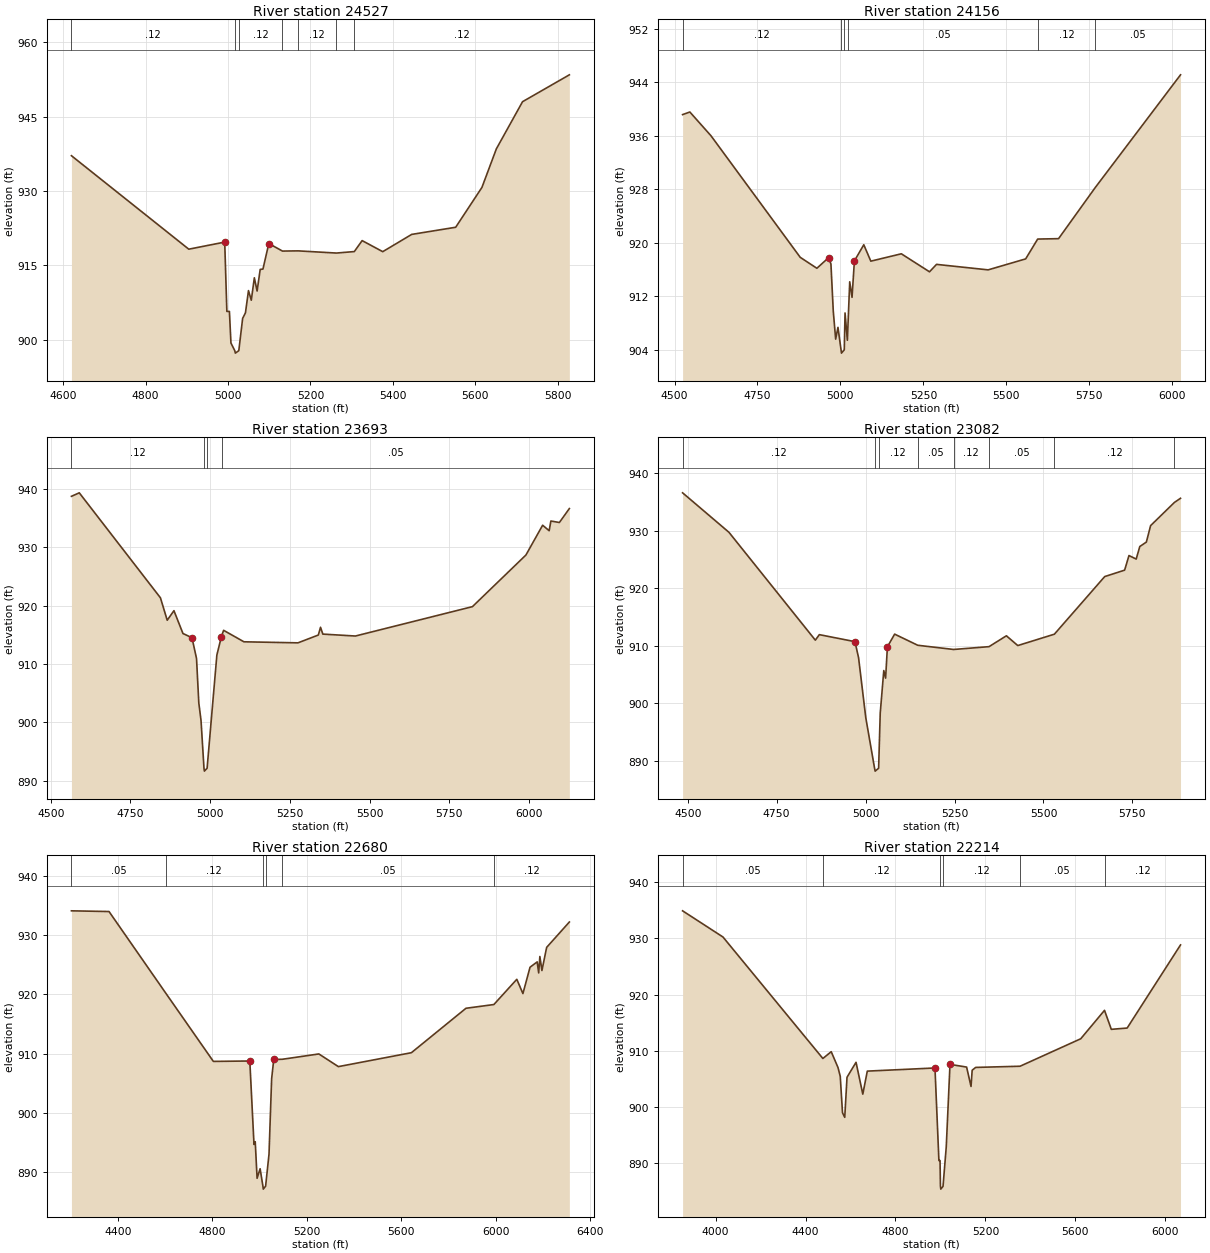
Type RM Length L Ch R = 1 ,24527   ,371,371,371
BEGIN DESCRIPTION:
Cottonwood Creek 48.0
END DESCRIPTION:
XS GIS Cut Line= 3
      2243011.79      7188893.18        2242829.        7188560.
      2242273.73      7187945.28
#Sta/Elev= 30
    4620  937.11  4904.8  918.26    4992  919.69  4997.2  905.71  5003.4  905.71
  5007.1  899.34  5016.4   897.8  5017.8   897.3  5026.2   897.8  5035.5  904.31
  5042.3  905.42  5049.7  909.91  5056.5  907.97  5063.9  912.49  5070.6  909.82
  5078.1  914.18  5084.8  914.25    5099   919.4  5132.2  917.88  5170.2  917.92
  5262.9  917.48  5306.5  917.78  5325.5  919.99  5375.5  917.76  5445.8  921.24
  5552.5  922.68  5616.2  930.71  5651.3   938.5  5714.8     948  5828.4  953.42
#Mann= 7 ,-1 , 0
    4620     .12       0  5016.4     .07       0  5026.2     .12       0
  5132.2     .05       0  5170.2     .12       0  5262.9     .05       0
  5306.5     .12       0
Bank Sta=4992,5099
XS Rating Curve= 0 ,0
Exp/Cntr=0.3,0.1

Type RM Length L Ch R = 1 ,24156   ,463,463,463
BEGIN DESCRIPTION:
Cottonwood Creek 47.0
END DESCRIPTION:
XS GIS Cut Line= 3
       2243459.7      7188749.85      2243218.82       7188466.4
      2242429.03      7187660.03
#Sta/Elev= 30
  4524.3  939.15  4546.2  939.54  4609.9  935.99  4878.9  917.84    4929  916.21
  4964.3  917.79  4971.4  916.85  4978.4  909.84  4985.6  905.63  4992.6  907.39
  5001.8  904.04  5003.2  903.54  5011.6  904.04  5013.9  909.54  5020.9  905.46
  5023.7   908.9    5028  914.19    5035  911.87  5042.1  917.31  5070.4  919.72
  5091.6  917.27  5183.6  918.37  5268.5  915.68  5289.6  916.79  5445.2  915.97
  5558.3  917.61  5594.5  920.57  5657.4  920.63    5768  928.26    6025  945.09
#Mann= 6 ,-1 , 0
  4524.3     .12       0  5001.8     .07       0  5011.6     .12       0
  5023.7     .05       0  5594.5     .12       0    5768     .05       0
Bank Sta=4964.3,5042.1
XS Rating Curve= 0 ,0
Exp/Cntr=0.3,0.1

Type RM Length L Ch R = 1 ,23693   ,611,611,611
BEGIN DESCRIPTION:
Cottonwood Creek 46.0
END DESCRIPTION:
XS GIS Cut Line= 3
      2243793.06      7188410.71      2243191.96      7187786.54
      2242529.12       7187577.4
#Sta/Elev= 30
  4564.9  938.76  4589.5  939.36    4844  921.35  4865.3   917.5  4886.4  919.14
  4914.7  915.22    4943   914.5  4957.2  910.94  4964.4   903.3  4971.3  900.32
  4980.6  892.11  4981.9  891.61  4990.4  892.11    5021  911.52  5035.1  914.66
  5035.6  914.74  5042.1  915.77  5105.9   913.8  5275.4  913.62  5339.2  914.96
  5346.1  916.29  5353.4  915.12  5455.5  914.79  5822.5  919.83  5990.3  928.69
  6042.7   933.8  6063.2  932.86  6068.5  934.52  6095.2  934.27  6126.5  936.66
#Mann= 4 ,-1 , 0
  4564.9     .12       0  4980.6     .07       0  4990.4     .12       0
  5035.6     .05       0
Bank Sta=4943,5035.1
XS Rating Curve= 0 ,0
Exp/Cntr=0.3,0.1

Type RM Length L Ch R = 1 ,23082   ,402,402,402
BEGIN DESCRIPTION:
Cottonwood Creek 45.0
END DESCRIPTION:
XS GIS Cut Line= 3
      2243885.08      7188268.71      2243954.24      7187827.71
       2243798.9      7186887.04
#Sta/Elev= 30
  4485.5   936.6  4615.8  929.73  4858.7  910.95  4869.9  911.91  4970.1  910.69
  4980.2   907.9  5000.5  897.45  5025.2  888.65  5026.8  888.15  5036.6  888.65
  5041.1  898.24  5051.1  905.66  5056.2  904.34  5061.3  909.79  5081.6     912
  5146.6  910.06  5247.5  909.33    5347  909.82  5395.8  911.71  5427.8  910.01
  5530.7  911.99  5672.2  922.02  5728.2  923.14  5740.4  925.68  5760.7  925.07
  5770.8  927.25  5789.3  928.03  5801.2  930.89  5868.2  934.93  5885.3  935.65
#Mann= 8 ,-1 , 0
  4485.5     .12       0  5025.2     .07       0  5036.6     .12       0
  5146.6     .05       0  5247.5     .12       0    5347     .05       0
  5530.7     .12       0  5868.2     .05       0
Bank Sta=4970.1,5061.3
XS Rating Curve= 0 ,0
Exp/Cntr=0.3,0.1

Type RM Length L Ch R = 1 ,22680   ,466,466,466
BEGIN DESCRIPTION:
Cottonwood Creek 44.0
END DESCRIPTION:
XS GIS Cut Line= 4
      2244065.01      7188460.69       2244280.1      7187909.55
        2244329.        7187710.      2244467.58      7186404.32
#Sta/Elev= 30
  4202.9   934.1  4362.2  933.98  4602.2  920.23  4804.4  908.68  4958.8  908.75
  4976.6  894.66  4981.8  895.12  4989.7  888.95  5002.5  890.56  5014.4  887.62
    5016  887.12  5025.8  887.62  5040.2  893.03  5051.3  905.74  5060.3  909.01
  5096.6  909.04  5251.4  909.94  5334.2   907.8  5643.6  910.15  5874.9  917.65
  5993.1  918.28  6090.3  922.54  6116.2  920.13  6146.4  924.58  6176.6  925.48
    6183  923.62    6188  926.39  6196.7  924.02  6216.8  927.93    6313  932.21
#Mann= 6 ,-1 , 0
  4202.9     .05       0  4602.2     .12       0  5014.4     .07       0
  5025.8     .12       0  5096.6     .05       0  5993.1     .12       0
Bank Sta=4958.8,5060.3
XS Rating Curve= 0 ,0
Exp/Cntr=0.3,0.1

Type RM Length L Ch R = 1 ,22214   ,437,437,437
BEGIN DESCRIPTION:
Cottonwood Creek 43.0
END DESCRIPTION:
XS GIS Cut Line= 3
      2244693.12        7188899.        2244779.        7187760.
      2244889.97      7186693.99
#Sta/Elev= 30
  3853.4  934.92  4032.9  930.26  4477.1  908.63  4514.3  909.84  4544.4  907.02
  4554.4  905.45  4564.4  898.97  4574.4  898.15  4584.5  905.29  4624.6  907.95
  4654.7  902.28  4674.7  906.38  4975.6  906.94  4993.1  890.46  4998.1  890.46
  4999.9  885.87  5001.5  885.37  5011.4  885.87  5025.8  892.92  5042.4  907.58
  5116.3   907.1  5135.9  903.65    5141  906.54  5156.5  907.04  5353.9  907.25
  5623.7  912.14  5729.4   917.2  5759.7  913.82  5830.1  914.05  6067.4  928.85
#Mann= 6 ,-1 , 0
  3853.4     .05       0  4477.1     .12       0  4999.9     .07       0
  5011.4     .12       0  5353.9     .05       0  5729.4     .12       0
Bank Sta=4975.6,5042.4
XS Rating Curve= 0 ,0
Exp/Cntr=0.3,0.1