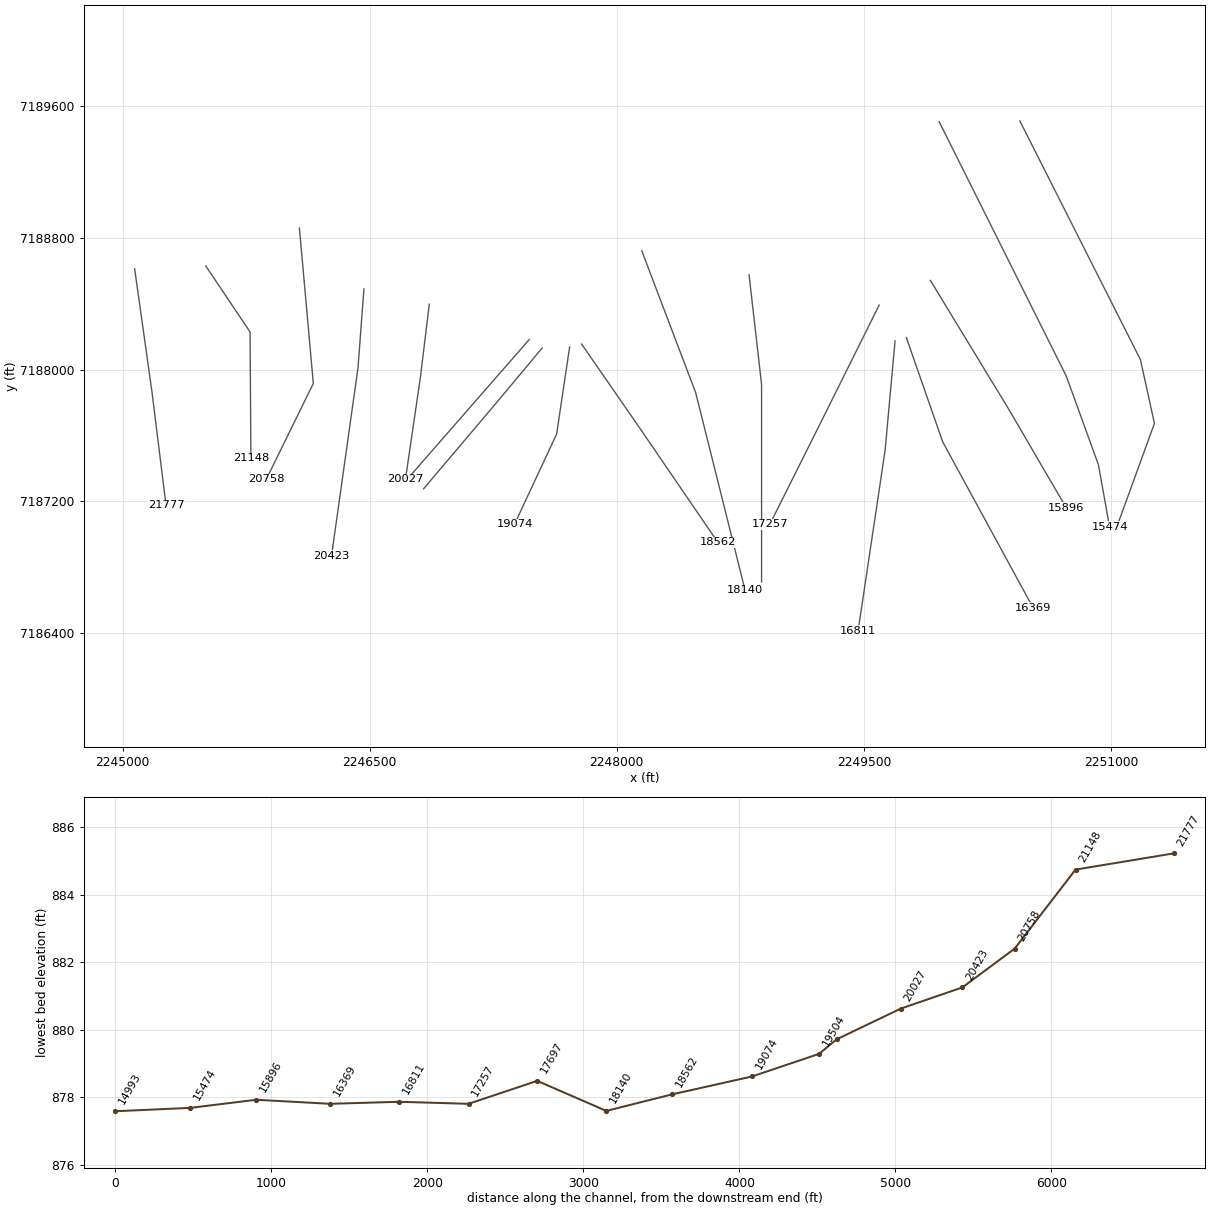
HEC-RAS study Cottonwood Creek.prj: Cottonwood Creek Base Level Engineering

--- Cottonwood Creek.g01 (geometry) --- (continued)

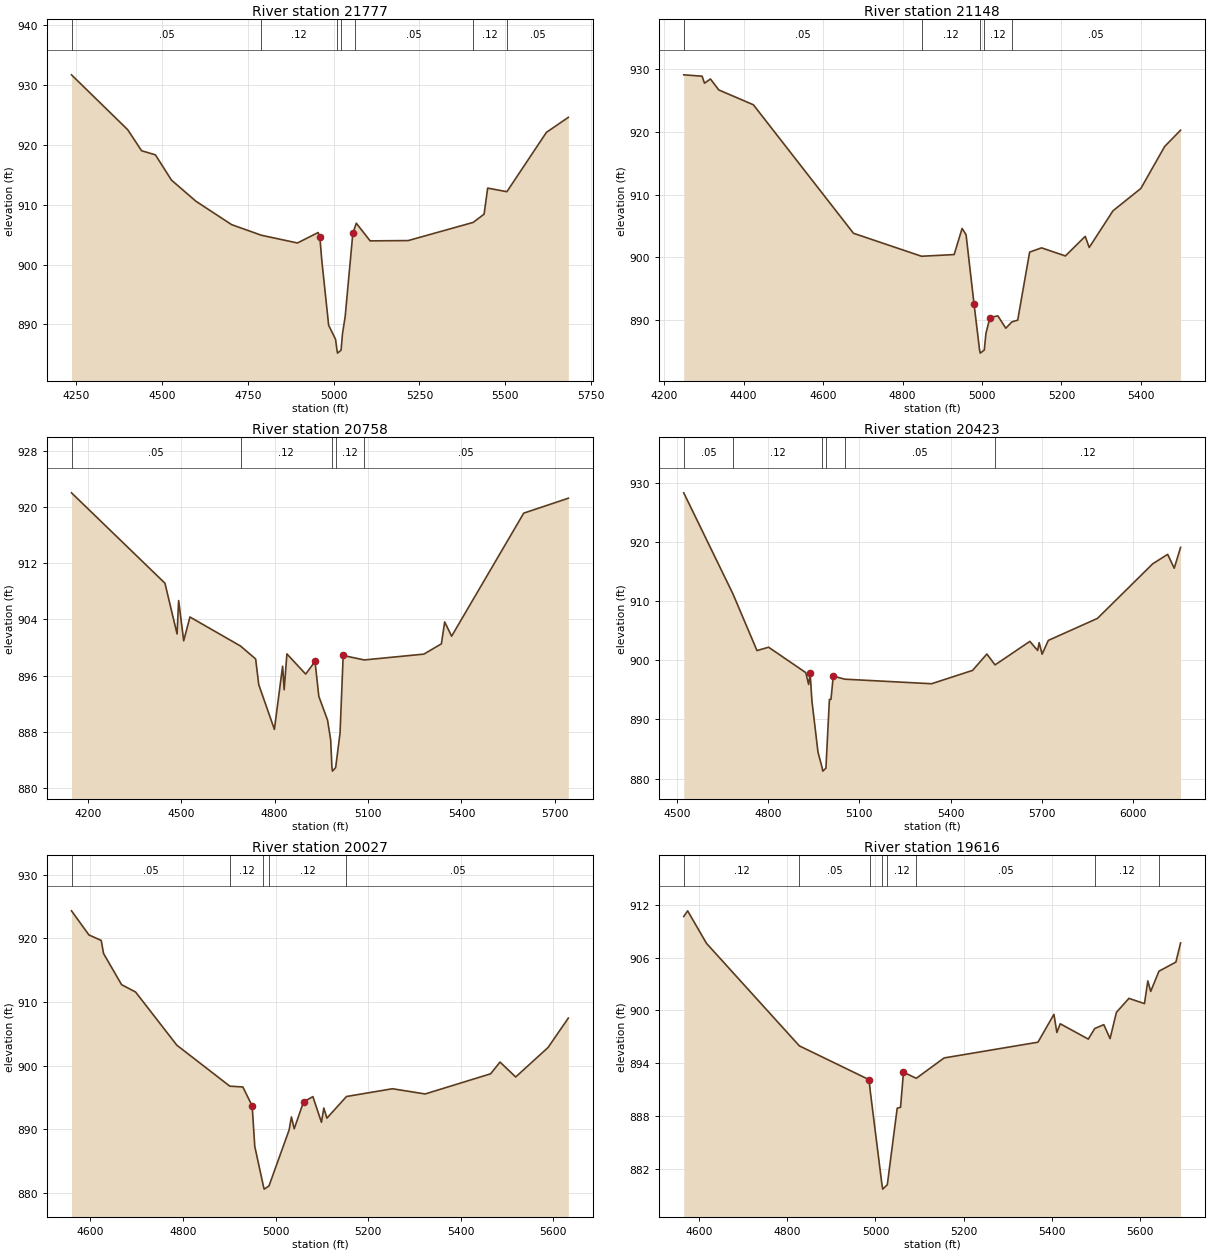
Type RM Length L Ch R = 1 ,21777   ,629,629,629
BEGIN DESCRIPTION:
Cottonwood Creek 42.0
END DESCRIPTION:
XS GIS Cut Line= 3
      2245073.27      7188612.19        2245179.        7187860.
       2245263.6      7187176.71
#Sta/Elev= 30
  4235.9  931.68  4399.7  922.52  4440.1  919.01  4480.5  918.32  4527.2  914.11
  4598.5  910.58  4702.6  906.67  4789.3   904.9  4894.5  903.61  4954.8  905.35
  4959.9  904.57  4965.2  900.83  4985.4  889.88  5005.6  887.52  5009.7  885.72
  5011.3  885.22  5021.6  885.72  5025.7  888.44  5033.5  891.29  5055.9  905.23
  5062.1  906.26    5066  906.91  5106.3  903.96  5217.2  904.01  5406.6  907.04
  5438.5  908.42  5448.9  912.77  5504.9  912.17  5620.2  922.08    5684  924.58
#Mann= 7 ,-1 , 0
  4235.9     .05       0  4789.3     .12       0  5009.7     .07       0
  5021.6     .12       0  5062.1     .05       0  5406.6     .12       0
  5504.9     .05       0
Bank Sta=4959.9,5055.9
XS Rating Curve= 0 ,0
Exp/Cntr=0.3,0.1

Type RM Length L Ch R = 1 ,21148   ,390,390,390
BEGIN DESCRIPTION:
Cottonwood Creek 41.0
END DESCRIPTION:
XS GIS Cut Line= 3
      2245505.27      7188628.93      2245773.83      7188228.66
        2245779.        7187460.
#Sta/Elev= 30
  4249.3  929.07  4295.5  928.85  4301.5  927.74  4316.5  928.41  4337.5  926.66
  4424.6   924.3  4676.6  903.83  4847.9  900.17    4930  900.44    4950   904.6
    4960  903.61    4980  892.61    4994  885.24  4995.7  884.74  5005.9  885.24
    5010  887.86    5020   890.4    5040  890.68    5060  888.71  5075.4  889.72
    5090  889.99    5120  900.83    5150  901.51    5210  900.22    5260  903.34
    5270  901.57    5330  907.42    5400  910.97    5460  917.66    5500  920.25
#Mann= 5 ,-1 , 0
  4249.3     .05       0  4847.9     .12       0    4994     .07       0
  5005.9     .12       0  5075.4     .05       0
Bank Sta=4980,5020
XS Rating Curve= 0 ,0
Exp/Cntr=0.3,0.1

Type RM Length L Ch R = 1 ,20758   ,335,335,335
BEGIN DESCRIPTION:
Cottonwood Creek 40.0
END DESCRIPTION:
XS GIS Cut Line= 3
      2246073.43      7188858.91      2246157.85      7187915.98
      2245872.38      7187333.47
#Sta/Elev= 30
  4147.7     922  4447.8  909.14  4486.7  901.92  4491.7  906.67    4508  900.95
  4528.1  904.33  4690.5   900.2    4739  898.36    4749  894.71  4799.2  888.34
  4825.6  897.33  4830.6  893.98  4839.4  899.08  4899.6  896.21  4929.7     898
  4941.9  893.04  4969.9  889.66  4979.9  886.86    4984   882.9  4985.7   882.4
  4995.9   882.9    5010   887.8  5020.1  898.86  5087.7  898.22  5279.2  899.05
  5335.4  900.51  5346.1  903.63  5368.3   901.6  5599.9  919.11  5743.1  921.23
#Mann= 5 ,-1 , 0
  4147.7     .05       0  4690.5     .12       0    4984     .07       0
  4995.9     .12       0  5087.7     .05       0
Bank Sta=4929.7,5020.1
XS Rating Curve= 0 ,0
Exp/Cntr=0.3,0.1

Type RM Length L Ch R = 1 ,20423   ,396,396,396
BEGIN DESCRIPTION:
Cottonwood Creek 39.0
END DESCRIPTION:
XS GIS Cut Line= 3
       2246465.2      7188490.08        2246429.        7188010.
      2246268.61      7186869.36
#Sta/Elev= 30
    4523  928.35  4684.7  911.25  4763.8  901.65  4801.9  902.22  4924.2  897.92
  4933.6  895.92  4938.6   897.8  4944.3  893.17  4964.3  884.48  4978.3  881.75
    4980  881.25  4990.4  881.75  5001.9  893.39    5007  893.39  5014.5  897.33
  5052.8  896.81  5337.7  896.04  5472.6   898.3  5519.5  901.07  5546.5  899.23
  5660.8  903.21  5686.4  901.67  5691.4  902.99  5701.2  901.04  5721.4  903.37
    5883   907.1  6064.8  916.34  6113.9  917.94  6135.5  915.59  6156.3  919.12
#Mann= 6 ,-1 , 0
    4523     .05       0  4684.7     .12       0  4978.3     .07       0
  4990.4     .12       0  5052.8     .05       0  5546.5     .12       0
Bank Sta=4938.6,5014.5
XS Rating Curve= 0 ,0
Exp/Cntr=0.3,0.1

Type RM Length L Ch R = 1 ,20027   ,411,411,411
BEGIN DESCRIPTION:
Cottonwood Creek 38.0
END DESCRIPTION:
XS GIS Cut Line= 3
      2246861.93      7188397.44      2246807.69      7187951.94
      2246717.33        7187334.
#Sta/Elev= 30
    4559  924.34  4596.7  920.55  4623.2  919.69  4628.3  917.63  4667.2  912.74
  4697.5  911.58  4786.6  903.23  4901.1  896.79  4929.2  896.67  4949.3  893.69
  4954.9  887.34  4973.5  881.12  4975.2  880.62  4985.6  881.12  5029.1  889.91
  5034.1  891.96  5040.1   890.1  5060.3  894.34  5080.5  895.15    5099  891.12
  5104.1  893.36  5110.8  891.77    5153  895.17  5252.3  896.39    5323  895.57
  5464.5  898.74  5484.7  900.58  5518.6  898.24  5588.5  902.87  5632.3  907.49
#Mann= 5 ,-1 , 0
    4559     .05       0  4901.1     .12       0  4973.5     .07       0
  4985.6     .12       0    5153     .05       0
Bank Sta=4949.3,5060.3
XS Rating Curve= 0 ,0
Exp/Cntr=0.3,0.1

Type RM Length L Ch R = 1 ,19616   ,112,112,112
BEGIN DESCRIPTION:
Cottonwood Creek 37.1
END DESCRIPTION:
XS GIS Cut Line= 2
      2247468.82       7188182.8      2246728.85      7187334.88
#Sta/Elev= 30
  4565.7  910.68  4574.5  911.32  4617.3  907.62  4827.6  895.98  4985.6  892.14
    4988  890.92  5014.7  880.21  5016.4  879.71  5026.8  880.21  5049.2   888.9
  5056.8  889.01  5063.4  892.98  5092.5   892.3  5155.5  894.61  5368.1   896.4
  5404.2  899.56  5410.9   897.5  5418.5  898.49  5482.1  896.75  5496.6  897.95
  5517.2  898.39  5531.4  896.81  5545.7  899.78  5574.1  901.38  5609.3  900.78
  5616.9  903.36  5623.5  902.17  5642.1  904.46  5680.5   905.5  5691.1  907.67
#Mann= 8 ,-1 , 0
  4565.7     .12       0  4827.6     .05       0    4988     .12       0
  5014.7     .07       0  5026.8     .12       0  5092.5     .05       0
  5496.6     .12       0  5642.1     .05       0
Bank Sta=4985.6,5063.4
XS Rating Curve= 0 ,0
Exp/Cntr=0.3,0.1

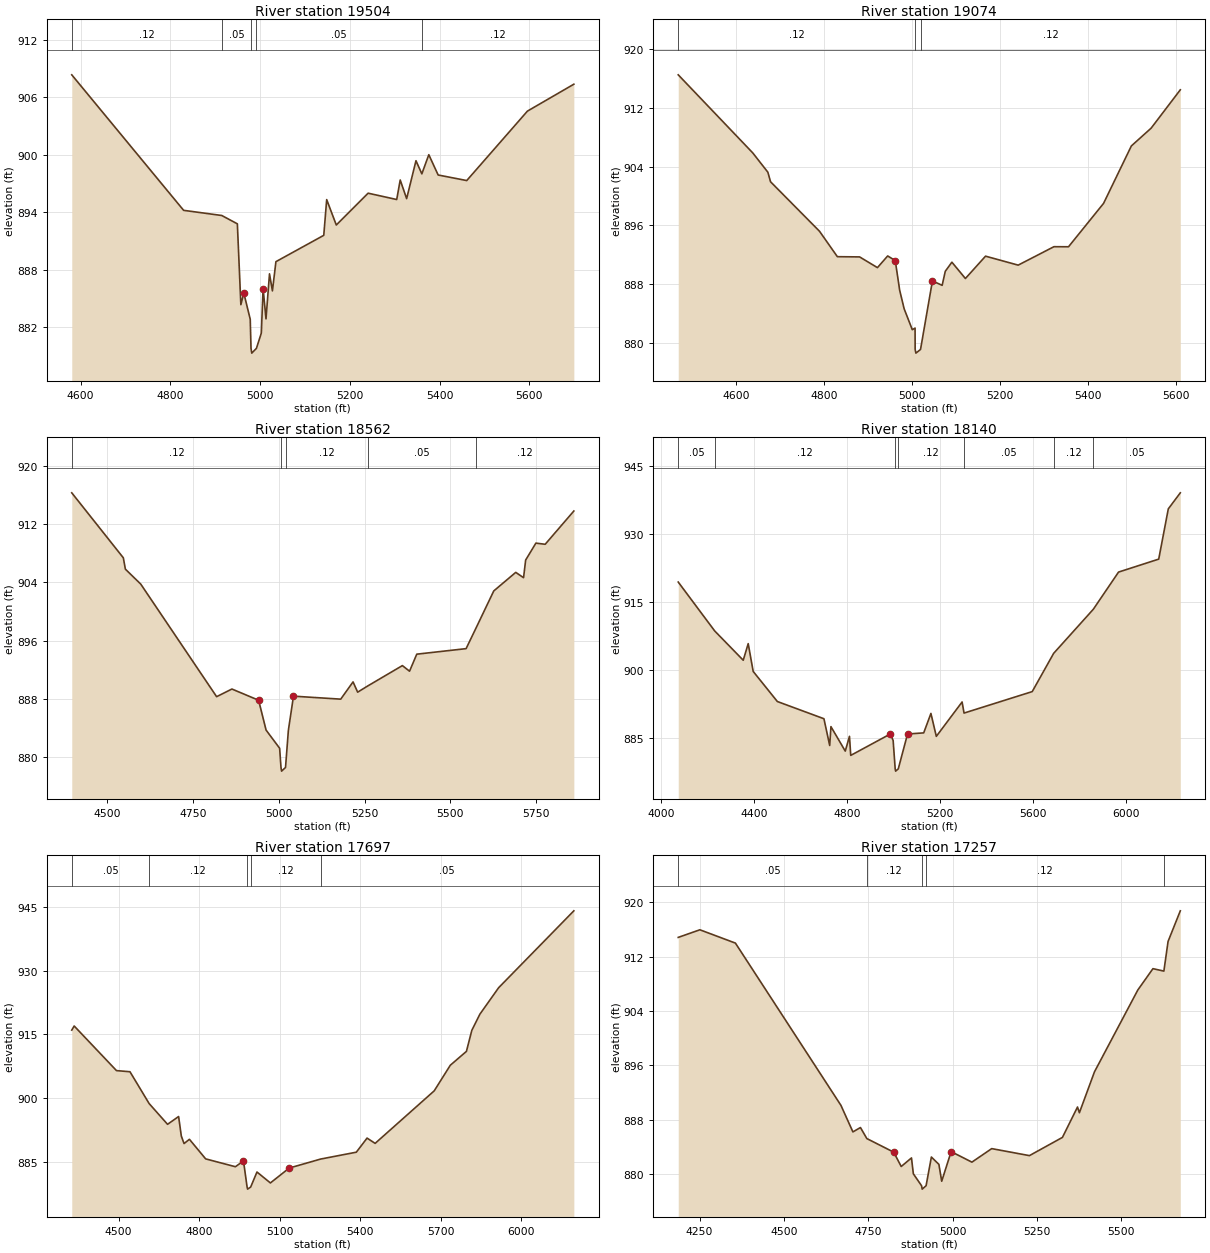
Type RM Length L Ch R = 1 ,19504   ,430,430,430
BEGIN DESCRIPTION:
Cottonwood Creek 37.0
END DESCRIPTION:
XS GIS Cut Line= 3
      2247547.71      7188131.54        2247279.        7187810.
      2246827.34      7187275.92
#Sta/Elev= 30
  4580.5  908.34  4829.7  894.19  4914.8  893.65  4949.4  892.78  4957.2  884.34
  4963.8  885.55  4978.1  882.81  4979.8  879.78  4981.5  879.28  4991.9  879.78
  5002.8  881.38  5006.7  886.02  5013.2  882.86    5021  887.56  5027.5  885.78
  5035.3  888.83  5141.9  891.58  5148.4  895.31  5169.8  892.66  5240.7  895.98
  5304.4  895.32  5312.2  897.36  5326.5  895.41  5347.3  899.37  5360.4     898
  5375.9     900  5396.7  897.88  5460.4   897.3  5595.6  904.55    5699  907.36
#Mann= 5 ,-1 , 0
  4580.5     .12       0  4914.8     .05       0  4979.8    .033       0
  4991.9     .05       0  5360.4     .12       0
Bank Sta=4963.8,5006.7
XS Rating Curve= 0 ,0
Exp/Cntr=0.3,0.1

Type RM Length L Ch R = 1 ,19074   ,512,512,512
BEGIN DESCRIPTION:
Cottonwood Creek 36.0
END DESCRIPTION:
XS GIS Cut Line= 3
      2247713.88       7188137.3      2247634.96      7187608.46
      2247379.02      7187060.04
#Sta/Elev= 30
    4469   916.5  4638.2  905.87  4672.5  903.24  4678.6  901.94  4789.8   895.2
  4830.3  891.74  4880.8  891.71  4921.3  890.25  4944.5  891.84  4961.7  891.21
  4971.8  887.16  4981.9  884.65  5000.4   881.8  5006.7  882.02  5006.9  879.11
  5008.6  878.61  5019.1  879.11  5046.1  888.44  5068.2  887.84  5075.3  889.75
  5090.3  890.99    5121  888.77  5166.7  891.81  5240.8  890.59    5322   893.1
  5355.1  893.09  5434.7     899  5497.8  906.82  5542.7  909.24  5608.9  914.46
#Mann= 3 ,-1 , 0
    4469     .12       0  5006.9     .07       0  5019.1     .12       0
Bank Sta=4961.7,5046.1
XS Rating Curve= 0 ,0
Exp/Cntr=0.3,0.1

Type RM Length L Ch R = 1 ,18562   ,422,422,422
BEGIN DESCRIPTION:
Cottonwood Creek 35.0
END DESCRIPTION:
XS GIS Cut Line= 3
      2247786.38      7188155.18        2248129.        7187660.
      2248613.98      7186950.35
#Sta/Elev= 30
  4397.6  916.32  4547.7  907.39  4553.7  905.83  4598.4  903.78  4819.3  888.31
  4863.9  889.36  4941.6  887.82  4963.3  883.72  5002.8  881.22  5006.7  878.58
  5008.5  878.08  5019.9  878.58  5028.2  883.68  5043.1  888.38  5180.6  887.97
  5216.5  890.34  5229.9  888.93  5259.2  889.78  5360.1  892.58    5381  891.81
    5402  894.15  5545.6  894.91  5573.5  897.64  5626.2  902.84  5690.2  905.39
  5712.9  904.66    5719  907.08  5748.8  909.41  5775.9  909.25  5859.3  913.82
#Mann= 5 ,-1 , 0
  4397.6     .12       0  5006.7     .07       0  5019.9     .12       0
  5259.2     .05       0  5573.5     .12       0
Bank Sta=4941.6,5043.1
XS Rating Curve= 0 ,0
Exp/Cntr=0.3,0.1

Type RM Length L Ch R = 1 ,18140   ,443,443,443
BEGIN DESCRIPTION:
Cottonwood Creek 34.0
END DESCRIPTION:
XS GIS Cut Line= 3
      2248151.83      7188721.18        2248479.        7187860.
      2248779.01      7186659.97
#Sta/Elev= 30
  4074.5  919.31  4231.3  908.52  4353.9  902.06  4375.3  905.72  4396.7  899.59
  4500.6  892.95  4700.8  889.15  4725.6  883.25  4730.9  887.41  4792.5  882.01
  4810.6  885.27    4816  881.06    4986  885.78  4998.3  884.35  5007.1  878.09
    5009  877.59  5020.4  878.09  5060.2  885.78  5129.7  886.03  5160.7  890.32
  5183.9  885.26  5294.7  892.85  5303.1   890.4  5596.2  895.14  5688.3  903.58
  5858.8  913.31  5967.2  921.51  6139.9  924.37  6181.1  935.46  6232.7     939
#Mann= 7 ,-1 , 0
  4074.5     .05       0  4231.3     .12       0  5007.1     .07       0
  5020.4     .12       0  5303.1     .05       0  5688.3     .12       0
  5858.8     .05       0
Bank Sta=4986,5060.2
XS Rating Curve= 0 ,0
Exp/Cntr=0.3,0.1

Type RM Length L Ch R = 1 ,17697   ,440,440,440
BEGIN DESCRIPTION:
Cottonwood Creek 33.0
END DESCRIPTION:
XS GIS Cut Line= 3
      2248803.15      7188575.38        2248879.        7187910.
        2248879.      7186709.99
#Sta/Elev= 30
  4325.7  916.02  4334.7  916.99  4492.2  906.46  4542.5  906.19  4613.8  898.68
  4682.4  893.78  4723.6  895.62  4733.7     891  4743.8  889.24  4763.9  890.24
  4824.3  885.62    4935  883.77  4965.2  885.13  4978.6  878.98  4980.5  878.48
    4992  878.98  5015.4  882.52  5065.4  879.94  5135.4  883.45  5252.6  885.58
  5385.4   887.2  5425.4  890.53  5455.4  889.28  5675.4  901.68  5735.4  907.73
  5795.4     911  5815.4  915.95  5845.4  919.77  5915.4  926.03  6195.4  944.18
#Mann= 5 ,-1 , 0
  4325.7     .05       0  4613.8     .12       0  4978.6     .07       0
    4992     .12       0  5252.6     .05       0
Bank Sta=4965.2,5135.4
XS Rating Curve= 0 ,0
Exp/Cntr=0.3,0.1

Type RM Length L Ch R = 1 ,17257   ,446,446,446
BEGIN DESCRIPTION:
Cottonwood Creek 32.0
END DESCRIPTION:
XS GIS Cut Line= 3
      2249592.82      7188391.82        2249229.        7187660.
      2248928.99      7187059.99
#Sta/Elev= 30
  4186.9  914.84    4251  915.96  4356.4     914  4669.1  890.13  4704.6  886.22
    4727  886.86  4745.9  885.24  4825.5  883.24  4847.8  881.13  4878.2  882.39
  4883.8  880.05  4908.1   878.3    4910   877.8  4921.5   878.3  4937.2  882.52
  4959.5  881.44  4967.8  878.96  4995.8  883.32  5057.3  881.77    5116  883.76
  5227.8  882.73  5325.6  885.41  5370.3  889.88  5375.9  889.04  5420.6  895.06
  5549.2  907.11  5593.9  910.24  5626.3  909.88  5638.7  914.24    5675  918.75
#Mann= 5 ,-1 , 0
  4186.9     .05       0  4745.9     .12       0  4908.1     .07       0
  4921.5     .12       0  5626.3     .05       0
Bank Sta=4825.5,4995.8
XS Rating Curve= 0 ,0
Exp/Cntr=0.3,0.1

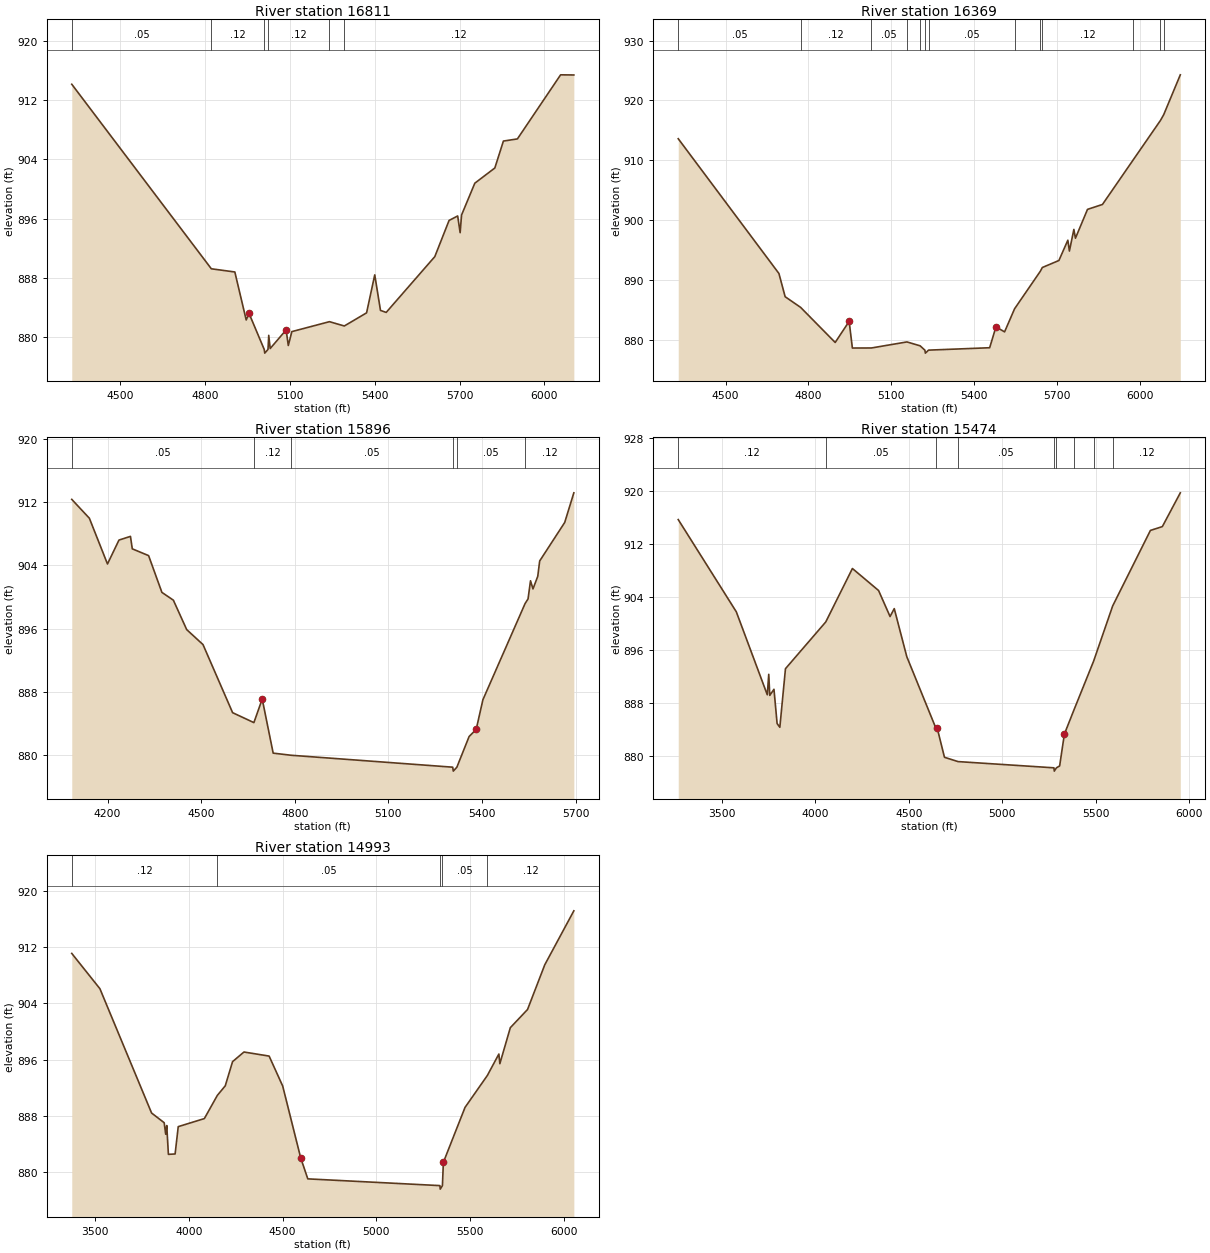
Type RM Length L Ch R = 1 ,16811   ,442,442,442
BEGIN DESCRIPTION:
Cottonwood Creek 31.0
END DESCRIPTION:
XS GIS Cut Line= 3
      2249689.38      7188174.35        2249629.        7187510.
      2249465.08      7186413.67
#Sta/Elev= 30
  4328.2  914.11  4821.8  889.23  4904.9   888.8  4945.1  882.33  4955.1  883.22
  5008.8  878.36  5010.7  877.86  5022.2  878.36  5024.8  880.26  5029.9  878.48
  5086.3  880.99    5094  878.89  5106.5  880.76  5239.5   882.1  5292.1  881.52
  5370.8  883.29  5399.7  888.41    5420  883.62  5440.2  883.35  5612.1  890.87
  5662.6  895.75    5693  896.35  5701.7   894.1  5706.7  896.48  5753.6  900.77
  5824.4  902.82  5854.7  906.45  5904.2  906.74    6057  915.38  6103.8  915.36
#Mann= 6 ,-1 , 0
  4328.2     .05       0  4821.8     .12       0  5008.8     .07       0
  5022.2     .12       0  5239.5     .05       0  5292.1     .12       0
Bank Sta=4955.1,5086.3
XS Rating Curve= 0 ,0
Exp/Cntr=0.3,0.1

Type RM Length L Ch R = 1 ,16369   ,473,473,473
BEGIN DESCRIPTION:
Cottonwood Creek 30.0
END DESCRIPTION:
XS GIS Cut Line= 3
      2249757.96      7188194.07        2249979.        7187560.
      2250526.77      7186554.07
#Sta/Elev= 30
  4328.8  913.61  4693.2   891.1  4715.7  887.22  4771.7  885.44  4896.8  879.58
  4947.3  883.11    4959  878.65  5027.9  878.66  5156.4  879.67  5204.1  879.02
  5221.3   878.3  5223.2   877.8  5234.7   878.3  5455.8   878.7  5478.5  882.18
  5509.8  881.35    5546  885.21  5639.1  891.47  5646.4   892.1  5706.4  893.27
  5738.7  896.66  5744.4  894.85  5760.5  898.46  5766.2  896.99  5809.9  901.81
    5864  902.63  5975.9  910.12    6074  916.67  6085.7  917.63  6145.7  924.28
#Mann= 13 ,-1 , 0
  4328.8     .05       0  4771.7     .12       0  5027.9     .05       0
  5156.4     .12       0  5204.1     .05       0  5221.3     .07       0
  5234.7     .05       0    5546     .12       0  5639.1     .05       0
  5646.4     .12       0  5975.9     .05       0    6074     .12       0
  6085.7     .05       0
Bank Sta=4947.3,5478.5
XS Rating Curve= 0 ,0
Exp/Cntr=0.3,0.1

Type RM Length L Ch R = 1 ,15896   ,422,422,422
BEGIN DESCRIPTION:
Cottonwood Creek 29.0
END DESCRIPTION:
XS GIS Cut Line= 3
       2249903.8       7188541.7        2250379.        7187760.
      2250728.99      7187160.02
#Sta/Elev= 30
  4085.2  912.37  4141.6  909.98  4199.7  904.18  4236.5  907.21  4273.3  907.68
  4279.2   906.1  4331.5  905.24  4374.1  900.58  4410.9  899.59  4453.6  895.86
  4505.9  893.96  4600.8  885.33    4669  884.07  4695.7  887.06  4730.8   880.2
  4788.7  879.93  5306.3  878.42  5308.2  877.92  5319.7  878.42  5358.9  882.31
  5381.6  883.21  5403.1  886.97  5538.3  899.16  5547.8  899.75  5555.7  902.05
  5563.6  901.02  5578.9  902.61  5585.1  904.56  5665.3  909.44  5694.6   913.2
#Mann= 6 ,-1 , 0
  4085.2     .05       0    4669     .12       0  4788.7     .05       0
  5306.3    .033       0  5319.7     .05       0  5538.3     .12       0
Bank Sta=4695.7,5381.6
XS Rating Curve= 0 ,0
Exp/Cntr=0.3,0.1

Type RM Length L Ch R = 1 ,15474   ,481,481,481
BEGIN DESCRIPTION:
Cottonwood Creek 28.0
END DESCRIPTION:
XS GIS Cut Line= 4
      2249956.83      7189505.93        2250729.        7187960.
      2250924.01      7187421.57      2250991.54      7187044.07
#Sta/Elev= 30
  3267.4  915.67  3577.9  901.74  3743.5  889.21  3751.3   892.3  3756.8  889.12
  3779.2  890.04    3796  884.87  3810.6   884.3  3840.7  893.15  4056.1  900.21
  4198.6  908.28  4338.4  904.96  4399.9  901.03  4422.3  902.22  4489.4  894.96
  4647.9  883.96  4651.5  884.23  4690.7  879.77  4763.4  879.12  5275.9  878.18
  5277.8  877.68  5289.3  878.18  5306.5  878.46  5331.8  883.27    5385  887.06
  5488.1  894.29  5590.2  902.64  5791.7  914.03  5855.6  914.61  5951.6  919.71
#Mann= 9 ,-1 , 0
  3267.4     .12       0  4056.1     .05       0  4647.9     .12       0
  4763.4     .05       0  5275.9    .033       0  5289.3     .05       0
    5385     .12       0  5488.1     .05       0  5590.2     .12       0
Bank Sta=4651.5,5331.8
XS Rating Curve= 0 ,0
Exp/Cntr=0.3,0.1

Type RM Length L Ch R = 1 ,14993   ,410,410,410
BEGIN DESCRIPTION:
Cottonwood Creek 27.0
END DESCRIPTION:
XS GIS Cut Line= 4
      2250447.03      7189510.25        2251179.        7188060.
      2251263.88      7187672.96      2251039.06      7187054.28
#Sta/Elev= 30
  3375.5  911.12  3525.6   906.1  3801.4  888.41  3868.6  887.03  3876.7  885.39
  3882.3  886.63  3891.1  882.53  3926.9  882.58  3943.6  886.47    4083  887.62
  4152.3  890.92  4194.5  892.28  4233.5  895.72  4294.3  897.09  4428.6  896.51
  4501.1  892.24  4596.7  882.06  4634.9  879.04  5339.8  878.08  5341.7  877.58
  5353.3  878.08  5358.3  881.39  5473.9  889.21    5593  893.75  5654.4   896.8
  5659.7  895.43  5715.6  900.55  5807.4  903.14  5899.5  909.51  6054.5  917.18
#Mann= 5 ,-1 , 0
  3375.5     .12       0  4152.3     .05       0  5339.8    .033       0
  5353.3     .05       0    5593     .12       0
Bank Sta=4596.7,5358.3
XS Rating Curve= 0 ,0
Exp/Cntr=0.3,0.1