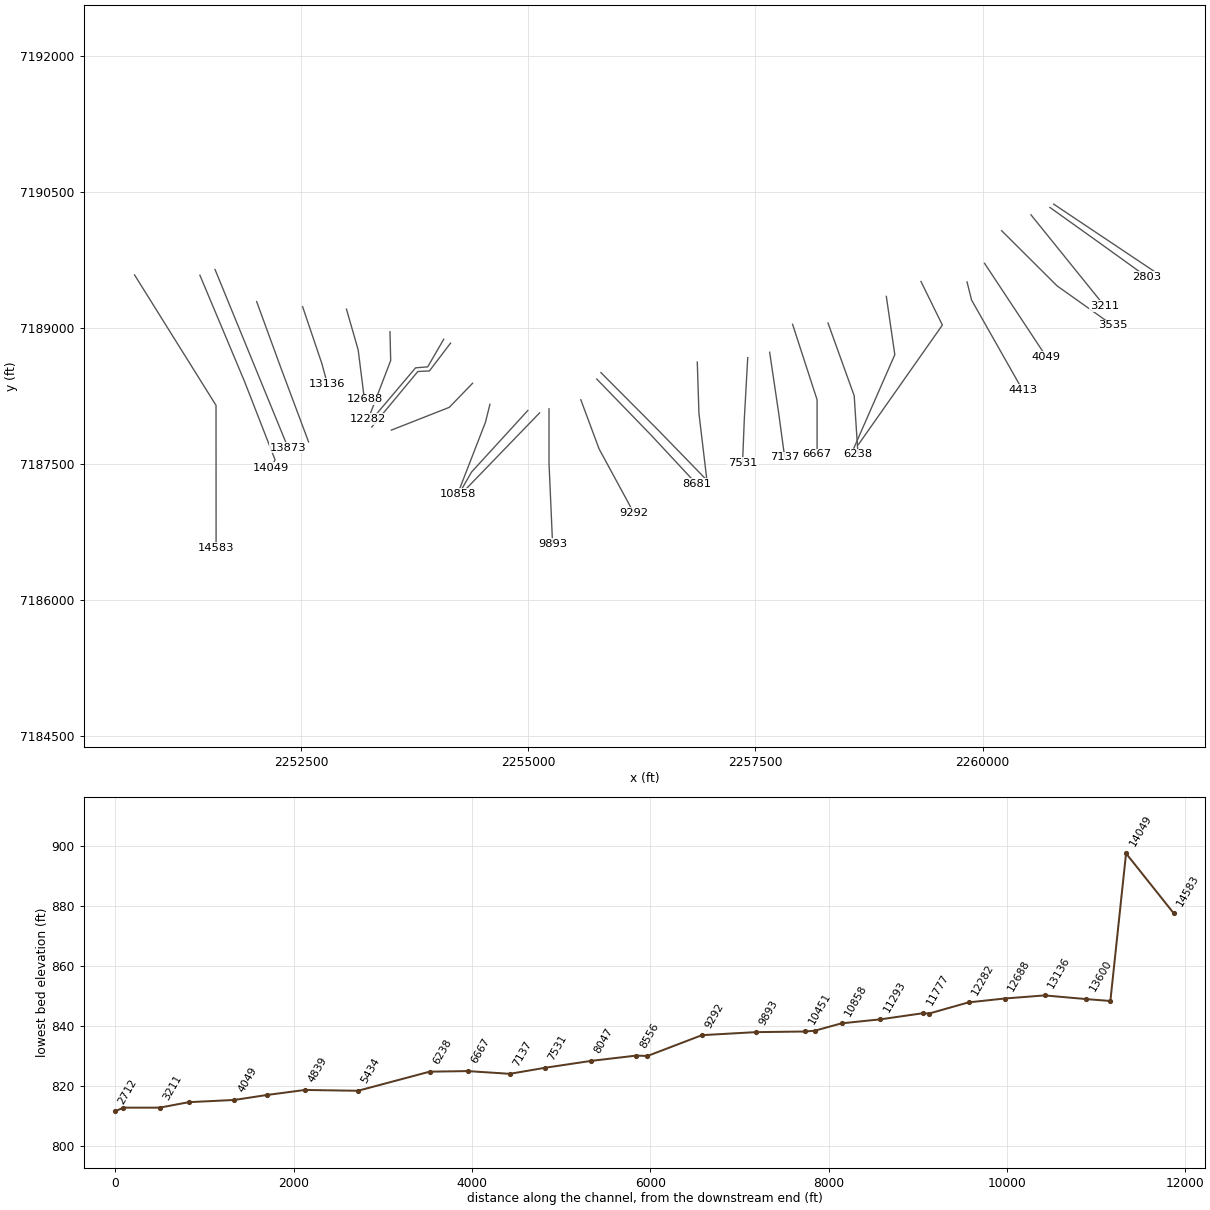
HEC-RAS study Cottonwood Creek.prj: Cottonwood Creek Base Level Engineering

--- Cottonwood Creek.g01 (geometry) --- (continued)

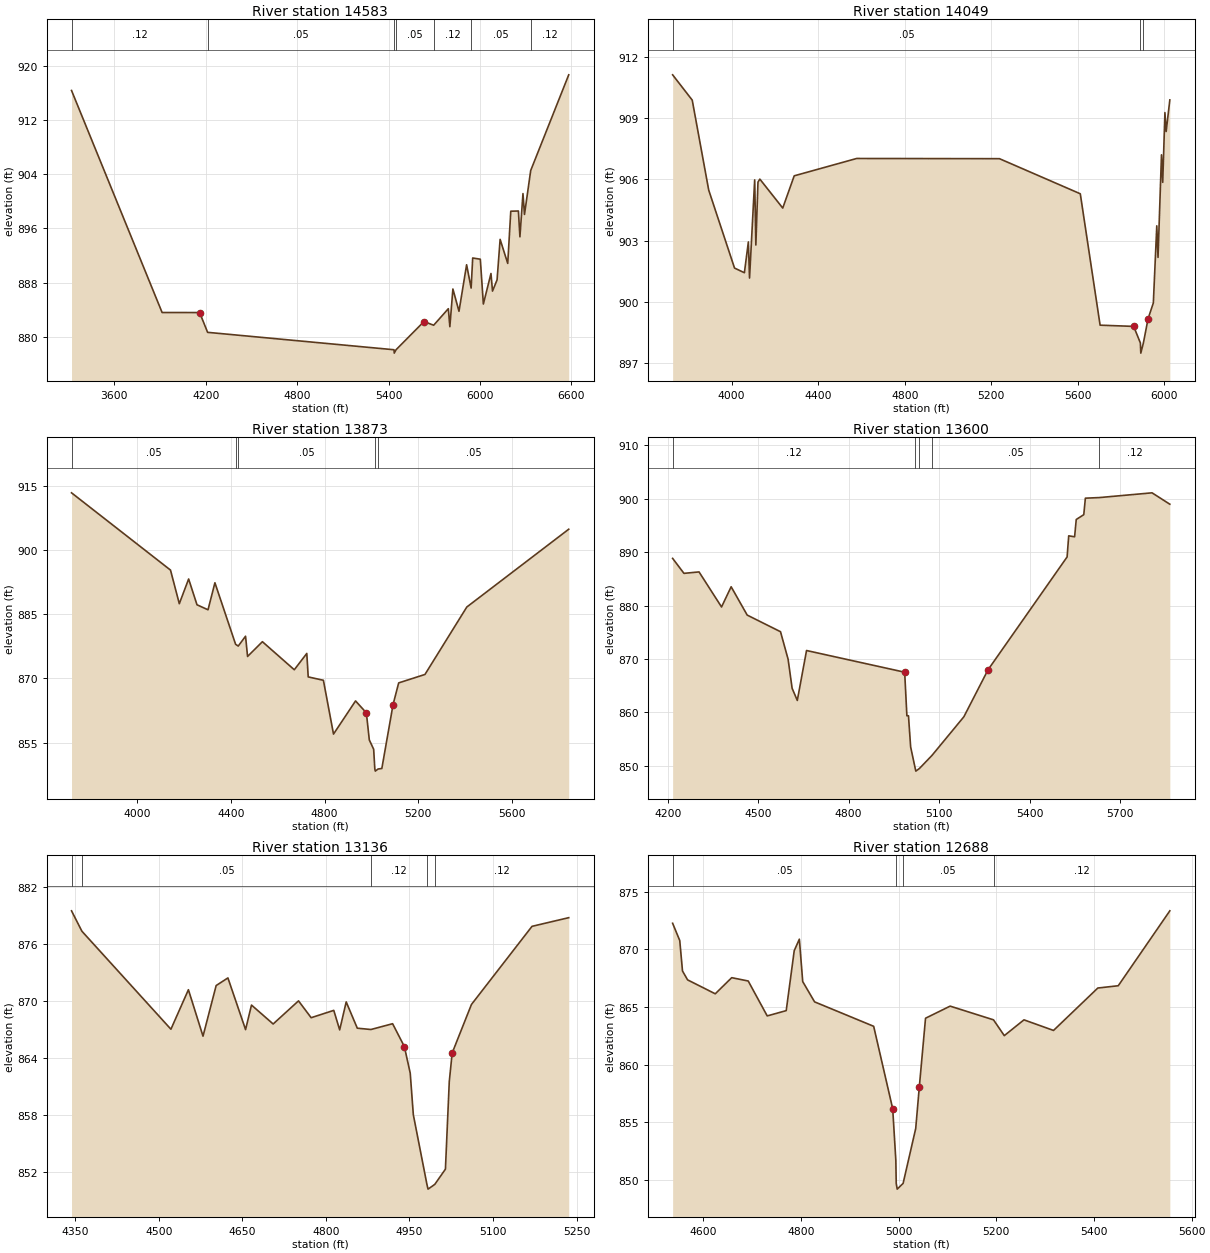
Type RM Length L Ch R = 1 ,14583   ,534,534,534
BEGIN DESCRIPTION:
Cottonwood Creek 26.0
END DESCRIPTION:
XS GIS Cut Line= 3
      2250667.88      7189587.06      2251564.66      7188148.36
      2251565.44      7186579.57
#Sta/Elev= 30
  3318.6  916.38  3913.2  883.59  4159.8  883.58  4211.9  880.66  5435.5  878.09
  5437.4  877.59  5449.1  878.09  5632.3  882.25  5696.1  881.71  5792.3  884.15
  5802.3   881.5  5822.3  887.06  5862.3  883.77  5912.3  890.64    5942   887.2
  5952.3  891.64  6002.3  891.46  6022.3  884.84  6072.3  889.35  6082.3  886.75
  6112.3  888.41  6132.3  894.39  6182.3  890.84  6202.3  898.55  6252.3  898.58
  6262.3  894.77  6282.3  901.15  6292.3  898.07  6333.1  904.56  6582.7  918.69
#Mann= 7 ,-1 , 0
  3318.6     .12       0  4211.9     .05       0  5435.5    .033       0
  5449.1     .05       0  5696.1     .12       0    5942     .05       0
  6333.1     .12       0
Bank Sta=4159.8,5632.3
XS Rating Curve= 0 ,0
Exp/Cntr=0.3,0.1

Type RM Length L Ch R = 1 ,14049   ,176,176,176
BEGIN DESCRIPTION:
Cottonwood Creek 25.0
END DESCRIPTION:
XS GIS Cut Line= 4
      2251386.99      7189583.88        2251879.        7188410.
      2252214.56       7187547.2       2252165.6      7187460.32
#Sta/Elev= 30
  3727.2  911.13  3817.8  909.89    3894  905.48  4013.3  901.66  4058.9  901.43
  4077.3  902.94  4082.7  901.17  4106.5  905.98  4111.9  902.79  4121.7  905.87
  4130.3  906.02  4236.2   904.6  4289.2  906.18  4577.9  907.03    5238  907.02
  5611.6   905.3  5703.2  898.86  5858.4   898.8  5889.3  897.99  5891.3  897.49
  5903.3  897.99    5925  899.18  5949.3  899.95  5965.2  903.73  5970.9  902.18
  5986.9  907.21  5992.6  905.86  6002.8  909.28  6008.5  908.35  6025.5   909.9
#Mann= 3 ,-1 , 0
  3727.2     .05       0  5889.3    .033       0  5903.3     .05       0
Bank Sta=5858.4,5925
XS Rating Curve= 0 ,0
Exp/Cntr=0.3,0.1

Type RM Length L Ch R = 1 ,13873   ,273,273,273
BEGIN DESCRIPTION:
Cottonwood Creek 24.1
END DESCRIPTION:
XS GIS Cut Line= 2
      2251553.84      7189646.34      2252357.79      7187679.51
#Sta/Elev= 30
  3718.6  913.35  4141.6  895.31  4179.2  887.46  4219.1  893.23  4254.8  887.21
  4301.9  886.04  4331.4  892.35  4419.8  877.98  4431.1  877.57  4462.3  879.87
  4470.9  875.14  4534.3  878.59  4670.6  872.04    4724  875.85  4730.1  870.37
    4795  869.58  4838.2  857.02  4932.4  864.76  4978.6  861.98  4991.2  855.65
  5009.8  853.47  5014.8  848.87  5016.8  848.37  5028.8  848.87  5044.7  848.98
  5092.7  863.91  5116.7  868.97    5229  870.94  5407.9  886.69  5843.4  904.85
#Mann= 5 ,-1 , 0
  3718.6     .05       0  4419.8     .12       0  4431.1     .05       0
  5014.8    .033       0  5028.8     .05       0
Bank Sta=4978.6,5092.7
XS Rating Curve= 0 ,0
Exp/Cntr=0.3,0.1

Type RM Length L Ch R = 1 ,13600   ,464,464,464
BEGIN DESCRIPTION:
Cottonwood Creek 24.0
END DESCRIPTION:
XS GIS Cut Line= 3
      2252011.85      7189292.34        2252279.        7188560.
      2252583.01      7187745.43
#Sta/Elev= 30
  4216.3  888.82  4253.9  886.02  4303.9  886.29  4378.5  879.73  4410.4  883.51
  4463.6  878.21  4574.1   875.1  4599.3  869.94  4612.6  864.51  4629.8  862.24
  4660.4  871.58  4985.9  867.52  4993.2  859.37  4998.5  859.37  5005.7  853.53
  5020.9  849.51  5022.9  849.01  5034.9  849.51  5076.3  851.94  5182.2  859.18
  5262.4  867.98  5524.6  889.09  5529.9  893.04  5549.5  892.87  5554.9   896.1
  5579.9     897  5585.2  900.09  5631.5   900.2  5806.3  901.09  5865.3  898.96
#Mann= 5 ,-1 , 0
  4216.3     .12       0  5020.9     .07       0  5034.9     .12       0
  5076.3     .05       0  5631.5     .12       0
Bank Sta=4985.9,5262.4
XS Rating Curve= 0 ,0
Exp/Cntr=0.3,0.1

Type RM Length L Ch R = 1 ,13136   ,448,448,448
BEGIN DESCRIPTION:
Cottonwood Creek 23.0
END DESCRIPTION:
XS GIS Cut Line= 3
      2252517.58      7189235.98        2252729.        7188610.
      2252789.85      7188386.45
#Sta/Elev= 30
  4343.4  879.47    4362  877.33  4521.8  867.03  4553.2  871.18  4579.4   866.3
    4603  871.62  4624.1  872.42  4655.8  866.99  4666.4  869.57  4705.3  867.58
  4750.8  870.01  4773.5  868.24  4814.1  869.01  4824.7  866.96  4836.4   869.9
  4856.3  867.14  4880.8     867  4919.7  867.61  4940.8  865.21  4951.3  862.42
  4956.9  858.04  4981.3  850.73  4983.3  850.23  4995.4  850.73  5014.5  852.33
  5021.4  861.52  5026.6  864.53  5061.2  869.63  5169.9  877.84  5235.8  878.75
#Mann= 5 ,-1 , 0
  4343.4     .12       0    4362     .05       0  4880.8     .12       0
  4981.3     .07       0  4995.4     .12       0
Bank Sta=4940.8,5026.6
XS Rating Curve= 0 ,0
Exp/Cntr=0.3,0.1

Type RM Length L Ch R = 1 ,12688   ,406,406,406
BEGIN DESCRIPTION:
Cottonwood Creek 22.0
END DESCRIPTION:
XS GIS Cut Line= 3
      2253000.07      7189209.39        2253129.        7188760.
      2253197.58      7188213.61
#Sta/Elev= 30
  4537.1  872.27  4551.7  870.77  4557.3  868.13  4567.7  867.36  4624.4  866.15
  4658.1  867.55  4691.9  867.26  4730.8  864.23  4769.7  864.69  4786.1  869.89
  4796.6  870.89  4803.5  867.21  4827.8  865.45  4948.8  863.33  4987.8  856.17
  4994.2  851.69    4995   849.7    4997   849.2  5009.1   849.7  5034.9  854.46
  5042.3  858.08    5055  864.03  5105.4  865.08  5194.2  863.89  5216.3  862.52
  5256.6  863.89  5317.1  862.97  5407.8  866.65  5449.7  866.85  5555.3  873.35
#Mann= 4 ,-1 , 0
  4537.1     .05       0    4995    .033       0  5009.1     .05       0
  5194.2     .12       0
Bank Sta=4987.8,5042.3
XS Rating Curve= 0 ,0
Exp/Cntr=0.3,0.1

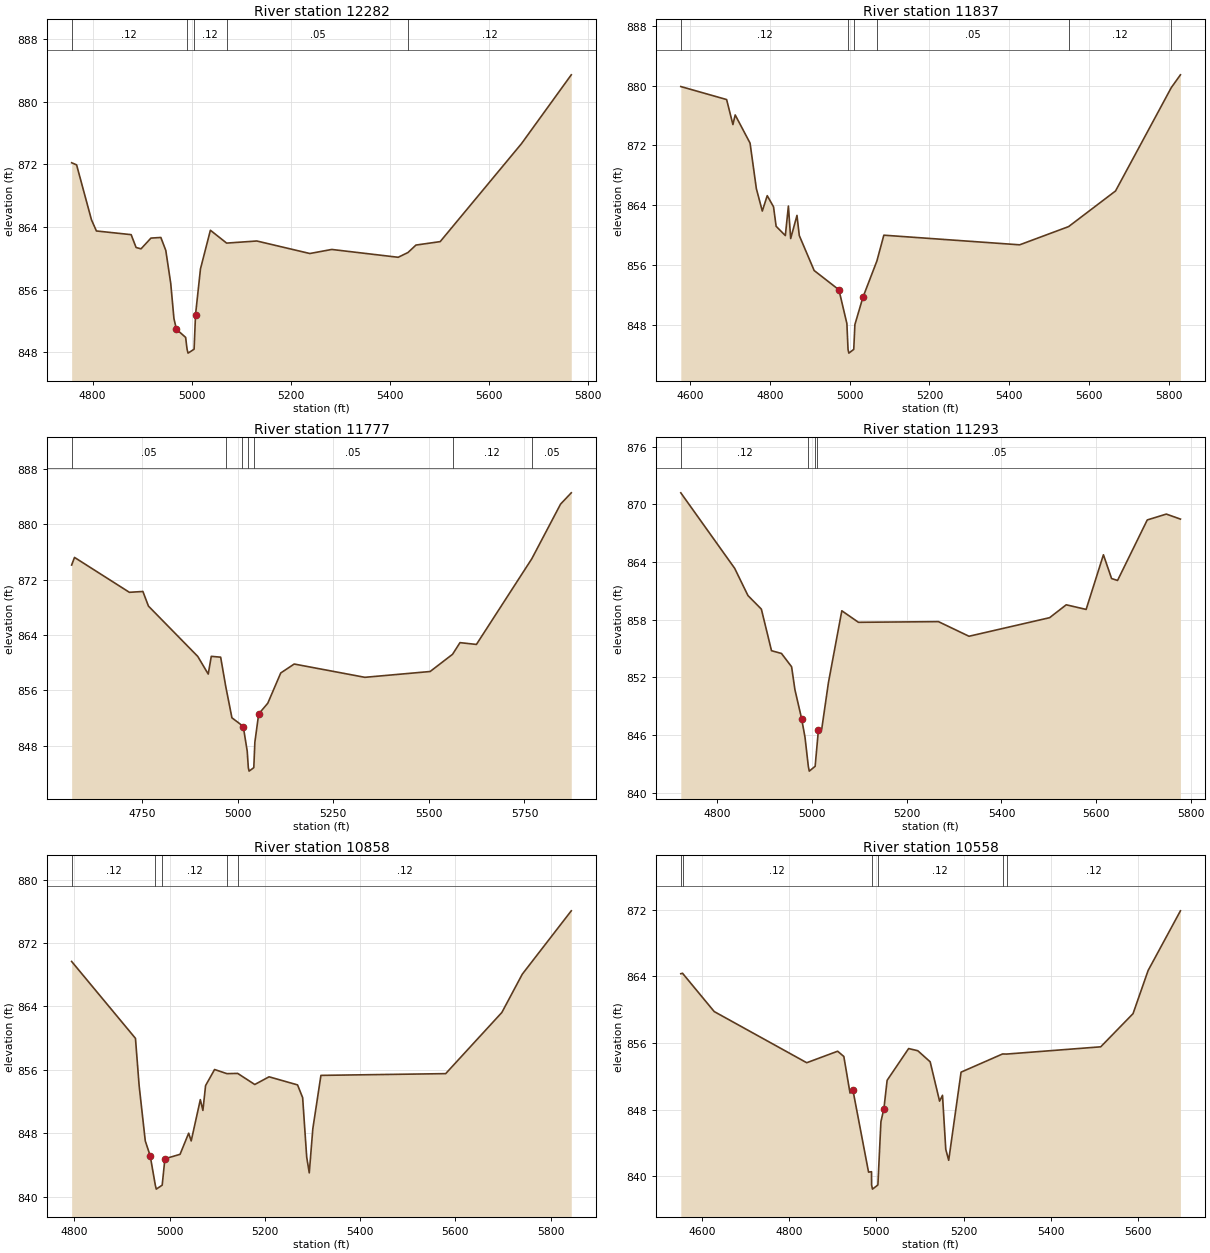
Type RM Length L Ch R = 1 ,12282   ,445,445,445
BEGIN DESCRIPTION:
Cottonwood Creek 21.0
END DESCRIPTION:
XS GIS Cut Line= 3
        2253479.      7188960.02      2253486.65      7188642.27
      2253239.61       7187997.2
#Sta/Elev= 30
  4757.9  872.22  4767.9  871.95  4797.9  864.94  4807.9  863.51    4878  863.04
    4888   861.4    4898  861.23    4918   862.6    4938  862.68    4948  861.02
    4958  856.78  4964.4  852.33  4969.4  850.96    4988  849.92  4990.9  848.41
  4992.9  847.91  5005.1  848.41    5008  852.82    5018  858.68    5038   863.6
  5070.8  861.96  5131.7  862.23  5238.8  860.63  5282.9  861.15  5417.1  860.15
  5436.9  860.76    5453  861.71  5501.9  862.15    5666  874.66  5766.5  883.45
#Mann= 5 ,-1 , 0
  4757.9     .12       0  4990.9     .07       0  5005.1     .12       0
  5070.8     .05       0  5436.9     .12       0
Bank Sta=4969.4,5008
XS Rating Curve= 0 ,0
Exp/Cntr=0.3,0.1

Type RM Length L Ch R = 1 ,11837   ,60,60,60
BEGIN DESCRIPTION:
Cottonwood Creek 20.1
END DESCRIPTION:
XS GIS Cut Line= 4
      2254070.14      7188876.92      2253894.13       7188572.9
       2253760.8      7188562.23      2253264.79      7187975.56
#Sta/Elev= 30
  4576.2  879.86  4691.1  878.12  4706.9  874.77  4712.6  876.06  4749.9  872.29
  4765.7   866.2  4780.6  863.19    4793  865.25  4808.8  863.76  4815.3  861.15
  4838.4  859.91  4846.1  863.86  4851.8  859.51  4867.6  862.61  4873.4  859.91
  4910.7  855.23  4972.8  852.65  4992.8  848.13  4995.7  844.67  4997.7  844.17
    5010  844.67  5012.9  847.99    5033  851.64  5068.1  856.51  5085.5  859.96
  5426.2  858.67    5549  861.11  5666.7  865.88  5806.6  879.72  5829.5  881.43
#Mann= 6 ,-1 , 0
  4576.2     .12       0  4995.7     .07       0    5010     .12       0
  5068.1     .05       0    5549     .12       0  5806.6     .05       0
Bank Sta=4972.8,5033
XS Rating Curve= 0 ,0
Exp/Cntr=0.3,0.1

Type RM Length L Ch R = 1 ,11777   ,484,484,484
BEGIN DESCRIPTION:
Cottonwood Creek 20.0
END DESCRIPTION:
XS GIS Cut Line= 4
      2254145.65      7188834.74      2253912.92      7188527.67
      2253785.26      7188521.56      2253279.01      7187910.01
#Sta/Elev= 30
  4565.4   874.1  4572.9   875.2  4716.4  870.16  4751.8  870.28  4766.3  868.17
  4895.3   860.9  4922.7  858.35  4930.7  860.91  4955.2  860.79  4968.7  856.51
  4984.7  852.03  5010.8  850.94  5014.7  850.66  5024.7  847.21  5027.6  844.83
  5029.6  844.33  5041.9  844.83  5044.7  848.51  5054.7  852.59  5078.5  854.14
  5112.4  858.51  5147.6   859.8  5332.5  857.88  5503.2  858.72  5561.9  861.21
  5581.3  862.89  5624.3  862.63  5769.2  875.01  5844.4   882.9  5872.4  884.53
#Mann= 7 ,-1 , 0
  4565.4     .05       0  4968.7     .12       0  5010.8     .05       0
  5027.6     .07       0  5041.9     .05       0  5561.9     .12       0
  5769.2     .05       0
Bank Sta=5014.7,5054.7
XS Rating Curve= 0 ,0
Exp/Cntr=0.3,0.1

Type RM Length L Ch R = 1 ,11293   ,435,435,435
BEGIN DESCRIPTION:
Cottonwood Creek 19.0
END DESCRIPTION:
XS GIS Cut Line= 3
      2254387.77      7188391.83       2254131.6      7188126.38
      2253493.83      7187875.06
#Sta/Elev= 30
  4723.3  871.19    4837  863.34    4865  860.51  4893.3   859.1  4914.7  854.78
  4935.8  854.49  4957.1  853.11  4964.1  850.73  4978.2  847.73  4985.4  845.78
  4992.4  842.76  4994.4  842.26  5006.8  842.76  5010.4  844.73  5013.7  846.54
  5020.7  846.63  5034.8  851.45  5063.1  858.93  5098.2  857.73    5267   857.8
  5331.5  856.28  5501.6  858.21  5536.7  859.55  5578.7  859.07  5615.2  864.75
  5632.4  862.28    5645  862.08  5707.7  868.37  5747.9  868.98  5777.7  868.46
#Mann= 4 ,-1 , 0
  4723.3     .12       0  4992.4     .07       0  5006.8     .12       0
  5010.4     .05       0
Bank Sta=4978.2,5013.7
XS Rating Curve= 0 ,0
Exp/Cntr=0.3,0.1

Type RM Length L Ch R = 1 ,10858   ,300,300,300
BEGIN DESCRIPTION:
Cottonwood Creek 18.0
END DESCRIPTION:
XS GIS Cut Line= 3
      2254578.99      7188159.98        2254529.        7187960.
      2254224.36      7187174.11
#Sta/Elev= 30
  4794.4  869.66  4928.4  859.96  4936.1     854    4949  847.02  4959.3  845.15
  4970.1  841.44  4972.1  840.94  4984.5  841.44  4990.2  844.77    5022  845.33
  5040.1     848  5045.4  847.02  5064.6  852.23    5070  850.87  5075.6     854
  5094.5  856.03  5120.3  855.51    5143  855.54  5178.9  854.14  5208.9  855.11
  5268.7  854.09  5279.4  852.48  5287.9  844.99  5293.3  842.99  5300.8  848.57
  5317.8  855.29  5579.7  855.51  5697.7  863.23  5740.6  868.06  5843.4  876.05
#Mann= 5 ,-1 , 0
  4794.4     .12       0  4970.1     .07       0  4984.5     .12       0
  5120.3     .05       0    5143     .12       0
Bank Sta=4959.3,4990.2
XS Rating Curve= 0 ,0
Exp/Cntr=0.3,0.1

Type RM Length L Ch R = 1 ,10558   ,107,107,107
BEGIN DESCRIPTION:
Cottonwood Creek 17.2
END DESCRIPTION:
XS GIS Cut Line= 3
      2254995.71      7188091.53      2254376.02      7187412.13
      2254263.63      7187215.67
#Sta/Elev= 30
  4551.5  864.33  4555.4  864.39  4628.1  859.79  4840.3  853.65  4911.2  855.03
  4925.4   854.4  4939.6  850.01  4946.4  850.32  4982.1  840.52  4988.9  840.57
  4989.1  838.98  4991.1  838.48  5003.5  838.98  5010.5  846.59  5017.3  848.13
  5024.7  851.54    5074  855.35    5095  855.09  5123.4  853.76    5145  849.04
  5151.7  849.74  5159.2  843.25  5165.9  841.94  5194.3  852.52  5289.4   854.7
    5299  854.69  5514.6  855.56  5588.7  859.54  5623.3  864.72  5697.4  871.88
#Mann= 6 ,-1 , 0
  4551.5     .05       0  4555.4     .12       0  4989.1     .07       0
  5003.5     .12       0  5289.4     .05       0    5299     .12       0
Bank Sta=4946.4,5017.3
XS Rating Curve= 0 ,0
Exp/Cntr=0.3,0.1

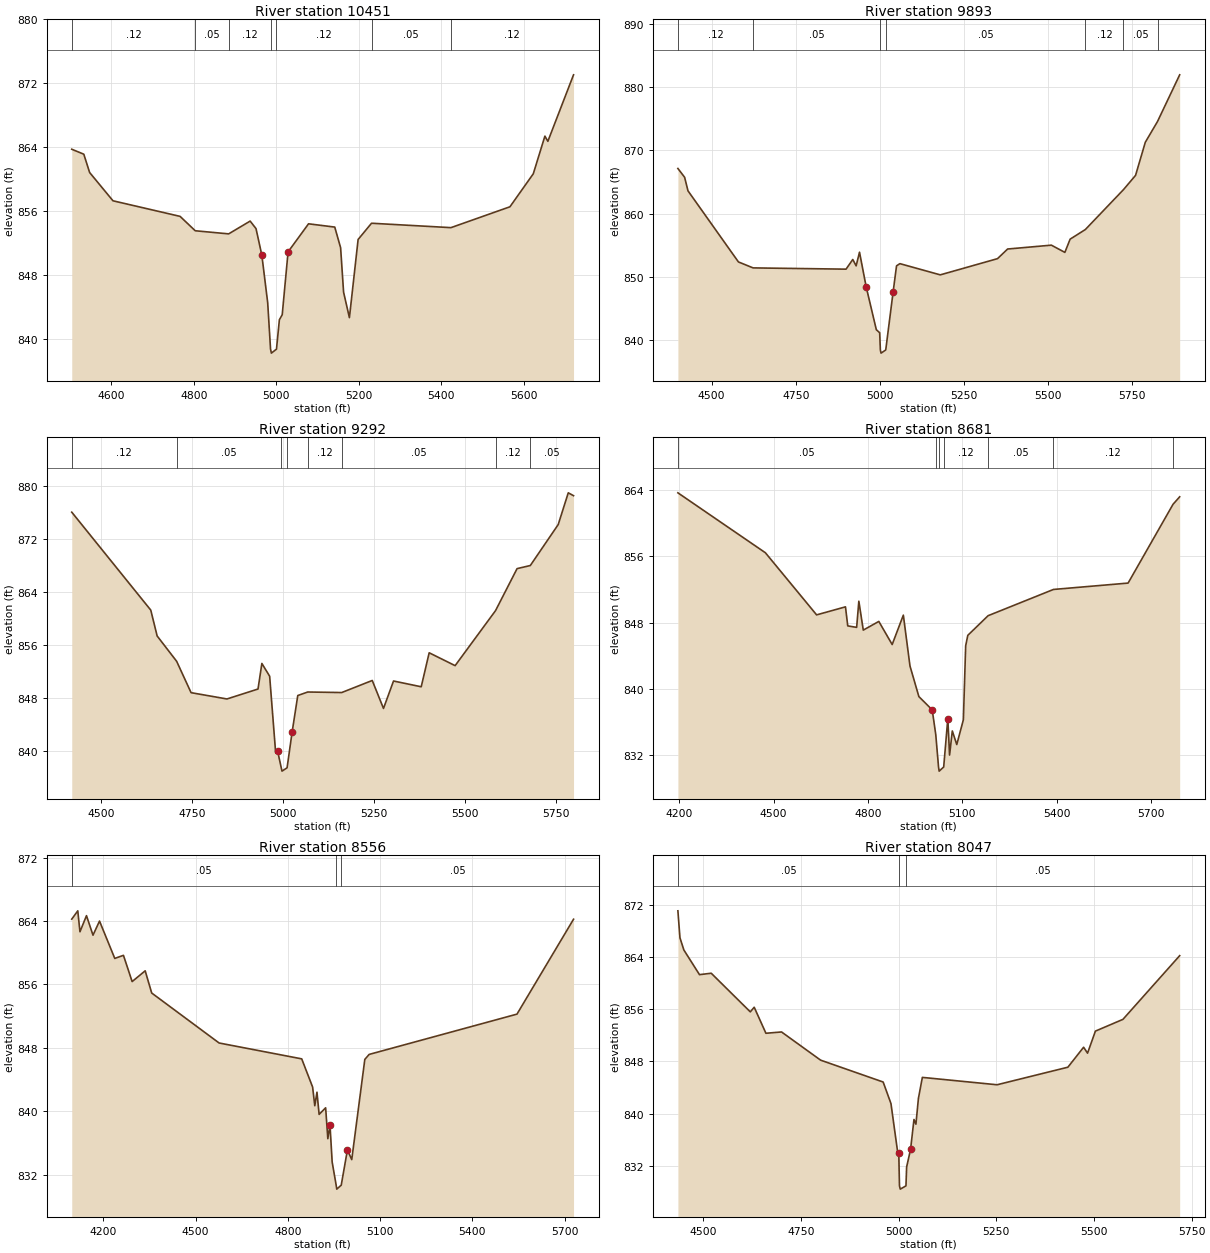
Type RM Length L Ch R = 1 ,10451   ,558,558,558
BEGIN DESCRIPTION:
Cottonwood Creek 17.1
END DESCRIPTION:
XS GIS Cut Line= 2
      2255125.24        7188065.      2254281.05      7187189.93
#Sta/Elev= 30
  4504.3  863.73  4533.5  863.11  4547.6  860.82  4604.2  857.28  4766.8  855.33
  4803.5  853.53  4884.5  853.14  4936.6  854.74  4950.8   853.8  4964.9  850.48
  4979.1  844.53    4986  838.72    4988  838.22  5000.4  838.72  5007.4  842.39
  5014.3  843.03  5028.5  850.89  5078.1   854.4  5141.6  853.99  5155.8  851.41
    5163  845.84  5177.1  842.66  5198.2  852.44  5230.7  854.47  5423.2  853.92
  5566.1  856.53  5622.7  860.66  5650.8  865.37    5658  864.72  5720.2  873.04
#Mann= 7 ,-1 , 0
  4504.3     .12       0  4803.5     .05       0  4884.5     .12       0
    4986     .07       0  5000.4     .12       0  5230.7     .05       0
  5423.2     .12       0
Bank Sta=4964.9,5028.5
XS Rating Curve= 0 ,0
Exp/Cntr=0.3,0.1

Type RM Length L Ch R = 1 ,9893    ,601,601,601
BEGIN DESCRIPTION:
Cottonwood Creek 17.0
END DESCRIPTION:
XS GIS Cut Line= 3
        2255229.      7188110.02        2255229.        7187510.
      2255268.33      7186618.89
#Sta/Elev= 30
  4399.6  867.16  4419.6  865.77  4429.6  863.63  4579.6   852.4  4623.2  851.46
  4899.6  851.26  4919.6  852.79  4929.6  851.78  4939.6  853.94  4959.6  848.43
  4989.6   841.7  4999.6  841.22  5001.6   838.5  5003.6     838  5017.6   838.5
  5039.7  847.72  5049.7  851.78  5059.7  852.13  5179.8  850.36    5350  852.92
    5380  854.44  5510.1  855.05  5550.2  853.91  5565.9     856  5611.2  857.52
  5724.5  863.82  5760.4  866.07  5789.4   871.3  5825.7  874.58  5891.6  881.95
#Mann= 7 ,-1 , 0
  4399.6     .12       0  4623.2     .05       0  5001.6    .033       0
  5017.6     .05       0  5611.2     .12       0  5724.5     .05       0
  5825.7     .12       0
Bank Sta=4959.6,5039.7
XS Rating Curve= 0 ,0
Exp/Cntr=0.3,0.1

Type RM Length L Ch R = 1 ,9292    ,611,611,611
BEGIN DESCRIPTION:
Cottonwood Creek 16.0
END DESCRIPTION:
XS GIS Cut Line= 3
      2255578.99      7188210.02      2255779.87      7187668.42
      2256161.59      7186963.49
#Sta/Elev= 30
  4419.7  876.08  4636.9   861.3  4654.4   857.4  4708.1  853.57  4747.7  848.84
  4846.3  847.89  4931.7  849.39  4942.3  853.25  4963.7  851.32  4980.1  839.83
  4985.4  840.07  4995.6   837.5  4997.6     837  5011.6   837.5  5025.5  842.91
    5041  848.41  5068.5  848.94  5161.8  848.86  5245.7  850.68  5276.6  846.46
  5304.2   850.6  5380.3  849.73  5402.2  854.86  5473.5  852.92  5584.6  861.22
  5643.8  867.56  5680.2  868.03  5756.9  874.21  5784.5     879    5799  878.57
#Mann= 8 ,-1 , 0
  4419.7     .12       0  4708.1     .05       0  4995.6    .033       0
  5011.6     .05       0  5068.5     .12       0  5161.8     .05       0
  5584.6     .12       0  5680.2     .05       0
Bank Sta=4985.4,5025.5
XS Rating Curve= 0 ,0
Exp/Cntr=0.3,0.1

Type RM Length L Ch R = 1 ,8681    ,125,125,125
BEGIN DESCRIPTION:
Cottonwood Creek 15.0
END DESCRIPTION:
XS GIS Cut Line= 3
      2255754.11      7188438.71      2256355.22      7187817.02
      2256852.53      7187281.49
#Sta/Elev= 30
  4195.6  863.68  4473.9  856.44  4636.7  848.94  4728.5  849.91  4735.7  847.61
    4764  847.43    4771  850.59  4785.1   847.1  4834.5  848.15    4877  845.36
  4912.5  848.91  4933.6  842.77  4961.9  839.07  5004.3  837.47  5015.6  834.48
  5024.4  830.57  5026.4  830.07  5040.8  830.57  5053.9  836.41  5059.5  832.01
  5068.2  834.92  5082.4  833.28  5103.4  836.28  5110.7  845.21  5117.5  846.47
    5182  848.84  5389.8  852.01  5627.2  852.78    5770  862.29  5791.2   863.2
#Mann= 7 ,-1 , 0
  4195.6     .05       0  5015.6     .12       0  5024.4    .033       0
  5040.8     .12       0    5182     .05       0  5389.8     .12       0
    5770     .05       0
Bank Sta=5004.3,5053.9
XS Rating Curve= 0 ,0
Exp/Cntr=0.3,0.1

Type RM Length L Ch R = 1 ,8556    ,509,509,509
BEGIN DESCRIPTION:
Cottonwood Creek 14.0
END DESCRIPTION:
XS GIS Cut Line= 3
      2255800.52      7188509.27      2256427.17      7187878.55
      2256944.29      7187345.32
#Sta/Elev= 30
  4097.4  864.23    4117  865.28  4124.1  862.64  4145.3  864.67  4166.5  862.21
  4187.7  863.99  4237.3  859.28  4265.5  859.67  4293.8  856.36  4336.2  857.72
  4357.4  854.92  4576.6  848.62  4845.3  846.62  4880.7  843.07  4887.8  840.71
  4894.9  842.42  4901.9  839.62  4923.1  840.45  4930.2  836.56  4937.3  838.28
  4944.3  833.62  4957.3   830.7  4959.3   830.2  4973.8   830.7  4993.9  835.14
    5008  833.92  5050.5  846.55  5064.6  847.18  5545.4  852.26  5729.3  864.22
#Mann= 3 ,-1 , 0
  4097.4     .05       0  4957.3    .033       0  4973.8     .05       0
Bank Sta=4937.3,4993.9
XS Rating Curve= 0 ,0
Exp/Cntr=0.3,0.1

Type RM Length L Ch R = 1 ,8047    ,516,516,516
BEGIN DESCRIPTION:
Cottonwood Creek 13.0
END DESCRIPTION:
XS GIS Cut Line= 3
      2256860.61       7188625.3        2256879.        7188060.
      2256963.64      7187345.69
#Sta/Elev= 30
  4434.5  871.07  4439.8  866.93  4449.8  865.07  4489.8  861.29  4519.8  861.51
  4619.9  855.59  4629.9   856.3  4659.9  852.31  4699.9  852.51    4800  848.19
  4960.1  844.84  4980.1  841.54  4997.6  833.95  5000.1  833.95  5001.9  828.93
  5003.9  828.43  5018.5  828.93  5020.2  831.82  5030.3  834.52    5039   839.1
    5044  838.38  5050.4  842.33  5060.5  845.55  5251.8  844.42  5433.1  847.11
  5473.4  850.17  5483.5  849.26  5503.6  852.64  5574.1  854.44  5719.4   864.2
#Mann= 3 ,-1 , 0
  4434.5     .05       0  5001.9    .033       0  5018.5     .05       0
Bank Sta=5000.1,5030.3
XS Rating Curve= 0 ,0
Exp/Cntr=0.3,0.1

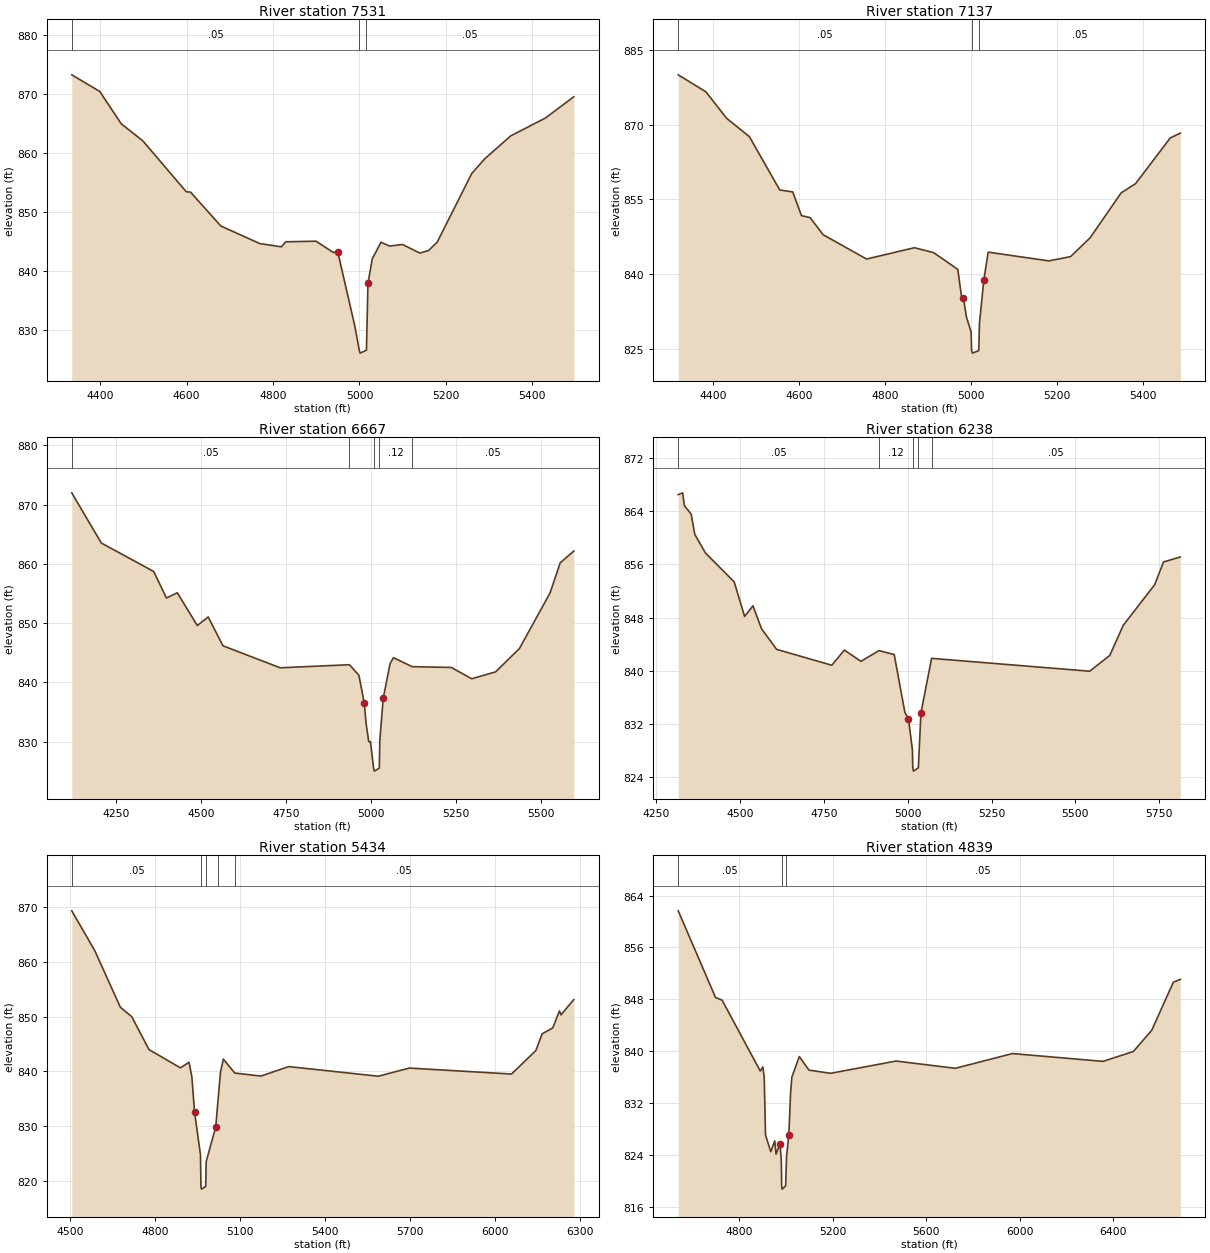
Type RM Length L Ch R = 1 ,7531    ,394,394,394
BEGIN DESCRIPTION:
Cottonwood Creek 12.0
END DESCRIPTION:
XS GIS Cut Line= 3
      2257415.79      7188674.48       2257378.3      7187998.79
      2257358.75      7187513.92
#Sta/Elev= 30
  4334.1  873.21  4398.7  870.41  4448.8  864.91  4498.8  862.03    4599  853.44
    4609  853.37  4679.1  847.64  4769.3  844.67  4819.3  844.12  4829.3  844.97
  4899.5  845.07  4939.5  843.16  4949.5  843.32  4989.6  830.59  4999.4  826.64
  5001.4  826.14  5016.1  826.64  5019.6  837.96  5029.6  842.08  5049.7  844.89
  5069.7  844.25  5099.7  844.51  5139.7  843.06  5159.7  843.49  5179.8   844.9
  5259.8  856.52  5289.9  859.01  5349.9  862.88    5430  865.89  5496.1   869.5
#Mann= 3 ,-1 , 0
  4334.1     .05       0  4999.4    .033       0  5016.1     .05       0
Bank Sta=4949.5,5019.6
XS Rating Curve= 0 ,0
Exp/Cntr=0.3,0.1

Type RM Length L Ch R = 1 ,7137    ,470,470,470
BEGIN DESCRIPTION:
Cottonwood Creek 11.0
END DESCRIPTION:
XS GIS Cut Line= 3
      2257657.12      7188733.71      2257756.89      7188059.34
      2257822.25      7187576.86
#Sta/Elev= 30
    4319     880  4383.4  876.59  4431.6  871.27  4484.5   867.6  4555.3  856.88
  4585.6  856.49  4605.8  851.73    4626  851.33  4656.3   847.9  4757.4  843.02
  4868.6  845.29  4913.4  844.31  4969.7  840.94  4977.9  835.77  4982.9  835.15
  4989.9  831.36  5000.7  828.38  5001.8  824.63  5003.8  824.13  5018.5  824.63
  5020.2  830.21  5030.3   838.8  5040.4   844.4  5181.7  842.65  5232.1   843.5
  5277.4  847.25  5349.9   856.3  5383.5  858.16  5464.2  867.33  5487.6  868.29
#Mann= 3 ,-1 , 0
    4319     .05       0  5001.8    .033       0  5018.5     .05       0
Bank Sta=4982.9,5030.3
XS Rating Curve= 0 ,0
Exp/Cntr=0.3,0.1

Type RM Length L Ch R = 1 ,6667    ,429,429,429
BEGIN DESCRIPTION:
Cottonwood Creek 10.0
END DESCRIPTION:
XS GIS Cut Line= 3
      2257909.25      7189042.54        2258179.        7188210.
        2258179.      7187610.05
#Sta/Elev= 30
  4120.2  872.01    4207  863.54    4361  858.73  4398.3  854.26  4430.3  855.14
    4489  849.61    4521  851.06  4564.4  846.19  4732.6  842.48  4935.9     843
  4963.8  841.22  4979.4  836.59  4984.8  833.16  4992.7  830.01  4997.8  830.01
    5007  825.54    5009  825.04  5023.7  825.54  5025.3  830.35  5035.3  837.33
  5055.3  843.17  5065.3  844.19  5120.3  842.67  5235.3  842.54  5295.3  840.63
  5365.3  841.79  5435.3  845.72  5525.3   855.1  5555.3   860.2  5595.3  862.19
#Mann= 5 ,-1 , 0
  4120.2     .05       0  4935.9     .12       0    5007     .07       0
  5023.7     .12       0  5120.3     .05       0
Bank Sta=4979.4,5035.3
XS Rating Curve= 0 ,0
Exp/Cntr=0.3,0.1

Type RM Length L Ch R = 1 ,6238    ,804,804,804
BEGIN DESCRIPTION:
Cottonwood Creek 9.0
END DESCRIPTION:
XS GIS Cut Line= 3
      2258299.17      7189056.39      2258587.49      7188253.86
        2258629.      7187610.04
#Sta/Elev= 30
    4315  866.53  4328.2   866.8  4333.5  864.85  4353.6  863.59  4364.3  860.55
  4396.2  857.73  4481.8  853.39    4513  848.17    4538  849.77  4563.4  846.32
  4608.7   843.2  4773.2  840.81  4810.6   843.1    4860   841.4  4913.9  843.02
  4959.3  842.42  4991.2  833.71  5001.8  832.75  5013.7  828.02  5014.7  825.35
  5016.7  824.85  5031.4  825.35  5039.1  833.63  5070.9  841.85  5542.4  839.91
  5602.5  842.29  5642.6  846.82  5736.5  852.96  5762.8  856.38  5812.9  857.13
#Mann= 5 ,-1 , 0
    4315     .05       0  4913.9     .12       0  5014.7     .07       0
  5031.4     .12       0  5070.9     .05       0
Bank Sta=5001.8,5039.1
XS Rating Curve= 0 ,0
Exp/Cntr=0.3,0.1

Type RM Length L Ch R = 1 ,5434    ,595,595,595
BEGIN DESCRIPTION:
Cottonwood Creek 8.0
END DESCRIPTION:
XS GIS Cut Line= 3
      2258941.01      7189349.83      2259034.42      7188707.24
      2258584.01      7187677.26
#Sta/Elev= 30
  4505.4  869.32  4586.1  862.11    4677  851.72  4717.4  849.98  4778.1  843.98
  4889.2  840.64  4919.5  841.66  4929.6  839.02    4939   832.6    4960  824.78
  4961.7  818.99  4963.7  818.49  4978.5  818.99  4980.2  823.51  5014.1  829.88
  5020.2  833.64  5030.7  839.84  5040.8  842.23  5081.1  839.69  5173.6  839.14
  5271.8  840.87  5588.3  839.11  5697.4   840.6  6058.7  839.51  6144.9  843.81
  6166.8  846.85  6204.5  847.94  6227.9  851.03  6233.4  850.32  6278.9  853.12
#Mann= 5 ,-1 , 0
  4505.4     .05       0  4961.7    .033       0  4978.5     .05       0
  5020.2     .12       0  5081.1     .05       0
Bank Sta=4939,5014.1
XS Rating Curve= 0 ,0
Exp/Cntr=0.3,0.1

Type RM Length L Ch R = 1 ,4839    ,426,426,426
BEGIN DESCRIPTION:
Cottonwood Creek 7.0
END DESCRIPTION:
XS GIS Cut Line= 3
      2259322.37      7189514.56      2259557.68      7189033.61
      2258633.44      7187715.72
#Sta/Elev= 30
  4540.9  861.65  4700.1   848.3  4728.2  847.89  4891.3  836.96  4902.2   837.6
  4908.2  836.05  4913.8  827.11  4936.3  824.53  4953.3   826.2  4958.8  824.16
  4975.8  825.75  4981.3  823.12  4982.8  819.26  4984.8  818.76  4999.7  819.26
  5003.8  823.84  5013.5  827.13  5020.8  833.47  5026.3  836.01  5058.1  839.19
  5099.6   837.1    5192  836.61  5471.8   838.5  5724.6  837.38  5968.6  839.65
  6355.6  838.45  6485.4  839.97  6563.9  843.24  6656.3  850.65    6686  851.08
#Mann= 3 ,-1 , 0
  4540.9     .05       0  4982.8    .033       0  4999.7     .05       0
Bank Sta=4975.8,5013.5
XS Rating Curve= 0 ,0
Exp/Cntr=0.3,0.1

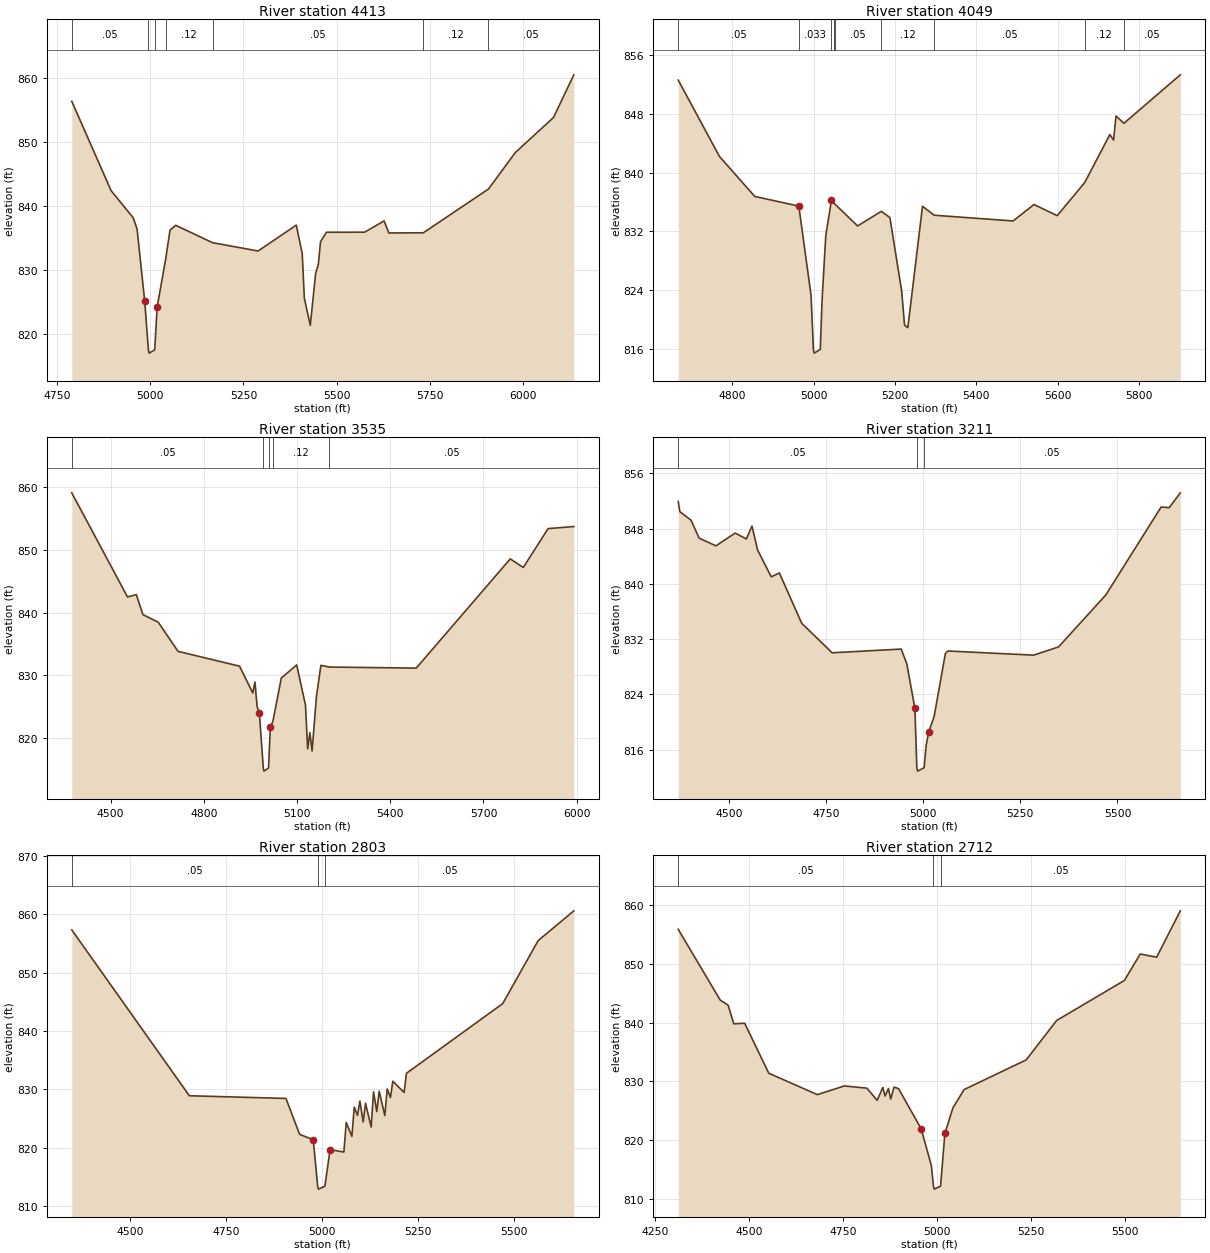
Type RM Length L Ch R = 1 ,4413    ,364,364,364
BEGIN DESCRIPTION:
Cottonwood Creek 6.0
END DESCRIPTION:
XS GIS Cut Line= 3
      2259829.01      7189509.97        2259879.        7189310.
       2260440.6      7188316.92
#Sta/Elev= 30
  4789.3  856.32  4894.9  842.39  4954.2  838.17  4964.5  836.42  4985.1  825.14
  4994.9  817.59  4996.9  817.09  5011.8  817.59  5018.4   824.3  5041.2  831.71
  5052.9  836.25  5068.3     837  5167.1  834.29  5289.2     833  5391.7  837.03
  5407.6  832.59  5413.3  825.63  5429.2  821.42  5443.5  829.46  5450.9  830.95
  5456.6  834.42  5472.5  835.92    5575  835.93  5627.3  837.69  5639.9  835.81
  5732.4  835.83  5907.3  842.65  5979.2  848.33  6081.7  853.79  6136.3  860.44
#Mann= 7 ,-1 , 0
  4789.3     .05       0  4994.9    .033       0  5011.8     .05       0
  5041.2     .12       0  5167.1     .05       0  5732.4     .12       0
  5907.3     .05       0
#XS Ineff= 2 , 0
       0                  5391.7       0  837.03
Permanent Ineff=
       F       F
Bank Sta=4985.1,5018.4
XS Rating Curve= 0 ,0
Exp/Cntr=0.3,0.1

Type RM Length L Ch R = 1 ,4049    ,514,514,514
BEGIN DESCRIPTION:
Cottonwood Creek 5.3
END DESCRIPTION:
XS GIS Cut Line= 2
      2260022.04      7189714.45      2260701.67      7188683.99
#Sta/Elev= 30
  4666.9   852.6  4768.1  842.22    4855  836.77  4963.4  835.45  4993.5  823.29
  4999.2  815.94  5001.2  815.44  5016.1  815.94  5020.6  822.74  5029.7  831.46
  5043.6  836.23  5050.9  835.79  5051.6  835.75  5107.9  832.75  5166.1  834.74
  5187.3  833.89  5216.3  823.87  5223.3  819.24  5231.4  818.91  5267.5  835.43
  5296.1  834.21  5490.3  833.43  5541.5  835.67  5598.7  834.15  5666.3  838.66
  5728.1  845.19  5737.2  844.44  5743.2  847.71  5762.6  846.72  5901.3  853.32
#Mann= 9 ,-1 , 0
  4666.9     .05       0  4963.4    .033       0  5043.6     .05       0
  5050.9     .12       0  5051.6     .05       0  5166.1     .12       0
  5296.1     .05       0  5666.3     .12       0  5762.6     .05       0
Bank Sta=4963.4,5043.6
XS Rating Curve= 0 ,0
Exp/Cntr=0.3,0.1

Type RM Length L Ch R = 1 ,3535    ,324,324,324
BEGIN DESCRIPTION:
Cottonwood Creek 5.2
END DESCRIPTION:
XS GIS Cut Line= 3
      2260209.87       7190074.6       2260820.2      7189465.76
      2261434.56      7189029.12
#Sta/Elev= 30
  4375.1   859.1  4554.5  842.48  4582.8  842.86    4604  839.67  4653.5  838.45
  4717.1   833.8  4915.1  831.44  4957.6  827.16  4964.6  828.91  4971.7  824.95
  4978.8  823.98  4991.5  815.19  4993.5  814.69  5008.4  815.19  5014.1  821.72
  5022.6  822.68  5049.5  829.55    5099  831.63  5127.3  825.21  5134.3  818.25
  5141.4  820.84  5148.5   817.9  5162.6  826.62  5176.8  831.57  5203.7   831.3
  5483.7  831.13  5786.3  848.56  5828.1  847.19    5908  853.39  5990.9  853.72
#Mann= 5 ,-1 , 0
  4375.1     .05       0  4991.5    .033       0  5008.4     .05       0
  5022.6     .12       0  5203.7     .05       0
Bank Sta=4978.8,5014.1
XS Rating Curve= 0 ,0
Exp/Cntr=0.3,0.1

Type RM Length L Ch R = 1 ,3211    ,408,408,408
BEGIN DESCRIPTION:
Cottonwood Creek 5.1
END DESCRIPTION:
XS GIS Cut Line= 2
      2260532.66      7190249.75      2261342.65       7189243.7
#Sta/Elev= 30
    4370  851.94  4374.1  850.46  4402.9  849.23  4423.7  846.63  4466.9  845.51
  4516.5  847.36  4545.3  846.51  4559.7  848.38  4574.1  844.92  4609.3  841.02
  4630.1  841.59  4687.6   834.3    4766  830.02  4943.6  830.56    4958  828.42
  4978.8  821.98  4983.8  813.38  4985.8  812.88  5002.6  813.38  5007.6  816.56
    5014  818.49  5028.4  820.81  5057.2   829.9  5063.6  830.28  5284.3  829.68
  5348.3  830.87  5469.9  838.39  5612.2  851.13  5633.1  851.05  5661.6  853.19
#Mann= 3 ,-1 , 0
    4370     .05       0  4983.8    .033       0  5002.6     .05       0
Bank Sta=4978.8,5014
XS Rating Curve= 0 ,0
Exp/Cntr=0.3,0.1

Type RM Length L Ch R = 1 ,2803    ,91,91,91
BEGIN DESCRIPTION:
Cottonwood Creek 5.0
END DESCRIPTION:
XS GIS Cut Line= 3
      2260741.21      7190330.98      2261312.96      7189921.79
      2261804.42      7189567.04
#Sta/Elev= 30
    4347  857.35  4653.6  828.89  4905.5  828.43  4941.1  822.27  4976.7  821.34
  4988.2  813.37  4990.2  812.87    5007  813.37  5020.6  819.65  5056.5  819.23
  5062.7   824.3  5077.4  821.93  5083.6  826.94  5092.1  825.54  5098.3  827.98
  5106.8   824.4    5113  827.59  5127.7  823.53  5133.9  829.57  5142.4  826.16
  5148.6  829.67  5163.3   825.5  5169.5  830.06    5178  828.59  5184.2  831.38
  5213.6  829.46  5219.7  832.74  5470.7   844.7  5563.3  855.52  5656.2  860.62
#Mann= 3 ,-1 , 0
    4347     .05       0  4988.2    .033       0    5007     .05       0
Bank Sta=4976.7,5020.6
XS Rating Curve= 0 ,0
Exp/Cntr=0.3,0.1

Type RM Length L Ch R = 1 ,2712    ,386,386,386
BEGIN DESCRIPTION:
Cottonwood Creek 4.1
END DESCRIPTION:
XS GIS Cut Line= 2
      2260782.22      7190367.75      2261891.27       7189624.8
#Sta/Elev= 30
  4311.7  855.83  4423.3  843.81  4444.3  842.95  4459.3  839.78  4488.4  839.87
  4552.4  831.38  4681.5  827.74  4753.5  829.22  4813.3  828.84  4840.6  826.77
  4855.6  828.97  4861.6   827.5  4870.6  828.78  4876.6  826.99  4885.6  829.02
  4897.6  828.75  4957.6  821.93  4984.7  815.69  4990.3  812.18  4992.3  811.68
  5009.1  812.18  5020.7  821.15    5042  825.48  5071.7   828.6  5236.8  833.64
  5317.8  840.34    5498  847.15    5540  851.64  5583.7   851.1  5646.6  858.98
#Mann= 3 ,-1 , 0
  4311.7     .05       0  4990.3    .033       0  5009.1     .05       0
Bank Sta=4957.6,5020.7
XS Rating Curve= 0 ,0
Exp/Cntr=0.3,0.1