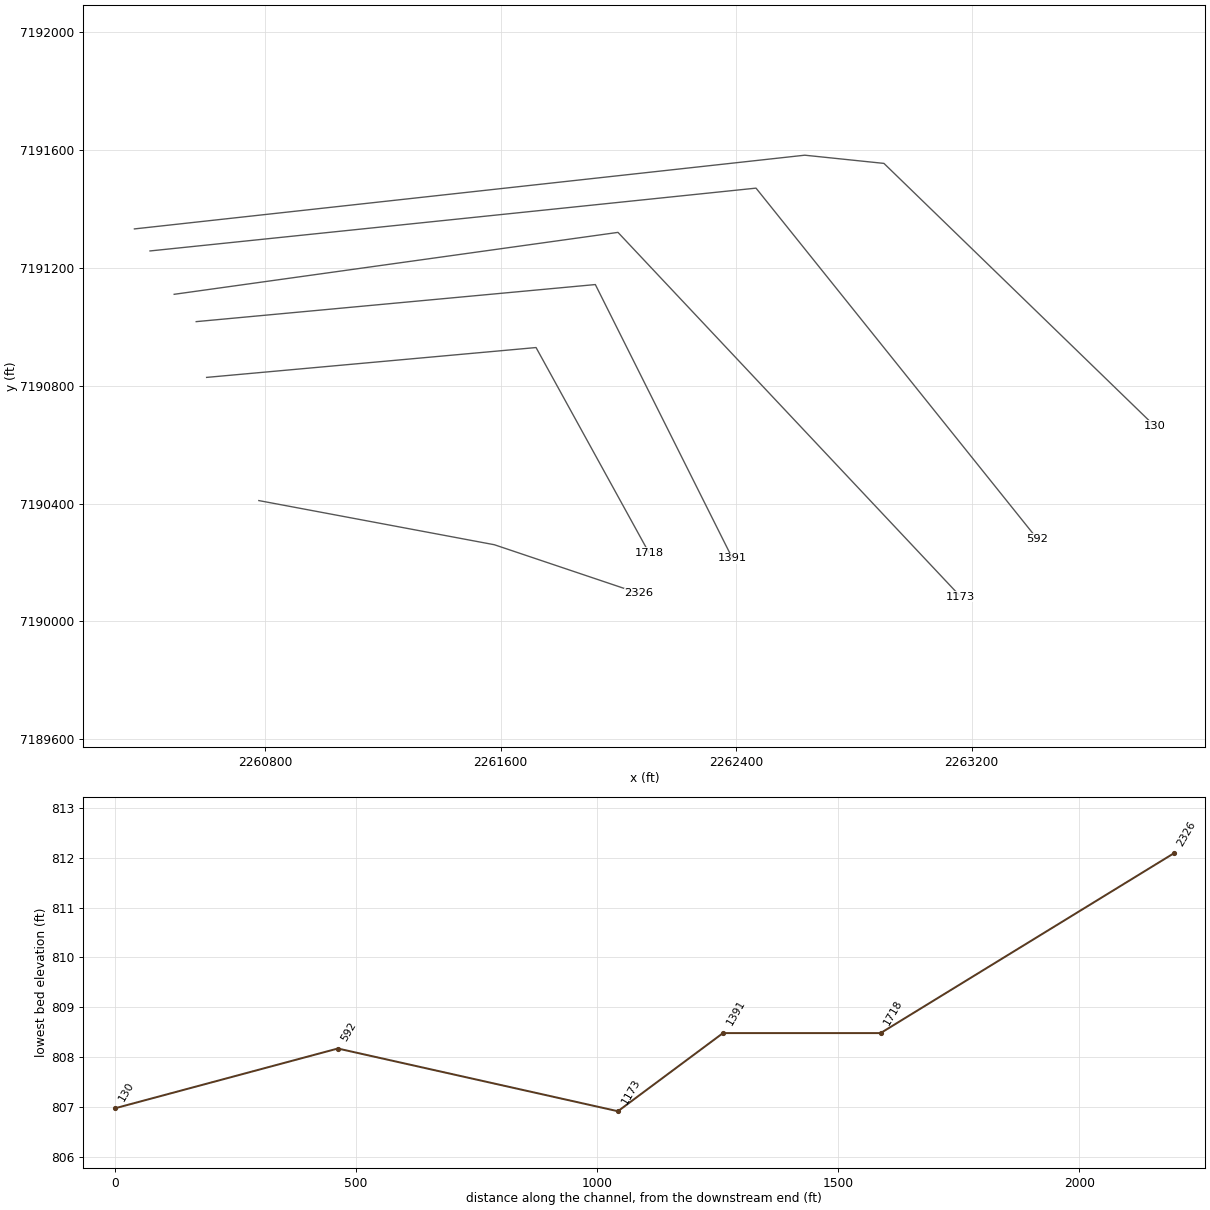
HEC-RAS study Cottonwood Creek.prj: Cottonwood Creek Base Level Engineering

--- Cottonwood Creek.g01 (geometry) --- (continued)

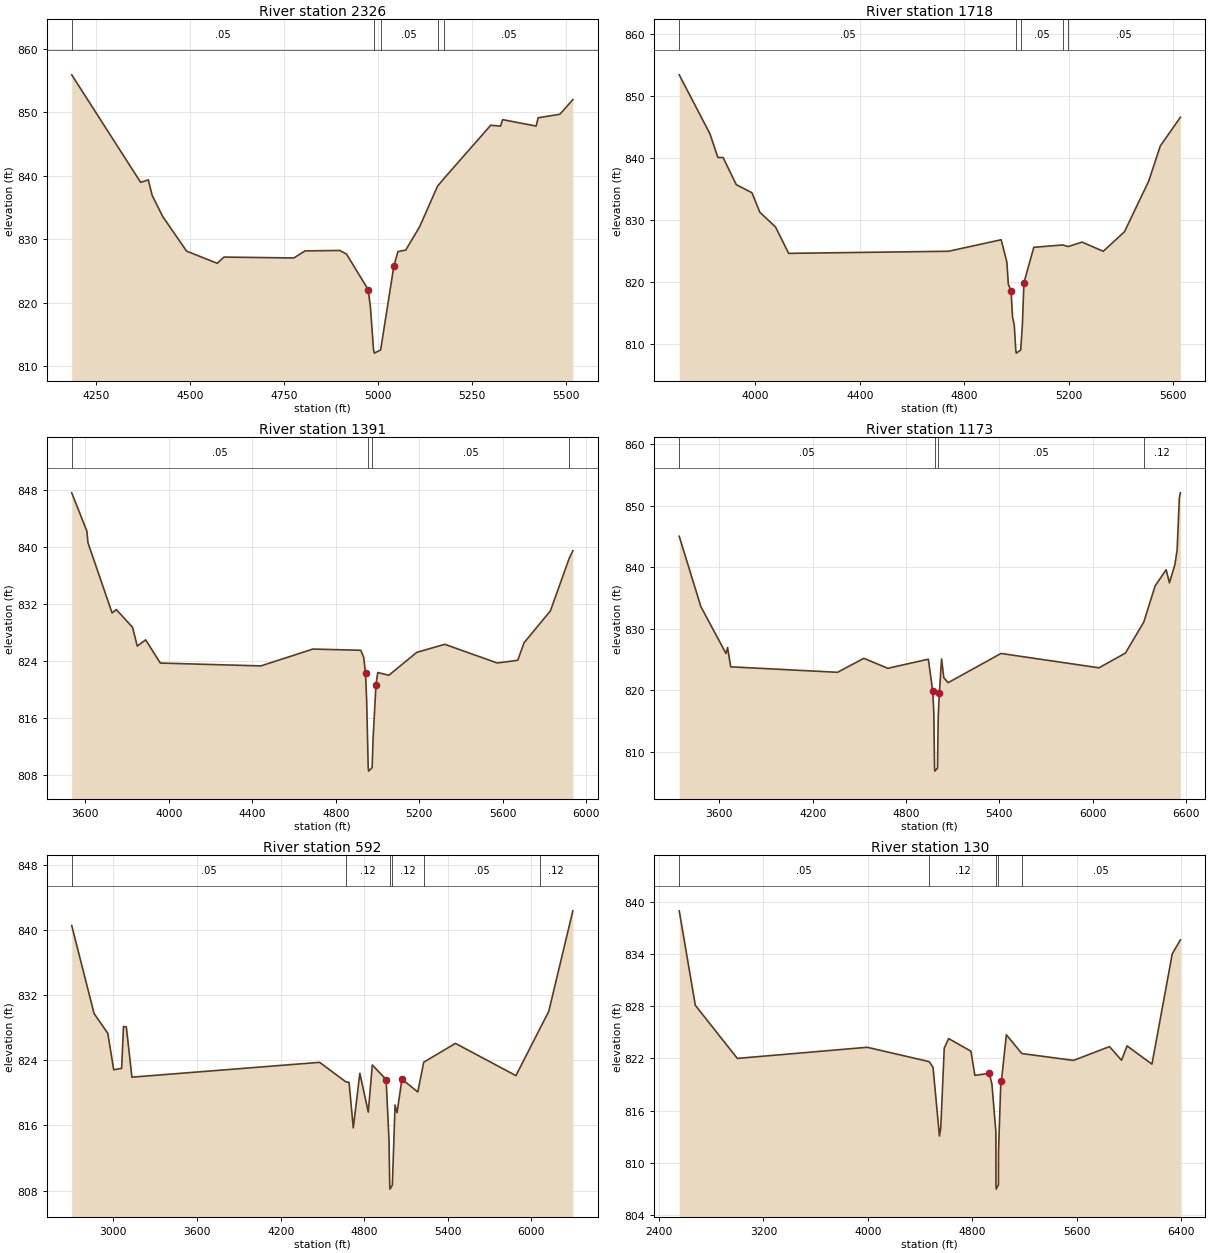
Type RM Length L Ch R = 1 ,2326    ,608,608,608
BEGIN DESCRIPTION:
Cottonwood Creek 4.0
END DESCRIPTION:
XS GIS Cut Line= 3
      2260778.95      7190410.01        2261579.        7190260.
      2262069.49      7190094.97
#Sta/Elev= 30
  4185.6  855.87  4368.8  838.95  4389.1  839.35  4399.3  836.91  4427.3  833.59
  4490.9  828.13  4572.3  826.22  4590.1   827.2  4775.8  827.06  4805.4  828.17
  4897.8  828.24  4915.7  827.68  4973.3  822.08  4979.2  819.38  4987.6  812.59
  4989.6  812.09  5006.4  812.59  5041.6   825.8  5052.3  828.06  5073.1   828.3
  5109.9  831.96  5157.6  838.36  5175.1  839.59  5298.9  847.94  5325.1   847.8
  5330.4  848.82  5419.6  847.81  5424.9  849.11  5482.7  849.67  5517.1  851.96
#Mann= 5 ,-1 , 0
  4185.6     .05       0  4987.6    .033       0  5006.4     .05       0
  5157.6     .12       0  5175.1     .05       0
Bank Sta=4973.3,5041.6
XS Rating Curve= 0 ,0
Exp/Cntr=0.3,0.1

Type RM Length L Ch R = 1 ,1718    ,327,327,327
BEGIN DESCRIPTION:
Cottonwood Creek 3.0
END DESCRIPTION:
XS GIS Cut Line= 3
       2260601.6      7190828.42      2261720.62      7190929.82
      2262104.33      7190232.65
#Sta/Elev= 30
  3708.3  853.45  3826.2   843.9  3856.3  840.09  3876.4  840.08  3926.6  835.71
  3986.8   834.4    4017  831.25  4077.2  828.86  4127.4   824.6  4739.9  824.94
  4941.4   826.8  4963.2  823.18  4968.9   819.6  4979.2  818.59  4984.9  814.31
  4991.5  813.03  4997.3  808.98  4999.3  808.48  5016.2  808.98  5022.8  813.24
  5028.5  819.84  5066.4  825.58  5177.6  825.96  5198.1   825.7    5251  826.42
  5332.4  824.94  5413.8   828.1  5506.7   836.3  5550.8  841.95  5627.7  846.59
#Mann= 5 ,-1 , 0
  3708.3     .05       0  4997.3    .033       0  5016.2     .05       0
  5177.6     .12       0  5198.1     .05       0
Bank Sta=4979.2,5028.5
XS Rating Curve= 0 ,0
Exp/Cntr=0.3,0.1

Type RM Length L Ch R = 1 ,1391    ,218,218,218
BEGIN DESCRIPTION:
Cottonwood Creek 2.0
END DESCRIPTION:
XS GIS Cut Line= 3
      2260566.21      7191017.84      2261922.02      7191143.78
       2262387.6      7190213.98
#Sta/Elev= 30
  3534.4  847.65  3607.2  842.25  3612.2  840.63    3728  830.74  3748.1  831.22
  3825.8  828.73  3848.5  826.08  3888.7  826.96    3959  823.69  4441.1  823.29
  4690.1  825.66  4919.9  825.49  4933.8  824.48  4942.3  822.26  4947.9  818.36
  4955.2  808.98  4957.2  808.48  4974.1  808.98  4978.6  813.07  4992.6  820.67
  5000.9  822.36    5054  821.97  5188.1   825.2  5322.2  826.33  5573.7   823.7
  5671.9  824.08  5702.2  826.55  5828.5  831.04  5917.9  838.39  5935.9   839.5
#Mann= 4 ,-1 , 0
  3534.4     .05       0  4955.2    .033       0  4974.1     .05       0
  5917.9     .12       0
Bank Sta=4942.3,4992.6
XS Rating Curve= 0 ,0
Exp/Cntr=0.3,0.1

Type RM Length L Ch R = 1 ,1173    ,581,581,581
BEGIN DESCRIPTION:
Cottonwood Creek 1.2
END DESCRIPTION:
XS GIS Cut Line= 3
      2260491.34      7191110.67      2261998.89      7191321.01
      2263162.28      7190084.13
#Sta/Elev= 30
  3342.7  845.03  3481.7  833.61  3643.2     826  3653.3  826.98  3673.5  823.84
  4360.1  822.95  4529.3  825.22  4683.2   823.6  4943.5  825.08  4971.8  819.85
  4978.7  816.36  4983.4  807.41  4985.4  806.91  5002.3  807.41    5007  815.76
  5014.3  819.62  5028.5  825.11  5042.7  822.08    5071  821.27  5410.4  826.01
    6040  823.68  6209.9  826.07  6327.8   831.1  6400.9  836.99  6471.7   839.6
  6492.7  837.48  6527.9  840.44  6542.1   842.8  6556.3  851.18  6562.9  852.08
#Mann= 4 ,-1 , 0
  3342.7     .05       0  4983.4    .033       0  5002.3     .05       0
  6327.8     .12       0
Bank Sta=4971.8,5014.3
XS Rating Curve= 0 ,0
Exp/Cntr=0.3,0.1

Type RM Length L Ch R = 1 ,592     ,462,462,462
BEGIN DESCRIPTION:
Cottonwood Creek 1.1
END DESCRIPTION:
XS GIS Cut Line= 3
      2260409.29      7191257.96      2262467.84      7191471.31
      2263422.81      7190280.38
#Sta/Elev= 30
  2700.9  840.56  2861.3  829.75  2960.1  827.31  3002.2  822.84  3058.9  823.01
  3072.6  828.16  3092.7  828.11  3132.9  821.93  4480.1  823.75  4668.5  821.35
  4691.2  821.29  4721.4   815.7  4768.5  822.41  4829.1  817.64  4857.9  823.43
  4957.1  821.64  4977.9  814.18  4982.9  808.67  4984.9  808.17  5001.8  808.67
  5021.1   818.5  5035.5  817.56  5070.7  821.69  5184.3  820.11    5227  823.77
  5454.8  826.08  5888.5  822.12  6058.8  827.83  6123.8  829.99    6297  842.37
#Mann= 6 ,-1 , 0
  2700.9     .05       0  4668.5     .12       0  4982.9     .07       0
  5001.8     .12       0    5227     .05       0  6058.8     .12       0
Bank Sta=4957.1,5070.7
XS Rating Curve= 0 ,0
Exp/Cntr=0.3,0.1

Type RM Length L Ch R = 1 ,130     ,0,0,0
BEGIN DESCRIPTION:
Cottonwood Creek 1.0
END DESCRIPTION:
XS GIS Cut Line= 4
      2260356.33       7191332.8      2262633.34      7191583.19
      2262902.31      7191555.36       2263821.1      7190664.23
#Sta/Elev= 30
  2554.3  838.99  2677.7  828.12  2999.6  822.01  3995.6  823.29  4469.8  821.64
  4499.6     821  4548.9  813.08    4559  814.06  4585.6  823.19  4619.3  824.29
  4790.4  822.84  4820.5  820.06  4931.2  820.29  4951.3  819.02  4981.4  813.53
    4982  807.47    4984  806.97  5000.9  807.47  5001.5  811.31  5019.2  819.22
  5024.2  819.45  5061.8  824.73  5180.2  822.57  5576.5  821.78  5852.3  823.37
  5944.4   821.8  5986.8  823.45  6177.7  821.35  6333.3  834.04  6395.4  835.65
#Mann= 5 ,-1 , 0
  2554.3     .05       0  4469.8     .12       0    4982     .07       0
  5000.9     .12       0  5180.2     .05       0
Bank Sta=4931.2,5024.2
XS Rating Curve= 0 ,0
Exp/Cntr=0.3,0.1

Chan Stop Cuts=-1
Use User Specified Reach Order=0
Composite Channel Slope=5