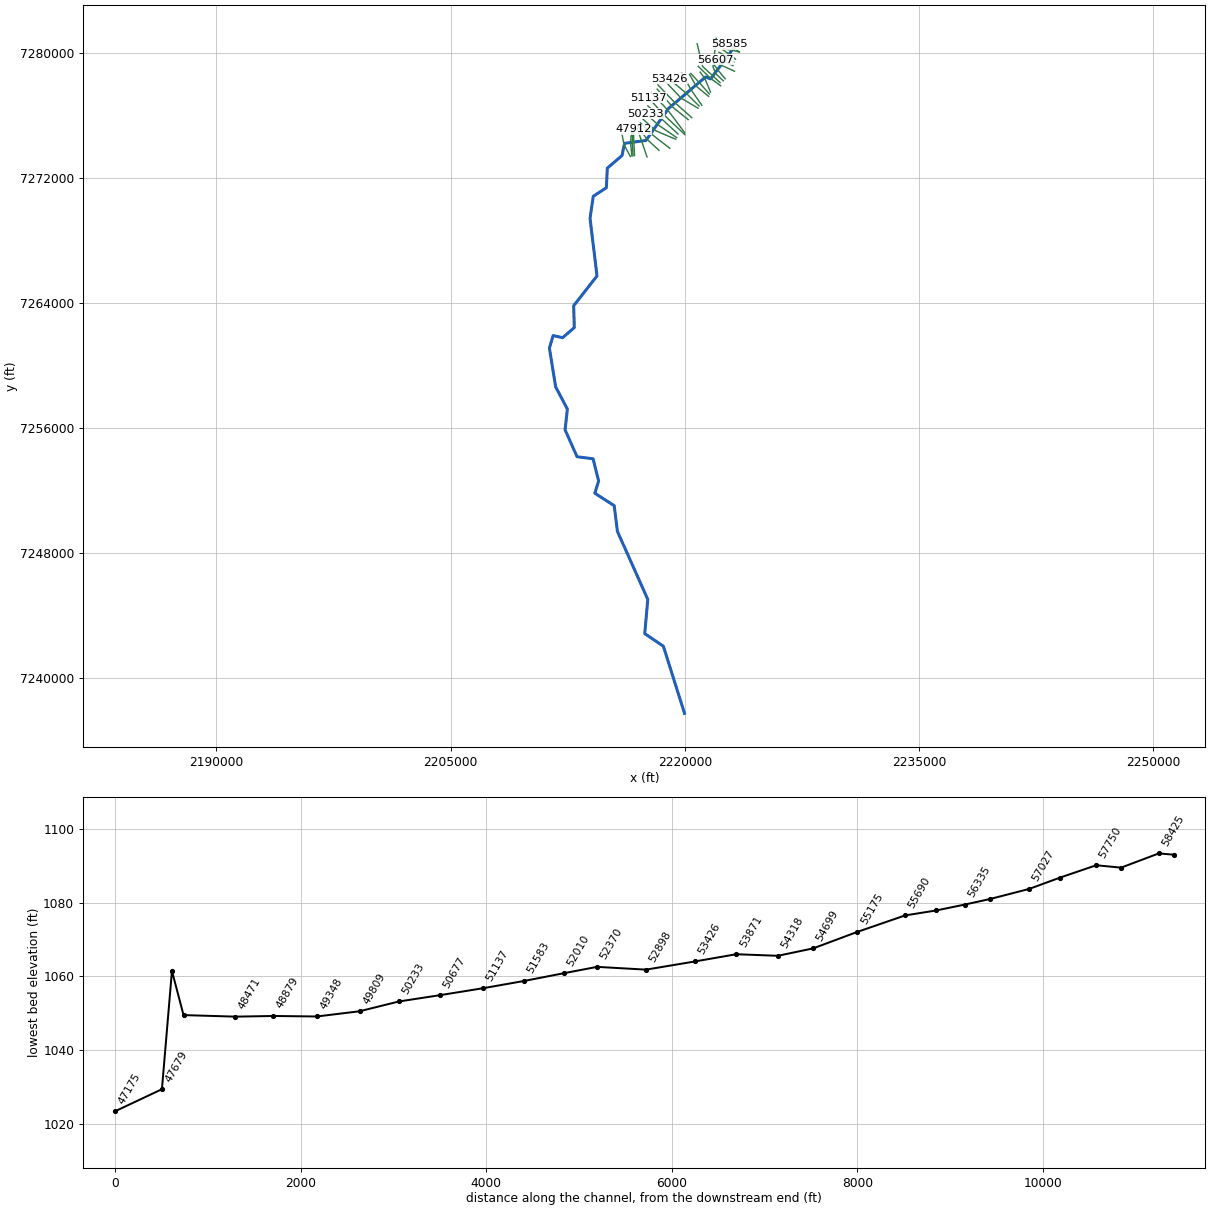
--- DRY VALLEY CREEK.prj (project) ---

Proj Title=DRY VALLEY CREEK Base Level Engineering
Current Plan=p01
Default Exp/Contr=0.3,0.1
English Units
Geom File=g01
Flow File=f01
Plan File=p01
Y Axis Title=Elevation
X Axis Title(PF)=Main Channel Distance
X Axis Title(XS)=Station
BEGIN DESCRIPTION:
DRY VALLEY CREEK
END DESCRIPTION:
DSS Export Rating Curves= 0
DSS Export Rating Curve Sorted= 0
DSS Export Volume Flow Curves= 0
DXF OffsetX= 0
DXF OffsetY= 0
DXF ScaleX= 1
DXF ScaleY= 10

--- DRY VALLEY CREEK.p01 (plan) ---

Plan Title=Multiple Run
Short Identifier=Multiple
Geom File=g01
Flow File=f01
Subcritical Flow
K Sum by GR= 0
Std Step Tol= 0.01
Critical Tol= 0.01
Num of Std Step Trials= 20
Max Error Tol= 0.3
Flow Tol Ratio= 0.001
Split Flow NTrial= 30
Split Flow Tol= 0.02
Split Flow Ratio= 0.02
Log Output Level= 0
Friction Slope Method= 1
Unsteady Friction Slope Method= 2
Unsteady Bridges Friction Slope Method= 1
Parabolic Critical Depth
Global Vel Dist=  1 , 1 , 1
Global Log Level= 0
CheckData=True
Encroach Param= -1, 0, 0, 0
BEGIN DESCRIPTION:
Multiple Run
END DESCRIPTION:

--- DRY VALLEY CREEK.f01 (steady flow) ---

Flow Title=Multiple
Program Version=4.10
Number of Profiles= 7
Profile Names=10-year,25-year,50-year,1pct_min,100-year,1pct_plu,500-year
River Rch & RM=DRY VALLEY CREEK,Reach-1         ,58585
     976    1401    1768    1108    2211    4411    3468
River Rch & RM=DRY VALLEY CREEK,Reach-1         ,55175
    1209    1738    2196    1375    2743    5473    4296
River Rch & RM=DRY VALLEY CREEK,Reach-1         ,45419
    2281    3371    4336    2759    5505   10983    8907
River Rch & RM=DRY VALLEY CREEK,Reach-1         ,44709
    2281    3371    4336    2759    5505   10983    8907
River Rch & RM=DRY VALLEY CREEK,Reach-1         ,38446
    2425    3591    4626    2946    5878   11729    9532
River Rch & RM=DRY VALLEY CREEK,Reach-1         ,35256
    2552    3774    4857    3090    6165   12300    9971
River Rch & RM=DRY VALLEY CREEK,Reach-1         ,29740
    3862    5799    7540    4840    9657   19268   15906
River Rch & RM=DRY VALLEY CREEK,Reach-1         ,27268
    4143    6227    8101    5202   10379   20708   17103
River Rch & RM=DRY VALLEY CREEK,Reach-1         ,26325
    4143    6227    8101    5202   10379   20708   17103
River Rch & RM=DRY VALLEY CREEK,Reach-1         ,23548
    4246    6378    8294    5323   10621   21191   17483
River Rch & RM=DRY VALLEY CREEK,Reach-1         ,19666
    4356    6540    8503    5455   10884   21716   17902
River Rch & RM=DRY VALLEY CREEK,Reach-1         ,18630
    4407    6620    8608    5523   11020   21988   18134
River Rch & RM=DRY VALLEY CREEK,Reach-1         ,15366
    4691    7045    9160    5875   11723   23390   19274
River Rch & RM=DRY VALLEY CREEK,Reach-1         ,8842
    6746   10237   13407    8655   17270   34458   28756
River Rch & RM=DRY VALLEY CREEK,Reach-1         ,2765
    7054   10704   14018    9049   18054   36023   30051
Boundary for River Rch & Prof#=DRY VALLEY CREEK,Reach-1         , 1
Up Type= 0
Dn Type= 3
Dn Slope=0.0033
Boundary for River Rch & Prof#=DRY VALLEY CREEK,Reach-1         , 2
Up Type= 0
Dn Type= 3
Dn Slope=0.0033
Boundary for River Rch & Prof#=DRY VALLEY CREEK,Reach-1         , 3
Up Type= 0
Dn Type= 3
Dn Slope=0.0033
Boundary for River Rch & Prof#=DRY VALLEY CREEK,Reach-1         , 4
Up Type= 0
Dn Type= 3
Dn Slope=0.0033
Boundary for River Rch & Prof#=DRY VALLEY CREEK,Reach-1         , 5
Up Type= 0
Dn Type= 3
Dn Slope=0.0033
Boundary for River Rch & Prof#=DRY VALLEY CREEK,Reach-1         , 6
Up Type= 0
Dn Type= 3
Dn Slope=0.0033
Boundary for River Rch & Prof#=DRY VALLEY CREEK,Reach-1         , 7
Up Type= 0
Dn Type= 3
Dn Slope=0.0033
DSS Import GetInterval= 0
DSS Import GetPeak= 0
DSS Import FillOption= 0

--- DRY VALLEY CREEK.g01 (geometry) ---

Geom Title=Existing Conditions
Program Version=4.10

River Reach=DRY VALLEY CREEK,Reach-1
Reach XY= 30
        2223129.        7280310.      2221649.12      7278329.28
      2221322.55      7278452.36      2218948.43      7276430.64
      2217502.34      7274383.06       2216137.5      7274206.45
      2215976.42      7273418.48      2215034.84      7272612.29
      2214975.55      7271361.25      2214134.46      7270812.44
       2213929.2       7269394.9      2214376.83      7265715.97
      2212882.74      7263808.48      2212921.19      7262403.81
      2212177.48      7261763.74      2211565.52      7261897.13
      2211329.07      7261089.97        2211729.        7258610.
      2212478.05      7257194.04      2212332.83      7255861.58
      2213098.61      7254139.75      2214125.39       7254008.5
      2214479.23      7252585.07      2214236.69      7251803.52
      2215475.25      7251008.45      2215682.55      7249361.47
      2217626.92      7245004.22      2217431.24      7242815.93
      2218623.55      7242012.47        2219979.        7237710.

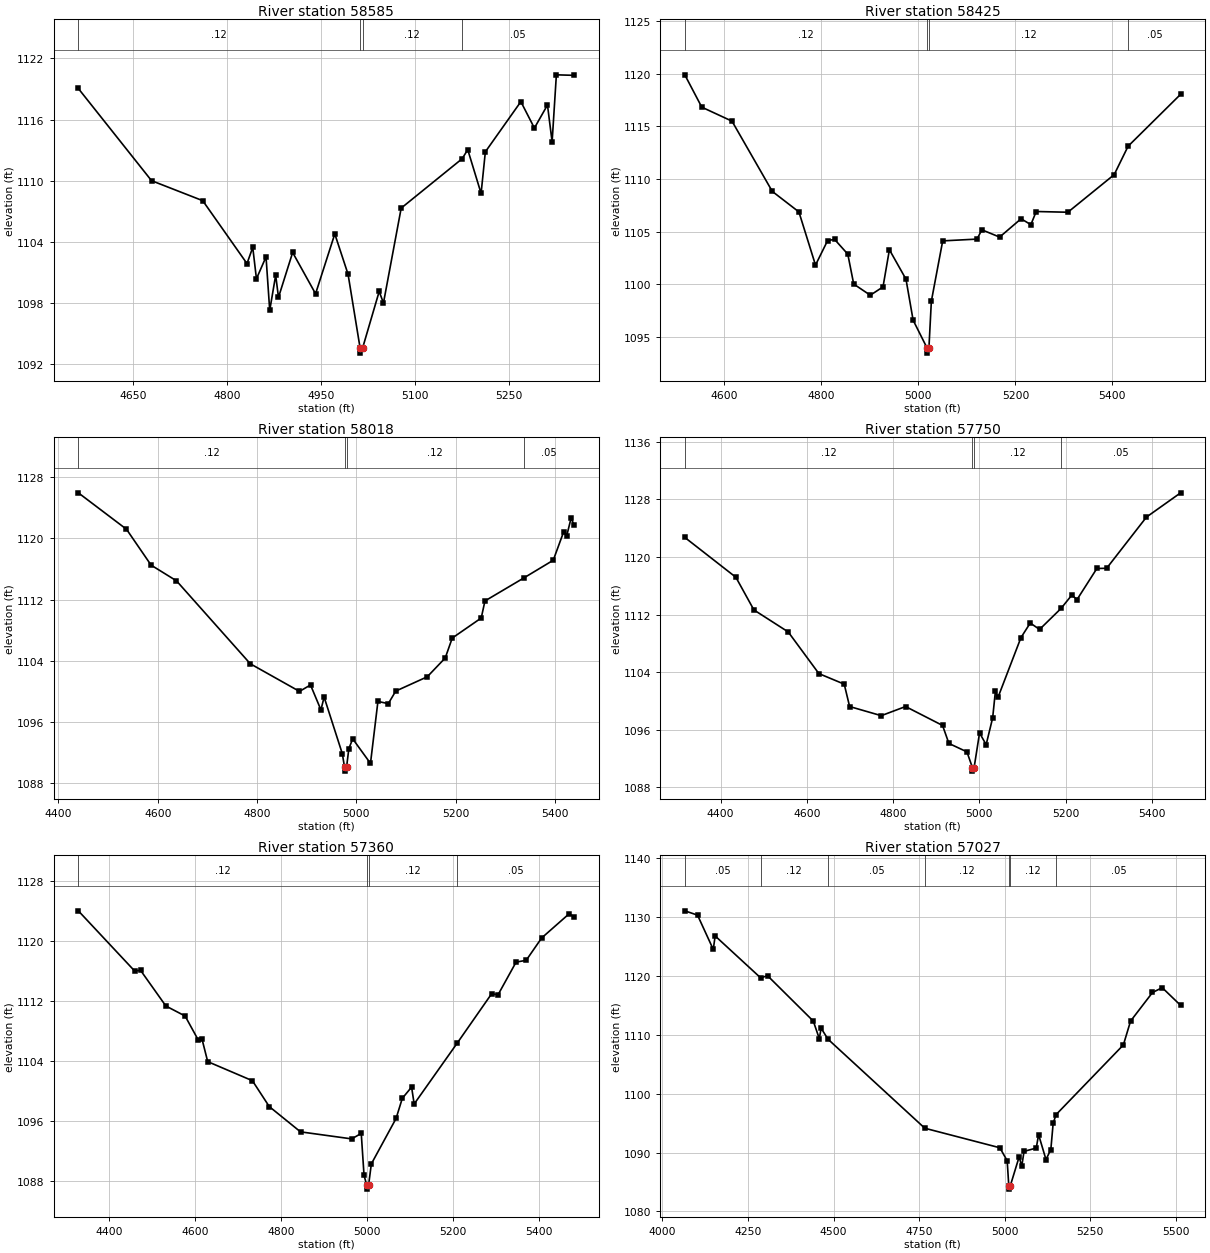
Type RM Length L Ch R = 1 ,58585   ,160,160,160
BEGIN DESCRIPTION:
DRY VALLEY CREEK 114.5
END DESCRIPTION:
XS GIS Cut Line= 3
      2223487.55      7280065.91      2223101.92      7280306.35
      2222854.27      7280535.28
#Sta/Elev= 30
  4562.5 1119.05  4679.4 1110.01  4761.1 1108.05  4831.8 1101.88    4841 1103.47
  4846.9 1100.39  4862.2 1102.54  4868.1 1097.29  4877.6 1100.74  4882.1 1098.57
  4904.7 1102.97  4941.3 1098.92    4972 1104.79  4993.2 1100.83  5012.4  1093.6
  5012.7  1093.1  5016.4  1093.6  5042.9 1099.15  5049.7 1098.01    5078 1107.32
  5175.3 1112.16  5184.3 1113.05  5205.6 1108.76  5212.4 1112.84  5269.1 1117.76
  5290.7 1115.17  5311.6 1117.43    5319 1113.81  5325.8 1120.39  5354.2 1120.34
#Mann= 4 ,-1 , 0
  4562.5     .12       0  5012.4     .07       0  5016.4     .12       0
  5175.3     .05       0
Bank Sta=5012.4,5016.4
XS Rating Curve= 0 ,0
Exp/Cntr=0.3,0.1

Type RM Length L Ch R = 1 ,58425   ,407,407,407
BEGIN DESCRIPTION:
DRY VALLEY CREEK 114.0
END DESCRIPTION:
XS GIS Cut Line= 3
      2223492.75      7280042.47      2223034.42      7280170.08
      2222493.38      7280248.11
#Sta/Elev= 30
  4518.3 1119.88  4553.3 1116.81  4615.6 1115.48  4698.7 1108.81  4753.6 1106.86
  4787.8 1101.81  4812.8 1104.14  4827.2 1104.25  4854.4 1102.85  4866.6 1100.01
  4900.8 1098.95    4927 1099.74  4940.2 1103.27  4974.4 1100.47  4989.1 1096.58
  5017.7 1093.95    5018 1093.45  5021.7 1093.95  5026.7 1098.38  5050.1 1104.11
  5120.8 1104.28  5130.9 1105.16  5167.5 1104.47  5211.7 1106.21  5231.9 1105.65
  5242.9  1106.9  5308.2 1106.83  5403.7  1110.4  5432.4  1113.1  5540.7 1118.03
#Mann= 4 ,-1 , 0
  4518.3     .12       0  5017.7     .07       0  5021.7     .12       0
  5432.4     .05       0
Bank Sta=5017.7,5021.7
XS Rating Curve= 0 ,0
Exp/Cntr=0.3,0.1

Type RM Length L Ch R = 1 ,58018   ,268,268,268
BEGIN DESCRIPTION:
DRY VALLEY CREEK 113.0
END DESCRIPTION:
XS GIS Cut Line= 3
      2223242.76      7279586.74      2222807.86      7279938.31
      2222444.12      7280185.13
#Sta/Elev= 30
    4440 1125.95    4537 1121.19  4586.6  1116.5  4637.7 1114.45  4786.4 1103.61
  4885.5    1100  4907.7 1100.84  4928.7 1097.58  4935.1 1099.26  4971.8 1091.85
  4976.3 1090.08  4976.5 1089.58  4980.3 1090.08  4984.9 1092.51  4992.7  1093.8
  5028.5 1090.59  5043.5 1098.69  5064.4  1098.4  5079.4 1100.04  5142.9 1101.91
  5179.1 1104.37  5193.2 1106.97  5251.6 1109.59  5259.1 1111.82    5337 1114.81
  5396.7 1117.14  5417.8 1120.88  5423.8 1120.34  5432.7 1122.66  5438.8 1121.69
#Mann= 4 ,-1 , 0
    4440     .12       0  4976.3     .07       0  4980.3     .12       0
    5337     .05       0
Bank Sta=4976.3,4980.3
XS Rating Curve= 0 ,0
Exp/Cntr=0.3,0.1

Type RM Length L Ch R = 1 ,57750   ,390,390,390
BEGIN DESCRIPTION:
DRY VALLEY CREEK 112.0
END DESCRIPTION:
XS GIS Cut Line= 3
      2223138.59      7279404.45        2222579.        7279810.
      2222180.22      7280037.28
#Sta/Elev= 30
  4316.8 1122.72  4435.3 1117.18  4477.1 1112.64  4556.7 1109.58  4627.8 1103.79
  4686.6 1102.32  4699.1 1099.21  4772.5 1097.94  4828.9 1099.21  4914.7 1096.58
  4929.4 1094.08  4971.2 1092.91  4983.9 1090.73  4984.1 1090.23  4987.9 1090.73
  5000.5 1095.54  5015.8 1093.91  5030.9 1097.64  5037.4 1101.41  5043.2 1100.47
  5096.5 1108.79  5118.1 1110.82  5139.7 1109.93  5189.4 1112.84  5214.6 1114.71
  5226.6 1114.08  5272.6  1118.4  5295.3 1118.43  5387.7 1125.55  5466.9 1128.92
#Mann= 4 ,-1 , 0
  4316.8     .12       0  4983.9     .07       0  4987.9     .12       0
  5189.4     .05       0
Bank Sta=4983.9,4987.9
XS Rating Curve= 0 ,0
Exp/Cntr=0.3,0.1

Type RM Length L Ch R = 1 ,57360   ,333,333,333
BEGIN DESCRIPTION:
DRY VALLEY CREEK 111.0
END DESCRIPTION:
XS GIS Cut Line= 3
      2223078.67      7279175.29      2222482.34      7279472.16
      2222076.08        7279743.
#Sta/Elev= 30
  4328.5 1124.04  4459.5 1116.01  4473.4 1116.09  4532.3 1111.33  4577.1 1109.99
  4607.4 1106.82  4616.3 1106.94  4629.7  1103.9  4733.8 1101.35    4773  1097.9
  4845.8 1094.52  4964.9 1093.58  4987.2 1094.31  4993.7  1088.7  5000.2 1087.37
  5000.5 1086.87  5004.2 1087.37  5010.7 1090.24  5068.3 1096.31  5082.8    1099
  5104.4  1100.5  5110.4 1098.24  5210.6 1106.37  5290.7 1112.96  5305.7 1112.83
  5347.7 1117.19  5371.2 1117.43  5407.3 1120.42  5470.9 1123.63  5482.9 1123.25
#Mann= 4 ,-1 , 0
  4328.5     .12       0  5000.2     .07       0  5004.2     .12       0
  5210.6     .05       0
Bank Sta=5000.2,5004.2
XS Rating Curve= 0 ,0
Exp/Cntr=0.3,0.1

Type RM Length L Ch R = 1 ,57027   ,420,420,420
BEGIN DESCRIPTION:
DRY VALLEY CREEK 110.0
END DESCRIPTION:
XS GIS Cut Line= 3
       2223178.7       7278819.9        2222329.        7279210.
       2221980.8      7279588.14
#Sta/Elev= 30
  4065.4 1131.09  4102.6 1130.36  4148.6 1124.53  4154.1 1126.82  4287.2 1119.69
  4307.1 1120.07  4440.9 1112.35  4458.4 1109.38  4463.9 1111.13  4483.9 1109.27
  4766.8 1094.14  4986.1 1090.82  5007.5 1088.62  5012.3 1084.29  5012.5 1083.79
  5016.3 1084.29  5042.6  1089.3    5050 1087.65  5056.8 1090.21  5092.5 1090.77
  5099.3 1093.05  5120.9 1088.82  5135.1 1090.52  5141.9 1094.99  5150.5 1096.46
  5347.1  1108.3  5368.1 1112.35  5432.2 1117.21  5460.6 1118.03  5514.4 1115.02
#Mann= 7 ,-1 , 0
  4065.4     .05       0  4287.2     .12       0  4483.9     .05       0
  4766.8     .12       0  5012.3     .07       0  5016.3     .12       0
  5150.5     .05       0
Bank Sta=5012.3,5016.3
XS Rating Curve= 0 ,0
Exp/Cntr=0.3,0.1

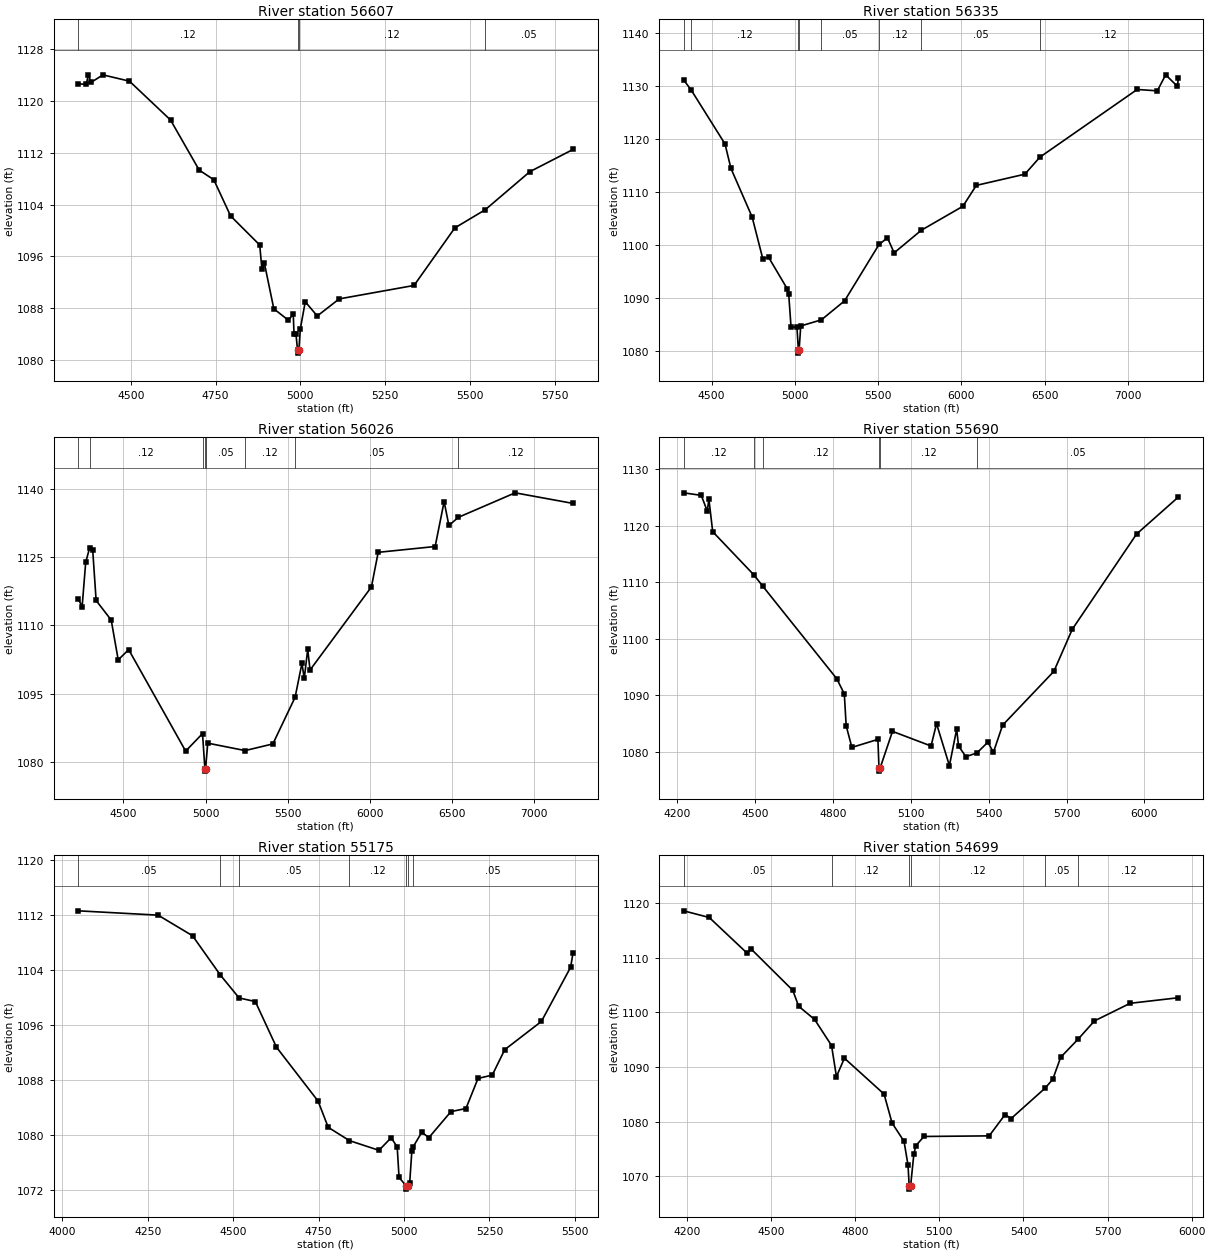
Type RM Length L Ch R = 1 ,56607   ,272,272,272
BEGIN DESCRIPTION:
DRY VALLEY CREEK 109.0
END DESCRIPTION:
XS GIS Cut Line= 4
      2222579.77      7278338.12      2222171.79      7278828.57
      2221899.39      7279191.76       2221941.6      7279556.38
#Sta/Elev= 30
  4345.2 1122.69  4368.5 1122.59    4375 1124.07  4382.8  1122.9    4418 1124.06
  4496.1 1123.09  4617.2 1117.09  4701.8 1109.34  4744.8 1107.86  4794.2 1102.27
  4880.2 1097.77  4886.7 1094.03    4894 1094.95  4921.8 1087.91  4964.8 1086.14
  4979.1 1087.09  4981.4 1083.94  4987.2 1083.94  4991.7 1081.56  4991.9 1081.06
  4995.7 1081.56  4999.9  1084.8  5014.5    1089  5049.9  1086.8  5114.5 1089.44
  5335.3 1091.52  5455.5 1100.41  5545.2 1103.22    5677 1109.11  5804.2 1112.54
#Mann= 4 ,-1 , 0
  4345.2     .12       0  4991.7     .07       0  4995.7     .12       0
  5545.2     .05       0
Bank Sta=4991.7,4995.7
XS Rating Curve= 0 ,0
Exp/Cntr=0.3,0.1

Type RM Length L Ch R = 1 ,56335   ,309,309,309
BEGIN DESCRIPTION:
DRY VALLEY CREEK 108.0
END DESCRIPTION:
XS GIS Cut Line= 4
      2222458.22      7278207.94        2221979.        7278660.
      2221802.29      7279098.68      2222005.31      7280925.91
#Sta/Elev= 30
  4332.3 1131.08  4378.3 1129.14  4580.7    1119  4616.3 1114.39  4743.6 1105.22
  4807.2 1097.39  4842.4 1097.63  4955.7  1091.6    4963 1090.75  4977.1  1084.5
  5012.7 1084.43  5021.4 1080.05  5021.7 1079.55  5025.4 1080.05  5035.4 1084.67
  5159.5 1085.83  5298.6 1089.41  5505.4 1100.04  5555.9 1101.29  5596.2 1098.46
    5759 1102.72  6008.7 1107.24  6089.2 1111.18  6380.5 1113.29  6471.3 1116.51
  7055.1 1129.27  7175.8 1129.01  7226.1 1132.03  7296.6 1129.86  7302.5 1131.52
#Mann= 8 ,-1 , 0
  4332.3     .05       0  4378.3     .12       0  5021.4     .07       0
  5025.4     .12       0  5159.5     .05       0  5505.4     .12       0
    5759     .05       0  6471.3     .12       0
Bank Sta=5021.4,5025.4
XS Rating Curve= 0 ,0
Exp/Cntr=0.3,0.1

Type RM Length L Ch R = 1 ,56026   ,336,336,336
BEGIN DESCRIPTION:
DRY VALLEY CREEK 107.0
END DESCRIPTION:
XS GIS Cut Line= 4
      2222254.27       7278091.8      2221685.68      7278616.98
      2221138.34      7279122.45      2220786.66      7280572.66
#Sta/Elev= 30
  4225.6 1115.78  4249.1 1114.13  4270.7 1123.82  4294.3 1126.97  4313.2 1126.64
  4334.2 1115.45    4426 1111.15  4468.6  1102.4  4532.3 1104.65  4879.1 1082.34
  4981.7 1086.19  4996.2 1078.44  4996.4 1077.94  5000.2 1078.44  5013.5 1084.09
  5240.8 1082.46  5409.8 1083.92  5545.2 1094.18  5586.8 1101.64  5600.9 1098.32
  5621.9 1104.71  5636.1 1100.17  6009.7 1118.43  6050.8 1126.04  6397.5 1127.32
  6452.1 1137.19  6481.1 1131.95  6539.1 1133.74  6884.3 1139.12  7236.9 1136.79
#Mann= 8 ,-1 , 0
  4225.6     .05       0  4294.3     .12       0  4981.7     .05       0
  4996.2    .033       0  5000.2     .05       0  5240.8     .12       0
  5545.2     .05       0  6539.1     .12       0
Bank Sta=4996.2,5000.2
XS Rating Curve= 0 ,0
Exp/Cntr=0.3,0.1

Type RM Length L Ch R = 1 ,55690   ,515,515,515
BEGIN DESCRIPTION:
DRY VALLEY CREEK 106.0
END DESCRIPTION:
XS GIS Cut Line= 3
       2222293.3      7277887.83      2221663.98      7278352.22
      2220853.18      7279132.67
#Sta/Elev= 30
  4223.8 1125.86    4292 1125.41    4315 1122.61  4321.2 1124.77  4335.9 1118.98
  4495.1 1111.31  4528.8 1109.34    4814 1092.96  4843.3 1090.27  4850.5 1084.61
  4872.5 1080.79  4972.8 1082.21    4977 1077.09  4977.2 1076.59    4981 1077.09
    5029 1083.63  5177.7 1081.04  5198.8 1084.99  5248.5 1077.57  5276.5 1084.01
  5283.7 1081.04    5312 1079.15  5354.6 1079.81  5396.9 1081.72    5418 1079.91
  5453.5 1084.72  5651.3 1094.26  5722.1  1101.7  5969.8 1118.55  6131.3 1125.12
#Mann= 6 ,-1 , 0
  4223.8     .12       0  4495.1     .05       0  4528.8     .12       0
    4977     .07       0    4981     .12       0  5354.6     .05       0
Bank Sta=4977,4981
XS Rating Curve= 0 ,0
Exp/Cntr=0.3,0.1

Type RM Length L Ch R = 1 ,55175   ,476,476,476
BEGIN DESCRIPTION:
DRY VALLEY CREEK 105.0
END DESCRIPTION:
XS GIS Cut Line= 3
      2221640.84      7277484.06        2221279.        7278360.
      2220979.02      7278759.98
#Sta/Elev= 30
    4047 1112.64  4280.6 1112.01  4381.3 1109.01  4462.5  1103.3  4517.6 1099.95
    4565 1099.43  4626.9 1092.78  4748.6 1084.93  4778.3 1081.11  4840.5 1079.17
  4926.8 1077.76  4962.3 1079.59  4980.1 1078.26  4985.5 1073.82  5005.9 1072.61
  5006.4 1072.11  5010.6 1072.61  5016.6 1072.97  5022.9 1077.63  5026.1 1078.22
    5052 1080.38  5072.9 1079.62  5137.4  1083.4  5181.2 1083.85  5216.6 1088.23
  5258.3 1088.72  5294.7 1092.42    5402 1096.53  5487.4 1104.41  5494.7 1106.53
#Mann= 7 ,-1 , 0
    4047     .05       0  4462.5     .12       0  4517.6     .05       0
  4840.5     .12       0  5005.9     .07       0  5010.6     .12       0
  5026.1     .05       0
Bank Sta=5005.9,5010.6
XS Rating Curve= 0 ,0
Exp/Cntr=0.3,0.1

Type RM Length L Ch R = 1 ,54699   ,381,381,381
BEGIN DESCRIPTION:
DRY VALLEY CREEK 104.0
END DESCRIPTION:
XS GIS Cut Line= 3
      2221562.67      7277364.34      2221026.25      7277978.89
      2220381.24       7278675.9
#Sta/Elev= 30
  4187.4 1118.58  4278.9 1117.36  4413.7 1110.84  4427.9 1111.61    4577 1104.02
  4597.9 1101.11  4654.8 1098.69  4715.2 1093.92  4732.7 1088.23  4761.1  1091.6
  4902.6 1085.03  4931.1 1079.74  4973.8 1076.38    4988 1072.06  4992.3 1068.13
  4992.8 1067.63  4997.1 1068.13    5009 1074.09  5016.3 1075.59  5044.7 1077.27
  5277.7 1077.38  5334.4 1081.28  5355.9 1080.55  5477.7 1086.14  5504.5 1087.74
  5532.8 1091.77  5595.9 1095.14  5653.1 1098.42  5780.6 1101.65  5952.8 1102.67
#Mann= 6 ,-1 , 0
  4187.4     .05       0  4715.2     .12       0  4992.3     .07       0
  4997.1     .12       0  5477.7     .05       0  5595.9     .12       0
Bank Sta=4992.3,4997.1
XS Rating Curve= 0 ,0
Exp/Cntr=0.3,0.1

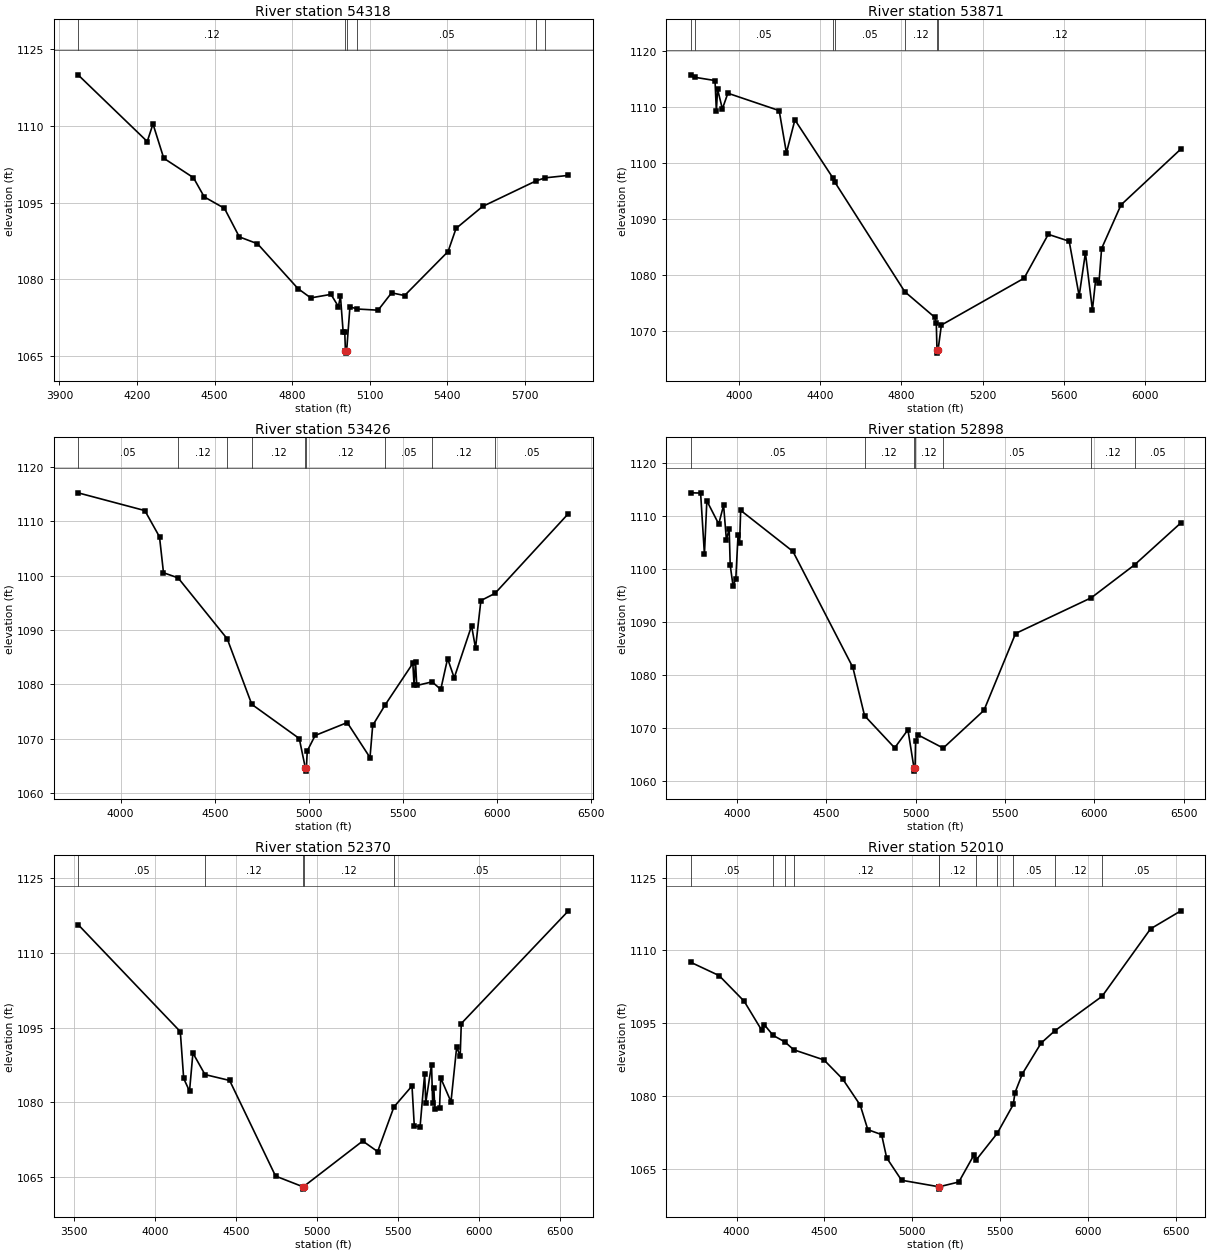
Type RM Length L Ch R = 1 ,54318   ,447,447,447
BEGIN DESCRIPTION:
DRY VALLEY CREEK 103.0
END DESCRIPTION:
XS GIS Cut Line= 3
      2221524.53      7277208.47        2220729.        7277860.
      2220300.57       7278614.7
#Sta/Elev= 30
  3972.2 1119.93  4239.7 1106.91  4261.9 1110.34  4303.6 1103.65  4418.4 1099.85
    4460 1096.11  4538.3 1093.87  4595.7  1088.3    4666 1086.96  4822.5 1078.21
    4872 1076.39  4950.2 1077.08  4978.9  1074.7  4986.8 1076.72  4997.2 1069.78
  5003.4 1069.78    5006 1066.11  5006.6 1065.61  5010.8 1066.11  5023.5 1074.65
  5052.5 1074.22  5132.4 1073.99  5184.5 1077.38  5234.8 1076.85  5402.9 1085.44
  5433.8 1089.95  5536.2 1094.23  5744.8 1099.27  5779.2 1099.83  5868.3  1100.3
#Mann= 6 ,-1 , 0
  3972.2     .12       0    5006     .07       0  5010.8     .12       0
  5052.5     .05       0  5744.8     .12       0  5779.2     .05       0
Bank Sta=5006,5010.8
XS Rating Curve= 0 ,0
Exp/Cntr=0.3,0.1

Type RM Length L Ch R = 1 ,53871   ,445,445,445
BEGIN DESCRIPTION:
DRY VALLEY CREEK 102.0
END DESCRIPTION:
XS GIS Cut Line= 3
      2221086.99      7276640.81        2220379.        7277660.
      2219810.98      7278692.84
#Sta/Elev= 30
  3759.3 1115.68  3780.5 1115.24  3880.1 1114.66  3886.7 1109.24  3892.8 1113.11
  3916.4  1109.6  3943.4  1112.4  4196.7  1109.3  4232.4 1101.77  4274.3 1107.64
  4463.6 1097.19  4471.5 1096.53  4816.4    1077  4963.7 1072.45  4971.9 1071.44
  4975.5 1066.54  4976.1 1066.04  4980.4 1066.54  4997.2 1071.05  5405.2  1079.4
  5524.5 1087.23  5627.7    1086    5677 1076.25  5707.8 1083.92  5742.4 1073.74
  5758.4 1079.17  5774.5 1078.48  5787.7  1084.7  5883.5 1092.48    6179 1102.45
#Mann= 7 ,-1 , 0
  3759.3     .12       0  3780.5     .05       0  4463.6     .12       0
  4471.5     .05       0  4816.4     .12       0  4975.5     .07       0
  4980.4     .12       0
Bank Sta=4975.5,4980.4
XS Rating Curve= 0 ,0
Exp/Cntr=0.3,0.1

Type RM Length L Ch R = 1 ,53426   ,528,528,528
BEGIN DESCRIPTION:
DRY VALLEY CREEK 101.0
END DESCRIPTION:
XS GIS Cut Line= 3
      2220909.94       7276599.1        2220029.        7277460.
      2218977.64       7278343.9
#Sta/Elev= 30
  3773.6  1115.2  4128.4 1111.94  4206.3 1107.12  4227.5 1100.52    4305 1099.58
  4566.3 1088.37  4696.5 1076.35  4948.9 1070.07  4981.7 1064.58  4982.3 1064.08
  4986.6 1064.58  4991.3 1067.79  5033.3 1070.63  5203.7    1073  5324.7 1066.57
    5339 1072.48  5405.1 1076.24  5552.3 1083.88  5558.8 1079.88  5566.6 1084.12
  5573.1 1079.81    5655 1080.48  5700.6 1079.08    5737 1084.76  5772.1 1081.21
  5864.4 1090.77  5885.3 1086.69  5913.9 1095.41  5988.8 1096.73  6378.9 1111.39
#Mann= 9 ,-1 , 0
  3773.6     .05       0    4305     .12       0  4566.3     .05       0
  4696.5     .12       0  4981.7     .07       0  4986.6     .12       0
  5405.1     .05       0    5655     .12       0  5988.8     .05       0
Bank Sta=4981.7,4986.6
XS Rating Curve= 0 ,0
Exp/Cntr=0.3,0.1

Type RM Length L Ch R = 1 ,52898   ,528,528,528
BEGIN DESCRIPTION:
DRY VALLEY CREEK 100.0
END DESCRIPTION:
XS GIS Cut Line= 3
       2220847.4       7276453.3      2219758.88      7277099.11
      2218743.64      7278171.63
#Sta/Elev= 30
  3741.1 1114.39  3797.4 1114.35  3818.8 1102.75  3832.3 1112.88  3898.7  1108.5
    3926 1112.04  3941.6 1105.54  3957.2 1107.55    3963 1100.73  3978.6 1096.89
  3994.2 1098.08  4006.7 1106.35  4015.6    1105  4021.5 1111.08  4313.8 1103.33
    4649 1081.43  4714.3 1072.32  4882.8 1066.24  4956.9 1069.65  4991.3 1062.35
  4992.1 1061.85  4996.7 1062.35  4999.8 1067.59  5014.4 1068.67  5154.3  1066.2
  5382.1 1073.32  5558.9 1087.83  5982.4 1094.58  6224.3 1100.79  6483.6 1108.72
#Mann= 7 ,-1 , 0
  3741.1     .05       0  4714.3     .12       0  4991.3     .07       0
  4996.7     .12       0  5154.3     .05       0  5982.4     .12       0
  6224.3     .05       0
Bank Sta=4991.3,4996.7
XS Rating Curve= 0 ,0
Exp/Cntr=0.3,0.1

Type RM Length L Ch R = 1 ,52370   ,360,360,360
BEGIN DESCRIPTION:
DRY VALLEY CREEK 99.0
END DESCRIPTION:
XS GIS Cut Line= 3
      2220444.64      7275844.89      2219348.73      7276821.44
      2218274.51      7277949.92
#Sta/Elev= 30
  3526.1 1115.68    4157  1094.2  4177.9  1084.8  4213.9 1082.26  4234.8  1089.9
  4309.4 1085.58  4461.4  1084.4  4744.8 1065.22  4911.8  1063.1  4912.6  1062.6
  4917.3  1063.1  5282.6 1072.25  5374.8 1070.13  5475.2 1079.08  5586.8  1083.3
  5600.9 1075.27  5636.5 1075.08  5664.8 1085.73  5671.7 1079.93  5707.3 1087.59
  5714.2  1079.9  5721.4 1082.83  5728.3 1078.62  5756.6 1078.87  5763.9  1084.9
  5827.4 1080.12  5862.6 1091.15    5884 1089.21  5890.9 1095.82    6552 1118.43
#Mann= 5 ,-1 , 0
  3526.1     .05       0  4309.4     .12       0  4911.8     .07       0
  4917.3     .12       0  5475.2     .05       0
Bank Sta=4911.8,4917.3
XS Rating Curve= 0 ,0
Exp/Cntr=0.3,0.1

Type RM Length L Ch R = 1 ,52010   ,427,427,427
BEGIN DESCRIPTION:
DRY VALLEY CREEK 98.0
END DESCRIPTION:
XS GIS Cut Line= 3
      2220212.03       7275724.1        2219229.        7276510.
      2218227.65      7277672.01
#Sta/Elev= 30
  3737.4 1107.58  3900.1 1104.82  4042.6 1099.55  4141.9 1093.62  4156.3 1094.75
    4208 1092.51  4274.9 1091.16  4325.3 1089.55  4497.3 1087.46  4604.5  1083.5
  4703.8 1078.15    4747 1073.11  4825.5 1072.09  4854.3 1067.31  4939.1  1062.7
  5149.5 1061.37  5150.3 1060.87    5155 1061.37  5265.3 1062.34  5350.9 1067.88
  5362.3 1066.79    5484 1072.36  5575.6  1078.3  5584.6 1080.68  5627.3 1084.62
  5733.8 1090.93  5811.6 1093.45  6081.1 1100.56    6357 1114.44  6529.9 1118.15
#Mann= 11 ,-1 , 0
  3737.4     .05       0    4208     .12       0  4274.9     .05       0
  4325.3     .12       0  5149.5     .07       0    5155     .12       0
  5362.3     .05       0    5484     .12       0  5575.6     .05       0
  5811.6     .12       0  6081.1     .05       0
Bank Sta=5149.5,5155
XS Rating Curve= 0 ,0
Exp/Cntr=0.3,0.1

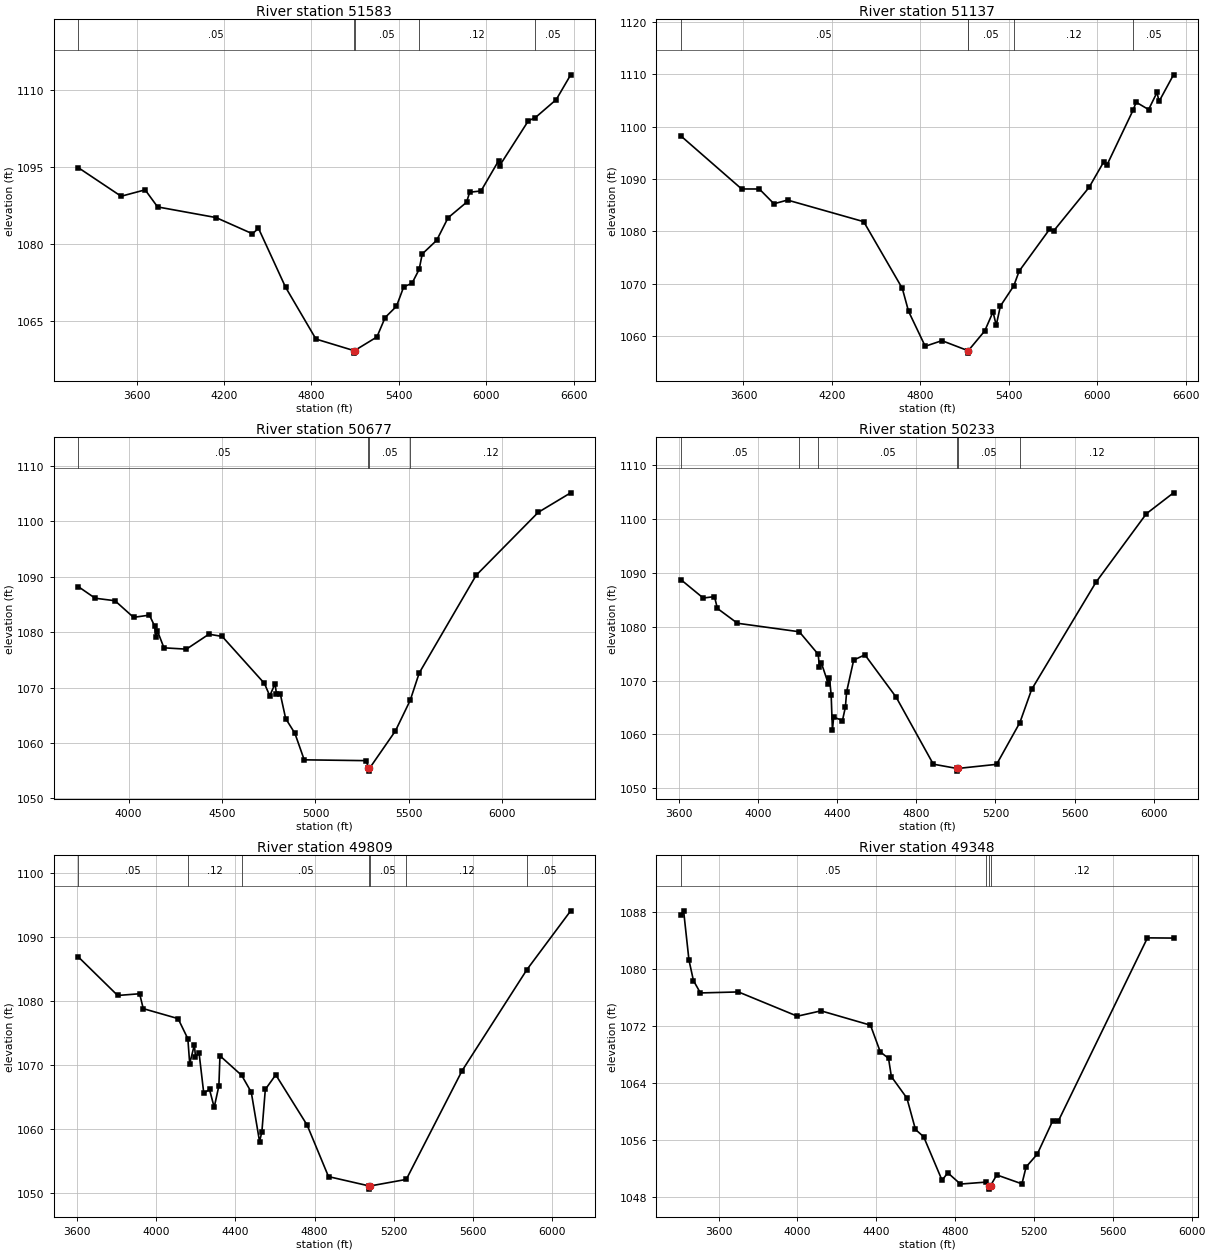
Type RM Length L Ch R = 1 ,51583   ,446,446,446
BEGIN DESCRIPTION:
DRY VALLEY CREEK 97.0
END DESCRIPTION:
XS GIS Cut Line= 3
      2219999.77      7274868.32        2218929.        7276310.
      2217840.47      7277461.65
#Sta/Elev= 30
  3199.5 1094.93  3494.3 1089.34  3659.1 1090.59  3744.7 1087.26  4145.2 1085.19
  4395.6 1082.03  4437.2 1083.09  4622.9 1071.62  4831.6 1061.51  5091.3 1059.27
  5092.2 1058.77  5097.1 1059.27    5250 1061.92  5306.6 1065.71  5384.3  1067.9
  5434.1  1071.7  5490.7 1072.37  5539.9 1075.09  5561.1 1078.09  5660.2 1080.75
  5738.3 1085.14  5865.3 1088.16  5886.7 1090.12  5964.4 1090.37  6084.6 1096.22
  6091.8 1095.27  6289.7 1104.05  6336.5 1104.64    6481 1108.18    6580    1113
#Mann= 5 ,-1 , 0
  3199.5     .05       0  5091.3    .033       0  5097.1     .05       0
  5539.9     .12       0  6336.5     .05       0
Bank Sta=5091.3,5097.1
XS Rating Curve= 0 ,0
Exp/Cntr=0.3,0.1

Type RM Length L Ch R = 1 ,51137   ,460,460,460
BEGIN DESCRIPTION:
DRY VALLEY CREEK 96.0
END DESCRIPTION:
XS GIS Cut Line= 3
      2219999.77      7274759.81        2218679.        7276010.
       2217656.5      7277135.58
#Sta/Elev= 30
  3176.4 1098.21  3587.5 1088.11  3707.6  1088.1  3806.7 1085.28  3898.6 1085.99
  4415.1 1081.87  4676.9 1069.14  4719.3 1064.76  4832.2 1058.09  4945.5 1059.16
  5119.5 1057.28  5120.4 1056.78  5125.3 1057.28  5235.9 1061.02  5292.3 1064.66
  5313.6 1062.09    5342 1065.76  5432.7 1069.62  5469.1 1072.43  5674.5 1080.38
  5702.9 1080.09  5943.4 1088.42  6042.8 1093.28  6063.7 1092.63  6242.6  1103.2
  6262.4 1104.67  6346.9 1103.26  6403.6 1106.52  6417.8 1104.81  6515.7 1109.89
#Mann= 5 ,-1 , 0
  3176.4     .05       0  5119.5    .033       0  5125.3     .05       0
  5432.7     .12       0  6242.6     .05       0
Bank Sta=5119.5,5125.3
XS Rating Curve= 0 ,0
Exp/Cntr=0.3,0.1

Type RM Length L Ch R = 1 ,50677   ,444,444,444
BEGIN DESCRIPTION:
DRY VALLEY CREEK 95.0
END DESCRIPTION:
XS GIS Cut Line= 3
      2219561.39      7274803.95        2218629.        7275660.
      2217634.32      7276600.81
#Sta/Elev= 30
  3730.4 1088.22  3821.3 1086.11  3927.3 1085.66  4026.6 1082.66  4111.7 1083.06
    4140 1081.04  4146.8 1079.18  4154.2 1080.22  4189.4 1077.16  4309.6 1076.92
  4429.8 1079.62  4500.7 1079.22    4727 1070.73  4755.4 1068.49  4783.8 1070.69
  4791.2 1068.84  4812.1 1068.79  4840.5 1064.39  4889.8 1061.74  4939.7 1056.95
  5271.9  1056.8    5283 1055.41    5284 1054.91    5289 1055.41  5427.6 1062.16
  5506.8 1067.69    5555 1072.62  5859.3 1090.24  6191.8 1101.61  6365.3 1105.13
#Mann= 4 ,-1 , 0
  3730.4     .05       0    5283    .033       0    5289     .05       0
  5506.8     .12       0
Bank Sta=5283,5289
XS Rating Curve= 0 ,0
Exp/Cntr=0.3,0.1

Type RM Length L Ch R = 1 ,50233   ,424,424,424
BEGIN DESCRIPTION:
DRY VALLEY CREEK 94.0
END DESCRIPTION:
XS GIS Cut Line= 3
      2219474.58      7274569.57        2218329.        7275360.
      2217504.14      7276088.63
#Sta/Elev= 30
  3608.4 1088.73    3721 1085.33  3777.8  1085.6  3792.7  1083.4  3894.1 1080.65
  4207.1 1079.07  4302.6 1074.89  4309.2 1072.59    4318 1073.35  4353.9 1069.44
  4359.9 1070.49  4368.4 1067.31  4374.8 1060.76  4380.9 1063.22  4425.5 1062.59
  4440.4 1065.08  4446.5 1067.91  4482.3 1073.81  4539.1 1074.79  4697.3 1066.92
  4885.3 1054.48  5004.3 1053.69  5005.3 1053.19  5010.3 1053.69  5205.6 1054.45
  5323.4 1062.21  5382.9 1068.36  5708.3 1088.26  5963.5 1100.99  6100.8 1104.87
#Mann= 6 ,-1 , 0
  3608.4     .05       0  4207.1     .12       0  4302.6     .05       0
  5004.3    .033       0  5010.3     .05       0  5323.4     .12       0
Bank Sta=5004.3,5010.3
XS Rating Curve= 0 ,0
Exp/Cntr=0.3,0.1

Type RM Length L Ch R = 1 ,49809   ,461,461,461
BEGIN DESCRIPTION:
DRY VALLEY CREEK 93.0
END DESCRIPTION:
XS GIS Cut Line= 3
      2219413.87      7274465.38        2218129.        7275010.
      2217322.89      7275749.13
#Sta/Elev= 30
    3605  1086.9  3804.7 1080.84  3915.7 1081.11  3933.9 1078.78  4109.9 1077.22
  4159.3 1074.07  4168.7 1070.17  4192.4 1073.13  4197.8 1071.26    4216 1071.85
  4239.7 1065.56  4268.8 1066.13  4292.5 1063.33  4316.2  1066.7  4321.6  1071.4
  4431.6 1068.33  4479.9  1065.7  4521.8 1057.97  4533.5 1059.51  4550.9 1066.14
  4603.7 1068.42  4762.1 1060.56  4870.2 1052.49  5075.5 1051.03  5076.5 1050.53
  5081.6 1051.03  5263.3 1052.05  5545.3 1069.06  5873.3  1084.9  6094.2 1094.09
#Mann= 7 ,-1 , 0
    3605     .05       0  4159.3     .12       0  4431.6     .05       0
  5075.5    .033       0  5081.6     .05       0  5263.3     .12       0
  5873.3     .05       0
Bank Sta=5075.5,5081.6
XS Rating Curve= 0 ,0
Exp/Cntr=0.3,0.1

Type RM Length L Ch R = 1 ,49348   ,469,469,469
BEGIN DESCRIPTION:
DRY VALLEY CREEK 92.0
END DESCRIPTION:
XS GIS Cut Line= 3
      2219040.57       7273883.8        2217779.        7274860.
      2217157.26      7275515.35
#Sta/Elev= 30
  3409.4 1087.56  3422.7 1088.12  3449.8 1081.22  3472.5 1078.35  3507.8 1076.61
  3700.7 1076.75  3999.5 1073.35  4119.9  1074.1  4370.7 1072.09  4420.5 1068.34
  4462.2 1067.45  4476.7 1064.88  4555.4 1061.87  4598.9 1057.47  4640.5 1056.45
  4733.8 1050.35  4762.8  1051.4  4827.1 1049.82  4954.8 1050.09  4973.3 1049.61
  4974.3 1049.11  4979.6 1049.61  5011.6  1051.1    5139 1049.85  5160.1 1052.22
  5216.7 1054.01  5294.4 1058.64  5322.7  1058.6  5775.7 1084.33  5907.9  1084.3
#Mann= 4 ,-1 , 0
  3409.4     .05       0  4954.8     .12       0  4973.3     .07       0
  4979.6     .12       0
Bank Sta=4973.3,4979.6
XS Rating Curve= 0 ,0
Exp/Cntr=0.3,0.1

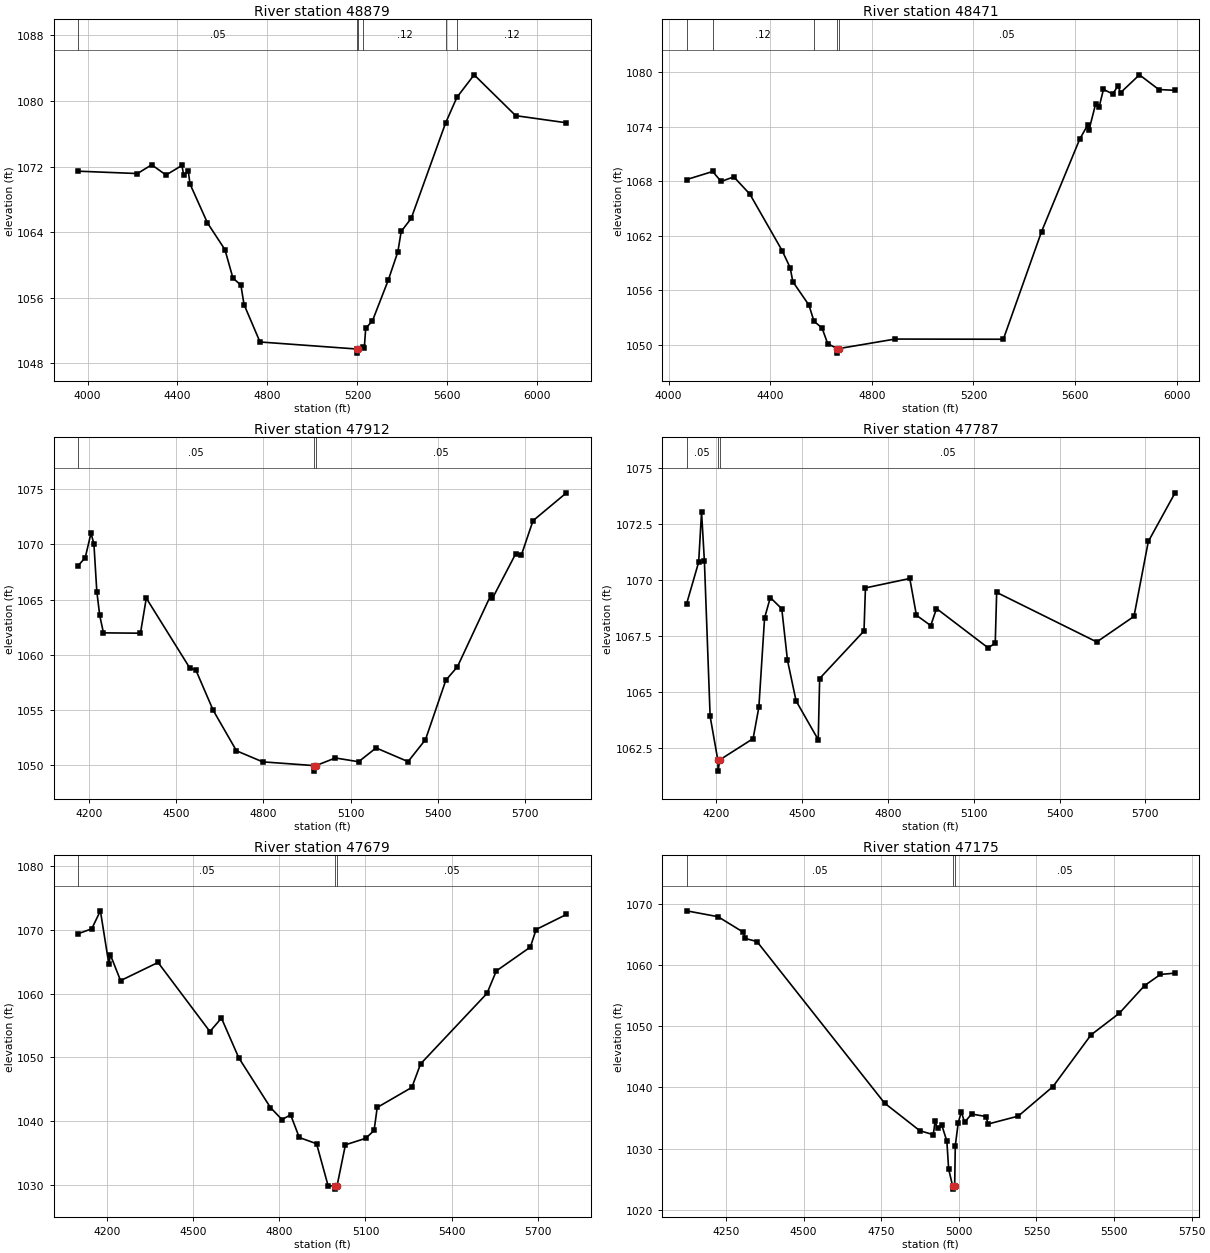
Type RM Length L Ch R = 1 ,48879   ,408,408,408
BEGIN DESCRIPTION:
DRY VALLEY CREEK 91.0
END DESCRIPTION:
XS GIS Cut Line= 3
      2218346.15      7273753.57        2217579.        7274460.
      2216931.36       7275385.3
#Sta/Elev= 30
  3957.4 1071.44  4221.9 1071.15  4285.4 1072.22  4348.9 1070.97  4419.8 1072.14
  4427.2 1071.01  4448.2 1071.41  4455.6 1069.88  4533.3 1065.13    4611 1061.87
  4646.7 1058.39  4681.8 1057.56    4696 1055.17  4766.9 1050.61    5198 1049.75
  5199.1 1049.25  5204.4 1049.75  5226.1 1049.95  5230.9 1049.92    5237 1052.29
  5266.6 1053.16  5338.1 1058.21    5380 1061.61  5394.8 1064.09  5439.3 1065.68
  5592.2 1077.31  5642.7 1080.45  5719.2 1083.19    5904 1078.21  6129.7 1077.34
#Mann= 6 ,-1 , 0
  3957.4     .05       0    5198    .033       0  5204.4     .05       0
  5226.1     .12       0  5592.2     .05       0  5642.7     .12       0
Bank Sta=5198,5204.4
XS Rating Curve= 0 ,0
Exp/Cntr=0.3,0.1

Type RM Length L Ch R = 1 ,48471   ,559,559,559
BEGIN DESCRIPTION:
DRY VALLEY CREEK 90.0
END DESCRIPTION:
XS GIS Cut Line= 3
      2217577.01      7273334.07        2217279.        7274210.
      2216952.04      7275152.56
#Sta/Elev= 30
  4070.9 1068.19  4173.6 1069.08  4206.8 1067.98  4256.7 1068.49  4320.1 1066.58
  4446.9 1060.37  4478.6 1058.48  4489.1 1056.94  4552.5 1054.36  4572.4 1052.58
    4604 1051.84  4626.4 1050.11  4663.6 1049.57  4664.6 1049.07    4670 1049.57
  4891.6 1050.62  5317.8  1050.6  5468.1 1062.45  5618.5 1072.65  5649.6 1074.18
  5654.9 1073.65  5680.8 1076.49  5694.7 1076.16  5711.9 1078.13  5748.3 1077.62
  5768.8  1078.5  5779.5 1077.77  5853.5 1079.73  5929.8 1078.11  5993.8 1078.02
#Mann= 5 ,-1 , 0
  4070.9     .05       0  4173.6     .12       0  4572.4     .05       0
  4663.6    .033       0    4670     .05       0
Bank Sta=4663.6,4670
XS Rating Curve= 0 ,0
Exp/Cntr=0.3,0.1

Type RM Length L Ch R = 1 ,47912   ,125,125,125
BEGIN DESCRIPTION:
DRY VALLEY CREEK 89.0
END DESCRIPTION:
XS GIS Cut Line= 3
      2216778.42      7273425.16      2216735.01      7274262.85
      2216704.63      7275104.89
#Sta/Elev= 30
  4161.8 1068.07  4186.7 1068.79  4206.7 1071.03  4216.7 1070.04  4226.7 1065.74
  4236.7 1063.58  4249.5    1062  4376.9 1061.97    4397 1065.14  4547.2  1058.8
  4567.2 1058.66  4627.3 1054.99  4707.4 1051.33  4797.5 1050.33  4974.5 1049.99
  4975.5 1049.49    4981 1049.99  5047.8 1050.68  5127.8 1050.34  5187.9 1051.59
    5298 1050.35    5358 1052.34    5428 1057.71  5468.1 1058.94  5583.3 1065.43
  5588.3 1065.11  5668.2 1069.14  5688.2 1069.05  5728.2 1072.15  5843.2 1074.67
#Mann= 3 ,-1 , 0
  4161.8     .05       0  4974.5    .033       0    4981     .05       0
Bank Sta=4974.5,4981
XS Rating Curve= 0 ,0
Exp/Cntr=0.3,0.1

Type RM Length L Ch R = 1 ,47787   ,108,108,108
BEGIN DESCRIPTION:
DRY VALLEY CREEK 88.5
END DESCRIPTION:
XS GIS Cut Line= 3
      2216682.93      7273407.84       2216626.4        7274310.
      2216661.23      7275113.52
#Sta/Elev= 30
  4095.7 1068.94  4137.9  1070.8    4148 1073.04    4158 1070.83    4178 1063.92
  4204.8 1061.98  4205.9 1061.48  4211.3 1061.98  4328.3 1062.93  4348.4 1064.33
  4368.4 1068.31  4388.4 1069.22  4428.5 1068.72  4448.5 1066.42  4478.6 1064.61
    4556 1062.88    4561 1065.61  4716.1 1067.73  4721.1 1069.65  4876.2 1070.07
  4899.4 1068.43  4949.5 1067.97  4969.6 1068.73  5149.8 1066.98    5175 1067.18
    5180 1069.45  5530.1 1067.24  5660.2 1068.38  5710.3 1071.72  5803.9 1073.89
#Mann= 3 ,-1 , 0
  4095.7     .05       0  4204.8    .033       0  4211.3     .05       0
Bank Sta=4204.8,4211.3
XS Rating Curve= 0 ,0
Exp/Cntr=0.3,0.1

Type RM Length L Ch R = 1 ,47679   ,504,504,504
BEGIN DESCRIPTION:
DRY VALLEY CREEK 88.0
END DESCRIPTION:
XS GIS Cut Line= 3
       2216604.8       7273412.2        2216518.      7274310.59
      2216613.49       7275104.9
#Sta/Elev= 30
    4098  1069.4    4146 1070.18  4176.2    1073  4205.8 1064.61  4210.8 1066.12
  4246.5 1062.05  4377.1  1064.9  4557.9 1054.06  4598.1 1056.17  4658.4 1049.95
  4768.9 1042.14  4809.1 1040.25  4839.2    1041  4869.4 1037.44  4929.7 1036.46
  4969.8 1029.88  4994.5 1029.84  4995.6 1029.34    5001 1029.84  5030.2 1036.29
  5100.7 1037.31  5130.2 1038.54    5141 1042.15  5261.8  1045.3  5292.1 1048.98
  5523.7 1060.05  5556.2 1063.57  5674.8 1067.31  5694.9 1070.07  5800.6 1072.43
#Mann= 3 ,-1 , 0
    4098     .05       0  4994.5    .033       0    5001     .05       0
Bank Sta=4994.5,5001
XS Rating Curve= 0 ,0
Exp/Cntr=0.3,0.1

Type RM Length L Ch R = 1 ,47175   ,628,628,628
BEGIN DESCRIPTION:
DRY VALLEY CREEK 87.0
END DESCRIPTION:
XS GIS Cut Line= 3
      2216513.75      7273359.16      2216104.01      7274116.15
       2215972.3       7274816.3
#Sta/Elev= 30
  4123.4 1068.92  4224.5 1067.96  4306.3 1065.41    4312  1064.4    4350 1063.89
  4761.1 1037.43  4874.1 1032.93  4917.9 1032.26  4923.6 1034.43  4931.7 1033.28
  4945.5 1033.77  4961.6 1031.22  4967.3 1026.66  4980.2 1023.85  4981.3 1023.35
  4986.8 1023.85  4988.7 1030.44  4998.3 1034.24  5008.4    1036  5018.6 1034.29
  5041.2 1035.65  5088.6 1035.23  5093.7    1034  5191.6 1035.31  5303.5 1040.15
  5425.6 1048.59  5517.2 1052.16  5598.6 1056.69  5649.5  1058.5  5696.6 1058.72
#Mann= 3 ,-1 , 0
  4123.4     .05       0  4980.2    .033       0  4986.8     .05       0
Bank Sta=4980.2,4986.8
XS Rating Curve= 0 ,0
Exp/Cntr=0.3,0.1