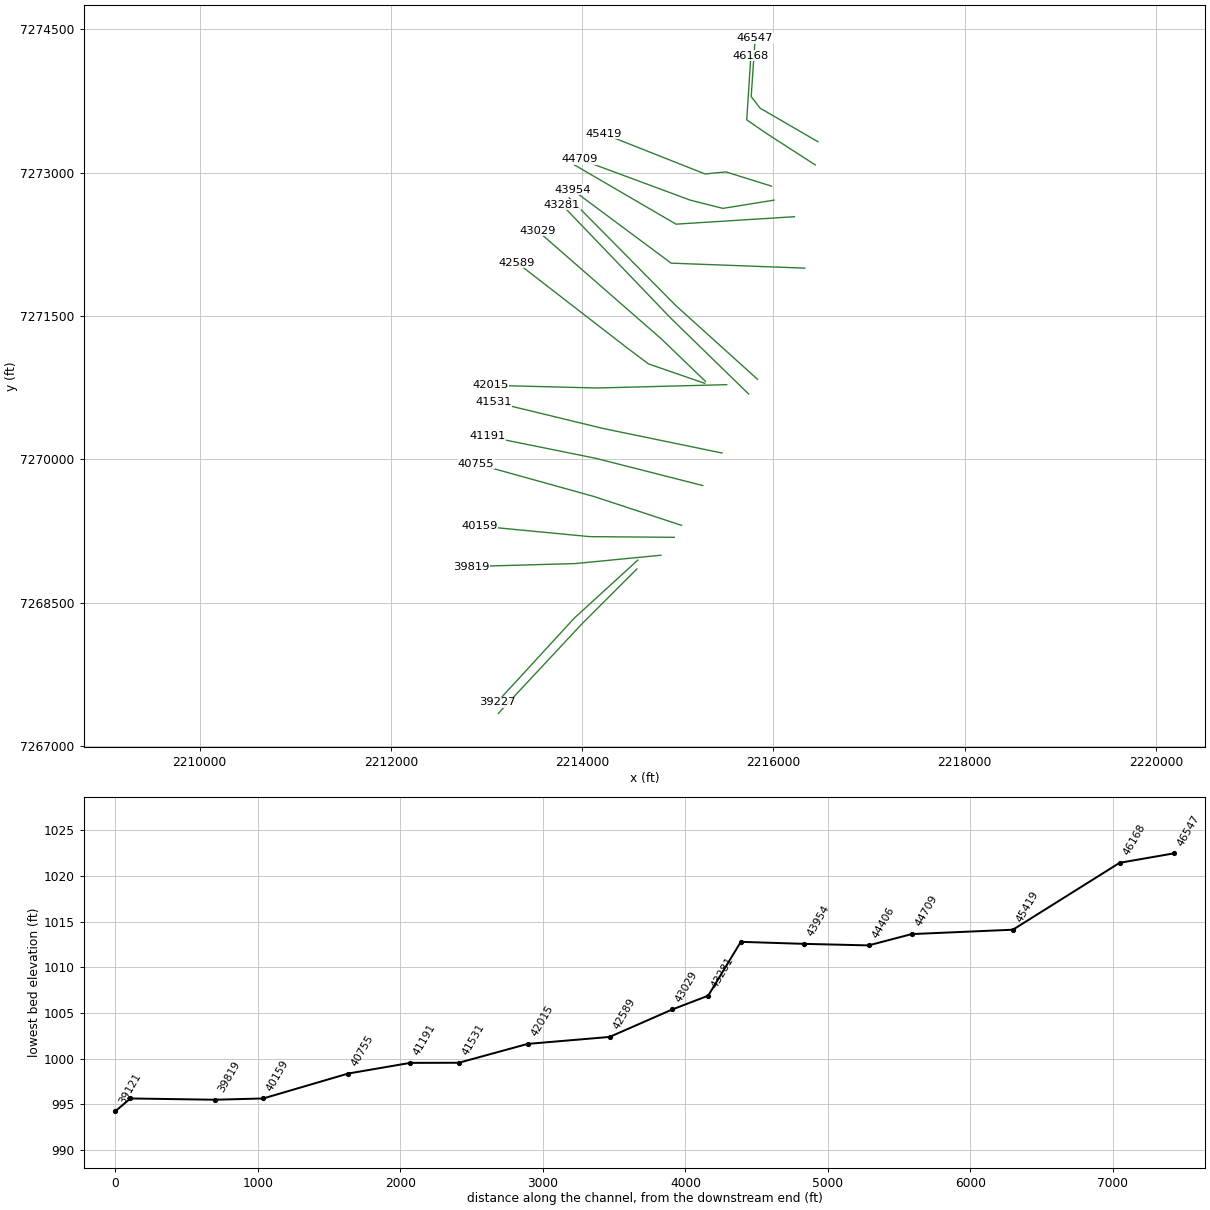
HEC-RAS study DRY VALLEY CREEK.prj: DRY VALLEY CREEK Base Level Engineering

--- DRY VALLEY CREEK.g01 (geometry) --- (continued)

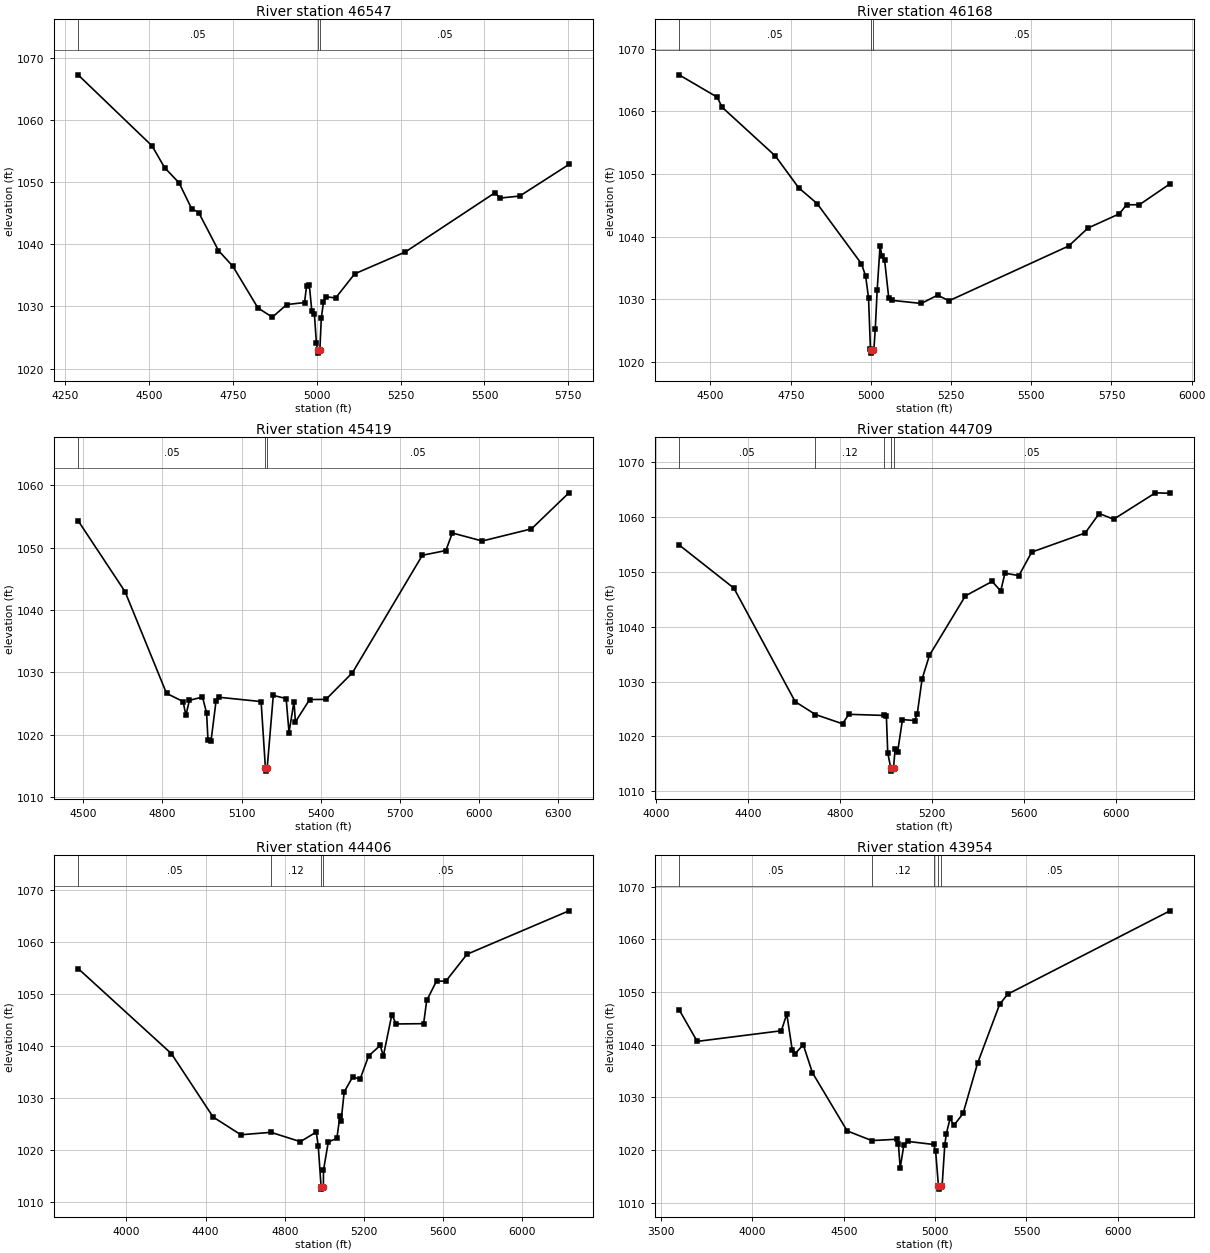
Type RM Length L Ch R = 1 ,46547   ,379,379,379
BEGIN DESCRIPTION:
DRY VALLEY CREEK 86.0
END DESCRIPTION:
XS GIS Cut Line= 4
      2216465.15      7273324.46      2215860.95      7273675.18
       2215767.2       7273796.7      2215808.77       7274406.4
#Sta/Elev= 30
  4288.7 1067.22  4509.3 1055.79  4546.6  1052.3  4589.6 1049.86  4626.9 1045.73
  4648.4 1045.06  4707.2 1038.97  4750.2 1036.43  4824.8 1029.74  4867.8 1028.26
  4910.8 1030.29  4963.8 1030.61  4969.6 1033.24    4978 1033.38  4985.4  1029.3
    4993 1028.85  4999.2 1024.04  5002.7 1022.98  5003.8 1022.48  5009.4 1022.98
  5013.7 1028.08    5020 1030.64  5028.2 1031.54  5056.5 1031.35  5113.3 1035.23
  5264.4 1038.75  5532.4  1048.3    5545  1047.4  5605.2 1047.73  5751.9 1052.81
#Mann= 3 ,-1 , 0
  4288.7     .05       0  5002.7    .033       0  5009.4     .05       0
Bank Sta=5002.7,5009.4
XS Rating Curve= 0 ,0
Exp/Cntr=0.3,0.1

Type RM Length L Ch R = 1 ,46168   ,749,749,749
BEGIN DESCRIPTION:
DRY VALLEY CREEK 85.0
END DESCRIPTION:
XS GIS Cut Line= 4
      2216436.49      7273082.28        2215929.        7273410.
      2215720.64      7273553.05        2215764.      7274225.01
#Sta/Elev= 30
  4402.1 1065.82  4520.9 1062.26  4536.1 1060.66  4702.4 1052.87  4774.9 1047.81
  4832.3  1045.3  4970.5  1035.7  4983.5 1033.77  4992.7 1030.25  4998.6 1022.16
  4999.9 1021.95    5001 1021.45  5006.6 1021.95  5009.2 1021.95  5013.7 1025.32
  5019.7 1031.56  5028.6 1038.57  5034.6 1036.91  5042.6 1036.37  5055.6  1030.3
  5064.4 1029.87  5157.1 1029.37  5207.9 1030.69  5243.7  1029.8  5616.6 1038.53
  5676.8 1041.39  5774.5 1043.66    5797  1045.1  5837.1 1045.11  5932.3 1048.44
#Mann= 3 ,-1 , 0
  4402.1     .05       0  4999.9    .033       0  5006.6     .05       0
Bank Sta=4999.9,5006.6
XS Rating Curve= 0 ,0
Exp/Cntr=0.3,0.1

Type RM Length L Ch R = 1 ,45419   ,710,710,710
BEGIN DESCRIPTION:
DRY VALLEY CREEK 84.0
END DESCRIPTION:
XS GIS Cut Line= 4
      2215978.95      7272860.01      2215501.89      7273008.78
      2215284.88      7272987.08      2214222.71      7273407.61
#Sta/Elev= 30
  4480.4 1054.35  4658.4 1042.94  4815.6 1026.61  4878.4  1025.3  4888.9 1023.09
  4902.4 1025.49  4951.7 1026.02  4967.4 1023.49  4972.7 1019.08  4984.1 1018.92
  5003.1 1025.34  5013.1 1025.99    5174 1025.29  5190.3 1014.62  5191.3 1014.12
    5197 1014.62  5220.2 1026.28  5268.9 1025.78  5279.8 1020.32  5298.6  1025.3
    5304 1022.03    5358 1025.62  5419.6 1025.64  5520.2 1029.93  5785.1 1048.79
  5874.2 1049.55  5898.6 1052.37    6012 1051.08  6198.5 1053.03  6340.6 1058.82
#Mann= 3 ,-1 , 0
  4480.4     .05       0  5190.3    .033       0    5197     .05       0
Bank Sta=5190.3,5197
XS Rating Curve= 0 ,0
Exp/Cntr=0.3,0.1

Type RM Length L Ch R = 1 ,44709   ,303,303,303
BEGIN DESCRIPTION:
DRY VALLEY CREEK 83.0
END DESCRIPTION:
XS GIS Cut Line= 4
      2216006.76      7272713.37      2215471.51      7272626.84
      2215128.63      7272713.64      2213969.82      7273143.31
#Sta/Elev= 30
  4101.3 1054.93  4339.4 1047.04  4605.5 1026.32  4693.6 1023.97  4811.1 1022.28
  4838.3 1024.01  4990.3 1023.81  5001.6 1023.64  5007.5 1016.98  5020.9 1014.14
  5022.5 1013.64  5032.5 1014.14  5039.5 1017.67  5050.1 1017.07  5071.5 1023.05
  5124.8 1022.87  5135.5 1024.07  5156.8 1030.47  5188.8  1034.8  5344.8 1045.63
    5461 1048.27  5498.1 1046.52  5516.5 1049.77  5577.2 1049.33  5632.7 1053.62
    5865 1057.11  5925.8 1060.66  5988.7 1059.62    6170 1064.44  6233.1 1064.36
#Mann= 5 ,-1 , 0
  4101.3     .05       0  4693.6     .12       0  4990.3     .05       0
  5020.9    .033       0  5032.5     .05       0
Bank Sta=5020.9,5032.5
XS Rating Curve= 0 ,0
Exp/Cntr=0.3,0.1

Type RM Length L Ch R = 1 ,44406   ,452,452,452
BEGIN DESCRIPTION:
DRY VALLEY CREEK 82.0
END DESCRIPTION:
XS GIS Cut Line= 3
      2216219.43      7272539.76      2214981.06       7272461.9
       2213911.8      7273085.84
#Sta/Elev= 30
  3756.3 1054.93  4227.7 1038.51  4438.1  1026.3  4578.3 1022.88  4730.5 1023.35
  4878.9 1021.55  4959.1  1023.4  4969.1 1020.72  4983.4  1012.9    4985  1012.4
    4995  1012.9  4995.6 1016.07    5020 1021.51    5063 1022.17  5078.7 1026.51
  5084.5 1025.55  5100.2 1031.15  5143.2 1034.04  5180.4  1033.6  5223.4 1038.07
  5282.1 1040.11  5297.8 1038.04  5340.8 1046.06  5362.3 1044.24  5501.2  1044.3
  5516.9 1048.77  5566.8 1052.54  5612.8 1052.45  5720.3 1057.68  6235.1 1066.05
#Mann= 4 ,-1 , 0
  3756.3     .05       0  4730.5     .12       0  4983.4    .033       0
    4995     .05       0
Bank Sta=4983.4,4995
XS Rating Curve= 0 ,0
Exp/Cntr=0.3,0.1

Type RM Length L Ch R = 1 ,43954   ,444,444,444
BEGIN DESCRIPTION:
DRY VALLEY CREEK 81.0
END DESCRIPTION:
XS GIS Cut Line= 3
      2216328.02      7272001.56       2214930.4      7272053.65
      2213897.43      7272821.86
#Sta/Elev= 30
  3599.2 1046.66  3698.3 1040.63  4158.6 1042.65  4188.6 1045.82  4218.6 1038.94
  4231.1 1038.18  4278.7 1039.99  4328.7 1034.69  4518.9 1023.63  4653.6 1021.79
    4789 1022.04    4799 1021.23  4809.1 1016.61  4829.1 1020.93  4849.1 1021.64
  4991.7 1021.05  5002.9 1019.78  5018.6 1013.07  5020.3 1012.57  5030.3 1013.07
  5038.4 1013.14    5053 1020.96  5061.3 1023.07  5082.2 1025.99    5103 1024.67
  5153.1 1026.95  5232.4 1036.48  5353.3 1047.68  5397.2  1049.6  6285.1 1065.43
#Mann= 5 ,-1 , 0
  3599.2     .05       0  4653.6     .12       0  4991.7     .05       0
  5018.6    .033       0  5030.3     .05       0
Bank Sta=5018.6,5030.3
XS Rating Curve= 0 ,0
Exp/Cntr=0.3,0.1

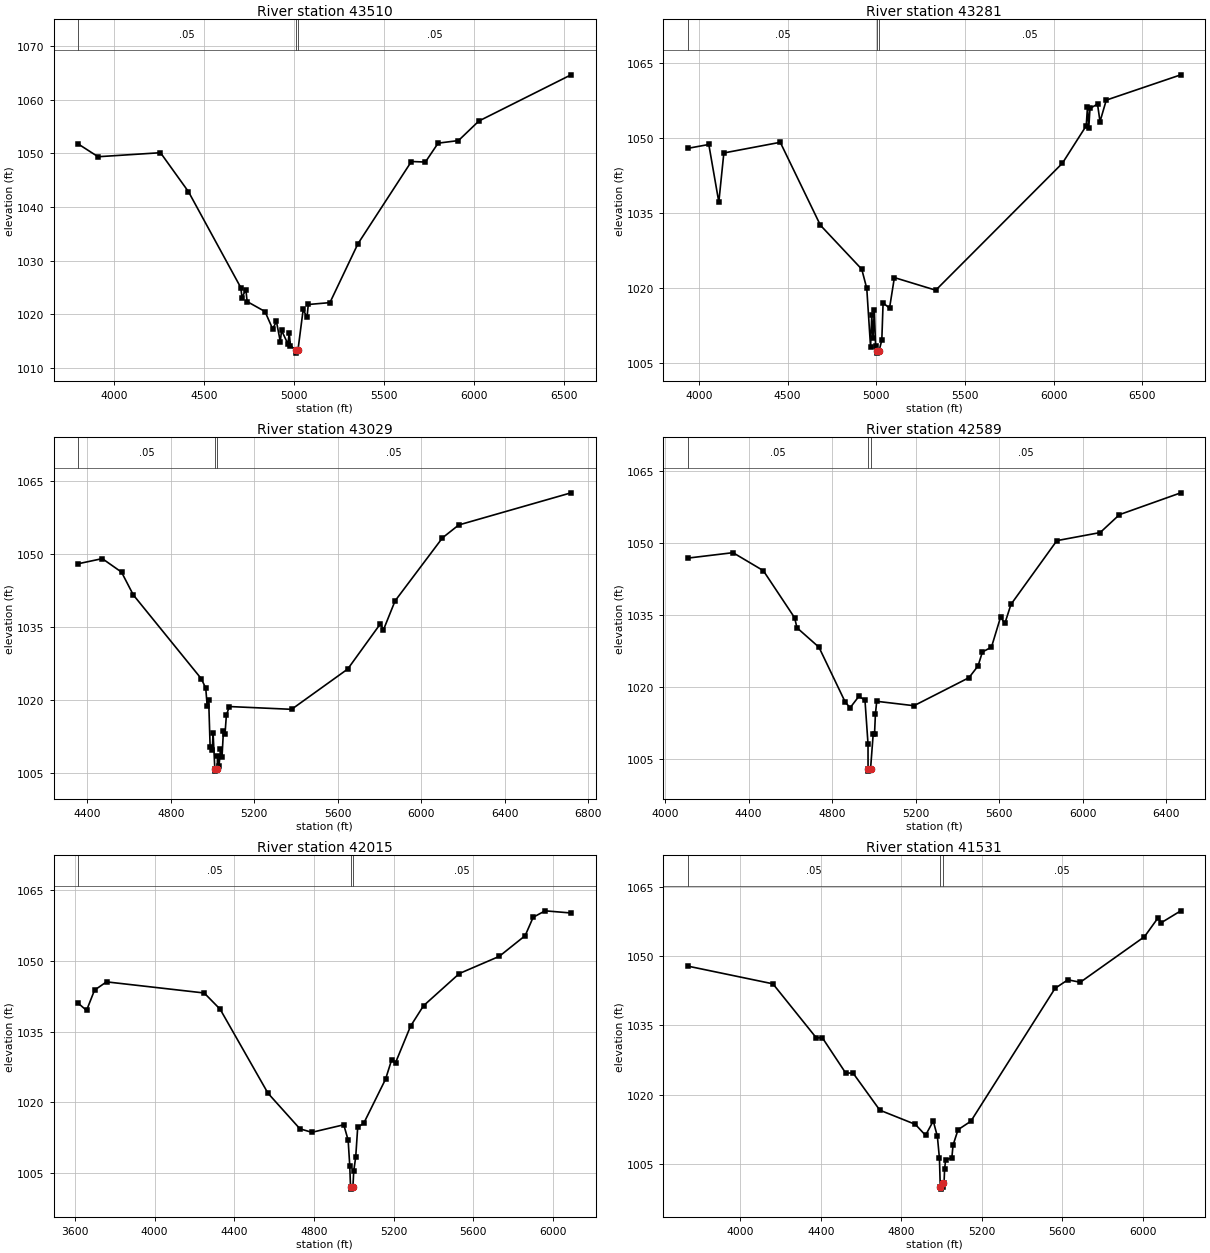
Type RM Length L Ch R = 1 ,43510   ,229,229,229
BEGIN DESCRIPTION:
DRY VALLEY CREEK 80.0
END DESCRIPTION:
XS GIS Cut Line= 3
      2215833.14       7270838.4        2214979.        7271610.
      2213863.35      7272738.74
#Sta/Elev= 30
  3800.8 1051.76  3911.3 1049.38    4258 1050.13  4413.4 1042.87  4704.1    1025
  4710.9 1023.15  4732.5 1024.63  4739.3  1022.4  4838.6 1020.54  4881.2  1017.3
  4902.2 1018.69  4923.8 1014.92  4930.6 1017.02    4966 1014.51  4973.1  1016.5
  4980.1 1014.21  5009.5 1013.29  5011.1 1012.79  5021.5 1013.29  5050.8 1020.92
  5072.1 1019.44  5079.1 1021.85  5199.4  1022.2  5354.9 1033.16  5651.9 1048.49
  5729.7 1048.39  5800.4 1051.91  5913.5 1052.39  6026.7 1056.03  6538.9 1064.64
#Mann= 3 ,-1 , 0
  3800.8     .05       0  5009.5    .033       0  5021.5     .05       0
Bank Sta=5009.5,5021.5
XS Rating Curve= 0 ,0
Exp/Cntr=0.3,0.1

Type RM Length L Ch R = 1 ,43281   ,252,252,252
BEGIN DESCRIPTION:
DRY VALLEY CREEK 79.5
END DESCRIPTION:
XS GIS Cut Line= 3
       2215740.3      7270684.72      2214927.79      7271476.39
      2213788.89       7272663.9
#Sta/Elev= 30
  3937.5 1047.96  4055.3 1048.73  4111.8 1037.18  4140.1 1047.03  4458.3 1049.17
  4684.7 1032.54    4918 1023.72  4946.3 1019.86  4967.6 1008.17  4974.5 1014.56
  4981.7  1009.9  4988.7 1015.56  4995.9 1008.41    5004 1007.39  5005.7 1006.89
    5016 1007.39  5031.1 1009.51  5038.3 1016.95  5074.7 1015.92    5102 1022.04
  5335.3 1019.51  6049.6 1044.97  6184.1 1052.48  6191.1 1056.23  6198.3 1052.03
  6205.2 1055.95  6247.7 1056.84  6261.8 1053.31  6297.1 1057.63  6717.3  1062.7
#Mann= 3 ,-1 , 0
  3937.5     .05       0    5004    .033       0    5016     .05       0
Bank Sta=5004,5016
XS Rating Curve= 0 ,0
Exp/Cntr=0.3,0.1

Type RM Length L Ch R = 1 ,43029   ,440,440,440
BEGIN DESCRIPTION:
DRY VALLEY CREEK 79.0
END DESCRIPTION:
XS GIS Cut Line= 3
      2215288.93      7270816.65        2214829.        7271260.
      2213532.99      7272392.16
#Sta/Elev= 30
  4356.9 1047.96  4472.3 1049.01  4564.4 1046.24  4620.8 1041.56  4946.2 1024.36
  4967.6 1022.42  4974.5  1018.8  4981.7 1019.98  4988.6 1010.38    4999 1009.71
  5002.8 1013.24  5011.1 1005.88  5012.7 1005.38  5023.1 1005.88  5023.7  1008.5
  5031.3  1006.4    5038  1009.9  5045.6 1008.33  5052.2 1013.53  5059.8 1012.95
  5066.4 1016.86  5080.7 1018.64  5378.7 1018.07  5647.4 1026.34    5804 1035.64
  5818.2 1034.36  5874.2 1040.34  6101.1 1053.28  6178.9 1055.92  6716.6 1062.52
#Mann= 3 ,-1 , 0
  4356.9     .05       0  5011.1    .033       0  5023.1     .05       0
Bank Sta=5011.1,5023.1
XS Rating Curve= 0 ,0
Exp/Cntr=0.3,0.1

Type RM Length L Ch R = 1 ,42589   ,574,574,574
BEGIN DESCRIPTION:
DRY VALLEY CREEK 78.0
END DESCRIPTION:
XS GIS Cut Line= 4
      2215281.98      7270795.83      2214693.25      7270999.31
        2214479.        7271160.      2213316.67      7272059.74
#Sta/Elev= 30
  4109.7 1046.76  4325.6 1047.89  4470.9 1044.14  4620.7 1034.33  4632.1 1032.24
  4737.3 1028.19    4864 1016.68  4886.9 1015.59  4928.5 1017.95  4957.7 1017.16
  4972.3 1008.06  4972.5 1002.87  4974.2 1002.37  4984.5 1002.87  4997.3 1010.19
  5003.6 1010.19  5007.7 1014.23    5014 1016.92  5192.4    1016  5455.8 1021.84
  5499.3 1024.29  5520.1 1027.19  5563.6 1028.21  5607.1 1034.44  5627.9 1033.17
  5656.9 1037.11  5876.9  1050.4  6084.2 1052.08  6176.5 1055.81  6470.3 1060.36
#Mann= 3 ,-1 , 0
  4109.7     .05       0  4972.5    .033       0  4984.5     .05       0
Bank Sta=4972.5,4984.5
XS Rating Curve= 0 ,0
Exp/Cntr=0.3,0.1

Type RM Length L Ch R = 1 ,42015   ,484,484,484
BEGIN DESCRIPTION:
DRY VALLEY CREEK 77.0
END DESCRIPTION:
XS GIS Cut Line= 3
      2215511.12      7270781.95      2214156.96      7270747.22
      2213038.91        7270775.
#Sta/Elev= 30
  3616.9 1041.04    3659 1039.53    3699 1043.83  3759.1 1045.58  4249.2 1043.22
  4329.3 1039.77  4569.3 1021.95  4729.4 1014.41  4789.4 1013.66  4949.5 1015.26
  4971.5    1012  4979.5 1006.59  4983.4 1002.11  4985.1 1001.61  4995.5 1002.11
  4999.5 1005.42  5009.5 1008.44  5019.5 1014.76  5049.5 1015.56  5159.5 1024.96
  5189.5 1029.02  5209.5 1028.45  5284.6 1036.18  5349.6 1040.51  5529.6 1047.35
  5729.7 1050.99  5859.7 1055.38  5899.8 1059.28  5959.8 1060.65  6089.9 1060.19
#Mann= 3 ,-1 , 0
  3616.9     .05       0  4983.4    .033       0  4995.5     .05       0
Bank Sta=4983.4,4995.5
XS Rating Curve= 0 ,0
Exp/Cntr=0.3,0.1

Type RM Length L Ch R = 1 ,41531   ,340,340,340
BEGIN DESCRIPTION:
DRY VALLEY CREEK 76.0
END DESCRIPTION:
XS GIS Cut Line= 3
      2215462.49      7270066.67      2214219.46      7270323.61
      2213073.85      7270601.34
#Sta/Elev= 30
  3740.5 1047.83  4162.7    1044  4378.4 1032.29  4407.8 1032.35  4523.9  1024.7
    4561 1024.66  4693.7 1016.64  4870.4 1013.56  4920.7 1011.19  4959.2 1014.29
  4979.6 1010.96  4989.9 1006.18    4994 1000.04  4995.7  999.54  5006.2 1000.04
  5009.8 1000.84  5012.6 1000.84  5015.6 1003.92  5020.7  1005.9  5051.4 1006.28
  5057.4 1009.05  5082.3 1012.41  5146.1 1014.25  5564.1 1043.02  5627.7 1044.87
  5689.4 1044.34  6008.4 1054.21    6076 1058.31  6090.7 1057.21  6188.6 1059.81
#Mann= 3 ,-1 , 0
  3740.5     .05       0    4994    .033       0  5006.2     .05       0
Bank Sta=4994,5009.8
XS Rating Curve= 0 ,0
Exp/Cntr=0.3,0.1

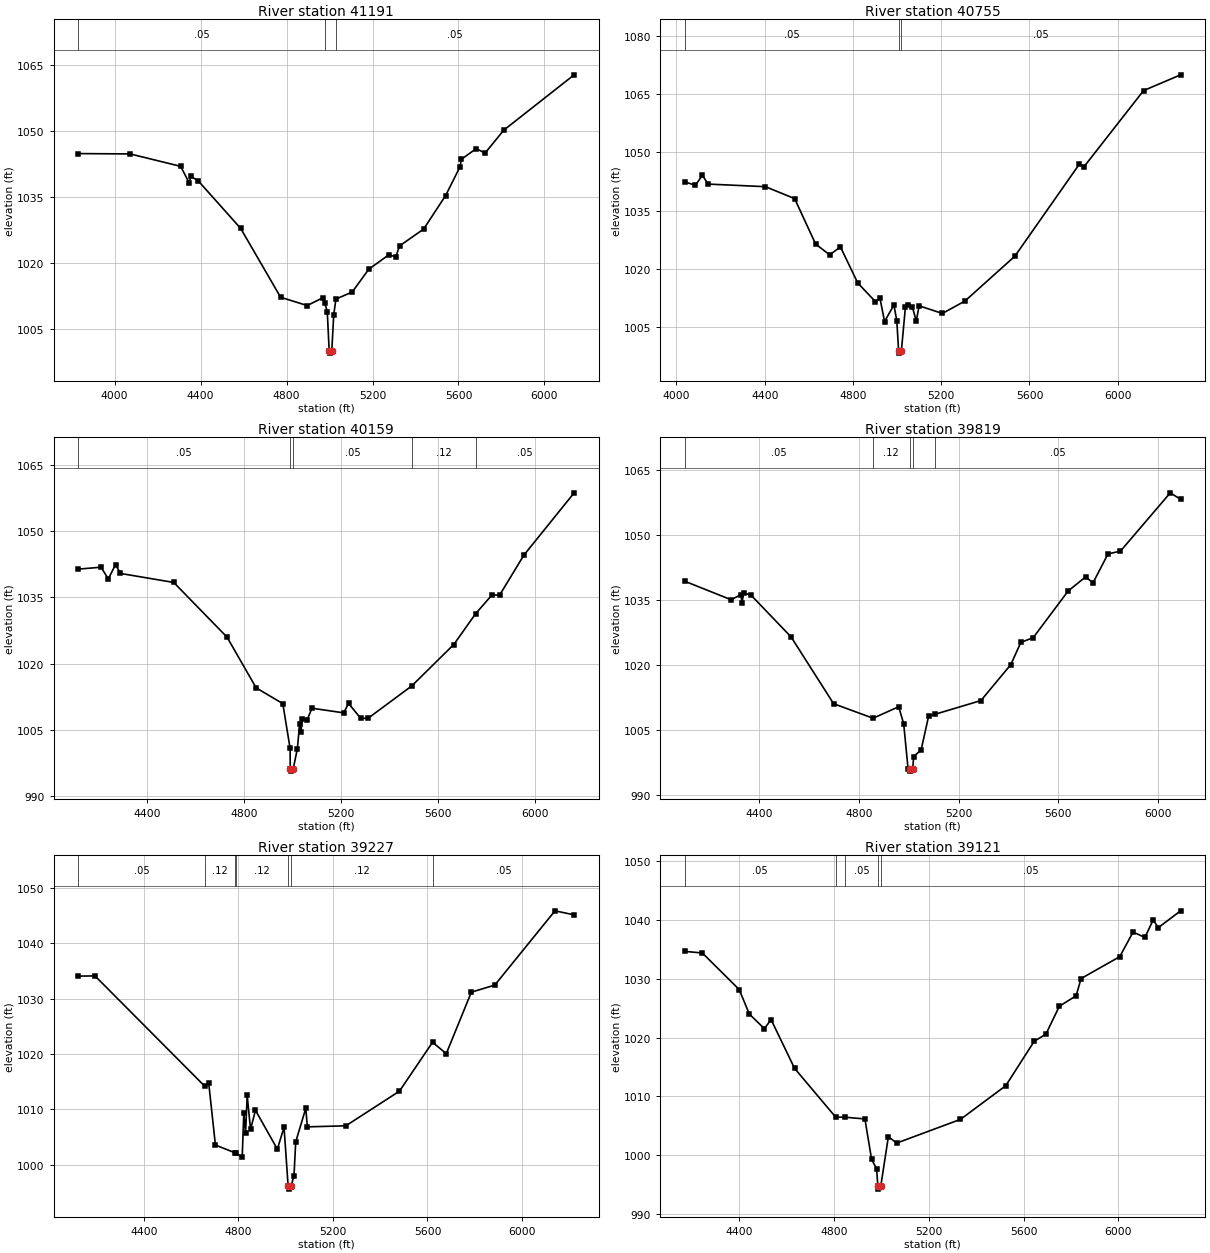
Type RM Length L Ch R = 1 ,41191   ,436,436,436
BEGIN DESCRIPTION:
DRY VALLEY CREEK 75.0
END DESCRIPTION:
XS GIS Cut Line= 3
      2215261.12      7269726.39      2214143.07      7270011.11
      2213012.54      7270239.99
#Sta/Elev= 30
  3831.1 1044.86  4072.2 1044.78  4307.3 1041.96  4348.2 1038.08  4353.3 1039.73
  4389.1 1038.66  4586.6 1027.86  4772.3 1012.22  4896.2 1010.34  4968.4  1012.1
  4978.7 1010.83  4989.5 1008.95  4998.3 1000.03    5000  999.53  5010.5 1000.03
  5019.6 1008.26  5029.8  1011.8  5105.8 1013.43  5182.8  1018.6  5274.7 1021.82
  5308.6 1021.44  5325.7 1023.88  5437.9 1027.71  5539.9  1035.3  5607.7 1041.91
  5612.8 1043.54  5682.8 1045.99  5723.6 1044.96  5810.5 1050.17  6138.3 1062.75
#Mann= 3 ,-1 , 0
  3831.1     .05       0  4978.7    .033       0  5029.8     .05       0
Bank Sta=4998.3,5010.5
XS Rating Curve= 0 ,0
Exp/Cntr=0.3,0.1

Type RM Length L Ch R = 1 ,40755   ,596,596,596
BEGIN DESCRIPTION:
DRY VALLEY CREEK 74.0
END DESCRIPTION:
XS GIS Cut Line= 3
      2215038.95      7269309.71        2214129.        7269610.
      2212887.13      7269955.28
#Sta/Elev= 30
  4037.8 1042.42  4085.9 1041.57  4117.6 1044.13  4143.1 1041.87  4403.4  1041.2
  4535.6 1038.13  4630.9 1026.42  4694.4 1023.66  4743.3 1025.69  4821.4 1016.44
  4901.2 1011.64  4922.3 1012.51  4943.1 1006.49  4985.5 1010.76  4998.6 1006.71
    5007  998.86  5008.7  998.36  5019.3  998.86  5037.5 1010.11  5047.4 1010.82
  5068.7 1010.36  5086.8 1006.61  5099.8 1010.54  5205.1 1008.57  5307.4 1011.76
  5533.9 1023.32  5826.4 1047.03  5847.1 1046.34    6117 1065.93    6285 1069.99
#Mann= 3 ,-1 , 0
  4037.8     .05       0    5007    .033       0  5019.3     .05       0
Bank Sta=5007,5019.3
XS Rating Curve= 0 ,0
Exp/Cntr=0.3,0.1

Type RM Length L Ch R = 1 ,40159   ,340,340,340
BEGIN DESCRIPTION:
DRY VALLEY CREEK 73.0
END DESCRIPTION:
XS GIS Cut Line= 3
      2214962.57      7269184.72      2214080.57      7269191.67
       2212922.4      7269302.63
#Sta/Elev= 30
  4116.5 1041.39  4210.1 1041.82  4240.1 1039.18  4270.1 1042.41  4290.1 1040.41
  4510.1 1038.37  4730.1 1025.97  4850.1 1014.49  4960.1 1010.92  4990.1 1000.78
  4990.7  996.13  4992.4  995.63    5003  996.13  5020.2 1000.74  5029.3 1006.32
  5034.4 1004.38  5040.3 1007.36  5060.4 1007.27  5080.5 1009.88  5211.1 1008.83
  5231.2 1010.96  5281.4  1007.6  5311.5 1007.59    5492 1014.93  5665.4 1024.31
  5755.9 1031.32  5823.9 1035.59    5854 1035.45  5954.5 1044.55    6162 1058.67
#Mann= 5 ,-1 , 0
  4116.5     .05       0  4990.7    .033       0    5003     .05       0
    5492     .12       0  5755.9     .05       0
Bank Sta=4990.7,5003
XS Rating Curve= 0 ,0
Exp/Cntr=0.3,0.1

Type RM Length L Ch R = 1 ,39819   ,592,592,592
BEGIN DESCRIPTION:
DRY VALLEY CREEK 72.0
END DESCRIPTION:
XS GIS Cut Line= 3
      2214823.66      7268997.23        2213929.        7268910.
      2212837.54      7268879.17
#Sta/Elev= 30
  4100.7 1039.32  4286.2 1035.06  4325.6 1036.19  4330.6 1034.39  4336.5 1036.64
  4366.6 1036.11  4527.4 1026.47  4698.2 1011.05  4856.6  1007.7  4959.4 1010.35
  4979.5 1006.45  4997.1  996.06  5003.5  995.99  5005.2  995.49  5015.8  995.99
  5019.6  998.86  5049.6 1000.39  5079.6 1008.17    5104 1008.59  5289.7 1011.78
  5409.8 1020.09  5449.8 1025.19  5499.8 1026.31  5639.9 1037.07  5709.9 1040.32
  5739.9 1038.97  5799.9 1045.63  5849.9 1046.27    6050 1059.73  6091.5 1058.23
#Mann= 5 ,-1 , 0
  4100.7     .05       0  4856.6     .12       0  5003.5     .07       0
  5015.8     .12       0    5104     .05       0
Bank Sta=5003.5,5015.8
XS Rating Curve= 0 ,0
Exp/Cntr=0.3,0.1

Type RM Length L Ch R = 1 ,39227   ,106,106,106
BEGIN DESCRIPTION:
DRY VALLEY CREEK 71.0
END DESCRIPTION:
XS GIS Cut Line= 3
      2214581.81      7268946.37      2213920.33      7268342.19
      2213107.82      7267456.77
#Sta/Elev= 30
  4122.9 1034.05  4193.4 1034.08  4657.2 1014.21  4674.4  1014.8  4702.8 1003.58
  4785.8 1002.18  4788.4 1002.15  4816.2  1001.4    4823  1009.4  4830.4 1005.72
  4837.2 1012.54  4851.4 1006.41  4872.3 1009.84  4964.9 1002.84  4993.2 1006.79
  5010.5  996.13  5012.2  995.63  5022.8  996.13  5035.3  998.06  5042.5 1004.14
  5085.1 1010.21  5091.8 1006.86  5254.6 1007.05  5481.5  1013.3  5621.4 1022.12
  5679.5 1020.06  5785.5 1031.15  5884.8 1032.43  6139.4 1045.82  6220.5 1045.09
#Mann= 7 ,-1 , 0
  4122.9     .05       0  4657.2     .12       0  4785.8     .05       0
  4788.4     .12       0  5010.5     .07       0  5022.8     .12       0
  5621.4     .05       0
Bank Sta=5010.5,5022.8
XS Rating Curve= 0 ,0
Exp/Cntr=0.3,0.1

Type RM Length L Ch R = 1 ,39121   ,675,675,675
BEGIN DESCRIPTION:
DRY VALLEY CREEK 70.0
END DESCRIPTION:
XS GIS Cut Line= 3
      2214571.39      7268852.63      2213988.04      7268269.27
      2213123.43      7267342.16
#Sta/Elev= 30
  4170.4 1034.65  4244.7 1034.37  4400.2 1028.15  4442.6    1024  4506.3 1021.51
  4534.6 1023.05  4633.6 1014.77  4807.3 1006.46  4846.1 1006.46  4930.6 1006.16
  4958.8   999.3  4980.1  997.68  4985.2  994.73  4986.9  994.23  4997.5  994.73
  5029.6 1003.14  5064.8 1002.06    5334 1006.09    5525 1011.81  5645.2 1019.37
  5694.5 1020.57  5751.2 1025.32    5822  1027.1    5843 1030.03  6006.2 1033.75
  6062.4 1037.93  6112.2 1037.02  6147.4 1039.99  6168.9 1038.68  6263.1 1041.54
#Mann= 5 ,-1 , 0
  4170.4     .05       0  4807.3     .12       0  4846.1     .05       0
  4985.2    .033       0  4997.5     .05       0
Bank Sta=4985.2,4997.5
XS Rating Curve= 0 ,0
Exp/Cntr=0.3,0.1