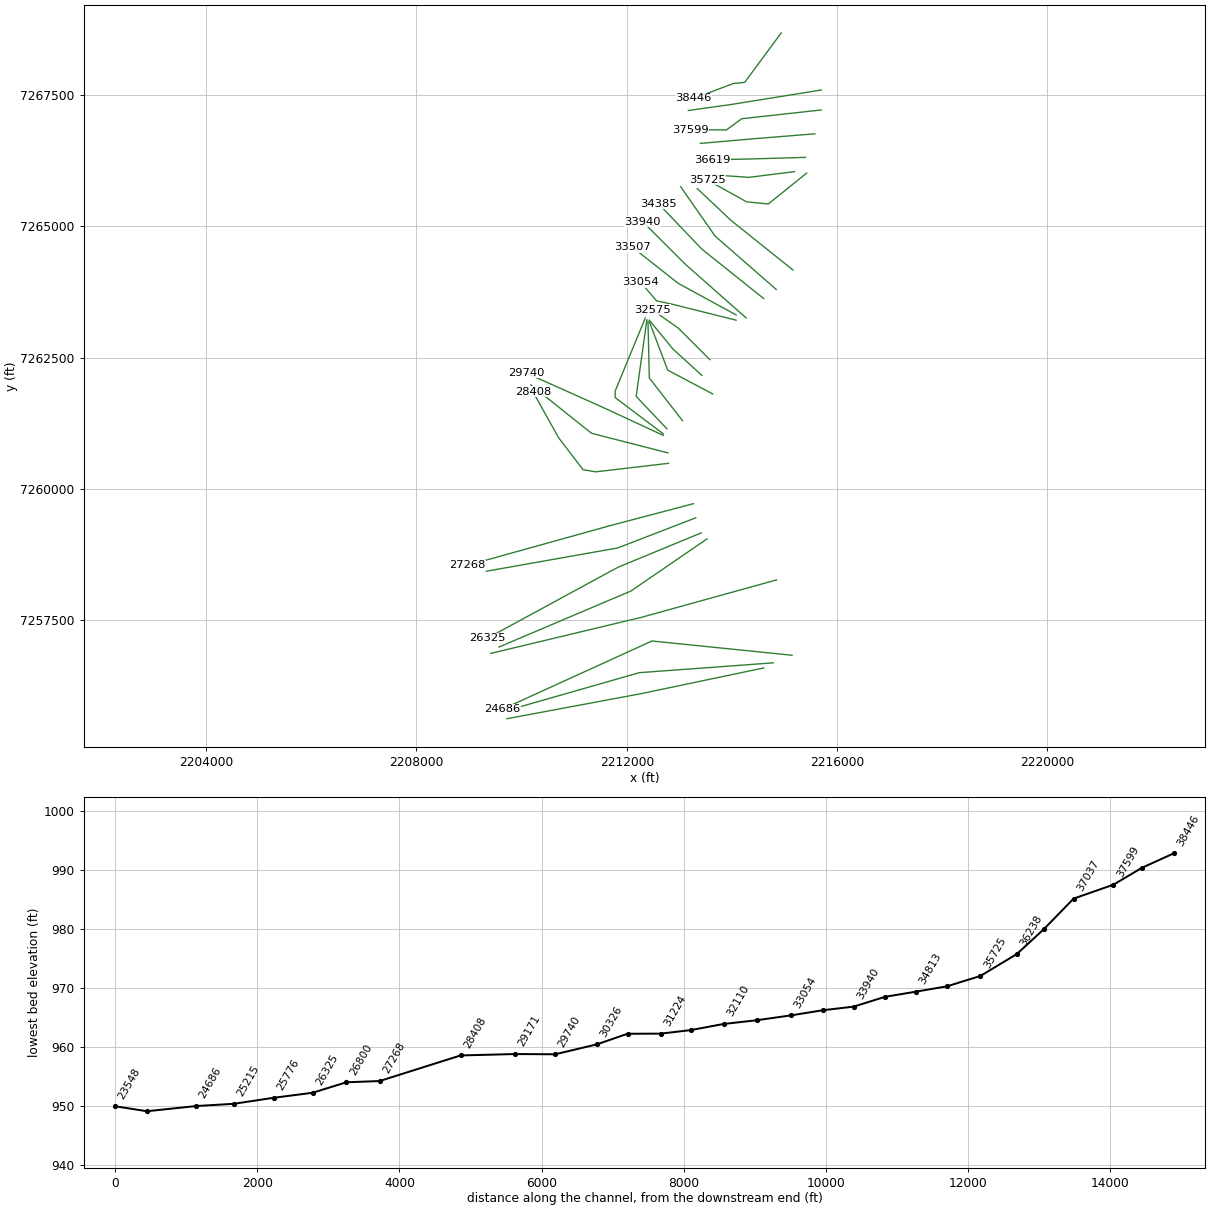
HEC-RAS study DRY VALLEY CREEK.prj: DRY VALLEY CREEK Base Level Engineering

--- DRY VALLEY CREEK.g01 (geometry) --- (continued)

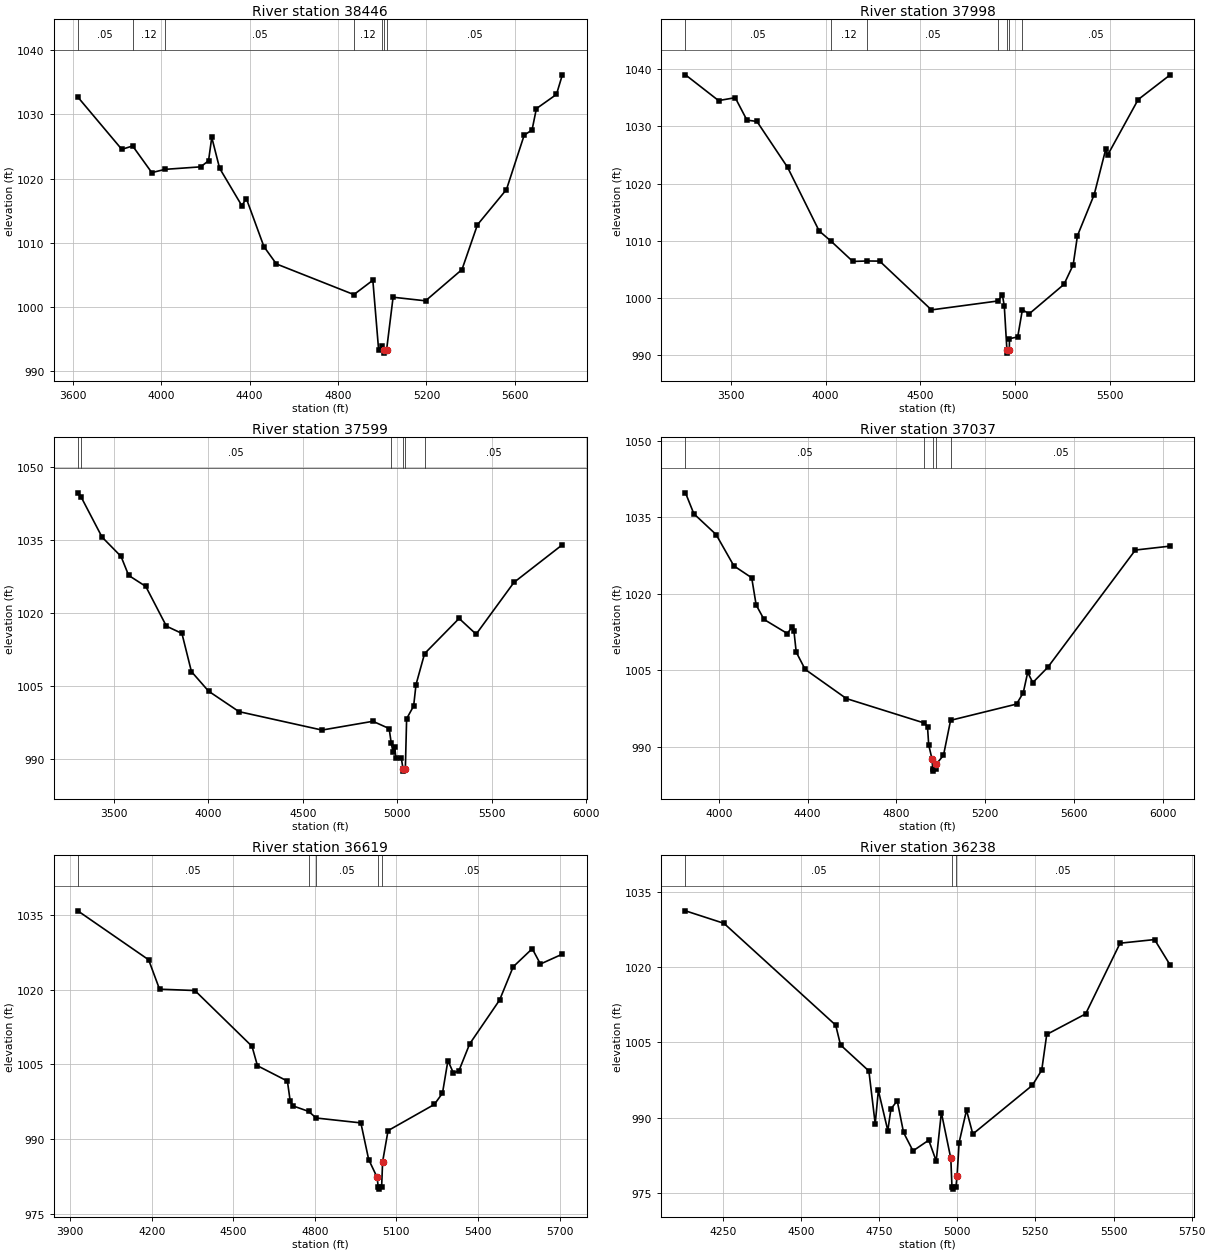
Type RM Length L Ch R = 1 ,38446   ,448,448,448
BEGIN DESCRIPTION:
DRY VALLEY CREEK 69.0
END DESCRIPTION:
XS GIS Cut Line= 4
      2214935.95      7268670.31      2214243.25      7267732.81
        2214029.        7267710.      2213269.32      7267425.54
#Sta/Elev= 30
  3622.9 1032.71  3822.1 1024.56  3871.1 1025.09  3957.8 1020.94  4017.7 1021.45
    4179 1021.84  4214.5 1022.79  4229.1 1026.42  4264.6 1021.62  4364.8 1015.81
  4385.7 1016.89  4465.1 1009.42  4521.4 1006.73    4872 1001.96  4957.8 1004.19
  4983.9  993.39  4998.4  993.91  5007.6  993.35  5009.4  992.85    5020  993.35
  5049.4 1001.55  5196.2 1000.99  5361.1 1005.86  5431.1 1012.83  5562.3 1018.31
  5642.5 1026.77  5678.1 1027.58  5697.7  1030.9  5788.5 1033.11  5815.2 1036.16
#Mann= 7 ,-1 , 0
  3622.9     .05       0  3871.1     .12       0  4017.7     .05       0
    4872     .12       0  4998.4     .05       0  5007.6    .033       0
    5020     .05       0
Bank Sta=5007.6,5020
XS Rating Curve= 0 ,0
Exp/Cntr=0.3,0.1

Type RM Length L Ch R = 1 ,37998   ,399,399,399
BEGIN DESCRIPTION:
DRY VALLEY CREEK 68.0
END DESCRIPTION:
XS GIS Cut Line= 3
      2215701.61      7267586.99        2213979.        7267310.
      2213172.16      7267196.61
#Sta/Elev= 30
  3260.3    1039  3435.1  1034.5    3523 1035.01  3584.9 1031.09  3637.7 1030.86
  3799.7 1022.84  3966.3 1011.74  4028.9 1009.96  4144.1 1006.41  4218.6 1006.49
  4285.9 1006.47  4559.4  997.95  4911.1  999.51  4934.1 1000.59  4944.3   998.6
  4958.2   990.9    4960   990.4  4970.9   990.9  4971.6  992.92  5015.1  993.23
  5039.8  997.97  5075.7  997.26  5259.5 1002.41    5308 1005.81  5330.8 1010.92
  5419.1 1018.09  5479.7 1025.96  5489.7 1024.96  5651.3 1034.68  5819.8 1038.98
#Mann= 7 ,-1 , 0
  3260.3     .05       0  4028.9     .12       0  4218.6     .05       0
  4911.1     .12       0  4958.2     .07       0  4970.9     .12       0
  5039.8     .05       0
Bank Sta=4958.2,4970.9
XS Rating Curve= 0 ,0
Exp/Cntr=0.3,0.1

Type RM Length L Ch R = 1 ,37599   ,562,562,562
BEGIN DESCRIPTION:
DRY VALLEY CREEK 67.0
END DESCRIPTION:
XS GIS Cut Line= 4
      2215696.39      7267206.78      2214185.95      7267040.11
      2213894.29      7266826.56      2213212.99      7266831.77
#Sta/Elev= 30
  3310.3 1044.62  3328.6 1043.72  3438.5 1035.55  3539.1 1031.58  3579.3 1027.69
  3669.9 1025.43  3778.9 1017.28    3861 1015.79  3911.3 1007.96  4001.9 1003.95
  4162.8  999.75  4601.7  995.97    4871  997.77  4956.7  996.28  4967.4  993.42
  4977.5  991.39    4986  992.54  4992.2  990.31  5021.5  990.17  5029.8  988.05
  5031.6  987.55  5042.5  988.05  5049.2   998.3  5086.3  1000.9  5098.8 1005.29
  5144.2 1011.65  5326.7 1018.86  5416.7 1015.63  5616.7 1026.25  5872.7 1033.97
#Mann= 6 ,-1 , 0
  3310.3     .12       0  3328.6     .05       0  4967.4     .12       0
  5029.8     .07       0  5042.5     .12       0  5144.2     .05       0
Bank Sta=5029.8,5042.5
XS Rating Curve= 0 ,0
Exp/Cntr=0.3,0.1

Type RM Length L Ch R = 1 ,37037   ,418,418,418
BEGIN DESCRIPTION:
DRY VALLEY CREEK 66.0
END DESCRIPTION:
XS GIS Cut Line= 3
      2215576.63      7266753.65      2214420.33       7266659.9
      2213399.45      7266571.35
#Sta/Elev= 30
    3849  1039.8  3886.8 1035.69  3987.1 1031.61  4067.3 1025.46  4147.6 1023.13
  4167.7 1017.79  4203.2 1014.95  4308.1 1012.19  4330.2 1013.49  4338.2  1012.6
  4348.3 1008.54  4388.4 1005.16  4574.4  999.42  4925.9  994.62  4940.2  993.92
  4945.6  990.32  4960.3   987.6  4963.9  985.68  4965.7  985.18  4976.6  985.68
  4980.3  986.58  5012.3  988.29  5044.3  995.15  5341.7  998.34  5371.8 1000.55
  5391.9 1004.55    5415 1002.56  5482.2 1005.54  5877.3 1028.57  6033.8 1029.34
#Mann= 5 ,-1 , 0
    3849     .05       0  4925.9     .12       0  4963.9     .07       0
  4976.6     .12       0  5044.3     .05       0
Bank Sta=4960.3,4980.3
XS Rating Curve= 0 ,0
Exp/Cntr=0.3,0.1

Type RM Length L Ch R = 1 ,36619   ,381,381,381
BEGIN DESCRIPTION:
DRY VALLEY CREEK 65.0
END DESCRIPTION:
XS GIS Cut Line= 3
      2215399.46      7266305.73      2214326.58      7266274.48
      2213618.29      7266258.86
#Sta/Elev= 30
  3928.3  1035.8  4188.9 1025.98  4228.9 1020.09  4358.9 1019.82    4569 1008.63
    4589 1004.74  4699.1 1001.66  4709.1  997.77  4719.1   996.7  4777.3  995.58
  4804.9  994.26  4969.2  993.28  4997.9  985.94  5029.2  982.34  5032.8   980.5
  5034.6     980  5045.6   980.5  5049.2   985.5  5069.2  991.73  5239.3  996.98
  5269.3  999.24  5289.3 1005.77  5309.3 1003.31  5329.3 1003.67  5369.3 1009.12
  5479.3 1017.91  5529.3 1024.58  5599.4 1028.21  5629.4 1025.13  5710.1 1027.12
#Mann= 5 ,-1 , 0
  3928.3     .05       0  4777.3     .12       0  4804.9     .05       0
  5032.8    .033       0  5045.6     .05       0
Bank Sta=5029.2,5049.2
XS Rating Curve= 0 ,0
Exp/Cntr=0.3,0.1

Type RM Length L Ch R = 1 ,36238   ,513,513,513
BEGIN DESCRIPTION:
DRY VALLEY CREEK 64.0
END DESCRIPTION:
XS GIS Cut Line= 3
      2215191.13      7266034.89      2214321.37      7265925.52
      2213649.52       7265972.4
#Sta/Elev= 30
  4130.8 1031.16  4253.9 1028.67  4611.3 1008.41  4626.8 1004.47  4717.5  999.29
  4737.7  988.76  4747.8  995.42    4778  987.43  4788.1  991.75  4808.2  993.35
  4828.4  987.05  4858.6  983.39    4909  985.52  4932.8  981.38  4949.3  991.02
  4979.6  981.88  4983.2  976.28    4985  975.78    4996  976.28  4999.7  978.44
  5006.1  985.05  5029.8   991.5  5049.9  986.74  5240.3  996.43  5270.4  999.46
  5286.4 1006.56  5410.8 1010.65    5521 1024.72  5631.3 1025.44  5680.9  1020.4
#Mann= 3 ,-1 , 0
  4130.8     .05       0  4983.2    .033       0    4996     .05       0
Bank Sta=4979.6,4999.7
XS Rating Curve= 0 ,0
Exp/Cntr=0.3,0.1

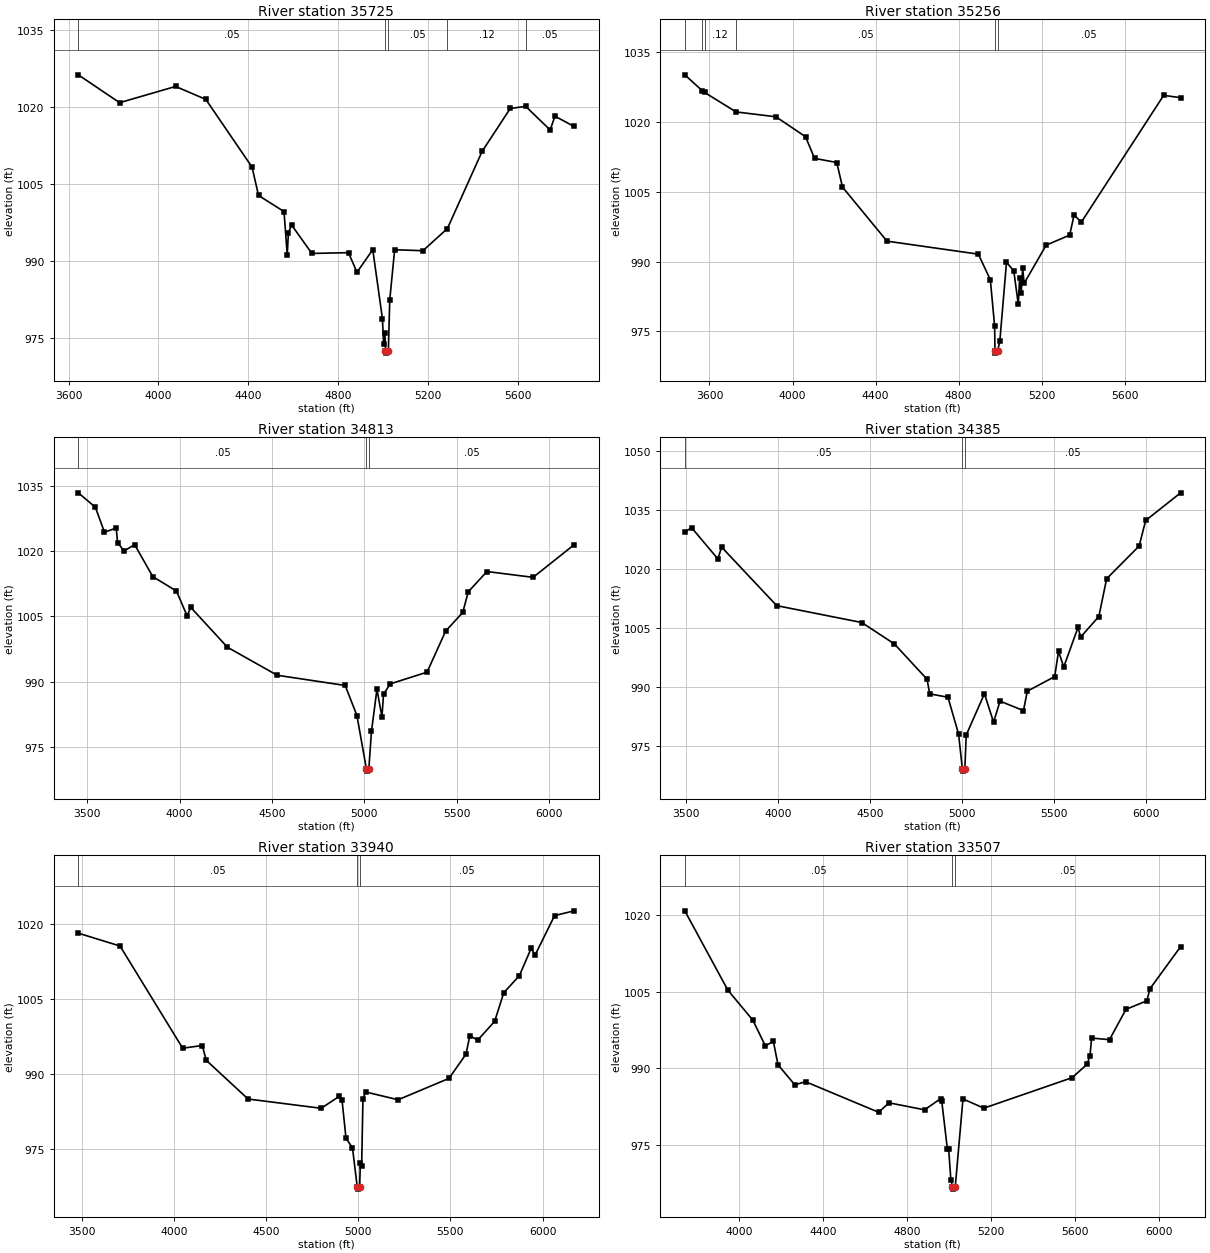
Type RM Length L Ch R = 1 ,35725   ,469,469,469
BEGIN DESCRIPTION:
DRY VALLEY CREEK 63.0
END DESCRIPTION:
XS GIS Cut Line= 4
      2215420.99       7266007.3      2214691.81      7265418.75
        2214279.        7265460.      2213530.37      7265877.07
#Sta/Elev= 30
  3643.5 1026.19  3827.4 1020.77  4076.8 1023.93  4211.5 1021.41  4417.5 1008.23
  4446.2 1002.73  4559.8  999.59  4574.2  991.15  4579.2  995.42  4593.4  996.99
  4683.9  991.45  4847.1   991.6  4884.9  987.78  4955.2  992.19  4998.3  978.73
  5003.4  973.84  5009.2  975.93  5011.9  972.56  5013.7  972.06  5024.7  972.56
  5030.9  982.43  5052.7  992.17  5178.6  991.98  5287.7  996.29  5442.4  1011.3
  5567.8 1019.65  5636.6 1020.05  5745.3 1015.47    5767 1018.14  5852.4 1016.14
#Mann= 5 ,-1 , 0
  3643.5     .05       0  5011.9    .033       0  5024.7     .05       0
  5287.7     .12       0  5636.6     .05       0
Bank Sta=5011.9,5024.7
XS Rating Curve= 0 ,0
Exp/Cntr=0.3,0.1

Type RM Length L Ch R = 1 ,35256   ,443,443,443
BEGIN DESCRIPTION:
DRY VALLEY CREEK 62.0
END DESCRIPTION:
XS GIS Cut Line= 3
      2215160.58      7264163.53        2213979.        7265110.
      2213343.41      7265709.89
#Sta/Elev= 30
  3481.2 1030.18  3565.1 1026.77  3576.5 1026.39  3728.1  1022.2  3920.3 1021.15
  4062.8 1016.86    4106 1012.21  4213.2 1011.31  4240.5 1006.04  4454.9   994.4
  4895.1   991.6  4952.7  986.08  4973.5  976.08  4974.9  970.81  4976.8  970.31
  4988.1  970.81  4998.6     973  5030.5  989.85  5065.7  987.99  5087.2  980.81
    5094  986.56  5101.3  983.14  5108.2  988.58  5115.5  985.32  5221.5  993.54
  5334.7  995.69  5355.8  999.98  5391.4  998.52  5787.5 1025.77  5869.1 1025.26
#Mann= 6 ,-1 , 0
  3481.2     .12       0  3565.1     .05       0  3576.5     .12       0
  3728.1     .05       0  4974.9    .033       0  4988.1     .05       0
Bank Sta=4974.9,4988.1
XS Rating Curve= 0 ,0
Exp/Cntr=0.3,0.1

Type RM Length L Ch R = 1 ,34813   ,428,428,428
BEGIN DESCRIPTION:
DRY VALLEY CREEK 61.0
END DESCRIPTION:
XS GIS Cut Line= 3
      2214842.87      7263793.74        2213679.        7264810.
      2213025.78      7265745.97
#Sta/Elev= 30
  3450.9  1033.4  3543.2 1030.08  3592.5 1024.34  3656.1  1025.3  3663.7 1021.95
  3698.9 1020.02  3755.8 1021.49  3854.5 1014.12  3982.7 1010.81  4039.7 1005.16
  4060.5 1007.03  4258.9  997.88  4528.5  991.44  4896.8  989.09  4960.4  982.17
  5011.7  969.89  5013.5  969.39  5024.9  969.89  5039.2  978.55  5068.9   988.2
  5095.9  981.87  5104.6  987.06  5140.4  989.45  5340.2  992.15  5441.4 1001.62
  5533.8 1005.88  5563.5 1010.63  5664.7  1015.3    5915 1013.96  6137.4 1021.47
#Mann= 3 ,-1 , 0
  3450.9     .05       0  5011.7    .033       0  5024.9     .05       0
Bank Sta=5011.7,5024.9
XS Rating Curve= 0 ,0
Exp/Cntr=0.3,0.1

Type RM Length L Ch R = 1 ,34385   ,445,445,445
BEGIN DESCRIPTION:
DRY VALLEY CREEK 60.0
END DESCRIPTION:
XS GIS Cut Line= 3
      2214603.27      7263621.88        2213429.        7264560.
      2212603.61       7265423.6
#Sta/Elev= 30
  3492.6  1029.5  3529.9 1030.55  3672.4 1022.62  3693.2  1025.6  3992.6  1010.7
  4455.3  1006.4    4633 1000.94  4810.7  991.93  4825.1  988.22  4924.4  987.36
    4982  977.99  5002.9  969.03  5004.8  968.53  5016.2  969.03  5023.7  977.73
  5122.8  988.25  5172.5  981.01  5207.7  986.37  5335.1  983.95  5356.2  988.91
  5504.9  992.61    5526  999.06  5554.3  995.07    5632 1005.16  5646.2 1002.69
  5745.2 1007.93  5787.7 1017.57  5964.4 1025.89    6000  1032.4  6190.2 1039.45
#Mann= 3 ,-1 , 0
  3492.6     .05       0  5002.9    .033       0  5016.2     .05       0
Bank Sta=5002.9,5016.2
XS Rating Curve= 0 ,0
Exp/Cntr=0.3,0.1

Type RM Length L Ch R = 1 ,33940   ,433,433,433
BEGIN DESCRIPTION:
DRY VALLEY CREEK 59.0
END DESCRIPTION:
XS GIS Cut Line= 3
      2214269.94      7263252.08        2213129.        7264260.
      2212302.81       7265083.8
#Sta/Elev= 30
    3482 1018.19  3708.2 1015.61  4047.8  995.12    4154  995.66  4175.8  992.69
  4402.5  984.93    4799  983.07  4897.7  985.48  4911.9  984.82  4933.7  977.04
  4968.8  975.16  4994.4  967.36  4996.3  966.86  5007.7  967.36  5011.5  972.18
  5018.5  971.43  5025.6  984.92  5039.7  986.35  5216.5  984.78  5492.3  989.07
  5584.2  993.91  5605.4  997.64  5647.8  996.73  5739.8  1000.5  5789.3 1006.24
  5874.1 1009.67  5937.8 1015.15    5959 1013.78    6065 1021.71  6171.1 1022.67
#Mann= 3 ,-1 , 0
    3482     .05       0  4994.4    .033       0  5007.7     .05       0
Bank Sta=4994.4,5007.7
XS Rating Curve= 0 ,0
Exp/Cntr=0.3,0.1

Type RM Length L Ch R = 1 ,33507   ,453,453,453
BEGIN DESCRIPTION:
DRY VALLEY CREEK 58.0
END DESCRIPTION:
XS GIS Cut Line= 3
      2214078.98      7263310.01        2212979.        7263910.
      2212109.03       7264595.4
#Sta/Elev= 30
  3741.3 1020.88  3946.3 1005.31  4065.4  999.41  4125.2  994.34  4162.7   995.3
    4185  990.65  4265.3  986.72    4316  987.34  4663.9  981.34  4713.8  983.19
  4882.7  981.82  4958.7  983.99  4964.4  983.59  4991.4  974.11  4997.5  974.11
  5007.9  968.12  5015.7  966.75  5017.6  966.25    5029  966.75  5065.6  983.96
    5165  982.14  5585.2  988.13  5656.3  990.75  5670.1   992.4  5678.2   995.9
  5763.2  995.59  5841.7 1001.54  5941.1 1003.22  5955.6 1005.57  6101.8 1013.85
#Mann= 3 ,-1 , 0
  3741.3     .05       0  5015.7    .033       0    5029     .05       0
Bank Sta=5015.7,5029
XS Rating Curve= 0 ,0
Exp/Cntr=0.3,0.1

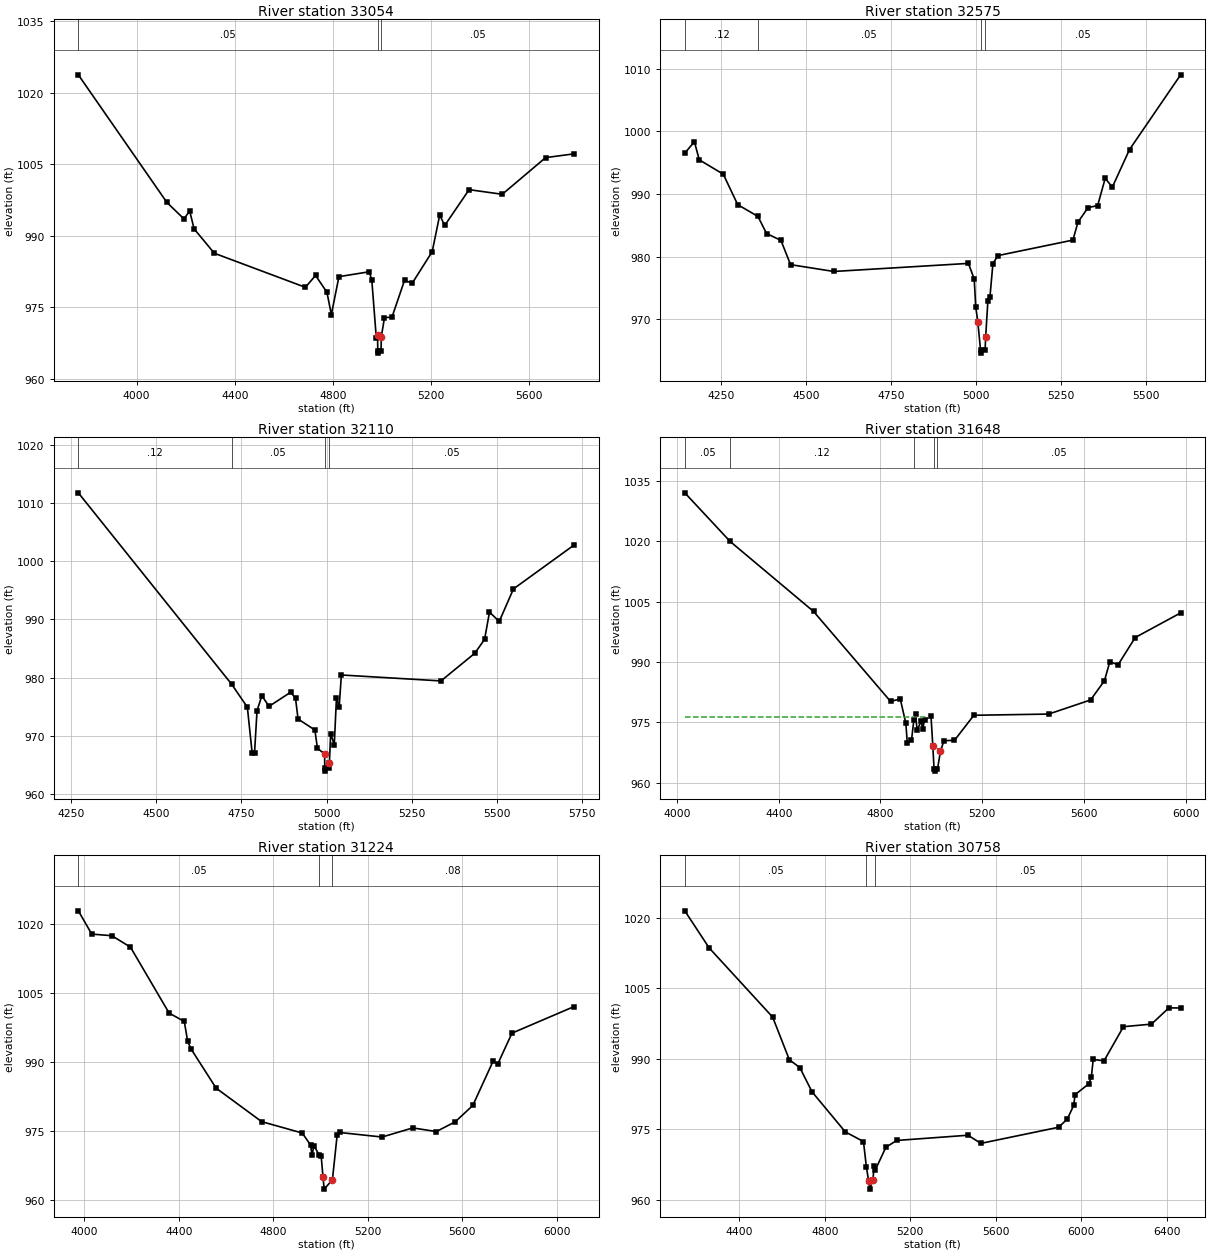
Type RM Length L Ch R = 1 ,33054   ,479,479,479
BEGIN DESCRIPTION:
DRY VALLEY CREEK 57.0
END DESCRIPTION:
XS GIS Cut Line= 4
      2214079.03      7263209.99        2212879.        7263510.
      2212567.28      7263577.19      2212264.72      7263929.18
#Sta/Elev= 30
    3763 1023.75  4123.8  996.98  4193.4  993.53  4216.6   995.2  4234.6  991.44
  4317.1  986.32  4688.2  979.17  4729.4  981.67  4775.8  978.14  4793.8  973.46
  4824.7  981.41  4948.4  982.44  4958.7  980.62  4976.8  968.64  4981.9  969.19
    4983  965.87  4984.9  965.37  4996.3  965.87  4997.4  968.82  5010.2  972.81
  5040.9  972.93    5092  980.65  5123.2  980.03  5204.6  986.65  5235.2  994.31
  5255.7  992.16    5355  999.66    5490  998.69  5666.7 1006.38    5783 1007.18
#Mann= 3 ,-1 , 0
    3763     .05       0    4983    .033       0  4996.3     .05       0
Bank Sta=4981.9,4997.4
XS Rating Curve= 0 ,0
Exp/Cntr=0.3,0.1

Type RM Length L Ch R = 1 ,32575   ,465,465,465
BEGIN DESCRIPTION:
DRY VALLEY CREEK 56.0
END DESCRIPTION:
XS GIS Cut Line= 3
      2213579.03      7262459.97        2212979.        7263060.
        2212479.        7263410.
#Sta/Elev= 30
  4143.1  996.55  4171.4  998.35  4185.6  995.47  4256.3  993.17  4298.7   988.3
  4358.4  986.41  4383.6  983.68    4426  982.58  4454.3   978.7  4581.5  977.61
  4977.5   978.9  4994.7  976.41  4999.1  971.96  5005.2  969.56  5013.3  965.05
  5015.2  964.55  5026.7  965.05  5028.3  967.07  5034.8  972.85  5040.9  973.51
  5049.7  978.87  5064.5  980.15  5285.1  982.63  5299.9  985.49  5329.5  987.82
  5357.9  988.15  5380.1  992.52    5401  991.09  5451.6  997.11    5602 1009.06
#Mann= 4 ,-1 , 0
  4143.1     .12       0  4358.4     .05       0  5013.3    .033       0
  5026.7     .05       0
Bank Sta=5005.2,5028.3
XS Rating Curve= 0 ,0
Exp/Cntr=0.3,0.1

Type RM Length L Ch R = 1 ,32110   ,462,462,462
BEGIN DESCRIPTION:
DRY VALLEY CREEK 55.0
END DESCRIPTION:
XS GIS Cut Line= 3
      2213428.99      7262160.01        2212879.        7262660.
      2212429.01      7263209.99
#Sta/Elev= 30
  4272.3 1011.74  4721.9  978.85  4767.9  974.91  4782.1  966.99  4788.9  966.97
  4796.3  974.31  4810.5  976.87  4831.4  975.05    4895  977.48  4909.2  976.42
  4916.6  972.87  4965.9  970.99  4973.4  967.85  4994.3  966.87    4995  964.42
  4996.9  963.92  5008.4  964.42  5008.5  965.37  5012.2  970.35  5022.8  968.45
  5029.2   976.5  5037.1  974.92  5043.6  980.44  5335.7  979.42  5434.8  984.17
  5463.5  986.56  5477.9  991.23  5506.6  989.65  5548.2  995.23  5726.2 1002.78
#Mann= 4 ,-1 , 0
  4272.3     .12       0  4721.9     .05       0    4995    .033       0
  5008.4     .05       0
Bank Sta=4994.3,5008.5
XS Rating Curve= 0 ,0
Exp/Cntr=0.3,0.1

Type RM Length L Ch R = 1 ,31648   ,424,424,424
BEGIN DESCRIPTION:
DRY VALLEY CREEK 54.0
END DESCRIPTION:
XS GIS Cut Line= 3
      2213632.26       7261808.5        2212779.        7262260.
      2212429.97      7263180.07
#Sta/Elev= 30
  4030.8 1032.09    4209    1020  4537.2 1002.58  4839.6  980.23    4878  980.81
    4900  974.74  4905.6  969.79    4922  970.53  4931.3  975.51  4938.3     977
    4944  973.08  4960.3  975.28    4966   973.4  4973.5  975.59  4998.8  976.57
  5005.9  969.14  5010.8  963.38  5012.7  962.88  5024.2  963.38    5036  967.78
  5049.6  970.46    5091  970.53  5167.3  976.77  5461.4  977.07  5626.2  980.58
  5680.7  985.36    5702  990.11  5734.1  989.31  5801.7  996.11  5980.2 1002.23
#Mann= 5 ,-1 , 0
  4030.8     .05       0    4209     .12       0  4931.3     .05       0
  5010.8    .033       0  5024.2     .05       0
#XS Ineff= 2 , 0
         4988.15  976.46
Permanent Ineff=
       F       F
Bank Sta=5005.9,5036
XS Rating Curve= 0 ,0
Exp/Cntr=0.3,0.1

Type RM Length L Ch R = 1 ,31224   ,466,466,466
BEGIN DESCRIPTION:
DRY VALLEY CREEK 53.0
END DESCRIPTION:
XS GIS Cut Line= 3
      2213059.31      7261300.71        2212429.        7262110.
      2212403.97      7263183.22
#Sta/Elev= 30
  3974.4  1022.8  4031.2 1017.74  4116.2 1017.39    4195 1014.91  4358.7 1000.57
    4423  998.74  4437.4  994.41  4451.9  992.74  4557.8  984.24  4750.5  976.96
  4922.4  974.48  4957.7  971.87    4964  969.65  4972.1  971.76  4992.9  969.78
  5002.7   969.4  5010.2  964.98  5015.3  962.28  5050.2  964.31  5070.2  974.04
  5080.2   974.6  5260.3  973.61  5390.3  975.59  5490.3   974.8  5570.3  976.93
  5644.5  980.47  5730.4   990.1  5750.4  989.52  5810.4   996.2  6073.7 1001.99
#Mann= 3 ,-1 , 0
  3974.4     .05       0  4992.9    .033       0  5050.2     .08       0
Bank Sta=5010.2,5050.2
XS Rating Curve= 0 ,0
Exp/Cntr=0.3,0.1

Type RM Length L Ch R = 1 ,30758   ,432,432,432
BEGIN DESCRIPTION:
DRY VALLEY CREEK 52.0
END DESCRIPTION:
XS GIS Cut Line= 3
      2212764.18      7261144.45        2212179.        7261760.
      2212382.24      7263214.75
#Sta/Elev= 30
  4145.8  1021.5  4259.6 1013.61  4556.5  998.88  4634.5  989.81  4683.9  988.11
  4740.5  982.98  4896.2  974.45  4981.1  972.39  4995.1  966.88  5005.2  964.05
  5010.5  962.26  5025.4  964.28  5030.9   967.1  5035.9  966.29    5086  971.18
  5136.5  972.62  5469.8  973.73  5530.3     972  5893.6  975.43  5934.2  977.18
  5964.4  980.11  5970.1  982.35  6035.1  984.69  6046.7   986.2  6055.3  989.86
  6105.8  989.56  6196.7  996.84  6327.5  997.38  6409.1 1000.84    6464 1000.82
#Mann= 3 ,-1 , 0
  4145.8     .05       0  4995.1    .033       0  5035.9     .05       0
Bank Sta=5005.2,5025.4
XS Rating Curve= 0 ,0
Exp/Cntr=0.3,0.1

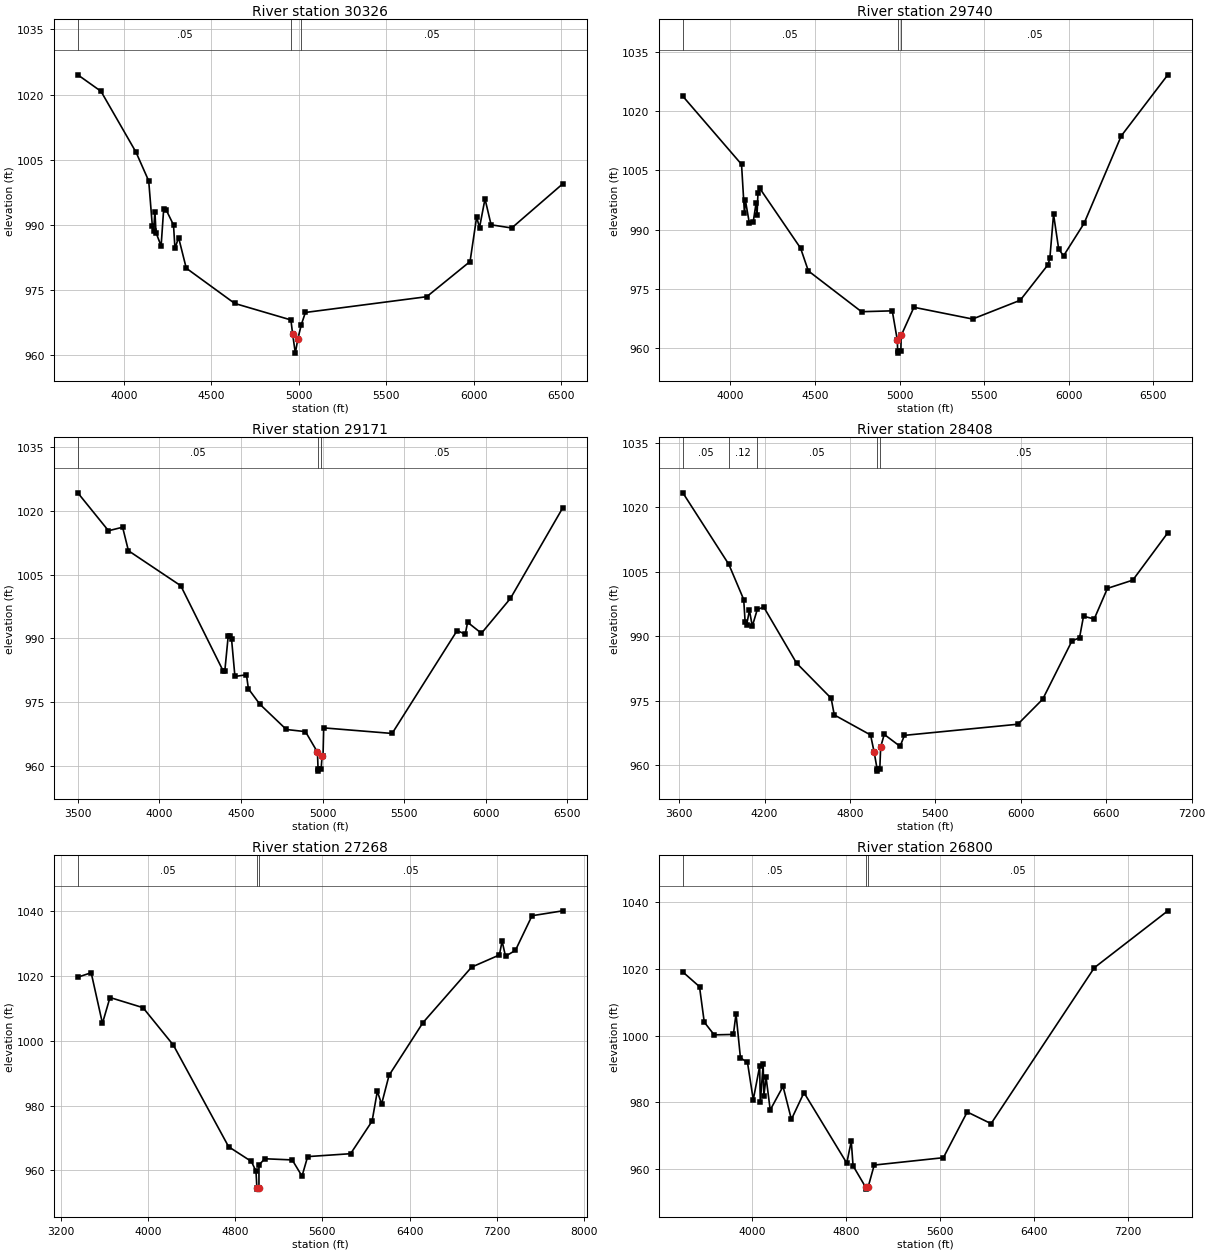
Type RM Length L Ch R = 1 ,30326   ,586,586,586
BEGIN DESCRIPTION:
DRY VALLEY CREEK 51.0
END DESCRIPTION:
XS GIS Cut Line= 4
      2212694.71      7261048.98      2211778.94      7261739.06
        2211779.        7261860.       2212351.6      7263249.65
#Sta/Elev= 30
  3737.4 1024.53  3869.9 1020.74  4070.1 1006.71  4142.6  1000.1  4163.4  989.69
  4170.3  988.62    4178  993.05  4184.2  988.22  4213.4  985.12  4227.9  993.53
  4242.5  993.41  4284.2  989.98  4292.5  984.56  4313.3  987.06    4357  980.02
  4633.9   971.9    4955   968.1    4965  964.77  4980.2  960.46    4995  963.82
  5014.3  966.98  5037.4  969.82  5730.9  973.45  5978.4  981.55  6015.9  991.77
  6032.5  989.36  6063.8  995.97  6098.6     990  6216.4  989.27    6508  999.44
#Mann= 3 ,-1 , 0
  3737.4     .05       0    4955    .033       0  5014.3     .05       0
Bank Sta=4965,4995
XS Rating Curve= 0 ,0
Exp/Cntr=0.3,0.1

Type RM Length L Ch R = 1 ,29740   ,569,569,569
BEGIN DESCRIPTION:
DRY VALLEY CREEK 50.0
END DESCRIPTION:
XS GIS Cut Line= 3
      2212691.93      7261020.49        2211529.        7261560.
      2210082.39      7262207.29
#Sta/Elev= 30
  3718.5 1023.71  4065.4  1006.5  4082.8   994.1  4088.3  997.42  4111.2  991.71
  4134.1  991.86  4151.5  996.73    4157  993.73  4162.7  999.38  4173.7  1000.4
  4414.5  985.31  4460.3  979.56  4774.6  969.25  4956.4  969.47  4986.3  962.06
  4988.3  959.28  4990.3  958.78  5007.2  959.28  5009.3  963.26  5084.4  970.37
  5431.1   967.4  5712.6  972.14  5876.9  981.12  5887.9  982.73  5909.8  993.88
  5940.1  985.11  5968.8  983.36  6090.3  991.59    6310 1013.69  6585.3 1029.13
#Mann= 3 ,-1 , 0
  3718.5     .05       0  4988.3    .033       0  5007.2     .05       0
Bank Sta=4986.3,5009.3
XS Rating Curve= 0 ,0
Exp/Cntr=0.3,0.1

Type RM Length L Ch R = 1 ,29171   ,763,763,763
BEGIN DESCRIPTION:
DRY VALLEY CREEK 49.0
END DESCRIPTION:
XS GIS Cut Line= 3
      2212782.12      7260687.19        2211329.        7261060.
      2210177.97      7261978.87
#Sta/Elev= 30
  3499.3  1024.2  3687.4 1015.29  3774.1 1016.12  3809.7  1010.6  4130.7 1002.37
  4390.4  982.36  4400.7   982.4  4421.3  990.51  4431.7  990.65    4442   989.8
  4462.6  981.06  4533.2  981.46  4545.2  978.17  4614.8  974.56  4777.8   968.6
    4895   968.1  4968.5  963.28  4972.2  959.32  4974.2  958.82  4991.1  959.32
  4996.9  962.35  5002.7  962.35  5006.7  968.98  5426.2  967.67  5824.9  991.85
  5874.5  990.97  5888.9  993.79  5973.8  991.21  6151.5  999.39  6472.3 1020.68
#Mann= 3 ,-1 , 0
  3499.3     .05       0  4972.2     .04       0  4991.1     .05       0
Bank Sta=4968.5,4996.9
XS Rating Curve= 0 ,0
Exp/Cntr=0.3,0.1

Type RM Length L Ch R = 1 ,28408   ,1140,1140,1140
BEGIN DESCRIPTION:
DRY VALLEY CREEK 48.0
END DESCRIPTION:
XS GIS Cut Line= 5
      2212793.46      7260488.18      2211413.29      7260326.72
      2211169.76       7260366.9      2210707.09      7260970.78
      2210214.89       7261851.3
#Sta/Elev= 30
  3626.2 1023.39  3949.2 1006.72  4053.6  998.54  4063.6  993.29  4073.7  992.59
  4093.8  996.02    4114  992.33  4148.8  996.22  4194.5  996.78  4424.6  983.74
  4667.7  975.55  4689.6  971.67  4944.6     967  4969.8  962.97  4990.5  959.08
  4992.5  958.58  5009.4  959.08  5015.4  964.19  5040.4  967.13  5151.9  964.35
  5182.3  966.91  5978.7   969.5  6153.4  975.33    6359  988.91    6412  989.63
  6440.1  994.66  6515.1  994.01    6608 1001.14  6786.1 1003.06  7032.1 1014.09
#Mann= 5 ,-1 , 0
  3626.2     .05       0  3949.2     .12       0  4148.8     .05       0
  4990.5    .033       0  5009.4     .05       0
Bank Sta=4969.8,5015.4
XS Rating Curve= 0 ,0
Exp/Cntr=0.3,0.1

Type RM Length L Ch R = 1 ,27268   ,468,468,468
BEGIN DESCRIPTION:
DRY VALLEY CREEK 46.0
END DESCRIPTION:
XS GIS Cut Line= 3
      2213267.89      7259720.82      2211688.03      7259304.15
      2208972.55      7258549.37
#Sta/Elev= 30
  3354.6 1019.62  3477.6 1020.99    3581 1005.38  3650.1 1013.35  3953.3 1010.22
  4232.5  998.64  4739.3  967.32  4948.6  962.77  4990.6  959.74  4998.7  954.74
  5000.7  954.24  5017.7  954.74    5018  961.67  5070.5  963.61  5323.1  963.25
    5413  958.25  5464.9  964.27  5859.3  965.17  6056.5  975.22  6104.4   984.4
  6143.8   980.5  6212.2  989.35  6523.6  1005.6  6969.9 1022.72    7225 1026.47
  7250.1 1030.73  7281.3 1026.08  7372.3 1027.89  7524.8 1038.58  7806.9 1040.09
#Mann= 3 ,-1 , 0
  3354.6     .05       0  4998.7    .033       0  5017.7     .05       0
Bank Sta=4998.7,5017.7
XS Rating Curve= 0 ,0
Exp/Cntr=0.3,0.1

Type RM Length L Ch R = 1 ,26800   ,475,475,475
BEGIN DESCRIPTION:
DRY VALLEY CREEK 45.0
END DESCRIPTION:
XS GIS Cut Line= 3
      2213311.27      7259451.72      2211826.92      7258878.81
      2209326.89      7258436.09
#Sta/Elev= 30
  3411.2  1019.1    3553  1014.7  3593.5 1004.07    3678 1000.26  3841.7 1000.39
  3863.8 1006.58  3901.7  993.36  3961.6     992  4010.8  980.81  4065.4  990.87
  4070.7  980.04  4095.3  991.41  4100.7   981.9  4119.9  987.53  4155.3  977.76
  4264.4  984.82  4335.5  974.93  4442.7  982.94  4807.1  961.83  4845.4  968.42
  4860.7  961.02  4969.1  954.53  4971.1  954.03  4988.1  954.53  5040.8  961.24
  5629.8  963.45  5832.9  977.15    6036  973.65  6915.6 1020.39  7541.2 1037.43
#Mann= 3 ,-1 , 0
  3411.2     .05       0  4969.1     .04       0  4988.1     .05       0
Bank Sta=4969.1,4988.1
XS Rating Curve= 0 ,0
Exp/Cntr=0.3,0.1

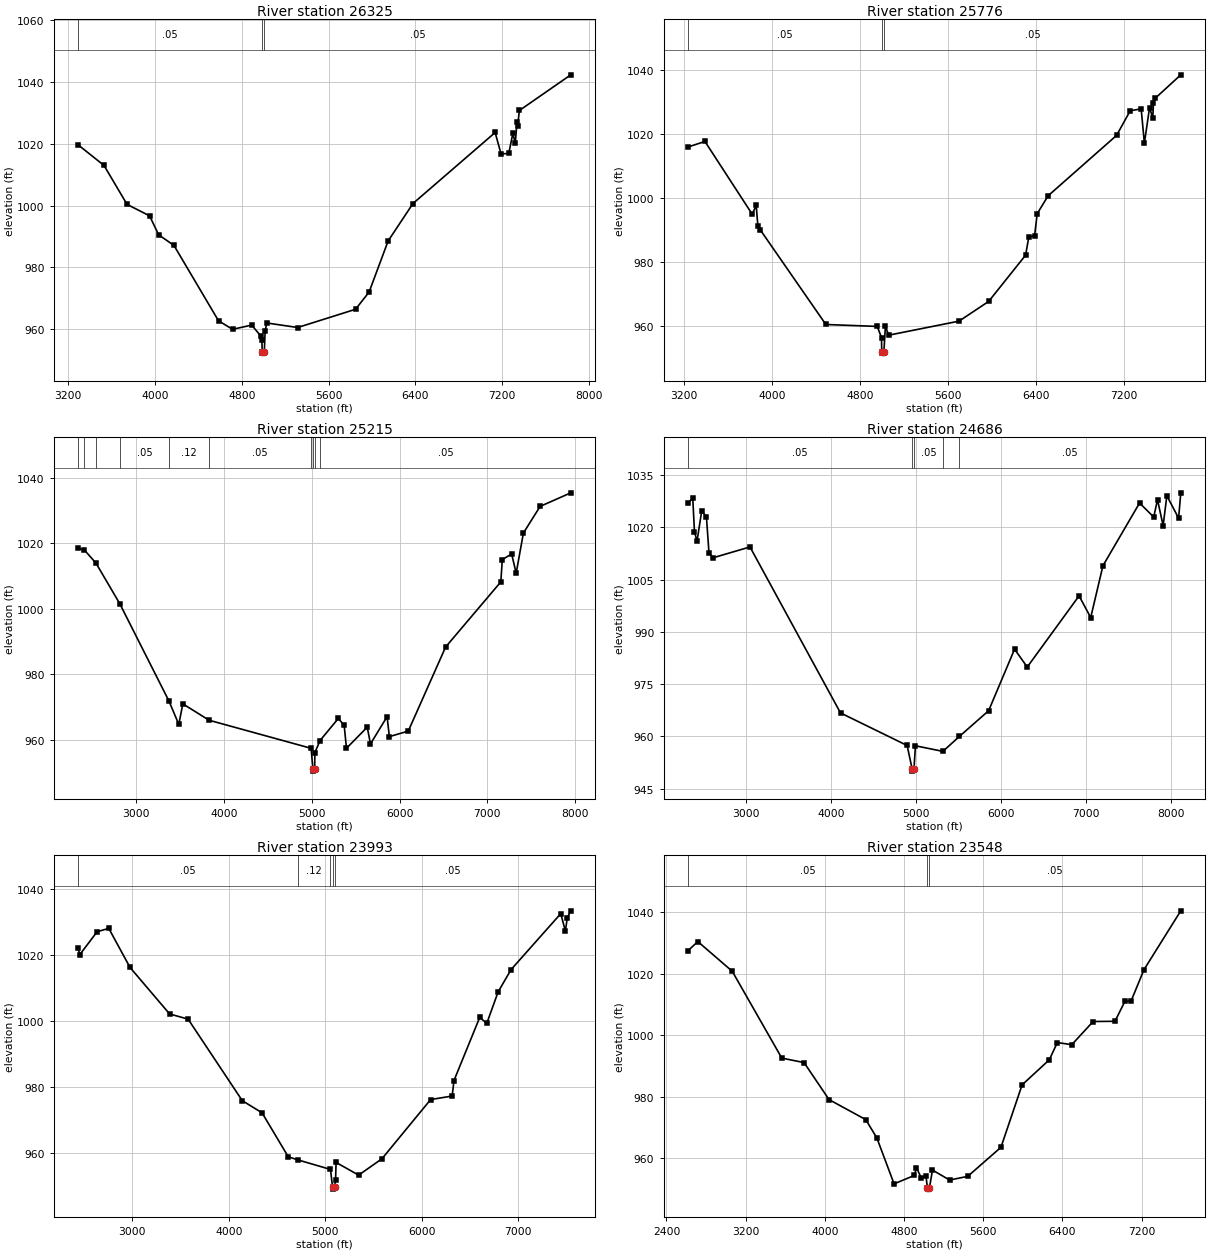
Type RM Length L Ch R = 1 ,26325   ,549,549,549
BEGIN DESCRIPTION:
DRY VALLEY CREEK 44.0
END DESCRIPTION:
XS GIS Cut Line= 3
      2213415.45      7259165.26        2211829.        7258510.
      2209344.28      7257160.06
#Sta/Elev= 30
  3290.6 1019.64  3528.6    1013  3741.6 1000.38  3949.2  996.68  4033.3  990.53
    4174  987.11  4585.1  962.72  4714.9  959.95  4891.3  961.33  4974.6  957.81
  4985.4  956.43  4987.8  952.75  4989.8  952.25  5007.7  952.75  5015.1  959.27
  5029.8  962.01  5315.4  960.54  5849.2  966.44  5974.4  972.03  6149.7  988.54
  6378.7 1000.66    7137 1023.65  7191.2 1016.71  7262.5 1016.87  7300.5 1023.38
  7322.4 1020.12  7338.5 1027.07  7344.2 1025.73  7360.4 1030.77  7834.8 1042.31
#Mann= 3 ,-1 , 0
  3290.6     .05       0  4987.8    .033       0  5007.7     .05       0
Bank Sta=4987.8,5007.7
XS Rating Curve= 0 ,0
Exp/Cntr=0.3,0.1

Type RM Length L Ch R = 1 ,25776   ,561,561,561
BEGIN DESCRIPTION:
DRY VALLEY CREEK 43.0
END DESCRIPTION:
XS GIS Cut Line= 3
      2213528.28       7259052.4        2212079.        7258060.
      2209570.01      7256995.14
#Sta/Elev= 30
    3239    1016  3391.7 1017.72  3822.2   994.9  3858.1  997.73    3873  991.36
    3894  990.09  4491.8  960.37  4959.1  959.77  4998.2  956.28  5000.1   951.9
  5002.1   951.4    5020   951.9  5033.7  959.84  5062.8  957.02  5703.2  961.42
  5973.2   967.6  6309.1  982.09  6338.2  987.75    6391  988.19  6414.6  995.09
  6514.7 1000.72  7136.9 1019.62  7260.6 1027.32  7360.7 1027.95  7389.8 1017.18
  7437.1 1028.36  7466.2 1025.04  7472.3 1029.68  7489.9  1031.3  7721.1  1038.6
#Mann= 3 ,-1 , 0
    3239     .05       0  5000.1     .04       0    5020     .05       0
Bank Sta=5000.1,5020
XS Rating Curve= 0 ,0
Exp/Cntr=0.3,0.1

Type RM Length L Ch R = 1 ,25215   ,529,529,529
BEGIN DESCRIPTION:
DRY VALLEY CREEK 42.0
END DESCRIPTION:
XS GIS Cut Line= 3
      2214847.75      7258271.17        2212279.        7257560.
      2209413.84      7256873.63
#Sta/Elev= 30
  2339.2 1018.55    2411 1017.95  2541.7 1013.99  2814.1 1001.52  3374.9  971.72
  3485.6  964.65  3531.2  970.95  3830.5  965.94  4993.1  957.35    5013  950.88
    5015  950.38    5033  950.88  5035.4  956.03  5094.5  959.74  5302.8  966.49
  5369.5  964.35  5395.3  957.36    5632  963.82  5668.9   958.7  5858.1  967.04
  5884.1  960.93  6099.4  962.62  6524.9  988.33  7153.7 1008.24  7170.7 1015.07
  7277.1 1016.77  7328.5 1010.89  7410.8 1023.17  7601.3 1031.32  7950.8 1035.47
#Mann= 10 ,-1 , 0
  2339.2     .12       0    2411     .05       0  2541.7     .12       0
  2814.1     .05       0  3374.9     .12       0  3830.5     .05       0
  4993.1     .12       0    5013     .07       0    5033     .12       0
  5094.5     .05       0
Bank Sta=5013,5033
XS Rating Curve= 0 ,0
Exp/Cntr=0.3,0.1

Type RM Length L Ch R = 1 ,24686   ,693,693,693
BEGIN DESCRIPTION:
DRY VALLEY CREEK 41.0
END DESCRIPTION:
XS GIS Cut Line= 3
      2215142.94      7256838.87        2212479.        7257110.
      2209639.89      7255814.78
#Sta/Elev= 30
  2322.4 1026.97  2376.6  1028.4  2396.7 1018.68  2426.9 1016.04  2481.9 1024.69
  2537.4 1023.02  2567.6 1012.63  2617.9 1011.27  3050.1 1014.36  4115.6  966.71
  4899.6  957.36  4959.8   950.5  4961.8     950  4980.1   950.5  4997.6  957.28
  5320.8  955.67  5515.8  959.98  5859.2  967.35  6164.2  985.01  6313.4  979.88
  6923.6 1000.32  7060.5  994.09  7204.3 1008.96  7635.4 1026.98  7802.2 1022.95
  7846.9 1027.92  7912.8 1020.46  7956.9 1029.07  8095.1 1022.61  8120.7  1029.9
#Mann= 5 ,-1 , 0
  2322.4     .05       0  4959.8    .033       0  4980.1     .05       0
  5320.8     .12       0  5515.8     .05       0
Bank Sta=4959.8,4980.1
XS Rating Curve= 0 ,0
Exp/Cntr=0.3,0.1

Type RM Length L Ch R = 1 ,23993   ,445,445,445
BEGIN DESCRIPTION:
DRY VALLEY CREEK 40.0
END DESCRIPTION:
XS GIS Cut Line= 3
      2214785.25      7256694.78      2212236.64      7256507.28
      2209785.21      7255805.88
#Sta/Elev= 30
  2440.1 1022.06  2456.4 1020.13  2636.9 1027.09  2757.2 1028.09  2977.5 1016.26
  3387.5 1002.18  3579.4  1000.6  4140.9  975.91  4345.8  972.23  4617.5  958.91
  4719.8  957.95    5055  955.09  5076.6  949.62  5078.7  949.12  5096.9  949.62
  5107.6  951.88  5112.9   957.2  5346.8  953.36  5588.4  958.32  6092.5  976.24
    6316  977.32  6334.9  982.02  6601.8 1001.15  6674.5  999.32  6792.6 1008.88
  6926.6 1015.62  7441.1 1032.55  7489.5 1027.28  7508.6 1031.29  7545.4 1033.41
#Mann= 5 ,-1 , 0
  2440.1     .05       0  4719.8     .12       0    5055     .05       0
  5076.6     .07       0  5096.9     .05       0
Bank Sta=5076.6,5096.9
XS Rating Curve= 0 ,0
Exp/Cntr=0.3,0.1

Type RM Length L Ch R = 1 ,23548   ,564,564,564
BEGIN DESCRIPTION:
DRY VALLEY CREEK 39.0
END DESCRIPTION:
XS GIS Cut Line= 3
      2214604.72      7256597.56        2212279.        7256110.
      2209723.42       7255632.4
#Sta/Elev= 30
  2619.4 1027.58  2717.2  1030.5  3064.6 1020.84  3565.2  992.59    3790  991.13
  4042.8  979.08  4413.3  972.58  4525.7   966.6  4699.4  951.67  4903.7  954.41
  4925.9  956.92  4975.8  953.49    5022  954.13    5036  950.46  5038.1  949.96
    5057  950.46  5087.2  956.16  5260.2  952.92  5443.3  954.11    5779  963.57
  5992.6  983.88  6267.3  992.03  6348.7  997.65  6494.4  996.95  6710.1 1004.49
  6930.9 1004.56  7030.3 1011.01  7093.9 1011.19  7223.6 1021.35  7595.5  1040.5
#Mann= 3 ,-1 , 0
  2619.4     .05       0    5036    .033       0    5057     .05       0
Bank Sta=5036,5057
XS Rating Curve= 0 ,0
Exp/Cntr=0.3,0.1