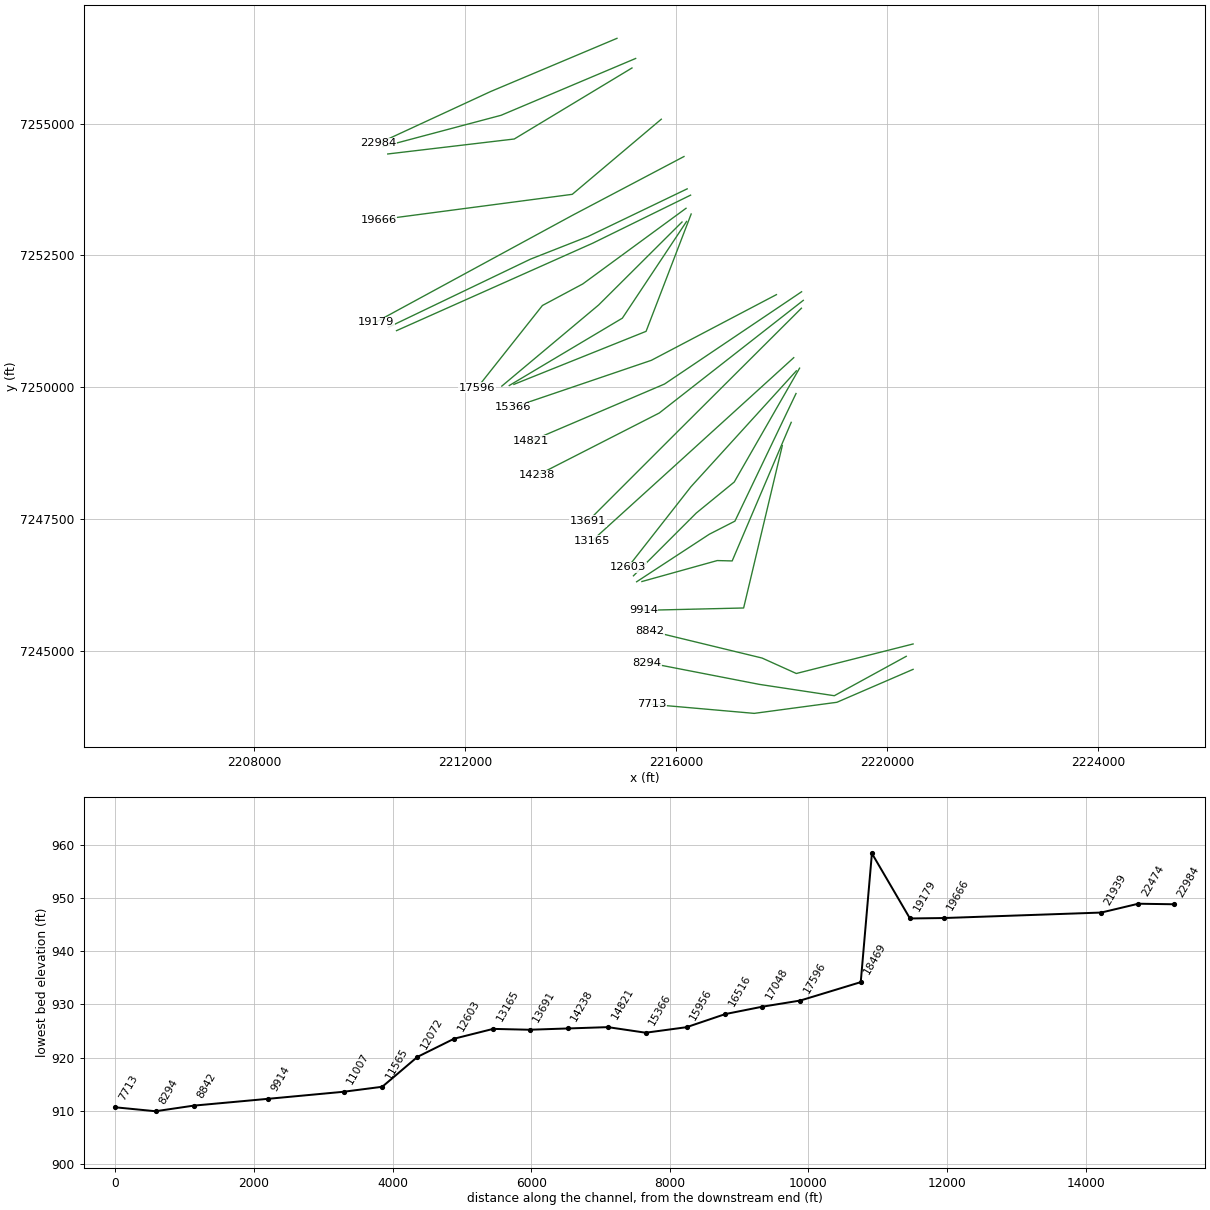
HEC-RAS study DRY VALLEY CREEK.prj: DRY VALLEY CREEK Base Level Engineering

--- DRY VALLEY CREEK.g01 (geometry) --- (continued)

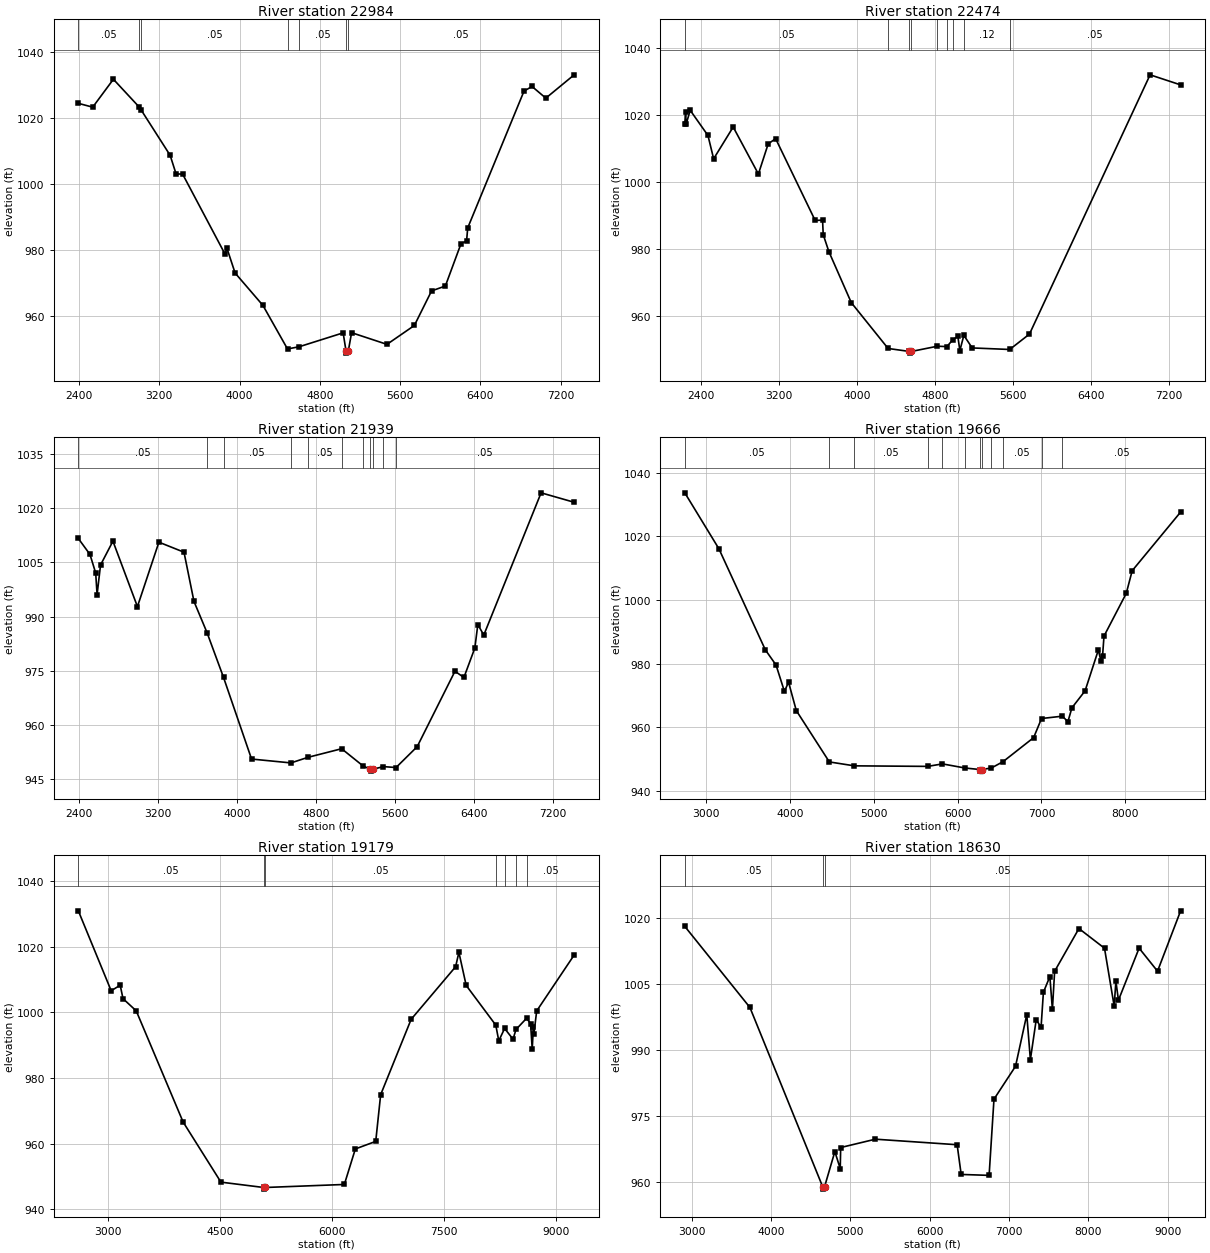
Type RM Length L Ch R = 1 ,22984   ,510,510,510
BEGIN DESCRIPTION:
DRY VALLEY CREEK 38.0
END DESCRIPTION:
XS GIS Cut Line= 3
      2214876.96      7256620.26        2212479.        7255610.
      2210356.05      7254627.17
#Sta/Elev= 30
  2393.4 1024.35  2536.7 1023.19  2742.8 1031.63  2997.3 1023.32  3020.6 1022.29
  3308.3 1008.64  3367.8 1002.98  3432.3 1002.98  3856.1  978.72  3873.7  980.61
  3955.8  973.05  4233.1  963.26    4478  950.09  4594.3  950.76  5032.6  954.96
    5062  949.33  5064.1  948.83  5083.2  949.33  5116.7  955.01  5469.3  951.48
  5742.3  957.19  5913.8  967.64  6051.3  969.12  6207.6  981.95  6262.7  982.72
  6274.1  986.69  6835.2 1028.05    6915 1029.45  7052.5 1025.92  7334.9 1032.97
#Mann= 7 ,-1 , 0
  2393.4     .05       0  2997.3     .12       0  3020.6     .05       0
    4478     .12       0  4594.3     .05       0    5062    .033       0
  5083.2     .05       0
Bank Sta=5062,5083.2
XS Rating Curve= 0 ,0
Exp/Cntr=0.3,0.1

Type RM Length L Ch R = 1 ,22474   ,535,535,535
BEGIN DESCRIPTION:
DRY VALLEY CREEK 37.0
END DESCRIPTION:
XS GIS Cut Line= 3
      2215231.04      7256238.28        2212679.        7255160.
      2210440.04      7254564.85
#Sta/Elev= 30
  2233.8 1017.42  2241.8 1020.93  2247.3 1017.23  2289.2  1021.4  2471.4 1013.88
  2529.7 1006.92  2730.2 1016.41  2988.9 1002.38  3089.2 1011.36  3165.7 1012.94
  3571.3  988.52  3647.3  988.62    3654  984.29  3712.4   979.2  3941.9     964
  4319.8  950.32  4537.7  949.43  4539.8  948.93  4558.9  949.43  4825.5  950.99
  4923.1  950.88  4981.3  952.85  5035.3  953.93    5056  949.69  5096.7  954.24
  5182.4  950.48  5567.4  950.02    5770  954.61  7007.7 1031.98    7321 1028.98
#Mann= 9 ,-1 , 0
  2233.8     .05       0  4319.8     .12       0  4537.7    .033       0
  4558.9     .12       0  4825.5     .05       0  4923.1     .12       0
  4981.3     .05       0  5096.7     .12       0  5567.4     .05       0
Bank Sta=4537.7,4558.9
XS Rating Curve= 0 ,0
Exp/Cntr=0.3,0.1

Type RM Length L Ch R = 1 ,21939   ,2273,2273,2273
BEGIN DESCRIPTION:
DRY VALLEY CREEK 36.0
END DESCRIPTION:
XS GIS Cut Line= 3
      2215161.63      7256057.74        2212929.        7254710.
      2210529.66      7254425.79
#Sta/Elev= 30
  2392.1 1011.57  2509.8 1007.17    2568 1002.02  2582.1  996.05  2617.1 1004.24
  2742.7 1010.83  2990.9  992.74  3208.5 1010.55  3462.8 1007.78  3563.7  994.19
  3695.7  985.58  3863.1  973.19  4147.3  950.61  4546.4  949.54  4718.2  951.08
    5060  953.46  5276.3  948.72  5351.9  947.77    5354  947.27  5373.1  947.77
  5483.8  948.52  5611.2  948.26  5825.7  954.04  6208.4  974.88    6299  973.15
  6409.8   981.3    6440  987.79  6500.4  984.87  7081.1 1024.19  7416.1 1021.58
#Mann= 11 ,-1 , 0
  2392.1     .05       0  3695.7     .12       0  3863.1     .05       0
  4546.4     .12       0  4718.2     .05       0    5060     .12       0
  5276.3      .1       0  5351.9    .033       0  5373.1      .1       0
  5483.8     .12       0  5611.2     .05       0
Bank Sta=5351.9,5373.1
XS Rating Curve= 0 ,0
Exp/Cntr=0.3,0.1

Type RM Length L Ch R = 1 ,19666   ,487,487,487
BEGIN DESCRIPTION:
DRY VALLEY CREEK 35.0
END DESCRIPTION:
XS GIS Cut Line= 3
      2215717.19      7255085.52        2214029.        7253660.
      2210356.13       7253175.8
#Sta/Elev= 30
  2745.5 1033.67  3152.4 1016.09  3706.2  984.34  3833.7  979.58  3933.7  971.29
  3983.1  974.18  4075.4  965.27  4469.6  949.13  4767.9   947.9  5642.1  947.73
  5819.3  948.51  6085.3  947.23  6265.3  946.74  6267.5  946.24  6287.4  946.74
  6402.7  947.23  6541.4  949.21  6906.4  956.76  7000.7  962.77    7249   963.5
  7315.3  961.77  7362.9  966.13  7520.1  971.46  7678.4   984.3  7708.7  980.89
  7728.8  982.55  7745.8  988.66  8011.3 1002.09  8081.9  1009.2  8659.7 1027.63
#Mann= 12 ,-1 , 0
  2745.5     .05       0  4469.6     .12       0  4767.9     .05       0
  5642.1     .12       0  5819.3     .05       0  6085.3      .1       0
  6265.3    .033       0  6287.4      .1       0  6402.7     .12       0
  6541.4     .05       0  7000.7     .12       0    7249     .05       0
Bank Sta=6265.3,6287.4
XS Rating Curve= 0 ,0
Exp/Cntr=0.3,0.1

Type RM Length L Ch R = 1 ,19179   ,549,549,549
BEGIN DESCRIPTION:
DRY VALLEY CREEK 34.0
END DESCRIPTION:
XS GIS Cut Line= 3
      2216147.78       7254377.2        2214029.        7253260.
      2210303.82      7251235.37
#Sta/Elev= 30
  2604.7 1030.93  3044.2 1006.58  3164.9 1008.27  3202.5 1004.18  3379.5 1000.46
  4006.9   966.6  4512.9  948.29  5084.4  946.66  5086.6  946.16  5106.6  946.66
  6164.4  947.58  6311.7   958.4  6584.4   960.7  6650.3  974.92  7058.5  997.89
  7653.3  1013.9  7697.4 1018.29  7794.9 1008.21  8191.1  996.11    8231  991.34
    8309  995.09    8422  991.84  8461.6  994.79  8603.7  998.22  8656.7  996.54
  8678.5  988.86  8694.7  995.66  8700.4  993.36  8738.4 1000.44  9239.8 1017.47
#Mann= 7 ,-1 , 0
  2604.7     .05       0  5084.4    .033       0  5106.6     .05       0
  8191.1     .12       0    8309     .05       0  8461.6     .12       0
  8603.7     .05       0
Bank Sta=5084.4,5106.6
XS Rating Curve= 0 ,0
Exp/Cntr=0.3,0.1

Type RM Length L Ch R = 1 ,18630   ,161,161,161
BEGIN DESCRIPTION:
DRY VALLEY CREEK 33.0
END DESCRIPTION:
XS GIS Cut Line= 4
      2216208.13       7253763.9        2214329.        7252860.
      2213235.01      7252429.25      2210544.03      7251138.02
#Sta/Elev= 30
  2914.8 1018.16    3735  999.72  4652.5  958.89  4654.7  958.39  4674.7  958.89
  4804.9  966.93  4872.8  963.05  4878.3  967.85  5315.5  969.75  6345.3  968.49
  6396.2  961.73  6748.1  961.52  6809.4  978.85  7080.9  986.34  7222.6  998.08
  7267.9  987.86  7341.4  996.92  7402.5  995.22    7432 1003.17  7513.4 1006.75
  7545.3  999.26  7573.5 1007.95  7879.5 1017.67  8201.6 1013.19  8323.1 1000.08
  8345.3 1005.66  8377.3 1001.37  8637.5 1013.21  8869.6 1007.97  9160.5  1021.7
#Mann= 3 ,-1 , 0
  2914.8     .05       0  4652.5    .033       0  4674.7     .05       0
Bank Sta=4652.5,4674.7
XS Rating Curve= 0 ,0
Exp/Cntr=0.3,0.1

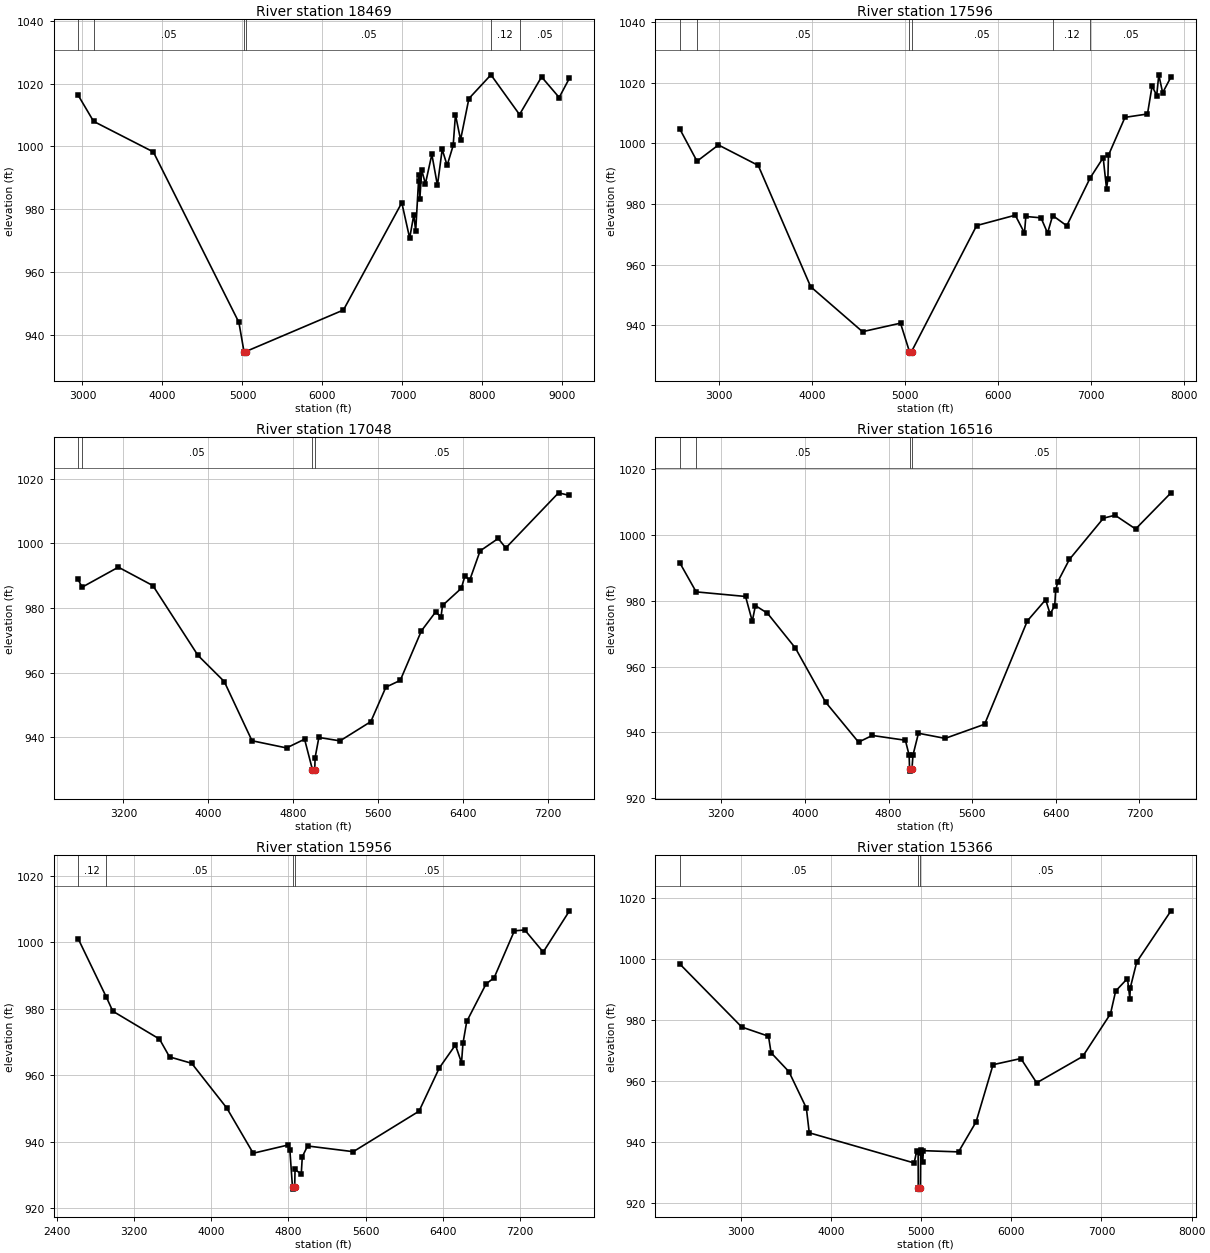
Type RM Length L Ch R = 1 ,18469   ,873,873,873
BEGIN DESCRIPTION:
DRY VALLEY CREEK 32.0
END DESCRIPTION:
XS GIS Cut Line= 3
      2216273.23      7253644.54      2214417.73      7252733.07
      2210695.99      7251072.94
#Sta/Elev= 30
  2945.2 1016.33  3138.5 1007.99  3885.8  998.25  4955.4  943.97  5018.8  934.69
    5021  934.19  5041.1  934.69  6262.3  947.92  6991.8  982.08  7090.2   970.8
  7142.1  978.26  7165.3  973.05    7201  988.96  7211.8  990.95  7217.2  983.16
  7240.5  992.49  7286.9  988.11  7367.5  997.48  7437.2   987.6  7496.7  999.04
  7558.8  993.96  7633.9  1000.3  7662.6 1010.08  7726.6 1002.12  7830.7 1015.24
  8106.3  1022.8  8463.5 1010.15  8739.2 1022.14  8959.2 1015.58  9087.7 1021.74
#Mann= 6 ,-1 , 0
  2945.2     .12       0  3138.5     .05       0  5018.8    .033       0
  5041.1     .05       0  8106.3     .12       0  8463.5     .05       0
Bank Sta=5018.8,5041.1
XS Rating Curve= 0 ,0
Exp/Cntr=0.3,0.1

Type RM Length L Ch R = 1 ,17596   ,548,548,548
BEGIN DESCRIPTION:
DRY VALLEY CREEK 31.0
END DESCRIPTION:
XS GIS Cut Line= 4
      2216186.39      7253394.96        2214229.        7251960.
      2213462.87      7251550.35      2212225.88      7249987.83
#Sta/Elev= 30
  2572.5 1004.87  2759.5  994.13    2990   999.5  3418.4  992.74  3982.8  952.67
  4540.8  937.81  4949.9  940.63    5046  931.23  5048.3  930.73  5068.4  931.23
  5769.3  972.87    6185   976.3  6284.3  970.41  6298.7  975.87  6462.2  975.43
  6532.7   970.4  6587.9  976.19  6739.4   972.8  6990.9  988.59  7131.4  995.29
  7167.4  985.05  7181.8  988.14  7188.2  996.11  7366.1 1008.62  7608.1 1009.73
  7657.8 1018.98  7707.4 1015.84  7729.9 1022.67  7771.5 1016.75  7861.2 1021.95
#Mann= 6 ,-1 , 0
  2572.5     .12       0  2759.5     .05       0    5046    .033       0
  5068.4     .05       0  6587.9     .12       0  6990.9     .05       0
Bank Sta=5046,5068.4
XS Rating Curve= 0 ,0
Exp/Cntr=0.3,0.1

Type RM Length L Ch R = 1 ,17048   ,532,532,532
BEGIN DESCRIPTION:
DRY VALLEY CREEK 30.0
END DESCRIPTION:
XS GIS Cut Line= 3
      2216110.48      7253134.58        2214529.        7251560.
      2212693.22      7250021.02
#Sta/Elev= 30
  2773.1  988.81  2810.5  986.42  3152.2  992.61  3477.4  986.91  3901.7  965.35
  4149.2  957.27  4410.8  938.96  4736.1  936.74  4905.8  939.44  4979.5  930.07
  4981.7  929.57  5001.9  930.07  5004.8  933.71  5040.5  939.98  5239.6  938.92
  5529.7  944.87  5671.6  955.53  5806.9  957.62  6005.9  972.92    6140  978.76
  6190.6  977.23  6204.9  980.77  6381.9  986.08    6417  990.02    6460  988.51
  6558.9  997.64  6729.3 1001.48  6800.8  998.55  7297.8 1015.59  7400.3 1014.78
#Mann= 4 ,-1 , 0
  2773.1     .12       0  2810.5     .05       0  4979.5    .033       0
  5001.9     .05       0
Bank Sta=4979.5,5001.9
XS Rating Curve= 0 ,0
Exp/Cntr=0.3,0.1

Type RM Length L Ch R = 1 ,16516   ,560,560,560
BEGIN DESCRIPTION:
DRY VALLEY CREEK 29.0
END DESCRIPTION:
XS GIS Cut Line= 3
      2216197.23      7253145.37        2214979.        7251310.
      2212833.81      7250031.41
#Sta/Elev= 30
  2801.4  991.64  2959.3  982.72    3432  981.32  3496.2   973.8  3526.3  978.53
  3640.5  976.25  3908.2  965.65  4196.9  949.21  4512.6  937.01  4644.2  939.04
  4960.7  937.58  4996.8  933.04  5000.9  928.69  5003.1  928.19  5023.3  928.69
  5033.5  933.07  5085.8  939.71  5341.1  938.15  5718.7  942.45  6127.5  973.89
  6302.7  980.34  6345.5  975.99  6389.6  978.55  6398.1  983.16  6419.5  985.85
  6529.3  992.57  6855.6 1005.14  6966.5 1006.04  7163.2 1001.85  7501.6 1012.85
#Mann= 4 ,-1 , 0
  2801.4     .12       0  2959.3     .05       0  5000.9     .04       0
  5023.3     .05       0
Bank Sta=5000.9,5023.3
XS Rating Curve= 0 ,0
Exp/Cntr=0.3,0.1

Type RM Length L Ch R = 1 ,15956   ,590,590,590
BEGIN DESCRIPTION:
DRY VALLEY CREEK 28.0
END DESCRIPTION:
XS GIS Cut Line= 3
      2216284.04      7253286.43        2215429.        7251060.
      2212922.21       7250053.7
#Sta/Elev= 30
  2622.3 1001.12  2915.5  983.45  2981.2  979.28  3464.7  970.88  3568.6  965.52
    3798  963.59  4161.5  950.12  4434.8  936.52  4792.9  938.98  4814.5  937.42
  4841.6  926.22  4843.9  925.72  4864.1  926.22    4868  931.63  4932.2  930.24
    4943  935.47  4997.6  938.71  5470.6  936.99  6151.5  949.18  6361.2  962.19
    6528   969.1  6591.3  963.78  6605.9  969.55  6645.2  976.18  6845.3  987.48
  6928.6  989.32  7138.4 1003.46  7245.9 1003.72  7436.9  997.07  7708.5 1009.48
#Mann= 4 ,-1 , 0
  2622.3     .12       0  2915.5     .05       0  4841.6    .033       0
  4864.1     .05       0
Bank Sta=4841.6,4864.1
XS Rating Curve= 0 ,0
Exp/Cntr=0.3,0.1

Type RM Length L Ch R = 1 ,15366   ,545,545,545
BEGIN DESCRIPTION:
DRY VALLEY CREEK 27.0
END DESCRIPTION:
XS GIS Cut Line= 3
      2217900.85      7251756.53        2215529.        7250510.
      2212909.47      7249618.92
#Sta/Elev= 30
  2324.4  998.42  3012.7  977.73  3309.3  974.73  3337.8  969.33  3536.2  963.11
  3728.9  951.22  3761.2  943.12  4923.9  933.24  4951.6  937.12    4968  936.68
  4969.4  925.18  4971.7  924.68  4993.2  925.18  4995.7  936.39    5001  937.44
  5019.5   933.6    5025  937.27  5415.8  936.87  5610.3  946.69  5798.5  965.41
  6106.9  967.43  6281.9  959.47  6791.8   968.1  7100.2  982.06  7157.7  989.52
  7288.4  993.62  7314.5  987.07  7319.8  990.58    7391  999.02  7770.8 1015.77
#Mann= 3 ,-1 , 0
  2324.4     .05       0  4969.4    .033       0  4993.2     .05       0
Bank Sta=4969.4,4993.2
XS Rating Curve= 0 ,0
Exp/Cntr=0.3,0.1

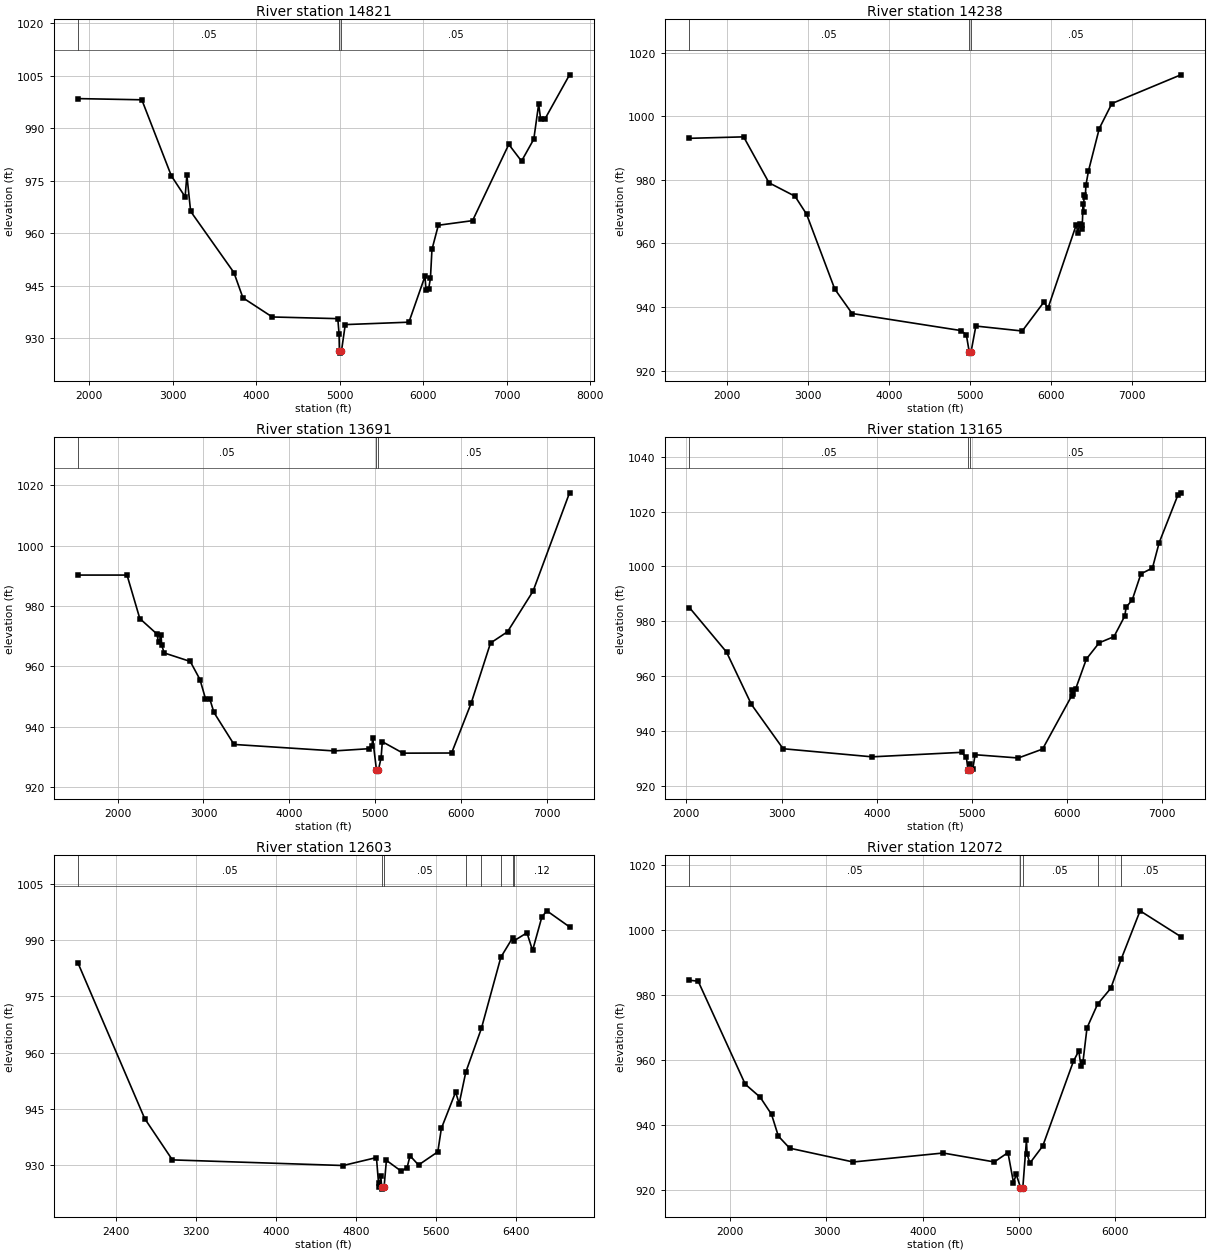
Type RM Length L Ch R = 1 ,14821   ,583,583,583
BEGIN DESCRIPTION:
DRY VALLEY CREEK 26.0
END DESCRIPTION:
XS GIS Cut Line= 3
      2218378.27      7251810.78        2215779.        7250060.
      2213245.84      7248978.72
#Sta/Elev= 30
  1866.1  998.52  2629.5  998.18  2983.4  976.42  3148.3  970.44  3169.3   976.6
  3214.3  966.28    3733  948.76    3841  941.54  4192.2  936.07  4977.6  935.59
  4992.5  931.34  4997.2  926.23  4999.6  925.73    5021  926.23  5067.2  933.89
  5829.8  934.58  6022.1  947.71    6035  943.71  6065.6  944.01  6087.7  947.15
  6105.8  955.37  6182.1   962.3  6592.5  963.62  7026.4  985.42    7179  980.64
  7326.1  986.92  7384.2  996.91  7407.8  992.74  7460.4  992.72  7754.3 1005.32
#Mann= 3 ,-1 , 0
  1866.1     .05       0  4997.2    .033       0    5021     .05       0
Bank Sta=4997.2,5021
XS Rating Curve= 0 ,0
Exp/Cntr=0.3,0.1

Type RM Length L Ch R = 1 ,14238   ,547,547,547
BEGIN DESCRIPTION:
DRY VALLEY CREEK 25.0
END DESCRIPTION:
XS GIS Cut Line= 3
      2218410.81      7251648.02        2215679.        7249510.
      2213365.26      7248327.71
#Sta/Elev= 30
  1530.9  993.07  2200.4  993.53  2513.3  979.08  2834.3  974.85  2977.2   969.2
  3325.3  945.64  3539.6  937.94  4878.7   932.6  4949.3  931.33  4984.8  925.98
  4987.2  925.48  5008.7  925.98  5067.3     934    5640  932.44  5907.9  941.56
    5958  939.63  6307.8  965.91  6324.4  963.41  6352.3  966.17  6374.5   964.5
  6381.2  965.65  6391.1  972.39  6396.7  969.84  6403.6  975.37  6418.9  974.74
  6426.1  978.33  6457.8  982.81  6591.1  996.16  6746.6 1004.02  7598.2 1013.05
#Mann= 3 ,-1 , 0
  1530.9     .05       0  4984.8    .035       0  5008.7     .05       0
Bank Sta=4984.8,5008.7
XS Rating Curve= 0 ,0
Exp/Cntr=0.3,0.1

Type RM Length L Ch R = 1 ,13691   ,526,526,526
BEGIN DESCRIPTION:
DRY VALLEY CREEK 24.0
END DESCRIPTION:
XS GIS Cut Line= 3
      2218375.18       7251498.7        2215929.        7249060.
      2214328.99      7247459.99
#Sta/Elev= 30
  1541.6  990.27  2110.7  990.27  2259.2  975.85  2457.2  970.75  2478.4  967.91
  2506.7  970.27  2513.8  967.09  2542.1  964.45  2846.1  961.62  2959.3  955.62
  3022.9  949.32  3072.4  949.28  3121.9  944.69  3355.3  934.09    4522  931.94
    4925  932.68  4960.4  933.51  4967.5   936.2  5012.1  925.74  5014.5  925.24
    5036  925.74  5066.4  929.69  5080.6     935    5321   931.2  5886.7  931.25
    6113  947.69  6339.2  967.73  6537.2  971.47  6834.2  984.94  7258.5 1017.55
#Mann= 3 ,-1 , 0
  1541.6     .05       0  5012.1    .035       0    5036     .05       0
Bank Sta=5012.1,5036
XS Rating Curve= 0 ,0
Exp/Cntr=0.3,0.1

Type RM Length L Ch R = 1 ,13165   ,562,562,562
BEGIN DESCRIPTION:
DRY VALLEY CREEK 23.0
END DESCRIPTION:
XS GIS Cut Line= 3
      2218228.99      7250559.99        2216029.        7248560.
       2214408.2        7247089.
#Sta/Elev= 30
  2031.7     985  2421.2  968.81  2682.8  949.71  3015.9  933.56  3950.4  930.61
  4891.7  932.25    4941  930.38  4957.5   925.9  4959.9   925.4  4981.4   925.9
  4983.6  927.89  5008.3  926.34  5032.9  931.38  5486.4  930.19  5741.2  933.43
  6045.3  952.72  6052.7  954.94  6059.5  953.39  6087.8  955.27  6201.4  966.25
  6335.9  972.17  6491.3  974.41  6604.8  981.94    6619  985.18  6682.5  987.75
  6774.4  997.31  6895.4  999.42  6965.7 1008.64  7164.4 1026.17  7193.7 1026.83
#Mann= 3 ,-1 , 0
  2031.7     .05       0  4957.5    .033       0  4981.4     .05       0
Bank Sta=4957.5,4981.4
XS Rating Curve= 0 ,0
Exp/Cntr=0.3,0.1

Type RM Length L Ch R = 1 ,12603   ,531,531,531
BEGIN DESCRIPTION:
DRY VALLEY CREEK 22.0
END DESCRIPTION:
XS GIS Cut Line= 3
      2218279.02      7250310.02        2216279.        7248110.
      2215085.26      7246585.51
#Sta/Elev= 30
  2021.9  983.81  2687.2  942.38  2963.6  931.36  4669.8  929.86  5002.4  931.98
  5023.2  925.16  5031.3  924.14  5045.8  927.06  5054.6  924.06    5057  923.56
  5078.5  924.06  5101.8  931.24    5251  928.33  5308.9  929.33  5337.8  932.46
  5422.8     930  5615.4  933.51  5650.7  939.74  5793.5  949.46  5828.8  946.35
    5895  954.78  6050.7  966.42  6245.4  985.44    6362  990.58  6372.1  989.74
    6506  991.95  6562.1  987.23  6655.2   996.2  6704.9  997.81  6931.4  993.52
#Mann= 8 ,-1 , 0
  2021.9     .05       0  5054.6    .035       0  5078.5     .05       0
    5895     .12       0  6050.7     .05       0  6245.4     .12       0
    6362     .05       0  6372.1     .12       0
Bank Sta=5054.6,5078.5
XS Rating Curve= 0 ,0
Exp/Cntr=0.3,0.1

Type RM Length L Ch R = 1 ,12072   ,507,507,507
BEGIN DESCRIPTION:
DRY VALLEY CREEK 21.0
END DESCRIPTION:
XS GIS Cut Line= 4
      2218340.45      7250361.51      2217100.94      7248200.29
        2216379.        7247610.      2215189.42      7246420.57
#Sta/Elev= 30
  1575.8   984.4  1666.6  984.11  2155.6  952.42    2311  948.41  2428.9  943.14
  2499.8  936.44  2617.3  932.73  3277.5  928.48  4211.6  931.24  4743.5   928.5
  4885.6  931.36  4943.1  922.15  4971.8  924.67  5015.9  920.63  5018.4  920.13
  5040.2  920.63  5077.6  935.17  5084.6  930.91  5112.9  928.11  5247.3  933.41
  5565.5  959.45    5622  962.69  5643.3  957.95  5664.5  959.16  5706.9  969.74
  5816.9  977.05  5954.4  981.94  6064.7  991.09  6258.4 1005.76    6682  997.81
#Mann= 5 ,-1 , 0
  1575.8     .05       0  5015.9    .033       0  5040.2     .05       0
  5816.9     .12       0  6064.7     .05       0
Bank Sta=5015.9,5040.2
XS Rating Curve= 0 ,0
Exp/Cntr=0.3,0.1

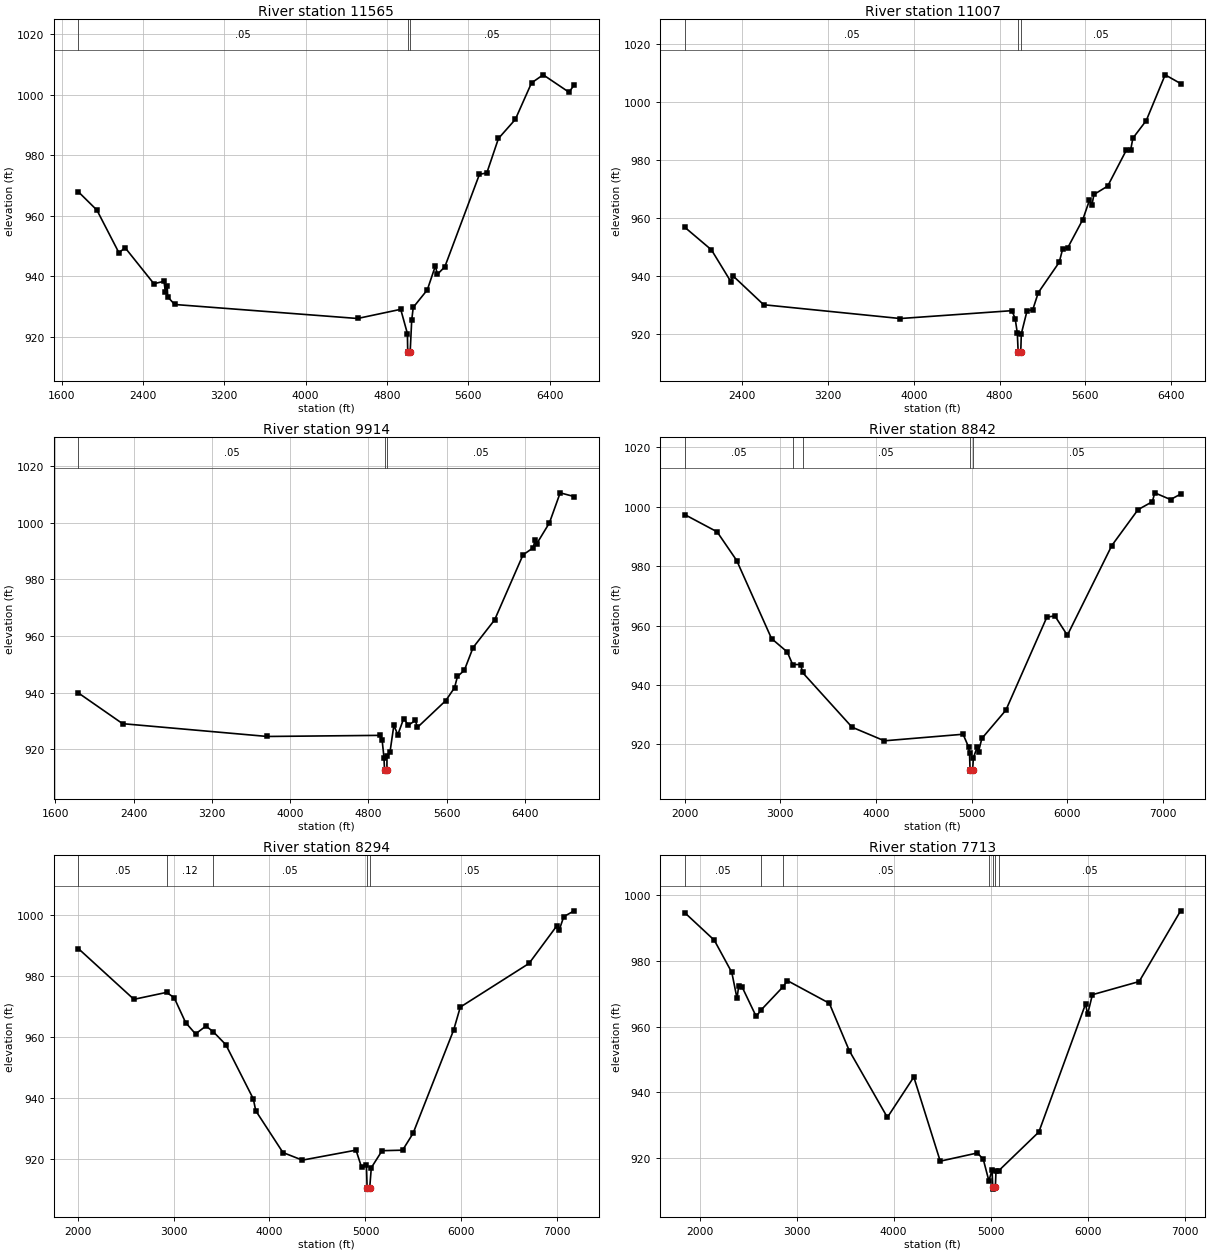
Type RM Length L Ch R = 1 ,11565   ,558,558,558
BEGIN DESCRIPTION:
DRY VALLEY CREEK 20.0
END DESCRIPTION:
XS GIS Cut Line= 4
      2218272.82      7249879.98      2217113.96       7247458.1
        2216629.        7247210.      2215250.17      7246307.72
#Sta/Elev= 30
  1764.6  967.86  1947.3   961.8  2163.7  947.71  2224.9  949.36  2508.1  937.45
  2607.1  938.27  2621.4  934.74  2638.5  936.71  2644.1  933.12  2712.1   930.6
  4511.2  925.97  4935.9     929  5001.7  920.98  5004.7  915.02  5007.1  914.52
    5029  915.02  5043.9  925.36    5059  929.65  5197.4  935.43  5276.2  943.29
  5297.2   940.6  5369.6  943.04  5710.4  973.63  5782.8  974.08  5897.3  985.48
  6063.2  991.78    6223 1003.87  6337.6 1006.52  6590.9 1000.78    6642 1003.14
#Mann= 3 ,-1 , 0
  1764.6     .05       0  5004.7    .033       0    5029     .05       0
Bank Sta=5004.7,5029
XS Rating Curve= 0 ,0
Exp/Cntr=0.3,0.1

Type RM Length L Ch R = 1 ,11007   ,1093,1093,1093
BEGIN DESCRIPTION:
DRY VALLEY CREEK 19.0
END DESCRIPTION:
XS GIS Cut Line= 4
      2218181.67       7249333.1      2217061.88      7246702.89
        2216779.        7246710.        2215350.      7246312.07
#Sta/Elev= 30
    1863  956.94  2111.6  949.16  2293.4  938.16  2311.6  940.24  2598.7  930.25
  3872.7   925.5  4914.6  928.21  4944.6  925.46  4964.6   920.5  4972.5  914.08
  4974.9  913.58  4996.8  914.08  5002.1  920.25  5055.9  928.22  5108.4   928.5
  5160.3  934.42  5355.6  944.89  5388.7  949.63  5434.4  949.84  5575.6  959.61
  5637.8  966.27  5660.4  964.58  5679.4  968.24  5807.6  971.13  5980.4  983.44
  6021.9  983.59  6042.7  987.65  6167.2   993.7  6343.7 1009.47    6488 1006.46
#Mann= 3 ,-1 , 0
    1863     .05       0  4972.5    .033       0  4996.8     .05       0
Bank Sta=4972.5,4996.8
XS Rating Curve= 0 ,0
Exp/Cntr=0.3,0.1

Type RM Length L Ch R = 1 ,9914    ,1072,1072,1072
BEGIN DESCRIPTION:
DRY VALLEY CREEK 17.0
END DESCRIPTION:
XS GIS Cut Line= 3
       2218012.4       7248890.4        2217279.        7245810.
      2215376.03       7245765.2
#Sta/Elev= 30
  1833.5  939.87  2286.2  929.01  3765.4  924.49  4917.8  924.88  4939.3  923.39
  4958.9  917.02  4964.2  912.75  4966.6  912.25  4988.6  912.75  4989.7  917.43
    5020   918.9    5060  928.46    5100  925.07    5160  930.79  5208.8  928.48
  5280.1  930.16  5300.1  927.67  5590.2  937.14  5680.2  941.69  5710.2  945.68
  5780.2  947.84  5870.2  955.91  6090.3  965.67  6380.4  988.62  6486.3  991.17
  6500.4  993.71  6520.4  992.54  6650.5  999.93  6760.5 1010.54  6903.5 1009.22
#Mann= 3 ,-1 , 0
  1833.5     .05       0  4964.2     .04       0  4988.6     .05       0
Bank Sta=4964.2,4988.6
XS Rating Curve= 0 ,0
Exp/Cntr=0.3,0.1

Type RM Length L Ch R = 1 ,8842    ,548,548,548
BEGIN DESCRIPTION:
DRY VALLEY CREEK 15.0
END DESCRIPTION:
XS GIS Cut Line= 4
      2220493.29      7245127.19      2218278.23       7244566.8
        2217629.        7244860.      2215506.29      7245374.57
#Sta/Elev= 30
  2002.9  997.36  2340.3  991.57  2545.4   981.9  2909.4  955.61  3073.4  951.11
    3130  946.87  3214.2  946.87  3233.1   944.2  3750.6  925.77  4088.5  921.18
    4911  923.39  4968.2  919.11  4978.2  917.06  4983.8  911.47  4986.5  910.97
  5010.9  911.47  5018.4  915.43  5060.2  919.23  5072.1  917.52  5107.2  921.98
    5358  931.49  5786.3  962.82  5869.9  963.26  6000.5  956.72  6465.5  986.96
  6739.1  999.03  6888.6 1001.71    6914  1004.7  7078.6 1002.44  7184.3 1004.27
#Mann= 5 ,-1 , 0
  2002.9     .05       0    3130     .12       0  3233.1     .05       0
  4983.8     .04       0  5010.9     .05       0
Bank Sta=4983.8,5010.9
XS Rating Curve= 0 ,0
Exp/Cntr=0.3,0.1

Type RM Length L Ch R = 1 ,8294    ,581,581,581
BEGIN DESCRIPTION:
DRY VALLEY CREEK 14.0
END DESCRIPTION:
XS GIS Cut Line= 4
      2220363.08      7244892.83      2218998.94      7244144.98
        2217579.        7244360.      2215444.18      7244775.03
#Sta/Elev= 30
  2008.1   989.1  2587.3  972.39    2927  974.67  3006.3  972.96  3125.8  964.76
  3229.1     961  3338.1   963.6  3414.2  961.72  3544.8  957.47  3831.4  939.62
    3857  935.71  4140.2  921.96  4342.5  919.46  4901.8  922.75  4959.5   917.1
  5010.1     918  5017.3  910.42    5020  909.92  5044.4  910.42    5061  916.97
  5173.1  922.57    5387  922.74  5495.9  928.27  5919.4  962.32  5988.1  969.83
  6704.6  984.21  6996.6  996.68  7019.7  995.27  7066.3   999.6  7174.7 1001.52
#Mann= 5 ,-1 , 0
  2008.1     .05       0    2927     .12       0  3414.2     .05       0
  5017.3     .04       0  5044.4     .05       0
Bank Sta=5017.3,5044.4
XS Rating Curve= 0 ,0
Exp/Cntr=0.3,0.1

Type RM Length L Ch R = 1 ,7713    ,566,566,566
BEGIN DESCRIPTION:
DRY VALLEY CREEK 13.0
END DESCRIPTION:
XS GIS Cut Line= 4
      2220493.25      7244645.41      2219047.94      7244020.41
        2217479.        7243810.      2215533.17      7243981.27
#Sta/Elev= 30
  1847.3  994.56  2151.1  986.23  2331.9  976.44  2385.8  968.54  2402.4  972.25
  2440.3  971.88  2583.2  963.07  2636.6  965.13  2858.4  972.03  2904.9  973.95
    3337  967.08  3542.5  952.71  3935.5  932.44  4207.9  944.69  4480.3  919.15
  4863.7  921.64  4924.2   919.7  4981.8  913.16    5015  916.56  5021.5  911.16
  5024.2  910.66  5048.6  911.16  5055.1  916.23  5081.5   916.2  5496.8     928
    5979  966.91  5998.8   963.7    6049  969.68  6530.8  973.67  6958.3  995.14
#Mann= 7 ,-1 , 0
  1847.3     .05       0  2636.6     .12       0  2858.4     .05       0
  4981.8     .12       0  5021.5     .07       0  5048.6     .12       0
  5081.5     .05       0
Bank Sta=5021.5,5048.6
XS Rating Curve= 0 ,0
Exp/Cntr=0.3,0.1