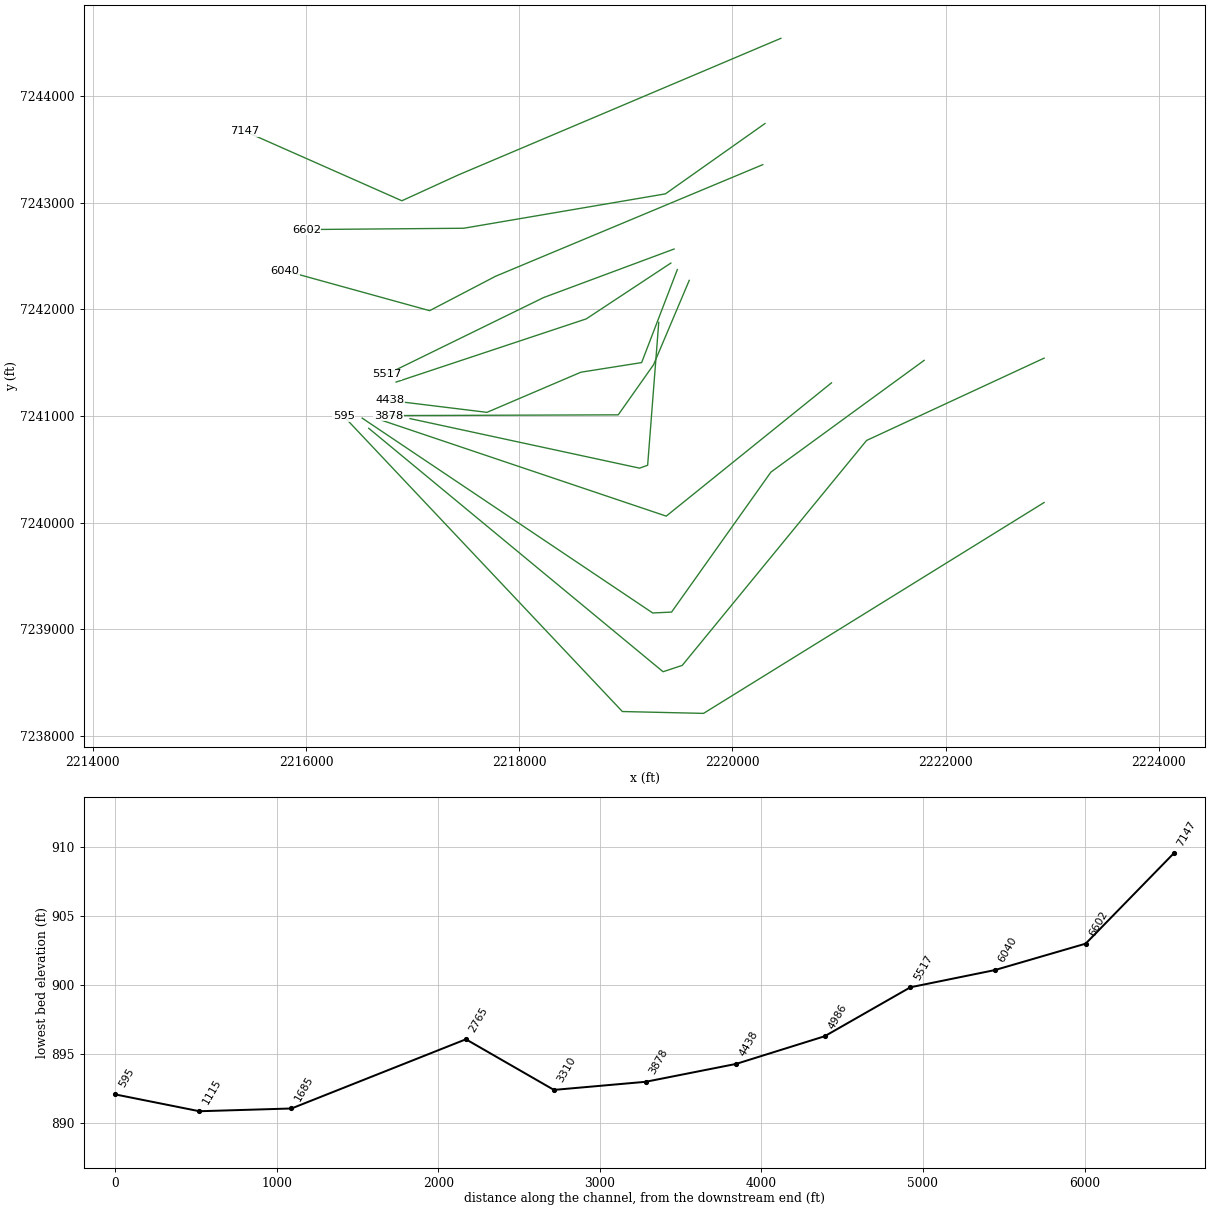
HEC-RAS study DRY VALLEY CREEK.prj: DRY VALLEY CREEK Base Level Engineering

--- DRY VALLEY CREEK.g01 (geometry) --- (continued)

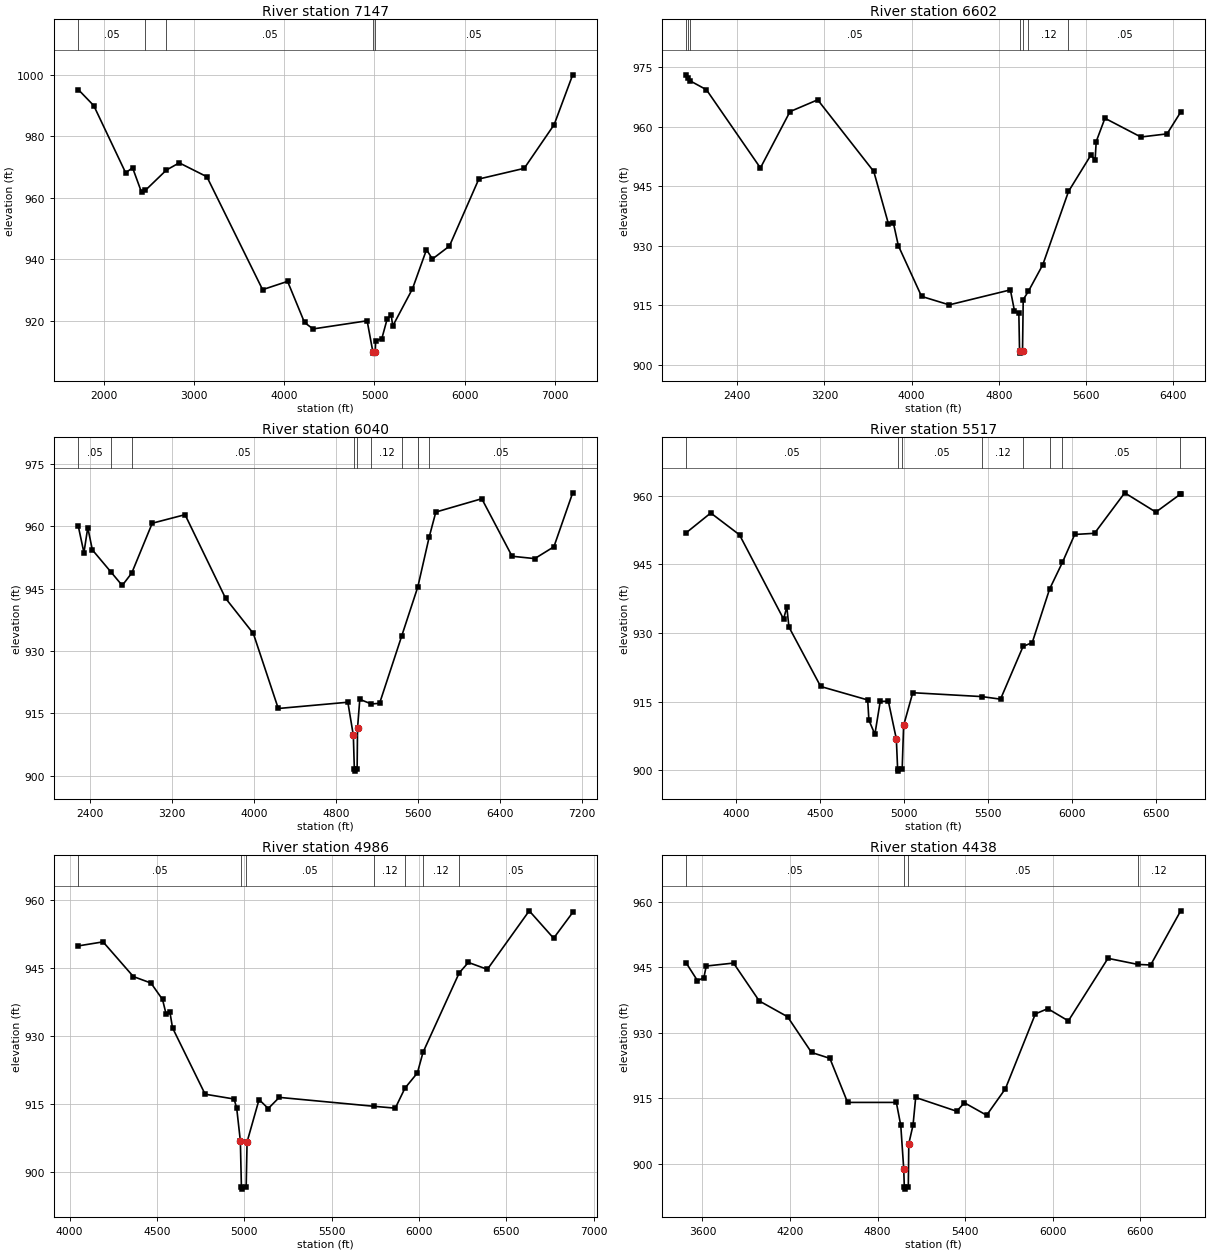
Type RM Length L Ch R = 1 ,7147    ,545,545,545
BEGIN DESCRIPTION:
DRY VALLEY CREEK 12.0
END DESCRIPTION:
XS GIS Cut Line= 4
      2220454.15      7244541.23        2217429.        7243260.
       2216899.5      7243017.81      2215428.14      7243668.85
#Sta/Elev= 30
    1719   995.2  1890.9  989.97  2244.1  968.14  2320.6   969.8  2419.6  961.84
  2461.1  962.42  2695.5  969.05  2837.6  971.38  3143.5  966.87  3760.7  930.19
  4037.5  932.88    4225  919.52  4319.7  917.43  4918.7  920.08  4981.6  910.07
  4984.3  909.57  5008.8  910.07    5013  913.56  5081.3  914.27  5139.1   920.5
  5185.2  921.95  5202.2  918.37  5420.8  930.46  5576.1  943.18  5641.8  940.15
  5829.9  944.34  6155.7  966.13  6658.7   969.6  6990.3  983.81  7195.5  999.98
#Mann= 5 ,-1 , 0
    1719     .05       0  2461.1     .12       0  2695.5     .05       0
  4981.6    .033       0  5008.8     .05       0
Bank Sta=4981.6,5008.8
XS Rating Curve= 0 ,0
Exp/Cntr=0.3,0.1

Type RM Length L Ch R = 1 ,6602    ,562,562,562
BEGIN DESCRIPTION:
DRY VALLEY CREEK 11.0
END DESCRIPTION:
XS GIS Cut Line= 4
      2220304.83        7243742.      2219371.53       7243082.6
        2217479.        7242760.      2216003.72      7242747.83
#Sta/Elev= 30
  1932.4  973.06  1948.6  972.16  1962.7  971.62  2117.5  969.31    2613  949.62
  2884.4   963.8  3138.6  966.77  3653.4  948.73  3787.8  935.57    3834  935.68
  3879.1  930.04  4092.1  917.29  4345.7  915.16  4907.2  918.93  4944.3   913.7
  4984.8  913.09  4991.4  903.51  4994.1  903.01  5018.6  903.51    5025  916.49
  5071.7  918.53    5205  925.28  5440.5   943.7    5645  952.81    5685  951.74
    5695  956.27    5775  962.13    6105  957.41    6345   958.2  6470.3  963.68
#Mann= 7 ,-1 , 0
  1932.4     .05       0  1948.6     .12       0  1962.7     .05       0
  4991.4    .033       0  5018.6     .05       0  5071.7     .12       0
  5440.5     .05       0
Bank Sta=4991.4,5018.6
XS Rating Curve= 0 ,0
Exp/Cntr=0.3,0.1

Type RM Length L Ch R = 1 ,6040    ,523,523,523
BEGIN DESCRIPTION:
DRY VALLEY CREEK 10.0
END DESCRIPTION:
XS GIS Cut Line= 4
      2220284.57      7243356.52        2217779.        7242310.
      2217159.97      7241986.97      2215802.27      7242361.85
#Sta/Elev= 30
  2284.4  960.11  2339.7  953.68  2377.1  959.72    2422  954.36  2603.1  949.04
  2713.1  945.79  2806.1  948.79  3005.7  960.78  3325.8  962.84    3721  942.71
  3991.9  934.23    4235  916.17  4913.7  917.68  4967.2   909.7  4976.9  901.59
  4979.6  901.09  5004.1  901.59    5008  911.42  5030.1  918.37  5143.3  917.26
  5223.2  917.42  5437.3  933.51  5596.1  945.45  5705.9  957.36  5771.6  963.47
  6219.8  966.68  6515.3  952.83  6736.4  952.26  6923.2  955.11  7106.5   968.1
#Mann= 9 ,-1 , 0
  2284.4     .05       0  2603.1     .12       0  2806.1     .05       0
  4976.9    .033       0  5004.1     .05       0  5143.3     .12       0
  5437.3     .05       0  5596.1     .12       0  5705.9     .05       0
Bank Sta=4967.2,5008
XS Rating Curve= 0 ,0
Exp/Cntr=0.3,0.1

Type RM Length L Ch R = 1 ,5517    ,531,531,531
BEGIN DESCRIPTION:
DRY VALLEY CREEK 9.0
END DESCRIPTION:
XS GIS Cut Line= 3
       2219452.7      7242565.22        2218229.        7242110.
      2216754.18      7241388.43
#Sta/Elev= 30
  3700.8  951.89  3846.8   956.2  4018.2  951.43  4280.9  933.05  4300.3  935.66
  4312.9   931.3  4502.1  918.32  4782.4  915.38  4789.5  910.99  4825.2  907.87
  4857.1  915.07  4905.6   915.1  4953.1  906.87  4960.8  900.34  4963.5  899.84
    4988  900.34  4996.6  909.82    5051  916.96  5463.7  916.11  5574.2  915.55
  5708.7  927.07  5763.3   927.9  5866.6  939.58  5943.2  945.41  6016.5  951.51
  6134.6  951.76  6314.7   960.6  6500.3  956.39  6646.9  960.32  6648.3  960.32
#Mann= 8 ,-1 , 0
  3700.8     .05       0  4960.8    .033       0    4988     .05       0
  5463.7     .12       0  5708.7     .05       0  5866.6     .12       0
  5943.2     .05       0  6646.9     .12       0
Bank Sta=4953.1,4996.6
XS Rating Curve= 0 ,0
Exp/Cntr=0.3,0.1

Type RM Length L Ch R = 1 ,4986    ,548,548,548
BEGIN DESCRIPTION:
DRY VALLEY CREEK 8.0
END DESCRIPTION:
XS GIS Cut Line= 3
      2219422.23      7242433.32        2218629.        7241910.
      2216845.47      7241317.41
#Sta/Elev= 30
  4049.9  949.88  4191.8  950.77  4365.3  943.12  4465.8   941.7  4532.1  938.08
  4553.1  934.78  4574.2  935.34  4589.3  931.83  4775.9   917.2  4941.5  916.14
  4956.5  914.17  4977.6  906.89  4983.6  896.78  4986.3  896.28  5010.9  896.78
    5016  906.67  5084.6  916.02  5137.2  914.04  5200.4   916.5  5743.1  914.53
  5864.3  914.12  5919.4  918.52  5990.7  921.88    6023  926.43  6230.2  943.94
  6282.6  946.24  6391.2  944.71  6630.9  957.61  6770.5  951.57  6879.6  957.25
#Mann= 7 ,-1 , 0
  4049.9     .05       0  4983.6    .033       0  5010.9     .05       0
  5743.1     .12       0  5919.4     .05       0    6023     .12       0
  6230.2     .05       0
Bank Sta=4977.6,5016
XS Rating Curve= 0 ,0
Exp/Cntr=0.3,0.1

Type RM Length L Ch R = 1 ,4438    ,560,560,560
BEGIN DESCRIPTION:
DRY VALLEY CREEK 7.0
END DESCRIPTION:
XS GIS Cut Line= 5
      2219483.12      7242372.47      2219148.35      7241500.02
        2218579.        7241410.      2217697.64      7241033.36
       2216784.6      7241144.95
#Sta/Elev= 30
  3489.1  945.94  3565.9  941.92  3609.6  942.58  3625.9  945.26  3813.1  945.94
  3989.4  937.28  4183.5  933.67  4347.6  925.51  4473.5  924.16    4595  914.09
  4929.1  914.09  4959.5  908.83  4979.7  898.92  4983.8  894.77  4986.5  894.27
  5011.1  894.77  5014.5  904.66  5043.5  908.89  5061.7  915.22    5343  912.07
  5395.7  914.01  5548.1  911.16    5677  917.23  5882.1  934.32  5967.1  935.52
  6108.2  932.72  6379.7  947.02  6584.9  945.63  6672.4   945.5  6878.3  957.88
#Mann= 4 ,-1 , 0
  3489.1     .05       0  4983.8    .033       0  5011.1     .05       0
  6584.9     .12       0
Bank Sta=4979.7,5014.5
XS Rating Curve= 0 ,0
Exp/Cntr=0.3,0.1

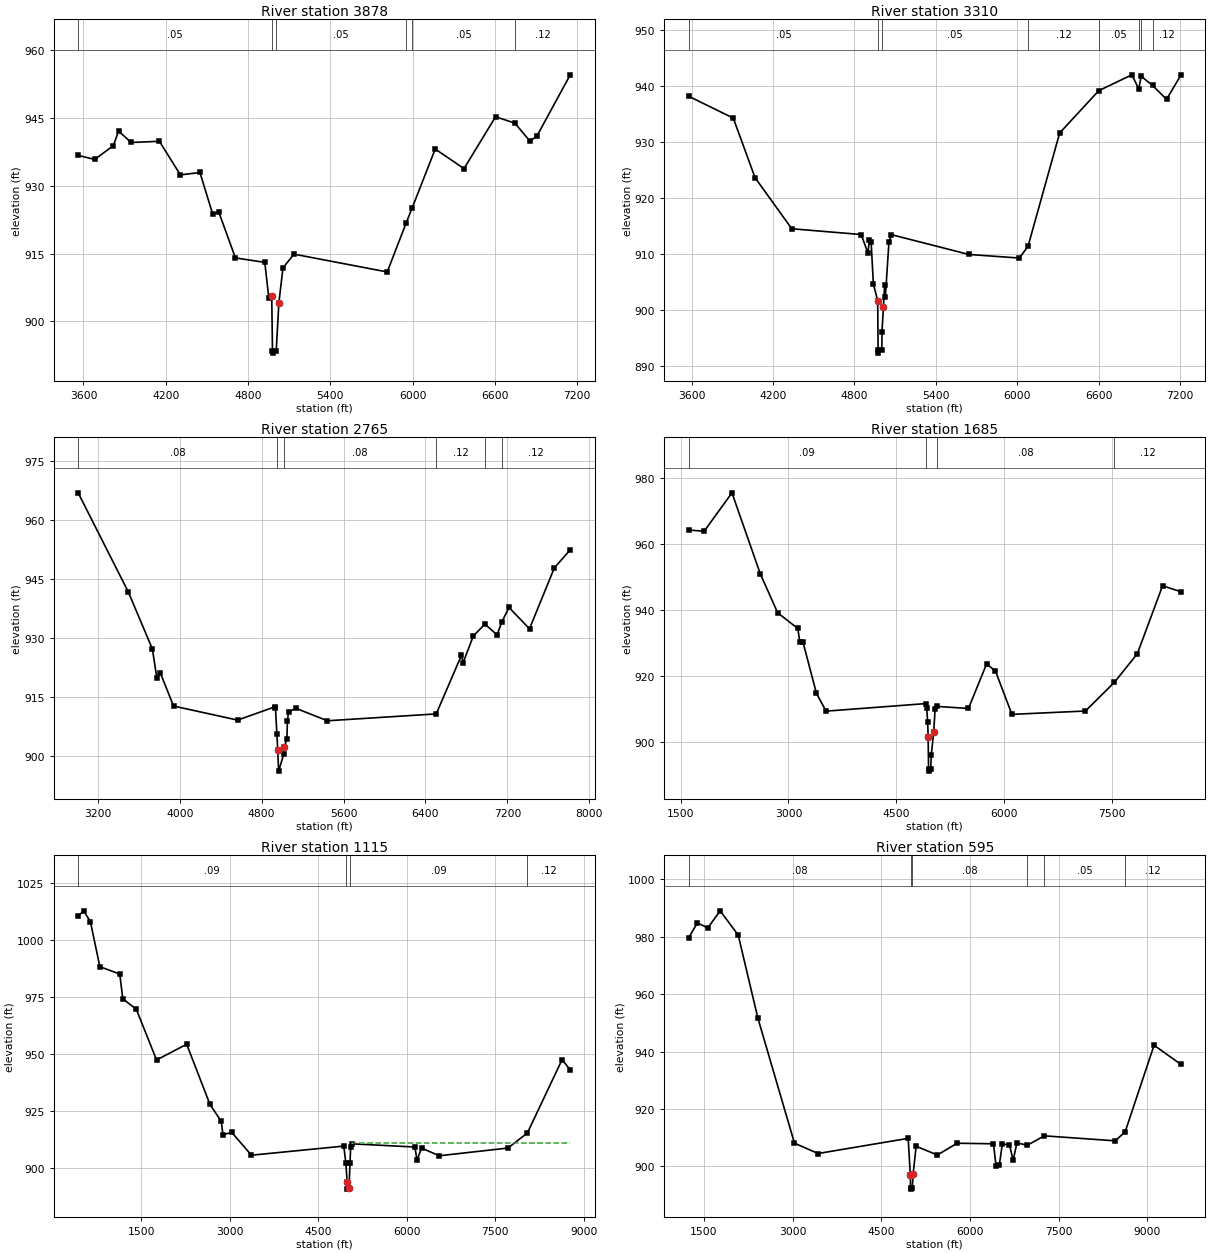
Type RM Length L Ch R = 1 ,3878    ,568,568,568
BEGIN DESCRIPTION:
DRY VALLEY CREEK 6.0
END DESCRIPTION:
XS GIS Cut Line= 4
      2219594.74      7242271.07      2219259.94      7241479.73
        2218929.        7241010.      2216774.46      7241002.92
#Sta/Elev= 30
  3561.4  936.72    3682  935.83  3818.8  938.89  3855.7  942.11  3948.1  939.58
    4154  939.84    4307  932.41  4449.6  932.94  4542.6  923.72  4586.3  924.24
  4708.3  914.04  4922.5  913.05  4952.1  905.11  4973.1  905.71  4978.5  893.47
  4981.2  892.97  5005.8  893.47  5025.2  904.14  5055.2  911.84  5135.2  914.87
  5815.3  910.93  5953.5  921.78  5996.1  925.01  6165.3  938.13  6375.3   933.8
  6605.3  945.27  6746.5  943.86  6855.3   939.9  6905.3  940.91  7149.8  954.55
#Mann= 6 ,-1 , 0
  3561.4     .05       0  4978.5    .033       0  5005.8     .05       0
  5953.5     .12       0  5996.1     .05       0  6746.5     .12       0
Bank Sta=4973.1,5025.2
XS Rating Curve= 0 ,0
Exp/Cntr=0.3,0.1

Type RM Length L Ch R = 1 ,3310    ,545,545,545
BEGIN DESCRIPTION:
DRY VALLEY CREEK 5.0
END DESCRIPTION:
XS GIS Cut Line= 4
      2219308.84      7241877.35      2219204.68      7240537.06
        2219129.        7240510.      2216976.16      7240974.59
#Sta/Elev= 30
  3579.6  938.25  3907.9  934.35  4068.4  923.71  4339.2  914.59  4850.8  913.56
  4900.9  910.23    4911  912.64  4923.9  912.23  4940.6  904.72  4972.4  901.75
  4975.3  892.88    4978  892.38  5002.6  892.88  5004.3  896.23  5014.5  900.62
  5023.8  904.61  5028.9  902.47  5055.4   912.2  5073.1  913.54    5644     910
  6017.1  909.36  6080.7  911.48  6313.8   931.7  6601.8  939.25  6845.7  942.08
  6896.6  939.58  6914.7  941.82  6998.6  940.18  7101.5   937.7  7206.7     942
#Mann= 8 ,-1 , 0
  3579.6     .05       0  4975.3    .033       0  5002.6     .05       0
  6080.7     .12       0  6601.8     .05       0  6896.6     .12       0
  6914.7     .05       0  6998.6     .12       0
Bank Sta=4972.4,5014.5
XS Rating Curve= 0 ,0
Exp/Cntr=0.3,0.1

Type RM Length L Ch R = 1 ,2765    ,1080,1080,1080
BEGIN DESCRIPTION:
DRY VALLEY CREEK 4.0
END DESCRIPTION:
XS GIS Cut Line= 3
      2220928.96      7241309.97        2219379.        7240060.
      2216712.24      7240958.38
#Sta/Elev= 30
  3008.3  966.96  3498.5  941.69  3733.6  927.16  3776.7  919.76  3811.9  921.01
  3939.9  912.64  4565.3  909.06  4928.3  912.43  4935.3  912.11  4949.1  905.41
  4957.1   901.5  4966.2  896.06  5015.2  900.32  5020.6  902.08  5046.7  904.26
  5052.2  908.91  5062.8  911.18  5135.9  912.05  5442.7  908.89  6505.2  910.64
  6751.1  925.55  6768.1  923.72  6867.9  930.53    6981  933.51  7099.4  930.77
  7144.6  933.99  7215.4  937.75  7415.9  932.33  7658.6  947.84  7813.5  952.43
#Mann= 6 ,-1 , 0
  3008.3     .08       0  4949.1    .033       0  5015.2     .08       0
  6505.2     .12       0    6981     .05       0  7144.6     .12       0
Bank Sta=4957.1,5020.6
XS Rating Curve= 0 ,0
Exp/Cntr=0.3,0.1

Type RM Length L Ch R = 1 ,1685    ,570,570,570
BEGIN DESCRIPTION:
DRY VALLEY CREEK 3.0
END DESCRIPTION:
XS GIS Cut Line= 5
      2221797.98      7241520.85      2220360.76      7240472.94
        2219429.        7239160.      2219252.15      7239151.68
      2216527.11      7240979.21
#Sta/Elev= 30
  1612.1  964.14  1826.6  963.77  2213.6  975.42  2606.8   950.9  2849.4  939.05
  3129.8  934.28  3157.8  930.24  3200.9   930.2    3389  914.62  3523.3  909.22
  4907.2   911.5    4922  910.32  4936.8  906.01  4942.9   901.4  4949.4  891.53
  4952.2  891.03  4978.6  891.53  4987.2  896.01  5020.8  902.95  5040.8     910
  5070.8  910.65  5503.8  910.03  5755.9   923.5  5878.9  921.44  6108.7  908.24
  7132.2  909.26  7533.5  917.92  7853.7  926.62  8204.9  947.22  8458.9  945.45
#Mann= 4 ,-1 , 0
  1612.1     .09       0  4907.2    .033       0  5070.8     .08       0
  7533.5     .12       0
Bank Sta=4942.9,5020.8
XS Rating Curve= 0 ,0
Exp/Cntr=0.3,0.1

Type RM Length L Ch R = 1 ,1115    ,520,520,520
BEGIN DESCRIPTION:
DRY VALLEY CREEK 2.0
END DESCRIPTION:
XS GIS Cut Line= 5
      2222922.97      7241541.68      2221257.84       7240769.6
        2219529.        7238660.      2219349.41      7238600.58
      2216588.96      7240883.59
#Sta/Elev= 30
   432.9 1010.45   525.5 1012.81   640.1 1008.11   800.4  988.33  1137.7   985.1
    1189  974.24  1418.1  969.66  1760.9  947.44  2271.3  954.33  2665.5  927.95
  2857.1  920.53  2885.8  914.65  3034.4  915.69  3368.1   905.7  4931.2  909.69
  4967.8  902.21  4988.7  893.89  4994.6  890.83    5021  891.33    5038  902.45
  5048.7  909.45  5075.1  910.68  6136.4  909.29  6171.8  903.58  6249.7  908.81
  6548.1  905.45  7713.8  908.84  8041.8  915.45  8629.5   947.6  8767.2  943.09
#Mann= 4 ,-1 , 0
   432.9     .09       0  4967.8    .033       0    5038     .09       0
  8041.8     .12       0
#XS Ineff= 2 , 0
                         5074.57          911.15
Permanent Ineff=
       F       F
Bank Sta=4988.7,5021
XS Rating Curve= 0 ,0
Exp/Cntr=0.3,0.1

Type RM Length L Ch R = 1 ,595     ,0,0,0
BEGIN DESCRIPTION:
DRY VALLEY CREEK 1.0
END DESCRIPTION:
XS GIS Cut Line= 4
      2222922.96       7240187.5        2219729.        7238210.
      2218967.47      7238227.31      2216355.25      7240995.74
#Sta/Elev= 30
  1243.7  979.65  1389.5  984.82  1565.7  983.07    1776  989.02  2080.9  980.55
  2412.9  951.67  3032.2  908.07  3431.6  904.46    4956  909.74  4992.6  896.84
  4995.7  892.55  4998.5  892.05  5024.9  892.55  5040.3  897.35  5090.3  906.99
  5450.4  903.94    5784  908.04  6399.3  907.85  6441.8  900.19  6498.4  900.48
  6548.2  907.66  6668.4  907.58  6731.9  902.11  6795.8  908.15  6974.3  907.36
  7258.5  910.62  8458.2  908.88  8626.4  911.99    9116  942.19  9568.3  935.53
#Mann= 6 ,-1 , 0
  1243.7     .08       0  4995.7    .033       0  5024.9     .08       0
  6974.3     .12       0  7258.5     .05       0  8626.4     .12       0
Bank Sta=4992.6,5040.3
XS Rating Curve= 0 ,0
Exp/Cntr=0.3,0.1

Chan Stop Cuts=-1
Use User Specified Reach Order=0
Composite Channel Slope=5