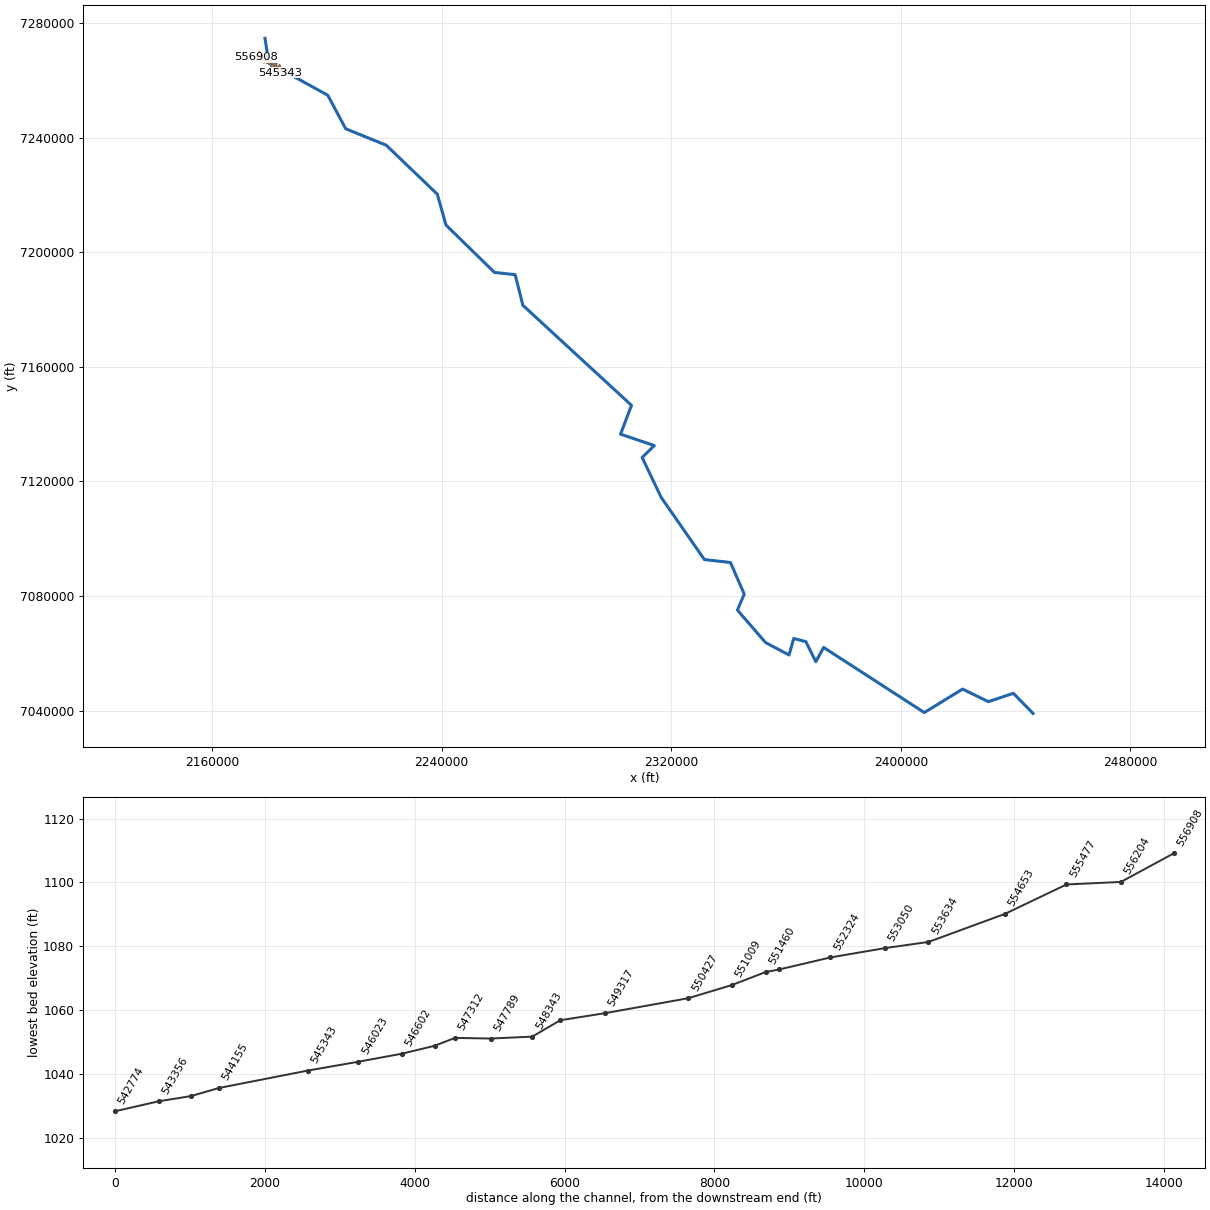
--- Denton Creek.prj (project) ---

Proj Title=Denton Creek Base Level Engineering
Current Plan=p01
Default Exp/Contr=0.3,0.1
English Units
Geom File=g01
Flow File=f01
Plan File=p01
Y Axis Title=Elevation
X Axis Title(PF)=Main Channel Distance
X Axis Title(XS)=Station
BEGIN DESCRIPTION:
Denton Creek
END DESCRIPTION:
DSS Export Rating Curves= 0
DSS Export Rating Curve Sorted= 0
DSS Export Volume Flow Curves= 0
DXF OffsetX= 0
DXF OffsetY= 0
DXF ScaleX= 1
DXF ScaleY= 10

--- Denton Creek.p01 (plan) ---

Plan Title=Multiple Run
Program Version=4.10
Short Identifier=Multiple
Geom File=g01
Flow File=f01
Subcritical Flow
K Sum by GR= 0
Std Step Tol= 0.01
Critical Tol= 0.01
Num of Std Step Trials= 20
Max Error Tol= 0.3
Flow Tol Ratio= 0.001
Split Flow NTrial= 30
Split Flow Tol= 0.02
Split Flow Ratio= 0.02
Log Output Level= 0
Friction Slope Method= 1
Unsteady Friction Slope Method= 2
Unsteady Bridges Friction Slope Method= 1
Parabolic Critical Depth
Global Vel Dist= 1 , 1 , 1
Global Log Level= 0
CheckData=True
Encroach Param=-1 ,0,0, 0
BEGIN DESCRIPTION:
Multiple Run
END DESCRIPTION:
Computation Interval=1HOUR
Output Interval=1HOUR
Run HTab= 0
Run UNet= 0
Run PostProcess= 0
Run WQNet= 0
UNET Theta= 1
UNET Theta Warmup= 1
UNET ZTol= 0.02
UNET ZSATol= 0.05
UNET MxIter= 20
UNET MaxInSteps= 0
UNET DtIC= 0
UNET DtMin= 0
UNET MaxCRTS= 20
UNET WFStab= 2
UNET SFStab= 1
UNET WFX= 1
UNET SFX= 1
UNET DSS MLevel= 4
UNET DZMax Abort= 100
UNET Convert EG Bridges= 0
UNET Use Existing IB Tables=-1
UNET Froude Reduction=False
UNET Froude Limit= 1
UNET Froude Power= 10
UNET Time Slicing=0,0, 5
UNET Junction Losses=0
Instantaneous Interval=1HOUR
Write IC File= 0
Write IC File at Sim End=0
Echo Input=False
Echo Parameters=False
Echo Output=False
Write Detailed= 0
WQ AD Non Conservative
WQ ULTIMATE=-1
WQ Max Comp Step=1HOUR
WQ Output Interval=15MIN
WQ Output Selected Increments= 0
WQ Output face flow=0
WQ Output face velocity=0
WQ Output face area=0
WQ Output face dispersion=0
WQ Output cell volume=0
WQ Output cell surface area=0
WQ Output cell continuity=0
WQ Output cumulative cell continuity=0
WQ Output face conc=0
WQ Output face dconc_dx=0
WQ Output face courant=0
WQ Output face peclet=0
WQ Output face adv mass=0
WQ Output face disp mass=0
WQ Output cell mass=0
WQ Output cell source sink temp=0
WQ Output cell source sink nsm=0
WQ Output MaxMinRange=-1
WQ Daily Max Min Mean=-1
WQ Daily Range=0
WQ Daily Time=0
WQ Create Restart=0
WQ Fixed Restart=0
WQ System Summary=0
WQ Use Fixed Temperature=0
Sorting and Armoring Iterations= 10
XS Update Threshold= 0.02
Hydraulics Update Threshold= 0.02
Energy Slope Method= 1
Volume Change Method= 0
XS Weighting Method= 0
Number of US Weighted Cross Sections= 1
Number of DS Weighted Cross Sections= 1
Upstream XS Weight=0.25
Main XS Weight=0.5
Downstream XS Weight=0.25
Number of DS XS's Weighted with US Boundary= 1
Upstream Boundary Weight= 1
Weight of XSs Associated with US Boundary= 0
Number of US XS's Weighted with DS Boundary= 1
Downstream Boundary Weight= 0.5
Weight of XSs Associated with DS Boundary= 0.5
Sediment Output Level= 4
Mass or Volume Output= 0
Output Increment Type= 1
Profile and TS Output Increment= 10
XS Output Flag= 0
XS Output Increment= 10
Disregard all LS=0
Disregard all Conn=0
Disregard all Breaches=0
Disregard all Pumps=0

--- Denton Creek.f01 (steady flow) ---

Flow Title=Multiple
Number of Profiles=7
Profile Names=10-year,25-year,50-year,1pct_min,100-year,1pct_plu,500-year
River Rch & RM= Denton Creek,Reach-1,556908
     516     742     923     876    1120    1490    1285
River Rch & RM= Denton Creek,Reach-1,552324
     927    1377    1747    1690    2160    2875    2575
River Rch & RM= Denton Creek,Reach-1,550427
    1101    1648    2103    2043    2611    3476    3142
River Rch & RM= Denton Creek,Reach-1,548718
    1260    1893    2421    2358    3013    4010    3641
River Rch & RM= Denton Creek,Reach-1,545343
    1456    2197    2819    2751    3516    4680    4270
River Rch & RM= Denton Creek,Reach-1,541952
    1824    2768    3564    3488    4457    5933    5443
River Rch & RM= Denton Creek,Reach-1,536885
    1987    3029    3911    3838    4905    6529    6022
River Rch & RM= Denton Creek,Reach-1,534323
    2015    3066    3954    3875    4952    6591    6063
River Rch & RM= Denton Creek,Reach-1,527938
    3781    5866    7669    7608    9723   12940   12189
River Rch & RM= Denton Creek,Reach-1,525359
    3917    6090    7971    7915   10115   13462   12708
River Rch & RM= Denton Creek,Reach-1,522192
    3987    6188    8090    8022   10252   13644   12845
River Rch & RM= Denton Creek,Reach-1,518174
    4205    6524    8526    8450   10798   14372   13513
River Rch & RM= Denton Creek,Reach-1,511326
    4318    6700    8757    8678   11090   14761   13878
River Rch & RM= Denton Creek,Reach-1,509975
    4480    6954    9091    9012   11516   15328   14417
River Rch & RM= Denton Creek,Reach-1,509123
    4625    7172    9371    9281   11861   15786   14823
River Rch & RM= Denton Creek,Reach-1,501605
    4930    7634    9966    9862   12603   16774   15716
River Rch & RM= Denton Creek,Reach-1,498714
    4932    7655   10007    9915   12671   16865   15848
River Rch & RM= Denton Creek,Reach-1,494220
    5075    7878   10300   10207   13044   17361   16316
River Rch & RM= Denton Creek,Reach-1,492109
    8116   12700   16707   16646   21273   28313   26874
River Rch & RM= Denton Creek,Reach-1,486610
    8103   12642   16595   16498   21084   28062   26517
River Rch & RM= Denton Creek,Reach-1,477778
    9325   14549   19101   18987   24265   32295   30501
River Rch & RM= Denton Creek,Reach-1,470522
    9584   14924   19569   19425   24824   33040   31115
River Rch & RM= Denton Creek,Reach-1,453375
   10509   16369   21471   21319   27244   36261   34158
River Rch & RM= Denton Creek,Reach-1,441762
   10844   16937   22254   22131   28283   37643   35585
River Rch & RM= Denton Creek,Reach-1,440166
   11412   17738   23234   23032   29434   39176   36778
River Rch & RM= Denton Creek,Reach-1,420089
   12815   19887   26031   25785   32952   43858   41088
River Rch & RM= Denton Creek,Reach-1,414166
   13483   20799   27121   26759   34197   45515   42282
River Rch & RM= Denton Creek,Reach-1,382531
   14219   21940   28617   28241   36090   48035   44637
River Rch & RM= Denton Creek,Reach-1,371235
   15183   23430   30566   30168   38554   51314   47689
River Rch & RM= Denton Creek,Reach-1,363703
   16327   25072   32609   32084   41001   54571   50371
River Rch & RM= Denton Creek,Reach-1,326552
   16895   25831   33496   31845   41981   54166   51245
River Rch & RM= Denton Creek,Reach-1,267991
   17100   26100   33800   33100   42300   56300   51500
River Rch & RM= Denton Creek,Reach-1,211572
   17954   27289   35294   34357   44163   59493   53793
River Rch & RM= Denton Creek,Reach-1,196958
   22172   33215   42797   40629   53591   75968   65572
River Rch & RM= Denton Creek,Reach-1,149137
   27700   40900   52500   48300   65800   98900   80900
River Rch & RM= Denton Creek,Reach-1,128744
   28838   42310   54130   49405   67662  102626   82748
River Rch & RM= Denton Creek,Reach-1,55440
    4446    6176    7581    7458    9053   11405   10560
River Rch & RM= Denton Creek,Reach-1,42698
    4094    5673    6955    6841    8303   10460    9690
Boundary for River Rch & Prof#=Denton Creek,Reach-1,1
Up Type=0
Dn Type=3
Dn Slope=0.0001
Boundary for River Rch & Prof#=Denton Creek,Reach-1,2
Up Type=0
Dn Type=3
Dn Slope=0.0001
Boundary for River Rch & Prof#=Denton Creek,Reach-1,3
Up Type=0
Dn Type=3
Dn Slope=0.0001
Boundary for River Rch & Prof#=Denton Creek,Reach-1,4
Up Type=0
Dn Type=3
Dn Slope=0.0001
Boundary for River Rch & Prof#=Denton Creek,Reach-1,5
Up Type=0
Dn Type=3
Dn Slope=0.0001
Boundary for River Rch & Prof#=Denton Creek,Reach-1,6
Up Type=0
Dn Type=3
Dn Slope=0.0001
Boundary for River Rch & Prof#=Denton Creek,Reach-1,7
Up Type=0
Dn Type=3
Dn Slope=0.0001

--- Denton Creek.g01 (geometry) ---

Geom Title=Existing Conditions
Program Version=4.10

River Reach=Denton Creek    ,Reach-1
Reach XY= 30
      2178408.36      7274602.27       2179768.4      7266075.55
      2200312.15      7254732.42      2206532.56       7243063.8
      2220687.42      7237301.63      2238473.69      7220228.37
      2241496.16      7209458.13       2258404.5      7192932.58
      2265605.81       7192149.4      2268306.38      7181459.74
      2306150.74      7146572.22       2302344.6       7136513.2
      2314103.99      7132528.86      2309858.84      7128370.66
      2316528.64       7114405.7      2331568.27      7092761.23
      2340640.61      7091752.21      2345447.38      7080695.53
       2343061.7      7075147.25      2352868.55      7063821.22
      2361056.67      7059472.98      2362697.01      7065238.14
      2366935.46      7064122.56      2370394.05      7057130.37
      2373128.39      7062101.75      2408198.66      7039389.72
      2421560.15      7047586.25      2430532.58      7043185.61
      2439236.94      7046094.88      2446108.64       7039105.7

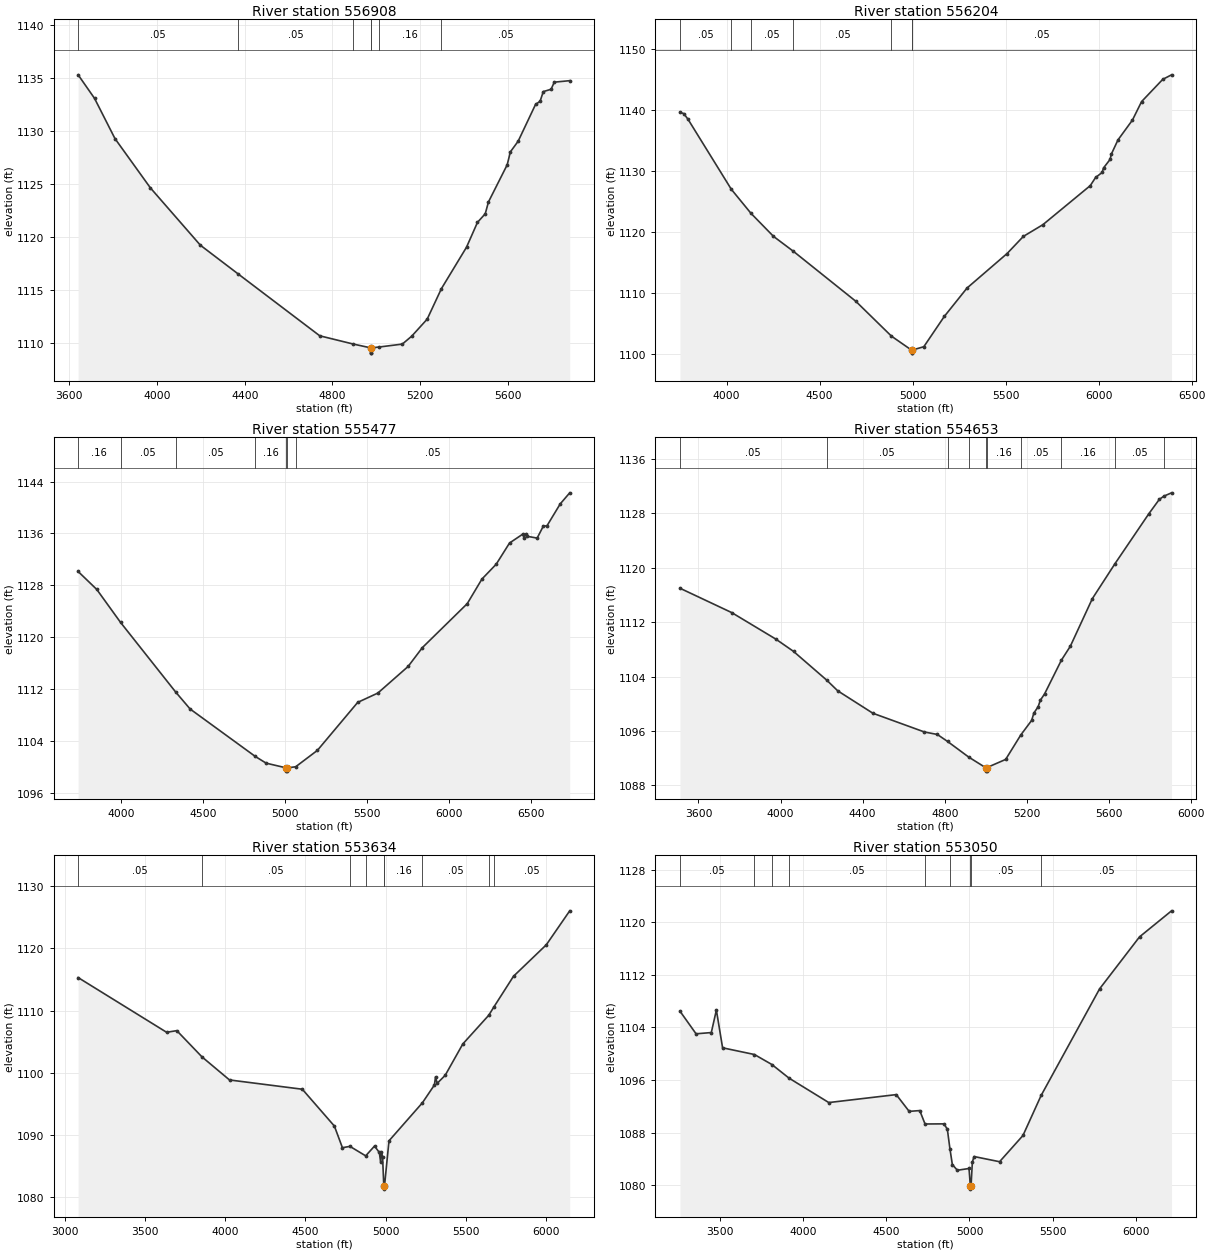
Type RM Length L Ch R = 1 ,556908  ,704,704,704
BEGIN DESCRIPTION:
Denton Creek 336.0
END DESCRIPTION:
XS GIS Cut Line= 3
      2176402.83      7269876.62       2175776.2      7268757.81
      2175201.62      7267985.67
#Sta/Elev= 30
  3639.9 1135.27  3714.9 1133.05  3807.9 1129.27  3969.5 1124.63  4197.6 1119.23
    4369 1116.54  4742.3  1110.7    4896 1109.92  4973.9 1109.57  4974.1 1109.07
  4977.6 1109.07  4977.9 1109.57  5011.1 1109.64  5118.9 1109.92  5161.5 1110.66
  5232.4 1112.27  5297.3 1115.14  5411.8 1119.04  5461.8 1121.38  5497.3 1122.19
  5511.9  1123.3  5597.4  1126.8    5612 1128.02  5647.4 1129.02  5726.7 1132.48
  5747.5 1132.78  5762.1 1133.69  5797.6 1133.91  5812.2 1134.58  5882.7 1134.72
#Mann= 7 ,-1 , 0
  3639.9     .05       0    4369     .05       0    4896     .05       0
  4973.9    .035       0  4977.9     .05       0  5011.1     .16       0
  5297.3     .05       0
Bank Sta=4973.9,4977.9
XS Rating Curve= 0 ,0
Exp/Cntr=0.3,0.1

Type RM Length L Ch R = 1 ,556204  ,727,727,727
BEGIN DESCRIPTION:
Denton311
END DESCRIPTION:
XS GIS Cut Line= 3
      2176803.72      7269500.43      2176036.28      7267752.98
      2175487.04      7267262.39
#Sta/Elev= 30
  3748.9 1139.56  3769.4 1139.37  3792.7 1138.41    4025 1126.97  4131.1 1123.02
  4251.7 1119.26  4359.3  1116.8  4693.6 1108.65    4886 1102.92  4993.8 1100.64
    4994 1100.14  4997.5 1100.14  4997.8 1100.64    5060 1101.19  5170.2 1106.15
  5292.4  1110.8  5507.8 1116.45  5595.1 1119.25  5700.1 1121.17    5955 1127.57
  5983.5  1128.9  6018.6 1129.72  6026.1 1130.46  6061.2 1131.85  6068.7 1132.76
  6103.8 1135.05  6181.6  1138.3  6230.9 1141.33  6344.6 1144.97  6391.9 1145.71
#Mann= 7 ,-1 , 0
  3748.9     .05       0    4025     .16       0  4131.1     .05       0
  4359.3     .05       0    4886     .05       0  4993.8    .035       0
  4997.8     .05       0
Bank Sta=4993.8,4997.8
XS Rating Curve= 0 ,0
Exp/Cntr=0.3,0.1

Type RM Length L Ch R = 1 ,555477  ,824,824,824
BEGIN DESCRIPTION:
Denton312
END DESCRIPTION:
XS GIS Cut Line= 4
      2177204.41      7269156.71      2176921.13      7268159.17
      2176499.81      7267496.24       2175471.1      7266926.78
#Sta/Elev= 30
  3736.7 1130.13  3850.4 1127.36  3995.2 1122.28  4331.9 1111.52  4419.4 1108.92
  4816.9  1101.6  4882.7 1100.57  5005.2 1099.84  5005.5 1099.34    5009 1099.34
  5009.2 1099.84  5062.7 1100.01  5195.2 1102.54  5440.8 1109.94  5563.8 1111.38
  5748.1 1115.48  5835.1 1118.39  6108.7 1125.17  6198.1 1128.96  6285.1 1131.25
  6366.4 1134.52  6447.7  1135.9  6453.5 1135.36  6469.5 1135.96  6475.2 1135.55
  6534.8 1135.28  6572.6 1137.14  6594.3 1137.16  6675.6 1140.56  6733.3 1142.26
#Mann= 7 ,-1 , 0
  3736.7     .16       0  3995.2     .05       0  4331.9     .05       0
  4816.9     .16       0  5005.2     .07       0  5009.2     .16       0
  5062.7     .05       0
Bank Sta=5005.2,5009.2
XS Rating Curve= 0 ,0
Exp/Cntr=0.3,0.1

Type RM Length L Ch R = 1 ,554653  ,1019,1019,1019
BEGIN DESCRIPTION:
Denton313
END DESCRIPTION:
XS GIS Cut Line= 3
      2177558.98      7268942.57      2177600.23      7268174.43
      2177075.97      7266634.17
#Sta/Elev= 30
  3509.7 1116.99  3762.6  1113.4  3977.1 1109.51  4063.1 1107.71  4224.7 1103.49
  4278.7 1101.91  4450.4 1098.61  4701.3 1095.86    4764  1095.5    4814 1094.47
  4916.7 1092.18  4999.9 1090.61  5000.2 1090.11  5003.7 1090.11    5004 1090.61
    5097 1091.83  5170.9 1095.43  5223.8 1097.57  5234.5 1098.65  5255.3 1099.57
    5266 1100.53  5286.6 1101.45  5368.5 1106.41  5412.1 1108.46  5519.5 1115.46
  5630.3 1120.62  5794.2 1127.91  5845.9 1130.05  5868.7 1130.53  5905.5 1131.01
#Mann= 10 ,-1 , 0
  3509.7     .05       0  4224.7     .05       0    4814     .05       0
  4916.7     .16       0  4999.9     .07       0    5004     .16       0
  5170.9     .05       0  5368.5     .16       0  5630.3     .05       0
  5868.7     .16       0
Bank Sta=4999.9,5004
XS Rating Curve= 0 ,0
Exp/Cntr=0.3,0.1

Type RM Length L Ch R = 1 ,553634  ,584,584,584
BEGIN DESCRIPTION:
Denton314
END DESCRIPTION:
XS GIS Cut Line= 3
      2177667.22      7269008.22      2178119.02      7267777.38
      2178012.78       7266023.4
#Sta/Elev= 30
  3081.9 1115.29  3633.9 1106.51  3697.8 1106.77  3854.8 1102.56  4026.5 1098.86
  4480.8 1097.37  4680.9 1091.46    4731 1087.99  4778.1  1088.2  4876.2 1086.68
  4931.4 1088.25  4961.4 1087.22  4969.3 1085.71  4974.3 1087.26  4981.5 1086.55
  4989.4 1081.84  4989.7 1081.34  4993.6 1081.84  5021.6 1089.09    5230 1095.19
    5305 1098.05  5312.1 1099.36  5322.1 1098.31  5372.2  1099.6  5482.4 1104.64
  5644.4 1109.25  5675.6 1110.55  5798.6  1115.5  6003.3 1120.55  6149.4    1126
#Mann= 9 ,-1 , 0
  3081.9     .05       0  3854.8     .05       0  4778.1     .05       0
  4876.2     .16       0  4989.4     .07       0  4993.6     .16       0
    5230     .05       0  5644.4     .16       0  5675.6     .05       0
Bank Sta=4989.4,4993.6
XS Rating Curve= 0 ,0
Exp/Cntr=0.3,0.1

Type RM Length L Ch R = 1 ,553050  ,726,726,726
BEGIN DESCRIPTION:
Denton315
END DESCRIPTION:
XS GIS Cut Line= 5
      2177948.72      7268891.01      2178391.33      7267681.76
      2178537.21       7267531.2      2178586.19      7266968.74
      2178211.16      7266154.57
#Sta/Elev= 30
    3258 1106.48  3354.9 1103.03  3446.7 1103.22  3477.2 1106.64  3514.6  1100.9
  3706.1 1099.88  3811.1 1098.36  3914.2 1096.29  4153.6 1092.57  4559.5 1093.78
  4637.2 1091.23    4701 1091.35  4732.8 1089.31  4846.9 1089.33    4867 1088.51
  4882.6 1085.53  4897.1 1083.14  4927.2 1082.27  4997.5 1082.54  5005.3  1079.9
  5005.7  1079.4  5009.6  1079.9  5017.5 1083.51  5027.6 1084.36  5181.3 1083.57
    5322 1087.56  5431.5 1093.66  5782.9 1109.86  6023.5 1117.78  6216.1 1121.74
#Mann= 9 ,-1 , 0
    3258     .05       0  3706.1     .05       0  3811.1     .05       0
  3914.2     .05       0  4732.8     .05       0  4882.6     .05       0
  5005.3    .045       0  5009.6     .05       0  5431.5     .05       0
Bank Sta=5005.3,5009.6
XS Rating Curve= 0 ,0
Exp/Cntr=0.3,0.1

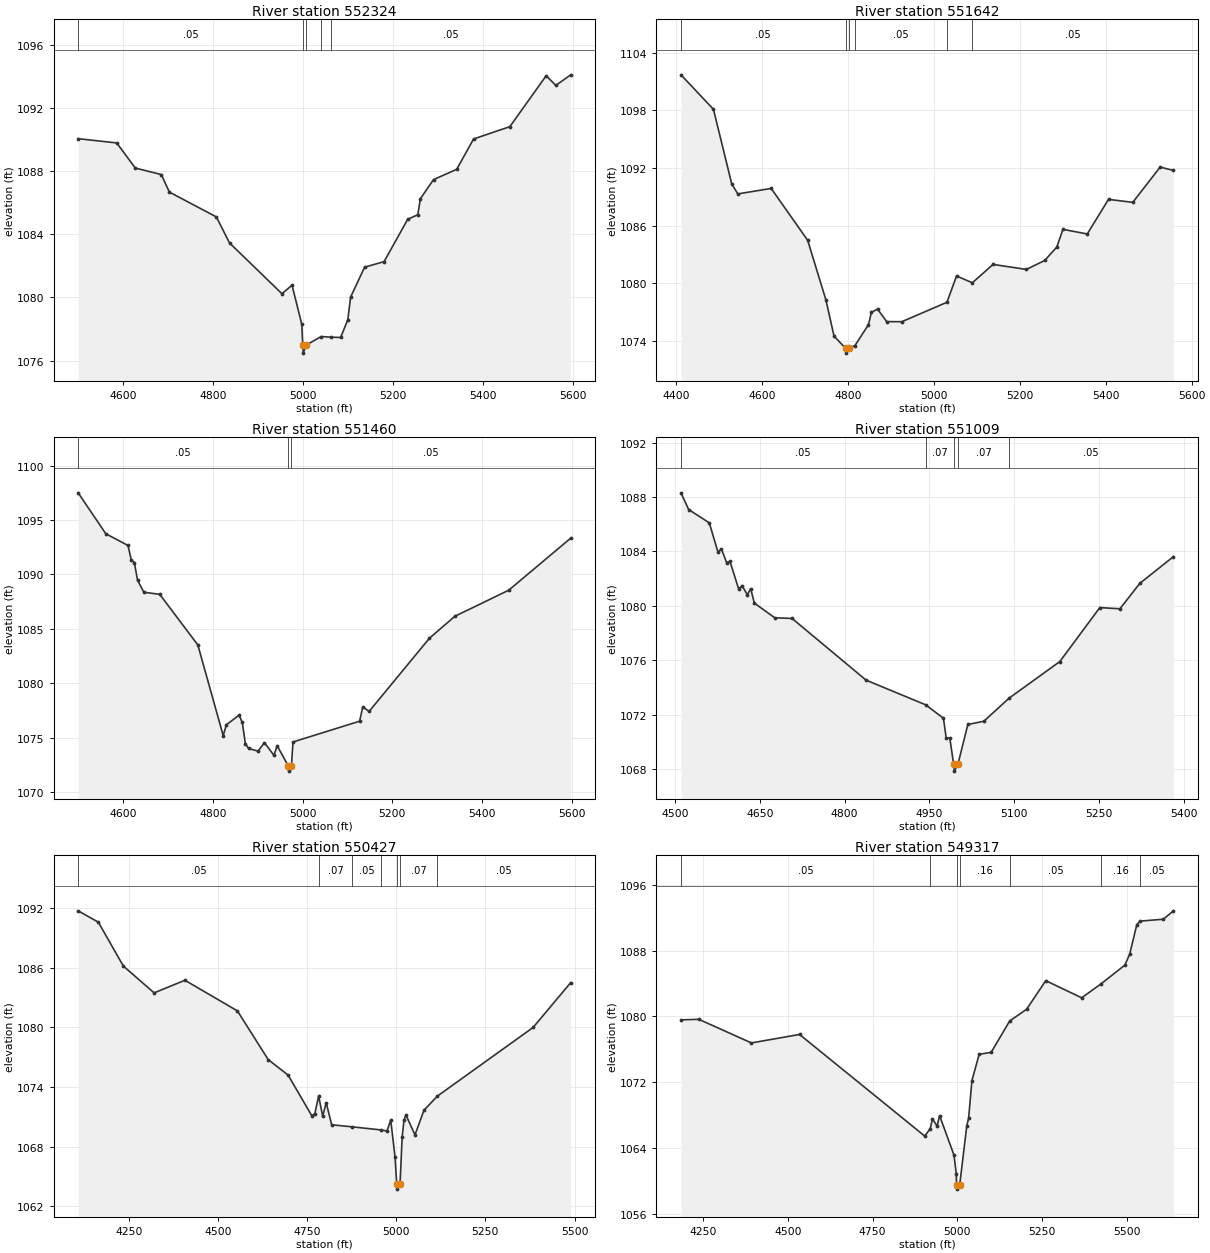
Type RM Length L Ch R = 1 ,552324  ,682,682,682
BEGIN DESCRIPTION:
Denton Creek 327.0
END DESCRIPTION:
XS GIS Cut Line= 3
       2179366.3       7267388.2        2179179.        7266960.
      2178868.43      7266415.17
#Sta/Elev= 30
  4500.1 1090.05  4585.8 1089.78  4627.1 1088.19  4684.8 1087.78  4702.8 1086.67
  4807.2  1085.1  4836.5 1083.45    4953 1080.24  4975.4 1080.78    4997 1078.31
  4999.2 1076.98  5000.3 1076.48  5006.3 1076.98  5040.2 1077.53  5062.7 1077.49
  5083.4 1077.47  5099.3 1078.59  5105.6 1080.03  5136.7 1081.92    5180 1082.27
  5232.2 1084.94  5254.9 1085.24  5260.6 1086.25  5289.8 1087.46  5341.3 1088.11
  5378.8 1090.03  5459.4 1090.81  5540.1 1094.03  5561.7 1093.42  5594.6 1094.09
#Mann= 5 ,-1 , 0
  4500.1     .05       0  4999.2    .035       0  5006.3     .05       0
  5040.2     .05       0  5062.7     .05       0
Bank Sta=4999.2,5006.3
XS Rating Curve= 0 ,0
Exp/Cntr=0.3,0.1

Type RM Length L Ch R = 1 ,551642  ,182,182,182
BEGIN DESCRIPTION:
Denton Creek 326.0
END DESCRIPTION:
XS GIS Cut Line= 3
      2179926.67      7266789.27      2179673.28      7266538.22
      2179114.71       7265980.4
#Sta/Elev= 30
  4411.6 1101.69  4487.2  1098.1  4529.7 1090.34  4543.8  1089.3  4621.5 1089.87
  4706.4 1084.47  4748.8 1078.28  4767.8  1074.5  4794.7 1073.23  4795.8 1072.73
    4802 1073.23  4816.5 1073.52  4847.8 1075.68  4854.9 1076.98  4869.1 1077.31
  4890.3 1076.01  4925.6    1076  5030.5 1078.02  5052.9 1080.76  5089.7 1080.05
  5137.8 1081.96  5215.5 1081.44    5258 1082.37  5286.2 1083.77  5300.4 1085.61
    5357 1085.13  5406.5 1088.73    5463 1088.42  5526.7 1092.09  5557.7 1091.74
#Mann= 6 ,-1 , 0
  4411.6     .05       0  4794.7     .05       0    4802     .05       0
  4816.5     .05       0  5030.5     .05       0  5089.7     .05       0
Bank Sta=4794.7,4802
XS Rating Curve= 0 ,0
Exp/Cntr=0.3,0.1

Type RM Length L Ch R = 1 ,551460  ,451,451,451
BEGIN DESCRIPTION:
Denton Creek 325.0
END DESCRIPTION:
XS GIS Cut Line= 3
      2180008.77      7266637.38        2179629.        7266260.
      2179237.29      7265856.56
#Sta/Elev= 30
  4499.8  1097.5  4561.4 1093.74  4610.9 1092.66    4618 1091.35  4625.1 1091.09
  4632.1 1089.47  4646.3 1088.36  4681.6 1088.17  4766.5 1083.52  4823.1 1075.18
  4830.1 1076.18  4858.4 1077.06  4865.5 1076.41  4872.5 1074.44  4879.6    1074
  4900.8 1073.76    4915 1074.54  4936.2 1073.37  4943.3 1074.26  4967.8 1072.42
    4969 1071.92  4975.2 1072.42  4978.6  1074.6  5127.1 1076.51  5134.1 1077.83
  5148.3 1077.41  5282.8 1084.14  5339.3 1086.15  5459.5 1088.55  5597.5 1093.33
#Mann= 3 ,-1 , 0
  4499.8     .05       0  4967.8    .035       0  4975.2     .05       0
Bank Sta=4967.8,4975.2
XS Rating Curve= 0 ,0
Exp/Cntr=0.3,0.1

Type RM Length L Ch R = 1 ,551009  ,582,582,582
BEGIN DESCRIPTION:
Denton Creek 324.0
END DESCRIPTION:
XS GIS Cut Line= 3
      2180179.01      7266360.01        2179929.        7265960.
      2179651.34      7265673.61
#Sta/Elev= 30
  4510.8 1088.31  4524.4 1087.08  4560.9  1086.1  4576.3 1083.93  4582.2 1084.19
  4591.6 1083.17  4597.5 1083.26  4612.8 1081.23  4618.7 1081.49  4628.1 1080.81
    4634 1081.26  4640.5  1080.2  4676.5 1079.12  4707.2 1079.07  4838.1 1074.53
  4943.2 1072.72  4974.8 1071.73  4979.6 1070.28    4986 1070.28  4992.8 1068.34
    4994 1067.84  5000.3 1068.34  5017.9 1071.27  5046.2 1071.51  5090.9 1073.21
  5180.5  1075.9  5251.2 1079.87  5286.7 1079.78  5321.9 1081.65  5381.4 1083.62
#Mann= 5 ,-1 , 0
  4510.8     .05       0  4943.2     .07       0  4992.8     .07       0
  5000.3     .07       0  5090.9     .05       0
Bank Sta=4992.8,5000.3
XS Rating Curve= 0 ,0
Exp/Cntr=0.3,0.1

Type RM Length L Ch R = 1 ,550427  ,1110,1110,1110
BEGIN DESCRIPTION:
Denton Creek316
END DESCRIPTION:
XS GIS Cut Line= 3
      2180647.87       7266413.1      2180294.89      7265447.94
      2180297.23      7265094.83
#Sta/Elev= 30
  4108.4 1091.74  4164.9  1090.6  4235.1 1086.18  4321.4 1083.48  4407.7 1084.75
    4555 1081.66  4641.2 1076.76    4697  1075.2  4763.4 1071.11  4771.9 1071.31
  4782.6  1073.1  4793.9 1071.06  4803.8 1072.42  4819.1  1070.2  4876.9 1069.99
  4957.6 1069.68  4974.2 1069.57  4984.8 1070.67  4996.9 1066.91  5001.5 1064.22
  5002.8 1063.72  5010.8 1064.22  5016.8    1069  5022.1 1070.71  5027.5 1071.18
  5052.7 1069.18  5077.9 1071.66    5115 1073.07    5384    1080  5489.2 1084.51
#Mann= 7 ,-1 , 0
  4108.4     .05       0  4782.6     .07       0  4876.9     .05       0
  4957.6     .07       0  5001.5     .07       0  5010.8     .07       0
    5115     .05       0
Bank Sta=5001.5,5010.8
XS Rating Curve= 0 ,0
Exp/Cntr=0.3,0.1

Type RM Length L Ch R = 1 ,549317  ,599,599,599
BEGIN DESCRIPTION:
Denton Creek315
END DESCRIPTION:
XS GIS Cut Line= 3
      2181172.97      7265890.09       2180871.5      7265029.24
      2180497.29      7264638.84
#Sta/Elev= 30
  4184.8 1079.59  4237.4 1079.66  4392.5 1076.79  4534.6 1077.82    4904 1065.48
  4920.2 1066.38  4926.6 1067.58  4940.3 1066.69  4947.8 1067.96  4990.2 1063.17
    4997 1060.86  4997.6 1059.54    4999 1059.04    5007 1059.54    5028 1066.75
  5033.3 1067.63  5043.1 1072.21  5064.4 1075.41  5099.9 1075.65  5154.6 1079.46
  5204.3 1080.87  5260.9 1084.35  5366.9 1082.27  5424.9 1083.99  5494.3 1086.24
  5508.4 1087.56  5529.5 1091.15  5539.5 1091.58  5607.5 1091.81  5637.7 1092.83
#Mann= 7 ,-1 , 0
  4184.8     .05       0  4920.2     .16       0  4997.6     .07       0
    5007     .16       0  5154.6     .05       0  5424.9     .16       0
  5539.5     .05       0
Bank Sta=4997.6,5007
XS Rating Curve= 0 ,0
Exp/Cntr=0.3,0.1

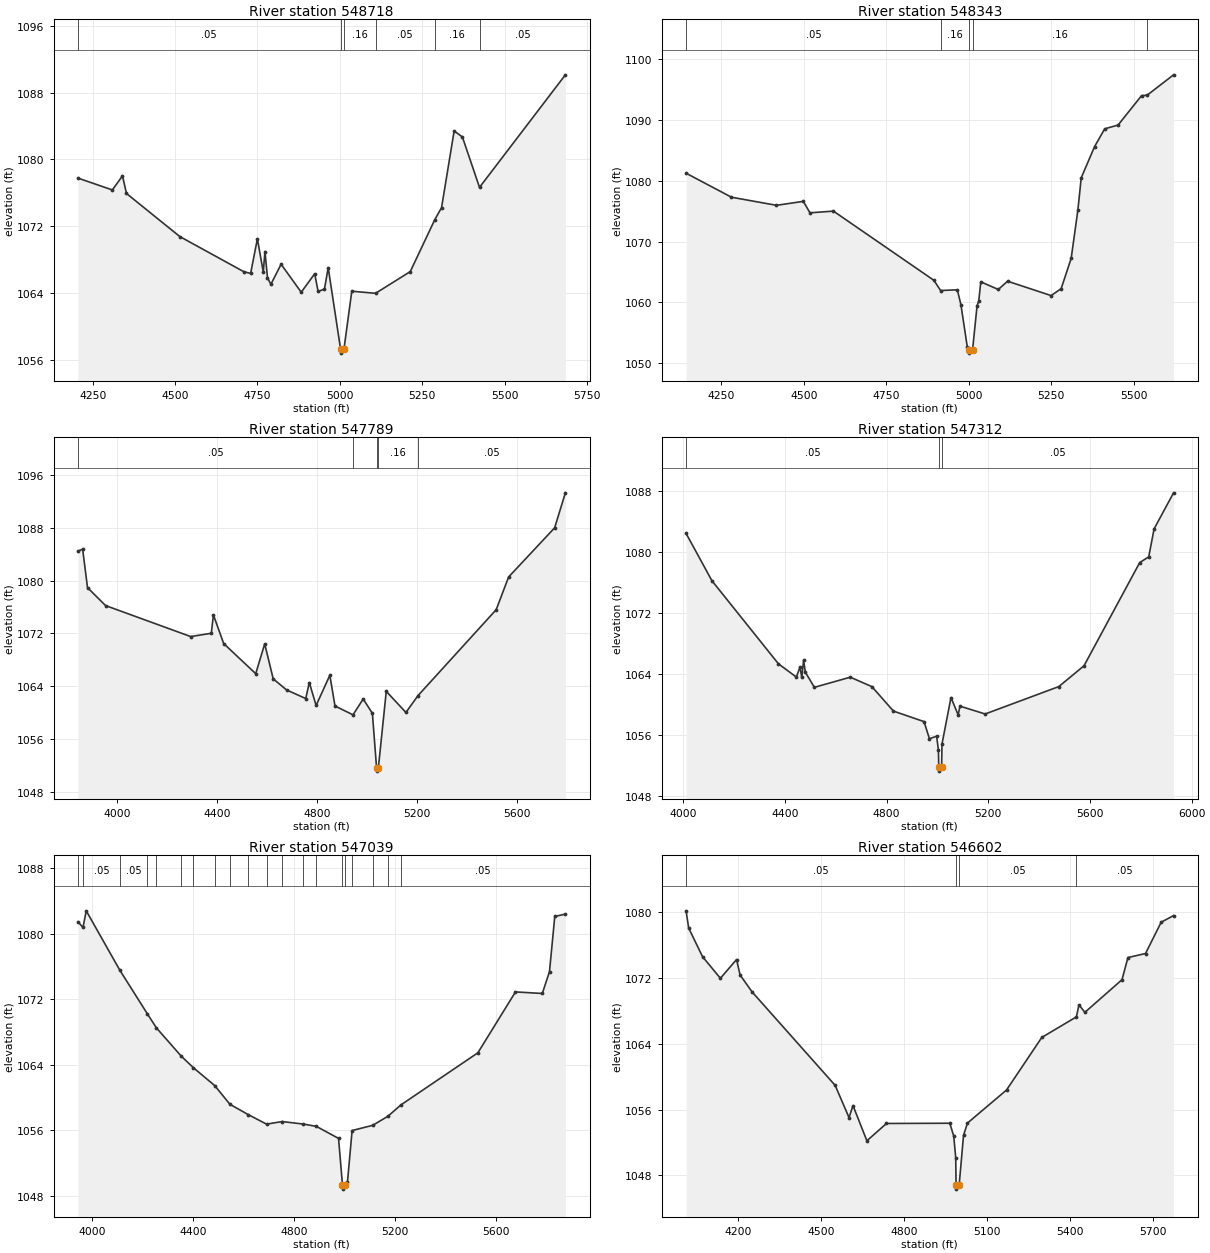
Type RM Length L Ch R = 1 ,548718  ,375,375,375
BEGIN DESCRIPTION:
Denton Creek314
END DESCRIPTION:
XS GIS Cut Line= 3
      2181614.82      7265692.21      2181423.57      7264818.19
      2181236.33      7264263.86
#Sta/Elev= 30
  4204.9 1077.77  4309.5 1076.35  4340.2 1078.04  4352.3 1075.93  4514.3 1070.77
  4708.8 1066.56  4729.2 1066.36  4749.7  1070.5  4767.6 1066.54  4772.7 1068.98
  4780.4 1065.82  4790.7 1065.06  4821.7 1067.46  4882.8 1064.11  4923.7 1066.32
    4934 1064.21  4953.3 1064.48  4964.7 1067.05  5002.2 1057.32  5003.6 1056.82
  5012.6 1057.32  5036.3 1064.23  5108.4 1063.98  5213.8 1066.58  5288.5 1072.81
  5308.8 1074.23    5347 1083.41  5372.1 1082.69    5424 1076.66  5684.7 1090.13
#Mann= 6 ,-1 , 0
  4204.9     .05       0  5002.2    .035       0  5012.6     .16       0
  5108.4     .05       0  5288.5     .16       0    5424     .05       0
Bank Sta=5002.2,5012.6
XS Rating Curve= 0 ,0
Exp/Cntr=0.3,0.1

Type RM Length L Ch R = 1 ,548343  ,554,554,554
BEGIN DESCRIPTION:
Denton Creek313
END DESCRIPTION:
XS GIS Cut Line= 2
      2181968.01      7265749.96       2181711.2      7264294.34
#Sta/Elev= 30
  4142.7 1081.21  4280.3 1077.27  4416.8 1075.94  4498.1 1076.59  4518.4 1074.71
  4589.5 1074.99  4894.1 1063.64  4914.5 1061.96  4965.2 1062.08    4976 1059.65
  4995.6 1052.63  5000.3 1052.19  5001.8 1051.69  5011.3 1052.19  5025.1  1059.5
  5030.1 1060.21  5036.3 1063.39  5089.4 1062.13  5117.5 1063.49  5249.5 1061.13
    5280 1062.27  5310.4 1067.24  5330.7 1075.16  5340.9 1080.46  5381.5 1085.59
    5412 1088.49  5452.6 1089.11  5523.7 1093.93  5540.8 1094.01  5620.8 1097.35
#Mann= 5 ,-1 , 0
  4142.7     .05       0  4914.5     .16       0  5000.3     .07       0
  5011.3     .16       0  5540.8     .05       0
Bank Sta=5000.3,5011.3
XS Rating Curve= 0 ,0
Exp/Cntr=0.3,0.1

Type RM Length L Ch R = 1 ,547789  ,477,477,477
BEGIN DESCRIPTION:
Denton Creek312
END DESCRIPTION:
XS GIS Cut Line= 4
      2182587.63      7265837.25       2182356.1      7264921.38
      2182254.73       7264477.4      2181974.06      7264004.86
#Sta/Elev= 30
  3844.3 1084.45  3863.2 1084.75  3882.7 1078.92  3954.9  1076.2  4295.3  1071.5
  4377.8    1072  4386.3 1074.78  4427.3 1070.44  4555.5 1065.87  4591.4 1070.39
  4625.4 1065.09  4678.6 1063.41  4755.5  1062.1  4769.8 1064.53    4797 1061.05
  4851.9 1065.63  4872.5 1060.97  4944.5 1059.63  4985.3 1062.03  5022.1 1059.86
  5038.8 1051.59    5041 1051.09    5046 1051.59  5077.6 1063.19  5156.2 1059.99
  5204.9 1062.56  5517.3 1075.58    5567 1080.54  5751.1    1088    5794  1093.3
#Mann= 5 ,-1 , 0
  3844.3     .05       0  4944.5     .16       0  5038.8     .07       0
    5046     .16       0  5204.9     .05       0
Bank Sta=5038.8,5046
XS Rating Curve= 0 ,0
Exp/Cntr=0.3,0.1

Type RM Length L Ch R = 1 ,547312  ,273,273,273
BEGIN DESCRIPTION:
Denton Creek310
END DESCRIPTION:
XS GIS Cut Line= 2
      2183437.66      7265274.96      2182078.76      7263922.11
#Sta/Elev= 30
  4011.3 1082.49  4112.8 1076.29  4374.5 1065.38  4445.2 1063.63  4459.3 1064.95
  4466.4 1063.59  4473.5 1065.84  4480.5 1064.27  4515.9 1062.29  4657.3 1063.62
  4742.2 1062.38    4827 1059.17  4947.2 1057.79  4968.5 1055.55  4996.8 1055.87
  5003.8  1054.1  5005.3 1051.79  5006.9 1051.29  5016.4 1051.79    5018 1054.86
  5053.3 1060.95  5081.6 1058.67  5088.7 1059.82  5187.7 1058.79  5477.6 1062.39
  5576.6 1065.12  5795.8 1078.67  5831.1 1079.41  5852.3 1083.09  5928.8 1087.82
#Mann= 3 ,-1 , 0
  4011.3     .05       0  5005.3    .035       0  5016.4     .05       0
Bank Sta=5005.3,5016.4
XS Rating Curve= 0 ,0
Exp/Cntr=0.3,0.1

Type RM Length L Ch R = 1 ,547039  ,437,437,437
BEGIN DESCRIPTION:
Denton Creek311
END DESCRIPTION:
XS GIS Cut Line= 4
      2183652.69       7265193.3      2183048.63      7264510.42
      2182611.04      7264071.12      2182312.68      7263807.05
#Sta/Elev= 30
  3943.3 1081.47  3963.5  1080.8  3976.3 1082.82  4108.9 1075.58  4218.1 1070.24
  4254.3 1068.51  4351.6 1065.09  4399.7 1063.67  4485.1 1061.46  4545.1 1059.18
  4618.6  1057.9  4690.5 1056.75  4752.1 1057.07  4835.8 1056.76  4887.4 1056.48
  4975.3 1055.01  4990.9 1049.31  4992.4 1048.81    5002 1049.31  5010.6 1049.67
    5029 1055.97  5110.8 1056.61  5170.6 1057.71  5222.6 1059.11    5527 1065.47
  5675.9 1072.91  5782.2 1072.72  5810.6  1075.4  5831.5 1082.13  5873.5 1082.42
#Mann= 20 ,-1 , 0
  3943.3     .05       0  3963.5     .05       0  4108.9     .05       0
  4218.1     .05       0  4254.3     .05       0  4351.6     .05       0
  4399.7     .05       0  4485.1     .05       0  4545.1     .05       0
  4618.6     .05       0  4690.5     .05       0  4752.1     .05       0
  4835.8     .05       0  4887.4     .05       0  4990.9    .035       0
    5002     .05       0    5029     .05       0  5110.8     .05       0
  5170.6     .05       0  5222.6     .05       0
Bank Sta=4990.9,5002
XS Rating Curve= 0 ,0
Exp/Cntr=0.3,0.1

Type RM Length L Ch R = 1 ,546602  ,579,579,579
BEGIN DESCRIPTION:
Denton Creek 314.0
END DESCRIPTION:
XS GIS Cut Line= 3
      2183857.05      7264966.05      2183288.32      7264207.26
      2182702.25      7263643.61
#Sta/Elev= 30
  4011.4 1080.17  4020.8 1078.07  4070.8  1074.6  4135.4 1071.97  4193.8 1074.25
  4206.4 1072.38    4250 1070.31  4550.1 1058.95  4600.1 1055.04  4614.6 1056.49
  4664.7 1052.22  4735.5 1054.32  4964.3 1054.35  4978.4 1052.81  4985.7 1050.17
    4987 1046.84  4988.5 1046.34  4998.1 1046.84    5014 1052.89  5028.1 1054.37
  5169.3 1058.39  5296.7 1064.78  5421.8 1067.28    5431 1068.75  5452.3 1067.83
  5586.6  1071.8    5608 1074.49  5671.5 1074.98  5728.1 1078.79  5772.8 1079.59
#Mann= 4 ,-1 , 0
  4011.4     .05       0    4987     .05       0  4998.1     .05       0
  5421.8     .05       0
Bank Sta=4987,4998.1
XS Rating Curve= 0 ,0
Exp/Cntr=0.3,0.1

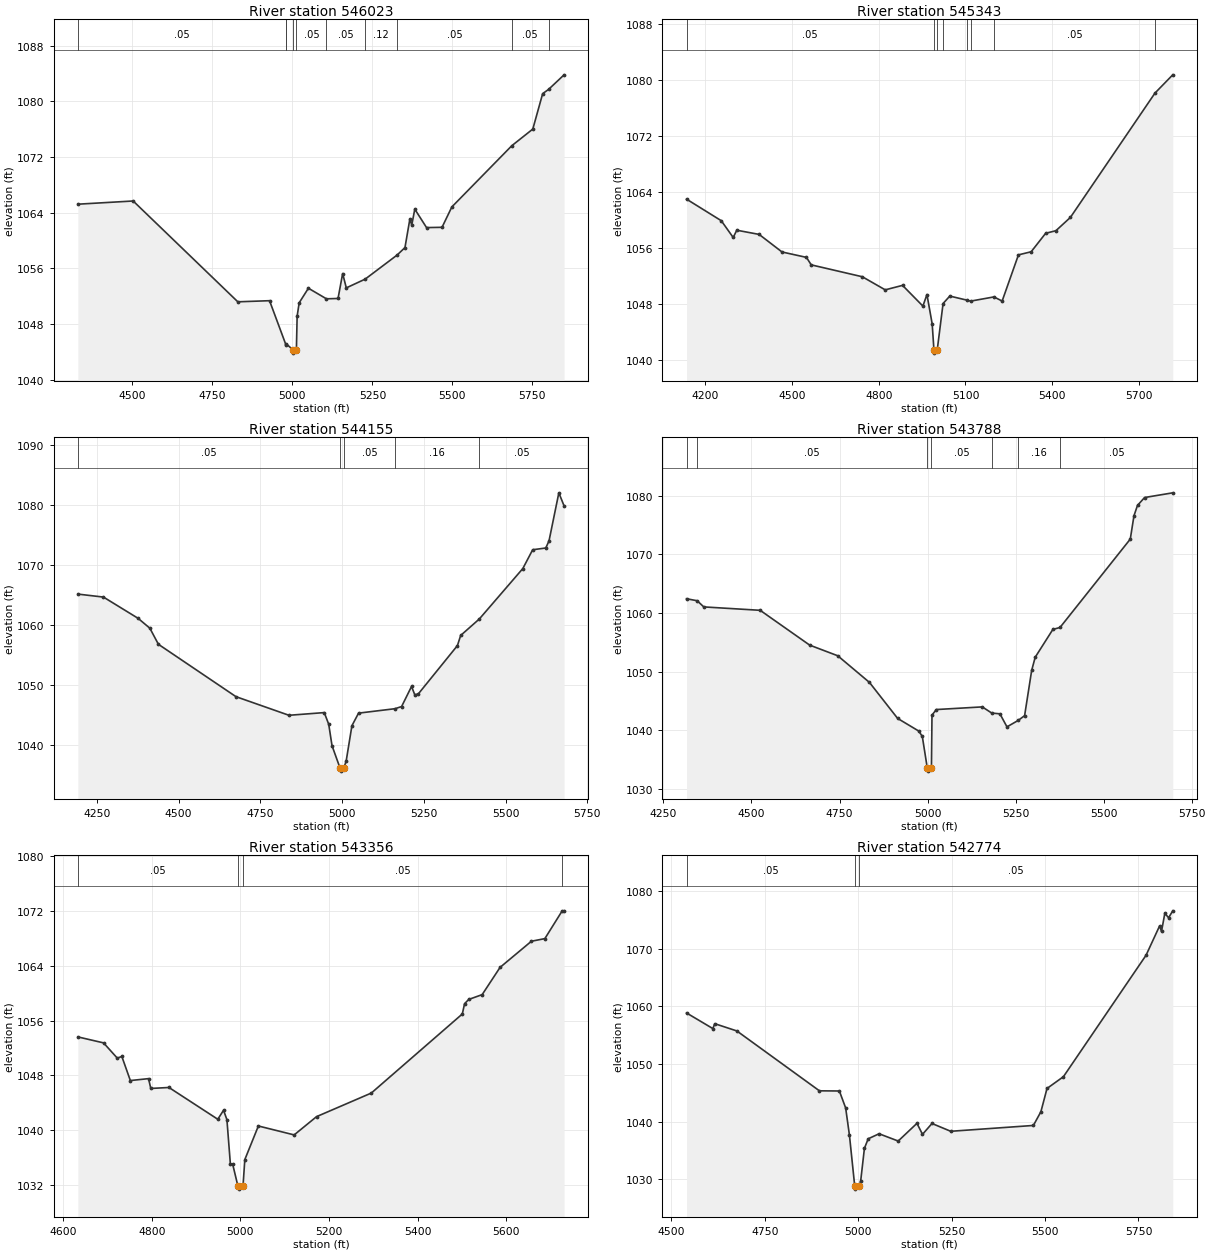
Type RM Length L Ch R = 1 ,546023  ,680,680,680
BEGIN DESCRIPTION:
Denton Creek 313.0
END DESCRIPTION:
XS GIS Cut Line= 3
      2184082.96      7264129.48      2183431.53      7263598.69
      2182854.26      7263241.56
#Sta/Elev= 30
  4329.8 1065.22  4502.6 1065.68  4829.6  1051.2  4928.7 1051.36  4979.9 1045.02
  4981.3 1045.14  5001.4 1044.33  5002.9 1043.83  5012.6 1044.33  5014.9 1049.13
  5021.3 1051.06  5050.1 1053.15  5106.5 1051.63  5142.7 1051.68  5157.1 1055.26
  5168.5  1053.2  5227.5 1054.46  5326.8  1057.9  5351.8 1058.99  5367.1 1063.09
    5373 1062.22  5382.5 1064.51  5419.2 1061.86  5467.6  1061.9  5498.3 1064.83
  5685.6 1073.62  5751.2 1076.01    5782  1081.1  5800.3  1081.7  5848.9  1083.8
#Mann= 10 ,-1 , 0
  4329.8     .05       0  4979.9     .12       0  4981.3     .05       0
  5001.4     .05       0  5012.6     .05       0  5106.5     .05       0
  5227.5     .12       0  5326.8     .05       0  5685.6     .05       0
  5800.3     .05       0
Bank Sta=5001.4,5012.6
XS Rating Curve= 0 ,0
Exp/Cntr=0.3,0.1

Type RM Length L Ch R = 1 ,545343  ,1188,1188,1188
BEGIN DESCRIPTION:
Denton Creek309
END DESCRIPTION:
XS GIS Cut Line= 3
      2184343.66      7264152.02      2184001.81      7263270.05
      2183565.26      7262678.37
#Sta/Elev= 30
  4135.5 1063.04  4255.6 1059.96  4296.9 1057.56  4309.3  1058.6  4386.6    1058
  4465.7 1055.49  4550.1 1054.72  4566.7 1053.65  4743.5 1051.95  4822.5 1050.08
  4882.4 1050.72  4952.8 1047.76  4966.8 1049.41  4984.9 1045.22  4990.9 1041.54
  4992.5 1041.04  5002.5 1041.54  5022.6 1048.13  5045.8 1049.19    5107 1048.59
  5117.8 1048.47  5198.4 1049.07  5226.8 1048.48  5283.2 1055.08  5327.1 1055.52
  5377.2 1058.16  5412.7 1058.53  5462.8 1060.43  5755.4  1078.2  5816.7  1080.8
#Mann= 8 ,-1 , 0
  4135.5     .05       0  4990.9     .05       0  5002.5     .05       0
  5022.6     .12       0    5107     .05       0  5117.8     .05       0
  5198.4     .05       0  5755.4     .16       0
Bank Sta=4990.9,5002.5
XS Rating Curve= 0 ,0
Exp/Cntr=0.3,0.1

Type RM Length L Ch R = 1 ,544155  ,367,367,367
BEGIN DESCRIPTION:
Denton Creek 309.0
END DESCRIPTION:
XS GIS Cut Line= 3
      2184565.04      7263987.33      2184728.48      7262963.26
      2184719.95      7262513.97
#Sta/Elev= 30
  4192.3 1065.16  4270.6 1064.66  4376.5 1061.11  4412.4 1059.46  4438.6 1056.77
  4675.7 1048.02  4837.7 1044.91  4945.6 1045.36  4959.2 1043.41  4969.3 1039.83
  4993.9 1036.08  4995.5 1035.58  5005.6 1036.08  5012.7 1037.31  5030.1 1043.16
  5050.4 1045.27  5161.9 1046.01    5182 1046.37  5212.4 1049.73  5222.5 1048.31
  5233.5 1048.51  5352.6 1056.55  5362.6 1058.25  5419.6    1061  5552.6 1069.43
  5582.7 1072.57  5622.7 1072.86  5632.7 1074.06  5662.7 1082.08  5678.7  1079.9
#Mann= 5 ,-1 , 0
  4192.3     .05       0  4993.9     .05       0  5005.6     .05       0
  5161.9     .16       0  5419.6     .05       0
Bank Sta=4993.9,5005.6
XS Rating Curve= 0 ,0
Exp/Cntr=0.3,0.1

Type RM Length L Ch R = 1 ,543788  ,432,432,432
BEGIN DESCRIPTION:
Denton Creek 308.0
END DESCRIPTION:
XS GIS Cut Line= 3
      2185058.62        7263859.        2185029.        7263160.
       2184986.8      7262480.13
#Sta/Elev= 30
  4315.5 1062.43  4345.8 1062.09  4364.5 1061.04  4524.7 1060.46  4665.3 1054.53
  4744.9 1052.72    4835 1048.18    4915 1042.05  4975.1 1039.89  4985.1 1038.98
  4999.3 1033.57  5000.9 1033.07    5011 1033.57  5012.6 1042.62  5025.1 1043.56
  5155.4 1044.01  5182.3 1042.96  5205.5 1042.83  5225.5 1040.61  5257.5 1041.71
  5275.6 1042.52  5295.7 1050.23  5305.7 1052.47  5355.8  1057.2  5376.2 1057.54
  5575.7 1072.59  5586.2 1076.57  5596.2 1078.33  5616.3 1079.67  5696.3 1080.47
#Mann= 7 ,-1 , 0
  4315.5     .05       0  4345.8     .05       0  4999.3     .05       0
    5011     .05       0  5182.3     .05       0  5257.5     .16       0
  5376.2     .05       0
Bank Sta=4999.3,5011
XS Rating Curve= 0 ,0
Exp/Cntr=0.3,0.1

Type RM Length L Ch R = 1 ,543356  ,582,582,582
BEGIN DESCRIPTION:
Denton Creek 307.0
END DESCRIPTION:
XS GIS Cut Line= 3
      2185344.09      7263646.27        2185429.        7263310.
      2185536.91      7262567.02
#Sta/Elev= 30
  4633.2 1053.62  4691.2 1052.75  4722.2 1050.53  4732.5 1050.77  4751.7 1047.26
  4792.7 1047.54  4797.9 1046.11  4838.9 1046.25  4949.1 1041.62  4962.1 1042.93
  4969.7 1041.56  4977.5  1035.1  4982.6  1035.1  4994.3 1031.94    4996 1031.44
  5006.1 1031.94  5010.1 1035.74  5040.7 1040.64  5121.5 1039.34    5172    1042
  5295.7 1045.44  5501.1 1056.96  5506.2 1058.46  5515.6 1059.08  5545.9 1059.78
  5586.3 1063.75  5657.1 1067.56  5687.4 1067.94  5725.9 1071.92  5730.8 1071.99
#Mann= 4 ,-1 , 0
  4633.2     .05       0  4994.3    .035       0  5006.1     .05       0
  5725.9     .16       0
Bank Sta=4994.3,5006.1
XS Rating Curve= 0 ,0
Exp/Cntr=0.3,0.1

Type RM Length L Ch R = 1 ,542774  ,408,408,408
BEGIN DESCRIPTION:
Denton Creek 306.0
END DESCRIPTION:
XS GIS Cut Line= 3
      2185927.61      7263934.14      2185990.33      7263235.02
      2185930.61      7262638.94
#Sta/Elev= 30
  4540.8 1058.84  4611.3 1056.13  4616.3 1056.98  4675.5 1055.72  4896.4 1045.35
  4949.8 1045.32  4966.6 1042.38  4976.7 1037.67  4990.9 1028.82  4992.5 1028.32
  5002.7 1028.82  5006.8 1029.73  5016.8 1035.39  5026.9 1037.04    5056 1037.91
  5107.2 1036.65  5157.4 1039.72  5172.2 1037.81  5197.6 1039.69  5247.8 1038.34
  5468.9 1039.35    5489 1041.73  5505.4 1045.76  5549.3  1047.8  5770.4 1068.84
  5806.7 1073.93  5811.7 1072.95  5820.6 1076.11  5830.7 1075.33  5841.8 1076.53
#Mann= 3 ,-1 , 0
  4540.8     .05       0  4990.9    .035       0  5002.7     .05       0
Bank Sta=4990.9,5002.7
XS Rating Curve= 0 ,0
Exp/Cntr=0.3,0.1