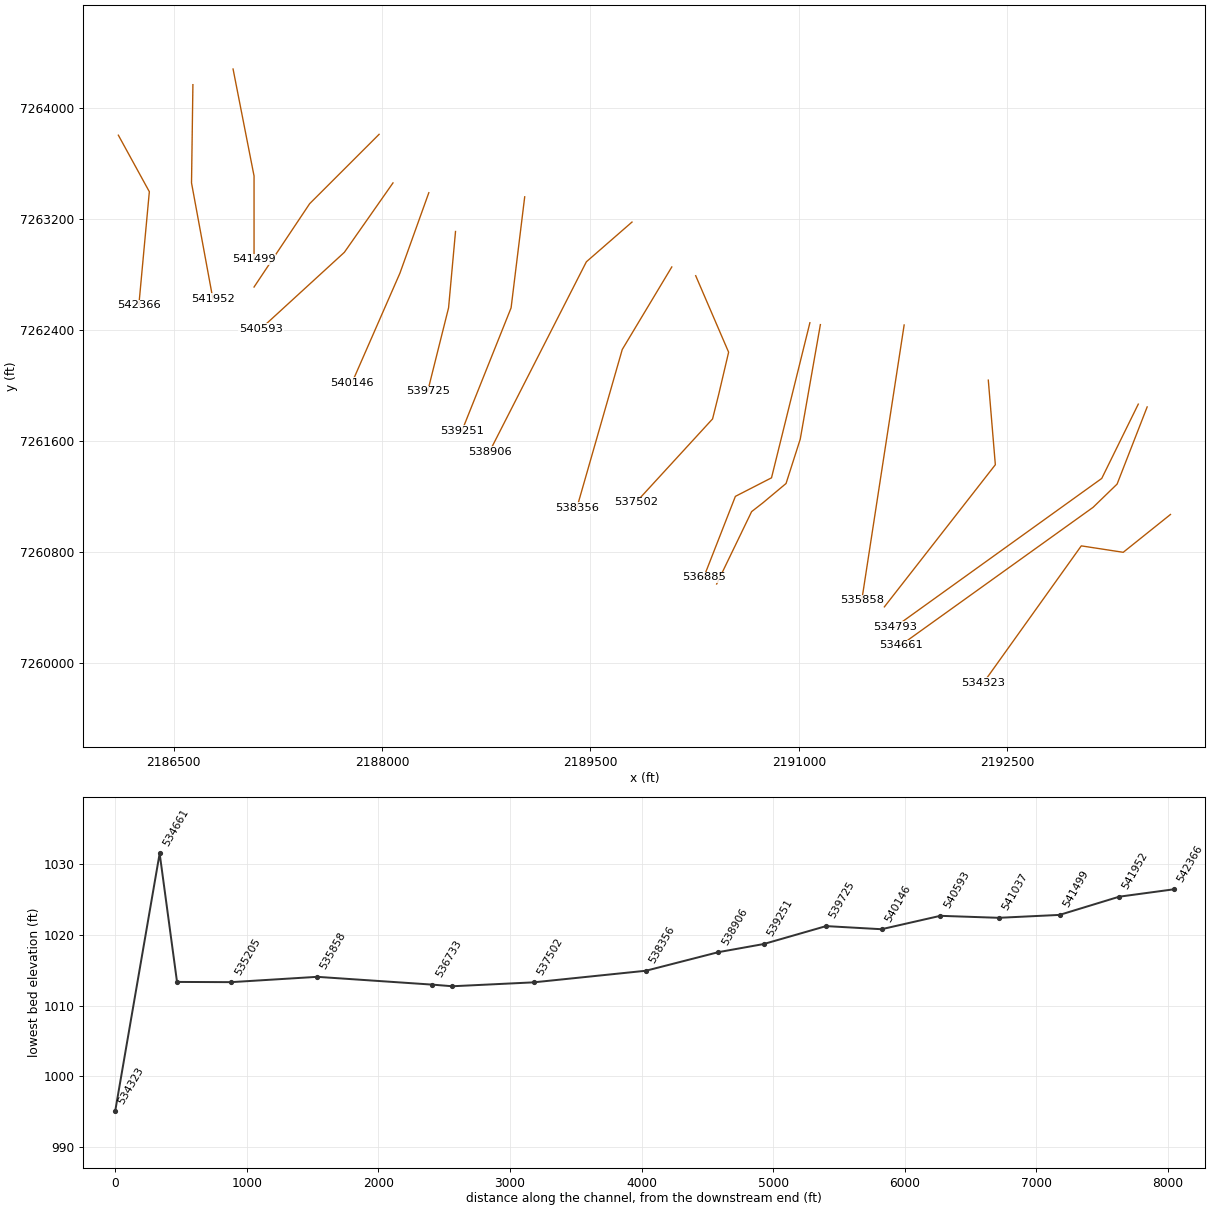
HEC-RAS study Denton Creek.prj: Denton Creek Base Level Engineering

--- Denton Creek.g01 (geometry) --- (continued)

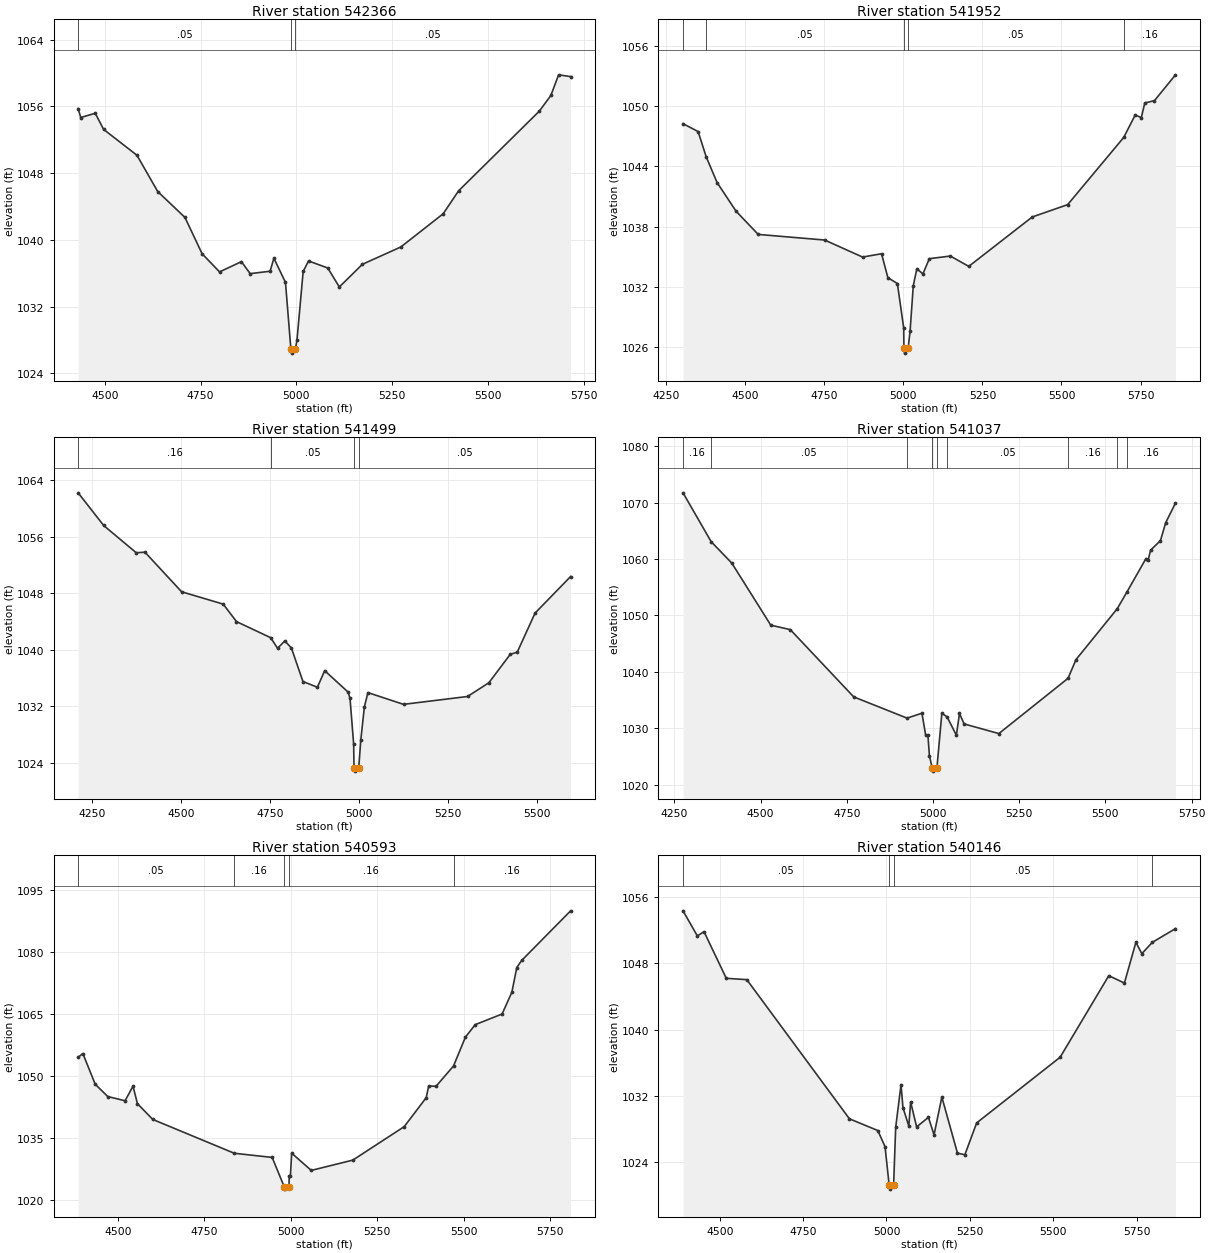
Type RM Length L Ch R = 1 ,542366  ,414,414,414
BEGIN DESCRIPTION:
Denton Creek 305.0
END DESCRIPTION:
XS GIS Cut Line= 3
       2186102.4      7263803.75      2186325.44      7263396.61
      2186249.84      7262578.72
#Sta/Elev= 30
  4430.6 1055.73  4437.3 1054.66  4475.2 1055.17    4497 1053.24  4584.2 1050.13
  4638.2 1045.79  4709.4 1042.68  4754.1 1038.33  4799.7 1036.15  4856.8 1037.38
  4879.6 1035.94  4931.6 1036.23  4941.6 1037.79  4971.8 1034.89  4985.9 1026.91
  4987.6 1026.41  4997.7 1026.91  5001.9 1028.01    5018  1036.2    5032 1037.46
  5082.2 1036.62  5112.4 1034.34  5172.6 1037.06    5273 1039.14  5383.5 1043.12
  5423.7 1045.87  5634.6 1055.43  5664.7 1057.31  5684.8 1059.78  5716.2 1059.57
#Mann= 3 ,-1 , 0
  4430.6     .05       0  4985.9    .035       0  4997.7     .05       0
Bank Sta=4985.9,4997.7
XS Rating Curve= 0 ,0
Exp/Cntr=0.3,0.1

Type RM Length L Ch R = 1 ,541952  ,453,453,453
BEGIN DESCRIPTION:
Denton Creek 304.0
END DESCRIPTION:
XS GIS Cut Line= 3
        2186639.      7264167.62        2186629.        7263460.
      2186782.75      7262624.52
#Sta/Elev= 30
  4303.4 1048.27    4351 1047.49  4376.6 1044.97    4411  1042.4    4471 1039.54
    4541 1037.22  4751.1 1036.66  4871.1 1034.96  4931.1 1035.29  4951.1  1032.9
  4981.1 1032.32  5001.1  1027.9  5001.9 1025.87  5003.8 1025.37  5015.2 1025.87
  5021.3 1027.54  5031.4 1032.09  5042.7 1033.79  5061.9 1033.28  5082.3  1034.8
  5148.8 1035.06  5206.9 1034.03  5407.6 1038.96  5519.5 1040.19  5696.9  1046.9
    5733 1049.13  5752.6 1048.89  5763.5 1050.34    5794 1050.57  5860.6 1053.15
#Mann= 5 ,-1 , 0
  4303.4     .16       0  4376.6     .05       0  5001.9    .035       0
  5015.2     .05       0  5696.9     .16       0
Bank Sta=5001.9,5015.2
XS Rating Curve= 0 ,0
Exp/Cntr=0.3,0.1

Type RM Length L Ch R = 1 ,541499  ,462,462,462
BEGIN DESCRIPTION:
Denton Creek 303.0
END DESCRIPTION:
XS GIS Cut Line= 3
      2186928.06      7264280.37        2187079.        7263510.
        2187079.      7262910.02
#Sta/Elev= 30
  4210.9 1062.18  4282.6 1057.56  4374.3  1053.7  4398.8 1053.78  4501.8 1048.18
  4618.9 1046.43  4656.2 1043.96  4752.4 1041.68  4771.7 1040.18  4792.1 1041.23
  4810.6 1040.22  4843.1 1035.48  4883.8 1034.67  4904.2 1037.02  4970.2 1033.98
  4975.5 1033.08  4985.7 1026.63  4986.7  1023.3  4988.6  1022.8    5000  1023.3
  5005.9 1027.25  5015.9 1031.91  5025.9 1033.91  5125.9 1032.25  5305.9 1033.36
  5365.9  1035.3  5425.9 1039.31  5445.9 1039.65  5495.9 1045.16  5595.9 1050.34
#Mann= 4 ,-1 , 0
  4210.9     .16       0  4752.4     .05       0  4986.7    .035       0
    5000     .05       0
Bank Sta=4986.7,5000
XS Rating Curve= 0 ,0
Exp/Cntr=0.3,0.1

Type RM Length L Ch R = 1 ,541037  ,444,444,444
BEGIN DESCRIPTION:
Denton Creek 302.0
END DESCRIPTION:
XS GIS Cut Line= 3
      2187978.97      7263809.97        2187479.        7263310.
      2187078.99      7262709.98
#Sta/Elev= 30
    4275 1071.74  4356.5 1063.08  4416.4 1059.28  4529.5 1048.27  4586.1 1047.48
  4769.9 1035.56  4924.6 1031.79  4967.9 1032.66  4978.5 1028.81  4985.1 1028.81
  4989.6  1025.1  4997.9 1022.89  4999.8 1022.39  5011.2 1022.89  5025.6 1032.65
  5040.9    1032  5067.7 1028.75  5076.7 1032.61  5090.2 1030.76  5190.9 1029.05
  5391.6 1038.85  5414.7 1042.17  5534.2 1051.19  5561.6 1054.07  5617.5 1060.08
  5623.6 1059.76  5631.1 1061.58  5659.6 1063.26  5674.6 1066.42  5703.2 1069.94
#Mann= 9 ,-1 , 0
    4275     .16       0  4356.5     .05       0  4924.6     .16       0
  4997.9     .07       0  5011.2     .16       0  5040.9     .05       0
  5391.6     .16       0  5534.2     .05       0  5561.6     .16       0
Bank Sta=4997.9,5011.2
XS Rating Curve= 0 ,0
Exp/Cntr=0.3,0.1

Type RM Length L Ch R = 1 ,540593  ,447,447,447
BEGIN DESCRIPTION:
Denton Creek 301.0
END DESCRIPTION:
XS GIS Cut Line= 3
      2188079.02      7263460.04        2187729.        7262960.
      2187129.01      7262410.01
#Sta/Elev= 30
  4384.9 1054.58  4398.5 1055.48  4434.2 1048.05  4470.4 1045.08  4520.5 1044.05
  4543.6 1047.58  4556.3 1043.35  4600.7 1039.53  4836.4 1031.35    4946 1030.34
  4981.2 1023.17  4983.1 1022.67  4994.6 1023.17  4995.3  1025.8  4998.7  1025.8
  5002.4 1031.37  5059.1  1027.2  5179.3 1029.69  5327.9 1037.79  5391.5 1044.79
  5398.8 1047.65  5419.8 1047.54  5470.5 1052.47  5504.9 1059.44  5533.3 1062.47
    5611 1065.04  5639.3 1070.32  5653.5 1076.29  5667.7 1078.01  5809.2 1090.01
#Mann= 5 ,-1 , 0
  4384.9     .05       0  4836.4     .16       0  4981.2    .035       0
  4994.6     .16       0  5470.5     .16       0
Bank Sta=4981.2,4994.6
XS Rating Curve= 0 ,0
Exp/Cntr=0.3,0.1

Type RM Length L Ch R = 1 ,540146  ,421,421,421
BEGIN DESCRIPTION:
Denton Creek 300.0
END DESCRIPTION:
XS GIS Cut Line= 3
      2188336.93      7263389.58        2188129.        7262810.
      2187784.05      7262021.28
#Sta/Elev= 30
  4390.1  1054.3  4432.9 1051.28    4453 1051.79  4519.8 1046.17  4581.3 1046.01
    4889 1029.25    4974 1027.84  4995.8  1025.9  5008.1 1021.28    5010 1020.78
  5021.5 1021.28  5027.7 1028.21  5043.7 1033.37  5049.5  1030.6  5067.1 1028.38
  5072.5 1031.29  5090.5 1028.27  5125.9 1029.43  5142.7 1027.32  5166.1 1031.87
  5212.9 1025.12  5235.1 1024.92  5270.6 1028.76  5520.9 1036.67  5666.7 1046.49
  5713.5  1045.6    5748 1050.51  5765.7 1049.14  5797.1  1050.5  5866.7 1052.16
#Mann= 4 ,-1 , 0
  4390.1     .05       0  5008.1    .035       0  5021.5     .05       0
  5797.1     .16       0
Bank Sta=5008.1,5021.5
XS Rating Curve= 0 ,0
Exp/Cntr=0.3,0.1

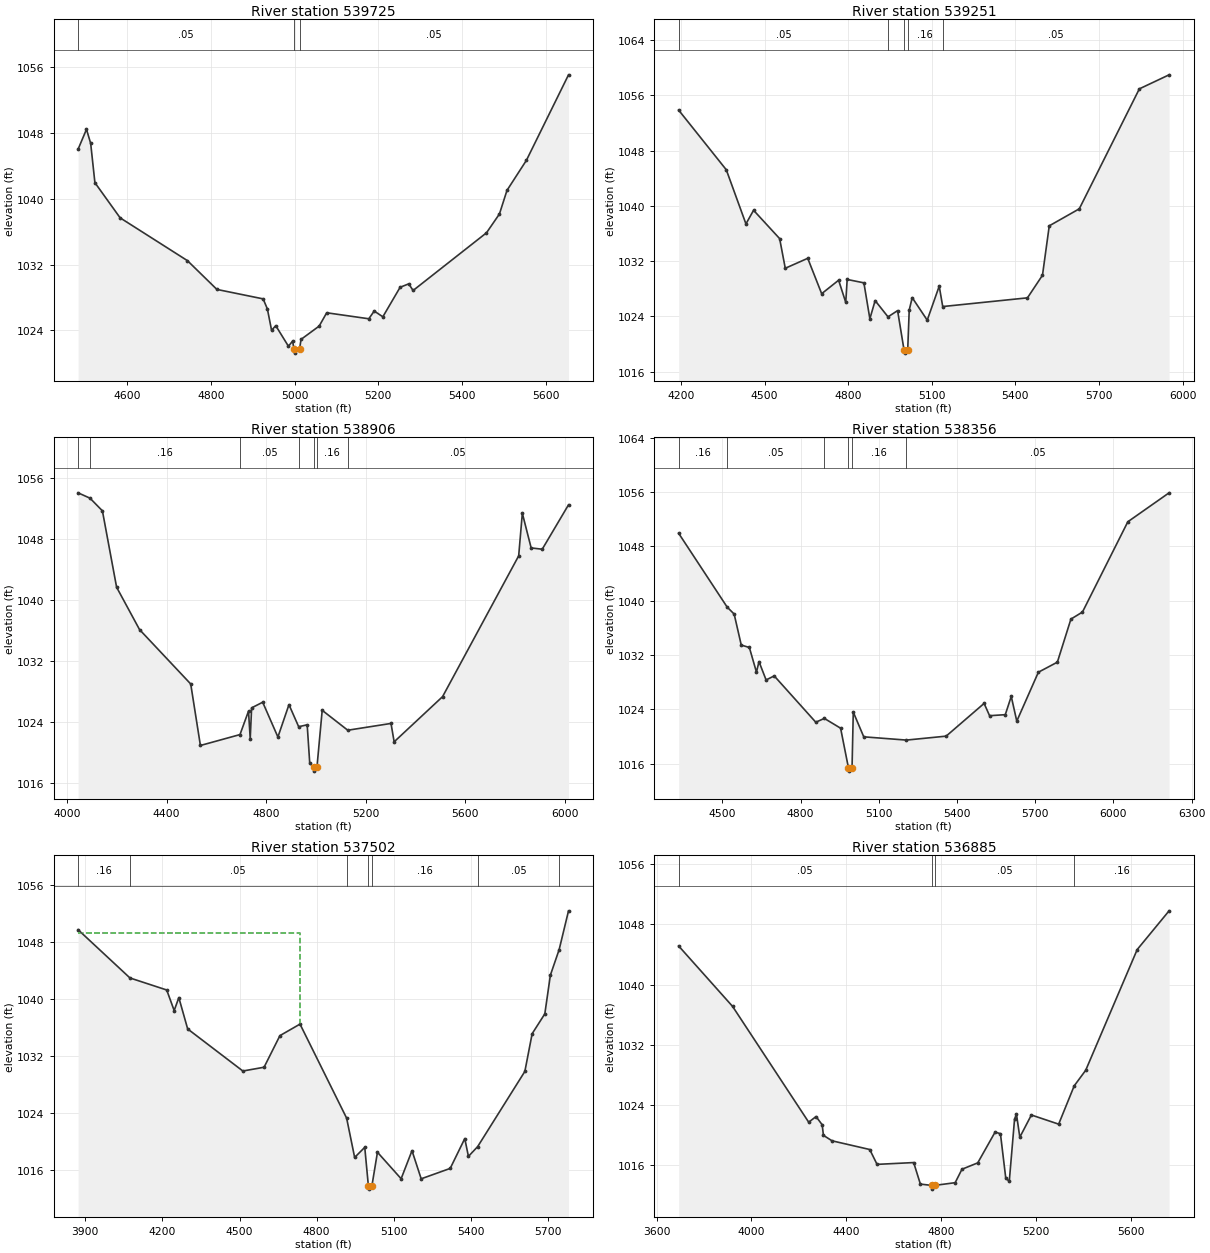
Type RM Length L Ch R = 1 ,539725  ,474,474,474
BEGIN DESCRIPTION:
Denton Creek 299.0
END DESCRIPTION:
XS GIS Cut Line= 3
        2188529.        7263110.        2188479.        7262560.
      2188329.01      7261960.03
#Sta/Elev= 30
  4483.3 1046.02  4503.4 1048.45  4513.4 1046.74  4523.5 1041.96  4583.7 1037.68
  4744.4 1032.47  4814.7 1028.97  4925.1 1027.82  4935.2 1026.59  4945.2    1024
  4955.2 1024.56  4985.4 1022.06  4995.4 1022.68  4998.7 1021.72  5000.6 1021.22
  5012.1 1021.72  5015.5 1022.89  5058.8 1024.51  5076.8 1026.13  5177.3  1025.4
  5190.2 1026.34  5210.8 1025.64    5252 1029.23  5272.6 1029.65    5283 1028.84
  5458.2 1035.86  5489.1 1038.15  5507.1 1041.02  5553.5 1044.68    5654 1055.08
#Mann= 3 ,-1 , 0
  4483.3     .05       0  4998.7    .035       0  5012.1     .05       0
Bank Sta=4998.7,5012.1
XS Rating Curve= 0 ,0
Exp/Cntr=0.3,0.1

Type RM Length L Ch R = 1 ,539251  ,345,345,345
BEGIN DESCRIPTION:
Denton Creek 298.0
END DESCRIPTION:
XS GIS Cut Line= 3
      2189026.96      7263359.75        2188929.        7262560.
      2188575.12       7261674.2
#Sta/Elev= 30
  4191.9 1053.86  4362.9 1045.22  4433.4 1037.39  4460.8 1039.36  4554.3 1035.26
  4574.5 1030.97  4655.1 1032.41  4705.1 1027.29  4765.9 1029.24  4791.5 1026.03
  4796.6 1029.35  4856.6 1028.86    4878 1023.66  4896.9 1026.29  4943.1 1023.94
  4977.5 1024.84  5000.4 1019.19  5002.3 1018.69  5013.8 1019.19  5019.2 1024.92
  5029.9 1026.72  5083.8 1023.46  5126.8 1028.38  5139.4 1025.43  5443.4 1026.69
  5497.3 1029.96  5521.6 1037.11  5629.3 1039.57  5844.8 1056.93  5951.5 1058.96
#Mann= 5 ,-1 , 0
  4191.9     .05       0  4943.1     .16       0  5000.4     .07       0
  5013.8     .16       0  5139.4     .05       0
Bank Sta=5000.4,5013.8
XS Rating Curve= 0 ,0
Exp/Cntr=0.3,0.1

Type RM Length L Ch R = 1 ,538906  ,550,550,550
BEGIN DESCRIPTION:
Denton Creek 297.0
END DESCRIPTION:
XS GIS Cut Line= 3
      2189799.17      7263178.02      2189470.73      7262891.77
      2188774.11       7261524.7
#Sta/Elev= 30
  4044.6 1054.01  4092.5 1053.31  4142.4 1051.65  4199.4 1041.64  4291.5 1036.09
  4497.1 1028.96    4536  1020.9    4695 1022.33  4729.2  1025.4  4736.1 1021.79
  4741.7 1025.83  4786.2 1026.57  4847.3 1022.01  4891.7 1026.25  4930.7 1023.36
  4964.9 1023.61  4975.1 1018.61  4990.6 1018.04  4992.5 1017.54  5004.1 1018.04
  5025.2 1025.51  5127.9  1022.9  5301.6 1023.79  5314.2 1021.38  5508.7  1027.3
  5814.4 1045.75  5829.1 1051.33  5864.5 1046.79    5909 1046.62  6014.6 1052.44
#Mann= 7 ,-1 , 0
  4044.6     .05       0  4092.5     .16       0    4695     .05       0
  4930.7     .16       0  4990.6     .07       0  5004.1     .16       0
  5127.9     .05       0
Bank Sta=4990.6,5004.1
XS Rating Curve= 0 ,0
Exp/Cntr=0.3,0.1

Type RM Length L Ch R = 1 ,538356  ,854,854,854
BEGIN DESCRIPTION:
Denton Creek 296.0
END DESCRIPTION:
XS GIS Cut Line= 3
      2190085.45      7262854.46        2189729.        7262260.
      2189401.82      7261118.09
#Sta/Elev= 30
  4332.4 1049.94  4518.3 1039.08  4545.4 1038.04  4572.6 1033.48  4603.7 1033.12
  4630.9 1029.49  4640.6 1031.04  4667.9 1028.34    4699 1028.94  4858.4 1022.12
  4891.3 1022.68  4953.6 1021.24  4983.6 1015.42  4985.6 1014.92  4997.5 1015.42
  5002.2 1023.61  5042.4 1019.97  5205.9 1019.49  5358.4 1020.07    5504 1024.89
  5524.9 1023.08  5585.2 1023.23  5608.1 1025.92  5629.3 1022.28  5712.1 1029.48
  5784.9 1030.96  5836.9  1037.3  5881.2 1038.34  6055.2 1051.63  6213.4 1055.89
#Mann= 6 ,-1 , 0
  4332.4     .16       0  4518.3     .05       0  4891.3     .16       0
  4983.6     .07       0  4997.5     .16       0  5205.9     .05       0
Bank Sta=4983.6,4997.5
XS Rating Curve= 0 ,0
Exp/Cntr=0.3,0.1

Type RM Length L Ch R = 1 ,537502  ,617,617,617
BEGIN DESCRIPTION:
Denton Creek 294.0
END DESCRIPTION:
XS GIS Cut Line= 5
       2190257.6      7262791.56      2190494.55      7262240.56
      2190422.54      7261934.14        2190379.        7261760.
        2189829.        7261160.
#Sta/Elev= 30
  3871.8 1049.72  4073.7 1042.94  4216.7 1041.25  4245.7 1038.36  4263.8 1040.18
  4298.2 1035.78  4512.9 1029.87  4595.4  1030.4  4657.1 1034.84  4735.2 1036.46
  4916.6 1023.25  4947.8 1017.73  4987.1 1019.15  5001.1 1013.78  5003.1 1013.28
  5015.1 1013.78  5036.5 1018.46  5128.6 1014.74  5170.9 1018.68  5206.6 1014.73
  5319.5 1016.19  5376.2 1020.38  5390.4 1017.88  5426.3 1019.25  5609.9 1029.81
  5638.3 1035.11  5687.6  1037.9  5709.2 1043.33  5743.4 1046.93  5779.8 1052.37
#Mann= 7 ,-1 , 0
  3871.8     .16       0  4073.7     .05       0  4916.6     .16       0
  5001.1     .16       0  5015.1     .16       0  5426.3     .05       0
  5743.4     .16       0
#XS Ineff= 2 , 0
       0  4733.7 1049.21               0
Permanent Ineff=
       F       F
Bank Sta=5001.1,5015.1
XS Rating Curve= 0 ,0
Exp/Cntr=0.3,0.1

Type RM Length L Ch R = 1 ,536885  ,152,152,152
BEGIN DESCRIPTION:
Denton Creek308
END DESCRIPTION:
XS GIS Cut Line= 4
      2191079.51      7262452.72      2190803.22       7261335.6
      2190543.28      7261202.19      2190315.43      7260618.76
#Sta/Elev= 30
  3692.8 1045.14  3920.5 1037.08  4241.6 1021.65  4272.5  1022.4  4298.5 1021.31
  4303.7  1019.9    4340 1019.17  4499.1 1018.01    4530 1016.03  4684.5 1016.27
  4712.8  1013.4  4759.9 1013.23  4761.9 1012.73  4773.9 1013.23  4859.6 1013.59
  4888.2 1015.38  4954.8 1016.23  5028.2 1020.34  5050.6 1020.11  5073.1 1014.18
  5087.9 1013.78  5110.1 1022.05  5118.1 1022.74  5132.3 1019.65  5181.1 1022.61
  5296.2 1021.39  5361.9  1026.5  5410.3 1028.57  5627.6 1044.66  5762.1 1049.82
#Mann= 4 ,-1 , 0
  3692.8     .05       0  4759.9    .035       0  4773.9     .05       0
  5361.9     .16       0
Bank Sta=4759.9,4773.9
XS Rating Curve= 0 ,0
Exp/Cntr=0.3,0.1

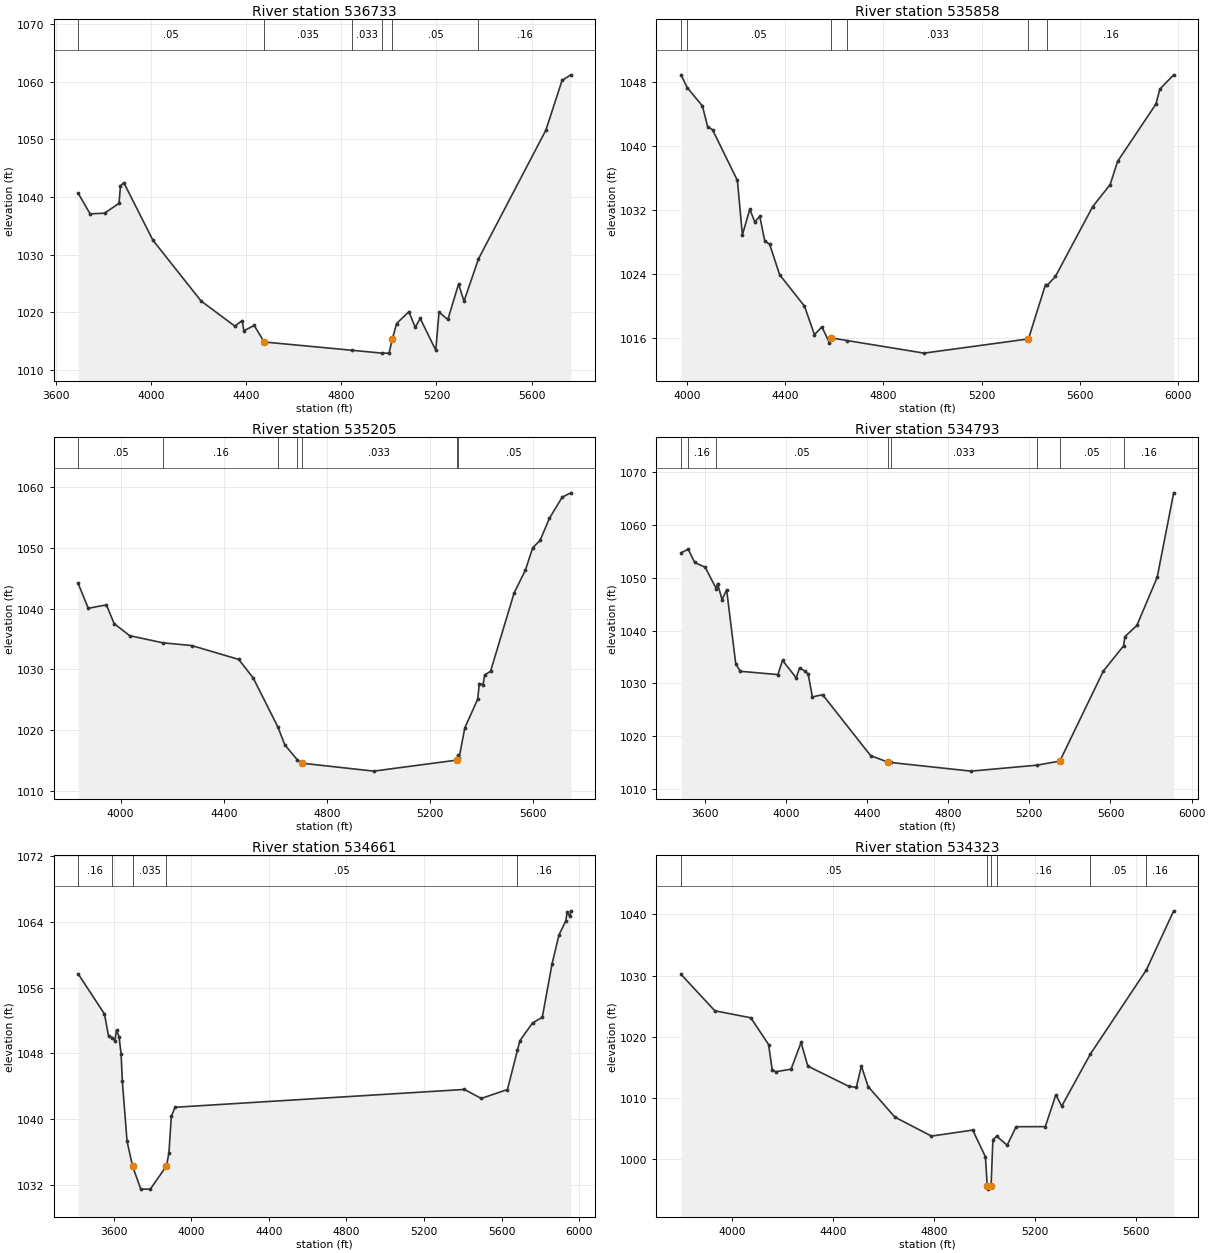
Type RM Length L Ch R = 1 ,536733  ,875,875,875
BEGIN DESCRIPTION:
Denton Creek307
END DESCRIPTION:
XS GIS Cut Line= 6
      2191154.95      7262439.34      2191009.98       7261614.1
      2190907.85      7261294.76       2190740.7      7261155.07
      2190659.98      7261092.17      2190408.54      7260570.97
#Sta/Elev= 30
  3693.1 1040.67  3743.2 1037.09  3804.1 1037.21    3865 1038.91    3871 1041.95
  3885.3 1042.48  4007.2 1032.54  4210.2 1021.99  4352.4 1017.63  4382.8 1018.61
    4390 1016.83  4433.6 1017.76  4475.5 1014.89  4843.6 1013.46  4970.8 1012.96
  5000.6 1012.96  5014.9 1015.44  5032.5 1018.09  5084.1 1020.13    5111 1017.43
  5131.8 1018.98  5197.3 1013.46    5211 1020.04  5248.1 1018.79  5293.3 1024.95
  5315.9 1021.95    5377 1029.29  5660.6 1051.61  5728.4  1060.2  5765.1 1061.18
#Mann= 6 ,-1 , 0
  3693.1     .05       0  4475.5    .035       0  4843.6    .033       0
  4970.8    .035       0  5014.9     .05       0    5377     .16       0
Bank Sta=4475.5,5014.9
XS Rating Curve= 0 ,0
Exp/Cntr=0.3,0.1

Type RM Length L Ch R = 1 ,535858  ,653,653,653
BEGIN DESCRIPTION:
Denton Creek306
END DESCRIPTION:
XS GIS Cut Line= 2
      2191757.85      7262436.66      2191452.96      7260454.27
#Sta/Elev= 30
  3976.6  1048.9  4001.6  1047.3  4063.5    1045  4084.5 1042.43  4104.8 1042.02
  4205.9 1035.68  4226.2 1028.87  4256.5 1032.08  4276.8 1030.47    4297 1031.19
  4317.2 1028.12  4337.5 1027.67  4377.9 1023.87  4479.1 1019.94  4519.6 1016.37
  4549.9 1017.35  4580.3 1015.39  4587.3 1015.97    4654 1015.63  4965.6 1014.06
    5391 1015.84  5460.5 1022.65  5467.2 1022.54    5501 1023.67  5652.7 1032.41
  5723.6 1035.16  5753.9 1038.06  5910.2 1045.25  5925.9 1047.11  5982.3  1048.9
#Mann= 6 ,-1 , 0
  3976.6     .16       0  4001.6     .05       0  4587.3    .033       0
    4654    .033       0    5391     .05       0  5467.2     .16       0
Bank Sta=4587.3,5391
XS Rating Curve= 0 ,0
Exp/Cntr=0.3,0.1

Type RM Length L Ch R = 1 ,535205  ,412,412,412
BEGIN DESCRIPTION:
Denton Creek305
END DESCRIPTION:
XS GIS Cut Line= 3
       2192363.5      7262039.17      2192414.15      7261429.95
      2191615.48      7260406.15
#Sta/Elev= 30
  3835.5 1044.11  3874.8 1040.04    3945  1040.6  3975.2 1037.51  4035.4 1035.54
    4164 1034.37  4276.2 1033.92  4458.2 1031.64  4514.3 1028.59  4610.2 1020.52
  4636.4 1017.64  4685.3 1015.16  4701.5 1014.62  4981.4 1013.31  5305.2 1015.13
  5306.6 1015.91  5312.1 1015.43  5334.6 1020.42  5384.5 1025.13  5390.8 1027.69
  5405.3 1027.51  5411.6 1029.11  5434.2 1029.68  5525.6 1042.55    5569 1046.26
    5598 1049.99  5626.3 1051.17  5662.2 1054.78  5711.9 1058.27  5745.3 1058.99
#Mann= 7 ,-1 , 0
  3835.5     .05       0    4164     .16       0  4610.2     .05       0
  4685.3     .05       0  4701.5    .033       0  5305.2     .05       0
  5306.6     .05       0
Bank Sta=4701.5,5305.2
XS Rating Curve= 0 ,0
Exp/Cntr=0.3,0.1

Type RM Length L Ch R = 1 ,534793  ,132,132,132
BEGIN DESCRIPTION:
Denton Creek304
END DESCRIPTION:
XS GIS Cut Line= 3
      2193442.95       7261866.6      2193180.05      7261331.42
      2191692.91      7260261.99
#Sta/Elev= 30
  3483.4 1054.76  3518.6 1055.43  3550.5 1052.92  3602.2 1052.01  3657.3 1047.91
    3663 1048.92  3685.4 1045.86  3707.9 1047.73  3752.9 1033.67  3775.4 1032.28
  3960.8 1031.65  3983.3 1034.36  4050.7 1031.03  4067.6 1032.93  4095.1 1032.28
  4109.8 1031.76  4130.7 1027.41    4181 1027.84  4417.9 1016.27  4503.6 1015.04
    4517 1014.98  4912.2 1013.34  5237.3 1014.47  5350.4 1015.25  5564.4  1032.3
  5664.3  1037.1  5671.2 1038.86  5730.1 1040.99    5830 1050.09  5911.4 1066.13
#Mann= 8 ,-1 , 0
  3483.4     .05       0  3518.6     .16       0  3657.3     .05       0
  4503.6    .033       0    4517    .033       0  5237.3    .035       0
  5350.4     .05       0  5664.3     .16       0
Bank Sta=4503.6,5350.4
XS Rating Curve= 0 ,0
Exp/Cntr=0.3,0.1

Type RM Length L Ch R = 1 ,534661  ,338,338,338
BEGIN DESCRIPTION:
Denton Creek303
END DESCRIPTION:
XS GIS Cut Line= 4
      2193506.88      7261846.31      2193290.48      7261290.64
      2193117.75      7261123.19      2191733.64      7260130.13
#Sta/Elev= 30
  3416.6 1057.67  3552.2 1052.79  3573.6 1050.06  3593.2 1049.92  3605.8 1049.54
  3614.3 1050.83  3627.3 1050.04    3638 1047.93  3644.2 1044.69  3668.7  1037.3
  3696.9 1034.29  3739.7 1031.48  3788.9 1031.48  3872.1 1034.31  3884.8 1035.92
    3897 1040.32  3916.1 1041.44  5408.9 1043.61    5495 1042.51  5630.4  1043.6
  5682.2 1048.39  5694.7 1049.54  5759.8  1051.7  5810.1 1052.38  5860.5 1058.88
  5896.1  1062.4  5931.7 1064.13  5938.1 1065.14  5952.6 1064.65    5957 1065.34
#Mann= 5 ,-1 , 0
  3416.6     .16       0  3593.2     .05       0  3696.9    .035       0
  3872.1     .05       0  5682.2     .16       0
Bank Sta=3696.9,3872.1
XS Rating Curve= 0 ,0
Exp/Cntr=0.3,0.1

Type RM Length L Ch R = 1 ,534323  ,447,447,447
BEGIN DESCRIPTION:
Denton Creek 287.0
END DESCRIPTION:
XS GIS Cut Line= 4
      2193674.66      7261071.71      2193334.52      7260799.16
      2193032.74      7260845.53      2192328.99      7259859.98
#Sta/Elev= 30
    3797 1030.19  3930.8 1024.24  4073.3  1023.1  4143.7 1018.73  4158.1  1014.6
  4172.5 1014.28  4232.9  1014.7  4272.6 1019.06  4299.2  1015.2    4461 1011.91
  4491.4 1011.71  4511.6 1015.22  4538.2 1011.86  4644.3 1006.86  4789.4 1003.76
  4952.8 1004.74  5003.2 1000.37  5010.3  995.59  5012.3  995.09  5025.6  995.59
  5032.7 1003.16  5047.8 1003.74  5089.2 1002.27  5124.9 1005.29  5240.4 1005.31
  5282.2 1010.49  5305.5 1008.66  5418.8 1017.15  5640.8 1030.91  5749.2 1040.58
#Mann= 6 ,-1 , 0
    3797     .05       0  5010.3    .035       0  5025.6     .05       0
  5047.8     .16       0  5418.8     .05       0  5640.8     .16       0
Bank Sta=5010.3,5025.6
XS Rating Curve= 0 ,0
Exp/Cntr=0.3,0.1