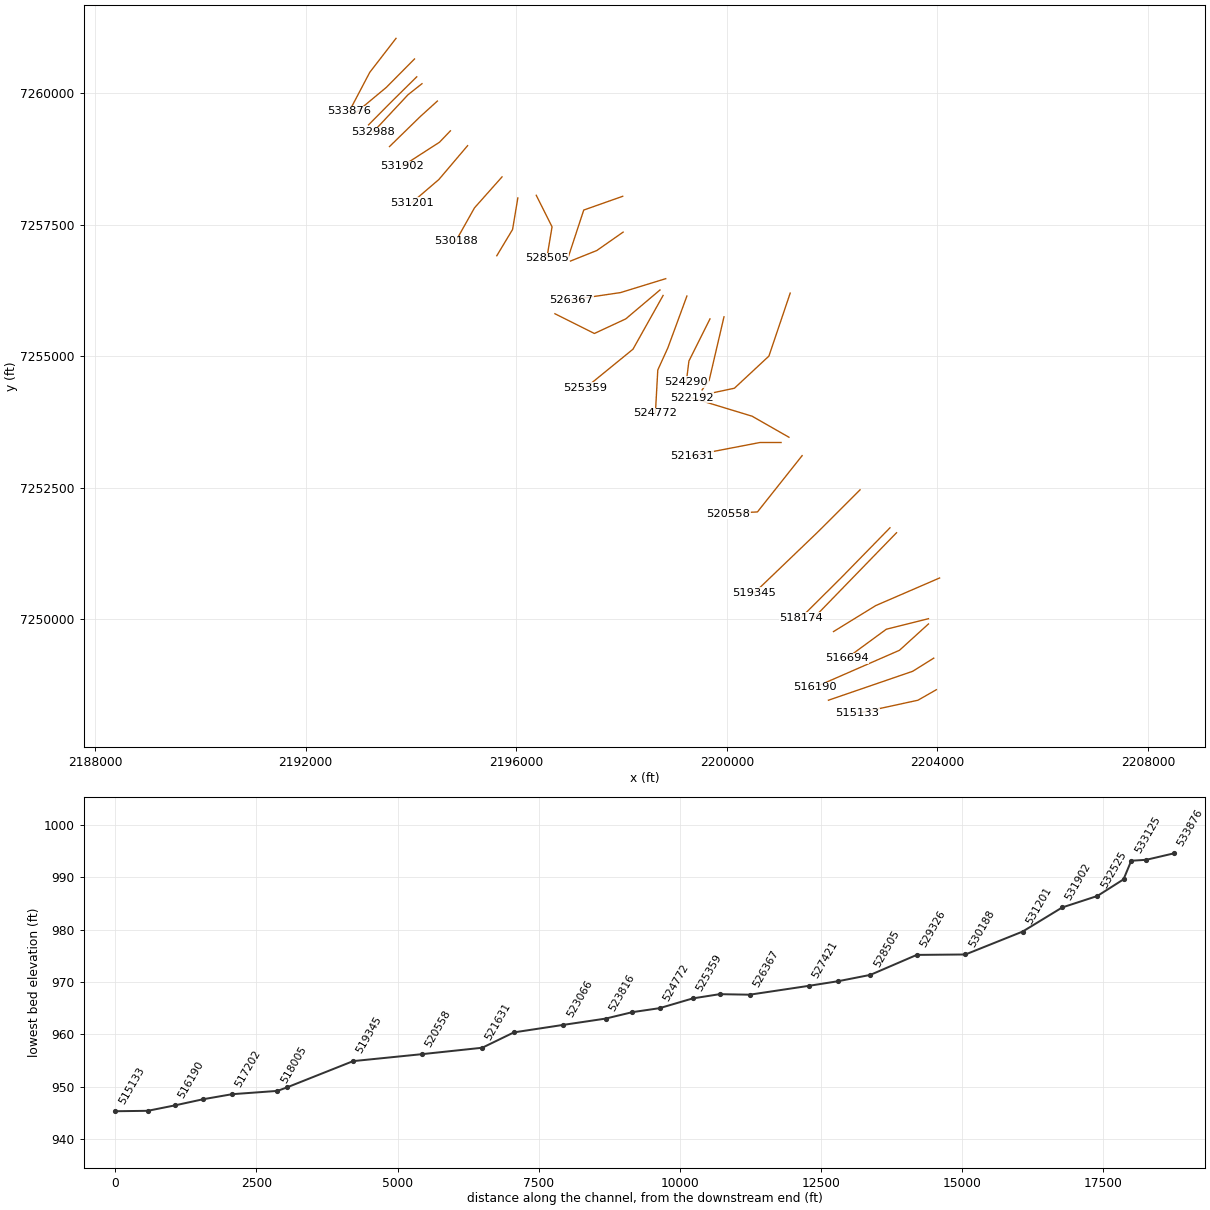
HEC-RAS study Denton Creek.prj: Denton Creek Base Level Engineering

--- Denton Creek.g01 (geometry) --- (continued)

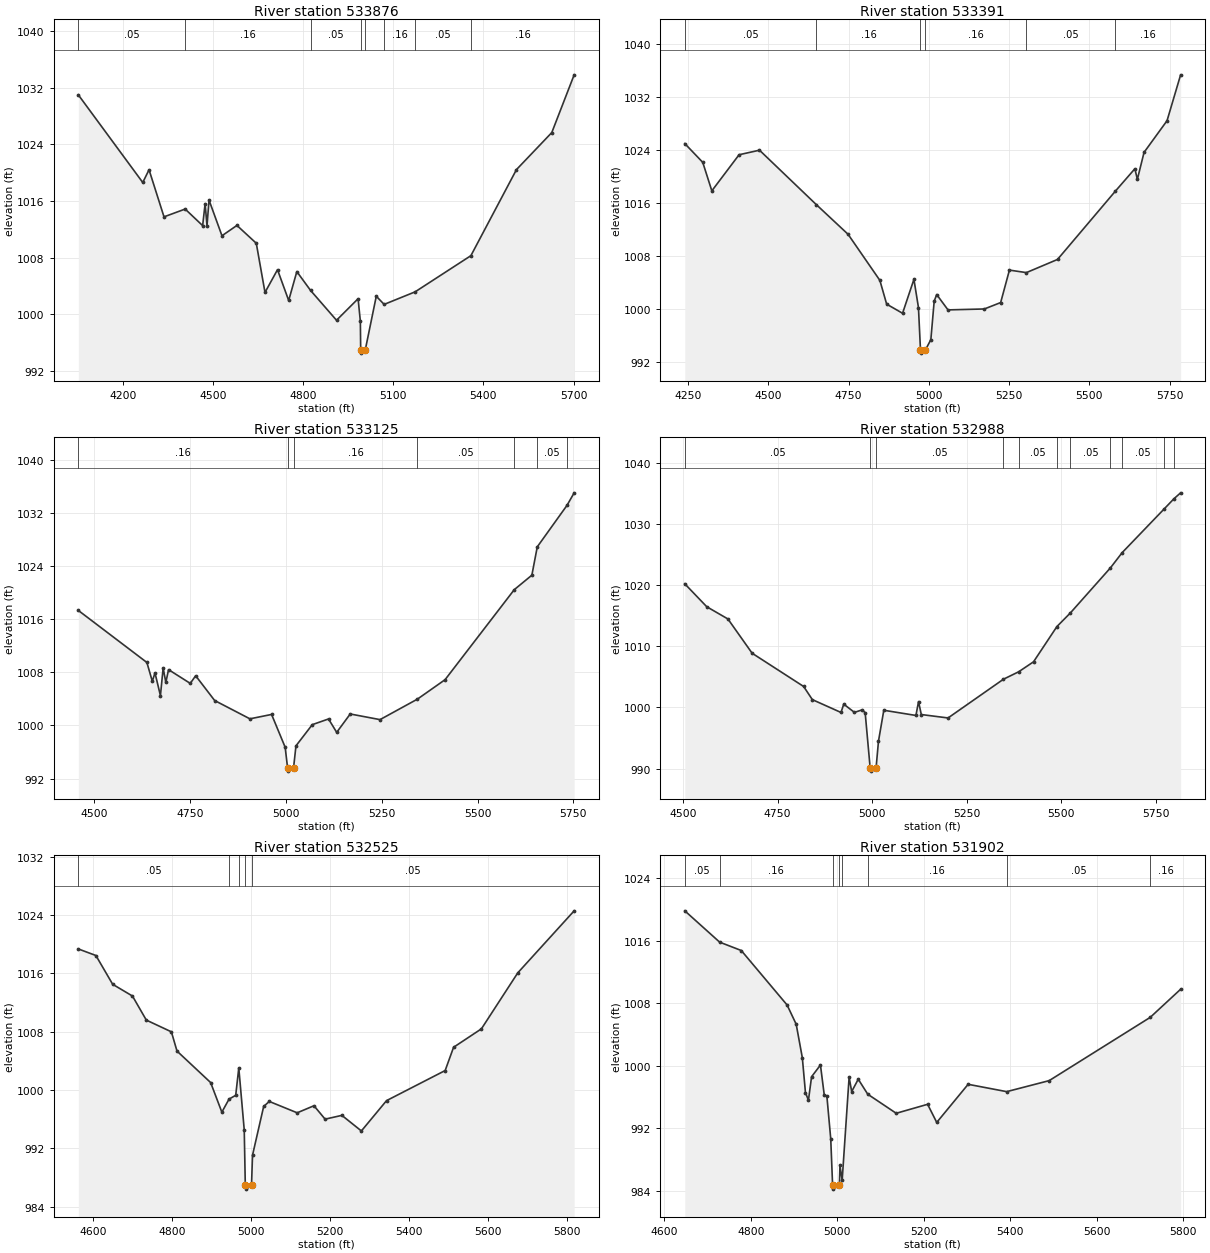
Type RM Length L Ch R = 1 ,533876  ,485,485,485
BEGIN DESCRIPTION:
Denton Creek 286.0
END DESCRIPTION:
XS GIS Cut Line= 3
       2193715.4      7261044.27       2193215.6      7260396.59
      2192828.99      7259659.98
#Sta/Elev= 30
  4052.1 1030.98  4266.5 1018.61  4287.4 1020.41  4337.2 1013.76  4407.6 1014.86
  4465.8 1012.52    4474 1015.62  4480.3 1012.51    4487 1016.13  4530.1 1011.09
  4579.9 1012.55  4644.3 1010.03  4673.3 1003.09  4714.9  1006.3  4752.1 1001.95
  4779.2 1006.03  4824.8 1003.38  4911.3  999.16  4983.1  1002.2  4990.6  999.03
  4991.7  995.02  4993.7  994.52  5007.2  995.02  5043.6 1002.55  5069.8  1001.4
  5172.8 1003.17  5358.5 1008.28  5510.1 1020.43  5627.7 1025.66  5702.1 1033.81
#Mann= 8 ,-1 , 0
  4052.1     .05       0  4407.6     .16       0  4824.8     .05       0
  4991.7    .035       0  5007.2     .05       0  5069.8     .16       0
  5172.8     .05       0  5358.5     .16       0
Bank Sta=4991.7,5007.2
XS Rating Curve= 0 ,0
Exp/Cntr=0.3,0.1

Type RM Length L Ch R = 1 ,533391  ,266,266,266
BEGIN DESCRIPTION:
Denton Creek 285.0
END DESCRIPTION:
XS GIS Cut Line= 3
      2194066.03      7260651.95        2193529.        7260110.
      2192928.99      7259609.99
#Sta/Elev= 30
  4240.1    1025    4296 1022.16  4324.3 1017.85  4409.1 1023.31  4472.7    1024
  4650.2 1015.74  4748.5 1011.28  4847.5 1004.31  4868.7 1000.71  4918.2  999.33
  4953.6 1004.46  4967.7  1000.2    4974   993.8    4976   993.3  4989.6   993.8
  5006.3  995.34  5016.7 1001.16  5024.5 1002.16  5059.7  999.84  5172.9  999.98
  5223.7 1000.95    5251 1005.86  5303.8 1005.48  5400.7 1007.47  5581.2 1017.82
  5641.6 1021.19  5649.4 1019.59  5670.2 1023.67  5741.8 1028.46  5784.1  1035.4
#Mann= 6 ,-1 , 0
  4240.1     .05       0  4650.2     .16       0    4974     .07       0
  4989.6     .16       0  5303.8     .05       0  5581.2     .16       0
Bank Sta=4974,4989.6
XS Rating Curve= 0 ,0
Exp/Cntr=0.3,0.1

Type RM Length L Ch R = 1 ,533125  ,137,137,137
BEGIN DESCRIPTION:
Denton Creek302
END DESCRIPTION:
XS GIS Cut Line= 3
      2194108.95      7260312.81      2193613.84      7259824.48
      2193193.84      7259399.23
#Sta/Elev= 30
  4458.8 1017.33  4637.6 1009.49  4651.7 1006.66  4658.7 1007.92  4672.9  1004.5
    4680 1008.66    4687 1006.49  4694.1 1008.41  4750.7 1006.34  4764.8 1007.49
  4814.3 1003.76  4906.3    1001  4962.8 1001.66  4998.2  996.72  5004.5  993.62
  5006.5  993.12  5020.1  993.62  5026.4  996.93  5068.9 1000.12  5111.3 1000.98
  5132.6  998.96  5167.9 1001.73  5245.6 1000.88  5343.2 1003.97  5415.3  1006.9
  5595.7 1020.46  5641.6 1022.64  5655.7 1026.91  5733.2 1033.16  5751.9 1035.05
#Mann= 7 ,-1 , 0
  4458.8     .16       0  5004.5     .07       0  5020.1     .16       0
  5343.2     .05       0  5595.7     .16       0  5655.7     .05       0
  5733.2     .16       0
Bank Sta=5004.5,5020.1
XS Rating Curve= 0 ,0
Exp/Cntr=0.3,0.1

Type RM Length L Ch R = 1 ,532988  ,463,463,463
BEGIN DESCRIPTION:
Denton Creek 284.0
END DESCRIPTION:
XS GIS Cut Line= 3
      2194208.41       7260181.9      2193943.25      7259972.26
      2193278.97      7259259.97
#Sta/Elev= 30
  4504.3 1020.22  4562.4 1016.47  4618.4 1014.47  4682.5 1008.86  4818.8 1003.42
  4841.8 1001.27  4917.6  999.17  4924.9 1000.53  4953.2  999.18  4974.2  999.61
  4981.6  999.11  4994.8  990.07  4996.8  989.57  5010.4  990.07  5016.8  994.47
  5030.9  999.53  5115.9  998.68  5122.8 1000.95  5130.1  998.83  5200.9  998.27
  5347.5 1004.61  5387.9 1005.83  5427.1 1007.46    5489 1013.23  5524.8 1015.47
  5630.4 1022.82  5661.7 1025.33  5771.9 1032.42  5798.6 1034.14  5816.3 1035.11
#Mann= 11 ,-1 , 0
  4504.3     .05       0  4994.8    .035       0  5010.4     .05       0
  5347.5    .063       0  5387.9     .05       0    5489    .063       0
  5524.8     .05       0  5630.4    .063       0  5661.7     .05       0
  5771.9    .063       0  5798.6     .05       0
Bank Sta=4994.8,5010.4
XS Rating Curve= 0 ,0
Exp/Cntr=0.3,0.1

Type RM Length L Ch R = 1 ,532525  ,623,623,623
BEGIN DESCRIPTION:
Denton Creek 283.0
END DESCRIPTION:
XS GIS Cut Line= 3
      2194500.64      7259851.51        2194179.        7259560.
      2193590.78      7258986.23
#Sta/Elev= 30
  4561.7 1019.35  4606.2 1018.45  4648.7  1014.5  4698.8 1012.89  4733.9 1009.59
  4797.4 1007.98  4811.6 1005.34  4896.8 1001.02  4925.2  996.96  4943.4  998.75
  4960.3  999.27  4968.1 1003.03  4981.9  994.52  4984.6   986.9  4986.6   986.4
  5000.3   986.9  5002.9  991.06  5031.1  997.74  5045.3  998.43    5116  996.87
  5158.5  997.84  5186.7     996  5229.2  996.52  5278.6  994.38  5342.3  998.54
  5490.8 1002.67  5512.1 1005.86  5582.6 1008.39  5674.7 1016.07  5817.5 1024.58
#Mann= 5 ,-1 , 0
  4561.7     .05       0  4943.4     .16       0  4968.1     .05       0
  4984.6    .035       0  5000.3     .05       0
Bank Sta=4984.6,5000.3
XS Rating Curve= 0 ,0
Exp/Cntr=0.3,0.1

Type RM Length L Ch R = 1 ,531902  ,701,701,701
BEGIN DESCRIPTION:
Denton Creek 282.0
END DESCRIPTION:
XS GIS Cut Line= 3
      2194748.15      7259285.29      2194540.96       7259069.1
      2193828.99      7258609.99
#Sta/Elev= 30
  4647.6 1019.84  4728.2 1015.83  4778.2 1014.76  4884.2 1007.78  4905.2 1005.32
  4919.4 1001.03  4926.6  996.58  4933.5  995.59  4940.8   998.6  4961.3  1000.1
  4970.1  996.26  4976.1  996.15  4985.1  990.64  4989.4  984.71  4991.4  984.21
  5005.1  984.71  5006.4  987.24  5011.5  985.33  5027.6  998.55  5033.5   996.7
  5048.7  998.28  5070.7  996.36  5136.5  993.92  5209.1  995.07  5230.2  992.75
  5302.8  997.63    5392  996.69  5490.2   998.1  5723.9  1006.2  5794.2  1009.8
#Mann= 8 ,-1 , 0
  4647.6     .05       0  4728.2     .16       0  4989.4     .07       0
  5005.1     .16       0  5011.5     .05       0  5070.7     .16       0
    5392     .05       0  5723.9     .16       0
Bank Sta=4989.4,5005.1
XS Rating Curve= 0 ,0
Exp/Cntr=0.3,0.1

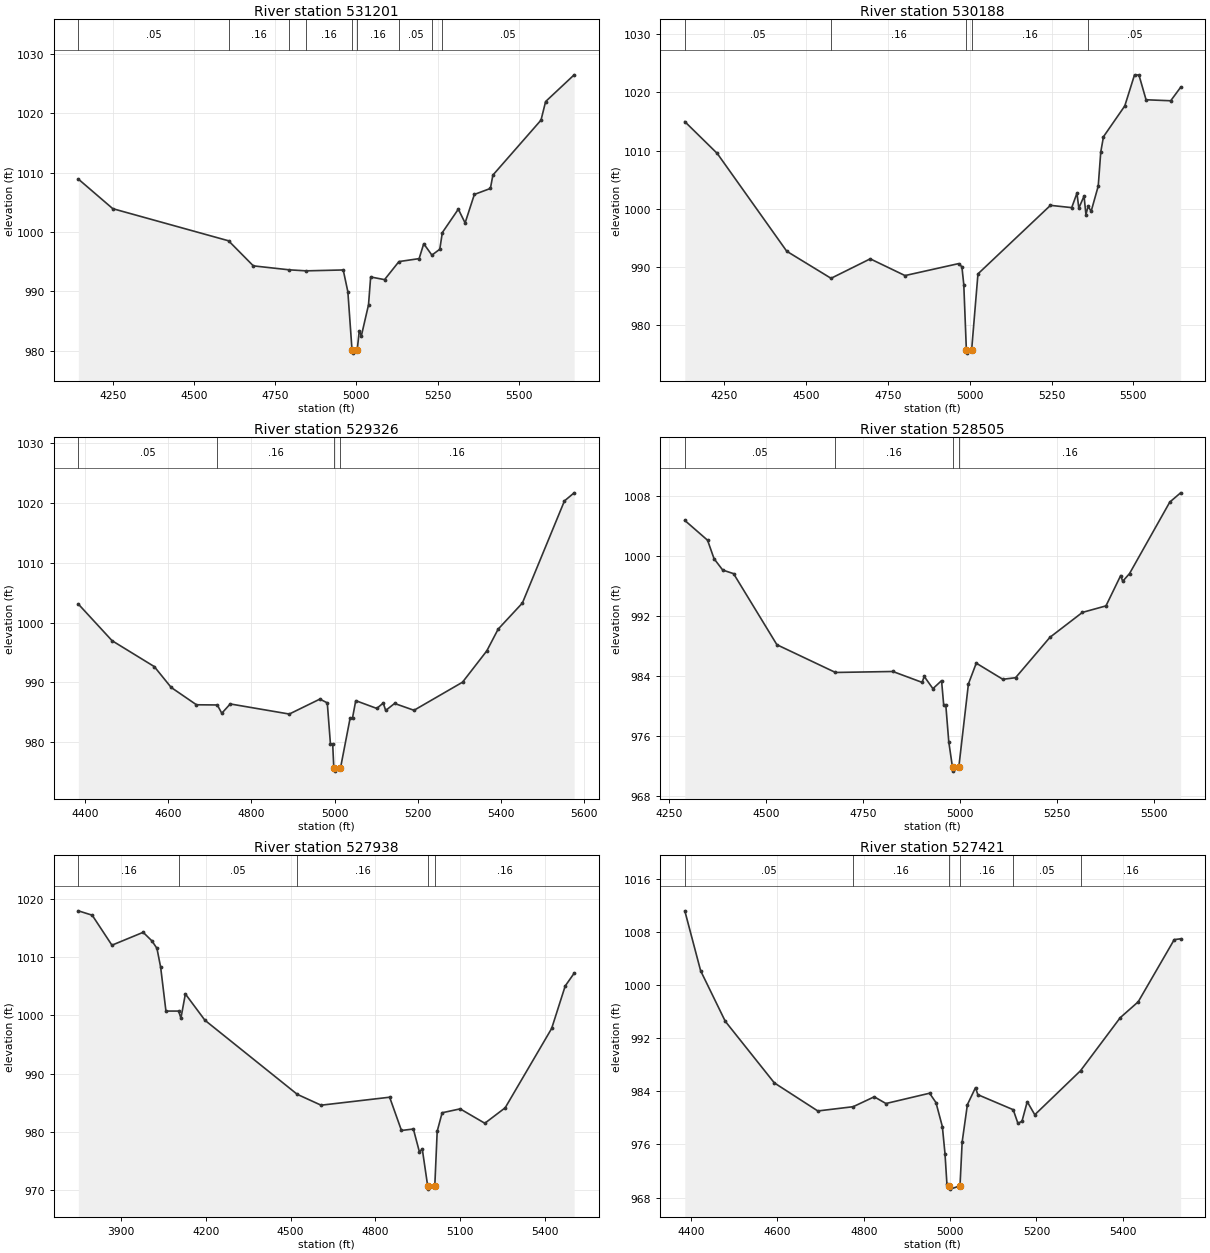
Type RM Length L Ch R = 1 ,531201  ,1013,1013,1013
BEGIN DESCRIPTION:
Denton Creek 280.0
END DESCRIPTION:
XS GIS Cut Line= 3
      2195074.78       7259003.6        2194529.        7258360.
      2194009.94      7257915.56
#Sta/Elev= 30
  4143.5 1008.93  4249.7 1003.94  4606.3  998.53  4682.5  994.31  4793.5  993.64
  4845.4  993.47  4959.4  993.62  4973.7  989.94  4986.5  980.11  4988.5  979.61
  5002.4  980.11  5008.8  983.37  5015.3  982.53  5037.3  987.75  5043.9  992.44
  5086.7  991.99    5131  995.03  5193.2  995.53  5207.4  998.04  5232.5  996.12
  5256.8  997.11  5264.7  999.92  5313.9 1003.86  5334.8 1001.54  5363.3 1006.34
  5412.7 1007.35  5420.4  1009.6  5568.6 1018.86  5582.8 1021.99  5670.7 1026.49
#Mann= 9 ,-1 , 0
  4143.5     .05       0  4606.3     .16       0  4793.5     .05       0
  4845.4     .16       0  4986.5     .07       0  5002.4     .16       0
    5131     .05       0  5232.5     .16       0  5264.7     .05       0
Bank Sta=4986.5,5002.4
XS Rating Curve= 0 ,0
Exp/Cntr=0.3,0.1

Type RM Length L Ch R = 1 ,530188  ,862,862,862
BEGIN DESCRIPTION:
Denton Creek 278.0
END DESCRIPTION:
XS GIS Cut Line= 3
      2195728.99      7258409.99      2195204.93      7257820.09
      2194849.92      7257187.23
#Sta/Elev= 30
  4129.7 1014.97  4228.8 1009.51  4441.2  992.72  4576.5  988.08  4696.2  991.42
  4802.4  988.55    4966   990.6  4976.2  990.07    4982  986.99  4989.9  975.74
  4991.9  975.24  5005.9  975.74  5025.3  988.84  5246.7  1000.6  5311.7 1000.21
  5327.7 1002.69  5333.4 1000.13  5349.4 1002.19  5355.1  999.02  5361.8 1000.44
  5371.1  999.58  5392.7 1003.91  5400.4 1009.74  5408.7 1012.38  5473.8 1017.66
  5503.6    1023  5517.1 1022.97  5538.8 1018.72  5614.1 1018.55  5644.4 1020.86
#Mann= 5 ,-1 , 0
  4129.7     .05       0  4576.5     .16       0  4989.9     .07       0
  5005.9     .16       0  5361.8     .05       0
Bank Sta=4989.9,5005.9
XS Rating Curve= 0 ,0
Exp/Cntr=0.3,0.1

Type RM Length L Ch R = 1 ,529326  ,821,821,821
BEGIN DESCRIPTION:
Denton Creek 276.0
END DESCRIPTION:
XS GIS Cut Line= 3
        2196029.      7258010.03        2195929.        7257410.
        2195629.        7256910.
#Sta/Elev= 30
    4384 1003.11  4465.1  996.98  4566.5  992.65  4607.1  989.16  4667.9  986.26
  4717.9  986.23  4728.7  984.84    4749   986.4  4890.9  984.71  4964.4  987.21
  4982.2  986.58  4989.8  979.69  4995.2  979.69  4997.9  975.66  4999.9  975.16
  5013.9  975.66    5037     984  5042.8  984.06  5050.6  986.95  5101.1  985.65
  5116.7  986.55  5122.5  985.31  5143.9  986.48  5190.6  985.34  5307.2  990.04
  5365.5  995.28  5392.7  998.91    5451 1003.28  5552.1 1020.37  5575.4 1021.72
#Mann= 4 ,-1 , 0
    4384     .05       0  4717.9     .16       0  4997.9     .07       0
  5013.9     .16       0
Bank Sta=4997.9,5013.9
XS Rating Curve= 0 ,0
Exp/Cntr=0.3,0.1

Type RM Length L Ch R = 1 ,528505  ,567,567,567
BEGIN DESCRIPTION:
Denton Creek 274.0
END DESCRIPTION:
XS GIS Cut Line= 3
        2196379.      7258060.01        2196679.        7257460.
        2196579.        7256860.
#Sta/Elev= 30
  4290.8 1004.79  4349.5 1002.15  4366.3  999.68  4388.6  998.17  4416.6  997.69
  4528.4  988.21  4679.5  984.51  4827.5  984.64  4902.9  983.19  4908.5  983.98
  4930.9  982.35  4953.2  983.42  4958.8  980.11  4964.2  980.11  4971.8  975.25
  4981.4  971.85  4983.4  971.35  4997.6  971.85  5022.5  982.99  5042.7  985.75
  5111.2   983.6  5144.1  983.81  5232.8   989.2  5316.5  992.52  5377.3  993.39
  5415.3  997.44  5420.4  996.67  5438.1   997.7    5542 1007.24  5569.9 1008.47
#Mann= 4 ,-1 , 0
  4290.8     .05       0  4679.5     .16       0  4981.4     .07       0
  4997.6     .16       0
Bank Sta=4981.4,4997.6
XS Rating Curve= 0 ,0
Exp/Cntr=0.3,0.1

Type RM Length L Ch R = 1 ,527938  ,517,517,517
BEGIN DESCRIPTION:
Denton Creek 273.0
END DESCRIPTION:
XS GIS Cut Line= 3
      2198021.01      7258041.03      2197280.81      7257779.46
      2196978.99      7256859.98
#Sta/Elev= 30
  3749.8 1017.93  3798.8 1017.18  3868.6 1012.03    3979 1014.24  4009.9 1012.77
  4027.7 1011.49  4040.8 1008.25  4059.5 1000.72  4104.3 1000.72  4112.5  999.51
  4128.2 1003.66  4197.4  999.14  4523.9  986.42    4608  984.56  4850.3  985.93
  4892.1  980.22  4934.2  980.47  4955.3  976.59  4965.8     977  4984.9  970.65
  4987.4  970.15  5009.9  970.65  5018.4  980.08  5035.9  983.26  5099.6  983.93
  5186.8  981.46  5258.7  984.11    5423  997.73    5471 1005.03  5502.6 1007.22
#Mann= 5 ,-1 , 0
  3749.8     .16       0  4104.3     .05       0  4523.9     .16       0
  4984.9     .07       0  5009.9     .16       0
Bank Sta=4984.9,5009.9
XS Rating Curve= 0 ,0
Exp/Cntr=0.3,0.1

Type RM Length L Ch R = 1 ,527421  ,1054,1054,1054
BEGIN DESCRIPTION:
Denton Creek 272.0
END DESCRIPTION:
XS GIS Cut Line= 3
      2198029.03      7257360.02        2197529.        7257010.
      2197028.98      7256809.99
#Sta/Elev= 30
  4385.3 1011.14    4422 1002.12  4479.1  994.52  4592.8  985.25  4693.5  981.03
  4775.4  981.67  4824.3  983.16  4851.4  982.15  4952.5   983.7  4967.3  982.29
  4982.1  978.68  4988.2  974.62  4992.6   970.1    4998  969.77  5000.5  969.27
    5023  969.77    5028  976.37  5040.1  981.98  5058.9  984.54  5064.3  983.48
  5146.3  981.22  5157.2  979.17  5166.6  979.48  5178.8  982.42  5196.3  980.46
  5302.2  987.08  5394.2  995.06  5435.9  997.45  5519.4 1006.81  5534.2 1006.93
#Mann= 6 ,-1 , 0
  4385.3     .05       0  4775.4     .16       0    4998     .07       0
    5023     .16       0  5146.3     .05       0  5302.2     .16       0
Bank Sta=4998,5023
XS Rating Curve= 0 ,0
Exp/Cntr=0.3,0.1

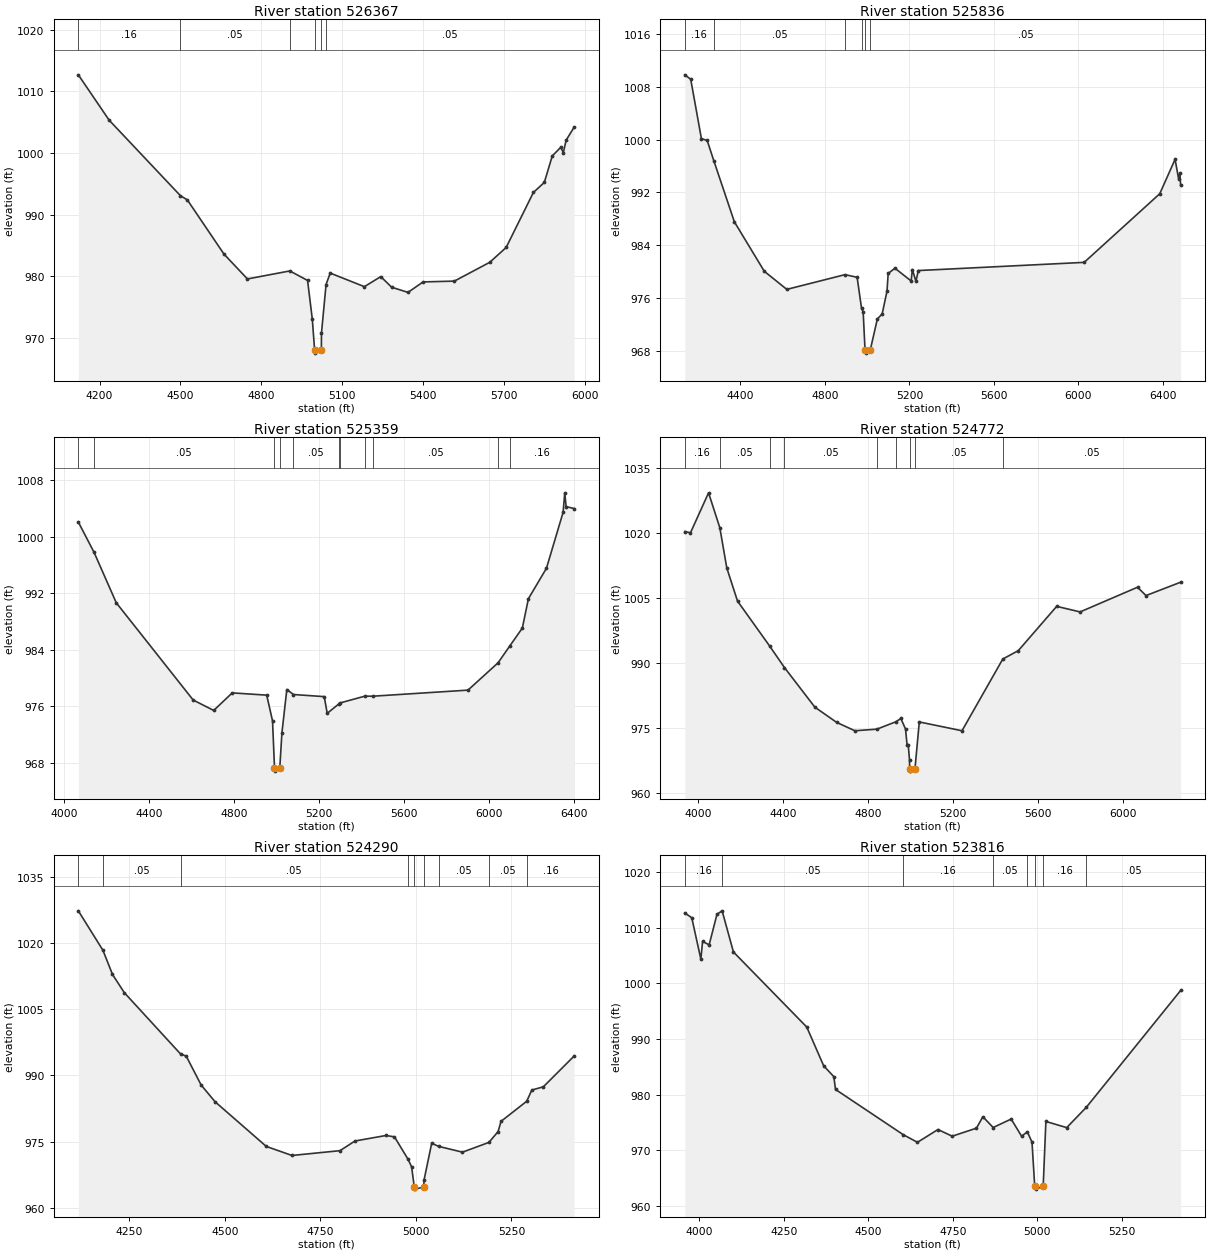
Type RM Length L Ch R = 1 ,526367  ,531,531,531
BEGIN DESCRIPTION:
Denton Creek 270.0
END DESCRIPTION:
XS GIS Cut Line= 3
      2198838.21       7256474.6        2197979.        7256210.
      2197049.45      7256073.87
#Sta/Elev= 30
  4121.4 1012.67  4235.7 1005.32  4499.6   993.1  4525.6   992.4  4661.6  983.61
  4748.4  979.59  4905.6  980.89  4971.4  979.35    4989  973.06  4997.5  968.07
    5000  967.57  5022.5  968.07    5023  970.82    5040  978.69  5055.4  980.54
  5182.1  978.34  5242.8  979.97  5283.2  978.25  5343.8  977.41  5399.7  979.11
  5515.7  979.24    5647  982.29  5707.7  984.69  5808.8  993.61  5849.2  995.23
  5878.8  999.53  5909.8 1000.91  5919.9 1000.08    5930 1002.06  5959.9  1004.2
#Mann= 6 ,-1 , 0
  4121.4     .16       0  4499.6     .05       0  4905.6     .16       0
  4997.5     .07       0  5022.5     .16       0    5040     .05       0
Bank Sta=4997.5,5022.5
XS Rating Curve= 0 ,0
Exp/Cntr=0.3,0.1

Type RM Length L Ch R = 1 ,525836  ,477,477,477
BEGIN DESCRIPTION:
Denton Creek 269.0
END DESCRIPTION:
XS GIS Cut Line= 4
      2198729.02      7256260.01        2198079.        7255710.
      2197483.13      7255432.81      2196733.24      7255808.03
#Sta/Elev= 30
  4136.5  1009.8  4164.5 1009.13  4215.1 1000.14  4242.5  999.86    4274  996.78
  4371.1  987.55  4512.8  980.06  4619.4  977.32  4894.8  979.55  4952.3  979.15
  4973.3  974.43  4980.8  973.96  4989.7  968.17  4992.2  967.67  5014.7  968.17
    5048  972.84  5070.8   973.6  5093.7  977.05  5099.2  979.73  5131.4  980.52
  5208.1  978.59  5213.7  980.32  5230.6  978.55  5242.1  980.17  6027.2  981.41
  6384.9   991.8  6457.5  997.01  6474.3  994.02  6479.9  994.97  6483.7  993.12
#Mann= 6 ,-1 , 0
  4136.5     .16       0    4274     .05       0  4894.8     .16       0
  4973.3     .05       0  4989.7    .035       0  5014.7     .05       0
Bank Sta=4989.7,5014.7
XS Rating Curve= 0 ,0
Exp/Cntr=0.3,0.1

Type RM Length L Ch R = 1 ,525359  ,587,587,587
BEGIN DESCRIPTION:
Denton Creek 268.0
END DESCRIPTION:
XS GIS Cut Line= 3
      2198788.33      7256155.64      2198215.85       7255133.3
      2197316.61       7254399.6
#Sta/Elev= 30
    4067 1002.07  4141.1  997.78  4245.4  990.66  4607.2  976.91  4703.8  975.44
    4791  977.92  4953.1   977.6  4980.5  973.96  4989.7  967.36  4992.2  966.86
  5014.7  967.36  5024.7  972.29  5047.7  978.39    5079  977.69  5223.7  977.39
  5237.7  975.03  5292.1  976.35  5299.5  976.51  5415.1  977.46  5451.4  977.45
  5899.9  978.31  6041.6  982.18  6097.4  984.59  6155.5  987.08  6184.2  991.24
  6268.9  995.53  6347.2 1003.43  6355.1  1006.2  6361.5 1004.25  6399.3 1003.98
#Mann= 11 ,-1 , 0
    4067     .16       0  4141.1     .05       0  4989.7    .035       0
  5014.7     .05       0    5079     .05       0  5292.1     .05       0
  5299.5     .05       0  5415.1     .05       0  5451.4     .05       0
  6041.6     .05       0  6097.4     .16       0
Bank Sta=4989.7,5014.7
XS Rating Curve= 0 ,0
Exp/Cntr=0.3,0.1

Type RM Length L Ch R = 1 ,524772  ,482,482,482
BEGIN DESCRIPTION:
Denton Creek 267.0
END DESCRIPTION:
XS GIS Cut Line= 4
      2199240.64      7256145.03        2198879.        7255160.
      2198687.47      7254738.62      2198642.06      7253917.26
#Sta/Elev= 30
  3936.8 1020.38  3963.5 1020.09  4048.7 1029.33  4101.7 1021.27  4134.7 1011.94
    4185 1004.31    4336  993.94  4406.1  988.94  4549.4  979.78  4651.5  976.28
  4737.6  974.33  4841.3   974.7  4931.7  976.43  4954.2  977.18  4976.2  974.72
  4983.5  971.09  4988.9  971.09  4994.9  967.62  4995.6   965.5  4998.1     965
  5020.6   965.5    5041  976.37  5242.1  974.33  5434.2  990.91  5507.2  992.85
    5688 1003.09  5798.1  1001.8  6068.6 1007.51  6108.6 1005.58  6271.6 1008.67
#Mann= 9 ,-1 , 0
  3936.8     .16       0  4101.7     .05       0    4336     .05       0
  4406.1     .05       0  4841.3     .05       0  4931.7     .05       0
  4995.6    .035       0  5020.6     .05       0  5434.2     .05       0
Bank Sta=4995.6,5020.6
XS Rating Curve= 0 ,0
Exp/Cntr=0.3,0.1

Type RM Length L Ch R = 1 ,524290  ,474,474,474
BEGIN DESCRIPTION:
Denton Creek 266.0
END DESCRIPTION:
XS GIS Cut Line= 3
        2199679.        7255710.        2199279.        7254910.
        2199229.      7254510.04
#Sta/Elev= 30
  4116.7 1027.33  4181.1 1018.38  4206.1 1012.91  4236.9 1008.79  4384.4  994.86
    4399   994.4  4438.1  987.84  4474.5  984.05  4608.6  973.92  4675.7  971.87
  4801.5  972.96  4840.6  975.15  4921.7   976.4    4944  976.09    4979  971.09
  4988.8  969.31  4995.8  964.74  4998.3  964.24  5020.8  964.74  5021.2  966.22
  5041.4  974.65  5059.3  973.94    5122  972.62  5191.1  974.83  5215.2  977.29
  5222.8   979.6    5290  984.16  5303.4   986.7  5333.6  987.44  5414.2  994.42
#Mann= 9 ,-1 , 0
  4116.7     .16       0  4181.1     .05       0  4384.4     .05       0
    4979     .05       0  4995.8    .035       0  5020.8     .05       0
  5059.3     .05       0  5191.1     .05       0    5290     .16       0
Bank Sta=4995.8,5020.8
XS Rating Curve= 0 ,0
Exp/Cntr=0.3,0.1

Type RM Length L Ch R = 1 ,523816  ,750,750,750
BEGIN DESCRIPTION:
Denton Creek 265.0
END DESCRIPTION:
XS GIS Cut Line= 3
      2199945.05      7255750.08      2199663.86      7254544.58
      2199528.98      7254359.97
#Sta/Elev= 30
  3957.5 1012.62  3978.1 1011.77    4005 1004.33  4010.1 1007.52  4029.5  1006.9
  4052.7 1012.39  4067.9 1013.01  4101.3 1005.62  4318.2  992.13  4368.3  985.16
  4398.2  983.22  4403.3  980.92  4603.4   972.8  4645.6  971.42  4706.3  973.72
  4748.3  972.52  4820.1  973.96  4839.1  976.02  4869.5  974.08  4922.8   975.6
  4953.6  972.52  4970.7   973.3  4984.4  971.45  4992.5  963.51    4995  963.01
  5017.5  963.51  5025.5  975.17  5087.1  974.06  5144.9   977.7    5424   998.7
#Mann= 8 ,-1 , 0
  3957.5     .16       0  4067.9     .05       0  4603.4     .16       0
  4869.5     .05       0  4970.7     .16       0  4992.5     .07       0
  5017.5     .16       0  5144.9     .05       0
Bank Sta=4992.5,5017.5
XS Rating Curve= 0 ,0
Exp/Cntr=0.3,0.1

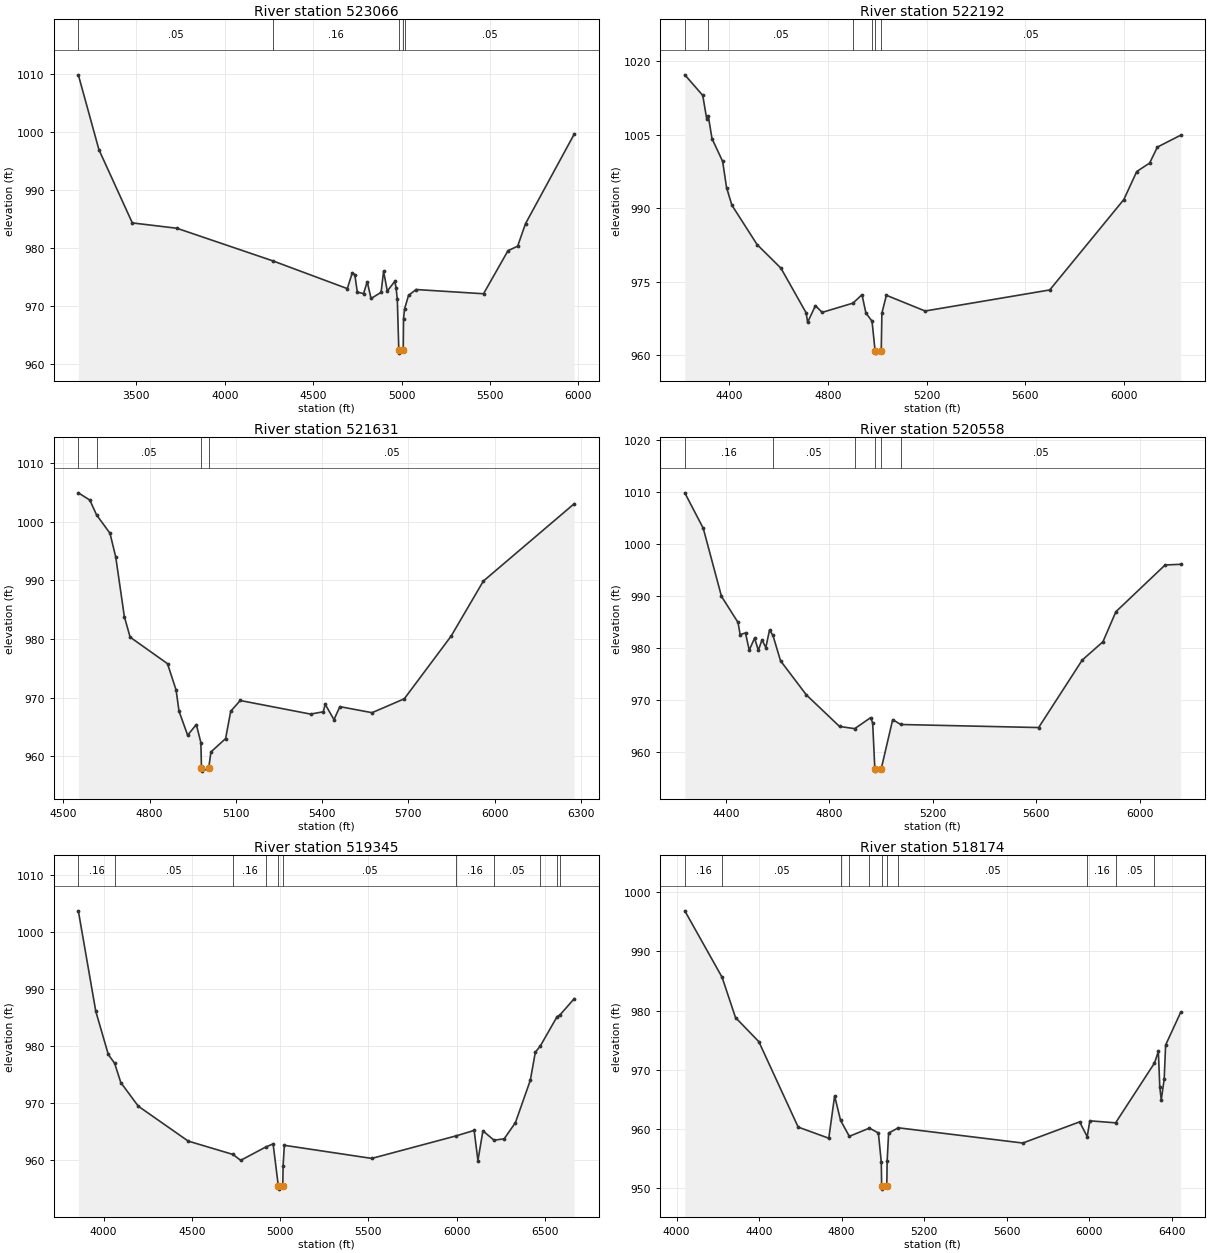
Type RM Length L Ch R = 1 ,523066  ,874,874,874
BEGIN DESCRIPTION:
Denton Creek301
END DESCRIPTION:
XS GIS Cut Line= 4
      2201202.86      7256200.74      2200798.45      7255003.02
      2200143.33       7254392.2      2199513.87      7254257.81
#Sta/Elev= 30
  3172.1  1009.9  3288.6  996.96  3477.4  984.31  3729.1  983.39  4270.2  977.77
  4692.9  972.96  4721.2  975.69  4735.4  975.36  4749.5  972.35  4784.7   972.1
  4805.7  974.14  4827.2  971.25  4883.9  972.31  4898.1  975.96  4919.1  972.53
  4961.6  974.23  4968.7  973.11  4975.7  971.08  4984.2  962.31  4986.7  961.81
  5009.2  962.31  5010.9   967.7  5016.4  969.43  5039.2  971.79  5081.8   972.8
  5463.2  972.07  5601.5  979.51  5656.1  980.29  5700.5  984.18  5975.6  999.64
#Mann= 5 ,-1 , 0
  3172.1     .05       0  4270.2     .16       0  4984.2     .07       0
  5009.2     .16       0  5016.4     .05       0
Bank Sta=4984.2,5009.2
XS Rating Curve= 0 ,0
Exp/Cntr=0.3,0.1

Type RM Length L Ch R = 1 ,522192  ,561,561,561
BEGIN DESCRIPTION:
Denton Creek 263.0
END DESCRIPTION:
XS GIS Cut Line= 3
      2201178.97      7253460.02        2200479.        7253860.
      2199328.98      7254210.01
#Sta/Elev= 30
  4220.6  1017.2  4293.3    1013  4309.1 1008.27    4316 1008.73  4330.7 1004.19
  4373.9  999.52  4389.7  994.19  4411.3  990.59  4513.5  982.54    4610  977.73
  4712.2  968.59    4718  966.69  4749.7  970.07    4777   968.7  4901.8  970.59
  4938.3  972.31  4954.1  968.58    4979  966.91  4991.3  960.88  4993.8  960.38
  5016.3  960.88  5018.9  968.56  5037.2  972.19    5194  968.98  5698.8  973.28
  5998.9  991.74  6051.2  997.46  6103.4  999.19  6134.8 1002.45  6228.9 1004.87
#Mann= 6 ,-1 , 0
  4220.6     .16       0    4316     .05       0  4901.8     .16       0
    4979     .05       0  4991.3    .035       0  5016.3     .05       0
Bank Sta=4991.3,5016.3
XS Rating Curve= 0 ,0
Exp/Cntr=0.3,0.1

Type RM Length L Ch R = 1 ,521631  ,1073,1073,1073
BEGIN DESCRIPTION:
Denton Creek 262.0
END DESCRIPTION:
XS GIS Cut Line= 3
        2201029.        7253360.        2200629.        7253360.
      2199329.02        7253110.
#Sta/Elev= 30
  4552.5 1004.97  4592.5 1003.73    4616 1001.19  4662.5  998.07  4682.5  994.03
  4712.5  983.83  4732.5  980.33  4862.5   975.8  4892.5  971.28  4902.5  967.69
  4932.5  963.59  4962.7   965.4  4978.5  962.33  4980.7  957.95  4983.2  957.45
  5005.7  957.95  5013.6  960.73  5064.5  963.01  5082.3  967.68  5115.4  969.51
  5359.8  967.19  5404.1  967.58  5410.7  968.87  5441.3  966.24  5461.7  968.46
  5573.7  967.43  5685.7   969.8  5848.6  980.51  5960.6   989.9  6276.3  1003.1
#Mann= 4 ,-1 , 0
  4552.5     .16       0    4616     .05       0  4980.7    .035       0
  5005.7     .05       0
Bank Sta=4980.7,5005.7
XS Rating Curve= 0 ,0
Exp/Cntr=0.3,0.1

Type RM Length L Ch R = 1 ,520558  ,1213,1213,1213
BEGIN DESCRIPTION:
Denton Creek 260.0
END DESCRIPTION:
XS GIS Cut Line= 3
      2201429.03      7253110.03      2200580.76      7252040.36
      2200028.99        7252010.
#Sta/Elev= 30
  4240.7 1009.87  4312.1 1003.03  4382.5  989.92  4446.6  984.88  4454.7  982.55
  4475.5  982.85  4489.9  979.55  4510.7  981.86  4525.1  979.52  4539.6  981.54
    4554  980.03  4568.4  983.41  4581.5  982.41  4610.9   977.5    4711  970.91
  4839.2  964.83    4898  964.41  4959.4  966.53  4967.4  965.51  4975.7  956.72
  4978.2  956.22  5000.7  956.72  5044.8  966.14  5076.1  965.21  5609.3  964.62
  5777.9  977.63    5858  981.16  5908.1  986.95  6098.4  995.96  6158.5  996.09
#Mann= 6 ,-1 , 0
  4240.7     .16       0  4581.5     .05       0    4898     .16       0
  4975.7     .07       0  5000.7     .16       0  5076.1     .05       0
Bank Sta=4975.7,5000.7
XS Rating Curve= 0 ,0
Exp/Cntr=0.3,0.1

Type RM Length L Ch R = 1 ,519345  ,1171,1171,1171
BEGIN DESCRIPTION:
Denton Creek 259.0
END DESCRIPTION:
XS GIS Cut Line= 3
      2202529.03      7252460.03        2201729.        7251660.
      2200519.49       7250498.8
#Sta/Elev= 30
  3857.1 1003.74  3956.1  986.09  4026.8  978.53  4062.7  976.98  4097.6  973.61
  4196.5  969.46  4479.4  963.33  4733.5  960.98  4776.4  959.95  4918.5  962.29
  4960.2  962.84    4990   955.4  4992.5   954.9    5015   955.4  5016.7  958.96
  5023.9  962.59  5518.9  960.29  5996.9  964.25  6098.8   965.2  6120.2  959.91
  6148.5  965.13  6211.1  963.49  6268.6  963.72  6332.4  966.56    6417  974.01
  6445.3  978.93  6473.9  980.04  6568.7  985.18  6583.3  985.42  6665.2  988.31
#Mann= 11 ,-1 , 0
  3857.1     .16       0  4062.7     .05       0  4733.5     .16       0
  4918.5     .05       0    4990    .035       0    5015     .05       0
  5996.9     .16       0  6211.1     .05       0  6473.9     .16       0
  6568.7     .05       0  6583.3     .16       0
Bank Sta=4990,5015
XS Rating Curve= 0 ,0
Exp/Cntr=0.3,0.1

Type RM Length L Ch R = 1 ,518174  ,169,169,169
BEGIN DESCRIPTION:
Denton Creek300
END DESCRIPTION:
XS GIS Cut Line= 3
      2203098.23      7251738.38      2202170.08      7250787.83
      2201407.24      7250029.03
#Sta/Elev= 30
  4039.4  996.86  4220.2  985.65  4285.3  978.85  4398.4  974.78  4589.3  960.36
  4737.7  958.48    4766  965.62  4794.7  961.51  4837.2   958.8  4934.7  960.19
  4978.2  959.37  4992.3  954.42    4994  950.39  4996.5  949.89    5019  950.39
  5020.6  954.56  5027.8  959.35  5074.8  960.24  5678.3  957.67  5954.1  961.24
  5990.9  958.74  6003.6  961.42  6128.6  961.08  6317.1  971.17  6335.9  973.12
    6343  967.07    6350  964.94  6364.2  968.47  6371.2  974.22  6443.9  979.71
#Mann= 11 ,-1 , 0
  4039.4     .16       0  4220.2     .05       0  4794.7     .16       0
  4837.2     .05       0  4934.7     .16       0    4994     .07       0
    5019     .16       0  5074.8     .05       0  5990.9     .16       0
  6128.6     .05       0  6317.1     .16       0
Bank Sta=4994,5019
XS Rating Curve= 0 ,0
Exp/Cntr=0.3,0.1

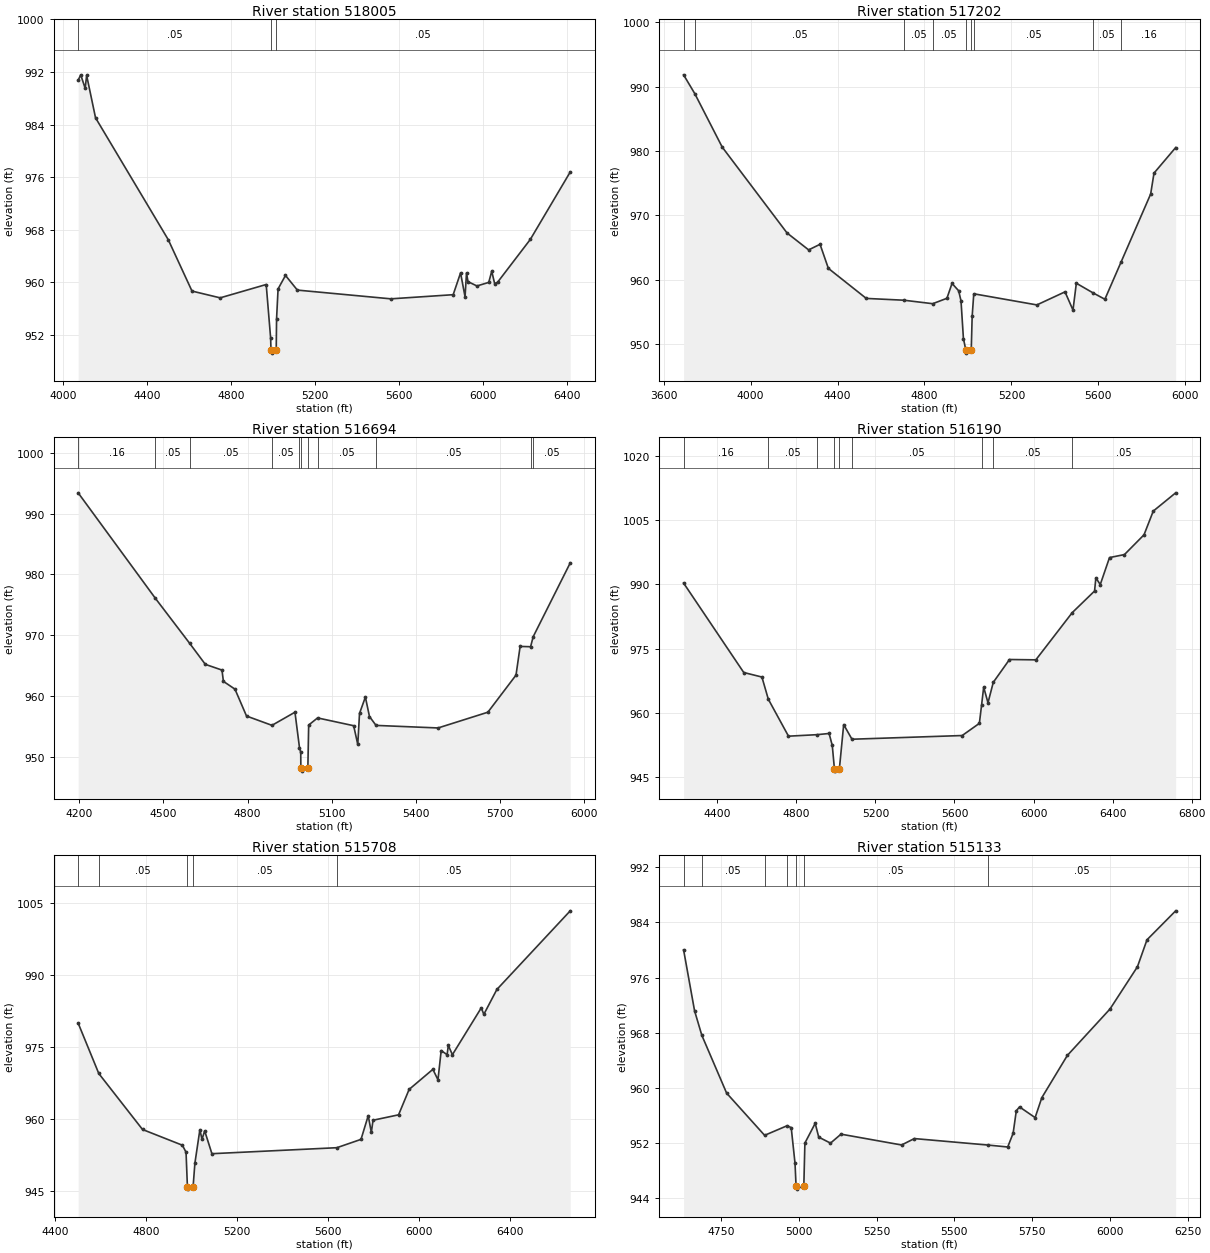
Type RM Length L Ch R = 1 ,518005  ,803,803,803
BEGIN DESCRIPTION:
Denton Creek 256.0
END DESCRIPTION:
XS GIS Cut Line= 3
      2203222.15      7251644.06      2202696.93      7251103.38
      2201588.92      7249961.05
#Sta/Elev= 30
  4072.5  990.73  4084.7  991.56    4106  989.51    4113  991.47  4155.4  985.02
  4501.9  966.48  4615.1  958.66  4749.3  957.63  4968.7  959.66  4989.8  951.52
  4991.5  949.72    4994  949.22  5016.5  949.72  5018.1  954.44  5025.3  958.99
  5060.6  961.04  5117.2  958.81  5562.7  957.48  5859.8  958.11    5895  961.43
  5916.4  957.78  5923.3  961.42  5930.5  960.09    5973  959.44  6029.3  959.98
  6043.5  961.68  6057.6  959.78  6071.8  960.02  6227.4  966.52  6417.7  976.78
#Mann= 3 ,-1 , 0
  4072.5     .05       0  4991.5    .035       0  5016.5     .05       0
Bank Sta=4991.5,5016.5
XS Rating Curve= 0 ,0
Exp/Cntr=0.3,0.1

Type RM Length L Ch R = 1 ,517202  ,508,508,508
BEGIN DESCRIPTION:
Denton Creek 255.0
END DESCRIPTION:
XS GIS Cut Line= 3
      2204040.26      7250784.21        2202829.        7250260.
      2202025.28       7249765.1
#Sta/Elev= 30
  3691.9  991.83  3743.4  988.91  3869.6   980.6  4167.8  967.26  4267.2  964.63
  4319.6   965.5  4357.9  961.76  4532.3  957.09  4705.6  956.81  4837.9  956.27
  4903.3  957.11  4926.8  959.42  4957.2  958.28  4968.1  956.71  4979.2  950.85
  4990.2  949.09  4992.7  948.59  5015.2  949.09  5019.4  954.31  5026.8  957.81
  5317.1  956.08  5446.5  958.11  5483.2  955.28  5498.6  959.45    5575  957.96
  5629.9  956.96    5705  962.79  5840.5  973.31  5855.9  976.56  5955.6  980.53
#Mann= 9 ,-1 , 0
  3691.9     .16       0  3743.4     .05       0  4705.6     .05       0
  4837.9     .05       0  4990.2    .035       0  5015.2     .05       0
  5026.8     .05       0    5575     .05       0    5705     .16       0
Bank Sta=4990.2,5015.2
XS Rating Curve= 0 ,0
Exp/Cntr=0.3,0.1

Type RM Length L Ch R = 1 ,516694  ,504,504,504
BEGIN DESCRIPTION:
Denton Creek 254.0
END DESCRIPTION:
XS GIS Cut Line= 3
      2203828.99        7250010.        2203029.        7249810.
      2202278.97      7249259.98
#Sta/Elev= 30
  4195.8  993.41  4471.5  976.04  4593.4  968.66  4649.3   965.2  4708.6  964.26
  4713.8   962.4    4755  961.12  4796.2   956.7  4886.9  955.17  4968.9  957.33
    4985  951.52  4989.5  950.72  4989.9  948.14  4992.4  947.64  5014.9  948.14
  5017.8  955.22  5049.6  956.39  5178.2  955.11  5192.9  952.02  5199.1  957.13
    5220  959.82  5234.6  956.62    5258  955.16  5479.2  954.74  5656.8  957.33
  5757.1  963.43  5771.8  968.15  5809.1   968.1  5818.5  969.76  5950.5  981.89
#Mann= 11 ,-1 , 0
  4195.8     .16       0  4471.5     .05       0  4593.4     .05       0
  4886.9     .05       0    4985     .05       0  4989.9    .045       0
  5014.9     .05       0  5049.6     .05       0    5258     .05       0
  5809.1     .05       0  5818.5     .05       0
Bank Sta=4989.9,5014.9
XS Rating Curve= 0 ,0
Exp/Cntr=0.3,0.1

Type RM Length L Ch R = 1 ,516190  ,482,482,482
BEGIN DESCRIPTION:
Denton Creek 253.0
END DESCRIPTION:
XS GIS Cut Line= 3
      2203829.01      7249910.01        2203279.        7249410.
      2201679.04      7248710.02
#Sta/Elev= 30
  4229.6  990.32    4534  969.46  4625.9   968.4  4658.3  963.23  4760.4  954.61
  4904.5  954.96  4965.8  955.24  4981.9  952.44  4992.8  946.96  4995.3  946.46
  5017.8  946.96  5039.6  957.31  5081.5   953.9  5639.1  954.76  5726.1   957.6
  5737.4  961.91  5747.9  966.04  5769.7   962.4  5796.5  967.17  5878.5  972.49
  6011.8  972.41  6195.7  983.41  6308.9  988.46  6315.5  991.53  6337.7  989.97
  6384.5  996.26  6460.1  996.96  6559.1 1001.57  6605.9  1007.1  6719.3 1011.36
#Mann= 9 ,-1 , 0
  4229.6     .16       0  4658.3     .05       0  4904.5     .05       0
  4992.8    .035       0  5017.8     .05       0  5081.5     .05       0
  5737.4     .05       0  5796.5     .05       0  6195.7     .05       0
Bank Sta=4992.8,5017.8
XS Rating Curve= 0 ,0
Exp/Cntr=0.3,0.1

Type RM Length L Ch R = 1 ,515708  ,575,575,575
BEGIN DESCRIPTION:
Denton Creek 252.0
END DESCRIPTION:
XS GIS Cut Line= 3
      2203929.04      7249260.02        2203529.        7249010.
      2201929.03      7248460.01
#Sta/Elev= 30
    4503  980.05  4593.7  969.54  4786.1  957.86  4961.2  954.58  4977.4  953.12
  4983.4  945.92  4985.9  945.42  5008.4  945.92  5016.3  950.82  5038.2  957.82
  5047.6  955.81  5059.3  957.58  5091.1  952.81  5640.4  954.06  5746.7   955.8
  5778.4  960.74  5792.1  957.24  5799.5  959.79  5911.8  960.92  5958.2  966.22
  6062.7  970.41    6085  968.22  6099.2  974.32  6125.2  973.46  6130.5  975.39
  6148.5  973.46  6275.4  983.23  6286.7  981.88  6343.9  987.06  6666.6 1003.47
#Mann= 5 ,-1 , 0
    4503     .16       0  4593.7     .05       0  4983.4    .045       0
  5008.4     .05       0  5640.4     .05       0
Bank Sta=4983.4,5008.4
XS Rating Curve= 0 ,0
Exp/Cntr=0.3,0.1

Type RM Length L Ch R = 1 ,515133  ,535,535,535
BEGIN DESCRIPTION:
Denton Creek 251.0
END DESCRIPTION:
XS GIS Cut Line= 3
      2203979.03      7248660.02        2203629.        7248460.
      2202479.01        7248210.
#Sta/Elev= 30
  4630.5  980.04  4665.8  971.19  4689.1  967.64  4768.7  959.26  4890.7  953.14
  4963.3  954.54  4976.1  954.25  4988.3  949.09  4991.6  945.84  4994.1  945.34
  5016.6  945.84    5020  952.02  5053.1  954.88  5064.4  952.88  5102.2  952.01
    5136  953.31  5330.4  951.74  5371.4  952.67  5607.8  951.73  5671.2  951.45
  5688.6  953.44  5698.8   956.7  5709.1  957.26  5759.2  955.71  5780.7   958.6
  5862.6  964.72  5999.7  971.46  6087.7  977.58  6118.4  981.49  6210.5  985.69
#Mann= 7 ,-1 , 0
  4630.5     .05       0  4689.1     .05       0  4890.7     .05       0
  4963.3     .05       0  4991.6    .045       0  5016.6     .05       0
  5607.8     .05       0
Bank Sta=4991.6,5016.6
XS Rating Curve= 0 ,0
Exp/Cntr=0.3,0.1