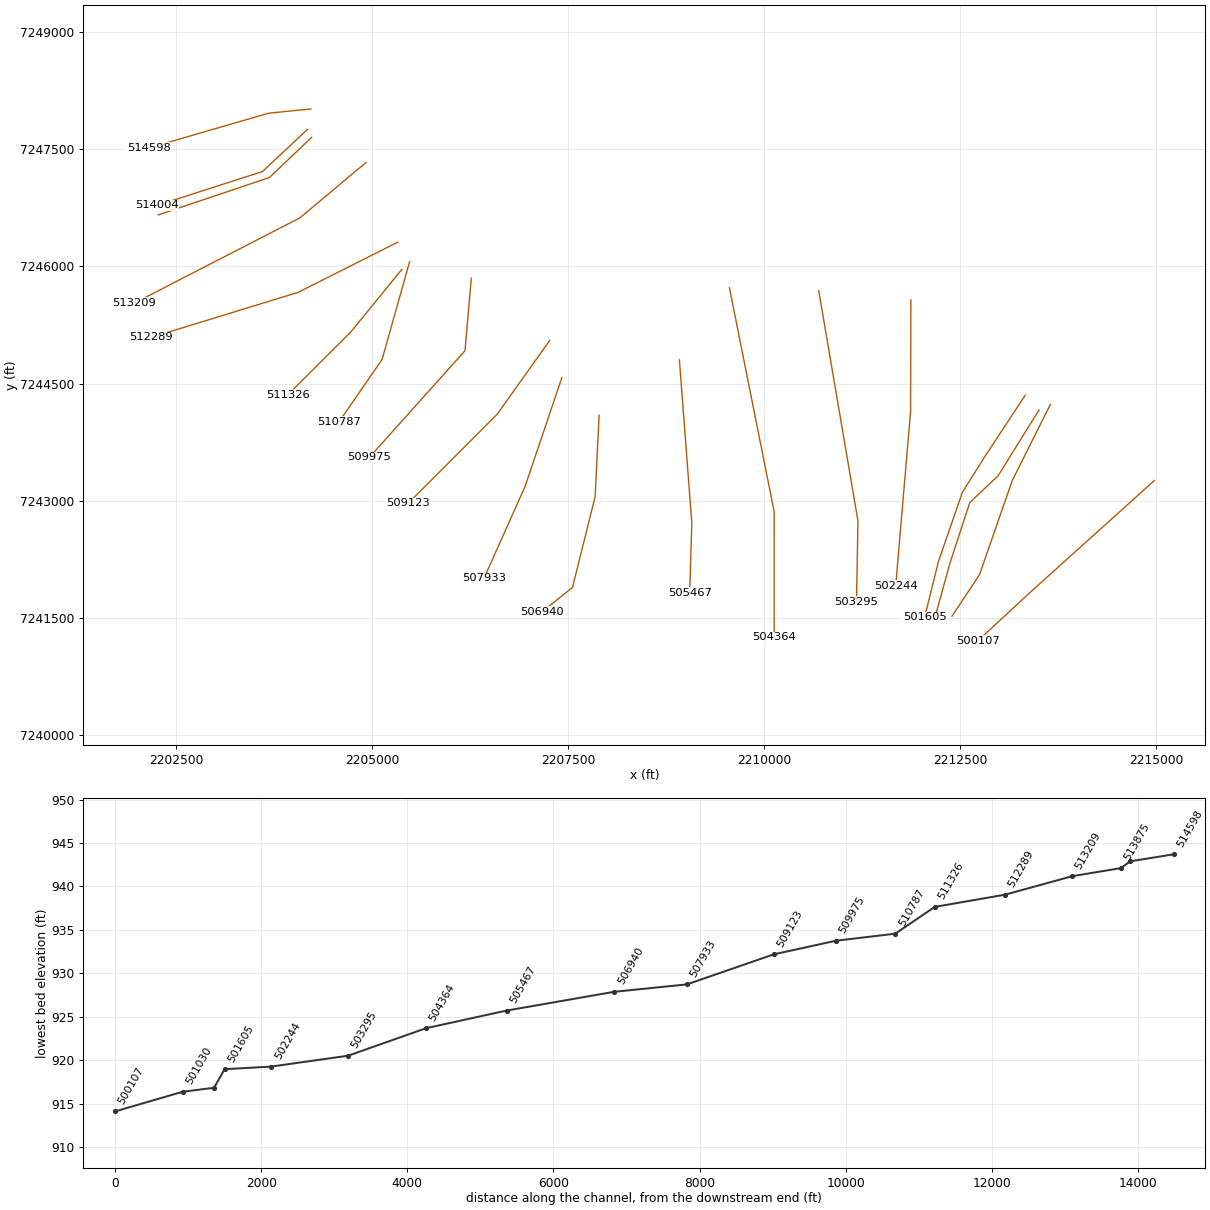
HEC-RAS study Denton Creek.prj: Denton Creek Base Level Engineering

--- Denton Creek.g01 (geometry) --- (continued)

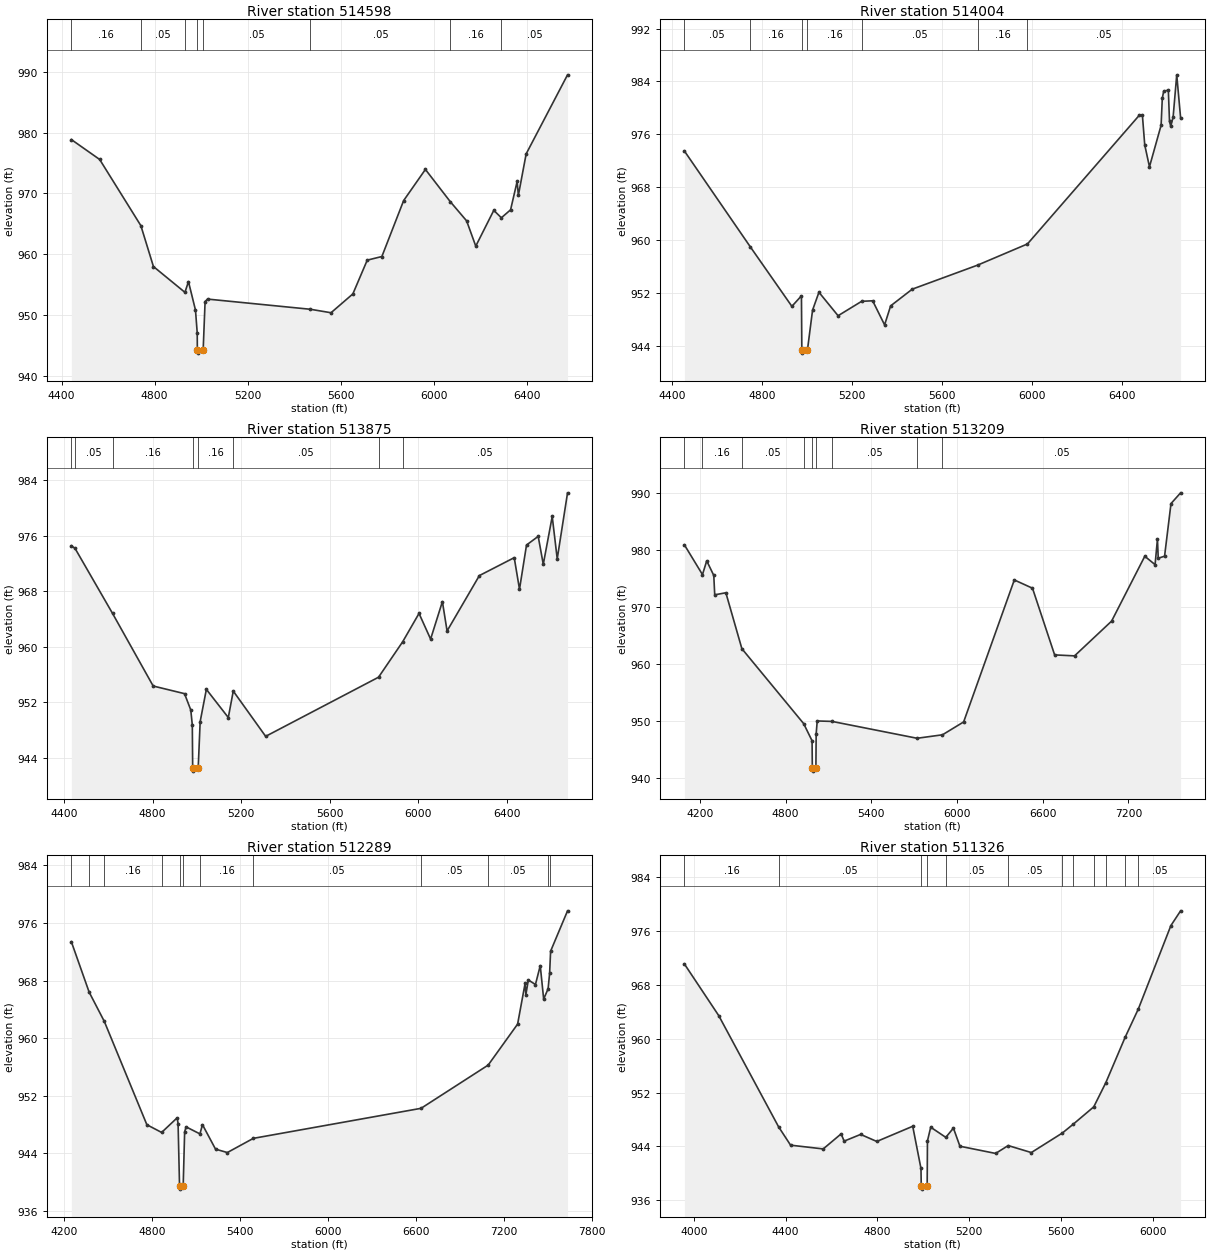
Type RM Length L Ch R = 1 ,514598  ,594,594,594
BEGIN DESCRIPTION:
Denton Creek 250.0
END DESCRIPTION:
XS GIS Cut Line= 3
      2204220.15      7248014.95        2203679.        7247960.
      2202152.34      7247515.47
#Sta/Elev= 30
  4441.9  978.87  4563.7  975.59  4740.9  964.69  4794.9  957.96  4930.4  953.71
  4945.6  955.48  4975.8  950.78  4983.3     947  4983.8   944.2  4986.3   943.7
  5008.8   944.2  5017.1   952.2  5027.5   952.6  5470.4  950.92  5558.7  950.35
  5652.6  953.45  5714.4  959.01  5777.4  959.61  5871.1  968.83  5964.6  973.95
  6071.4  968.65  6141.9  965.48  6181.2  961.32  6258.7  967.21  6291.3  965.99
  6330.9   967.3  6359.2  971.98  6364.4  969.67  6397.9  976.51  6575.9  989.53
#Mann= 8 ,-1 , 0
  4441.9     .16       0  4740.9     .05       0  4930.4     .05       0
  4983.8    .045       0  5008.8     .05       0  5470.4     .05       0
  6071.4     .16       0  6291.3     .05       0
Bank Sta=4983.8,5008.8
XS Rating Curve= 0 ,0
Exp/Cntr=0.3,0.1

Type RM Length L Ch R = 1 ,514004  ,129,129,129
BEGIN DESCRIPTION:
Denton Creek299
END DESCRIPTION:
XS GIS Cut Line= 3
      2204178.61      7247754.93       2203602.6      7247213.87
      2202257.38      7246779.78
#Sta/Elev= 30
  4455.8  973.47  4747.5  959.02  4933.1  949.97  4975.6  951.56  4977.3  943.39
  4979.8  942.89  5002.3  943.39    5025   949.4  5053.3   952.1  5138.3  948.55
    5243  950.73  5291.9  950.81  5344.9  947.16  5371.7  950.04  5467.8  952.57
  5757.6   956.2  5979.4  959.41  6476.9  978.91  6489.8  978.93  6500.3  974.39
  6521.3  971.08    6573  977.37  6578.3  981.45  6584.3   982.5  6605.1  982.69
  6610.3  977.95  6615.9  977.21  6626.4  978.63  6642.4     985  6659.6  978.49
#Mann= 7 ,-1 , 0
  4455.8     .05       0  4747.5     .16       0  4977.3     .07       0
  5002.3     .16       0    5243     .05       0  5757.6     .16       0
  5979.4     .05       0
Bank Sta=4977.3,5002.3
XS Rating Curve= 0 ,0
Exp/Cntr=0.3,0.1

Type RM Length L Ch R = 1 ,513875  ,666,666,666
BEGIN DESCRIPTION:
Denton Creek298
END DESCRIPTION:
XS GIS Cut Line= 3
      2204230.06      7247651.36      2203690.16      7247136.59
       2202273.4      7246658.89
#Sta/Elev= 30
  4432.9  974.57  4449.5   974.2  4619.1  964.82  4802.5  954.37    4944  953.27
  4972.3  950.92  4979.2  948.76  4980.9  942.61  4983.4  942.11  5005.9  942.61
  5014.7  949.24  5042.7  953.89  5141.8  949.83  5164.2  953.64  5310.5  947.12
  5820.4  955.64  5929.3  960.74  6003.2  964.83  6055.5  961.13  6108.8  966.53
  6129.9   962.3  6275.8  970.28  6433.2  972.86    6457  968.31  6488.7  974.68
  6541.5  975.93  6564.4   971.9  6604.8  978.79  6627.4  972.69    6674   982.2
#Mann= 8 ,-1 , 0
  4432.9     .16       0  4449.5     .05       0  4619.1     .16       0
  4980.9     .07       0  5005.9     .16       0  5164.2     .05       0
  5820.4     .16       0  5929.3     .05       0
Bank Sta=4980.9,5005.9
XS Rating Curve= 0 ,0
Exp/Cntr=0.3,0.1

Type RM Length L Ch R = 1 ,513209  ,920,920,920
BEGIN DESCRIPTION:
Denton Creek 247.0
END DESCRIPTION:
XS GIS Cut Line= 3
      2204921.18      7247327.47      2204078.19      7246619.95
      2201969.23      7245530.91
#Sta/Elev= 30
  4091.4  980.91  4217.9  975.69  4247.6  978.11    4297  975.54  4303.6  972.14
  4381.6   972.5  4493.7  962.68  4926.4  949.52  4985.2  946.51    4987  941.68
  4989.5  941.18    5012  941.68  5013.8   947.7  5021.2  949.99    5125  949.91
  5720.6  946.95  5898.3  947.56  6046.4  949.82  6401.2  974.75  6528.5   973.3
  6683.5  961.59    6823  961.42  7082.3  967.52  7314.7  978.91  7386.8  977.44
  7403.3  981.91  7408.9  978.57  7453.2  978.92  7498.2  988.16  7565.5  990.05
#Mann= 9 ,-1 , 0
  4091.4     .05       0  4217.9     .16       0  4493.7     .05       0
  4926.4     .16       0    4987     .07       0    5012     .16       0
    5125     .05       0  5720.6     .16       0  5898.3     .05       0
Bank Sta=4987,5012
XS Rating Curve= 0 ,0
Exp/Cntr=0.3,0.1

Type RM Length L Ch R = 1 ,512289  ,963,963,963
BEGIN DESCRIPTION:
Denton Creek 245.0
END DESCRIPTION:
XS GIS Cut Line= 3
      2205329.04      7246310.02       2204056.2       7245667.4
      2202183.32      7245091.09
#Sta/Elev= 30
  4249.1   973.4  4370.5   966.4  4473.9  962.34  4764.4  947.99  4865.1  946.92
    4971  948.95  4977.3  948.15  4987.2  939.55  4989.7  939.05  5012.2  939.55
  5022.1  947.01  5032.3  947.69  5126.4  946.72  5143.7     948  5232.9   944.6
  5313.4  944.13  5490.8   946.1  6635.2  950.27  7092.9  956.27  7293.8  961.96
    7345  967.62  7350.2  966.05    7367  968.09  7415.6  967.46  7448.3  970.08
  7471.6  965.44  7501.8  966.86  7512.3  969.03    7519  972.09  7634.5  977.69
#Mann= 12 ,-1 , 0
  4249.1     .16       0  4370.5     .05       0  4473.9     .16       0
  4865.1     .05       0  4987.2    .035       0  5012.2     .05       0
  5126.4     .16       0  5490.8     .05       0  6635.2     .05       0
  7092.9     .05       0  7501.8     .16       0  7512.3     .05       0
Bank Sta=4987.2,5012.2
XS Rating Curve= 0 ,0
Exp/Cntr=0.3,0.1

Type RM Length L Ch R = 1 ,511326  ,539,539,539
BEGIN DESCRIPTION:
Denton Creek 244.0
END DESCRIPTION:
XS GIS Cut Line= 3
      2205378.99      7245959.99        2204729.        7245160.
      2203929.02      7244360.02
#Sta/Elev= 30
  3958.8  971.13  4108.2  963.46    4369  946.92  4421.4  944.18  4563.6  943.62
  4641.7  945.86  4654.8  944.78  4726.7  945.78    4797  944.73  4953.6  946.99
  4989.6  940.71  4990.8  938.14  4993.4  937.64  5016.6  938.14  5017.8  944.81
    5032  946.85  5097.8  945.34    5131  946.72  5159.3  944.02  5314.8  942.95
  5369.7  944.12  5470.4  943.08  5605.8  945.99  5653.4  947.31  5742.5  949.88
  5795.2  953.49  5879.1  960.22  5937.1  964.47  6078.5  976.84  6120.9  979.04
#Mann= 12 ,-1 , 0
  3958.8     .16       0    4369     .05       0  4990.8    .035       0
  5016.6     .05       0  5097.8     .05       0  5369.7     .05       0
  5605.8     .05       0  5653.4     .05       0  5742.5     .05       0
  5795.2     .05       0  5879.1     .05       0  5937.1     .05       0
Bank Sta=4990.8,5016.6
XS Rating Curve= 0 ,0
Exp/Cntr=0.3,0.1

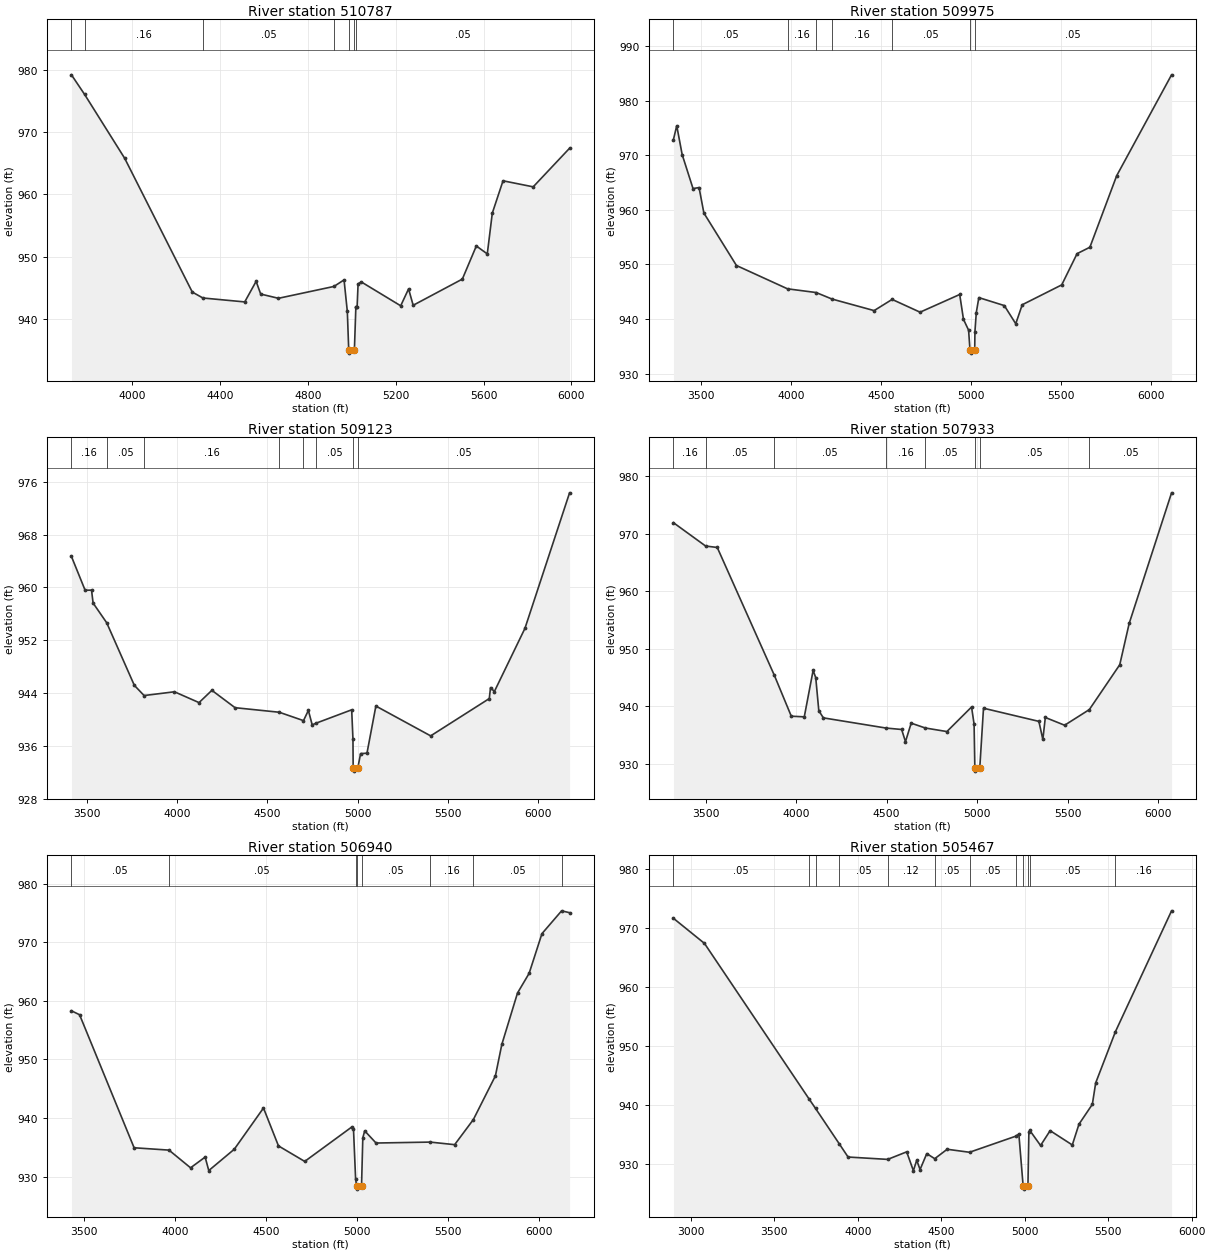
Type RM Length L Ch R = 1 ,510787  ,812,812,812
BEGIN DESCRIPTION:
Denton Creek 243.0
END DESCRIPTION:
XS GIS Cut Line= 3
      2205479.01      7246060.05        2205129.        7244810.
      2204579.03      7244010.04
#Sta/Elev= 30
  3722.7  979.18  3782.6  976.04  3965.3  965.79  4273.1  944.35  4321.4   943.4
    4512  942.77  4563.9  946.07  4584.7  944.03  4665.5  943.35  4918.2  945.25
  4964.4   946.3  4979.3  941.24  4985.7  935.06  4988.3  934.56  5011.5  935.06
  5018.2  941.95  5020.5  941.95  5023.9  941.95  5028.3  945.67  5043.2  945.97
  5222.4  942.15  5258.3  944.86  5279.2  942.23  5503.2  946.43  5566.9  951.74
  5616.8  950.47  5639.7  957.01  5688.5  962.19  5825.9  961.22  5991.6  967.41
#Mann= 7 ,-1 , 0
  3722.7     .05       0  3782.6     .16       0  4321.4     .05       0
  4918.2     .16       0  4985.7     .07       0  5011.5     .16       0
  5020.5     .05       0
Bank Sta=4985.7,5011.5
XS Rating Curve= 0 ,0
Exp/Cntr=0.3,0.1

Type RM Length L Ch R = 1 ,509975  ,852,852,852
BEGIN DESCRIPTION:
Denton Creek 242.0
END DESCRIPTION:
XS GIS Cut Line= 3
       2206266.1      7245848.26      2206185.98      7244921.23
      2204964.74      7243554.17
#Sta/Elev= 30
    3348  972.87  3366.3  975.41  3396.4  970.12  3456.7  963.89  3490.1  964.08
  3516.9  959.41  3697.6   949.8  3980.9  945.53  4139.7  944.85  4227.4  943.66
  4461.4  941.54  4561.3  943.59  4716.3  941.25  4936.2  944.49  4957.1  939.94
  4985.5  937.96  4993.5  934.25  4996.1  933.75  5019.4  934.25  5020.7  937.69
  5028.2  941.17  5042.4  943.92  5183.7  942.46  5247.2  939.13  5283.1  942.61
  5502.2  946.25  5587.4  951.97  5658.5  953.15  5807.3  966.26  6111.6  984.73
#Mann= 7 ,-1 , 0
    3348     .05       0  3980.9     .16       0  4139.7     .05       0
  4227.4     .16       0  4561.3     .05       0  4993.5    .035       0
  5019.4     .05       0
Bank Sta=4993.5,5019.4
XS Rating Curve= 0 ,0
Exp/Cntr=0.3,0.1

Type RM Length L Ch R = 1 ,509123  ,1190,1190,1190
BEGIN DESCRIPTION:
Denton Creek297
END DESCRIPTION:
XS GIS Cut Line= 3
      2207265.31      7245050.51      2206598.02      7244110.44
       2205460.9      7242967.76
#Sta/Elev= 30
    3412   964.7  3487.9  959.58  3523.5   959.6  3532.2  957.64  3607.8  954.65
    3761  945.18  3815.2  943.63  3983.6   944.2  4120.2  942.56  4191.5  944.42
  4320.1  941.79  4565.6   941.1    4700  939.83  4727.1  941.38  4748.3  939.19
  4771.5  939.46  4967.5  941.47  4974.6  937.01  4975.7  932.68  4978.3  932.18
  5001.6  932.68    5017  934.83  5052.4   934.9  5101.8  942.04  5405.9  937.52
  5731.2  943.17  5738.2  944.83  5759.5  944.24  5929.2  953.81  6176.9  974.34
#Mann= 8 ,-1 , 0
    3412     .16       0  3607.8     .05       0  3815.2     .16       0
  4565.6     .05       0    4700     .16       0  4771.5     .05       0
  4975.7     .05       0  5001.6     .05       0
Bank Sta=4975.7,5001.6
XS Rating Curve= 0 ,0
Exp/Cntr=0.3,0.1

Type RM Length L Ch R = 1 ,507933  ,993,993,993
BEGIN DESCRIPTION:
Denton Creek 241.0
END DESCRIPTION:
XS GIS Cut Line= 3
      2207421.08      7244575.45      2206952.91      7243186.66
        2206429.        7242010.
#Sta/Elev= 30
  3321.5  971.92  3499.3  967.86  3563.7  967.61  3879.3  945.38    3973  938.27
  4044.8  938.16  4093.7  946.24  4108.2  944.96  4125.1  939.22  4150.4  937.98
  4496.5  936.21    4583  935.96  4604.2  933.84  4635.8  937.06  4713.7  936.22
  4833.1   935.6  4969.5  939.87  4983.5  936.88  4987.7  929.22  4990.4  928.72
  5014.8  929.22  5035.5  939.66  5341.7  937.37  5363.6  934.22  5377.2  938.05
    5484   936.7  5620.5  939.42  5788.7  947.22  5840.7  954.39  6075.1  977.11
#Mann= 8 ,-1 , 0
  3321.5     .16       0  3499.3     .05       0  3879.3     .05       0
  4496.5     .16       0  4713.7     .05       0  4987.7     .05       0
  5014.8     .05       0  5620.5     .05       0
Bank Sta=4987.7,5014.8
XS Rating Curve= 0 ,0
Exp/Cntr=0.3,0.1

Type RM Length L Ch R = 1 ,506940  ,1473,1473,1473
BEGIN DESCRIPTION:
Denton Creek 239.0
END DESCRIPTION:
XS GIS Cut Line= 4
      2207895.94      7244094.12      2207845.71       7243054.8
      2207557.12      7241892.46      2207167.93      7241577.87
#Sta/Elev= 30
  3431.8  958.31  3476.5  957.64  3776.3  934.93  3968.1  934.53  4086.7  931.51
  4166.8  933.34  4186.8  931.04    4327  934.68  4487.6  941.72    4570  935.25
  4714.3   932.6  4971.9  938.45  4982.4  938.15    4994  929.67  4999.5  928.37
  5002.2  927.87  5026.6  928.37  5033.7  936.62    5044  937.82  5106.4  935.74
    5404   935.9  5538.6  935.46  5641.5  939.75  5762.7  947.21  5797.9  952.57
  5884.2  961.35  5948.1  964.71  6018.5  971.48  6126.7  975.38  6170.4  975.06
#Mann= 8 ,-1 , 0
  3431.8     .05       0  3968.1     .05       0    4994     .05       0
  4999.5    .035       0  5026.6     .05       0    5404     .16       0
  5641.5     .05       0  6126.7     .05       0
Bank Sta=4999.5,5026.6
XS Rating Curve= 0 ,0
Exp/Cntr=0.3,0.1

Type RM Length L Ch R = 1 ,505467  ,1103,1103,1103
BEGIN DESCRIPTION:
Denton Creek 237.0
END DESCRIPTION:
XS GIS Cut Line= 3
      2208920.16      7244803.14        2209079.        7242710.
      2209051.29       7241825.7
#Sta/Elev= 30
  2895.7   971.7  3081.5  967.44  3706.3   941.1    3747  939.41  3889.6  933.38
  3941.8  931.16  4179.1  930.76  4292.9  932.04    4333  928.84    4353  930.61
  4373.1  929.04  4413.2  931.74  4460.9  930.88  4535.4  932.48  4669.4  931.97
  4945.4  934.69  4964.8  935.06  4990.6  926.21  4993.4  925.71  5019.2  926.21
  5024.9   935.4  5030.3  935.68  5094.9  933.12  5152.2  935.64    5285  933.21
    5325  936.74  5405.1  940.11  5425.1  943.75  5543.4  952.45  5879.6  972.97
#Mann= 12 ,-1 , 0
  2895.7     .05       0  3706.3     .05       0    3747     .05       0
  3889.6     .05       0  4179.1     .12       0  4460.9     .05       0
  4669.4     .05       0  4945.4     .16       0  4990.6     .07       0
  5019.2     .16       0  5030.3     .05       0  5543.4     .16       0
Bank Sta=4990.6,5019.2
XS Rating Curve= 0 ,0
Exp/Cntr=0.3,0.1

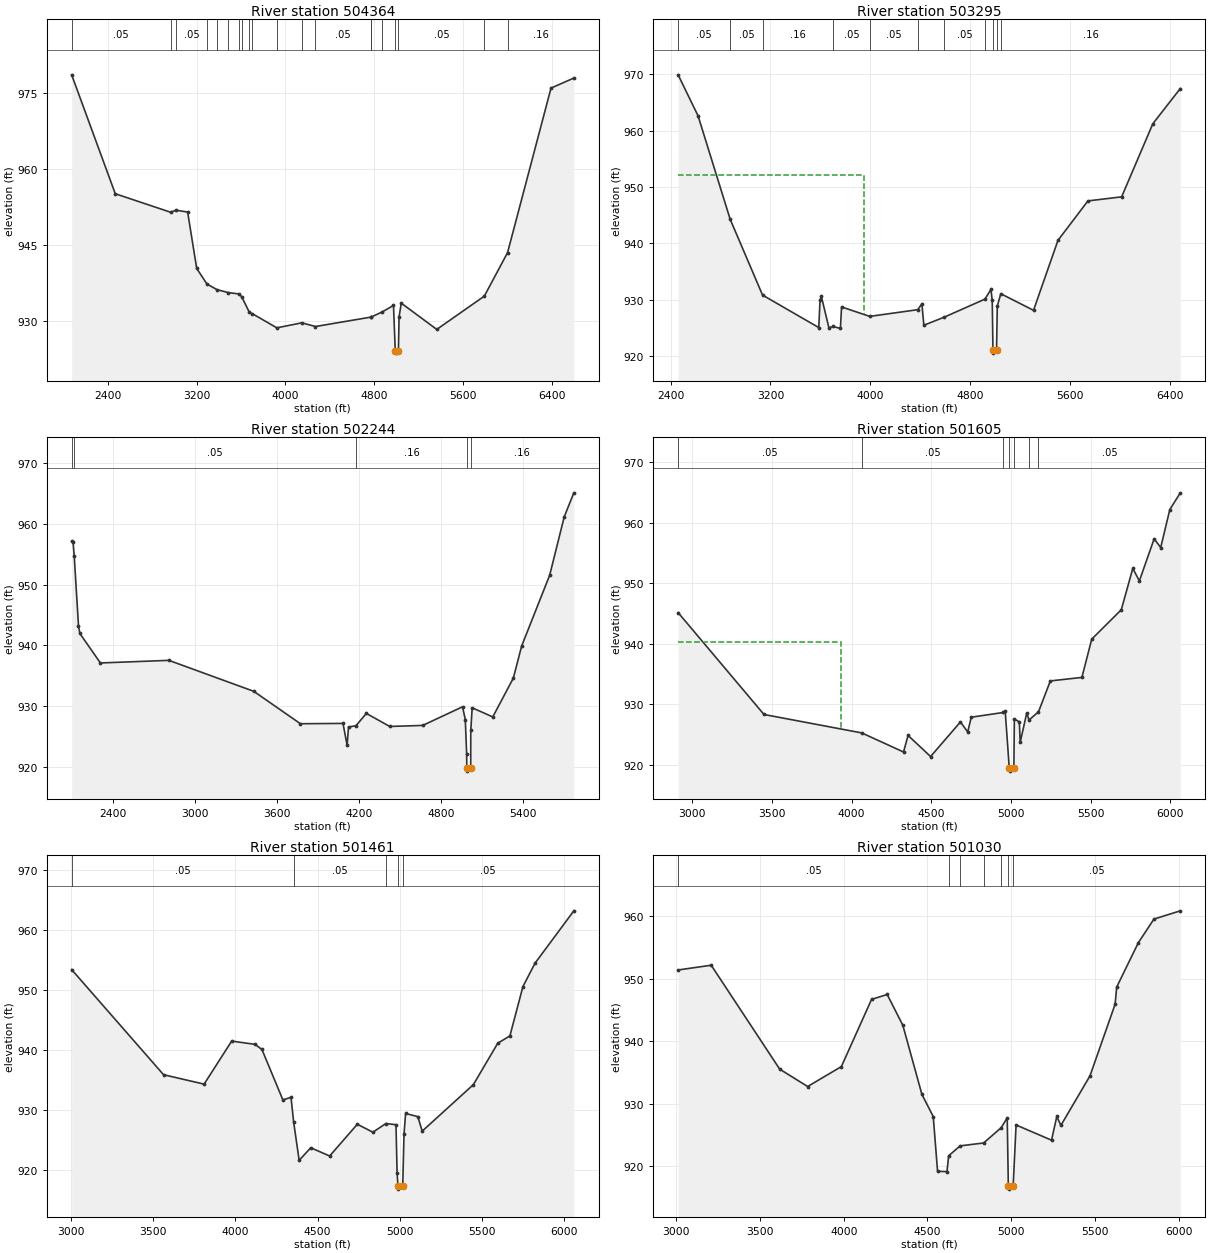
Type RM Length L Ch R = 1 ,504364  ,1069,1069,1069
BEGIN DESCRIPTION:
Denton Creek 235.0
END DESCRIPTION:
XS GIS Cut Line= 3
      2209558.47       7245725.7        2210129.        7242860.
      2210128.73      7241254.34
#Sta/Elev= 30
  2072.2  978.49  2465.5  955.07  2965.3  951.42  3013.5  951.83    3118  951.46
  3199.6  940.36  3292.4  937.28  3383.2  936.18  3482.4  935.61  3581.6  935.33
  3605.7  934.77  3674.8   931.7    3702  931.44    3922  928.66  4147.8  929.65
  4270.4  928.92  4771.8  930.78  4772.1  930.78  4870.9  931.78  4973.8  933.07
  4989.8  924.18  4992.6  923.68  5018.4  924.18  5024.1  930.82  5044.1  933.52
  5364.1  928.35  5792.9  934.91  6002.2  943.47  6394.1  975.88  6599.8  977.85
#Mann= 20 ,-1 , 0
  2072.2     .05       0  2965.3     .05       0  3013.5     .05       0
  3292.4     .05       0  3383.2     .05       0  3482.4     .12       0
  3581.6     .05       0  3605.7     .12       0  3674.8     .05       0
    3702     .12       0    3922     .05       0  4147.8     .16       0
  4270.4     .05       0  4771.8     .05       0  4772.1     .05       0
  4870.9     .05       0  4989.8     .05       0  5018.4     .05       0
  5792.9     .05       0  6002.2     .16       0
Bank Sta=4989.8,5018.4
XS Rating Curve= 0 ,0
Exp/Cntr=0.3,0.1

Type RM Length L Ch R = 1 ,503295  ,1051,1051,1051
BEGIN DESCRIPTION:
Denton Creek 233.0
END DESCRIPTION:
XS GIS Cut Line= 3
      2210696.98      7245691.02      2211197.84      7242742.37
        2211179.      7241710.03
#Sta/Elev= 30
  2460.4  969.91  2620.2  962.63  2877.4  944.27    3137  930.81  3587.3  925.05
  3597.5  929.87  3607.6  930.61  3668.5  925.01  3701.4  925.24  3760.6  924.89
  3769.9  928.71  3995.4  927.03  4379.8  928.22  4413.6  929.25  4429.2  925.46
  4594.1  926.91  4918.9   930.1  4966.8  931.82    4977  929.87  4982.9  921.01
  4985.7  920.51  5011.5  921.01  5017.5  928.86  5045.8  931.05  5307.8  928.11
  5503.7  940.53  5743.7  947.53  6013.7  948.25  6263.8  961.23  6483.8  967.48
#Mann= 11 ,-1 , 0
  2460.4     .05       0  2877.4     .05       0    3137     .16       0
  3701.4     .05       0  3995.4     .05       0  4379.8     .16       0
  4594.1     .05       0  4918.9     .05       0  4982.9    .035       0
  5011.5     .05       0  5045.8     .16       0
#XS Ineff= 2 , 0
       0  3949.8  952.05               0
Permanent Ineff=
       F       F
Bank Sta=4982.9,5011.5
XS Rating Curve= 0 ,0
Exp/Cntr=0.3,0.1

Type RM Length L Ch R = 1 ,502244  ,639,639,639
BEGIN DESCRIPTION:
Denton Creek 231.0
END DESCRIPTION:
XS GIS Cut Line= 3
       2211872.4      7245570.01      2211868.76      7244141.42
        2211679.      7241909.97
#Sta/Elev= 30
  2101.2  957.16  2111.2  957.09  2120.1  954.67  2151.2  943.21  2161.2  941.94
  2311.2  937.08  2811.2  937.51  3431.2  932.41  3772.1  927.07  4083.2  927.12
  4113.3  923.51  4123.4  926.52  4178.4  926.75  4253.8  928.77  4424.4  926.62
  4665.3  926.79  4956.3  929.86  4976.4  927.76  4986.5  922.06  4987.5  919.76
  4990.3  919.26  5016.1  919.76  5016.6  925.99  5026.6   929.7  5177.1  928.19
  5327.7   934.6  5387.9  939.86  5592.9  951.54    5699  961.15  5769.3  965.11
#Mann= 5 ,-1 , 0
  2101.2     .05       0  2120.1     .05       0  4178.4     .16       0
  4987.5     .07       0  5016.1     .16       0
Bank Sta=4987.5,5016.1
XS Rating Curve= 0 ,0
Exp/Cntr=0.3,0.1

Type RM Length L Ch R = 1 ,501605  ,144,144,144
BEGIN DESCRIPTION:
Denton Creek296
END DESCRIPTION:
XS GIS Cut Line= 5
      2213331.71       7244351.7      2212801.37      7243542.46
      2212529.17      7243107.47      2212224.14      7242222.03
      2212048.28      7241510.73
#Sta/Elev= 30
  2912.1  945.13  3450.7  928.31  4063.7  925.27    4326  922.12  4354.4  924.85
  4495.7  921.37    4683  927.08  4728.6  925.42  4750.7  927.86  4951.2  928.64
  4963.9  928.82  4989.2  919.46    4992  918.96    5018  919.46  5021.1  927.57
  5052.3  927.09  5057.6  923.71  5098.7  928.54  5113.4   927.4  5172.5  928.75
  5246.8  933.85  5444.7  934.43  5506.5  940.75  5691.9   945.6    5764  952.43
  5805.2  950.36  5897.9  957.31  5939.1  955.87  5996.2  962.14    6062   964.9
#Mann= 7 ,-1 , 0
  2912.1     .05       0  4063.7     .05       0  4951.2     .05       0
  4989.2    .035       0    5018     .05       0  5113.4     .16       0
  5172.5     .05       0
#XS Ineff= 2 , 0
       0  3936.5   940.2               0
Permanent Ineff=
       F       F
Bank Sta=4989.2,5018
XS Rating Curve= 0 ,0
Exp/Cntr=0.3,0.1

Type RM Length L Ch R = 1 ,501461  ,431,431,431
BEGIN DESCRIPTION:
Denton Creek295
END DESCRIPTION:
XS GIS Cut Line= 5
      2213507.19      7244162.61      2212984.34      7243318.74
      2212624.41      7242978.33      2212369.34      7242197.16
      2212171.81      7241477.04
#Sta/Elev= 30
  3003.4  953.39  3562.7  935.88  3809.6  934.31  3977.4  941.48  4119.2  940.94
  4161.7  940.08  4289.1  931.68  4338.5  932.11  4354.8  927.95  4388.2  921.62
  4458.6  923.71  4573.9  922.34  4742.2  927.63  4836.9   926.3  4916.2  927.75
  4977.5  927.55  4984.2  919.55  4989.7  917.32  4992.6  916.82  5018.5  917.32
  5026.3  925.97    5036  929.42  5110.4   928.9    5137  926.48  5448.6  934.23
  5596.8  941.12  5670.9  942.35  5750.2  950.57  5824.3  954.48    6060  963.18
#Mann= 5 ,-1 , 0
  3003.4     .05       0  4354.8     .05       0  4916.2     .05       0
  4989.7    .035       0  5018.5     .05       0
Bank Sta=4989.7,5018.5
XS Rating Curve= 0 ,0
Exp/Cntr=0.3,0.1

Type RM Length L Ch R = 1 ,501030  ,923,923,923
BEGIN DESCRIPTION:
Denton Creek 229.0
END DESCRIPTION:
XS GIS Cut Line= 4
      2213651.65      7244232.97      2213166.06      7243259.52
      2212747.48      7242052.85      2212397.21       7241523.5
#Sta/Elev= 30
  3010.9  951.41  3208.5  952.17  3617.7  935.55  3784.7  932.77  3986.1  935.96
  4166.5  946.71  4259.9  947.49  4353.3  942.56  4467.3   931.5  4534.9  927.97
  4560.7  919.21  4616.9  919.16  4626.9  921.69  4695.6  923.28  4835.7  923.74
  4940.5  926.18  4976.8  927.76  4983.5  916.86  4986.4  916.36  5012.3  916.86
  5029.7  926.62  5241.4  924.19  5273.1  927.99  5297.3  926.55  5471.1  934.47
  5621.5  945.95  5630.6  948.67    5760  955.77  5853.2  959.55  6010.7  960.87
#Mann= 7 ,-1 , 0
  3010.9     .05       0  4626.9     .12       0  4695.6     .05       0
  4835.7     .16       0  4940.5     .05       0  4983.5    .035       0
  5012.3     .05       0
Bank Sta=4983.5,5012.3
XS Rating Curve= 0 ,0
Exp/Cntr=0.3,0.1

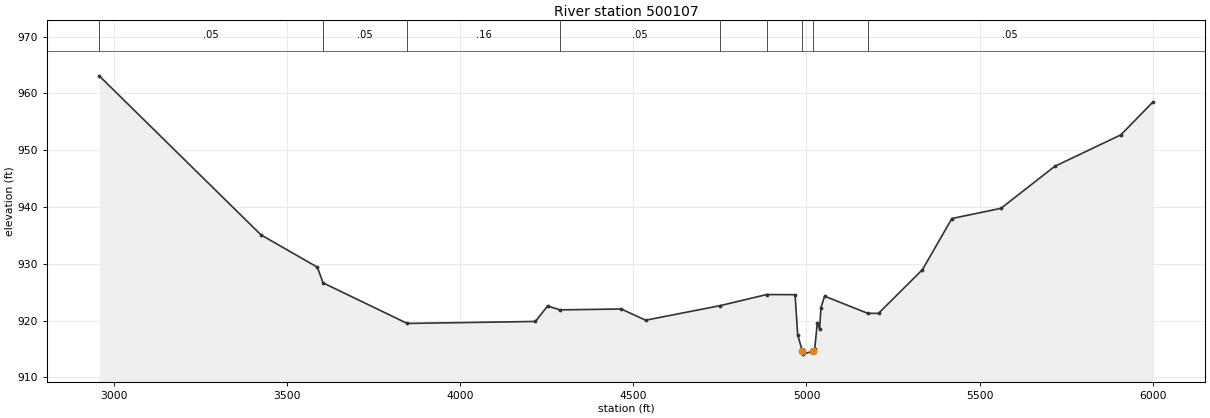
Type RM Length L Ch R = 1 ,500107  ,1393,1393,1393
BEGIN DESCRIPTION:
Denton Creek 227.0
END DESCRIPTION:
XS GIS Cut Line= 3
      2214978.98      7243259.98        2213429.        7241860.
      2212728.98      7241209.99
#Sta/Elev= 30
  2956.5  963.08  3423.9  935.09  3586.8   929.4  3603.3  926.64  3846.4   919.5
  4216.8  919.85  4251.9  922.57  4287.8  921.89  4464.9  922.04  4535.1  920.07
  4749.5  922.62  4885.4  924.59    4967  924.56  4974.5  917.54    4988   914.6
  4990.9   914.1  5017.8   914.6  5023.8  915.03  5031.3  919.63    5038  918.49
  5041.8  922.29  5052.2   924.3    5177  921.28  5208.1  921.28  5335.1  928.97
  5420.1  937.97  5561.9  939.76  5717.2  947.15  5908.3  952.69  6000.4  958.44
#Mann= 9 ,-1 , 0
  2956.5     .05       0  3603.3     .05       0  3846.4     .16       0
  4287.8     .05       0  4749.5     .05       0  4885.4     .16       0
    4988     .07       0  5017.8     .16       0    5177     .05       0
Bank Sta=4988,5017.8
XS Rating Curve= 0 ,0
Exp/Cntr=0.3,0.1