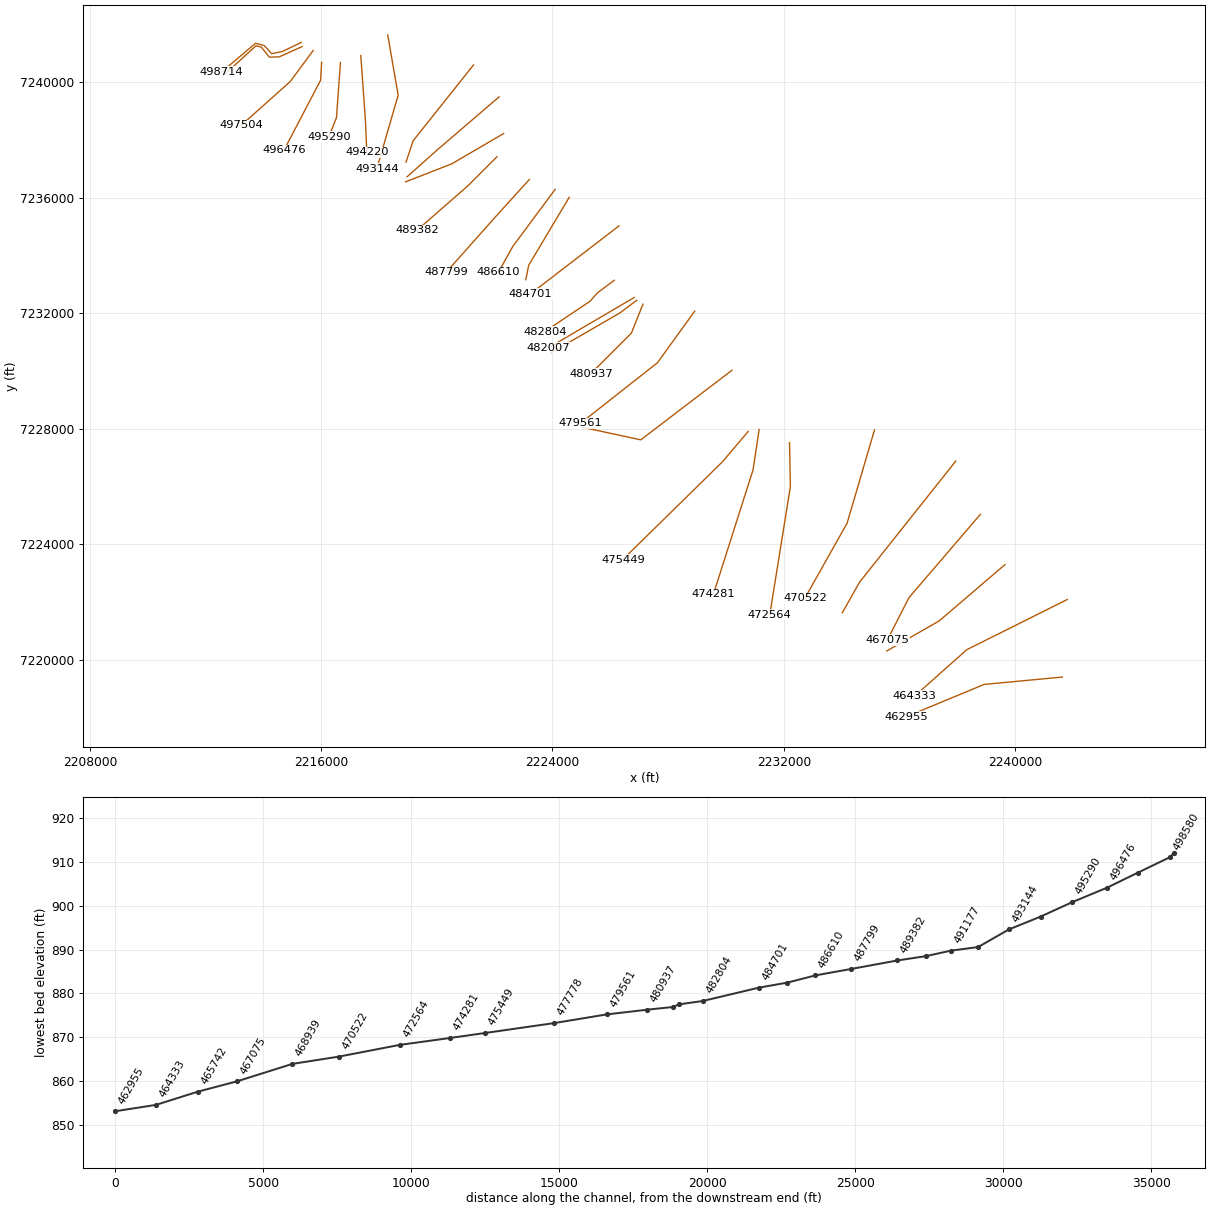
HEC-RAS study Denton Creek.prj: Denton Creek Base Level Engineering

--- Denton Creek.g01 (geometry) --- (continued)

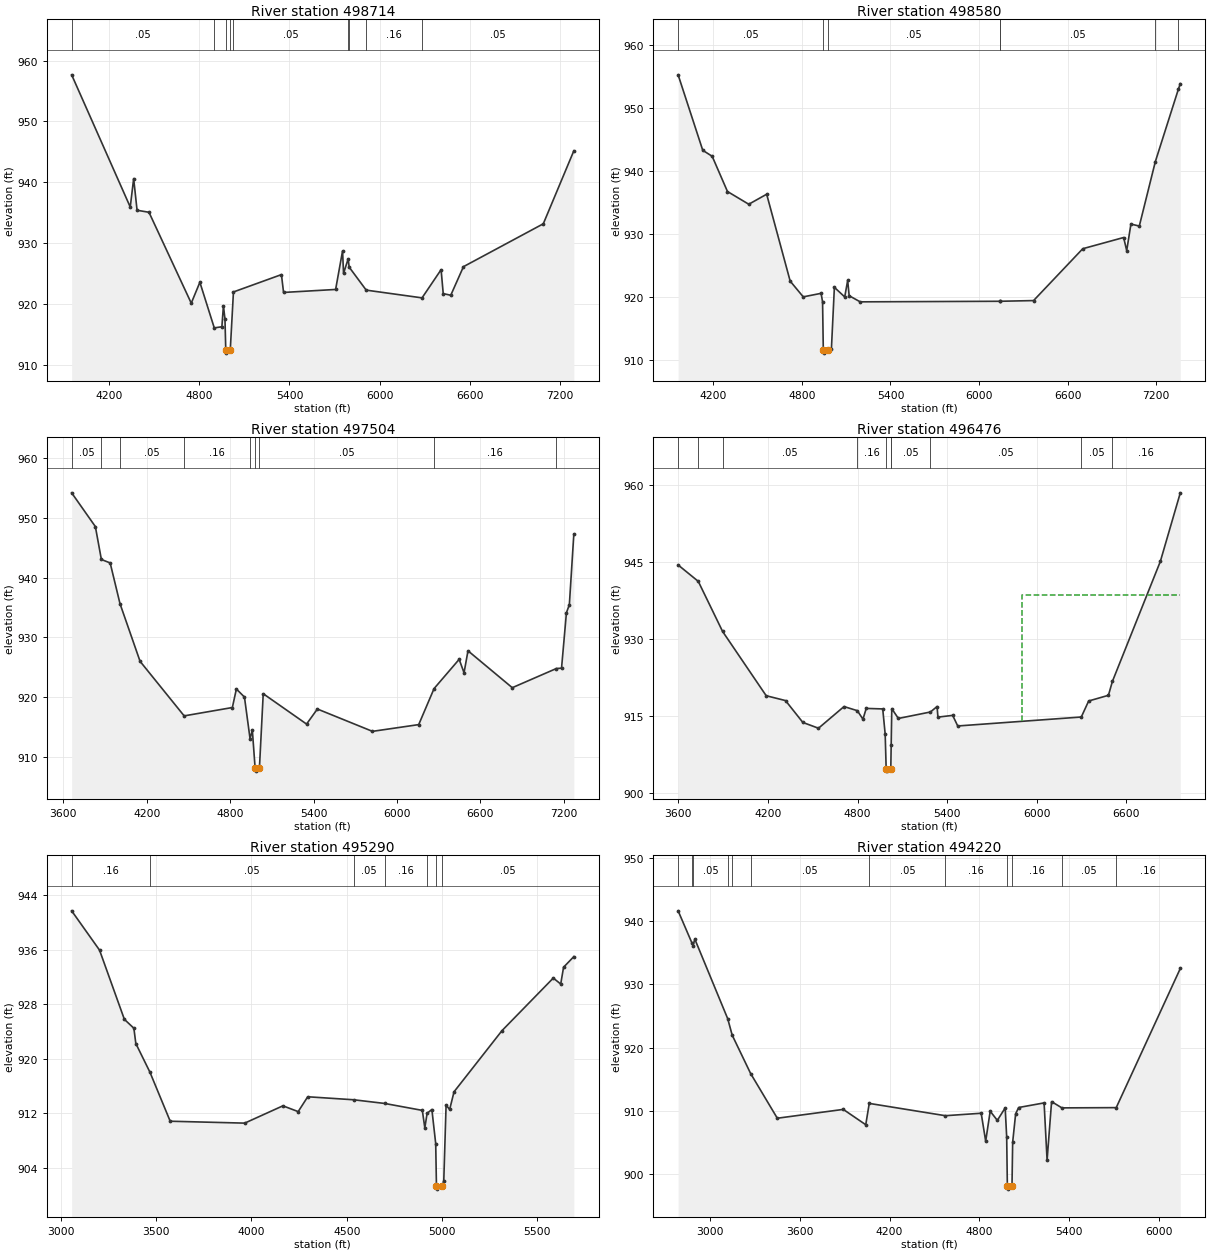
Type RM Length L Ch R = 1 ,498714  ,134,134,134
BEGIN DESCRIPTION:
Denton Creek294
END DESCRIPTION:
XS GIS Cut Line= 6
      2215313.35      7241363.98      2214651.11      7241049.36
       2214286.1      7240975.12      2214031.35      7241258.89
      2213731.66      7241335.95      2212557.34      7240343.93
#Sta/Elev= 30
  3949.4  957.66  4339.7  935.96  4362.4  940.63  4385.1  935.43  4464.4   935.1
    4746  920.18  4803.4  923.61  4899.3  916.12    4950  916.31  4960.3  919.75
  4970.5  917.59  4975.9  912.48  4978.9  911.98  5005.8  912.48    5027  922.02
  5346.6  924.87  5360.8  921.94  5707.5  922.43  5753.7  928.75  5760.3  925.07
  5791.1  927.46  5797.6   926.1  5911.3  922.32  6283.1  921.05    6410  925.68
  6424.2  921.75  6474.4  921.48  6558.9  926.17  7090.7  933.21  7294.1  945.19
#Mann= 9 ,-1 , 0
  3949.4     .05       0  4899.3     .16       0  4975.9     .07       0
  5005.8     .16       0    5027     .05       0  5791.1     .16       0
  5797.6     .05       0  5911.3     .16       0  6283.1     .05       0
Bank Sta=4975.9,5005.8
XS Rating Curve= 0 ,0
Exp/Cntr=0.3,0.1

Type RM Length L Ch R = 1 ,498580  ,1076,1076,1076
BEGIN DESCRIPTION:
Denton Creek293
END DESCRIPTION:
XS GIS Cut Line= 6
      2215341.07      7241221.35      2214552.81      7240866.06
      2214207.26      7240855.47      2213932.08      7241202.57
      2213745.62      7241248.76      2212597.06      7240200.27
#Sta/Elev= 30
  3961.6  955.26  4128.5  943.28  4192.4  942.33  4295.9  936.74  4440.2  934.72
  4561.4  936.31  4720.7  922.52  4809.2  920.02  4930.1  920.58  4940.1  919.23
  4945.1  911.59  4948.1  911.09  4975.1  911.59  5000.1  911.81  5020.1  921.53
  5090.2  920.01  5110.2  922.63  5120.2   920.2  5195.1  919.23  6140.1  919.32
  6140.2  919.32  6369.4  919.43  6702.6  927.66  6979.5  929.44  7000.3  927.36
  7028.9  931.57  7085.7  931.26  7194.1  941.47  7350.1  952.96  7363.4  953.86
#Mann= 7 ,-1 , 0
  3961.6     .05       0  4945.1    .035       0  4975.1     .05       0
  6140.1     .16       0  6140.2     .05       0  7194.1     .16       0
  7350.1     .05       0
Bank Sta=4945.1,4975.1
XS Rating Curve= 0 ,0
Exp/Cntr=0.3,0.1

Type RM Length L Ch R = 1 ,497504  ,1028,1028,1028
BEGIN DESCRIPTION:
Denton Creek 223.0
END DESCRIPTION:
XS GIS Cut Line= 3
      2215727.56      7241089.38        2214929.        7240010.
      2213234.93      7238498.83
#Sta/Elev= 30
  3659.8  954.18  3830.4  948.53  3873.6  943.02  3936.9  942.44  4007.7  935.61
  4151.9  925.97  4469.2  916.83  4815.9  918.23  4844.9  921.33    4903  919.98
  4943.2  913.02  4959.7  914.43  4979.7  908.08  4982.7  907.58  5010.7  908.08
    5038  920.54  5349.8  915.46  5427.6  917.98  5823.9  914.24  6156.6  915.37
    6267   921.4  6447.6   926.3  6482.7  924.05  6511.1  927.73  6829.7  921.55
  7146.8  924.76  7184.1  924.82  7219.3  934.11  7240.3  935.43  7272.6  947.29
#Mann= 9 ,-1 , 0
  3659.8     .05       0  3873.6     .16       0  4007.7     .05       0
  4469.2     .16       0  4943.2     .05       0  4979.7    .035       0
  5010.7     .05       0    6267     .16       0  7146.8     .05       0
Bank Sta=4979.7,5010.7
XS Rating Curve= 0 ,0
Exp/Cntr=0.3,0.1

Type RM Length L Ch R = 1 ,496476  ,1186,1186,1186
BEGIN DESCRIPTION:
Denton Creek 221.0
END DESCRIPTION:
XS GIS Cut Line= 3
      2216016.56      7240678.89      2215981.47      7240059.61
      2214710.65      7237629.17
#Sta/Elev= 30
  3598.1  944.46    3733  941.26  3895.8  931.48  4187.9  918.92  4317.3  917.97
  4433.4   913.7  4538.1  912.57    4709   916.8  4798.1     916  4835.9  914.34
  4857.9  916.44  4968.3  916.34  4984.7  911.41  4991.3  904.69  4994.3  904.19
  5022.3  904.69  5024.9   909.3  5028.9  916.39    5073  914.48  5287.5  915.74
  5332.3  916.81  5337.9  914.74  5436.7  915.08  5470.5  913.01    6298  914.76
  6347.3  917.89  6479.7     919  6506.1   921.7  6827.3  945.15    6961  958.55
#Mann= 10 ,-1 , 0
  3598.1     .05       0    3733     .16       0  3895.8     .05       0
  4798.1     .16       0  4991.3     .07       0  5022.3     .16       0
  5024.9     .05       0  5287.5     .05       0    6298     .05       0
  6506.1     .16       0
#XS Ineff= 2 , 0
       0                  5898.7       0  938.66
Permanent Ineff=
       F       F
Bank Sta=4991.3,5022.3
XS Rating Curve= 0 ,0
Exp/Cntr=0.3,0.1

Type RM Length L Ch R = 1 ,495290  ,1070,1070,1070
BEGIN DESCRIPTION:
Denton Creek 219.0
END DESCRIPTION:
XS GIS Cut Line= 3
      2216667.97      7240675.99        2216529.        7238760.
      2216263.56      7238096.01
#Sta/Elev= 30
  3056.2  941.71  3202.6  935.94  3332.9  925.78  3382.8  924.47  3393.1  922.23
  3467.1  918.02  3573.5  910.82  3964.6  910.54  4165.1  913.08  4245.3  912.23
  4295.4  914.41  4536.3  913.97    4699  913.43    4897  912.41  4910.1  909.84
  4922.1  911.99  4947.1  912.54  4967.2  907.54  4971.1  901.35  4974.1  900.85
  5002.1  901.35  5009.5  902.01  5021.7  913.17  5040.5  912.55  5063.4  915.14
  5315.2  924.12  5584.5  931.84  5623.4  930.96  5638.4  933.43  5692.3  934.99
#Mann= 7 ,-1 , 0
  3056.2     .16       0  3467.1     .05       0  4536.3     .05       0
    4699     .16       0  4922.1     .05       0  4971.1    .035       0
  5002.1     .05       0
Bank Sta=4971.1,5002.1
XS Rating Curve= 0 ,0
Exp/Cntr=0.3,0.1

Type RM Length L Ch R = 1 ,494220  ,1076,1076,1076
BEGIN DESCRIPTION:
Denton Creek 217.0
END DESCRIPTION:
XS GIS Cut Line= 3
      2217370.71      7240911.62        2217529.        7238710.
        2217579.      7237559.99
#Sta/Elev= 30
  2785.6  941.67  2879.3   936.5  2885.4  936.17  2897.5  937.18  3117.4  924.56
  3147.2  921.96  3270.7  915.87  3448.9  908.79  3890.1  910.19  4040.4  907.76
  4063.8  911.14  4572.9  909.19  4812.4  909.58  4842.5  905.15  4872.6   909.9
  4920.4  908.45  4972.8  910.43  4982.9  905.82  4987.4  898.05  4990.4  897.55
  5018.4  898.05  5022.9  904.99  5042.9   909.5    5063  910.49  5233.1  911.22
  5253.1  902.15  5283.2  911.42  5352.2  910.43  5715.5  910.47    6144  932.53
#Mann= 12 ,-1 , 0
  2785.6     .05       0  2879.3     .16       0  2885.4     .05       0
  3117.4     .16       0  3147.2     .05       0  3270.7     .05       0
  4063.8     .05       0  4572.9     .16       0  4987.4     .07       0
  5018.4     .16       0  5352.2     .05       0  5715.5     .16       0
Bank Sta=4987.4,5018.4
XS Rating Curve= 0 ,0
Exp/Cntr=0.3,0.1

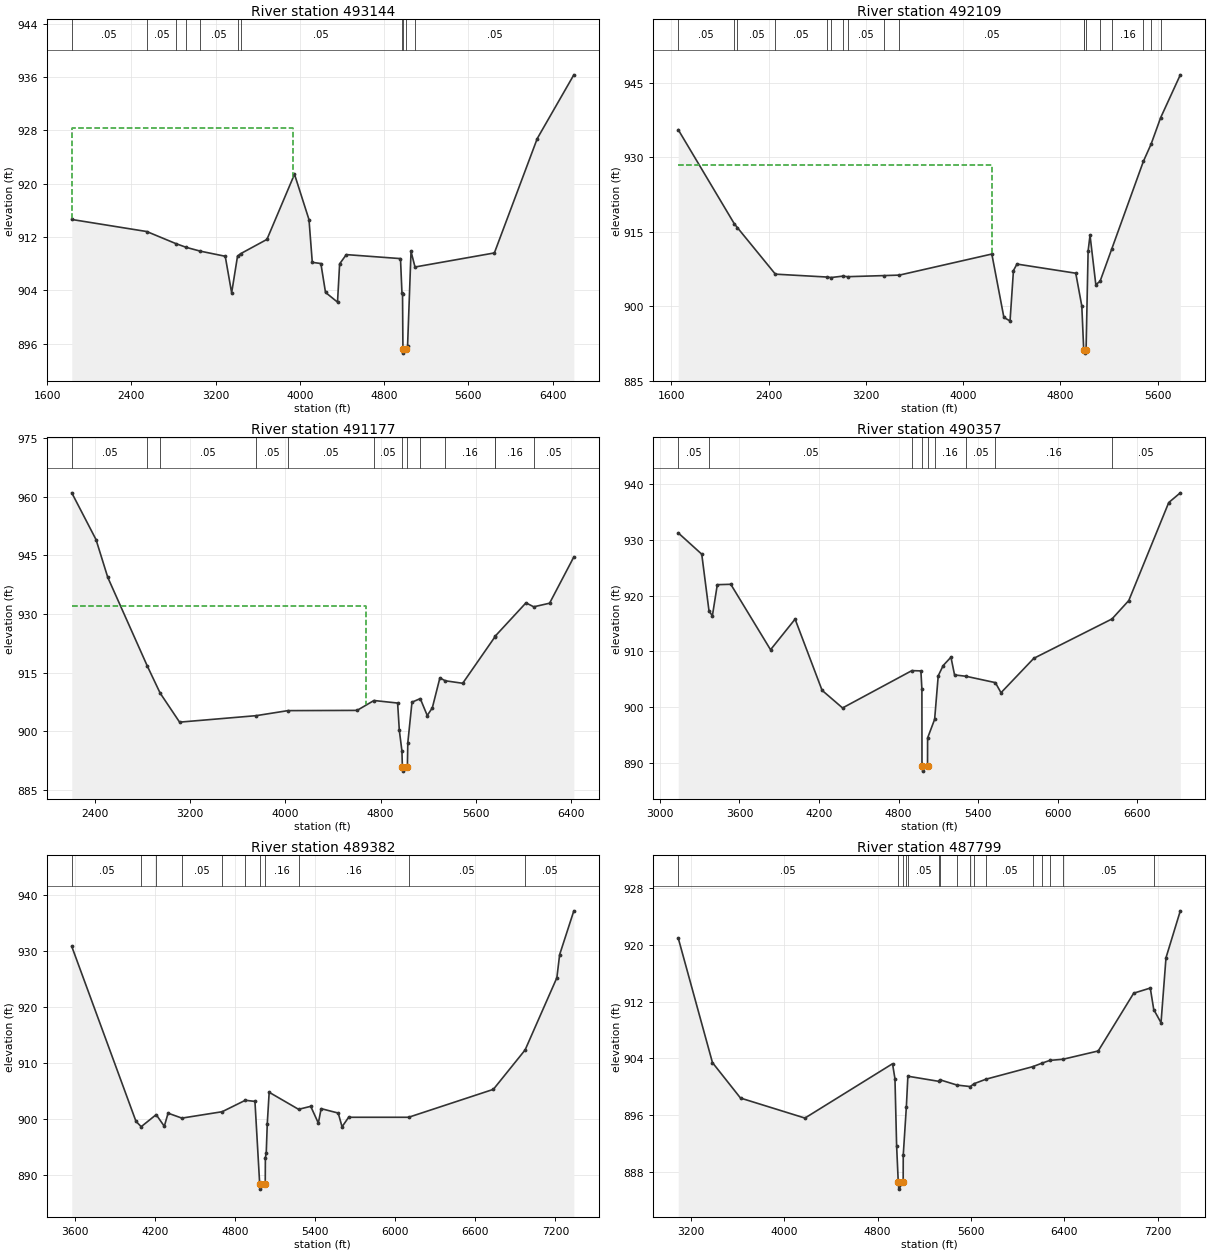
Type RM Length L Ch R = 1 ,493144  ,1035,1035,1035
BEGIN DESCRIPTION:
Denton Creek 216.0
END DESCRIPTION:
XS GIS Cut Line= 4
      2218302.34      7241625.27      2218664.54      7239540.65
        2218379.        7238560.      2217926.31       7236995.3
#Sta/Elev= 30
  1834.8  914.65    2547  912.84  2824.4  911.02  2923.2  910.46  3054.4   909.9
  3291.6  909.13  3352.5  903.64  3408.2  909.14  3436.9  909.51  3687.4  911.66
  3949.1  921.44  4086.7  914.63    4118  908.22  4199.5  908.04  4243.5  903.71
  4357.5  902.25  4377.5  907.99  4440.9  909.38  4955.3  908.78  4969.1  903.68
  4974.6  903.48  4978.5   895.2  4981.5   894.6  5009.5   895.2  5022.4  895.65
  5055.3  909.85    5093  907.52  5846.5  909.63  6253.5  926.79  6600.9  936.35
#Mann= 11 ,-1 , 0
  1834.8     .05       0    2547     .05       0  2824.4     .05       0
  2923.2     .05       0  3054.4     .05       0  3408.2     .05       0
  3436.9     .05       0  4969.1     .16       0  4978.5     .07       0
  5009.5     .16       0    5093     .05       0
#XS Ineff= 2 , 0
       0  3934.6  928.37               0
Permanent Ineff=
       F       F
Bank Sta=4978.5,5009.5
XS Rating Curve= 0 ,0
Exp/Cntr=0.3,0.1

Type RM Length L Ch R = 1 ,492109  ,932,932,932
BEGIN DESCRIPTION:
Denton Creek 214.0
END DESCRIPTION:
XS GIS Cut Line= 3
      2221268.32      7240585.05        2219179.        7237960.
      2218934.95       7237225.4
#Sta/Elev= 30
  1657.4  935.57  2117.9  916.66  2143.8  915.86  2456.2  906.49  2879.6  905.91
  2914.8  905.81  3010.4  906.09  3050.1  905.98  3348.5   906.2  3476.7   906.3
  4236.4  910.54  4335.7  897.77  4386.2  897.07  4414.2  907.21    4443  908.52
  4926.7  906.68  4976.4  900.07  4992.2  891.19  4994.4  891.05  5001.8  890.59
  5011.4  891.19  5028.3  911.15    5044  914.32  5091.6  904.38  5126.6  905.05
  5222.7  911.56  5482.5  929.18  5546.5  932.69  5624.6  937.98  5786.5  946.62
#Mann= 18 ,-1 , 0
  1657.4     .05       0  2117.9     .05       0  2143.8     .05       0
  2456.2     .05       0  2879.6     .05       0  2914.8     .05       0
  3010.4     .05       0  3050.1     .05       0  3348.5     .05       0
  3476.7     .05       0  4992.2     .07       0  4994.4     .16       0
  5011.4     .05       0  5126.6     .05       0  5222.7     .16       0
  5482.5     .05       0  5546.5     .16       0  5624.6     .05       0
#XS Ineff= 2 , 0
       0  4236.8  928.51               0
Permanent Ineff=
       F       F
Bank Sta=4992.2,5011.4
XS Rating Curve= 0 ,0
Exp/Cntr=0.3,0.1

Type RM Length L Ch R = 1 ,491177  ,820,820,820
BEGIN DESCRIPTION:
Denton Creek 213.0
END DESCRIPTION:
XS GIS Cut Line= 3
      2222154.45      7239480.93        2220029.        7237660.
      2218973.05      7236718.55
#Sta/Elev= 30
  2207.8     961  2411.3  949.03  2510.1  939.34  2840.8  916.72  2949.4  909.73
  3112.7  902.29  3755.6  903.95  4021.7  905.24  4602.1   905.3  4743.9  907.83
  4942.4  907.18  4956.7  900.18  4978.6   894.9  4982.4  890.75  4987.2  889.75
  5024.2  890.75  5027.9     897    5063   907.4  5132.4  908.32    5191  903.99
  5233.6  905.95  5297.1  913.62  5342.6  912.88  5488.6  912.24  5759.1  924.13
  5762.6  924.35  6019.5  932.83  6084.6  931.82  6217.7  932.74  6421.3  944.59
#Mann= 13 ,-1 , 0
  2207.8     .05       0  2840.8     .05       0  2949.4     .05       0
  3755.6     .05       0  4021.7     .05       0  4743.9     .05       0
  4982.4    .035       0  5024.2     .05       0  5132.4     .05       0
  5342.6     .16       0  5759.1     .05       0  5762.6     .16       0
  6084.6     .05       0
#XS Ineff= 2 , 0
       0    4673  932.14               0
Permanent Ineff=
       F       F
Bank Sta=4982.4,5024.2
XS Rating Curve= 0 ,0
Exp/Cntr=0.3,0.1

Type RM Length L Ch R = 1 ,490357  ,975,975,975
BEGIN DESCRIPTION:
Denton Creek 212.0
END DESCRIPTION:
XS GIS Cut Line= 3
      2222310.74      7238212.31      2220517.55       7237166.4
      2218922.18      7236543.47
#Sta/Elev= 30
  3137.9  931.22  3315.3  927.41  3370.1  917.23  3395.5  916.35  3432.7  921.94
  3534.4  922.01  3834.5  910.28  4019.7  915.77  4223.3  903.01  4377.9  899.85
  4900.9  906.54    4969  906.49  4976.6  903.22  4977.2  889.53    4982  888.53
    5019  889.53  5019.6  894.47  5072.7  897.82  5099.8  905.62  5137.1  907.45
  5195.8  908.95    5223  905.77    5309  905.53  5530.9  904.39  5573.5  902.58
  5820.7  908.74    6411   915.8  6537.7   919.1  6839.2  936.66  6926.5   938.4
#Mann= 9 ,-1 , 0
  3137.9     .05       0  3370.1     .05       0  4900.9     .05       0
  4977.2    .035       0    5019     .05       0  5072.7     .16       0
    5309     .05       0  5530.9     .16       0    6411     .05       0
Bank Sta=4977.2,5019
XS Rating Curve= 0 ,0
Exp/Cntr=0.3,0.1

Type RM Length L Ch R = 1 ,489382  ,1583,1583,1583
BEGIN DESCRIPTION:
Denton Creek 211.0
END DESCRIPTION:
XS GIS Cut Line= 3
      2222079.03      7237410.03        2221079.        7236410.
      2219313.56      7234865.42
#Sta/Elev= 30
  3578.2  930.81  4059.1  899.61  4098.2  898.66  4210.4  900.81  4271.2  898.73
  4299.5  901.07  4402.8  900.19  4704.5  901.33  4877.8  903.37    4950  903.17
  4985.3  888.52  4990.1  887.52  5027.1  888.52  5028.1  893.09  5034.7  894.04
  5042.3  899.19  5056.5   904.8  5276.6  901.76  5367.8  902.29  5424.8  899.29
  5445.7  901.88  5573.8  901.09  5602.3  898.64  5651.6  900.34  6100.8  900.34
  6735.5  905.32  6973.2  912.35    7211  925.23  7231.9  929.36  7338.2  937.17
#Mann= 11 ,-1 , 0
  3578.2     .05       0  4098.2     .05       0  4210.4     .05       0
  4402.8     .05       0  4704.5     .05       0  4877.8     .05       0
  4985.3     .07       0  5027.1     .16       0  5276.6     .16       0
  6100.8     .05       0  6973.2     .05       0
Bank Sta=4985.3,5027.1
XS Rating Curve= 0 ,0
Exp/Cntr=0.3,0.1

Type RM Length L Ch R = 1 ,487799  ,1189,1189,1189
BEGIN DESCRIPTION:
Denton Creek 209.0
END DESCRIPTION:
XS GIS Cut Line= 3
      2223199.49       7236624.1      2222026.48       7235329.1
      2220326.35      7233418.88
#Sta/Elev= 30
  3090.2  920.96  3383.6   903.4  3624.2   898.4  4176.4  895.58  4927.4  903.24
  4948.3  901.12  4962.5  891.65  4976.5  886.56  4981.3  885.56  5018.7  886.56
  5019.3  890.35  5045.9  897.13    5059  901.48  5326.8  900.75  5333.1  900.98
  5480.6  900.23  5594.6  900.02  5625.5  900.42  5728.5  901.06  6130.1  902.83
  6205.2   903.3  6275.5  903.71  6388.4  903.87  6690.8  905.04  6995.2  913.19
  7137.3  913.91  7166.9  910.88  7229.3  909.02    7272  918.19  7394.7   924.8
#Mann= 16 ,-1 , 0
  3090.2     .05       0  4976.5     .05       0  5018.7     .05       0
  5045.9     .05       0    5059     .05       0  5326.8     .05       0
  5333.1     .05       0  5480.6     .05       0  5594.6     .05       0
  5625.5     .05       0  5728.5     .05       0  6130.1     .05       0
  6205.2     .05       0  6275.5     .05       0  6388.4     .05       0
  7166.9     .05       0
Bank Sta=4976.5,5018.7
XS Rating Curve= 0 ,0
Exp/Cntr=0.3,0.1

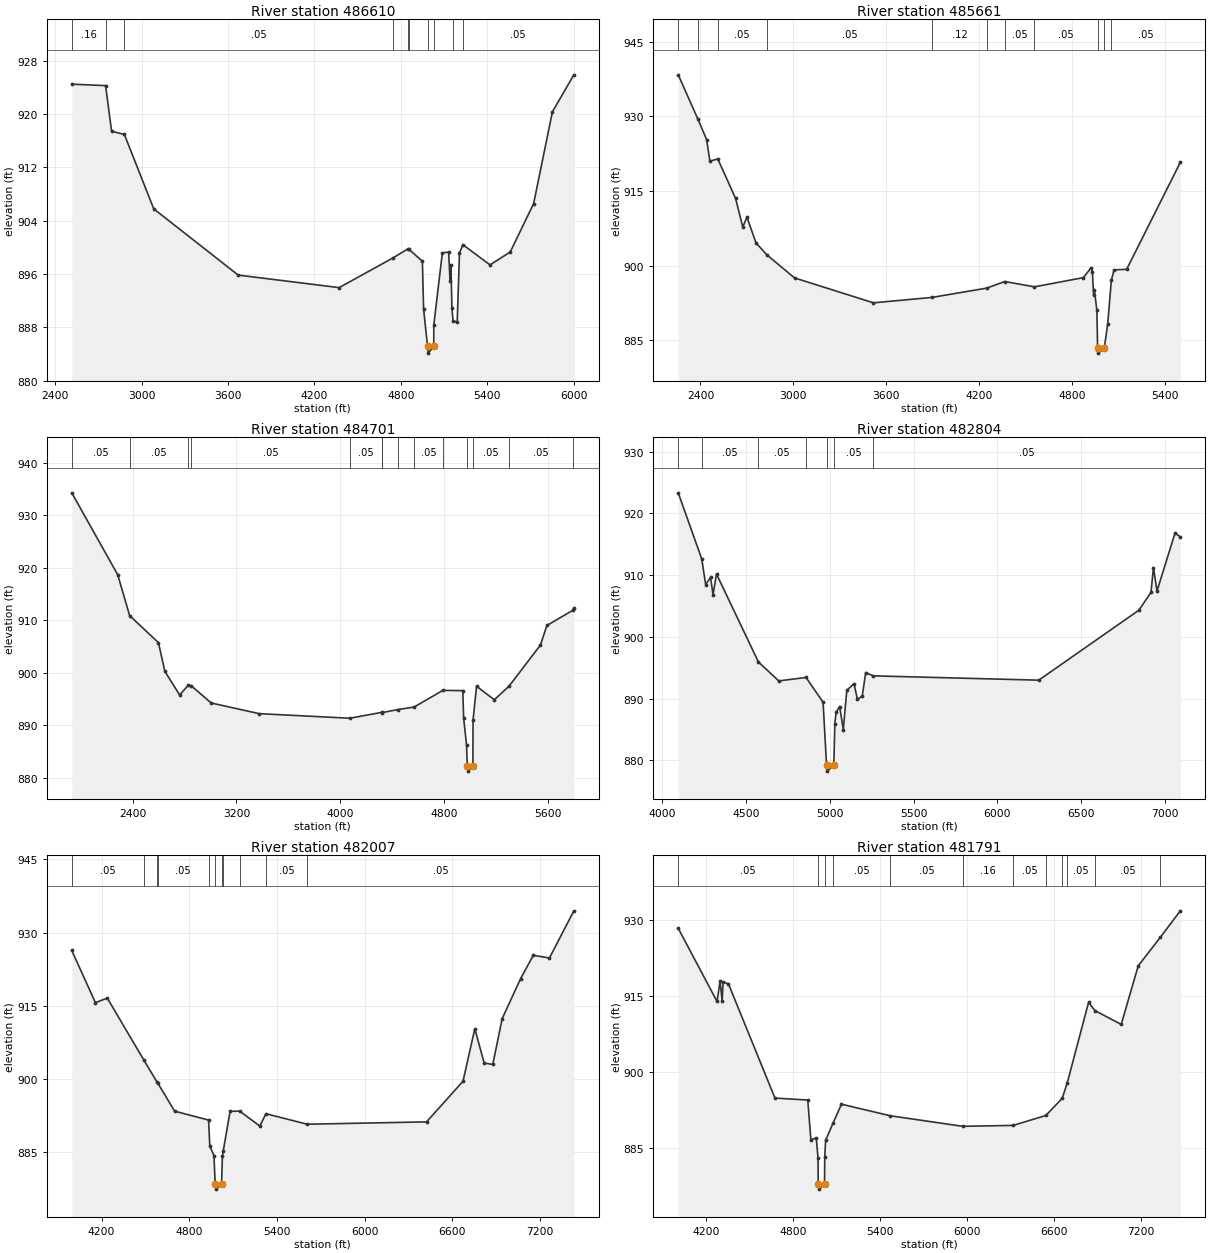
Type RM Length L Ch R = 1 ,486610  ,949,949,949
BEGIN DESCRIPTION:
Denton Creek 208.0
END DESCRIPTION:
XS GIS Cut Line= 3
      2224093.04      7236282.03        2222629.        7234310.
      2222129.02      7233410.04
#Sta/Elev= 30
  2515.8  924.47  2750.6  924.25  2792.3  917.41    2881  916.92  3084.8  905.76
  3671.1  895.82  4372.1  893.94  4745.4  898.39  4848.4  899.74  4857.1  899.68
    4950   897.9  4958.3  890.72  4985.9  885.11  4990.6  884.11  5028.7  885.11
  5029.1  888.33  5088.6  899.17    5132  899.26  5142.3  894.91    5148  897.36
  5154.9  890.93  5162.4  888.99  5191.5  888.72  5207.5  899.08  5230.2   900.4
  5419.2  897.35  5559.9  899.29  5722.3  906.55  5852.7  920.33  6001.4  925.87
#Mann= 10 ,-1 , 0
  2515.8     .16       0  2750.6     .05       0    2881     .05       0
  4745.4     .05       0  4848.4     .05       0  4857.1     .05       0
  4985.9    .035       0  5028.7     .05       0  5162.4     .16       0
  5230.2     .05       0
Bank Sta=4985.9,5028.7
XS Rating Curve= 0 ,0
Exp/Cntr=0.3,0.1

Type RM Length L Ch R = 1 ,485661  ,960,960,960
BEGIN DESCRIPTION:
Denton Creek 207.0
END DESCRIPTION:
XS GIS Cut Line= 3
      2224580.51      7236008.14        2223179.        7233660.
        2223079.        7233160.
#Sta/Elev= 30
  2256.5  938.34  2384.1  929.41  2439.8  925.35  2461.2     921    2512  921.46
    2627  913.54  2673.4   907.8  2700.6  909.75    2759   904.6  2827.7  902.23
  3008.1  897.56  3517.9  892.56  3896.8  893.65  4250.9  895.52  4366.3  896.84
  4558.4  895.77  4874.6  897.62  4924.9  899.62  4932.9  898.81  4940.5  894.16
  4946.3  895.04  4961.9  891.03  4966.6  883.46  4971.3  882.46  5009.7  883.46
  5031.9  888.35  5055.4  897.07  5072.7  899.17  5154.3  899.29    5501  920.76
#Mann= 11 ,-1 , 0
  2256.5     .05       0  2384.1     .16       0    2512     .05       0
  2827.7     .05       0  3896.8     .12       0  4250.9     .05       0
  4366.3     .05       0  4558.4     .05       0  4966.6    .035       0
  5009.7     .05       0  5055.4     .05       0
Bank Sta=4966.6,5009.7
XS Rating Curve= 0 ,0
Exp/Cntr=0.3,0.1

Type RM Length L Ch R = 1 ,484701  ,1897,1897,1897
BEGIN DESCRIPTION:
Denton Creek 206.0
END DESCRIPTION:
XS GIS Cut Line= 3
      2226303.59      7235021.96        2223879.        7233160.
      2223233.12      7232665.65
#Sta/Elev= 30
  1930.6  934.24    2285  918.65  2376.8  910.88  2598.6  905.75  2648.4  900.28
  2762.6  895.78  2828.4  897.66  2850.3  897.57  3005.5  894.27  3375.2  892.24
  4074.6  891.37  4320.6  892.49  4322.1  892.43  4443.7  893.02  4568.6  893.49
  4791.8  896.67  4945.1  896.62  4951.4  891.38  4974.1  886.23  4979.7  882.31
  4984.4  881.31  5022.8  882.31    5024  891.04  5051.1  897.45  5188.1  894.88
  5301.4  897.47  5543.4  905.29  5593.3  909.01  5791.1  911.87    5801  912.34
#Mann= 14 ,-1 , 0
  1930.6     .05       0  2376.8     .05       0  2828.4     .05       0
  2850.3     .05       0  4074.6     .05       0  4320.6     .05       0
  4322.1     .05       0  4443.7     .05       0  4568.6     .05       0
  4791.8     .05       0  4979.7    .035       0  5022.8     .05       0
  5301.4     .05       0  5791.1     .05       0
Bank Sta=4979.7,5022.8
XS Rating Curve= 0 ,0
Exp/Cntr=0.3,0.1

Type RM Length L Ch R = 1 ,482804  ,797,797,797
BEGIN DESCRIPTION:
Denton Creek 204.0
END DESCRIPTION:
XS GIS Cut Line= 4
      2226139.29      7233139.72      2225557.67      7232706.45
      2225307.33      7232418.72      2223740.02      7231366.52
#Sta/Elev= 30
  4096.8  923.33  4236.9  912.63  4260.4  908.48  4289.6  909.64  4304.2  906.84
  4325.1  910.18  4574.9  895.94  4696.3  892.87    4859  893.43  4960.7  889.41
  4981.3  879.26  4985.9  878.26  5024.6  879.26  5030.9  885.97  5038.5   887.8
  5059.4  888.72  5081.2     885  5102.1  891.34  5144.9  892.42  5165.7  889.89
  5194.2  890.39  5214.8  894.23  5259.5  893.69    6247  892.99  6844.1  904.32
  6916.2  907.21  6931.1  911.22  6952.2  907.43  7060.2  916.86  7091.2  916.17
#Mann= 7 ,-1 , 0
  4096.8     .05       0  4236.9     .05       0  4574.9     .05       0
    4859     .05       0  4981.3    .035       0  5024.6     .05       0
  5259.5     .05       0
Bank Sta=4981.3,5024.6
XS Rating Curve= 0 ,0
Exp/Cntr=0.3,0.1

Type RM Length L Ch R = 1 ,482007  ,216,216,216
BEGIN DESCRIPTION:
Denton Creek292
END DESCRIPTION:
XS GIS Cut Line= 3
      2226828.85      7232542.06      2225617.87      7231833.91
      2223865.03      7230804.51
#Sta/Elev= 30
  3996.3  926.36  4158.3  915.67  4239.4  916.62    4488  903.99  4578.5  899.48
    4585   899.2  4700.3  893.46  4932.3  891.64  4940.8  886.31  4969.2  884.38
  4977.7   878.5  4982.4   877.5  5021.2   878.5  5027.1  884.35  5032.5  885.27
  5079.6  893.43  5145.6  893.47  5282.9  890.42  5325.2  892.94  5606.5  890.79
    6424  891.27  6673.5  899.59  6754.2  910.33  6818.6   903.3  6877.2  903.04
  6941.6  912.41  7067.8  920.61  7154.6  925.38  7264.9  924.82  7431.9  934.48
#Mann= 11 ,-1 , 0
  3996.3     .05       0    4488     .05       0  4578.5     .05       0
    4585     .05       0  4932.3     .05       0  4977.7    .035       0
  5021.2     .05       0  5032.5     .05       0  5145.6     .05       0
  5325.2     .05       0  5606.5     .05       0
Bank Sta=4977.7,5021.2
XS Rating Curve= 0 ,0
Exp/Cntr=0.3,0.1

Type RM Length L Ch R = 1 ,481791  ,854,854,854
BEGIN DESCRIPTION:
Denton Creek 203.0
END DESCRIPTION:
XS GIS Cut Line= 3
      2226916.09      7232447.56      2226341.12      7232014.33
      2223965.22      7230638.14
#Sta/Elev= 30
  4008.2  928.42    4276  913.96  4296.9  917.94  4311.4   914.1  4317.7  917.86
  4355.1  917.42  4675.8  894.88  4902.2  894.49  4923.8  886.69  4961.1  886.96
  4973.2  883.01  4974.6  877.89  4979.3  876.89  5018.1  877.89  5019.5  883.31
  5025.6  886.54  5076.2  889.89    5135  893.67  5472.1  891.38  5971.3   889.3
  6319.9  889.48  6545.7  891.44  6658.6  894.83  6693.4  897.87  6840.6  913.79
  6884.3  912.16  7065.9  909.43  7183.5  921.01  7335.9  926.64  7473.8  931.87
#Mann= 12 ,-1 , 0
  4008.2     .05       0  4974.6    .035       0  5018.1     .05       0
  5076.2     .05       0  5472.1     .05       0  5971.3     .16       0
  6319.9     .05       0  6545.7     .05       0  6658.6     .05       0
  6693.4     .05       0  6884.3     .05       0  7335.9    .063       0
Bank Sta=4974.6,5018.1
XS Rating Curve= 0 ,0
Exp/Cntr=0.3,0.1

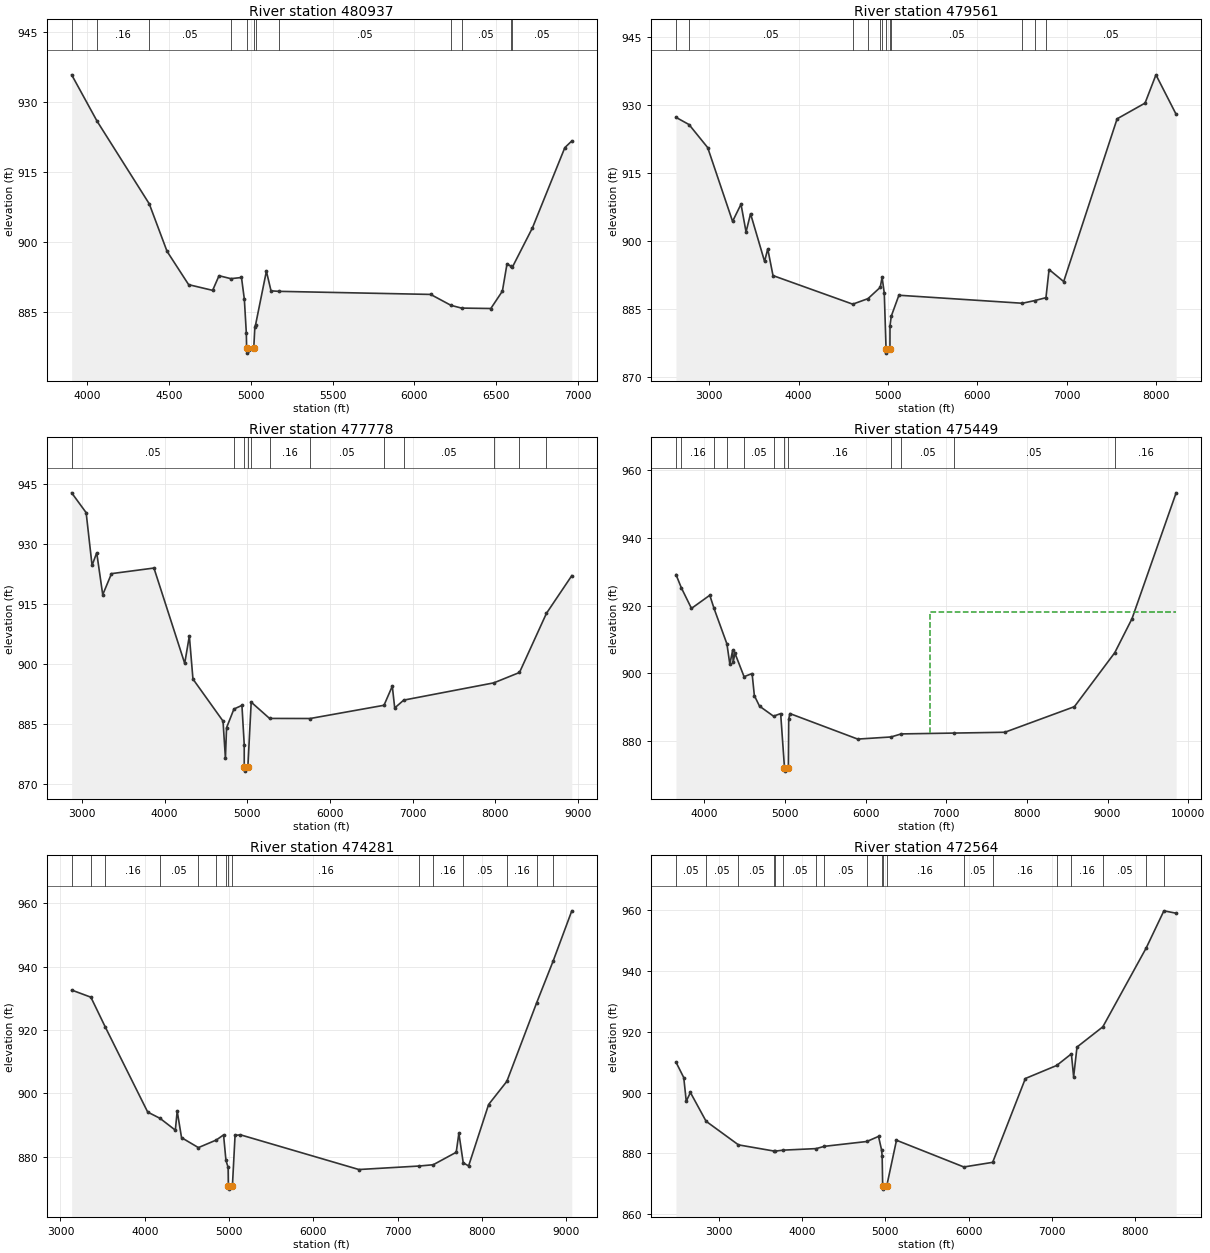
Type RM Length L Ch R = 1 ,480937  ,1376,1376,1376
BEGIN DESCRIPTION:
Denton Creek 202.0
END DESCRIPTION:
XS GIS Cut Line= 3
      2227129.01      7232310.02        2226729.        7231310.
      2225328.97      7229909.97
#Sta/Elev= 30
  3905.6  935.78  4060.7  925.88  4379.8   908.2  4488.6  898.04  4620.5  890.92
  4767.2   889.7  4806.3  892.83  4878.7   892.2  4943.6  892.45  4961.1   887.8
  4973.2  880.54    4975  877.28  4979.7  876.28  5018.5  877.28  5025.1  881.76
  5029.8  882.35  5095.8  893.79  5124.1   889.6  5171.6  889.49  6099.9  888.83
  6223.9   886.5  6288.4  885.91  6467.6  885.82  6538.3  889.53  6566.6  895.37
  6590.1  894.87  6599.9   894.7  6722.1  903.07  6920.1  920.22  6962.6  921.64
#Mann= 12 ,-1 , 0
  3905.6     .05       0  4060.7     .16       0  4379.8     .05       0
  4878.7     .16       0    4975     .07       0  5018.5     .16       0
  5029.8     .05       0  5171.6     .05       0  6223.9     .05       0
  6288.4     .05       0  6590.1     .05       0  6599.9     .05       0
Bank Sta=4975,5018.5
XS Rating Curve= 0 ,0
Exp/Cntr=0.3,0.1

Type RM Length L Ch R = 1 ,479561  ,1783,1783,1783
BEGIN DESCRIPTION:
Denton Creek 200.0
END DESCRIPTION:
XS GIS Cut Line= 3
      2228922.19      7232072.05      2227631.05      7230286.64
      2224964.06      7228187.25
#Sta/Elev= 30
  2628.6  927.25  2774.5  925.66  2983.4  920.57  3261.8  904.29  3356.2  908.08
  3412.6  901.95  3462.9  905.98  3619.9  895.45  3655.5  898.21  3714.3  892.32
  4606.6  886.01  4777.4  887.23  4914.3  889.72  4935.2  891.94  4959.7  888.46
  4979.6   876.2  4984.2   875.2  5023.1   876.2  5023.8  881.26    5038  883.36
  5123.3  887.98  6505.2  886.21  6645.5  886.81  6769.2  887.44  6803.9  893.66
  6967.5     891  7565.6  926.93  7878.3   930.4  8000.2  936.64  8226.1  927.92
#Mann= 12 ,-1 , 0
  2628.6     .05       0  2774.5     .05       0  4606.6     .16       0
  4777.4     .05       0  4914.3     .16       0  4935.2     .05       0
  4979.6    .035       0  5023.1     .05       0    5038     .05       0
  6505.2     .05       0  6645.5     .05       0  6769.2     .05       0
Bank Sta=4979.6,5023.1
XS Rating Curve= 0 ,0
Exp/Cntr=0.3,0.1

Type RM Length L Ch R = 1 ,477778  ,2329,2329,2329
BEGIN DESCRIPTION:
Denton Creek 198.0
END DESCRIPTION:
XS GIS Cut Line= 3
      2230208.16       7230026.2      2227054.17      7227619.64
      2225019.49      7228057.83
#Sta/Elev= 30
  2877.2  942.81  3052.2  937.85  3123.9  924.65  3180.1  927.83  3252.8  917.33
  3358.8   922.6  3872.2     924  4244.2  900.16  4300.4  907.02    4344  896.24
  4707.7  885.72  4736.7  876.41  4750.3  884.07  4839.6  888.74  4936.3  889.65
  4964.2  879.83  4964.4  874.21    4969  873.21    5008  874.21  5048.4  890.46
  5270.5  886.39  5761.3  886.37  6654.6  889.68  6754.9  894.47    6784  889.01
  6893.3  890.97    7982  895.28    8293  897.88  8619.1  912.67  8925.8   922.1
#Mann= 12 ,-1 , 0
  2877.2     .05       0  4839.6     .16       0  4964.4     .07       0
    5008     .16       0  5048.4     .05       0  5270.5     .16       0
  5761.3     .05       0  6654.6     .05       0  6893.3     .05       0
    7982     .05       0    8293     .16       0  8619.1     .05       0
Bank Sta=4964.4,5008
XS Rating Curve= 0 ,0
Exp/Cntr=0.3,0.1

Type RM Length L Ch R = 1 ,475449  ,1168,1168,1168
BEGIN DESCRIPTION:
Denton Creek 196.0
END DESCRIPTION:
XS GIS Cut Line= 3
      2230769.53       7227909.6        2229879.        7226860.
      2226434.66      7223480.48
#Sta/Elev= 30
  3648.5  929.16  3715.3  925.21  3840.3  919.14  4067.6  923.04  4119.3  919.19
    4280  908.62    4316  902.64  4351.1  906.75  4357.7   903.3  4379.7  905.86
  4492.7  898.92  4592.2  899.85  4620.2  893.31    4684   890.2  4857.9  887.22
  4946.4  887.99  4993.8  871.95    4998  870.95  5041.9  871.95  5046.2  886.24
  5060.3     888  5901.8  880.44  6315.1  881.07  6441.2  881.97  7092.8  882.22
  7726.3  882.46  8588.9  890.04  9089.6  906.03  9303.2   916.1  9850.4  953.37
#Mann= 12 ,-1 , 0
  3648.5     .05       0  3715.3     .16       0  4119.3     .05       0
    4280     .16       0  4492.7     .05       0  4857.9     .16       0
  4993.8     .07       0  5041.9     .16       0  6315.1     .12       0
  6441.2     .05       0  7092.8     .05       0  9089.6     .16       0
#XS Ineff= 2 , 0
       0                    6800       0     918
Permanent Ineff=
       F       F
Bank Sta=4993.8,5041.9
XS Rating Curve= 0 ,0
Exp/Cntr=0.3,0.1

Type RM Length L Ch R = 1 ,474281  ,1717,1717,1717
BEGIN DESCRIPTION:
Denton Creek 194.0
END DESCRIPTION:
XS GIS Cut Line= 3
       2231149.8      7227977.61       2230936.4      7226577.62
      2229564.62       7222273.5
#Sta/Elev= 30
  3133.2  932.59    3361  930.34  3531.2  920.98  4035.3  894.12  4181.9  892.14
    4363  888.42  4385.1  894.43  4436.7  886.06  4636.6  882.92  4847.9   885.3
  4935.2  886.92  4963.7  878.86  4989.2  876.73  4992.1  870.83  4996.3  869.83
  5040.2  870.83  5071.6  886.74  5134.6  886.96    6541  876.01  7258.8  877.12
  7422.9  877.52  7695.6  881.45    7727  887.45  7778.8  878.13  7842.5  877.14
  8079.8  896.51  8296.2  903.81  8650.9  928.65  8844.1  941.65  9066.8  957.57
#Mann= 15 ,-1 , 0
  3133.2     .05       0    3361     .05       0  3531.2     .16       0
  4181.9     .05       0  4636.6     .05       0  4847.9     .05       0
  4963.7     .16       0  4992.1     .07       0  5040.2     .16       0
  7258.8     .05       0  7422.9     .16       0  7778.8     .05       0
  8296.2     .16       0  8650.9     .05       0  8844.1     .16       0
Bank Sta=4992.1,5040.2
XS Rating Curve= 0 ,0
Exp/Cntr=0.3,0.1

Type RM Length L Ch R = 1 ,472564  ,2042,2042,2042
BEGIN DESCRIPTION:
Denton Creek 193.0
END DESCRIPTION:
XS GIS Cut Line= 3
      2232199.58      7227523.11      2232229.48      7226006.43
      2231517.24      7221574.77
#Sta/Elev= 30
  2485.7     910  2578.8  904.92  2608.8  897.14  2658.8  900.02  2847.1  890.55
  3235.8  882.79  3668.1  880.73    3677  880.73  3774.7  881.06  4168.5  881.56
  4267.9  882.31  4777.2   883.9  4917.6  885.57  4953.9  881.17  4961.2  879.15
  4967.5  869.23  4971.7  868.23  5015.8  869.23  5133.4  884.31  5942.1  875.52
  6288.1  877.04    6681  904.62    7057  908.91  7233.5  912.73  7260.4  905.18
  7300.9  914.97    7611  921.62  8131.7  947.56  8344.4  959.78  8491.2     959
#Mann= 19 ,-1 , 0
  2485.7     .05       0  2847.1     .05       0  3235.8     .05       0
  3668.1     .05       0    3677     .05       0  3774.7     .05       0
  4168.5     .05       0  4267.9     .05       0  4777.2     .05       0
  4953.9     .16       0  4967.5     .07       0  5015.8     .16       0
  5942.1     .05       0  6288.1     .16       0    7057     .05       0
  7233.5     .16       0    7611     .05       0  8131.7    .063       0
  8344.4     .16       0
Bank Sta=4967.5,5015.8
XS Rating Curve= 0 ,0
Exp/Cntr=0.3,0.1

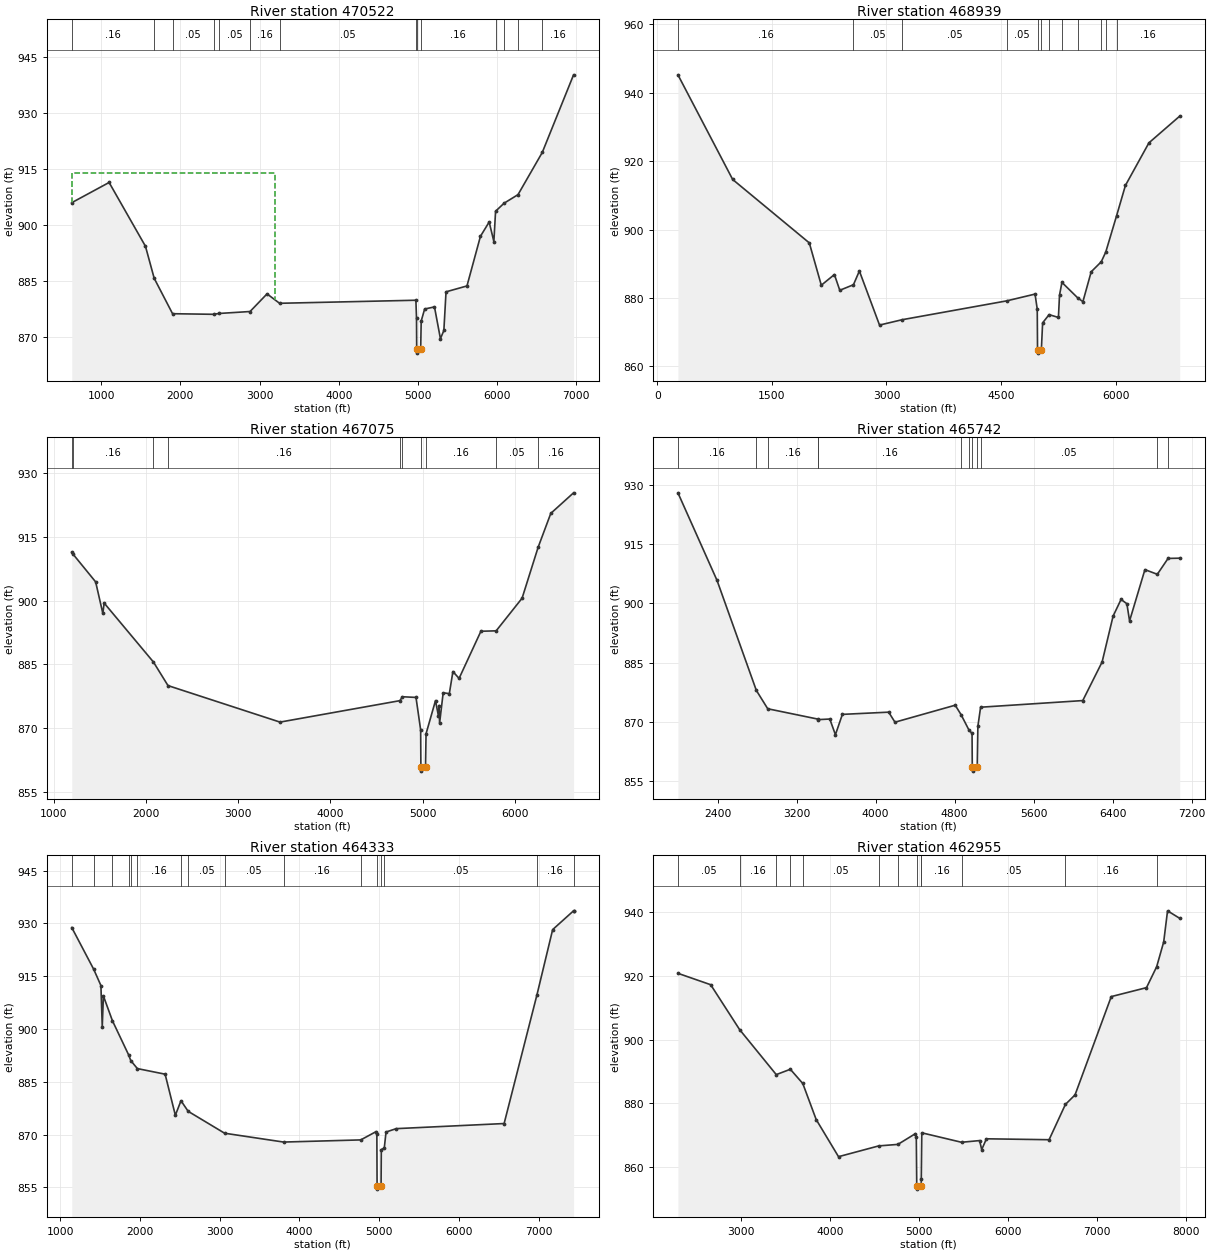
Type RM Length L Ch R = 1 ,470522  ,1583,1583,1583
BEGIN DESCRIPTION:
Denton Creek 191.0
END DESCRIPTION:
XS GIS Cut Line= 3
      2235138.22      7227963.02      2234190.05      7224734.32
      2232731.42      7222145.62
#Sta/Elev= 30
   628.1  905.99  1099.7  911.42  1558.8  894.28  1669.1  885.67    1901  876.16
  2418.2     876  2490.5  876.23  2879.4  876.75    3094  881.49  3252.2  878.96
  4973.6  879.78  4981.4  874.88  4983.8  866.57  4987.8  865.57  5033.8  866.57
  5040.6   874.2    5084  877.42  5208.2  877.99  5283.4  869.45  5326.7  871.65
  5354.1  882.04  5618.5  883.62  5788.7  896.96  5898.8   900.8  5958.1  895.56
  5979.7  903.69  6086.6  905.84    6263  908.15  6569.2  919.48  6964.5  940.34
#Mann= 14 ,-1 , 0
   628.1     .16       0  1669.1     .05       0    1901     .05       0
  2418.2     .05       0  2490.5     .05       0  2879.4     .16       0
  3252.2     .05       0  4973.6     .16       0  4983.8     .07       0
  5033.8     .16       0  5979.7     .05       0  6086.6     .16       0
    6263     .05       0  6569.2     .16       0
#XS Ineff= 2 , 0
       0  3190.9  913.88               0
Permanent Ineff=
       F       F
Bank Sta=4983.8,5033.8
XS Rating Curve= 0 ,0
Exp/Cntr=0.3,0.1

Type RM Length L Ch R = 1 ,468939  ,1864,1864,1864
BEGIN DESCRIPTION:
Denton Creek 190.0
END DESCRIPTION:
XS GIS Cut Line= 3
      2237950.23       7226885.2      2234624.81      7222701.57
       2234024.2      7221636.86
#Sta/Elev= 30
     271  945.24   987.4  914.65  1990.2  896.11  2147.2  883.74  2318.6  886.86
    2389  882.26  2567.7  883.88  2645.4   887.9  2909.1  872.09  3205.5  873.66
  4572.2  879.16  4944.1  881.15    4973  876.75  4976.8  864.89  4980.8  863.89
  5026.8  864.89  5043.4  872.74  5128.2  875.14  5250.1  874.32  5264.5  880.86
    5296  884.57    5505  879.99  5570.5  878.94  5679.1  887.67  5810.7  890.59
  5869.8  893.45    6012   904.1  6126.9  912.91  6434.5  925.36  6837.7  933.17
#Mann= 12 ,-1 , 0
     271     .16       0  2567.7     .05       0  3205.5     .05       0
  4572.2     .05       0  4976.8     .07       0  5026.8     .05       0
  5128.2     .05       0    5296     .16       0    5505     .05       0
  5810.7     .16       0  5869.8     .05       0    6012     .16       0
Bank Sta=4976.8,5026.8
XS Rating Curve= 0 ,0
Exp/Cntr=0.3,0.1

Type RM Length L Ch R = 1 ,467075  ,1333,1333,1333
BEGIN DESCRIPTION:
Denton Creek 189.0
END DESCRIPTION:
XS GIS Cut Line= 3
      2238801.48      7225043.02        2236329.        7222160.
       2235582.1      7220694.47
#Sta/Elev= 30
    1195  911.36  1203.3  911.06  1454.1  904.39    1532  896.99  1546.3  899.42
  2080.9  885.56  2238.9  880.02  3453.7  871.44    4754  876.48  4782.2   877.4
  4928.8  877.24  4979.3  869.61  4981.9  860.92  4985.9  859.92  5031.9  860.92
  5037.9   868.7  5140.4   876.5  5172.6  872.85  5179.2  875.34  5184.8  871.22
  5223.7  878.33  5290.4  878.13  5329.2  883.32    5396  881.71  5632.8  892.79
  5798.4  892.89  6079.6  900.56  6253.3  912.51  6390.9  920.49  6637.9  925.32
#Mann= 10 ,-1 , 0
    1195     .05       0  1203.3     .16       0  2080.9     .05       0
  2238.9     .16       0    4754     .05       0  4782.2     .16       0
  4981.9     .07       0  5031.9     .16       0  5798.4     .05       0
  6253.3     .16       0
Bank Sta=4981.9,5031.9
XS Rating Curve= 0 ,0
Exp/Cntr=0.3,0.1

Type RM Length L Ch R = 1 ,465742  ,1409,1409,1409
BEGIN DESCRIPTION:
Denton Creek 188.0
END DESCRIPTION:
XS GIS Cut Line= 3
      2239651.92      7223304.74        2237379.        7221360.
      2235567.56      7220319.83
#Sta/Elev= 30
  1998.8  927.95  2394.6   905.8  2792.4  877.97  2907.9  873.32  3412.2  870.72
  3418.5  870.57  3536.2  870.72  3593.3  866.75  3663.6   871.9  4132.3  872.46
    4196  869.92  4805.9  874.22  4865.1  871.83    4944  867.99  4976.4  867.07
  4978.8  858.54  4982.8  857.54  5028.8  858.54  5035.4  868.89    5063  873.71
  6097.2  875.39  6293.2  885.16  6404.3  896.76  6484.9  900.98  6543.8  899.89
  6571.1  895.55  6726.4  908.52    6852  907.34  6960.6  911.35    7079  911.42
#Mann= 12 ,-1 , 0
  1998.8     .16       0  2792.4     .05       0  2907.9     .16       0
  3412.2     .05       0  3418.5     .16       0  4865.1     .05       0
    4944     .16       0  4978.8     .07       0  5028.8     .16       0
    5063     .05       0    6852     .16       0  6960.6     .05       0
Bank Sta=4978.8,5028.8
XS Rating Curve= 0 ,0
Exp/Cntr=0.3,0.1

Type RM Length L Ch R = 1 ,464333  ,1378,1378,1378
BEGIN DESCRIPTION:
Denton Creek 187.0
END DESCRIPTION:
XS GIS Cut Line= 3
      2241803.99      7222097.09        2238329.        7220360.
        2236529.        7218760.
#Sta/Elev= 30
  1146.1  928.84  1421.7  916.96  1511.8  912.36  1528.6  900.68    1543   909.4
  1656.2  902.36  1859.4  892.66  1886.4  891.04  1968.8  888.77  2316.9  887.18
  2445.4  875.51  2515.9  879.64    2606  876.63    3063  870.41  3802.5   867.9
  4770.3  868.51    4964  870.88  4972.4  870.19  4975.3  855.53  4979.3  854.53
  5025.3  855.53  5028.3  865.74  5065.7  866.23  5087.5  870.75  5215.5  871.71
  6568.5  873.16  6979.5  909.65  7177.2  928.25    7439  933.58  7439.4  933.58
#Mann= 16 ,-1 , 0
  1146.1     .05       0  1421.7     .16       0  1656.2     .05       0
  1859.4     .16       0  1886.4     .05       0  1968.8     .16       0
  2515.9     .05       0    2606     .05       0    3063     .05       0
  3802.5     .16       0  4770.3     .05       0  4975.3     .07       0
  5025.3     .05       0  5065.7     .05       0  6979.5     .16       0
    7439     .05       0
Bank Sta=4975.3,5025.3
XS Rating Curve= 0 ,0
Exp/Cntr=0.3,0.1

Type RM Length L Ch R = 1 ,462955  ,2155,2155,2155
BEGIN DESCRIPTION:
Denton Creek 186.0
END DESCRIPTION:
XS GIS Cut Line= 3
      2241635.27      7219415.13        2238929.        7219160.
       2236232.5       7218040.3
#Sta/Elev= 30
  2289.2  920.87  2657.1  917.29  2981.7  903.21    3394  889.05  3552.1  890.73
    3692  886.26  3842.3  874.95  4093.4  863.27  4545.6  866.66  4760.5  867.13
  4958.2  870.52  4967.3  869.53  4972.4  854.08  4976.4  853.08  5022.4  854.08
  5023.3  856.32  5029.1  870.77  5475.2   867.8  5678.8  868.33  5702.2   865.5
  5755.3  868.89  6459.3   868.6  6642.3  879.67  6750.8  882.68  7157.8  913.56
  7553.7  916.37  7668.1  922.95  7746.9  930.73  7790.2   940.5  7927.2  938.14
#Mann= 13 ,-1 , 0
  2289.2     .05       0  2981.7     .16       0    3394     .05       0
  3552.1     .16       0    3692     .05       0  4545.6     .16       0
  4760.5     .05       0  4972.4    .035       0  5022.4     .05       0
  5023.3     .16       0  5475.2     .05       0  6642.3     .16       0
  7668.1     .05       0
Bank Sta=4972.4,5022.4
XS Rating Curve= 0 ,0
Exp/Cntr=0.3,0.1