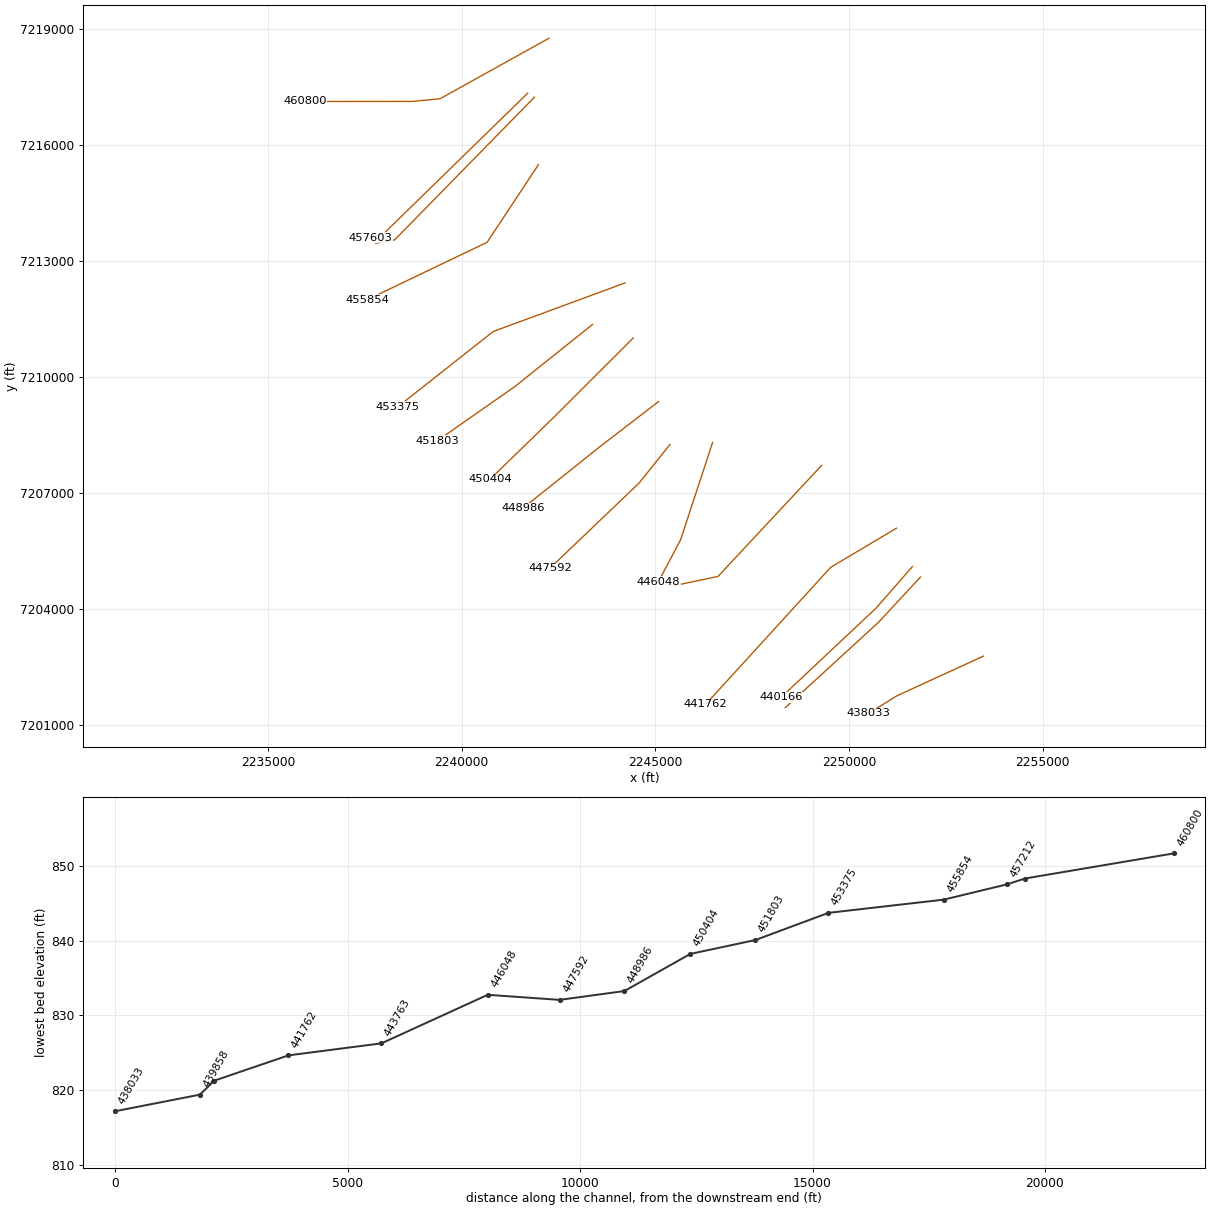
HEC-RAS study Denton Creek.prj: Denton Creek Base Level Engineering

--- Denton Creek.g01 (geometry) --- (continued)

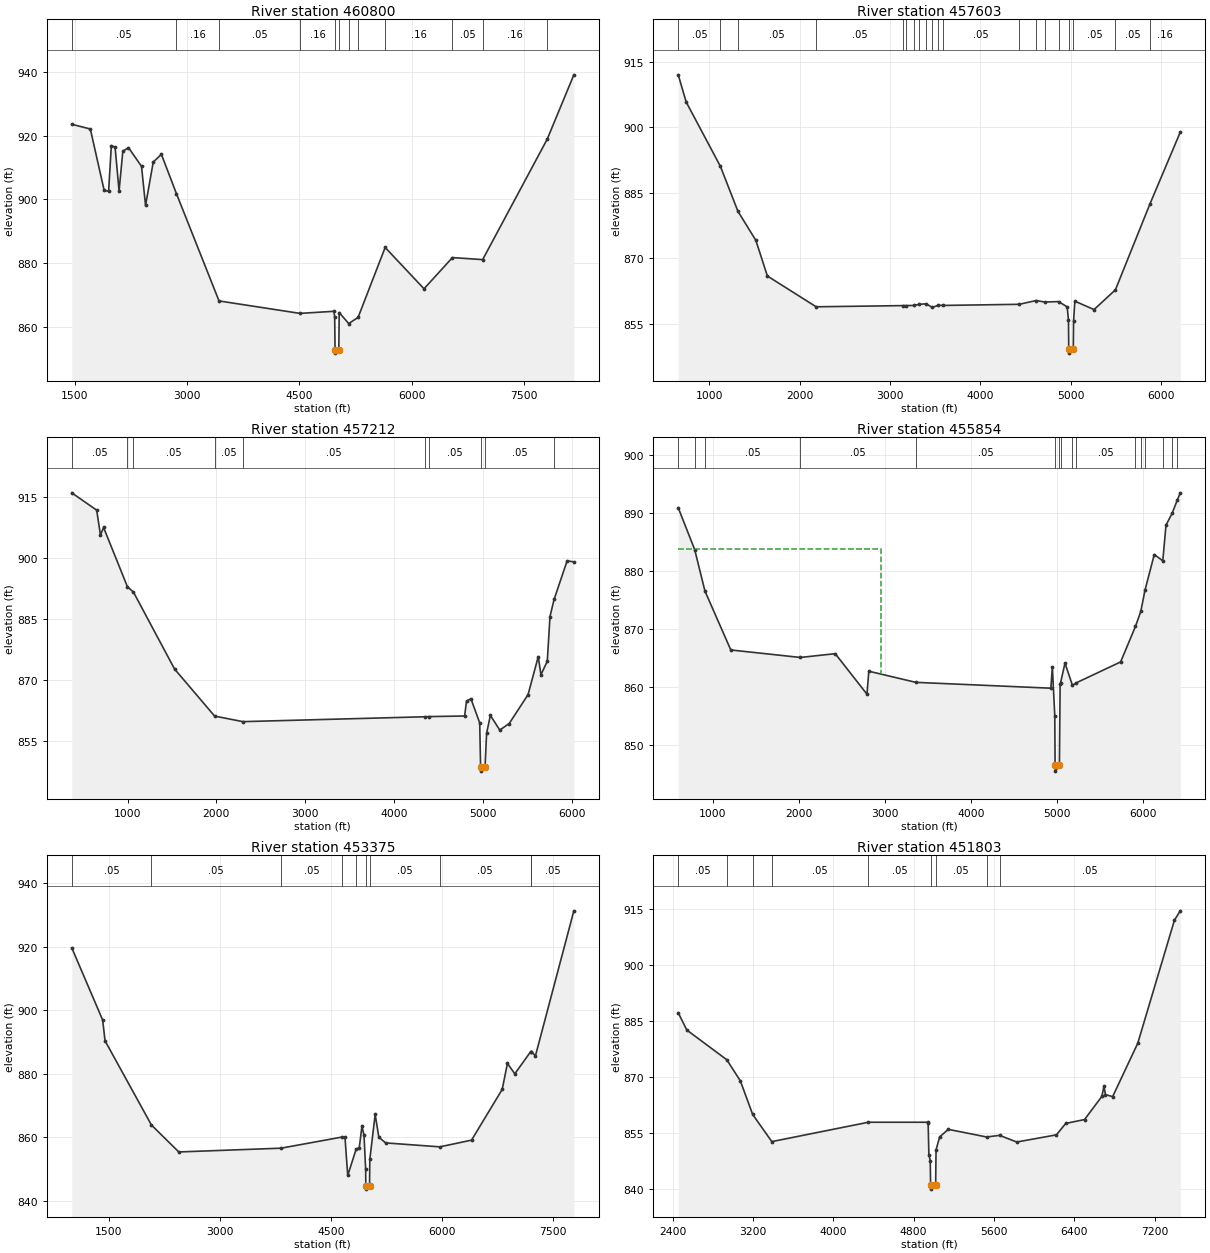
Type RM Length L Ch R = 1 ,460800  ,3197,3197,3197
BEGIN DESCRIPTION:
Denton Creek 185.0
END DESCRIPTION:
XS GIS Cut Line= 4
      2242250.44      7218755.45      2239442.45      7217193.92
      2238728.99      7217125.56      2235959.89       7217123.1
#Sta/Elev= 30
  1462.8  923.57  1710.5  922.09  1894.7  902.83  1954.1  902.51  1990.8  916.87
  2041.1  916.35  2093.8  902.61    2144  915.09  2219.5  916.24  2393.3  910.36
  2447.1  898.06    2550  911.72  2658.6  914.13  2859.9  901.75  3427.5  868.07
  4506.6  864.16  4960.5  864.81  4970.6  863.06  4975.7  852.67  4979.7  851.67
  5025.7  852.67  5030.8  864.41  5157.9  860.97  5282.6  862.88  5644.1  884.87
  6162.5  871.89  6541.9  881.69    6945  881.05  7806.7  918.91  8161.6  939.11
#Mann= 12 ,-1 , 0
  1462.8     .05       0  2859.9     .16       0  3427.5     .05       0
  4506.6     .16       0  4975.7     .07       0  5025.7     .16       0
  5157.9     .16       0  5282.6     .05       0  5644.1     .16       0
  6541.9     .05       0    6945     .16       0  7806.7     .05       0
Bank Sta=4975.7,5025.7
XS Rating Curve= 0 ,0
Exp/Cntr=0.3,0.1

Type RM Length L Ch R = 1 ,457603  ,391,391,391
BEGIN DESCRIPTION:
Denton Creek291
END DESCRIPTION:
XS GIS Cut Line= 4
      2241705.25       7217337.8        2240738.      7216394.52
      2237991.41      7213711.58      2237644.32      7213604.87
#Sta/Elev= 30
   658.3  912.03   746.1  905.81  1124.6  891.08  1318.9  880.77  1516.9  874.13
  1644.2  865.97  2183.7  858.92  3143.9  859.19  3181.9   859.2  3265.1  859.22
  3325.5  859.48  3400.3  859.61  3469.1  858.78  3535.5  859.27  3590.1  859.23
  4430.1  859.49    4617  860.35  4711.7  860.01  4865.5  860.11  4960.6   858.9
  4974.8  855.95  4978.1  849.31  4982.1  848.31  5028.1  849.31  5031.4  855.71
  5045.5  860.21  5257.7  858.28  5494.4  862.81    5877  882.52    6212  898.93
#Mann= 20 ,-1 , 0
   658.3     .05       0  1124.6     .16       0  1318.9     .05       0
  2183.7     .05       0  3143.9     .05       0  3181.9     .05       0
  3265.1     .05       0  3325.5     .05       0  3400.3     .05       0
  3469.1     .05       0  3535.5     .05       0  3590.1     .05       0
  4430.1     .05       0    4617     .05       0  4711.7     .05       0
  4865.5     .05       0  4978.1    .045       0  5028.1     .05       0
  5494.4     .05       0    5877     .16       0
Bank Sta=4978.1,5028.1
XS Rating Curve= 0 ,0
Exp/Cntr=0.3,0.1

Type RM Length L Ch R = 1 ,457212  ,1358,1358,1358
BEGIN DESCRIPTION:
Denton Creek 182.0
END DESCRIPTION:
XS GIS Cut Line= 3
      2241880.32      7217235.44      2238271.47       7213547.7
      2237784.49      7213460.49
#Sta/Elev= 30
   371.2  915.91   651.8  911.65   694.2  905.55   729.5  907.39   998.2  892.82
    1066  891.51  1528.6  872.62    1980  861.05  2297.9  859.68  4350.7  860.88
  4393.3  860.92  4795.7  861.07  4816.8  864.72  4866.4  865.31  4965.4  859.39
  4975.7  848.52  4979.7  847.52  5025.7  848.52  5043.1  856.84  5085.6  861.21
  5191.7  857.61  5297.7  859.22  5509.9  866.31  5624.9  875.66    5655  871.21
  5726.5   874.5    5757  885.49  5802.9   889.7    5950   899.2  6025.7  898.94
#Mann= 10 ,-1 , 0
   371.2     .05       0   998.2     .16       0    1066     .05       0
    1980     .05       0  2297.9     .05       0  4350.7     .05       0
  4393.3     .05       0  4975.7    .035       0  5025.7     .05       0
  5802.9     .16       0
Bank Sta=4975.7,5025.7
XS Rating Curve= 0 ,0
Exp/Cntr=0.3,0.1

Type RM Length L Ch R = 1 ,455854  ,2479,2479,2479
BEGIN DESCRIPTION:
Denton Creek 181.0
END DESCRIPTION:
XS GIS Cut Line= 3
      2241982.26      7215490.84      2240658.22      7213484.77
      2237571.17      7212004.57
#Sta/Elev= 30
   601.5  890.86   792.2  883.67   911.3  876.52  1211.6  866.36    2018  865.07
  2423.7  865.72  2792.1  858.74  2813.1   862.7    3359  860.78  4926.4  859.77
  4943.5  863.46  4971.7  855.06  4975.5  846.48  4979.5  845.48  5025.5  846.48
  5033.8  860.51  5039.3  860.73  5090.5   864.1  5176.4  860.27  5220.2  860.69
  5735.9   864.3    5908  870.41  5970.5  873.03  6018.9  876.67  6126.6  882.81
  6225.3  881.72  6262.5  887.87  6333.2   889.9  6392.4  892.14  6428.7  893.44
#Mann= 16 ,-1 , 0
   601.5     .05       0   792.2     .05       0   911.3     .05       0
    2018     .05       0    3359     .05       0  4975.5     .05       0
  5025.5     .05       0  5039.3     .05       0  5176.4     .05       0
  5220.2     .05       0    5908     .05       0  5970.5     .05       0
  6018.9     .05       0  6225.3     .05       0  6333.2     .05       0
  6392.4     .05       0
#XS Ineff= 2 , 0
       0  2958.3  883.78               0
Permanent Ineff=
       F       F
Bank Sta=4975.5,5025.5
XS Rating Curve= 0 ,0
Exp/Cntr=0.3,0.1

Type RM Length L Ch R = 1 ,453375  ,1572,1572,1572
BEGIN DESCRIPTION:
Denton Creek 179.0
END DESCRIPTION:
XS GIS Cut Line= 3
      2244220.46      7212434.71      2240817.16      7211179.65
      2238343.33      7209226.77
#Sta/Elev= 30
  1001.1  919.73  1418.3  896.98  1450.3  890.44  2076.8  863.91  2446.1  855.42
  3826.7  856.61  4649.1  860.11  4690.3  860.02  4727.2  848.03  4840.9  856.31
  4882.7  856.73  4919.1  863.51  4946.8  860.75  4969.3  850.05  4971.5  844.71
  4975.5  843.71  5021.5  844.71  5025.4  853.06  5097.5  867.23  5147.2  860.09
  5238.5  858.27  5971.8  857.03  6399.2  859.15  6812.9  875.13  6883.4  883.31
  6983.1  880.04  7197.2  887.01  7202.4  887.06  7261.8  885.71  7780.2  931.38
#Mann= 10 ,-1 , 0
  1001.1     .05       0  2076.8     .05       0  3826.7     .05       0
  4649.1     .05       0  4840.9     .05       0  4971.5    .035       0
  5021.5     .05       0  5971.8     .05       0  7197.2     .16       0
  7202.4     .05       0
Bank Sta=4971.5,5021.5
XS Rating Curve= 0 ,0
Exp/Cntr=0.3,0.1

Type RM Length L Ch R = 1 ,451803  ,1399,1399,1399
BEGIN DESCRIPTION:
Denton Creek 178.0
END DESCRIPTION:
XS GIS Cut Line= 3
      2243379.03      7211360.03        2241379.        7209760.
        2239379.        7208360.
#Sta/Elev= 30
  2454.2  887.24  2539.9  882.62  2937.7  874.68  3072.9  869.04    3196  860.04
  3386.6  852.78    4349  857.96  4937.9  857.96  4944.3   857.7  4951.5  849.29
  4965.1   847.7  4968.9  841.07  4972.9  840.07  5018.9  841.07  5022.9  850.55
  5058.7  854.03    5145  856.06  5526.6  854.02  5656.3  854.45  5826.8  852.67
  6222.6  854.59  6315.1  857.64  6502.5  858.68  6675.1  864.87  6696.1   867.6
  6710.9  865.36  6782.4  864.81  7032.6  879.07  7398.8  912.05  7456.8  914.51
#Mann= 9 ,-1 , 0
  2454.2     .05       0  2937.7     .05       0    3196     .05       0
  3386.6     .05       0    4349     .05       0  4968.9    .035       0
  5018.9     .05       0  5526.6     .05       0  5656.3     .05       0
Bank Sta=4968.9,5018.9
XS Rating Curve= 0 ,0
Exp/Cntr=0.3,0.1

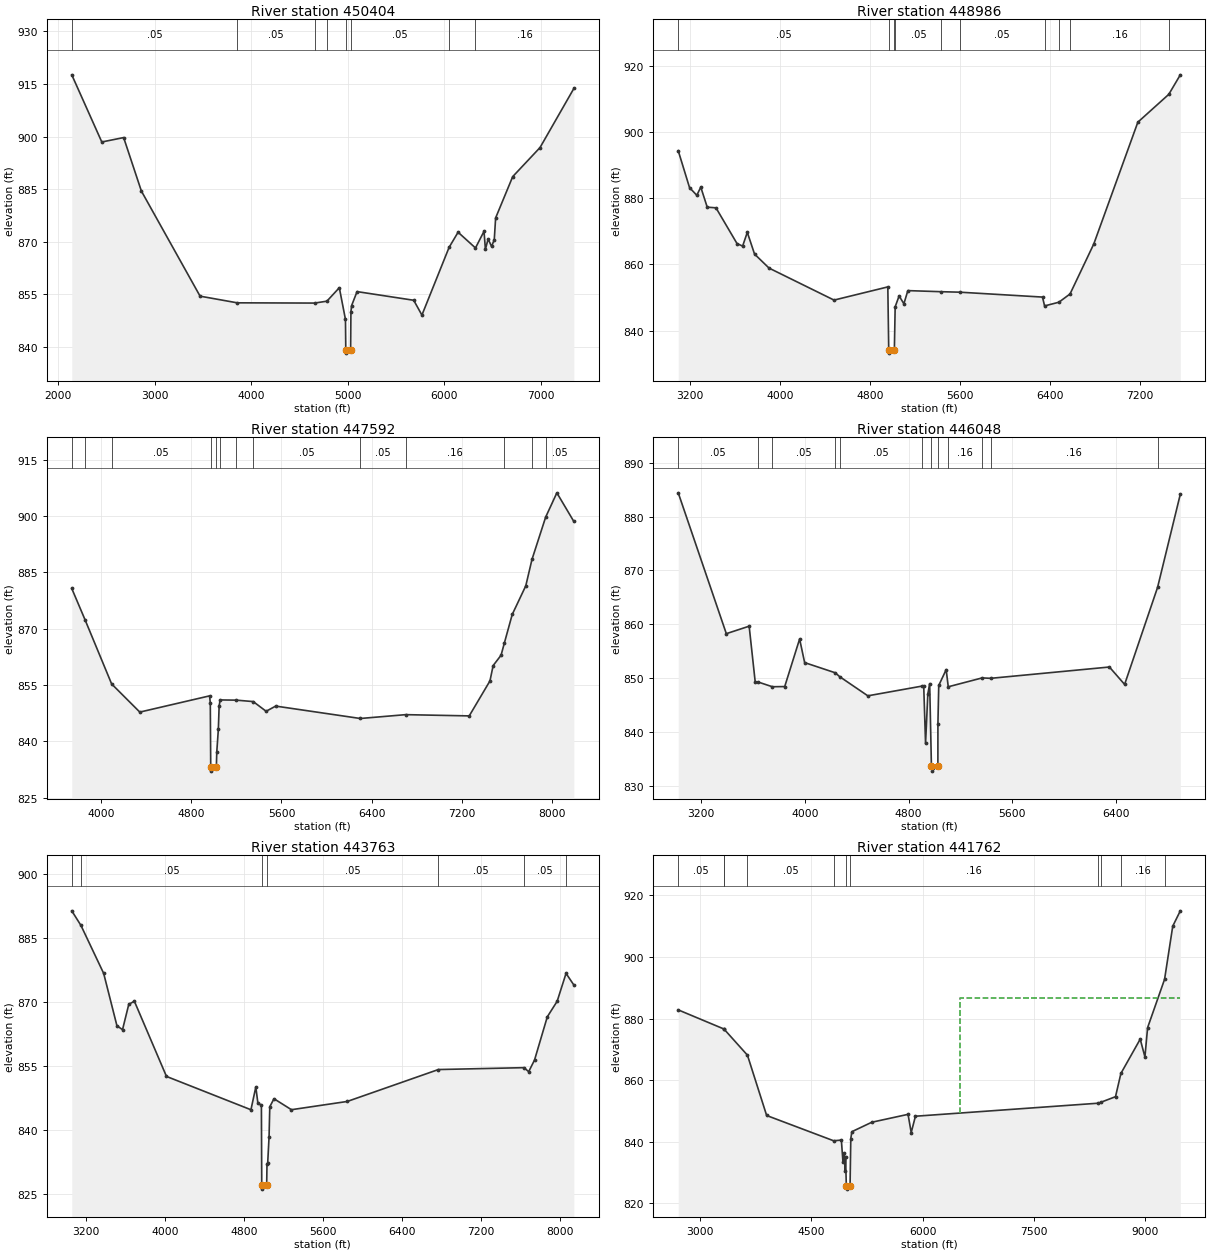
Type RM Length L Ch R = 1 ,450404  ,1418,1418,1418
BEGIN DESCRIPTION:
Denton Creek 177.0
END DESCRIPTION:
XS GIS Cut Line= 3
      2244428.98      7211009.98        2242429.        7209010.
       2240727.7      7207355.55
#Sta/Elev= 30
  2141.2   917.6  2452.3  898.44  2678.6   899.7  2862.4  884.44  3470.5  854.46
  3855.3  852.56  4657.3  852.49  4784.4  853.03    4913  856.87  4976.7  847.82
    4980  839.21    4984  838.21    5030  839.21  5033.3  850.01  5040.2  851.76
  5096.8  855.76  5683.8  853.29  5768.7  849.06  6050.3  868.38  6143.4   872.7
  6323.6  868.21  6412.2  872.97  6426.4  867.82  6454.7  870.76    6490  868.65
  6518.2  870.53  6532.4  876.78  6709.3  888.56  6992.2  896.85  7342.7   913.7
#Mann= 8 ,-1 , 0
  2141.2     .05       0  3855.3     .05       0  4657.3     .05       0
  4784.4     .05       0    4980     .05       0    5030     .05       0
  6050.3     .05       0  6323.6     .16       0
Bank Sta=4980,5030
XS Rating Curve= 0 ,0
Exp/Cntr=0.3,0.1

Type RM Length L Ch R = 1 ,448986  ,1394,1394,1394
BEGIN DESCRIPTION:
Denton Creek 176.0
END DESCRIPTION:
XS GIS Cut Line= 3
        2245083.      7209366.83        2243579.        7208210.
      2241578.99        7206610.
#Sta/Elev= 30
  3098.7  894.33  3199.2  883.19  3263.6  880.89  3298.9  883.35  3356.1   877.3
  3433.9   877.1  3620.6  866.32  3670.5  865.55  3712.1   869.7  3776.4  863.14
  3905.1  858.91  4482.3  849.25  4959.9  853.23    4968  834.24    4972  833.24
    5018  834.24  5025.2  847.23  5060.2  850.51  5102.6  848.14  5137.8  852.11
  5436.2  851.78  5597.8  851.64  6333.6  850.16    6352  847.49  6479.4  848.61
  6578.1   851.1    6789  866.19  7180.4  902.96  7455.1  911.36  7557.4  917.25
#Mann= 10 ,-1 , 0
  3098.7     .05       0    4968    .035       0    5018     .05       0
  5025.2     .05       0  5436.2     .05       0  5597.8     .05       0
    6352     .16       0  6479.4     .05       0  6578.1     .16       0
  7455.1     .05       0
Bank Sta=4968,5018
XS Rating Curve= 0 ,0
Exp/Cntr=0.3,0.1

Type RM Length L Ch R = 1 ,447592  ,1544,1544,1544
BEGIN DESCRIPTION:
Denton Creek 175.0
END DESCRIPTION:
XS GIS Cut Line= 3
      2245378.97      7208259.96        2244579.        7207260.
      2242281.77      7205063.68
#Sta/Elev= 30
  3737.6  880.67  3855.8  872.32  4091.7  855.26  4341.8  847.77  4961.4  852.09
  4967.8  850.17  4971.6  833.06  4975.6  832.06  5021.6  833.06  5025.3  837.12
  5039.4  843.22  5046.3   849.4  5055.3  851.01  5199.1  850.95  5349.1  850.57
  5463.7  847.99  5548.6  849.37    6300  846.07  6702.9  847.09  7267.4  846.76
  7451.4  856.07  7479.7  860.15  7550.1  862.91  7579.9  866.22  7649.2  873.75
  7769.6  881.38  7824.6   888.4  7946.2  899.67  8045.5  906.13  8196.4   898.5
#Mann= 13 ,-1 , 0
  3737.6     .05       0  3855.8     .05       0  4091.7     .05       0
  4971.6    .035       0  5021.6     .05       0  5055.3     .05       0
  5199.1     .05       0  5349.1     .05       0    6300     .05       0
  6702.9     .16       0  7579.9     .05       0  7824.6     .16       0
  7946.2     .05       0
Bank Sta=4971.6,5021.6
XS Rating Curve= 0 ,0
Exp/Cntr=0.3,0.1

Type RM Length L Ch R = 1 ,446048  ,2285,2285,2285
BEGIN DESCRIPTION:
Denton Creek 174.0
END DESCRIPTION:
XS GIS Cut Line= 3
      2246478.99      7208309.98      2245653.91       7205797.8
      2245078.99      7204709.98
#Sta/Elev= 30
  3022.7  884.41  3393.8  858.26    3570  859.65  3616.5  849.34  3637.3   849.3
  3748.7  848.41  3844.4  848.44  3959.4  857.27  3998.2  852.89  4235.4  850.99
  4267.9  850.29  4485.9  846.72  4902.4  848.52  4917.3  848.46  4931.3  837.87
  4948.8  847.06  4963.1  848.99  4976.5  833.74  4980.5  832.74  5026.5  833.74
  5026.7  841.51  5033.1  848.64  5090.4  851.59  5106.5   848.4  5368.4  850.05
  5433.8  849.97  6350.1  852.07  6467.5  848.84  6721.9  866.86  6897.3  884.15
#Mann= 12 ,-1 , 0
  3022.7     .05       0  3637.3     .05       0  3748.7     .05       0
  4235.4     .05       0  4267.9     .05       0  4902.4     .05       0
  4976.5    .035       0  5026.5     .05       0  5106.5     .16       0
  5368.4     .05       0  5433.8     .16       0  6721.9     .05       0
Bank Sta=4976.5,5026.5
XS Rating Curve= 0 ,0
Exp/Cntr=0.3,0.1

Type RM Length L Ch R = 1 ,443763  ,2001,2001,2001
BEGIN DESCRIPTION:
Denton Creek 172.0
END DESCRIPTION:
XS GIS Cut Line= 3
       2249295.7      7207720.42      2246620.34      7204850.34
      2245479.01        7204610.
#Sta/Elev= 30
    3053  891.38  3146.3  887.95  3376.5  876.73  3510.8  864.49  3567.5  863.56
    3631   869.5  3687.7  870.22  4013.1  852.62  4869.5  844.82  4918.8  850.14
  4940.2  846.32  4975.5  845.93  4978.9  827.24  4982.9  826.24  5028.9  827.24
  5032.2  832.13    5039  832.25  5053.2  838.51  5060.5  845.52    5103   847.4
  5279.9  844.83  5845.6  846.76  6769.7  854.23  7637.6  854.67  7685.1  853.73
  7744.5  856.46  7874.1  866.58  7973.8  870.21  8063.9  876.74    8143  874.02
#Mann= 7 ,-1 , 0
    3053     .05       0  3146.3     .05       0  4978.9     .05       0
  5028.9     .05       0  6769.7     .05       0  7637.6     .05       0
  8063.9     .05       0
Bank Sta=4978.9,5028.9
XS Rating Curve= 0 ,0
Exp/Cntr=0.3,0.1

Type RM Length L Ch R = 1 ,441762  ,1596,1596,1596
BEGIN DESCRIPTION:
Denton Creek 171.0
END DESCRIPTION:
XS GIS Cut Line= 3
      2251226.29      7206095.82      2249527.84      7205083.49
      2246301.15      7201544.37
#Sta/Elev= 30
  2704.9   882.8  3320.8   876.6  3325.8  876.47  3637.6   868.1  3896.5  848.53
  4799.5  840.32  4903.4  840.55  4924.5  833.59  4945.5   836.4  4952.9  830.49
  4959.7  834.91  4970.5  825.63  4974.5  824.63  5020.5  825.63  5030.6  841.05
  5044.8  843.27  5313.7  846.34  5802.2   848.9  5844.7  842.98  5901.5  848.29
  8367.7  852.52  8408.4  852.89    8598  854.63  8670.8  862.18    8931  873.31
  8994.6  867.53  9030.4  877.02  9259.2  892.72  9369.5  909.97  9471.4  914.95
#Mann= 11 ,-1 , 0
  2704.9     .05       0  3320.8     .05       0  3325.8     .05       0
  3637.6     .05       0  4799.5     .16       0  4970.5     .05       0
  5020.5     .16       0  8367.7     .05       0  8408.4     .05       0
  8670.8     .16       0  9259.2     .05       0
#XS Ineff= 2 , 0
       0                  6498.2       0   886.8
Permanent Ineff=
       F       F
Bank Sta=4970.5,5020.5
XS Rating Curve= 0 ,0
Exp/Cntr=0.3,0.1

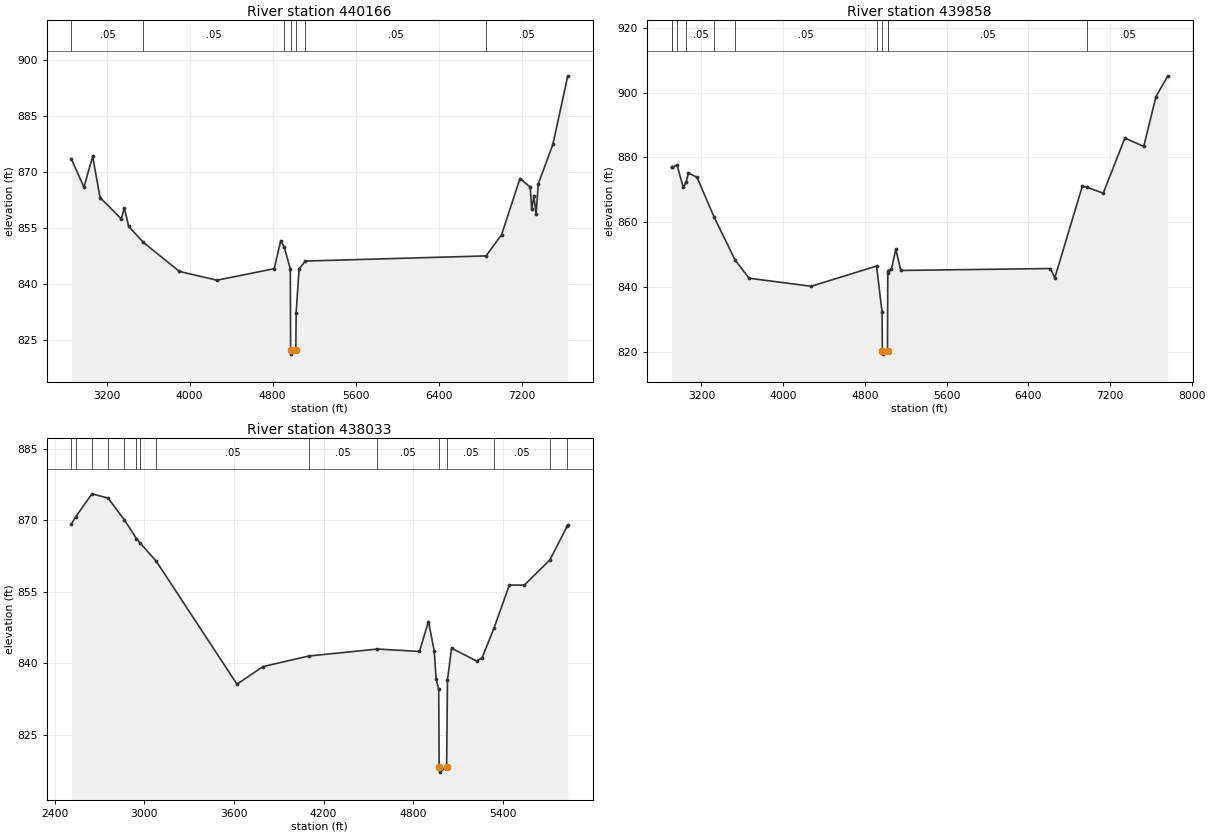
Type RM Length L Ch R = 1 ,440166  ,308,308,308
BEGIN DESCRIPTION:
Denton Creek 170.0
END DESCRIPTION:
XS GIS Cut Line= 3
      2251635.75      7205102.01      2250704.38      7204034.11
      2248250.47      7201726.91
#Sta/Elev= 30
  2860.5  873.45  2980.4     866  3064.9  874.23  3136.1   863.2  3341.1  857.49
  3369.6  860.43  3412.4  855.44  3554.6  851.16  3901.3   843.4    4263  841.05
  4814.8  844.13  4878.3  851.64    4912  849.99  4970.6  844.02  4973.6  822.24
  4977.6  821.24  5023.6  822.24  5026.8  832.38  5055.2  844.09  5115.8  846.18
  6857.9  847.56  7007.8  853.24  7184.6  868.29  7283.8  865.99  7297.9  860.02
  7318.9  863.58  7340.4  858.86  7361.4  866.84  7503.1  877.52  7645.7  895.81
#Mann= 7 ,-1 , 0
  2860.5     .05       0  3554.6     .05       0    4912     .05       0
  4973.6    .035       0  5023.6     .05       0  5115.8     .05       0
  6857.9     .05       0
Bank Sta=4973.6,5023.6
XS Rating Curve= 0 ,0
Exp/Cntr=0.3,0.1

Type RM Length L Ch R = 1 ,439858  ,1825,1825,1825
BEGIN DESCRIPTION:
Denton Creek 169.0
END DESCRIPTION:
XS GIS Cut Line= 3
      2251847.24      7204833.81      2250759.94      7203660.57
      2248357.36      7201457.71
#Sta/Elev= 30
  2907.5   877.1  2916.3  876.95  2960.7  877.69  3021.9  870.79  3052.8  872.57
  3071.8  875.24  3156.8  873.86  3325.8   861.5  3530.1  848.34    3666  842.77
  4274.9  840.28  4914.7  846.52  4968.5  832.33  4971.8  820.37  4975.8  819.37
  5021.8  820.37  5024.6  844.43  5030.4  845.13  5060.3  845.53  5102.9  851.73
  5152.2  845.16  6617.3  845.75  6659.8  842.87  6928.7  871.07  6975.2  870.81
    7134  868.96  7346.1  885.98  7530.5  883.38  7650.7  898.75  7766.7  905.14
#Mann= 11 ,-1 , 0
  2907.5     .05       0  2916.3     .05       0  2960.7     .05       0
  3052.8     .05       0  3325.8     .05       0  3530.1     .05       0
  4914.7     .05       0  4971.8    .035       0  5021.8     .05       0
  5030.4     .05       0  6975.2     .05       0
Bank Sta=4971.8,5021.8
XS Rating Curve= 0 ,0
Exp/Cntr=0.3,0.1

Type RM Length L Ch R = 1 ,438033  ,1400,1400,1400
BEGIN DESCRIPTION:
Denton Creek 168.0
END DESCRIPTION:
XS GIS Cut Line= 3
      2253475.22      7202791.11        2251229.        7201760.
      2250508.82      7201310.35
#Sta/Elev= 30
  2513.1  869.28  2542.3  870.82  2650.1   875.6  2757.9  874.71  2865.7  870.18
  2948.1   866.2  2973.5  865.24  3081.3  861.41  3620.3  835.62  3794.5  839.32
  4099.9  841.53  4559.4     843  4841.6   842.5  4901.5  848.78  4940.7  842.58
  4952.9   836.7  4970.4  834.51  4973.2  818.25  4977.2  817.15  5023.2  818.25
  5028.9  836.48    5056  843.18  5223.5   840.5  5260.1  841.12  5340.9  847.45
  5442.9  856.44  5543.2  856.43  5714.3  861.73  5829.3  868.76  5833.7     869
#Mann= 15 ,-1 , 0
  2513.1     .05       0  2542.3     .05       0  2650.1     .05       0
  2757.9     .05       0  2865.7     .05       0  2948.1     .05       0
  2973.5     .05       0  3081.3     .05       0  4099.9     .05       0
  4559.4     .05       0  4973.2    .035       0  5023.2     .05       0
  5340.9     .05       0  5714.3     .05       0  5829.3     .05       0
Bank Sta=4973.2,5023.2
XS Rating Curve= 0 ,0
Exp/Cntr=0.3,0.1