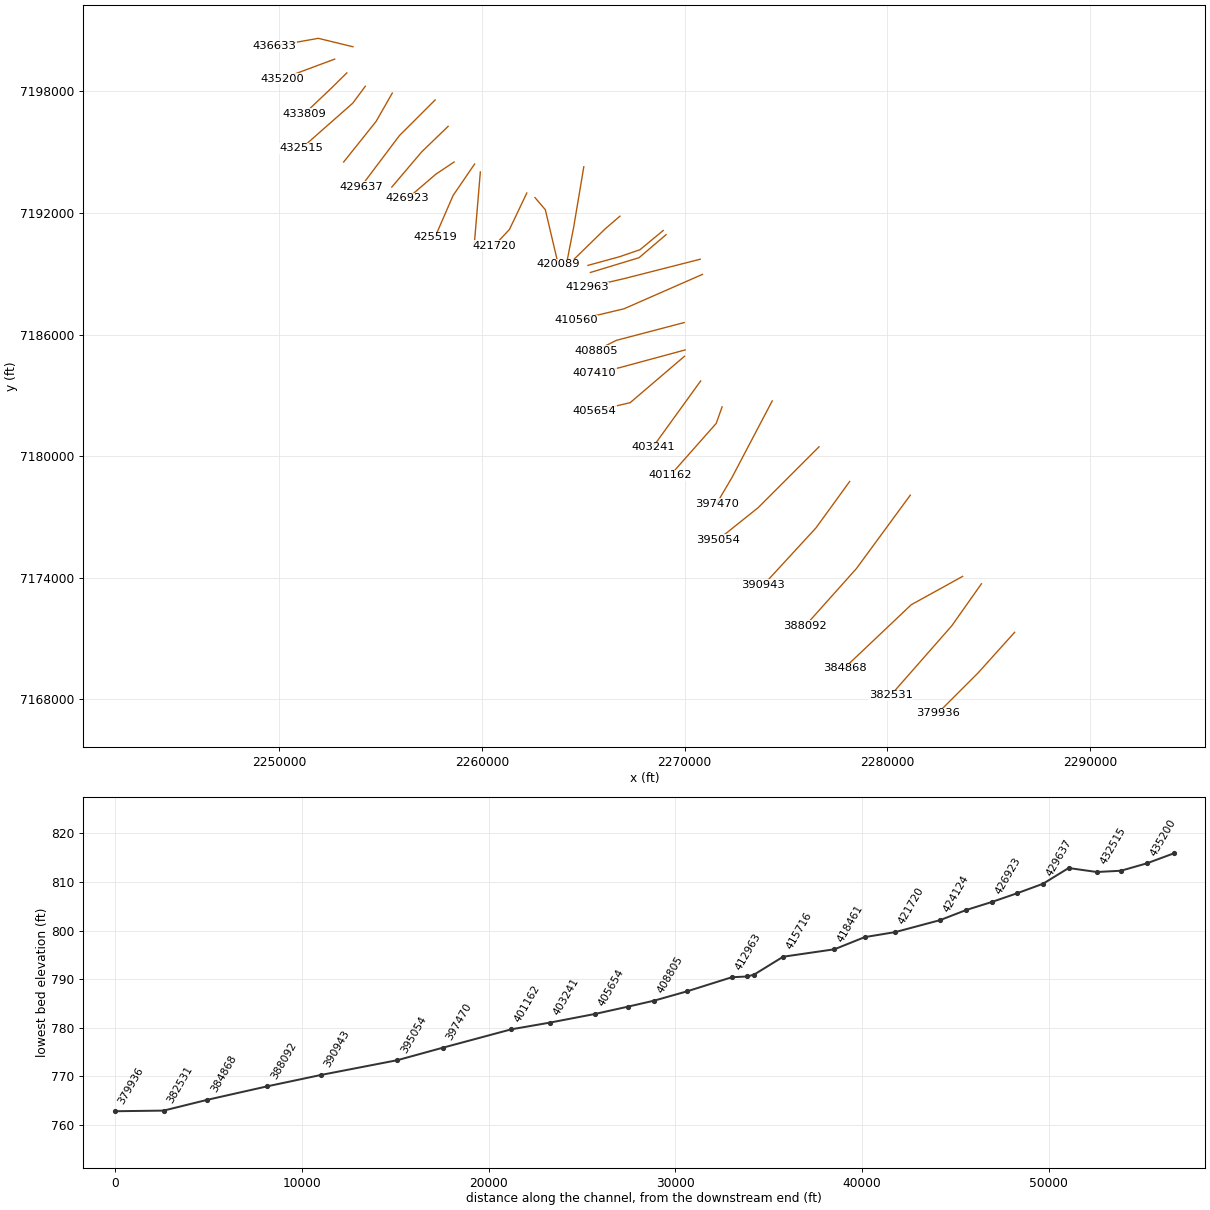
HEC-RAS study Denton Creek.prj: Denton Creek Base Level Engineering

--- Denton Creek.g01 (geometry) --- (continued)

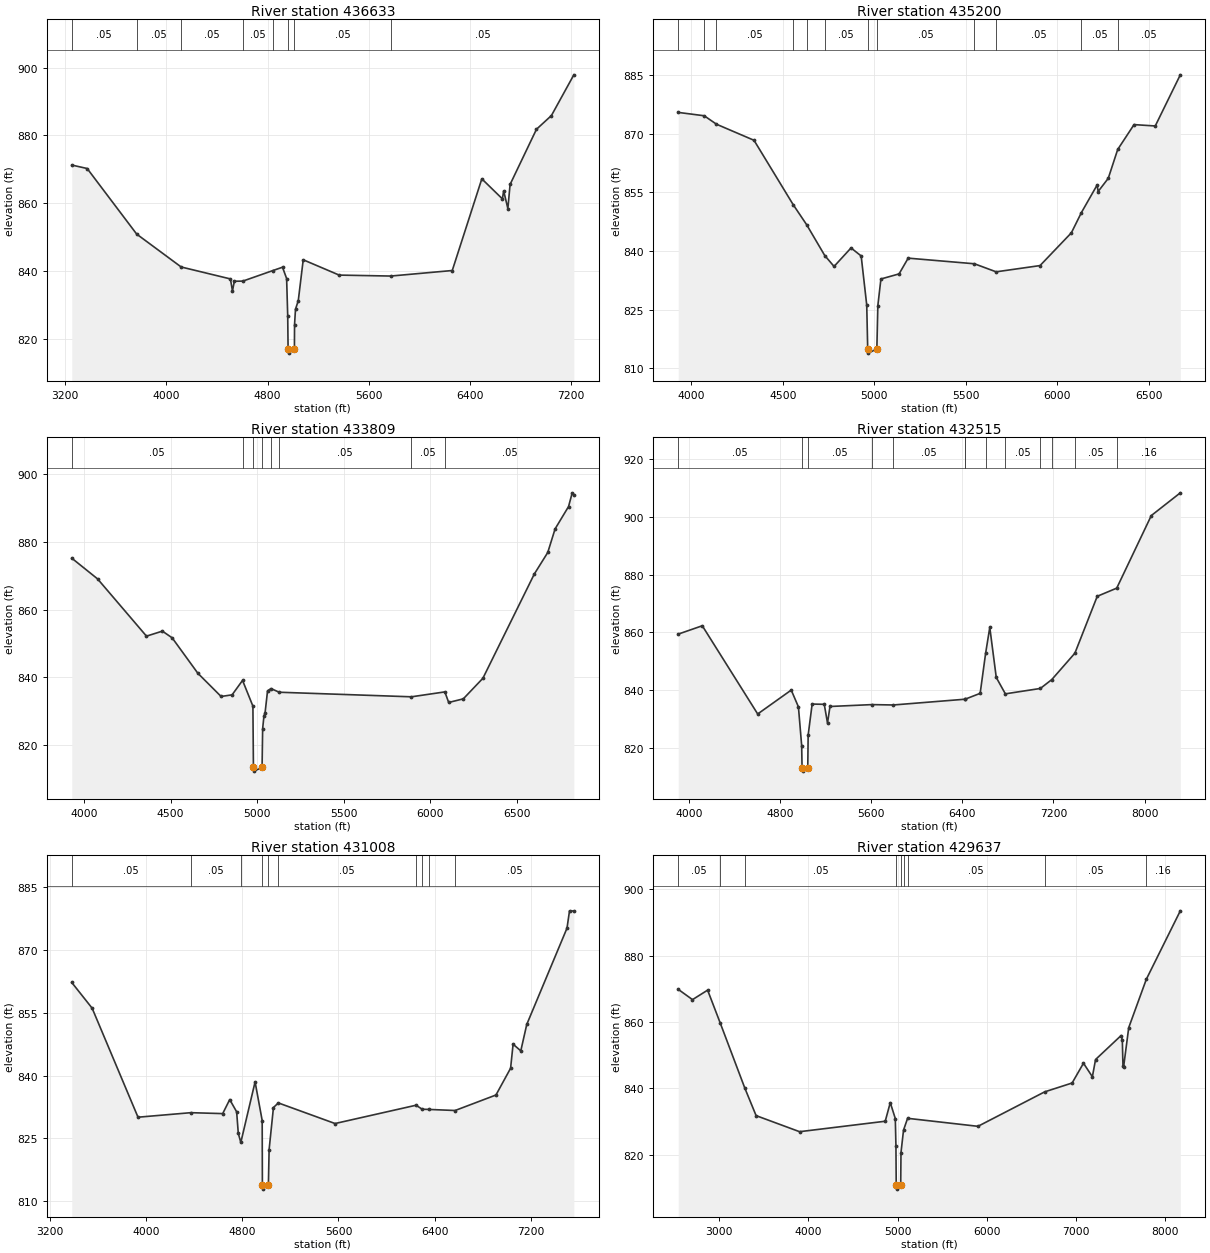
Type RM Length L Ch R = 1 ,436633  ,1433,1433,1433
BEGIN DESCRIPTION:
Denton Creek 167.0
END DESCRIPTION:
XS GIS Cut Line= 3
      2253637.72      7200195.18        2251929.        7200610.
      2249752.83      7200223.39
#Sta/Elev= 30
  3251.6  871.28  3373.3  870.26  3764.8  850.94  4116.3  841.26  4505.7  837.74
  4521.8  834.19  4536.6  837.06  4603.8   837.1  4842.2  840.22  4917.3  841.19
  4949.9  837.86  4958.5  826.87  4961.5  816.99  4965.5  815.89  5011.5  816.99
  5012.5  824.31  5020.1  828.82    5042  831.35  5081.1  843.38  5365.4  838.87
  5773.3  838.59  6259.2  840.22  6492.8  867.22  6655.3  861.32  6665.5  863.66
  6698.7  858.46  6716.3  865.57  6924.8  881.82  7042.9  885.85  7220.2  897.85
#Mann= 8 ,-1 , 0
  3251.6     .05       0  3764.8     .05       0  4116.3     .05       0
  4603.8     .05       0  4842.2     .05       0  4961.5     .05       0
  5011.5     .05       0  5773.3     .05       0
Bank Sta=4961.5,5011.5
XS Rating Curve= 0 ,0
Exp/Cntr=0.3,0.1

Type RM Length L Ch R = 1 ,435200  ,1391,1391,1391
BEGIN DESCRIPTION:
Denton Creek 166.0
END DESCRIPTION:
XS GIS Cut Line= 3
      2252737.04      7199584.61        2251729.        7199210.
      2250166.47      7198626.85
#Sta/Elev= 30
  3929.1  875.41    4071  874.55  4138.1  872.39  4343.1  868.28  4557.1  851.82
  4630.7  846.69  4729.6  838.81  4780.5  836.02  4873.2  840.75  4928.6   838.7
    4959  826.14  4964.3  814.95  4968.3  813.85  5014.3  814.95  5019.7  826.01
  5036.5  832.81  5135.6  834.11  5185.5  838.14  5547.4   836.7    5666  834.64
  5905.9  836.24  6077.1  844.62  6132.1  849.81    6218  856.86  6223.3  855.18
  6278.6  858.55  6330.2  865.93  6419.5  872.29  6535.4  871.94  6672.3  885.02
#Mann= 12 ,-1 , 0
  3929.1     .05       0    4071     .05       0  4138.1     .05       0
  4557.1     .05       0  4630.7     .05       0  4729.6     .05       0
  4964.3     .05       0  5014.3     .05       0  5547.4     .05       0
    5666     .05       0  6132.1     .05       0  6330.2     .05       0
Bank Sta=4964.3,5014.3
XS Rating Curve= 0 ,0
Exp/Cntr=0.3,0.1

Type RM Length L Ch R = 1 ,433809  ,1294,1294,1294
BEGIN DESCRIPTION:
Denton Creek 165.0
END DESCRIPTION:
XS GIS Cut Line= 3
      2253335.54      7198904.22        2252579.        7198160.
      2251244.79      7196890.94
#Sta/Elev= 30
  3928.4  875.16  4077.5  869.05  4360.3  852.15  4452.2  853.63  4508.8  851.65
  4657.3   841.2  4791.7  834.35  4855.3  834.83  4915.7  839.09  4975.6   831.5
  4978.6  813.42  4982.6  812.32  5028.6  813.42  5031.9  824.84  5039.2  828.47
  5046.1   829.6  5060.2     836  5080.1  836.68  5127.6   835.6    5892  834.25
  6085.3   835.7  6107.4  832.58    6192  833.65  6305.2  839.72  6602.5  870.49
  6680.2  876.84  6722.6   883.8  6800.3  890.38  6821.7  894.44    6831  893.83
#Mann= 8 ,-1 , 0
  3928.4     .05       0  4915.7     .16       0  4978.6     .07       0
  5028.6     .16       0  5080.1     .05       0  5127.6     .05       0
    5892     .05       0  6085.3     .05       0
Bank Sta=4978.6,5028.6
XS Rating Curve= 0 ,0
Exp/Cntr=0.3,0.1

Type RM Length L Ch R = 1 ,432515  ,1507,1507,1507
BEGIN DESCRIPTION:
Denton Creek 164.0
END DESCRIPTION:
XS GIS Cut Line= 3
       2254247.5      7198247.37      2253627.62      7197410.72
      2251103.49      7195186.27
#Sta/Elev= 30
  3907.5  859.41  4118.5   862.3  4604.7  831.81  4899.1  840.07  4962.2  834.26
  4990.6  820.87  4994.1  813.16  4998.1  812.06  5044.1  813.16  5047.5  824.49
  5082.6  835.24  5188.9  835.15  5217.4  828.67  5239.1   834.4  5607.2  835.05
  5794.2  834.92  6423.6  836.91  6424.1  836.91  6556.9  838.94  6604.7  852.76
  6641.3  861.73  6698.2  844.43  6777.9  838.77    7085  840.63  7185.2  843.69
  7388.3  852.83  7584.3  872.48  7755.3   875.3  8058.6  900.38  8313.2  908.24
#Mann= 13 ,-1 , 0
  3907.5     .05       0  4994.1    .035       0  5044.1     .05       0
  5607.2     .05       0  5794.2     .05       0  6423.6     .05       0
  6424.1     .05       0  6604.7     .05       0  6777.9     .05       0
    7085     .05       0  7185.2     .16       0  7388.3     .05       0
  7755.3     .16       0
Bank Sta=4994.1,5044.1
XS Rating Curve= 0 ,0
Exp/Cntr=0.3,0.1

Type RM Length L Ch R = 1 ,431008  ,1371,1371,1371
BEGIN DESCRIPTION:
Denton Creek 163.0
END DESCRIPTION:
XS GIS Cut Line= 3
        2255579.      7197910.01        2254779.        7196510.
      2253179.01      7194510.01
#Sta/Elev= 30
  3383.2  862.21  3552.4  856.08  3933.9  830.05  4372.7  831.13  4637.9  830.91
  4696.2  834.26  4753.8  831.34  4767.5  826.18  4788.5  824.03  4907.1  838.48
  4966.1  829.26  4967.8  813.98  4971.8  812.88  5017.8  813.98  5023.7  822.32
  5059.7  832.36  5100.4  833.46  5571.9  828.54    6245  832.91  6296.5  831.95
    6349  831.91  6569.8  831.65  6909.4  835.35  7031.1  841.74  7051.9  847.48
  7115.9  845.89  7165.5   852.2  7500.1  875.19  7520.9  879.32  7556.9  879.27
#Mann= 10 ,-1 , 0
  3383.2     .05       0  4372.7     .05       0  4788.5     .05       0
  4967.8    .035       0  5017.8     .05       0  5100.4     .05       0
    6245     .05       0  6296.5     .05       0    6349     .05       0
  6569.8     .05       0
Bank Sta=4967.8,5017.8
XS Rating Curve= 0 ,0
Exp/Cntr=0.3,0.1

Type RM Length L Ch R = 1 ,429637  ,1376,1376,1376
BEGIN DESCRIPTION:
Denton Creek 162.0
END DESCRIPTION:
XS GIS Cut Line= 3
      2257693.53      7197571.82        2255929.        7195810.
      2254037.16      7193300.15
#Sta/Elev= 30
  2537.8  869.82  2697.9  866.72  2867.6  869.58  3009.9  859.63  3286.4     840
    3412  831.78  3899.9  826.94  4861.6  830.09  4918.2  835.69  4974.7   830.9
  4981.8  822.66  4985.1  810.74  4989.1  809.64  5035.1  810.74  5038.6  820.67
    5067  827.41  5112.6  830.97  5902.6  828.56  6651.5  838.94  6959.8  841.61
  7087.2  847.57  7187.1  843.49  7222.8  848.68  7509.8  855.91  7523.3  854.47
  7530.6  846.73  7536.9  846.28  7595.1  858.28  7792.8  872.86  8174.3  893.47
#Mann= 9 ,-1 , 0
  2537.8     .05       0  3009.9     .05       0  3286.4     .05       0
  4985.1     .07       0  5035.1     .05       0    5067     .05       0
  5112.6     .05       0  6651.5     .05       0  7792.8     .16       0
Bank Sta=4985.1,5035.1
XS Rating Curve= 0 ,0
Exp/Cntr=0.3,0.1

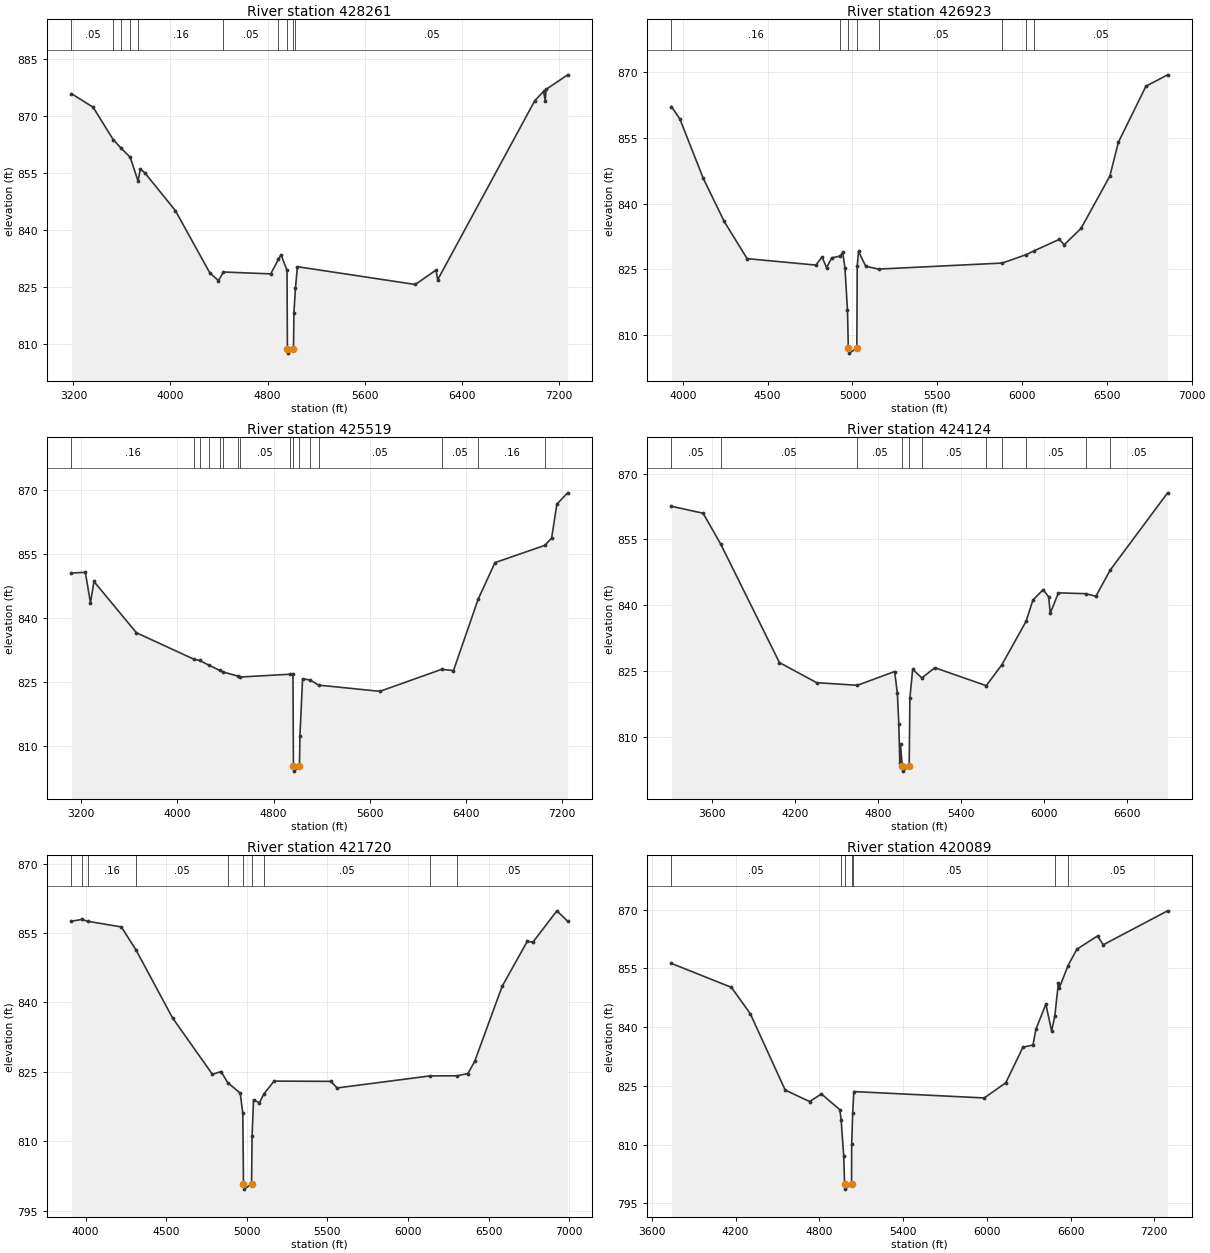
Type RM Length L Ch R = 1 ,428261  ,1338,1338,1338
BEGIN DESCRIPTION:
Denton Creek 161.0
END DESCRIPTION:
XS GIS Cut Line= 3
      2258332.63      7196268.49        2257029.        7195010.
      2255555.06      7193273.73
#Sta/Elev= 30
    3184  875.92  3362.3  872.37  3527.6  863.85  3588.2  861.75    3667  859.26
  3732.7  852.99  3751.3  856.09  3786.7  855.19  4041.2  845.14  4324.2   828.8
  4394.9  826.76  4436.9  829.03  4826.3  828.54  4889.1  832.32  4911.2  833.58
  4960.6  829.48  4963.9   808.8  4967.9   807.7  5013.9   808.8  5017.4  818.31
  5030.1  824.73    5046  830.43  6018.1  825.75  6188.3  829.54  6202.6     827
  7003.2  874.11  7074.7   876.5    7089   874.1  7095.5  877.04  7273.5  880.88
#Mann= 10 ,-1 , 0
    3184     .05       0  3527.6     .05       0  3588.2     .05       0
    3667     .05       0  3732.7     .16       0  4436.9     .05       0
  4889.1     .07       0  4963.9     .07       0  5013.9     .07       0
  5030.1     .05       0
Bank Sta=4963.9,5013.9
XS Rating Curve= 0 ,0
Exp/Cntr=0.3,0.1

Type RM Length L Ch R = 1 ,426923  ,1404,1404,1404
BEGIN DESCRIPTION:
Denton Creek 160.0
END DESCRIPTION:
XS GIS Cut Line= 3
        2258629.        7194510.        2257729.        7193910.
      2256328.98      7192709.98
#Sta/Elev= 30
  3932.5  862.13  3982.1  859.31  4120.3  845.75  4243.5  835.95  4378.7  827.46
  4784.3  825.99  4820.4  827.84  4847.4   825.4  4877.5  827.62  4928.8  828.07
  4942.1  828.93  4955.6  825.42  4970.6  815.68  4975.6  807.02  4979.6  805.92
  5025.6  807.02  5027.9   825.7  5035.6  829.12  5078.4  825.71  5154.3  825.08
    5883  826.45  6022.5  828.35  6071.4  829.25  6219.8  831.86  6248.4  830.63
  6347.2  834.33  6517.3  846.25  6567.8  853.98  6730.2  866.76  6858.1  869.36
#Mann= 8 ,-1 , 0
  3932.5     .16       0  4928.8     .05       0  4975.6    .035       0
  5025.6     .05       0  5154.3     .05       0    5883     .05       0
  6022.5     .05       0  6071.4     .05       0
Bank Sta=4975.6,5025.6
XS Rating Curve= 0 ,0
Exp/Cntr=0.3,0.1

Type RM Length L Ch R = 1 ,425519  ,1395,1395,1395
BEGIN DESCRIPTION:
Denton Creek 159.0
END DESCRIPTION:
XS GIS Cut Line= 3
      2259639.13      7194410.22        2258579.        7192860.
      2257684.91      7190797.83
#Sta/Elev= 30
  3119.2  850.52  3234.6  850.67    3277  843.55  3306.3  848.54  3659.2  836.56
  4138.3  830.36  4184.5  830.09  4258.8  829.03  4353.8  827.74  4379.4  827.39
  4499.9  826.46  4518.5  826.21  4937.2  826.87  4960.9  826.99  4964.8  805.33
  4968.8  804.23  5014.8  805.33    5019  812.54  5040.8   825.8  5102.8  825.53
  5173.7  824.33  5683.5  822.87  6196.8  828.01  6295.8  827.73  6500.8  844.39
  6640.7  852.94  7054.4  856.97  7111.7  858.67  7155.3   866.6  7244.9  869.25
#Mann= 16 ,-1 , 0
  3119.2     .16       0  4138.3     .05       0  4184.5     .16       0
  4258.8     .05       0  4353.8     .16       0  4379.4     .05       0
  4499.9     .05       0  4518.5     .05       0  4937.2     .16       0
  4964.8     .07       0  5014.8     .16       0  5102.8     .05       0
  5173.7     .05       0  6196.8     .05       0  6500.8     .16       0
  7054.4     .05       0
Bank Sta=4964.8,5014.8
XS Rating Curve= 0 ,0
Exp/Cntr=0.3,0.1

Type RM Length L Ch R = 1 ,424124  ,2404,2404,2404
BEGIN DESCRIPTION:
Denton Creek 158.0
END DESCRIPTION:
XS GIS Cut Line= 3
      2259921.57      7194018.08        2259779.        7192310.
      2259623.06      7190443.22
#Sta/Elev= 30
  3304.4  862.55  3533.3  860.97    3662  853.85  4085.2  826.91  4354.2  822.32
  4649.2  821.73  4918.1  824.87  4938.1  819.87  4948.2  812.98  4955.7  803.95
  4960.8  808.32  4973.3  803.25  4977.3  802.15  5023.3  803.25  5028.5  818.86
  5048.5  825.36    5115  823.41  5209.1  825.73  5580.3  821.64  5693.7  826.42
  5868.3   836.3    5918  841.16  5991.8  843.55  6031.9  841.89  6043.2  838.15
  6102.2  842.81  6298.2  842.62  6373.1  842.03  6476.4  847.99  6891.7  865.62
#Mann= 11 ,-1 , 0
  3304.4     .05       0    3662     .05       0  4649.2     .05       0
  4973.3    .035       0  5023.3     .05       0    5115     .05       0
  5580.3     .05       0  5693.7     .05       0  5868.3     .05       0
  6298.2     .05       0  6476.4     .05       0
Bank Sta=4973.3,5023.3
XS Rating Curve= 0 ,0
Exp/Cntr=0.3,0.1

Type RM Length L Ch R = 1 ,421720  ,1631,1631,1631
BEGIN DESCRIPTION:
Denton Creek 156.0
END DESCRIPTION:
XS GIS Cut Line= 3
       2262214.2       7192979.2      2261359.16      7191184.43
       2260616.9      7190388.04
#Sta/Elev= 30
  3912.9  857.57  3976.7  857.93  4012.3  857.55  4222.2  856.32  4314.2  851.28
  4539.5  836.68  4787.1  824.47  4840.2  825.09  4881.1  822.71  4959.2  820.42
  4975.4   816.1  4979.6  800.78  4983.6  799.68  5029.6  800.78  5032.9  811.13
  5041.8  818.96  5078.3  818.32  5105.6  820.21  5169.1  823.02  5520.7  822.96
  5560.5  821.54  6136.3  824.14  6304.5  824.17  6371.4  824.65  6413.4   827.3
  6583.4  843.49  6739.3  853.21  6774.4  853.04    6923   859.8  6989.6  857.56
#Mann= 10 ,-1 , 0
  3912.9     .16       0  3976.7     .05       0  4012.3     .16       0
  4314.2     .05       0  4881.1     .16       0  4979.6     .07       0
  5029.6     .16       0  5105.6     .05       0  6136.3     .05       0
  6304.5     .05       0
Bank Sta=4979.6,5029.6
XS Rating Curve= 0 ,0
Exp/Cntr=0.3,0.1

Type RM Length L Ch R = 1 ,420089  ,1628,1628,1628
BEGIN DESCRIPTION:
Denton Creek 155.0
END DESCRIPTION:
XS GIS Cut Line= 3
      2262617.14      7192754.36      2263128.08      7192156.46
      2263762.93       7189461.1
#Sta/Elev= 30
  3740.2  856.27  4169.9  850.17  4304.9  843.45  4555.7  823.93  4730.3  821.02
    4815  822.95  4947.2  818.92  4956.1   816.4  4975.1     807  4980.9  799.95
  4984.9  798.65  5030.9  799.95  5031.9  810.07  5039.1  818.06    5047  823.56
  5981.9  821.93    6136   825.8  6259.3  834.88  6331.2  835.45  6351.8  839.43
  6423.3  845.87  6464.8  838.99  6487.6  842.87  6513.2  851.26  6518.3  849.88
  6582.5  855.73  6645.4   859.9  6793.5  863.28  6834.6  861.03  7295.8   869.7
#Mann= 7 ,-1 , 0
  3740.2     .05       0  4956.1     .16       0  4980.9     .07       0
  5030.9     .16       0  5039.1     .05       0  6487.6     .16       0
  6582.5     .05       0
Bank Sta=4980.9,5030.9
XS Rating Curve= 0 ,0
Exp/Cntr=0.3,0.1

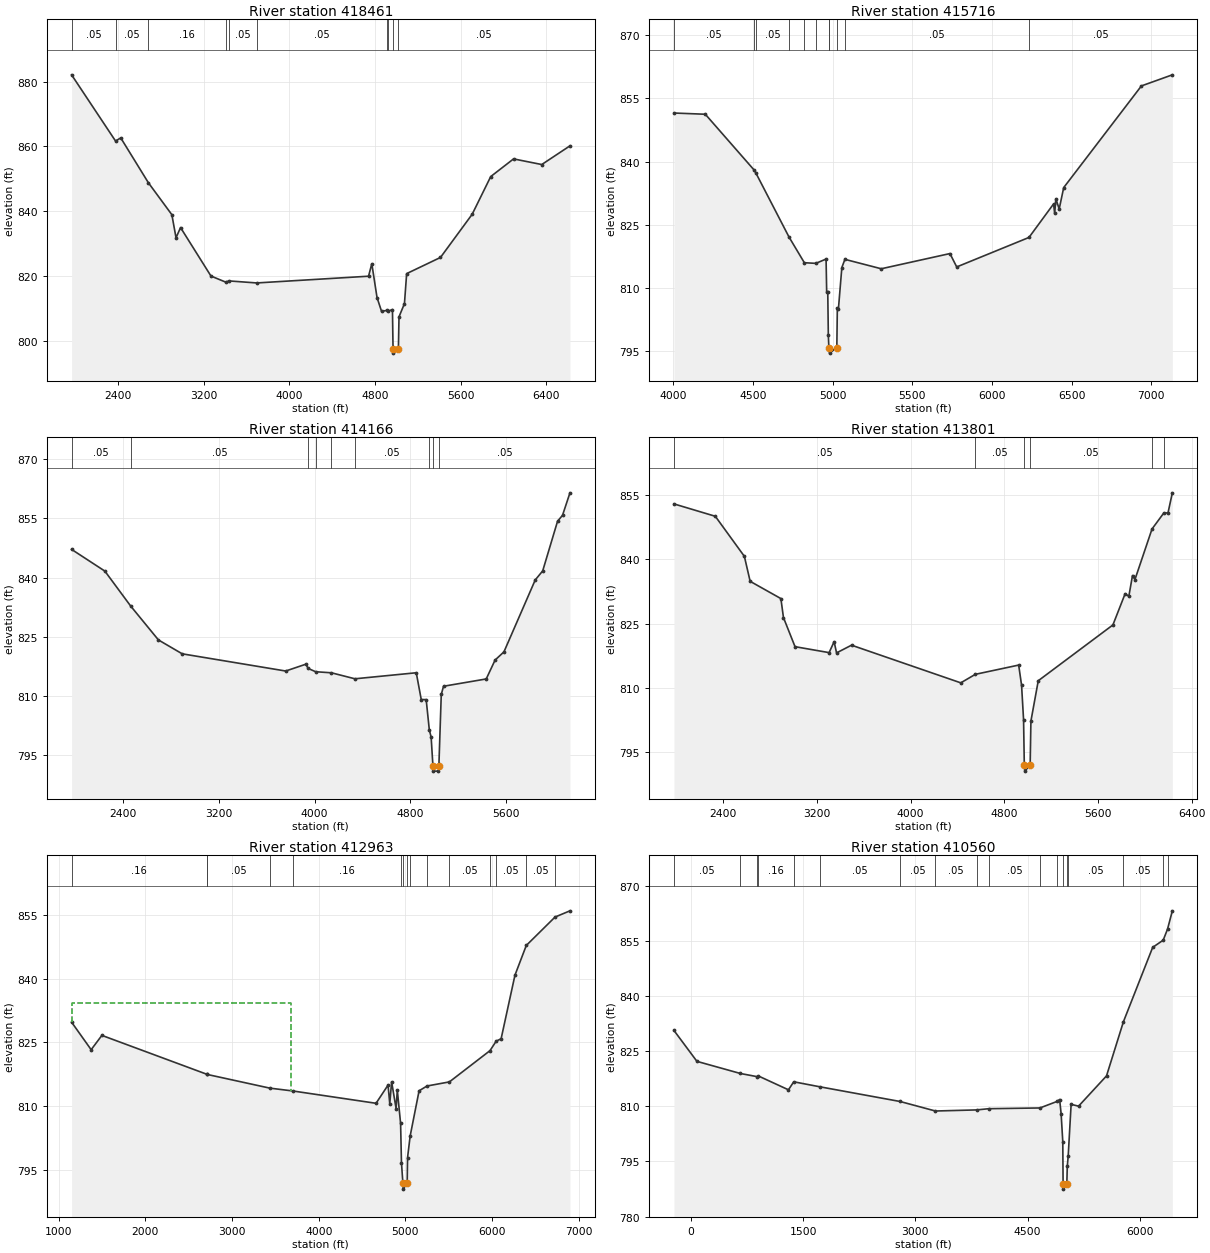
Type RM Length L Ch R = 1 ,418461  ,2745,2745,2745
BEGIN DESCRIPTION:
Denton Creek 154.0
END DESCRIPTION:
XS GIS Cut Line= 3
      2265025.75      7194272.59        2264529.        7191310.
      2264214.13      7189694.45
#Sta/Elev= 30
  1969.2  882.11  2379.2  861.67  2428.1  862.62  2685.8  848.77  2904.7  838.91
  2943.7  831.78  2985.8  834.93  3269.7  819.95  3405.5   818.1  3440.4  818.44
  3696.6  817.82  4739.9   819.9  4770.4  823.76    4819  813.32  4861.6  809.02
    4912  809.36  4924.9  809.14    4963   809.6  4968.5  797.44  4972.5  796.14
  5018.5  797.44  5024.1  807.35    5075  811.44  5095.4   820.7  5411.2   825.7
  5706.7  839.03  5879.9  850.68  6092.9  856.14    6356   854.4  6619.1  860.17
#Mann= 10 ,-1 , 0
  1969.2     .05       0  2379.2     .05       0  2685.8     .16       0
  3405.5     .05       0  3440.4     .05       0  3696.6     .05       0
    4912     .16       0  4924.9     .05       0  4968.5    .035       0
  5018.5     .05       0
Bank Sta=4968.5,5018.5
XS Rating Curve= 0 ,0
Exp/Cntr=0.3,0.1

Type RM Length L Ch R = 1 ,415716  ,1550,1550,1550
BEGIN DESCRIPTION:
Denton Creek 152.0
END DESCRIPTION:
XS GIS Cut Line= 3
      2266808.65      7191837.23        2266079.        7191210.
       2264527.7      7189696.64
#Sta/Elev= 30
  4003.7   851.5  4200.5  851.21  4507.5  837.97  4517.6  837.32  4726.2  822.11
  4822.4  816.03  4894.4  815.88  4958.8   816.9  4962.6  809.01  4969.4  809.01
    4973  798.79  4976.2     796  4976.3  795.91  4980.3  794.61  5026.3  795.91
  5029.5  805.25  5036.5  805.17  5057.8  814.89    5077  816.83  5305.3   814.6
  5736.6   818.2  5779.1  815.03  6232.9  822.02  6387.3  829.96  6394.3   827.7
  6401.5   831.2  6422.6  828.76  6450.9  833.83  6938.8  857.92  7133.1  860.55
#Mann= 11 ,-1 , 0
  4003.7     .05       0  4507.5     .16       0  4517.6     .05       0
  4726.2     .16       0  4822.4     .05       0  4894.4     .16       0
  4976.2     .05       0  4976.3    .035       0  5026.3     .05       0
    5077     .05       0  6232.9     .05       0
Bank Sta=4976.3,5026.3
XS Rating Curve= 0 ,0
Exp/Cntr=0.3,0.1

Type RM Length L Ch R = 1 ,414166  ,365,365,365
BEGIN DESCRIPTION:
Denton Creek 151.0
END DESCRIPTION:
XS GIS Cut Line= 4
      2268941.74      7191129.92      2267800.17      7190184.19
      2266809.81       7189842.5      2265228.98      7189409.99
#Sta/Elev= 30
  1966.7  847.16  2245.2  841.65  2460.1  832.83  2693.2   824.2  2892.2  820.68
  3757.8  816.32  3926.4  818.05  3945.6  816.98  4008.5  816.14  4140.5  815.87
  4336.9  814.35  4850.1  815.88  4891.6   809.1    4933  809.07  4959.2   801.4
  4974.5  799.56  4989.3  792.34  4993.3  790.94  5035.3  790.94  5039.3  792.34
  5059.2  810.38  5078.2  812.46  5435.3  814.31  5509.4   819.1  5583.6  821.18
  5845.4  839.42  5907.6   841.7    6032   854.3  6073.5   855.8  6135.7   861.5
#Mann= 9 ,-1 , 0
  1966.7     .05       0  2460.1     .05       0  3945.6     .05       0
  4008.5     .05       0  4140.5     .05       0  4336.9     .05       0
  4959.2     .05       0  4989.3    .035       0  5039.3     .05       0
Bank Sta=4989.3,5039.3
XS Rating Curve= 0 ,0
Exp/Cntr=0.3,0.1

Type RM Length L Ch R = 1 ,413801  ,838,838,838
BEGIN DESCRIPTION:
Denton Creek290
END DESCRIPTION:
XS GIS Cut Line= 3
      2269083.12      7190923.46      2267751.57      7189788.94
      2265353.45      7189060.33
#Sta/Elev= 30
  1979.4  852.98  2332.3  850.09  2580.5  840.73  2629.9  834.89  2892.3  830.86
  2914.3  826.43  3013.1  819.62  3304.1  818.23  3346.9  820.79  3367.8  818.17
  3495.6  819.97  4428.4  811.17    4553  813.16  4922.9  815.32  4947.6  810.62
  4964.7  802.54    4971  791.94    4975  790.54    5021  791.94  5027.4  802.23
  5090.1  811.66  5727.6   824.7  5832.1  832.01  5863.5  831.38  5894.9  836.25
  5915.8  835.31  6061.5  847.12    6163  850.89  6197.9  850.86  6235.1  855.57
#Mann= 6 ,-1 , 0
  1979.4     .05       0    4553     .05       0    4971     .05       0
    5021     .05       0  6061.5     .05       0    6163     .05       0
Bank Sta=4971,5021
XS Rating Curve= 0 ,0
Exp/Cntr=0.3,0.1

Type RM Length L Ch R = 1 ,412963  ,2403,2403,2403
BEGIN DESCRIPTION:
Denton Creek 150.0
END DESCRIPTION:
XS GIS Cut Line= 3
      2270767.83      7189713.34        2267029.        7188760.
      2265185.33      7188331.36
#Sta/Elev= 30
  1148.2  829.79    1374  823.29  1497.9  826.67  2709.4  817.49  2711.3  817.46
  3435.7  814.22  3701.3  813.55  4661.8  810.64  4800.3  814.94  4820.1  810.54
  4841.5  815.72  4893.1  809.41    4907  813.76  4945.1  805.88  4955.1  796.63
  4971.3  791.88  4975.3  790.38  5021.3  791.88  5025.4  797.82  5055.5  802.93
  5158.4  813.59  5249.8  814.72  5508.2  815.69  5976.9  823.07  6047.9   825.3
  6105.2  825.88  6264.8  840.88  6395.7   847.9  6727.4   854.6  6899.5  856.07
#Mann= 15 ,-1 , 0
  1148.2     .16       0  2709.4     .05       0  2711.3     .05       0
  3435.7     .05       0  3701.3     .16       0  4945.1     .05       0
  4971.3    .035       0  5021.3     .05       0  5055.5     .05       0
  5249.8     .05       0  5508.2     .05       0  5976.9     .05       0
  6047.9     .05       0  6395.7     .05       0  6727.4     .05       0
#XS Ineff= 2 , 0
       0  3682.1  834.21               0
Permanent Ineff=
       F       F
Bank Sta=4971.3,5021.3
XS Rating Curve= 0 ,0
Exp/Cntr=0.3,0.1

Type RM Length L Ch R = 1 ,410560  ,1755,1755,1755
BEGIN DESCRIPTION:
Denton Creek 149.0
END DESCRIPTION:
XS GIS Cut Line= 3
      2270879.49      7188966.37      2267008.08      7187267.77
       2264643.3      7186705.77
#Sta/Elev= 30
  -224.3  830.65    82.6  822.24   663.7  818.94   891.6  818.06   901.9  818.28
  1305.1   814.5    1376  816.68  1727.3  815.31  2796.8  811.32  3268.8  808.73
  3820.7  809.03  3982.2  809.36  4664.9  809.56  4894.3  811.34  4928.1  811.86
    4948     808  4970.3   800.4  4974.4  788.97  4978.4  787.47  5024.4  788.97
  5030.3  793.63  5042.9  796.57  5081.7  810.54  5181.2  810.05  5554.5  818.29
  5780.3  833.02  6171.2  853.26  6311.9  855.23  6369.6  858.22    6434  863.21
#Mann= 18 ,-1 , 0
  -224.3     .05       0   663.7     .16       0   891.6     .05       0
   901.9     .16       0    1376     .05       0  1727.3     .05       0
  2796.8     .05       0  3268.8     .05       0  3820.7     .05       0
  3982.2     .05       0  4664.9     .05       0  4894.3     .16       0
  4974.4     .07       0  5024.4     .16       0  5042.9     .05       0
  5780.3     .05       0  6311.9     .05       0  6369.6     .05       0
Bank Sta=4974.4,5024.4
XS Rating Curve= 0 ,0
Exp/Cntr=0.3,0.1

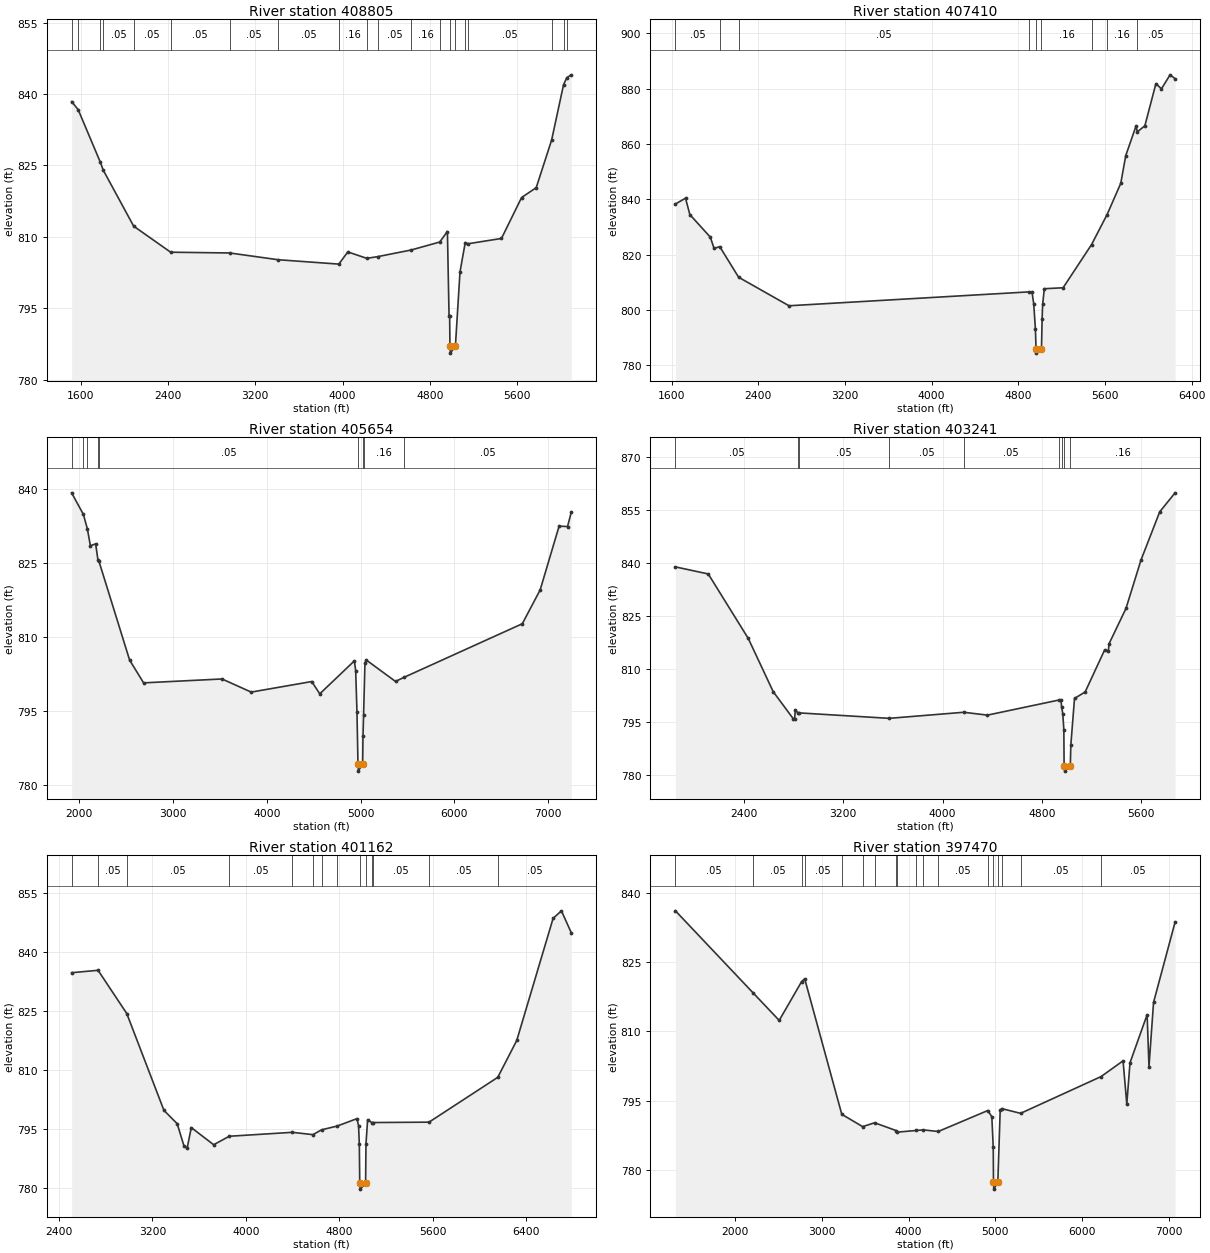
Type RM Length L Ch R = 1 ,408805  ,1395,1395,1395
BEGIN DESCRIPTION:
Denton Creek 148.0
END DESCRIPTION:
XS GIS Cut Line= 3
      2269977.91      7186589.06        2266629.        7185710.
      2265628.99        7185210.
#Sta/Elev= 30
  1516.9  838.42  1576.7  836.73  1780.2  825.67  1806.7  824.01  2085.6  812.24
  2424.6  806.77  2965.6  806.61  3409.6  805.19  3966.2  804.27  4048.6  806.83
  4223.2  805.48    4325  805.85  4630.4  807.24  4891.2  808.91  4961.7  811.12
  4976.7  793.43  4982.1  793.43    4985  787.06    4989  785.56    5035  787.06
  5077.1  802.63  5125.1   808.8  5151.3  808.55  5457.2  809.66  5641.7  818.26
  5775.9  820.34  5917.2  830.35  6026.6     842  6057.1  843.47  6097.3  844.05
#Mann= 20 ,-1 , 0
  1516.9     .05       0  1576.7     .05       0  1780.2     .16       0
  1806.7     .05       0  2085.6     .05       0  2424.6     .05       0
  2965.6     .05       0  3409.6     .05       0  3966.2     .16       0
  4223.2     .05       0    4325     .05       0  4630.4     .16       0
  4891.2     .05       0    4985    .035       0    5035     .05       0
  5125.1     .16       0  5151.3     .05       0  5917.2     .05       0
  6026.6     .05       0  6057.1     .05       0
Bank Sta=4985,5035
XS Rating Curve= 0 ,0
Exp/Cntr=0.3,0.1

Type RM Length L Ch R = 1 ,407410  ,1756,1756,1756
BEGIN DESCRIPTION:
Denton Creek 147.0
END DESCRIPTION:
XS GIS Cut Line= 3
      2270025.49       7185238.9        2266779.        7184360.
      2265555.51      7184116.68
#Sta/Elev= 30
  1636.2  838.28  1729.3  840.37  1769.2  834.45  1958.1  826.28  1992.7  822.22
  2045.2  822.84  2219.4  811.77  2684.2  801.46    4898  806.48    4927  806.38
  4942.4   802.2  4958.1  793.14  4964.2  785.83  4968.2  784.33  5014.2  785.83
  5019.9  796.77  5025.1  802.04  5040.3  807.63  5213.7  807.97  5476.2  823.59
  5619.5  834.43  5745.9  845.76    5792  855.78  5886.6  866.48  5898.9  864.38
  5968.2  866.55  6070.1   881.8  6121.1  879.92    6201  884.99    6247   883.6
#Mann= 9 ,-1 , 0
  1636.2     .05       0  2045.2     .05       0  2219.4     .05       0
    4898     .16       0  4964.2     .07       0  5014.2     .16       0
  5476.2     .05       0  5619.5     .16       0  5898.9     .05       0
Bank Sta=4964.2,5014.2
XS Rating Curve= 0 ,0
Exp/Cntr=0.3,0.1

Type RM Length L Ch R = 1 ,405654  ,2413,2413,2413
BEGIN DESCRIPTION:
Denton Creek 146.0
END DESCRIPTION:
XS GIS Cut Line= 3
      2269993.56      7184926.91      2267312.71      7182636.94
      2265555.62      7182225.82
#Sta/Elev= 30
  1917.6  839.21  2043.1  834.82  2085.6  831.89  2117.5  828.49  2173.5  828.87
  2198.2  825.61  2209.5  825.31  2535.8  805.34  2685.1  800.71  3521.6   801.5
  3833.4  798.84    4479  800.98  4564.6  798.49  4933.5  805.16  4947.8  803.21
  4961.6  794.73  4972.2  784.33  4976.2  782.83  5022.2  784.33  5025.7  789.88
    5032  794.18  5046.6  804.69  5060.8  805.34  5372.6     801  5461.1  801.81
  6725.3  812.69  6915.8  819.54  7117.9  832.46    7208  832.38  7247.9  835.29
#Mann= 9 ,-1 , 0
  1917.6     .05       0  2043.1     .05       0  2085.6     .05       0
  2198.2     .05       0  2209.5     .05       0  4972.2     .05       0
  5022.2     .05       0    5032     .16       0  5461.1     .05       0
Bank Sta=4972.2,5022.2
XS Rating Curve= 0 ,0
Exp/Cntr=0.3,0.1

Type RM Length L Ch R = 1 ,403241  ,2079,2079,2079
BEGIN DESCRIPTION:
Denton Creek289
END DESCRIPTION:
XS GIS Cut Line= 2
      2270789.56      7183708.47      2268431.67      7180444.94
#Sta/Elev= 30
  1847.9  838.93  2112.4  836.93    2435  818.64  2635.6  803.58  2799.3   795.8
  2807.9  795.78    2814  798.38  2838.1  797.41    2846  797.55  3570.6  796.01
  4170.8  797.73    4362  796.92  4937.1  801.19  4954.9  801.22  4959.3  799.35
  4969.3  797.34  4977.8  792.81  4979.9  782.55  4983.9  781.05  5029.9  782.55
  5034.3  788.53  5063.7  801.64  5149.6  803.49  5306.6   815.4    5336  815.01
  5342.2  817.16  5478.3  827.14  5599.8  840.91  5750.6  854.55  5874.1  859.92
#Mann= 9 ,-1 , 0
  1847.9     .05       0  2838.1     .05       0    2846     .05       0
  3570.6     .05       0  4170.8     .05       0  4937.1     .05       0
  4959.3     .16       0  4979.9     .07       0  5029.9     .16       0
Bank Sta=4979.9,5029.9
XS Rating Curve= 0 ,0
Exp/Cntr=0.3,0.1

Type RM Length L Ch R = 1 ,401162  ,3692,3692,3692
BEGIN DESCRIPTION:
Denton Creek288
END DESCRIPTION:
XS GIS Cut Line= 3
      2271847.71      7182430.21      2271558.99      7181617.07
      2269298.92      7179060.77
#Sta/Elev= 30
  2508.6  834.76  2734.6  835.37  2980.2  824.37  3298.1  799.72  3411.7  796.31
  3468.6  790.76  3497.1   790.1  3532.2  795.33  3723.8  790.96  3856.9  793.12
    4396  794.12  4572.5  793.53  4647.3  794.76  4780.8  795.72  4949.2   797.6
  4963.4  795.85  4970.1  791.04  4973.6  781.16  4977.6  779.66  5023.6  781.16
    5027  791.19  5041.2  797.36  5078.7  796.54  5083.4  796.61  5566.4  796.71
  6154.5  808.12  6316.9   817.5    6628  848.59  6699.2  850.51  6783.6  844.92
#Mann= 14 ,-1 , 0
  2508.6     .05       0  2734.6     .05       0  2980.2     .05       0
  3856.9     .05       0    4396     .05       0  4572.5     .05       0
  4647.3     .05       0  4780.8     .05       0  4973.6    .035       0
  5023.6     .05       0  5078.7     .16       0  5083.4     .05       0
  5566.4     .05       0  6154.5     .05       0
Bank Sta=4973.6,5023.6
XS Rating Curve= 0 ,0
Exp/Cntr=0.3,0.1

Type RM Length L Ch R = 1 ,397470  ,2416,2416,2416
BEGIN DESCRIPTION:
Denton Creek 143.0
END DESCRIPTION:
XS GIS Cut Line= 3
      2274320.67      7182723.82      2272334.03      7178943.95
      2271579.02      7177660.04
#Sta/Elev= 30
  1311.5  836.11    2207  818.34  2507.8  812.38  2766.5   820.8  2801.7  821.39
  3229.2  792.05  3469.8  789.38  3607.1  790.22  3854.1  788.54    3868  788.19
  4088.3  788.55    4167  788.68  4341.2  788.33  4912.4  792.87  4958.8  791.53
  4975.1   784.9  4977.8  777.35  4981.8  775.85  5027.8  777.35  5055.1  792.89
  5073.5  793.28  5290.3  792.26    6218  800.22  6471.6  803.63  6514.5  794.27
  6551.6  803.21  6748.9  813.62  6770.3  802.37  6823.1  816.29  7071.1  833.66
#Mann= 18 ,-1 , 0
  1311.5     .05       0    2207     .05       0  2766.5     .16       0
  2801.7     .05       0  3229.2     .05       0  3469.8     .05       0
  3607.1     .05       0  3854.1     .05       0    3868     .05       0
  4088.3     .05       0    4167     .05       0  4341.2     .05       0
  4912.4     .16       0  4977.8     .07       0  5027.8     .16       0
  5073.5     .05       0  5290.3     .05       0    6218     .05       0
Bank Sta=4977.8,5027.8
XS Rating Curve= 0 ,0
Exp/Cntr=0.3,0.1

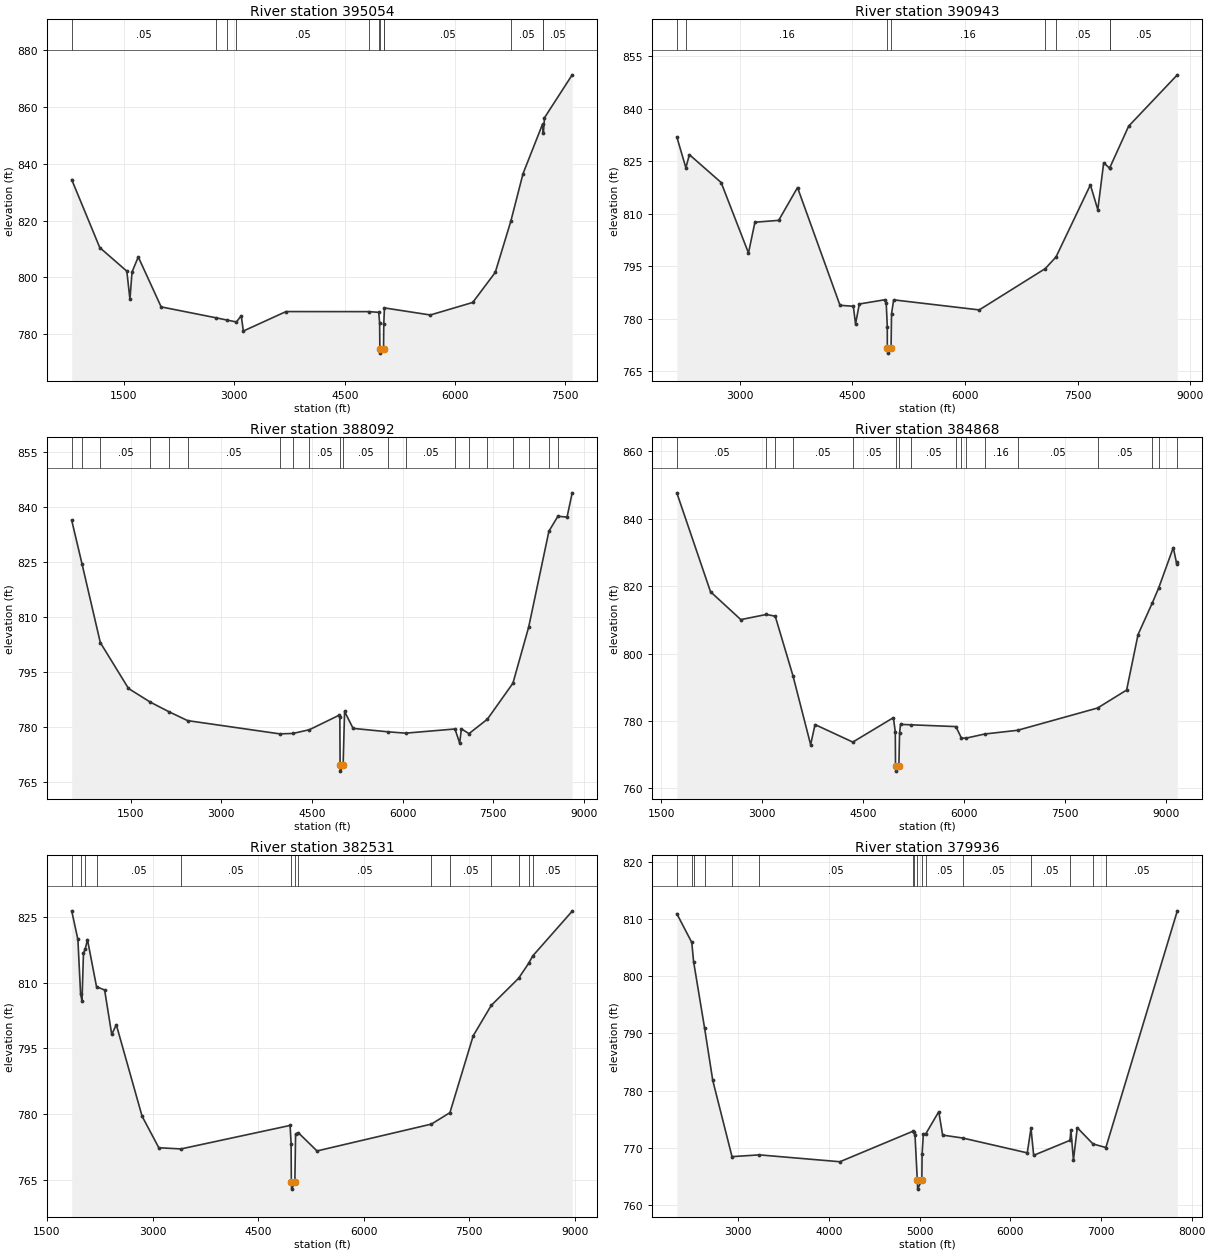
Type RM Length L Ch R = 1 ,395054  ,4111,4111,4111
BEGIN DESCRIPTION:
Denton Creek 141.0
END DESCRIPTION:
XS GIS Cut Line= 3
      2276628.98      7180459.98        2273629.        7177460.
      2271628.97      7175859.97
#Sta/Elev= 30
   788.8  834.44  1170.6  810.48  1538.3  802.18  1580.7  792.24    1609   801.9
  1693.9  807.19    2005  789.59  2756.2  785.72  2897.6  784.97  3027.6  784.28
  3093.9  786.47  3122.2  781.08    3702  787.94  4827.9  787.92  4962.4  787.67
  4974.8  784.04  4978.1   774.8  4982.1   773.3  5028.1   774.8  5031.4   783.7
  5040.5  789.23  5664.5  786.74  6240.8  791.16  6546.5  801.73  6757.7  819.71
  6924.3  836.54  7190.7  854.05    7201   850.7  7215.7  856.22  7592.7  871.35
#Mann= 12 ,-1 , 0
   788.8     .05       0  2756.2     .05       0  2897.6     .05       0
  3027.6     .05       0  4827.9     .05       0  4962.4     .16       0
  4978.1     .07       0  5028.1     .16       0  5040.5     .05       0
  6757.7     .05       0  7190.7     .16       0    7201     .05       0
Bank Sta=4978.1,5028.1
XS Rating Curve= 0 ,0
Exp/Cntr=0.3,0.1

Type RM Length L Ch R = 1 ,390943  ,2851,2851,2851
BEGIN DESCRIPTION:
Denton Creek 138.0
END DESCRIPTION:
XS GIS Cut Line= 3
      2278142.36      7178750.16        2276479.        7176460.
      2273884.09      7173639.32
#Sta/Elev= 30
  2164.1  831.93  2284.9  823.11  2331.3  826.87  2754.1  818.92  3118.2  798.81
    3204  807.59  3520.1  808.12    3771  817.48  4336.4  783.89  4514.2  783.61
  4543.5  778.56  4593.8  784.26    4937  785.48  4951.7  784.61  4966.4  777.77
  4966.5  771.84  4970.5  770.24  5016.5  771.84  5022.6  781.47    5051  785.44
  6190.3  782.57  7070.1  794.37  7212.5  797.69    7670  818.23  7768.6  811.16
  7846.9  824.53  7925.1  823.04    7926  823.04  8179.2  834.99  8827.3  849.64
#Mann= 8 ,-1 , 0
  2164.1     .05       0  2284.9     .16       0  4966.5     .07       0
  5016.5     .16       0  7070.1     .05       0  7212.5     .05       0
  7925.1     .05       0    7926     .05       0
Bank Sta=4966.5,5016.5
XS Rating Curve= 0 ,0
Exp/Cntr=0.3,0.1

Type RM Length L Ch R = 1 ,388092  ,3224,3224,3224
BEGIN DESCRIPTION:
Denton Creek 136.0
END DESCRIPTION:
XS GIS Cut Line= 3
      2281130.64      7178072.62        2278479.        7174460.
      2275944.94       7171623.9
#Sta/Elev= 30
   522.5  836.37   692.3  824.53   996.1  802.99  1462.8  790.47  1825.8  786.72
  2128.3  784.16  2441.1   781.7  3964.5  778.09  4185.4   778.2  4458.6  779.23
  4946.3  783.15    4961  782.55  4965.3  769.52  4969.3  767.92  5015.3  769.52
  5039.3  784.19  5180.6  779.58  5761.1  778.64  6050.3  778.28  6866.9  779.42
  6944.5  775.56  6972.9  779.45  7098.8  778.15  7403.2  782.09  7825.7   791.9
  8087.4  807.26  8421.7  833.37  8570.5  837.45  8721.8  837.22  8807.1  843.84
#Mann= 20 ,-1 , 0
   522.5     .05       0   692.3     .05       0   996.1     .05       0
  1825.8     .05       0  2128.3     .05       0  2441.1     .05       0
  3964.5     .05       0  4185.4     .16       0  4458.6     .05       0
  4965.3    .035       0  5015.3     .05       0  5761.1     .05       0
  6050.3     .05       0  6866.9     .05       0  7098.8     .05       0
  7403.2     .05       0  7825.7     .16       0  8087.4     .05       0
  8421.7     .16       0  8570.5     .05       0
Bank Sta=4965.3,5015.3
XS Rating Curve= 0 ,0
Exp/Cntr=0.3,0.1

Type RM Length L Ch R = 1 ,384868  ,2337,2337,2337
BEGIN DESCRIPTION:
Denton Creek 134.0
END DESCRIPTION:
XS GIS Cut Line= 3
      2283712.41      7174066.86      2281179.84      7172670.68
      2277880.17      7169543.84
#Sta/Elev= 30
  1729.6  847.68  2230.4  818.34  2680.9  810.07  3062.1  811.61  3192.2  811.08
  3456.9  793.33  3718.3  772.97  3783.6  778.94  4344.8  773.75    4948  780.99
  4976.3   776.8  4979.7  766.73  4983.7  765.13  5029.7  766.73  5039.9   776.5
    5054     779  5210.5  778.87  5877.1  778.34  5958.3  774.96  6023.1  774.89
  6305.2  776.14  6792.5  777.24  7982.1  783.85    8414  789.18  8583.8  805.64
  8797.7  815.11  8891.3  819.51  9107.3  831.43  9157.9  826.67  9167.4  827.06
#Mann= 17 ,-1 , 0
  1729.6     .05       0  3062.1     .16       0  3192.2     .05       0
  3456.9     .05       0  4344.8     .05       0  4979.7    .035       0
  5029.7     .05       0  5210.5     .05       0  5877.1     .05       0
  5958.3     .16       0  6023.1     .05       0  6305.2     .16       0
  6792.5     .05       0  7982.1     .05       0  8797.7     .05       0
  8891.3     .05       0  9157.9     .16       0
Bank Sta=4979.7,5029.7
XS Rating Curve= 0 ,0
Exp/Cntr=0.3,0.1

Type RM Length L Ch R = 1 ,382531  ,2595,2595,2595
BEGIN DESCRIPTION:
Denton Creek 132.0
END DESCRIPTION:
XS GIS Cut Line= 3
      2284640.31        7173702.      2283178.23       7171630.5
       2280160.2      7168194.17
#Sta/Elev= 30
    1852   826.4  1940.1  819.87  1978.2  807.49  1998.4   805.8  2019.4  816.75
  2045.5  817.76    2076  819.84  2204.8  809.09  2319.8  808.34  2420.7  798.21
    2486  800.41  2851.7  779.55  3089.4  772.35  3403.8  772.08  4954.2  777.44
  4968.4   773.3  4971.9  764.51  4975.9  762.91  5021.9  764.51    5032  775.45
  5069.6   775.8  5336.6  771.62  6961.7  777.75  7224.3  780.36  7555.1   797.9
  7811.2  804.83  8199.7  811.01    8343  814.44  8400.8  816.12    8961  826.32
#Mann= 14 ,-1 , 0
    1852     .05       0  1978.2     .16       0  2045.5     .05       0
  2204.8     .05       0  3403.8     .05       0  4971.9    .035       0
  5021.9     .05       0  5069.6     .05       0  6961.7     .16       0
  7224.3     .05       0  7811.2     .05       0  8199.7     .05       0
    8343     .05       0  8400.8     .05       0
Bank Sta=4971.9,5021.9
XS Rating Curve= 0 ,0
Exp/Cntr=0.3,0.1

Type RM Length L Ch R = 1 ,379936  ,2092,2092,2092
BEGIN DESCRIPTION:
Denton Creek 130.0
END DESCRIPTION:
XS GIS Cut Line= 3
        2286279.        7171310.        2284479.        7169310.
      2282478.97      7167309.97
#Sta/Elev= 30
  2323.2  810.94  2488.3  805.91  2508.4  802.54  2629.6  790.93  2719.7  781.78
  2931.9  768.46  3232.5  768.77  4121.9  767.57  4931.1  772.93  4934.8  772.84
    4950  772.18  4975.1  764.38  4979.1  762.78  5025.1  764.38  5028.1  768.94
  5042.2  772.47  5068.5  772.45  5211.9  776.32  5254.3  772.23  5477.7  771.71
  6187.7  769.12  6228.9  773.42  6258.4  768.69    6659  771.31  6668.6  773.11
  6696.8  767.89  6739.3  773.52  6912.5  770.68  7054.4  770.05  7842.4  811.44
#Mann= 16 ,-1 , 0
  2323.2     .05       0  2488.3     .05       0  2508.4     .05       0
  2629.6     .16       0  2931.9     .05       0  3232.5     .05       0
  4931.1     .05       0  4934.8     .16       0  4975.1     .07       0
  5025.1     .16       0  5068.5     .05       0  5477.7     .05       0
  6228.9     .05       0    6659     .05       0  6912.5     .05       0
  7054.4     .05       0
Bank Sta=4975.1,5025.1
XS Rating Curve= 0 ,0
Exp/Cntr=0.3,0.1