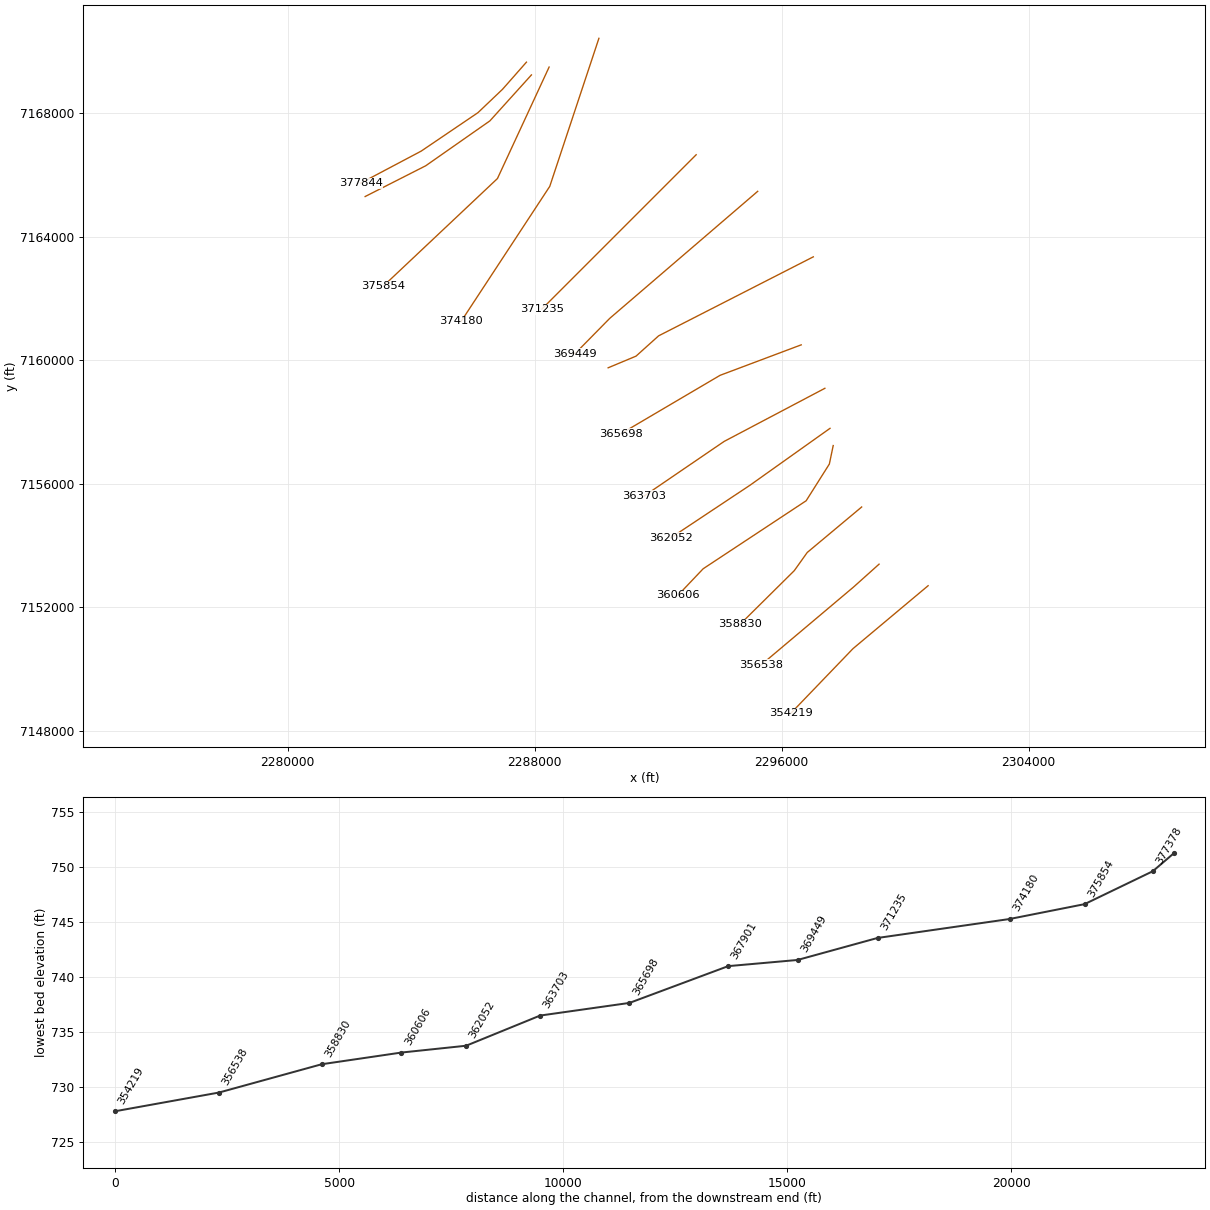
HEC-RAS study Denton Creek.prj: Denton Creek Base Level Engineering

--- Denton Creek.g01 (geometry) --- (continued)

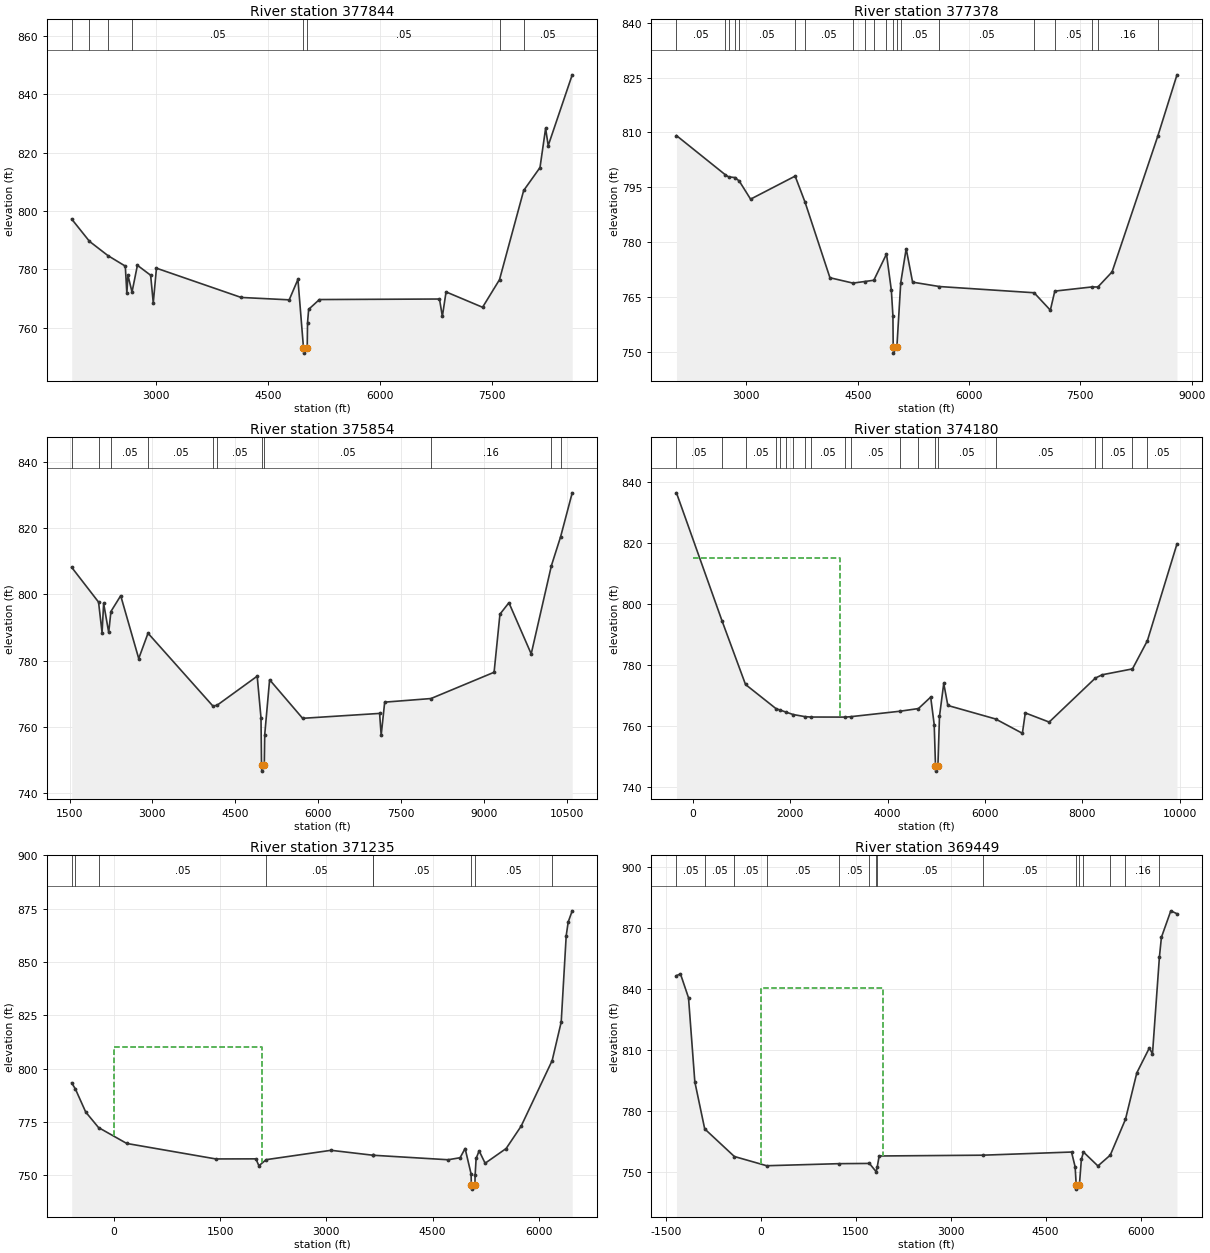
Type RM Length L Ch R = 1 ,377844  ,466,466,466
BEGIN DESCRIPTION:
Denton Creek287
END DESCRIPTION:
XS GIS Cut Line= 5
      2287732.45      7169659.95      2286956.31      7168779.55
      2286161.45      7168023.64      2284324.75      7166779.57
      2282363.88      7165742.23
#Sta/Elev= 30
    1865  797.18  2103.3  789.54    2351  784.65  2583.3  781.05  2604.2  771.69
  2618.4  777.94  2673.5  772.17  2745.6  781.33    2923  777.92  2958.1  768.43
  3000.8  780.34  4135.6  770.31  4779.9  769.49  4896.7   776.5  4971.1  753.02
  4975.1  751.22  5021.1  753.02  5025.5  761.67  5040.5  766.24  5184.3  769.59
  6793.7  769.77  6832.1  763.81  6881.7  772.21  7370.9  766.94  7597.9  776.41
  7921.8  806.98  8140.5  814.84  8215.8   828.3  8250.5  822.35  8572.3  846.63
#Mann= 8 ,-1 , 0
    1865     .16       0  2103.3     .05       0    2351     .16       0
  2673.5     .05       0  4971.1    .035       0  5021.1     .05       0
  7597.9     .16       0  7921.8     .05       0
Bank Sta=4971.1,5021.1
XS Rating Curve= 0 ,0
Exp/Cntr=0.3,0.1

Type RM Length L Ch R = 1 ,377378  ,1524,1524,1524
BEGIN DESCRIPTION:
Denton Creek286
END DESCRIPTION:
XS GIS Cut Line= 4
      2287893.58      7169246.01      2286547.83      7167757.35
      2284468.99      7166303.08      2282507.61      7165307.24
#Sta/Elev= 30
  2058.2  809.13    2713  798.46  2760.7  797.83  2847.9  797.64  2904.5  796.68
  3056.9  791.73  3657.2  798.04    3792  790.83    4126  770.23    4436  768.76
  4591.7  769.19  4717.2  769.54    4888  776.72  4953.6  766.76  4974.5  759.85
  4978.3   751.4  4982.3   749.6  5028.3   751.4    5080  768.89  5153.2  778.16
  5239.6  769.02    5601  767.82  6876.8  766.12  7095.4  761.35  7155.5  766.57
  7655.7  767.71  7736.4   767.7    7927  771.82  8541.9  808.91  8801.7  825.75
#Mann= 20 ,-1 , 0
  2058.2     .05       0    2713     .05       0  2760.7     .05       0
  2847.9     .05       0  2904.5     .05       0  3657.2     .05       0
    3792     .05       0    4436     .05       0  4591.7     .05       0
  4717.2     .05       0    4888     .05       0  4978.3     .07       0
  5028.3     .16       0    5080     .05       0    5601     .05       0
  6876.8     .16       0  7155.5     .05       0  7655.7     .05       0
  7736.4     .16       0  8541.9     .05       0
Bank Sta=4978.3,5028.3
XS Rating Curve= 0 ,0
Exp/Cntr=0.3,0.1

Type RM Length L Ch R = 1 ,375854  ,1674,1674,1674
BEGIN DESCRIPTION:
Denton Creek 127.0
END DESCRIPTION:
XS GIS Cut Line= 3
      2288466.62      7169501.08      2286793.11       7165889.7
      2283094.83      7162404.51
#Sta/Elev= 30
  1538.8  808.12  2025.1  797.63  2088.8  788.41  2117.2  797.25  2208.9  788.47
  2249.1  794.79  2426.1  799.56  2752.4  780.59  2920.6  788.24  4096.4  766.24
  4171.5   766.5  4897.3  775.27  4966.1  762.67  4975.7  748.41  4979.7  746.61
  5025.7  748.41  5033.8  757.65    5122  774.19  5719.7  762.55  7113.5  764.03
  7141.8   757.4  7205.4  767.43  8043.8  768.52  9186.2  776.45  9292.2  793.98
  9454.8  797.44  9858.2  781.99 10223.4   808.6 10391.2  817.39 10600.8  830.61
#Mann= 11 ,-1 , 0
  1538.8     .05       0  2025.1     .16       0  2249.1     .05       0
  2920.6     .05       0  4096.4     .05       0  4171.5     .05       0
  4975.7     .05       0  5025.7     .05       0  8043.8     .16       0
 10223.4     .05       0 10391.2     .16       0
Bank Sta=4975.7,5025.7
XS Rating Curve= 0 ,0
Exp/Cntr=0.3,0.1

Type RM Length L Ch R = 1 ,374180  ,2945,2945,2945
BEGIN DESCRIPTION:
Denton Creek 126.0
END DESCRIPTION:
XS GIS Cut Line= 3
      2290079.38       7170431.4      2288487.71      7165636.43
      2285617.74      7161265.23
#Sta/Elev= 30
  -337.6  836.48   598.4  794.52    1081  773.66  1709.2  765.72  1784.6  765.31
  1903.2  764.66  2056.9  763.82  2303.2  763.12  2420.6  762.99  3134.4  762.97
  3238.3   763.1  4257.1   764.9  4633.3  765.77  4884.6  769.52  4956.9  760.49
  4983.2  747.06  4987.2  745.26  5033.2  747.06  5065.4  763.26  5152.8  773.99
  5237.1  766.78  6216.4  762.36    6768  757.66  6827.8  764.34  7318.3  761.34
  8267.3  775.77  8409.6  776.85  9029.7  778.77  9335.7  788.01  9943.8  819.74
#Mann= 20 ,-1 , 0
  -337.6     .05       0   598.4     .16       0    1081     .05       0
  1709.2     .16       0  1784.6     .05       0  1903.2     .16       0
  2056.9     .16       0  2303.2     .05       0  2420.6     .05       0
  3134.4     .05       0  3238.3     .05       0  4257.1     .05       0
  4633.3     .05       0  4983.2     .05       0  5033.2     .05       0
  6216.4     .05       0  8267.3     .05       0  8409.6     .05       0
  9029.7     .05       0  9335.7     .05       0
#XS Ineff= 2 , 0
       0    3018   815.2               0
Permanent Ineff=
       F       F
Bank Sta=4983.2,5033.2
XS Rating Curve= 0 ,0
Exp/Cntr=0.3,0.1

Type RM Length L Ch R = 1 ,371235  ,1786,1786,1786
BEGIN DESCRIPTION:
Denton Creek 124.0
END DESCRIPTION:
XS GIS Cut Line= 3
      2293229.02      7166660.02        2289229.        7162660.
        2288229.        7161660.
#Sta/Elev= 30
  -598.2  793.35  -545.7  790.46  -400.2  779.68    -219   772.4   179.6  764.95
  1438.3  757.69    2004  757.73  2046.4   754.5  2149.7  757.35  3064.6  761.74
  3653.4  759.44  3661.1  759.42  4719.3  757.31    4889  758.26  4959.7  762.58
  5044.5  750.62  5047.7  745.54  5051.6  743.54    5098  745.54  5101.1     750
  5115.3  757.93  5157.7  761.48  5242.5  755.67  5539.5  762.58  5751.6  773.08
  6189.4   803.8  6317.3  821.87    6388  862.37  6416.3   868.8  6472.9  873.99
#Mann= 9 ,-1 , 0
  -598.2     .05       0  -545.7     .05       0    -219     .05       0
  2149.7     .05       0  3653.4     .05       0  3661.1     .05       0
  5047.7     .05       0    5098     .05       0  6189.4     .05       0
#XS Ineff= 2 , 0
       0    2096  810.14               0
Permanent Ineff=
       F       F
Bank Sta=5047.7,5098
XS Rating Curve= 0 ,0
Exp/Cntr=0.3,0.1

Type RM Length L Ch R = 1 ,369449  ,1548,1548,1548
BEGIN DESCRIPTION:
Denton Creek 123.0
END DESCRIPTION:
XS GIS Cut Line= 3
      2295222.79      7165475.72        2290429.        7161360.
       2289309.4      7160221.45
#Sta/Elev= 30
 -1338.7  846.64 -1275.3  847.51   -1148  835.75 -1048.1  794.34    -892  771.19
  -422.9   757.6    88.3  753.06  1238.5  754.08  1712.8  754.19  1819.1  750.12
  1836.8  752.54  1866.6  757.86  3505.5  758.25  4908.7   759.8  4965.8   752.5
  4982.6  743.54  4986.5  741.54  5032.9  743.54  5064.3  756.18  5097.6  759.79
    5326  752.95  5521.3  758.28  5761.5  775.91  5941.2  798.81  6139.2  811.05
  6188.7   808.1  6298.1  855.72  6330.1  865.52  6478.7  878.56  6576.3  877.13
#Mann= 15 ,-1 , 0
 -1338.7     .05       0    -892     .05       0  -422.9     .05       0
    88.3     .05       0  1238.5     .05       0  1712.8     .16       0
  1819.1     .05       0  1836.8     .05       0  3505.5     .05       0
  4982.6     .05       0  5032.9     .05       0  5097.6     .05       0
  5521.3     .05       0  5761.5     .16       0  6298.1     .05       0
#XS Ineff= 2 , 0
       0  1927.1  840.56               0
Permanent Ineff=
       F       F
Bank Sta=4982.6,5032.9
XS Rating Curve= 0 ,0
Exp/Cntr=0.3,0.1

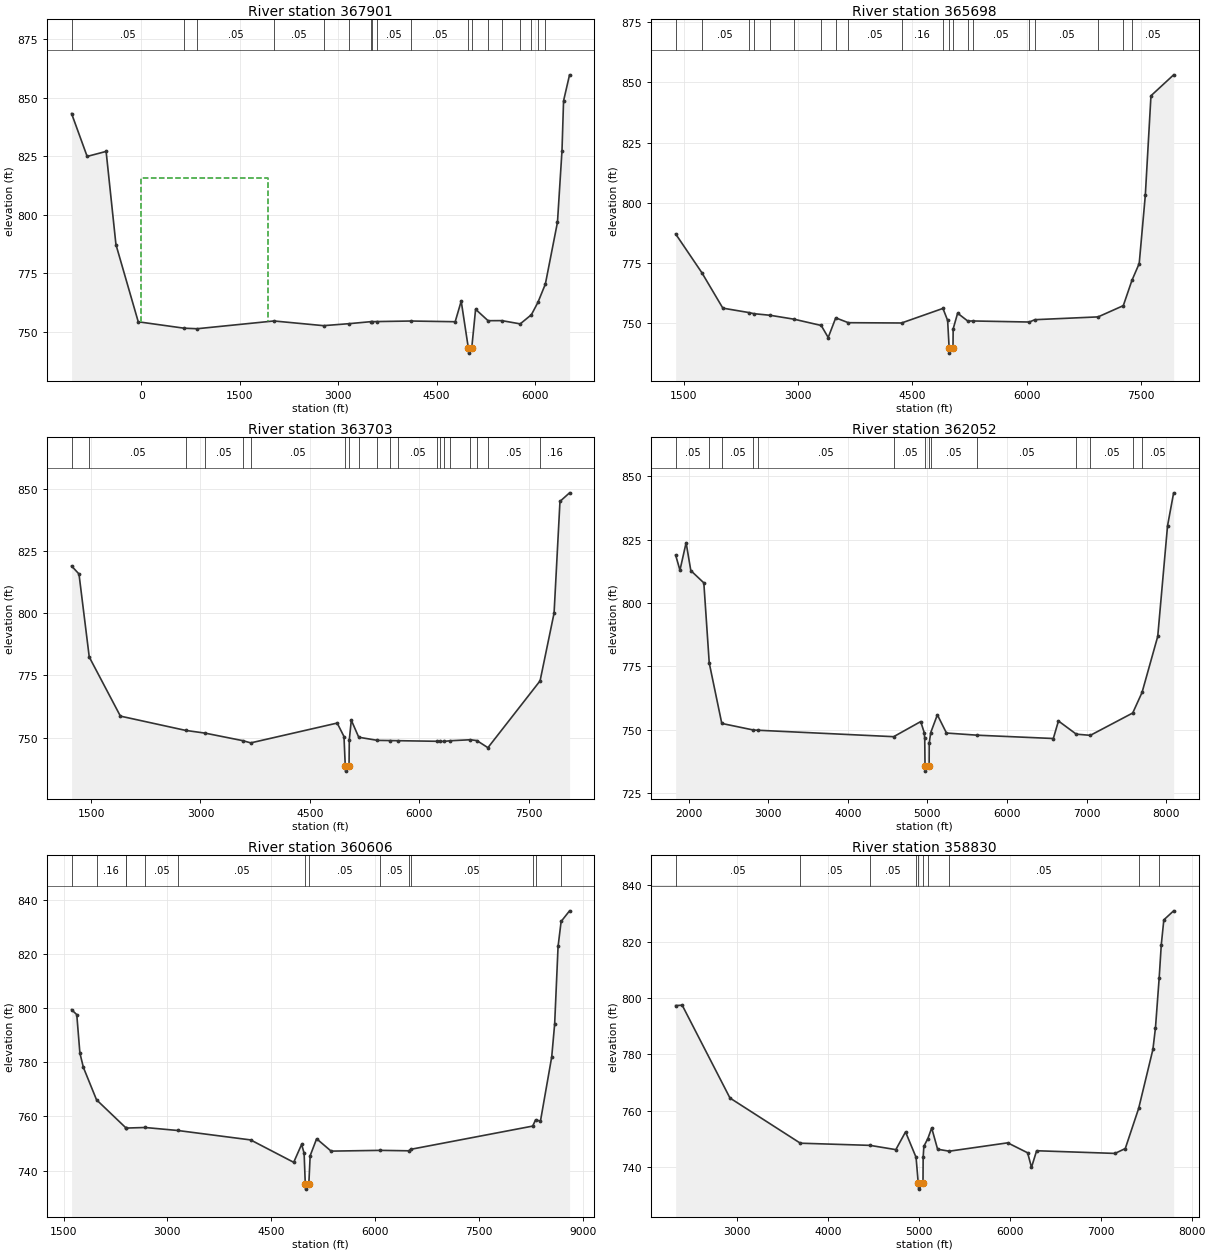
Type RM Length L Ch R = 1 ,367901  ,2203,2203,2203
BEGIN DESCRIPTION:
Denton Creek 122.0
END DESCRIPTION:
XS GIS Cut Line= 4
      2297023.84      7163353.92      2292012.81      7160794.39
      2291281.75      7160137.31      2290379.04      7159760.02
#Sta/Elev= 30
   -1061  843.22  -823.5  824.91  -534.6  827.05  -384.7  787.29     -45  754.35
     653  751.62     852  751.39  2022.9   754.7  2778.3   752.7  3167.6  753.55
  3498.1   754.4  3519.5  754.41  3598.5  754.45  4110.6  754.68  4784.4  754.38
  4876.3  763.17  4985.7  742.98  4989.7  740.98    5036  742.98  5095.4  759.69
  5285.4  754.82  5494.8  754.85  5775.3  753.46  5945.7  757.37    6045  762.63
  6158.3  770.43    6343  796.84    6412  827.42  6435.8  848.63  6527.2  859.73
#Mann= 18 ,-1 , 0
   -1061     .05       0     653     .16       0     852     .05       0
  2022.9     .05       0  2778.3     .16       0  3167.6     .05       0
  3498.1     .05       0  3519.5     .05       0  3598.5     .05       0
  4110.6     .05       0  4985.7     .05       0    5036     .05       0
  5285.4     .05       0  5494.8     .05       0  5775.3     .16       0
  5945.7     .05       0    6045     .05       0  6158.3     .05       0
#XS Ineff= 2 , 0
       0  1928.5   815.7               0
Permanent Ineff=
       F       F
Bank Sta=4985.7,5036
XS Rating Curve= 0 ,0
Exp/Cntr=0.3,0.1

Type RM Length L Ch R = 1 ,365698  ,1995,1995,1995
BEGIN DESCRIPTION:
Denton Creek 121.0
END DESCRIPTION:
XS GIS Cut Line= 3
      2296632.09      7160503.24      2294003.28      7159515.47
       2290794.5      7157626.03
#Sta/Elev= 30
  1393.4   787.1  1737.9  770.99  2012.4  756.31    2350   754.5  2422.7     754
  2632.4  753.35  2946.7  751.72  3302.6  749.12  3394.4  744.12  3493.1  752.28
  3658.4  750.27  4356.5  750.15  4899.6   756.2  4960.9  751.21  4980.9  739.64
  4984.9  737.64  5031.2  739.64  5033.4  747.69  5091.9  754.21  5225.5  750.95
  5288.5  750.99  6032.5  750.55  6105.2  751.52  6934.3  752.68  7265.1  757.35
  7378.4  767.84  7473.8  774.84  7553.8  803.12    7628  844.46  7925.4  853.15
#Mann= 20 ,-1 , 0
  1393.4     .05       0  1737.9     .05       0    2350     .05       0
  2422.7     .05       0  2632.4     .05       0  2946.7     .05       0
  3302.6     .05       0  3493.1     .05       0  3658.4     .05       0
  4356.5     .16       0  4899.6     .05       0  4980.9    .035       0
  5031.2     .16       0  5225.5     .05       0  5288.5     .05       0
  6032.5     .16       0  6105.2     .05       0  6934.3     .05       0
  7265.1     .16       0  7378.4     .05       0
Bank Sta=4980.9,5031.2
XS Rating Curve= 0 ,0
Exp/Cntr=0.3,0.1

Type RM Length L Ch R = 1 ,363703  ,1651,1651,1651
BEGIN DESCRIPTION:
Denton Creek 120.0
END DESCRIPTION:
XS GIS Cut Line= 3
      2297398.94      7159095.55      2294134.06      7157374.01
      2291545.43      7155607.65
#Sta/Elev= 30
  1233.2  818.91  1334.9   815.7  1475.5  782.34  1902.4  758.59  2795.4  752.86
  3063.4  751.76  3576.9  748.75  3689.2  747.84  4873.3   755.8  4966.6  750.39
  4984.2  738.49    4988  736.49  5035.8  738.49  5039.2  748.97  5066.9  756.96
  5168.9  750.11    5425  748.85  5602.3  748.77  5703.4  748.72  6241.2  748.48
  6279.3  748.46  6338.3  748.43  6418.5  748.69  6698.5   749.1  6788.1  748.76
  6939.2  745.91  7653.9  772.76  7845.8  799.99  7926.6  844.86    8058  848.31
#Mann= 20 ,-1 , 0
  1233.2     .05       0  1475.5     .05       0  2795.4     .16       0
  3063.4     .05       0  3576.9     .16       0  3689.2     .05       0
  4984.2    .035       0  5035.8     .05       0  5168.9     .05       0
    5425     .05       0  5602.3     .05       0  5703.4     .05       0
  6241.2     .05       0  6279.3     .05       0  6338.3     .05       0
  6418.5     .05       0  6698.5     .05       0  6788.1     .16       0
  6939.2     .05       0  7653.9     .16       0
Bank Sta=4984.2,5035.8
XS Rating Curve= 0 ,0
Exp/Cntr=0.3,0.1

Type RM Length L Ch R = 1 ,362052  ,1446,1446,1446
BEGIN DESCRIPTION:
Denton Creek 119.0
END DESCRIPTION:
XS GIS Cut Line= 3
      2297564.91      7157798.59        2294979.        7155960.
       2292409.8      7154252.79
#Sta/Elev= 30
  1836.3   818.9  1890.4  812.97  1967.8  823.81  2026.9  812.82  2190.4  807.97
  2258.4  776.39  2416.1  752.55  2814.3  749.95  2869.9  749.87  4575.9  747.33
  4915.7  753.29    4960  748.92  4966.2  746.65  4969.9  735.75  4973.7  733.75
  5021.5  735.75  5022.7  744.79  5041.4  748.93    5125  755.96  5239.2  748.77
  5628.6  747.91  6582.1  746.61  6646.3  753.52  6870.7  748.32  7047.3  747.86
  7579.7  756.67  7696.7  764.76    7894  786.86  8017.2  830.47  8093.9  843.47
#Mann= 14 ,-1 , 0
  1836.3     .05       0  2258.4     .16       0  2416.1     .05       0
  2814.3     .05       0  2869.9     .05       0  4575.9     .05       0
  4969.9     .05       0  5021.5     .05       0  5041.4     .05       0
  5628.6     .05       0  6870.7     .16       0  7047.3     .05       0
  7579.7     .16       0  7696.7     .05       0
Bank Sta=4969.9,5021.5
XS Rating Curve= 0 ,0
Exp/Cntr=0.3,0.1

Type RM Length L Ch R = 1 ,360606  ,1776,1776,1776
BEGIN DESCRIPTION:
Denton Creek285
END DESCRIPTION:
XS GIS Cut Line= 5
       2297668.8      7157241.29      2297544.06      7156642.58
      2296792.82      7155453.11      2293456.04       7153250.4
      2292646.61      7152398.06
#Sta/Elev= 30
  1616.2  799.53  1691.4  797.68  1736.4  783.49  1786.4  778.19  1976.6  766.18
  2403.9  755.72  2407.4  755.72  2677.5  755.93  3150.3  754.82  4202.4  751.33
  4824.3  743.05  4938.7  749.69  4974.8  746.43  4991.4  735.13  4995.2  733.13
    5043  735.13  5062.1   745.5  5155.4  751.76  5364.6  747.19  6072.8  747.47
    6484  747.31  6511.8  747.84  8275.5  756.45  8317.6  758.75    8388   758.3
  8550.6  782.04  8593.1  794.23  8642.4  822.91  8686.5  832.14  8808.3  836.08
#Mann= 14 ,-1 , 0
  1616.2     .05       0  1976.6     .16       0  2403.9     .05       0
  2407.4     .05       0  2677.5     .05       0  3150.3     .05       0
  4991.4    .035       0    5043     .05       0  6072.8     .05       0
    6484     .05       0  6511.8     .05       0  8275.5     .05       0
  8317.6     .16       0  8686.5     .05       0
Bank Sta=4991.4,5043
XS Rating Curve= 0 ,0
Exp/Cntr=0.3,0.1

Type RM Length L Ch R = 1 ,358830  ,2292,2292,2292
BEGIN DESCRIPTION:
Denton Creek284
END DESCRIPTION:
XS GIS Cut Line= 4
      2298590.06      7155250.78       2296827.4      7153778.19
      2296408.06      7153189.51      2294658.77      7151457.49
#Sta/Elev= 30
  2320.6   797.3  2392.8  797.42  2918.6  764.44  3693.2  748.39  4460.4  747.62
    4744   746.1    4851   752.4  4966.9  743.36    4991  734.07  4994.7  732.07
    5043  734.07  5044.9  743.32  5052.6  747.29  5096.7  750.04  5138.7  753.81
  5203.9  746.25  5332.2  745.55  5975.6  748.52  6194.8  744.98  6237.3   739.8
  6293.8  745.71  7156.5  744.76  7269.6  746.49    7417  760.77  7573.7  781.71
    7602  789.43  7642.6  807.07  7665.6  818.81  7693.9  827.75  7801.9  830.96
#Mann= 10 ,-1 , 0
  2320.6     .05       0  3693.2     .05       0  4460.4     .05       0
  4966.9     .16       0    4991     .07       0    5043     .16       0
  5096.7     .05       0  5332.2     .05       0    7417     .16       0
  7642.6     .05       0
Bank Sta=4991,5043
XS Rating Curve= 0 ,0
Exp/Cntr=0.3,0.1

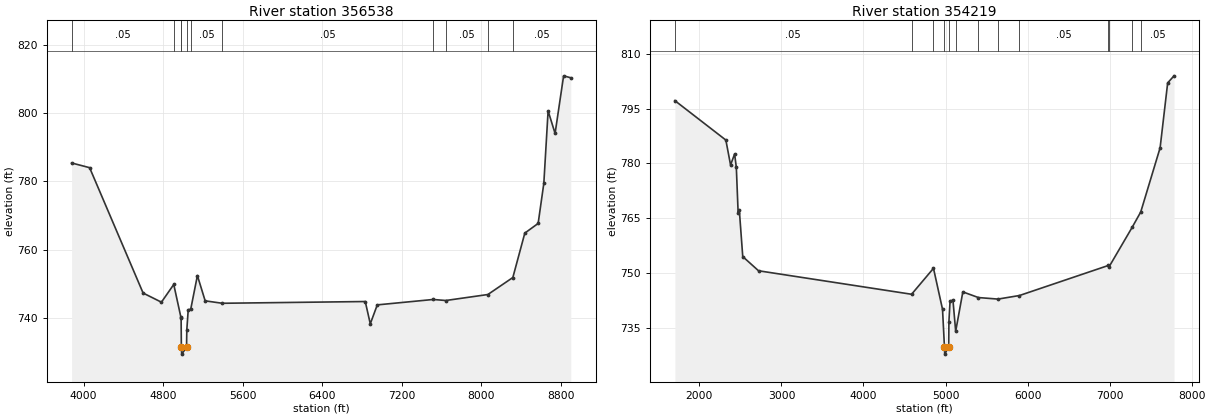
Type RM Length L Ch R = 1 ,356538  ,2319,2319,2319
BEGIN DESCRIPTION:
Denton Creek 117.0
END DESCRIPTION:
XS GIS Cut Line= 3
      2299154.45      7153399.51        2298329.        7152660.
       2295337.5      7150139.73
#Sta/Elev= 30
    3879   785.4  4059.9  784.02  4597.9  747.36  4782.1  744.69  4906.1  749.87
  4977.5  740.35  4980.2  739.96  4982.7   731.5  4986.4   729.5  5034.7   731.5
  5037.3  736.53  5051.6  742.48  5076.8  742.63  5143.9  752.47    5222  745.08
  5394.2  744.37    6832  744.88  6882.6  738.36  6952.9   743.9  7515.1  745.48
  7641.9  745.18    8065  746.93  8316.2   751.9  8436.7  764.89  8570.7  767.72
  8627.9  779.45  8670.8  800.63    8741  794.03  8826.8  810.88  8898.9  810.31
#Mann= 11 ,-1 , 0
    3879     .05       0  4906.1     .05       0  4977.5     .16       0
  4982.7     .07       0  5034.7     .16       0  5076.8     .05       0
  5394.2     .05       0  7515.1     .05       0  7641.9     .05       0
    8065     .16       0  8316.2     .05       0
Bank Sta=4982.7,5034.7
XS Rating Curve= 0 ,0
Exp/Cntr=0.3,0.1

Type RM Length L Ch R = 1 ,354219  ,1518,1518,1518
BEGIN DESCRIPTION:
Denton Creek 116.0
END DESCRIPTION:
XS GIS Cut Line= 3
      2300743.17      7152701.66      2298309.99      7150663.63
      2296292.81       7148566.3
#Sta/Elev= 30
  1701.4  797.16  2322.8  786.37    2380  779.56  2429.5  782.56  2450.4  778.87
  2472.4  766.44  2486.7  767.22  2528.6  754.49  2720.9  750.61  4586.3  744.18
  4853.4  751.28  4963.6  740.06    4987   729.8  4990.7   727.8    5039   729.8
  5041.3  736.66  5055.5  742.36  5090.7  742.55  5123.9  734.06  5211.1  744.83
    5401  743.28  5639.2  742.86  5901.6  743.84  6984.6  752.06  6995.3  751.77
  7273.9  762.46  7379.3  766.69  7615.5  784.25  7707.7  802.02  7785.3  803.95
#Mann= 13 ,-1 , 0
  1701.4     .05       0  4586.3     .05       0  4853.4     .05       0
    4987    .035       0    5039     .05       0  5123.9     .05       0
    5401     .05       0  5639.2     .05       0  5901.6     .05       0
  6984.6     .16       0  6995.3     .05       0  7273.9     .16       0
  7379.3     .05       0
Bank Sta=4987,5039
XS Rating Curve= 0 ,0
Exp/Cntr=0.3,0.1