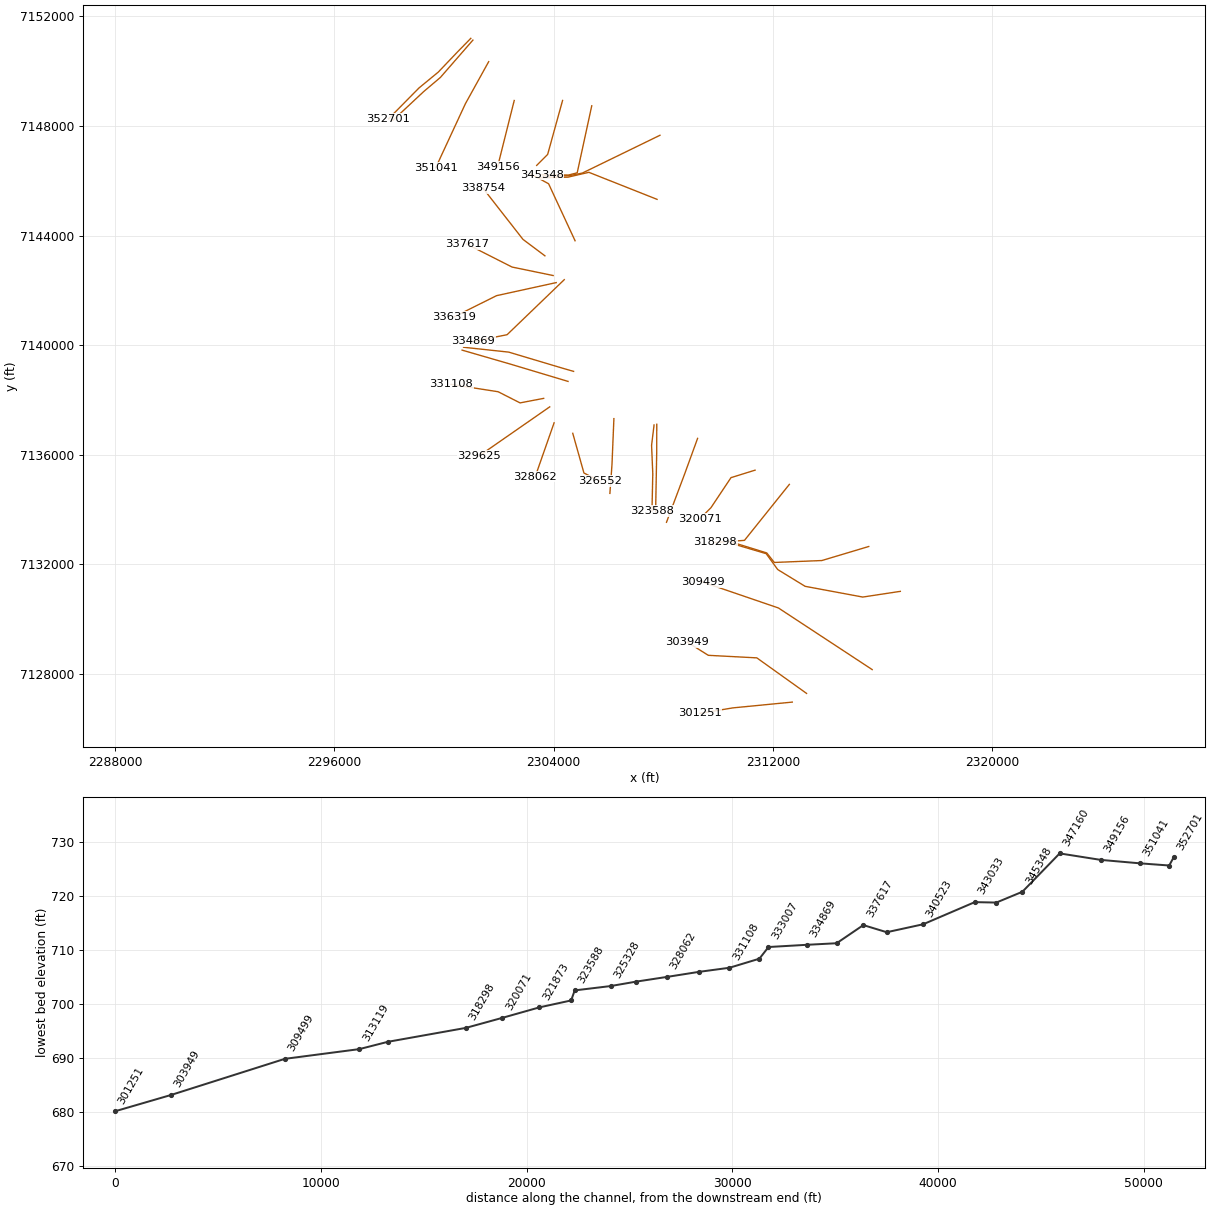
HEC-RAS study Denton Creek.prj: Denton Creek Base Level Engineering

--- Denton Creek.g01 (geometry) --- (continued)

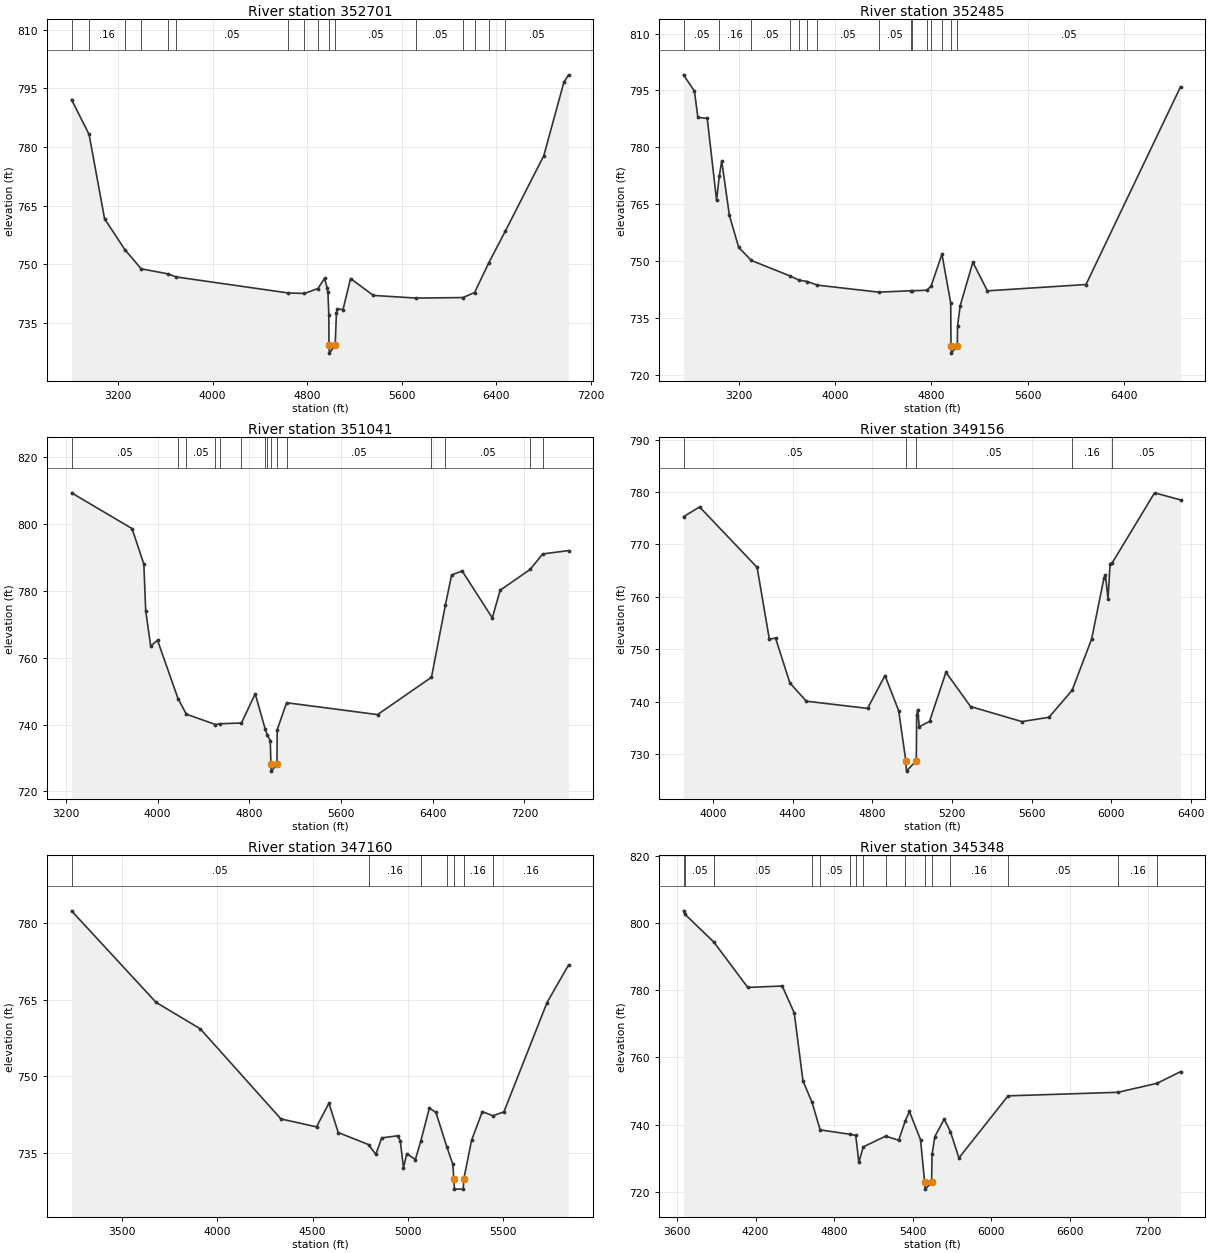
Type RM Length L Ch R = 1 ,352701  ,216,216,216
BEGIN DESCRIPTION:
Denton Creek283
END DESCRIPTION:
XS GIS Cut Line= 5
      2300976.86      7151197.61      2300501.95       7150712.2
      2299789.75      7149964.61      2299086.69      7149385.95
      2297974.74      7148257.69
#Sta/Elev= 30
  2805.6  792.14  2954.3   783.2  3085.2  761.63  3257.1  753.69  3395.2  748.79
  3621.8  747.49  3690.3  746.71  4639.6   742.6  4776.9  742.47  4891.1  743.74
  4946.8  746.34    4969  743.89  4975.5  742.77  4983.3  736.94  4984.4  729.19
    4988  727.19  5036.9  729.19  5047.2  737.34  5053.7  738.51  5103.2  738.36
    5167  746.29    5360  741.97  5721.8  741.29  6117.5  741.42  6216.5  742.71
  6337.5  750.37  6476.5  758.42  6802.2  777.75  6971.9  796.54  7011.9  798.47
#Mann= 16 ,-1 , 0
  2805.6     .05       0  2954.3     .16       0  3257.1     .05       0
  3395.2     .05       0  3621.8     .05       0  3690.3     .05       0
  4639.6     .05       0  4776.9    .063       0  4891.1     .05       0
  4984.4    .035       0  5036.9     .05       0  5721.8     .05       0
  6117.5     .16       0  6216.5     .05       0  6337.5     .16       0
  6476.5     .05       0
Bank Sta=4984.4,5036.9
XS Rating Curve= 0 ,0
Exp/Cntr=0.3,0.1

Type RM Length L Ch R = 1 ,352485  ,1444,1444,1444
BEGIN DESCRIPTION:
Denton Creek282
END DESCRIPTION:
XS GIS Cut Line= 4
      2301053.91      7151133.52      2299868.11      7149770.62
      2299262.54       7149257.9      2298138.91      7148207.45
#Sta/Elev= 30
  2736.1  799.12  2827.1  794.82  2855.6  787.87  2933.5  787.64  3011.3  766.04
  3033.5   772.3  3054.1  776.41  3117.7  762.08  3195.5  753.57  3301.4  750.12
  3620.6  746.07  3698.9  744.92  3767.3  744.57  3850.7  743.62  4361.4  741.76
  4633.5  742.14  4641.3  742.13  4760.6  742.27  4797.2  743.35  4887.7  751.79
  4960.8  738.88  4962.8  727.67  4966.4  725.67  5015.3  727.67  5017.7  732.82
  5039.4  738.17  5145.1  749.67    5266  742.11  6087.1  743.78  6874.3  795.98
#Mann= 15 ,-1 , 0
  2736.1     .05       0  3033.5     .16       0  3301.4     .05       0
  3620.6     .05       0  3698.9     .05       0  3767.3     .05       0
  3850.7     .05       0  4361.4     .05       0  4633.5     .05       0
  4641.3     .05       0  4760.6     .05       0  4797.2     .05       0
  4887.7     .05       0  4962.8    .035       0  5015.3     .05       0
Bank Sta=4962.8,5015.3
XS Rating Curve= 0 ,0
Exp/Cntr=0.3,0.1

Type RM Length L Ch R = 1 ,351041  ,1885,1885,1885
BEGIN DESCRIPTION:
Denton Creek 114.0
END DESCRIPTION:
XS GIS Cut Line= 3
      2301629.26      7150347.31        2300779.        7148810.
      2299694.89      7146470.23
#Sta/Elev= 30
  3248.9  809.24  3776.8  798.56  3879.8  787.95  3895.9  774.02  3939.4  763.48
    3999  765.18  4177.8  747.78  4250.2   743.1  4504.4  740.01  4547.5  740.24
    4731  740.46  4851.1   749.2  4939.1  738.55  4957.7  736.83  4982.8  735.23
  4988.1  728.08  4991.7  726.08  5040.6  728.08  5042.8  738.42  5124.7  746.52
  5918.2  742.97  6388.7  754.13  6510.9  775.87  6564.4   784.7  6656.1   785.9
  6919.2  771.87  6987.9  780.14  7249.4  786.35  7358.5  790.98  7584.4  791.98
#Mann= 15 ,-1 , 0
  3248.9     .05       0  4177.8     .05       0  4250.2     .05       0
  4504.4     .05       0  4547.5     .05       0    4731     .05       0
  4939.1     .05       0  4957.7     .16       0  4988.1     .07       0
  5040.6     .16       0  5124.7     .05       0  6388.7     .16       0
  6510.9     .05       0  7249.4     .05       0  7358.5     .05       0
Bank Sta=4988.1,5040.6
XS Rating Curve= 0 ,0
Exp/Cntr=0.3,0.1

Type RM Length L Ch R = 1 ,349156  ,1996,1996,1996
BEGIN DESCRIPTION:
Denton Creek 113.0
END DESCRIPTION:
XS GIS Cut Line= 3
      2302560.26       7148928.4        2302279.        7147810.
      2301952.74      7146506.64
#Sta/Elev= 30
  3851.7  775.29  3932.5  777.14  4221.3  765.61  4282.7  751.93  4314.1   752.1
  4386.2  743.53  4468.7  740.06  4776.2  738.69  4863.6  744.96  4932.7  738.23
  4968.2  728.71  4971.8  726.71    5021  728.71  5022.9  737.39  5028.1  738.45
  5035.8  735.19  5087.4   736.2  5169.9  745.58  5293.6  739.04  5551.3  736.17
  5687.4  736.99  5803.6  742.13  5901.8  751.94  5963.6  763.55  5970.7  764.19
  5984.2  759.62  5994.5  766.31  6005.8  766.51    6218  779.84  6348.5  778.49
#Mann= 5 ,-1 , 0
  3851.7     .05       0  4968.2    .035       0    5021     .05       0
  5803.6     .16       0  6005.8     .05       0
Bank Sta=4968.2,5021
XS Rating Curve= 0 ,0
Exp/Cntr=0.3,0.1

Type RM Length L Ch R = 1 ,347160  ,1812,1812,1812
BEGIN DESCRIPTION:
Denton Creek 112.0
END DESCRIPTION:
XS GIS Cut Line= 3
      2304323.15      7148929.56        2303779.        7146960.
      2303379.02      7146560.02
#Sta/Elev= 30
  3234.4  782.35  3678.3  764.44  3910.3  759.27  4333.7  741.64  4520.4  740.09
  4585.4  744.72  4634.5  738.98  4793.7  736.62  4831.6  734.71  4862.8  737.94
  4945.8  738.34  4959.9  737.41  4976.9   732.1  4994.3  734.84  5039.1   733.7
  5067.7  737.29  5112.9  743.77  5147.2  742.92    5205  736.11  5236.2  732.77
    5241  729.91  5244.5  727.91  5290.2  727.91  5293.8  729.91  5334.3  737.48
  5390.9  743.07  5445.9  742.27    5504  743.02  5730.3   764.4  5843.4  771.76
#Mann= 7 ,-1 , 0
  3234.4     .05       0  4793.7     .16       0  5067.7     .05       0
    5205     .16       0    5241     .07       0  5293.8     .16       0
  5445.9     .16       0
Bank Sta=5241,5293.8
XS Rating Curve= 0 ,0
Exp/Cntr=0.3,0.1

Type RM Length L Ch R = 1 ,345348  ,1267,1267,1267
BEGIN DESCRIPTION:
Denton Creek281
END DESCRIPTION:
XS GIS Cut Line= 4
      2305387.54      7148737.18      2304856.85      7146290.16
      2304541.33      7146208.93      2303572.07      7146224.73
#Sta/Elev= 30
  3648.9  803.58  3661.4  802.51    3882  794.23  4139.9  780.79  4403.2  781.23
  4495.3  773.22  4561.9  753.02  4631.7  746.58  4693.5  738.43  4921.9  737.12
  4965.2  736.76  4989.1   728.8  5022.5  733.38    5194  736.57  5293.4  735.35
  5343.8  741.09  5375.3  743.92  5460.4  735.53  5492.2  722.81  5495.7  720.81
    5545  722.81  5548.5  731.13  5569.7  736.43  5641.3  741.63    5689   737.9
  5753.9  730.09  6129.3  748.55  6970.2  749.61  7267.7  752.28    7448  755.75
#Mann= 16 ,-1 , 0
  3648.9     .05       0  3661.4     .05       0    3882     .05       0
  4631.7     .16       0  4693.5     .05       0  4921.9     .07       0
  4965.2     .16       0  5022.5     .07       0    5194     .16       0
  5343.8     .05       0  5492.2     .07       0    5545     .05       0
    5689     .16       0  6129.3     .05       0  6970.2     .16       0
  7267.7     .05       0
Bank Sta=5492.2,5545
XS Rating Curve= 0 ,0
Exp/Cntr=0.3,0.1

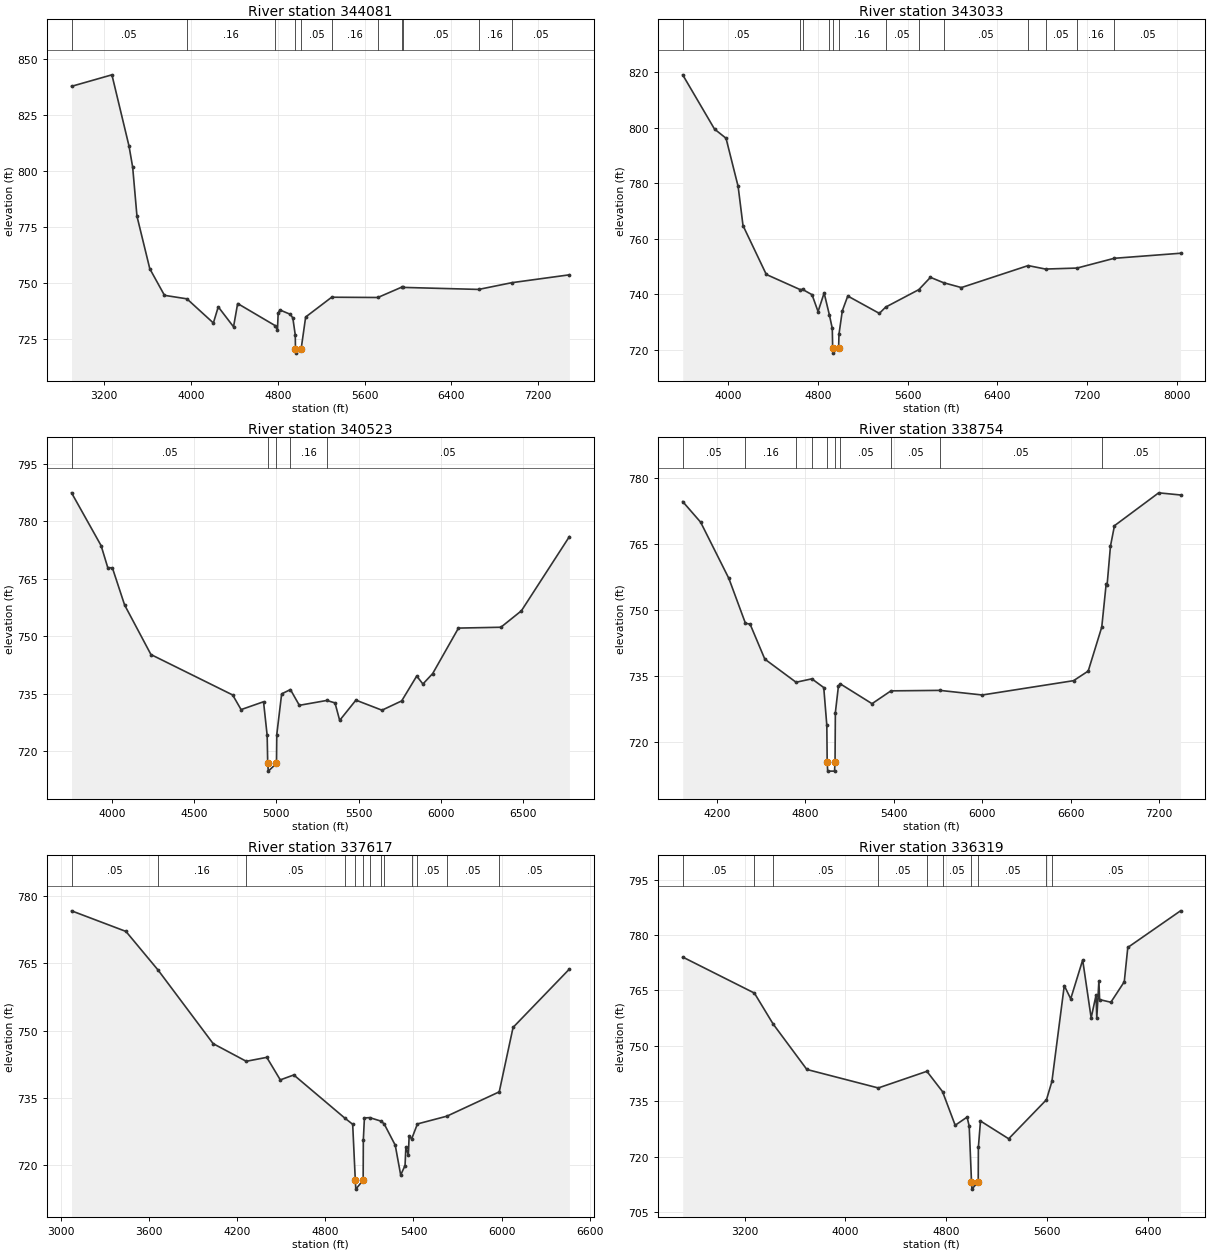
Type RM Length L Ch R = 1 ,344081  ,1048,1048,1048
BEGIN DESCRIPTION:
Denton Creek280
END DESCRIPTION:
XS GIS Cut Line= 4
      2307875.14      7147659.52      2305042.42      7146279.11
      2304552.51      7146183.08      2303614.46      7146173.27
#Sta/Elev= 30
  2898.1  837.88  3270.1  843.01  3427.8   811.2  3461.5  801.75    3501  779.92
  3619.3  756.46  3754.5   744.6  3961.3  743.04  4205.2  732.26  4250.3  739.46
  4391.1  730.55  4428.9  740.95  4773.1  731.13    4796   729.2  4802.4  736.66
  4818.3  738.08  4915.1  736.11  4937.6  734.48  4960.1  726.88  4961.8  720.81
  4965.4  718.81  5014.6  720.81  5055.8  734.93  5295.7  743.76  5721.2  743.64
  5943.9  748.31  5956.5  748.14  6650.1  747.24  6956.4  750.25  7486.6  753.76
#Mann= 11 ,-1 , 0
  2898.1     .05       0  3961.3     .16       0  4773.1     .05       0
  4961.8    .035       0  5014.6     .05       0  5295.7     .16       0
  5721.2     .05       0  5943.9     .16       0  5956.5     .05       0
  6650.1     .16       0  6956.4     .05       0
Bank Sta=4961.8,5014.6
XS Rating Curve= 0 ,0
Exp/Cntr=0.3,0.1

Type RM Length L Ch R = 1 ,343033  ,2510,2510,2510
BEGIN DESCRIPTION:
Denton Creek 111.0
END DESCRIPTION:
XS GIS Cut Line= 4
      2307768.96      7145320.83      2305282.13       7146307.6
      2304520.33      7146130.79      2303538.71      7146107.55
#Sta/Elev= 30
  3592.8  819.03  3876.5  799.51  3979.2  796.21  4087.2  778.85  4130.7  764.78
  4338.3   747.2  4640.3  741.75  4661.4  741.82  4746.1  739.92  4800.1  733.83
  4854.1  740.54  4901.8  732.48  4926.8  727.78  4930.1  720.89  4933.6  718.89
  4983.4  720.89  4986.4  725.68  5016.1  734.09  5064.8  739.44  5346.4  733.19
  5402.9  735.45  5698.5  741.74    5802  746.16  5918.7  744.23    6078  742.48
  6673.5  750.39  6828.2  749.14  7109.6   749.5  7440.7  753.01  8032.2  754.83
#Mann= 13 ,-1 , 0
  3592.8     .05       0  4640.3     .16       0  4661.4     .05       0
  4901.8     .16       0  4930.1     .07       0  4983.4     .16       0
  5402.9     .05       0  5698.5     .16       0  5918.7     .05       0
  6673.5     .16       0  6828.2     .05       0  7109.6     .16       0
  7440.7     .05       0
Bank Sta=4930.1,4983.4
XS Rating Curve= 0 ,0
Exp/Cntr=0.3,0.1

Type RM Length L Ch R = 1 ,340523  ,1769,1769,1769
BEGIN DESCRIPTION:
Denton Creek 110.0
END DESCRIPTION:
XS GIS Cut Line= 3
        2304779.        7143810.      2303813.74      7145889.65
      2303167.73      7146245.76
#Sta/Elev= 30
  3753.1   787.4  3933.1  773.61  3973.4   767.9  4001.8  767.81    4076  758.14
  4236.3  745.21  4733.8  734.66  4785.1  730.84  4921.7  732.89  4943.8   724.1
  4947.2  716.79  4950.7  714.79  5000.5  716.79  5002.3  724.33    5032  734.95
  5085.4  736.07  5139.7  731.96  5306.6  733.23  5356.8  732.59  5385.2  728.03
    5484  733.31  5642.6  730.69  5762.6  733.11  5854.2   739.6  5891.9  737.52
  5951.4  740.25  6108.3  752.11  6366.5  752.33  6491.4  756.62  6783.5  775.98
#Mann= 5 ,-1 , 0
  3753.1     .05       0  4947.2    .035       0  5000.5     .05       0
  5085.4     .16       0  5306.6     .05       0
Bank Sta=4947.2,5000.5
XS Rating Curve= 0 ,0
Exp/Cntr=0.3,0.1

Type RM Length L Ch R = 1 ,338754  ,1137,1137,1137
BEGIN DESCRIPTION:
Denton Creek 109.0
END DESCRIPTION:
XS GIS Cut Line= 3
      2303678.98      7143260.02        2302879.        7143860.
      2301415.28      7145734.81
#Sta/Elev= 30
  3967.2  774.71    4089  770.01  4280.7  757.19    4393  746.99  4424.5   746.8
  4524.5  738.83  4736.6  733.56  4843.7  734.34  4924.5  732.35  4945.3  723.75
  4947.8  715.32  4951.3  713.32  4997.6  713.32  5001.1  715.32  5003.3  726.65
  5024.2  732.72  5037.5  733.18  5252.1  728.68  5380.4   731.6  5712.4  731.71
  6000.1  730.66  6619.7  733.92  6719.2  736.11  6811.2  746.13  6841.3  756.01
  6847.6  755.79  6870.2  764.55  6897.3  769.21  7197.6   776.7  7345.7  776.21
#Mann= 10 ,-1 , 0
  3967.2     .05       0    4393     .16       0  4736.6     .05       0
  4843.7     .16       0  4947.8     .07       0  5001.1     .16       0
  5037.5     .05       0  5380.4     .05       0  5712.4     .05       0
  6811.2     .05       0
Bank Sta=4947.8,5001.1
XS Rating Curve= 0 ,0
Exp/Cntr=0.3,0.1

Type RM Length L Ch R = 1 ,337617  ,1298,1298,1298
BEGIN DESCRIPTION:
Denton Creek279
END DESCRIPTION:
XS GIS Cut Line= 3
      2303979.63      7142540.86      2302481.68      7142849.91
      2300825.49      7143689.84
#Sta/Elev= 30
  3074.2  776.75  3444.3  772.15  3663.7  763.49  4037.4  747.11  4262.6  743.17
  4402.2  744.05  4494.1  739.02    4586  740.12  4932.4  730.51  4986.6  729.11
  5004.4  716.64  5007.9  714.64  5057.8  716.64    5059  725.62  5066.4  730.52
  5102.2   730.6  5181.6  729.79  5201.7  729.14    5276  724.45  5313.1  717.79
  5342.8  719.91  5348.4  724.03  5365.1  722.25  5370.7  726.55  5387.6  725.83
  5426.9  729.19  5627.3  730.92  5983.5  736.35  6077.6  750.73  6460.7  763.75
#Mann= 13 ,-1 , 0
  3074.2     .05       0  3663.7     .16       0  4262.6     .05       0
  4932.4     .16       0  5004.4     .07       0  5057.8     .16       0
  5102.2     .05       0  5181.6     .05       0  5201.7     .05       0
  5387.6     .05       0  5426.9     .05       0  5627.3     .05       0
  5983.5     .05       0
Bank Sta=5004.4,5057.8
XS Rating Curve= 0 ,0
Exp/Cntr=0.3,0.1

Type RM Length L Ch R = 1 ,336319  ,1450,1450,1450
BEGIN DESCRIPTION:
Denton Creek 108.0
END DESCRIPTION:
XS GIS Cut Line= 3
      2304091.49      7142282.31      2301914.27      7141805.09
      2300373.47       7141036.2
#Sta/Elev= 30
  2708.8  774.04  3277.7   764.3  3426.2  755.95  3694.1  743.64    4261  738.64
  4646.7  743.14  4770.9  737.65  4871.4  728.55  4965.9  730.76  4982.7   728.3
  5000.8  713.28  5004.2  711.28  5054.2  713.28  5055.4  722.58  5072.2   729.7
  5295.9   724.9    5596  735.47  5639.1  740.42  5737.1  766.32  5788.2  762.74
  5883.2  773.24  5950.4  757.59  5989.5  763.77  5995.1  757.52  6011.9  767.59
  6017.5  762.53    6107  761.82  6213.3  767.36  6241.2  776.63  6659.7  786.54
#Mann= 10 ,-1 , 0
  2708.8     .05       0  3277.7     .05       0  3426.2     .05       0
    4261     .05       0  4646.7     .05       0  4770.9     .05       0
  5000.8    .035       0  5054.2     .05       0    5596     .16       0
  5639.1     .05       0
Bank Sta=5000.8,5054.2
XS Rating Curve= 0 ,0
Exp/Cntr=0.3,0.1

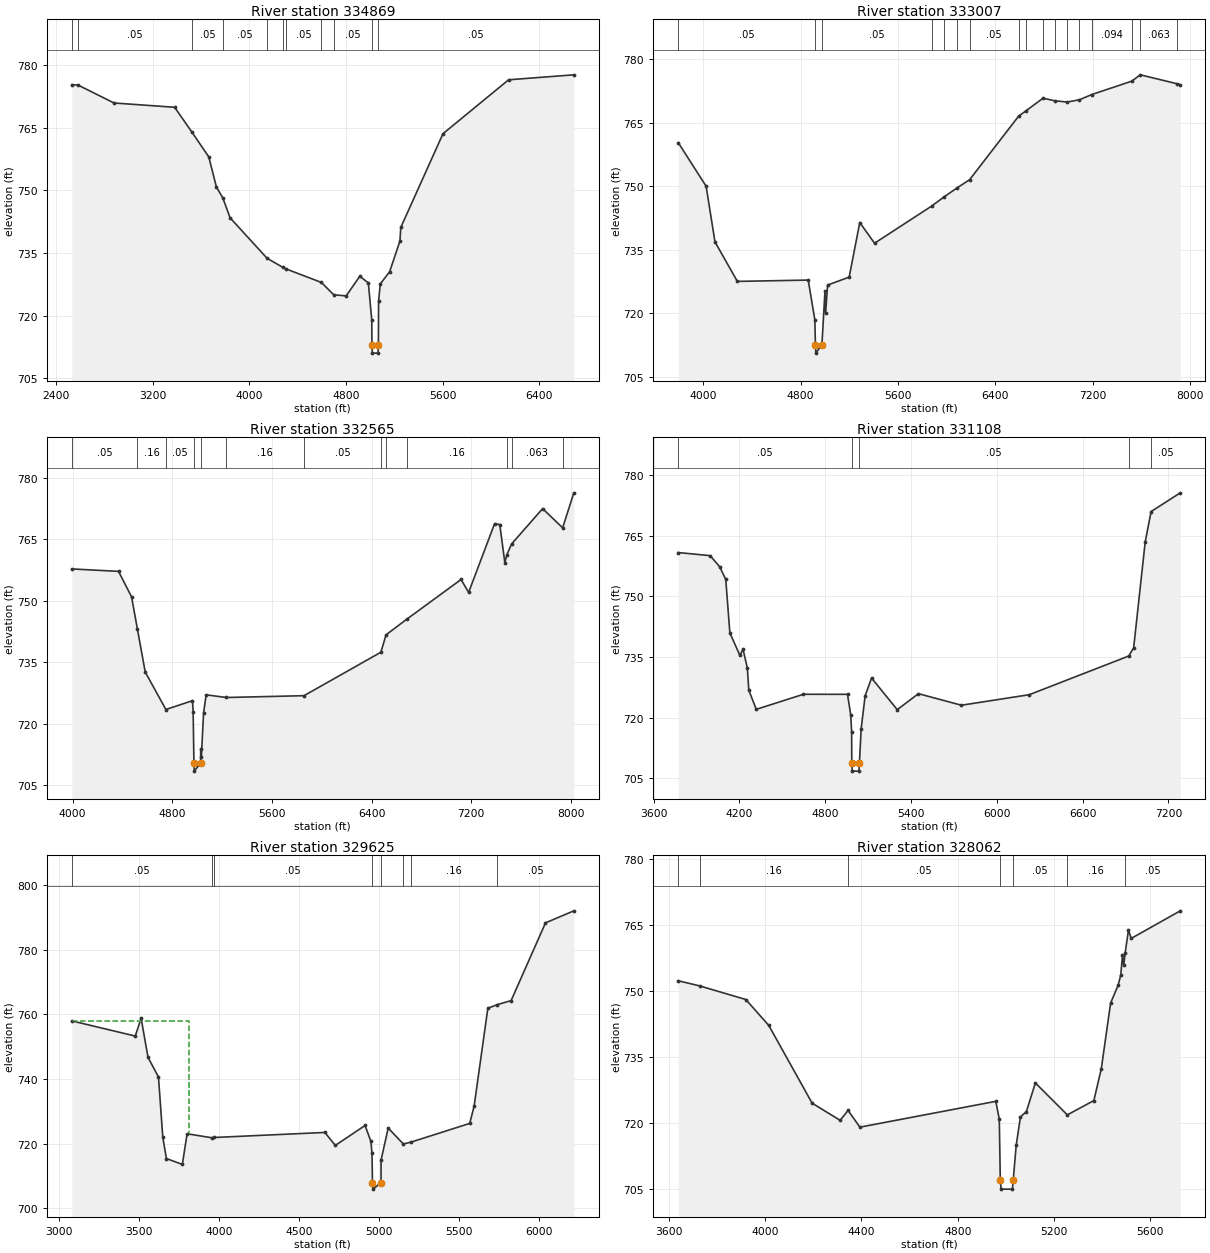
Type RM Length L Ch R = 1 ,334869  ,1862,1862,1862
BEGIN DESCRIPTION:
Denton Creek 107.0
END DESCRIPTION:
XS GIS Cut Line= 3
      2304384.89      7142389.24      2302300.05      7140380.59
      2301058.75      7140133.96
#Sta/Elev= 30
  2527.2  775.36  2580.9  775.24  2877.4  770.97  3379.6  769.94  3524.1  763.93
  3662.3  758.06  3726.1  750.81  3778.9  748.21  3839.3  743.43  4145.5  733.74
  4277.2  731.54  4302.9  731.18  4595.7  727.94  4697.5  724.99  4800.9  724.71
  4914.1  729.42  4984.9  727.82  5013.2  718.91  5014.7  712.99  5018.2  710.99
  5064.7  710.99  5068.2  712.99  5069.8  723.52  5083.9  727.58  5161.6  730.52
  5246.5  737.86  5253.7  741.12  5603.3   763.6  6147.2  776.53  6687.8  777.72
#Mann= 11 ,-1 , 0
  2527.2     .05       0  2580.9     .05       0  3524.1     .05       0
  3778.9     .05       0  4145.5     .05       0  4277.2     .16       0
  4302.9     .05       0  4595.7     .16       0  4697.5     .05       0
  5014.7    .035       0  5068.2     .05       0
Bank Sta=5014.7,5068.2
XS Rating Curve= 0 ,0
Exp/Cntr=0.3,0.1

Type RM Length L Ch R = 1 ,333007  ,442,442,442
BEGIN DESCRIPTION:
Denton Creek278
END DESCRIPTION:
XS GIS Cut Line= 4
      2304725.43      7139042.32      2304375.23      7139142.54
      2302361.21      7139744.88      2300712.87      7139922.45
#Sta/Elev= 30
  3795.2  760.26  4024.3  749.97    4097  736.84  4280.8  727.51  4863.1  727.82
  4917.5  718.41    4922  712.58  4925.5  710.58  4975.5  712.58  5000.7  725.27
  5005.9  720.03  5021.9  726.64  5199.3  728.52  5286.4  741.39    5408  736.52
  5876.1  745.27  5980.3  747.48  6084.5  749.55  6188.7  751.51  6591.5  766.51
  6649.8  767.72  6791.4  770.74  6891.3  770.12  6991.3  769.84  7091.2  770.38
  7191.2   771.6    7520  774.76    7591  776.26  7890.8  774.17  7919.5  773.93
#Mann= 17 ,-1 , 0
  3795.2     .05       0    4922    .035       0  4975.5     .05       0
  5876.1    .063       0  5980.3    .094       0  6084.5    .063       0
  6188.7     .05       0  6591.5    .063       0  6649.8     .05       0
  6791.4    .063       0  6891.3    .094       0  6991.3     .05       0
  7091.2    .063       0  7191.2    .094       0    7520     .05       0
    7591    .063       0  7890.8    .094       0
Bank Sta=4922,4975.5
XS Rating Curve= 0 ,0
Exp/Cntr=0.3,0.1

Type RM Length L Ch R = 1 ,332565  ,1457,1457,1457
BEGIN DESCRIPTION:
Denton Creek277
END DESCRIPTION:
XS GIS Cut Line= 3
      2304521.91      7138676.57      2302431.27      7139304.07
      2300658.27      7139818.13
#Sta/Elev= 30
  3993.8  757.74  4369.2  757.14  4473.6  750.93  4520.7  743.04  4583.2  732.59
  4749.1  723.45  4962.5  725.61  4967.8  722.86    4974  710.42  4977.4  708.42
  5027.5  710.42  5028.6  713.92  5033.8  711.89  5051.4  722.61  5072.2  727.03
  5234.3  726.38  5857.2  726.82  6474.2  737.42  6515.8  741.67  6685.4  745.55
  7117.4  755.16  7178.5  752.02  7386.7  768.78  7428.4  768.56  7468.8  759.27
  7485.7  761.22  7522.9  763.82    7772  772.45  7932.7  767.77  8022.6   776.3
#Mann= 13 ,-1 , 0
  3993.8     .05       0  4520.7     .16       0  4749.1     .05       0
    4974    .035       0  5027.5     .05       0  5234.3     .16       0
  5857.2     .05       0  6474.2     .16       0  6515.8     .05       0
  6685.4     .16       0  7485.7    .094       0  7522.9    .063       0
  7932.7    .094       0
Bank Sta=4974,5027.5
XS Rating Curve= 0 ,0
Exp/Cntr=0.3,0.1

Type RM Length L Ch R = 1 ,331108  ,1483,1483,1483
BEGIN DESCRIPTION:
Denton Creek276
END DESCRIPTION:
XS GIS Cut Line= 4
       2303633.7      7138056.92      2302773.31      7137892.11
       2301972.5      7138299.35      2300256.53      7138567.28
#Sta/Elev= 30
  3771.6  760.87  3994.9   760.1  4061.5  757.35    4104   754.2  4132.7  740.97
    4203  735.38  4224.4  736.97  4254.9  732.27  4265.2  726.79  4317.2  722.04
  4647.3  725.77  4955.4  725.76  4977.8  720.67  4984.2  716.47  4985.3  708.74
  4988.7  706.74  5035.3  706.74  5038.8  708.74  5050.9  717.25  5078.8  725.41
  5123.7  729.79  5303.2  721.96  5451.4  725.92    5752  723.06  6226.8  725.67
  6922.4  735.25  6956.4  737.25  7037.4  763.54  7078.5  771.02  7282.8  775.66
#Mann= 5 ,-1 , 0
  3771.6     .05       0  4985.3    .035       0  5038.8     .05       0
  6922.4     .16       0  7078.5     .05       0
Bank Sta=4985.3,5038.8
XS Rating Curve= 0 ,0
Exp/Cntr=0.3,0.1

Type RM Length L Ch R = 1 ,329625  ,1563,1563,1563
BEGIN DESCRIPTION:
Denton Creek275
END DESCRIPTION:
XS GIS Cut Line= 2
      2303855.08      7137747.52      2301276.91      7135954.78
#Sta/Elev= 30
  3079.6  757.98  3476.8  753.29  3513.3  758.79  3556.4  746.72  3621.9  740.64
    3649  721.94  3671.6  715.44  3771.2  713.61  3800.9  723.09  3958.7  721.83
  3970.1  721.94  4662.4   723.5  4727.9  719.49    4914  725.65  4950.5  720.73
  4957.4  717.07  4960.3  707.98  4963.8  705.98  5013.8  707.98  5014.2  714.99
  5058.7  724.86  5153.4  719.93  5198.3  720.46  5568.5  726.29  5596.1  731.62
  5681.9  761.88  5740.8     763  5827.5  764.25  6042.5  788.28  6219.8     792
#Mann= 8 ,-1 , 0
  3079.6     .05       0  3958.7     .16       0  3970.1     .05       0
  4960.3    .035       0  5013.8     .05       0  5153.4     .07       0
  5198.3     .16       0  5740.8     .05       0
#XS Ineff= 2 , 0
       0  3815.4  757.85               0
Permanent Ineff=
       F       F
Bank Sta=4960.3,5013.8
XS Rating Curve= 0 ,0
Exp/Cntr=0.3,0.1

Type RM Length L Ch R = 1 ,328062  ,1510,1510,1510
BEGIN DESCRIPTION:
Denton Creek274
END DESCRIPTION:
XS GIS Cut Line= 2
        2304014.      7137164.86      2303325.21      7135196.71
#Sta/Elev= 30
  3639.1  752.39    3728  751.22  3919.7  748.13  4015.1  742.24  4195.2  724.57
  4311.7  720.67  4344.4  722.93  4393.6  719.12    4958  724.99  4972.5  720.94
  4976.7  707.04  4980.1  705.04  5026.9  705.04  5030.3  707.04  5042.7  714.99
  5060.3  721.44  5085.1  722.67  5122.3  729.17    5255  721.91  5365.3  725.17
  5396.3  732.45  5434.8  747.32  5466.5  751.42  5477.1  753.75  5484.1  758.16
  5489.4  755.89    5495  758.61  5508.9  763.88  5520.4  762.01  5724.3  768.28
#Mann= 7 ,-1 , 0
  3639.1     .05       0    3728     .16       0  4344.4     .05       0
  4976.7    .035       0  5030.3     .05       0    5255     .16       0
    5495     .05       0
Bank Sta=4976.7,5030.3
XS Rating Curve= 0 ,0
Exp/Cntr=0.3,0.1

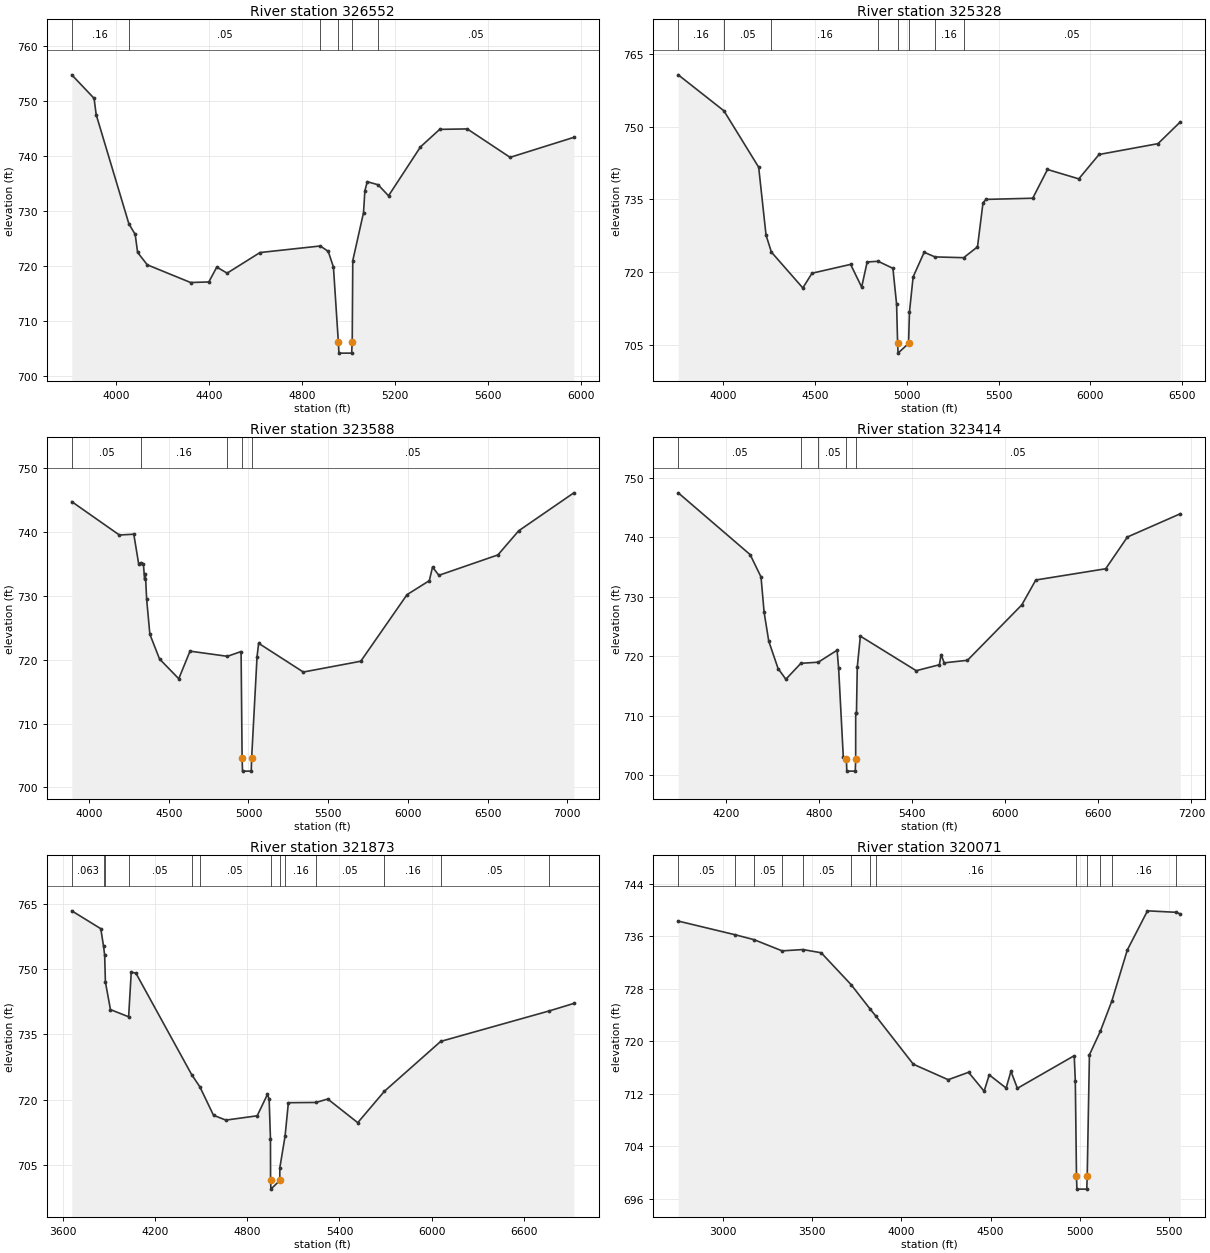
Type RM Length L Ch R = 1 ,326552  ,1224,1224,1224
BEGIN DESCRIPTION:
Denton Creek273
END DESCRIPTION:
XS GIS Cut Line= 3
      2304694.55      7136782.34       2305102.6      7135332.13
      2305684.02      7135039.57
#Sta/Elev= 30
  3811.1  754.68    3907  750.41    3916  747.45  4056.7  727.61  4083.6  725.72
    4094  722.44  4135.6  720.19  4321.7  716.98  4400.1  717.08  4434.2  719.78
  4478.6  718.68    4620  722.42    4879  723.61  4913.1  722.63  4935.5  719.78
  4956.6  706.16  4959.1  704.16  5013.7  704.16  5016.2  706.16  5018.6  720.96
  5064.8  729.67  5070.5  733.62  5080.9  735.28  5127.6  734.72  5172.2  732.72
  5309.5   741.6    5392  744.78  5510.5  744.86  5694.6   739.7  5968.5  743.33
#Mann= 6 ,-1 , 0
  3811.1     .16       0  4056.7     .05       0    4879     .16       0
  4956.6     .07       0  5016.2     .16       0  5127.6     .05       0
Bank Sta=4956.6,5016.2
XS Rating Curve= 0 ,0
Exp/Cntr=0.3,0.1

Type RM Length L Ch R = 1 ,325328  ,1740,1740,1740
BEGIN DESCRIPTION:
Denton Creek272
END DESCRIPTION:
XS GIS Cut Line= 3
      2306194.85      7137317.53      2306125.17      7135641.55
      2306048.93      7134588.83
#Sta/Elev= 30
  3756.1  760.68  4004.8  753.27    4194  741.64    4234  727.66  4263.3  724.16
  4434.2  716.78  4484.3  719.81  4694.4  721.63  4754.5  716.95  4784.5  722.13
  4844.3  722.27  4924.6  720.82  4944.7  713.41  4950.2  705.35  4952.7  703.35
  5009.8  705.35  5014.7  711.83  5034.7  719.06  5094.8  724.13  5153.6  723.17
  5309.7  723.01    5385  725.24  5415.1  734.34  5431.8  735.02  5685.7  735.26
  5765.9  741.18  5936.4  739.25  6046.7  744.27  6367.5   746.5    6489  750.98
#Mann= 8 ,-1 , 0
  3756.1     .16       0  4004.8     .05       0  4263.3     .16       0
  4844.3     .05       0  4950.2    .035       0  5009.8     .05       0
  5153.6     .16       0  5309.7     .05       0
Bank Sta=4950.2,5009.8
XS Rating Curve= 0 ,0
Exp/Cntr=0.3,0.1

Type RM Length L Ch R = 1 ,323588  ,174,174,174
BEGIN DESCRIPTION:
Denton Creek271
END DESCRIPTION:
XS GIS Cut Line= 4
      2307659.55       7137086.2      2307569.16      7136345.05
      2307612.87      7135306.59      2307583.64      7133943.83
#Sta/Elev= 30
  3891.7  744.73  4190.2  739.51  4280.8  739.63    4311  735.04  4327.2  735.19
  4341.2  734.93  4348.4  732.59  4353.5  733.43  4361.4  729.44  4381.5  723.98
    4442  720.11  4562.8  717.01  4633.3  721.33    4868  720.52  4953.7  721.27
  4960.1  704.55  4962.6  702.55  5017.3  702.55  5019.8  704.55  5053.8  720.47
  5063.8  722.56    5344  718.06  5704.3  719.75  5994.4  730.17  6134.4  732.36
  6154.4  734.49  6194.4   733.2  6564.5  736.39  6694.5  740.16  7040.8  746.11
#Mann= 5 ,-1 , 0
  3891.7     .05       0  4327.2     .16       0    4868     .05       0
  4960.1    .035       0  5019.8     .05       0
Bank Sta=4960.1,5019.8
XS Rating Curve= 0 ,0
Exp/Cntr=0.3,0.1

Type RM Length L Ch R = 1 ,323414  ,1541,1541,1541
BEGIN DESCRIPTION:
Denton Creek 101.0
END DESCRIPTION:
XS GIS Cut Line= 3
      2307757.48      7137113.25      2307756.99      7136126.26
      2307715.25      7133879.14
#Sta/Elev= 30
  3893.7  747.49    4357   737.1    4427  733.34    4447   727.4    4477  722.53
    4537  717.94    4587  716.14  4683.8  718.82  4796.1  719.01    4917  721.02
    4927  717.98    4957   703.1  4977.1  702.69  4979.6  700.69  5034.3  700.69
  5036.8  702.69  5036.9  710.48  5041.9  710.42    5047  718.15    5067  723.39
    5427  717.58  5576.1  718.58  5587.1  720.29  5607.1   718.9  5757.1  719.33
  6107.2  728.65  6197.2  732.83  6647.3  734.72  6787.3  740.06  7128.2  743.97
#Mann= 5 ,-1 , 0
  3893.7     .05       0  4683.8     .16       0  4796.1     .05       0
  4977.1    .035       0  5036.8     .05       0
Bank Sta=4977.1,5036.8
XS Rating Curve= 0 ,0
Exp/Cntr=0.3,0.1

Type RM Length L Ch R = 1 ,321873  ,1802,1802,1802
BEGIN DESCRIPTION:
Denton Creek 100.0
END DESCRIPTION:
XS GIS Cut Line= 3
      2309247.04      7136596.53        2308779.        7135310.
      2308112.22      7133533.85
#Sta/Elev= 30
  3658.4   763.4  3847.2  759.29  3865.3  755.22  3872.4  753.17  3877.2  747.03
  3910.1  740.69  4028.3  739.04  4045.3  749.32  4075.9  749.05  4438.2  725.75
  4491.9  722.92  4580.5  716.39    4661  715.28  4864.5  716.27  4931.6   721.2
  4942.3  720.13    4951     711  4951.6  701.41    4954  699.41  5011.5  701.41
  5012.1  704.35  5045.9  711.57  5067.5  719.28  5247.2  719.34  5323.7  720.13
  5518.8  714.69  5692.2  721.91  6058.6  733.38    6766   740.4  6924.6  742.11
#Mann= 13 ,-1 , 0
  3658.4    .063       0  3865.3     .05       0  3877.2    .063       0
  4028.3     .05       0  4438.2     .16       0  4491.9     .05       0
  4951.6    .035       0  5011.5     .05       0  5045.9     .16       0
  5247.2     .05       0  5692.2     .16       0  6058.6     .05       0
    6766     .16       0
Bank Sta=4951.6,5011.5
XS Rating Curve= 0 ,0
Exp/Cntr=0.3,0.1

Type RM Length L Ch R = 1 ,320071  ,1773,1773,1773
BEGIN DESCRIPTION:
Denton Creek 99.0
END DESCRIPTION:
XS GIS Cut Line= 4
       2311343.7      7135437.09      2310464.73      7135163.59
        2309729.        7134060.      2309328.98      7133659.98
#Sta/Elev= 30
  2749.7  738.31    3069  736.22    3174  735.48  3331.8  733.77    3448  733.97
  3550.6  733.48  3717.9  728.63  3825.3  724.89  3856.6  723.83  4066.7   716.5
    4262  714.14  4376.1  715.27  4463.3  712.39  4491.8  714.88  4586.5  712.87
  4613.5  715.42  4649.6  712.83    4968   717.8  4974.1  713.98  4980.7  699.47
  4983.1  697.47  5038.3  697.47  5040.8  699.47  5053.2  717.94  5114.1  721.51
  5178.9  726.14  5265.3   733.9  5378.4  739.87  5535.5  739.65  5562.3  739.41
#Mann= 13 ,-1 , 0
  2749.7     .05       0    3069     .05       0    3174     .05       0
  3331.8     .16       0    3448     .05       0  3717.9     .16       0
  3825.3     .05       0  3856.6     .16       0  4980.7     .07       0
  5040.8     .16       0  5114.1     .05       0  5178.9     .16       0
  5535.5     .05       0
Bank Sta=4980.7,5040.8
XS Rating Curve= 0 ,0
Exp/Cntr=0.3,0.1

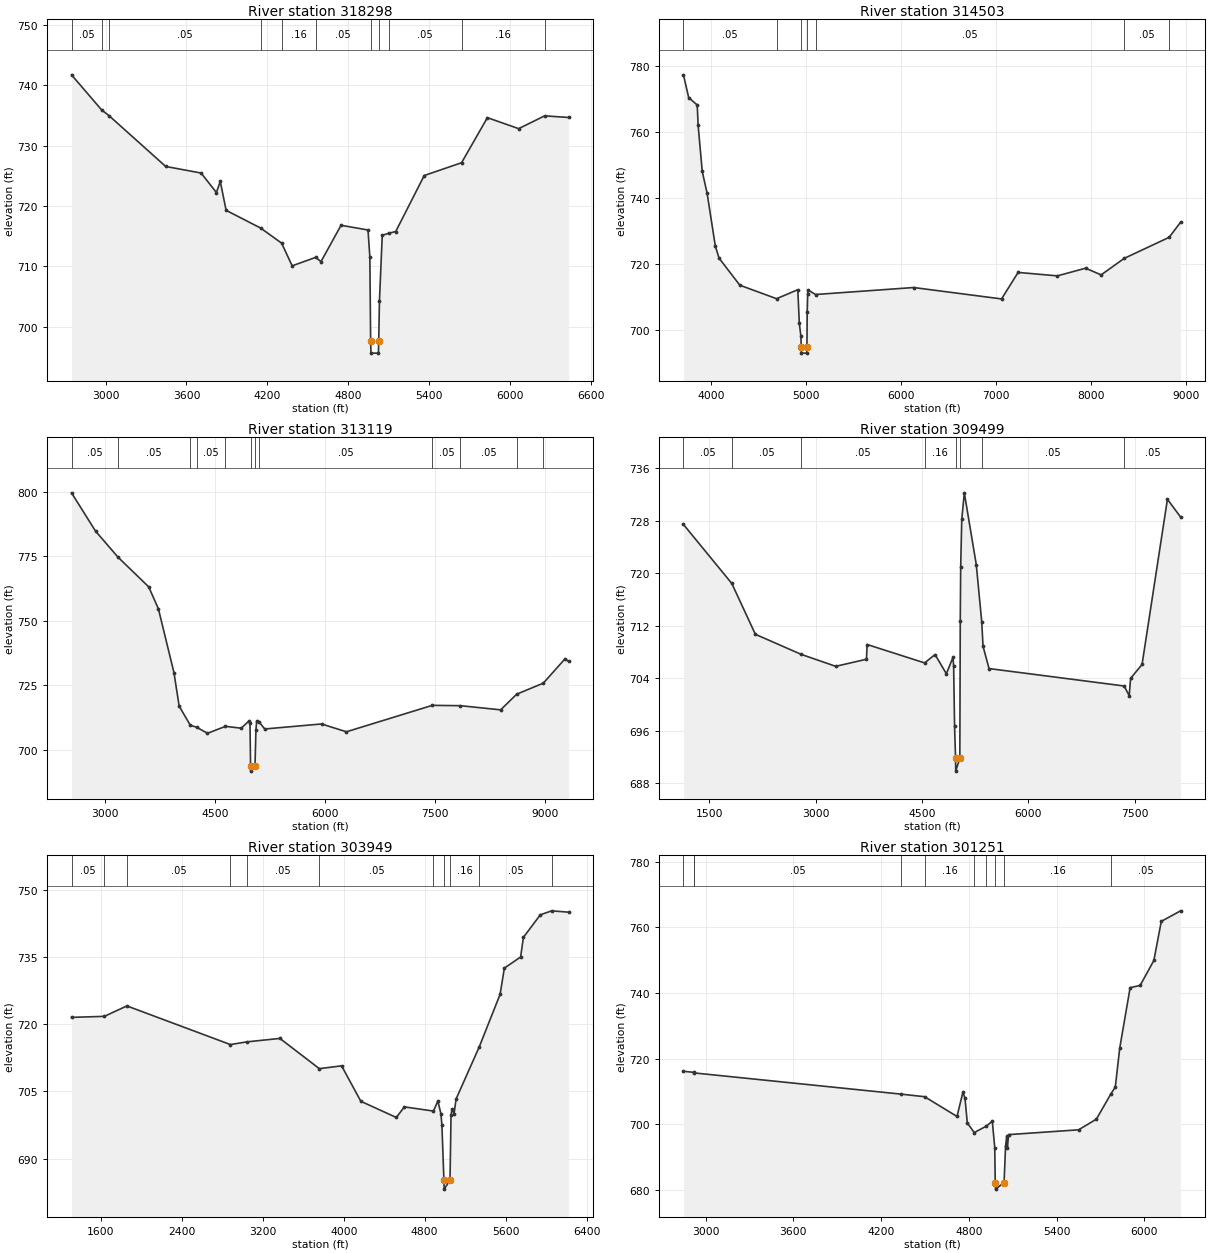
Type RM Length L Ch R = 1 ,318298  ,3795,3795,3795
BEGIN DESCRIPTION:
Denton Creek 98.0
END DESCRIPTION:
XS GIS Cut Line= 3
      2312593.38      7134918.02      2310956.36      7132874.64
      2309887.63      7132798.33
#Sta/Elev= 30
  2746.9  741.74    2970  735.93  3024.3  734.99  3446.2  726.55  3708.7  725.46
  3822.3  722.23  3851.1  724.07  3894.3  719.28  4150.7  716.34  4306.4  713.84
  4384.5  710.08    4559  711.48  4598.5  710.78  4747.4   716.8  4947.5  716.02
  4961.1  711.55    4967  697.61  4969.5  695.61  5024.7  695.61  5027.1  697.61
  5032.3  704.21  5053.1  715.13  5100.3  715.47  5153.3  715.77  5364.9  725.05
  5641.9  727.17  5833.7  734.64  6065.7  732.82  6258.6  734.94  6436.6  734.67
#Mann= 11 ,-1 , 0
  2746.9     .05       0    2970     .05       0  3024.3     .05       0
  4150.7     .05       0  4306.4     .16       0    4559     .05       0
    4967     .07       0  5027.1     .05       0  5100.3     .05       0
  5641.9     .16       0  6258.6     .05       0
Bank Sta=4967,5027.1
XS Rating Curve= 0 ,0
Exp/Cntr=0.3,0.1

Type RM Length L Ch R = 1 ,314503  ,1384,1384,1384
BEGIN DESCRIPTION:
Denton Creek270
END DESCRIPTION:
XS GIS Cut Line= 5
      2315488.09      7132650.57      2313780.06      7132138.67
      2312045.47      7132068.12       2311768.9       7132415.8
      2310553.68      7132792.35
#Sta/Elev= 30
  3711.7  777.24  3767.1  770.34  3856.9  768.11  3866.3  761.95  3909.8  747.99
  3961.3  741.36  4047.3  725.46  4086.6  721.78  4305.8  713.58  4692.5   709.5
    4916  712.22  4932.2     702    4949  698.07    4952  695.03  4954.4  693.03
  5009.8  693.03  5012.2  695.03  5015.2  705.35  5020.4  711.02  5026.1  712.08
  5103.7  710.77  6136.4  712.88  7061.9  709.43  7236.4  717.45  7649.7  716.41
  7947.5  718.73  8110.5   716.7  8353.7   721.7  8827.5  728.08  8947.3  732.63
#Mann= 7 ,-1 , 0
  3711.7     .05       0  4692.5     .16       0    4952     .07       0
  5012.2     .16       0  5103.7     .05       0  8353.7     .05       0
  8827.5     .16       0
Bank Sta=4952,5012.2
XS Rating Curve= 0 ,0
Exp/Cntr=0.3,0.1

Type RM Length L Ch R = 1 ,313119  ,3620,3620,3620
BEGIN DESCRIPTION:
Denton Creek269
END DESCRIPTION:
XS GIS Cut Line= 6
      2316640.82      7131013.75      2315269.87      7130805.54
      2313168.06      7131197.07      2312168.29      7131809.71
      2311747.35       7132389.6      2310433.74       7132778.1
#Sta/Elev= 30
  2543.9  799.62  2871.5  784.78  3177.4  774.69  3596.9  763.16  3729.2  754.65
  3941.6  729.91  4012.8  716.89  4165.6  709.44  4249.6  708.73  4399.4  706.36
    4645  709.05  4859.1  708.33  4969.6  711.25  4979.2  710.37  4987.2  693.68
  4989.6  691.68  5047.4  693.68  5060.6  707.74    5070  710.98  5099.4  710.89
  5180.5  708.03  5955.7  709.97  6295.2  706.94  7467.5  717.19  7851.4  717.06
  8399.5  715.45  8618.5  721.52  8982.2  725.81  9278.2  735.24  9327.5   734.2
#Mann= 12 ,-1 , 0
  2543.9     .05       0  3177.4     .05       0  4165.6     .05       0
  4249.6     .05       0    4645     .16       0  4987.2     .07       0
  5047.4     .16       0  5099.4     .05       0  7467.5     .05       0
  7851.4     .05       0  8618.5     .05       0  8982.2     .16       0
Bank Sta=4987.2,5047.4
XS Rating Curve= 0 ,0
Exp/Cntr=0.3,0.1

Type RM Length L Ch R = 1 ,309499  ,5550,5550,5550
BEGIN DESCRIPTION:
Denton Creek268
END DESCRIPTION:
XS GIS Cut Line= 3
      2315613.01      7128158.58       2312194.2      7130407.45
      2309433.86      7131351.95
#Sta/Elev= 30
  1135.6   727.4  1817.2  718.43    2150  710.69  2798.2  707.63  3282.9  705.82
  3716.4   706.9  3725.5  709.14  4536.5  706.34  4683.4  707.61  4843.1  704.69
  4936.4  707.19  4945.5  705.85  4958.7  696.67  4972.6  691.88    4975  689.88
  5032.8  691.88  5038.9  712.71  5044.9  720.91    5060  728.16  5096.1  732.21
    5265  721.27  5341.8  712.57  5360.1  708.87  5444.6  705.48  7349.5  702.83
  7421.1  701.36  7440.6  703.99  7602.3   706.1  7960.1  731.23  8145.2  728.53
#Mann= 8 ,-1 , 0
  1135.6     .05       0  1817.2     .05       0  2798.2     .05       0
  4536.5     .16       0  4972.6     .07       0  5032.8     .16       0
  5341.8     .05       0  7349.5     .05       0
#XS Ineff= 2 , 0
       0                  5122.3       0  727.18
Permanent Ineff=
       F       F
Bank Sta=4972.6,5032.8
XS Rating Curve= 0 ,0
Exp/Cntr=0.3,0.1

Type RM Length L Ch R = 1 ,303949  ,2698,2698,2698
BEGIN DESCRIPTION:
Denton Creek 96.0
END DESCRIPTION:
XS GIS Cut Line= 4
      2313220.87      7127288.75      2311407.34      7128585.93
      2309636.68      7128678.96      2308867.49      7129164.27
#Sta/Elev= 30
  1310.4   721.5  1634.5  721.72  1857.5  724.05  2880.5  715.43    3043  716.03
  3369.4   716.8  3759.4  710.05  3979.1  710.68  4169.3  702.77  4519.8  699.16
  4599.9  701.52  4886.6  700.59  4930.4  702.83  4960.4  700.03  4970.4  697.46
  4990.3  685.17  4992.7  683.17  5050.6  685.17  5060.5  699.67  5070.6  701.08
  5090.6  700.01  5110.6  703.28  5339.5  714.92  5545.2  726.62  5587.6  732.48
    5748  734.97  5775.9  739.36    5943  744.38  6054.6  745.27  6222.7  744.97
#Mann= 11 ,-1 , 0
  1310.4     .05       0  1634.5     .05       0  1857.5     .05       0
  2880.5     .05       0    3043     .05       0  3759.4     .05       0
  4886.6     .16       0  4990.3     .07       0  5050.6     .16       0
  5339.5     .05       0  6054.6     .05       0
Bank Sta=4990.3,5050.6
XS Rating Curve= 0 ,0
Exp/Cntr=0.3,0.1

Type RM Length L Ch R = 1 ,301251  ,1864,1864,1864
BEGIN DESCRIPTION:
Denton Creek 95.0
END DESCRIPTION:
XS GIS Cut Line= 3
      2312700.33      7126971.46        2310529.        7126760.
      2309328.96      7126559.99
#Sta/Elev= 30
  2849.2  716.12    2918   715.8  2924.5  715.61    4335  709.16  4497.9  708.36
  4719.3  702.34  4759.5  709.72  4773.7  707.92  4789.7  700.37  4837.1  697.42
  4920.2  699.41  4960.5  700.88  4977.4  692.83  4980.5  682.18  4982.9  680.18
  5040.9  682.18  5051.1   693.2  5058.7  696.23  5063.8  692.75  5071.4   696.8
  5550.4  698.27    5672  701.52  5769.9  709.13  5801.3  711.31  5831.7  723.23
  5902.7  741.62  5971.1  742.29  6064.9  749.91  6115.6  761.83  6247.4  765.05
#Mann= 10 ,-1 , 0
  2849.2     .05       0    2918     .05       0  2924.5     .05       0
    4335     .05       0  4497.9     .16       0  4837.1     .05       0
  4920.2     .16       0  4980.5     .07       0  5040.9     .16       0
  5769.9     .05       0
Bank Sta=4980.5,5040.9
XS Rating Curve= 0 ,0
Exp/Cntr=0.3,0.1