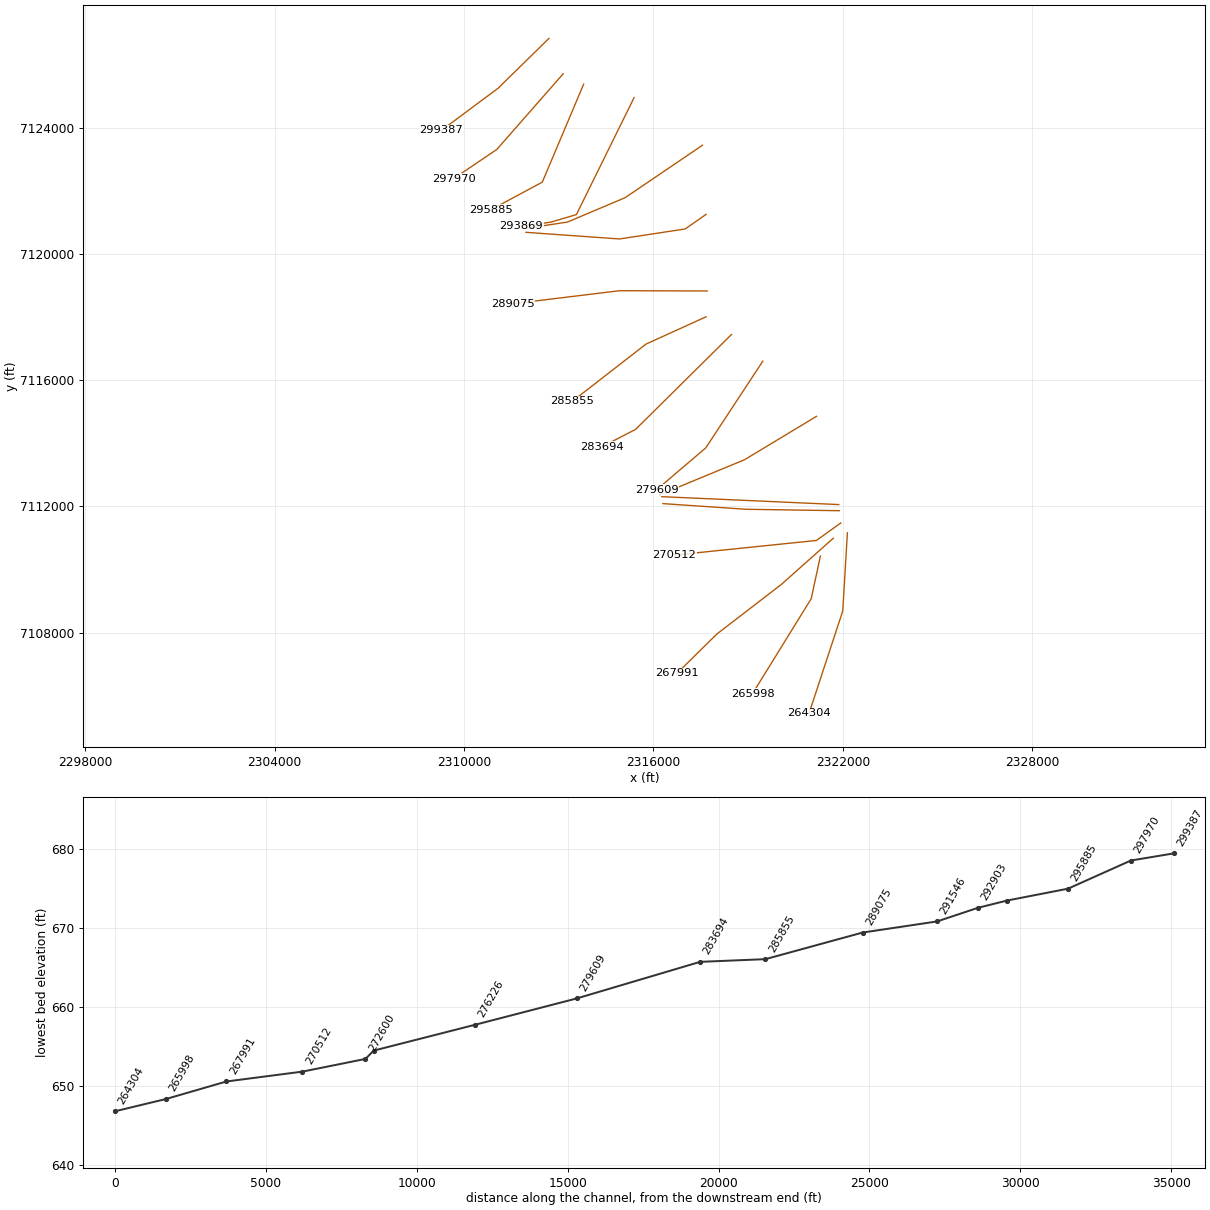
HEC-RAS study Denton Creek.prj: Denton Creek Base Level Engineering

--- Denton Creek.g01 (geometry) --- (continued)

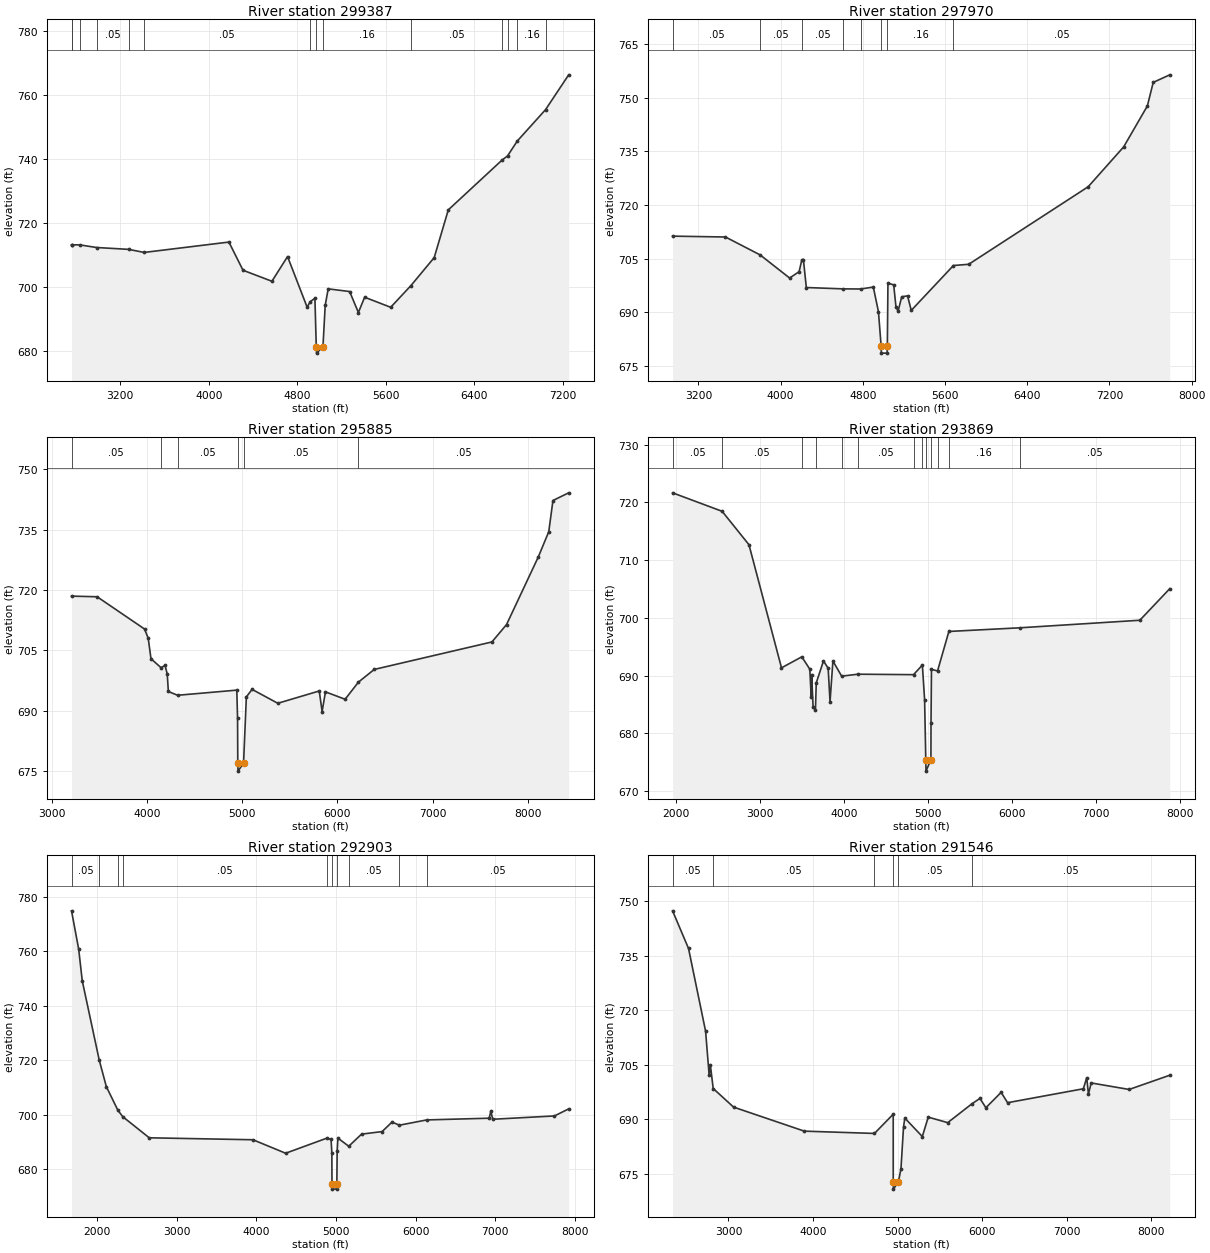
Type RM Length L Ch R = 1 ,299387  ,1417,1417,1417
BEGIN DESCRIPTION:
Denton Creek 94.0
END DESCRIPTION:
XS GIS Cut Line= 3
      2312690.82      7126841.48        2311079.        7125260.
      2309283.66      7123922.48
#Sta/Elev= 30
  2758.3  713.29  2759.5  713.29  2832.8  713.27  2984.8  712.45  3274.7  711.87
  3415.4  710.91    4182  714.15  4309.3  705.35  4570.9   701.9  4712.3  709.62
  4889.2  693.83  4918.6  695.57  4959.9  696.57  4972.1  681.45  4974.5  679.45
  5032.6  681.45  5052.9  694.39    5080  699.53  5273.9  698.69  5353.1  692.13
  5409.5  696.92  5645.1  693.77    5827   700.5  6038.9   709.3  6166.4  724.21
  6651.7  739.74  6701.9  741.05  6790.3  745.72  7045.7  755.51  7255.2   766.4
#Mann= 14 ,-1 , 0
  2758.3     .05       0  2759.5     .05       0  2832.8     .05       0
  2984.8     .05       0  3274.7     .05       0  3415.4     .05       0
  4918.6     .16       0  4972.1     .07       0  5032.6     .16       0
    5827     .05       0  6651.7     .16       0  6701.9     .05       0
  6790.3     .16       0  7045.7     .05       0
Bank Sta=4972.1,5032.6
XS Rating Curve= 0 ,0
Exp/Cntr=0.3,0.1

Type RM Length L Ch R = 1 ,297970  ,2085,2085,2085
BEGIN DESCRIPTION:
Denton Creek267
END DESCRIPTION:
XS GIS Cut Line= 3
      2313139.54      7125716.49      2311036.43      7123317.49
      2309671.47      7122394.45
#Sta/Elev= 30
  2948.5  711.25  3463.3  711.01  3800.8     706  4087.5  699.54  4179.8  701.32
  4206.2  704.58  4221.6  704.72    4250  696.89  4609.6  696.51  4777.4  696.48
    4902  697.01  4951.9  690.14    4978  680.55  4980.4  678.55  5036.1  678.55
  5038.5  680.55  5044.3  698.12  5100.3  697.63  5122.2  691.56    5143  690.26
  5178.2  694.29  5235.1  694.56  5271.1  690.49  5681.6  703.04  5830.1  703.38
  6992.8  725.05  7338.1  736.19  7568.8  747.63  7625.8  754.22  7786.6  756.34
#Mann= 8 ,-1 , 0
  2948.5     .05       0  3800.8     .05       0  4206.2     .05       0
  4609.6     .05       0  4777.4     .16       0    4978     .07       0
  5038.5     .16       0  5681.6     .05       0
Bank Sta=4978,5038.5
XS Rating Curve= 0 ,0
Exp/Cntr=0.3,0.1

Type RM Length L Ch R = 1 ,295885  ,2016,2016,2016
BEGIN DESCRIPTION:
Denton Creek266
END DESCRIPTION:
XS GIS Cut Line= 3
      2313787.14      7125385.77      2312477.67      7122280.99
      2310849.36      7121406.49
#Sta/Elev= 30
  3209.9  718.47  3478.7  718.31  3975.9   710.3  4014.8  708.01  4043.9  702.91
  4149.2  700.69  4191.7  701.24  4214.6  699.08  4226.2  694.77  4323.2  693.83
  4944.6  695.11  4952.6  688.09  4954.9  676.98  4957.3  674.98  5015.5  676.98
  5044.9  693.42  5104.6   695.3    5375  691.84    5810   694.9  5839.9  689.78
  5875.1  694.68  6081.4  692.84  6221.2   697.1  6386.9  700.25  7622.2  707.08
  7775.6   711.4  8109.3  728.22  8218.9  734.49  8262.7  742.23  8427.8  744.14
#Mann= 6 ,-1 , 0
  3209.9     .05       0  4149.2     .16       0  4323.2     .05       0
  4954.9     .05       0  5015.5     .05       0  6221.2     .05       0
Bank Sta=4954.9,5015.5
XS Rating Curve= 0 ,0
Exp/Cntr=0.3,0.1

Type RM Length L Ch R = 1 ,293869  ,966,966,966
BEGIN DESCRIPTION:
Denton Creek265
END DESCRIPTION:
XS GIS Cut Line= 4
      2315385.52      7124961.45      2313558.62      7121253.67
      2312742.38      7121011.16      2311815.57      7120897.35
#Sta/Elev= 30
  1959.2  721.66  2549.2  718.46  2868.5  712.68  3255.9  691.36  3497.7  693.27
  3592.8  691.13  3609.7  686.29  3615.3  690.19  3632.2   684.5  3660.2   684.1
  3669.6  688.75  3755.6  692.55  3811.4  691.29  3833.7  685.49  3867.9  692.54
  3972.2  689.92  4165.2  690.26  4827.5  690.18    4933  691.84  4959.6  685.84
  4973.7  675.48    4976  673.48  5034.8  675.48  5035.9  681.82  5041.5   691.1
  5113.6  690.82  5248.6  697.66  6090.7  698.29  7521.8   699.6  7877.9  705.06
#Mann= 13 ,-1 , 0
  1959.2     .05       0  2549.2     .05       0  3497.7     .05       0
  3669.6     .16       0  3972.2     .05       0  4165.2     .05       0
  4827.5     .05       0    4933     .16       0  4973.7     .07       0
  5034.8     .16       0  5113.6     .05       0  5248.6     .16       0
  6090.7     .05       0
Bank Sta=4973.7,5034.8
XS Rating Curve= 0 ,0
Exp/Cntr=0.3,0.1

Type RM Length L Ch R = 1 ,292903  ,1357,1357,1357
BEGIN DESCRIPTION:
Denton Creek263
END DESCRIPTION:
XS GIS Cut Line= 4
      2317552.53      7123452.57      2315103.17      7121789.75
      2313277.29      7121016.89      2311992.53      7120821.53
#Sta/Elev= 30
  1678.1  774.93  1767.9  760.84  1812.7  749.22  2025.5  720.09  2115.2  710.27
  2259.2  701.63  2320.1  699.24  2654.2  691.44  3956.7  690.72  4366.9  685.76
  4881.9  691.29  4937.3  690.87  4947.1  685.77  4948.7  674.56    4951  672.56
  5007.5  672.56  5009.8  674.56  5013.8  686.66  5023.2  691.32  5159.2  688.33
  5319.8  692.79  5578.3  693.73  5702.2  697.22    5796  696.08  6138.8  698.02
    6923  698.65  6943.2  701.19  6967.5  698.26  7742.3  699.48  7920.8  702.08
#Mann= 10 ,-1 , 0
  1678.1     .05       0  2025.5     .07       0  2259.2     .05       0
  2320.1     .05       0  4881.9     .05       0  4948.7     .07       0
  5009.8     .05       0  5159.2     .05       0    5796     .16       0
  6138.8     .05       0
Bank Sta=4948.7,5009.8
XS Rating Curve= 0 ,0
Exp/Cntr=0.3,0.1

Type RM Length L Ch R = 1 ,291546  ,2471,2471,2471
BEGIN DESCRIPTION:
Denton Creek262
END DESCRIPTION:
XS GIS Cut Line= 4
      2317663.65      7121259.03      2317002.69      7120797.35
      2314921.66      7120480.28      2311959.74      7120691.11
#Sta/Elev= 30
  2338.6  747.34  2527.2  736.99  2729.2  714.24  2771.2  702.17  2785.9  704.84
  2819.2  698.49  3059.7  693.38  3897.1  686.77  4726.8  686.14  4948.5  691.43
  4948.9  672.83  4951.2  670.83    5010  672.83  5040.1  676.44  5070.5  687.95
  5085.7  690.37  5292.6  685.29  5362.8  690.62  5593.3  689.11  5881.2  694.32
  5974.4  695.77  6044.5  693.21    6225  697.43  6301.3  694.59  7197.5  698.42
  7237.6  701.46  7257.6  696.96  7290.5  700.02  7738.8  698.23  8219.3  702.14
#Mann= 6 ,-1 , 0
  2338.6     .05       0  2819.2     .05       0  4726.8     .05       0
  4948.9     .07       0    5010     .05       0  5881.2     .05       0
Bank Sta=4948.9,5010
XS Rating Curve= 0 ,0
Exp/Cntr=0.3,0.1

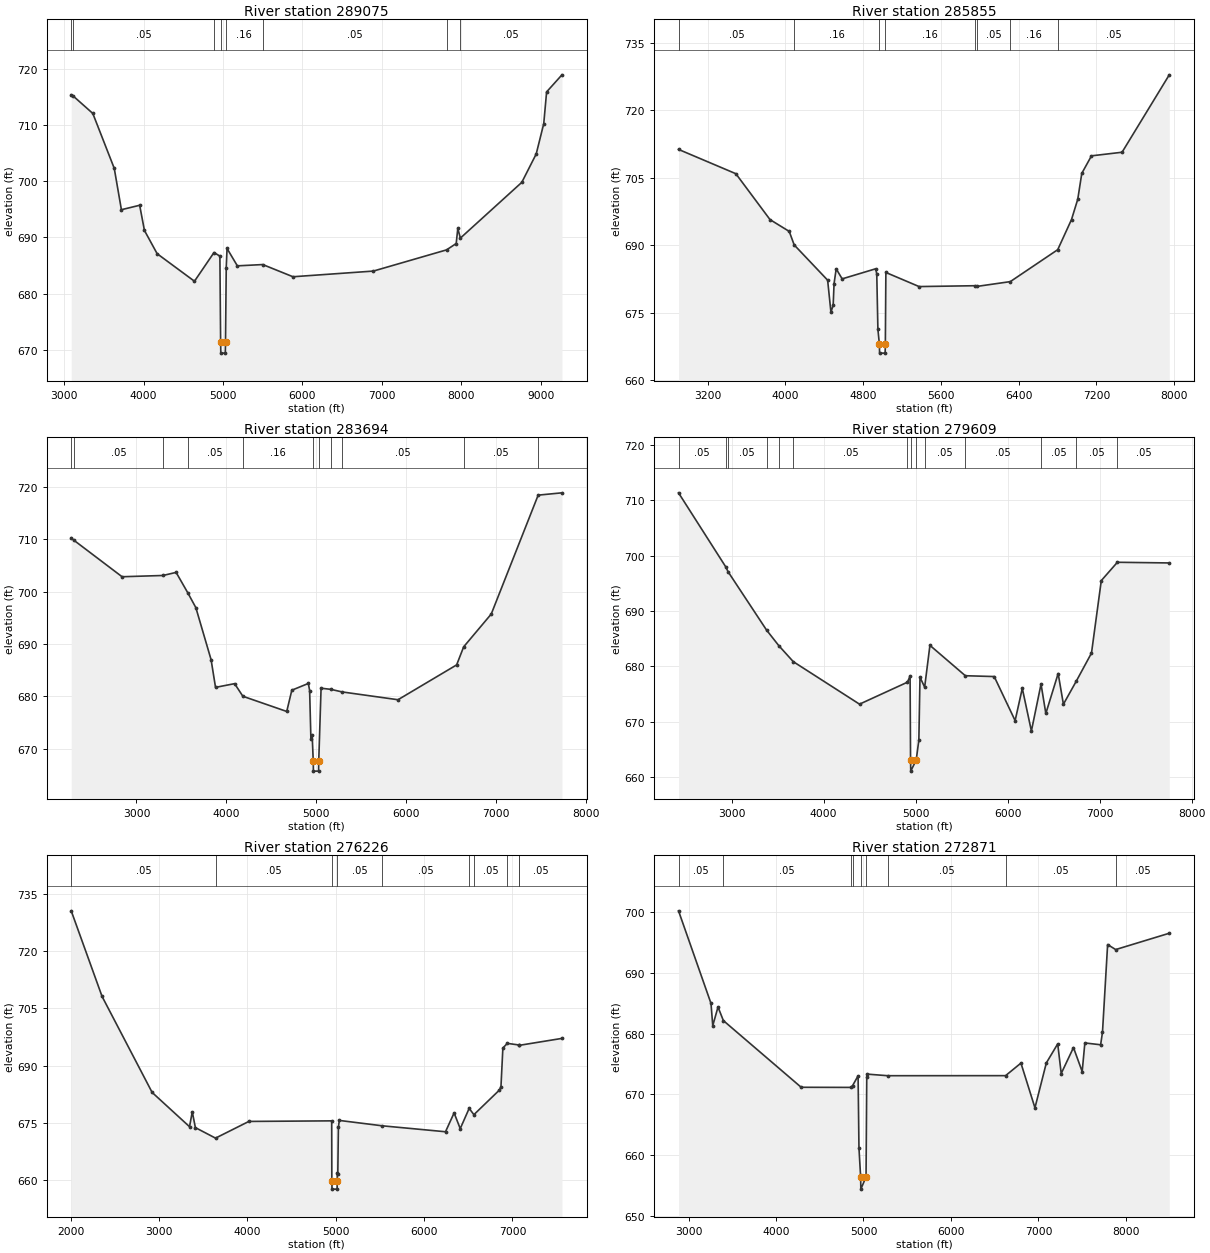
Type RM Length L Ch R = 1 ,289075  ,3220,3220,3220
BEGIN DESCRIPTION:
Denton Creek260
END DESCRIPTION:
XS GIS Cut Line= 3
      2317701.03        7118831.      2314927.53      7118839.94
      2311547.16      7118427.08
#Sta/Elev= 30
  3089.3  715.38  3112.5  715.19  3361.3  712.07  3631.3   702.3  3721.3  694.94
  3951.3  695.73  4011.3  691.25  4171.3  687.11  4641.3  682.21  4887.1  687.32
  4961.3  686.68  4970.7  671.42  4972.9  669.42  5029.7  669.42    5032  671.42
  5041.3  684.62  5051.3  688.04  5181.3  684.95    5501  685.18  5881.5  683.01
  6893.7  684.02  7814.8  687.79  7936.6  688.92  7956.8   691.6  7989.5  689.89
  8762.7  699.81  8944.1  704.86  9038.9  710.25    9075   715.9  9268.3  718.94
#Mann= 8 ,-1 , 0
  3089.3     .05       0  3112.5     .05       0  4887.1     .16       0
  4970.7     .07       0    5032     .16       0    5501     .05       0
  7814.8     .16       0  7989.5     .05       0
Bank Sta=4970.7,5032
XS Rating Curve= 0 ,0
Exp/Cntr=0.3,0.1

Type RM Length L Ch R = 1 ,285855  ,2161,2161,2161
BEGIN DESCRIPTION:
Denton Creek 88.0
END DESCRIPTION:
XS GIS Cut Line= 3
      2317666.23       7118012.5      2315764.72      7117147.77
      2313425.71      7115330.49
#Sta/Elev= 30
  2899.7  711.29  3489.9  705.89  3841.4   695.7  4039.1  693.08  4090.1  690.08
  4434.4  682.25  4468.5  675.11  4491.5  676.75  4500.5  681.49  4522.5  684.77
  4583.8  682.54    4929  684.78    4940  683.63  4951.7  671.36  4966.9  668.05
  4969.1  666.05  5026.2  666.05  5028.4  668.05  5033.8  683.96  5375.7  680.83
  5953.5  681.02    5976  680.88  6314.4  681.93  6802.4  689.02  6944.3  695.71
  7008.6  700.22  7050.2  705.97  7149.8  709.86  7464.7  710.66  7950.6  727.85
#Mann= 8 ,-1 , 0
  2899.7     .05       0  4090.1     .16       0  4966.9     .07       0
  5028.4     .16       0  5953.5     .05       0    5976     .05       0
  6314.4     .16       0  6802.4     .05       0
Bank Sta=4966.9,5028.4
XS Rating Curve= 0 ,0
Exp/Cntr=0.3,0.1

Type RM Length L Ch R = 1 ,283694  ,4085,4085,4085
BEGIN DESCRIPTION:
Denton Creek 87.0
END DESCRIPTION:
XS GIS Cut Line= 3
      2318469.38      7117449.79      2315433.58      7114443.03
      2314380.15      7113899.22
#Sta/Elev= 30
  2273.8  710.25  2301.1  709.82  2839.6  702.82  3294.7  703.06  3440.7  703.65
  3568.9   699.8  3659.9  696.93  3829.6  686.99    3879   681.7  4091.2  682.41
  4183.2     680    4671   677.1  4727.6  681.16  4911.5  682.45  4925.6   681.1
  4939.7  671.91  4953.9  672.57  4965.6  667.71  4967.8  665.71  5024.9  665.71
  5027.1  667.71  5052.9  681.54  5162.9  681.32  5286.8  680.83  5908.5  679.34
  6560.7  685.99  6638.9  689.44  6945.6   695.7  7467.5   718.4  7732.1  718.84
#Mann= 11 ,-1 , 0
  2273.8     .05       0  2301.1     .05       0  3294.7     .16       0
  3568.9     .05       0  4183.2     .16       0  4965.6     .07       0
  5027.1     .16       0  5162.9     .05       0  5286.8     .05       0
  6638.9     .05       0  7467.5     .05       0
Bank Sta=4965.6,5027.1
XS Rating Curve= 0 ,0
Exp/Cntr=0.3,0.1

Type RM Length L Ch R = 1 ,279609  ,3383,3383,3383
BEGIN DESCRIPTION:
Denton Creek 86.0
END DESCRIPTION:
XS GIS Cut Line= 3
      2319461.36      7116603.51      2317656.75      7113856.75
      2316098.56      7112528.22
#Sta/Elev= 30
  2422.5  711.37    2937  697.96  2960.8  697.12    3379  686.58  3512.1  683.76
    3670  680.86  4389.8  673.18  4910.8  677.15  4939.4  678.27  4944.5  663.08
  4946.7  661.08  5006.1  663.08  5034.7   666.7  5047.1  678.04  5097.8  676.26
  5155.1  683.81  5539.8  678.32  5853.8  678.17  6081.1  670.21  6159.1  676.04
    6258  668.33  6362.8   676.8  6414.9   671.5  6548.9  678.72    6606  673.17
  6745.3  677.32  6911.2  682.41  7017.7  695.51  7192.5  698.82  7756.7   698.7
#Mann= 14 ,-1 , 0
  2422.5     .05       0    2937     .05       0  2960.8     .05       0
    3379     .16       0  3512.1     .05       0    3670     .05       0
  4910.8     .05       0  4944.5    .035       0  5006.1     .05       0
  5097.8     .05       0  5539.8     .05       0  6362.8     .05       0
  6745.3     .05       0  7192.5     .05       0
Bank Sta=4944.5,5006.1
XS Rating Curve= 0 ,0
Exp/Cntr=0.3,0.1

Type RM Length L Ch R = 1 ,276226  ,3355,3355,3355
BEGIN DESCRIPTION:
Denton Creek 85.0
END DESCRIPTION:
XS GIS Cut Line= 3
      2321162.16      7114856.01      2318883.94      7113480.51
      2316211.17      7112374.31
#Sta/Elev= 30
  2006.3  730.53  2355.6  708.13  2922.3  683.02  3345.4  674.06  3376.4  677.96
  3411.7  673.82  3639.6  671.07  4016.9  675.44  4954.3  675.59  4955.9  659.73
  4958.1  657.73  5015.5  657.73  5017.6  659.73  5017.9  662.04  5023.3  661.64
    5030  673.98  5040.9   675.7  5528.5  674.29  6242.2  672.74  6339.6  677.67
  6408.9  673.55  6509.9  678.85  6563.7  677.21    6853  683.66  6869.9  684.55
  6891.5  694.64  6941.8  695.86  7069.1  695.45  7078.7  695.35  7560.2  697.16
#Mann= 10 ,-1 , 0
  2006.3     .05       0  3639.6     .05       0  4955.9    .045       0
  5017.6     .05       0  5528.5     .05       0  6509.9     .05       0
  6563.7     .05       0  6941.8     .05       0  7069.1     .05       0
  7078.7     .05       0
Bank Sta=4955.9,5017.6
XS Rating Curve= 0 ,0
Exp/Cntr=0.3,0.1

Type RM Length L Ch R = 1 ,272871  ,271,271,271
BEGIN DESCRIPTION:
Denton Creek259
END DESCRIPTION:
XS GIS Cut Line= 2
      2321869.96      7112058.73      2316264.76      7112309.27
#Sta/Elev= 30
  2885.4  700.15  3256.7  684.95  3276.8  681.29  3336.8  684.36  3398.1  682.13
  4287.8  671.18  4857.6  671.16  4875.2  671.45  4938.4  673.06  4948.4   661.2
  4967.6  656.46  4969.8  654.46  5029.3  656.46  5037.4  672.82  5042.4  673.34
  5277.2  673.08  6624.6  673.09  6800.3  675.15  6960.4  667.81  7090.6  675.18
  7220.7  678.31  7260.7  673.44  7400.9   677.7  7500.4  673.76    7531  678.46
  7711.2  678.16  7732.5   680.2  7791.3  694.61  7883.4  693.79  8496.2  696.47
#Mann= 9 ,-1 , 0
  2885.4     .05       0  3398.1     .05       0  4857.6     .05       0
  4875.2     .16       0  4967.6     .07       0  5029.3     .16       0
  5277.2     .05       0  6624.6     .05       0  7883.4     .05       0
Bank Sta=4967.6,5029.3
XS Rating Curve= 0 ,0
Exp/Cntr=0.3,0.1

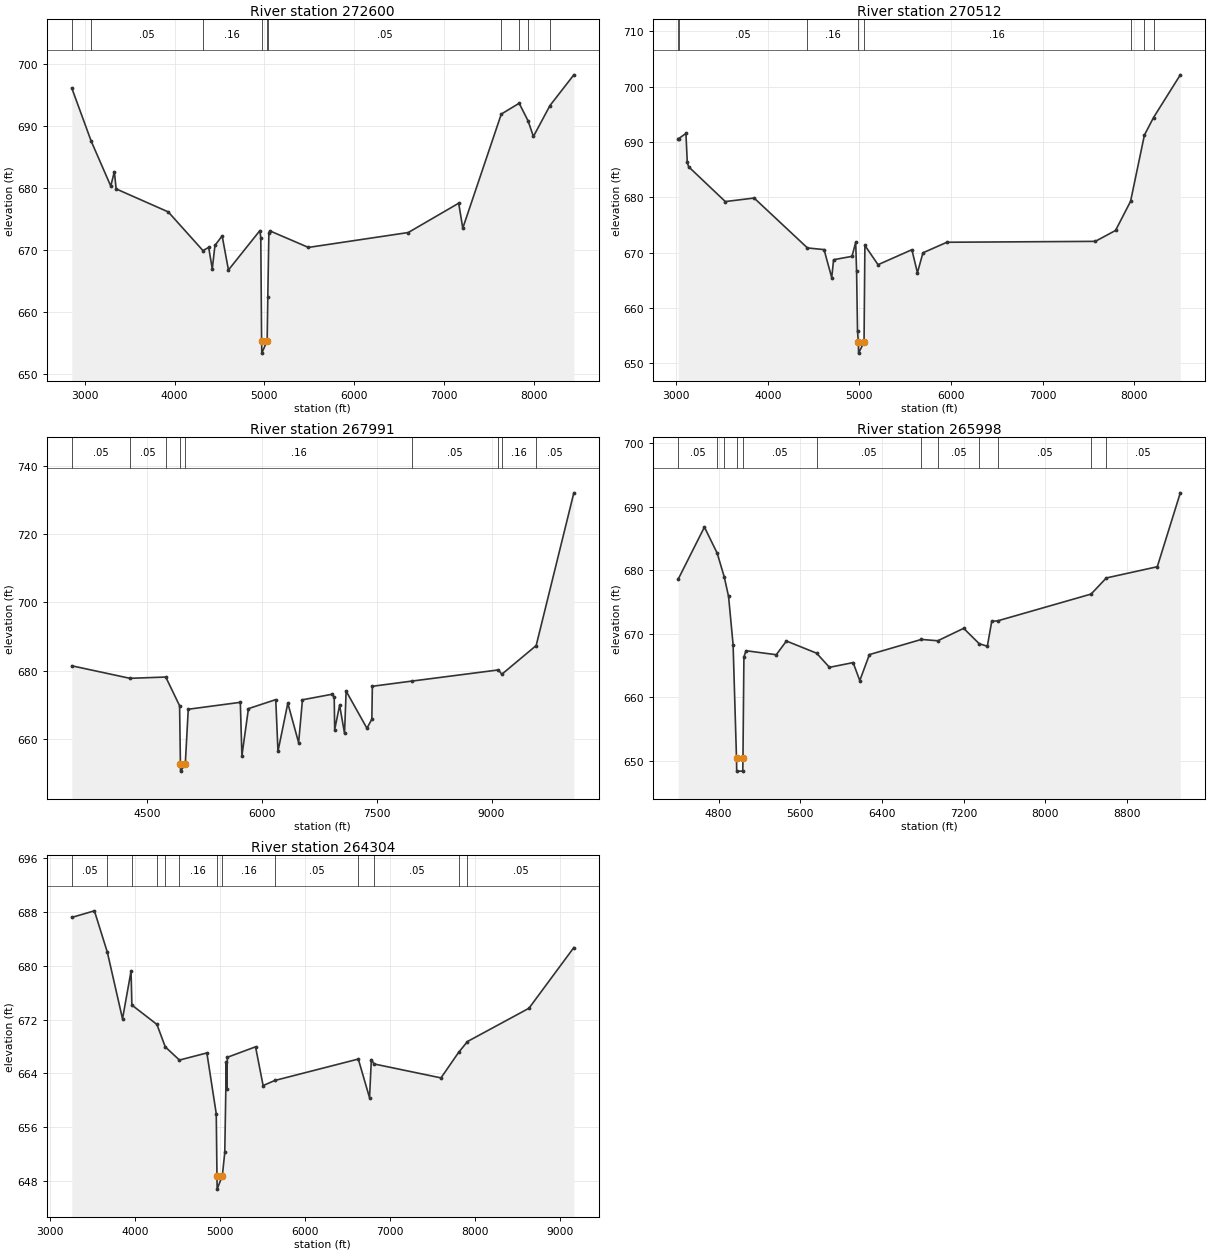
Type RM Length L Ch R = 1 ,272600  ,2088,2088,2088
BEGIN DESCRIPTION:
Denton Creek258
END DESCRIPTION:
XS GIS Cut Line= 3
      2321883.01      7111864.08      2318933.83      7111909.71
      2316299.95      7112088.88
#Sta/Elev= 30
  2855.3   696.1    3071  687.56  3289.4  680.31  3329.4  682.62  3349.4  679.85
  3929.4  676.15    4316  669.92  4379.5  670.43  4419.5  666.98  4449.5  670.76
  4529.5  672.29  4599.5   666.8  4949.6  673.14  4959.6  672.01  4968.7  655.41
  4970.9  653.41  5030.5  655.41  5037.7  662.44  5049.6  672.71  5059.6   673.1
  5489.6  670.43  6601.5  672.83  7162.8  677.55  7208.4  673.53    7637   691.9
    7836  693.64  7935.5   690.8  7994.7  688.29  8178.8  693.27  8444.8  698.22
#Mann= 10 ,-1 , 0
  2855.3     .05       0    3071     .05       0    4316     .16       0
  4968.7     .07       0  5030.5     .16       0  5037.7     .05       0
    7637    .063       0    7836     .05       0  7935.5     .05       0
  8178.8     .05       0
Bank Sta=4968.7,5030.5
XS Rating Curve= 0 ,0
Exp/Cntr=0.3,0.1

Type RM Length L Ch R = 1 ,270512  ,2521,2521,2521
BEGIN DESCRIPTION:
Denton Creek257
END DESCRIPTION:
XS GIS Cut Line= 3
      2321930.94      7111474.99      2321161.65      7110921.14
      2316656.18      7110456.46
#Sta/Elev= 30
  3023.9  690.61  3029.2  690.62  3107.9  691.54  3122.6  686.32  3137.2  685.52
  3537.5  679.22  3851.9  679.86  4433.6  670.83  4614.7  670.53  4698.3  665.46
  4718.7   668.7  4919.5  669.31  4959.7  671.83  4969.7  666.61  4979.8  655.72
  4989.1   653.8  4991.3   651.8  5050.9   653.8  5060.2  671.28  5203.7   667.8
  5572.9  670.51  5633.2  666.34  5693.7  669.95  5954.9  671.86  7573.5  672.02
  7794.6  673.99  7958.4  679.26  8109.6  691.25  8208.9  694.42  8501.2  702.15
#Mann= 8 ,-1 , 0
  3023.9     .05       0  3029.2     .05       0  4433.6     .16       0
  4989.1     .07       0  5050.9     .16       0  7958.4     .05       0
  8109.6    .063       0  8208.9     .05       0
Bank Sta=4989.1,5050.9
XS Rating Curve= 0 ,0
Exp/Cntr=0.3,0.1

Type RM Length L Ch R = 1 ,267991  ,1993,1993,1993
BEGIN DESCRIPTION:
Denton Creek256
END DESCRIPTION:
XS GIS Cut Line= 4
      2321696.05      7110991.96      2320041.16      7109519.33
      2318004.89      7107951.75      2316740.82      7106704.67
#Sta/Elev= 30
  3515.1  681.41  4275.7  677.74  4743.3  678.12    4924  669.71    4935  652.55
    4937  650.55  4998.2  652.55  5037.2  668.68  5717.5  670.71  5738.4  655.05
  5823.6  668.86  6180.6   671.5  6209.6  656.34  6338.3  670.46  6479.5  658.88
  6529.4  671.45  6915.4  673.07  6944.4  672.24  6950.7  662.72  7015.1  669.87
  7079.4  661.62  7100.2     674  7372.1  663.11  7436.4  665.78  7442.7  675.41
    7962  676.94  9090.1   680.2  9134.6  678.93  9583.5  687.34 10075.8  732.09
#Mann= 9 ,-1 , 0
  3515.1     .05       0  4275.7     .05       0  4743.3     .16       0
    4935     .07       0  4998.2     .16       0    7962     .05       0
  9090.1     .05       0  9134.6     .16       0  9583.5     .05       0
Bank Sta=4935,4998.2
XS Rating Curve= 0 ,0
Exp/Cntr=0.3,0.1

Type RM Length L Ch R = 1 ,265998  ,1694,1694,1694
BEGIN DESCRIPTION:
Denton Creek255
END DESCRIPTION:
XS GIS Cut Line= 3
       2321287.2      7110429.07      2320996.23      7109075.27
      2319139.51       7106068.1
#Sta/Elev= 30
  4404.1  678.61  4660.6  686.81  4785.4  682.71  4854.6  678.97  4897.2  675.87
  4941.5   668.3    4975  650.34    4977  648.34  5036.3  648.34  5038.2  650.34
  5047.5  666.34    5068  667.32  5364.6  666.69    5464  668.85  5760.1  666.93
  5885.7   664.7  6117.4  665.45  6182.8  662.61  6276.9  666.71  6786.3   669.1
  6946.6  668.89  7200.5  670.85  7353.1  668.42  7432.3  668.03  7475.6  671.96
  7533.6  672.03  8448.7  676.25    8598  678.79  9097.5  680.56    9323  692.21
#Mann= 12 ,-1 , 0
  4404.1     .05       0  4785.4     .16       0  4854.6     .05       0
    4975    .035       0  5038.2     .05       0  5760.1     .05       0
  6786.3     .05       0  6946.6     .05       0  7353.1     .16       0
  7533.6     .05       0  8448.7     .05       0    8598     .05       0
Bank Sta=4975,5038.2
XS Rating Curve= 0 ,0
Exp/Cntr=0.3,0.1

Type RM Length L Ch R = 1 ,264304  ,1900,1900,1900
BEGIN DESCRIPTION:
Denton Creek254
END DESCRIPTION:
XS GIS Cut Line= 3
      2322141.89      7111165.67      2321994.44      7108683.65
      2320926.88      7105438.33
#Sta/Elev= 30
  3256.6  687.18  3522.7  688.16  3674.9     682  3853.3   672.1  3953.5  679.19
  3963.3  674.15  4257.7  671.27  4355.8  667.93  4522.5  665.97  4845.1  667.03
  4955.3  657.99  4963.7  648.78  4965.7  646.78  5026.9  648.78  5055.4  652.24
  5073.2  665.67  5078.2   661.6  5085.5  666.38  5417.2  667.94  5506.2  662.18
    5645  662.94  6625.2  666.12  6757.4  660.37  6778.5  666.04  6811.1  665.39
  7597.4  663.32  7805.1  667.12  7908.9  668.73  8631.3  673.67  9159.4   682.7
#Mann= 13 ,-1 , 0
  3256.6     .05       0  3674.9     .05       0  3963.3     .05       0
  4257.7     .05       0  4355.8     .05       0  4522.5     .16       0
  4963.7     .07       0  5026.9     .16       0    5645     .05       0
  6625.2     .16       0  6811.1     .05       0  7805.1     .05       0
  7908.9     .05       0
Bank Sta=4963.7,5026.9
XS Rating Curve= 0 ,0
Exp/Cntr=0.3,0.1