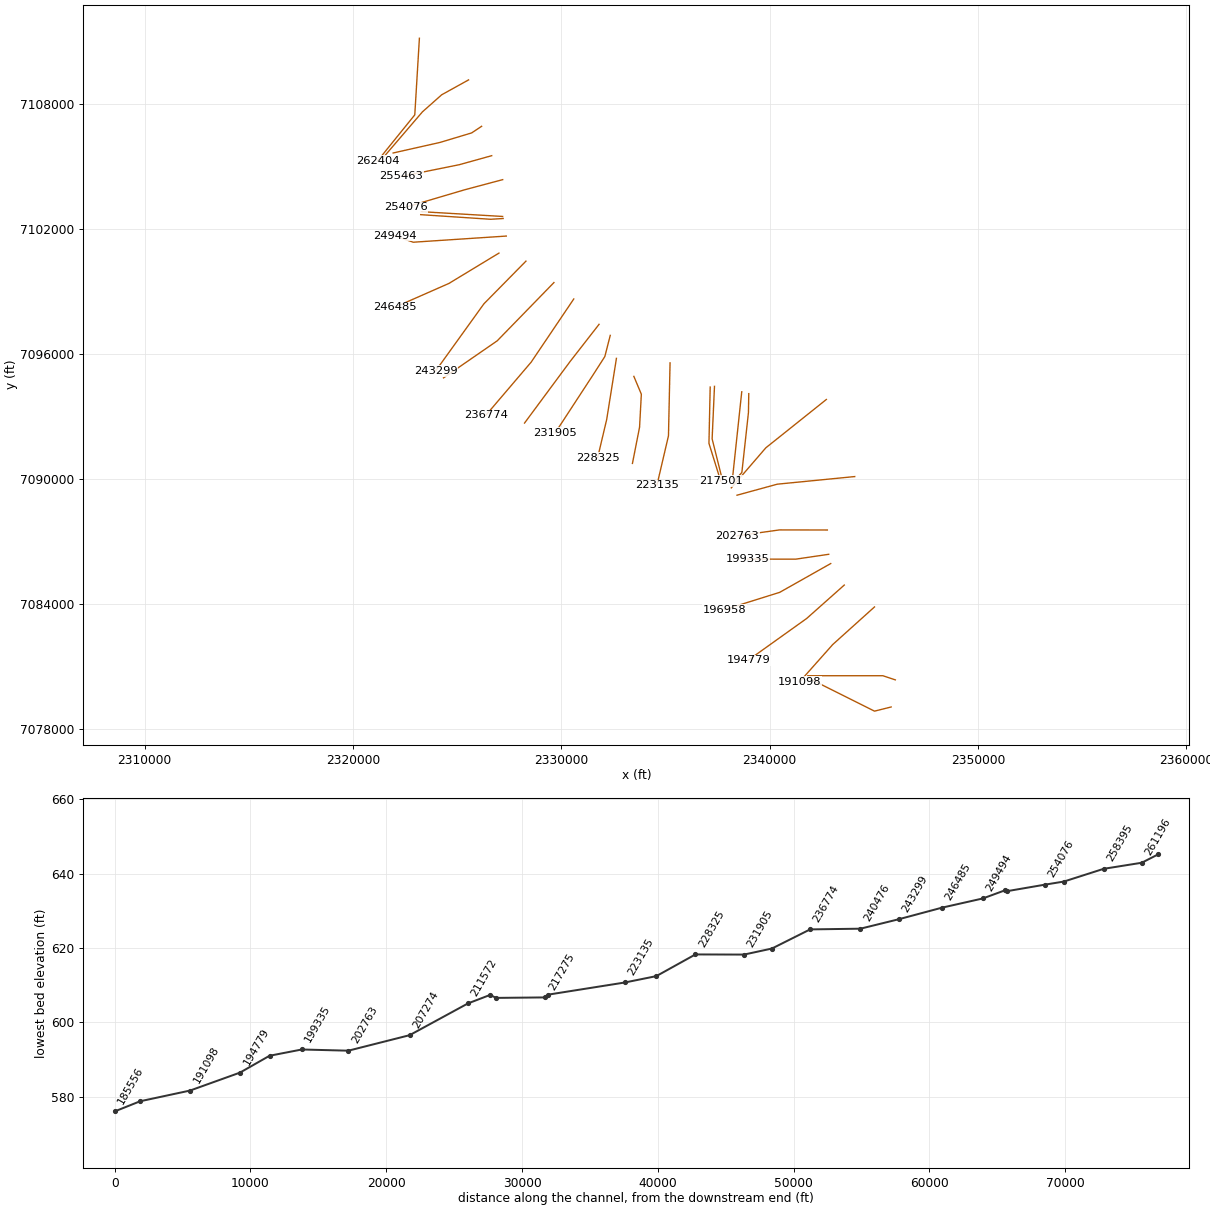
HEC-RAS study Denton Creek.prj: Denton Creek Base Level Engineering

--- Denton Creek.g01 (geometry) --- (continued)

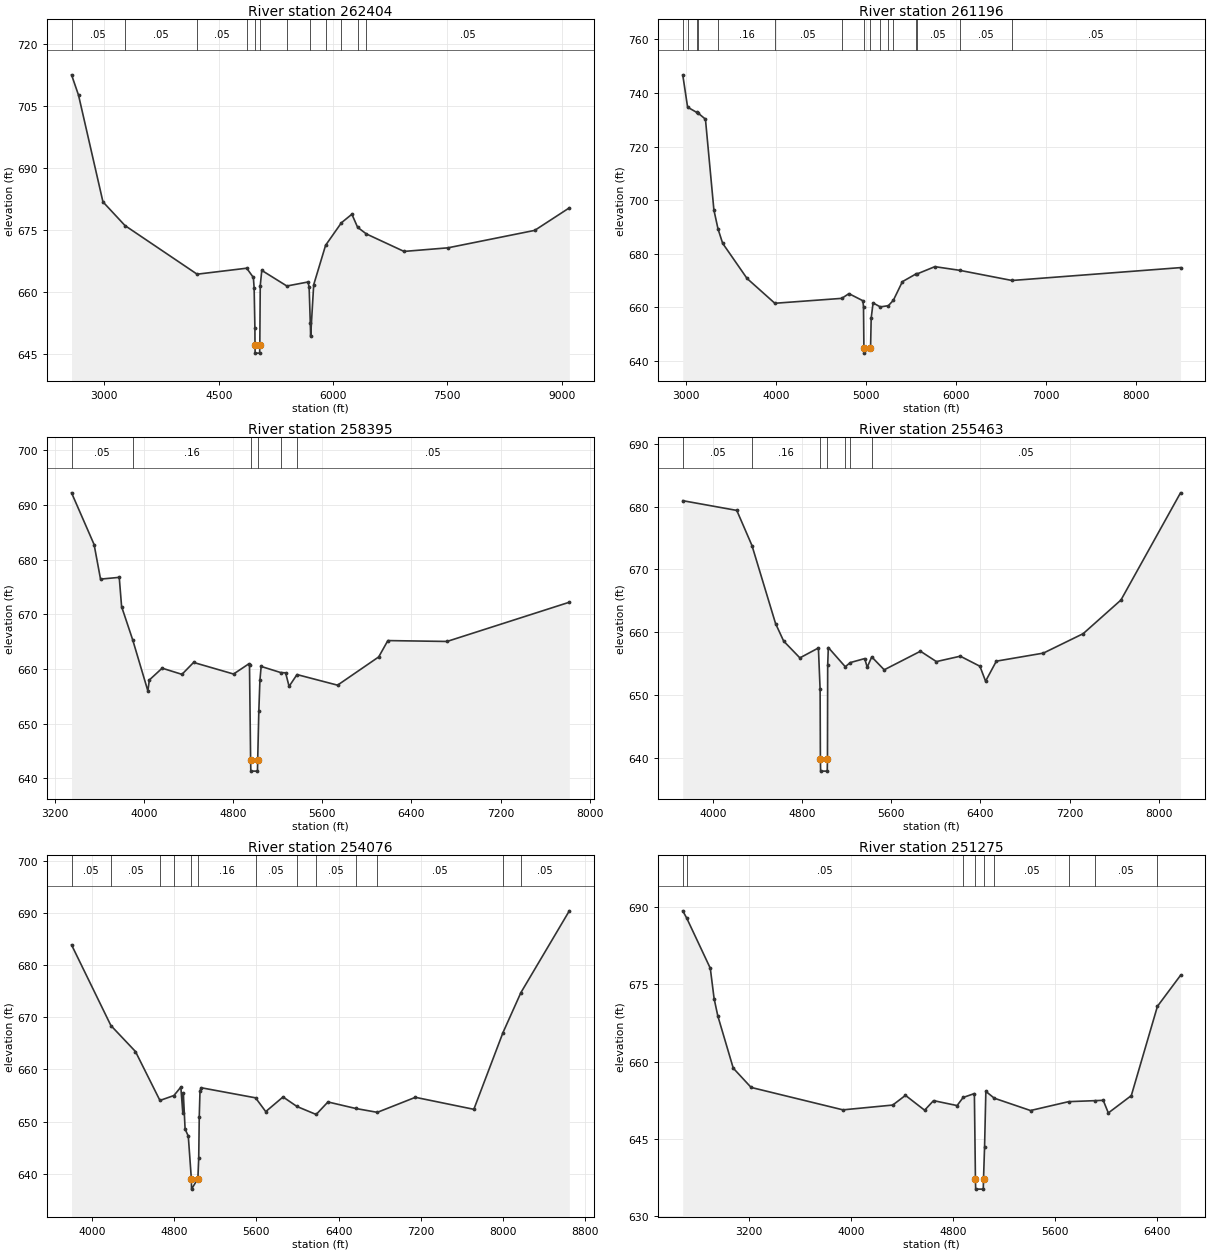
Type RM Length L Ch R = 1 ,262404  ,1208,1208,1208
BEGIN DESCRIPTION:
Denton Creek253
END DESCRIPTION:
XS GIS Cut Line= 3
       2323190.5      7111151.21      2322968.94      7107473.67
      2321180.06      7105259.28
#Sta/Elev= 30
  2569.6  712.52    2661   707.6  2981.6  681.78  3270.5  676.05  4216.9  664.28
  4867.5  665.73  4955.1  663.48  4965.2  660.91  4975.2  651.21  4976.3  647.18
  4978.3  645.18  5037.6  645.18  5039.5  647.18  5045.3   661.5  5065.3   665.2
  5394.5  661.42  5671.1  662.39  5686.5  661.23    5702  652.38  5706.5  649.26
  5746.6  661.73  5902.6  671.27  6109.9  676.72  6247.5  678.79  6322.6  675.63
  6437.7  674.02  6931.7  669.79  7507.4  670.66  8645.9  674.88  9100.5  680.33
#Mann= 12 ,-1 , 0
  2569.6     .05       0  3270.5     .05       0  4216.9     .05       0
  4867.5     .16       0  4976.3     .07       0  5039.5     .16       0
  5394.5     .05       0    5702     .16       0  5902.6     .05       0
  6109.9     .05       0  6322.6     .05       0  6437.7     .05       0
Bank Sta=4976.3,5039.5
XS Rating Curve= 0 ,0
Exp/Cntr=0.3,0.1

Type RM Length L Ch R = 1 ,261196  ,2801,2801,2801
BEGIN DESCRIPTION:
Denton Creek252
END DESCRIPTION:
XS GIS Cut Line= 4
      2325549.88       7109151.5      2324258.08      7108435.91
      2323338.69       7107620.6      2321494.53      7105470.53
#Sta/Elev= 30
  2960.4  746.75  3014.3  734.69  3116.6  732.72    3126  732.62  3212.9  730.21
    3307  696.33  3352.9  689.25  3404.4   683.9  3675.7  670.79    3985  661.53
  4729.5  663.36  4809.4  665.12    4965  662.47  4971.6   660.1  4975.9  644.93
  4977.8  642.93  5039.3  644.93  5050.3   645.3    5057     656  5077.9  661.66
    5158  660.18  5248.2  660.63  5303.7  662.65    5404  669.59  5552.2  672.41
    5565  672.44  5765.5  675.19  6039.5  673.83  6623.5  670.03  8498.6  674.83
#Mann= 16 ,-1 , 0
  2960.4     .05       0  3014.3     .05       0  3116.6     .05       0
    3126     .05       0  3352.9     .16       0    3985     .05       0
  4729.5     .16       0  4975.9     .07       0  5039.3     .16       0
    5158     .05       0  5248.2     .05       0  5303.7     .05       0
  5552.2     .05       0    5565     .05       0  6039.5     .05       0
  6623.5     .05       0
Bank Sta=4975.9,5039.3
XS Rating Curve= 0 ,0
Exp/Cntr=0.3,0.1

Type RM Length L Ch R = 1 ,258395  ,2932,2932,2932
BEGIN DESCRIPTION:
Denton Creek251
END DESCRIPTION:
XS GIS Cut Line= 4
      2326175.41      7106924.83      2325698.29      7106607.83
      2324174.16      7106149.39      2321931.48      7105644.58
#Sta/Elev= 30
  3352.2  692.23  3554.3  682.77    3612  676.44  3779.8  676.76  3800.9  671.41
  3900.6  665.31  4036.5  655.98  4049.6  657.98  4164.5  660.14    4342  659.01
  4446.4  661.19  4804.7  659.07    4942  660.94  4947.7  660.68  4957.7   643.3
  4959.6   641.3  5019.2   641.3  5021.1   643.3  5031.2  652.22  5041.1  657.92
  5052.1  660.46  5227.4  659.34  5271.4  659.29  5302.7  656.81  5373.5  658.97
  5737.2  657.03  6106.2   662.2  6188.2  665.19  6718.3  665.03  7815.4  672.21
#Mann= 6 ,-1 , 0
  3352.2     .05       0  3900.6     .16       0  4957.7     .07       0
  5021.1     .16       0  5227.4     .05       0  5373.5     .05       0
Bank Sta=4957.7,5021.1
XS Rating Curve= 0 ,0
Exp/Cntr=0.3,0.1

Type RM Length L Ch R = 1 ,255463  ,1387,1387,1387
BEGIN DESCRIPTION:
Denton Creek250
END DESCRIPTION:
XS GIS Cut Line= 3
      2326660.79       7105514.7      2325103.54      7105081.82
      2322313.71      7104518.63
#Sta/Elev= 30
    3731  680.93  4215.4  679.38  4351.5  673.79  4563.2  661.36  4635.8  658.57
  4781.1   655.9  4947.2  657.48  4962.4  650.87  4964.9  639.87  4966.8  637.87
  5026.5  637.87  5028.4  639.87  5030.3  654.74  5036.1  657.55    5188  654.49
  5232.6  655.15  5362.1  655.79  5384.7  654.41  5425.2  656.06    5537     654
    5862  656.96  6004.8  655.31  6219.1  656.17    6395  654.57  6445.8  652.19
  6542.3  655.38  6963.8  656.66  7320.9  659.76  7659.2  665.11  8193.4  682.18
#Mann= 7 ,-1 , 0
    3731     .05       0  4351.5     .16       0  4964.9     .07       0
  5028.4     .16       0    5188     .05       0  5232.6     .16       0
  5425.2     .05       0
Bank Sta=4964.9,5028.4
XS Rating Curve= 0 ,0
Exp/Cntr=0.3,0.1

Type RM Length L Ch R = 1 ,254076  ,2801,2801,2801
BEGIN DESCRIPTION:
Denton Creek249
END DESCRIPTION:
XS GIS Cut Line= 3
      2327186.98      7104364.78      2325357.23      7103876.91
      2322526.28      7103040.48
#Sta/Elev= 30
  3801.4  683.86  4184.3   668.4  4423.5  663.42  4661.7  654.04  4797.7  654.98
  4865.3   656.6  4884.1   651.7  4889.3  655.45  4906.7  648.54  4937.7  647.21
  4967.5  639.04  4969.4  637.04    5031  639.04  5039.3  642.95  5044.5  650.88
  5051.6  655.76  5061.9  656.48  5592.9  654.54  5691.6   651.9  5860.1  654.71
  5995.9  652.88  6182.5  651.35  6297.3  653.75  6567.7   652.5  6778.1  651.76
  7148.3  654.64  7717.4  652.34  8001.3  667.06  8175.7  674.72    8647  690.39
#Mann= 13 ,-1 , 0
  3801.4     .05       0  4184.3     .05       0  4661.7     .05       0
  4797.7     .16       0  4967.5     .07       0    5031     .16       0
  5592.9     .05       0  5995.9     .16       0  6182.5     .05       0
  6567.7     .05       0  6778.1     .05       0  8001.3     .05       0
  8175.7     .05       0
Bank Sta=4967.5,5031
XS Rating Curve= 0 ,0
Exp/Cntr=0.3,0.1

Type RM Length L Ch R = 1 ,251275  ,159,159,159
BEGIN DESCRIPTION:
Denton Creek248
END DESCRIPTION:
XS GIS Cut Line= 2
      2327184.82      7102598.62      2323283.16      7102827.98
#Sta/Elev= 30
  2679.7  689.24  2710.3  687.86  2895.9  678.11  2925.9  672.23  2954.9  668.87
  3076.2  658.74  3216.4     655  3937.7  650.65  4328.4  651.58  4428.5  653.46
  4578.8  650.58  4648.9  652.44  4833.7  651.48  4881.2  653.05  4969.5  653.81
  4977.8  637.28  4979.6  635.28  5039.4  635.28  5041.3  637.28  5049.6  643.54
  5059.6  654.23  5125.8  652.91  5410.2  650.52  5709.5  652.24    5913  652.43
  5981.2   652.5  6021.2  650.05  6201.6  653.41  6406.9  670.73  6588.1  676.73
#Mann= 9 ,-1 , 0
  2679.7     .05       0  2710.3     .05       0  4881.2     .16       0
  4977.8     .07       0  5041.3     .16       0  5125.8     .05       0
  5709.5     .05       0    5913     .05       0  6406.9     .05       0
Bank Sta=4977.8,5041.3
XS Rating Curve= 0 ,0
Exp/Cntr=0.3,0.1

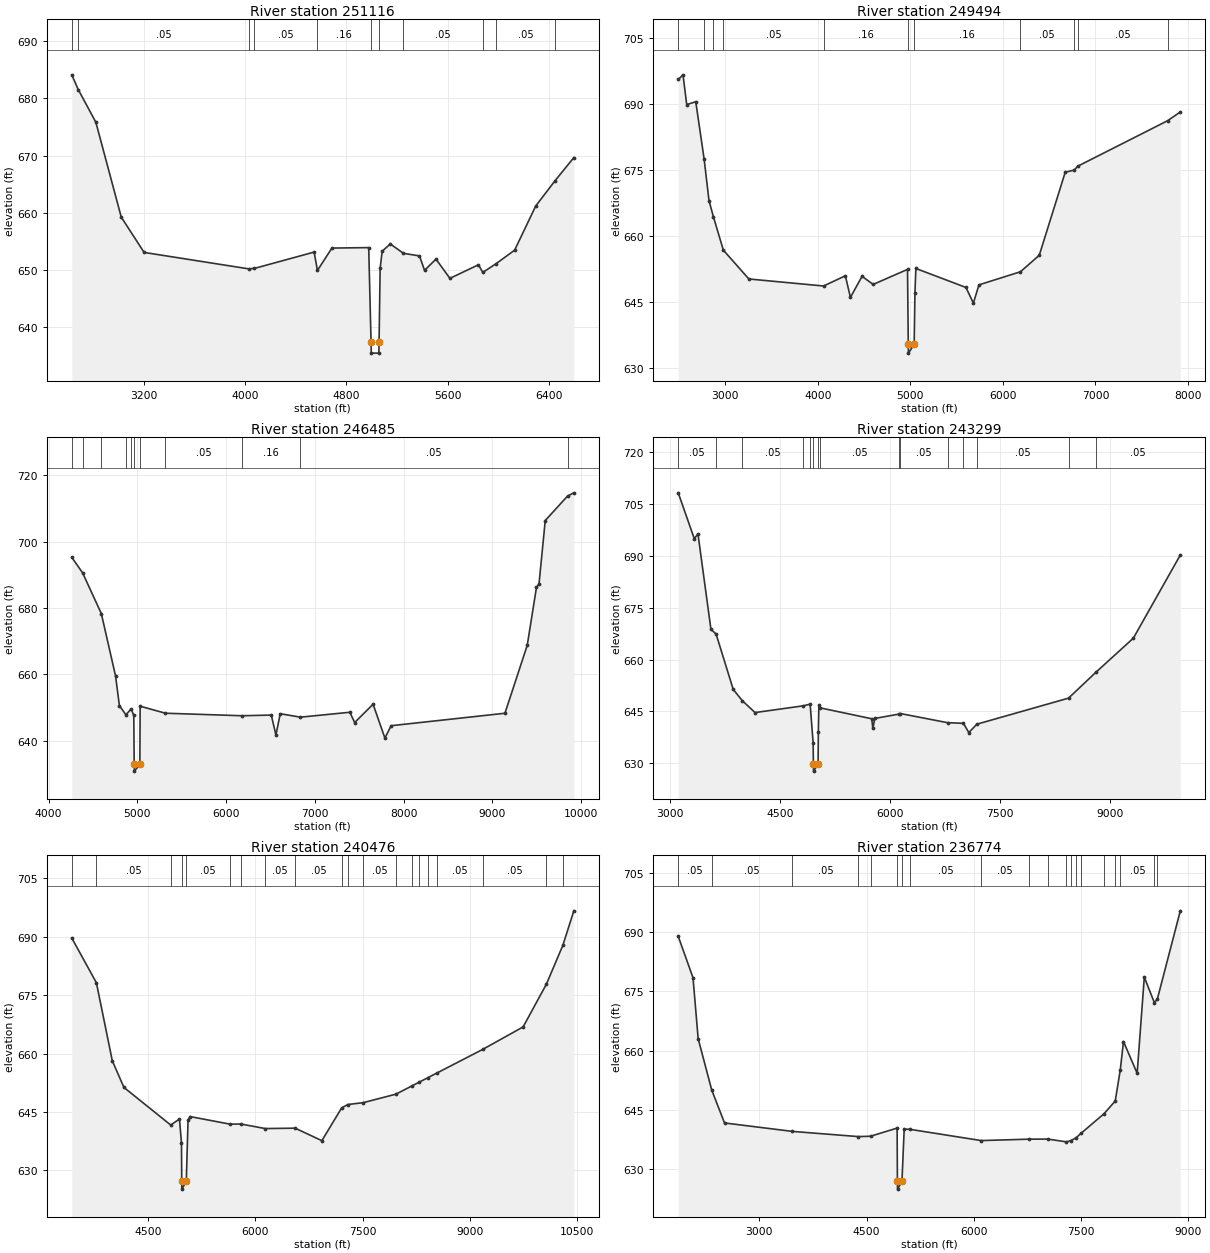
Type RM Length L Ch R = 1 ,251116  ,1622,1622,1622
BEGIN DESCRIPTION:
Denton Creek247
END DESCRIPTION:
XS GIS Cut Line= 4
      2327208.95      7102500.52      2326615.14      7102463.19
      2324934.72       7102573.6      2323252.62      7102684.74
#Sta/Elev= 30
  2631.9  684.11  2684.1  681.49  2822.2  675.82  3022.6  659.26    3203  653.09
  4028.7  650.22  4074.7   650.3  4545.9  653.15    4572  649.94  4686.2  653.85
  4976.8  653.93  4995.2   637.5    4997   635.5  5056.8   635.5  5058.7   637.5
    5067  650.29    5083   653.3  5147.2  654.57  5251.5  652.93  5377.7  652.48
  5417.8  649.96  5507.9  651.92  5618.2  648.56    5843  650.93  5877.9   649.6
  5984.5  651.15  6129.3  653.49    6296  661.21  6448.5  665.62  6596.7  669.66
#Mann= 11 ,-1 , 0
  2631.9     .05       0  2684.1     .05       0  4028.7     .05       0
  4074.7     .05       0    4572     .16       0  4995.2     .07       0
  5058.7     .16       0  5251.5     .05       0  5877.9     .05       0
  5984.5     .05       0  6448.5     .05       0
Bank Sta=4995.2,5058.7
XS Rating Curve= 0 ,0
Exp/Cntr=0.3,0.1

Type RM Length L Ch R = 1 ,249494  ,3009,3009,3009
BEGIN DESCRIPTION:
Denton Creek246
END DESCRIPTION:
XS GIS Cut Line= 3
      2327360.46      7101657.65      2322894.13      7101362.42
      2321999.45      7101675.01
#Sta/Elev= 30
  2492.7  695.61  2544.3  696.67  2584.4  689.89    2682  690.55  2772.6  677.47
  2824.9  668.06  2873.4   664.3  2980.2  656.76  3255.8   650.2    4063   648.6
  4298.1  650.93  4352.7  646.01  4478.5   650.8  4598.7  648.96  4969.6  652.38
  4977.8  635.32  4979.7  633.32  5041.4  635.32  5049.7  646.92  5059.8  652.59
  5600.9  648.27  5681.1   644.7  5741.2  648.86  6189.4  651.84  6392.7  655.59
  6673.3   674.5  6769.6  674.97  6809.7  675.88  7779.8  686.23  7916.5  688.22
#Mann= 11 ,-1 , 0
  2492.7     .05       0  2772.6     .16       0  2873.4     .05       0
  2980.2     .05       0    4063     .16       0  4977.8    .035       0
  5041.4     .16       0  6189.4     .05       0  6769.6     .05       0
  6809.7     .05       0  7779.8     .05       0
Bank Sta=4977.8,5041.4
XS Rating Curve= 0 ,0
Exp/Cntr=0.3,0.1

Type RM Length L Ch R = 1 ,246485  ,3186,3186,3186
BEGIN DESCRIPTION:
Denton Creek245
END DESCRIPTION:
XS GIS Cut Line= 3
      2327007.85      7100839.87      2324608.27      7099385.13
      2321998.41      7098235.37
#Sta/Elev= 30
  4260.9  695.28  4383.3  690.58  4593.9  678.32  4754.5  659.51  4797.5  650.58
  4871.3  647.81  4929.6  649.59    4960  647.63  4964.4  632.84  4966.3  630.84
  5028.1  632.84  5031.4  650.41  5316.4  648.29    6178  647.53  6509.3  647.73
  6561.6   641.7  6610.1  648.14  6838.1   647.1  7394.6  648.58  7448.7  645.48
  7656.3     651  7789.8   640.8  7859.8  644.53  9142.4  648.28  9393.6  668.75
  9497.8   686.2  9526.6  687.32  9596.6  706.36  9848.4  713.75  9918.9  714.71
#Mann= 11 ,-1 , 0
  4260.9     .05       0  4383.3     .05       0  4593.9     .16       0
  4871.3     .12       0  4929.6     .16       0  4964.4     .07       0
  5028.1     .16       0  5316.4     .05       0    6178     .16       0
  6838.1     .05       0  9848.4     .05       0
Bank Sta=4964.4,5028.1
XS Rating Curve= 0 ,0
Exp/Cntr=0.3,0.1

Type RM Length L Ch R = 1 ,243299  ,2823,2823,2823
BEGIN DESCRIPTION:
Denton Creek244
END DESCRIPTION:
XS GIS Cut Line= 3
      2328303.98      7100455.12      2326285.68      7098405.64
      2323969.97      7095185.96
#Sta/Elev= 30
  3114.2  708.28  3333.4  694.98    3383  696.42  3559.7  668.78  3630.1   667.4
  3863.9  651.36  3986.8  648.13  4160.8  644.67  4820.4  646.63  4911.6  647.11
  4952.8  635.91  4956.3  629.72  4958.2  627.72    5020  629.72  5023.5  638.91
  5030.5  646.81  5049.3  646.03  5751.8  642.88    5766   640.1  5794.3  642.98
  6126.6  644.24  6141.3  644.39    6786  641.74  7000.7  641.56  7073.9  638.89
  7184.4  641.31  8433.4  648.85  8803.8  656.29  9316.6  666.21  9956.6  690.28
#Mann= 15 ,-1 , 0
  3114.2     .05       0  3630.1     .16       0  3986.8     .05       0
  4820.4     .05       0  4911.6     .16       0  4956.3    .035       0
    5020     .16       0  5049.3     .05       0  6126.6     .05       0
  6141.3     .05       0    6786     .05       0  7000.7     .16       0
  7184.4     .05       0  8433.4     .05       0  8803.8     .05       0
Bank Sta=4956.3,5020
XS Rating Curve= 0 ,0
Exp/Cntr=0.3,0.1

Type RM Length L Ch R = 1 ,240476  ,3702,3702,3702
BEGIN DESCRIPTION:
Denton Creek243
END DESCRIPTION:
XS GIS Cut Line= 3
       2329646.1      7099425.96      2326925.57      7096631.52
      2324348.37      7094852.35
#Sta/Elev= 30
  3427.2   689.7  3771.9  678.21    3995  658.14  4157.8  651.31  4813.1  641.65
  4935.6  643.18  4963.9  636.97  4967.3  627.18  4969.2  625.18    5031  627.18
  5055.8  642.95  5084.1  643.82  5642.7  641.88  5797.7   641.9  6137.5  640.74
  6556.2  640.84  6929.8  637.63  7207.6  646.06  7293.8  646.92  7507.6  647.39
    7967  649.58  8198.6  651.77  8293.6  652.67  8411.9  653.79  8545.2  655.05
  9181.9  661.07  9748.7  666.86   10075  677.86 10305.2  687.83 10458.9  696.68
#Mann= 20 ,-1 , 0
  3427.2     .16       0  3771.9     .05       0  4813.1     .05       0
  4967.3     .07       0    5031     .05       0  5642.7     .05       0
  5797.7     .05       0  6137.5     .05       0  6556.2     .05       0
  7207.6     .05       0  7293.8     .05       0  7507.6     .05       0
    7967     .05       0  8198.6     .05       0  8293.6     .05       0
  8411.9     .05       0  8545.2     .05       0  9181.9     .05       0
   10075     .16       0 10305.2     .05       0
Bank Sta=4967.3,5031
XS Rating Curve= 0 ,0
Exp/Cntr=0.3,0.1

Type RM Length L Ch R = 1 ,236774  ,2812,2812,2812
BEGIN DESCRIPTION:
Denton Creek 73.0
END DESCRIPTION:
XS GIS Cut Line= 3
      2330598.07      7098638.21      2328552.04      7095605.51
      2326371.12      7093047.46
#Sta/Elev= 30
  1867.1  688.92  2073.6  678.48  2145.5  663.07  2335.8  650.03  2514.2  641.73
  3464.5  639.59  4384.9  638.28  4555.6  638.37  4927.4  640.43  4931.5  626.99
  4933.4  624.99  4995.2  626.99  5026.4  640.17  5102.8  640.13  6104.2  637.27
  6769.6  637.63  7032.9  637.65  7295.5  636.95  7352.7  637.24  7426.9  637.94
    7501  639.14  7820.8  644.07  7977.1  647.28  8047.8  655.17  8092.6  662.33
  8283.6  654.29  8383.5  678.62  8525.3  672.11  8567.5  673.18    8887  695.39
#Mann= 20 ,-1 , 0
  1867.1     .05       0  2335.8     .05       0  3464.5     .05       0
  4384.9     .05       0  4555.6     .05       0  4931.5     .07       0
  4995.2     .16       0  5102.8     .05       0  6104.2     .05       0
  6769.6     .05       0  7032.9     .05       0  7295.5     .05       0
  7352.7     .16       0  7426.9     .05       0    7501     .16       0
  7820.8     .05       0  7977.1     .16       0  8047.8     .05       0
  8525.3     .05       0  8567.5     .05       0
Bank Sta=4931.5,4995.2
XS Rating Curve= 0 ,0
Exp/Cntr=0.3,0.1

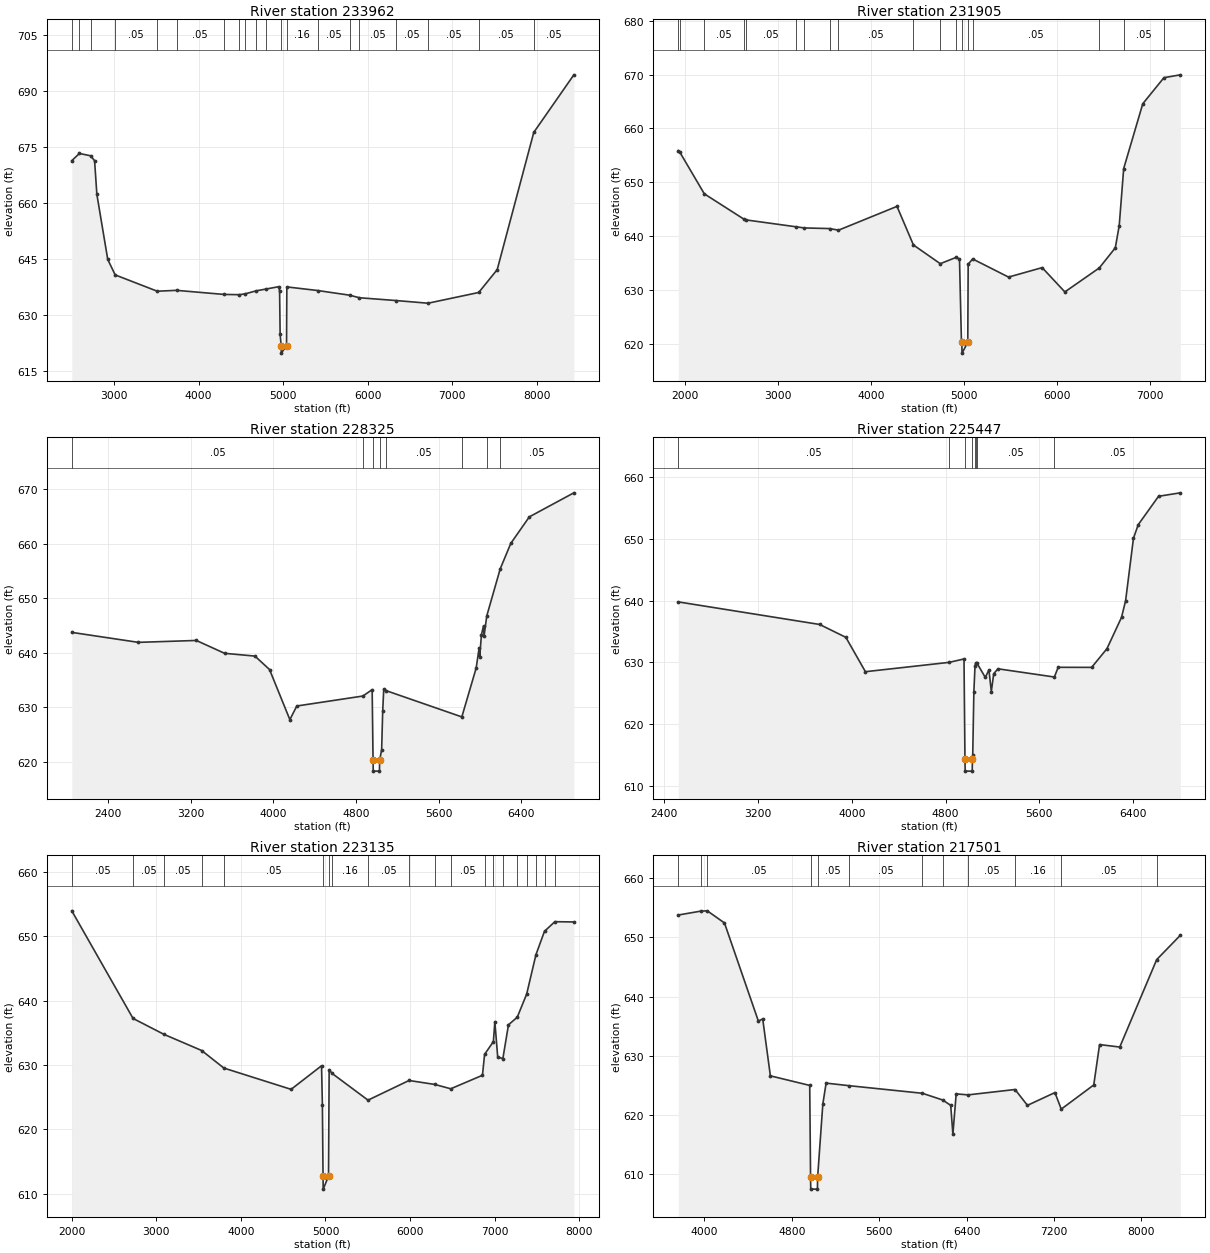
Type RM Length L Ch R = 1 ,233962  ,2057,2057,2057
BEGIN DESCRIPTION:
Denton Creek 72.0
END DESCRIPTION:
XS GIS Cut Line= 3
      2331813.24      7097423.43      2330425.06      7095641.89
       2328236.1      7092684.73
#Sta/Elev= 30
    2501  671.28  2591.1  673.21  2724.2  672.59  2770.8  671.28  2797.9  662.26
  2926.4  644.89  3014.4  640.75  3511.8  636.39  3740.2  636.62  4300.8  635.53
  4483.8  635.46  4553.7   635.7  4680.2  636.48  4803.1  636.99  4950.5  637.61
  4958.9  636.33  4965.1  624.91  4977.1  621.84    4979  619.84  5040.8  621.84
  5044.4  637.54  5407.5  636.58  5786.5  635.33  5903.3  634.64  6339.2  633.89
    6714  633.18  7313.7  636.05  7532.4  642.16  7964.9  678.85  8438.7  694.23
#Mann= 20 ,-1 , 0
    2501     .05       0  2591.1     .05       0  2724.2     .05       0
  3014.4     .05       0  3511.8     .05       0  3740.2     .05       0
  4300.8     .05       0  4483.8     .05       0  4553.7     .05       0
  4680.2     .05       0  4803.1     .16       0  4977.1     .07       0
  5040.8     .16       0  5407.5     .05       0  5786.5     .05       0
  5903.3     .05       0  6339.2     .05       0    6714     .05       0
  7313.7     .05       0  7964.9     .05       0
Bank Sta=4977.1,5040.8
XS Rating Curve= 0 ,0
Exp/Cntr=0.3,0.1

Type RM Length L Ch R = 1 ,231905  ,3580,3580,3580
BEGIN DESCRIPTION:
Denton Creek 71.0
END DESCRIPTION:
XS GIS Cut Line= 4
      2332348.96      7096892.07      2332089.13      7095875.64
      2331543.17      7095024.91      2329714.08      7092224.97
#Sta/Elev= 30
  1926.9  655.86  1941.5  655.65  2207.6  647.83  2631.4  643.15  2657.3  642.98
  3191.9  641.71  3282.8  641.49  3557.5  641.37  3651.9  641.07  4281.6   645.5
  4458.5  638.32  4747.5  634.84  4921.9  636.04  4954.4  635.67  4975.4  620.31
  4979.7  620.21  4981.6  618.21  5043.5  620.21  5047.8  634.75  5096.3  635.72
  5482.3  632.35  5844.2  634.11  6088.5  629.59  6459.2  634.05  6631.6  637.79
  6673.7  641.92  6721.9  652.54  6927.2  664.58    7155  669.43  7331.3  669.96
#Mann= 18 ,-1 , 0
  1926.9     .05       0  1941.5     .16       0  2207.6     .05       0
  2631.4     .05       0  2657.3     .05       0  3191.9    .063       0
  3282.8     .05       0  3557.5    .063       0  3651.9     .05       0
  4458.5     .05       0  4747.5     .12       0  4921.9     .16       0
  4979.7     .07       0  5043.5     .16       0  5096.3     .05       0
  6459.2     .16       0  6721.9     .05       0    7155     .05       0
Bank Sta=4979.7,5043.5
XS Rating Curve= 0 ,0
Exp/Cntr=0.3,0.1

Type RM Length L Ch R = 1 ,228325  ,2878,2878,2878
BEGIN DESCRIPTION:
Denton Creek 70.0
END DESCRIPTION:
XS GIS Cut Line= 3
      2332645.67      7095789.83        2332179.        7092860.
      2331743.74      7091020.56
#Sta/Elev= 30
  2050.6  643.71  2695.2  641.88  3255.4  642.23  3528.8  639.87  3822.5  639.36
  3963.8  636.89  4160.4   627.7  4227.6   630.2  4866.6  632.03  4956.6   633.2
  4965.2  620.25  4967.1  618.25  5027.2  618.25    5029  620.25  5048.2  622.16
  5058.5  629.27  5068.7  633.32  5091.3  633.02  5823.9   628.2  5962.8  637.17
  5991.5  640.88  5996.6  639.23  6014.1  643.32  6033.7  644.89  6038.9     643
  6065.2  646.73  6195.2  655.36  6297.6  660.04  6476.9  664.91  6907.6  669.32
#Mann= 8 ,-1 , 0
  2050.6     .05       0  4866.6     .05       0  4965.2     .07       0
    5029     .05       0  5091.3     .05       0  5823.9     .16       0
  6065.2     .05       0  6195.2     .05       0
Bank Sta=4965.2,5029
XS Rating Curve= 0 ,0
Exp/Cntr=0.3,0.1

Type RM Length L Ch R = 1 ,225447  ,2312,2312,2312
BEGIN DESCRIPTION:
Denton Creek242
END DESCRIPTION:
XS GIS Cut Line= 4
      2333482.39      7094924.01      2333840.97      7094068.18
      2333755.57      7092485.58      2333413.75      7090747.79
#Sta/Elev= 30
  2518.5  639.78    3725  636.13  3948.6  634.05  4115.6  628.49  4829.7     630
  4956.8  630.55  4964.9  614.41  4966.8  612.41  5026.9  612.41  5028.7  614.41
  5031.3  615.07  5040.8  625.15  5050.6  629.36  5056.7  629.89  5064.7  629.96
  5138.5  627.56  5169.5  628.79  5189.8  625.27  5210.3  628.16  5246.3  628.96
  5727.9  627.63  5760.2   629.2    6046  629.19  6176.4  632.21  6300.8  637.28
  6335.6  639.97  6402.7  650.08  6443.5  652.27  6616.7  656.86  6802.4  657.42
#Mann= 8 ,-1 , 0
  2518.5     .05       0  4829.7     .16       0  4964.9     .07       0
  5028.7     .16       0  5050.6     .05       0  5056.7     .05       0
  5064.7     .05       0  5727.9     .05       0
Bank Sta=4964.9,5028.7
XS Rating Curve= 0 ,0
Exp/Cntr=0.3,0.1

Type RM Length L Ch R = 1 ,223135  ,5634,5634,5634
BEGIN DESCRIPTION:
Denton Creek 69.0
END DESCRIPTION:
XS GIS Cut Line= 3
      2335219.26      7095573.32       2335142.9      7092071.41
      2334588.41      7089700.32
#Sta/Elev= 30
  1999.7  653.99  2724.4  637.25  3089.6  634.78  3536.2  632.26  3798.7  629.53
  4593.6  626.22  4953.7  629.89  4963.7  623.78  4971.4   612.7  4973.2   610.7
    5036   612.7  5043.7  629.28  5078.2   628.7  5503.2  624.54  5988.5   627.6
  6290.5  626.99  6481.7  626.31  6856.7  628.41  6881.9  631.66  6985.9  633.65
  7003.3  636.75  7036.9  631.25  7098.1  631.01  7164.4  636.26  7268.3  637.44
  7379.8  641.05  7489.5  647.18  7590.5  650.81  7713.1   652.3  7937.5  652.26
#Mann= 20 ,-1 , 0
  1999.7     .05       0  2724.4     .05       0  3089.6     .05       0
  3536.2     .05       0  3798.7     .05       0  4971.4     .07       0
    5036     .16       0  5078.2     .16       0  5503.2     .05       0
  5988.5     .05       0  6290.5     .05       0  6481.7     .05       0
  6881.9     .05       0  6985.9     .05       0  7098.1     .05       0
  7268.3     .05       0  7379.8     .05       0  7489.5     .05       0
  7590.5     .05       0  7713.1     .05       0
Bank Sta=4971.4,5036
XS Rating Curve= 0 ,0
Exp/Cntr=0.3,0.1

Type RM Length L Ch R = 1 ,217501  ,226,226,226
BEGIN DESCRIPTION:
Denton Creek241
END DESCRIPTION:
XS GIS Cut Line= 3
      2337144.77        7094413.       2337085.3      7091709.72
      2337648.62      7089904.61
#Sta/Elev= 30
  3761.1   653.8  3967.4  654.46  4026.9  654.51  4184.2  652.46  4494.3  635.87
  4534.3  636.22  4604.3   626.6  4964.4  624.98  4972.1  609.44  4973.8  607.44
    5035  607.44  5036.7  609.44  5084.4  621.83  5114.4  625.37  5322.3  624.94
  5995.8  623.65  6180.4  622.52  6254.7  621.61  6274.7  616.72  6304.7  623.55
  6413.4  623.38  6843.4  624.29  6957.1  621.61  7208.5  623.77  7266.4  620.97
  7563.9  625.06  7617.1  631.89  7801.9  631.47  8139.9  646.26    8356  650.37
#Mann= 12 ,-1 , 0
  3761.1     .05       0  3967.4     .05       0  4026.9     .05       0
  4972.1     .07       0  5036.7     .05       0  5322.3     .05       0
  5995.8     .05       0  6180.4     .16       0  6413.4     .05       0
  6843.4     .16       0  7266.4     .05       0  8139.9     .05       0
Bank Sta=4972.1,5036.7
XS Rating Curve= 0 ,0
Exp/Cntr=0.3,0.1

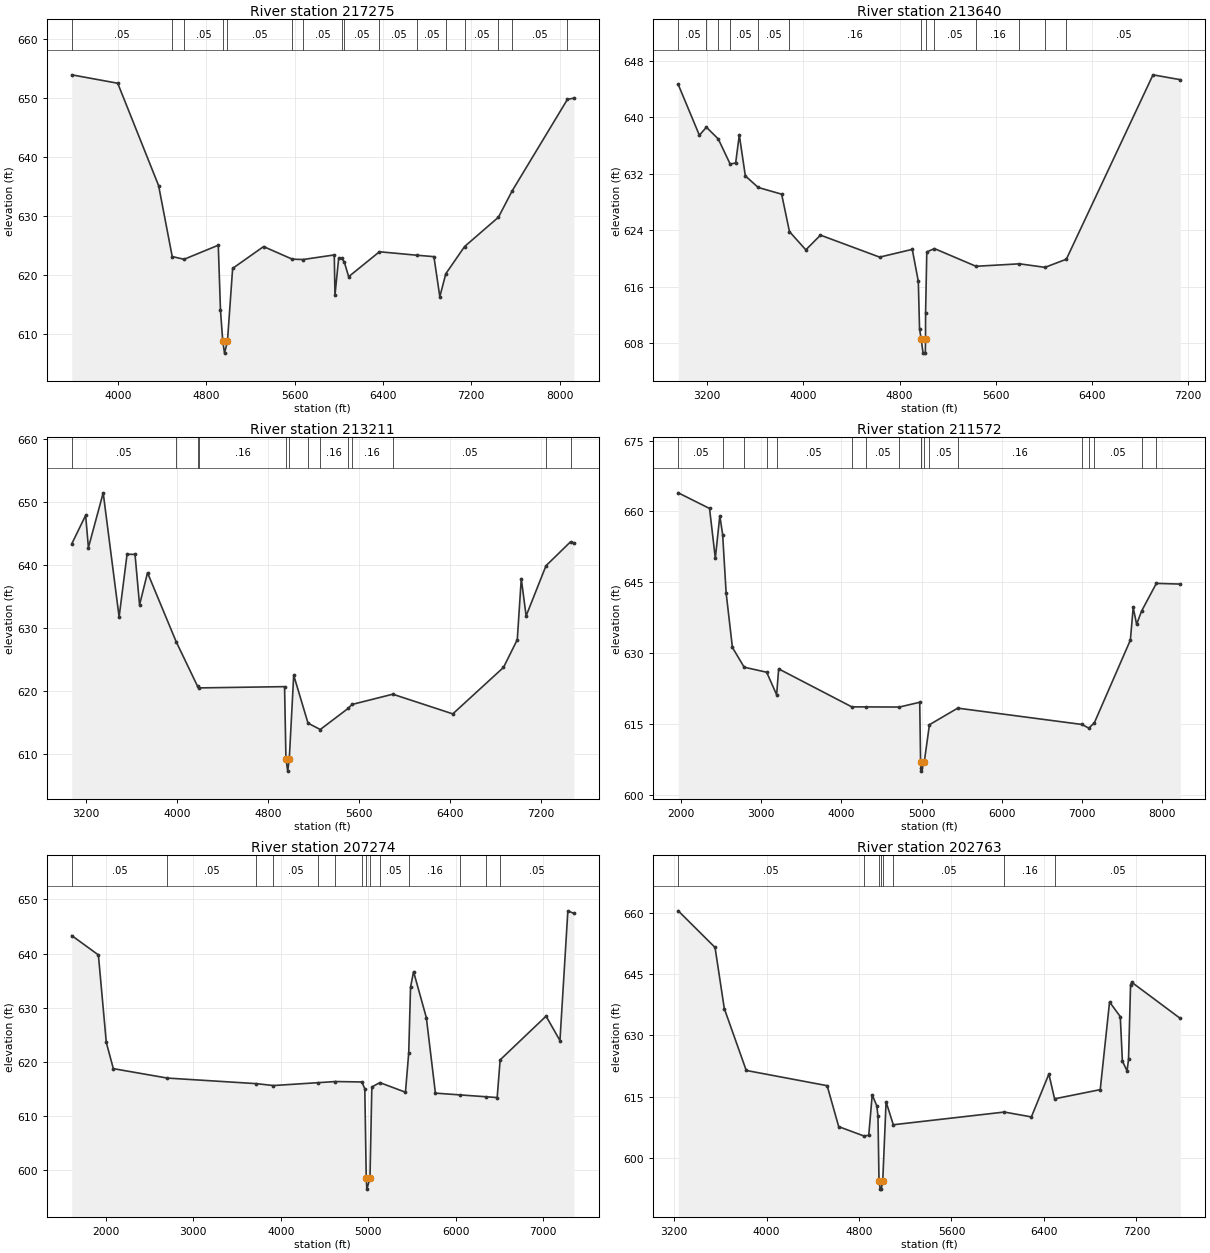
Type RM Length L Ch R = 1 ,217275  ,3635,3635,3635
BEGIN DESCRIPTION:
Denton Creek 68.0
END DESCRIPTION:
XS GIS Cut Line= 3
      2337351.12      7094446.02      2337237.88      7091926.45
      2337729.01      7089959.97
#Sta/Elev= 30
  3580.1  653.98  3996.5  652.55  4366.9  635.15  4490.2  623.09  4597.6  622.63
  4907.5  625.02  4927.5  613.98  4948.2  608.68  4964.1  606.68  4990.6  608.68
  5037.6  621.08  5317.9  624.79  5577.8  622.65  5675.8  622.59  5958.5  623.37
  5964.7  616.52  5998.6  622.86  6024.5  622.87  6050.3  622.11  6088.7  619.67
  6367.7  623.91  6712.2  623.31  6861.3  623.08  6914.8  616.27  6968.9  620.17
  7138.8  624.79  7445.9  629.78    7570  634.25    8071  649.81  8129.1  650.02
#Mann= 16 ,-1 , 0
  3580.1     .05       0  4490.2     .05       0  4597.6     .05       0
  4948.2    .035       0  4990.6     .05       0  5577.8     .16       0
  5675.8     .05       0  6024.5     .16       0  6050.3     .05       0
  6367.7     .05       0  6712.2     .05       0  6968.9     .16       0
  7138.8     .05       0  7445.9     .05       0    7570     .05       0
    8071     .05       0
Bank Sta=4948.2,4990.6
XS Rating Curve= 0 ,0
Exp/Cntr=0.3,0.1

Type RM Length L Ch R = 1 ,213640  ,429,429,429
BEGIN DESCRIPTION:
Denton Creek240
END DESCRIPTION:
XS GIS Cut Line= 2
      2338659.13      7094184.72      2338215.93      7090034.32
#Sta/Elev= 30
  2959.6  644.66  3135.3  637.46  3193.9   638.6  3292.5  636.93  3391.1  633.38
    3437  633.52  3467.2  637.49  3517.5  631.69  3624.8  630.05  3819.2   629.1
  3884.3  623.79  4020.3   621.2    4142  623.29  4633.8  620.17  4905.3  621.27
  4955.6  616.72  4965.7  609.99  4979.5  608.55    4995  606.55  5013.8  606.55
  5015.5  608.55  5015.9  612.19    5026  620.91  5089.5  621.38  5435.1  618.87
  5796.6  619.22  6008.5  618.72  6186.1  619.87  6906.6  646.03  7133.6  645.34
#Mann= 13 ,-1 , 0
  2959.6     .05       0  3193.9     .05       0  3292.5     .05       0
  3391.1     .05       0  3624.8     .05       0  3884.3     .16       0
  4979.5     .07       0  5015.5     .16       0  5089.5     .05       0
  5435.1     .16       0  5796.6     .05       0  6008.5     .05       0
  6186.1     .05       0
Bank Sta=4979.5,5015.5
XS Rating Curve= 0 ,0
Exp/Cntr=0.3,0.1

Type RM Length L Ch R = 1 ,213211  ,1639,1639,1639
BEGIN DESCRIPTION:
Denton Creek 67.0
END DESCRIPTION:
XS GIS Cut Line= 4
      2338996.09      7094096.41      2338980.69      7093190.28
       2338664.9      7090315.15      2338256.72      7089849.77
#Sta/Elev= 30
  3073.2  643.41  3195.3  647.93  3219.6  642.81  3349.7   651.5  3489.7  631.81
  3559.7  641.75  3629.7  641.74  3669.7  633.72  3739.7  638.83    3992  627.88
  4180.1  620.82  4193.4  620.56  4945.5  620.76  4957.7  609.36  4973.2  607.36
  4987.2  609.36    5026  622.57  5151.9  614.97  5259.6  613.96  5506.3  617.33
  5538.1  617.93  5897.9  619.56  6425.8  616.44  6871.9  623.81  6993.2  628.21
  7028.3  637.89    7071  631.98    7246  639.94  7461.7  643.73  7490.9  643.55
#Mann= 13 ,-1 , 0
  3073.2     .05       0    3992     .16       0  4180.1     .05       0
  4193.4     .16       0  4957.7     .07       0  4987.2     .05       0
  5151.9     .05       0  5259.6     .16       0  5506.3     .05       0
  5538.1     .16       0  5897.9     .05       0    7246    .063       0
  7461.7     .05       0
Bank Sta=4957.7,4987.2
XS Rating Curve= 0 ,0
Exp/Cntr=0.3,0.1

Type RM Length L Ch R = 1 ,211572  ,4298,4298,4298
BEGIN DESCRIPTION:
Denton Creek 65.0
END DESCRIPTION:
XS GIS Cut Line= 3
      2342720.59      7093817.11       2339814.3      7091495.42
      2338157.74      7089573.63
#Sta/Elev= 30
  1968.1  663.95  2358.3  660.64  2430.3   650.1  2486.3   659.1  2521.6  655.13
  2564.8  642.81  2643.2  631.23  2789.8  627.05  3070.1  625.99  3194.4  621.22
  3219.6   626.7  4130.9  618.66  4307.5  618.65  4723.7  618.62  4977.6  619.63
  4988.3  607.06  4993.8  605.65  4996.1  605.06  5034.7  607.06  5098.5  614.88
  5451.1  618.39  6996.8  614.94    7085  614.17  7153.4  615.27  7602.8  632.79
  7637.9  639.69  7680.7  636.13  7743.1  638.95  7926.6  644.79  8225.1  644.64
#Mann= 18 ,-1 , 0
  1968.1     .05       0  2521.6     .05       0  2789.8     .05       0
  3070.1     .16       0  3194.4     .05       0  4130.9     .16       0
  4307.5     .05       0  4723.7     .05       0  4988.3     .07       0
  4993.8     .16       0  5034.7     .05       0  5098.5     .05       0
  5451.1     .16       0  6996.8     .05       0    7085     .16       0
  7153.4     .05       0  7743.1    .063       0  7926.6     .05       0
Bank Sta=4988.3,5034.7
XS Rating Curve= 0 ,0
Exp/Cntr=0.3,0.1

Type RM Length L Ch R = 1 ,207274  ,4511,4511,4511
BEGIN DESCRIPTION:
Denton Creek 63.0
END DESCRIPTION:
XS GIS Cut Line= 3
      2344081.71       7090116.9      2340364.26      7089751.24
      2338433.02      7089222.52
#Sta/Elev= 30
  1611.4  643.31  1915.6  639.74    2006  623.58  2086.4  618.75  2702.6  617.01
  3721.6  615.98  3915.6  615.63  4424.4  616.16  4623.7  616.37  4926.8  616.29
  4960.2  615.03  4976.7  598.51  4983.7  596.51  5019.2  598.51  5040.6  615.37
  5132.1  616.17  5424.8   614.4  5462.2  621.67  5482.9   633.8  5517.4  636.65
  5663.3  628.18    5767  614.23  6050.9   613.9  6344.9  613.56  6472.9  613.41
  6506.9  620.37  7031.7  628.44  7190.4  623.93  7280.7  647.88  7349.1  647.41
#Mann= 14 ,-1 , 0
  1611.4     .05       0  2702.6     .05       0  3721.6     .05       0
  3915.6     .05       0  4424.4     .05       0  4623.7     .05       0
  4926.8     .16       0  4976.7     .07       0  5019.2     .05       0
  5132.1     .05       0  5462.2     .16       0  6050.9     .05       0
  6344.9     .16       0  6506.9     .05       0
Bank Sta=4976.7,5019.2
XS Rating Curve= 0 ,0
Exp/Cntr=0.3,0.1

Type RM Length L Ch R = 1 ,202763  ,3428,3428,3428
BEGIN DESCRIPTION:
Denton Creek 61.0
END DESCRIPTION:
XS GIS Cut Line= 3
      2342767.63      7087552.55      2340467.18      7087556.58
      2338442.68      7087272.35
#Sta/Elev= 30
  3235.6  660.51  3554.2  651.54  3634.2  636.57  3824.2  621.41  4524.2  617.68
  4624.2  607.65  4841.2  605.37  4884.2  605.52  4914.2  615.41  4954.2  612.74
  4964.2  610.14    4973  594.34  4983.8  592.34  4992.2  592.34  5005.4  594.34
  5034.2  613.71  5096.7  608.11  6057.4  611.22  6291.6  610.03    6443  620.53
  6492.4  614.46  6887.4  616.71  6968.1  638.18  7060.9   634.6  7079.2   623.7
  7119.6  621.29  7132.3  624.13  7149.9  642.41    7160  643.01  7580.4  634.15
#Mann= 8 ,-1 , 0
  3235.6     .05       0  4841.2     .16       0    4973    .035       0
  4992.2    .035       0  5005.4     .16       0  5096.7     .05       0
  6057.4     .16       0  6492.4     .05       0
Bank Sta=4973,5005.4
XS Rating Curve= 0 ,0
Exp/Cntr=0.3,0.1

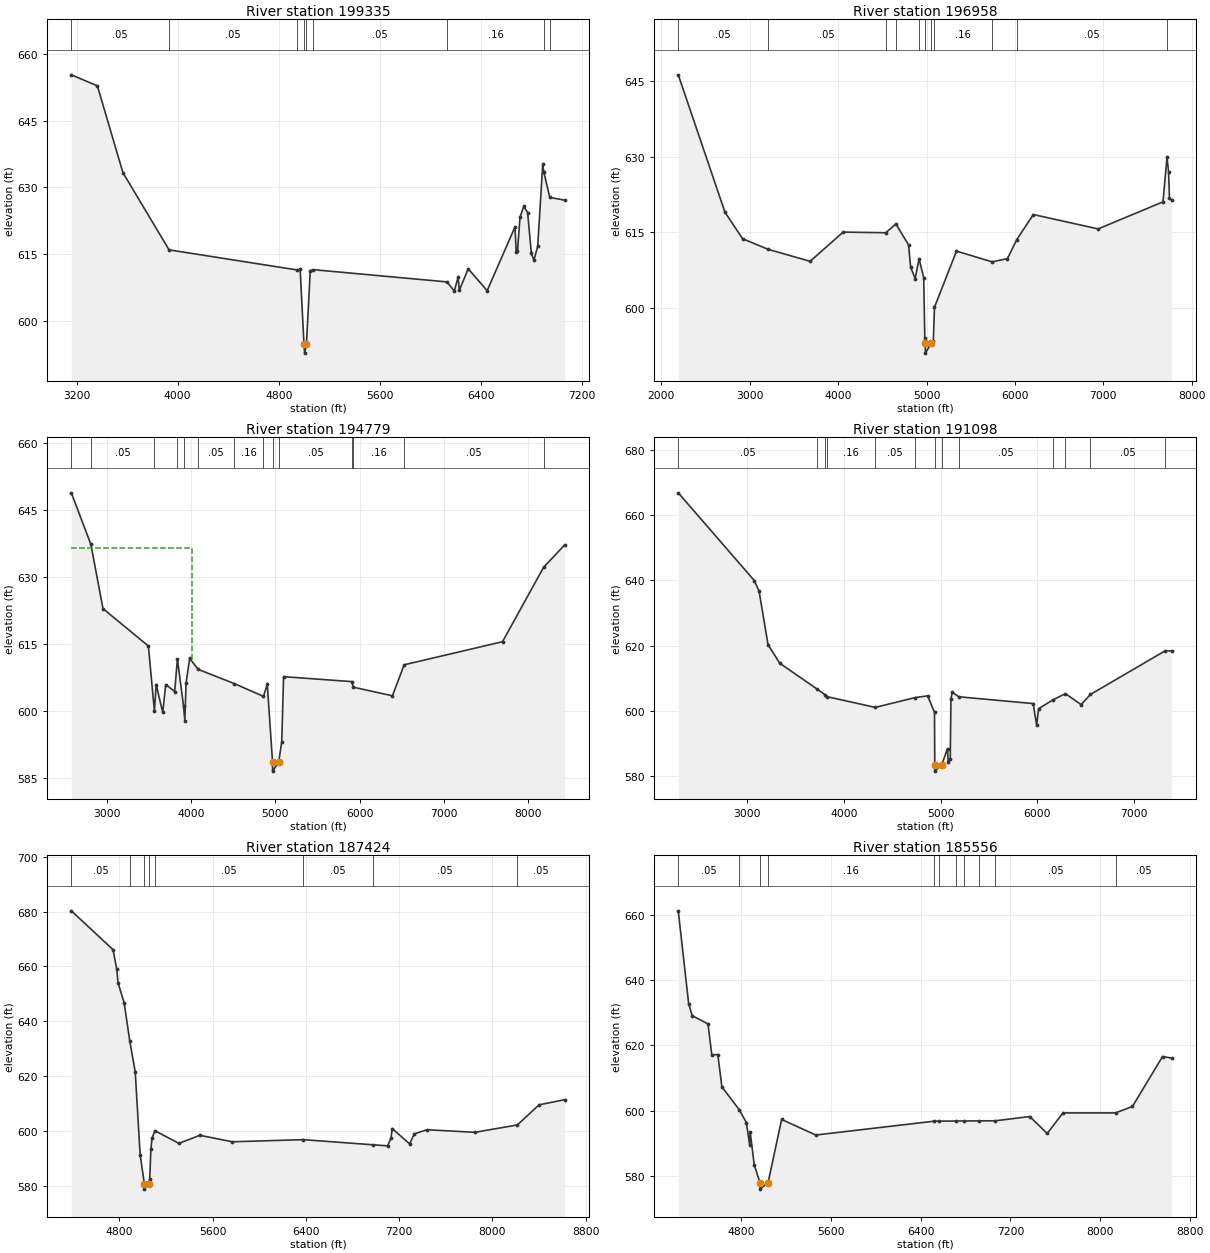
Type RM Length L Ch R = 1 ,199335  ,2377,2377,2377
BEGIN DESCRIPTION:
Denton Creek 60.0
END DESCRIPTION:
XS GIS Cut Line= 3
      2342832.91      7086386.29      2341245.94      7086152.88
      2338945.39      7086157.02
#Sta/Elev= 30
  3158.8  655.34  3364.9  652.85  3567.1  633.31  3932.3  615.92  4948.6  611.38
  4969.8  611.51  5000.1  594.66  5004.9  592.66  5019.4  594.66  5049.8  611.22
  5073.5  611.46  6132.1   608.7  6189.8  606.64  6219.8  609.77  6229.8  606.83
  6299.8  611.66  6449.8  606.73  6669.8  621.06  6679.8  615.52  6689.8  615.63
  6709.8  623.25  6739.8  625.71  6769.8  624.33  6799.8  615.11  6819.8  613.58
  6849.8  616.72  6889.8  635.24  6898.3  633.43  6945.4  627.73  7063.4  627.11
#Mann= 9 ,-1 , 0
  3158.8     .05       0  3932.3     .05       0  4948.6     .16       0
  5000.1     .07       0  5019.4     .16       0  5073.5     .05       0
  6132.1     .16       0  6898.3     .05       0  6945.4     .05       0
Bank Sta=5000.1,5019.4
XS Rating Curve= 0 ,0
Exp/Cntr=0.3,0.1

Type RM Length L Ch R = 1 ,196958  ,2179,2179,2179
BEGIN DESCRIPTION:
Denton Creek 59.0
END DESCRIPTION:
XS GIS Cut Line= 3
      2342928.54      7085942.09        2340479.        7084560.
      2337835.88      7083733.43
#Sta/Elev= 30
  2191.3  646.31  2719.6     619  2918.9  613.72  3209.9   611.6  3683.4  609.23
  4057.1  615.04  4538.5  614.91  4653.9  616.65  4797.2  612.48  4820.1  608.09
  4871.7  605.77  4915.9  609.73  4968.5  605.99  4980.9   593.9  4986.7  592.97
  4988.1  590.97  5053.4  592.97  5077.2  593.42  5090.1  600.09  5339.1  611.26
  5741.8  609.12  5915.4  609.76  6021.5  613.55  6208.8  618.53  6942.2  615.67
  7675.6  621.05  7721.1  629.89  7739.1  626.99    7749  621.83  7773.2  621.37
#Mann= 11 ,-1 , 0
  2191.3     .05       0  3209.9     .05       0  4538.5     .05       0
  4653.9     .16       0  4915.9     .05       0  4986.7    .033       0
  5053.4     .05       0  5090.1     .16       0  5741.8     .05       0
  6021.5     .05       0  7721.1    .063       0
Bank Sta=4986.7,5053.4
XS Rating Curve= 0 ,0
Exp/Cntr=0.3,0.1

Type RM Length L Ch R = 1 ,194779  ,3681,3681,3681
BEGIN DESCRIPTION:
Denton Creek 58.0
END DESCRIPTION:
XS GIS Cut Line= 3
      2343579.03      7084910.03        2341779.        7083310.
        2338979.        7081310.
#Sta/Elev= 30
  2582.9  648.77  2814.6  637.22    2958  622.84  3496.5  614.45  3568.1  599.88
  3588.5   605.8  3666.7  599.59  3702.2  605.82  3808.4  604.26  3840.4  611.58
    3913  601.05  3928.8  597.73  3943.1  606.17  3985.7  611.68  4087.1  609.22
  4513.9  606.05  4860.8  603.17  4906.4  605.87  4968.5  588.43    4969  586.43
    5041  588.43  5077.3  592.96  5099.4  607.59  5910.1  606.48  5923.4  605.24
  6389.8  603.31  6528.9  610.25  7694.9  615.42  8183.1  632.11  8432.2  637.11
#Mann= 14 ,-1 , 0
  2582.9     .05       0  2814.6     .05       0  3568.1     .16       0
  3840.4     .05       0    3913     .16       0  4087.1     .05       0
  4513.9     .16       0  4860.8     .05       0  4968.5    .035       0
    5041     .05       0  5910.1     .12       0  5923.4     .16       0
  6528.9     .05       0  8183.1     .05       0
#XS Ineff= 2 , 0
       0  4018.3  636.51               0
Permanent Ineff=
       F       F
Bank Sta=4968.5,5041
XS Rating Curve= 0 ,0
Exp/Cntr=0.3,0.1

Type RM Length L Ch R = 1 ,191098  ,3674,3674,3674
BEGIN DESCRIPTION:
Denton Creek 57.0
END DESCRIPTION:
XS GIS Cut Line= 3
      2345029.01      7083860.01        2343029.        7082060.
      2341428.98      7080259.97
#Sta/Elev= 30
  2287.9  666.78  3073.8  639.94  3123.2   636.7  3215.8  620.32  3336.2  614.64
  3724.1  606.69  3808.7  604.91  3821.4  604.42  4324.5  601.11  4737.7  604.12
  4865.4  604.65  4936.4  599.58    4939   583.6  4939.5   581.6  5011.6   583.6
    5071  588.51  5077.7  584.31  5099.1  585.17  5106.2   603.8  5120.4  605.72
  5188.2  604.35  5955.8  602.28  5991.7  595.76  6012.6  600.71  6159.5  603.41
  6289.8  605.31  6451.6  601.96  6547.7  605.06  7317.8  618.38    7387  618.42
#Mann= 13 ,-1 , 0
  2287.9     .05       0  3724.1     .05       0  3808.7     .05       0
  3821.4     .16       0  4324.5     .05       0  4737.7     .16       0
    4939     .07       0  5011.6     .16       0  5188.2     .05       0
  6159.5     .05       0  6289.8     .05       0  6547.7     .05       0
  7317.8    .063       0
Bank Sta=4939,5011.6
XS Rating Curve= 0 ,0
Exp/Cntr=0.3,0.1

Type RM Length L Ch R = 1 ,187424  ,1868,1868,1868
BEGIN DESCRIPTION:
Denton Creek 56.0
END DESCRIPTION:
XS GIS Cut Line= 3
      2346029.02      7080359.99        2345429.        7080560.
      2341828.98        7080560.
#Sta/Elev= 30
  4387.7   680.3  4746.1   666.1  4777.7  658.91  4788.3  654.07    4841   646.7
  4889.6  632.65  4935.9  621.48    4978   591.3  5013.9  580.72  5014.3  578.72
  5049.7  580.72  5060.2  582.29  5070.2  593.33  5080.2  597.39  5104.6  600.04
  5310.2  595.43  5490.2  598.36  5770.2     596  6376.2  596.78  6974.4  594.91
  7100.2  594.52  7130.2  597.26  7140.2  600.84  7290.2  595.23  7330.2   598.9
  7440.2   600.4  7850.2  599.46  8214.2  602.15  8400.2  609.49  8620.2  611.37
#Mann= 8 ,-1 , 0
  4387.7     .05       0  4889.6     .16       0  5013.9     .07       0
  5049.7     .16       0  5104.6     .05       0  6376.2     .05       0
  6974.4     .05       0  8214.2     .05       0
Bank Sta=5013.9,5049.7
XS Rating Curve= 0 ,0
Exp/Cntr=0.3,0.1

Type RM Length L Ch R = 1 ,185556  ,1953,1953,1953
BEGIN DESCRIPTION:
Denton Creek 55.0
END DESCRIPTION:
XS GIS Cut Line= 3
      2345829.04      7079060.01        2345029.        7078860.
      2341828.98      7080460.01
#Sta/Elev= 30
  4235.9  661.17  4328.7  632.77  4359.6  629.11  4501.4  626.54  4534.9  617.12
    4589  617.16  4625.1  607.31  4779.4  600.33  4844.1  596.34  4872.4  589.64
  4877.6  593.57  4913.7  583.46    4965  577.99  4965.4  575.99  5037.6  577.99
  5158.4  597.32  5463.1  592.55  6520.3  596.79  6558.5   596.8  6710.4  596.83
  6782.8  596.85  6918.8  596.88  7066.7  596.91  7372.1  598.21  7528.6  593.03
  7668.4  599.31  8137.7  599.32  8288.9  601.29  8557.2  616.57  8638.3  616.11
#Mann= 11 ,-1 , 0
  4235.9     .05       0  4779.4     .16       0    4965     .07       0
  5037.6     .16       0  6520.3     .05       0  6558.5     .05       0
  6710.4     .15       0  6782.8     .05       0  6918.8     .15       0
  7066.7     .05       0  8137.7     .05       0
Bank Sta=4965,5037.6
XS Rating Curve= 0 ,0
Exp/Cntr=0.3,0.1