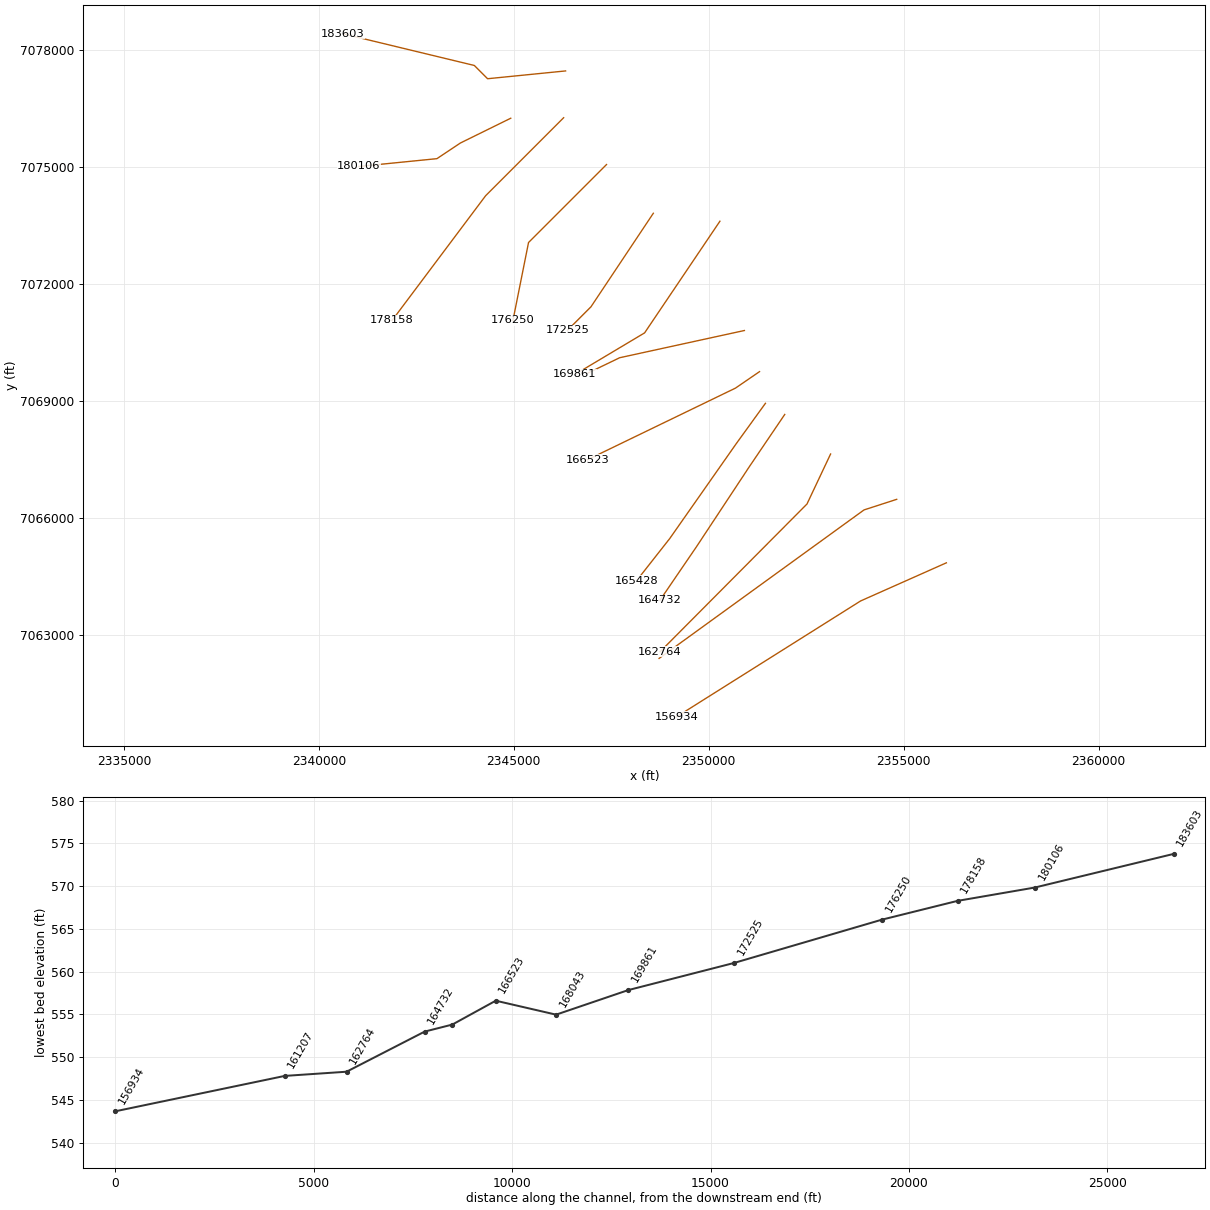
HEC-RAS study Denton Creek.prj: Denton Creek Base Level Engineering

--- Denton Creek.g01 (geometry) --- (continued)

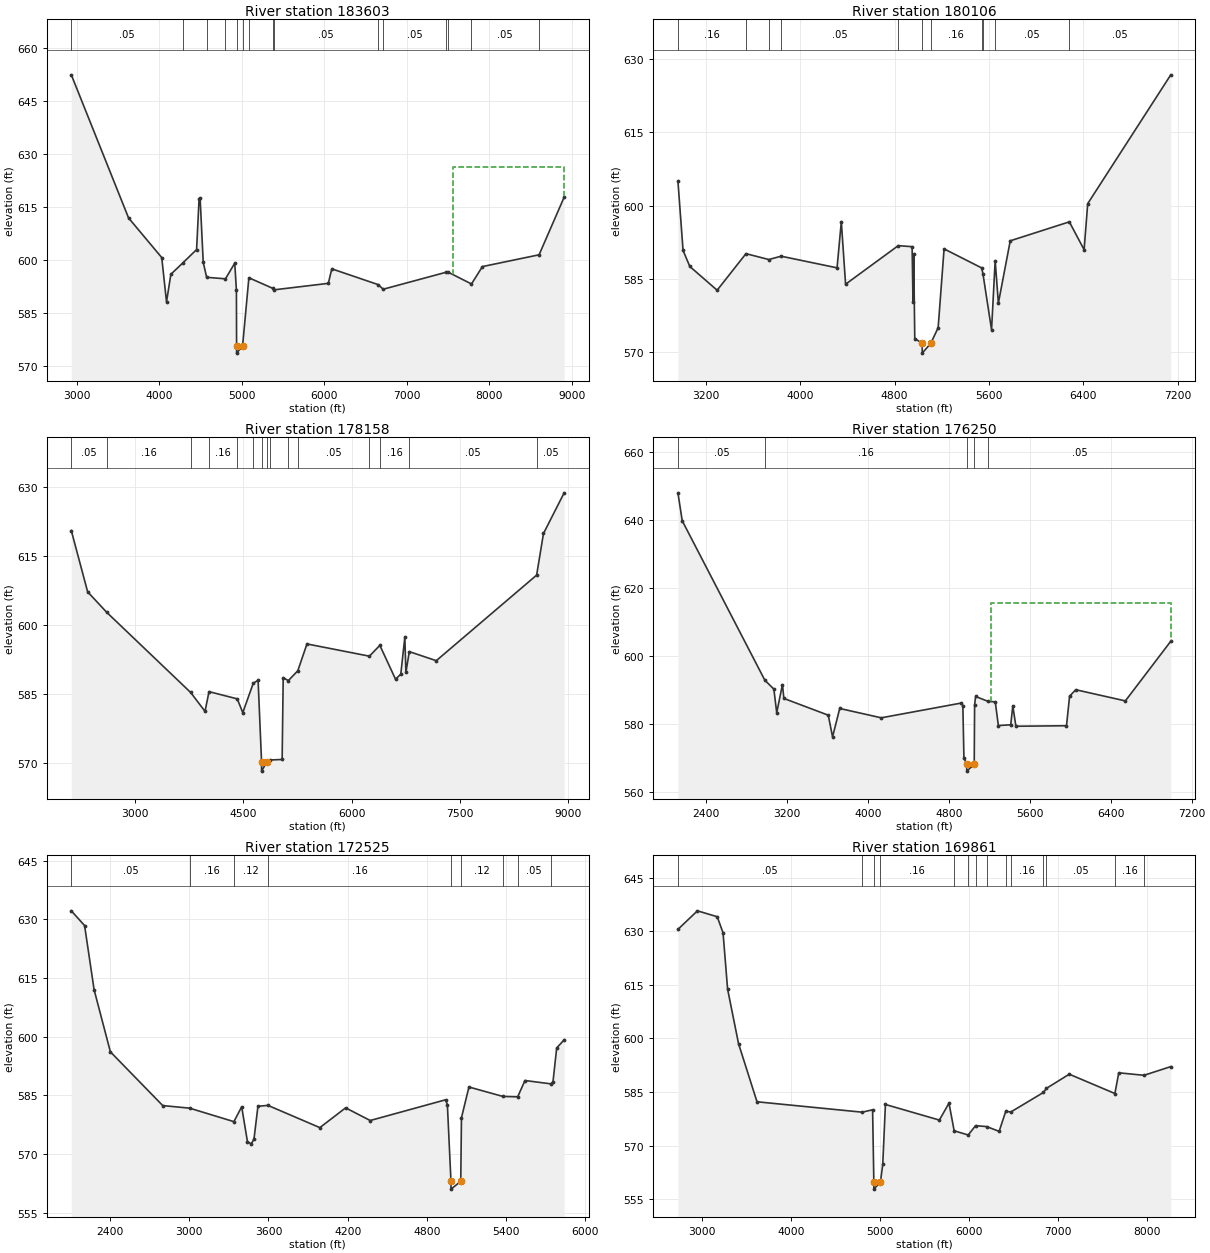
Type RM Length L Ch R = 1 ,183603  ,3497,3497,3497
BEGIN DESCRIPTION:
Denton Creek 54.0
END DESCRIPTION:
XS GIS Cut Line= 4
      2346329.02        7077460.        2344329.        7077260.
       2343989.1      7077599.86      2340607.12      7078416.33
#Sta/Elev= 30
  2935.8  652.38  3629.3  611.95  4031.3  600.75    4089  588.22  4141.8  596.04
  4290.4  599.33  4453.4  603.02  4483.5  617.39  4496.1  617.54  4533.8  599.41
  4575.2  595.18  4802.9  594.75  4915.6  599.17  4935.7   591.5  4937.8  575.76
  4938.2  573.76  5010.4  575.76  5086.7  595.05  5373.9  592.09  5394.5  591.65
  6048.9  593.47  6091.3  597.57  6653.3  593.11  6713.6  591.81  7479.4  596.63
  7497.3  596.67  7782.8   593.3  7915.6  598.21    8602  601.54  8905.6  617.82
#Mann= 15 ,-1 , 0
  2935.8     .05       0  4290.4     .16       0  4575.2     .05       0
  4802.9     .16       0  4937.8     .07       0  5010.4     .16       0
  5086.7     .05       0  5373.9     .05       0  5394.5     .05       0
  6653.3     .05       0  6713.6     .05       0  7479.4     .05       0
  7497.3     .05       0  7782.8     .05       0    8602     .05       0
#XS Ineff= 2 , 0
       0                  7562.4       0  626.31
Permanent Ineff=
       F       F
Bank Sta=4937.8,5010.4
XS Rating Curve= 0 ,0
Exp/Cntr=0.3,0.1

Type RM Length L Ch R = 1 ,180106  ,1948,1948,1948
BEGIN DESCRIPTION:
Denton Creek 53.0
END DESCRIPTION:
XS GIS Cut Line= 4
      2344922.86      7076246.96      2343631.43       7075611.6
        2343029.        7075210.      2341028.96        7075010.
#Sta/Elev= 30
    2966  605.04  3009.5  590.84  3066.6  587.56    3298   582.7  3542.1  590.18
  3735.7  588.98  3839.9  589.66  4313.5  587.28  4349.6  596.74  4385.6  583.93
  4831.7  591.82    4949  591.61  4956.5  580.19  4962.5  590.08  4971.5  572.82
  5034.4  571.83  5034.8  569.83    5107  571.83  5169.5  575.03  5219.7  591.16
  5537.3  587.27  5548.6  586.11  5621.7  574.62  5652.3  588.74  5679.5  580.07
    5780  592.81  6280.4  596.69  6405.6  590.98  6435.8  600.41  7139.3  626.77
#Mann= 11 ,-1 , 0
    2966     .16       0  3542.1     .05       0  3735.7     .16       0
  3839.9     .05       0  4831.7     .16       0  5034.4     .07       0
    5107     .16       0  5537.3     .12       0  5548.6     .16       0
  5652.3     .05       0  6280.4     .05       0
Bank Sta=5034.4,5107
XS Rating Curve= 0 ,0
Exp/Cntr=0.3,0.1

Type RM Length L Ch R = 1 ,178158  ,1908,1908,1908
BEGIN DESCRIPTION:
Denton Creek 52.0
END DESCRIPTION:
XS GIS Cut Line= 3
      2346278.99      7076259.99        2344279.        7074260.
      2341879.01      7071060.02
#Sta/Elev= 30
  2115.9  620.49  2342.2   607.2  2607.4  602.74  3768.9  585.36  3968.5  581.25
  4023.9  585.53  4415.1  583.96  4491.8  580.96  4636.7  587.35  4703.9     588
  4751.8  570.27    4752  568.27  4825.8  570.27    4871  570.69    5037   570.8
  5051.6  588.56  5122.9  587.93    5254  590.06  5380.8  595.89  6246.3  593.23
  6390.6  595.58  6607.9  588.23  6680.8  589.32    6737  597.37  6751.6   589.7
  6798.8  594.22  7172.4  592.25  8562.9  610.83  8657.9  619.87  8944.3   628.7
#Mann= 15 ,-1 , 0
  2115.9     .05       0  2607.4     .16       0  3768.9     .12       0
  4023.9     .16       0  4415.1     .12       0  4636.7     .16       0
  4751.8     .07       0  4825.8     .16       0    4871     .16       0
  5122.9     .05       0    5254     .05       0  6246.3     .05       0
  6390.6     .16       0  6798.8     .05       0  8562.9     .05       0
Bank Sta=4751.8,4825.8
XS Rating Curve= 0 ,0
Exp/Cntr=0.3,0.1

Type RM Length L Ch R = 1 ,176250  ,3725,3725,3725
BEGIN DESCRIPTION:
Denton Creek 51.0
END DESCRIPTION:
XS GIS Cut Line= 3
      2347378.99      7075059.99        2345379.        7073060.
      2344979.01      7071060.03
#Sta/Elev= 30
  2125.1  647.92  2167.5  639.71  2983.8  592.79  3072.6   590.2  3100.9  583.24
  3157.5  591.53  3171.6  587.45    3610  582.52  3652.4  576.15  3723.2   584.5
  4133.3  581.75  4925.2   586.1  4939.4  585.34    4950  569.97  4977.7  568.07
    4978  566.07  5051.7  568.07  5055.5  585.62  5065.7  588.02  5191.6  586.55
  5259.5  586.45  5290.1  579.47  5412.4   579.7  5432.8  585.25  5463.4  579.27
  5963.1  579.42  5993.7  588.12  6054.9  590.01  6544.4  586.72  6993.1  604.27
#Mann= 5 ,-1 , 0
  2125.1     .05       0  2983.8     .16       0  4977.7     .07       0
  5051.7     .16       0  5191.6     .05       0
#XS Ineff= 2 , 0
       0                    5216       0  615.57
Permanent Ineff=
       F       F
Bank Sta=4977.7,5051.7
XS Rating Curve= 0 ,0
Exp/Cntr=0.3,0.1

Type RM Length L Ch R = 1 ,172525  ,2664,2664,2664
BEGIN DESCRIPTION:
Denton Creek 50.0
END DESCRIPTION:
XS GIS Cut Line= 3
      2348578.98      7073809.97        2346979.        7071410.
      2346379.03      7070810.03
#Sta/Elev= 30
  2106.6  632.19  2207.2  628.42  2279.3  612.01  2402.5  596.13  2799.1  582.38
  3002.7  581.72    3338  578.27  3397.1  582.07  3440.6  573.18  3469.2  572.59
  3490.2  573.81  3520.2   582.2  3596.1  582.43    3989  576.74  4184.3   581.8
  4370.6  578.56  4941.4  583.86    4955   582.6  4982.2  563.01  4982.5  561.01
  5056.3  563.01  5061.7  579.26  5118.3  587.13  5375.2  584.72  5487.6  584.62
  5542.6  588.79  5737.9  587.94  5754.7  588.41    5783  597.12  5839.5   599.2
#Mann= 9 ,-1 , 0
  2106.6     .05       0  3002.7     .16       0    3338     .12       0
  3596.1     .16       0  4982.2     .07       0  5056.3     .12       0
  5375.2     .05       0  5487.6     .05       0  5737.9    .094       0
Bank Sta=4982.2,5056.3
XS Rating Curve= 0 ,0
Exp/Cntr=0.3,0.1

Type RM Length L Ch R = 1 ,169861  ,1818,1818,1818
BEGIN DESCRIPTION:
Denton Creek 49.0
END DESCRIPTION:
XS GIS Cut Line= 3
      2350286.64      7073605.91      2348355.19      7070742.29
      2346570.39       7069677.1
#Sta/Elev= 30
  2731.7  630.52  2950.5  635.71  3173.1  634.06  3238.3  629.54  3289.2  613.82
  3412.1  598.54  3619.4  582.28  4799.9  579.37  4917.1  580.04    4931  559.84
  4931.2  557.84  5005.2  559.84  5031.1  564.79    5061  581.53  5666.6  577.16
  5774.5   581.9  5832.6  574.16  5990.6  572.99  6072.9   575.6  6197.4  575.34
  6337.6     574  6412.1  579.64  6468.7  579.42  6835.3   584.9  6868.6  586.04
  7124.7     590    7637  584.59  7680.4  590.39  7963.8  589.69  8264.3  592.12
#Mann= 14 ,-1 , 0
  2731.7     .05       0  4799.9     .16       0    4931     .07       0
  5005.2     .16       0  5832.6     .05       0  5990.6     .16       0
  6072.9     .05       0  6197.4     .16       0  6412.1     .05       0
  6468.7     .16       0  6835.3     .05       0  6868.6     .05       0
    7637     .16       0  7963.8     .05       0
Bank Sta=4931,5005.2
XS Rating Curve= 0 ,0
Exp/Cntr=0.3,0.1

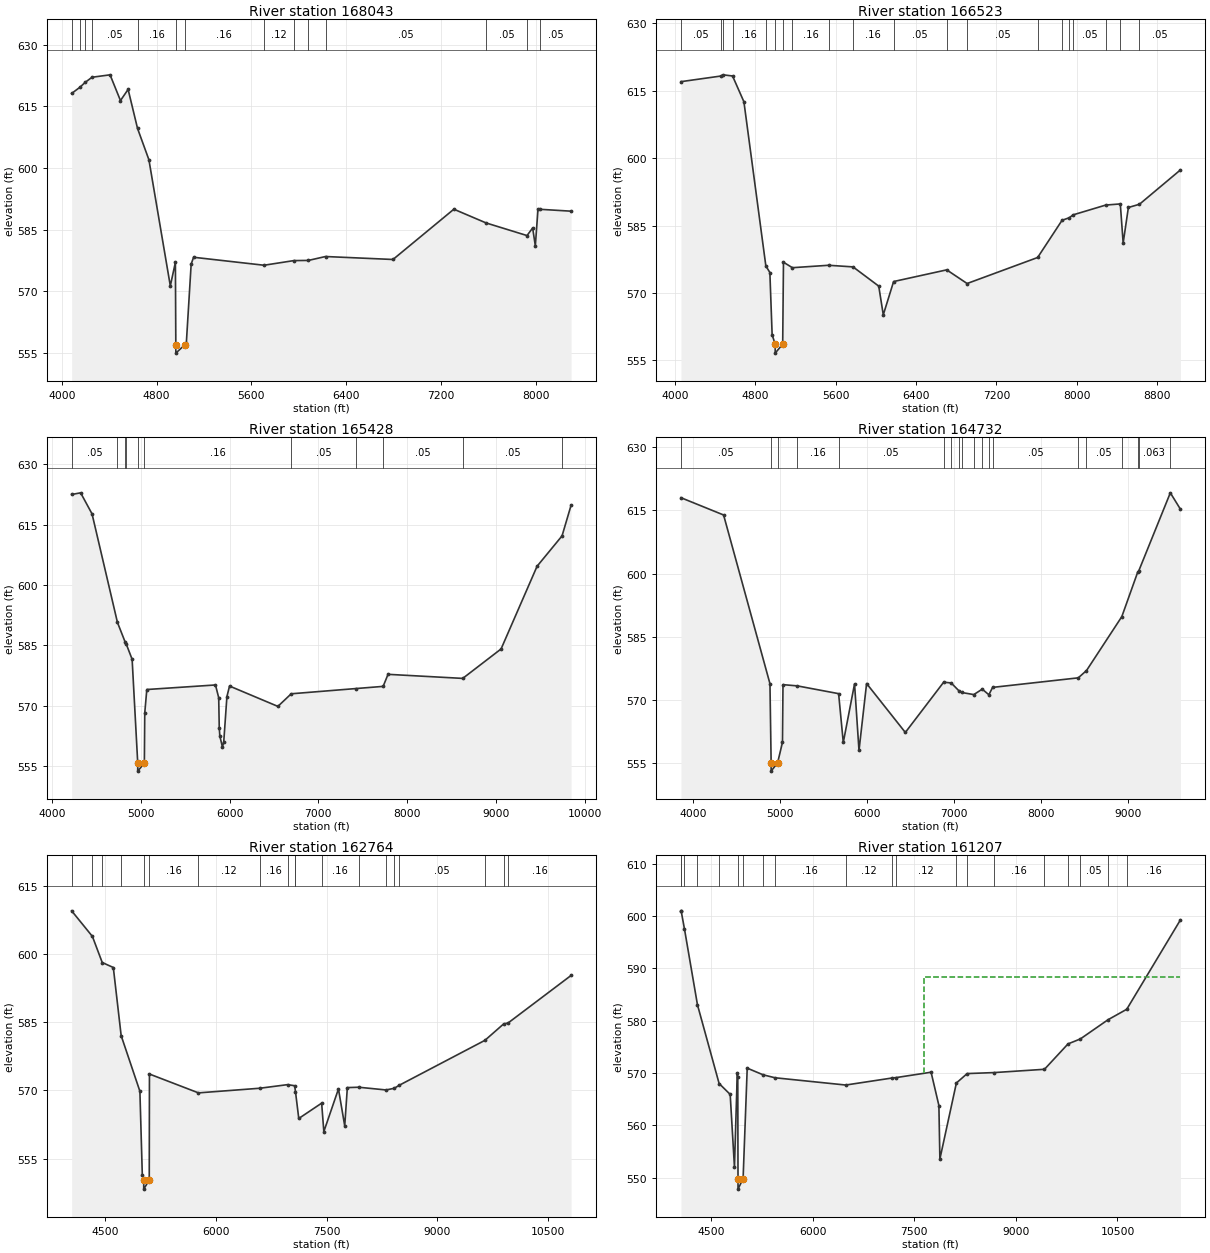
Type RM Length L Ch R = 1 ,168043  ,1520,1520,1520
BEGIN DESCRIPTION:
Denton Creek239
END DESCRIPTION:
XS GIS Cut Line= 3
      2350914.69      7070803.31      2347716.18      7070105.17
      2346867.52      7069695.92
#Sta/Elev= 30
  4082.8  618.14  4154.2  619.68  4196.3  620.82    4255  622.08  4407.1  622.67
  4494.9  616.41  4559.5  619.12  4638.9  609.64    4735  602.01  4915.8  571.32
  4958.6  577.07  4962.2  556.97  4962.4  554.97  5036.9  556.97  5050.8  557.36
  5091.7  576.63  5112.2  578.29  5706.6  576.35    5959  577.48    6081  577.52
  6225.6  578.47  6795.3  577.75  7309.1  589.98    7582  586.63  7926.5  583.57
  7974.1  585.41  7996.7  581.07  8019.4  590.05  8035.2  589.96  8298.8   589.5
#Mann= 14 ,-1 , 0
  4082.8     .05       0  4154.2     .05       0  4196.3     .05       0
    4255     .05       0  4638.9     .16       0  4962.2     .07       0
  5036.9     .16       0  5706.6     .12       0    5959     .16       0
    6081     .05       0  6225.6     .05       0    7582     .05       0
  7926.5     .16       0  8035.2     .05       0
Bank Sta=4962.2,5036.9
XS Rating Curve= 0 ,0
Exp/Cntr=0.3,0.1

Type RM Length L Ch R = 1 ,166523  ,1095,1095,1095
BEGIN DESCRIPTION:
Denton Creek 48.0
END DESCRIPTION:
XS GIS Cut Line= 3
      2351302.22      7069748.38      2350686.55      7069326.47
      2346882.44      7067485.78
#Sta/Elev= 30
  4058.8  617.01  4455.4  618.26  4478.3  618.53  4572.4  618.27  4685.5  612.53
  4903.8  576.01  4943.8  574.54  4966.4  560.68  4996.8   558.6    4997   556.6
  5071.5   558.6  5079.3  576.83    5168  575.61  5528.8  576.15  5771.9  575.79
  6027.7  571.51  6072.9  565.12  6175.7  572.53  6704.4  575.13  6907.5  572.09
  7609.6  577.88  7852.7  586.16  7925.7  586.74  7961.5  587.36  8287.7  589.55
  8432.5   589.8    8461   581.1  8512.9  589.01  8623.3  589.73  9031.2  597.37
#Mann= 20 ,-1 , 0
  4058.8     .05       0  4455.4     .05       0  4478.3     .05       0
  4572.4     .16       0  4903.8     .12       0  4996.8     .07       0
  5071.5     .12       0    5168     .16       0  5528.8     .12       0
  5771.9     .16       0  6175.7     .05       0  6704.4     .16       0
  6907.5     .05       0  7609.6     .16       0  7852.7     .05       0
  7925.7     .16       0  7961.5     .05       0  8287.7     .05       0
  8432.5     .16       0  8623.3     .05       0
Bank Sta=4996.8,5071.5
XS Rating Curve= 0 ,0
Exp/Cntr=0.3,0.1

Type RM Length L Ch R = 1 ,165428  ,696,696,696
BEGIN DESCRIPTION:
Denton Creek238
END DESCRIPTION:
XS GIS Cut Line= 4
      2351454.11      7068936.33      2350703.51      7067898.61
      2348999.41      7065467.61      2348146.64       7064383.8
#Sta/Elev= 30
  4219.5  622.49    4321   622.9  4449.5  617.67  4735.6  590.73  4820.1  585.99
  4833.7  585.42  4901.1  581.58  4964.3  555.81  4964.4  553.81    5039  555.81
  5043.4  568.23  5066.6  574.07  5840.5   575.2  5876.8  572.03  5882.9  564.64
  5889.3  562.55  5918.7  559.79  5933.5  561.04  5969.2   572.3  5998.9  574.93
  6543.7  569.88  6694.1  573.01  7423.5  574.31  7729.8  574.85    7785  577.84
  8626.8  576.83  9058.8  584.14  9464.5  604.67  9745.9  612.21  9848.1  619.84
#Mann= 11 ,-1 , 0
  4219.5     .05       0  4735.6     .16       0  4820.1     .05       0
  4833.7     .16       0  4964.3     .07       0    5039     .16       0
  6694.1     .05       0  7423.5     .16       0  7729.8     .05       0
  8626.8     .05       0  9745.9    .125       0
Bank Sta=4964.3,5039
XS Rating Curve= 0 ,0
Exp/Cntr=0.3,0.1

Type RM Length L Ch R = 1 ,164732  ,1968,1968,1968
BEGIN DESCRIPTION:
Denton Creek237
END DESCRIPTION:
XS GIS Cut Line= 4
      2351948.94      7068650.52      2351046.61      7067319.18
      2349687.29      7065260.77      2348747.26      7063884.04
#Sta/Elev= 30
  3858.4  618.03  4348.4  613.92  4881.5  573.79    4895  554.99  4895.2  552.99
  4969.7  554.99  5025.3  559.83  5031.3  573.56    5195  573.27  5670.8  571.42
  5724.4   559.8  5853.9  573.74  5905.1   557.9  5992.4  573.83  6437.8  562.19
  6878.3  574.14  6964.6  573.97  7051.5  572.15  7083.8   571.7  7224.7   571.2
  7322.2  572.49  7397.8  571.16  7441.4  572.91  8425.9  575.18  8520.5  576.91
  8926.5  589.74  9108.6  600.29  9118.5  600.48  9484.2  619.19  9600.5  615.29
#Mann= 19 ,-1 , 0
  3858.4     .05       0    4895    .035       0  4969.7     .05       0
    5195     .16       0  5670.8     .05       0  6878.3     .16       0
  6964.6     .05       0  7051.5     .16       0  7083.8     .05       0
  7224.7     .16       0  7322.2     .05       0  7397.8     .16       0
  7441.4     .05       0  8425.9    .094       0  8520.5     .05       0
  8926.5    .063       0  9108.6    .094       0  9118.5    .063       0
  9484.2    .094       0
Bank Sta=4895,4969.7
XS Rating Curve= 0 ,0
Exp/Cntr=0.3,0.1

Type RM Length L Ch R = 1 ,162764  ,1557,1557,1557
BEGIN DESCRIPTION:
Denton Creek 47.0
END DESCRIPTION:
XS GIS Cut Line= 3
      2353124.84      7067635.68      2352519.42      7066353.96
      2348750.46      7062563.72
#Sta/Elev= 30
  4047.7  609.48    4329  603.85  4461.8  598.12    4612  597.02  4718.2  582.04
  4971.9  569.81  5004.6  551.34  5023.7   550.3  5023.9   548.3  5098.6   550.3
  5101.2   573.6  5764.7  569.46  6596.4  570.48  6971.2  571.27  7067.3  571.03
  7078.4  569.74  7122.9  563.83  7432.7   567.2  7462.4  560.95  7660.3  570.32
  7745.2  562.21  7780.6  570.62  7934.5   570.7  8304.8   570.1  8416.6  570.47
  8481.9  571.12  9643.4  581.01  9896.4  584.61  9955.9  584.81 10810.4  595.28
#Mann= 19 ,-1 , 0
  4047.7     .05       0    4329     .05       0  4461.8     .05       0
  4718.2     .16       0  5023.7     .07       0  5098.6     .16       0
  5764.7     .12       0  6596.4     .16       0  6971.2     .12       0
  7067.3     .16       0  7078.4     .12       0  7432.7     .16       0
  7934.5     .05       0  8304.8     .16       0  8416.6     .05       0
  8481.9     .05       0  9643.4     .16       0  9896.4     .05       0
  9955.9     .16       0
Bank Sta=5023.7,5098.6
XS Rating Curve= 0 ,0
Exp/Cntr=0.3,0.1

Type RM Length L Ch R = 1 ,161207  ,4273,4273,4273
BEGIN DESCRIPTION:
Denton Creek 46.0
END DESCRIPTION:
XS GIS Cut Line= 3
      2354819.96      7066473.64      2353982.58      7066202.54
      2348726.56      7062394.15
#Sta/Elev= 30
  4058.3  600.99  4060.8  600.99  4108.8  597.61  4302.1  583.01  4621.3  567.99
  4784.6  565.91  4847.6  552.05  4889.7  570.06  4896.5   569.3  4900.2  549.81
  4900.3  547.81  4975.2  549.81    5036  570.93  5269.5  569.66  5445.8  569.09
  6490.1   567.7  7176.5  569.05  7226.7  569.11  7749.4  570.15  7864.6  563.79
  7879.3  553.57  8122.7  568.09  8281.9  569.89  8679.3  570.08  9422.8  570.71
  9770.2  575.56  9952.1  576.51 10360.8  580.18 10636.8  582.18 11429.2  599.26
#Mann= 20 ,-1 , 0
  4058.3    .063       0  4060.8     .16       0  4108.8     .05       0
  4302.1     .16       0  4621.3     .12       0  4900.2     .07       0
  4975.2     .16       0  5269.5     .12       0  5445.8     .16       0
  6490.1     .12       0  7176.5     .16       0  7226.7     .12       0
  8122.7     .12       0  8281.9     .05       0  8679.3     .16       0
  9422.8     .05       0  9770.2     .05       0  9952.1     .05       0
 10360.8     .05       0 10636.8     .16       0
#XS Ineff= 2 , 0
       0                    7643       0  588.33
Permanent Ineff=
       F       F
Bank Sta=4900.2,4975.2
XS Rating Curve= 0 ,0
Exp/Cntr=0.3,0.1

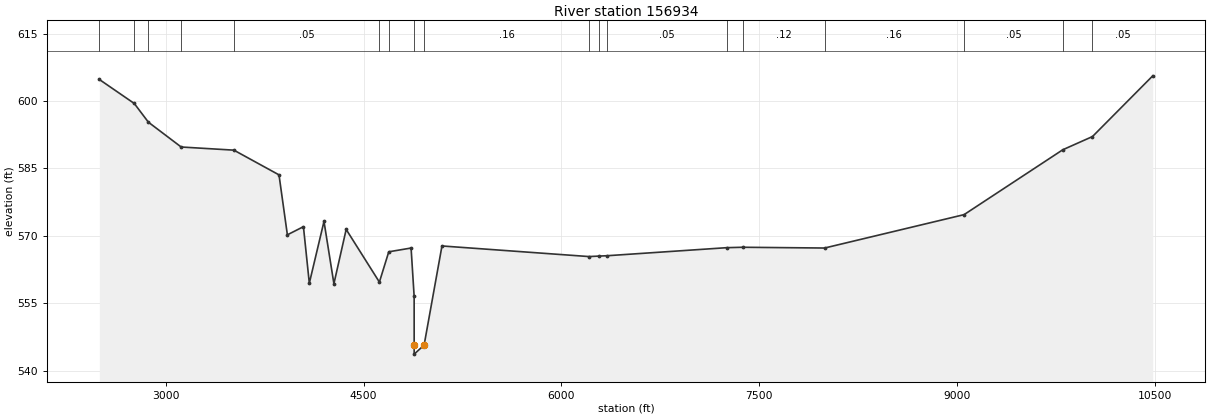
Type RM Length L Ch R = 1 ,156934  ,4713,4713,4713
BEGIN DESCRIPTION:
Denton Creek 45.0
END DESCRIPTION:
XS GIS Cut Line= 3
      2356093.94       7064845.9      2353894.14      7063867.45
      2349170.96      7060894.36
#Sta/Elev= 30
  2495.6  604.79  2760.4  599.45  2867.7  595.28  3116.3  589.76    3516  589.06
  3858.1  583.56  3921.6  570.22  4043.4  572.03    4088  559.45  4199.3   573.2
  4274.5  559.34  4367.5  571.42  4619.4   559.7  4690.5  566.44  4859.8  567.28
    4883  556.52  4883.2  545.67  4883.3  543.67  4958.5  545.67    5094  567.74
  6208.4  565.38  6287.8  565.49  6348.1  565.57  7254.7  567.36  7374.2  567.45
  7995.6  567.28  9053.4  574.71  9802.1  589.15 10027.3  592.09 10484.2   605.6
#Mann= 18 ,-1 , 0
  2495.6     .05       0  2760.4     .05       0  2867.7    .063       0
  3116.3     .05       0    3516     .05       0  4619.4     .12       0
  4690.5     .16       0  4883.2     .07       0  4958.5     .16       0
  6208.4     .05       0  6287.8     .16       0  6348.1     .05       0
  7254.7     .16       0  7374.2     .12       0  7995.6     .16       0
  9053.4     .05       0  9802.1     .05       0 10027.3     .05       0
Bank Sta=4883.2,4958.5
XS Rating Curve= 0 ,0
Exp/Cntr=0.3,0.1