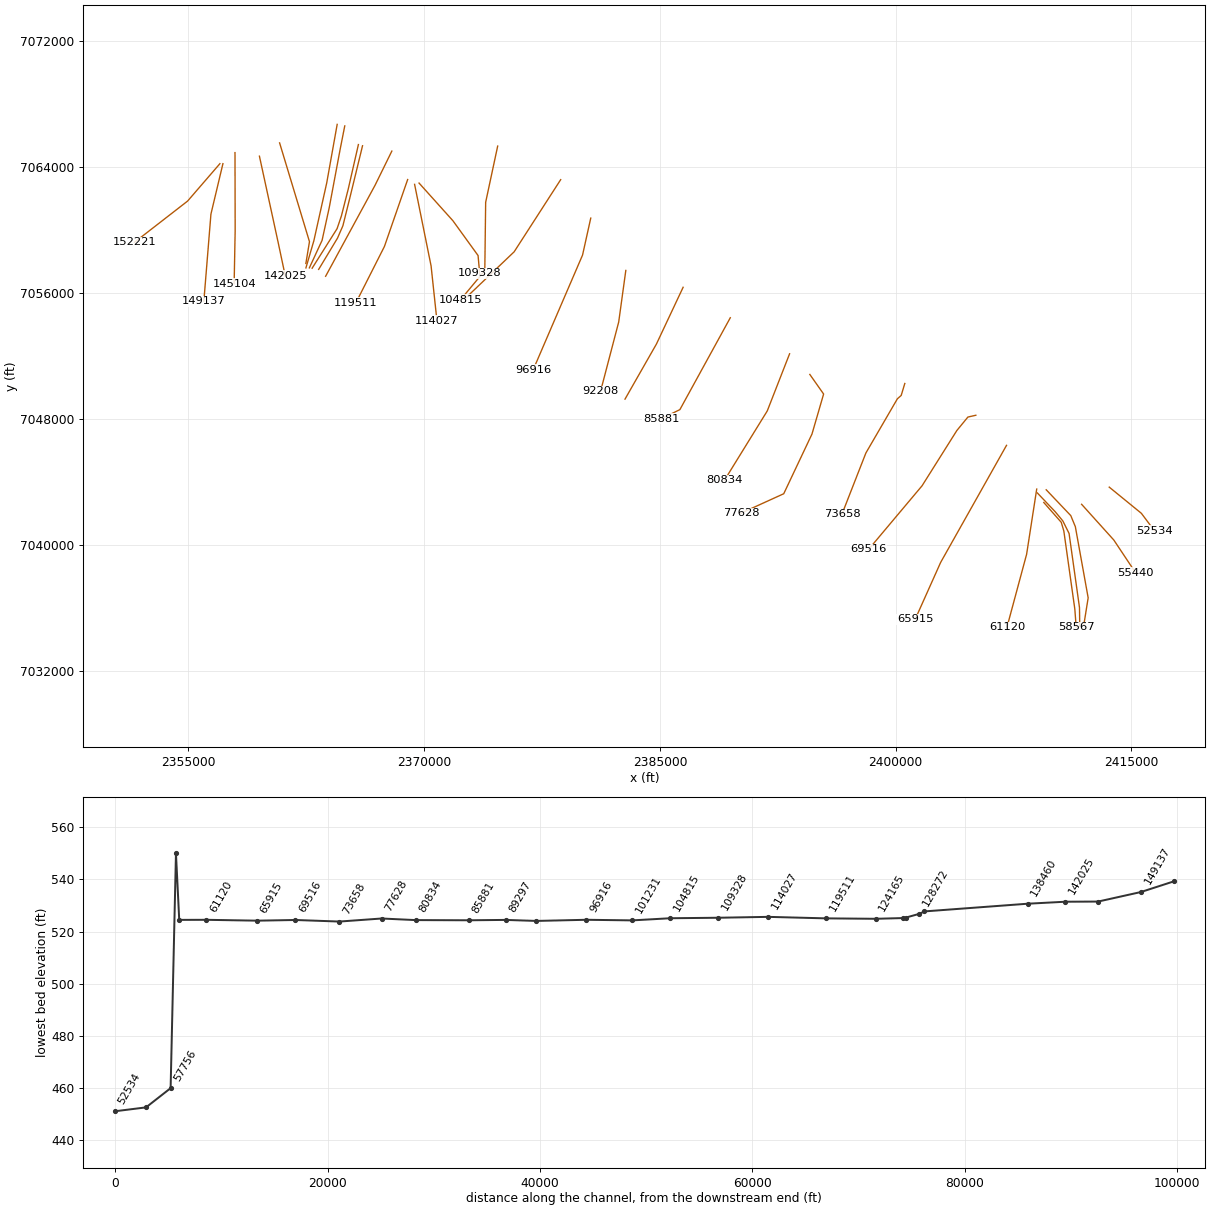
HEC-RAS study Denton Creek.prj: Denton Creek Base Level Engineering

--- Denton Creek.g01 (geometry) --- (continued)

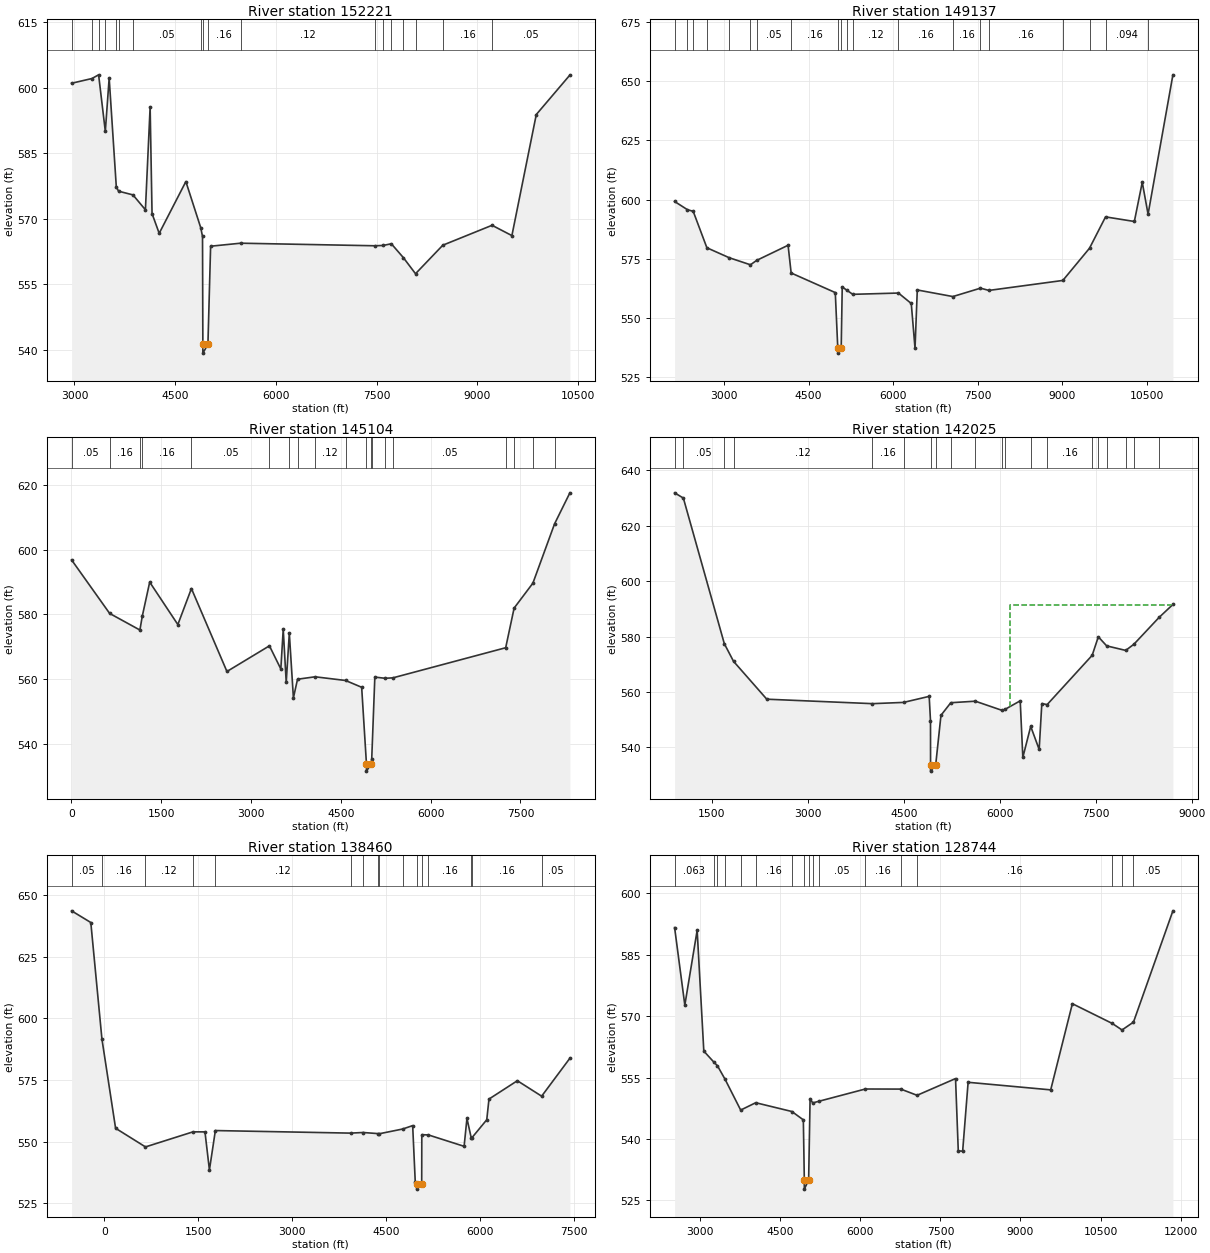
Type RM Length L Ch R = 1 ,152221  ,3084,3084,3084
BEGIN DESCRIPTION:
Denton Creek 44.0
END DESCRIPTION:
XS GIS Cut Line= 3
      2357006.88      7064211.97      2354953.17      7061837.86
      2351569.73      7059217.68
#Sta/Elev= 30
  2957.2  601.04  3259.6  602.12  3359.6  602.97  3459.4  590.03  3516.8  602.23
  3622.9  577.34  3656.2  576.33  3870.8  575.48  4056.4  572.07  4126.6  595.61
  4155.1   571.2  4261.5  566.68  4658.6  578.53  4880.3  567.95  4906.5  565.96
  4911.6  541.25  4911.7  539.25  4986.9  541.25  5027.1  563.73  5473.9  564.42
  7471.5  563.83  7594.4   563.9  7717.3  564.29  7896.2  561.12  8077.6  557.43
  8483.8  563.96  9216.9  568.52  9512.3  566.16  9875.4  593.88 10375.7  602.92
#Mann= 18 ,-1 , 0
  2957.2     .05       0  3259.6    .063       0  3359.6     .05       0
  3459.4    .063       0  3622.9     .05       0  3656.2     .16       0
  3870.8     .05       0  4880.3     .16       0  4911.6     .07       0
  4986.9     .16       0  5473.9     .12       0  7471.5     .05       0
  7594.4     .12       0  7717.3     .05       0  7896.2     .05       0
  8077.6     .05       0  8483.8     .16       0  9216.9     .05       0
Bank Sta=4911.6,4986.9
XS Rating Curve= 0 ,0
Exp/Cntr=0.3,0.1

Type RM Length L Ch R = 1 ,149137  ,4033,4033,4033
BEGIN DESCRIPTION:
Denton Creek 43.0
END DESCRIPTION:
XS GIS Cut Line= 3
      2357200.87      7064214.36      2356437.61      7061011.17
      2355986.83      7055477.77
#Sta/Elev= 30
  2122.8  599.19  2351.7  595.71  2452.9  595.04  2695.9  579.65  3093.1  575.44
  3468.9  572.47  3580.2  574.34    4137  580.71  4191.3  569.01  4974.8  560.73
  5019.3  537.18  5019.4  535.18  5079.7  537.18  5098.2  563.13  5184.2  561.65
  5285.4     560  6095.9  560.54  6323.5  556.13  6390.1  537.18  6430.2  561.84
  7061.8  559.06  7551.7   562.6  7702.4  561.65  9013.7  565.86  9487.1  579.46
  9771.7  592.69 10282.9  590.75 10423.4   607.3 10526.4  593.81 10967.4  652.65
#Mann= 20 ,-1 , 0
  2122.8     .05       0  2351.7     .05       0  2452.9    .063       0
  2695.9    .063       0  3093.1     .05       0  3468.9    .063       0
  3580.2     .05       0  4191.3     .16       0  5019.3     .07       0
  5079.7     .12       0  5184.2     .16       0  5285.4     .12       0
  6095.9     .16       0  7061.8     .16       0  7551.7     .12       0
  7702.4     .16       0  9013.7     .05       0  9487.1    .094       0
  9771.7    .094       0 10526.4     .05       0
Bank Sta=5019.3,5079.7
XS Rating Curve= 0 ,0
Exp/Cntr=0.3,0.1

Type RM Length L Ch R = 1 ,145104  ,3079,3079,3079
BEGIN DESCRIPTION:
Denton Creek 41.0
END DESCRIPTION:
XS GIS Cut Line= 3
      2357968.38      7064914.59        2357979.        7059960.
      2357913.89      7056593.13
#Sta/Elev= 30
     4.1  596.86     640   580.3    1145  575.17  1185.3  579.49  1308.7  589.99
  1778.7  576.86  2005.6     588  2598.7  562.34  3308.3  570.28  3498.7  563.12
  3538.7  575.39  3588.7     559  3640.4  574.21  3708.7  554.17  3777.5  559.95
  4071.6   560.7  4579.7  559.56  4848.7  557.46  4928.7  533.72  4928.8  531.52
  5008.7  533.72  5016.6  535.25  5068.7  560.61  5240.3  560.24  5371.5  560.38
  7253.9  569.69  7394.8  581.96  7708.4  589.67  8069.9     608  8326.2  617.61
#Mann= 19 ,-1 , 0
     4.1     .05       0     640     .16       0    1145     .05       0
  1185.3     .16       0  2005.6     .05       0  3308.3     .16       0
  3640.4     .12       0  3777.5     .16       0  4071.6     .12       0
  4579.7     .16       0  4928.7     .07       0  5008.7     .16       0
  5016.6     .12       0  5240.3     .16       0  5371.5     .05       0
  7253.9    .063       0  7394.8    .094       0  7708.4    .063       0
  8069.9    .094       0
Bank Sta=4928.7,5008.7
XS Rating Curve= 0 ,0
Exp/Cntr=0.3,0.1

Type RM Length L Ch R = 1 ,142025  ,3565,3565,3565
BEGIN DESCRIPTION:
Denton Creek 40.0
END DESCRIPTION:
XS GIS Cut Line= 3
      2359523.08      7064687.71      2360715.04      7059204.98
      2361167.86      7057076.11
#Sta/Elev= 30
   919.1  631.82    1056  629.92  1696.2  577.41  1839.9  571.06  2359.7   557.4
  4011.6  555.79  4496.2  556.24  4897.6  558.42  4918.1  549.58    4919  533.66
  4919.1  531.46    4999  533.66  5081.8  551.59  5235.2  556.13  5618.6  556.68
  6035.1  553.38  6081.4  553.72  6320.1  556.81    6361   536.4  6484.1   547.6
  6616.4  539.26  6657.7  555.82  6741.3  555.46  7444.6  573.22  7540.8   579.9
    7671  576.63  7968.6  574.99  8096.3  577.21  8489.7  586.88  8706.4  591.56
#Mann= 20 ,-1 , 0
   919.1     .16       0    1056     .05       0  1696.2     .16       0
  1839.9     .12       0  4011.6     .16       0  4496.2     .12       0
    4919     .07       0    4999     .16       0  5235.2     .12       0
  5618.6     .16       0  6035.1     .12       0  6081.4     .16       0
  6484.1     .12       0  6741.3     .16       0  7444.6    .063       0
  7540.8    .094       0    7671    .094       0  7968.6    .063       0
  8096.3    .094       0  8489.7    .063       0
#XS Ineff= 2 , 0
       0                    6160       0  591.36
Permanent Ineff=
       F       F
Bank Sta=4919,4999
XS Rating Curve= 0 ,0
Exp/Cntr=0.3,0.1

Type RM Length L Ch R = 1 ,138460  ,9716,9716,9716
BEGIN DESCRIPTION:
Denton Creek 39.0
END DESCRIPTION:
XS GIS Cut Line= 3
      2360806.07      7065532.58      2362706.38      7059260.02
      2362477.55       7057875.2
#Sta/Elev= 30
  -525.2  643.63  -218.1  638.89   -40.6  591.61   177.6  555.39     655  547.82
  1414.4  553.94  1604.9  553.92    1676  538.48    1771  554.46  3929.2  553.42
  4131.4  553.67  4373.7  553.21  4390.2  553.17  4762.9  555.09  4921.8  556.47
  4963.1  533.59  4985.8  532.89  4985.9  530.69  5065.9  532.89  5067.6  552.78
  5172.3  552.69  5743.2  548.06  5788.6  559.38  5858.3  551.35  5866.8  551.51
  6104.9  558.84  6140.4  567.24  6593.5  574.68  6981.5  568.41  7432.5  583.81
#Mann= 16 ,-1 , 0
  -525.2     .05       0   -40.6     .16       0     655     .12       0
  1414.4     .16       0    1771     .12       0  3929.2     .16       0
  4131.4     .12       0  4373.7     .16       0  4390.2     .12       0
  4762.9     .16       0  4985.8     .07       0  5065.9     .16       0
  5172.3     .16       0  5858.3     .12       0  5866.8     .16       0
  6981.5     .05       0
Bank Sta=4985.8,5065.9
XS Rating Curve= 0 ,0
Exp/Cntr=0.3,0.1

Type RM Length L Ch R = 1 ,128744  ,472,472,472
BEGIN DESCRIPTION:
Denton Creek236
END DESCRIPTION:
XS GIS Cut Line= 4
      2364468.82      7066708.61      2363803.78      7062991.07
      2362986.65      7059324.39      2362480.68      7057594.45
#Sta/Elev= 30
  2520.2  591.64  2711.8  572.69  2942.7  590.97  3067.4  561.46  3249.9  558.85
  3322.8  557.88  3465.4  554.58  3758.3  547.05    4040  548.85  4717.7   546.7
  4932.1  544.66  4950.5  529.94  4950.6  527.74  5031.3  529.94  5058.5  549.85
  5106.8   548.8  5222.6   549.2    6093   552.2  6757.6  552.18  7062.8  550.66
  7783.4  554.75  7834.7  537.09  7916.6  537.01  8019.1  553.84  9566.1  551.99
  9972.2  573.04 10720.5  568.21 10902.5  566.62 11116.9  568.54 11855.8  595.73
#Mann= 17 ,-1 , 0
  2520.2    .063       0  3249.9     .16       0  3322.8     .05       0
  3465.4     .16       0  3758.3     .12       0    4040     .16       0
  4717.7     .15       0  4950.5     .07       0  5031.3     .15       0
  5106.8     .16       0  5222.6     .05       0    6093     .16       0
  6757.6     .05       0  7062.8     .16       0 10720.5     .05       0
 10902.5     .16       0 11116.9     .05       0
Bank Sta=4950.5,5031.3
XS Rating Curve= 0 ,0
Exp/Cntr=0.3,0.1

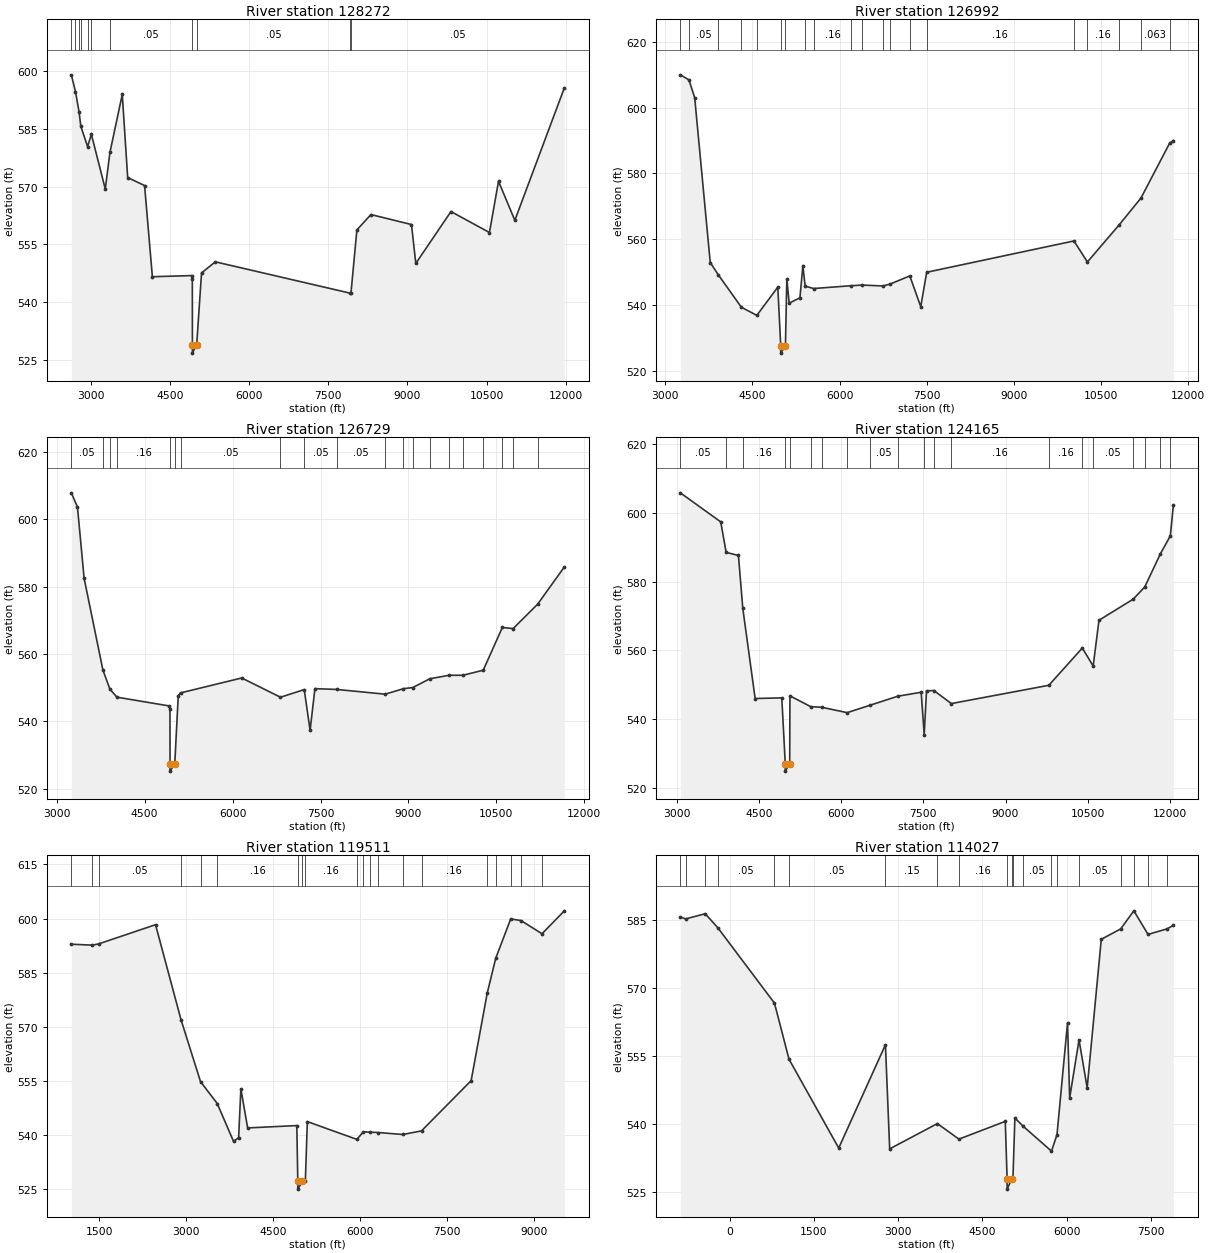
Type RM Length L Ch R = 1 ,128272  ,1280,1280,1280
BEGIN DESCRIPTION:
Denton Creek235
END DESCRIPTION:
XS GIS Cut Line= 5
      2364951.23       7066610.6      2364662.95      7065152.61
      2363964.95      7061429.96      2363509.21      7059346.57
      2362699.26       7057596.5
#Sta/Elev= 30
  2635.2  598.97  2714.2  594.61  2782.1  589.36  2814.5  585.65  2943.5  580.36
  3014.9  583.54    3278  569.36  3366.6  578.85  3599.8   593.9  3702.3  572.33
  4022.1  570.26  4169.9  546.62  4917.7  546.92  4926.2  545.91  4928.1  529.01
  4928.2  526.81  5008.9  529.01  5100.8  547.62    5362  550.48    7917  542.35
  7930.5  542.44    8042  558.76  8308.1  562.74  9075.9  560.15  9157.7  550.07
  9823.1  563.52 10552.1  558.08 10723.6  571.37 11032.6  561.24   11970  595.58
#Mann= 11 ,-1 , 0
  2635.2     .05       0  2714.2    .063       0  2782.1     .05       0
  2814.5    .063       0  2943.5     .05       0  3014.9    .063       0
  3366.6     .05       0  4928.1    .035       0  5008.9     .05       0
    7917     .16       0  7930.5     .05       0
Bank Sta=4928.1,5008.9
XS Rating Curve= 0 ,0
Exp/Cntr=0.3,0.1

Type RM Length L Ch R = 1 ,126992  ,263,263,263
BEGIN DESCRIPTION:
Denton Creek234
END DESCRIPTION:
XS GIS Cut Line= 5
      2365818.93       7065426.6      2365175.48      7062613.62
      2364737.25      7060894.04      2364462.78      7060085.52
      2362875.33      7057573.84
#Sta/Elev= 30
    3258  609.93  3405.8  608.41  3505.1  603.01    3773   552.9  3910.4   549.2
  4308.7  539.32  4574.8  536.84  4935.6  545.42  4986.2  527.57  4986.3  525.37
    5067  527.57  5090.7  547.81  5131.8  540.55  5316.4  542.18  5367.7  551.99
  5405.8  545.73  5552.2     545  6197.8  545.85  6386.4  546.05  6744.5  545.78
  6866.6  546.34  7207.5  548.83    7396  539.49  7498.2  549.94 10032.8  559.46
 10263.8  553.06 10807.2  564.27 11185.1  572.47 11678.6  589.13 11743.3  589.96
#Mann= 20 ,-1 , 0
    3258     .05       0  3405.8     .05       0  3910.4     .16       0
  4308.7     .15       0  4574.8     .16       0  4986.2     .07       0
    5067     .16       0  5405.8     .05       0  5552.2     .16       0
  6197.8     .05       0  6386.4     .16       0  6744.5     .05       0
  6866.6     .16       0  7207.5     .05       0  7498.2     .16       0
 10032.8     .12       0 10263.8     .16       0 10807.2     .05       0
 11185.1    .063       0 11678.6     .05       0
Bank Sta=4986.2,5067
XS Rating Curve= 0 ,0
Exp/Cntr=0.3,0.1

Type RM Length L Ch R = 1 ,126729  ,2564,2564,2564
BEGIN DESCRIPTION:
Denton Creek233
END DESCRIPTION:
XS GIS Cut Line= 5
      2366082.34      7065351.91      2365249.42      7061939.25
      2364832.42      7060271.87        2364492.      7059488.51
      2363291.18      7057499.83
#Sta/Elev= 30
    3250  607.83  3354.9  603.61  3468.1  582.47  3788.5  555.23  3907.2  549.58
  4027.3  547.15  4919.5  544.55  4932.5   543.6  4933.8  527.39  4933.9  525.19
  5014.6  527.39  5073.9  547.62  5112.7  548.42  6156.5  552.85  6817.4  547.13
  7222.8  549.41  7322.4  537.29  7404.9  549.68  7773.4  549.45  8602.3  548.04
  8915.1  549.67  9072.3     550  9364.2  552.62  9695.3  553.66    9928  553.65
 10275.4  555.16 10601.3  567.84 10785.2  567.52 11203.5  574.77 11658.8  585.81
#Mann= 20 ,-1 , 0
    3250     .05       0  3788.5     .16       0  3907.2     .05       0
  4027.3     .16       0  4933.8     .07       0  5014.6     .15       0
  5112.7     .05       0  6817.4     .05       0  7222.8     .05       0
  7773.4     .05       0  8602.3     .16       0  8915.1     .16       0
  9072.3     .05       0  9364.2     .16       0  9695.3     .16       0
    9928     .05       0 10275.4     .05       0 10601.3     .16       0
 10785.2     .16       0 11203.5     .05       0
Bank Sta=4933.8,5014.6
XS Rating Curve= 0 ,0
Exp/Cntr=0.3,0.1

Type RM Length L Ch R = 1 ,124165  ,4654,4654,4654
BEGIN DESCRIPTION:
Denton Creek 36.0
END DESCRIPTION:
XS GIS Cut Line= 3
      2367945.91      7065011.39      2366879.01      7062842.44
      2363734.46      7057064.34
#Sta/Elev= 30
  3065.9  605.86    3803  597.42  3902.1  588.54  4126.2  587.64  4205.8  572.24
  4431.1  546.03  4917.4  546.22  4980.6  527.11  4980.7  524.91  5061.4  527.11
  5065.9   546.8  5445.9  543.66  5646.6  543.48  6109.3  541.92  6520.9  544.04
    7037  546.71  7460.6  547.85  7515.4  535.55  7557.9  548.26  7691.5  548.35
  8010.9  544.56  9789.7  549.88 10400.7  560.72 10598.7  555.47 10704.2  568.79
 11328.8  574.93 11539.3  578.47 11826.2  588.16 12006.2  593.33 12061.4  602.19
#Mann= 20 ,-1 , 0
  3065.9     .05       0  3902.1     .05       0  4205.8     .16       0
  4980.6     .07       0  5061.4     .15       0  5445.9     .05       0
  5646.6     .16       0  6109.3     .16       0  6520.9     .05       0
    7037     .16       0  7515.4     .05       0  7691.5     .16       0
  8010.9     .16       0  9789.7     .16       0 10400.7     .05       0
 10598.7     .05       0 11328.8    .063       0 11539.3    .094       0
 11826.2     .05       0 12006.2    .063       0
Bank Sta=4980.6,5061.4
XS Rating Curve= 0 ,0
Exp/Cntr=0.3,0.1

Type RM Length L Ch R = 1 ,119511  ,5484,5484,5484
BEGIN DESCRIPTION:
Denton Creek 35.0
END DESCRIPTION:
XS GIS Cut Line= 3
      2368952.73       7063205.8       2367474.1      7058953.93
      2365659.01      7055374.13
#Sta/Elev= 30
  1015.8  592.89  1379.6  592.64  1490.1  592.99  2470.2   598.3  2910.7  571.97
  3247.3  554.84  3536.6  548.76  3817.6  538.29  3905.6  539.33  3944.1  552.87
  4061.1  542.02  4910.8  542.67  4927.4  527.27  4927.5  525.07  5008.2  527.27
  5057.9  527.41  5092.2  543.77  5948.1  538.84  6059.2  540.94    6180  540.85
  6312.3  540.75  6741.1   540.2  7064.1   541.2  7921.2  555.11  8198.2  579.27
  8345.5  588.97  8604.7   599.9  8782.5  599.44  9145.1  595.79  9531.1  602.14
#Mann= 20 ,-1 , 0
  1015.8     .05       0  1379.6    .063       0  1490.1     .05       0
  2910.7     .16       0  3247.3     .05       0  3536.6     .16       0
  4927.4     .07       0  5008.2     .16       0  5057.9     .16       0
  5948.1     .15       0  6059.2     .16       0    6180     .05       0
  6312.3     .16       0  6741.1     .15       0  7064.1     .16       0
  8198.2    .094       0  8345.5    .094       0  8604.7    .125       0
  8782.5    .094       0  9145.1    .094       0
Bank Sta=4927.4,5008.2
XS Rating Curve= 0 ,0
Exp/Cntr=0.3,0.1

Type RM Length L Ch R = 1 ,114027  ,4699,4699,4699
BEGIN DESCRIPTION:
Denton Creek 34.0
END DESCRIPTION:
XS GIS Cut Line= 3
      2369394.06      7062899.65      2370443.19      7057718.22
      2370814.68      7054243.79
#Sta/Elev= 30
    -881  585.74  -786.8   585.3  -437.4  586.45  -213.2  583.35   795.5  566.72
    1055  554.32  1940.1  534.72    2772  557.52  2847.7  534.54  3697.1  540.12
    4081  536.69  4906.6  540.61  4939.4  527.85  4939.5  525.65  5020.2  527.85
  5042.5  527.87  5077.6  541.35  5222.5  539.56  5729.4  534.04  5827.5  537.68
  6015.1  562.36  6053.1  545.76  6220.1  558.59  6364.9  548.03  6616.3   580.8
  6961.4   583.1  7196.2  587.09  7449.4  581.88  7789.9  583.12  7899.8  583.89
#Mann= 20 ,-1 , 0
    -881     .05       0  -786.8     .05       0  -437.4     .05       0
  -213.2     .05       0   795.5     .16       0    1055     .05       0
    2772     .15       0  3697.1     .16       0    4081     .16       0
  4939.4    .033       0  5020.2     .15       0  5042.5     .16       0
  5222.5     .05       0  5729.4     .15       0  5827.5     .16       0
  6220.1     .05       0  6961.4     .05       0  7196.2    .063       0
  7449.4    .063       0  7789.9    .094       0
Bank Sta=4939.4,5020.2
XS Rating Curve= 0 ,0
Exp/Cntr=0.3,0.1

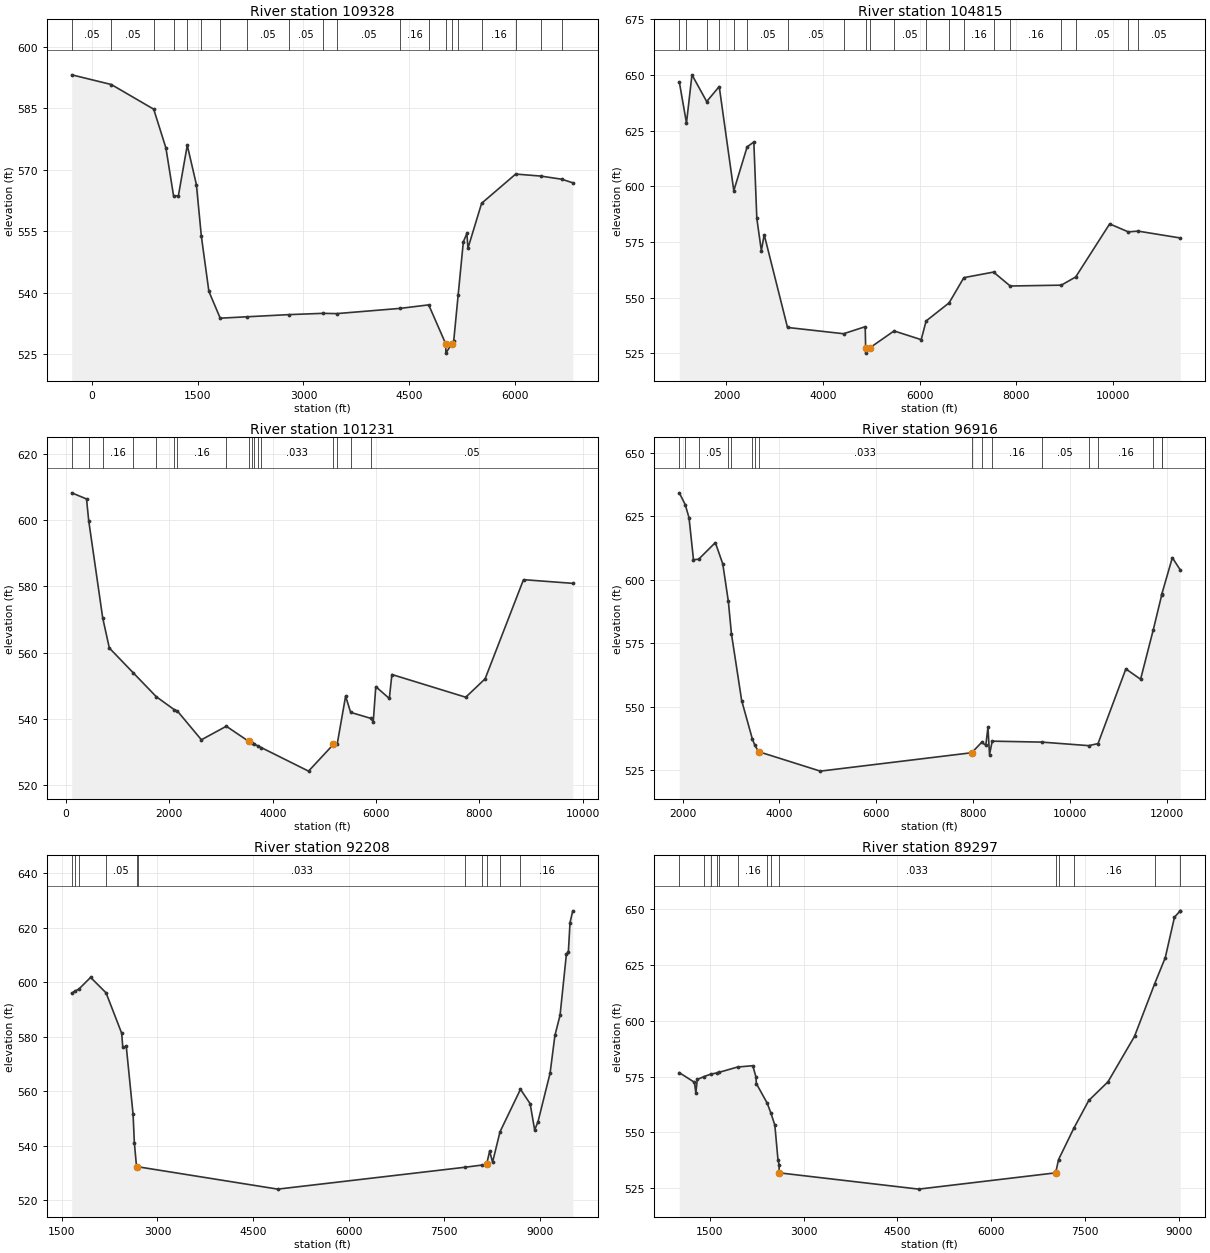
Type RM Length L Ch R = 1 ,109328  ,4513,4513,4513
BEGIN DESCRIPTION:
Denton Creek 33.0
END DESCRIPTION:
XS GIS Cut Line= 4
      2369677.44      7062981.08      2371829.36      7060592.53
      2373432.41      7058379.01      2373534.14      7057239.13
#Sta/Elev= 30
  -280.7  593.18   279.6  590.82   879.9   584.8  1052.7  575.34  1160.8  563.69
    1229  563.67    1355     576    1484  566.41  1554.5  553.78    1661  540.36
  1821.4  533.83  2206.3  534.18  2789.9   534.7  3271.1  535.01  3472.5  534.95
  4372.4  536.23  4772.2  537.08  5015.1  527.51  5015.2  525.31    5096  527.51
  5126.7  528.28  5189.5  539.51  5262.8  552.47  5313.1  554.51  5327.8  550.88
  5521.4  561.85  6003.7  568.98    6358  568.49  6655.7  567.72  6811.7  566.85
#Mann= 20 ,-1 , 0
  -280.7     .05       0   279.6     .05       0   879.9     .16       0
  1160.8     .16       0    1355     .05       0  1554.5     .16       0
  1821.4     .15       0  2206.3     .05       0  2789.9     .05       0
  3271.1     .15       0  3472.5     .05       0  4372.4     .16       0
  4772.2     .15       0  5015.1    .033       0    5096     .05       0
  5189.5     .05       0  5521.4     .16       0  6003.7     .05       0
    6358     .16       0  6655.7     .05       0
Bank Sta=5015.1,5096
XS Rating Curve= 0 ,0
Exp/Cntr=0.3,0.1

Type RM Length L Ch R = 1 ,104815  ,3584,3584,3584
BEGIN DESCRIPTION:
Denton Creek 32.0
END DESCRIPTION:
XS GIS Cut Line= 4
      2374679.34      7065329.39      2373914.91      7061761.52
      2373860.15      7057423.41      2372329.72      7055586.12
#Sta/Elev= 30
  1023.1  646.89  1171.5  628.45  1285.3  650.08  1590.1  638.09    1850  644.82
  2151.7  598.05  2428.2  617.75  2566.8  619.91  2628.5  585.63  2722.3  571.13
  2781.5   578.3  3264.2  536.65  4425.8  533.83  4873.5  536.99  4882.7  527.42
  4882.8  525.12  4964.2  527.42  5471.1  535.08  6033.6  531.17    6135  539.56
  6611.1  547.68  6917.1  559.01  7531.5  561.51  7877.4  555.26  8935.9  555.64
  9233.6  559.32  9937.1  583.14 10324.4  579.56 10524.1  579.91 11401.6  576.82
#Mann= 20 ,-1 , 0
  1023.1     .05       0  1171.5     .16       0  1590.1     .05       0
    1850     .16       0  2151.7     .16       0  2428.2     .05       0
  3264.2     .05       0  4425.8     .15       0  4882.7    .033       0
  4964.2     .05       0  5471.1     .05       0    6135     .16       0
  6611.1     .05       0  6917.1     .16       0  7531.5     .05       0
  7877.4     .16       0  8935.9     .05       0  9233.6     .05       0
 10324.4     .16       0 10524.1     .05       0
Bank Sta=4882.7,4964.2
XS Rating Curve= 0 ,0
Exp/Cntr=0.3,0.1

Type RM Length L Ch R = 1 ,101231  ,4315,4315,4315
BEGIN DESCRIPTION:
Denton Creek 31.0
END DESCRIPTION:
XS GIS Cut Line= 3
      2378687.69      7063198.53      2375726.75      7058615.73
      2372657.05      7055694.56
#Sta/Elev= 30
   111.5  608.23   398.1  606.38     440  599.87   710.9  570.51   839.4  561.43
  1303.7  553.92  1747.4  546.75  2096.6  542.82  2156.2  542.42  2620.1  533.75
  3102.6  537.84  3534.4  533.29  3593.9  532.83  3645.9  532.43  3712.2  531.92
  3781.5  531.38  4693.4   524.3  5173.5  532.35  5249.2  532.61  5410.3   546.9
  5507.9  542.02  5896.9  540.22    5945  539.19  5994.3  549.78    6256  546.21
  6305.8  553.44  7734.4  546.59  8109.3  552.14  8851.9  582.04  9805.1  580.93
#Mann= 17 ,-1 , 0
   111.5     .16       0     440     .05       0   710.9     .16       0
  1303.7     .05       0  1747.4     .16       0  2096.6     .05       0
  2156.2     .16       0  3102.6     .05       0  3534.4    .033       0
  3593.9     .15       0  3645.9    .033       0  3712.2     .15       0
  3781.5    .033       0  5173.5     .05       0  5249.2     .05       0
  5507.9     .16       0  5896.9     .05       0
Bank Sta=3534.4,5173.5
XS Rating Curve= 0 ,0
Exp/Cntr=0.3,0.1

Type RM Length L Ch R = 1 ,96916   ,4708,4708,4708
BEGIN DESCRIPTION:
Denton Creek 30.0
END DESCRIPTION:
XS GIS Cut Line= 3
      2380600.32      7060755.56        2380079.        7058410.
      2376937.61      7051125.04
#Sta/Elev= 30
  1933.3  634.29  2055.9  629.61  2133.6  624.46  2225.8  607.91  2332.6  608.11
  2676.6  614.66  2830.2  606.24    2945  591.46  3008.2  578.77  3219.5  552.38
    3441  537.15  3492.7  534.69  3570.4   532.2  4841.6  524.53  7966.5  531.79
  8167.3  535.83  8256.5  534.81  8300.1  541.77  8332.8  531.04  8387.8  536.35
  9409.7  535.98 10379.1  534.58 10571.1  535.39   11145  564.84   11449  560.77
 11711.4  580.33 11886.7  594.17   11888  594.43   12104  608.72 12269.5  603.82
#Mann= 17 ,-1 , 0
  1933.3     .05       0  2055.9    .063       0  2332.6     .05       0
    2945     .16       0  3008.2     .05       0    3441     .15       0
  3492.7     .05       0  3570.4    .033       0  7966.5     .05       0
  8167.3     .05       0  8387.8     .16       0  9409.7     .05       0
 10379.1     .15       0 10571.1     .16       0 11711.4     .05       0
 11886.7     .16       0   11888    .063       0
Bank Sta=3570.4,7966.5
XS Rating Curve= 0 ,0
Exp/Cntr=0.3,0.1

Type RM Length L Ch R = 1 ,92208   ,2911,2911,2911
BEGIN DESCRIPTION:
Denton Creek 28.0
END DESCRIPTION:
XS GIS Cut Line= 3
      2382830.86      7057433.71        2382379.        7054160.
      2381223.17       7049753.1
#Sta/Elev= 30
  1655.3  595.95  1708.4  596.76    1765   597.4  1951.8  601.74  2194.3  596.06
  2439.1  581.27  2456.5  576.11    2511  576.45  2618.1  551.48  2638.2  541.02
  2672.1  532.37  2689.8   532.3  4887.5  524.09  7830.7  532.13    8090  532.91
  8163.6  533.13  8211.7  538.01  8257.9  533.98  8374.8  545.13  8695.5  560.71
  8847.5  555.42    8918  545.78  8971.3  548.88  9160.3  566.64  9235.9  580.45
  9316.6  587.86  9415.8   610.2  9446.8  611.06    9473  621.84    9516  626.15
#Mann= 11 ,-1 , 0
  1655.3     .16       0  1708.4     .05       0    1765     .16       0
  2194.3     .05       0  2672.1    .033       0  2689.8    .033       0
  7830.7     .15       0    8090     .16       0  8163.6     .05       0
  8374.8     .05       0  8695.5     .16       0
Bank Sta=2672.1,8163.6
XS Rating Curve= 0 ,0
Exp/Cntr=0.3,0.1

Type RM Length L Ch R = 1 ,89297   ,3416,3416,3416
BEGIN DESCRIPTION:
Denton Creek 27.0
END DESCRIPTION:
XS GIS Cut Line= 3
      2386476.88      7056364.07        2384779.        7052760.
        2382779.      7049260.01
#Sta/Elev= 30
    1012  576.76  1253.8  572.44  1276.6  567.66  1299.4  573.69  1403.8  574.95
  1513.2  576.09  1622.7  576.68  1652.4  576.94  1943.9  579.28  2187.3  579.88
  2238.4  574.82    2244  571.87  2418.1  563.06  2478.6  558.48  2540.2  553.19
  2591.3  537.35  2608.3  535.51    2610  531.79  4841.6  524.48    7032  531.79
  7078.5  537.74  7323.5  551.85  7562.2  564.28  7868.9  572.63  8293.6  593.05
  8617.2  616.75  8785.2  628.32  8932.8  646.54  9015.6   649.1  9027.1  649.39
#Mann= 14 ,-1 , 0
    1012     .05       0  1403.8    .063       0  1513.2     .05       0
  1622.7     .16       0  1652.4     .05       0  1943.9     .16       0
  2418.1    .063       0  2478.6     .05       0    2610    .033       0
    7032     .05       0  7078.5     .05       0  7323.5     .16       0
  8617.2     .05       0  9015.6    .063       0
Bank Sta=2610,7032
XS Rating Curve= 0 ,0
Exp/Cntr=0.3,0.1

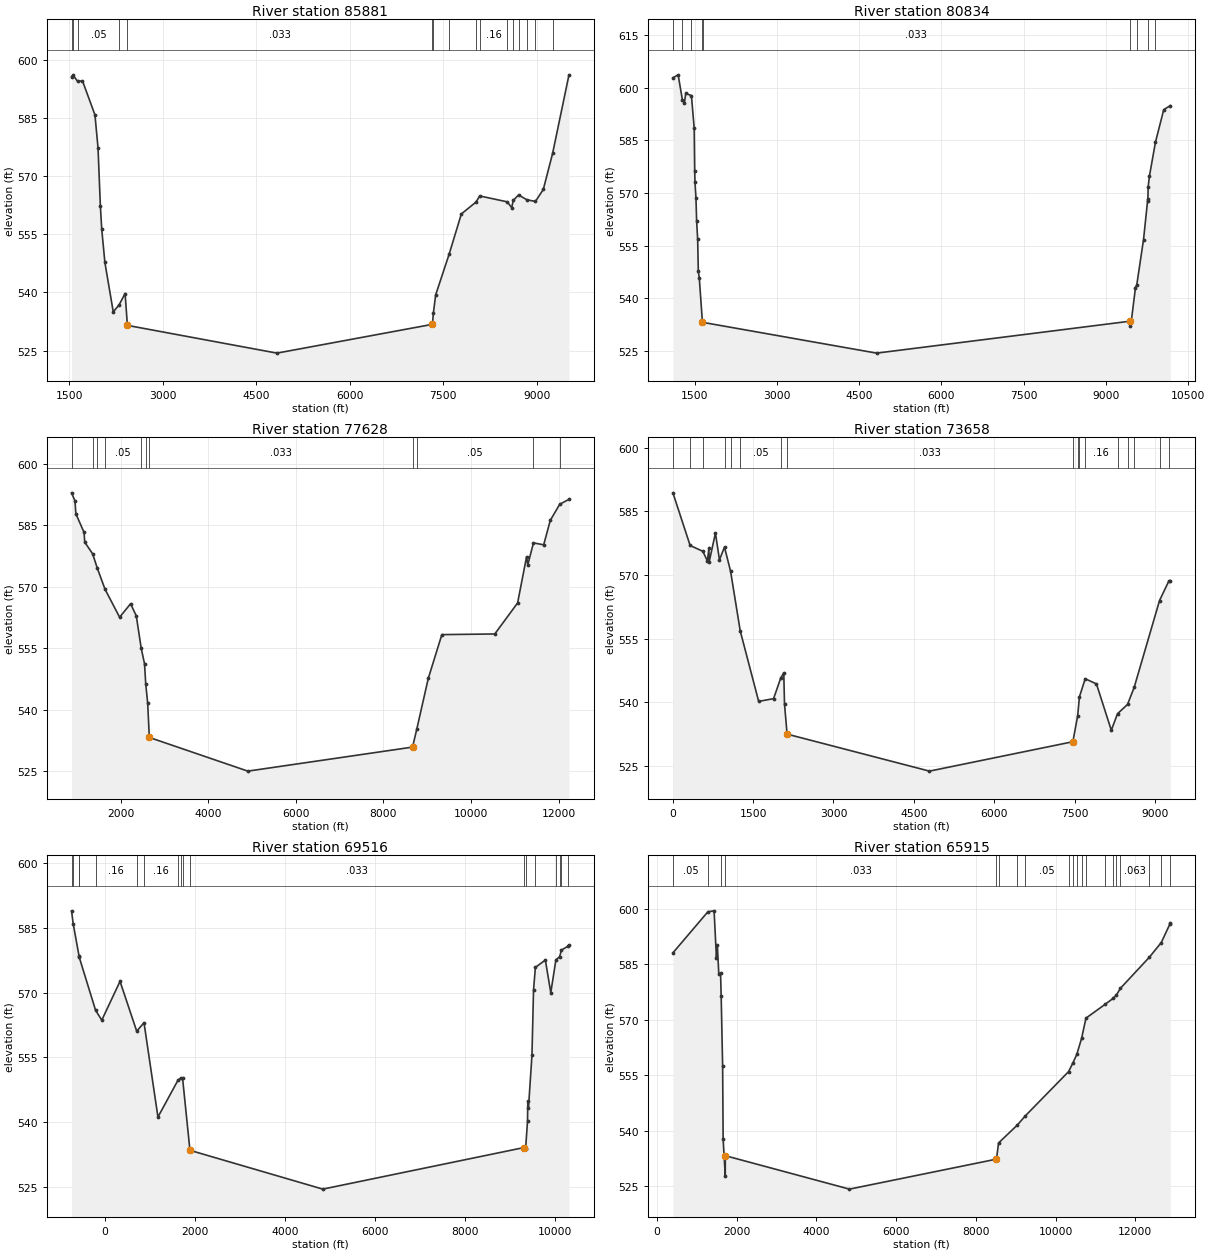
Type RM Length L Ch R = 1 ,85881   ,5047,5047,5047
BEGIN DESCRIPTION:
Denton Creek 25.0
END DESCRIPTION:
XS GIS Cut Line= 3
      2389477.98      7054429.22       2386271.3      7048595.56
      2385079.03      7048010.02
#Sta/Elev= 30
  1534.7  595.63  1558.3   596.1  1633.3  594.42  1709.9   594.6  1910.4  585.81
  1959.9   577.3  1997.8  562.19  2019.6  556.27  2070.1  547.73  2204.3  534.98
  2297.7  536.78  2394.7  539.72  2431.2   531.5  4831.7  524.34  7327.7  531.77
  7343.3  534.66  7379.2  539.33  7594.7   549.8  7792.2  560.25  8025.9  563.29
  8087.5  564.89  8529.3  563.37    8601  561.85  8623.9  563.73    8711  565.15
  8841.9  563.92  8981.1  563.47  9107.7  566.57  9257.4  575.89  9519.9  596.14
#Mann= 16 ,-1 , 0
  1534.7     .05       0  1558.3     .16       0  1633.3     .05       0
  2297.7     .05       0  2431.2    .033       0  7327.7     .05       0
  7343.3     .05       0  7594.7     .16       0  8025.9     .05       0
  8087.5     .16       0  8529.3     .05       0  8623.9     .16       0
    8711     .05       0  8841.9     .16       0  8981.1     .05       0
  9257.4     .16       0
Bank Sta=2431.2,7327.7
XS Rating Curve= 0 ,0
Exp/Cntr=0.3,0.1

Type RM Length L Ch R = 1 ,80834   ,3206,3206,3206
BEGIN DESCRIPTION:
Denton Creek 24.0
END DESCRIPTION:
XS GIS Cut Line= 3
      2393250.05      7052141.24        2391829.        7048510.
      2389109.95      7044114.17
#Sta/Elev= 30
  1106.2  602.87    1202  603.71  1280.5  596.41  1315.9  595.73  1340.4  598.42
    1444  597.78  1494.1   588.5  1503.2  576.24  1508.6  573.13  1526.3  568.62
  1538.4  562.12  1557.5  556.83  1569.3  547.73  1587.3  545.77  1644.1   533.2
    1646  533.19  4819.4  524.41  9435.1   533.5  9438.5  532.23  9465.6  533.95
  9538.9  543.11  9562.1  543.84  9685.5  556.78  9759.3  567.81  9764.7  568.37
  9770.6  571.86  9791.8  574.76  9902.9  584.53 10054.2   593.8 10174.4  594.94
#Mann= 9 ,-1 , 0
  1106.2     .05       0  1280.5    .063       0    1444     .05       0
  1644.1    .033       0    1646    .033       0  9435.1     .05       0
  9562.1     .05       0  9759.3     .16       0  9902.9     .05       0
Bank Sta=1644.1,9435.1
XS Rating Curve= 0 ,0
Exp/Cntr=0.3,0.1

Type RM Length L Ch R = 1 ,77628   ,3970,3970,3970
BEGIN DESCRIPTION:
Denton Creek 23.0
END DESCRIPTION:
XS GIS Cut Line= 5
      2394538.07      7050827.89      2395414.63      7049585.27
       2394674.3      7047043.42      2392877.88      7043253.18
      2390151.11      7042014.67
#Sta/Elev= 30
   878.1  592.91   956.4  590.95   977.3  587.79  1164.5  583.24  1179.3  580.87
  1360.7  578.02  1463.1  574.62  1643.4  569.37  1976.1  562.56    2226  565.86
  2356.3  562.89  2469.6  554.96  2544.5  551.21  2572.1  546.28  2616.7  541.56
  2653.9  533.24  4902.9  525.02  8663.5  530.88  8762.9  535.37  9022.8  547.63
  9332.9  558.32 10541.5  558.48 11062.6  566.05 11266.6  577.28 11295.2  575.36
 11424.8   580.7 11657.8  580.23 11809.5  586.21 12024.8  590.13 12235.5  591.32
#Mann= 11 ,-1 , 0
   878.1    .063       0  1360.7     .05       0  1463.1     .16       0
  1643.4     .05       0  2469.6     .16       0  2572.1     .05       0
  2653.9    .033       0  8663.5     .05       0  8762.9     .05       0
 11424.8    .094       0 12024.8     .05       0
Bank Sta=2653.9,8663.5
XS Rating Curve= 0 ,0
Exp/Cntr=0.3,0.1

Type RM Length L Ch R = 1 ,73658   ,4142,4142,4142
BEGIN DESCRIPTION:
Denton Creek 22.0
END DESCRIPTION:
XS GIS Cut Line= 5
       2400579.2      7050253.41      2400349.76      7049494.15
      2400108.31      7049283.42      2398104.77      7045842.31
       2396581.1      7041953.58
#Sta/Elev= 30
     6.8  589.34   327.8  576.95   564.1  575.58   649.9  573.31   677.7  576.25
   682.9  573.11   799.5  579.86   874.3  573.59   968.5  576.57    1082  570.86
  1261.9  556.83  1605.3  540.26  1883.3  540.91  2018.7  545.84  2073.3  546.95
  2086.8  539.63    2135  532.56  4788.5  523.85  7461.6  530.77  7551.3  536.87
    7584  541.34    7692  545.59  7901.5  544.37  8178.2  533.47    8294  537.36
  8480.5  539.54  8604.8  543.57  9077.5     564  9248.9  568.54  9278.9  568.65
#Mann= 17 ,-1 , 0
     6.8     .16       0   327.8    .063       0   564.1     .16       0
   968.5     .05       0    1082     .16       0  1261.9     .05       0
  2018.7     .05       0    2135    .033       0  7461.6     .05       0
  7551.3     .05       0    7584     .05       0    7692     .16       0
    8294     .05       0  8480.5     .16       0  8604.8     .05       0
  9077.5     .16       0  9248.9     .05       0
Bank Sta=2135,7461.6
XS Rating Curve= 0 ,0
Exp/Cntr=0.3,0.1

Type RM Length L Ch R = 1 ,69516   ,3601,3601,3601
BEGIN DESCRIPTION:
Denton Creek 20.0
END DESCRIPTION:
XS GIS Cut Line= 5
      2405098.74        7048237.      2404593.52      7048122.59
      2403888.43      7047264.46        2401679.        7043760.
      2398274.09      7039715.06
#Sta/Elev= 30
  -745.2  588.97    -709  585.99    -580   578.6  -577.8  578.34    -210  565.88
   -72.7  563.63   332.7  572.62   703.6  561.06   865.9  563.04  1175.7  541.16
  1623.9  549.75  1681.6   550.2    1724   550.1    1887  533.45  4840.7  524.45
  9319.1   534.1  9348.5   533.7  9391.5   540.2    9398  544.84  9412.3  543.18
  9490.4  555.49  9525.5  570.65  9566.9  575.86  9788.2  577.56  9909.1     570
 10021.9  577.55 10105.4  578.36 10146.7  579.87 10282.8  580.72 10313.5     581
#Mann= 18 ,-1 , 0
  -745.2     .16       0    -709     .05       0    -580     .16       0
  -577.8     .05       0    -210     .16       0   703.6     .05       0
   865.9     .16       0  1623.9     .05       0  1681.6     .16       0
    1724    .063       0    1887    .033       0  9319.1    .063       0
  9348.5     .05       0  9566.9    .063       0 10021.9     .05       0
 10105.4     .16       0 10146.7     .05       0 10282.8    .063       0
Bank Sta=1887,9319.1
XS Rating Curve= 0 ,0
Exp/Cntr=0.3,0.1

Type RM Length L Ch R = 1 ,65915   ,4795,4795,4795
BEGIN DESCRIPTION:
Denton Creek 18.0
END DESCRIPTION:
XS GIS Cut Line= 3
      2407050.56      7046326.53      2402860.69      7038893.49
       2401245.5      7035293.52
#Sta/Elev= 30
   402.6  588.07  1279.6  599.17  1435.8  599.43  1495.1  586.55  1516.8  590.16
  1554.3  582.22  1597.7  582.59  1613.2  576.42  1649.9   557.4  1662.6  537.71
  1716.2   527.7  1716.9  533.23  4831.1  524.19  8519.1   532.3  8572.1  536.68
  9037.4  541.46    9244  544.01 10328.4  555.97 10436.8  558.32 10534.4  560.63
 10653.7  564.93 10763.6  570.41 11241.5  574.13 11451.2  575.81 11521.1  576.56
 11629.6   578.5   12356  586.91 12652.1  590.84 12871.4  595.89 12880.9  596.09
#Mann= 20 ,-1 , 0
   402.6     .05       0  1279.6     .16       0  1613.2     .05       0
  1716.9    .033       0  8519.1     .05       0  8572.1     .05       0
  9037.4     .16       0    9244     .05       0 10328.4    .063       0
 10436.8    .094       0 10534.4     .16       0 10653.7    .063       0
 10763.6     .16       0 11241.5     .05       0 11451.2     .05       0
 11521.1     .16       0 11629.6    .063       0   12356     .05       0
 12652.1    .063       0 12871.4     .05       0
Bank Sta=1716.9,8519.1
XS Rating Curve= 0 ,0
Exp/Cntr=0.3,0.1

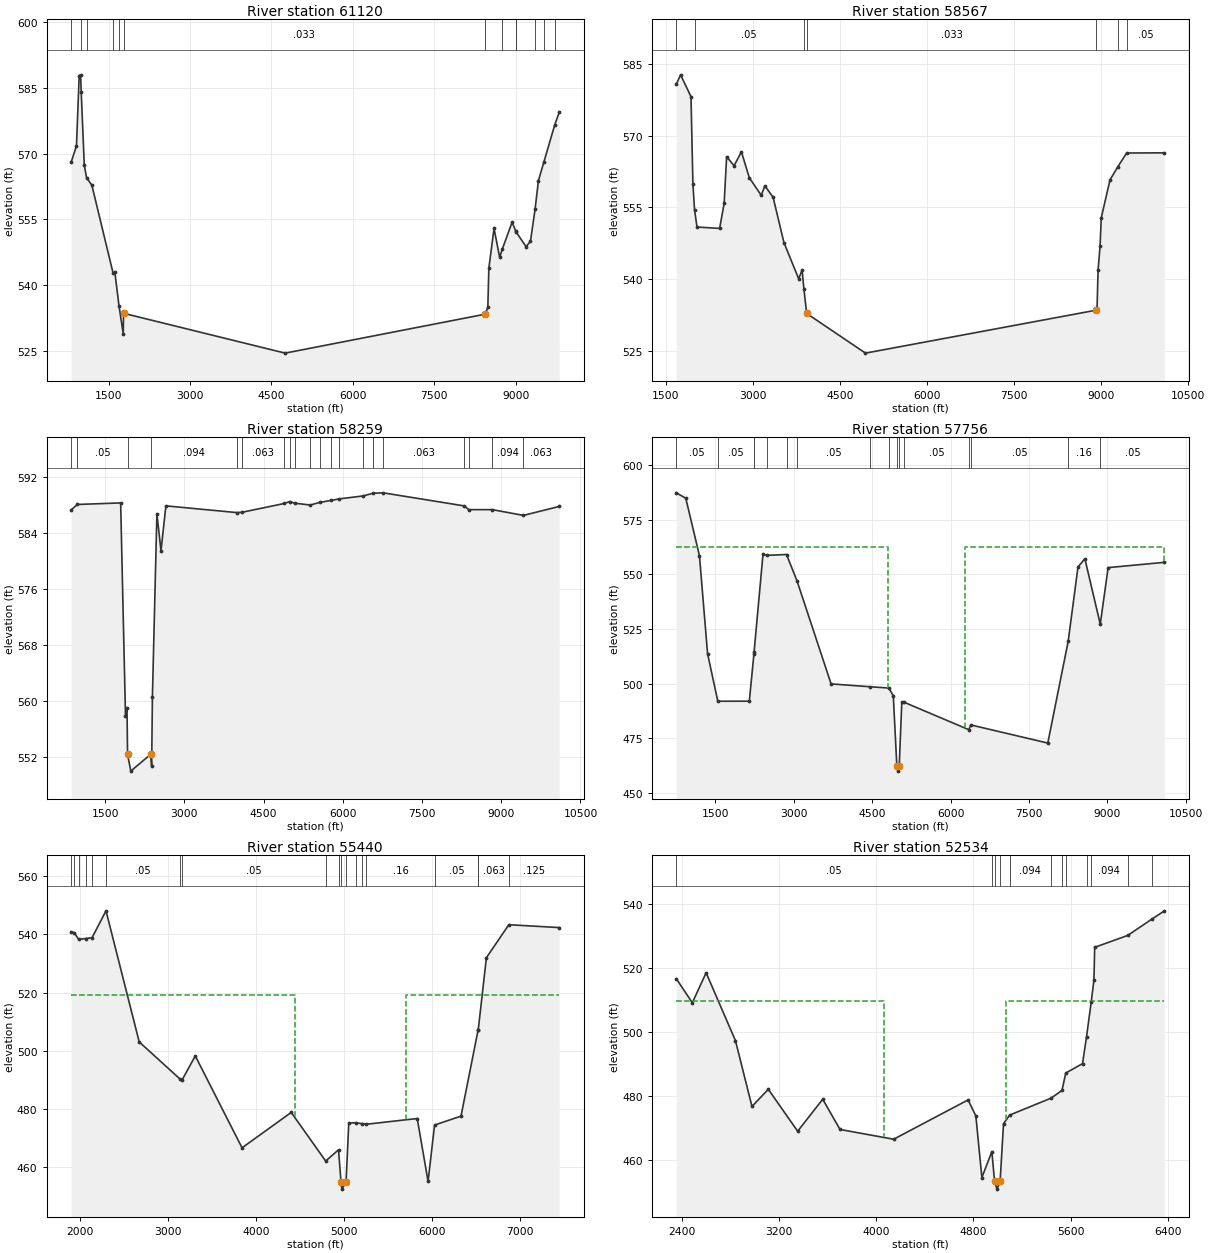
Type RM Length L Ch R = 1 ,61120   ,2553,2553,2553
BEGIN DESCRIPTION:
Denton Creek 17.0
END DESCRIPTION:
XS GIS Cut Line= 3
      2408970.93       7043547.7        2408329.        7039410.
      2407076.54      7034769.03
#Sta/Elev= 30
   808.9  568.01   907.8  571.73   958.4   587.8   984.1  587.97   995.5  584.08
  1052.2  567.36  1094.9  564.49  1191.1  562.83  1581.4  542.83  1616.1  542.91
  1691.2  535.35  1770.2  528.88  1776.2   533.6  4752.6  524.52  8437.4   533.4
  8486.7  534.97  8505.1  543.88  8600.6  552.96  8704.6  546.33  8750.9  548.16
  8933.7  554.37  9001.5   552.3  9012.3  552.06    9191  548.78  9272.1  550.06
  9356.7  557.32  9418.9  563.86  9516.7  567.99  9720.4  576.62  9803.1  579.46
#Mann= 13 ,-1 , 0
   808.9     .05       0   995.5    .094       0  1094.9     .05       0
  1581.4    .094       0  1691.2     .05       0  1776.2    .033       0
  8437.4     .05       0  8750.9     .16       0  9001.5     .05       0
  9012.3     .16       0  9356.7     .05       0  9516.7    .063       0
  9720.4     .05       0
Bank Sta=1776.2,8437.4
XS Rating Curve= 0 ,0
Exp/Cntr=0.3,0.1

Type RM Length L Ch R = 1 ,58567   ,308,308,308
BEGIN DESCRIPTION:
Denton Creek232
END DESCRIPTION:
XS GIS Cut Line= 6
      2409422.24      7042697.73      2409589.34      7042506.82
      2410532.16      7041439.28      2410697.45      7040880.53
      2411396.08      7035924.15      2411481.75      7034783.81
#Sta/Elev= 30
  1681.6  580.81  1755.9  582.79  1935.3  578.21  1968.5  559.85  1996.3  554.54
  2038.7   550.9  2428.6  550.62  2506.4  555.86    2549  565.65  2677.1  563.74
  2804.2  566.67  2938.9  561.25  3144.7  557.56  3208.2  559.53  3349.6  557.14
  3536.1  547.65  3790.3  540.06    3849  541.93  3879.7     538  3928.3   532.8
  4940.5  524.49  8915.7  533.49  8929.7  533.98  8947.2  541.91  8981.9  546.95
  9001.9  552.83  9152.4  560.77  9288.7  563.56  9439.2  566.41 10091.2  566.45
#Mann= 7 ,-1 , 0
  1681.6    .063       0  1996.3     .05       0  3879.7     .05       0
  3928.3    .033       0  8915.7     .05       0  9288.7    .063       0
  9439.2     .05       0
Bank Sta=3928.3,8915.7
XS Rating Curve= 0 ,0
Exp/Cntr=0.3,0.1

Type RM Length L Ch R = 1 ,58259   ,503,503,503
BEGIN DESCRIPTION:
Denton Creek 16.0
END DESCRIPTION:
XS GIS Cut Line= 6
      2409013.34      7043301.03      2410138.49      7042120.27
      2410634.63      7041524.21      2411029.74      7040731.52
      2411692.48      7036023.81      2411708.95      7034827.22
#Sta/Elev= 30
     856  587.26   974.8  588.05  1794.5  588.27  1886.3   557.9  1914.6  559.06
  1925.3   552.4  1986.9     550  2362.7   552.4  2381.4  550.71  2395.6  560.52
  2480.5  586.71  2558.5  581.45    2651  587.85  3994.8  586.89  4088.4  586.93
  4893.6  588.19  4992.1  588.46  5090.7  588.23  5385.9  587.97  5561.5  588.34
  5779.7  588.63  5937.4  588.85  6389.9  589.27  6567.3  589.64  6764.2  589.71
  8301.8  587.84  8384.3  587.31  8831.8  587.31  9419.1  586.49 10099.1  587.77
#Mann= 20 ,-1 , 0
     856     .05       0   974.8     .05       0  1925.3    .063       0
  2362.7    .094       0  3994.8     .05       0  4088.4    .063       0
  4893.6     .05       0  4992.1    .063       0  5090.7    .063       0
  5385.9     .05       0  5561.5     .05       0  5779.7    .063       0
  5937.4    .063       0  6389.9     .05       0  6567.3    .094       0
  6764.2    .063       0  8301.8    .094       0  8384.3    .063       0
  8831.8    .094       0  9419.1    .063       0
Bank Sta=1925.3,2362.7
XS Rating Curve= 0 ,0
Exp/Cntr=0.3,0.1

Type RM Length L Ch R = 1 ,57756   ,2316,2316,2316
BEGIN DESCRIPTION:
Denton Creek231
END DESCRIPTION:
XS GIS Cut Line= 5
       2409575.7      7043503.97       2411139.3      7041863.18
      2411429.17       7041160.7      2412244.48      7036642.28
      2411970.25      7034934.89
#Sta/Elev= 30
   749.8   587.4   931.9  584.93  1193.6  558.61  1349.2  513.72  1544.9  491.94
  2148.5  491.96  2236.2  513.45    2239  514.35  2410.2  559.15    2479  558.77
  2860.8  559.14    3064  546.88  3713.9  499.87  4454.8  498.58  4817.8  497.98
  4904.9  494.47  4972.6  462.32  4989.1  459.92  5018.4  462.32  5067.5  491.44
  5113.8  491.45  6351.5   478.9  6386.8  481.09  7862.5  472.77  8253.3   519.4
  8440.8  553.44  8572.5  557.21  8867.1  527.23  9018.1  553.14 10096.9  555.57
#Mann= 16 ,-1 , 0
   749.8     .05       0  1544.9     .05       0  2236.2     .05       0
    2239     .16       0    2479     .05       0  2860.8    .063       0
    3064     .05       0  4454.8    .094       0  4817.8    .063       0
  4972.6    .063       0  5018.4    .063       0  5113.8     .05       0
  6351.5    .063       0  6386.8     .05       0  8253.3     .16       0
  8867.1     .05       0
#XS Ineff= 2 , 0
       0  4800.7   562.4  6269.5       0   562.4
Permanent Ineff=
       F       F
Bank Sta=4972.6,5018.4
XS Rating Curve= 0 ,0
Exp/Cntr=0.3,0.1

Type RM Length L Ch R = 1 ,55440   ,2906,2906,2906
BEGIN DESCRIPTION:
Denton Creek 15.0
END DESCRIPTION:
XS GIS Cut Line= 3
      2411827.77      7042582.53        2413879.        7040310.
      2415259.14      7038240.57
#Sta/Elev= 30
  1897.6  540.86  1934.9  540.52    1984  538.26  2063.8  538.57  2136.1  538.85
  2294.5  548.07  2671.8  503.08    3134  490.38  3160.9   490.1  3309.3  498.26
  3840.6  466.72  4399.6  478.87  4791.2  462.18  4937.2  466.04  4965.8  454.94
  4975.3  452.54  5022.7  454.94  5053.6  475.21    5131  475.33  5202.1  475.03
    5253  474.81  5831.7  476.78  5954.9  455.18  6028.6  474.54  6329.2   477.6
  6523.4  507.13  6525.6  507.33  6617.7  531.97  6872.6   543.3  7446.4  542.32
#Mann= 19 ,-1 , 0
  1897.6     .16       0  1934.9     .05       0    1984    .094       0
  2063.8    .125       0  2136.1    .094       0  2294.5     .05       0
    3134    .063       0  3160.9     .05       0  4791.2     .16       0
  4937.2     .12       0  4965.8     .07       0  5022.7     .16       0
    5131     .16       0  5202.1     .12       0    5253     .16       0
  6028.6     .05       0  6523.4     .16       0  6525.6    .063       0
  6872.6    .125       0
#XS Ineff= 2 , 0
       0  4444.5  519.16  5705.1       0  519.16
Permanent Ineff=
       F       F
Bank Sta=4965.8,5022.7
XS Rating Curve= 0 ,0
Exp/Cntr=0.3,0.1

Type RM Length L Ch R = 1 ,52534   ,2006,2006,2006
BEGIN DESCRIPTION:
Denton Creek 14.0
END DESCRIPTION:
XS GIS Cut Line= 3
      2413585.83       7043671.7        2415629.        7042010.
      2416459.09      7040906.43
#Sta/Elev= 30
  2356.7  516.78  2488.7  509.24  2602.2  518.61  2843.5  497.41  2979.2  476.87
  3113.5  482.23  3354.8  469.14    3561  479.13  3703.2  469.68  4144.2  466.64
  4756.2  478.92  4820.1   473.9  4869.6  454.69  4951.6  462.79  4974.1  453.46
  4993.6  451.06  5019.5  453.46  5047.6   471.5  5098.1  474.18  5438.7  479.47
  5528.3  481.88  5559.5  487.31  5697.3  490.24    5730  498.61  5768.7  509.48
    5791   516.3  5797.3  526.56  6068.1  530.26    6269   535.4  6371.2  537.95
#Mann= 12 ,-1 , 0
  2356.7     .05       0  4951.6     .16       0  4974.1     .07       0
  5019.5     .16       0  5098.1    .094       0  5438.7    .125       0
  5528.3    .094       0  5559.5    .063       0    5730     .05       0
  5768.7    .094       0  6068.1    .125       0    6269    .094       0
#XS Ineff= 2 , 0
       0  4062.2   509.9  5066.9       0   509.9
Permanent Ineff=
       F       F
Bank Sta=4974.1,5019.5
XS Rating Curve= 0 ,0
Exp/Cntr=0.3,0.1