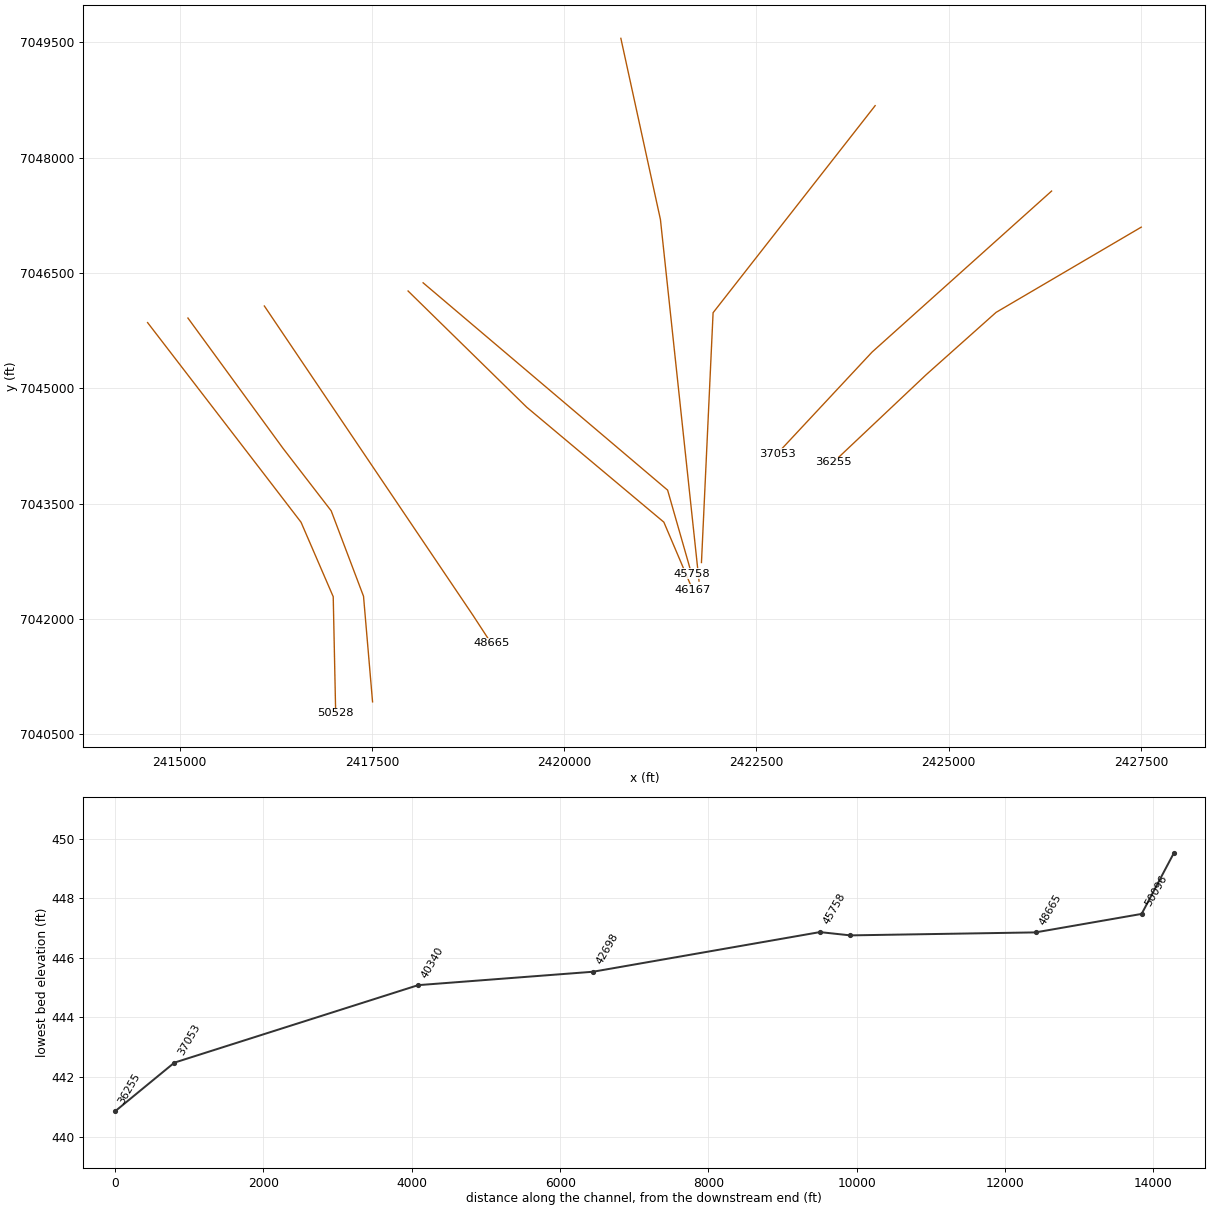
HEC-RAS study Denton Creek.prj: Denton Creek Base Level Engineering

--- Denton Creek.g01 (geometry) --- (continued)

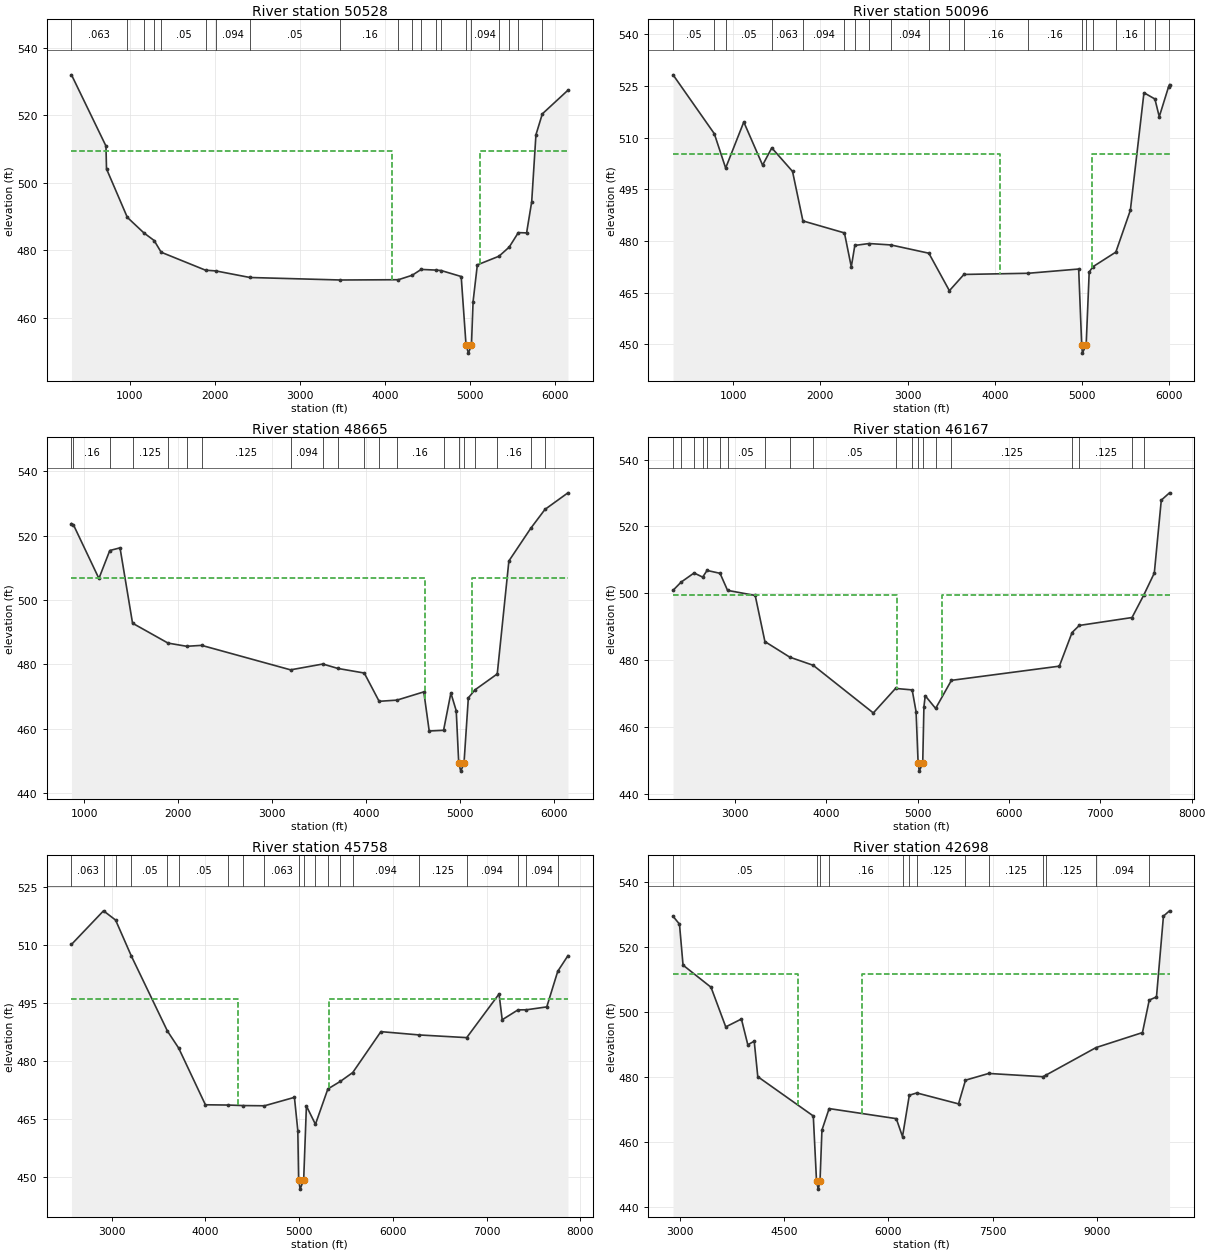
Type RM Length L Ch R = 1 ,50528   ,432,432,432
BEGIN DESCRIPTION:
Denton Creek230
END DESCRIPTION:
XS GIS Cut Line= 5
      2414584.46      7045854.22      2416066.82      7043926.84
      2416579.59      7043258.68      2416998.04      7042290.52
       2417030.1      7040773.31
#Sta/Elev= 30
   311.8  531.96   717.8  510.86   724.1   504.1   969.2  489.73  1163.9  485.13
    1285  482.87  1367.7   479.4  1890.6  474.07  2011.7  473.86  2413.5  471.91
  3478.4  471.17  4160.8  471.25  4323.7  472.57  4429.2   474.3  4598.7  474.11
  4663.8  473.98  4900.8   472.2  4957.8   451.9  4985.8   449.5  5021.5   451.9
  5040.9  464.79  5090.9  475.65  5346.1  478.22  5466.3  480.92  5573.5  485.21
    5671  485.12    5731  494.35    5781   514.2  5856.2  520.39  6157.8   527.4
#Mann= 20 ,-1 , 0
   311.8    .063       0   969.2    .063       0  1163.9    .063       0
    1285     .05       0  1367.7     .05       0  1890.6    .094       0
  2011.7    .094       0  2413.5     .05       0  3478.4     .16       0
  4160.8     .05       0  4323.7     .16       0  4429.2     .15       0
  4598.7     .05       0  4663.8     .15       0  4957.8     .07       0
  5021.5    .094       0  5346.1    .063       0  5466.3    .094       0
  5573.5    .063       0  5856.2    .094       0
#XS Ineff= 2 , 0
       0  4083.6  509.33  5127.6       0  509.33
Permanent Ineff=
       F       F
Bank Sta=4957.8,5021.5
XS Rating Curve= 0 ,0
Exp/Cntr=0.3,0.1

Type RM Length L Ch R = 1 ,50096   ,1431,1431,1431
BEGIN DESCRIPTION:
Denton Creek229
END DESCRIPTION:
XS GIS Cut Line= 5
      2415108.95      7045913.46      2416347.36      7044216.44
      2416971.55      7043406.99        2417392.      7042296.01
      2417509.51      7040923.01
#Sta/Elev= 30
   312.7  528.22   785.4  511.14   915.4  501.17  1123.2  514.53  1338.7  502.01
  1443.9  507.03  1681.7   500.2  1800.8  485.83  2276.6  482.35  2355.2   472.5
  2395.6  478.72  2558.2  479.27  2809.2  478.86  3243.9  476.46  3479.2  465.58
    3646   470.3  4382.3  470.64  4960.8  471.87  4995.4  449.87  5003.6  447.47
  5046.6  449.87  5081.3  470.99    5123  472.52  5386.5  476.78    5553  488.92
  5708.8  523.02  5834.2  521.21  5884.2  516.06  5990.9  524.76  6001.6  525.38
#Mann= 20 ,-1 , 0
   312.7     .05       0   785.4     .16       0   915.4     .05       0
  1443.9    .063       0  1800.8    .094       0  2276.6    .063       0
  2395.6    .094       0  2558.2    .125       0  2809.2    .094       0
  3243.9    .063       0  3479.2     .05       0    3646     .16       0
  4382.3     .16       0  4995.4     .07       0  5046.6     .16       0
    5123     .05       0  5386.5     .16       0  5708.8     .05       0
  5834.2     .16       0  5990.9     .05       0
#XS Ineff= 2 , 0
       0  4060.8  505.16  5110.3       0  505.16
Permanent Ineff=
       F       F
Bank Sta=4995.4,5046.6
XS Rating Curve= 0 ,0
Exp/Cntr=0.3,0.1

Type RM Length L Ch R = 1 ,48665   ,2498,2498,2498
BEGIN DESCRIPTION:
Denton Creek 13.0
END DESCRIPTION:
XS GIS Cut Line= 3
      2416102.71      7046070.09      2418818.46      7042043.21
      2419052.65      7041683.96
#Sta/Elev= 30
   866.4  523.77   887.5  523.39  1158.4  506.73  1274.2  515.42  1383.2  516.25
  1516.5  492.83  1894.6  486.64  2093.5  485.65  2252.4  485.94    3199  478.33
  3542.3  480.14    3702  478.77  3983.7  477.34  4142.1  468.55  4331.9  468.92
  4617.7  471.48  4675.1  459.32  4828.2  459.54  4905.9  471.13  4962.9  465.61
  4989.7  449.25  5011.4  446.85  5045.5  449.25  5091.8  469.63  5162.6  472.11
  5399.6  477.06  5523.5  512.17  5756.2  522.32  5907.5  528.19  6152.3  533.35
#Mann= 20 ,-1 , 0
   866.4     .05       0   887.5     .16       0  1274.2     .05       0
  1516.5    .125       0  1894.6    .094       0  2093.5    .094       0
  2252.4    .125       0    3199    .094       0  3542.3    .125       0
    3702    .094       0  3983.7    .063       0  4142.1     .05       0
  4331.9     .16       0  4828.2     .05       0  4989.7    .035       0
  5045.5     .12       0  5162.6     .05       0  5399.6     .16       0
  5756.2     .05       0  5907.5     .05       0
#XS Ineff= 2 , 0
       0  4628.9  506.92  5134.5       0  506.92
Permanent Ineff=
       F       F
Bank Sta=4989.7,5045.5
XS Rating Curve= 0 ,0
Exp/Cntr=0.3,0.1

Type RM Length L Ch R = 1 ,46167   ,409,409,409
BEGIN DESCRIPTION:
Denton Creek228
END DESCRIPTION:
XS GIS Cut Line= 4
      2417971.46      7046264.94      2419513.86      7044754.11
      2421296.97      7043259.72      2421669.85      7042383.45
#Sta/Elev= 30
  2319.5  500.89  2407.6  503.34  2549.7  506.08  2643.9  504.84  2691.9  506.84
    2834  505.98  2916.6  500.87  3219.3  499.35  3325.7  485.54  3598.4  480.87
  3854.5  478.44  4513.1  464.17  4756.4  471.51  4938.7  471.07  4981.5  464.53
  5003.8  449.15  5016.5  446.75  5054.2  449.15  5067.3  465.99  5081.7  469.32
  5195.4  465.52  5368.3  473.93  6550.6  478.18  6690.1  488.25    6769  490.37
  7346.8  492.74  7473.3  499.35    7591  506.07  7667.3  527.89  7757.4  530.08
#Mann= 20 ,-1 , 0
  2319.5     .05       0  2407.6     .05       0  2549.7     .05       0
  2643.9     .16       0  2691.9     .05       0    2834    .063       0
  2916.6     .05       0  3325.7    .094       0  3598.4    .063       0
  3854.5     .05       0  4756.4    .063       0  4938.7    .094       0
  5003.8     .07       0  5054.2     .16       0  5195.4    .063       0
  5368.3    .125       0  6690.1    .094       0    6769    .125       0
  7346.8    .094       0  7473.3    .063       0
#XS Ineff= 2 , 0
       0    4770  499.45  5269.2       0  499.45
Permanent Ineff=
       F       F
Bank Sta=5003.8,5054.2
XS Rating Curve= 0 ,0
Exp/Cntr=0.3,0.1

Type RM Length L Ch R = 1 ,45758   ,3060,3060,3060
BEGIN DESCRIPTION:
Denton Creek 12.0
END DESCRIPTION:
XS GIS Cut Line= 3
      2418166.92       7046371.6      2421345.84      7043675.97
      2421656.64      7042589.52
#Sta/Elev= 30
  2570.5  510.16  2912.2  518.85  3041.3  516.46  3208.1  507.22  3594.5  487.74
  3714.2  483.35  3999.5  468.68  4244.3  468.61  4395.9  468.48  4630.2  468.42
  4949.7   470.6  4985.7  462.02  4994.7  449.26  5010.6  446.86  5048.3  449.26
  5077.5  468.37  5173.8  463.63  5306.5  472.78  5439.2  474.72    5572  477.02
  5872.4   487.6  6283.5  486.74  6788.1  486.05  7133.2  497.34    7167  490.67
  7335.4  493.23  7425.5  493.25  7642.6     494  7759.9  503.22  7868.5  507.25
#Mann= 20 ,-1 , 0
  2570.5    .063       0  2912.2    .094       0  3041.3    .063       0
  3208.1     .05       0  3594.5    .063       0  3714.2     .05       0
  4244.3     .16       0  4395.9     .05       0  4630.2    .063       0
  4994.7     .07       0  5048.3    .094       0  5173.8    .063       0
  5306.5    .094       0  5439.2    .094       0    5572    .094       0
  6283.5    .125       0  6788.1    .094       0  7335.4    .125       0
  7425.5    .094       0  7759.9    .063       0
#XS Ineff= 2 , 0
       0    4345  495.99  5316.3       0  495.99
Permanent Ineff=
       F       F
Bank Sta=4994.7,5048.3
XS Rating Curve= 0 ,0
Exp/Cntr=0.3,0.1

Type RM Length L Ch R = 1 ,42698   ,2358,2358,2358
BEGIN DESCRIPTION:
Denton Creek 11.0
END DESCRIPTION:
XS GIS Cut Line= 3
      2420737.97      7049550.32       2421252.6      7047193.99
      2421754.36      7042493.27
#Sta/Elev= 30
    2904   529.5  2996.4  527.08  3047.6  514.47  3449.9  507.66  3661.8  495.46
    3887  497.88  3979.1  489.95  4071.2  491.06  4122.4  480.14  4920.8  468.04
  4967.3  447.93  4992.3  445.53  5017.3  447.93    5045  463.69  5148.3  470.32
  6114.4  467.22  6203.6  461.69  6301.7  474.43  6409.1  475.13  7009.4  471.77
  7109.4  479.06  7443.1  481.13  8221.6  480.13    8260  480.54  8987.4   489.1
  9654.4  493.71    9752  503.71    9856  504.69  9956.1  529.55 10043.3  531.18
#Mann= 13 ,-1 , 0
    2904     .05       0  4967.3     .07       0  5017.3     .05       0
  5148.3     .16       0  6203.6     .05       0  6301.7    .094       0
  6409.1    .125       0  7109.4    .094       0  7443.1    .125       0
  8221.6    .094       0    8260    .125       0  8987.4    .094       0
    9752    .063       0
#XS Ineff= 2 , 0
       0  4703.6  511.75  5621.3       0  511.75
Permanent Ineff=
       F       F
Bank Sta=4967.3,5017.3
XS Rating Curve= 0 ,0
Exp/Cntr=0.3,0.1

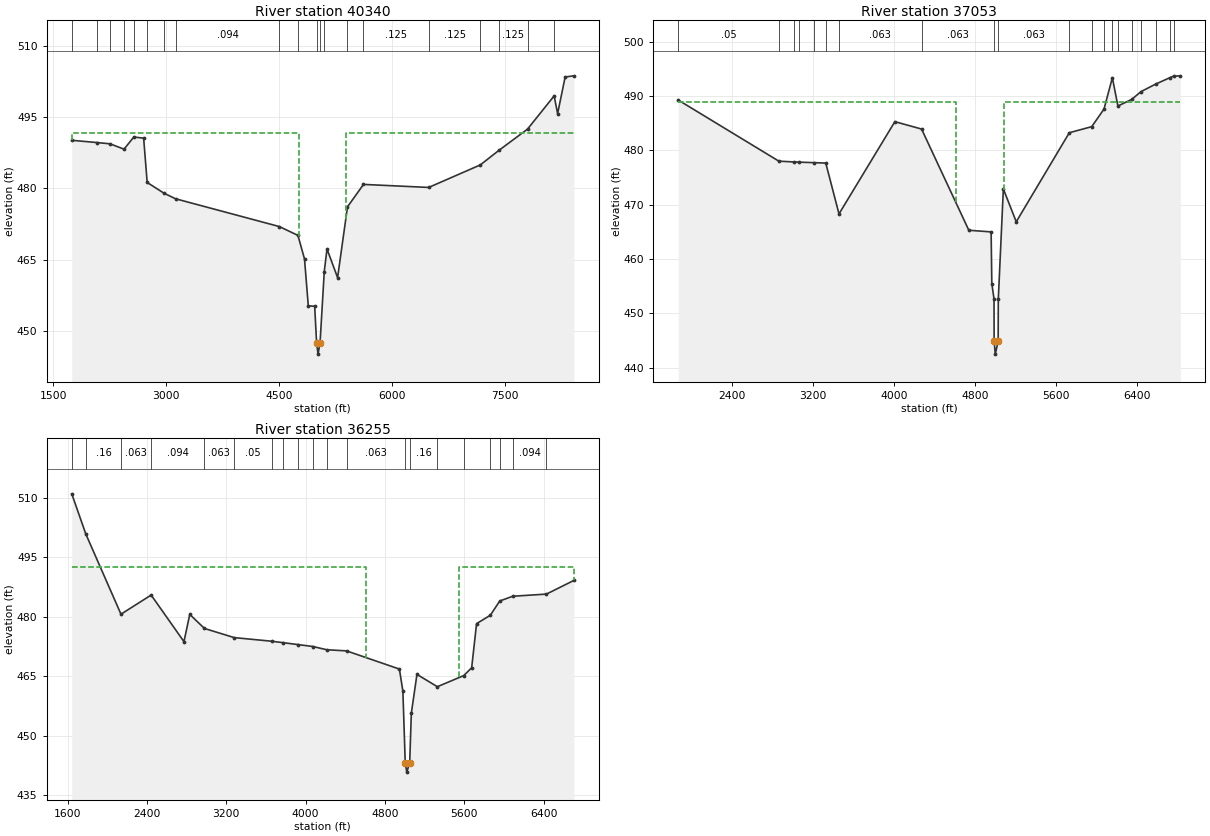
Type RM Length L Ch R = 1 ,40340   ,3287,3287,3287
BEGIN DESCRIPTION:
Denton Creek 10.0
END DESCRIPTION:
XS GIS Cut Line= 3
      2424044.24      7048674.85      2421937.23      7045982.89
      2421785.98      7042734.61
#Sta/Elev= 30
  1746.1  490.16  2075.2  489.69  2254.1  489.42  2440.3  488.29  2570.2  490.85
    2701  490.61  2747.9  481.27    2969  479.03  3124.8  477.83  4504.5  471.97
  4750.8  470.11  4838.1  465.15  4888.3  455.28  4973.3  455.16  4998.7  447.48
    5018  445.08  5044.8  447.48  5100.5  462.48    5137  467.25  5277.6  461.21
  5409.2  476.13  5621.5  480.86  6487.7  480.22    7174  484.97  7422.8  488.06
  7801.1  492.52  8154.7  499.52  8200.8  495.78  8300.9  503.51  8416.4  503.75
#Mann= 20 ,-1 , 0
  1746.1     .05       0  2075.2     .05       0  2254.1    .094       0
  2440.3     .05       0  2570.2    .063       0  2747.9    .094       0
    2969    .063       0  3124.8    .094       0  4504.5    .063       0
  4750.8     .05       0  4998.7     .07       0  5044.8     .15       0
  5100.5     .15       0  5409.2    .094       0  5621.5    .125       0
  6487.7    .125       0    7174    .094       0  7422.8    .125       0
  7801.1    .094       0  8154.7    .063       0
#XS Ineff= 2 , 0
       0  4762.2  491.74  5385.9       0  491.74
Permanent Ineff=
       F       F
Bank Sta=4998.7,5044.8
XS Rating Curve= 0 ,0
Exp/Cntr=0.3,0.1

Type RM Length L Ch R = 1 ,37053   ,798,798,798
BEGIN DESCRIPTION:
Denton Creek 9.0
END DESCRIPTION:
XS GIS Cut Line= 3
      2426338.44      7047564.56       2424004.2      7045470.96
      2422767.91      7044146.19
#Sta/Elev= 30
  1874.9  489.27  2866.1  478.02  3012.6  477.87  3068.5  477.83  3214.8  477.74
  3328.8  477.66    3459   468.3  4009.6  485.29  4272.7  483.93  4738.5  465.29
  4958.3  464.99    4965  455.47  4986.7  452.66  4987.9  444.88  4999.4  442.48
  5027.6  444.88  5028.9  452.56  5078.7   472.9  5205.7  466.85  5728.6  483.25
  5949.5  484.37  6070.6  487.61    6153  493.38  6207.5  488.17  6344.5   489.4
  6435.9  490.83    6581  492.22  6718.7  493.38  6755.4  493.67  6822.5  493.73
#Mann= 20 ,-1 , 0
  1874.9     .05       0  2866.1    .094       0  3012.6    .063       0
  3068.5     .05       0  3214.8     .05       0  3328.8     .05       0
    3459    .063       0  4272.7    .063       0  4987.9    .063       0
  5027.6    .063       0  5728.6    .094       0  5949.5    .125       0
  6070.6    .094       0    6153    .125       0  6207.5     .05       0
  6344.5    .125       0  6435.9    .063       0    6581    .063       0
  6718.7    .094       0  6755.4    .063       0
#XS Ineff= 2 , 0
       0  4616.6  488.96  5081.4       0  488.96
Permanent Ineff=
       F       F
Bank Sta=4987.9,5027.6
XS Rating Curve= 0 ,0
Exp/Cntr=0.3,0.1

Type RM Length L Ch R = 1 ,36255   ,3479,3479,3479
BEGIN DESCRIPTION:
Denton Creek 8.0
END DESCRIPTION:
XS GIS Cut Line= 4
      2427504.08      7047095.21      2425616.66      7045987.29
       2424708.8      7045177.91      2423502.73      7044039.54
#Sta/Elev= 30
  1641.6  510.93  1783.2  500.81  2137.8  480.62    2442  485.44    2773  473.71
  2831.6  480.57  2979.7  477.03  3280.4  474.72  3658.9  473.81  3772.1  473.45
  3922.5  472.97  4073.7  472.48  4212.8  471.67  4412.7  471.38  4945.7   466.8
  4980.8  461.25  5004.5  443.25  5020.3  440.85  5049.6  443.25    5066  455.68
  5122.7  465.46  5328.4  462.36  5594.6  465.16  5674.5  467.13  5723.8  478.24
  5862.5  480.35  5957.8  483.95  6089.2  485.14  6428.7  485.68  6704.9  489.12
#Mann= 20 ,-1 , 0
  1641.6     .05       0  1783.2     .16       0  2137.8    .063       0
    2442    .094       0  2979.7    .063       0  3280.4     .05       0
  3658.9    .063       0  3772.1    .063       0  3922.5    .063       0
  4073.7     .05       0  4212.8    .063       0  4412.7    .063       0
  5004.5     .07       0  5049.6     .16       0  5328.4    .063       0
  5594.6    .063       0  5862.5     .05       0  5957.8    .063       0
  6089.2    .094       0  6428.7    .063       0
#XS Ineff= 2 , 0
       0  4612.6  492.41  5550.8       0  492.41
Permanent Ineff=
       F       F
Bank Sta=5004.5,5049.6
XS Rating Curve= 0 ,0
Exp/Cntr=0.3,0.1