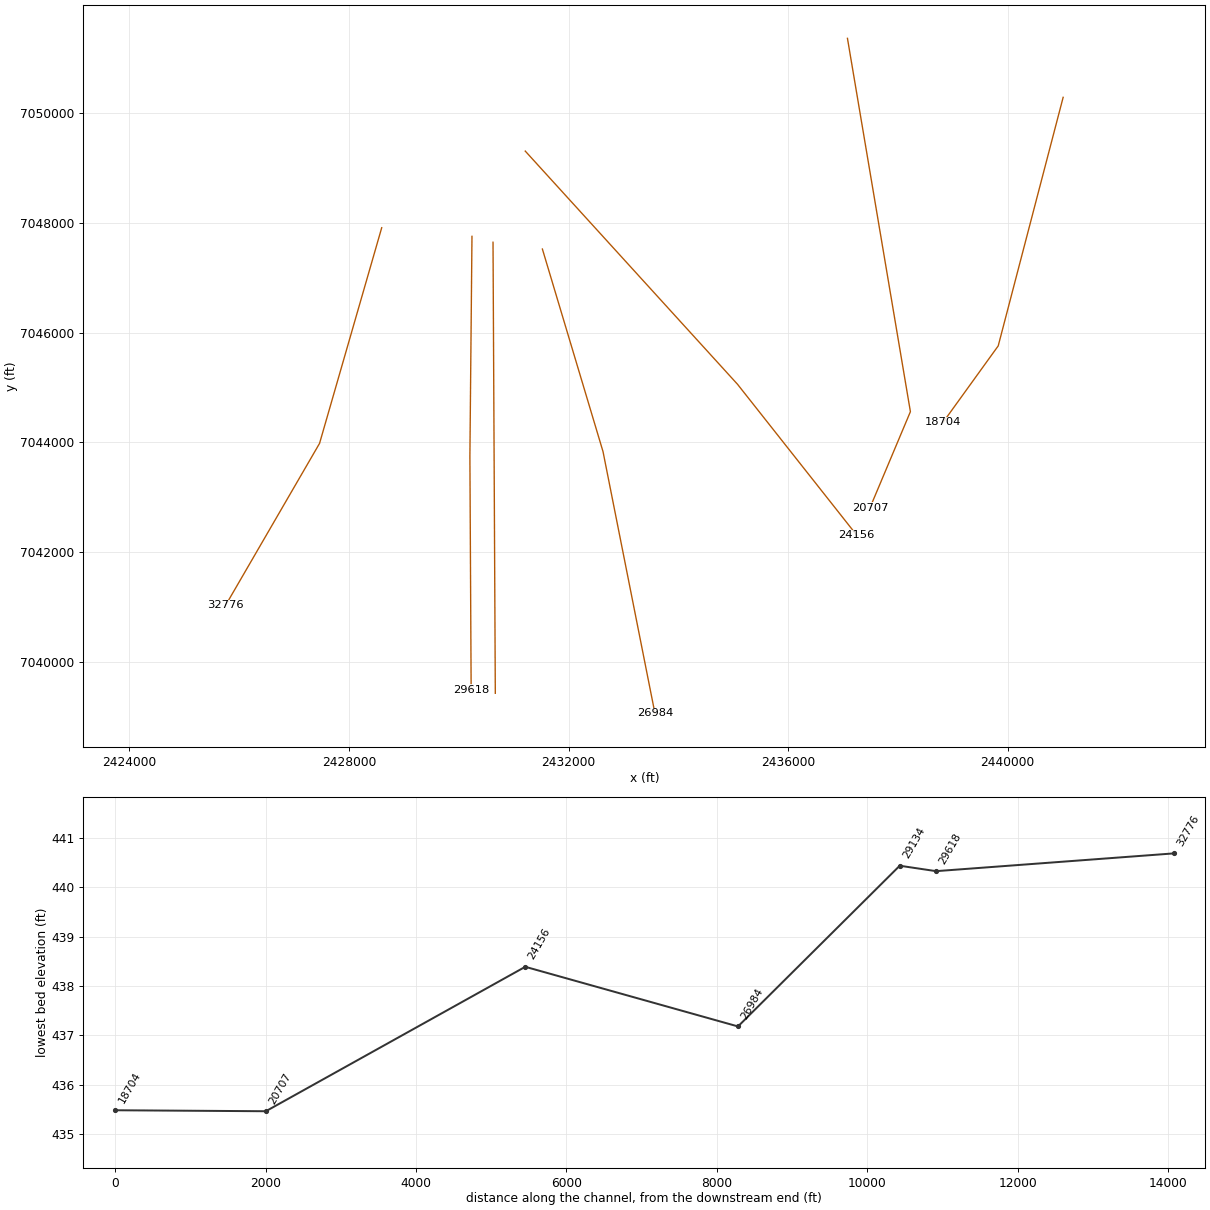
HEC-RAS study Denton Creek.prj: Denton Creek Base Level Engineering

--- Denton Creek.g01 (geometry) --- (continued)

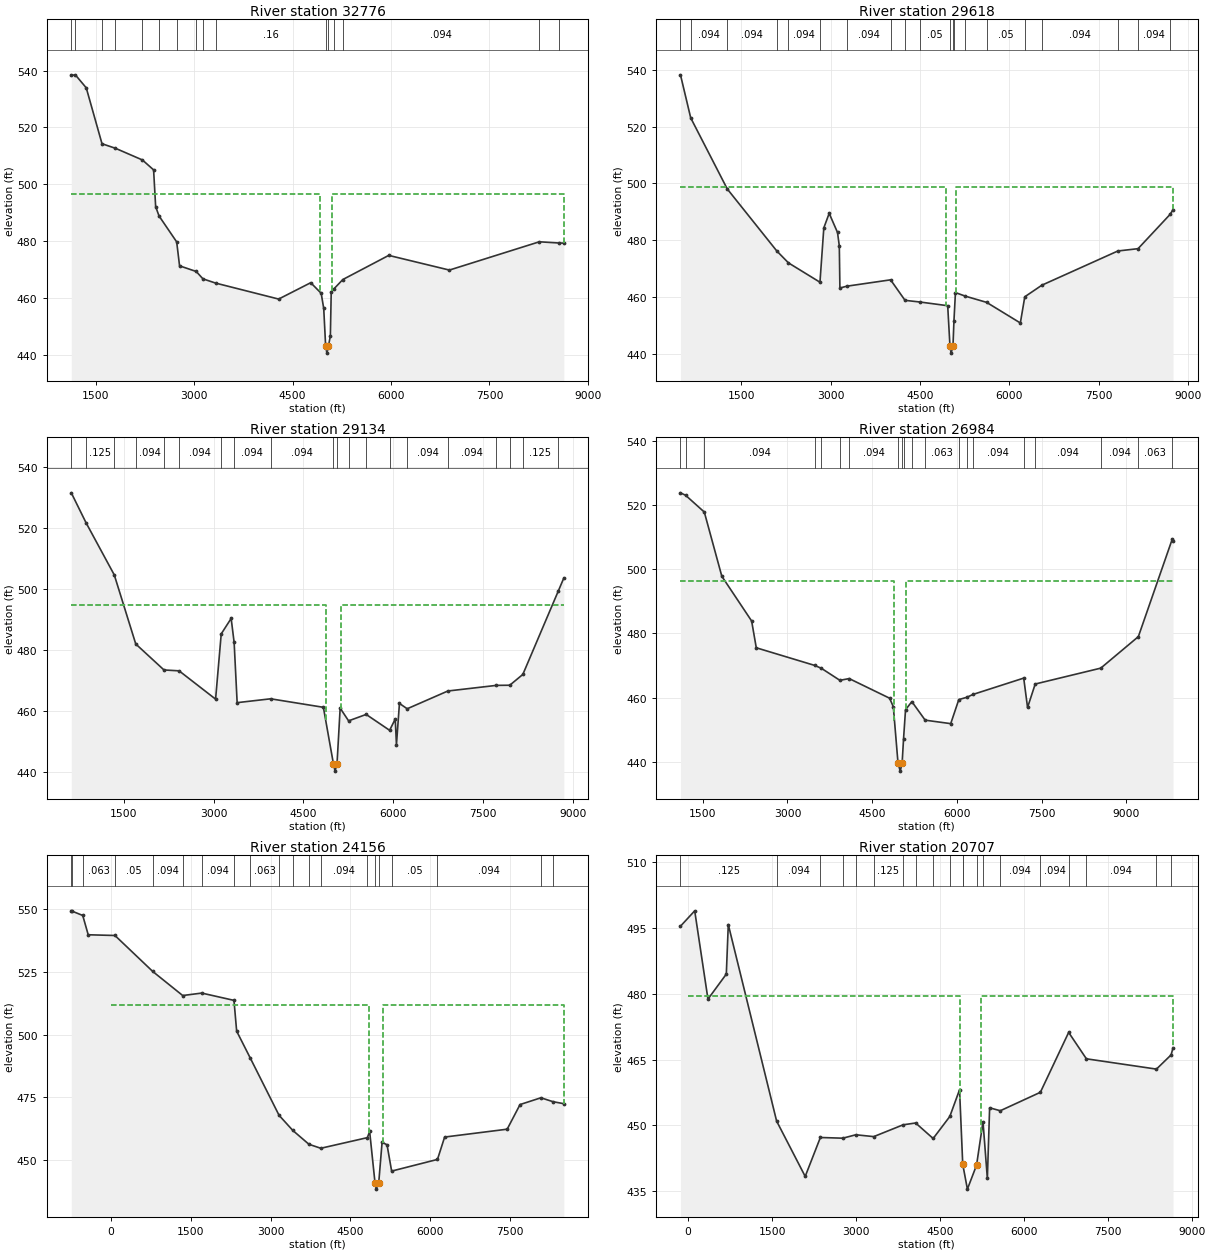
Type RM Length L Ch R = 1 ,32776   ,3158,3158,3158
BEGIN DESCRIPTION:
Denton Creek 7.0
END DESCRIPTION:
XS GIS Cut Line= 3
      2428596.84      7047914.84      2427464.16      7043981.64
      2425753.95      7041031.32
#Sta/Elev= 30
  1129.5   538.3  1191.1   538.5  1357.4  533.92  1597.3  514.28  1802.3  512.68
  2212.5  508.58  2383.3  505.09  2414.5  492.18    2466   488.9  2734.9  479.78
  2778.7  471.37  3032.7  469.38  3135.3  466.79  3328.8   465.3  4288.2  459.69
  4776.8  465.44  4936.1  461.72  4974.9  456.39  5004.2  443.09  5023.4  440.69
  5045.9  443.09    5076  446.75    5089  462.25    5128  463.23  5266.2  466.56
  5965.3  475.04  6888.9  469.88  8259.2  479.82    8560  479.39  8632.7  479.35
#Mann= 16 ,-1 , 0
  1129.5    .063       0  1191.1     .16       0  1597.3     .05       0
  1802.3    .063       0  2212.5     .05       0    2466    .063       0
  2734.9    .125       0  3032.7    .063       0  3135.3     .05       0
  3328.8     .16       0  5004.2     .07       0  5045.9     .16       0
    5128     .05       0  5266.2    .094       0  8259.2    .063       0
    8560    .094       0
#XS Ineff= 2 , 0
       0  4923.9  496.65  5102.4       0  496.65
Permanent Ineff=
       F       F
Bank Sta=5004.2,5045.9
XS Rating Curve= 0 ,0
Exp/Cntr=0.3,0.1

Type RM Length L Ch R = 1 ,29618   ,484,484,484
BEGIN DESCRIPTION:
Denton Creek 6.0
END DESCRIPTION:
XS GIS Cut Line= 3
      2430241.28      7047757.13      2430203.31      7043745.89
      2430226.17      7039486.27
#Sta/Elev= 30
   477.3  538.17   649.5  523.03  1262.7  498.06  2095.4  476.23  2291.1  472.05
  2819.8  465.26  2884.5  484.36  2974.5  489.47  3114.5  482.75  3144.6  478.02
  3154.6  463.22  3269.7  463.86    4006   466.1  4248.2  458.89  4503.3  458.29
  4964.6     457    5003  442.73  5021.7  440.33  5053.3  442.73  5069.2  451.46
  5094.6  461.62  5259.3  460.37  5617.8  458.18  6184.6  450.93  6259.2  460.14
  6546.5  464.22  7822.3  476.24    8161  477.05  8702.5  489.18  8748.4   490.8
#Mann= 20 ,-1 , 0
   477.3    .063       0   649.5    .094       0  1262.7    .094       0
  2095.4     .05       0  2291.1    .094       0  2819.8    .125       0
  3269.7    .094       0    4006    .094       0  4248.2     .05       0
  4503.3     .05       0    5003    .035       0  5053.3     .05       0
  5069.2    .063       0  5259.3    .125       0  5617.8     .05       0
  6259.2    .094       0  6546.5    .094       0  7822.3    .125       0
    8161    .094       0  8702.5    .125       0
#XS Ineff= 2 , 0
       0  4944.2  498.62  5100.1       0  498.62
Permanent Ineff=
       F       F
Bank Sta=5003,5053.3
XS Rating Curve= 0 ,0
Exp/Cntr=0.3,0.1

Type RM Length L Ch R = 1 ,29134   ,2150,2150,2150
BEGIN DESCRIPTION:
Denton Creek227
END DESCRIPTION:
XS GIS Cut Line= 2
      2430624.73      7047649.36      2430666.35      7039424.76
#Sta/Elev= 30
   624.4  531.44   868.9  521.72  1342.1   504.6  1700.9  482.01    2172  473.52
  2424.8  473.23  3033.8  463.98    3128  485.32  3293.8  490.37  3343.6   482.5
  3393.8  462.83  3953.8  464.09  4833.8  461.31  5001.4  442.84  5028.6  440.44
  5061.6  442.84  5113.8  461.03  5254.8  456.88  5548.3  458.98  5939.6  453.79
  6033.8  457.48  6053.8  449.09  6103.8  462.57  6233.3  460.83  6912.5  466.64
  7722.9  468.48  7946.1  468.53  8164.2  472.06  8753.5   499.2  8849.1  503.61
#Mann= 20 ,-1 , 0
   624.4    .063       0   868.9    .125       0  1342.1     .05       0
  1700.9    .094       0    2172    .125       0  2424.8    .094       0
    3128    .125       0  3343.6    .094       0  3953.8    .094       0
  5001.4     .07       0  5061.6     .16       0  5254.8    .094       0
  5548.3     .05       0  5939.6    .063       0  6233.3    .094       0
  6912.5    .094       0  7722.9    .125       0  7946.1    .094       0
  8164.2    .125       0  8753.5    .125       0
#XS Ineff= 2 , 0
       0  4872.4  494.88  5120.5       0  494.88
Permanent Ineff=
       F       F
Bank Sta=5001.4,5061.6
XS Rating Curve= 0 ,0
Exp/Cntr=0.3,0.1

Type RM Length L Ch R = 1 ,26984   ,2828,2828,2828
BEGIN DESCRIPTION:
Denton Creek 5.0
END DESCRIPTION:
XS GIS Cut Line= 3
      2431523.99      7047526.25      2432628.67      7043832.65
      2433574.87      7039058.56
#Sta/Elev= 30
  1104.8  523.73  1195.5  522.97    1527  517.75  1837.2  497.78  2365.1  483.87
  2447.3  475.54  3482.9  470.05  3601.6  469.14  3927.9  465.42  4092.5  465.96
  4807.8  459.86    4874  457.21  4957.6  439.58  4996.5  437.18  5029.7  439.58
  5054.9  447.17  5090.3  456.28  5202.5  458.79  5438.2  453.03  5890.5  451.95
  6033.7  459.43  6175.4  460.14  6286.5  461.04    7183  466.11  7251.1  456.97
  7386.6  464.27  8547.4  469.21  9213.2  479.01  9814.9  509.41    9827  508.89
#Mann= 20 ,-1 , 0
  1104.8    .094       0  1195.5    .125       0    1527    .094       0
  3482.9    .094       0  3601.6    .125       0  3927.9    .063       0
  4092.5    .094       0  4957.6    .035       0  5029.7     .05       0
  5054.9     .16       0  5202.5     .05       0  5438.2    .063       0
  6033.7    .094       0  6175.4    .063       0  6286.5    .094       0
    7183    .063       0  7386.6    .094       0  8547.4    .094       0
  9213.2    .063       0  9814.9    .094       0
#XS Ineff= 2 , 0
       0  4894.5  496.27  5105.5       0  496.27
Permanent Ineff=
       F       F
Bank Sta=4957.6,5029.7
XS Rating Curve= 0 ,0
Exp/Cntr=0.3,0.1

Type RM Length L Ch R = 1 ,24156   ,3449,3449,3449
BEGIN DESCRIPTION:
Denton Creek 4.0
END DESCRIPTION:
XS GIS Cut Line= 3
      2431211.87      7049311.92        2435079.        7045060.
      2437252.19      7042306.83
#Sta/Elev= 30
  -743.8  549.41  -723.1  549.23  -528.7  547.56    -426  539.86    76.7  539.57
   786.3  525.23  1349.4  515.62  1707.5   516.6  2312.9  513.69  2363.3  501.41
  2615.8  490.82  3160.1  467.84  3418.8  461.79  3722.2  456.27  3944.6  454.69
  4819.4  458.93  4862.1   461.4  4963.5  440.79  4982.5  438.39  5032.3  440.79
  5095.8  457.05  5188.9  456.08  5275.3  445.58  6136.6  450.24    6271  459.16
  7446.1   462.3  7688.2  472.13  8080.1  474.83  8307.4  473.27  8511.2  472.47
#Mann= 20 ,-1 , 0
  -743.8     .05       0  -723.1     .05       0  -528.7    .063       0
    76.7     .05       0   786.3    .094       0  1349.4    .063       0
  1707.5    .094       0  2312.9    .125       0  2615.8    .063       0
  3160.1    .125       0  3418.8    .125       0  3722.2    .063       0
  3944.6    .094       0  4819.4    .063       0  4963.5    .035       0
  5032.3     .05       0  5275.3     .05       0  6136.6    .094       0
  8080.1    .063       0  8307.4    .094       0
#XS Ineff= 2 , 0
       0  4847.7  511.89  5118.1       0  511.89
Permanent Ineff=
       F       F
Bank Sta=4963.5,5032.3
XS Rating Curve= 0 ,0
Exp/Cntr=0.3,0.1

Type RM Length L Ch R = 1 ,20707   ,2003,2003,2003
BEGIN DESCRIPTION:
Denton Creek 3.0
END DESCRIPTION:
XS GIS Cut Line= 3
      2437082.11      7051368.16        2438229.        7044560.
      2437493.58      7042809.93
#Sta/Elev= 30
  -136.5  495.44     118  498.95     355  478.81     683  484.52   718.1  495.82
  1581.9  450.98  2092.6  438.36  2363.8  447.24  2764.8  447.08  2997.6  447.86
  3317.7  447.44  3841.9  450.13  4066.2  450.55  4379.1  447.01  4677.2  452.04
    4851  458.14  4907.9  441.13  4909.4  441.03  4991.2  435.46  5154.9  440.93
  5269.9  450.84  5347.9  437.89  5388.4  454.02  5578.5  453.34  6295.4  457.55
  6800.7  471.21  7117.8  465.19  8369.5  462.84  8631.4  466.08  8665.9   467.7
#Mann= 20 ,-1 , 0
  -136.5    .125       0  1581.9    .094       0  2363.8     .12       0
  2764.8     .16       0  2997.6     .05       0  3317.7    .125       0
  3841.9    .094       0  4066.2    .063       0  4379.1    .094       0
  4677.2     .05       0  4907.9    .035       0  4909.4    .035       0
  5154.9    .094       0  5269.9     .16       0  5578.5    .094       0
  6295.4    .094       0  6800.7    .094       0  7117.8    .094       0
  8369.5    .125       0  8631.4    .094       0
#XS Ineff= 2 , 0
       0  4857.9  479.49  5239.6       0  479.49
Permanent Ineff=
       F       F
Bank Sta=4907.9,5154.9
XS Rating Curve= 0 ,0
Exp/Cntr=0.3,0.1

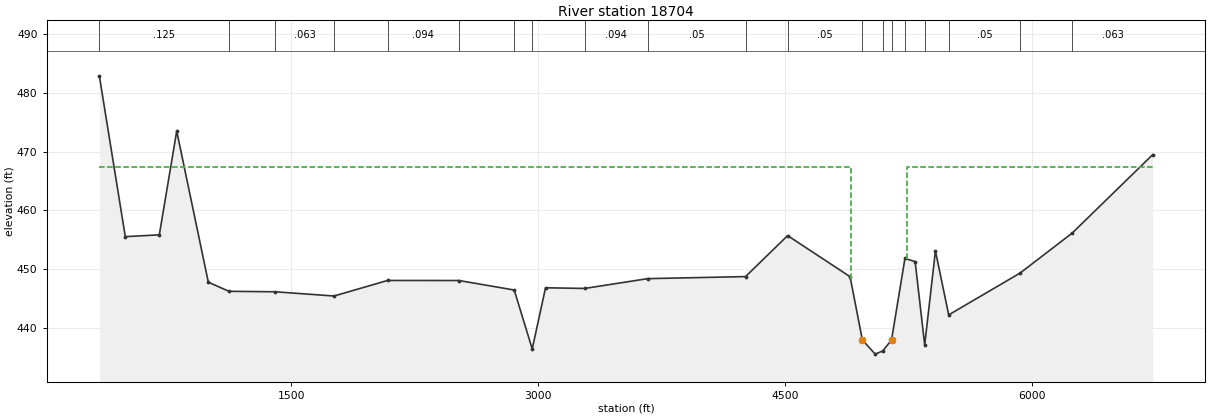
Type RM Length L Ch R = 1 ,18704   ,0,0,0
BEGIN DESCRIPTION:
Denton Creek 2.0
END DESCRIPTION:
XS GIS Cut Line= 3
      2441011.99      7050292.58        2439829.        7045760.
      2438826.33      7044369.16
#Sta/Elev= 30
   333.5  482.93   491.2  455.51   697.9  455.82   803.6  473.51   995.6  447.74
    1121  446.19  1401.5  446.11  1759.3  445.39  2084.5  448.04  2518.4  448.03
  2853.7  446.41  2963.2  436.36  3043.9  446.79  3282.4  446.68    3665  448.35
  4258.8   448.7  4514.7  455.69  4893.9  448.68  4968.5   437.9  5046.6  435.48
  5092.6  436.03  5145.8   437.9  5227.2  451.79  5289.1  451.26  5347.2  437.05
  5412.4  453.07    5493  442.17  5927.1  449.31  6243.4  456.12  6732.5   469.5
#Mann= 20 ,-1 , 0
   333.5    .125       0    1121     .16       0  1401.5    .063       0
  1759.3    .094       0  2084.5    .094       0  2518.4    .094       0
  2853.7    .063       0  2963.2    .094       0  3282.4    .094       0
    3665     .05       0  4258.8    .063       0  4514.7     .05       0
  4968.5    .035       0  5092.6     .15       0  5145.8     .05       0
  5227.2     .16       0  5347.2     .05       0    5493     .05       0
  5927.1    .094       0  6243.4    .063       0
#XS Ineff= 2 , 0
       0  4897.7  467.47  5240.2       0  467.47
Permanent Ineff=
       F       F
Bank Sta=4968.5,5145.8
XS Rating Curve= 0 ,0
Exp/Cntr=0.3,0.1

Chan Stop Cuts=-1
Use User Specified Reach Order=0
Composite Channel Slope=5