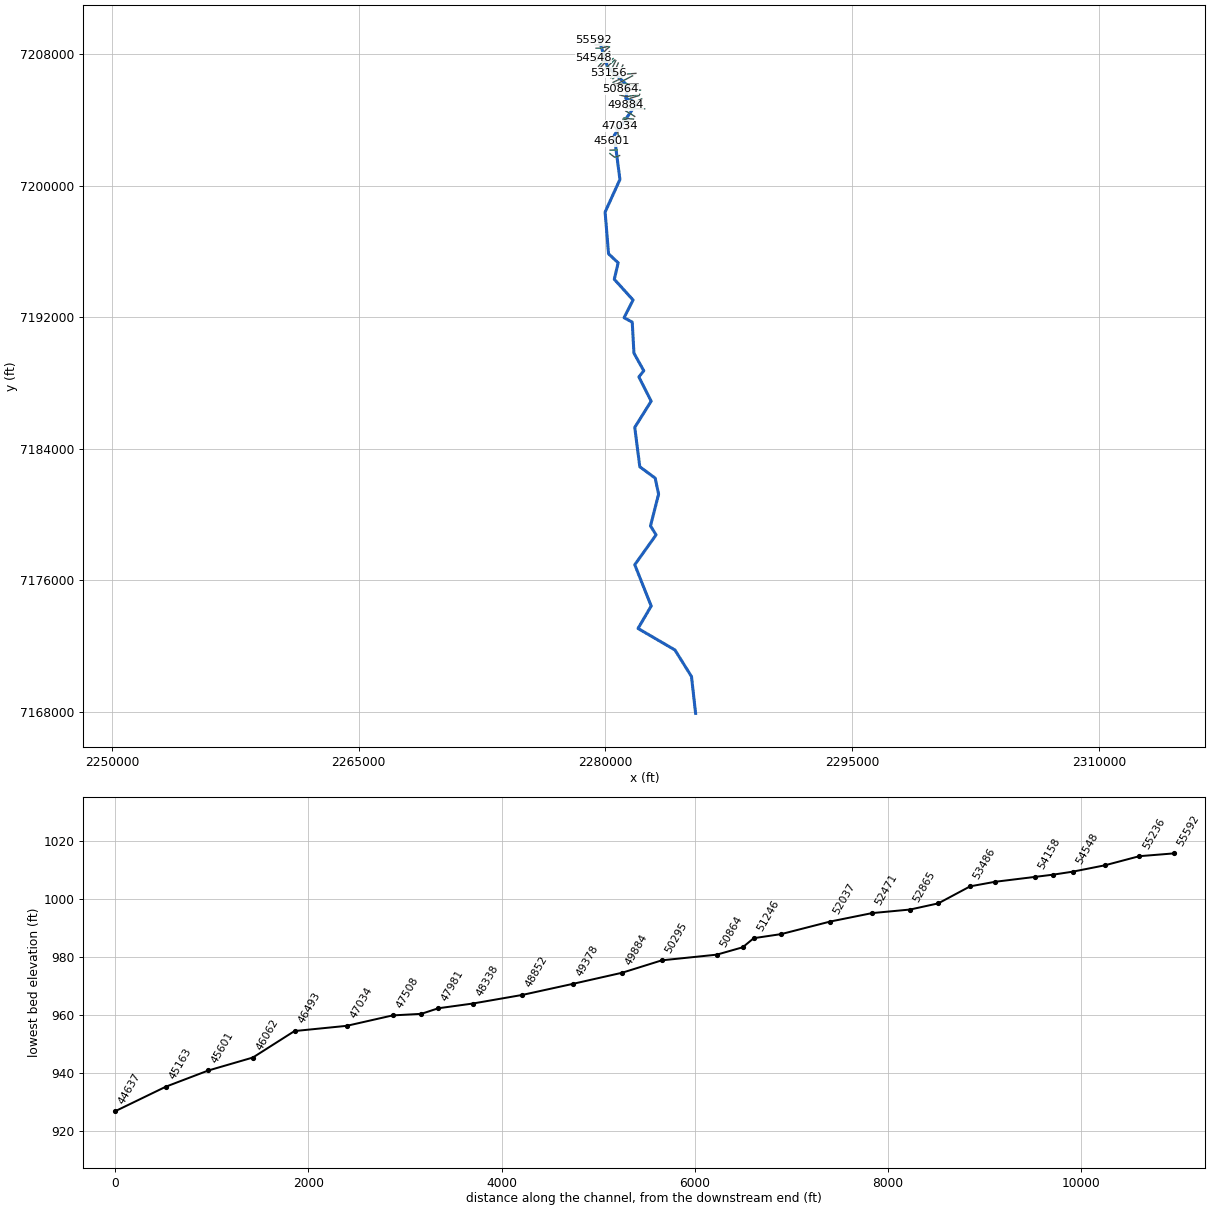
--- Harts Creek.prj (project) ---

Proj Title=Harts Creek Base Level Engineering
Current Plan=p01
Default Exp/Contr=0.3,0.1
English Units
Geom File=g01
Flow File=f01
Plan File=p01
Y Axis Title=Elevation
X Axis Title(PF)=Main Channel Distance
X Axis Title(XS)=Station
BEGIN DESCRIPTION:
Harts Creek
END DESCRIPTION:
DSS Export Rating Curves= 0
DSS Export Rating Curve Sorted= 0
DSS Export Volume Flow Curves= 0
DXF OffsetX= 0
DXF OffsetY= 0
DXF ScaleX= 1
DXF ScaleY= 10

--- Harts Creek.p01 (plan) ---

Plan Title=Multiple Run
Short Identifier=Multiple
Geom File=g01
Flow File=f01
Subcritical Flow
K Sum by GR= 0
Std Step Tol= 0.01
Critical Tol= 0.01
Num of Std Step Trials= 20
Max Error Tol= 0.3
Flow Tol Ratio= 0.001
Split Flow NTrial= 30
Split Flow Tol= 0.02
Split Flow Ratio= 0.02
Log Output Level= 0
Friction Slope Method= 1
Unsteady Friction Slope Method= 2
Unsteady Bridges Friction Slope Method= 1
Parabolic Critical Depth
Global Vel Dist=  1 , 1 , 1
Global Log Level= 0
CheckData=True
Encroach Param= -1, 0, 0, 0
BEGIN DESCRIPTION:
Multiple Run
END DESCRIPTION:

--- Harts Creek.f01 (steady flow) ---

Flow Title=Multiple
Program Version=4.10
Number of Profiles= 7
Profile Names=10-year,25-year,50-year,1pct_min,100-year,1pct_plu,500-year
River Rch & RM=Harts Creek,Reach-1         ,55592
     417     559     675     405     808    1612    1159
River Rch & RM=Harts Creek,Reach-1         ,53743
     506     687     835     505    1007    2009    1466
River Rch & RM=Harts Creek,Reach-1         ,51531
     797    1111    1376     845    1686    3363    2538
River Rch & RM=Harts Creek,Reach-1         ,48852
     908    1271    1577     971    1937    3865    2928
River Rch & RM=Harts Creek,Reach-1         ,47508
    1075    1527    1911    1187    2368    4724    3643
River Rch & RM=Harts Creek,Reach-1         ,44436
    1494    2150    2717    1701    3394    6771    5310
River Rch & RM=Harts Creek,Reach-1         ,41958
    1484    2133    2692    1683    3359    6702    5243
River Rch & RM=Harts Creek,Reach-1         ,40575
    1685    2432    3080    1931    3853    7688    6047
River Rch & RM=Harts Creek,Reach-1         ,38658
    1778    2573    3264    2049    4089    8158    6436
River Rch & RM=Harts Creek,Reach-1         ,38550
    2027    2950    3757    2367    4722    9422    7485
River Rch & RM=Harts Creek,Reach-1         ,30198
    2081    3028    3856    2429    4846    9669    7677
River Rch & RM=Harts Creek,Reach-1         ,27286
    3236    4792    6175    3931    7842   15648   12691
River Rch & RM=Harts Creek,Reach-1         ,22211
    3219    4760    6127    3895    7772   15506   12545
River Rch & RM=Harts Creek,Reach-1         ,18752
    3235    4778    6145    3903    7787   15538   12547
River Rch & RM=Harts Creek,Reach-1         ,15194
    3363    4965    6384    4053    8086   16134   13016
River Rch & RM=Harts Creek,Reach-1         ,9246
    3536    5202    6673    4226    8432   16824   13501
Boundary for River Rch & Prof#=Harts Creek,Reach-1         , 1
Up Type= 0
Dn Type= 3
Dn Slope=0.002
Boundary for River Rch & Prof#=Harts Creek,Reach-1         , 2
Up Type= 0
Dn Type= 3
Dn Slope=0.002
Boundary for River Rch & Prof#=Harts Creek,Reach-1         , 3
Up Type= 0
Dn Type= 3
Dn Slope=0.002
Boundary for River Rch & Prof#=Harts Creek,Reach-1         , 4
Up Type= 0
Dn Type= 3
Dn Slope=0.002
Boundary for River Rch & Prof#=Harts Creek,Reach-1         , 5
Up Type= 0
Dn Type= 3
Dn Slope=0.002
Boundary for River Rch & Prof#=Harts Creek,Reach-1         , 6
Up Type= 0
Dn Type= 3
Dn Slope=0.002
Boundary for River Rch & Prof#=Harts Creek,Reach-1         , 7
Up Type= 0
Dn Type= 3
Dn Slope=0.002
DSS Import GetInterval= 0
DSS Import GetPeak= 0
DSS Import FillOption= 0

--- Harts Creek.g01 (geometry) ---

Geom Title=Existing Conditions
Program Version=4.10

River Reach=Harts Creek     ,Reach-1
Reach XY= 30
        2279579.        7208960.      2280134.52      7207207.57
      2281375.46      7206058.54      2281233.97      7205307.42
      2281929.27      7205037.52      2280530.79      7203053.92
      2280878.93      7200375.37      2279978.52      7198396.19
      2280187.03      7195856.65      2280771.69      7195310.11
      2280537.08       7194306.7       2281677.4      7193048.19
       2281129.7      7191969.79      2281626.77       7191704.1
      2281730.74      7189815.63      2282329.19      7188744.74
       2282029.9      7188369.84      2282778.33      7186896.07
      2281780.19      7185299.52      2282086.88      7182906.78
      2283021.24      7182216.17      2283229.04      7181240.02
      2282736.28      7179310.03      2283077.32      7178765.68
       2281780.2       7176949.5       2282779.3      7174439.61
      2281979.67      7173073.91      2284220.98      7171766.34
      2285226.82      7170154.55        2285479.        7167910.

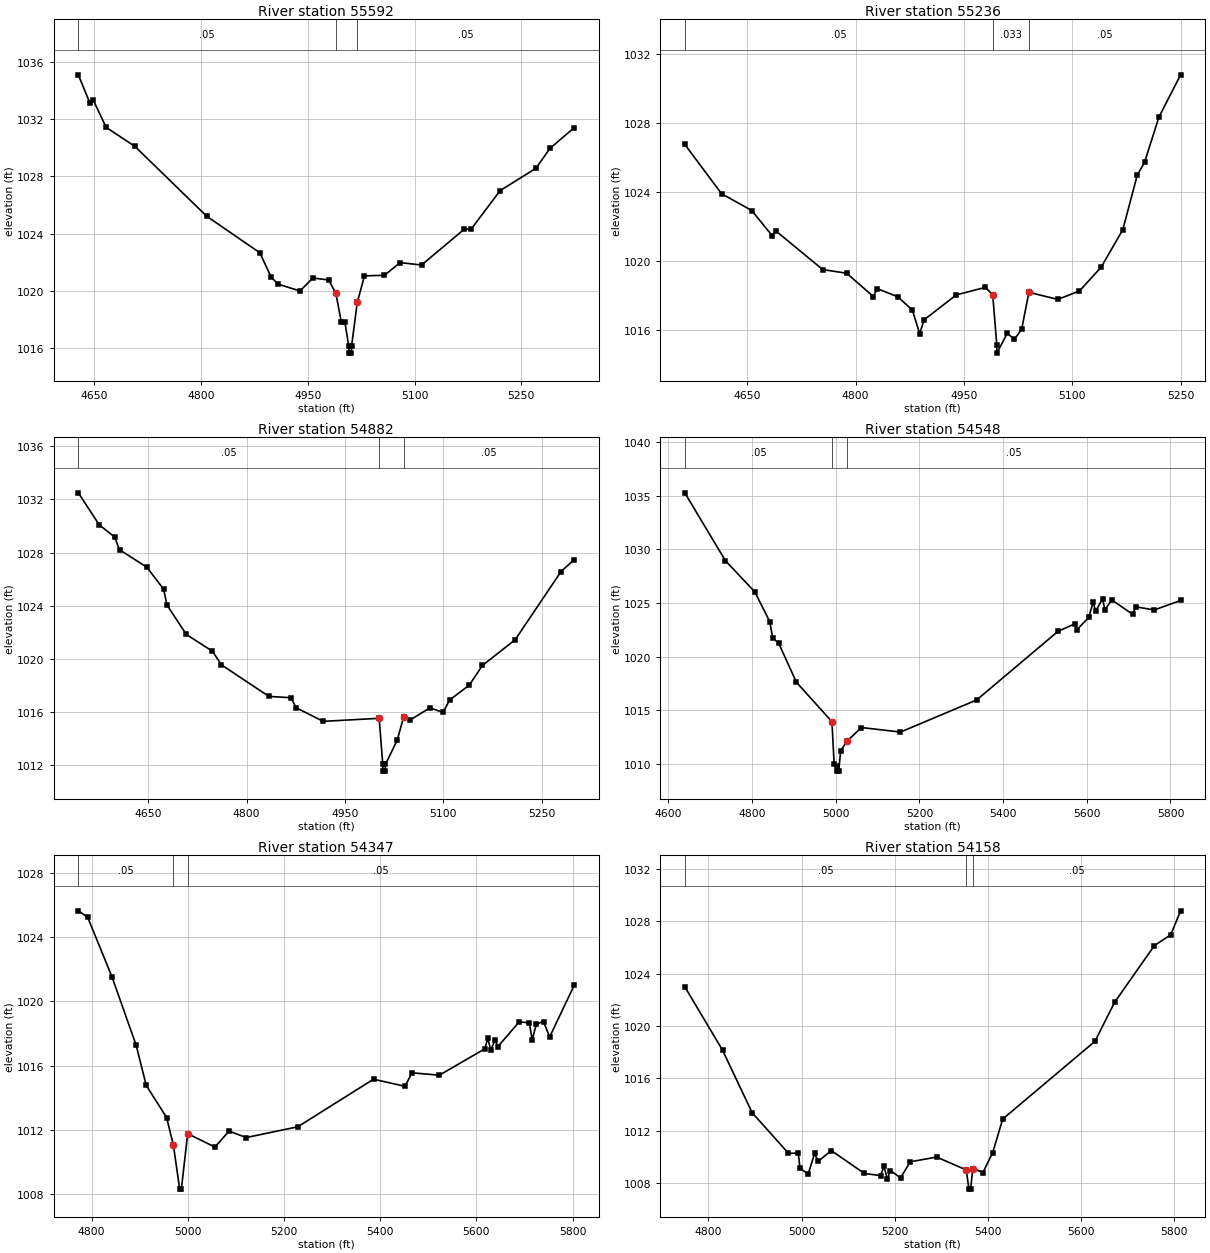
Type RM Length L Ch R = 1 ,55592   ,356,356,356
BEGIN DESCRIPTION:
Harts Creek 104.0
END DESCRIPTION:
XS GIS Cut Line= 3
      2279947.85      7208907.33        2279579.        7208860.
      2279255.36      7208833.51
#Sta/Elev= 30
  4627.6 1035.13  4643.7 1033.17  4648.8 1033.33  4666.8 1031.44  4707.1 1030.11
    4808 1025.21  4882.6 1022.65  4898.7 1020.92  4908.7 1020.44    4939 1019.97
  4957.1 1020.88  4979.3 1020.74  4989.4 1019.81    4997 1017.81    5002 1017.81
  5007.5 1016.11  5007.8 1015.61  5011.3 1015.61  5011.5 1016.11  5019.5 1019.17
  5029.6 1021.03  5057.7 1021.07  5079.7 1021.96  5109.8 1021.79    5170 1024.31
  5179.2 1024.29  5220.2 1027.01  5270.4 1028.57  5290.4 1029.98  5324.2 1031.42
#Mann= 3 , 0 , 0
  4627.6     .05       0  4989.4    .033       0  5019.5     .05       0
Bank Sta=4989.4,5019.5
XS Rating Curve= 0 ,0
Exp/Cntr=0.3,0.1

Type RM Length L Ch R = 1 ,55236   ,354,354,354
BEGIN DESCRIPTION:
Harts Creek 103.0
END DESCRIPTION:
XS GIS Cut Line= 3
      2280060.74      7208497.18        2279629.        7208560.
      2279378.99        7208560.
#Sta/Elev= 30
  4563.7 1026.77  4614.5 1023.91  4656.4 1022.93  4684.6 1021.47  4689.6 1021.75
  4754.7  1019.5  4787.8 1019.29  4824.8 1017.93  4829.8  1018.4  4858.5 1017.92
  4878.7 1017.15  4888.8 1015.78  4894.9 1016.58  4939.4 1018.03  4979.8 1018.47
  4989.9 1018.04  4995.5 1015.15  4995.7 1014.65    5010  1015.8    5020 1015.45
    5030 1016.04    5040 1018.18    5080 1017.77    5110 1018.26    5140 1019.64
    5170 1021.82    5190 1024.99    5200 1025.72    5220 1028.36    5250 1030.81
#Mann= 3 , 0 , 0
  4563.7     .05       0  4989.9    .033       0    5040     .05       0
Bank Sta=4989.9,5040
XS Rating Curve= 0 ,0
Exp/Cntr=0.3,0.1

Type RM Length L Ch R = 1 ,54882   ,334,334,334
BEGIN DESCRIPTION:
Harts Creek 102.0
END DESCRIPTION:
XS GIS Cut Line= 3
      2280169.77      7208478.75        2279729.        7208360.
      2279428.99        7208360.
#Sta/Elev= 30
  4543.2  1032.5  4575.1 1030.09  4598.5 1029.17  4606.1 1028.21  4647.6  1026.9
  4673.2 1025.25  4678.6 1024.03    4708 1021.83  4747.9 1020.56  4761.5 1019.54
    4834 1017.16  4867.7 1017.06  4875.4 1016.31  4916.8 1015.28  5002.2 1015.51
  5007.7 1012.03  5007.9 1011.53  5011.4 1011.53  5011.7 1012.03  5029.7 1013.86
  5039.7 1015.63  5049.7 1015.39  5079.7  1016.3  5099.7 1015.95  5109.7 1016.89
  5139.7 1018.01  5159.7 1019.49  5209.7 1021.43  5279.7 1026.57  5299.7 1027.47
#Mann= 3 , 0 , 0
  4543.2     .05       0  5002.2    .033       0  5039.7     .05       0
Bank Sta=5002.2,5039.7
XS Rating Curve= 0 ,0
Exp/Cntr=0.3,0.1

Type RM Length L Ch R = 1 ,54548   ,201,201,201
BEGIN DESCRIPTION:
Harts Creek 101.0
END DESCRIPTION:
XS GIS Cut Line= 5
      2280244.53      7208440.49      2280082.57      7208304.75
      2279976.52      7208199.82      2279807.22      7208068.31
      2279262.98      7207793.01
#Sta/Elev= 30
  4639.4 1035.26  4736.4 1028.94  4806.7 1026.03  4842.3 1023.27  4849.6 1021.72
  4863.7 1021.25  4906.1 1017.61    4991 1013.94  4996.2 1010.02  5003.4 1009.83
  5003.7 1009.33  5007.2 1009.33  5011.8 1011.21  5026.3  1012.1  5061.5 1013.39
  5154.8 1012.97  5336.8 1015.96  5531.7 1022.37  5570.7 1023.04  5576.3  1022.5
  5604.5 1023.65  5615.3 1025.08  5620.9 1024.22  5637.6 1025.39  5643.2 1024.37
  5659.8 1025.28    5710 1023.93  5716.6 1024.64  5761.4 1024.35  5824.2 1025.23
#Mann= 3 , 0 , 0
  4639.4     .05       0    4991    .033       0  5026.3     .05       0
Bank Sta=4991,5026.3
XS Rating Curve= 0 ,0
Exp/Cntr=0.3,0.1

Type RM Length L Ch R = 1 ,54347   ,189,189,189
BEGIN DESCRIPTION:
Harts Creek 100.1
END DESCRIPTION:
XS GIS Cut Line= 2
      2280248.89      7208156.71      2279407.33      7207561.46
#Sta/Elev= 30
  4772.6 1025.63  4791.9 1025.24  4842.3 1021.54  4892.8 1017.27  4913.7 1014.77
  4956.2 1012.76  4970.3 1011.03  4983.3 1008.31  4986.8 1008.31  4999.9 1011.76
  5056.5 1010.93    5086 1011.92  5121.7 1011.52  5228.8 1012.19  5386.3 1015.15
  5451.6 1014.71  5466.4 1015.55    5523  1015.4  5617.6 1017.04  5623.9  1017.7
    5630 1016.96  5638.7 1017.59  5644.8 1017.18  5689.2 1018.72  5710.1 1018.66
  5716.2 1017.61  5724.9 1018.59  5739.7 1018.74  5752.4 1017.78  5803.4 1020.99
#Mann= 3 , 0 , 0
  4772.6     .05       0  4970.3    .033       0  4999.9     .05       0
Bank Sta=4970.3,4999.9
XS Rating Curve= 0 ,0
Exp/Cntr=0.3,0.1

Type RM Length L Ch R = 1 ,54158   ,415,415,415
BEGIN DESCRIPTION:
Harts Creek 100.0
END DESCRIPTION:
XS GIS Cut Line= 3
      2280302.93      7208040.69        2280129.        7207860.
      2279579.02      7207260.03
#Sta/Elev= 30
  4749.2    1023  4830.3 1018.15  4893.9 1013.37  4971.8 1010.27  4992.9 1010.28
  4996.5 1009.15  5013.9 1008.66    5028 1010.26  5035.4 1009.65  5063.8 1010.48
  5134.7 1008.73  5169.9 1008.56  5176.7 1009.29  5184.1 1008.31  5190.8 1008.95
  5212.4 1008.39  5233.4 1009.62  5290.1 1009.98  5353.6    1009  5359.3 1007.53
  5362.8 1007.53  5367.8  1009.1  5389.4  1008.8  5410.4 1010.33  5431.9 1012.89
  5629.9 1018.83  5672.4 1021.83  5757.5 1026.15  5792.7 1026.98  5813.9 1028.81
#Mann= 3 , 0 , 0
  4749.2     .05       0  5353.6    .033       0  5367.8     .05       0
Bank Sta=5353.6,5367.8
XS Rating Curve= 0 ,0
Exp/Cntr=0.3,0.1

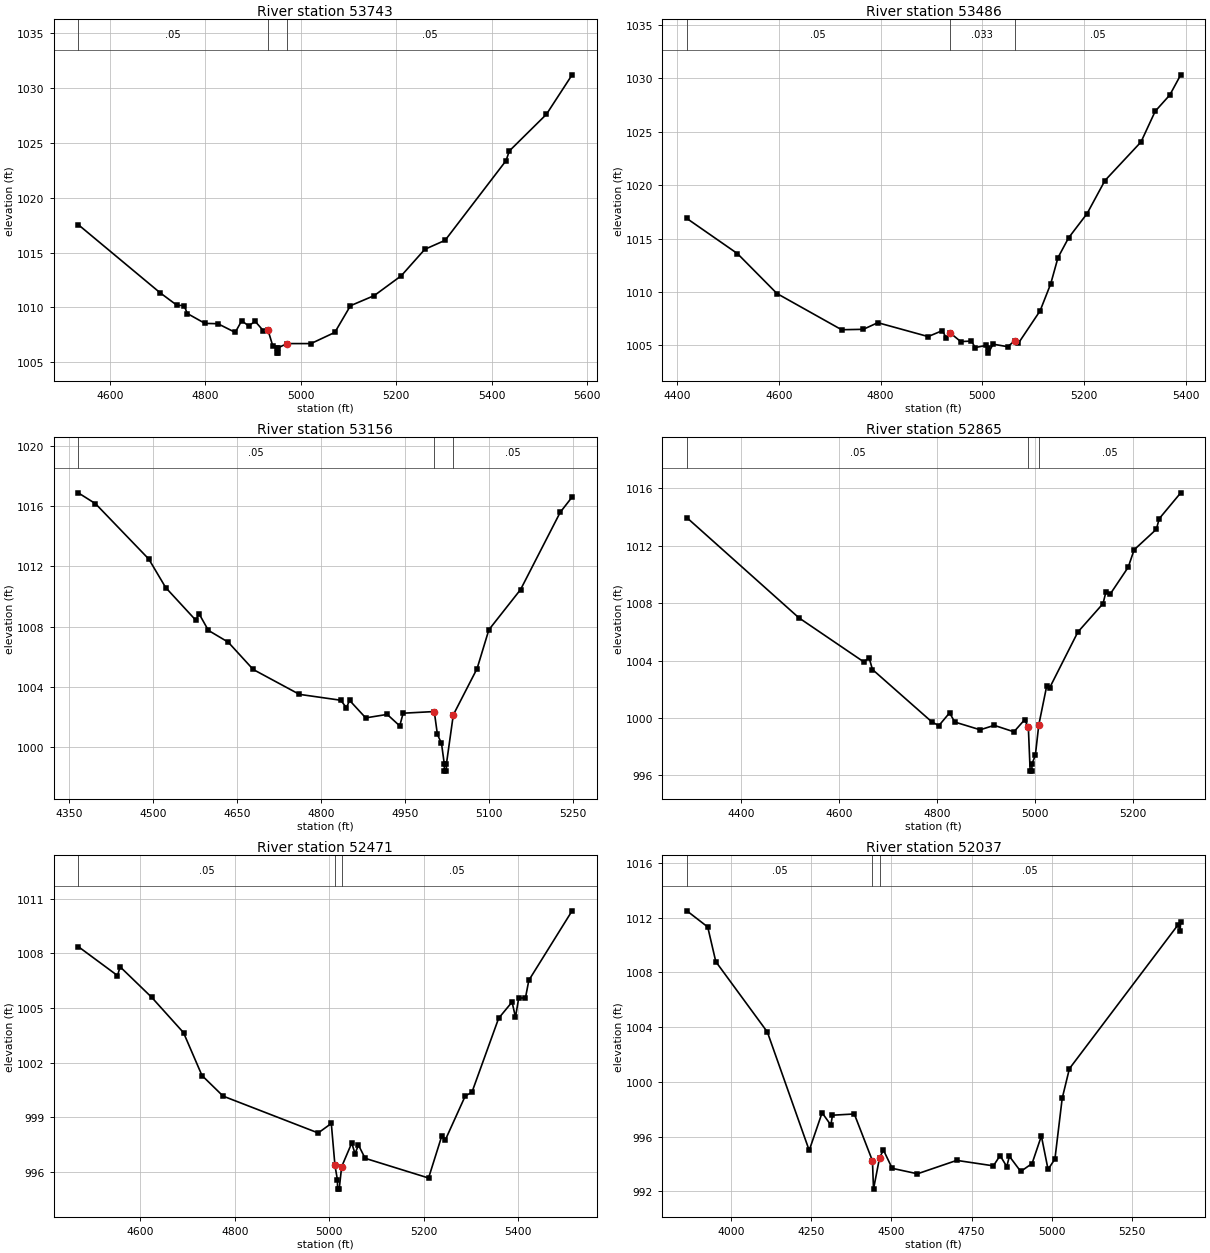
Type RM Length L Ch R = 1 ,53743   ,257,257,257
BEGIN DESCRIPTION:
Harts Creek 99.0
END DESCRIPTION:
XS GIS Cut Line= 4
      2280471.08      7207728.44      2280175.64      7207504.79
      2279985.18      7207496.44      2279662.96      7207150.29
#Sta/Elev= 30
    4534 1017.55  4705.7 1011.33    4741 1010.19  4755.6 1010.18  4762.4 1009.45
  4799.3 1008.55  4826.4 1008.52  4862.7 1007.73  4876.3 1008.79  4890.8 1008.32
  4904.4 1008.74  4921.2  1007.9  4931.2 1007.96  4941.2 1006.52  4949.2 1006.34
  4949.5 1005.84    4953 1005.84  4953.2 1006.34  4971.2 1006.71  5021.3 1006.71
  5071.3 1007.73    5104 1010.16  5153.7 1011.08  5210.4 1012.89  5259.7  1015.3
  5302.2 1016.12  5429.8 1023.38  5436.6 1024.26  5514.3  1027.6  5568.1  1031.2
#Mann= 3 , 0 , 0
    4534     .05       0  4931.2    .033       0  4971.2     .05       0
Bank Sta=4931.2,4971.2
XS Rating Curve= 0 ,0
Exp/Cntr=0.3,0.1

Type RM Length L Ch R = 1 ,53486   ,330,330,330
BEGIN DESCRIPTION:
Harts Creek 98.0
END DESCRIPTION:
XS GIS Cut Line= 3
      2280566.27      7207642.78        2280129.        7207260.
      2279828.96      7207009.97
#Sta/Elev= 30
  4418.8 1016.89  4518.3  1013.6  4596.1 1009.86  4723.3 1006.47    4766 1006.51
  4794.5 1007.13  4893.6 1005.83  4921.6 1006.39  4929.2 1005.69  4935.9 1006.21
  4957.7 1005.36  4978.6 1005.41  4986.2  1004.8  5007.1    1005  5011.6 1004.78
  5011.9 1004.28  5021.4 1005.12  5050.1 1004.88  5064.4 1005.46  5070.9 1005.19
  5113.8 1008.24  5134.7 1010.77    5149 1013.22  5169.8 1015.07  5206.3 1017.35
  5241.4 1020.44  5312.3 1024.05  5340.3 1026.93    5369 1028.45  5390.5 1030.34
#Mann= 3 , 0 , 0
  4418.8     .05       0  4935.9    .033       0  5064.4     .05       0
Bank Sta=4935.9,5064.4
XS Rating Curve= 0 ,0
Exp/Cntr=0.3,0.1

Type RM Length L Ch R = 1 ,53156   ,291,291,291
BEGIN DESCRIPTION:
Harts Creek 97.0
END DESCRIPTION:
XS GIS Cut Line= 3
      2280628.98      7207609.97      2280343.54      7207034.56
        2280179.        7206860.
#Sta/Elev= 30
  4366.4 1016.87  4397.2 1016.15  4492.4 1012.48  4522.6 1010.59  4576.5 1008.42
  4582.1 1008.86  4598.9 1007.75  4634.3 1006.97  4678.9 1005.16  4761.4 1003.51
  4835.2 1003.12  4845.5 1002.63  4851.1 1003.11  4879.9 1001.95  4918.3 1002.18
  4940.7 1001.42  4946.8 1002.26  5002.4 1002.37    5008 1000.85  5015.3 1000.26
  5020.2  998.92  5020.5  998.42    5024  998.42  5024.2  998.92  5036.4 1002.15
  5078.9 1005.22  5099.9 1007.79  5156.6 1010.46  5227.4 1015.58  5248.6 1016.59
#Mann= 3 , 0 , 0
  4366.4     .05       0  5002.4    .033       0  5036.4     .05       0
Bank Sta=5002.4,5036.4
XS Rating Curve= 0 ,0
Exp/Cntr=0.3,0.1

Type RM Length L Ch R = 1 ,52865   ,394,394,394
BEGIN DESCRIPTION:
Harts Creek 96.0
END DESCRIPTION:
XS GIS Cut Line= 3
      2280779.01      7207460.03      2280485.54      7206802.18
        2280329.      7206560.01
#Sta/Elev= 30
  4288.9 1013.96  4517.8 1006.98  4650.3 1003.91  4661.2 1004.19    4668 1003.38
  4789.6  999.72  4803.6  999.47  4825.5 1000.36  4836.1  999.72    4888  999.18
  4916.7  999.49  4956.9  999.04  4978.8  999.88  4986.4  999.34  4990.1   996.3
  4993.6   996.3  4993.8   996.8  5000.7  997.41  5007.7  999.52  5023.7  1002.2
  5030.1 1002.12  5087.5 1005.99  5138.9 1007.97  5144.9  1008.8  5154.1 1008.66
  5190.4 1010.51  5202.4 1011.72  5247.8 1013.15  5253.7 1013.89  5297.6 1015.69
#Mann= 3 , 0 , 0
  4288.9     .05       0  4986.4    .033       0  5007.7     .05       0
Bank Sta=4986.4,5007.7
XS Rating Curve= 0 ,0
Exp/Cntr=0.3,0.1

Type RM Length L Ch R = 1 ,52471   ,434,434,434
BEGIN DESCRIPTION:
Harts Creek 95.0
END DESCRIPTION:
XS GIS Cut Line= 3
      2281062.87      7207335.94      2280822.57      7206855.25
      2280453.99      7206505.38
#Sta/Elev= 30
  4468.3 1008.37  4551.4 1006.78    4557 1007.26  4624.1 1005.58  4691.2 1003.65
  4730.3  1001.3    4775 1000.17  4976.3  998.15  5004.1  998.67  5011.8  996.37
  5017.1  995.57  5017.3  995.07  5020.8  995.07    5026   996.3  5047.4   997.6
  5054.3  997.01  5061.5  997.49  5075.7  996.76    5210  995.68  5238.3  998.01
  5245.2  997.75  5287.7 1000.18  5301.8 1000.38  5358.4 1004.44  5386.8 1005.33
    5394  1004.5  5400.9 1005.55  5415.1 1005.55  5422.3 1006.52  5513.9 1010.33
#Mann= 3 , 0 , 0
  4468.3     .05       0  5011.8    .033       0    5026     .05       0
Bank Sta=5011.8,5026
XS Rating Curve= 0 ,0
Exp/Cntr=0.3,0.1

Type RM Length L Ch R = 1 ,52037   ,506,506,506
BEGIN DESCRIPTION:
Harts Creek 94.0
END DESCRIPTION:
XS GIS Cut Line= 4
      2281848.82      7206830.05      2281246.89       7206783.1
        2280829.        7206460.      2280463.64      7206283.37
#Sta/Elev= 30
  3863.4 1012.49  3928.4 1011.31  3953.5 1008.78    4114 1003.64  4244.4  994.99
  4284.5  997.74  4311.8  996.84  4316.8  997.56  4384.8  997.65  4441.3  994.23
  4444.6  992.16  4463.6  994.47  4475.6  995.01  4502.7  993.68  4581.5  993.28
  4703.8  994.26  4817.9  993.86  4838.7  994.61  4859.5  993.81  4867.7  994.56
    4903  993.45  4938.3  994.03  4967.3  996.04  4988.1   993.6  5009.5  994.36
  5032.1  998.79  5054.6 1000.96  5393.6 1011.49  5399.1 1011.05  5401.2 1011.66
#Mann= 3 , 0 , 0
  3863.4     .05       0  4441.3    .033       0  4463.6     .05       0
Bank Sta=4441.3,4463.6
XS Rating Curve= 0 ,0
Exp/Cntr=0.3,0.1

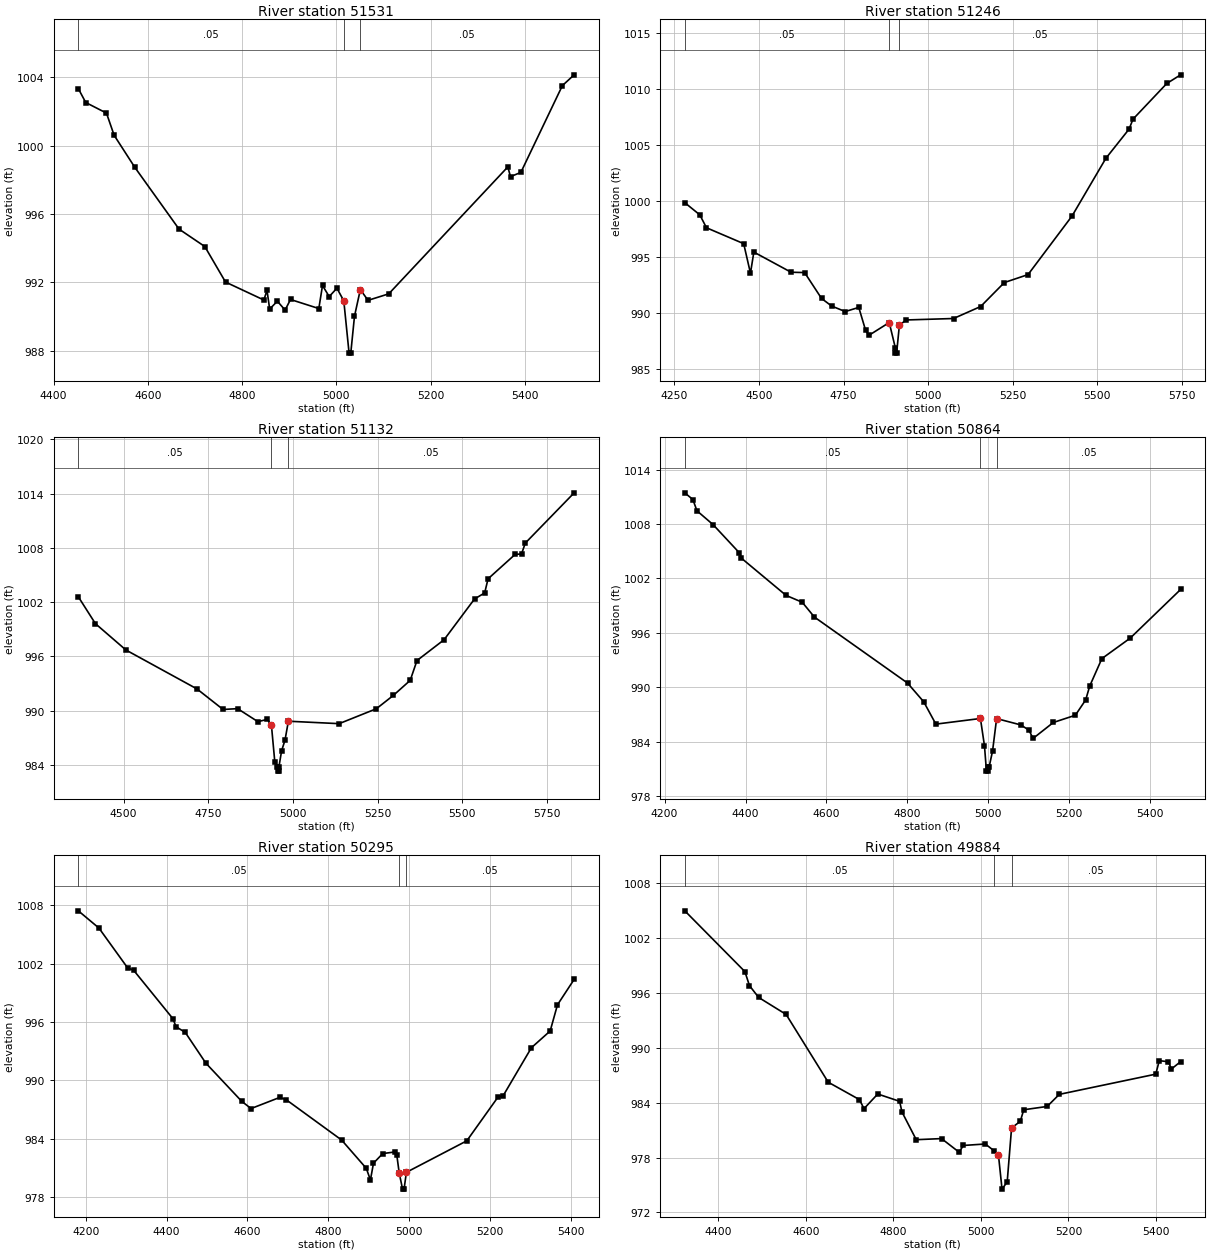
Type RM Length L Ch R = 1 ,51531   ,285,285,285
BEGIN DESCRIPTION:
Harts Creek 93.2
END DESCRIPTION:
XS GIS Cut Line= 2
      2281647.02      7206682.75      2280716.91      7206190.59
#Sta/Elev= 30
  4452.5 1003.33  4468.2 1002.52  4512.2  1001.9  4528.5  1000.6  4572.5  998.72
  4666.2  995.11  4720.9  994.09  4764.9  992.01  4846.2  990.96  4852.9  991.52
  4858.6  990.43  4874.9  990.89  4891.3  990.37  4902.8  990.99  4962.9  990.46
  4970.7  991.81  4984.9  991.16  5001.3  991.65  5015.9  990.91  5027.1  987.85
  5030.7  987.85  5038.6  990.01    5051  991.57  5067.3  990.94  5111.3  991.32
    5364  998.75  5369.7  998.18  5391.7  998.43  5479.8 1003.51  5504.8 1004.14
#Mann= 3 , 0 , 0
  4452.5     .05       0  5015.9    .033       0    5051     .05       0
Bank Sta=5015.9,5051
XS Rating Curve= 0 ,0
Exp/Cntr=0.3,0.1

Type RM Length L Ch R = 1 ,51246   ,114,114,114
BEGIN DESCRIPTION:
Harts Creek 93.1
END DESCRIPTION:
XS GIS Cut Line= 2
      2281982.95      7206185.62      2280518.23      7206162.67
#Sta/Elev= 30
  4281.1  999.87  4325.5  998.78  4345.1  997.63  4455.1  996.21  4475.1  993.57
  4485.1  995.46  4595.1  993.66  4635.1  993.63  4685.1  991.32  4715.1  990.64
  4755.1  990.15  4795.1  990.52  4815.1  988.49  4825.1  988.03  4885.1  989.17
  4902.9  986.94  4903.3  986.44  4906.9  986.44  4915.1  988.93  4935.1   989.4
  5075.1  989.53  5155.2   990.6  5225.2  992.74  5295.2  993.45  5425.2  998.68
  5525.2 1003.83  5593.8 1006.44  5605.2 1007.32  5705.2 1010.51    5746 1011.28
#Mann= 3 , 0 , 0
  4281.1     .05       0  4885.1    .033       0  4915.1     .05       0
Bank Sta=4885.1,4915.1
XS Rating Curve= 0 ,0
Exp/Cntr=0.3,0.1

Type RM Length L Ch R = 1 ,51132   ,268,268,268
BEGIN DESCRIPTION:
Harts Creek 93.0
END DESCRIPTION:
XS GIS Cut Line= 3
      2281979.51      7206088.62      2281487.29      7206095.93
      2280514.65      7206082.98
#Sta/Elev= 30
    4366 1002.59  4416.5  999.62  4506.5  996.71  4716.6   992.4  4793.6  990.13
  4836.6  990.22  4896.6  988.78  4924.9  989.04  4936.6  988.36  4946.6  984.29
  4954.3  983.81  4954.8  983.31  4958.4  983.31  4958.8  983.81  4966.6  985.56
  4976.6  986.73  4986.6  988.83  5136.6  988.56  5246.6  990.21  5296.6  991.68
  5346.6  993.35  5366.6  995.54  5446.6  997.84  5536.6 1002.35  5566.6 1003.02
  5576.6 1004.58  5656.6 1007.28  5675.5 1007.33  5686.6 1008.53    5831 1014.09
#Mann= 3 , 0 , 0
    4366     .05       0  4936.6    .033       0  4986.6     .05       0
Bank Sta=4936.6,4986.6
XS Rating Curve= 0 ,0
Exp/Cntr=0.3,0.1

Type RM Length L Ch R = 1 ,50864   ,569,569,569
BEGIN DESCRIPTION:
Harts Creek 92.0
END DESCRIPTION:
XS GIS Cut Line= 3
      2282128.97        7205810.      2281380.48      7205837.76
      2280904.55      7205853.75
#Sta/Elev= 30
  4249.9 1011.44  4269.9  1010.7  4279.9 1009.46  4319.9 1007.93  4384.9 1004.82
    4390 1004.23    4500 1000.14  4540.1  999.38  4570.1  997.75  4800.2  990.48
  4840.3  988.41  4870.3  985.95  4980.4  986.57  4990.4  983.56  4995.3  980.77
    4999  980.77  4999.5  981.27  5002.1  981.27  5010.4  982.99  5020.4  986.56
  5080.4  985.86  5100.4  985.28  5110.4  984.37  5160.5  986.13    5215  986.93
  5240.5  988.62  5250.5  990.15  5280.5  993.17  5350.6  995.43  5475.1 1000.79
#Mann= 3 , 0 , 0
  4249.9     .05       0  4980.4    .033       0  5020.4     .05       0
Bank Sta=4980.4,5020.4
XS Rating Curve= 0 ,0
Exp/Cntr=0.3,0.1

Type RM Length L Ch R = 1 ,50295   ,411,411,411
BEGIN DESCRIPTION:
Harts Creek 91.0
END DESCRIPTION:
XS GIS Cut Line= 3
      2282079.01        7205560.        2281279.        7205410.
      2280878.96      7205510.01
#Sta/Elev= 30
  4181.9 1007.45  4232.8 1005.68    4304 1001.57  4318.4 1001.35  4415.9  996.35
  4423.5  995.53  4446.4  994.94  4497.3  991.78  4586.3  987.84  4609.2  987.11
  4680.4  988.26  4696.6     988  4833.1  983.87  4894.1  980.96  4904.3  979.76
  4911.9  981.49  4934.8  982.48  4964.5  982.64  4969.6  982.31  4975.5  980.48
  4983.8  978.82  4987.5  978.82  4993.3  980.55  5142.7  983.79    5220   988.3
  5232.9  988.45  5302.5  993.37  5348.9  995.09  5366.9  997.78  5408.2  1000.4
#Mann= 3 , 0 , 0
  4181.9     .05       0  4975.5    .033       0  4993.3     .05       0
Bank Sta=4975.5,4993.3
XS Rating Curve= 0 ,0
Exp/Cntr=0.3,0.1

Type RM Length L Ch R = 1 ,49884   ,506,506,506
BEGIN DESCRIPTION:
Harts Creek 90.0
END DESCRIPTION:
XS GIS Cut Line= 4
      2282040.16      7205480.71       2281490.1      7205310.83
      2281490.25      7205109.53      2281212.59      7204887.19
#Sta/Elev= 30
  4323.6 1004.95  4460.9  998.31  4471.3  996.78  4492.3  995.49  4555.1  993.63
  4651.2  986.23  4722.5  984.33    4733  983.34  4764.4  984.94  4814.4  984.14
  4819.7  982.98  4852.3  979.95  4910.1  980.07  4950.1  978.59  4960.1  979.32
  5010.1  979.48  5030.1  978.74  5040.1  978.29  5048.3  974.55  5060.1  975.34
  5070.1  981.23  5090.1  981.96  5097.9  983.22  5151.4  983.58  5179.1   984.9
  5399.5  987.11  5407.5  988.58  5428.3  988.47  5435.3  987.67  5456.3  988.48
#Mann= 3 ,-1 , 0
  4323.6     .05       0  5030.1    .033       0  5070.1     .05       0
Bank Sta=5040.1,5070.1
XS Rating Curve= 0 ,0
Exp/Cntr=0.3,0.1

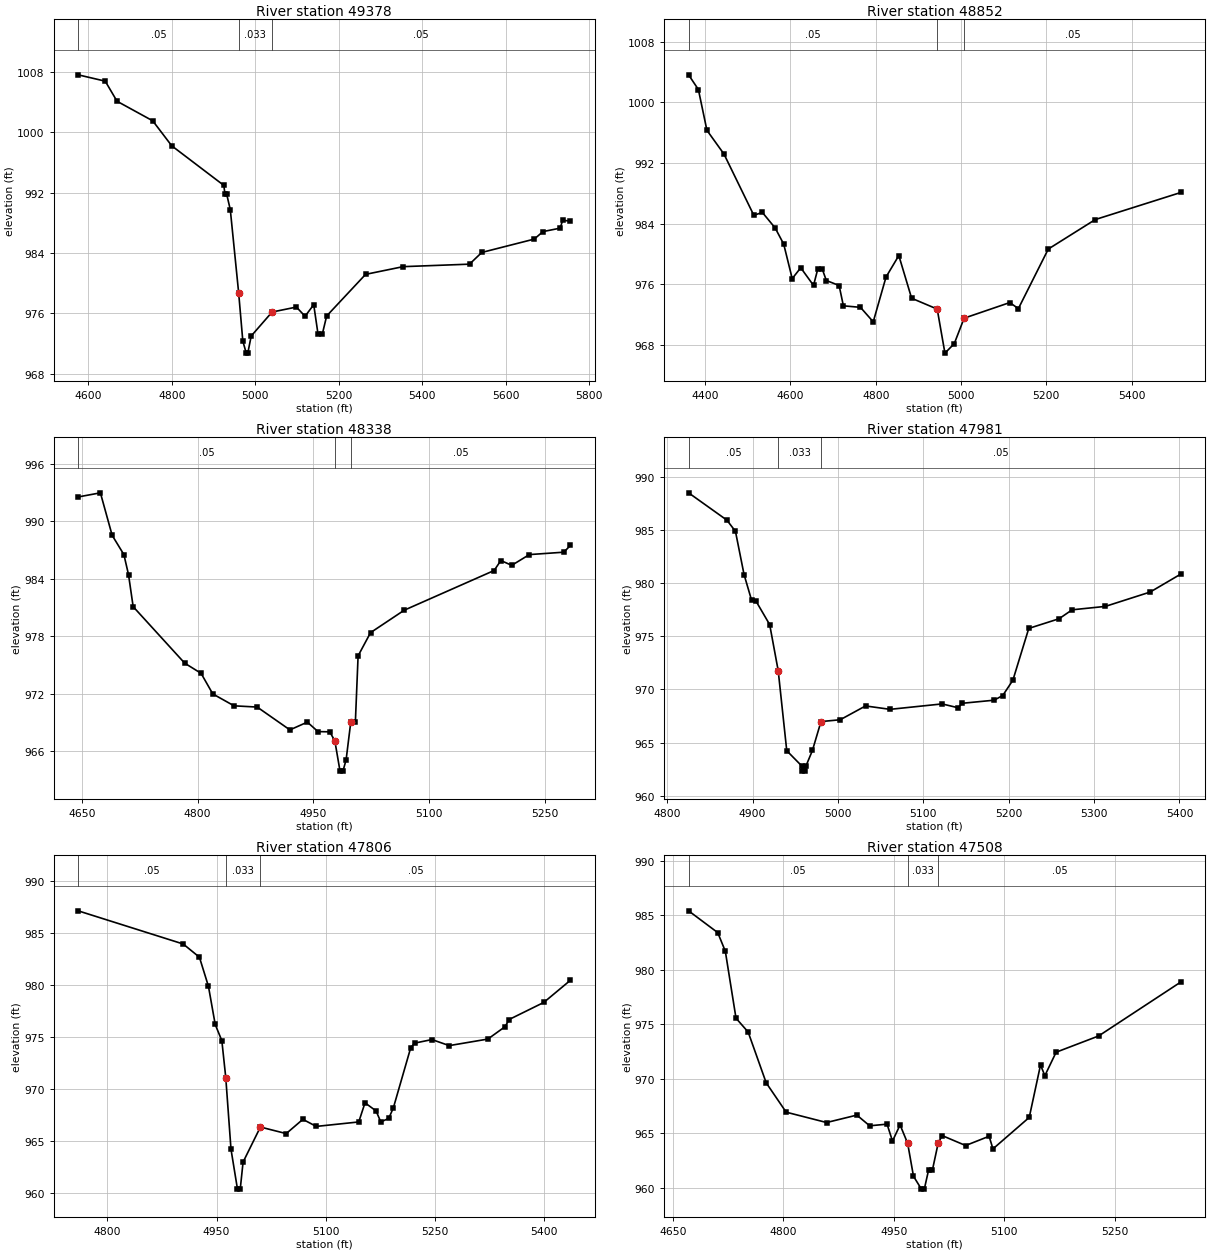
Type RM Length L Ch R = 1 ,49378   ,526,526,526
BEGIN DESCRIPTION:
Harts Creek 89.0
END DESCRIPTION:
XS GIS Cut Line= 4
      2282201.82      7205283.17      2281883.85      7205132.86
      2281876.17      7204989.92       2281215.5      7204810.31
#Sta/Elev= 30
  4575.5  1007.6  4640.4 1006.76  4668.7  1004.1  4754.2 1001.51  4799.8   998.2
  4924.6  992.96  4927.1  991.87  4931.1  991.87  4940.1  989.74  4960.1  978.74
  4970.1  972.34  4978.3  970.75    4982  970.75  4990.2  973.02  5040.2  976.19
  5098.5  976.85  5119.2  975.63    5140  977.16  5150.3  973.27  5160.4  973.23
    5171  975.67  5264.3  981.18  5354.2   982.2  5513.3  982.53  5542.7  984.08
  5668.5  985.85  5689.2  986.84  5730.6   987.3  5736.5  988.34    5755  988.23
#Mann= 3 , 0 , 0
  4575.5     .05       0  4960.1    .033       0  5040.2     .05       0
Bank Sta=4960.1,5040.2
XS Rating Curve= 0 ,0
Exp/Cntr=0.3,0.1

Type RM Length L Ch R = 1 ,48852   ,514,514,514
BEGIN DESCRIPTION:
Harts Creek 88.0
END DESCRIPTION:
XS GIS Cut Line= 3
      2282381.98      7204674.53      2281741.32      7204674.75
      2281228.99        7204710.
#Sta/Elev= 30
  4361.2 1003.63  4384.2 1001.69  4404.2  996.31  4444.2  993.18  4514.2   985.1
  4534.2  985.48  4564.2  983.43  4584.2  981.31  4604.2  976.75  4624.2  978.18
  4654.2  975.85  4664.2  978.03  4674.2  978.08  4684.2   976.5  4714.2  975.84
  4724.2  973.16  4764.2  972.96  4794.2  971.05  4824.2  976.96  4854.2  979.79
  4884.2  974.16  4944.2  972.73  4962.3  966.92  4984.2  968.17  5007.3  971.53
  5114.4  973.59  5134.5  972.79  5204.7  980.65  5314.9  984.54  5515.4  988.11
#Mann= 3 , 0 , 0
  4361.2     .05       0  4944.2    .033       0  5007.3     .05       0
#XS Ineff= 2 , 0
       0  4854.2  979.79               0
Permanent Ineff=
       F       F
Bank Sta=4944.2,5007.3
XS Rating Curve= 0 ,0
Exp/Cntr=0.3,0.1

Type RM Length L Ch R = 1 ,48338   ,357,357,357
BEGIN DESCRIPTION:
Harts Creek 87.0
END DESCRIPTION:
XS GIS Cut Line= 3
      2281779.02      7204209.99      2281479.02      7204401.63
      2281232.46      7204536.86
#Sta/Elev= 30
  4645.4  992.54  4674.2  992.97  4689.4  988.54  4704.6  986.53  4710.6  984.44
  4716.6   981.1  4783.3  975.21  4804.5  974.15  4819.7     972  4847.2  970.76
  4877.2  970.63  4919.5  968.25  4942.1  969.06  4955.9  968.07  4971.1  968.05
  4977.7   967.1  4984.4  963.95  4988.2  963.95  4992.3  965.14  4998.4  969.12
  5004.3  969.12  5007.8  975.97  5023.9  978.39  5067.5  980.73  5183.9  984.87
  5192.6  985.91  5206.7  985.41  5229.5  986.53  5274.1  986.78  5282.6  987.48
#Mann= 3 , 0 , 0
  4645.4     .05       0  4977.7    .033       0  4998.4     .05       0
Bank Sta=4977.7,4998.4
XS Rating Curve= 0 ,0
Exp/Cntr=0.3,0.1

Type RM Length L Ch R = 1 ,47981   ,175,175,175
BEGIN DESCRIPTION:
Harts Creek 86.0
END DESCRIPTION:
XS GIS Cut Line= 3
      2281703.87      7204051.01        2281529.        7204060.
      2281133.61      7204129.79
#Sta/Elev= 30
    4825  988.49  4869.9  985.92  4879.9  984.87    4890   980.8  4898.8  978.39
  4903.8  978.33    4920   976.1    4930  971.76    4940  964.24  4957.4  962.82
  4958.1  962.32  4961.9  962.32  4962.6  962.82  4970.1  964.27  4980.1  966.98
  5002.6  967.15  5032.3  968.45    5061  968.13    5122  968.64  5140.6  968.28
  5145.6   968.7  5182.9  968.99    5193  969.43  5204.9  970.87  5223.5  975.74
    5259  976.65  5274.3  977.49  5313.2  977.81  5365.7  979.16  5401.6  980.85
#Mann= 3 , 0 , 0
    4825     .05       0    4930    .033       0  4980.1     .05       0
Bank Sta=4930,4980.1
XS Rating Curve= 0 ,0
Exp/Cntr=0.3,0.1

Type RM Length L Ch R = 1 ,47806   ,298,298,298
BEGIN DESCRIPTION:
Harts Creek 85.1
END DESCRIPTION:
XS GIS Cut Line= 2
      2281702.81      7203807.42       2281078.6      7204068.45
#Sta/Elev= 30
  4759.7  987.17  4904.1  983.98  4926.4  982.71  4938.8  979.91  4948.1  976.24
  4957.2  974.69  4962.6  971.14  4969.8  964.24  4978.7  960.41  4982.5  960.41
  4986.4  963.01  5010.2  966.38  5045.7  965.75  5068.6  967.12    5087  966.44
  5145.4  966.87    5154  968.71  5169.2  967.93  5175.7  966.87  5186.6  967.21
    5193  968.23  5216.8     974  5222.2  974.45    5246  974.79  5269.8  974.21
  5322.9  974.84  5346.7  976.04  5352.1  976.72  5399.7  978.36  5436.3  980.49
#Mann= 3 , 0 , 0
  4759.7     .05       0  4962.6    .033       0  5010.2     .05       0
Bank Sta=4962.6,5010.2
XS Rating Curve= 0 ,0
Exp/Cntr=0.3,0.1

Type RM Length L Ch R = 1 ,47508   ,474,474,474
BEGIN DESCRIPTION:
Harts Creek 85.0
END DESCRIPTION:
XS GIS Cut Line= 4
      2281359.53      7203441.58        2281279.        7203760.
      2281239.08      7203881.97      2281060.13      7203994.93
#Sta/Elev= 30
  4671.5  985.39  4711.1  983.39  4721.4  981.68  4735.9  975.54  4752.4  974.27
  4776.9  969.61    4804  966.92  4858.9  965.97    4900  966.65  4917.4  965.67
    4941  965.82  4948.4  964.27  4958.7  965.75    4969  964.06  4976.9  961.04
  4987.7  959.86  4991.6  959.86  4997.4  961.61  5002.6  961.61  5010.5   964.1
  5015.9  964.77  5047.7  963.86  5079.6  964.71  5084.8  963.55  5134.1  966.44
  5149.4  971.25  5155.3  970.27  5170.6  972.42  5228.3  973.91  5339.9  978.86
#Mann= 3 , 0 , 0
  4671.5     .05       0    4969    .033       0  5010.5     .05       0
Bank Sta=4969,5010.5
XS Rating Curve= 0 ,0
Exp/Cntr=0.3,0.1

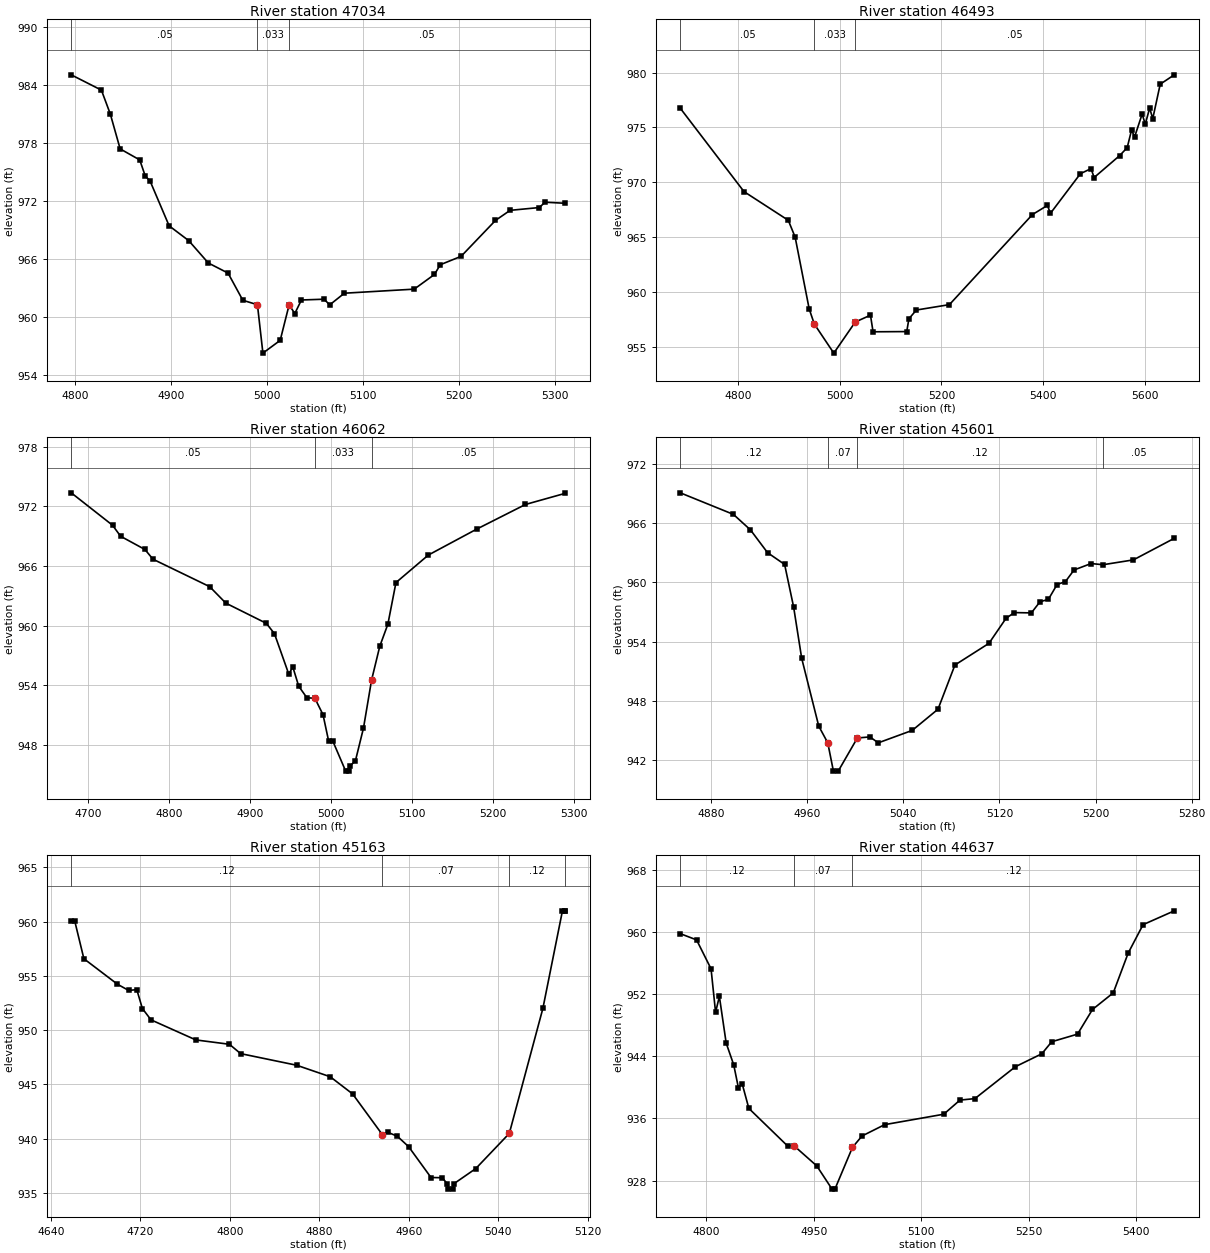
Type RM Length L Ch R = 1 ,47034   ,541,541,541
BEGIN DESCRIPTION:
Harts Creek 84.0
END DESCRIPTION:
XS GIS Cut Line= 3
      2281328.92      7203419.64        2281129.        7203460.
       2280867.7      7203627.26
#Sta/Elev= 30
  4796.2  985.03  4827.6  983.45  4836.9  980.97  4847.1  977.38  4867.5  976.24
  4873.2  974.59  4878.3  974.05  4898.1  969.43  4918.5   967.9  4938.9  965.59
  4959.4  964.55  4974.8  961.74    4990  961.28  4995.7  956.28  5013.7   957.6
    5023  961.27  5028.9  960.37  5035.8  961.77  5059.3  961.85  5065.3  961.27
  5080.5  962.47  5153.2  962.89  5174.3  964.41  5180.3  965.41    5202  966.28
  5237.8  969.99    5253  971.03  5283.4  971.32  5289.4  971.87  5310.4  971.76
#Mann= 3 , 0 , 0
  4796.2     .05       0    4990    .033       0    5023     .05       0
Bank Sta=4990,5023
XS Rating Curve= 0 ,0
Exp/Cntr=0.3,0.1

Type RM Length L Ch R = 1 ,46493   ,431,431,431
BEGIN DESCRIPTION:
Harts Creek 83.0
END DESCRIPTION:
XS GIS Cut Line= 4
      2280959.59      7202946.38      2280773.29      7203070.07
      2280745.73      7203290.58      2280438.48      7203718.32
#Sta/Elev= 30
  4685.8  976.75  4811.2  969.17  4898.4  966.56  4911.9  965.03  4939.6  958.49
  4949.7  957.12    4988  954.48  5030.3  957.31  5060.2  957.93  5065.3  956.42
  5131.6  956.44  5135.9  957.61  5150.6   958.4  5215.6  958.89    5379  967.08
  5408.4  967.91  5414.6   967.2  5473.5   970.8  5494.4  971.26  5500.5  970.45
  5550.9  972.45  5565.6  973.17  5574.1  974.75  5580.3  974.16    5595  976.22
  5601.2   975.3  5609.8  976.77  5615.9   975.8  5630.6  978.94  5658.3  979.79
#Mann= 3 , 0 , 0
  4685.8     .05       0  4949.7    .033       0  5030.3     .05       0
Bank Sta=4949.7,5030.3
XS Rating Curve= 0 ,0
Exp/Cntr=0.3,0.1

Type RM Length L Ch R = 1 ,46062   ,461,461,461
BEGIN DESCRIPTION:
Harts Creek 82.0
END DESCRIPTION:
XS GIS Cut Line= 3
      2280899.94      7202928.45      2280580.39      7202936.16
      2280289.94      7202944.16
#Sta/Elev= 30
  4678.9  973.37  4729.9  970.11  4739.9     969  4769.9  967.67  4779.9  966.69
  4849.9  963.93  4869.9  962.27  4919.9  960.24  4929.9   959.2  4947.6  955.13
  4952.6  955.85  4959.9  953.91  4969.9  952.76  4979.9  952.69  4989.9  951.05
  4996.7  948.45  5001.7  948.45  5017.9  945.37  5021.9  945.37  5022.9  945.87
  5029.9   946.4  5039.9  949.71  5049.9  954.54    5060  957.93    5070  960.15
    5080  964.34    5120  967.11    5180  969.73    5240   972.2  5289.1  973.32
#Mann= 3 , 0 , 0
  4678.9     .05       0  4979.9    .033       0  5049.9     .05       0
Bank Sta=4979.9,5049.9
XS Rating Curve= 0 ,0
Exp/Cntr=0.3,0.1

Type RM Length L Ch R = 1 ,45601   ,438,438,438
BEGIN DESCRIPTION:
Harts Creek 81.0
END DESCRIPTION:
XS GIS Cut Line= 3
      2280680.01      7202398.18        2280579.        7202510.
      2280399.41      7202698.45
#Sta/Elev= 30
  4854.5  969.05  4898.7  966.87  4912.9   965.3  4927.1     963  4941.3  961.81
  4948.8   957.5  4955.5  952.32  4969.7  945.46  4977.2  943.77  4981.9  940.91
  4985.9  940.91  5001.8  944.26  5012.3  944.37  5019.2  943.77  5047.5  945.03
  5068.9  947.17    5083  951.64  5111.3  953.83  5125.5  956.36  5132.4  956.94
  5146.6  956.91  5153.8  958.04  5160.7  958.27    5168  959.78  5174.9  960.07
  5182.1  961.25  5196.3   961.9  5206.2  961.78  5231.5  962.27  5265.5  964.45
#Mann= 4 ,-1 , 0
  4854.5     .12       0  4977.2     .07       0  5001.8     .12       0
  5206.2     .05       0
Bank Sta=4977.2,5001.8
XS Rating Curve= 0 ,0
Exp/Cntr=0.3,0.1

Type RM Length L Ch R = 1 ,45163   ,526,526,526
BEGIN DESCRIPTION:
Harts Creek 80.0
END DESCRIPTION:
XS GIS Cut Line= 3
      2280720.24      7202177.79      2280378.98      7202162.16
        2280279.      7202162.16
#Sta/Elev= 30
  4658.2  960.06  4661.3  960.06  4669.5  956.58  4699.5  954.23  4709.5  953.66
  4716.8  953.73  4721.8  951.99  4729.5  950.95  4769.6   949.1  4799.6   948.7
  4809.6  947.84  4859.7  946.77  4889.7  945.71  4909.7  944.13  4936.3  940.38
  4941.3  940.59  4949.7  940.23  4959.8  939.27  4979.8  936.43  4989.8  936.41
  4994.3  935.86  4995.3  935.36  4999.3  935.36  5000.3  935.86  5019.8  937.25
  5049.8  940.49  5079.8     952  5097.3  960.99  5099.3  960.99  5099.8  960.99
#Mann= 4 ,-1 , 0
  4658.2     .12       0  4936.3     .07       0  5049.8     .12       0
  5099.3     .05       0
Bank Sta=4936.3,5049.8
XS Rating Curve= 0 ,0
Exp/Cntr=0.3,0.1

Type RM Length L Ch R = 1 ,44637   ,201,201,201
BEGIN DESCRIPTION:
Harts Creek 79.0
END DESCRIPTION:
XS GIS Cut Line= 3
       2280859.8      7201830.67      2280554.02      7201730.28
      2280263.88      7201954.96
#Sta/Elev= 30
    4764  959.77  4786.7  958.97  4806.9  955.24  4813.2  949.65  4818.5  951.69
    4828  945.68  4838.5  942.89    4845  939.95  4850.3  940.45  4859.6  937.28
  4913.9  932.42  4922.7  932.46  4954.3  929.88  4975.6  926.89  4979.6  926.89
  5004.1  932.27  5017.4  933.73    5049  935.19  5131.3  936.53    5154  938.35
  5174.8  938.54  5231.3  942.65  5268.1  944.31  5281.9  945.86  5317.9  946.84
  5338.7  950.01  5367.7  952.15  5388.5  957.27  5409.3  960.93  5452.8  962.71
#Mann= 3 , 0 , 0
    4764     .12       0  4922.7     .07       0  5004.1     .12       0
Bank Sta=4922.7,5004.1
XS Rating Curve= 0 ,0
Exp/Cntr=0.3,0.1