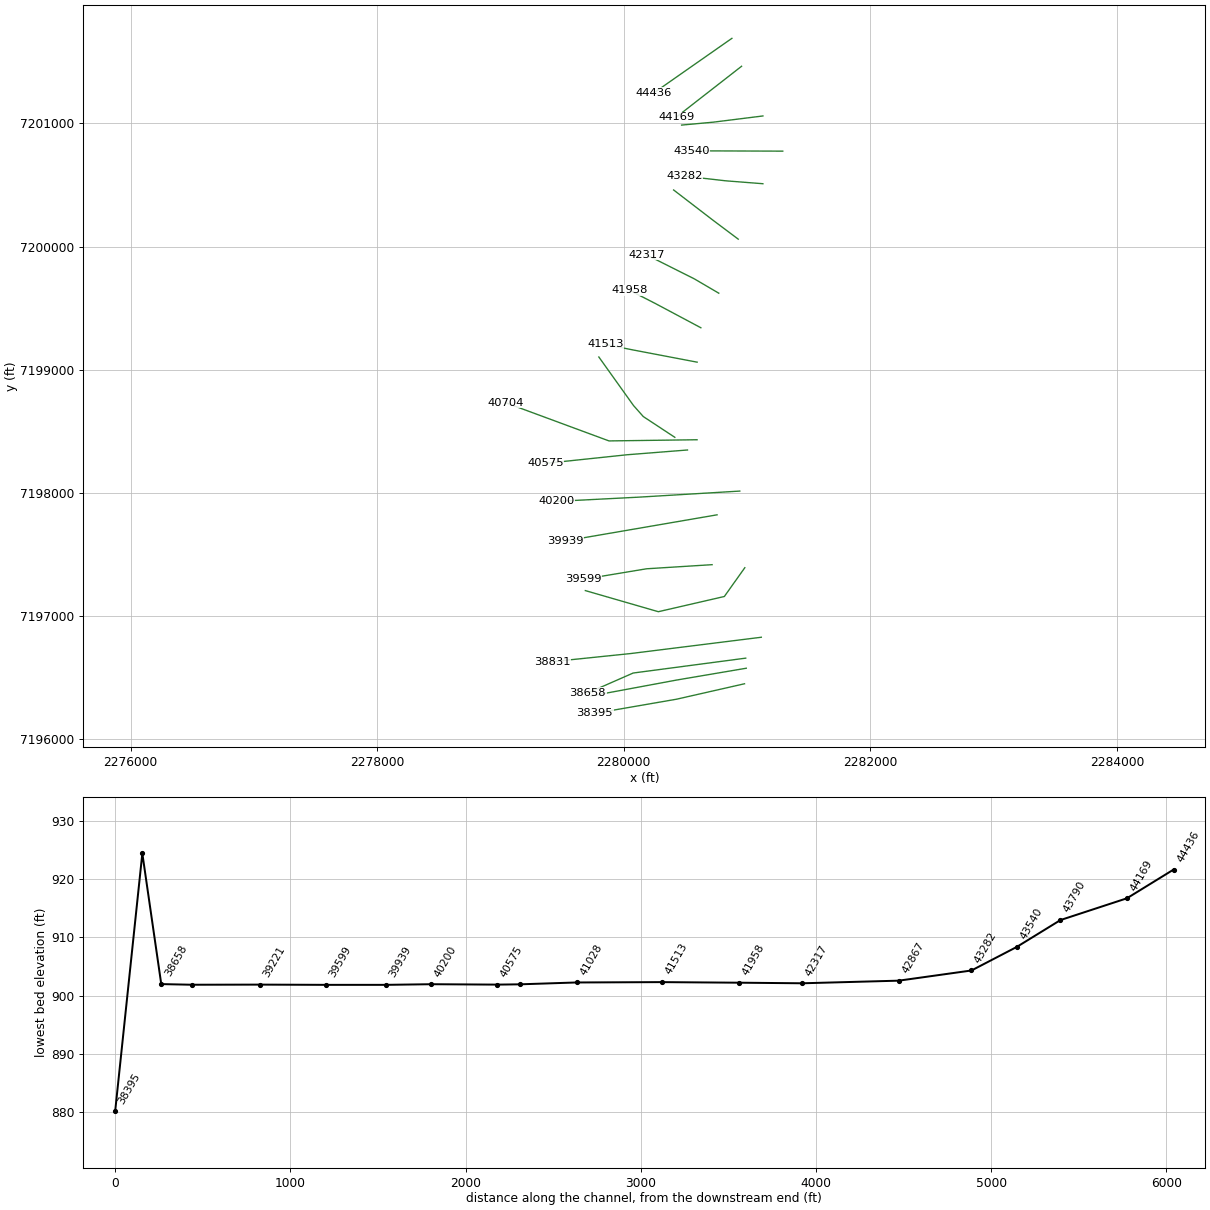
HEC-RAS study Harts Creek.prj: Harts Creek Base Level Engineering

--- Harts Creek.g01 (geometry) --- (continued)

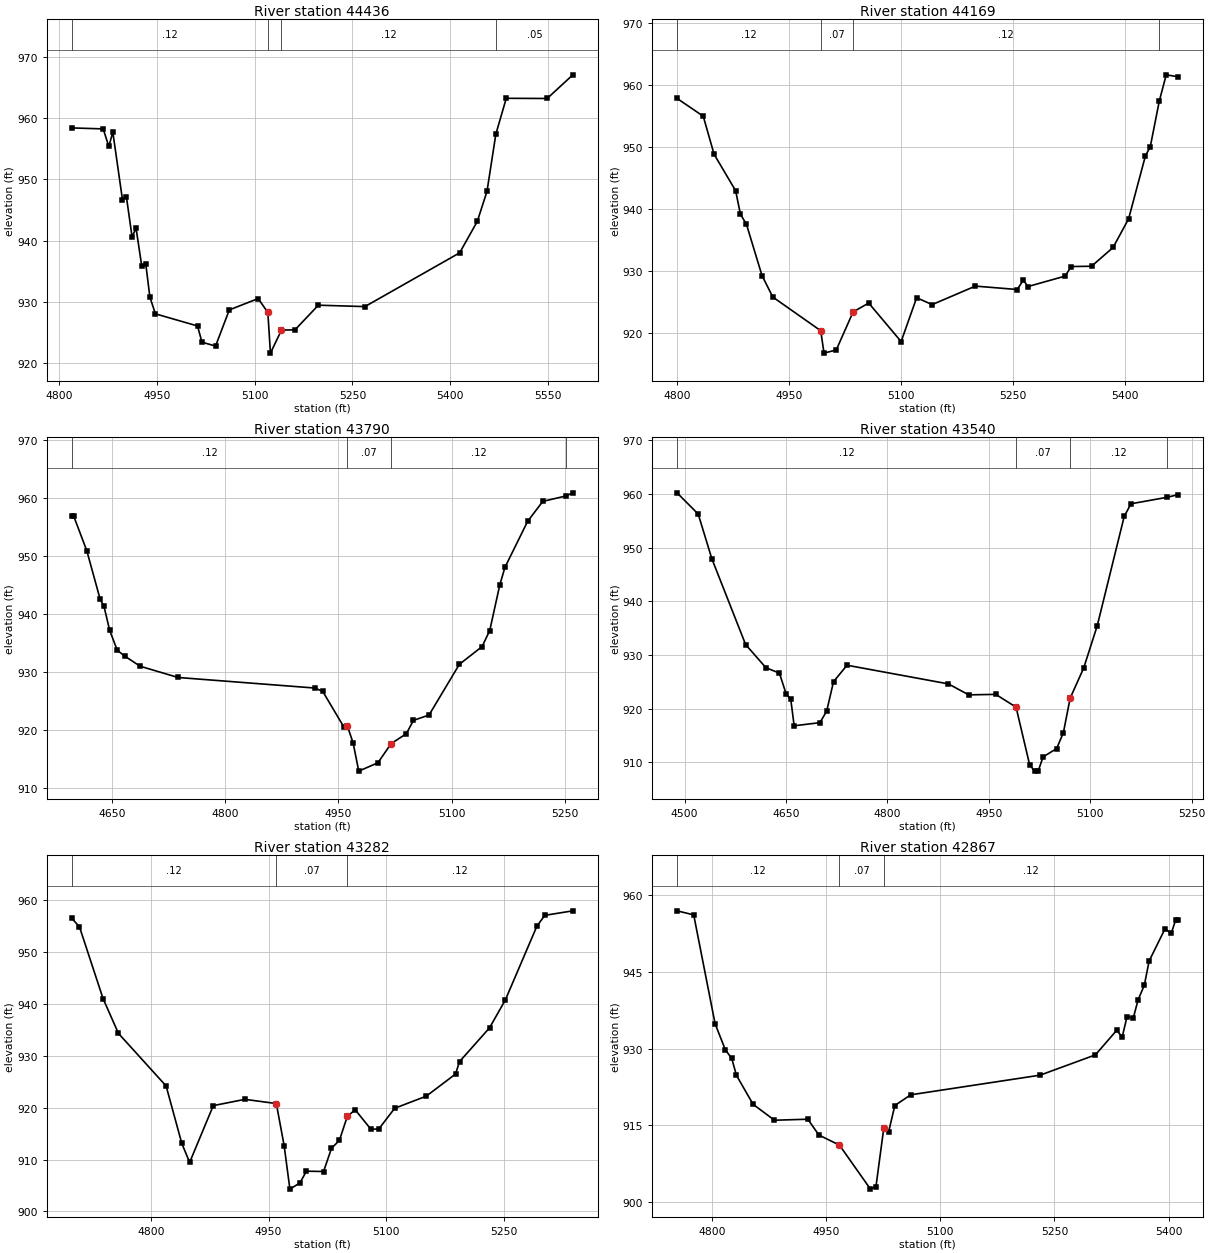
Type RM Length L Ch R = 1 ,44436   ,267,267,267
BEGIN DESCRIPTION:
Harts Creek 78.1
END DESCRIPTION:
XS GIS Cut Line= 2
      2280877.48      7201690.14      2280246.53      7201248.95
#Sta/Elev= 30
  4818.7  958.41  4867.2  958.25  4875.9  955.38    4882  957.73  4896.8  946.71
  4902.9  947.15  4911.6  940.62  4917.7  942.06  4926.5  935.82  4932.6  936.23
  4938.9  930.83  4947.4  928.08  5012.1   926.1  5018.9  923.46  5039.8  922.82
  5060.9  928.72  5105.2  930.57  5120.1  928.31  5124.1  921.67    5141  925.42
  5161.9  925.48  5197.7  929.49  5269.2  929.26  5414.7  938.03  5441.8  943.16
  5456.7  948.06  5470.3  957.39  5486.3  963.24  5549.1  963.21  5588.6  967.07
#Mann= 4 ,-1 , 0
  4818.7     .12       0  5120.1     .07       0    5141     .12       0
  5470.3     .05       0
Bank Sta=5120.1,5141
XS Rating Curve= 0 ,0
Exp/Cntr=0.3,0.1

Type RM Length L Ch R = 1 ,44169   ,379,379,379
BEGIN DESCRIPTION:
Harts Creek 78.0
END DESCRIPTION:
XS GIS Cut Line= 2
      2280955.86      7201463.36      2280426.23       7201050.4
#Sta/Elev= 30
  4800.1  957.88  4835.2     955  4849.7  948.86  4878.6  942.96    4885  939.18
  4893.1  937.53  4913.9  929.26  4928.4  925.78  4992.6  920.34    4997  916.72
  5013.4  917.23    5036  923.38  5056.9  924.81  5100.3  918.59  5121.1  925.67
  5141.9  924.56  5199.8  927.55  5255.9     927    5264  928.52  5270.3  927.48
  5320.1  929.17  5328.2  930.71  5355.4  930.76  5384.3  933.79  5405.1  938.42
  5427.7  948.63  5434.1  950.05  5446.2  957.44  5455.5  961.69  5471.7  961.37
#Mann= 4 ,-1 , 0
  4800.1     .12       0  4992.6     .07       0    5036     .12       0
  5446.2     .05       0
Bank Sta=4992.6,5036
XS Rating Curve= 0 ,0
Exp/Cntr=0.3,0.1

Type RM Length L Ch R = 1 ,43790   ,250,250,250
BEGIN DESCRIPTION:
Harts Creek 77.0
END DESCRIPTION:
XS GIS Cut Line= 3
      2281129.03        7201060.        2280729.        7201010.
      2280469.36      7200985.88
#Sta/Elev= 30
  4596.7  956.97  4599.3  956.97  4616.9  950.91  4634.5  942.59  4639.6  941.35
  4647.1  937.24  4657.2  933.79  4667.3  932.78  4687.4  931.05  4737.8  929.11
  4919.2  927.29  4929.3  926.71    4957  920.65  4962.1  920.69  4969.6  917.82
    4977  912.98  5002.4  914.42  5019.9  917.72    5040  919.42  5049.5  921.73
  5070.1  922.64  5110.3  931.38  5140.4  934.44  5150.5   937.2  5163.8  945.05
  5170.6  948.07  5200.7  956.01  5220.8  959.45  5251.1  960.37  5260.6  960.92
#Mann= 4 ,-1 , 0
  4596.7     .12       0  4962.1     .07       0  5019.9     .12       0
  5251.1     .05       0
Bank Sta=4962.1,5019.9
XS Rating Curve= 0 ,0
Exp/Cntr=0.3,0.1

Type RM Length L Ch R = 1 ,43540   ,258,258,258
BEGIN DESCRIPTION:
Harts Creek 76.1
END DESCRIPTION:
XS GIS Cut Line= 2
      2281290.35       7200774.4      2280548.95      7200777.01
#Sta/Elev= 30
  4488.8   960.2  4520.1  956.24  4540.2  947.94  4590.2  931.94  4620.2  927.62
  4640.2  926.61  4650.2  922.71    4657  921.72    4662   916.8  4700.2  917.38
  4710.2  919.57  4720.2  925.01  4740.2  928.08  4890.2   924.6  4920.2  922.56
  4960.2  922.65  4990.2  920.27  5010.2  909.58  5017.5  908.35  5022.9  908.35
  5030.2     911  5050.2  912.55  5060.2  915.51  5070.2  921.94  5090.2  927.55
  5110.2   935.4  5150.2  955.81  5160.2  958.16  5214.2  959.38  5230.2  959.88
#Mann= 4 ,-1 , 0
  4488.8     .12       0  4990.2     .07       0  5070.2     .12       0
  5214.2     .05       0
Bank Sta=4990.2,5070.2
XS Rating Curve= 0 ,0
Exp/Cntr=0.3,0.1

Type RM Length L Ch R = 1 ,43282   ,415,415,415
BEGIN DESCRIPTION:
Harts Creek 76.0
END DESCRIPTION:
XS GIS Cut Line= 3
      2281128.99        7200510.      2280827.67      7200533.53
      2280493.49      7200571.76
#Sta/Elev= 30
  4699.1  956.59  4709.1  954.92  4739.2  941.06  4758.8  934.35  4819.5  924.21
  4839.5  913.12  4849.5  909.47  4879.6  920.42  4919.8  921.63  4959.9  920.82
  4969.9  912.67  4977.2  904.31    4990  905.51  4998.2  907.77  5020.1  907.71
  5030.2  912.19  5040.3  913.72  5050.3  918.33  5060.4  919.62  5080.5  915.84
  5090.6  915.94  5110.7  919.91    5151  922.25  5188.2  926.51  5193.3  928.91
  5231.5  935.42  5251.6  940.78  5291.9  955.05    5302  957.13  5337.7     958
#Mann= 3 , 0 , 0
  4699.1     .12       0  4959.9     .07       0  5050.3     .12       0
Bank Sta=4959.9,5050.3
XS Rating Curve= 0 ,0
Exp/Cntr=0.3,0.1

Type RM Length L Ch R = 1 ,42867   ,550,550,550
BEGIN DESCRIPTION:
Harts Creek 75.0
END DESCRIPTION:
XS GIS Cut Line= 3
        2280929.        7200060.        2280729.        7200210.
      2280404.74      7200459.28
#Sta/Elev= 30
  4753.9  956.89  4775.8   956.1  4803.9  934.85  4817.4  929.76  4825.8  928.07
    4832  924.77  4853.9  919.11    4882  916.01  4925.8  916.21  4940.4  913.12
  4967.4  911.15  5008.2  902.56  5015.4  903.06  5025.7  914.49    5032   913.7
  5040.2  918.88    5061  920.97  5231.3  924.81  5303.9  928.77  5331.8  933.55
  5339.2  932.29  5345.5  936.25  5353.7  935.95    5360  939.51  5368.2  942.36
  5374.5  947.08  5395.3  953.35  5403.6  952.52  5409.4  955.08  5412.9  955.08
#Mann= 3 , 0 , 0
  4753.9     .12       0  4967.4     .07       0  5025.7     .12       0
Bank Sta=4967.4,5025.7
XS Rating Curve= 0 ,0
Exp/Cntr=0.3,0.1

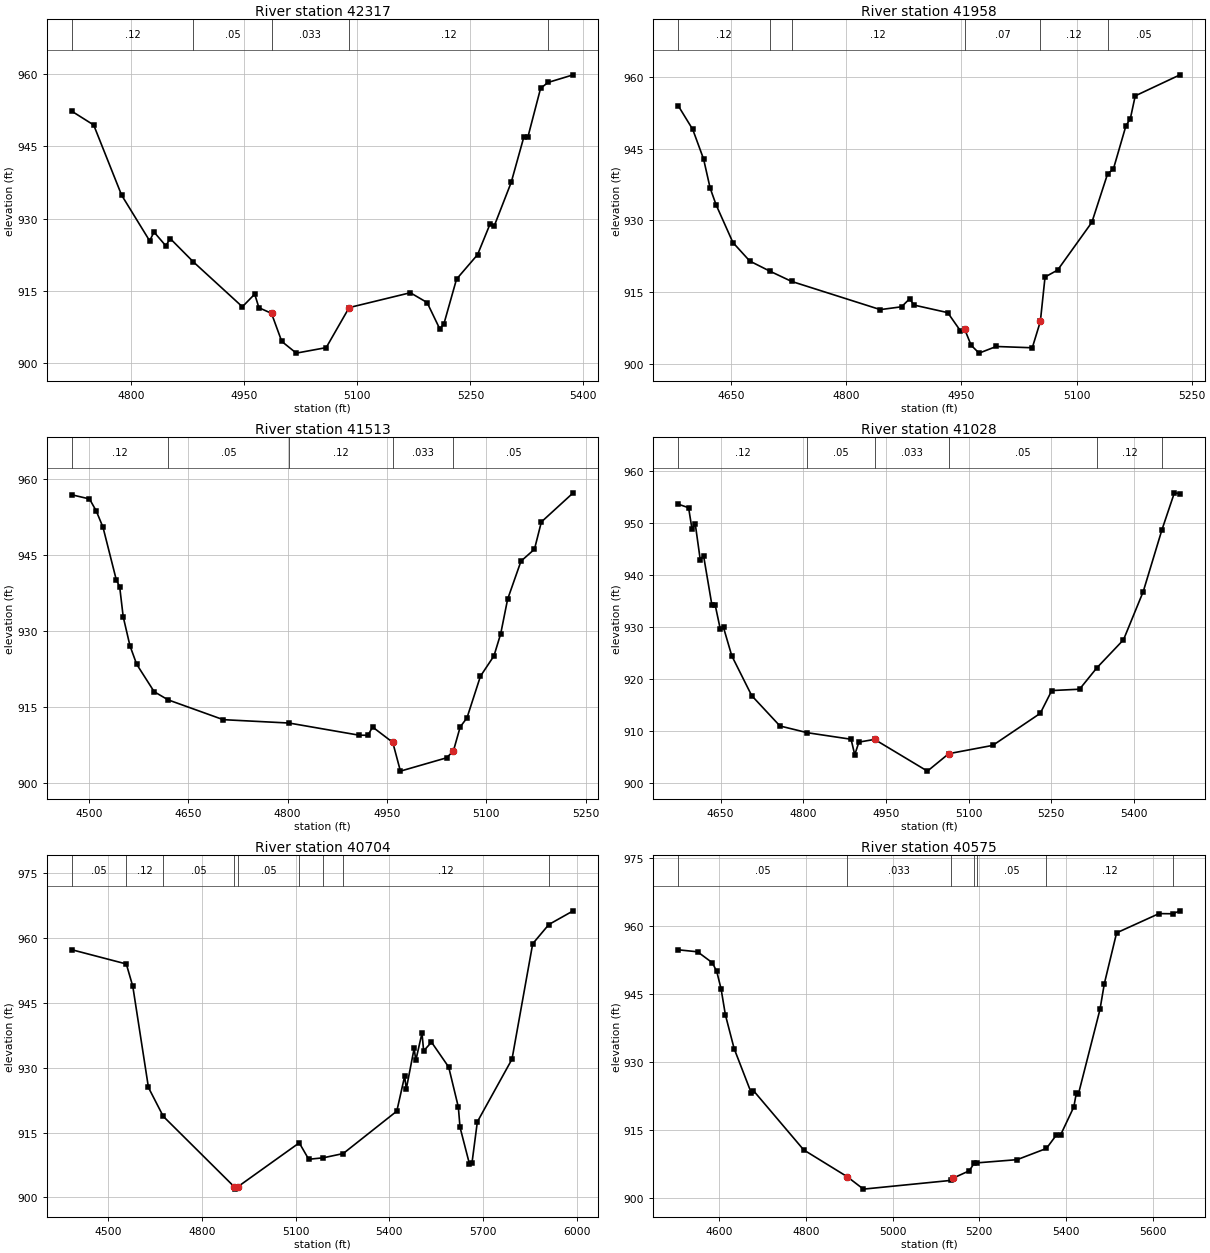
Type RM Length L Ch R = 1 ,42317   ,359,359,359
BEGIN DESCRIPTION:
Harts Creek 74.0
END DESCRIPTION:
XS GIS Cut Line= 3
      2280771.18      7199621.32      2280572.95      7199737.55
      2280183.13       7199933.3
#Sta/Elev= 30
  4720.5  952.28  4749.8   949.4  4786.9  934.85  4824.1  925.39  4829.9  927.21
  4845.6  924.35  4851.4  925.86  4882.1  921.03  4947.2  911.72  4963.6  914.34
  4969.2  911.52  4985.9  910.36  4999.5  904.54  5018.8  902.11  5058.5  903.25
    5089  911.55  5170.2  914.63  5192.5   912.6  5209.3  907.14  5214.8  908.16
  5231.6  917.45  5259.5  922.52  5276.2  928.92  5281.8  928.53  5304.2  937.52
  5320.9  946.88  5326.5     947  5343.2  957.01  5353.1  958.22  5386.5   959.8
#Mann= 5 ,-1 , 0
  4720.5     .12       0  4882.1     .05       0  4985.9    .033       0
    5089     .12       0  5353.1     .05       0
Bank Sta=4985.9,5089
XS Rating Curve= 0 ,0
Exp/Cntr=0.3,0.1

Type RM Length L Ch R = 1 ,41958   ,445,445,445
BEGIN DESCRIPTION:
Harts Creek 73.0
END DESCRIPTION:
XS GIS Cut Line= 3
      2280625.47      7199340.95      2280258.71      7199536.52
      2280047.08      7199644.86
#Sta/Elev= 30
  4581.4  953.88  4600.1  948.98  4614.2   942.8  4622.7  936.75  4630.5  933.22
  4652.4  925.34  4674.4  921.46  4700.7  919.34  4728.8  917.21  4844.4  911.31
  4872.1   911.9  4882.6  913.57  4888.3  912.26  4932.2  910.68  4948.5  906.94
  4954.2  907.25  4962.7  903.86  4973.1  902.21  4995.4   903.6  5042.4  903.33
  5052.9  908.84    5059  918.13  5075.4  919.58    5120  929.57  5140.6  939.76
  5147.9  940.64  5164.4  949.76  5170.1  951.23  5176.5  956.01  5234.8  960.41
#Mann= 6 ,-1 , 0
  4581.4     .12       0  4700.7     .05       0  4728.8     .12       0
  4954.2     .07       0  5052.9     .12       0  5140.6     .05       0
Bank Sta=4954.2,5052.9
XS Rating Curve= 0 ,0
Exp/Cntr=0.3,0.1

Type RM Length L Ch R = 1 ,41513   ,485,485,485
BEGIN DESCRIPTION:
Harts Creek 72.0
END DESCRIPTION:
XS GIS Cut Line= 3
      2280595.53      7199061.45        2280079.        7199160.
      2279851.63      7199205.36
#Sta/Elev= 30
  4473.7  956.98  4500.7  956.15  4510.9  953.77  4521.1  950.55  4541.2  940.14
  4546.3  938.77  4551.6  932.86  4561.8  927.12    4572  923.44  4598.4  918.02
  4619.4  916.41  4702.7  912.49  4802.3  911.82  4907.9  909.42  4921.4   909.4
  4928.3  911.04  4958.8     908  4970.4  902.31  5040.3  904.95  5050.5  906.33
  5060.7  911.06  5070.9  912.83  5091.3  921.09  5111.7  925.11  5121.9  929.49
  5132.3   936.3  5152.5  943.84  5172.9  946.21  5183.3   951.6  5231.4  957.36
#Mann= 5 ,-1 , 0
  4473.7     .12       0  4619.4     .05       0  4802.3     .12       0
  4958.8    .033       0  5050.5     .05       0
Bank Sta=4958.8,5050.5
XS Rating Curve= 0 ,0
Exp/Cntr=0.3,0.1

Type RM Length L Ch R = 1 ,41028   ,324,324,324
BEGIN DESCRIPTION:
Harts Creek 71.0
END DESCRIPTION:
XS GIS Cut Line= 4
      2280414.48      7198451.47      2280158.71      7198619.97
        2280079.        7198710.      2279798.24      7199103.47
#Sta/Elev= 30
  4573.5  953.66    4592  952.99  4598.1  948.91  4604.1  949.84  4613.1  942.99
  4619.1  943.77  4634.2  934.29  4640.2  934.25  4649.3  929.69  4655.3  929.92
  4670.3  924.47  4706.5  916.79  4757.7  910.95  4807.3  909.65  4886.7  908.39
  4893.4   905.4  4900.9  907.84  4929.4  908.36  5025.2  902.25  5063.9  905.61
  5143.8  907.21  5229.9  913.38  5250.8  917.77  5301.2  918.03  5332.6  922.15
  5380.9  927.55  5416.7  936.83  5450.6  948.72  5473.2  955.86  5483.4  955.69
#Mann= 6 ,-1 , 0
  4573.5     .12       0  4807.3     .05       0  4929.4    .033       0
  5063.9     .05       0  5332.6     .12       0  5450.6     .05       0
Bank Sta=4929.4,5063.9
XS Rating Curve= 0 ,0
Exp/Cntr=0.3,0.1

Type RM Length L Ch R = 1 ,40704   ,129,129,129
BEGIN DESCRIPTION:
Harts Creek 70.5
END DESCRIPTION:
XS GIS Cut Line= 3
      2280594.83      7198431.76      2279880.49      7198422.22
      2279045.35      7198731.02
#Sta/Elev= 30
  4383.7   957.2  4558.7   953.9  4579.5  948.71  4629.5  925.39  4676.8  918.74
  4904.6  902.43    4906  901.93  4914.6  902.43    5112  912.61  5142.3  908.82
  5188.7  909.16  5252.6  910.14  5424.1  919.93  5449.2  927.99  5454.5  925.06
  5479.6  934.42  5484.9  931.65  5504.7  937.95    5510  933.83  5535.1  935.86
  5590.1  930.11    5621  920.88  5626.3  916.24  5656.7   907.7  5664.8  908.05
  5681.8  917.47  5792.7  931.93  5858.9  958.57  5910.6  963.01  5988.5  966.17
#Mann= 9 ,-1 , 0
  4383.7     .05       0  4558.7     .12       0  4676.8     .05       0
  4904.6    .033       0  4914.6     .05       0    5112     .12       0
  5188.7     .05       0  5252.6     .12       0  5910.6     .05       0
#XS Ineff= 2 , 0
       0                  5504.7       0  937.95
Permanent Ineff=
       F       F
Bank Sta=4904.6,4914.6
XS Rating Curve= 0 ,0
Exp/Cntr=0.3,0.1

Type RM Length L Ch R = 1 ,40575   ,375,375,375
BEGIN DESCRIPTION:
Harts Creek 70.0
END DESCRIPTION:
XS GIS Cut Line= 3
      2280517.11      7198348.57        2280029.        7198310.
      2279365.51      7198239.98
#Sta/Elev= 30
    4506  954.66  4550.3  954.22  4584.3   951.8  4594.4  949.89  4604.4  946.05
  4614.4   940.3  4634.5  932.88  4673.9  923.13    4679  923.61    4795  910.53
  4895.3  904.62  4932.7  901.88    5135  903.81    5140  904.33  5176.6  905.91
  5188.2  907.58  5195.6  907.68  5287.2  908.38  5354.7  910.85  5377.7  913.81
  5387.8   913.9    5418  920.02  5423.7  923.08  5428.7  922.91  5478.3  941.52
  5488.3  947.19  5516.6   958.4  5614.5  962.65  5646.3  962.61  5662.8  963.26
#Mann= 7 ,-1 , 0
    4506     .05       0  4895.3    .033       0    5135     .05       0
  5188.2     .12       0  5195.6     .05       0  5354.7     .12       0
  5646.3     .05       0
Bank Sta=4895.3,5140
XS Rating Curve= 0 ,0
Exp/Cntr=0.3,0.1

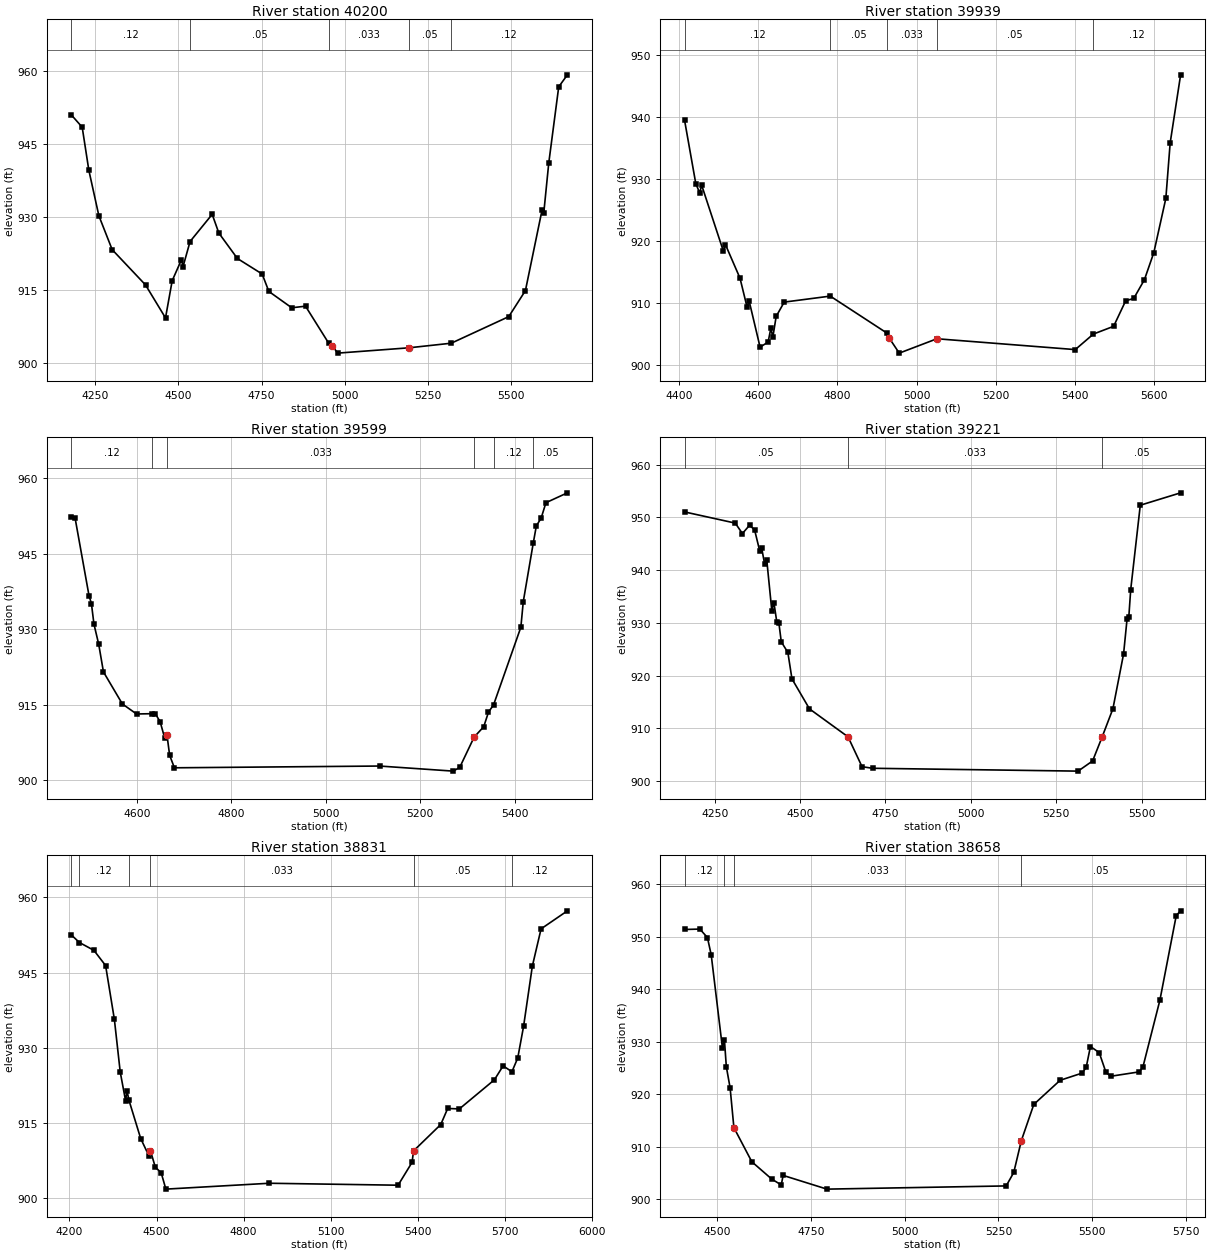
Type RM Length L Ch R = 1 ,40200   ,261,261,261
BEGIN DESCRIPTION:
Harts Creek 69.0
END DESCRIPTION:
XS GIS Cut Line= 3
      2280941.51      7198015.05      2280126.95      7197965.99
      2279452.97      7197931.35
#Sta/Elev= 30
  4178.1  950.91  4210.7  948.39  4230.7  939.53  4260.8  930.19  4300.8  923.22
    4401  915.97  4461.1  909.19  4481.2  916.84  4508.9  921.12  4513.9  919.75
  4534.9  924.89  4601.4  930.48  4621.4  926.63  4677.2   921.4  4751.6  918.21
  4771.7  914.63  4840.5  911.27  4881.9   911.6    4952  903.94    4962   903.5
  4978.5  901.95  5192.3  903.04  5319.9  903.99  5492.7  909.45  5542.8   914.8
  5592.9  931.39  5597.9  930.72  5612.9     941  5642.9  956.69    5669  959.15
#Mann= 5 ,-1 , 0
  4178.1     .12       0  4534.9     .05       0    4952    .033       0
  5192.3     .05       0  5319.9     .12       0
Bank Sta=4962,5192.3
XS Rating Curve= 0 ,0
Exp/Cntr=0.3,0.1

Type RM Length L Ch R = 1 ,39939   ,340,340,340
BEGIN DESCRIPTION:
Harts Creek 68.1
END DESCRIPTION:
XS GIS Cut Line= 2
      2280757.03      7197822.27      2279522.29      7197609.77
#Sta/Elev= 30
  4413.9  939.47  4442.3  929.22  4452.1  927.73  4457.2  928.95    4512   918.3
  4517.1  919.38    4554  913.94  4571.9  909.24    4577  910.27  4604.7   902.8
    4625  903.64  4631.9  905.86  4636.9  904.41  4645.3  907.77  4665.6  910.08
  4781.9  911.05  4926.4  905.02  4931.5  904.21  4956.2  901.84  5051.3  904.16
  5400.7  902.41  5446.5  904.92  5497.6  906.17  5528.1   910.3  5548.4  910.67
  5575.4   913.7  5599.1  918.07  5629.5  926.84  5640.4  935.78  5666.8  946.79
#Mann= 5 ,-1 , 0
  4413.9     .12       0  4781.9     .05       0  4926.4    .033       0
  5051.3     .05       0  5446.5     .12       0
Bank Sta=4931.5,5051.3
XS Rating Curve= 0 ,0
Exp/Cntr=0.3,0.1

Type RM Length L Ch R = 1 ,39599   ,378,378,378
BEGIN DESCRIPTION:
Harts Creek 68.0
END DESCRIPTION:
XS GIS Cut Line= 3
      2280716.84      7197417.63      2280185.25      7197384.31
      2279674.11      7197299.25
#Sta/Elev= 30
  4460.9  952.28  4468.8  952.08  4498.3  936.68  4503.4   935.1  4508.8  931.01
  4518.9     927  4528.9  921.53    4569  915.17    4599  913.18  4631.6  913.24
  4639.1   913.2  4649.1  911.61  4658.4  908.48  4663.5     909  4669.1  904.99
  4679.2   902.5  5113.8  902.85  5269.9  901.84  5283.7   902.6  5314.1  908.59
  5334.4  910.65  5344.5  913.54  5355.3     915  5413.1   930.4  5418.2  935.47
  5439.3  947.07  5445.9  950.51  5456.1  952.06  5466.2  955.11  5511.7  957.07
#Mann= 6 ,-1 , 0
  4460.9     .12       0  4631.6     .05       0  4663.5    .033       0
  5314.1     .05       0  5355.3     .12       0  5439.3     .05       0
Bank Sta=4663.5,5314.1
XS Rating Curve= 0 ,0
Exp/Cntr=0.3,0.1

Type RM Length L Ch R = 1 ,39221   ,390,390,390
BEGIN DESCRIPTION:
Harts Creek 67.0
END DESCRIPTION:
XS GIS Cut Line= 4
      2280982.23      7197392.98      2280816.05      7197159.33
      2280280.85      7197035.89      2279688.61      7197207.25
#Sta/Elev= 30
  4161.9  951.02  4310.4   948.9  4331.3  946.92  4352.2  948.49    4367  947.62
  4381.7   943.7  4387.9   944.1  4396.5   941.1  4402.6  941.92  4417.4   932.3
  4423.5  933.84  4432.1  930.13  4438.3  929.87  4445.1   926.4  4464.4  924.38
  4476.4  919.37  4527.7  913.68  4640.6  908.38  4681.6  902.72  4712.4  902.42
  5314.1  901.88  5356.7  903.81    5385  908.42  5416.2  913.71  5447.4   924.1
  5457.5  930.65  5462.7  931.08  5468.3  936.31  5496.3  952.29  5614.4  954.64
#Mann= 3 , 0 , 0
  4161.9     .05       0  4640.6    .033       0    5385     .05       0
Bank Sta=4640.6,5385
XS Rating Curve= 0 ,0
Exp/Cntr=0.3,0.1

Type RM Length L Ch R = 1 ,38831   ,173,173,173
BEGIN DESCRIPTION:
Harts Creek 66.15
END DESCRIPTION:
XS GIS Cut Line= 3
      2281116.09      7196828.54      2280057.53      7196696.31
      2279418.82      7196630.22
#Sta/Elev= 30
  4206.6   952.5  4234.3  950.99  4284.3  949.43  4324.6   946.4  4354.8  935.69
    4375  925.19  4393.3  919.51  4398.4  921.43  4404.8  919.62  4445.5  911.94
    4474  908.48    4479  909.51  4495.9  906.24  4516.1  905.11  4532.2  901.86
  4888.9  903.03  5332.2  902.64  5380.4   907.2  5385.4  909.47  5479.2  914.73
  5503.1  917.93  5543.3  917.84    5664  923.64  5694.1  926.42  5724.3  925.24
  5744.4  927.98  5764.5  934.29  5794.7  946.28  5824.8  953.71  5915.5   957.3
#Mann= 6 ,-1 , 0
  4206.6     .05       0  4234.3     .12       0  4404.8     .05       0
    4479    .033       0  5385.4     .05       0  5724.3     .12       0
Bank Sta=4479,5385.4
XS Rating Curve= 0 ,0
Exp/Cntr=0.3,0.1

Type RM Length L Ch R = 1 ,38658   ,108,108,108
BEGIN DESCRIPTION:
Harts Creek 66.1
END DESCRIPTION:
XS GIS Cut Line= 3
      2280989.44      7196658.86      2280076.49      7196538.05
      2279708.37      7196376.29
#Sta/Elev= 30
  4412.7  951.36  4453.5  951.44  4473.7  949.83  4483.8  946.54  4513.7  928.83
    4519  930.43  4524.1  925.27  4534.2  921.24  4544.3  913.67  4592.1  907.18
  4645.1  903.89  4670.6  902.77  4675.6  904.58  4792.5  901.97  5270.5  902.58
  5290.7  905.14  5310.9  911.19  5344.2  918.09  5414.3  922.67  5472.9  924.04
  5483.8  925.11  5495.2   929.1  5518.6  927.94  5536.5   924.2  5549.3  923.44
  5625.8  924.28  5635.4  925.27  5680.4   937.9  5724.1  954.02  5735.7  954.91
#Mann= 4 ,-1 , 0
  4412.7     .12       0    4519     .05       0  4544.3    .033       0
  5310.9     .05       0
Bank Sta=4544.3,5310.9
XS Rating Curve= 0 ,0
Exp/Cntr=0.3,0.1

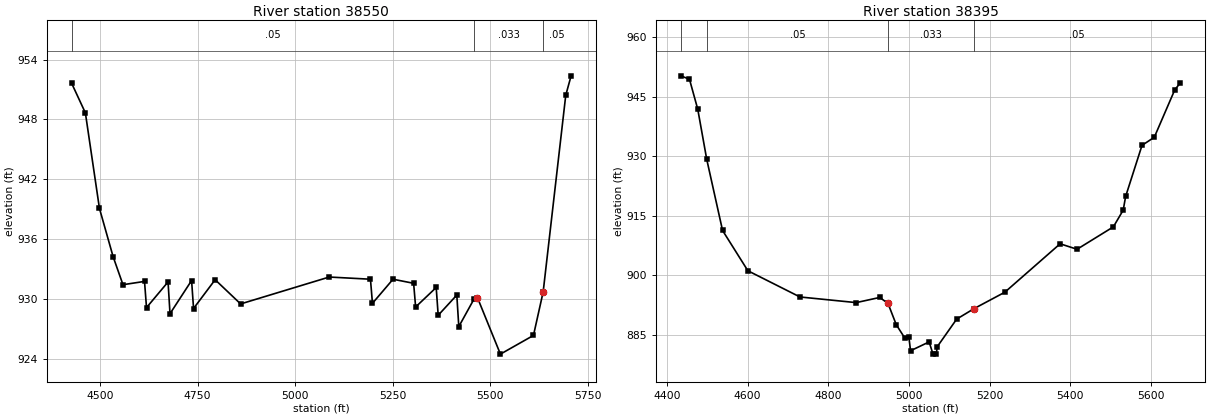
Type RM Length L Ch R = 1 ,38550   ,155,155,155
BEGIN DESCRIPTION:
Harts Creek 66.0
END DESCRIPTION:
XS GIS Cut Line= 3
        2280994.      7196577.04      2280431.47      7196481.52
      2279734.22      7196351.81
#Sta/Elev= 30
  4427.1  951.66  4462.6  948.66  4498.6  939.08  4533.6  934.23  4558.9  931.41
  4614.1  931.74  4619.2  929.11  4674.4  931.69  4679.4   928.5  4734.7  931.83
  4739.7  929.02    4795  931.91  4860.3  929.48  5087.3  932.18  5192.9  931.96
    5198  929.54  5250.7  931.96  5303.5  931.55  5308.6  929.17  5361.3  931.13
  5366.4  928.34  5414.1  930.37  5419.2   927.2  5457.9  929.95  5466.9  930.12
  5525.8  924.44  5610.5  926.32  5635.3  930.68  5693.2  950.43  5706.9  952.38
#Mann= 3 ,-1 , 0
  4427.1     .05       0  5457.9    .033       0  5635.3     .05       0
Bank Sta=5466.9,5635.3
XS Rating Curve= 0 ,0
Exp/Cntr=0.3,0.1

Type RM Length L Ch R = 1 ,38395   ,546,546,546
BEGIN DESCRIPTION:
Harts Creek 65.0
END DESCRIPTION:
XS GIS Cut Line= 3
      2280979.83      7196450.98      2280428.63      7196325.65
       2279765.1      7196210.58
#Sta/Elev= 30
  4434.6  950.28    4456  949.41  4476.5  941.86  4498.8  929.21    4538  911.29
  4600.8  901.13    4730  894.52  4869.4   893.1  4927.7   894.4  4948.2   892.9
  4968.7  887.53  4989.2  884.27  4999.9  884.48  5004.1  880.96  5050.2  883.19
  5059.8  880.11  5067.8  880.11  5070.5  882.01  5118.5  888.94  5161.9   891.6
  5237.9  895.72    5375  907.93    5417  906.55    5507   912.2  5531.4  916.42
  5537.4  919.86    5578  932.75  5608.5  934.79  5659.2  946.74  5673.3  948.54
#Mann= 4 ,-1 , 0
  4434.6     .12       0  4498.8     .05       0  4948.2    .033       0
  5161.9     .05       0
Bank Sta=4948.2,5161.9
XS Rating Curve= 0 ,0
Exp/Cntr=0.3,0.1