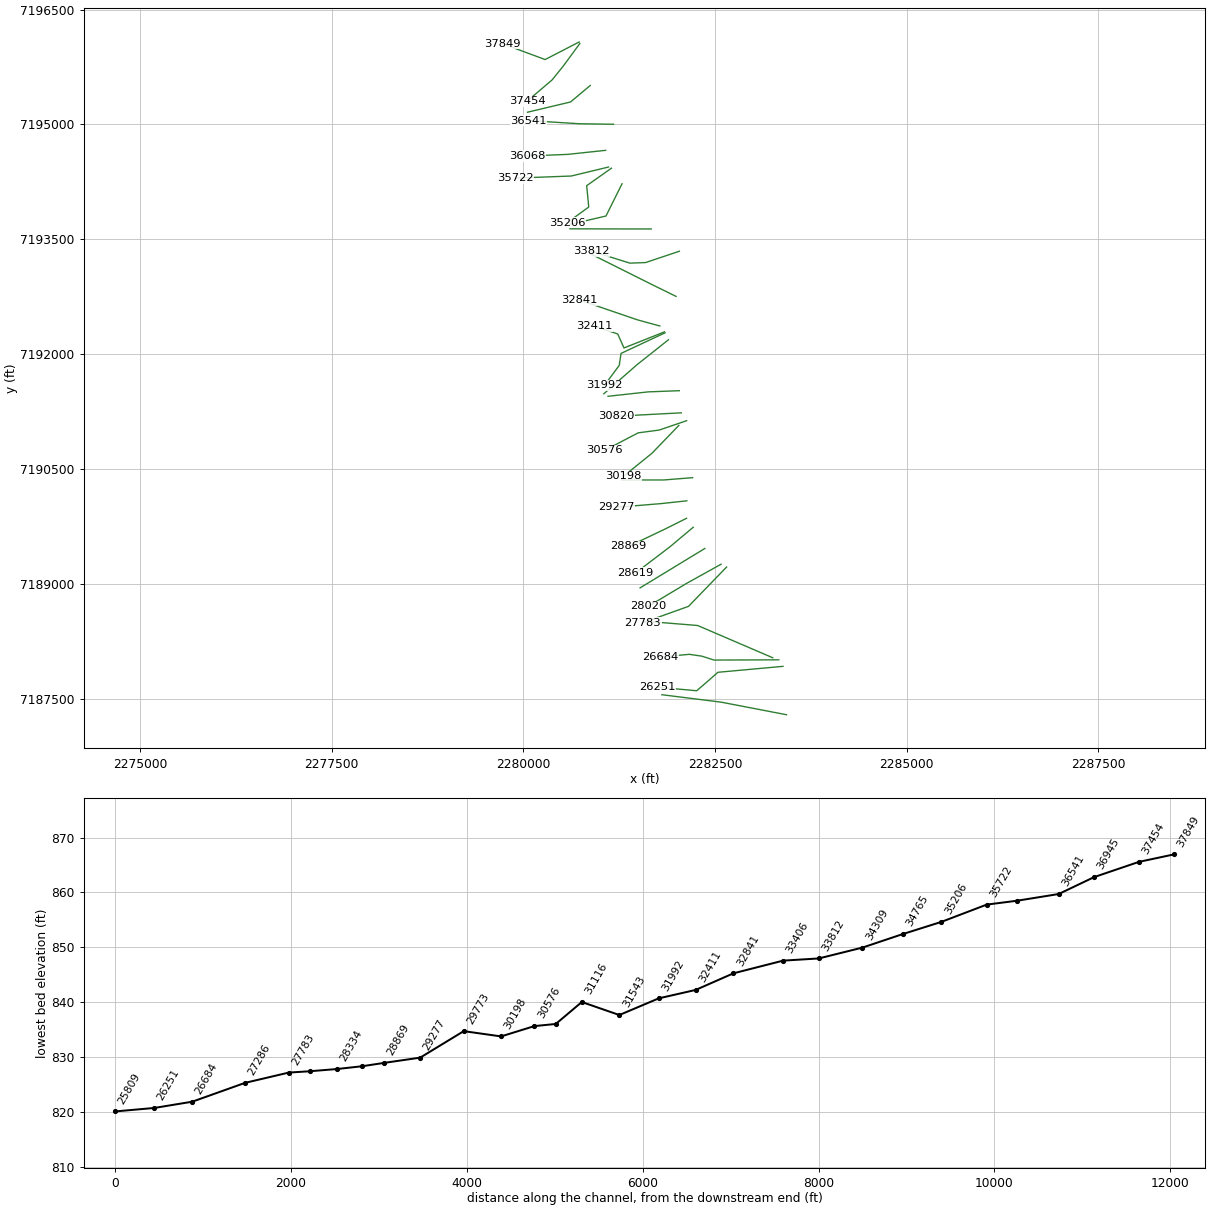
HEC-RAS study Harts Creek.prj: Harts Creek Base Level Engineering

--- Harts Creek.g01 (geometry) --- (continued)

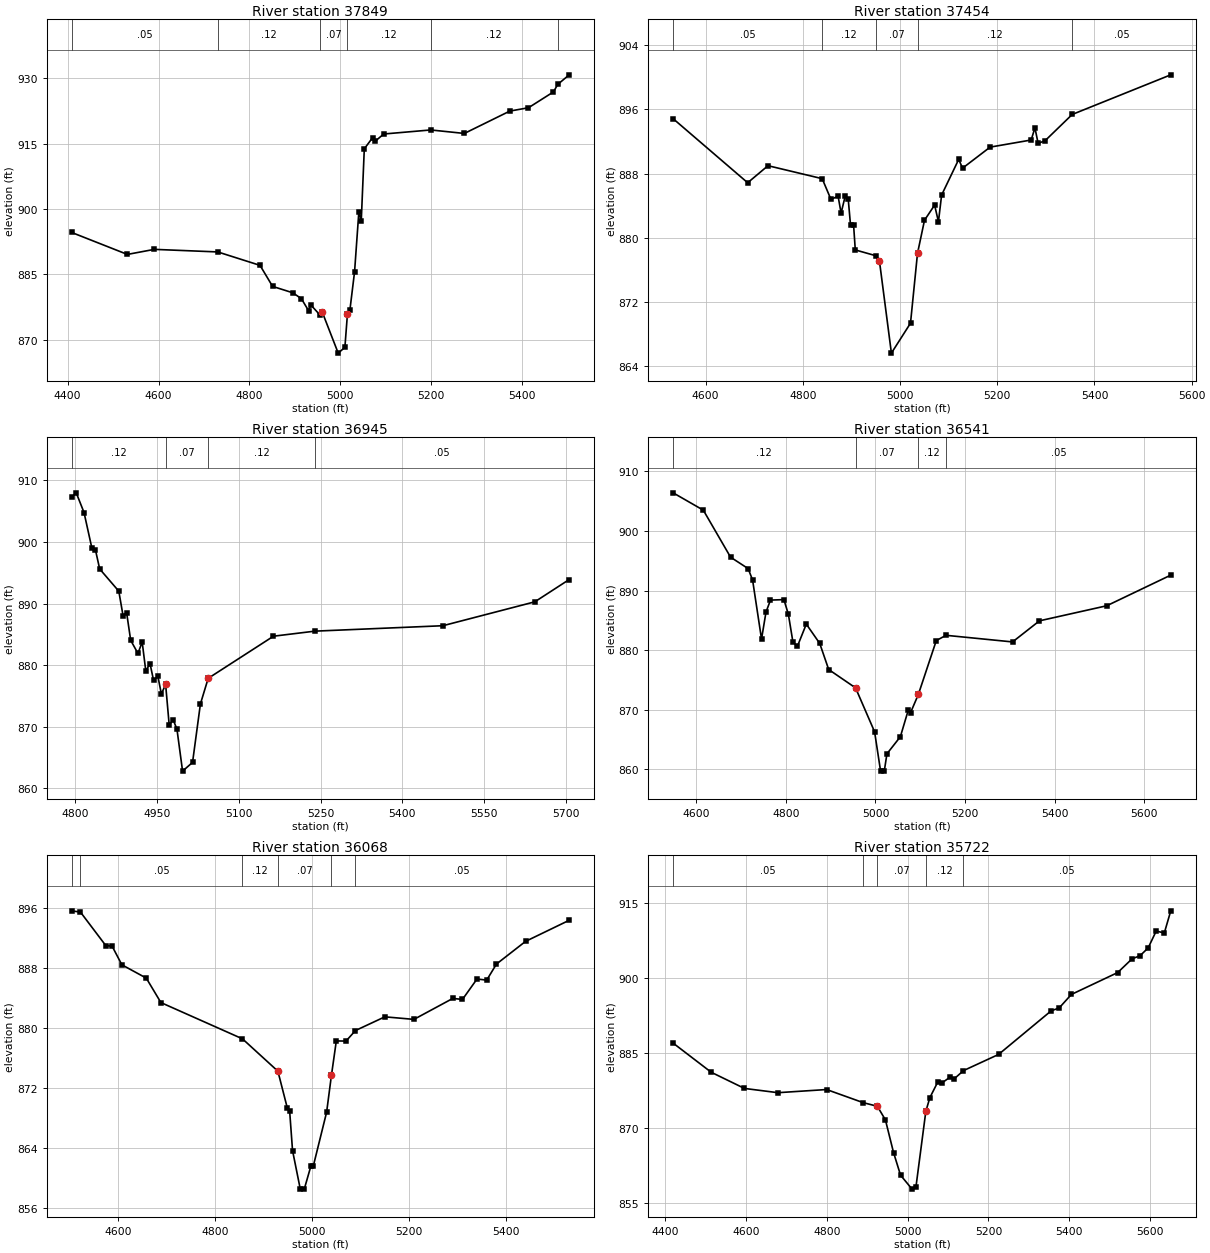
Type RM Length L Ch R = 1 ,37849   ,395,395,395
BEGIN DESCRIPTION:
Harts Creek 64.0
END DESCRIPTION:
XS GIS Cut Line= 3
       2280728.1      7196077.51      2280283.52      7195847.73
      2279726.55      7196054.88
#Sta/Elev= 30
  4408.7  894.62  4531.5  889.57  4590.9  890.73  4730.3  890.14  4823.3  887.06
    4851  882.23  4895.3  880.77  4914.2  879.43    4930  876.68  4935.3  877.95
    4955  875.69  4960.3  876.31  4995.3  866.92    5010  868.25  5015.7  876.01
    5021  876.78  5031.3   885.6  5040.7  899.34    5046  897.24  5052.7   913.8
  5071.1  916.38  5076.4  915.52  5095.4   917.2  5198.9  918.13  5272.8  917.33
  5372.8  922.46  5413.9  923.23  5468.8  926.86  5478.2  928.58  5503.4  930.78
#Mann= 6 ,-1 , 0
  4408.7     .05       0  4730.3     .12       0    4955     .07       0
  5015.7     .12       0  5198.9     .12       0  5478.2     .05       0
Bank Sta=4960.3,5015.7
XS Rating Curve= 0 ,0
Exp/Cntr=0.3,0.1

Type RM Length L Ch R = 1 ,37454   ,509,509,509
BEGIN DESCRIPTION:
Harts Creek 63.0
END DESCRIPTION:
XS GIS Cut Line= 4
      2280736.23      7196056.79      2280518.37       7195760.3
      2280373.43      7195580.53      2280049.33      7195305.52
#Sta/Elev= 30
  4533.1  894.85  4686.5  886.85  4728.3  888.98  4839.8  887.36  4857.9  884.76
  4872.5  885.18  4878.7  883.06  4887.2   885.2  4893.4  884.78  4898.1  881.57
  4904.4  881.57  4907.9  878.46  4951.1  877.72  4957.5  877.12  4982.2  865.57
  5021.5  869.31  5035.9  878.03  5050.3  882.17  5071.1  884.06    5079  881.98
  5085.5  885.31  5120.7  889.77  5128.6  888.67  5185.3   891.3  5269.8  892.19
  5277.5  893.71  5284.1  891.77  5298.4   892.1  5354.2  895.38    5557  900.33
#Mann= 5 ,-1 , 0
  4533.1     .05       0  4839.8     .12       0  4951.1     .07       0
  5035.9     .12       0  5354.2     .05       0
Bank Sta=4957.5,5035.9
XS Rating Curve= 0 ,0
Exp/Cntr=0.3,0.1

Type RM Length L Ch R = 1 ,36945   ,404,404,404
BEGIN DESCRIPTION:
Harts Creek 62.0
END DESCRIPTION:
XS GIS Cut Line= 3
      2280872.24      7195509.17       2280614.4       7195293.7
      2280053.05       7195160.3
#Sta/Elev= 30
    4793  907.29  4801.6  907.99  4815.9  904.79  4830.2  899.05  4836.8  898.74
  4844.6  895.63  4879.7  892.02  4887.5  888.04    4894  888.55  4901.5  884.04
  4914.8  881.92  4922.6  883.76  4929.2  879.07    4937  880.25  4943.5  877.52
  4951.3  878.25  4957.8  875.33  4965.6  876.87  4972.1  870.34  4979.7  871.08
  4986.4   869.6  4996.7   862.8    5015  864.22  5029.4   873.7  5043.7  877.87
  5163.5  884.71  5239.5  885.53  5474.2  886.41  5642.9  890.29    5706  893.91
#Mann= 4 ,-1 , 0
    4793     .12       0  4965.6     .07       0  5043.7     .12       0
  5239.5     .05       0
Bank Sta=4965.6,5043.7
XS Rating Curve= 0 ,0
Exp/Cntr=0.3,0.1

Type RM Length L Ch R = 1 ,36541   ,473,473,473
BEGIN DESCRIPTION:
Harts Creek 61.0
END DESCRIPTION:
XS GIS Cut Line= 3
      2281176.35      7195003.08        2280729.        7195010.
      2280066.38      7195051.14
#Sta/Elev= 30
  4548.2  906.41  4615.6   903.5  4676.5  895.61  4715.6   893.7  4725.6   891.8
  4745.6  881.87  4755.6   886.4  4765.6  888.41  4795.6  888.49  4805.6  886.02
  4815.6  881.43  4825.6  880.63  4845.6  884.38  4875.6  881.14  4895.6  876.76
  4955.6  873.68  4998.1  866.31  5011.5  859.71  5019.7  859.71  5025.7  862.62
  5055.7  865.49  5073.5  869.99  5078.5  869.54  5095.8  872.57  5135.9  881.62
  5157.7   882.5  5306.2  881.39  5366.3  884.93  5516.6  887.46  5659.5   892.6
#Mann= 4 ,-1 , 0
  4548.2     .12       0  4955.6     .07       0  5095.8     .12       0
  5157.7     .05       0
Bank Sta=4955.6,5095.8
XS Rating Curve= 0 ,0
Exp/Cntr=0.3,0.1

Type RM Length L Ch R = 1 ,36068   ,346,346,346
BEGIN DESCRIPTION:
Harts Creek 60.0
END DESCRIPTION:
XS GIS Cut Line= 3
      2281072.24      7194662.67        2280579.        7194610.
      2280049.08      7194588.65
#Sta/Elev= 30
  4503.5  895.56  4521.9  895.39    4574  890.94  4587.2  890.85  4607.3  888.37
  4657.6   886.6  4687.8  883.34    4856  878.51  4929.1   874.2  4948.3  869.35
  4953.4  868.84  4959.3  863.63  4975.3  858.49  4983.5  858.49    4997  861.53
    5002  861.53  5029.6  868.74  5039.6  873.68  5049.6  878.23  5069.6  878.21
    5089  879.61  5149.7  881.44  5209.7   881.1  5289.8  883.89  5309.8  883.76
  5339.8  886.48  5359.8  886.33  5379.9  888.47  5439.9  891.49  5529.9   894.3
#Mann= 6 ,-1 , 0
  4503.5     .12       0  4521.9     .05       0    4856     .12       0
  4929.1     .07       0  5039.6     .12       0    5089     .05       0
Bank Sta=4929.1,5039.6
XS Rating Curve= 0 ,0
Exp/Cntr=0.3,0.1

Type RM Length L Ch R = 1 ,35722   ,516,516,516
BEGIN DESCRIPTION:
Harts Creek 59.0
END DESCRIPTION:
XS GIS Cut Line= 3
      2281110.64      7194444.86      2280624.46      7194327.44
      2279893.03      7194300.07
#Sta/Elev= 30
  4419.3  886.94  4513.6  881.12  4595.9  877.89  4678.8  877.04  4799.3  877.67
  4889.9  875.05  4924.9  874.33  4944.9  871.61    4965  865.09  4982.4  860.56
  5010.9  857.78  5020.6  858.28    5045  873.33    5055  876.06    5075  879.25
    5085  878.99  5105.1  880.16  5115.1   879.8  5138.2  881.45  5225.1  884.68
  5355.2  893.38  5375.2  893.97  5405.3  896.66    5520  901.03  5555.4  903.76
  5575.4   904.4  5595.4  905.95  5615.4  909.33  5635.4  908.93  5651.4  913.36
#Mann= 5 ,-1 , 0
  4419.3     .05       0  4889.9     .12       0  4924.9     .07       0
    5045     .12       0  5138.2     .05       0
Bank Sta=4924.9,5045
XS Rating Curve= 0 ,0
Exp/Cntr=0.3,0.1

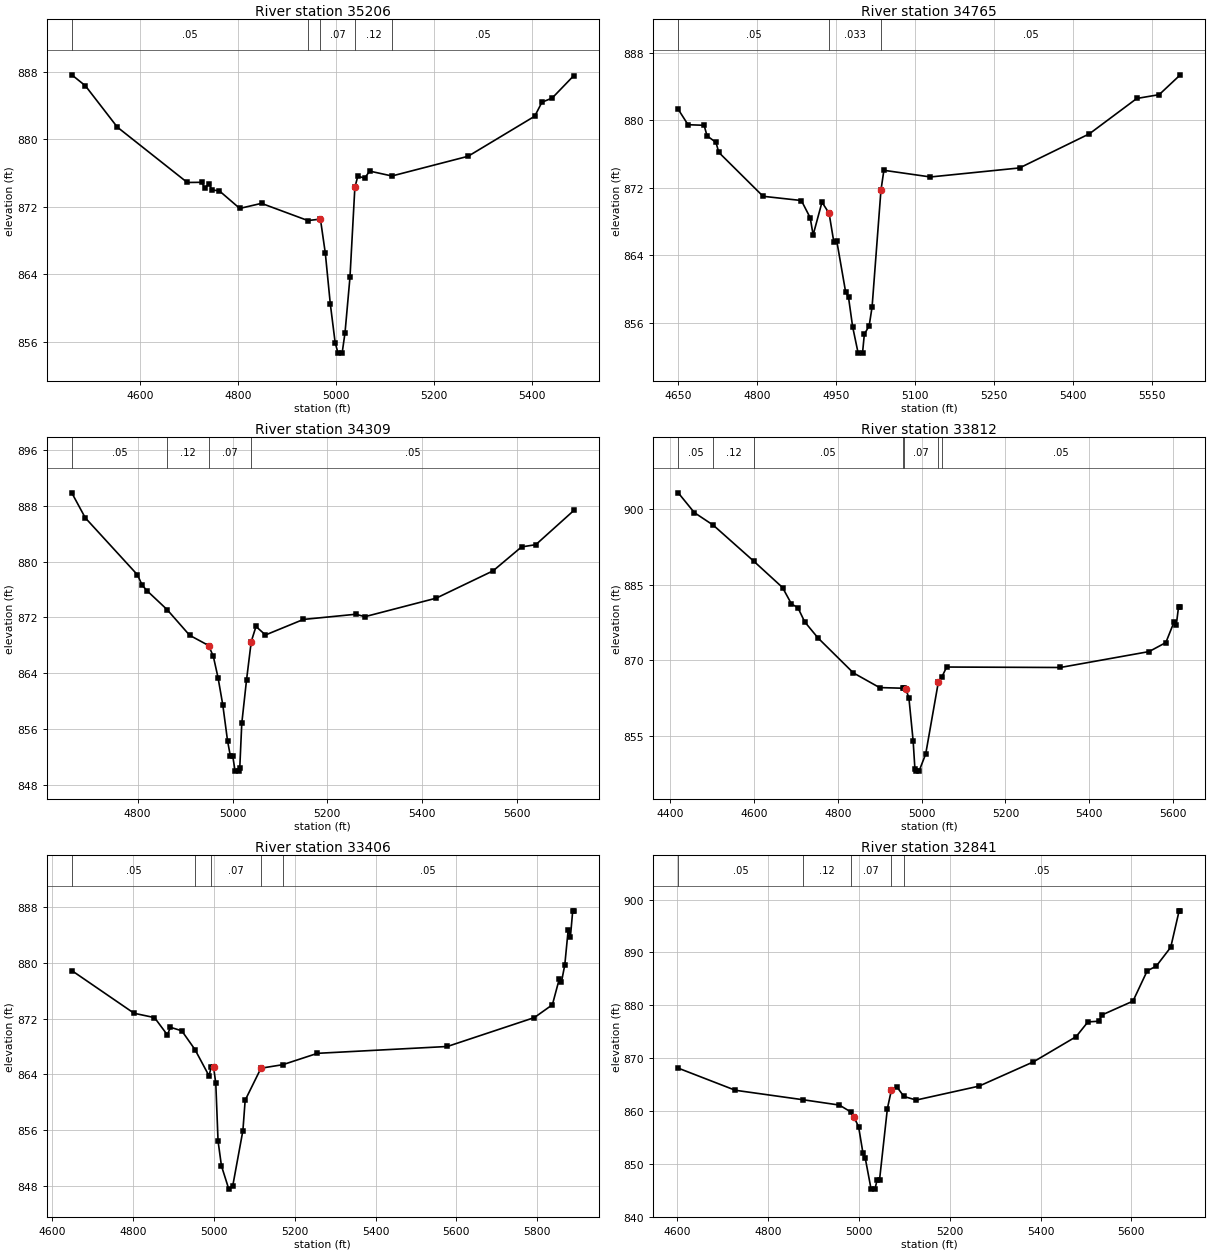
Type RM Length L Ch R = 1 ,35206   ,441,441,441
BEGIN DESCRIPTION:
Harts Creek 58.0
END DESCRIPTION:
XS GIS Cut Line= 4
       2281148.6      7194429.67      2280825.47       7194201.4
      2280852.87      7193922.88      2280570.18      7193717.52
#Sta/Elev= 30
  4460.9  887.67  4488.7  886.37  4553.9  881.46  4696.7  874.89  4726.3  874.91
  4732.4  874.24  4741.1   874.7  4747.2     874    4762   873.9  4803.8  871.81
  4848.2  872.41  4942.8  870.37  4968.5  870.54  4978.5  866.48  4988.6   860.5
  4998.6  855.85  5004.5  854.63  5012.8  854.63  5018.7  857.06  5028.8  863.63
  5038.8  874.32  5044.8  875.63  5058.9  875.41    5069  876.24  5114.4  875.66
  5269.9     878    5406  882.76  5420.7  884.42  5441.5  884.91  5485.8  887.58
#Mann= 5 ,-1 , 0
  4460.9     .05       0  4942.8     .12       0  4968.5     .07       0
  5038.8     .12       0  5114.4     .05       0
Bank Sta=4968.5,5038.8
XS Rating Curve= 0 ,0
Exp/Cntr=0.3,0.1

Type RM Length L Ch R = 1 ,34765   ,456,456,456
BEGIN DESCRIPTION:
Harts Creek 57.0
END DESCRIPTION:
XS GIS Cut Line= 3
      2281287.07      7194226.66      2281077.68      7193805.59
      2280606.76      7193695.39
#Sta/Elev= 30
  4650.3  881.28  4668.9  879.46  4699.5  879.39    4705  878.14  4721.9  877.37
  4727.4  876.18  4811.5  870.98  4884.2  870.48    4901  868.44  4906.6   866.4
  4923.4  870.28  4936.9  868.97  4945.8   865.6  4951.4  865.72  4968.2  859.69
  4973.8  859.02  4981.6  855.54  4992.1   852.4  5000.4   852.4  5003.9  854.65
    5013  855.62  5018.6  857.87  5035.4  871.67    5041  874.06  5129.5  873.27
  5298.8  874.34  5431.4  878.38  5521.5  882.57    5564  883.02  5604.2  885.37
#Mann= 3 , 0 , 0
  4650.3     .05       0  4936.9    .033       0  5035.4     .05       0
Bank Sta=4936.9,5035.4
XS Rating Curve= 0 ,0
Exp/Cntr=0.3,0.1

Type RM Length L Ch R = 1 ,34309   ,497,497,497
BEGIN DESCRIPTION:
Harts Creek 56.0
END DESCRIPTION:
XS GIS Cut Line= 3
      2281667.53      7193636.46      2281332.05      7193636.65
      2280608.74      7193638.26
#Sta/Elev= 30
    4661  889.87  4689.5  886.28  4799.5  878.11  4809.5  876.62  4819.5  875.84
    4862  873.12  4909.5  869.44  4949.5  867.97  4959.5  866.42  4969.5  863.35
  4979.5  859.44  4989.5   854.3  4995.5   852.1  5000.5   852.1  5005.4  849.95
  5013.7  849.95  5015.3  850.45  5019.5  856.79  5029.5     863  5039.5  868.54
  5049.5   870.7  5069.5  869.48  5149.5  871.71  5259.5  872.45  5279.5  872.11
  5429.5  874.76  5549.5  878.68  5609.5  882.11  5639.5  882.43  5719.8  887.34
#Mann= 4 ,-1 , 0
    4661     .05       0    4862     .12       0  4949.5     .07       0
  5039.5     .05       0
Bank Sta=4949.5,5039.5
XS Rating Curve= 0 ,0
Exp/Cntr=0.3,0.1

Type RM Length L Ch R = 1 ,33812   ,406,406,406
BEGIN DESCRIPTION:
Harts Creek 55.0
END DESCRIPTION:
XS GIS Cut Line= 4
      2282034.98      7193345.69      2281593.41      7193197.65
      2281388.69      7193190.45      2280886.07      7193348.32
#Sta/Elev= 30
  4419.6  903.26    4458  899.33  4503.2  896.83  4599.2  889.72  4668.3  884.45
  4689.6  881.19  4705.1  880.42  4721.2  877.63  4752.9  874.43  4837.2  867.49
  4899.7  864.57  4955.2  864.44  4957.7  864.57  4962.7  864.25  4969.8  862.44
  4979.8  854.01    4984  848.47  4985.6  847.97  4993.9  847.97  5009.8  851.38
  5039.8  865.59  5048.6  866.73  5059.8  868.65  5330.9  868.56  5542.5  871.72
  5582.5  873.51  5602.1  877.61  5607.3  876.93  5612.8  880.61    5617  880.61
#Mann= 7 ,-1 , 0
  4419.6     .05       0  4503.2     .12       0  4599.2     .05       0
  4955.2     .12       0  4957.7     .07       0  5039.8     .12       0
  5048.6     .05       0
Bank Sta=4962.7,5039.8
XS Rating Curve= 0 ,0
Exp/Cntr=0.3,0.1

Type RM Length L Ch R = 1 ,33406   ,565,565,565
BEGIN DESCRIPTION:
Harts Creek 54.0
END DESCRIPTION:
XS GIS Cut Line= 3
      2281991.37       7192756.5        2281679.        7192910.
      2280878.98      7193310.01
#Sta/Elev= 30
  4648.1  878.89  4802.3  872.77  4852.8  872.15  4884.7  869.67  4892.2  870.76
  4920.3  870.26    4953  867.57  4987.7  863.81  4993.4   865.1  4998.9   865.1
  5004.5  862.75  5010.1  854.47  5018.5  850.91  5036.7  847.57  5046.6  848.07
  5071.6  855.96  5077.2  860.31  5116.3   864.9  5170.2   865.4  5256.1  867.03
  5577.5  868.01  5792.8  872.15  5837.5  873.99  5854.2  877.61  5859.8  877.21
  5868.2  879.71  5876.6  884.72  5882.2  883.77  5887.8  887.45  5890.6  887.45
#Mann= 5 ,-1 , 0
  4648.1     .05       0    4953     .12       0  4993.4     .07       0
  5116.3     .12       0  5170.2     .05       0
Bank Sta=4998.9,5116.3
XS Rating Curve= 0 ,0
Exp/Cntr=0.3,0.1

Type RM Length L Ch R = 1 ,32841   ,430,430,430
BEGIN DESCRIPTION:
Harts Creek 53.0
END DESCRIPTION:
XS GIS Cut Line= 3
      2281780.16      7192370.04      2281487.42       7192450.3
        2280729.        7192710.
#Sta/Elev= 30
  4602.5  868.13  4728.1  863.95  4877.8  862.15  4957.2  861.15    4983  859.82
  4988.9  858.95  4999.5  857.07    5009  852.14  5014.3  851.06    5027  845.26
  5035.4  845.26  5040.3  846.99  5045.6  846.99  5062.9  860.49  5071.6  863.93
  5084.1  864.55  5099.2  862.78  5126.3   862.1  5264.6  864.73  5384.4  869.32
  5478.3  874.08  5504.3  876.87    5528     877  5535.6   878.2  5603.5   880.8
  5634.8  886.52  5654.8  887.42  5686.6  890.98  5705.1  897.87  5707.7  897.87
#Mann= 5 ,-1 , 0
  4602.5     .05       0  4877.8     .12       0    4983     .07       0
  5071.6     .12       0  5099.2     .05       0
Bank Sta=4988.9,5071.6
XS Rating Curve= 0 ,0
Exp/Cntr=0.3,0.1

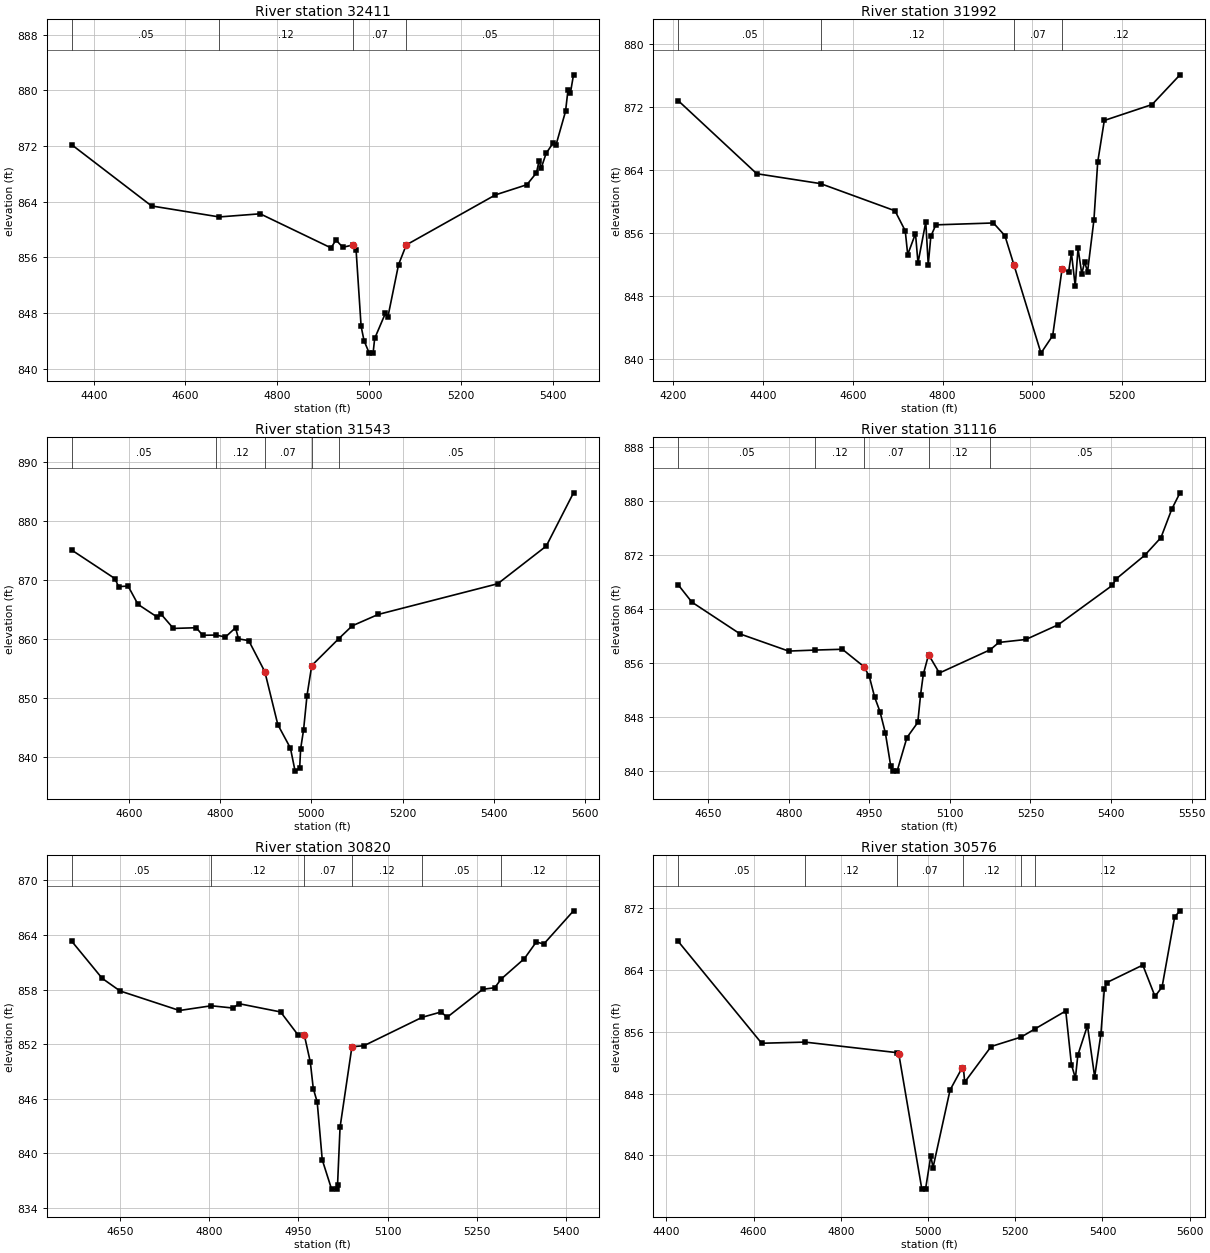
Type RM Length L Ch R = 1 ,32411   ,419,419,419
BEGIN DESCRIPTION:
Harts Creek 52.0
END DESCRIPTION:
XS GIS Cut Line= 4
      2281840.61       7192293.1      2281312.35      7192083.23
      2281230.87      7192265.83      2280922.49      7192368.82
#Sta/Elev= 30
  4352.2  872.17  4526.1  863.38  4673.6   861.8  4762.8  862.25  4917.3  857.35
    4928  858.49  4942.8  857.44    4966  857.78  4971.8  857.11  4982.8  846.09
  4989.2  844.02  5000.5  842.23  5008.9  842.23  5012.4  844.34  5035.7  847.95
  5041.1   847.4  5064.4  854.95  5081.3  857.78  5275.6  864.97  5344.1  866.43
    5365  868.14  5370.4   869.8  5375.7   868.9  5386.1  870.95    5402  872.49
  5407.3  872.08  5428.3  876.96  5433.6  879.99  5438.9  879.59  5445.7  882.22
#Mann= 4 ,-1 , 0
  4352.2     .05       0  4673.6     .12       0    4966     .07       0
  5081.3     .05       0
Bank Sta=4966,5081.3
XS Rating Curve= 0 ,0
Exp/Cntr=0.3,0.1

Type RM Length L Ch R = 1 ,31992   ,449,449,449
BEGIN DESCRIPTION:
Harts Creek 51.0
END DESCRIPTION:
XS GIS Cut Line= 4
      2281848.32      7192280.98      2281273.83      7192011.86
      2281250.66      7191855.79      2281057.42      7191594.57
#Sta/Elev= 30
  4211.5  872.84  4386.3  863.54  4528.4  862.28  4694.1  858.82  4716.9  856.27
  4722.4  853.24  4739.7  855.92  4745.3  852.19  4762.6  857.39  4768.1  851.97
  4773.9  855.57    4785  857.03  4913.2  857.27  4938.8  855.65    4959  851.91
  5019.1   840.7  5045.2  842.93  5066.1  851.44  5080.7  851.03  5086.9  853.46
  5095.3  849.25  5101.6  854.03    5110  850.77  5116.2  852.33  5122.8  851.06
    5137  857.66  5145.4  865.02  5160.1  870.32  5266.5  872.35  5328.6  876.13
#Mann= 4 ,-1 , 0
  4211.5     .05       0  4528.4     .12       0    4959     .07       0
  5066.1     .12       0
Bank Sta=4959,5066.1
XS Rating Curve= 0 ,0
Exp/Cntr=0.3,0.1

Type RM Length L Ch R = 1 ,31543   ,427,427,427
BEGIN DESCRIPTION:
Harts Creek 50.0
END DESCRIPTION:
XS GIS Cut Line= 3
      2281892.63      7192190.16      2281478.64      7191861.48
       2281049.6      7191485.15
#Sta/Elev= 30
  4475.2   875.1  4569.8  870.27  4577.8  868.91  4598.6  869.01  4620.3  865.91
  4662.7  863.74  4670.7  864.27  4697.9  861.83    4748  861.95    4762  860.67
  4791.5  860.71  4811.8  860.37  4834.1  861.95  4840.5  860.06  4862.9  859.77
  4898.2   854.5  4926.7  845.53  4954.3  841.56  4964.5  837.66  4974.5  838.16
  4976.7  841.46  4983.1  844.65  4990.6  850.46    5001  855.54  5060.5  860.12
  5089.6  862.27  5146.6   864.2  5408.5   869.4  5514.8  875.78  5574.5   884.8
#Mann= 5 ,-1 , 0
  4475.2     .05       0  4791.5     .12       0  4898.2     .07       0
    5001     .12       0  5060.5     .05       0
Bank Sta=4898.2,5001
XS Rating Curve= 0 ,0
Exp/Cntr=0.3,0.1

Type RM Length L Ch R = 1 ,31116   ,296,296,296
BEGIN DESCRIPTION:
Harts Creek 49.0
END DESCRIPTION:
XS GIS Cut Line= 3
      2282034.33      7191525.21        2281629.        7191510.
      2281103.78      7191452.25
#Sta/Elev= 30
  4594.4  867.62  4619.8  865.06  4709.8  860.34  4799.9  857.81  4848.9  857.96
  4899.9  858.08    4940  855.51    4950  854.08    4960  850.99    4970  848.83
    4980  845.67    4990  840.76  4993.3  840.03  5001.8  840.03  5020.1     845
  5040.3  847.24  5045.5  851.34  5050.6  854.37  5060.4  857.28  5080.5  854.56
  5175.2  858.01  5191.2  859.09  5241.5  859.53  5301.8  861.71  5402.4  867.54
  5409.6   868.5  5462.8     872    5493  874.62  5513.1  878.83  5528.4  881.25
#Mann= 5 ,-1 , 0
  4594.4     .05       0  4848.9     .12       0    4940     .07       0
  5060.4     .12       0  5175.2     .05       0
Bank Sta=4940,5060.4
XS Rating Curve= 0 ,0
Exp/Cntr=0.3,0.1

Type RM Length L Ch R = 1 ,30820   ,244,244,244
BEGIN DESCRIPTION:
Harts Creek 48.1
END DESCRIPTION:
XS GIS Cut Line= 2
      2282060.18      7191236.42      2281216.43      7191192.26
#Sta/Elev= 30
  4568.3  863.31  4619.5  859.23  4649.6  857.84  4749.7  855.69  4803.2  856.21
  4839.8  855.96  4849.9  856.44    4920  855.53    4950  852.94    4960  852.96
    4970  850.02    4975   847.1  4981.6  845.62  4990.1  839.26  5005.8  836.03
  5014.3  836.03  5015.9  836.53  5020.1  842.84  5040.1  851.71  5060.2  851.81
  5158.3  854.94  5190.3  855.53  5200.3  854.94  5260.4  858.02  5280.5   858.2
  5291.7  859.17  5330.5   861.4  5350.5  863.23  5363.2  863.01  5413.2  866.66
#Mann= 6 ,-1 , 0
  4568.3     .05       0  4803.2     .12       0    4960     .07       0
  5040.1     .12       0  5158.3     .05       0  5291.7     .12       0
Bank Sta=4960,5040.1
XS Rating Curve= 0 ,0
Exp/Cntr=0.3,0.1

Type RM Length L Ch R = 1 ,30576   ,378,378,378
BEGIN DESCRIPTION:
Harts Creek 48.0
END DESCRIPTION:
XS GIS Cut Line= 4
      2282130.08      7191133.65      2281771.42      7191011.49
      2281498.68      7190975.36      2281058.16      7190745.71
#Sta/Elev= 30
    4427   867.7  4618.3  854.52  4717.6  854.67  4927.9  853.31  4932.9  853.13
  4985.7  835.64  4994.2  835.64  5006.3  839.94  5011.4  838.43  5050.4  848.46
  5078.3  851.36    5081  851.36    5084  849.48  5144.7   854.1  5213.4  855.32
  5245.3  856.38  5315.8   858.7  5328.8  851.77  5337.9     850  5343.5  852.99
  5365.6  856.81  5382.1  850.17  5396.4  855.71  5404.2  861.48  5409.8  862.37
  5492.5  864.64  5520.5  860.59  5536.7   861.8  5565.6  870.89  5577.8  871.66
#Mann= 6 ,-1 , 0
    4427     .05       0  4717.6     .12       0  4927.9     .07       0
    5081     .12       0  5213.4     .05       0  5245.3     .12       0
Bank Sta=4932.9,5078.3
XS Rating Curve= 0 ,0
Exp/Cntr=0.3,0.1

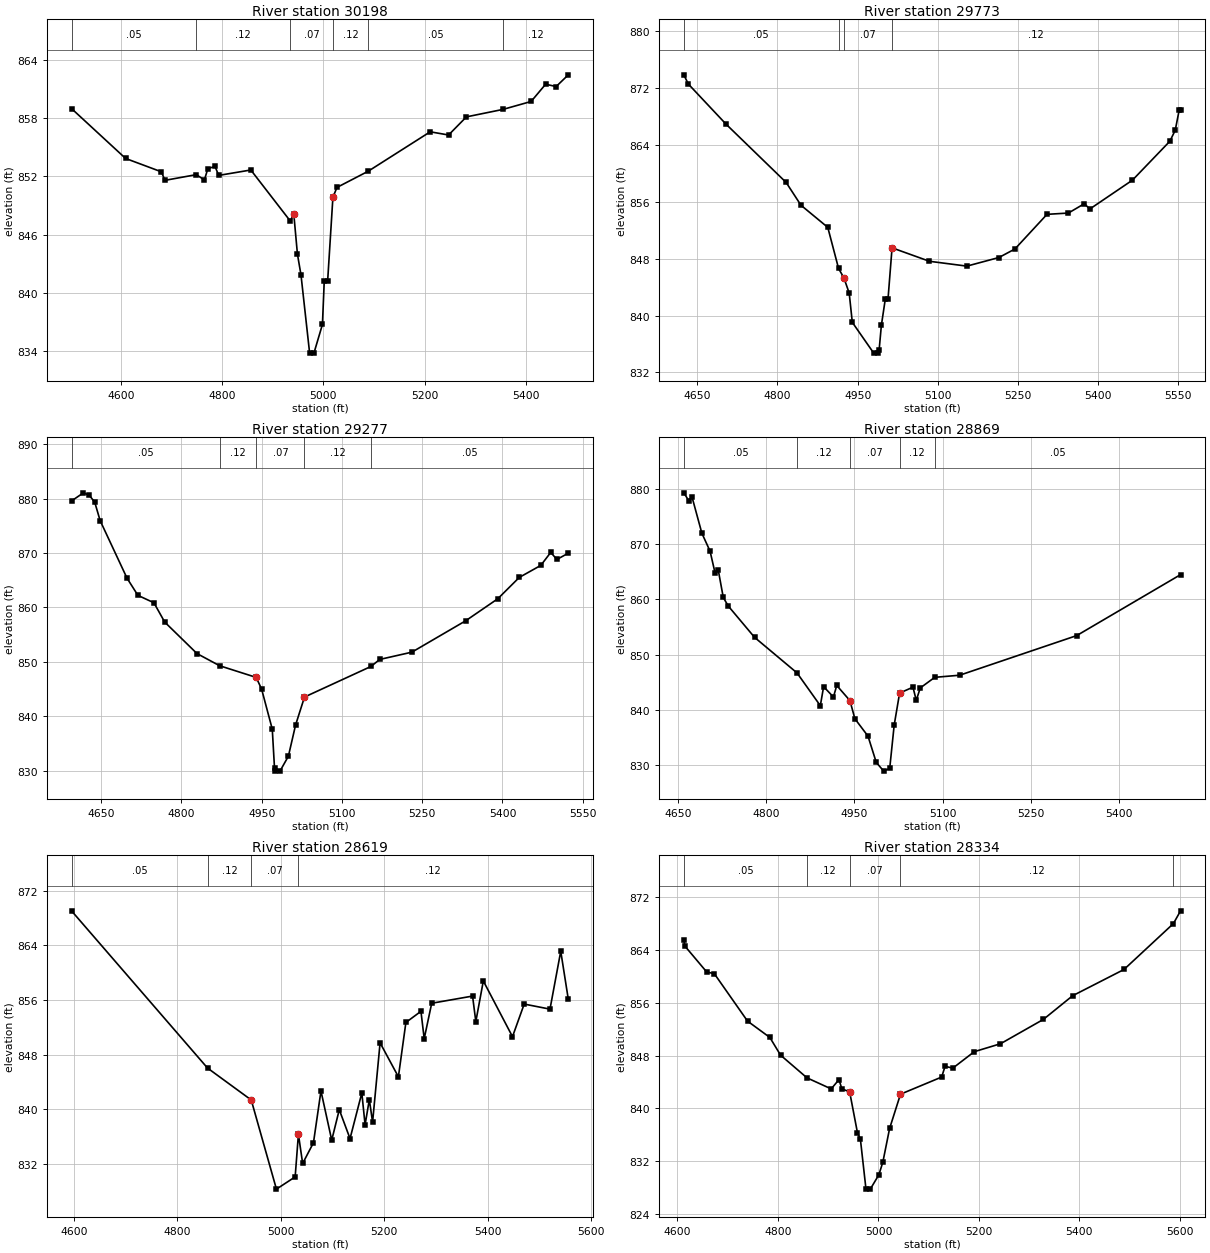
Type RM Length L Ch R = 1 ,30198   ,425,425,425
BEGIN DESCRIPTION:
Harts Creek 47.0
END DESCRIPTION:
XS GIS Cut Line= 3
      2282028.15      7191072.06        2281679.        7190710.
      2281306.86      7190408.71
#Sta/Elev= 30
  4502.3     859  4609.2  853.85    4680  852.47  4686.9  851.59    4749  852.18
  4764.9  851.63  4771.8  852.81    4786  853.02  4793.2   852.1  4856.7  852.66
  4934.7  847.39  4941.6  848.11  4948.8  843.97  4955.8  841.84  4972.9  833.76
  4981.4  833.76  4998.2  836.72  5001.8   841.2  5008.5   841.2  5018.9  849.84
  5026.9  850.86  5088.6  852.53  5211.2   856.6  5247.5  856.27  5282.7  858.14
  5354.9  858.91  5410.6  859.73  5439.3  861.51  5460.1  861.27  5484.1  862.48
#Mann= 6 ,-1 , 0
  4502.3     .05       0    4749     .12       0  4934.7     .07       0
  5018.9     .12       0  5088.6     .05       0  5354.9     .12       0
Bank Sta=4941.6,5018.9
XS Rating Curve= 0 ,0
Exp/Cntr=0.3,0.1

Type RM Length L Ch R = 1 ,29773   ,496,496,496
BEGIN DESCRIPTION:
Harts Creek 46.0
END DESCRIPTION:
XS GIS Cut Line= 3
      2282207.66      7190389.83        2281829.        7190360.
      2281279.04        7190360.
#Sta/Elev= 30
  4624.6  873.84  4633.3  872.53  4703.5  866.92  4816.2  858.71  4843.9  855.51
  4894.1   852.4  4914.3  846.62  4924.2  845.31  4934.2  843.16    4940  839.05
  4980.1  834.72  4988.6  834.72  4990.3  835.22  4994.4  838.63  5001.9  842.38
  5006.9  842.38  5014.4  849.52  5084.4  847.63  5154.4  846.95  5214.4  848.16
  5244.4  849.36  5304.4  854.23  5344.4  854.41  5374.4  855.73  5384.4  854.97
  5464.4  859.04  5534.4  864.51  5544.4  866.05  5551.9  868.92  5554.4  868.92
#Mann= 4 ,-1 , 0
  4624.6     .05       0  4914.3     .12       0  4924.2     .07       0
  5014.4     .12       0
Bank Sta=4924.2,5014.4
XS Rating Curve= 0 ,0
Exp/Cntr=0.3,0.1

Type RM Length L Ch R = 1 ,29277   ,408,408,408
BEGIN DESCRIPTION:
Harts Creek 45.0
END DESCRIPTION:
XS GIS Cut Line= 3
      2282132.16       7190087.8      2281796.99      7190051.62
      2281207.74      7190002.58
#Sta/Elev= 30
  4594.6  879.55  4616.8  881.05    4628  880.58    4638  879.33  4648.1  875.94
  4698.4  865.35  4718.7   862.2  4748.6  860.84  4768.8  857.29  4829.1   851.5
  4871.5  849.26  4939.7  847.12  4949.8  844.99  4969.8   837.6    4974  830.39
  4975.6  829.89  4984.2  829.89  4999.9  832.63  5013.3  838.35    5030  843.51
  5154.4  849.14  5170.5  850.42  5230.7  851.76  5331.1  857.52  5391.3  861.58
  5431.4   865.5  5471.6  867.71  5490.2   870.1  5501.7   868.8    5523  869.96
#Mann= 5 ,-1 , 0
  4594.6     .05       0  4871.5     .12       0  4939.7     .07       0
    5030     .12       0  5154.4     .05       0
Bank Sta=4939.7,5030
XS Rating Curve= 0 ,0
Exp/Cntr=0.3,0.1

Type RM Length L Ch R = 1 ,28869   ,250,250,250
BEGIN DESCRIPTION:
Harts Creek 44.0
END DESCRIPTION:
XS GIS Cut Line= 3
      2282128.99      7189859.99        2281829.        7189710.
      2281369.56       7189491.6
#Sta/Elev= 30
  4660.3  879.29  4668.7  877.89  4674.3  878.54    4691  871.99    4705  868.72
  4713.4  864.81    4719  865.26  4727.4  860.36  4735.8  858.82  4780.5  853.15
  4852.7  846.71  4892.3  840.78  4897.9  844.22  4914.6  842.35  4920.2  844.44
  4942.6   841.7    4951  838.42  4973.3  835.27  4987.3  830.53    5000  828.94
  5010.2  829.44  5017.8  837.27    5027  843.06  5049.7  844.13  5055.3  841.75
  5062.1  843.99  5086.7  845.91    5129  846.29  5327.9  853.46  5504.4  864.49
#Mann= 5 ,-1 , 0
  4660.3     .05       0  4852.7     .12       0  4942.6     .07       0
    5027     .12       0  5086.7     .05       0
Bank Sta=4942.6,5027
XS Rating Curve= 0 ,0
Exp/Cntr=0.3,0.1

Type RM Length L Ch R = 1 ,28619   ,285,285,285
BEGIN DESCRIPTION:
Harts Creek 43.0
END DESCRIPTION:
XS GIS Cut Line= 3
      2282215.47      7189742.32      2281908.57      7189484.76
      2281463.13      7189145.64
#Sta/Elev= 30
  4595.6  869.04  4858.6  846.04  4943.1  841.37  4991.8  828.33    5028  830.12
  5034.3  836.35  5042.5  832.08  5063.4  835.12  5077.9  842.69  5098.7  835.49
  5113.3  839.95  5134.1  835.72  5156.9   842.4  5163.2  837.74  5171.4  841.43
  5177.7  838.13  5192.2  849.73  5227.6  844.76  5242.1  852.71  5271.2  854.34
  5277.5  850.34    5292  855.52    5371  856.57  5377.3  852.84  5391.8  858.78
  5448.2  850.63  5470.8   855.4  5520.7  854.66  5541.5  863.13  5556.1   856.1
#Mann= 4 ,-1 , 0
  4595.6     .05       0  4858.6     .12       0  4943.1     .07       0
  5034.3     .12       0
Bank Sta=4943.1,5034.3
XS Rating Curve= 0 ,0
Exp/Cntr=0.3,0.1

Type RM Length L Ch R = 1 ,28334   ,314,314,314
BEGIN DESCRIPTION:
Harts Creek 42.1
END DESCRIPTION:
XS GIS Cut Line= 2
      2282367.45      7189465.75       2281522.8      7188951.85
#Sta/Elev= 30
  4612.6  865.39  4615.3  864.49    4658  860.64  4673.5  860.35  4739.5   853.2
  4783.9  850.73  4805.2  848.06  4857.8  844.63    4906  842.96  4921.4  844.36
  4927.3  842.96  4942.7  842.52  4958.2  836.35  4964.1  835.36  4975.2  827.82
  4983.8  827.82  5000.9  829.99  5008.8  831.91  5022.2  836.98  5043.9  842.16
  5125.8  844.75  5132.6  846.37  5148.1   846.1  5190.7  848.58  5242.9  849.78
  5328.3  853.46  5386.4  857.03  5488.7     861    5587  867.93  5601.3  869.86
#Mann= 5 ,-1 , 0
  4612.6     .05       0  4857.8     .12       0  4942.7     .07       0
  5043.9     .12       0    5587     .05       0
Bank Sta=4942.7,5043.9
XS Rating Curve= 0 ,0
Exp/Cntr=0.3,0.1

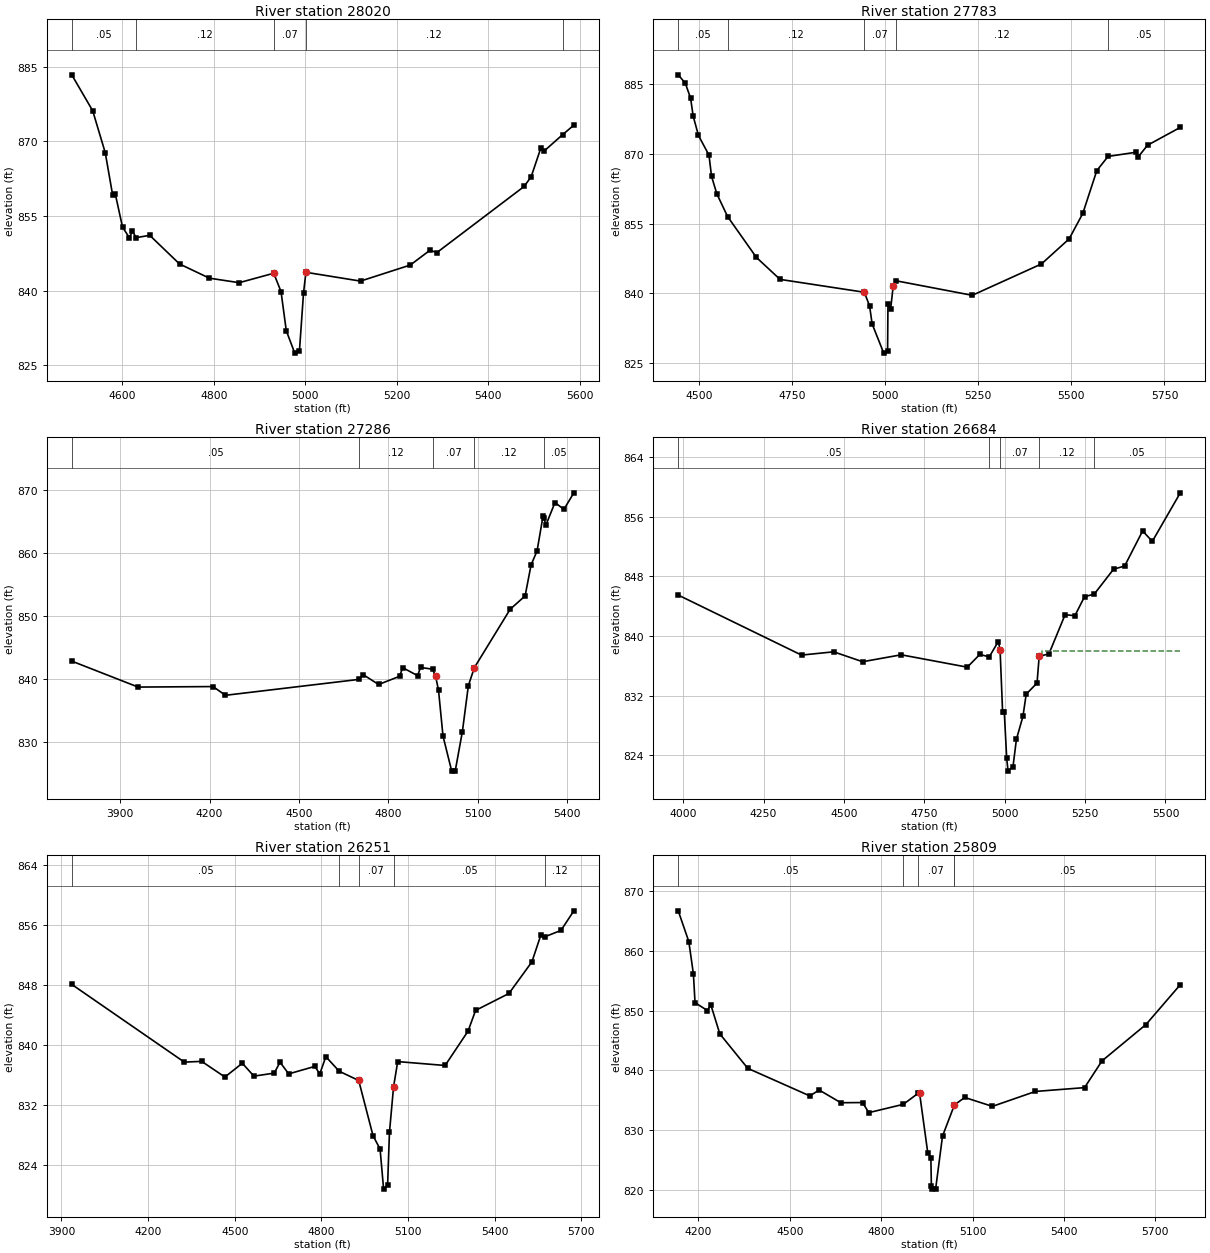
Type RM Length L Ch R = 1 ,28020   ,237,237,237
BEGIN DESCRIPTION:
Harts Creek 42.0
END DESCRIPTION:
XS GIS Cut Line= 3
      2282579.04      7189260.02        2282129.        7189010.
      2281629.02      7188710.01
#Sta/Elev= 30
  4489.3  883.36  4535.1  876.13  4562.6  867.67  4578.6  859.22  4584.3  859.48
  4600.3  852.73  4615.2  850.63    4622  851.91  4630.1  850.63  4659.8  851.09
    4725  845.33  4790.2  842.48  4855.4  841.57  4930.9  843.47  4946.9  839.78
  4958.4  831.91  4976.9  827.41  4987.2  827.91  4996.1  839.52  5001.3  843.66
  5120.7  841.89  5229.6  845.12  5272.4  848.08  5287.9  847.64  5478.4  860.91
  5493.9  862.88  5515.3  868.72  5521.1  867.95  5562.4  871.31  5587.2  873.24
#Mann= 5 ,-1 , 0
  4489.3     .05       0  4630.1     .12       0  4930.9     .07       0
  5001.3     .12       0  5562.4     .05       0
Bank Sta=4930.9,5001.3
XS Rating Curve= 0 ,0
Exp/Cntr=0.3,0.1

Type RM Length L Ch R = 1 ,27783   ,497,497,497
BEGIN DESCRIPTION:
Harts Creek 41.2
END DESCRIPTION:
XS GIS Cut Line= 3
      2282651.75      7189224.01      2282154.19      7188710.07
      2281557.82      7188496.46
#Sta/Elev= 30
  4443.7  886.96  4462.7  885.16  4476.9  881.95  4483.8   878.1    4498  873.94
  4526.3   869.7  4533.2  865.14  4547.4  861.39  4576.3  856.51  4653.6  847.74
  4717.2  843.01  4943.5  840.25  4957.7  837.34  4964.6  833.44  4995.8  827.17
  5006.1  827.67  5007.1  837.62  5014.3  836.62  5021.2  841.61  5028.4  842.72
  5233.5  839.59  5419.5  846.33  5493.8  851.71  5530.5  857.18  5568.2  866.39
  5598.4  869.43  5673.7  870.33    5679   869.3  5704.4  871.83  5792.5  875.67
#Mann= 5 ,-1 , 0
  4443.7     .05       0  4576.3     .12       0  4943.5     .07       0
  5028.4     .12       0  5598.4     .05       0
Bank Sta=4943.5,5021.2
XS Rating Curve= 0 ,0
Exp/Cntr=0.3,0.1

Type RM Length L Ch R = 1 ,27286   ,602,602,602
BEGIN DESCRIPTION:
Harts Creek 41.1
END DESCRIPTION:
XS GIS Cut Line= 3
      2283253.62      7188039.17      2282273.68      7188460.38
      2281655.85      7188510.61
#Sta/Elev= 30
  3737.1  842.81  3959.9  838.68  4211.6  838.76  4253.3  837.37  4701.6   839.9
  4715.2  840.68  4767.8  839.09  4838.5   840.4  4848.6  841.77  4898.7   840.5
  4908.8  841.81  4948.9  841.52  4958.9  840.46    4969  838.19  4984.1  830.88
  5013.3   825.3    5025   825.3  5049.2   831.6  5069.3  838.91  5089.3  841.76
  5209.7  851.07  5259.9  853.19    5280  858.14    5300  860.34  5320.1   865.9
  5322.8  865.52  5330.1  864.51  5360.2  868.05  5390.3  866.97  5423.6   869.6
#Mann= 5 ,-1 , 0
  3737.1     .05       0  4701.6     .12       0  4948.9     .07       0
  5089.3     .12       0  5322.8     .05       0
Bank Sta=4958.9,5089.3
XS Rating Curve= 0 ,0
Exp/Cntr=0.3,0.1

Type RM Length L Ch R = 1 ,26684   ,433,433,433
BEGIN DESCRIPTION:
Harts Creek 41.0
END DESCRIPTION:
XS GIS Cut Line= 5
      2283332.41      7188012.38      2282486.94      7188009.29
        2282329.        7188060.       2282165.9      7188084.07
      2281782.29      7188049.29
#Sta/Elev= 30
  3984.7  845.47  4368.1  837.42  4468.1  837.86  4558.1  836.53  4678.1  837.46
  4883.7   835.8  4922.5  837.51  4951.9  837.18    4980  839.24  4985.6  838.12
  4993.4  829.84  4998.6  829.84  5006.2  823.56  5010.4  821.86  5025.8  822.47
  5036.5  826.15  5056.7   829.2  5066.8  832.18  5100.5  833.67  5107.2  837.25
  5137.6  837.59  5187.9  842.85  5218.1  842.69  5248.2  845.25  5278.5   845.6
  5338.5  848.94  5372.9  849.36  5428.9  854.07    5459  852.67  5546.1  859.18
#Mann= 5 ,-1 , 0
  3984.7     .05       0  4951.9     .12       0  4985.6     .07       0
  5107.2     .12       0  5278.5     .05       0
#XS Ineff= 2 , 0
       0    4980  839.24  5117.4       0  837.99
Permanent Ineff=
       F       F
Bank Sta=4985.6,5107.2
XS Rating Curve= 0 ,0
Exp/Cntr=0.3,0.1

Type RM Length L Ch R = 1 ,26251   ,442,442,442
BEGIN DESCRIPTION:
Harts Creek 40.0
END DESCRIPTION:
XS GIS Cut Line= 5
      2283386.97      7187927.21       2282537.9      7187849.62
        2282379.        7187710.      2282260.62      7187608.81
      2281744.42      7187655.72
#Sta/Elev= 30
  3935.6  848.04  4325.2  837.67  4385.4  837.77  4465.8  835.68    4526  837.52
  4566.2   835.8  4636.5   836.2  4656.6  837.66  4686.7   836.1  4777.1   837.1
  4794.3   836.1  4815.2   838.4  4861.5  836.45    4929  835.22  4978.4  827.87
    5003  826.06  5015.2  820.72    5029  821.22  5035.4  828.28  5049.7  834.39
    5064  837.74  5228.1  837.22  5307.7  841.82  5333.6  844.57  5449.1  846.83
  5528.6  851.05  5559.6  854.63  5574.8  854.42    5629  855.24  5673.8  857.86
#Mann= 5 ,-1 , 0
  3935.6     .05       0  4861.5     .12       0    4929     .07       0
  5049.7     .05       0  5574.8     .12       0
Bank Sta=4929,5049.7
XS Rating Curve= 0 ,0
Exp/Cntr=0.3,0.1

Type RM Length L Ch R = 1 ,25809   ,453,453,453
BEGIN DESCRIPTION:
Harts Creek 39.0
END DESCRIPTION:
XS GIS Cut Line= 3
      2283433.08      7187295.64        2282579.        7187460.
      2281807.19      7187556.75
#Sta/Elev= 30
  4134.2   866.7  4168.9  861.55    4184  856.12  4189.3  851.32    4230     850
    4241  850.98  4270.7  846.09  4362.4  840.32  4566.1   835.7  4596.6  836.69
  4667.9  834.56  4739.2  834.59  4759.5   832.9  4872.7  834.29    4921  836.12
  4926.1  836.19    4953  826.19  4963.2  825.32  4964.9  820.59  4966.9  820.09
  4978.8  820.09  5001.4  828.96  5040.6   834.2  5074.5  835.44  5165.2  833.95
  5306.3  836.45  5467.6  837.09  5524.7  841.56  5669.1  847.66  5781.8  854.33
#Mann= 5 ,-1 , 0
  4134.2     .05       0  4872.7     .12       0    4921     .07       0
  5040.6     .12       0  5040.6     .05       0
Bank Sta=4926.1,5040.6
XS Rating Curve= 0 ,0
Exp/Cntr=0.3,0.1