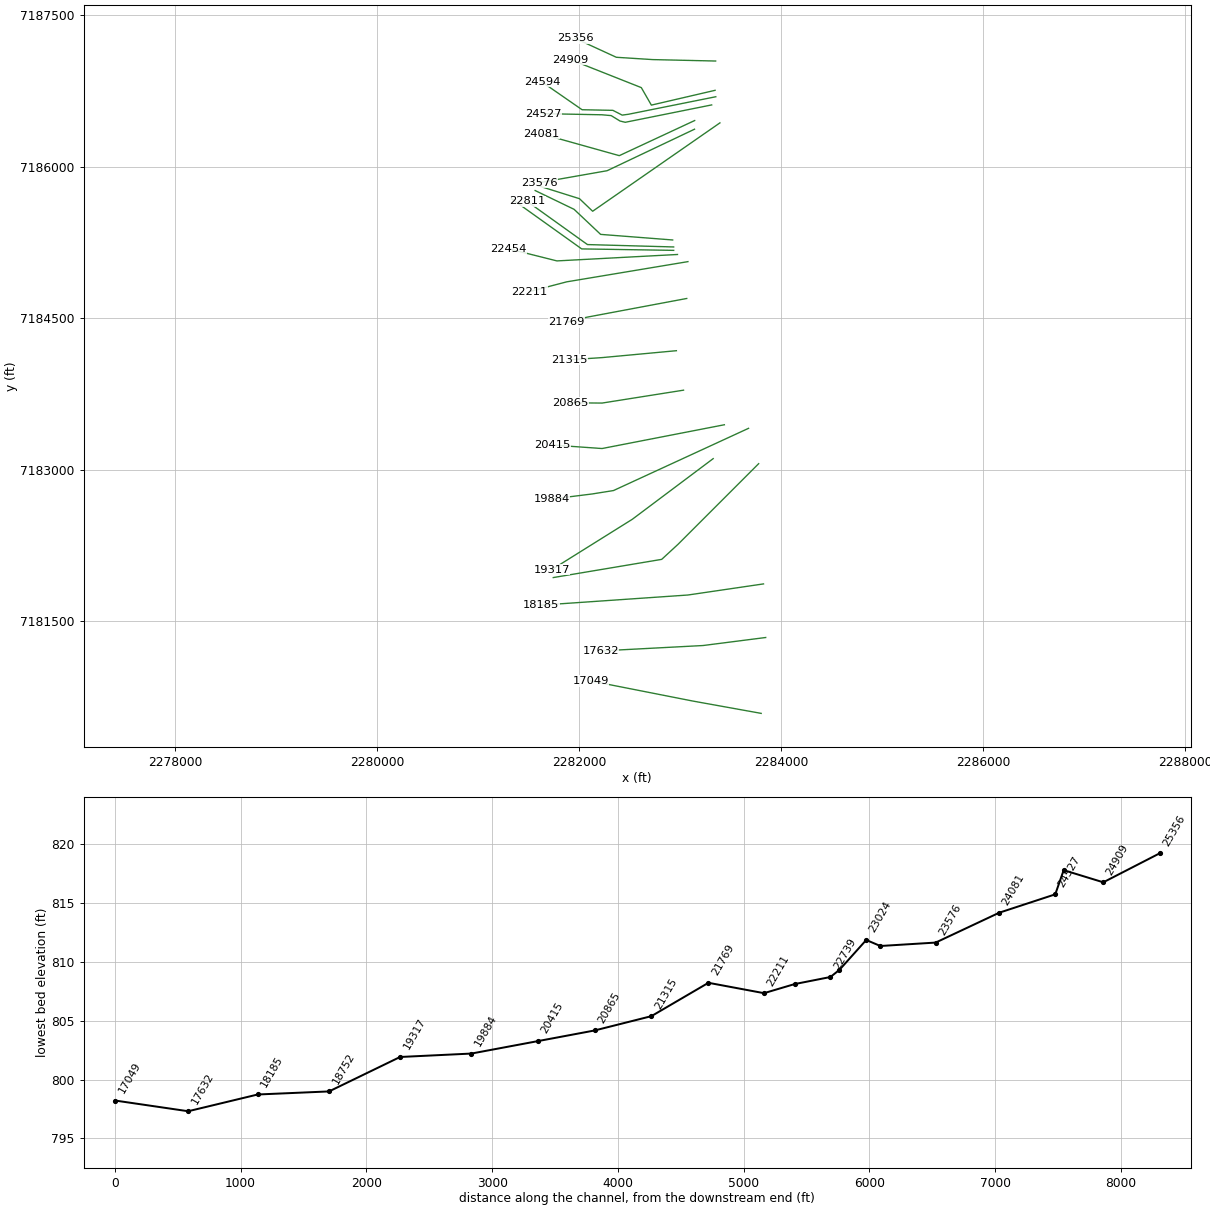
HEC-RAS study Harts Creek.prj: Harts Creek Base Level Engineering

--- Harts Creek.g01 (geometry) --- (continued)

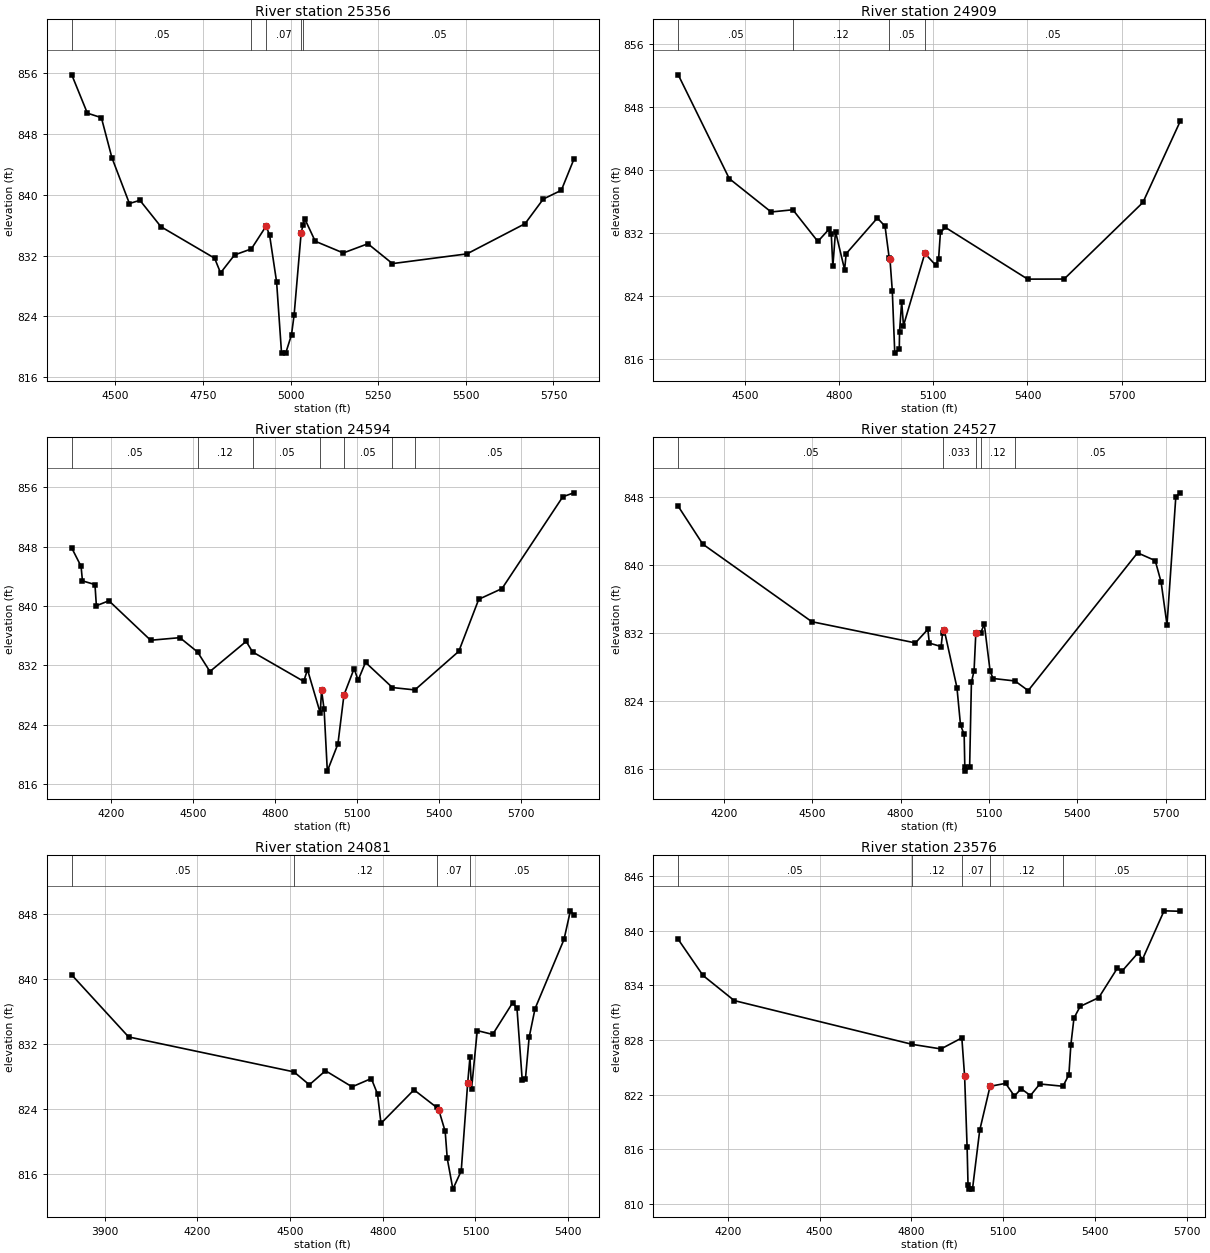
Type RM Length L Ch R = 1 ,25356   ,447,447,447
BEGIN DESCRIPTION:
Harts Creek 38.0
END DESCRIPTION:
XS GIS Cut Line= 4
      2283353.45      7187045.72        2282729.        7187060.
      2282370.36      7187082.84      2281962.49      7187270.37
#Sta/Elev= 30
  4375.3  855.76  4419.8  850.72  4459.8  850.13  4489.8  844.87  4539.8  838.84
  4569.8  839.26  4629.8  835.79    4783  831.65  4799.9  829.72  4839.9  832.08
  4887.8  832.87  4929.9  835.87  4939.9  834.68  4959.9  828.52    4974  819.17
  4985.9  819.17  5002.4  821.58  5009.9  824.21    5030  835.02  5035.6  836.04
    5040  836.85  5070.1  833.88  5150.2  832.34  5220.4  833.55  5290.5  830.94
  5503.2  832.22    5669  836.19    5721  839.43  5772.5  840.58  5808.2  844.65
#Mann= 5 ,-1 , 0
  4375.3     .05       0  4887.8     .12       0  4929.9     .07       0
    5030     .12       0  5035.6     .05       0
Bank Sta=4929.9,5030
XS Rating Curve= 0 ,0
Exp/Cntr=0.3,0.1

Type RM Length L Ch R = 1 ,24909   ,315,315,315
BEGIN DESCRIPTION:
Harts Creek 37.0
END DESCRIPTION:
XS GIS Cut Line= 4
      2283347.62      7186755.79      2282717.08      7186609.34
      2282617.35      7186782.66      2281916.27      7187060.15
#Sta/Elev= 30
  4286.1  852.11  4448.9  838.91  4582.4  834.67  4651.7  834.95  4731.4  830.92
  4767.2  832.49  4774.1  831.89  4779.2  827.76  4787.7  832.17  4816.7  827.34
  4821.8  829.37  4921.2   833.9  4945.7  832.85  4958.8  828.87  4961.3  828.71
  4968.8  824.65  4976.7  816.72  4991.1  817.22  4991.9  819.45  4998.7  823.26
  5004.5  820.22  5072.6   829.4  5107.3   827.9  5116.5  828.71  5122.3  832.07
  5138.4   832.7  5400.5  826.13  5516.8  826.14  5768.1  835.88  5887.4  846.23
#Mann= 4 ,-1 , 0
  4286.1     .05       0  4651.7     .12       0  4958.8     .05       0
  5072.6     .05       0
Bank Sta=4961.3,5072.6
XS Rating Curve= 0 ,0
Exp/Cntr=0.3,0.1

Type RM Length L Ch R = 1 ,24594   ,67,67,67
BEGIN DESCRIPTION:
Harts Creek 36.3
END DESCRIPTION:
XS GIS Cut Line= 6
      2283354.75      7186692.22      2282490.25       7186518.8
      2282428.23       7186510.4      2282336.25      7186557.56
      2282031.11      7186563.66       2281632.9      7186839.52
#Sta/Elev= 30
  4057.4   847.8  4091.4  845.34  4096.5  843.38  4142.3  842.88  4147.4  840.03
  4193.3   840.7    4346  835.38    4453  835.73  4517.7   833.8    4563  831.17
  4695.6  835.23  4718.9  833.81  4906.2  829.84    4920  831.42  4966.5   825.6
  4971.6  828.62  4980.8  826.06  4992.6  817.75  5031.3  821.41  5053.5  828.01
  5090.7  831.57  5105.1  829.98  5132.3   832.4  5230.7  829.01  5312.9  828.69
  5473.7  833.89  5546.7   840.9  5631.8  842.34  5854.3  854.71  5894.7  855.24
#Mann= 7 ,-1 , 0
  4057.4     .05       0  4517.7     .12       0  4718.9     .05       0
  4966.5    .033       0  5053.5     .05       0  5230.7     .12       0
  5312.9     .05       0
Bank Sta=4971.6,5053.5
XS Rating Curve= 0 ,0
Exp/Cntr=0.3,0.1

Type RM Length L Ch R = 1 ,24527   ,446,446,446
BEGIN DESCRIPTION:
Harts Creek 36.2
END DESCRIPTION:
XS GIS Cut Line= 6
      2283314.12      7186611.29      2282458.34      7186439.27
      2282407.01      7186451.76      2282319.32      7186505.44
      2282227.72      7186513.64      2281643.79      7186524.81
#Sta/Elev= 30
  4044.9  846.95  4128.1  842.49  4498.6  833.33  4850.2  830.83  4892.3  832.43
  4897.5  830.81  4937.4   830.4  4942.5  832.02  4948.1  832.34  4991.2  825.56
  5003.3  821.14  5015.7  820.03  5017.9   816.2  5019.9   815.7  5034.3   816.2
  5040.3  826.16  5049.3  827.54  5055.3  831.98  5071.2  831.96    5084  833.05
    5104  827.46  5114.1  826.63  5188.3  826.34  5233.1   825.2  5604.4  841.46
  5664.4  840.54  5684.4  838.01  5704.4  832.97  5734.4   848.1  5749.6  848.54
#Mann= 5 ,-1 , 0
  4044.9     .05       0  4942.5    .033       0  5055.3     .05       0
  5071.2     .12       0  5188.3     .05       0
Bank Sta=4948.1,5055.3
XS Rating Curve= 0 ,0
Exp/Cntr=0.3,0.1

Type RM Length L Ch R = 1 ,24081   ,505,505,505
BEGIN DESCRIPTION:
Harts Creek 36.1
END DESCRIPTION:
XS GIS Cut Line= 3
      2283145.68      7186456.67       2282399.5      7186109.11
      2281628.18      7186324.94
#Sta/Elev= 30
  3794.1   840.5    3978  832.87  4512.8  828.57  4562.6  826.98  4614.8  828.71
  4700.8  826.73  4763.1  827.75  4783.1  825.85  4794.3  822.23  4901.1  826.36
  4974.6  824.19  4981.2   823.9    5002  821.24  5008.7  817.91  5026.9  814.14
  5053.9  816.38  5074.7  827.16  5082.1  830.36  5087.3  826.51  5105.8  833.65
  5155.6  833.18  5220.1  837.07  5234.2  836.42  5251.2  827.56  5261.6  827.69
  5273.6  832.82  5292.7  836.35  5386.4  844.87    5407  848.39  5418.2  847.89
#Mann= 4 ,-1 , 0
  3794.1     .05       0  4512.8     .12       0  4974.6     .07       0
  5082.1     .05       0
#XS Ineff= 2 , 0
       0                  5220.1       0  837.07
Permanent Ineff=
       F       F
Bank Sta=4981.2,5074.7
XS Rating Curve= 0 ,0
Exp/Cntr=0.3,0.1

Type RM Length L Ch R = 1 ,23576   ,440,440,440
BEGIN DESCRIPTION:
Harts Creek 36.0
END DESCRIPTION:
XS GIS Cut Line= 3
      2283144.37      7186370.95        2282279.        7185960.
      2281606.73      7185841.63
#Sta/Elev= 30
  4038.3  839.04  4119.2  835.08  4221.4  832.32  4803.2  827.51  4896.8  827.01
    4965  828.22  4974.1  823.99  4982.2  816.24  4985.2  812.11  4987.2  811.61
  4999.8  811.61  5023.4  818.07  5057.2   822.9    5108  823.23  5136.9  821.83
  5158.8  822.64  5189.2  821.89  5219.7  823.16  5295.5  822.91  5314.8  824.18
  5321.2  827.44  5331.4   830.4  5351.7  831.68  5412.6  832.65  5473.5   835.9
  5487.6  835.52  5541.8   837.6  5554.8  836.81  5625.8  842.18  5678.9  842.13
#Mann= 5 ,-1 , 0
  4038.3     .05       0  4803.2     .12       0    4965     .07       0
  5057.2     .12       0  5295.5     .05       0
Bank Sta=4974.1,5057.2
XS Rating Curve= 0 ,0
Exp/Cntr=0.3,0.1

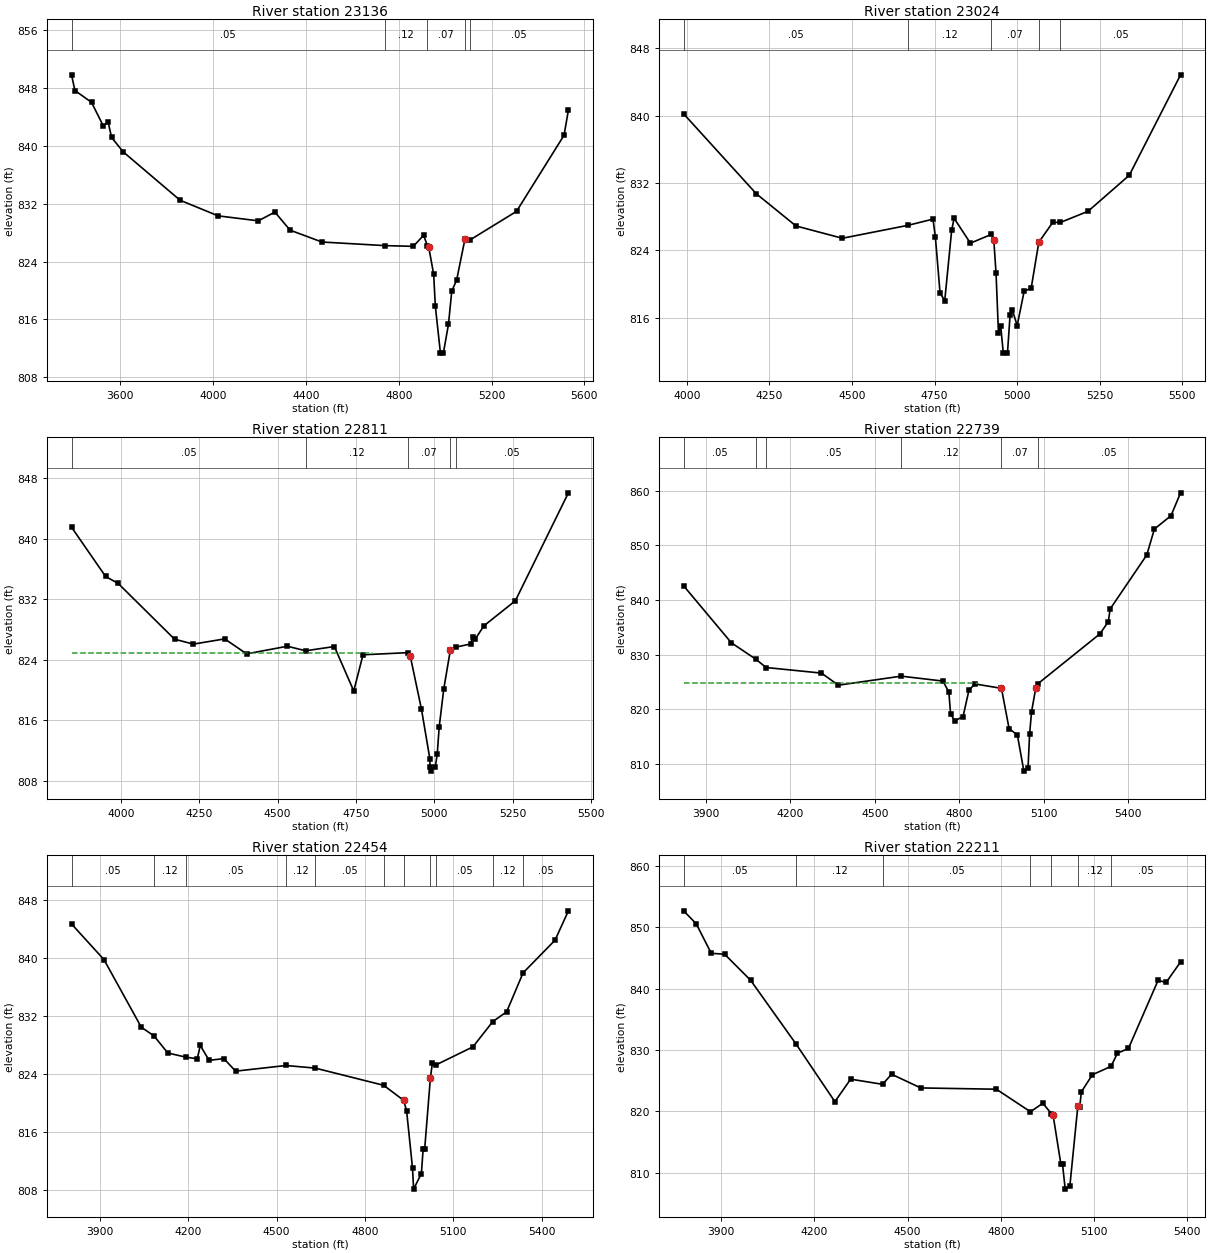
Type RM Length L Ch R = 1 ,23136   ,112,112,112
BEGIN DESCRIPTION:
Harts Creek 35.0
END DESCRIPTION:
XS GIS Cut Line= 4
      2283395.78      7186433.58      2282135.76      7185558.75
      2282005.62      7185683.02      2281597.62      7185811.05
#Sta/Elev= 30
  3389.9  849.84  3404.6  847.67  3476.2  846.03  3526.8  842.77  3547.8   843.3
  3562.6  841.17  3613.3  839.16  3857.8  832.48  4021.9  830.32  4194.8  829.63
  4266.4  830.84  4331.9  828.34    4469   826.7  4741.2   826.2  4862.7   826.1
  4907.3  827.62  4923.8  826.19  4929.6  825.97  4950.7  822.23  4957.9  817.82
  4979.9  811.32  4992.5  811.32  5014.5  815.31  5028.7   819.9  5049.7  821.43
  5085.3  827.07  5106.6  826.97  5307.7  830.94  5512.7  841.48  5531.4  844.96
#Mann= 5 ,-1 , 0
  3389.9     .05       0  4741.2     .12       0  4923.8     .07       0
  5085.3     .12       0  5106.6     .05       0
#XS Ineff= 2 , 0
       0  4266.4  830.84               0
Permanent Ineff=
       F       F
Bank Sta=4929.6,5085.3
XS Rating Curve= 0 ,0
Exp/Cntr=0.3,0.1

Type RM Length L Ch R = 1 ,23024   ,213,213,213
BEGIN DESCRIPTION:
Harts Creek 34.3
END DESCRIPTION:
XS GIS Cut Line= 4
      2282927.98      7185274.41      2282214.82      7185329.76
      2281951.98      7185577.84      2281566.67      7185763.66
#Sta/Elev= 30
  3990.4   840.2    4210  830.74  4330.4  826.91  4470.8  825.45  4670.2  826.99
  4745.3  827.72  4752.6  825.55  4766.7  818.94  4780.9  818.07  4801.9  826.42
  4809.2  827.82  4858.6  824.87  4922.1  825.91  4929.4  825.24  4936.2   821.3
  4943.5  814.24  4950.4  814.99  4958.2  811.83  4970.8  811.83  4978.7  816.38
    4986  816.89  5000.2  815.09  5021.2  819.16  5042.6  819.54  5065.7  824.98
    5108  827.34  5131.3  827.33  5214.8  828.65  5339.6  832.92  5494.9  844.83
#Mann= 5 ,-1 , 0
  3990.4     .05       0  4670.2     .12       0  4922.1     .07       0
  5065.7     .12       0  5131.3     .05       0
#XS Ineff= 2 , 0
       0  4809.2  827.82               0
Permanent Ineff=
       F       F
Bank Sta=4929.4,5065.7
XS Rating Curve= 0 ,0
Exp/Cntr=0.3,0.1

Type RM Length L Ch R = 1 ,22811   ,72,72,72
BEGIN DESCRIPTION:
Harts Creek 34.2
END DESCRIPTION:
XS GIS Cut Line= 3
       2282937.9      7185205.31      2282084.33      7185228.92
      2281488.85      7185655.49
#Sta/Elev= 30
  3841.8  841.55  3950.7  835.03  3990.8  834.11  4170.8  826.74  4230.8  826.09
  4330.9  826.78  4400.9   824.8    4531  825.81  4589.4  825.21    4681  825.77
  4742.9   819.9  4772.4  824.68  4914.9  824.96  4923.4  824.49  4959.1  817.48
  4986.1  810.88  4986.3   809.8  4988.3   809.3    5003   809.8  5009.4  811.53
  5015.6  815.11  5030.3  820.17  5051.2  825.28  5068.1  825.69  5116.3  826.11
  5122.4  827.09    5131  826.76  5158.1   828.5  5258.8  831.82  5428.2  846.09
#Mann= 5 ,-1 , 0
  3841.8     .05       0  4589.4     .12       0  4914.9     .07       0
  5051.2     .12       0  5068.1     .05       0
#XS Ineff= 2 , 0
       0  4800.7  824.87               0
Permanent Ineff=
       F       F
Bank Sta=4923.4,5051.2
XS Rating Curve= 0 ,0
Exp/Cntr=0.3,0.1

Type RM Length L Ch R = 1 ,22739   ,285,285,285
BEGIN DESCRIPTION:
Harts Creek 34.1
END DESCRIPTION:
XS GIS Cut Line= 3
      2282938.26      7185171.55      2282027.18        7185186.
      2281332.75      7185682.23
#Sta/Elev= 30
  3821.5  842.59  3990.8  832.18  4076.9   829.2  4114.4  827.65  4310.8  826.63
  4370.8  824.42  4594.1  826.07  4742.4  825.17  4763.3  823.14  4769.4  819.16
  4784.2   817.9  4813.7  818.67  4834.5  823.48  4855.4  824.65  4950.1  823.84
  4977.1  816.49  5006.6  815.29  5029.7  808.69  5044.4  809.19    5050  815.41
    5057  819.58  5071.7  823.82  5079.2  824.67  5300.3  833.83  5329.8  836.07
  5335.9  838.35  5466.2  848.25  5493.2  852.99  5552.2  855.44  5586.2  859.62
#Mann= 6 ,-1 , 0
  3821.5     .05       0  4076.9     .12       0  4114.4     .05       0
  4594.1     .12       0  4950.1     .07       0  5079.2     .05       0
#XS Ineff= 2 , 0
       0    4864  824.77               0
Permanent Ineff=
       F       F
Bank Sta=4950.1,5071.7
XS Rating Curve= 0 ,0
Exp/Cntr=0.3,0.1

Type RM Length L Ch R = 1 ,22454   ,243,243,243
BEGIN DESCRIPTION:
Harts Creek 34.0
END DESCRIPTION:
XS GIS Cut Line= 3
      2282975.69      7185130.79      2281782.09      7185067.16
      2281304.43      7185187.16
#Sta/Elev= 30
  3803.1  844.66  3913.4  839.74  4040.1  830.42  4083.1  829.23  4130.3  826.86
    4193  826.28  4230.4  826.07  4240.4  827.91  4270.5  825.85  4320.5  826.09
  4360.6  824.36  4531.7  825.14  4630.9  824.78  4863.3  822.41  4931.4  820.33
  4941.4  818.85  4961.4  810.98  4965.1  808.09  4991.5  810.24  4997.4  813.58
  5002.6  813.58  5022.2  823.46    5029  825.51  5041.5  825.23  5166.6  827.71
  5234.1   831.2    5281  832.54    5337  837.92  5445.5  842.42  5490.9  846.47
#Mann= 11 ,-1 , 0
  3803.1     .05       0  4083.1     .12       0    4193     .05       0
  4531.7     .12       0  4630.9     .05       0  4863.3     .12       0
  4931.4     .07       0  5022.2     .12       0  5041.5     .05       0
  5234.1     .12       0    5337     .05       0
#XS Ineff= 2 , 0
       0  4240.4  827.91               0
Permanent Ineff=
       F       F
Bank Sta=4931.4,5022.2
XS Rating Curve= 0 ,0
Exp/Cntr=0.3,0.1

Type RM Length L Ch R = 1 ,22211   ,442,442,442
BEGIN DESCRIPTION:
Harts Creek 33.0
END DESCRIPTION:
XS GIS Cut Line= 3
      2283079.02        7185060.        2281879.        7184860.
      2281509.03       7184763.2
#Sta/Elev= 30
  3779.2  852.67  3819.8  850.54  3867.9  845.75    3911   845.6  3994.7  841.35
  4141.7   830.9  4265.8  821.57  4316.5  825.24  4419.1   824.4  4448.3  826.04
  4542.1  823.81  4785.4   823.6  4895.1  819.93  4934.9  821.31  4962.8   819.6
  4967.9  819.41  4993.2  811.34  4998.4  811.34    5007  807.32  5021.9  807.82
  5047.5  820.79  5053.8  820.78    5059  823.17  5094.3  825.96  5154.4  827.32
  5175.1  829.48  5210.4  830.24  5305.9  841.34  5331.7     841  5378.2  844.34
#Mann= 7 ,-1 , 0
  3779.2     .05       0  4141.7     .12       0  4419.1     .05       0
  4895.1     .12       0  4962.8     .07       0  5047.5     .12       0
  5154.4     .05       0
#XS Ineff= 2 , 0
       0  4448.3  826.04               0
Permanent Ineff=
       F       F
Bank Sta=4967.9,5047.5
XS Rating Curve= 0 ,0
Exp/Cntr=0.3,0.1

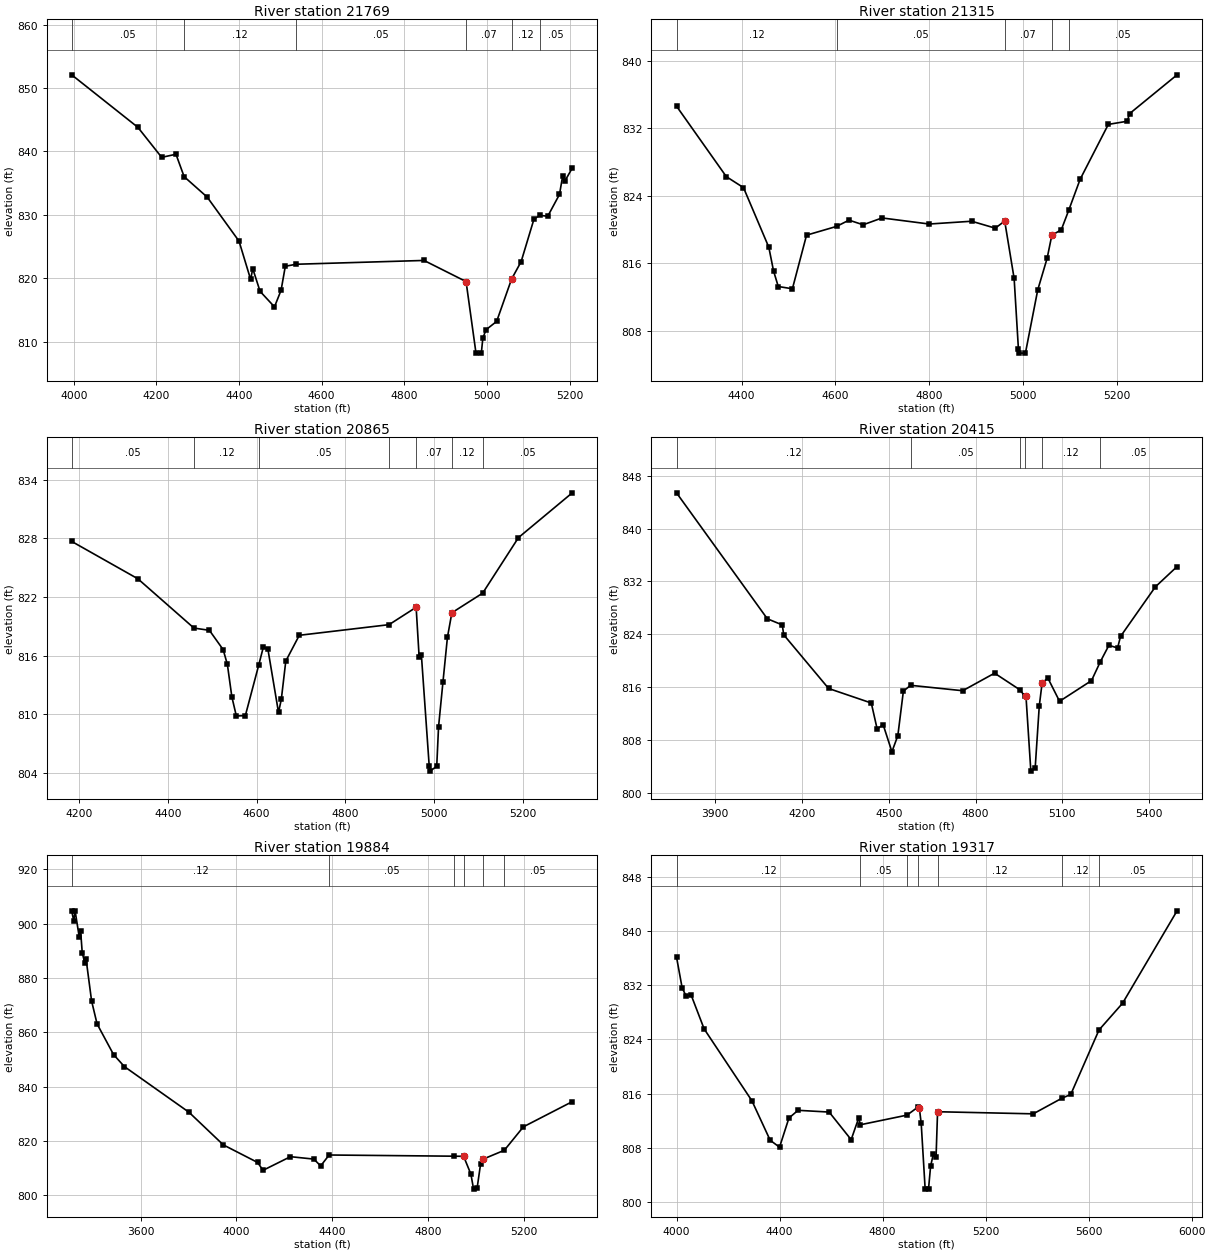
Type RM Length L Ch R = 1 ,21769   ,454,454,454
BEGIN DESCRIPTION:
Harts Creek 32.0
END DESCRIPTION:
XS GIS Cut Line= 3
      2283067.09      7184695.33        2282079.        7184510.
      2281878.98      7184459.99
#Sta/Elev= 30
    3995  852.07  4155.1   843.8  4212.8  839.06  4247.4  839.55  4267.1  836.02
    4323  832.79    4400  825.85  4428.1  819.81  4433.2  821.52  4450.9  817.94
  4485.8  815.49  4501.8  818.12    4512  821.89  4538.2  822.21  4847.7  822.81
  4949.5  819.48  4973.5   808.2  4986.4   808.2  4990.1  810.56  4997.8  811.89
  5023.5   813.2  5059.6  819.87  5082.8  822.63  5113.7   829.3  5127.7  829.92
  5147.2  829.78  5175.6  833.22  5183.3  836.13  5188.4   835.3  5206.5  837.37
#Mann= 6 ,-1 , 0
    3995     .05       0  4267.1     .12       0  4538.2     .05       0
  4949.5     .07       0  5059.6     .12       0  5127.7     .05       0
Bank Sta=4949.5,5059.6
XS Rating Curve= 0 ,0
Exp/Cntr=0.3,0.1

Type RM Length L Ch R = 1 ,21315   ,450,450,450
BEGIN DESCRIPTION:
Harts Creek 31.0
END DESCRIPTION:
XS GIS Cut Line= 3
      2282964.64      7184178.32        2282229.        7184110.
      2281903.02      7184088.33
#Sta/Elev= 30
  4261.6  834.62  4367.7  826.27  4404.2  824.97  4458.1  817.91  4468.1  815.12
  4478.2  813.26  4508.3  812.99  4538.4  819.34  4602.4  820.38  4628.8  821.12
  4658.9  820.57  4699.1  821.38  4799.5  820.66  4889.9  820.99  4940.1  820.17
  4960.2  821.01  4980.3  814.21  4989.4  805.87  4991.4  805.37  5004.3  805.37
  5030.5  812.85  5050.5   816.6  5060.5  819.33  5080.7  819.98  5096.5  822.29
  5120.7  825.95  5180.8  832.46  5220.9  832.83  5226.2  833.74  5327.1  838.33
#Mann= 5 ,-1 , 0
  4261.6     .12       0  4602.4     .05       0  4960.2     .07       0
  5060.5     .12       0  5096.5     .05       0
Bank Sta=4960.2,5060.5
XS Rating Curve= 0 ,0
Exp/Cntr=0.3,0.1

Type RM Length L Ch R = 1 ,20865   ,450,450,450
BEGIN DESCRIPTION:
Harts Creek 30.0
END DESCRIPTION:
XS GIS Cut Line= 3
      2283035.36      7183787.68        2282229.        7183660.
      2281917.82      7183662.45
#Sta/Elev= 30
  4183.6   827.7  4332.7  823.87    4459  818.82  4493.8  818.59  4524.8  816.61
  4534.3  815.09  4544.4  811.77  4554.5  809.81  4574.8  809.85  4605.1  815.06
  4615.3  816.87  4625.4  816.71  4649.5  810.17  4655.8  811.52  4665.9  815.44
  4696.3  818.08  4898.5  819.17  4959.5  820.95  4966.3  815.84  4971.4  816.02
    4989  804.66    4991  804.16  5005.9  804.66    5010   808.7    5020  813.33
    5030  817.87    5040  820.39  5109.4   822.4    5190  828.09  5311.2  832.68
#Mann= 7 ,-1 , 0
  4183.6     .05       0    4459     .12       0  4605.1     .05       0
  4898.5     .12       0  4959.5     .07       0    5040     .12       0
  5109.4     .05       0
Bank Sta=4959.5,5040
XS Rating Curve= 0 ,0
Exp/Cntr=0.3,0.1

Type RM Length L Ch R = 1 ,20415   ,531,531,531
BEGIN DESCRIPTION:
Harts Creek 29.0
END DESCRIPTION:
XS GIS Cut Line= 3
      2283439.65      7183445.33        2282229.        7183210.
      2281734.05        7183245.
#Sta/Elev= 30
  3766.8  845.42  4080.6  826.34  4132.2  825.41  4137.3  823.91  4292.4  815.78
  4439.8  813.58  4460.2  809.62  4480.6  810.32  4511.1   806.2  4531.5  808.63
  4550.7  815.38  4575.8  816.26  4755.6  815.44  4865.8   818.1  4954.9  815.53
  4969.2  814.63  4974.3  814.58  4991.1  803.26  5006.1  803.76  5020.2  813.13
  5030.2  816.68  5050.2  817.33  5090.3  813.84  5200.6  816.97  5231.4  819.85
  5260.8  822.32  5290.8  821.92  5300.9  823.66  5421.2  831.17  5496.3  834.25
#Mann= 6 ,-1 , 0
  3766.8     .12       0  4575.8     .05       0  4954.9     .12       0
  4969.2     .07       0  5030.2     .12       0  5231.4     .05       0
Bank Sta=4974.3,5030.2
XS Rating Curve= 0 ,0
Exp/Cntr=0.3,0.1

Type RM Length L Ch R = 1 ,19884   ,567,567,567
BEGIN DESCRIPTION:
Harts Creek 28.0
END DESCRIPTION:
XS GIS Cut Line= 4
      2283678.98      7183409.99      2282341.87      7182793.89
        2282129.        7182760.      2281728.99        7182710.
#Sta/Elev= 30
  3311.9  904.56  3320.6  901.07  3326.1  904.71  3343.6  894.96  3349.1   897.4
  3355.9  889.29  3366.5  885.53    3372  886.93    3395  871.52  3417.9  863.06
  3486.8  851.76  3532.1  847.33  3801.8  830.52    3945  818.51  4088.3  812.03
  4111.3  809.14  4225.7  814.15  4323.4  813.26  4351.9  810.75  4387.2  814.77
  4909.8  814.33    4949  814.29  4979.4  807.71  4990.6   802.2  5005.6   802.7
  5019.8  811.44  5029.9  813.23    5119  816.51  5198.7  825.15  5402.8  834.42
#Mann= 6 ,-1 , 0
  3311.9     .12       0  4387.2     .05       0  4909.8     .12       0
    4949     .07       0  5029.9     .12       0    5119     .05       0
Bank Sta=4949,5029.9
XS Rating Curve= 0 ,0
Exp/Cntr=0.3,0.1

Type RM Length L Ch R = 1 ,19317   ,565,565,565
BEGIN DESCRIPTION:
Harts Creek 27.0
END DESCRIPTION:
XS GIS Cut Line= 3
      2283329.01      7183110.01        2282529.        7182510.
      2281729.01        7182010.
#Sta/Elev= 30
    4000  836.14  4021.9  831.59  4036.5  830.43  4057.3  830.48  4107.3  825.53
  4292.7  814.94  4363.6  809.12    4400  808.09  4436.5  812.39  4471.9  813.53
  4592.7  813.27  4678.1   809.2  4707.3  812.39    4714   811.4  4894.9  812.82
  4936.5  813.98  4942.7  813.88    4950  811.63  4965.4  801.91  4978.4  801.91
  4986.5  805.28  4996.9  807.05  5007.7  806.64  5013.6  813.32    5385  813.01
  5496.7  815.32  5530.7  815.87  5640.4  825.38  5731.7  829.31  5943.4  842.94
#Mann= 7 ,-1 , 0
    4000     .12       0    4714     .05       0  4894.9     .12       0
  4936.5    .033       0  5013.6     .12       0  5496.7     .12       0
  5640.4     .05       0
Bank Sta=4942.7,5013.6
XS Rating Curve= 0 ,0
Exp/Cntr=0.3,0.1

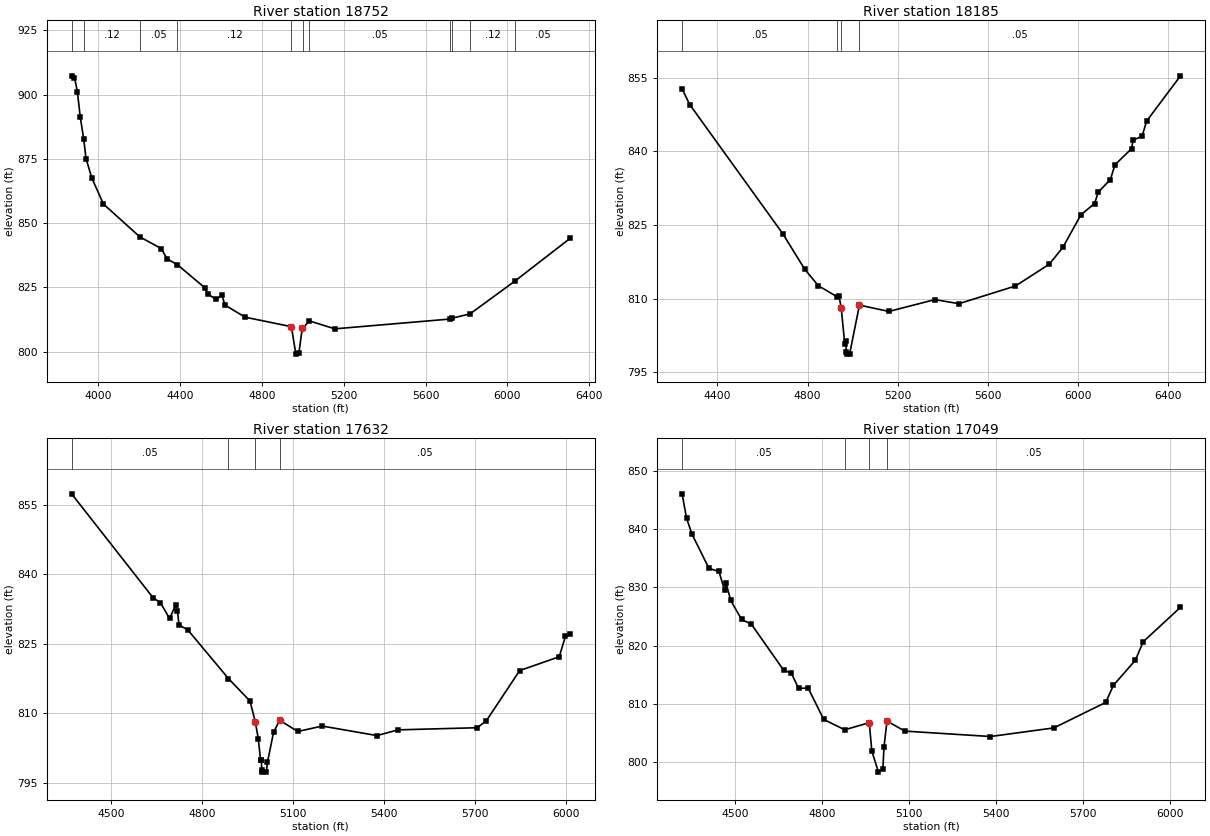
Type RM Length L Ch R = 1 ,18752   ,567,567,567
BEGIN DESCRIPTION:
Harts Creek 26.0
END DESCRIPTION:
XS GIS Cut Line= 4
        2283779.        7183060.        2282979.        7182260.
      2282819.29      7182112.86      2281745.84      7181932.66
#Sta/Elev= 30
  3868.9   907.3    3883  906.63  3897.2  901.18  3911.3  891.25  3928.1  882.79
  3939.6  875.07  3967.9  867.51  4024.5   857.4  4203.1  844.59  4307.3  840.09
  4335.6  836.08  4386.3   833.8  4519.4  824.88  4533.6  822.45    4576  820.28
  4604.3  821.93  4618.4  818.11  4717.4  813.37  4943.7  809.68  4965.4  798.99
  4980.5  799.49  4996.7  809.03  5000.3  809.03  5030.4  811.95  5155.9  808.83
  5717.5  812.63  5730.9  812.99  5817.6  814.67  6036.1  827.39  6305.9  844.01
#Mann= 11 ,-1 , 0
  3868.9     .05       0  3928.1     .12       0  4203.1     .05       0
  4386.3     .12       0  4943.7     .07       0  5000.3     .12       0
  5030.4     .05       0  5717.5     .12       0  5730.9     .05       0
  5817.6     .12       0  6036.1     .05       0
Bank Sta=4943.7,4996.7
XS Rating Curve= 0 ,0
Exp/Cntr=0.3,0.1

Type RM Length L Ch R = 1 ,18185   ,553,553,553
BEGIN DESCRIPTION:
Harts Creek 25.0
END DESCRIPTION:
XS GIS Cut Line= 3
      2283827.14      7181869.95        2283079.        7181760.
      2281629.02        7181660.
#Sta/Elev= 30
  4243.9  852.73  4277.7  849.54  4691.2  823.19  4787.8  815.99  4848.5  812.64
  4931.3   810.4  4939.4  810.65  4949.5  808.08  4965.2  800.74  4970.2  801.45
  4971.3  799.23  4973.3  798.73  4986.5  798.73  5030.1  808.71  5160.5  807.42
  5364.7  809.83  5471.2     809  5721.8   812.6  5872.1  817.05  5932.3  820.48
  6012.5  827.14  6072.6  829.38  6088.9  831.72  6142.8  834.27  6162.8  837.27
  6236.8  840.58    6243  842.29  6283.1  843.09  6303.2  846.17  6453.5  855.39
#Mann= 4 ,-1 , 0
  4243.9     .05       0  4931.3     .12       0  4949.5    .033       0
  5030.1     .05       0
Bank Sta=4949.5,5030.1
XS Rating Curve= 0 ,0
Exp/Cntr=0.3,0.1

Type RM Length L Ch R = 1 ,17632   ,583,583,583
BEGIN DESCRIPTION:
Harts Creek 24.0
END DESCRIPTION:
XS GIS Cut Line= 3
      2283849.06      7181339.44        2283229.        7181260.
      2282213.74      7181206.53
#Sta/Elev= 30
  4370.7  857.35  4639.8  834.88  4663.1   833.9  4693.4  830.46  4713.5  833.33
  4719.5  832.13  4724.5  829.07  4753.9  827.97  4887.5  817.49  4958.5  812.64
  4975.7  808.18  4985.7  804.54  4993.3  799.89  4995.8  799.89  4997.2  797.81
  4999.2  797.31  5012.4  797.31  5015.9  799.44  5035.9  805.87  5055.9   808.5
    5116  806.08  5196.1  807.25  5376.4   805.2  5446.5  806.43  5706.8  806.89
  5736.9  808.38  5846.7  819.22  5977.2   822.2  5997.2  826.58  6012.5  827.06
#Mann= 4 ,-1 , 0
  4370.7     .05       0  4887.5     .12       0  4975.7    .033       0
  5055.9     .05       0
Bank Sta=4975.7,5055.9
XS Rating Curve= 0 ,0
Exp/Cntr=0.3,0.1

Type RM Length L Ch R = 1 ,17049   ,525,525,525
BEGIN DESCRIPTION:
Harts Creek 23.0
END DESCRIPTION:
XS GIS Cut Line= 3
      2283804.15      7180588.35        2283129.        7180710.
      2282116.18      7180909.47
#Sta/Elev= 30
  4318.2  846.12  4333.6  841.92  4352.3  839.18  4410.9  833.28  4445.4  832.76
  4464.5  829.53  4469.6  830.78    4486  827.76  4523.2   824.5  4557.1  823.68
  4668.9  815.72  4694.2  815.31  4719.7  812.65  4752.9  812.68  4806.5  807.28
  4878.9  805.51  4963.6  806.73  4972.3  801.86  4995.1  798.22  5010.3  798.72
  5014.4  802.59  5024.6     807  5086.3  805.28  5381.3  804.35  5599.9  805.83
  5778.8  810.22  5805.3  813.17  5880.7  817.47    5908  820.66  6036.5   826.6
#Mann= 4 ,-1 , 0
  4318.2     .05       0  4878.9     .12       0  4963.6    .035       0
  5024.6     .05       0
Bank Sta=4963.6,5024.6
XS Rating Curve= 0 ,0
Exp/Cntr=0.3,0.1