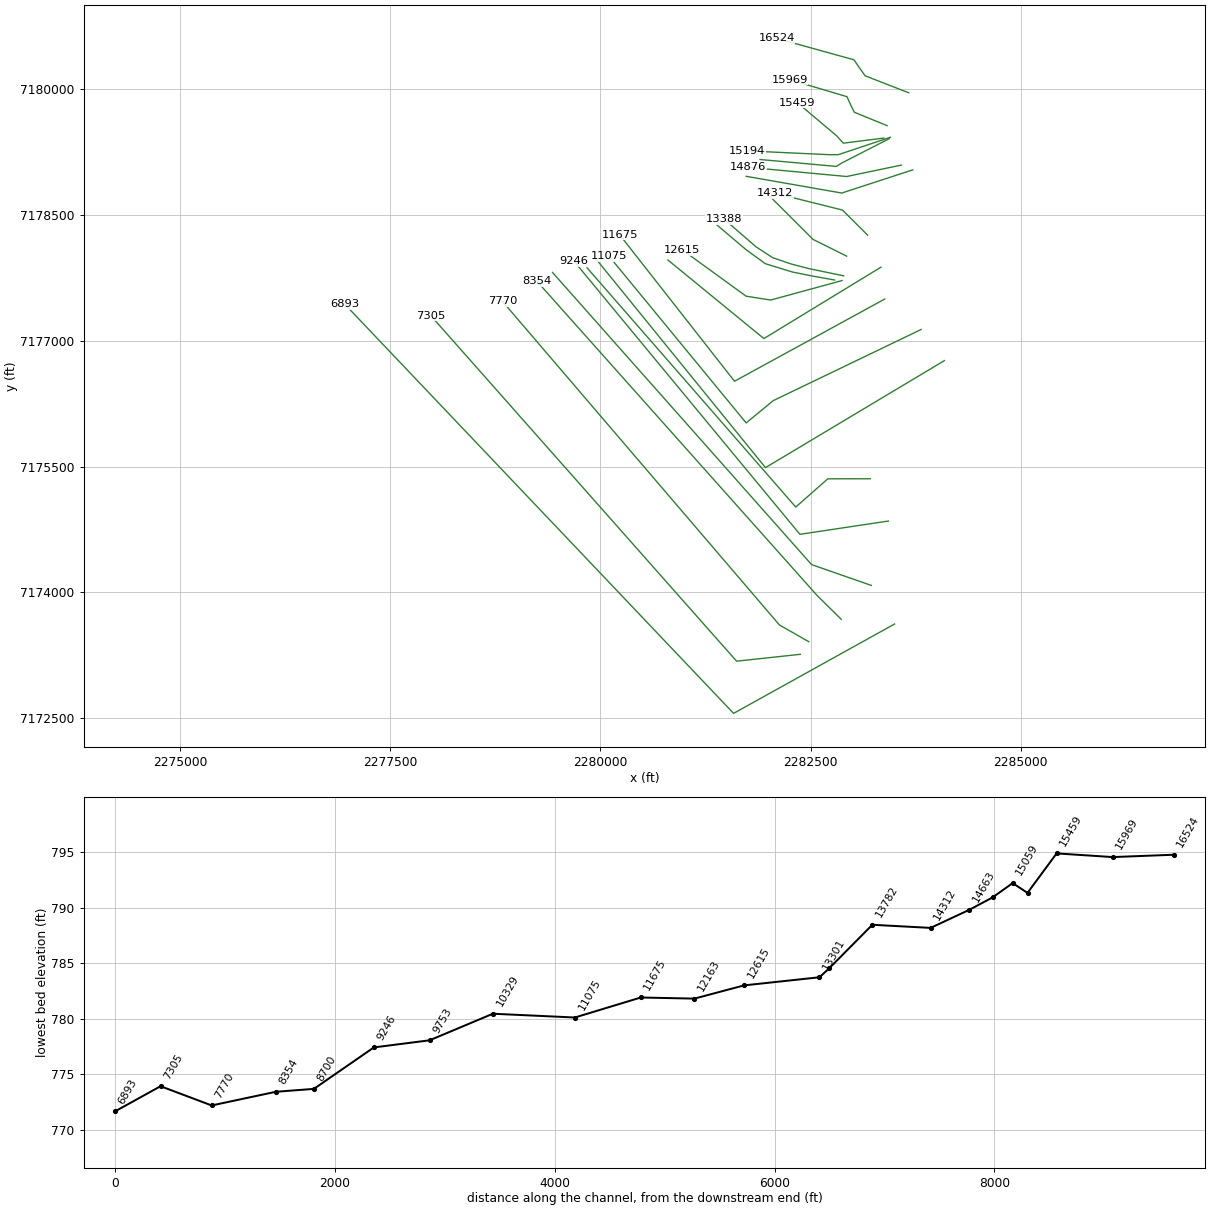
HEC-RAS study Harts Creek.prj: Harts Creek Base Level Engineering

--- Harts Creek.g01 (geometry) --- (continued)

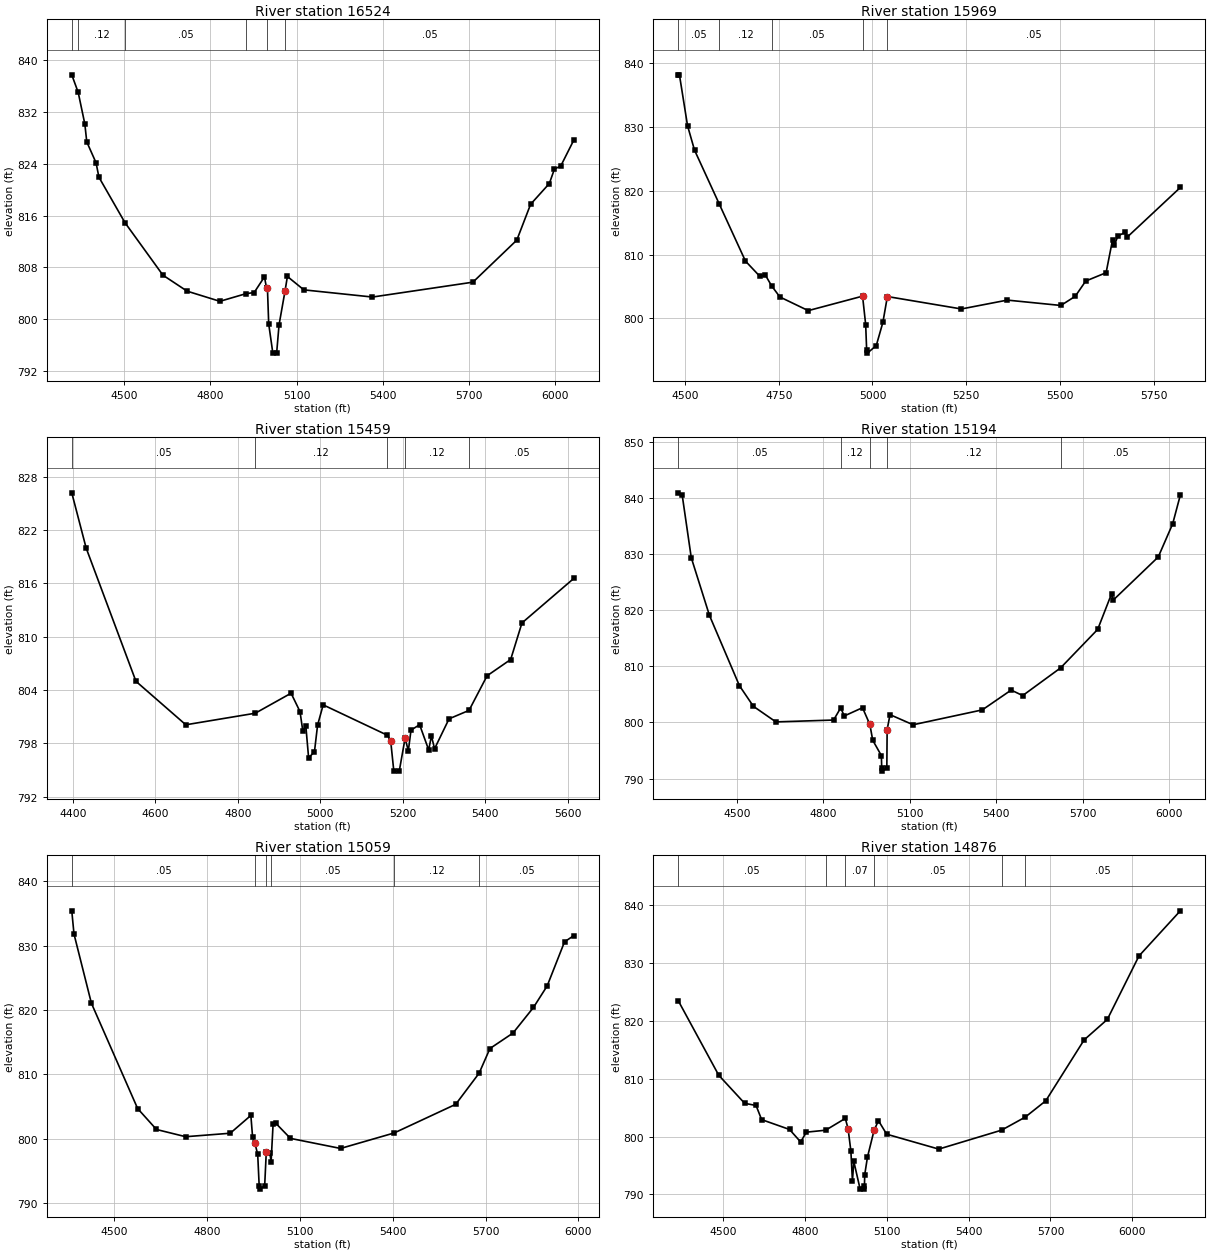
Type RM Length L Ch R = 1 ,16524   ,555,555,555
BEGIN DESCRIPTION:
Harts Creek 22.0
END DESCRIPTION:
XS GIS Cut Line= 5
      2283667.58      7179958.88      2283148.99      7180161.59
        2283079.        7180260.      2283016.35      7180352.49
      2282094.07       7180608.4
#Sta/Elev= 30
  4317.5  837.78  4339.9  835.06    4363  830.16  4369.7  827.41  4401.9  824.19
    4412  821.95  4502.5  814.93  4634.6  806.81  4718.7  804.34  4832.7  802.77
  4922.6  803.94    4952  804.13  4987.7  806.55  4995.1  804.81  4998.1  804.81
  5002.5  799.28  5016.9  794.76  5030.1  794.76  5038.5  799.14  5059.5  804.41
  5067.5  806.61  5124.8  804.54  5363.5  803.43  5712.9  805.73  5865.5  812.23
  5913.5  817.77  5978.7  820.98  5996.5  823.23  6018.1  823.66  6063.9  827.71
#Mann= 6 ,-1 , 0
  4317.5     .05       0  4339.9     .12       0  4502.5     .05       0
  4922.6     .12       0  4995.1     .07       0  5059.5     .05       0
Bank Sta=4998.1,5059.5
XS Rating Curve= 0 ,0
Exp/Cntr=0.3,0.1

Type RM Length L Ch R = 1 ,15969   ,510,510,510
BEGIN DESCRIPTION:
Harts Creek 21.0
END DESCRIPTION:
XS GIS Cut Line= 5
      2283409.83      7179566.76      2283019.99      7179726.95
        2282979.        7179810.      2282932.81      7179912.24
      2282249.33       7180116.4
#Sta/Elev= 30
  4481.8  838.22    4485  838.22  4506.6  830.24  4525.2  826.41    4591  817.98
  4661.2  808.99  4698.9  806.64  4714.6  806.76  4730.9  805.11    4753  803.36
  4828.7  801.22  4973.6  803.49  4981.9  799.04  4984.5  795.05  4986.5  794.55
  5010.2  795.74  5027.8  799.37  5039.8  803.43  5237.3  801.48  5359.8  802.87
  5502.7  802.03  5541.1  803.47    5569  805.86  5623.4  807.17  5640.5   812.3
  5645.7  811.53  5654.8  812.92  5673.6   813.5  5678.8   812.7  5821.4  820.54
#Mann= 5 ,-1 , 0
  4481.8     .05       0    4591     .12       0  4730.9     .05       0
  4973.6     .07       0  5039.8     .05       0
Bank Sta=4973.6,5039.8
XS Rating Curve= 0 ,0
Exp/Cntr=0.3,0.1

Type RM Length L Ch R = 1 ,15459   ,265,265,265
BEGIN DESCRIPTION:
Harts Creek 20.0
END DESCRIPTION:
XS GIS Cut Line= 4
      2283373.52      7179418.74       2282889.2      7179357.71
      2282812.52      7179443.22      2282342.71       7179840.4
#Sta/Elev= 30
    4397  826.17  4431.9  819.96  4552.7  804.98  4673.7  800.09  4842.2  801.39
  4929.1  803.64  4950.8  801.57  4957.5  799.41    4965   799.9  4971.7  796.36
  4985.9  797.08  4993.4  800.05    5007  802.33    5163  798.91  5170.7  798.31
  5178.4  794.88  5191.6  794.88  5205.8  798.59  5213.6  797.16  5220.1  799.49
    5241   800.1    5263  797.26  5269.6  798.83  5277.3   797.4  5312.4  800.76
  5360.9  801.71  5404.7   805.6  5461.9  807.43  5489.3  811.54  5615.2  816.55
#Mann= 5 ,-1 , 0
    4397     .05       0  4842.2     .12       0    5163     .07       0
  5205.8     .12       0  5360.9     .05       0
Bank Sta=5170.7,5205.8
XS Rating Curve= 0 ,0
Exp/Cntr=0.3,0.1

Type RM Length L Ch R = 1 ,15194   ,135,135,135
BEGIN DESCRIPTION:
Harts Creek 19.2
END DESCRIPTION:
XS GIS Cut Line= 4
      2283450.32      7179428.17      2282831.16       7179220.8
      2282734.18      7179219.85       2281742.5       7179265.9
#Sta/Elev= 30
  4296.4  840.91    4310  840.55  4341.6  829.36  4404.7  819.08  4508.7  806.56
  4557.2  802.88  4635.3   800.1  4835.6  800.43  4860.1  802.58  4872.9  801.16
    4936  802.63  4961.5  799.64  4971.5  796.83  5001.5   794.1  5002.7  791.83
  5004.7  791.33  5020.4  791.83  5021.5  798.72  5031.5  801.39  5111.6  799.59
  5351.9  802.24    5452  805.77    5492  804.79  5623.5  809.72  5752.3  816.58
  5800.7  822.96  5805.7  821.77  5962.5  829.48  6012.6  835.39  6039.1   840.5
#Mann= 5 ,-1 , 0
  4296.4     .05       0  4860.1     .12       0  4961.5     .07       0
  5020.4     .12       0  5623.5     .05       0
Bank Sta=4961.5,5021.5
XS Rating Curve= 0 ,0
Exp/Cntr=0.3,0.1

Type RM Length L Ch R = 1 ,15059   ,183,183,183
BEGIN DESCRIPTION:
Harts Creek 19.1
END DESCRIPTION:
XS GIS Cut Line= 4
      2283435.37      7179411.18      2282869.12      7179120.05
      2282806.51      7179080.33      2281899.01      7179162.88
#Sta/Elev= 30
  4363.3  835.38  4370.5  831.78  4426.7  821.05  4576.1  804.71    4637  801.46
  4731.3  800.34  4875.3  800.88  4941.9  803.64  4947.5  800.28  4955.2  799.29
    4964  797.61  4968.8  792.71  4970.8  792.21  4986.5  792.71  4991.8  798.04
    5003  797.87  5007.3  796.48  5013.7  802.27    5023   802.4  5069.8  800.08
  5231.7  798.52  5404.8  800.92  5603.8  805.37  5679.4   810.2  5714.3  814.02
  5788.8  816.42  5854.9  820.39  5899.2  823.73  5955.3  830.57  5985.4  831.54
#Mann= 6 ,-1 , 0
  4363.3     .05       0  4955.2     .07       0  4991.8     .12       0
  5007.3     .05       0  5404.8     .12       0  5679.4     .05       0
Bank Sta=4955.2,4991.8
XS Rating Curve= 0 ,0
Exp/Cntr=0.3,0.1

Type RM Length L Ch R = 1 ,14876   ,213,213,213
BEGIN DESCRIPTION:
Harts Creek 19.0
END DESCRIPTION:
XS GIS Cut Line= 3
      2283577.93      7179095.69        2282929.        7178960.
      2281758.23      7179070.08
#Sta/Elev= 30
  4336.7  823.45  4485.2  810.57    4580  805.73  4621.7  805.36  4642.1  802.92
  4744.3  801.22  4785.1  799.06  4805.6  800.75  4876.6  801.09  4948.6  803.13
  4958.8  801.35    4969   797.5  4974.7  792.36  4979.8  795.69  5002.9  790.92
  5016.6  790.92  5018.6  791.42  5019.8  793.44  5029.8  796.46    5054  801.07
    5070  802.74  5100.1   800.4  5290.9  797.83    5521   801.1  5607.6  803.35
  5682.7  806.16  5823.3  816.68  5908.2  820.21  6024.2  831.17  6175.6  838.96
#Mann= 6 ,-1 , 0
  4336.7     .05       0  4876.6     .12       0  4948.6     .07       0
    5054     .05       0    5521     .12       0  5607.6     .05       0
Bank Sta=4958.8,5054
XS Rating Curve= 0 ,0
Exp/Cntr=0.3,0.1

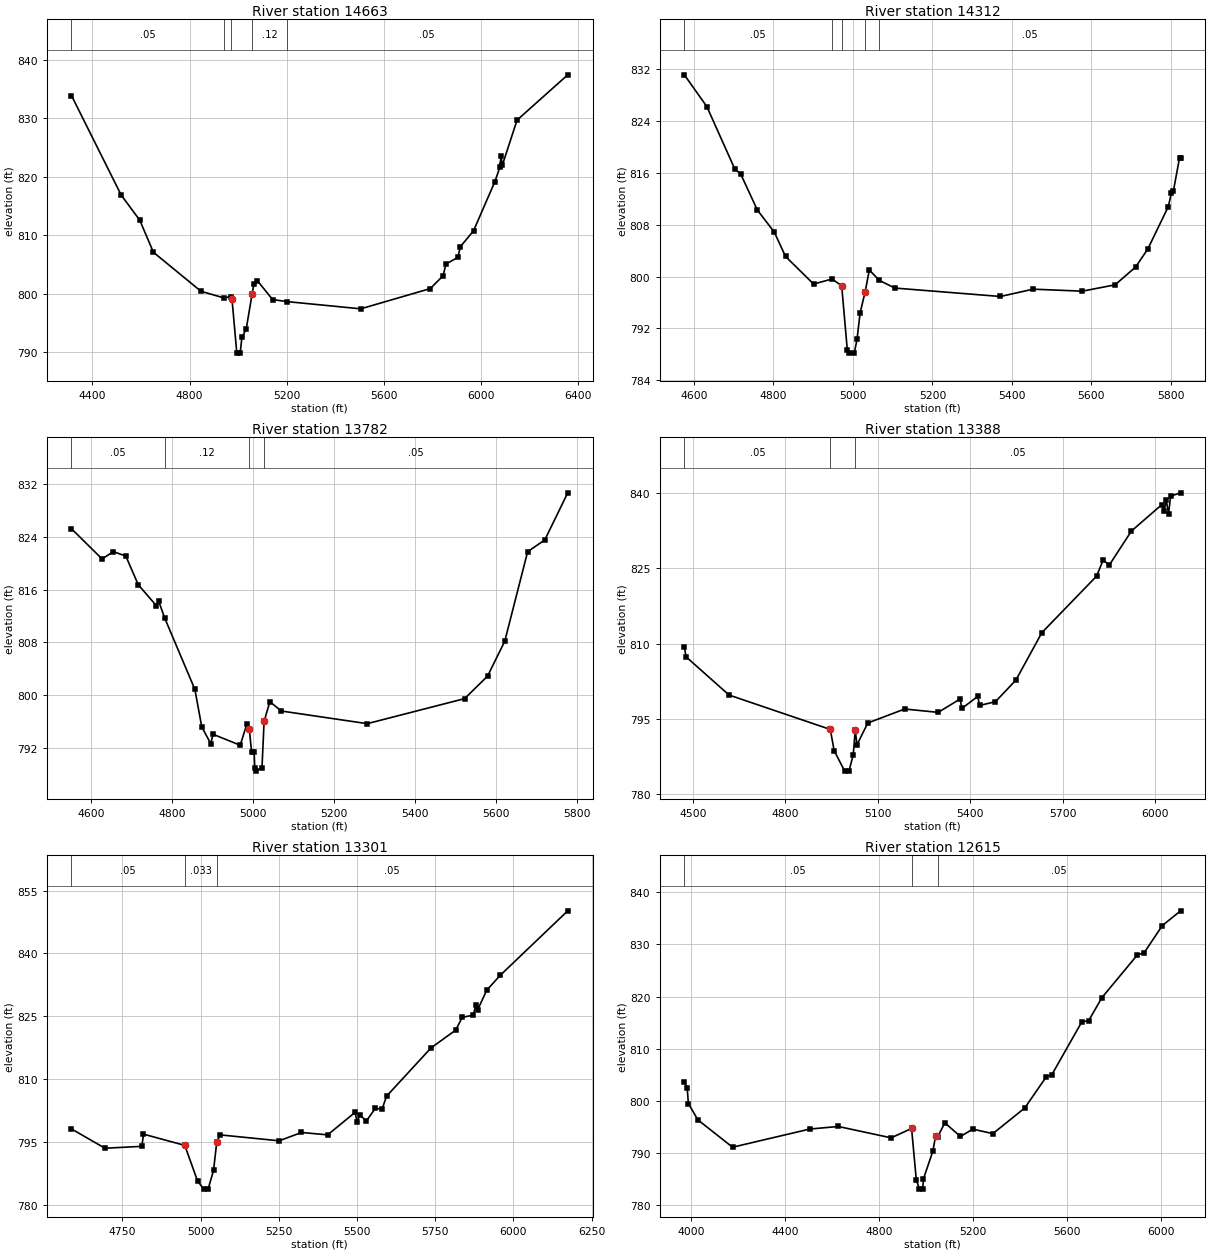
Type RM Length L Ch R = 1 ,14663   ,351,351,351
BEGIN DESCRIPTION:
Harts Creek 18.1
END DESCRIPTION:
XS GIS Cut Line= 3
      2283716.48      7179039.48      2282870.66      7178762.67
      2281733.25      7178962.48
#Sta/Elev= 30
  4313.4  833.87  4518.3  816.83  4594.8  812.54    4651  807.05  4847.4  800.37
  4941.3  799.25  4969.6  799.46  4974.9  799.02  4994.6   789.8  5008.3   789.8
  5015.7  792.49  5033.3  793.91  5057.8  799.95  5065.2  801.68  5078.9  802.22
    5142  798.97    5200  798.62  5505.2  797.38  5791.8  800.84  5844.7  803.05
  5856.3  805.03  5905.5  806.19  5915.8  808.01  5969.9  810.72  6057.9  819.13
  6078.2  821.58  6083.5  823.53  6088.6  821.94  6149.3  829.66  6358.2  837.41
#Mann= 5 ,-1 , 0
  4313.4     .05       0  4941.3     .12       0  4969.6     .07       0
  5057.8     .12       0    5200     .05       0
Bank Sta=4974.9,5057.8
XS Rating Curve= 0 ,0
Exp/Cntr=0.3,0.1

Type RM Length L Ch R = 1 ,14312   ,530,530,530
BEGIN DESCRIPTION:
Harts Creek 18.0
END DESCRIPTION:
XS GIS Cut Line= 3
      2283179.01      7178259.99        2282879.        7178560.
        2282079.        7178760.
#Sta/Elev= 30
  4575.7  831.17  4632.3  826.27    4703  816.58  4717.1   815.9  4759.6  810.27
    4802  806.88  4830.3  803.12    4901  798.85  4947.3  799.63  4971.7  798.59
  4985.8  788.69  4989.6  788.18  5003.3  788.18  5010.3  790.29    5018  794.38
  5030.9  797.69  5041.2  801.03  5066.5  799.41  5105.6  798.23  5371.1  796.93
  5453.5  798.06  5577.2  797.75  5659.7  798.73  5711.2  801.47  5742.1  804.27
  5793.7  810.82  5801.4  812.89  5806.6  813.27    5822  818.37  5824.6  818.37
#Mann= 5 ,-1 , 0
  4575.7     .05       0  4947.3     .12       0  4971.7     .07       0
  5030.9     .12       0  5066.5     .05       0
Bank Sta=4971.7,5030.9
XS Rating Curve= 0 ,0
Exp/Cntr=0.3,0.1

Type RM Length L Ch R = 1 ,13782   ,394,394,394
BEGIN DESCRIPTION:
Harts Creek 17.0
END DESCRIPTION:
XS GIS Cut Line= 3
      2282929.03      7178009.98        2282529.        7178210.
      2281978.98      7178760.02
#Sta/Elev= 30
  4552.5  825.23    4628  820.65    4656  821.76  4686.7  821.08  4717.4  816.73
  4762.2  813.55  4767.8  814.24  4782.5   811.7  4857.2  800.85    4874  795.19
  4896.3  792.62  4901.9  794.05    4969  792.39  4985.8  795.66  4991.4   794.9
    4997  791.43  5003.3  791.43    5005  788.96    5007  788.46  5022.8  788.96
    5028  796.01  5042.2  798.99  5070.5  797.58  5282.6  795.66    5523  799.46
  5579.6  802.87    5622  808.15  5678.6  821.75    5721  823.54  5777.6  830.68
#Mann= 4 ,-1 , 0
  4552.5     .05       0  4782.5     .12       0  4991.4     .07       0
    5028     .05       0
Bank Sta=4991.4,5028
XS Rating Curve= 0 ,0
Exp/Cntr=0.3,0.1

Type RM Length L Ch R = 1 ,13388   ,87,87,87
BEGIN DESCRIPTION:
Harts Creek 16.3
END DESCRIPTION:
XS GIS Cut Line= 6
      2282894.27      7177775.02      2282485.15      7177860.18
      2282266.27      7177916.91      2282046.47      7177992.68
      2281850.49       7178121.5      2281473.19      7178449.56
#Sta/Elev= 30
  4472.2  809.38  4477.6  807.36  4617.4  799.72  4946.1  792.85  4958.4  788.64
  4992.8  784.53  5006.6  784.53  5020.4  787.77  5027.2  792.78  5032.4  789.77
  5067.8  794.14  5187.4  796.93  5296.4  796.26  5367.4  798.93  5373.4  797.05
  5424.6  799.45  5430.6  797.64  5481.8  798.38  5548.2  802.67  5632.9  812.18
  5810.5  823.46  5831.4  826.62  5852.3  825.72  5923.5  832.46  6022.5  837.75
  6029.8  836.41  6036.5  838.66  6044.1  835.87  6050.7  839.43  6083.2  840.09
#Mann= 3 , 0 , 0
  4472.2     .05       0  4946.1    .033       0  5027.2     .05       0
Bank Sta=4946.1,5027.2
XS Rating Curve= 0 ,0
Exp/Cntr=0.3,0.1

Type RM Length L Ch R = 1 ,13301   ,686,686,686
BEGIN DESCRIPTION:
Harts Creek 16.2
END DESCRIPTION:
XS GIS Cut Line= 6
      2282785.06      7177725.46      2282536.17      7177769.77
      2282282.46      7177820.97      2281961.44      7177919.99
      2281733.13      7178086.59      2281385.83      7178381.92
#Sta/Elev= 30
  4587.5   798.1  4694.6   793.5  4812.6  793.95  4817.6  796.86  4949.6  794.18
  4990.4   785.7  5010.3  783.74  5024.1  783.74  5041.5  788.19  5051.7  794.88
  5061.9  796.69  5251.5  795.27  5322.5  797.26  5406.2  796.69  5494.1  802.07
  5500.3  799.69  5508.8  801.52  5529.7  799.98    5559  803.05  5579.9  802.76
  5594.6  805.93  5736.8  817.45    5815  821.66  5836.7  824.75  5871.9  825.24
  5879.6  827.62  5886.1   826.6  5914.7   831.2  5957.5  834.74  6173.6  850.15
#Mann= 3 , 0 , 0
  4587.5     .05       0  4949.6    .033       0  5051.7     .05       0
Bank Sta=4949.6,5051.7
XS Rating Curve= 0 ,0
Exp/Cntr=0.3,0.1

Type RM Length L Ch R = 1 ,12615   ,452,452,452
BEGIN DESCRIPTION:
Harts Creek 16.1
END DESCRIPTION:
XS GIS Cut Line= 4
      2282874.51      7177718.53      2282024.79      7177486.17
      2281732.58      7177532.31      2280975.19      7178083.73
#Sta/Elev= 30
  3971.4  803.61  3983.5  802.42  3988.7  799.45  4028.9  796.32  4176.8  791.06
  4505.8  794.55  4627.2  795.04  4852.3  792.86  4939.2  794.66  4959.4  784.76
  4972.8  783.01  4986.6  783.01  4989.8  784.99  5030.3  790.35  5041.3  793.18
  5050.5  793.07  5080.9  795.74  5147.4  793.12  5199.8  794.53  5285.5  793.67
  5421.5   798.6  5513.5  804.62    5536  804.94  5664.2  815.13  5693.5  815.37
  5749.9  819.79  5900.6  827.98    5930  828.43  6007.2  833.63    6085  836.46
#Mann= 3 ,-1 , 0
  3971.4     .05       0  4939.2    .033       0  5050.5     .05       0
Bank Sta=4939.2,5041.3
XS Rating Curve= 0 ,0
Exp/Cntr=0.3,0.1

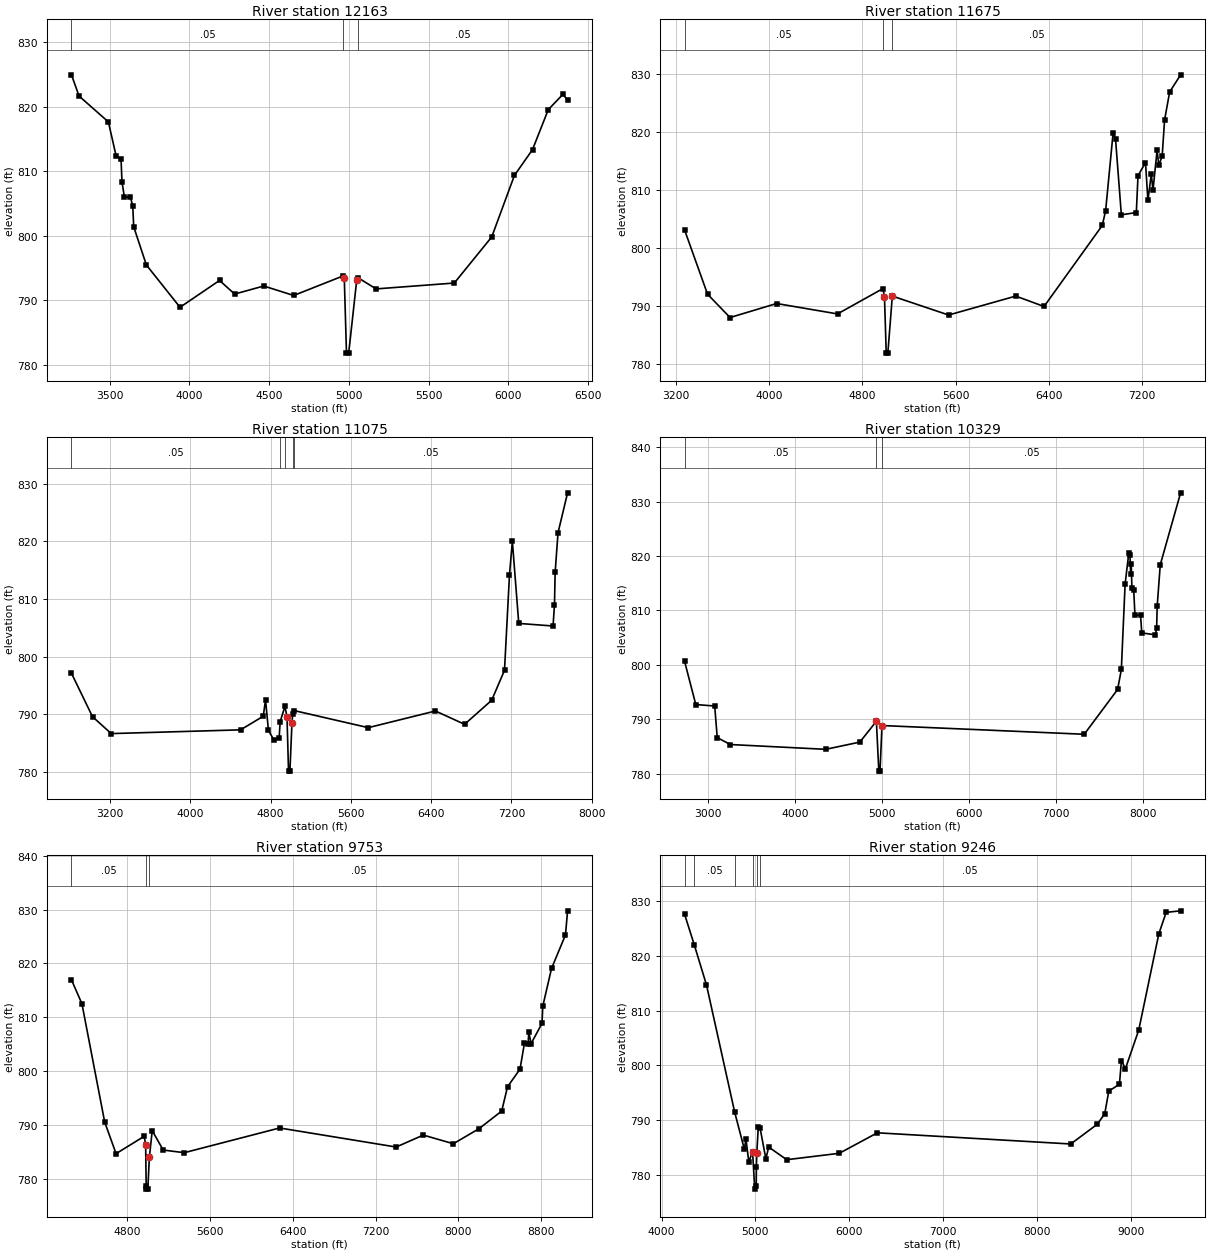
Type RM Length L Ch R = 1 ,12163   ,488,488,488
BEGIN DESCRIPTION:
Harts Creek 16.0
END DESCRIPTION:
XS GIS Cut Line= 3
      2283337.07      7177878.28      2281944.56      7177026.55
      2280802.95       7177963.5
#Sta/Elev= 30
  3261.4  824.98  3308.9  821.69  3492.7  817.68  3541.2   812.4    3572  811.98
  3577.9  808.38  3593.4  805.96  3630.1  806.09  3645.5   804.6  3651.4  801.42
  3730.8  795.49  3941.7  788.93  4189.3  793.09  4284.1  790.98  4466.5  792.23
  4654.1  790.76  4964.6   793.8  4971.1  793.47    4985  781.82  4998.8  781.82
  5049.3  793.19  5056.2  793.53  5170.6  791.78  5660.7  792.69  5895.3  799.84
  6037.4  809.38  6150.8  813.38  6249.8  819.59  6342.4  821.98  6370.6     821
#Mann= 3 ,-1 , 0
  3261.4     .05       0  4964.6    .033       0  5056.2     .05       0
Bank Sta=4971.1,5049.3
XS Rating Curve= 0 ,0
Exp/Cntr=0.3,0.1

Type RM Length L Ch R = 1 ,11675   ,600,600,600
BEGIN DESCRIPTION:
Harts Creek 15.6
END DESCRIPTION:
XS GIS Cut Line= 3
      2283381.49      7177497.77      2281594.96      7176517.52
      2280229.46      7178263.47
#Sta/Elev= 30
  3275.7  803.16  3473.4  792.06  3666.4  788.05  4065.6  790.46  4587.9  788.67
  4978.1  793.04  4990.7  791.53  5005.6  781.92  5019.4  781.92  5057.9  791.74
  5540.5  788.48  6116.6  791.74  6358.9  789.95  6858.1   803.9    6887  806.44
  6951.2  819.85    6972  818.77  7021.8  805.73  7150.2  806.12  7164.7  812.48
  7228.9  814.71  7249.7   808.2  7278.6  812.74  7293.1  809.96  7328.3  816.85
  7342.8  814.29  7371.7  815.78  7392.5  822.05  7435.9  826.87    7530  829.83
#Mann= 3 ,-1 , 0
  3275.7     .05       0  4978.1    .033       0  5057.9     .05       0
Bank Sta=4990.7,5057.9
XS Rating Curve= 0 ,0
Exp/Cntr=0.3,0.1

Type RM Length L Ch R = 1 ,11075   ,746,746,746
BEGIN DESCRIPTION:
Harts Creek  15.5
END DESCRIPTION:
XS GIS Cut Line= 4
      2283815.19      7177134.94      2282056.43      7176286.54
      2281733.51      7176020.19      2280103.19      7178008.06
#Sta/Elev= 30
  2816.9  797.09  3026.5  789.56    3213  786.63  4501.4  787.28  4727.5  789.64
  4750.1  792.47  4779.2  787.17  4836.2  785.45  4885.7  785.87  4895.9   788.7
  4943.1  791.33  4963.9  789.57  4979.2  780.12    4993  780.12  5013.4  788.51
  5021.2  790.09  5038.3  790.61  5773.6  787.66  6442.4  790.55  6733.1  788.24
    7003  792.41  7130.7  797.61  7180.2  814.13  7208.9  819.99  7272.8  805.74
  7614.4  805.29  7628.7  809.02  7635.2  814.58  7663.9  821.47  7759.1  828.39
#Mann= 5 ,-1 , 0
  2816.9     .05       0  4895.9     .12       0  4943.1     .07       0
  5021.2     .12       0  5038.3     .05       0
Bank Sta=4963.9,5013.4
XS Rating Curve= 0 ,0
Exp/Cntr=0.3,0.1

Type RM Length L Ch R = 1 ,10329   ,576,576,576
BEGIN DESCRIPTION:
Harts Creek 15.4
END DESCRIPTION:
XS GIS Cut Line= 3
      2284092.01      7176763.63      2281963.27      7175486.85
      2279933.59      7177993.19
#Sta/Elev= 30
  2728.1  800.71  2857.8  792.71  3075.5  792.43  3104.8  786.62  3256.3  785.35
  4352.5  784.47  4745.2   785.8  4935.5  789.63  4963.6  780.46  4977.4  780.46
  4999.9  788.79  5005.7  788.84  7326.9  787.24  7710.8  795.48  7753.7  799.15
  7796.8  814.83  7839.5  820.58  7852.9  820.21  7860.8  816.65  7867.2  818.58
  7875.2  814.21    7896  813.72  7910.4  809.11  7974.3  809.19  7988.7  805.88
  8145.4  805.52  8159.7  806.77  8166.2  810.84  8201.4  818.41  8435.5  831.64
#Mann= 3 ,-1 , 0
  2728.1     .05       0  4935.5     .04       0  5005.7     .05       0
Bank Sta=4935.5,4999.9
XS Rating Curve= 0 ,0
Exp/Cntr=0.3,0.1

Type RM Length L Ch R = 1 ,9753    ,507,507,507
BEGIN DESCRIPTION:
Harts Creek 15.3
END DESCRIPTION:
XS GIS Cut Line= 4
      2283210.23      7175354.14      2282705.21      7175353.52
       2282323.4      7175016.45      2279840.89      7177870.67
#Sta/Elev= 30
  4258.4  816.96  4359.6   812.5  4579.6  790.53  4689.6  784.66  4961.4  787.88
  4975.6  786.31  4980.9  778.57  4982.9  778.07  4996.7  778.07  5011.6     784
  5039.2  788.92  5145.4  785.33  5349.2  784.84  6271.1  789.43  7397.9  785.89
  7660.3  788.11  7950.8   786.5  8198.6  789.29  8418.4  792.57  8474.9  797.09
  8595.5  800.36  8638.2  805.17  8673.4  805.05    8681  807.29  8701.8  805.08
  8808.2  808.86  8815.8  812.06  8900.3  819.06  9035.1  825.29  9055.5  829.77
#Mann= 3 , 0 , 0
  4258.4     .05       0  4975.6     .04       0  5011.6     .05       0
Bank Sta=4975.6,5011.6
XS Rating Curve= 0 ,0
Exp/Cntr=0.3,0.1

Type RM Length L Ch R = 1 ,9246    ,546,546,546
BEGIN DESCRIPTION:
Harts Creek 15.2
END DESCRIPTION:
XS GIS Cut Line= 3
      2283425.88      7174849.77      2282373.19      7174691.24
      2279688.18      7177946.27
#Sta/Elev= 30
  4244.9  827.65  4348.5  822.05  4478.9  814.71  4779.9  791.44  4882.6   784.7
  4899.1  786.62  4929.4  782.44  4969.9  784.22  4993.2  777.43  5009.2  777.93
  5010.3  781.52  5015.5   784.1  5030.5  788.77  5049.1  788.66  5111.4  782.96
  5141.8  785.11  5333.5   782.8  5893.7  783.97  6298.9  787.71  8358.8  785.67
  8642.8  789.29    8721  791.21    8764  795.32  8877.4  796.57  8898.6  800.88
  8941.2   799.4  9083.2  806.48  9296.9  824.03  9375.1  827.95    9529  828.23
#Mann= 6 ,-1 , 0
  4244.9     .12       0  4348.5     .05       0  4779.9     .12       0
  4969.9     .07       0  5015.5     .12       0  5049.1     .05       0
Bank Sta=4969.9,5015.5
XS Rating Curve= 0 ,0
Exp/Cntr=0.3,0.1

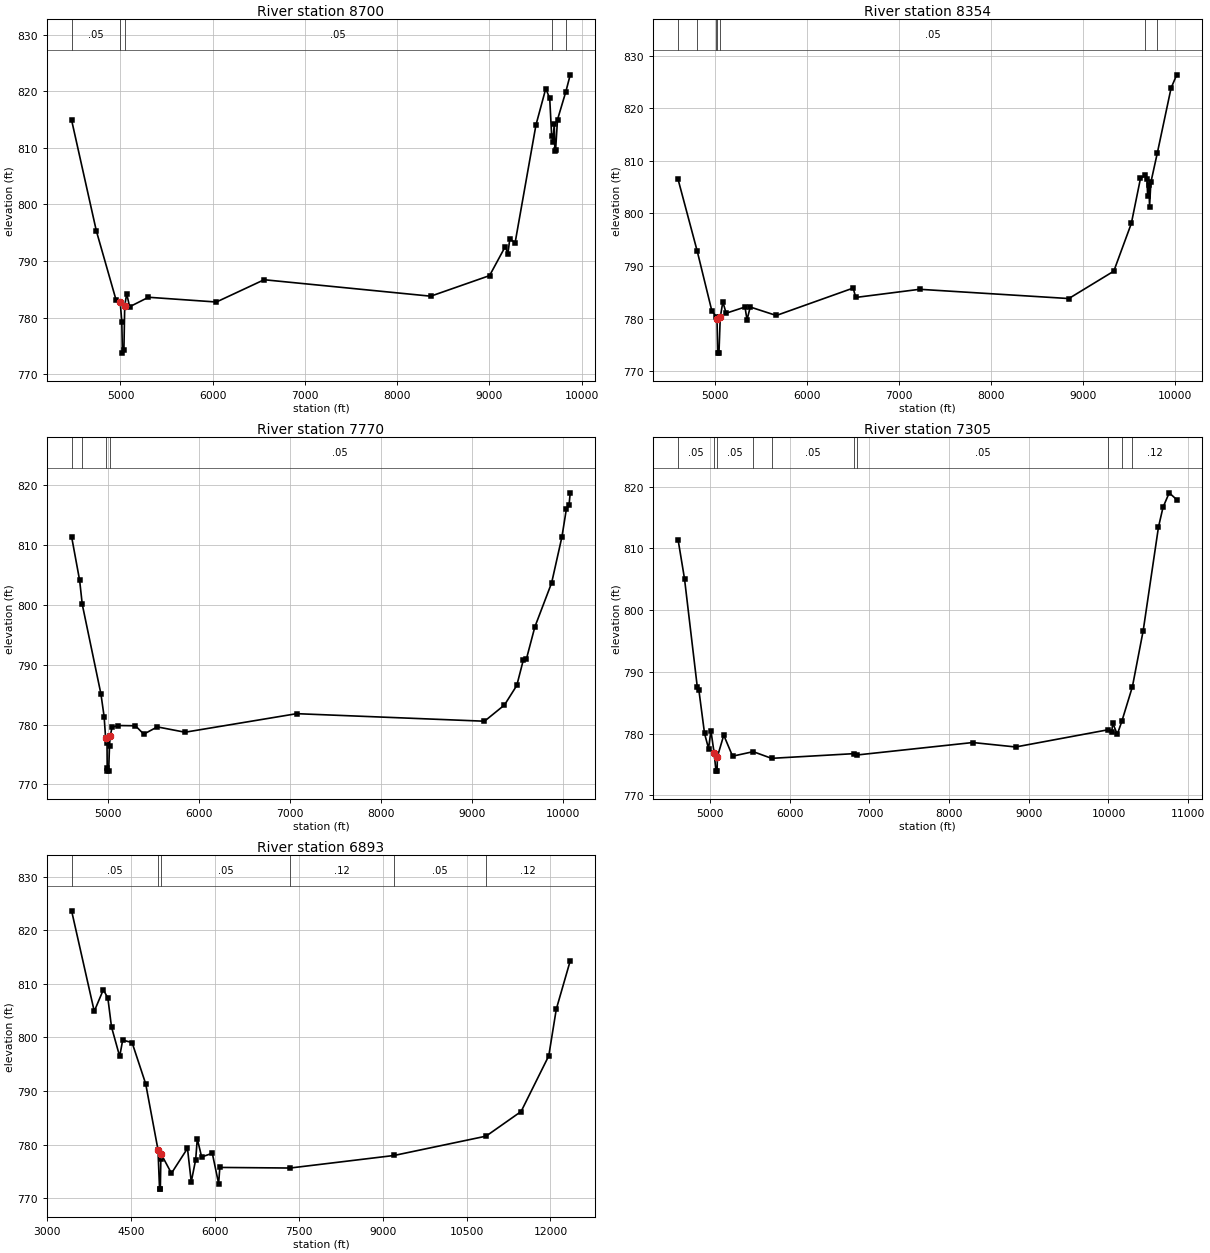
Type RM Length L Ch R = 1 ,8700    ,346,346,346
BEGIN DESCRIPTION:
Harts Creek 15.1
END DESCRIPTION:
XS GIS Cut Line= 3
       2283222.7      7174081.56      2282511.78        7174330.
      2279429.77      7177815.01
#Sta/Elev= 30
  4470.1  814.91  4738.8  795.29  4950.7  783.18  4997.1   782.7  5014.3  779.28
  5021.1   773.7  5037.1   774.2    5046  782.04  5067.2  784.22    5099   781.9
  5303.3  783.58  6039.6  782.74  6557.4  786.68  8363.3  783.77  9001.1  787.41
  9171.3  792.54  9199.8  791.27  9220.7  793.95  9277.6  793.19  9504.3  814.07
  9610.5  820.49  9653.2  818.75  9674.1  812.17  9688.3  811.11  9702.5   814.3
  9709.2  809.38  9716.7  809.55  9737.6     815  9828.1  819.95  9875.5  822.92
#Mann= 5 ,-1 , 0
  4470.1     .05       0  4997.1     .04       0    5046     .05       0
  9674.1     .12       0  9828.1     .05       0
Bank Sta=4997.1,5046
XS Rating Curve= 0 ,0
Exp/Cntr=0.3,0.1

Type RM Length L Ch R = 1 ,8354    ,584,584,584
BEGIN DESCRIPTION:
Harts Creek 15.0
END DESCRIPTION:
XS GIS Cut Line= 3
      2282864.85      7173677.55        2282579.        7173960.
      2279243.69      7177711.07
#Sta/Elev= 30
  4598.4  806.48    4807   792.8  4964.9  781.51  5014.1  780.34  5021.6  779.97
  5028.8  773.44  5042.8  773.44  5056.7  780.23  5085.1  783.19  5120.7  781.03
    5326  782.21  5347.7  779.75  5382.8  782.21  5666.3   780.6  6501.7  785.81
  6530.1  784.03  7224.1  785.58  8846.4  783.82  9335.6  789.03  9526.2   798.1
  9625.7  806.67  9680.1  807.25  9696.8  806.53  9703.5  803.34  9717.7  805.33
  9724.4  801.26  9738.6  805.91  9809.7  811.57  9958.5  823.86 10019.7  826.37
#Mann= 7 ,-1 , 0
  4598.4     .05       0    4807     .12       0  5014.1     .05       0
  5021.6     .07       0  5056.7     .05       0  9680.1     .12       0
  9809.7     .05       0
Bank Sta=5021.6,5056.7
XS Rating Curve= 0 ,0
Exp/Cntr=0.3,0.1

Type RM Length L Ch R = 1 ,7770    ,465,465,465
BEGIN DESCRIPTION:
Harts Creek 14.0
END DESCRIPTION:
XS GIS Cut Line= 3
      2282478.99      7173410.01        2282129.        7173610.
      2278832.76      7177472.24
#Sta/Elev= 30
  4601.3  811.38  4689.8  804.07  4718.5  800.07  4923.8   785.1    4959  781.29
  4974.9   777.8  4990.7   776.9  4992.5  772.71  4994.5  772.21  5008.5  772.21
  5018.1  776.47  5025.8  778.12  5046.7  779.54  5110.3  779.83  5302.5  779.79
  5394.7  778.39  5543.4   779.6  5848.1  778.71  7075.6  781.81  9139.7  780.55
  9359.3  783.26  9494.4  786.52  9565.8  790.74  9600.9  790.98  9693.1   796.3
  9877.6  803.67  9990.6  811.34   10040  816.03 10068.6   816.6   10082  818.71
#Mann= 4 ,-1 , 0
  4601.3     .12       0  4718.5     .05       0  4974.9    .033       0
  5025.8     .05       0
Bank Sta=4974.9,5025.8
XS Rating Curve= 0 ,0
Exp/Cntr=0.3,0.1

Type RM Length L Ch R = 1 ,7305    ,412,412,412
BEGIN DESCRIPTION:
Harts Creek 13.0
END DESCRIPTION:
XS GIS Cut Line= 3
      2282379.04        7173260.      2281619.86      7173177.79
      2277983.53      7177297.76
#Sta/Elev= 30
  4597.6   811.4  4678.1  805.09    4839  787.52  4859.2     787  4929.6  780.04
  4979.9   777.6    5010  780.47  5050.3  776.84  5073.4  773.94  5087.4  773.94
  5090.5  776.24    5171  779.76  5281.6  776.36  5540.6  777.09  5770.9  776.01
  6806.8  776.77  6841.4  776.55  8296.8  778.57  8834.7  777.85  9996.8  780.64
 10039.4  780.23 10053.6  781.71 10110.5  779.89 10167.8  782.02 10300.2  787.61
 10435.9   796.7 10627.5  813.45 10684.4  816.64 10762.2  818.99 10856.4  817.89
#Mann= 10 ,-1 , 0
  4597.6     .05       0  5050.3     .04       0  5090.5     .05       0
  5540.6     .12       0  5770.9     .05       0  6806.8     .12       0
  6841.4     .05       0  9996.8     .12       0 10167.8     .05       0
 10300.2     .12       0
Bank Sta=5050.3,5090.5
XS Rating Curve= 0 ,0
Exp/Cntr=0.3,0.1

Type RM Length L Ch R = 1 ,6893    ,0,0,0
BEGIN DESCRIPTION:
Harts Creek 12.0
END DESCRIPTION:
XS GIS Cut Line= 3
      2283499.24       7173621.5      2281583.97      7172555.14
      2276955.58      7177439.12
#Sta/Elev= 30
  3432.7  823.65    3838  804.89  4000.3  808.92  4081.5  807.36  4146.7  801.97
    4293  796.46  4346.7  799.52  4514.8  799.05  4758.3  791.35  4978.1  779.06
  5006.3  771.69  5020.3  771.69  5029.3  777.33  5035.3  778.23  5219.1  774.65
    5506   779.3  5573.3  773.04    5653  777.22  5681.3   781.1    5759  777.69
  5949.9  778.39  6063.2  772.72  6084.6  775.74  7341.5  775.63  9199.9  777.97
 10847.3  781.58 11474.4  786.18 11969.6  796.58 12104.2  805.29 12353.5  814.32
#Mann= 6 ,-1 , 0
  3432.7     .05       0  4978.1    .033       0  5035.3     .05       0
  7341.5     .12       0  9199.9     .05       0 10847.3     .12       0
Bank Sta=4978.1,5035.3
XS Rating Curve= 0 ,0
Exp/Cntr=0.3,0.1

Chan Stop Cuts=-1
Use User Specified Reach Order=0
Composite Channel Slope=5