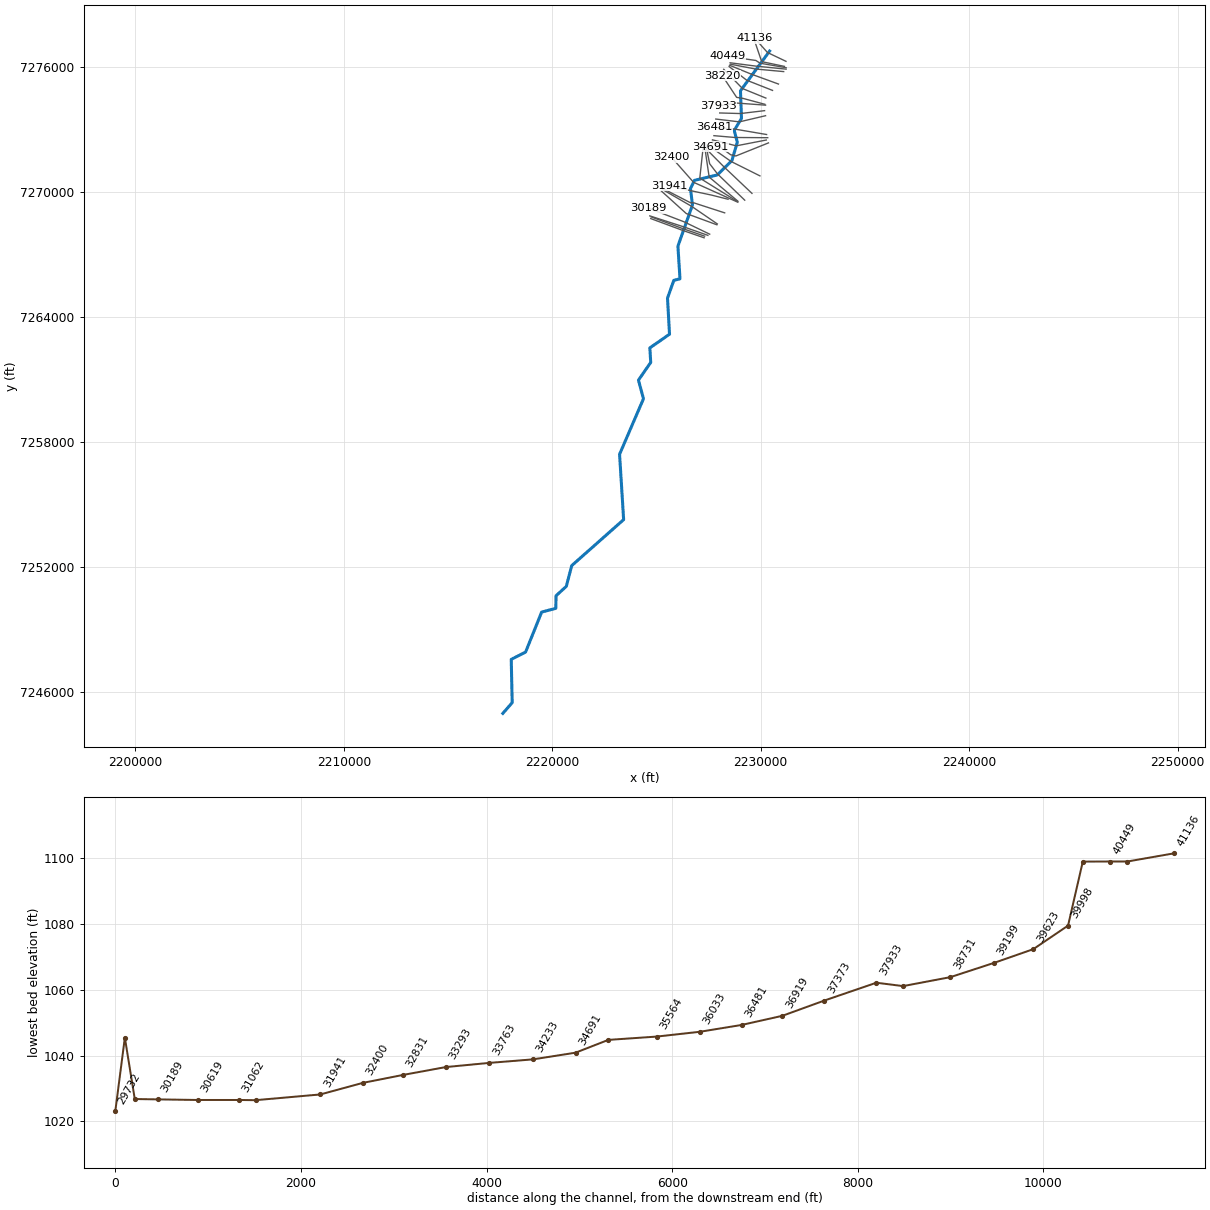
--- MALLARD CREEK.prj (project) ---

Proj Title=MALLARD CREEK Base Level Engineering
Current Plan=p01
Default Exp/Contr=0.3,0.1
English Units
Geom File=g01
Flow File=f01
Plan File=p01
Y Axis Title=Elevation
X Axis Title(PF)=Main Channel Distance
X Axis Title(XS)=Station
BEGIN DESCRIPTION:
MALLARD CREEK
END DESCRIPTION:
DSS Export Rating Curves= 0
DSS Export Rating Curve Sorted= 0
DSS Export Volume Flow Curves= 0
DXF OffsetX= 0
DXF OffsetY= 0
DXF ScaleX= 1
DXF ScaleY= 10

--- MALLARD CREEK.p01 (plan) ---

Plan Title=Multiple Run
Short Identifier=Multiple
Geom File=g01
Flow File=f01
Subcritical Flow
K Sum by GR= 0
Std Step Tol= 0.01
Critical Tol= 0.01
Num of Std Step Trials= 20
Max Error Tol= 0.3
Flow Tol Ratio= 0.001
Split Flow NTrial= 30
Split Flow Tol= 0.02
Split Flow Ratio= 0.02
Log Output Level= 0
Friction Slope Method= 1
Unsteady Friction Slope Method= 2
Unsteady Bridges Friction Slope Method= 1
Parabolic Critical Depth
Global Vel Dist=  1 , 1 , 1
Global Log Level= 0
CheckData=True
Encroach Param= -1, 0, 0, 0
BEGIN DESCRIPTION:
Multiple Run
END DESCRIPTION:

--- MALLARD CREEK.f01 (steady flow) ---

Flow Title=Multiple
Program Version=4.10
Number of Profiles= 7
Profile Names=10-year,25-year,50-year,1pct_min,100-year,1pct_plu,500-year
River Rch & RM=MALLARD CREEK,Reach-1         ,41136
     758    1070    1336     829    1654    3300    2542
River Rch & RM=MALLARD CREEK,Reach-1         ,38731
    1153    1659    2097    1314    2622    5231    4114
River Rch & RM=MALLARD CREEK,Reach-1         ,33763
    1431    2073    2632    1656    3303    6591    5222
River Rch & RM=MALLARD CREEK,Reach-1         ,26504
    2027    2977    3812    2415    4819    9615    7732
River Rch & RM=MALLARD CREEK,Reach-1         ,18829
    2529    3745    4823    3071    6127   12226    9930
River Rch & RM=MALLARD CREEK,Reach-1         ,16940
    3615    5419    7037    4513    9004   17965   14801
River Rch & RM=MALLARD CREEK,Reach-1         ,15472
    3615    5419    7037    4513    9004   17965   14801
River Rch & RM=MALLARD CREEK,Reach-1         ,9603
    3607    5393    6990    4474    8927   17811   14616
River Rch & RM=MALLARD CREEK,Reach-1         ,4376
    3688    5509    7137    4564    9107   18171   14887
Boundary for River Rch & Prof#=MALLARD CREEK,Reach-1         , 1
Up Type= 0
Dn Type= 3
Dn Slope=0.00368
Boundary for River Rch & Prof#=MALLARD CREEK,Reach-1         , 2
Up Type= 0
Dn Type= 3
Dn Slope=0.00368
Boundary for River Rch & Prof#=MALLARD CREEK,Reach-1         , 3
Up Type= 0
Dn Type= 3
Dn Slope=0.00368
Boundary for River Rch & Prof#=MALLARD CREEK,Reach-1         , 4
Up Type= 0
Dn Type= 3
Dn Slope=0.00368
Boundary for River Rch & Prof#=MALLARD CREEK,Reach-1         , 5
Up Type= 0
Dn Type= 3
Dn Slope=0.00368
Boundary for River Rch & Prof#=MALLARD CREEK,Reach-1         , 6
Up Type= 0
Dn Type= 3
Dn Slope=0.00368
Boundary for River Rch & Prof#=MALLARD CREEK,Reach-1         , 7
Up Type= 0
Dn Type= 3
Dn Slope=0.00368
DSS Import GetInterval= 0
DSS Import GetPeak= 0
DSS Import FillOption= 0

--- MALLARD CREEK.g01 (geometry) ---

Geom Title=Existing Conditions
Program Version=4.10

River Reach=MALLARD CREEK   ,Reach-1
Reach XY= 30
        2230429.        7276760.      2229031.23       7274854.1
      2229078.61      7273525.16       2228730.2       7272949.5
      2228879.15      7272384.89      2228619.99      7271502.98
       2227920.7      7270813.08      2226822.62      7270551.98
      2226631.07      7270154.14      2226727.96      7269370.44
      2226029.38      7267394.73      2226128.48      7265825.56
       2225832.5      7265751.54      2225529.86      7264899.69
      2225626.91      7263165.21      2224682.55      7262508.53
      2224725.25      7261811.55      2224136.25       7260959.7
      2224376.65      7260065.52      2223230.22       7257399.5
      2223425.25      7254261.55      2220934.61      7252054.41
      2220673.65      7251057.27      2220182.46       7250608.5
      2220171.33      7250003.48      2219492.11      7249823.21
      2218721.12      7247903.87      2218032.37      7247551.85
      2218078.33      7245473.91        2217629.        7244960.

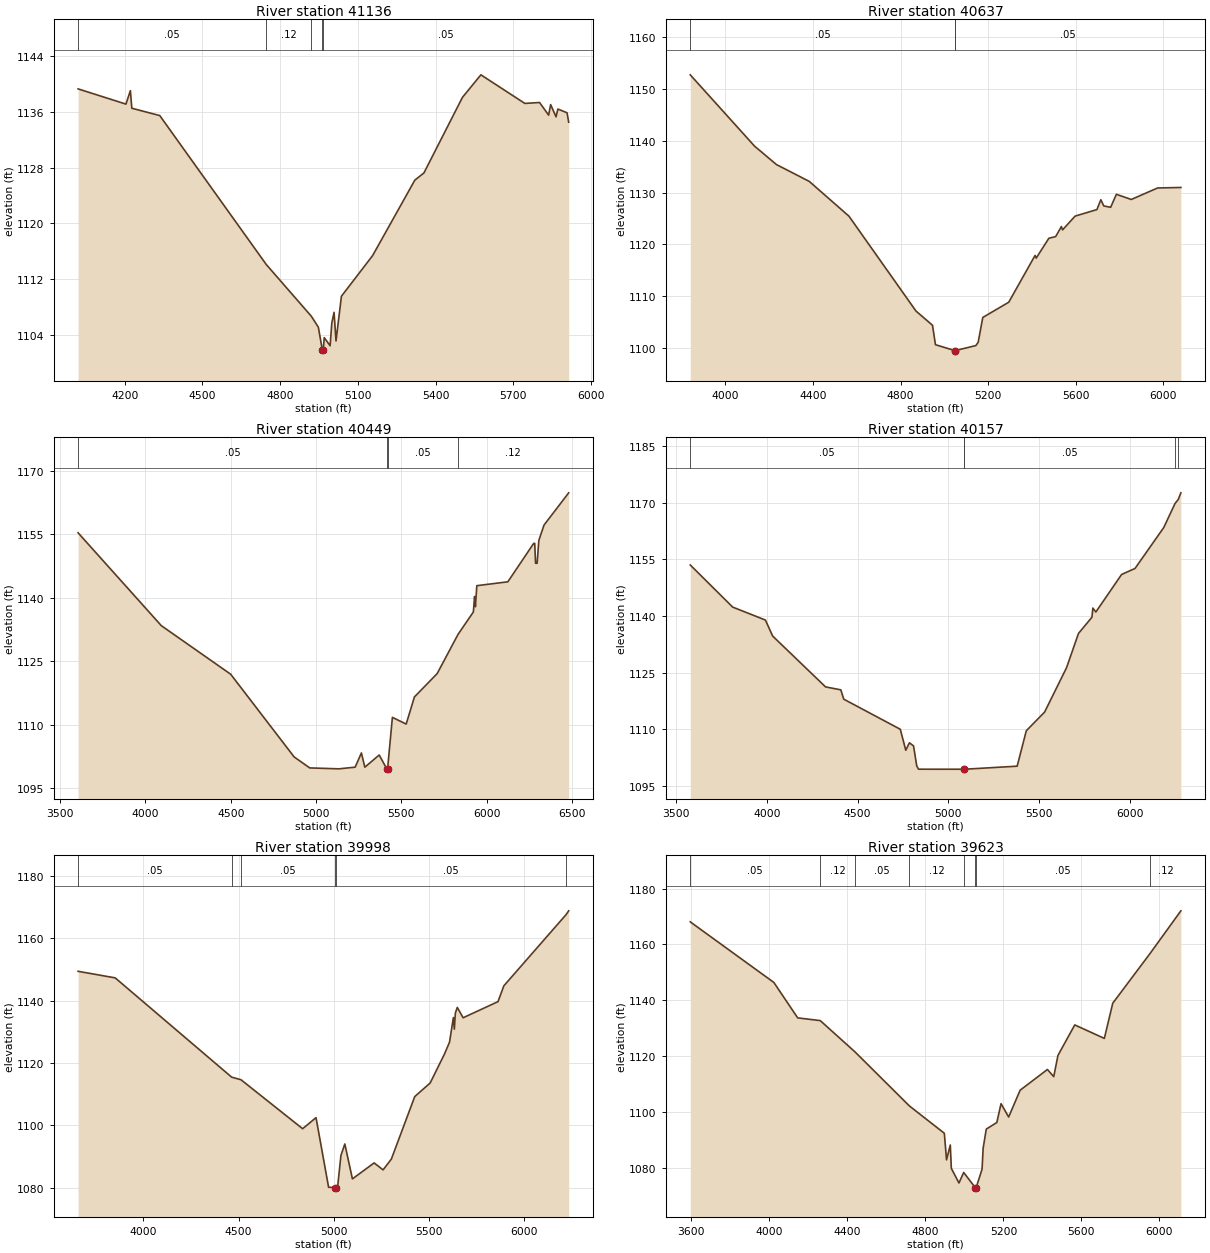
Type RM Length L Ch R = 1 ,41136   ,499,499,499
BEGIN DESCRIPTION:
MALLARD CREEK 78.0
END DESCRIPTION:
XS GIS Cut Line= 3
      2231214.26      7276267.06      2230325.37      7276690.68
      2229721.21      7277371.22
#Sta/Elev= 30
  4019.5 1139.26  4204.4 1137.08  4221.5 1139.01  4227.1 1136.49    4335 1135.44
  4746.1 1114.14  4920.5 1106.72  4947.4 1105.16  4962.6 1101.95  4962.8 1101.45
  4966.6 1101.95  4970.1 1103.67  4992.8 1102.51  4999.4 1105.76  5008.1 1107.29
  5015.6 1103.19  5036.5 1109.59  5156.9  1115.4    5320  1126.2  5355.1 1127.23
    5504 1138.05  5575.1 1141.27  5744.9 1137.18  5801.7 1137.31  5836.8  1135.5
  5844.4 1137.01  5865.3 1135.26  5872.4 1136.37  5907.9 1135.84  5914.2  1134.5
#Mann= 5 ,-1 , 0
  4019.5     .05       0  4746.1     .12       0  4920.5     .05       0
  4962.6    .033       0  4966.6     .05       0
Bank Sta=4962.6,4966.6
XS Rating Curve= 0 ,0
Exp/Cntr=0.3,0.1

Type RM Length L Ch R = 1 ,40637   ,188,188,188
BEGIN DESCRIPTION:
MALLARD CREEK 77.0
END DESCRIPTION:
XS GIS Cut Line= 4
      2231137.84      7276024.02      2230128.17      7276235.62
        2230029.        7276310.       2229679.8      7277335.72
#Sta/Elev= 30
  3840.5 1152.73  4134.2 1138.95    4234  1135.4  4383.7 1132.15  4564.7 1125.44
  4870.6 1107.12  4946.1 1104.37  4959.6 1100.62  5046.9 1099.49  5047.1 1098.99
  5050.9 1099.49    5144 1100.45  5154.5 1101.09  5175.6 1105.88    5294 1108.82
  5414.1 1117.85  5419.4 1117.34  5476.9 1121.16  5508.2  1121.5  5534.3 1123.43
  5539.6 1122.79    5597 1125.45  5696.4 1126.71  5714.4 1128.61  5727.7 1127.41
  5759.1 1127.15  5785.2 1129.66  5853.2 1128.66  5973.3 1130.88  6079.6 1130.98
#Mann= 3 ,-1 , 0
  3840.5     .05       0  5046.9    .033       0  5050.9     .05       0
Bank Sta=5046.9,5050.9
XS Rating Curve= 0 ,0
Exp/Cntr=0.3,0.1

Type RM Length L Ch R = 1 ,40449   ,292,292,292
BEGIN DESCRIPTION:
MALLARD CREEK 76.0
END DESCRIPTION:
XS GIS Cut Line= 4
      2231221.17      7275961.52       2229971.2      7276176.79
      2229769.81      7276308.73      2228415.63      7276503.18
#Sta/Elev= 30
  3604.8 1155.31  4092.8 1133.37    4500 1121.88  4871.8 1102.35  4963.3 1099.75
    5135 1099.53  5229.7 1099.93  5266.3 1103.29  5286.5 1099.92  5370.7  1102.8
  5415.8 1099.49  5416.1 1098.99  5419.8 1099.49  5448.1 1111.69    5529 1110.11
  5577.3 1116.52  5710.8 1122.04  5832.6 1131.27    5923  1136.6    5930 1140.26
    5935 1137.85  5943.2 1142.81    6125 1143.72  6276.5 1152.79  6282.7 1152.83
  6287.7 1148.11  6296.8  1148.1  6306.9  1153.5  6337.2 1157.13    6482 1164.75
#Mann= 4 ,-1 , 0
  3604.8     .05       0  5415.8    .033       0  5419.8     .05       0
  5832.6     .12       0
Bank Sta=5415.8,5419.8
XS Rating Curve= 0 ,0
Exp/Cntr=0.3,0.1

Type RM Length L Ch R = 1 ,40157   ,159,159,159
BEGIN DESCRIPTION:
MALLARD CREEK 75.5
END DESCRIPTION:
XS GIS Cut Line= 3
       2231221.2      7275892.07      2229743.23      7276040.68
      2228533.89       7276197.6
#Sta/Elev= 30
    3577 1153.49  3810.8 1142.35  3991.3 1138.92  4031.5 1134.68  4322.9 1121.24
  4407.1 1120.46  4423.4 1117.99    4735 1110.03  4765.2 1104.49  4785.3 1106.46
  4808.1 1105.62  4825.5 1100.36  4835.5 1099.47  5084.9 1099.46  5085.1 1098.96
  5088.9 1099.46  5379.3 1100.27  5429.7 1109.64  5530.5 1114.57  5651.6 1126.32
  5717.4 1135.38  5791.6 1139.67  5796.6  1142.1  5812.9 1141.04    5955 1150.97
  6029.1 1152.57  6187.5 1163.39  6249.3 1169.71  6267.8 1170.85  6281.9 1172.57
#Mann= 5 ,-1 , 0
    3577     .05       0  5084.9    .033       0  5088.9     .05       0
  6249.3     .12       0  6267.8     .05       0
Bank Sta=5084.9,5088.9
XS Rating Curve= 0 ,0
Exp/Cntr=0.3,0.1

Type RM Length L Ch R = 1 ,39998   ,375,375,375
BEGIN DESCRIPTION:
MALLARD CREEK 75.0
END DESCRIPTION:
XS GIS Cut Line= 3
      2231103.09      7275774.01      2229748.98      7275899.01
      2228554.54      7276128.18
#Sta/Elev= 30
  3657.6 1149.46  3852.5 1147.35  4463.8 1115.48  4513.2 1114.63  4836.7 1098.91
    4907 1102.46  4973.1 1080.11  5005.4 1080.01  5005.7 1079.51  5009.4 1080.01
    5020 1080.02  5037.8 1090.31  5058.2 1094.01  5098.1  1082.8  5212.2 1087.93
  5259.1 1085.69  5302.6 1089.16  5425.3 1109.23  5506.2 1113.58  5581.3 1122.87
    5608  1126.7  5628.2  1134.6  5633.3 1130.88  5638.6 1136.04  5648.8 1137.87
  5679.3 1134.54  5862.6 1139.72  5893.1 1144.79    6220 1167.66  6233.7 1168.88
#Mann= 6 ,-1 , 0
  3657.6     .05       0  4463.8     .12       0  4513.2     .05       0
  5005.4    .033       0  5009.4     .05       0    6220     .12       0
Bank Sta=5005.4,5009.4
XS Rating Curve= 0 ,0
Exp/Cntr=0.3,0.1

Type RM Length L Ch R = 1 ,39623   ,424,424,424
BEGIN DESCRIPTION:
MALLARD CREEK 74.0
END DESCRIPTION:
XS GIS Cut Line= 3
      2230853.14      7275176.79        2229529.        7275660.
      2228505.95      7276079.56
#Sta/Elev= 30
  3594.6 1168.07  4023.2 1146.37  4145.4 1133.68  4261.2  1132.7  4439.6 1121.47
  4718.5 1102.12  4897.2 1092.36  4908.4 1082.82  4927.8 1088.16  4933.1 1079.79
  4972.2 1074.55  4996.4 1078.32  5056.2 1072.85  5056.4 1072.35  5060.2 1072.85
  5090.6 1079.49  5096.2 1087.05  5112.2 1093.84  5166.3 1096.21  5187.9 1102.96
    5227 1098.18  5285.7 1107.77  5425.7  1115.2  5458.1 1112.64  5479.7 1120.24
  5565.8 1131.16  5717.5 1126.33  5760.7 1138.94  5953.5  1156.9  6109.9 1172.02
#Mann= 8 ,-1 , 0
  3594.6     .05       0  4261.2     .12       0  4439.6     .05       0
  4718.5     .12       0  4996.4     .05       0  5056.2    .033       0
  5060.2     .05       0  5953.5     .12       0
Bank Sta=5056.2,5060.2
XS Rating Curve= 0 ,0
Exp/Cntr=0.3,0.1

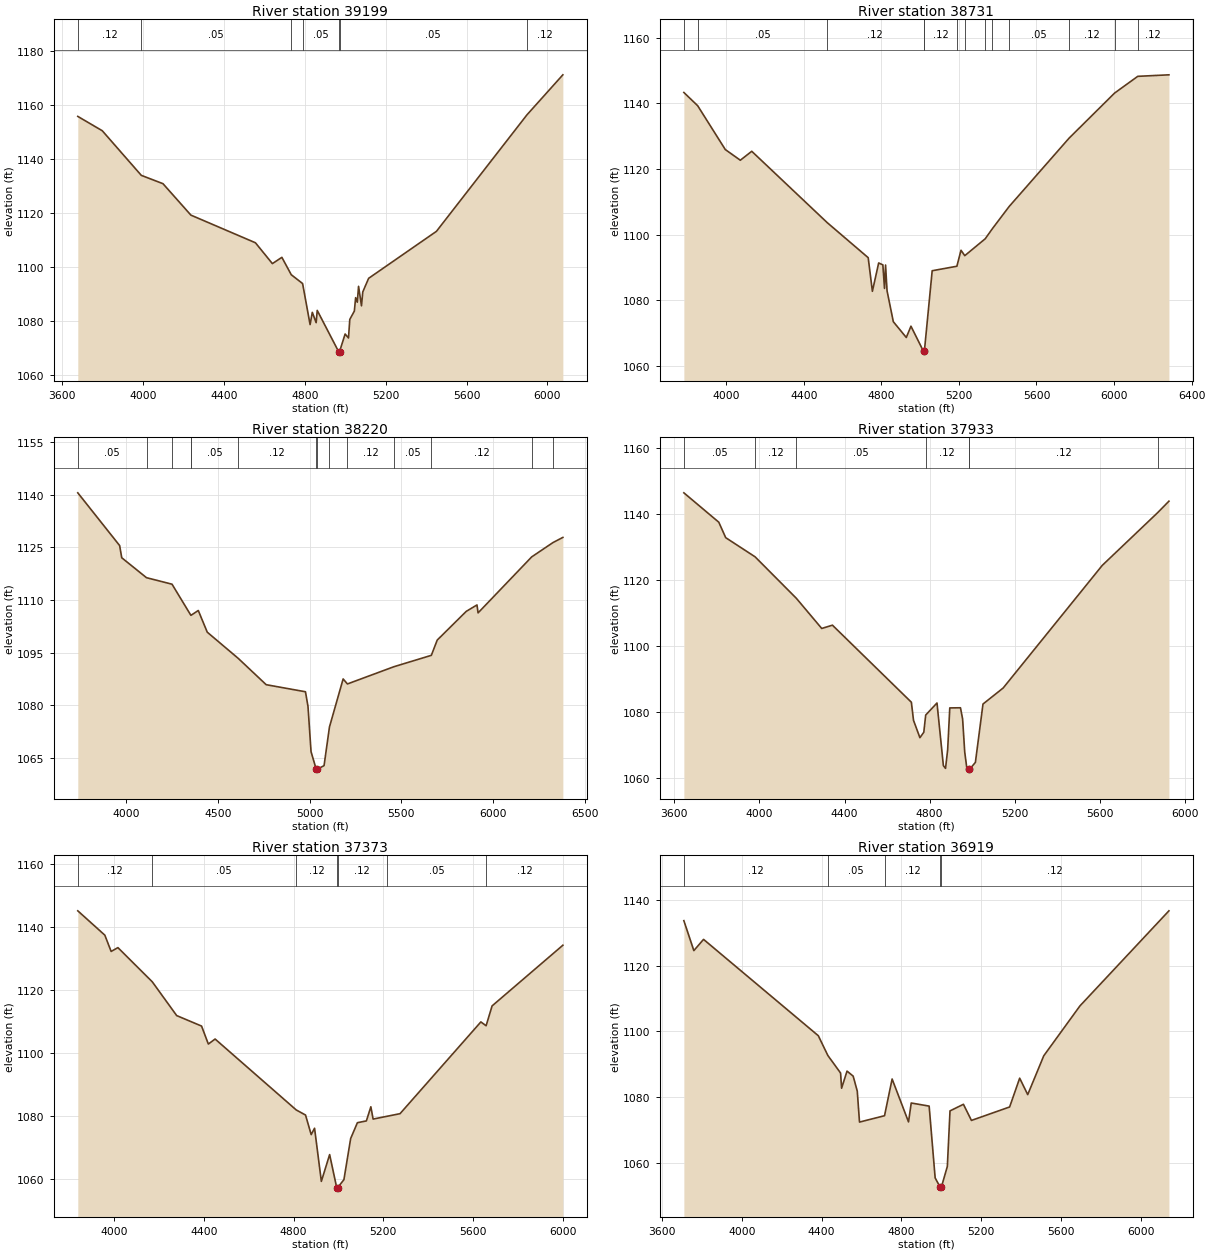
Type RM Length L Ch R = 1 ,39199   ,468,468,468
BEGIN DESCRIPTION:
MALLARD CREEK 73.0
END DESCRIPTION:
XS GIS Cut Line= 3
       2230568.4      7274871.24        2229329.        7275360.
      2228486.38      7276016.06
#Sta/Elev= 30
  3676.2  1155.9  3797.3 1150.59  3990.5 1134.05  4097.7 1130.97  4235.8 1119.32
  4555.2 1109.07  4639.1 1101.34    4686 1103.67  4732.5 1097.23  4788.6 1093.95
  4825.7 1078.74  4836.6 1083.29  4855.6 1079.46    4861    1084  4967.2 1068.67
  4967.5 1068.17  4971.2 1068.67    4999 1075.25  5015.7 1073.79  5022.1 1080.66
  5044.7 1083.76    5051 1088.72  5059.2 1087.04  5065.5 1092.92    5080 1085.71
  5086.3 1090.83  5115.3 1095.89  5450.9 1113.31  5898.7 1156.48  6076.4 1171.31
#Mann= 7 ,-1 , 0
  3676.2     .12       0  3990.5     .05       0  4732.5     .12       0
  4788.6     .05       0  4967.2    .033       0  4971.2     .05       0
  5898.7     .12       0
Bank Sta=4967.2,4971.2
XS Rating Curve= 0 ,0
Exp/Cntr=0.3,0.1

Type RM Length L Ch R = 1 ,38731   ,511,511,511
BEGIN DESCRIPTION:
MALLARD CREEK 72.0
END DESCRIPTION:
XS GIS Cut Line= 3
      2230248.96      7274503.18        2229129.        7274960.
      2228228.23      7275885.04
#Sta/Elev= 30
  3782.1 1143.33  3853.2  1139.3  3995.7 1125.93  4073.2 1122.67  4132.1  1125.4
  4520.7 1103.67  4732.4 1092.96    4754 1082.71  4786.4 1091.35    4808 1090.77
  4816.5 1083.59  4821.9 1090.72  4829.6 1082.86    4862 1073.43  4928.8 1068.63
  4952.9 1072.07  5017.8 1064.36  5018.1 1063.86  5021.9 1064.36  5062.3 1088.98
  5189.6 1090.35  5210.9 1095.23  5230.2 1093.57  5335.6 1098.72    5373 1101.83
  5458.9 1108.55  5767.9 1129.39  6002.7 1143.15  6122.1 1148.25  6282.8 1148.71
#Mann= 13 ,-1 , 0
  3782.1     .12       0  3853.2     .05       0  4520.7     .12       0
  5017.8     .07       0  5021.9     .12       0  5189.6     .05       0
  5230.2     .12       0  5335.6     .05       0    5373     .12       0
  5458.9     .05       0  5767.9     .12       0  6002.7     .05       0
  6122.1     .12       0
Bank Sta=5017.8,5021.9
XS Rating Curve= 0 ,0
Exp/Cntr=0.3,0.1

Type RM Length L Ch R = 1 ,38220   ,287,287,287
BEGIN DESCRIPTION:
MALLARD CREEK 71.0
END DESCRIPTION:
XS GIS Cut Line= 4
      2230200.36      7274204.57      2229144.81      7274489.29
       2228846.2       7274537.9       2228158.7      7275579.56
#Sta/Elev= 30
  3736.5 1140.59  3964.6 1125.53  3976.1 1122.05    4111 1116.36  4250.1  1114.5
  4352.9 1105.62  4353.5 1105.62  4393.3 1106.99  4442.2  1100.8  4610.9 1093.33
  4763.3 1085.81  4977.5 1083.79  4991.2 1079.61  5007.9 1066.68  5036.2 1061.63
  5036.5 1061.13  5040.3 1061.63  5078.8  1062.7  5108.3 1073.74  5182.8 1087.45
  5206.2 1086.02  5459.4 1090.94  5663.6 1094.19  5695.5 1098.54  5853.7 1106.74
  5912.3 1108.58  5918.3 1106.31  6210.6  1122.3  6326.6 1126.39  6380.4 1127.86
#Mann= 14 ,-1 , 0
  3736.5     .05       0    4111     .12       0  4250.1     .05       0
  4352.9     .12       0  4353.5     .05       0  4610.9     .12       0
  5036.2     .07       0  5040.3     .12       0  5108.3     .05       0
  5206.2     .12       0  5459.4     .05       0  5663.6     .12       0
  6210.6     .05       0  6326.6     .12       0
Bank Sta=5036.2,5040.3
XS Rating Curve= 0 ,0
Exp/Cntr=0.3,0.1

Type RM Length L Ch R = 1 ,37933   ,560,560,560
BEGIN DESCRIPTION:
MALLARD CREEK 70.0
END DESCRIPTION:
XS GIS Cut Line= 3
      2230235.12       7274162.9      2228804.53      7274267.07
      2227972.55      7274121.47
#Sta/Elev= 30
  3645.2 1146.38  3809.3 1137.49  3841.8 1132.81  3979.7 1127.02  4173.7 1114.46
    4293 1105.33  4343.2 1106.33  4714.1 1083.01  4724.2 1077.53  4754.2 1072.28
  4772.5 1073.92  4781.4 1079.13  4834.5 1082.78  4864.5 1063.81  4874.6 1062.99
  4884.6 1068.65  4894.6 1081.29  4944.8 1081.33  4954.8 1077.96  4964.8 1067.95
  4974.8 1062.97  4982.7 1062.66  4983.1 1062.16    4987 1062.66  5014.9 1064.81
  5050.6 1082.46  5145.3 1087.31  5610.8 1124.41  5871.6  1140.4  5924.2 1143.85
#Mann= 7 ,-1 , 0
  3645.2     .05       0  3979.7     .12       0  4173.7     .05       0
  4781.4     .12       0  4982.7     .07       0    4987     .12       0
  5871.6     .05       0
Bank Sta=4982.7,4987
XS Rating Curve= 0 ,0
Exp/Cntr=0.3,0.1

Type RM Length L Ch R = 1 ,37373   ,454,454,454
BEGIN DESCRIPTION:
MALLARD CREEK 69.0
END DESCRIPTION:
XS GIS Cut Line= 3
      2230186.52      7273899.02        2229029.        7273760.
      2228033.83       7273787.9
#Sta/Elev= 30
  3838.5 1145.16    3959 1137.43  3987.1 1132.26  4017.3 1133.47  4170.3 1122.62
  4279.2 1111.88    4390 1108.55  4420.2 1102.84  4450.4 1104.43  4811.9  1081.9
  4853.3 1080.29  4878.5 1074.07  4893.5  1076.1  4923.8 1059.22  4960.7 1067.72
  4992.1 1057.25  4992.5 1056.75  4996.5 1057.25  5024.3 1059.75  5054.4 1072.83
  5084.4 1077.85  5124.4 1078.42  5144.4 1082.91  5154.4    1079  5216.4 1079.89
  5274.4 1080.72  5634.6 1109.87  5657.9 1108.65  5684.6 1114.96  5999.9 1134.23
#Mann= 7 ,-1 , 0
  3838.5     .12       0  4170.3     .05       0  4811.9     .12       0
  4992.1     .07       0  4996.5     .12       0  5216.4     .05       0
  5657.9     .12       0
Bank Sta=4992.1,4996.5
XS Rating Curve= 0 ,0
Exp/Cntr=0.3,0.1

Type RM Length L Ch R = 1 ,36919   ,438,438,438
BEGIN DESCRIPTION:
MALLARD CREEK 68.0
END DESCRIPTION:
XS GIS Cut Line= 3
      2230235.07      7273655.95        2228979.        7273360.
      2227846.23      7273496.23
#Sta/Elev= 30
  3709.5 1133.62  3759.6 1124.53  3808.2 1127.94  4383.5 1098.68  4431.2 1092.69
    4495 1087.36  4500.1 1082.74  4527.4 1087.94  4558.2 1086.41  4578.7 1081.86
  4589.9 1072.46  4715.3 1074.39  4753.4 1085.54  4835.6 1072.52  4849.2 1078.25
    4939 1077.31  4969.1 1055.51    4995  1052.6  4995.5  1052.1  4999.8  1052.6
  5030.2    1059  5043.6 1075.86  5110.8 1077.86    5151 1072.96  5342.4 1077.05
  5392.8 1085.79  5433.1  1080.8  5513.6  1092.6  5694.9 1107.74  6140.9 1136.61
#Mann= 5 ,-1 , 0
  3709.5     .12       0  4431.2     .05       0  4715.3     .12       0
    4995     .07       0  4999.8     .12       0
Bank Sta=4995,4999.8
XS Rating Curve= 0 ,0
Exp/Cntr=0.3,0.1

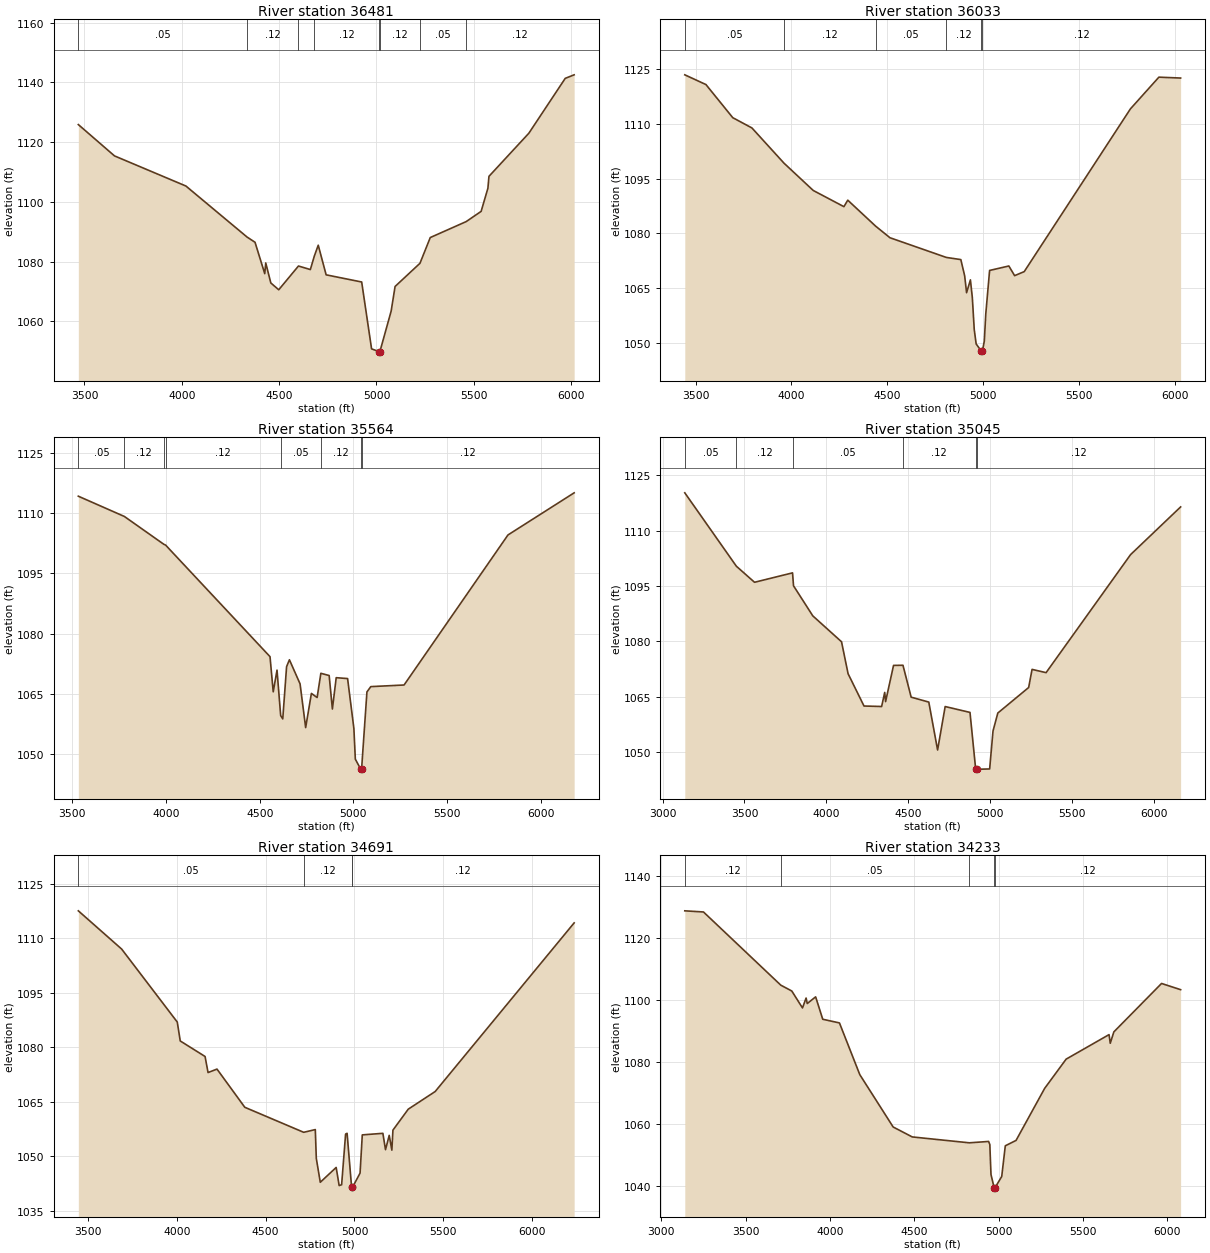
Type RM Length L Ch R = 1 ,36481   ,448,448,448
BEGIN DESCRIPTION:
MALLARD CREEK 67.0
END DESCRIPTION:
XS GIS Cut Line= 3
       2230283.7      7272753.18        2228779.        7273010.
      2227763.41      7273107.29
#Sta/Elev= 30
  3468.7 1125.87  3654.4 1115.38  4021.3 1105.29  4335.2 1088.21  4376.3 1086.45
  4426.2 1075.94  4431.3 1079.53  4457.5 1072.82  4498.1 1070.55  4599.3  1078.5
  4660.4 1077.32  4680.8 1081.82    4701 1085.47  4741.5 1075.55  4924.1 1073.15
  4974.9 1050.76  5012.8 1049.83  5013.4 1049.33  5017.6 1049.83  5075.5 1063.42
  5095.6 1071.65  5223.4 1079.41  5276.4 1088.04  5460.6 1093.37  5537.6  1096.8
  5572.4 1104.55  5577.8 1108.53  5782.7 1122.97  5969.6 1141.35  6015.4 1142.53
#Mann= 8 ,-1 , 0
  3468.7     .05       0  4335.2     .12       0  4599.3     .05       0
  4680.8     .12       0  5012.8     .07       0  5017.6     .12       0
  5223.4     .05       0  5460.6     .12       0
Bank Sta=5012.8,5017.6
XS Rating Curve= 0 ,0
Exp/Cntr=0.3,0.1

Type RM Length L Ch R = 1 ,36033   ,469,469,469
BEGIN DESCRIPTION:
MALLARD CREEK 66.0
END DESCRIPTION:
XS GIS Cut Line= 3
      2230339.29       7272600.4        2228779.        7272610.
      2227755.97      7272697.62
#Sta/Elev= 30
  3444.1 1123.37  3554.4 1120.71  3694.4 1111.65  3794.4 1108.84  3962.1 1099.19
  4114.4 1091.74  4274.4 1087.32  4294.4 1089.09  4439.8 1081.99  4514.4 1078.82
  4808.8 1073.43  4884.4 1072.84  4904.4  1068.4  4914.4 1063.78  4934.4  1067.3
  4944.4 1062.44  4954.4 1053.69  4964.4 1049.77    4992 1047.76  4992.6 1047.26
  4996.9 1047.76  5006.9 1050.55  5014.5 1057.95  5034.5 1069.87  5134.9 1071.09
    5165 1068.45  5215.2 1069.55  5769.2 1114.05  5917.8 1122.73  6031.2 1122.49
#Mann= 6 ,-1 , 0
  3444.1     .05       0  3962.1     .12       0  4439.8     .05       0
  4808.8     .12       0    4992     .07       0  4996.9     .12       0
Bank Sta=4992,4996.9
XS Rating Curve= 0 ,0
Exp/Cntr=0.3,0.1

Type RM Length L Ch R = 1 ,35564   ,519,519,519
BEGIN DESCRIPTION:
MALLARD CREEK 65.0
END DESCRIPTION:
XS GIS Cut Line= 3
      2230269.77      7272489.28        2228829.        7272210.
       2227686.5      7272496.23
#Sta/Elev= 30
  3532.4 1114.17  3778.1 1109.13  3988.6 1102.21  3998.1 1102.01  4555.1 1074.26
  4572.2 1065.52  4592.5 1070.91    4612  1059.6  4623.1 1058.78  4643.5 1071.76
  4658.6 1073.49  4715.4  1067.5  4745.3 1056.62  4775.9 1065.12  4806.5  1064.1
  4826.4 1070.12  4870.6 1069.57  4887.9 1061.24  4908.3 1069.03    4969 1068.81
  5002.6 1056.39  5010.3 1048.77  5038.8 1046.29  5039.4 1045.79  5043.7 1046.29
  5072.2 1065.49  5092.8 1066.81  5270.3 1067.21  5824.7 1104.53  6177.8 1115.01
#Mann= 8 ,-1 , 0
  3532.4     .05       0  3778.1     .12       0  3988.6     .05       0
  3998.1     .12       0    4612     .05       0  4826.4     .12       0
  5038.8     .07       0  5043.7     .12       0
Bank Sta=5038.8,5043.7
XS Rating Curve= 0 ,0
Exp/Cntr=0.3,0.1

Type RM Length L Ch R = 1 ,35045   ,354,354,354
BEGIN DESCRIPTION:
MALLARD CREEK 64.0
END DESCRIPTION:
XS GIS Cut Line= 4
      2230374.02      7272350.42      2228809.76      7271722.83
      2228561.48      7271780.95      2227687.67       7272425.9
#Sta/Elev= 30
  3135.7 1120.24  3450.5 1100.34  3561.3 1095.99  3793.4 1098.54  3799.3 1095.04
  3916.9 1086.89  4092.4 1079.86  4132.4  1071.2  4229.6 1062.44  4337.2 1062.31
    4356 1066.13  4361.4 1063.64  4409.8 1073.45  4467.4 1073.49  4517.4 1064.84
    4625 1063.51  4678.8 1050.52    4725  1062.3  4876.5 1060.71  4911.3 1045.29
    4912 1044.79  4916.3 1045.29  4996.5 1045.38  5017.1 1055.68  5046.4 1060.54
  5234.6 1067.46  5255.4 1072.37    5341 1071.49  5856.8 1103.49  6162.2 1116.42
#Mann= 6 ,-1 , 0
  3135.7     .05       0  3450.5     .12       0  3793.4     .05       0
  4467.4     .12       0  4911.3     .07       0  4916.3     .12       0
Bank Sta=4911.3,4916.3
XS Rating Curve= 0 ,0
Exp/Cntr=0.3,0.1

Type RM Length L Ch R = 1 ,34691   ,458,458,458
BEGIN DESCRIPTION:
MALLARD CREEK 63.0
END DESCRIPTION:
XS GIS Cut Line= 3
      2229964.27      7270767.06        2228579.        7271460.
      2227563.98      7272175.02
#Sta/Elev= 30
  3445.9 1117.55  3689.7 1107.02  4002.7 1086.92  4019.5 1081.71  4159.2 1077.43
    4176 1073.01  4226.3 1073.96  4382.8 1063.44  4714.2 1056.55  4779.6  1057.3
  4785.2 1049.37  4807.6 1042.79    4897 1046.87  4913.8 1041.89  4927.7  1042.1
  4950.1 1056.07  4958.5 1056.28  4983.9  1041.4  4984.5  1040.9  4988.9  1041.4
  5031.5 1045.31    5044 1055.84  5159.9 1056.27  5174.7 1051.77  5195.6 1055.71
  5210.4 1051.64  5216.5 1057.15  5302.7 1062.92  5454.2 1067.78  6236.4 1114.23
#Mann= 4 ,-1 , 0
  3445.9     .05       0  4714.2     .12       0  4983.9     .07       0
  4988.9     .12       0
Bank Sta=4983.9,4988.9
XS Rating Curve= 0 ,0
Exp/Cntr=0.3,0.1

Type RM Length L Ch R = 1 ,34233   ,470,470,470
BEGIN DESCRIPTION:
MALLARD CREEK 62.0
END DESCRIPTION:
XS GIS Cut Line= 3
      2229582.33      7269926.77        2228229.        7271210.
       2227472.8      7271973.78
#Sta/Elev= 30
  3139.6 1128.71  3250.4 1128.34  3708.9 1104.71  3773.9 1102.83  3837.4 1097.36
  3858.8 1100.56  3865.7 1098.78  3915.4 1100.94  3957.5 1093.71  4056.6 1092.52
  4177.2 1075.83    4375 1058.93  4488.2 1055.72  4826.4 1053.82  4940.9 1054.26
  4948.2 1053.25    4955 1043.61  4973.5 1039.37  4974.5 1038.87  4979.5 1039.37
  5018.7 1042.95  5039.9 1052.86  5103.6 1054.59  5273.3  1071.4  5400.6 1080.83
  5655.1 1088.75  5662.2 1085.96  5683.4 1089.62  5966.3 1105.26  6079.4 1103.26
#Mann= 5 ,-1 , 0
  3139.6     .12       0  3708.9     .05       0  4826.4     .12       0
  4973.5     .07       0  4979.5     .12       0
Bank Sta=4973.5,4979.5
XS Rating Curve= 0 ,0
Exp/Cntr=0.3,0.1

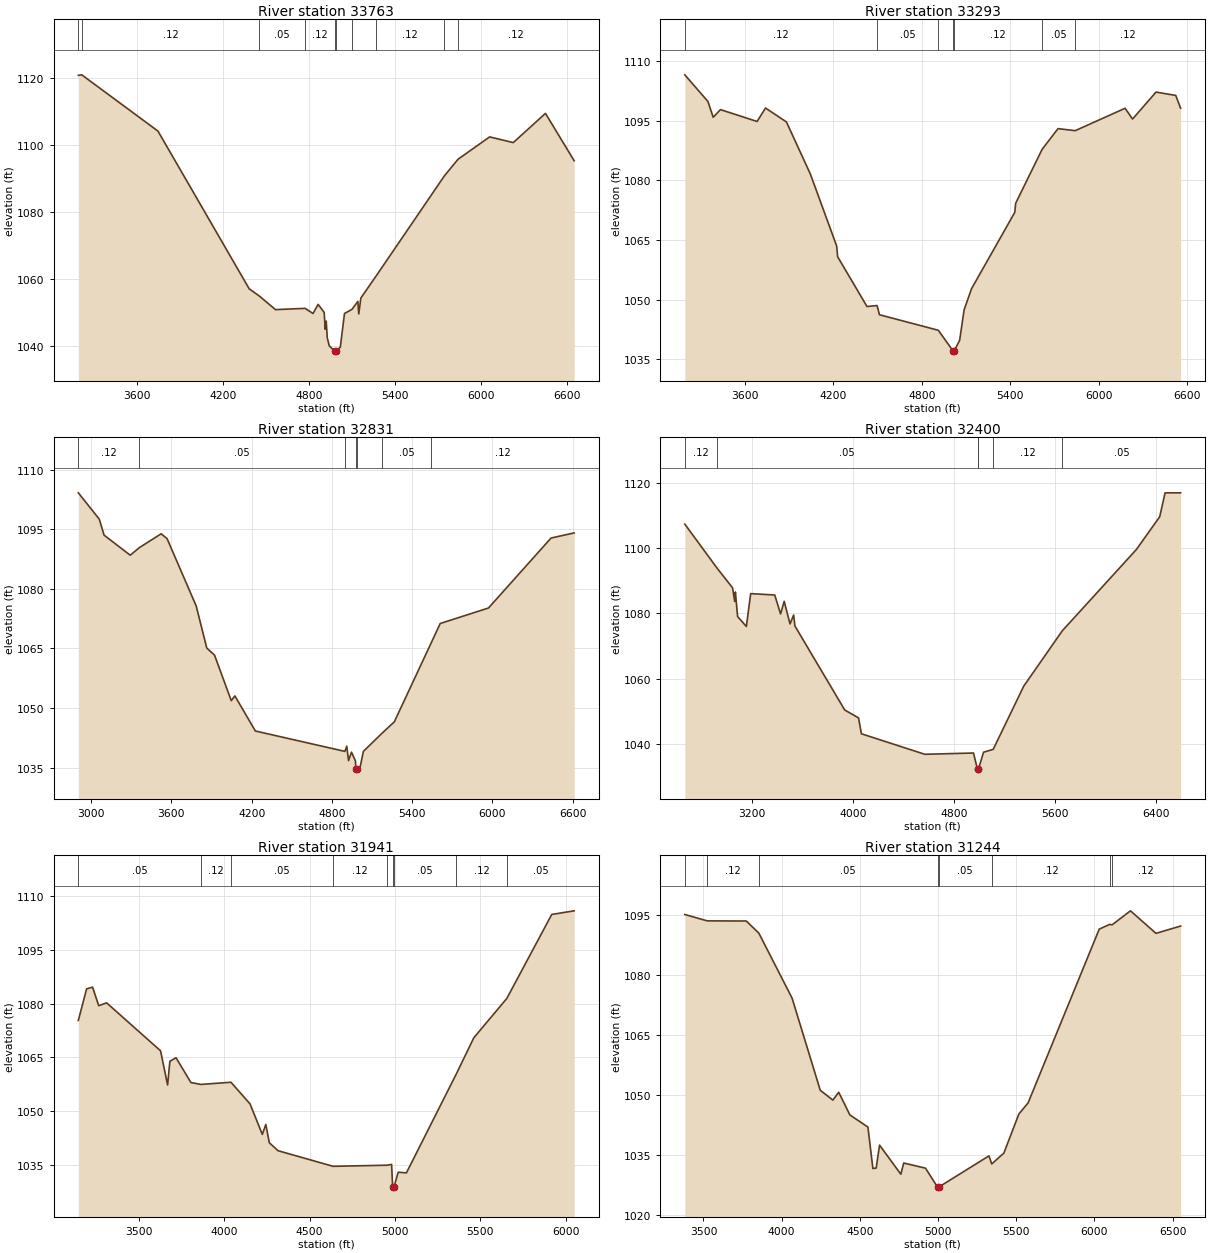
Type RM Length L Ch R = 1 ,33763   ,470,470,470
BEGIN DESCRIPTION:
MALLARD CREEK 61.0
END DESCRIPTION:
XS GIS Cut Line= 4
      2229235.09      7269600.39        2227929.        7270860.
       2227552.6      7271348.91      2227346.43      7272356.19
#Sta/Elev= 30
  3190.6 1120.89  3214.4 1121.04  3746.2 1104.21  4382.7 1057.05  4454.3 1054.85
  4566.6 1050.81  4772.9 1051.19  4828.3 1049.65  4863.8 1052.38  4906.2 1049.96
  4913.2 1044.94  4920.4 1047.37  4927.3 1042.47  4941.5 1039.98  4980.8  1038.3
  4981.8  1037.8  4986.9  1038.3  5018.7 1039.58  5047.7 1049.65  5099.8 1050.89
    5141 1053.28  5147.4 1049.52  5161.9 1054.27  5267.1 1060.78  5745.2 1090.84
  5840.4  1095.8  6060.5 1102.48  6225.5 1100.77    6450 1109.51  6650.3 1095.35
#Mann= 10 ,-1 , 0
  3190.6     .05       0  3214.4     .12       0  4454.3     .05       0
  4772.9     .12       0  4980.8     .07       0  4986.9     .12       0
  5099.8     .05       0  5267.1     .12       0  5745.2     .05       0
  5840.4     .12       0
Bank Sta=4980.8,4986.9
XS Rating Curve= 0 ,0
Exp/Cntr=0.3,0.1

Type RM Length L Ch R = 1 ,33293   ,462,462,462
BEGIN DESCRIPTION:
MALLARD CREEK 60.0
END DESCRIPTION:
XS GIS Cut Line= 3
      2228909.25      7269549.33        2227529.        7270710.
      2227299.85      7272252.48
#Sta/Elev= 30
  3192.3 1106.52  3349.4 1099.81  3384.8 1095.85  3434.3 1097.77  3682.7 1094.79
  3739.9 1098.17  3881.7 1094.67  4044.3 1081.53  4222.4 1063.46    4229 1060.77
    4428 1048.26  4496.6 1048.49  4512.5 1046.18  4911.8 1042.28  5012.8 1037.03
  5013.8 1036.53    5019 1037.03  5056.4 1039.76  5086.7 1047.42  5137.2 1052.74
  5430.4 1071.94  5436.7 1074.24  5615.7 1087.78  5723.6 1092.99    5840 1092.47
  6178.5 1098.11  6229.1  1095.4  6388.3 1102.18    6522 1101.34  6555.1 1098.13
#Mann= 7 ,-1 , 0
  3192.3     .12       0  4496.6     .05       0  4911.8     .12       0
  5012.8     .07       0    5019     .12       0  5615.7     .05       0
    5840     .12       0
Bank Sta=5012.8,5019
XS Rating Curve= 0 ,0
Exp/Cntr=0.3,0.1

Type RM Length L Ch R = 1 ,32831   ,431,431,431
BEGIN DESCRIPTION:
MALLARD CREEK 59.0
END DESCRIPTION:
XS GIS Cut Line= 3
      2228862.38      7269549.34        2227079.        7270660.
      2227252.82      7272256.31
#Sta/Elev= 30
  2904.5 1104.18  3061.1 1097.56    3097 1093.53  3292.4 1088.48  3361.4  1090.4
  3523.7 1093.87  3568.2 1092.64  3785.7 1075.69  3864.8 1065.11  3922.6 1063.33
  4047.8 1051.87  4074.9 1053.06  4227.9 1044.23  4897.2  1039.1  4911.2 1040.42
  4924.6 1036.77  4946.5  1038.9  4976.5 1036.68  4979.3 1034.63  4980.3 1034.13
  4985.5 1034.63    5008 1034.64  5035.6  1039.1  5172.3 1043.59    5267 1046.55
  5540.6 1066.28    5610 1071.29  5970.8 1075.19  6438.1 1092.79  6611.2 1094.09
#Mann= 7 ,-1 , 0
  2904.5     .12       0  3361.4     .05       0  4897.2     .12       0
  4979.3     .07       0  4985.5     .12       0  5172.3     .05       0
  5540.6     .12       0
Bank Sta=4979.3,4985.5
XS Rating Curve= 0 ,0
Exp/Cntr=0.3,0.1

Type RM Length L Ch R = 1 ,32400   ,459,459,459
BEGIN DESCRIPTION:
MALLARD CREEK 58.0
END DESCRIPTION:
XS GIS Cut Line= 3
      2228903.97       7269502.5        2226779.        7270460.
      2225722.84      7271657.46
#Sta/Elev= 30
  2668.6 1107.29  2923.2 1093.87    3047 1087.79  3063.8 1083.61  3069.3 1086.53
  3086.9 1079.01  3156.3 1075.98  3190.4 1086.02    3381  1085.6  3427.3 1079.81
  3455.9 1083.67  3502.2 1076.75  3530.9 1079.48  3540.5 1076.15  3935.2 1050.44
  4045.1    1048  4067.3 1043.16  4569.7 1036.88  4955.5 1037.27  4987.1 1032.23
  4988.2 1031.73  4993.9 1032.23  5034.9 1037.52  5111.4 1038.38  5353.6 1057.74
  5658.9 1074.66  6246.3 1099.55  6430.3 1109.53    6473 1116.85    6596 1116.85
#Mann= 6 ,-1 , 0
  2668.6     .12       0  2923.2     .05       0  4987.1    .033       0
  4993.9     .05       0  5111.4     .12       0  5658.9     .05       0
Bank Sta=4987.1,4993.9
XS Rating Curve= 0 ,0
Exp/Cntr=0.3,0.1

Type RM Length L Ch R = 1 ,31941   ,697,697,697
BEGIN DESCRIPTION:
MALLARD CREEK 57.0
END DESCRIPTION:
XS GIS Cut Line= 4
      2228436.09        7269645.      2227634.05      7269846.38
        2226629.        7270060.      2225606.23       7270294.3
#Sta/Elev= 30
  3145.9 1075.33  3194.5 1084.15  3229.3 1084.62  3265.3 1079.44  3311.6 1080.24
  3627.5 1066.84  3668.7 1057.29    3682 1063.93    3718  1064.9  3805.4 1057.98
  3864.1 1057.45  4039.8 1058.06  4151.8 1051.99  4223.4  1043.5  4243.8 1046.27
  4264.3 1041.17  4315.4 1038.94    4638 1034.58  4955.5 1034.89  4980.6 1035.11
  4986.7 1028.71  4987.8 1028.21  4993.6 1028.71  5019.2 1032.93  5067.3 1032.75
  5359.4 1060.37    5462 1070.48  5655.4 1081.48  5918.4 1104.93  6049.6 1105.94
#Mann= 9 ,-1 , 0
  3145.9     .05       0  3864.1     .12       0  4039.8     .05       0
    4638     .12       0  4955.5     .05       0  4986.7    .033       0
  4993.6     .05       0  5359.4     .12       0  5655.4     .05       0
Bank Sta=4986.7,4993.6
XS Rating Curve= 0 ,0
Exp/Cntr=0.3,0.1

Type RM Length L Ch R = 1 ,31244   ,182,182,182
BEGIN DESCRIPTION:
MALLARD CREEK 56.0
END DESCRIPTION:
XS GIS Cut Line= 4
       2228272.9      7268992.22      2226798.12      7269470.61
      2226630.57      7269478.32      2225338.93       7270141.5
#Sta/Elev= 30
  3380.9 1095.14  3524.3 1093.55  3773.8 1093.51  3854.4 1090.48  4066.8 1074.23
  4247.1 1051.18  4327.8 1048.73  4365.1 1050.69  4436.3 1045.03  4551.7 1041.99
  4583.5 1031.63  4604.5 1031.74  4626.1 1037.47  4762.2  1030.2  4780.7    1033
  4919.9 1031.71  4996.9 1026.97    4998 1026.47  5004.1 1026.97  5325.6 1034.78
  5343.3 1032.77  5420.7 1035.47  5516.7 1045.24    5576 1048.05  6030.7 1091.48
  6097.4 1092.67  6112.8 1092.56  6230.4 1096.06  6393.5 1090.43    6551 1092.25
#Mann= 8 ,-1 , 0
  3380.9     .05       0  3524.3     .12       0  3854.4     .05       0
  4996.9    .033       0  5004.1     .05       0  5343.3     .12       0
  6097.4     .05       0  6112.8     .12       0
Bank Sta=4996.9,5004.1
XS Rating Curve= 0 ,0
Exp/Cntr=0.3,0.1

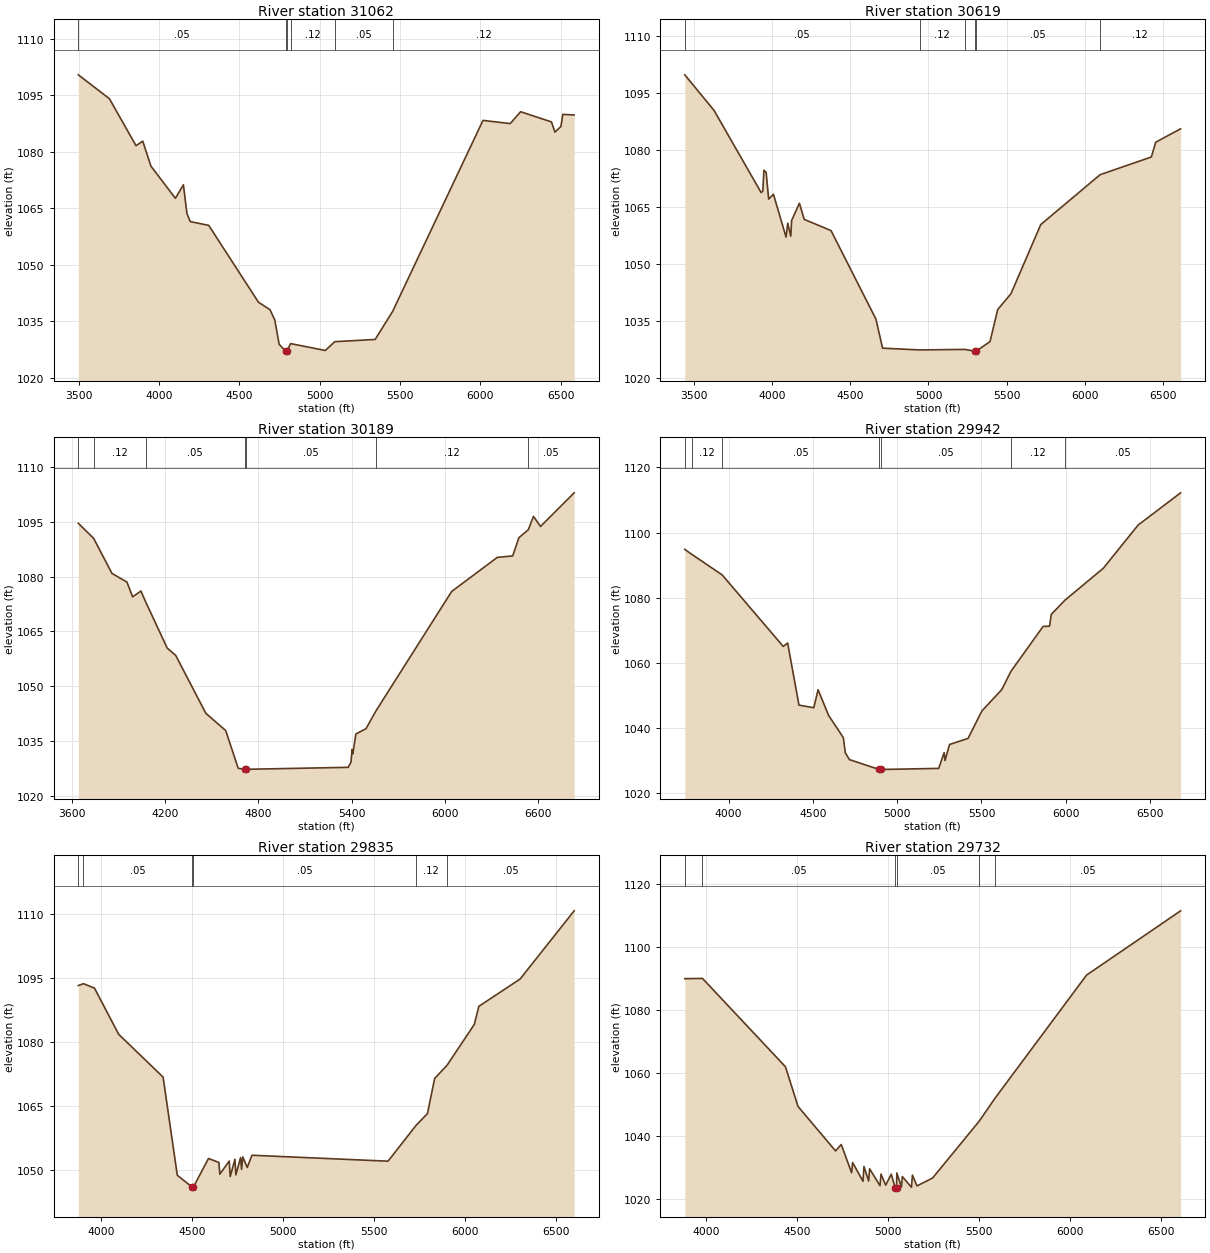
Type RM Length L Ch R = 1 ,31062   ,443,443,443
BEGIN DESCRIPTION:
MALLARD CREEK 55.0
END DESCRIPTION:
XS GIS Cut Line= 3
      2227918.78      7268460.95        2226679.        7269310.
      2225307.68      7270103.31
#Sta/Elev= 30
  3497.4 1100.42  3691.1 1094.07  3856.6 1081.61  3898.5 1082.81  3949.3 1076.18
  4101.7 1067.64  4151.6 1071.22  4173.4 1063.62  4194.4 1061.45  4309.2 1060.45
  4618.9 1040.05  4690.7 1038.06  4720.5 1035.33  4747.5 1028.89  4788.6 1027.03
  4789.7 1026.53  4795.8 1027.03  4818.9 1029.06  5035.2 1027.23  5093.7 1029.57
  5345.2 1030.16  5454.4 1037.62  6016.7 1088.32  6186.2 1087.48  6250.9 1090.62
  6443.1 1087.92  6464.7 1085.21  6501.9 1086.71  6513.5 1089.92  6584.3 1089.76
#Mann= 6 ,-1 , 0
  3497.4     .05       0  4788.6     .07       0  4795.8     .05       0
  4818.9     .12       0  5093.7     .05       0  5454.4     .12       0
Bank Sta=4788.6,4795.8
XS Rating Curve= 0 ,0
Exp/Cntr=0.3,0.1

Type RM Length L Ch R = 1 ,30619   ,430,430,430
BEGIN DESCRIPTION:
MALLARD CREEK 54.0
END DESCRIPTION:
XS GIS Cut Line= 3
      2227897.94      7268419.29        2226429.        7268960.
      2225234.76      7270040.81
#Sta/Elev= 30
    3439 1099.79  3626.8  1090.4    3928 1068.79  3938.7 1069.18  3945.8 1074.68
    3960 1074.12  3976.3 1067.08  4006.8 1068.36  4087.5  1057.1  4098.5 1060.73
  4117.9 1057.31  4123.3 1061.46  4173.1 1065.99    4204 1061.74  4375.6 1058.79
  4663.3 1035.49  4705.9 1027.84  4942.5 1027.37  5233.8 1027.51  5297.7 1027.03
  5298.8 1026.53    5305 1027.03    5394 1029.56  5443.3    1038  5528.4 1042.18
  5719.1 1060.37  6099.2  1073.5  6427.4 1078.16  6455.7 1082.06    6615 1085.58
#Mann= 6 ,-1 , 0
    3439     .05       0  4942.5     .12       0  5233.8     .05       0
  5297.7     .07       0    5305     .05       0  6099.2     .12       0
Bank Sta=5297.7,5305
XS Rating Curve= 0 ,0
Exp/Cntr=0.3,0.1

Type RM Length L Ch R = 1 ,30189   ,247,247,247
BEGIN DESCRIPTION:
MALLARD CREEK 53.0
END DESCRIPTION:
XS GIS Cut Line= 3
      2227554.16      7267967.92        2226329.        7268560.
      2224616.67      7269217.91
#Sta/Elev= 30
  3639.7 1094.58  3738.6 1090.44  3856.5 1080.85  3952.8 1078.49  3989.7 1074.44
  4043.2 1076.03    4073 1073.11  4212.5 1060.41  4267.4 1058.39  4461.1 1042.56
  4589.5 1037.81    4670 1027.48  4711.4 1027.21  4712.5 1026.71    4719 1027.21
  5378.8 1027.75  5396.8 1029.16  5403.4 1032.64  5408.8 1031.47  5428.1 1036.88
  5493.5 1038.34  5557.5  1043.2  6045.5 1075.91  6339.5 1085.24  6438.8 1085.64
  6478.8 1090.63  6539.1  1092.8  6572.8 1096.47    6618 1093.71  6834.8 1102.92
#Mann= 7 ,-1 , 0
  3639.7     .05       0  3738.6     .12       0    4073     .05       0
  4711.4    .033       0    4719     .05       0  5557.5     .12       0
  6539.1     .05       0
Bank Sta=4711.4,4719
XS Rating Curve= 0 ,0
Exp/Cntr=0.3,0.1

Type RM Length L Ch R = 1 ,29942   ,107,107,107
BEGIN DESCRIPTION:
MALLARD CREEK 52.0
END DESCRIPTION:
XS GIS Cut Line= 3
       2227467.4      7267912.34      2226279.88      7268329.02
      2224679.21      7268846.37
#Sta/Elev= 30
  3740.3 1094.82  3785.4 1093.18  3961.6 1087.01  4324.5 1065.05  4350.2 1066.12
  4417.5 1047.06  4505.2 1046.26  4530.9 1051.78  4592.9 1043.94  4680.6 1037.09
  4692.4 1032.44  4716.9 1030.35  4893.7 1027.32  4894.9 1026.82  4901.4 1027.32
  5246.3 1027.66  5278.3 1032.49  5283.6 1030.07  5310.3 1034.99  5420.1 1036.84
  5502.5 1045.29  5619.8 1051.79    5675 1057.46  5865.2 1071.19  5903.5 1071.27
    5914 1074.89  5994.4 1079.22  6222.7 1089.05    6429 1102.29    6681 1112.17
#Mann= 7 ,-1 , 0
  3740.3     .05       0  3785.4     .12       0  3961.6     .05       0
  4893.7    .033       0  4901.4     .05       0    5675     .12       0
  5994.4     .05       0
Bank Sta=4893.7,4901.4
XS Rating Curve= 0 ,0
Exp/Cntr=0.3,0.1

Type RM Length L Ch R = 1 ,29835   ,103,103,103
BEGIN DESCRIPTION:
MALLARD CREEK 51.6
END DESCRIPTION:
XS GIS Cut Line= 3
      2227312.88      7267872.42      2226255.04      7268238.13
      2224750.41      7268796.01
#Sta/Elev= 30
  3874.1 1093.24  3902.3 1093.68  3962.8 1092.64  4095.7  1081.8  4339.8 1071.76
  4417.8 1048.72  4498.6 1045.96  4499.8 1045.46  4506.3 1045.96  4589.2 1052.65
  4646.2 1051.72  4651.5 1048.97  4703.3 1052.06  4708.6 1048.42  4734.5 1052.47
  4739.7 1048.82  4765.6 1052.87  4770.9 1050.11  4777.6 1053.01  4802.1 1050.55
    4828 1053.41  5575.7 1052.02  5727.3 1060.31  5792.1  1063.2  5831.7 1071.43
  5899.7 1074.53  6049.5 1084.11  6074.5 1088.36    6301 1094.77  6598.1 1110.78
#Mann= 6 ,-1 , 0
  3874.1     .12       0  3902.3     .05       0  4498.6    .033       0
  4506.3     .05       0  5727.3     .12       0  5899.7     .05       0
Bank Sta=4498.6,4506.3
XS Rating Curve= 0 ,0
Exp/Cntr=0.3,0.1

Type RM Length L Ch R = 1 ,29732   ,463,463,463
BEGIN DESCRIPTION:
MALLARD CREEK 51.5
END DESCRIPTION:
XS GIS Cut Line= 3
      2227286.82      7267794.29        2226229.        7268160.
      2224724.35      7268717.89
#Sta/Elev= 30
  3885.1 1089.86  3982.3 1089.94  4438.2 1061.92  4507.1 1049.34  4713.5 1035.23
  4744.7 1037.26  4801.7  1028.3    4807 1031.55  4864.1 1025.59  4869.4 1030.31
  4895.2 1025.71  4900.5 1029.56  4957.6 1024.21  4962.9 1027.86  4988.8 1024.39
  5019.5 1027.85  5040.7 1023.61  5041.9 1023.11  5048.4 1023.61  5049.9 1028.25
    5075 1023.81  5080.3  1027.1  5130.4  1023.7  5135.7 1027.56  5160.8 1024.13
  5246.6 1026.64  5502.5 1044.66  5589.2 1051.93  6092.2 1090.99  6609.1 1111.38
#Mann= 6 ,-1 , 0
  3885.1     .12       0  3982.3     .05       0  5040.7    .033       0
  5048.4     .05       0  5502.5     .12       0  5589.2     .05       0
Bank Sta=5040.7,5048.4
XS Rating Curve= 0 ,0
Exp/Cntr=0.3,0.1