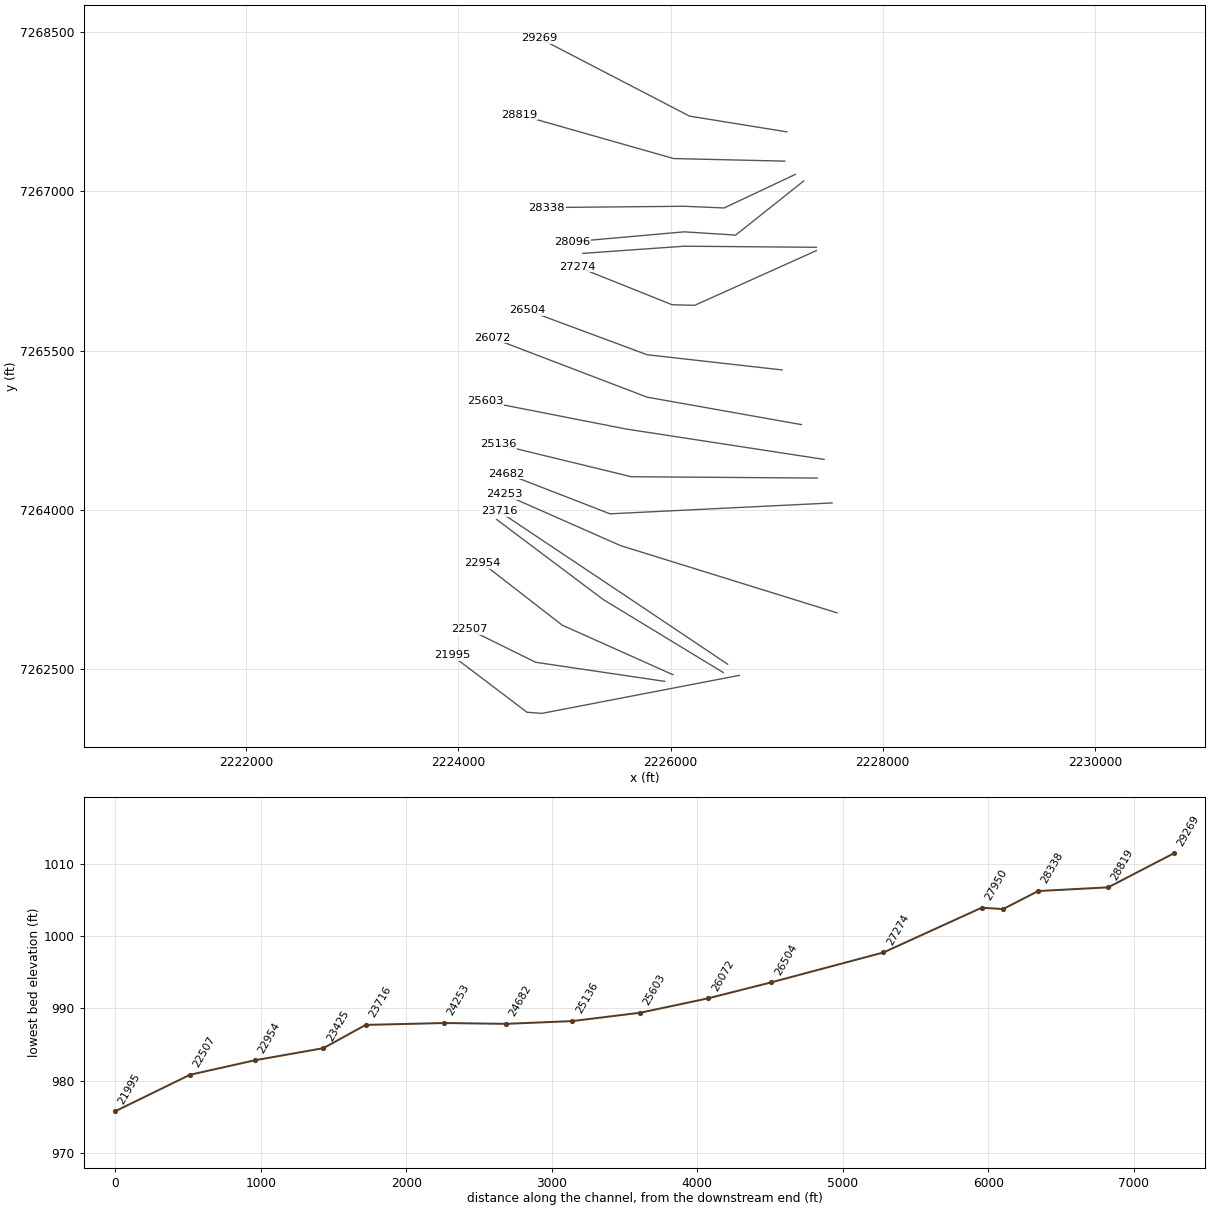
HEC-RAS study MALLARD CREEK.prj: MALLARD CREEK Base Level Engineering

--- MALLARD CREEK.g01 (geometry) --- (continued)

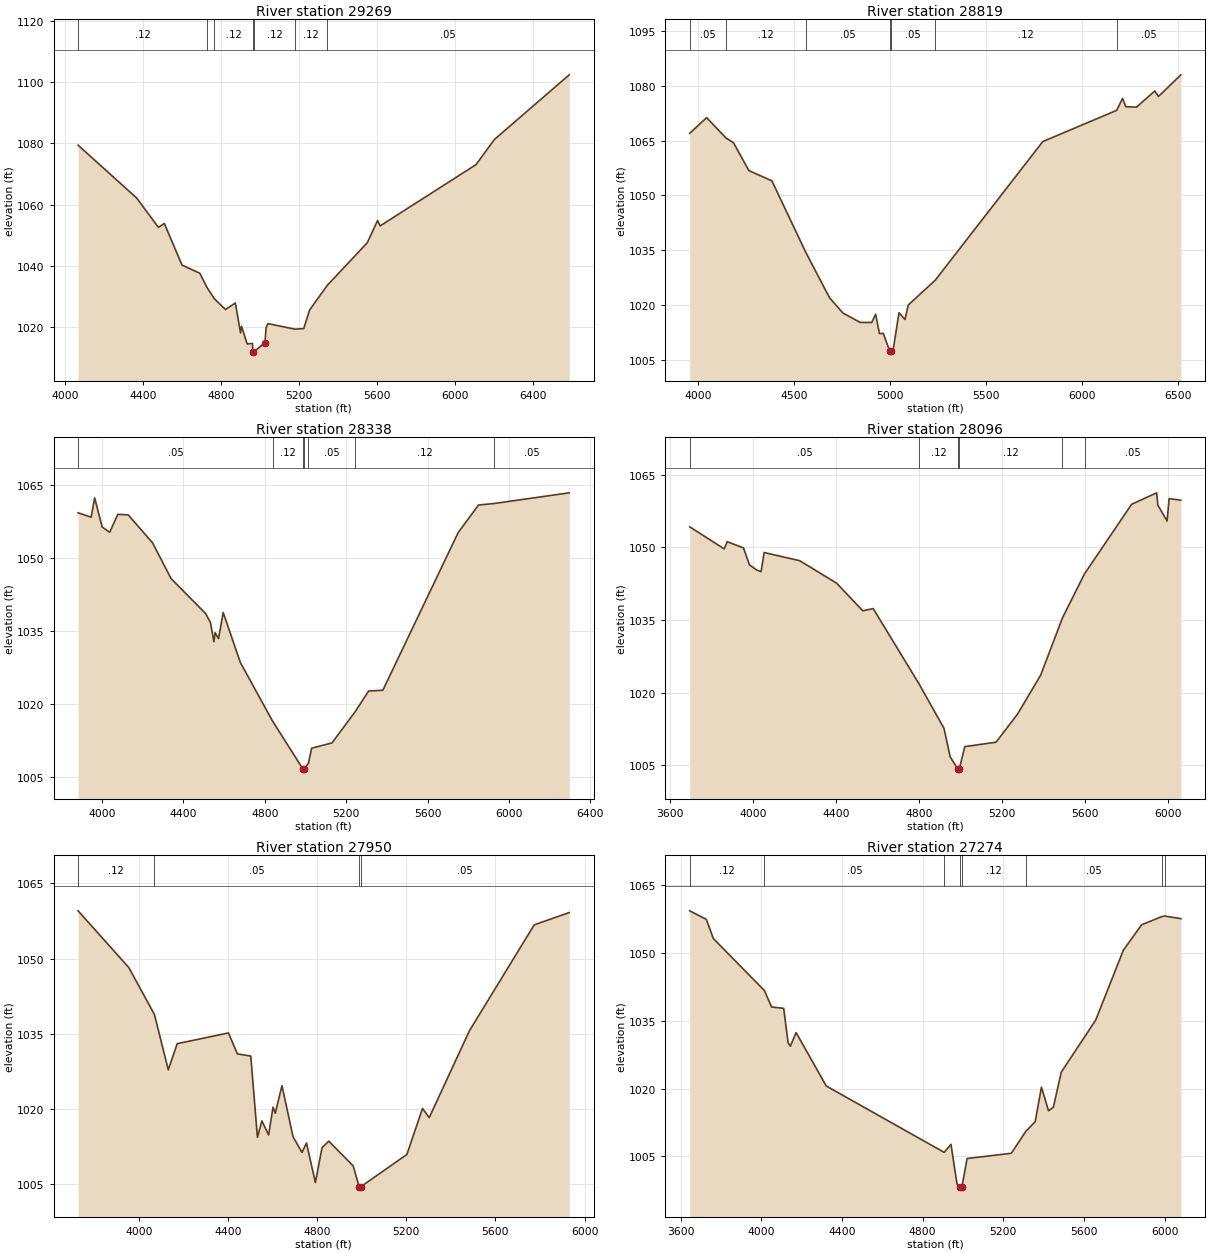
Type RM Length L Ch R = 1 ,29269   ,450,450,450
BEGIN DESCRIPTION:
MALLARD CREEK 51.0
END DESCRIPTION:
XS GIS Cut Line= 3
      2227095.88      7267561.65        2226179.        7267710.
      2224765.99       7268443.6
#Sta/Elev= 30
  4067.1 1079.42  4367.8 1062.17  4479.3 1052.58  4509.7 1053.85  4600.8 1040.24
    4692  1037.6  4728.4    1033  4766.3 1029.29  4823.7 1025.76  4874.3  1027.9
  4900.8 1018.16  4905.9 1020.28  4935.1 1014.52  4962.5  1014.7  4963.7 1012.02
  4964.9 1011.52  4971.4 1012.02  5026.3 1014.96  5031.9 1019.73    5041 1021.16
  5179.8 1019.35  5225.3 1019.52  5255.1 1025.56  5345.7 1033.61  5551.5 1047.57
  5604.3 1054.82  5617.8 1053.07  6109.7 1073.07  6203.8 1081.27    6588 1102.39
#Mann= 7 ,-1 , 0
  4067.1     .12       0  4728.4     .05       0  4766.3     .12       0
  4963.7    .033       0  4971.4     .12       0  5179.8     .12       0
  5345.7     .05       0
Bank Sta=4963.7,5026.3
XS Rating Curve= 0 ,0
Exp/Cntr=0.3,0.1

Type RM Length L Ch R = 1 ,28819   ,481,481,481
BEGIN DESCRIPTION:
MALLARD CREEK 50.0
END DESCRIPTION:
XS GIS Cut Line= 3
      2227076.94      7267285.61        2226029.        7267310.
      2224576.95      7267723.11
#Sta/Elev= 30
  3956.3 1067.04  4044.3 1071.32    4146  1065.7  4184.3 1064.44  4264.3 1056.82
  4384.4    1054  4559.7 1034.53  4684.4 1021.98  4754.5 1017.78  4844.5 1015.22
  4904.5 1015.22  4924.5 1017.47  4944.5 1012.17  4964.5 1012.21  4998.1 1007.31
  4999.3 1006.81  5005.9 1007.31  5014.9 1007.41  5046.1 1017.88  5077.3 1016.05
  5094.4 1019.99  5234.9 1026.78  5795.1 1064.77  6179.6 1073.31  6210.6 1076.59
  6227.5 1074.31  6283.3  1074.2  6378.5 1078.63  6397.7 1077.12  6514.2 1083.05
#Mann= 7 ,-1 , 0
  3956.3     .05       0    4146     .12       0  4559.7     .05       0
  4998.1    .033       0  5005.9     .05       0  5234.9     .12       0
  6179.6     .05       0
Bank Sta=4998.1,5005.9
XS Rating Curve= 0 ,0
Exp/Cntr=0.3,0.1

Type RM Length L Ch R = 1 ,28338   ,242,242,242
BEGIN DESCRIPTION:
MALLARD CREEK 49.0
END DESCRIPTION:
XS GIS Cut Line= 4
      2227175.84      7267160.59      2226504.28      7266844.11
        2226129.        7266860.      2224833.07      7266848.12
#Sta/Elev= 30
    3882 1059.27  3946.2 1058.37  3963.5 1062.32  4000.1 1056.37  4037.3 1055.28
  4077.4 1058.95  4128.5 1058.84  4247.9 1053.11    4339 1045.78  4509.6 1038.57
  4532.4 1036.79  4549.6 1032.83  4555.2 1034.69  4572.4 1033.47  4595.2 1038.83
  4679.7 1028.56  4837.7 1016.57  4986.1  1006.8  4987.3  1006.3    4994  1006.8
  5014.1 1007.89    5030    1011    5130 1012.09  5243.9 1018.48    5310 1022.73
    5380 1022.88    5750 1055.19    5850 1060.86  5927.1 1061.17    6296 1063.36
#Mann= 7 ,-1 , 0
    3882     .05       0  4837.7     .12       0  4986.1     .07       0
    4994     .12       0  5014.1     .05       0  5243.9     .12       0
  5927.1     .05       0
Bank Sta=4986.1,4994
XS Rating Curve= 0 ,0
Exp/Cntr=0.3,0.1

Type RM Length L Ch R = 1 ,28096   ,146,146,146
BEGIN DESCRIPTION:
MALLARD CREEK 48.5
END DESCRIPTION:
XS GIS Cut Line= 4
      2227253.99       7267098.1      2226613.42      7266588.29
      2226129.01      7266618.95      2225072.82      7266525.29
#Sta/Elev= 30
    3696 1054.22  3861.9 1049.67  3876.3 1051.15  3954.8 1049.87  3983.6 1046.36
  4018.8  1045.3  4039.6 1044.97  4054.1 1048.92  4225.5 1047.23  4403.2 1042.59
  4529.1 1036.89  4579.2 1037.34  4800.5 1021.76  4919.9 1012.65    4950 1006.72
    4986 1004.29  4987.3 1003.79  4994.1 1004.29  5020.2 1008.85  5170.7 1009.76
  5273.7 1015.54  5385.5  1023.6  5490.2  1035.4  5596.5 1044.51  5823.3 1058.87
  5943.8 1061.24  5949.6 1058.71    5994 1055.42    6004 1060.04  6060.4 1059.72
#Mann= 6 ,-1 , 0
    3696     .05       0  4800.5     .12       0    4986    .033       0
  4994.1     .12       0  5490.2     .12       0  5596.5     .05       0
Bank Sta=4986,4994.1
XS Rating Curve= 0 ,0
Exp/Cntr=0.3,0.1

Type RM Length L Ch R = 1 ,27950   ,676,676,676
BEGIN DESCRIPTION:
MALLARD CREEK 48.0
END DESCRIPTION:
XS GIS Cut Line= 3
       2227373.8      7266473.11      2226129.01      7266483.53
      2225172.33      7266415.94
#Sta/Elev= 30
  3727.2 1059.53  3954.8 1048.21  4069.7 1038.86    4132  1027.8    4172 1033.02
    4402 1035.16    4442 1030.98    4502 1030.55    4532 1014.33    4552 1017.61
    4582 1014.79    4602 1020.35    4612 1019.14    4642 1024.65    4692 1014.42
    4732 1011.31    4752  1013.2    4792 1005.32    4822 1012.25    4852 1013.57
    4962 1008.61    4988 1004.49  4989.2 1003.99  4996.2 1004.49  5202.6  1010.9
  5272.8 1020.09  5302.9 1018.26  5483.3 1035.59    5774 1056.73  5931.1 1059.18
#Mann= 4 ,-1 , 0
  3727.2     .12       0  4069.7     .05       0    4988    .033       0
  4996.2     .05       0
Bank Sta=4988,4996.2
XS Rating Curve= 0 ,0
Exp/Cntr=0.3,0.1

Type RM Length L Ch R = 1 ,27274   ,770,770,770
BEGIN DESCRIPTION:
MALLARD CREEK 47.0
END DESCRIPTION:
XS GIS Cut Line= 4
      2227373.82      7266441.87      2226227.97      7265926.24
      2226014.43      7265931.45      2225118.56      7266290.84
#Sta/Elev= 30
  3645.1 1059.34  3727.1 1057.46  3762.4  1053.2  4015.4  1041.7  4051.2 1038.06
    4111 1037.77  4132.9 1030.15  4143.8 1029.39  4172.4  1032.4  4322.3 1020.58
    4907  1005.9  4940.6 1007.68  4970.6  998.91  4986.5  998.27  4987.7  997.77
  4994.8  998.27  5020.6 1004.54  5239.6  1005.7  5311.3 1010.52  5358.1  1012.7
  5389.2 1020.33  5424.2 1015.11  5448.4  1015.9  5487.4 1023.64  5658.2 1035.17
  5795.4 1050.63  5886.1 1056.26  5985.3 1058.05  5999.5 1058.19  6080.5 1057.61
#Mann= 8 ,-1 , 0
  3645.1     .12       0  4015.4     .05       0    4907     .12       0
  4986.5     .07       0  4994.8     .12       0  5311.3     .05       0
  5985.3     .12       0  5999.5     .05       0
Bank Sta=4986.5,4994.8
XS Rating Curve= 0 ,0
Exp/Cntr=0.3,0.1

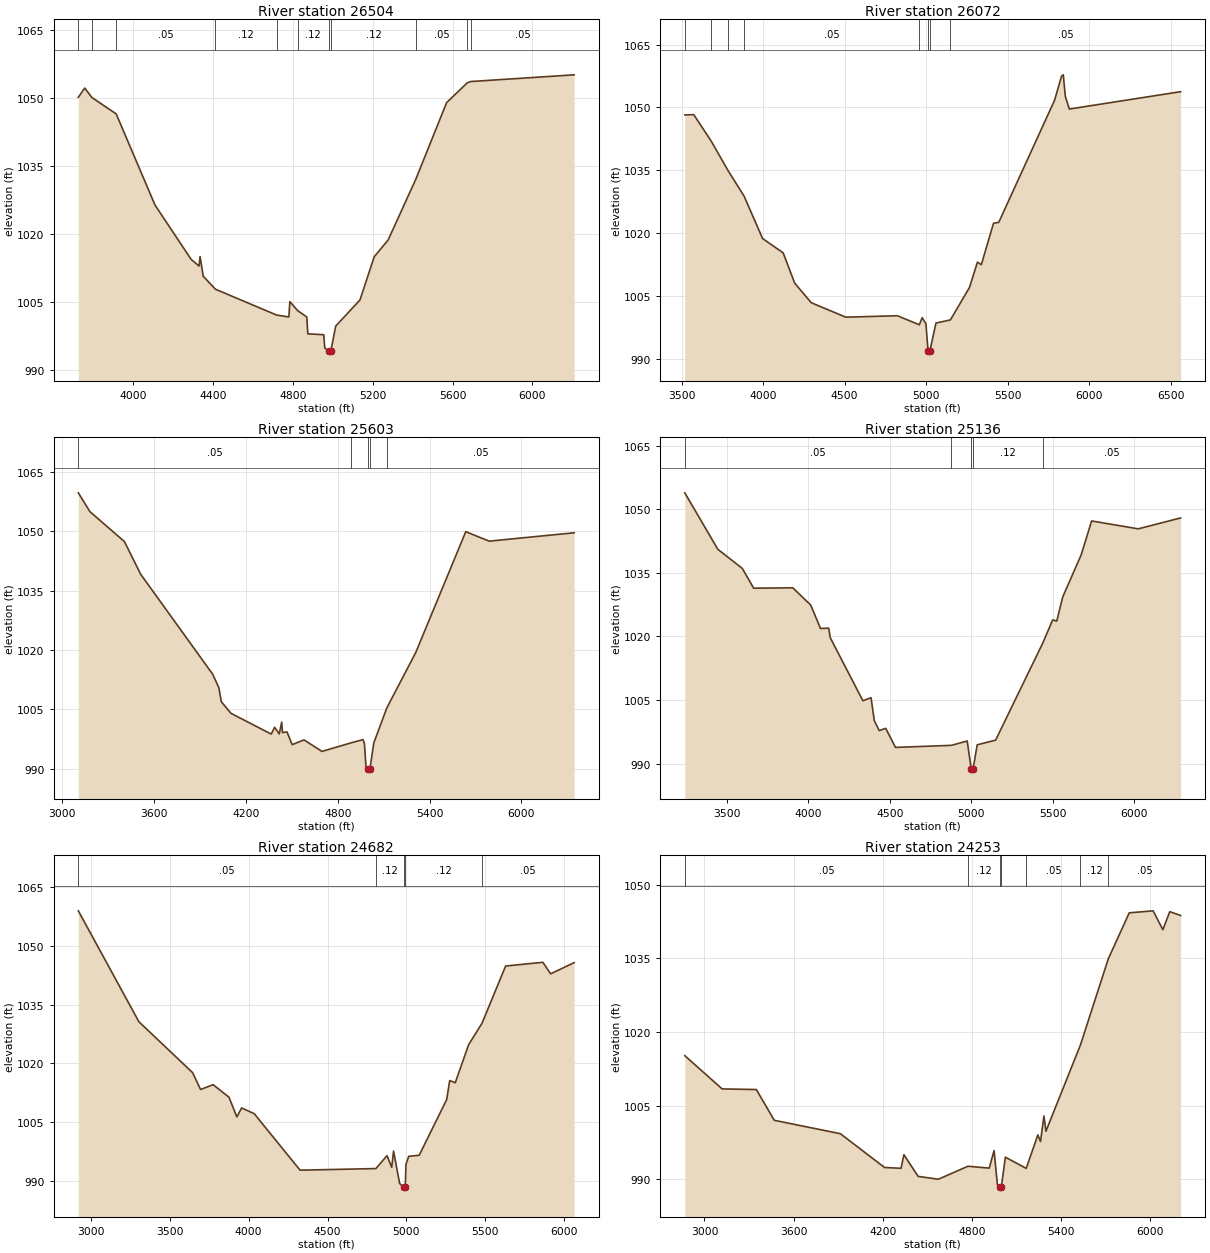
Type RM Length L Ch R = 1 ,26504   ,432,432,432
BEGIN DESCRIPTION:
MALLARD CREEK 45.0
END DESCRIPTION:
XS GIS Cut Line= 3
      2227050.87      7265316.87        2225779.        7265460.
      2224649.85      7265879.36
#Sta/Elev= 30
  3724.5 1050.15  3756.6 1052.19  3792.7 1050.09  3914.2 1046.48  4108.8 1026.33
  4289.9 1014.34  4329.4 1012.87  4334.5 1014.97  4350.3 1010.62  4411.4 1007.75
  4718.2 1002.04  4779.4 1001.62  4784.4    1005    4824    1003  4869.4 1001.61
  4874.4   997.9  4954.1  997.69  4959.4  994.77  4978.7  994.13  4980.2  993.63
  4989.8  994.13  5014.2  999.61  5135.7 1005.37  5207.1 1014.92  5276.8 1018.62
  5416.2 1032.12  5569.8 1048.96    5673 1053.33  5691.7 1053.63  6208.9 1055.11
#Mann= 11 ,-1 , 0
  3724.5     .05       0  3792.7     .12       0  3914.2     .05       0
  4411.4     .12       0  4718.2     .05       0    4824     .12       0
  4978.7     .07       0  4989.8     .12       0  5416.2     .05       0
    5673     .12       0  5691.7     .05       0
Bank Sta=4978.7,4989.8
XS Rating Curve= 0 ,0
Exp/Cntr=0.3,0.1

Type RM Length L Ch R = 1 ,26072   ,469,469,469
BEGIN DESCRIPTION:
MALLARD CREEK 44.0
END DESCRIPTION:
XS GIS Cut Line= 3
      2227233.13      7264801.25        2225779.        7265060.
      2224316.55      7265618.93
#Sta/Elev= 30
  3519.2 1048.23  3574.2 1048.29  3681.2 1041.99  3782.3 1035.11  3883.5 1028.83
  3996.5 1018.75  4122.7 1015.34  4193.8  1008.1  4295.3 1003.44  4507.3  999.99
  4823.5 1000.34  4958.4  998.18  4975.9  999.87  4998.9  998.42    5012  991.92
  5013.5  991.42  5023.1  991.92  5060.4  998.59    5149  999.34  5265.7 1007.04
  5315.1 1013.12  5338.8 1012.52  5413.7 1022.39  5445.8  1022.6  5788.4 1051.73
  5831.2  1057.5  5841.9 1057.79  5854.2 1052.67  5878.9 1049.63  6561.8 1053.77
#Mann= 8 ,-1 , 0
  3519.2     .12       0  3681.2     .05       0  3782.3     .12       0
  3883.5     .05       0  4958.4     .12       0    5012     .07       0
  5023.1     .12       0    5149     .05       0
Bank Sta=5012,5023.1
XS Rating Curve= 0 ,0
Exp/Cntr=0.3,0.1

Type RM Length L Ch R = 1 ,25603   ,467,467,467
BEGIN DESCRIPTION:
MALLARD CREEK 43.0
END DESCRIPTION:
XS GIS Cut Line= 3
      2227446.72      7264473.11        2225579.        7264760.
      2224253.99      7265019.99
#Sta/Elev= 30
  3105.2 1059.74  3181.1 1054.98  3406.4 1047.42  3512.7 1039.16  3983.1  1013.9
  4023.6  1010.5  4039.3 1006.97  4102.5 1004.02  4365.8  998.77  4387.8 1000.49
  4418.1  998.81  4434.1 1001.78  4439.2  999.16  4468.7  999.31  4502.5   996.1
    4580   997.3  4697.4  994.39  4889.2  996.58  4965.7  997.37  4974.6  996.42
  4984.7   990.6  4999.5  989.91    5001  989.41  5010.6  989.91  5035.6  996.51
  5120.9 1005.37  5310.7 1019.44  5636.8 1049.92  5789.7 1047.53  6345.1 1049.64
#Mann= 5 ,-1 , 0
  3105.2     .05       0  4889.2     .12       0  4999.5     .07       0
  5010.6     .12       0  5120.9     .05       0
Bank Sta=4999.5,5010.6
XS Rating Curve= 0 ,0
Exp/Cntr=0.3,0.1

Type RM Length L Ch R = 1 ,25136   ,454,454,454
BEGIN DESCRIPTION:
MALLARD CREEK 42.0
END DESCRIPTION:
XS GIS Cut Line= 3
      2227381.55      7264297.09        2225629.        7264310.
      2224376.34       7264614.8
#Sta/Elev= 30
  3242.4 1053.85    3445 1040.54    3595 1036.04    3665 1031.37    3905 1031.46
    4015 1027.39    4075 1021.87    4125 1021.95    4135 1019.68    4335 1004.84
    4385 1005.56    4405 1000.16    4435  997.81    4475  998.33    4535  993.84
  4878.2  994.33    4975  995.35  4999.7  988.75  5001.2  988.25  5010.9  988.75
  5036.2  994.45  5149.4  995.56  5438.2 1018.41  5499.3  1023.9  5524.4 1023.62
    5561 1029.31  5674.2 1039.23  5738.2 1047.22  6024.2 1045.36  6284.2 1047.93
#Mann= 5 ,-1 , 0
  3242.4     .05       0  4878.2     .12       0  4999.7     .07       0
  5010.9     .12       0  5438.2     .05       0
Bank Sta=4999.7,5010.9
XS Rating Curve= 0 ,0
Exp/Cntr=0.3,0.1

Type RM Length L Ch R = 1 ,24682   ,429,429,429
BEGIN DESCRIPTION:
MALLARD CREEK 41.0
END DESCRIPTION:
XS GIS Cut Line= 3
      2227522.18      7264062.71        2225429.        7263960.
      2224454.42      7264338.77
#Sta/Elev= 30
  2921.4 1058.94    3305 1030.62  3645.5 1017.61  3695.7 1013.31  3775.6 1014.54
  3875.7 1011.35  3925.8 1006.31  3955.8  1008.6  4035.9 1007.13  4326.3  992.71
  4806.6  993.12  4876.9  996.41    4907  993.44  4918.5  997.59    4957  989.32
  4981.5  988.37    4983  987.87  4992.7  988.37  4997.1   994.2  5014.6  996.24
  5081.1  996.52  5255.1 1010.74  5274.3 1015.59  5309.5 1015.04  5393.9 1024.74
    5479 1030.23  5628.6 1044.85  5864.7 1045.79  5913.6 1042.85  6062.7 1045.71
#Mann= 5 ,-1 , 0
  2921.4     .05       0  4806.6     .12       0  4981.5     .07       0
  4992.7     .12       0    5479     .05       0
Bank Sta=4981.5,4992.7
XS Rating Curve= 0 ,0
Exp/Cntr=0.3,0.1

Type RM Length L Ch R = 1 ,24253   ,537,537,537
BEGIN DESCRIPTION:
MALLARD CREEK 40.0
END DESCRIPTION:
XS GIS Cut Line= 3
      2227569.05      7263026.25        2225529.        7263660.
      2224429.57      7264145.54
#Sta/Elev= 30
  2867.6 1015.16    3119 1008.39  3349.3 1008.26  3469.9    1002  3914.8  999.27
  4212.5  992.39  4323.2  992.22  4342.7  994.99  4438.4  990.58  4574.5  989.99
  4774.3  992.64  4917.2  992.26  4949.7  995.83  4972.4  988.84  4987.8  988.48
  4989.3  987.98    4999  988.48  5025.7  994.49  5166.3   992.2  5244.4  999.02
  5262.2  997.68  5285.5 1002.88    5299  999.78    5531 1017.32  5719.3 1034.92
  5859.9 1044.25  6020.5 1044.66  6086.1 1040.82  6132.7 1044.49  6205.7 1043.71
#Mann= 7 ,-1 , 0
  2867.6     .05       0  4774.3     .12       0  4987.8     .07       0
    4999     .12       0  5166.3     .05       0    5531     .12       0
  5719.3     .05       0
Bank Sta=4987.8,4999
XS Rating Curve= 0 ,0
Exp/Cntr=0.3,0.1

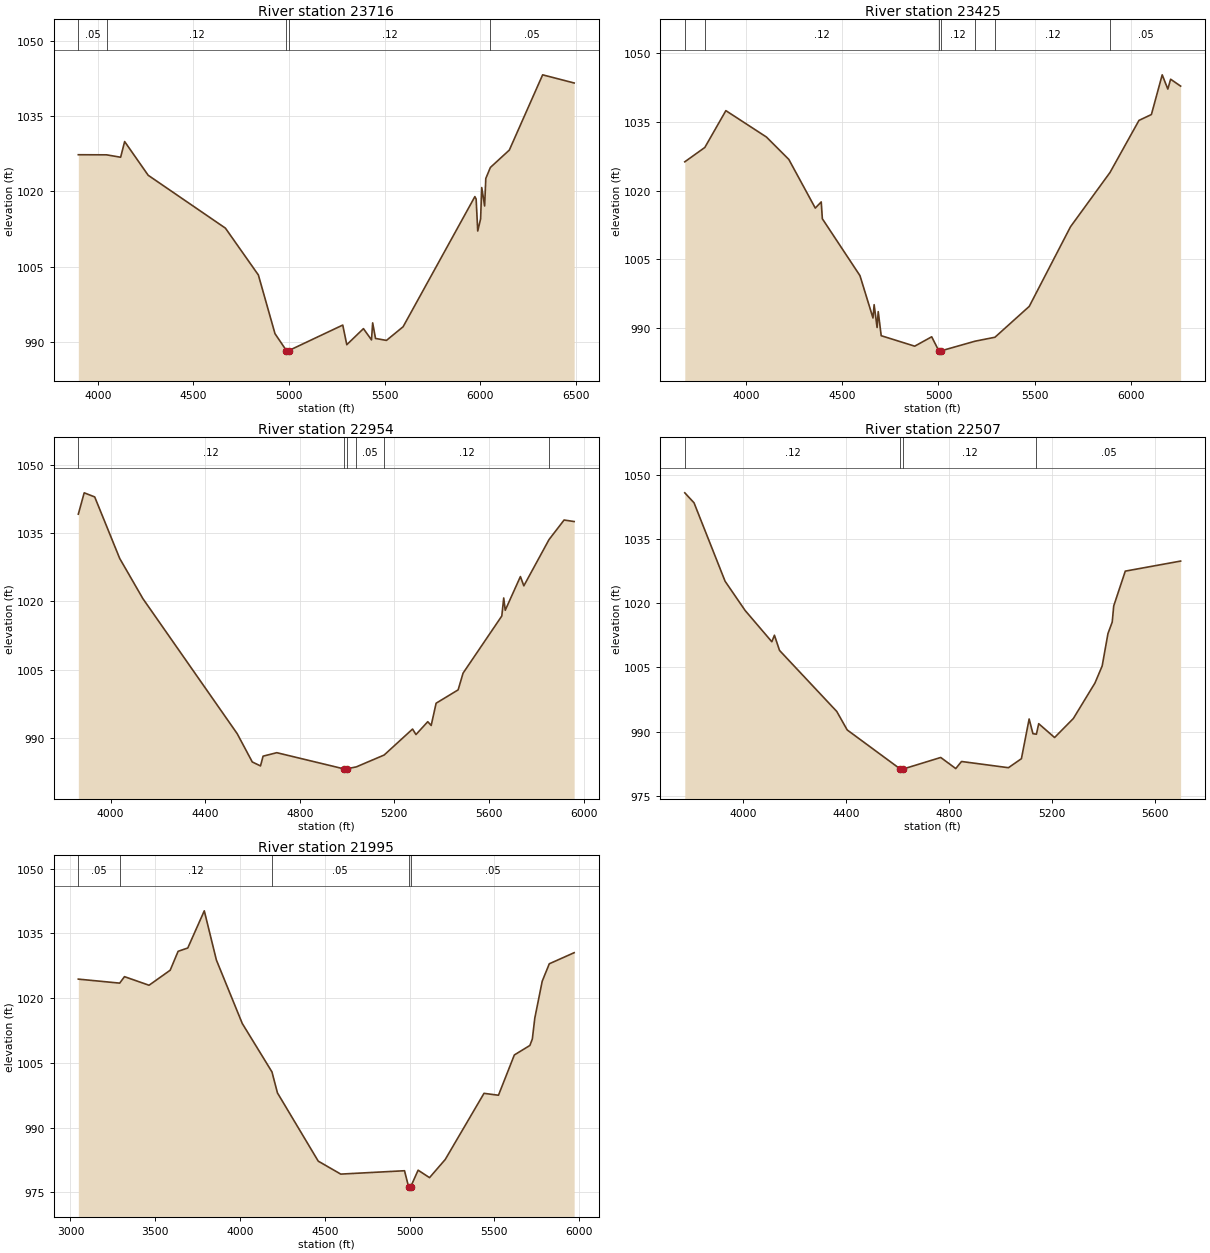
Type RM Length L Ch R = 1 ,23716   ,291,291,291
BEGIN DESCRIPTION:
MALLARD CREEK 39.0
END DESCRIPTION:
XS GIS Cut Line= 3
      2226537.81      7262541.87      2225652.38      7263135.63
      2224382.79      7263983.75
#Sta/Elev= 30
  3898.1 1027.32    4046  1027.3  4119.3 1026.82  4140.3 1029.95  4263.4 1023.22
  4667.2 1012.67  4839.6 1003.32  4926.6   991.6  4986.5  988.22  4988.1  987.72
  4998.2  988.22  5280.9  993.32    5302   989.4  5389.1  992.61  5431.2  990.36
  5437.3  993.76  5452.2  990.65  5509.4  990.26  5596.4  992.98  5971.8 1018.96
  5978.4 1018.48  5986.8 1012.09  6001.8 1014.52  6007.8 1020.77  6022.9 1017.09
  6028.9 1022.58  6052.9 1024.78    6152 1028.25  6326.2 1043.27    6491 1041.64
#Mann= 5 ,-1 , 0
  3898.1     .05       0    4046     .12       0  4986.5     .07       0
  4998.2     .12       0  6052.9     .05       0
Bank Sta=4986.5,4998.2
XS Rating Curve= 0 ,0
Exp/Cntr=0.3,0.1

Type RM Length L Ch R = 1 ,23425   ,471,471,471
BEGIN DESCRIPTION:
MALLARD CREEK 38.0
END DESCRIPTION:
XS GIS Cut Line= 3
      2226496.16      7262463.74      2225365.92      7263151.26
      2224361.68      7263905.73
#Sta/Elev= 30
  3680.7 1026.31  3784.8 1029.44  3894.4 1037.49  4105.5 1031.72  4221.8 1026.83
  4359.4 1016.19  4390.3 1017.54  4396.2 1013.86  4591.9 1001.42  4659.6  992.17
  4665.5  995.08  4680.9  990.09  4686.8  993.56  4702.3   988.3  4876.6  986.01
  4964.9  988.06  5002.1  984.99  5003.7  984.49  5013.8  984.99  5190.6   987.1
    5294  987.96  5472.4  994.71  5686.9 1012.11  5892.4 1023.98  6043.1 1035.36
  6107.7 1036.64  6163.9 1045.32  6193.1 1042.21  6207.7 1044.36  6259.7 1042.85
#Mann= 7 ,-1 , 0
  3680.7     .05       0  3784.8     .12       0  5002.1     .07       0
  5013.8     .12       0  5190.6     .05       0    5294     .12       0
  5892.4     .05       0
Bank Sta=5002.1,5013.8
XS Rating Curve= 0 ,0
Exp/Cntr=0.3,0.1

Type RM Length L Ch R = 1 ,22954   ,447,447,447
BEGIN DESCRIPTION:
MALLARD CREEK 37.0
END DESCRIPTION:
XS GIS Cut Line= 3
       2226022.2      7262442.91        2224979.        7262910.
      2224225.29      7263495.01
#Sta/Elev= 30
  3863.3 1039.13  3888.1  1043.8  3932.6  1042.9  4038.2 1029.43  4136.4 1020.61
  4535.2  991.02    4599  984.82  4633.8  983.95  4644.7  986.09  4702.7  986.85
  4986.1  983.31  4987.7  982.81  4997.8  983.31    5039  983.74  5156.8  986.34
  5276.9  992.03  5291.4  990.83  5341.2  993.64  5355.7  992.82  5376.5  997.69
  5469.7 1000.62  5490.5 1004.28  5654.4 1016.81  5662.5 1020.76  5668.9 1018.06
  5733.1 1025.45  5747.6 1023.42  5854.1 1033.55  5917.8 1037.84  5960.4 1037.51
#Mann= 6 ,-1 , 0
  3863.3     .12       0  4986.1     .07       0  4997.8     .12       0
    5039     .05       0  5156.8     .12       0  5854.1     .05       0
Bank Sta=4986.1,4997.8
XS Rating Curve= 0 ,0
Exp/Cntr=0.3,0.1

Type RM Length L Ch R = 1 ,22507   ,512,512,512
BEGIN DESCRIPTION:
MALLARD CREEK 36.0
END DESCRIPTION:
XS GIS Cut Line= 3
      2225944.07      7262380.42        2224729.        7262560.
      2224100.34      7262869.98
#Sta/Elev= 30
  3771.7 1045.79  3807.6 1043.46  3928.5 1025.14  4006.2 1018.33  4110.4    1011
  4120.5 1012.53  4140.3 1008.98  4363.1  994.72  4403.6  990.41    4610  981.29
  4611.6  980.79  4621.7  981.29  4767.5  983.98    4826  981.39  4848.3  983.04
  5030.9  981.59  5081.4  983.69  5111.5  992.97  5126.3  989.53  5139.8  989.41
  5148.7  991.87  5210.5  988.64  5283.5  993.08  5367.7 1001.38  5395.7 1005.36
  5418.2 1012.92  5434.8 1015.61  5440.6 1019.37  5485.6  1027.5  5700.9 1029.85
#Mann= 4 ,-1 , 0
  3771.7     .12       0    4610     .07       0  4621.7     .12       0
  5139.8     .05       0
Bank Sta=4610,4621.7
XS Rating Curve= 0 ,0
Exp/Cntr=0.3,0.1

Type RM Length L Ch R = 1 ,21995   ,428,428,428
BEGIN DESCRIPTION:
MALLARD CREEK 35.0
END DESCRIPTION:
XS GIS Cut Line= 4
      2226648.46      7262437.06      2224787.79      7262078.34
      2224647.17      7262088.76      2223938.99       7262625.1
#Sta/Elev= 30
  3046.4 1024.39  3290.3 1023.46  3318.6 1024.96  3463.4 1022.97  3588.1 1026.45
  3634.9 1030.83  3691.9  1031.6  3789.3 1040.21  3860.6 1028.82  4013.3 1014.11
  4188.5 1002.89  4220.8  998.03  4461.4  982.22  4594.1  979.22  4970.2     980
  4994.4  976.24    4996  975.74  5006.1  976.24  5050.4  980.13  5117.7   978.4
  5210.2   982.6    5439  997.93  5524.3  997.49  5617.9 1006.82  5709.5 1009.02
  5724.1 1010.52  5738.6 1015.36  5782.3  1023.9    5824 1027.94  5970.7 1030.51
#Mann= 5 ,-1 , 0
  3046.4     .05       0  3290.3     .12       0  4188.5     .05       0
  4994.4    .033       0  5006.1     .05       0
Bank Sta=4994.4,5006.1
XS Rating Curve= 0 ,0
Exp/Cntr=0.3,0.1