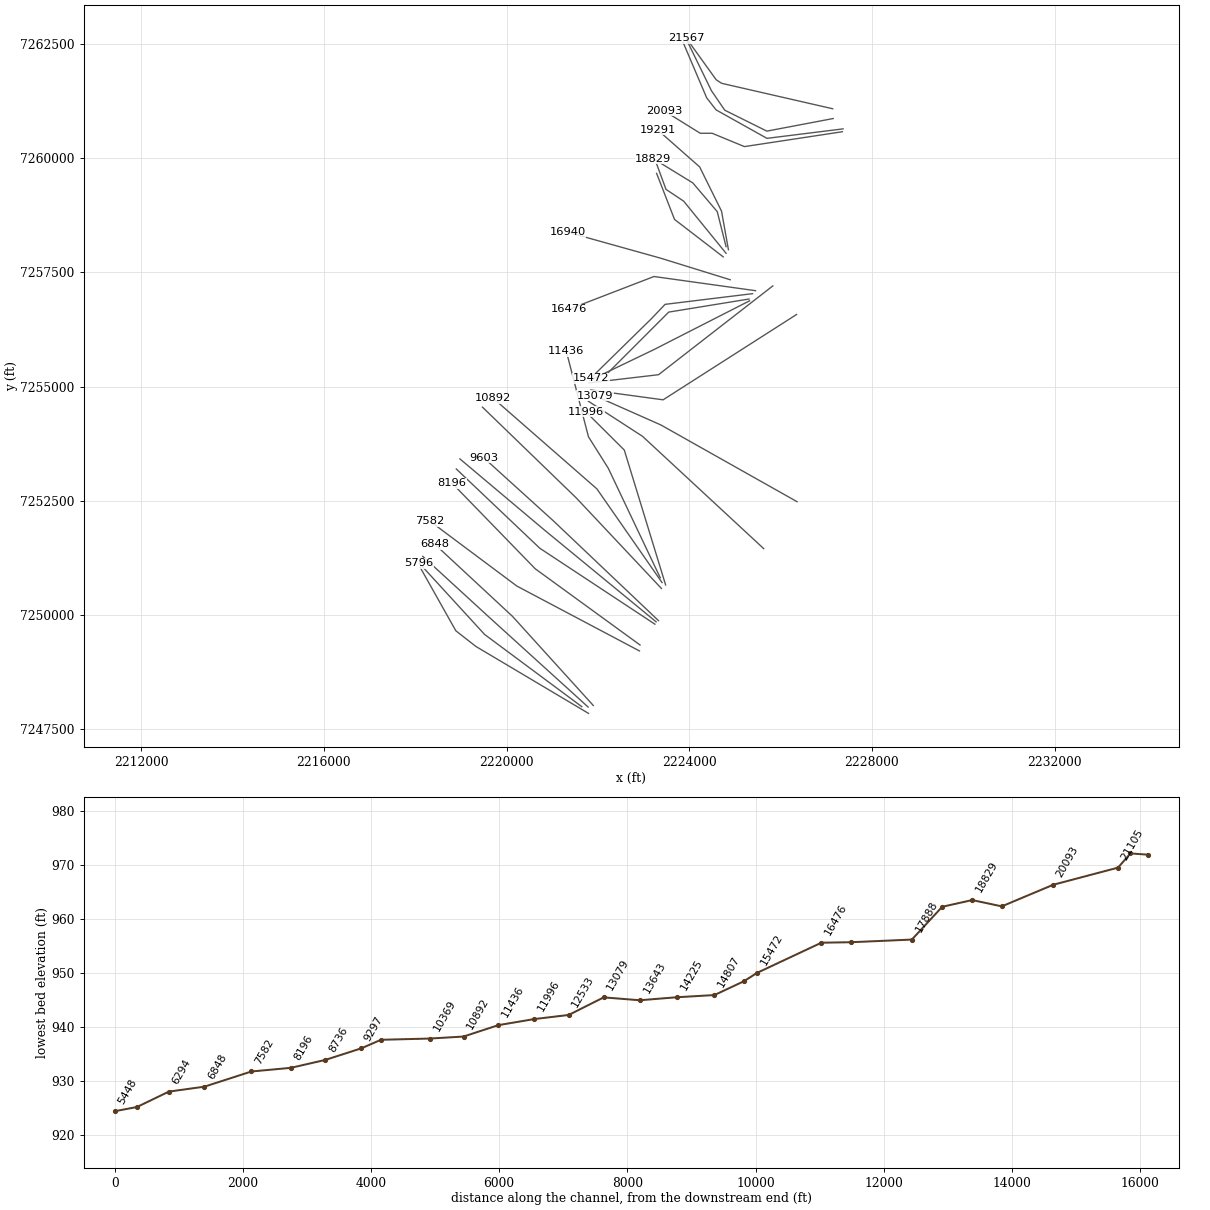
HEC-RAS study MALLARD CREEK.prj: MALLARD CREEK Base Level Engineering

--- MALLARD CREEK.g01 (geometry) --- (continued)

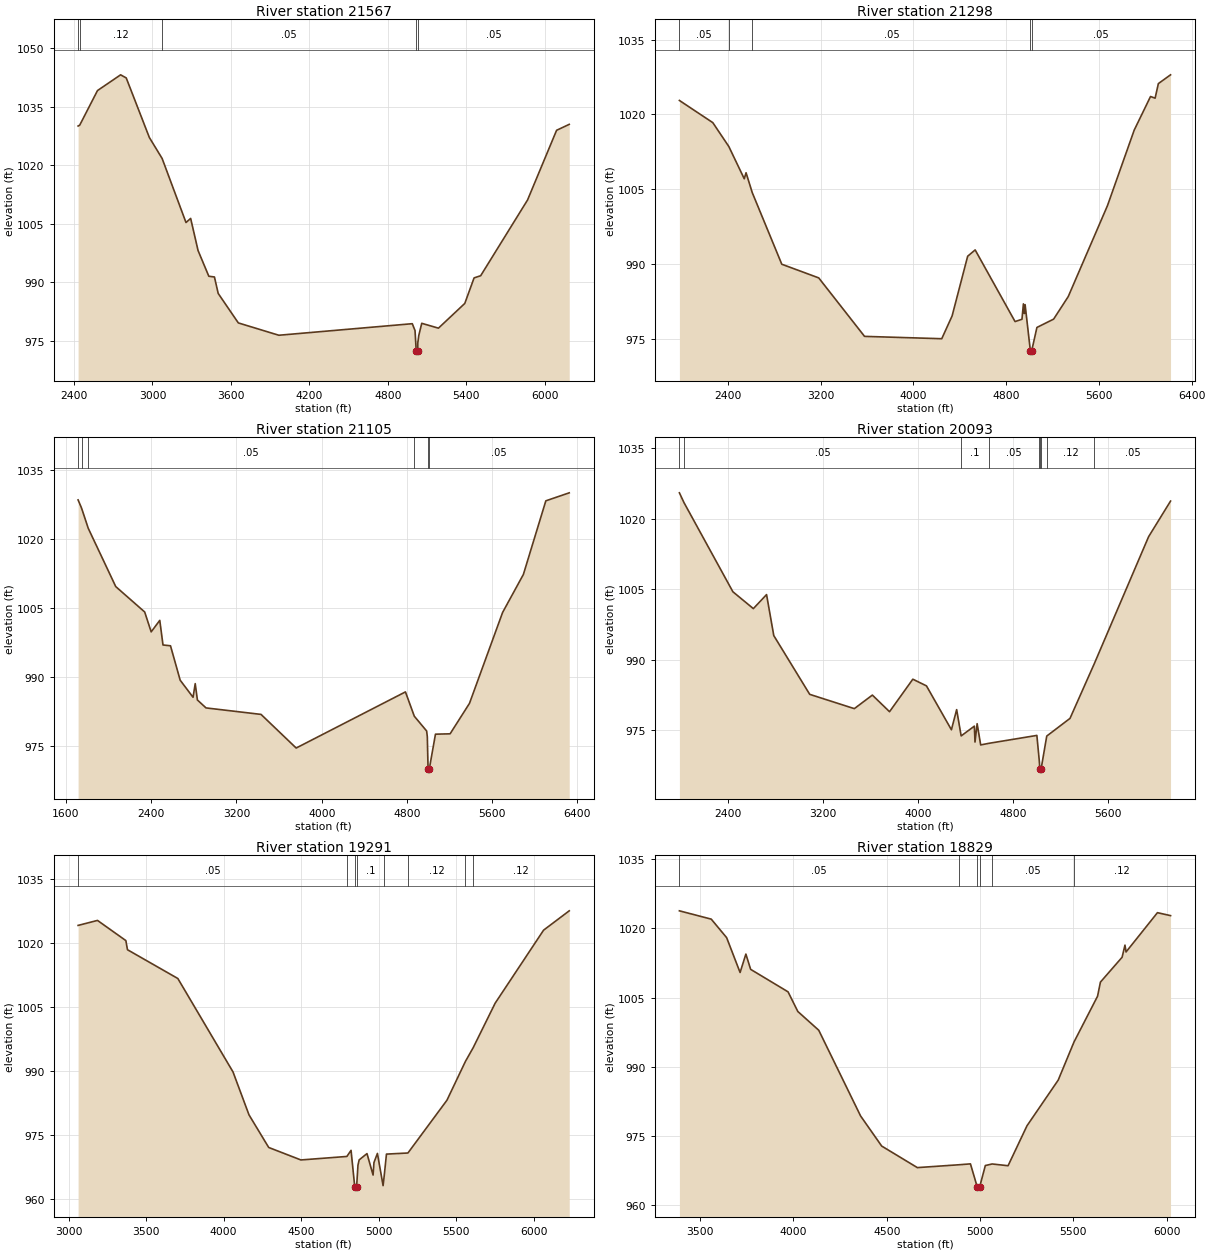
Type RM Length L Ch R = 1 ,21567   ,269,269,269
BEGIN DESCRIPTION:
MALLARD CREEK 34.5
END DESCRIPTION:
XS GIS Cut Line= 4
      2227143.27      7261082.89      2224710.97      7261640.19
      2224591.18      7261718.31      2223938.89      7262625.14
#Sta/Elev= 30
  2431.5 1030.08  2443.8  1030.3  2579.9 1039.17  2756.7  1043.2  2799.6  1042.4
  2976.4 1027.14    3074 1021.77  3256.6 1005.35  3292.1 1006.41  3348.9  998.17
  3431.1  991.59    3474   991.4  3502.8  987.18  3656.7  979.63  3966.5  976.47
  4986.7  979.43  5007.8  977.67    5017  972.39  5018.7  971.89  5028.8  972.39
  5028.9  974.52  5036.6  976.42  5059.2  979.53  5186.9  978.29  5388.2  984.62
  5459.4  991.17  5509.7  991.72  5868.2 1011.13  6090.3 1028.99  6186.9 1030.51
#Mann= 5 ,-1 , 0
  2431.5     .05       0  2443.8     .12       0    3074     .05       0
    5017    .033       0  5028.8     .05       0
Bank Sta=5017,5028.8
XS Rating Curve= 0 ,0
Exp/Cntr=0.3,0.1

Type RM Length L Ch R = 1 ,21298   ,193,193,193
BEGIN DESCRIPTION:
MALLARD CREEK 34.0
END DESCRIPTION:
XS GIS Cut Line= 5
      2227153.69      7260869.36      2225700.55      7260593.31
      2224778.68      7261051.65      2224487.01      7261478.73
      2223956.33      7262566.12
#Sta/Elev= 30
  1982.1  1022.8  2270.1 1018.35  2408.1 1013.57  2541.4 1007.09  2556.9  1008.3
  2610.5 1004.31  2865.1  989.95  3183.6  987.21  3578.8  975.48  4244.7  975.01
    4334  979.58  4468.1  991.55  4532.8  992.82  4876.9  978.45  4936.5  978.91
  4948.9     982  4957.5  980.06  4963.6  981.85  5008.9  972.62  5010.6  972.12
  5020.7  972.62  5065.5  977.27  5209.6  978.94  5335.8  983.47  5673.7 1001.69
  5904.5 1016.85  6045.3 1023.59  6084.8 1023.26  6112.9 1026.18  6217.9 1027.94
#Mann= 5 ,-1 , 0
  1982.1     .05       0  2408.1     .12       0  2610.5     .05       0
  5008.9    .033       0  5020.7     .05       0
Bank Sta=5008.9,5020.7
XS Rating Curve= 0 ,0
Exp/Cntr=0.3,0.1

Type RM Length L Ch R = 1 ,21105   ,1012,1012,1012
BEGIN DESCRIPTION:
MALLARD CREEK 33.0
END DESCRIPTION:
XS GIS Cut Line= 5
      2227369.68      7260642.72      2225702.44      7260435.22
      2224588.37      7261058.72      2224382.85      7261322.48
      2223867.46      7262535.47
#Sta/Elev= 30
  1713.9 1028.44  1746.6 1026.65    1809 1022.28  2067.3  1009.6  2338.8 1004.08
  2399.8  999.76  2480.4 1002.26  2510.7  996.91  2581.1  996.73    2672  989.25
  2792.8  985.54    2813  988.51  2833.6  984.95  2914.4  983.23  3430.6  981.82
  3760.5  974.51  4785.9  986.71  4869.2  981.42  4984.9  978.21  4991.2  976.96
  4998.2  969.99  4999.9  969.49    5010  969.99  5067.6  977.52    5205   977.6
  5386.9  984.22  5697.9 1003.99  5892.5 1012.23  6103.4 1028.24    6323 1029.98
#Mann= 6 ,-1 , 0
  1713.9     .05       0  1746.6     .12       0    1809     .05       0
  4869.2     .12       0  4998.2     .07       0    5010     .05       0
Bank Sta=4998.2,5010
XS Rating Curve= 0 ,0
Exp/Cntr=0.3,0.1

Type RM Length L Ch R = 1 ,20093   ,802,802,802
BEGIN DESCRIPTION:
MALLARD CREEK 32.0
END DESCRIPTION:
XS GIS Cut Line= 5
      2227354.01      7260580.21      2225209.18      7260254.42
      2224502.64      7260546.44      2224242.22      7260546.44
      2223445.39       7261041.2
#Sta/Elev= 30
  1991.7 1025.47  2030.7 1023.37  2441.8 1004.44  2613.8 1000.86    2725 1003.84
  2785.7  995.13    3088  982.64  3463.4   979.6  3615.1  982.48  3759.7  978.95
  3955.7  985.86  4070.3  984.44  4280.3  975.11  4324.4  979.39  4362.2   973.8
  4473.3  975.88  4478.7   972.5  4496.8   976.4  4526.5  971.89  4595.7  972.23
  4999.3  973.91  5020.5  968.28  5023.4  966.82    5025  966.32  5035.2  966.82
  5082.4  973.77  5278.1  977.53  5482.2  989.14  5939.5 1016.15    6124 1023.71
#Mann= 9 ,-1 , 0
  1991.7     .12       0  2030.7     .05       0  4362.2      .1       0
  4595.7     .05       0  5020.5      .1       0  5023.4     .04       0
  5035.2      .1       0  5082.4     .12       0  5482.2     .05       0
Bank Sta=5023.4,5035.2
XS Rating Curve= 0 ,0
Exp/Cntr=0.3,0.1

Type RM Length L Ch R = 1 ,19291   ,462,462,462
BEGIN DESCRIPTION:
MALLARD CREEK 30.0
END DESCRIPTION:
XS GIS Cut Line= 4
      2224859.27      7257996.85      2224708.22      7258840.64
        2224229.        7259810.       2223307.2      7260621.87
#Sta/Elev= 30
  3061.4 1024.16  3186.5 1025.33  3369.4  1020.6  3379.8 1018.46  3704.6 1011.71
  4060.4   989.8  4163.3  979.75  4290.4   972.1    4498  969.17  4794.5  969.99
  4821.5  971.42  4845.4  962.83  4847.1  962.33  4857.2  962.83  4866.1  967.96
  4873.8  969.19  4924.2  970.66  4963.5  965.63  4969.1  968.56  4991.5   970.7
    5028  963.15  5034.8  965.31  5049.8  970.54  5188.2   970.8  5439.7  983.17
  5559.3   992.3  5608.4  995.45  5750.9 1005.94    6063 1023.05  6228.3 1027.58
#Mann= 8 ,-1 , 0
  3061.4     .05       0  4794.5      .1       0  4845.4     .07       0
  4857.2      .1       0  5034.8     .05       0  5188.2     .12       0
  5559.3     .05       0  5608.4     .12       0
Bank Sta=4845.4,4857.2
XS Rating Curve= 0 ,0
Exp/Cntr=0.3,0.1

Type RM Length L Ch R = 1 ,18829   ,468,468,468
BEGIN DESCRIPTION:
MALLARD CREEK 29.0
END DESCRIPTION:
XS GIS Cut Line= 4
      2224807.18       7258064.6      2224614.47      7258830.22
        2224079.        7259460.      2223213.33      7259991.18
#Sta/Elev= 30
  3388.8 1023.78  3559.4 1021.98  3641.9 1017.97    3714 1010.42    3745 1014.41
  3770.6  1011.1    3971 1006.23  4023.4 1001.97  4135.5  997.91  4359.7  979.34
  4472.8  972.82  4663.9  968.15  4887.6  968.77  4948.4  968.96  4984.6  963.99
  4986.5  963.49  4997.8  963.99  5028.1   968.6  5064.4  968.94    5150  968.56
  5251.3  977.21  5418.7  987.11  5503.1  995.35  5629.5 1005.28  5644.9 1008.34
    5761 1013.72  5776.4 1016.35  5782.2 1014.87  5950.4 1023.38  6020.6 1022.74
#Mann= 6 ,-1 , 0
  3388.8     .05       0  4887.6      .1       0  4984.6     .07       0
  4997.8      .1       0  5064.4     .05       0  5503.1     .12       0
Bank Sta=4984.6,4997.8
XS Rating Curve= 0 ,0
Exp/Cntr=0.3,0.1

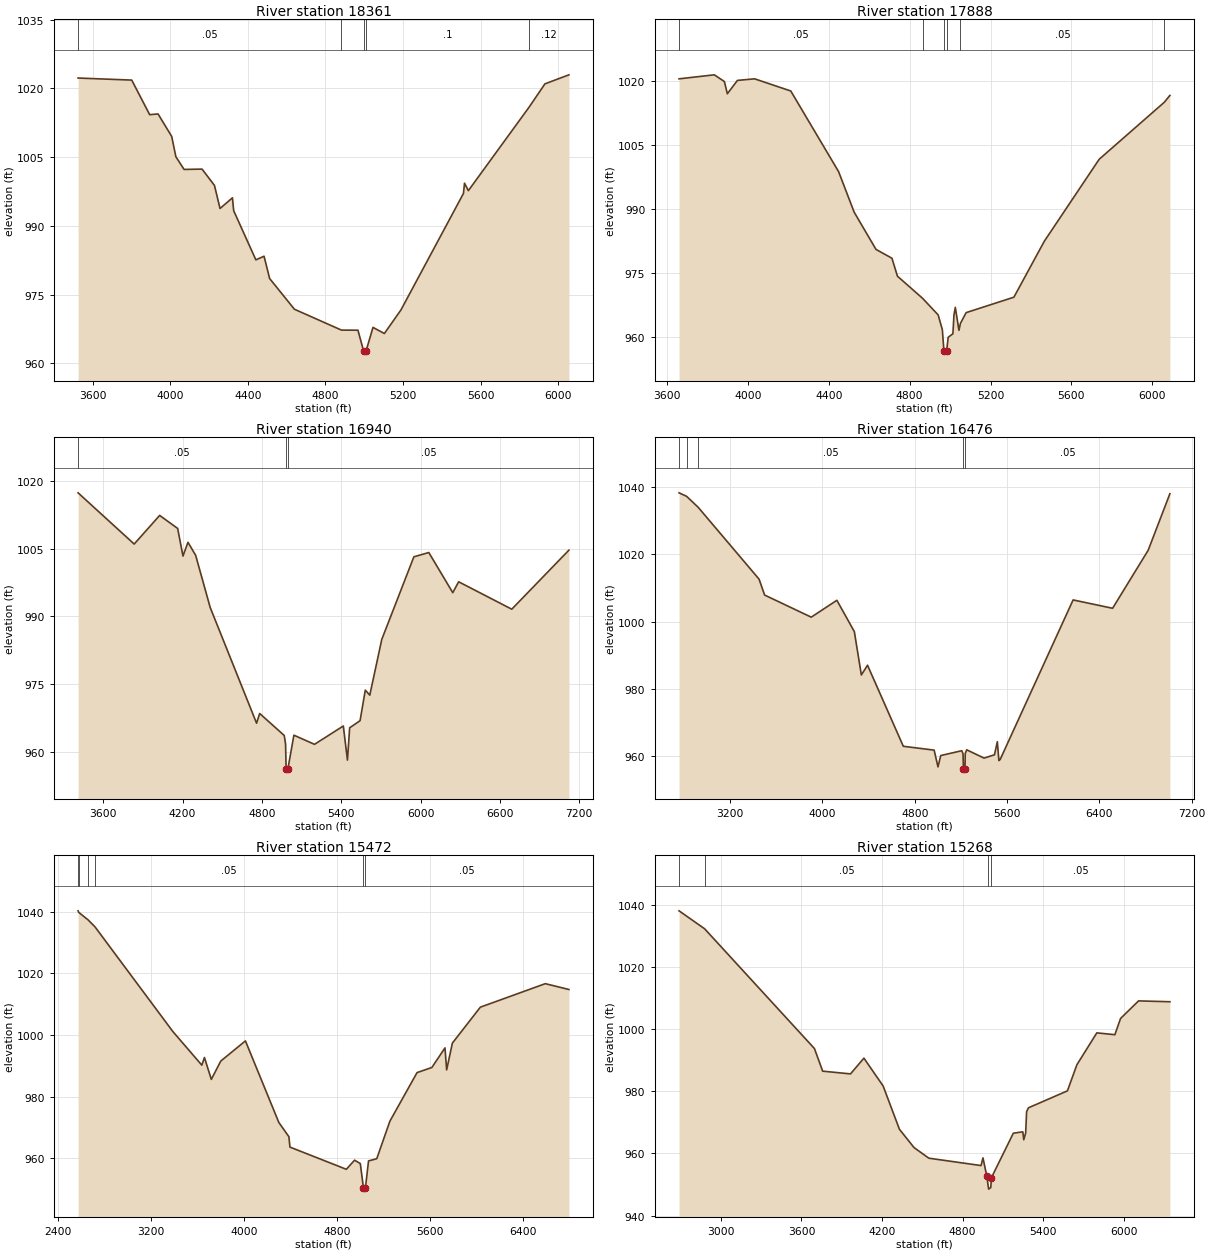
Type RM Length L Ch R = 1 ,18361   ,473,473,473
BEGIN DESCRIPTION:
MALLARD CREEK 28.0
END DESCRIPTION:
XS GIS Cut Line= 4
      2224807.15       7257918.8        2223879.        7259060.
      2223491.82      7259318.12      2223286.71      7259876.09
#Sta/Elev= 30
  3524.7 1022.24  3801.3 1021.79  3893.9 1014.25    3937 1014.41  4007.4 1009.51
    4029 1005.07  4071.3 1002.31    4164 1002.38  4227.9  998.82  4256.6  993.79
  4320.6  996.12    4327  993.31  4441.4  982.59  4483.6  983.38  4512.3  978.52
  4640.2  971.82  4882.7  967.27  4967.7  967.25  4996.6  962.75  4998.5  962.25
  5009.8  962.75  5045.3  967.86  5103.9  966.53  5189.5  971.67  5511.8  997.08
  5517.1  999.31    5537  997.68  5851.5 1015.97  5931.8 1020.97  6055.5 1022.94
#Mann= 5 ,-1 , 0
  3524.7     .05       0  4882.7      .1       0  4996.6     .04       0
  5009.8      .1       0  5851.5     .12       0
Bank Sta=4996.6,5009.8
XS Rating Curve= 0 ,0
Exp/Cntr=0.3,0.1

Type RM Length L Ch R = 1 ,17888   ,948,948,948
BEGIN DESCRIPTION:
MALLARD CREEK 27.0
END DESCRIPTION:
XS GIS Cut Line= 3
      2224744.71      7257840.61        2223679.        7258660.
      2223286.34      7259668.78
#Sta/Elev= 30
  3660.1 1020.53  3834.5 1021.47  3884.3 1019.89  3898.8 1017.03  3948.7 1020.16
  4033.8 1020.53  4212.4 1017.68  4448.9  998.76  4525.9  989.25  4633.8  980.52
  4712.6  978.45  4739.8  974.24  4864.1  969.05    4941  965.16  4961.8  961.71
  4969.7  956.69  4971.6  956.19  4982.9  956.69  4990.8  959.91    5014  960.73
  5019.3  965.15  5025.9  966.92  5043.9  961.54  5051.2  963.16  5079.5  965.69
  5315.6  969.31  5465.8  982.42  5737.2 1001.66  6059.1 1015.03  6086.9 1016.64
#Mann= 6 ,-1 , 0
  3660.1     .05       0  4864.1      .1       0  4969.7     .07       0
  4982.9      .1       0  5051.2     .05       0  6059.1     .12       0
Bank Sta=4969.7,4982.9
XS Rating Curve= 0 ,0
Exp/Cntr=0.3,0.1

Type RM Length L Ch R = 1 ,16940   ,464,464,464
BEGIN DESCRIPTION:
MALLARD CREEK 25.0
END DESCRIPTION:
XS GIS Cut Line= 3
      2224898.31      7257339.08        2223379.        7257810.
      2221335.83      7258380.74
#Sta/Elev= 30
  3409.5 1017.42  3833.8 1006.06  4026.5 1012.41  4162.6 1009.52  4202.8 1003.39
  4240.6 1006.45  4298.7 1003.56  4408.8  991.98  4759.3  966.33    4783  968.48
  4968.7   963.6  4978.6  961.72    4983   956.2  4984.9   955.7  4996.3   956.2
  5041.6  963.67  5197.4  961.64  5415.4  965.71  5446.6  958.15  5463.4  965.31
  5542.1  966.89  5581.6  973.66  5615.6  972.55  5706.1   984.9    5949 1003.23
  6061.9 1004.18  6243.1  995.28  6287.6  997.69  6689.3  991.61  7121.5 1004.71
#Mann= 3 ,-1 , 0
  3409.5     .05       0    4983    .033       0  4996.3     .05       0
Bank Sta=4983,4996.3
XS Rating Curve= 0 ,0
Exp/Cntr=0.3,0.1

Type RM Length L Ch R = 1 ,16476   ,1004,1004,1004
BEGIN DESCRIPTION:
MALLARD CREEK 24.0
END DESCRIPTION:
XS GIS Cut Line= 3
      2225453.04      7257099.49        2223229.        7257410.
      2221356.68      7256688.04
#Sta/Elev= 30
  2758.7 1038.29  2823.9 1037.25  2924.4 1033.99  3451.9 1012.64  3499.9 1007.92
  3903.7 1001.35  4125.9 1006.36  4277.3  997.05  4337.9  984.18  4391.5  987.07
  4701.4  962.99  4968.6  961.85  5001.8  956.87  5025.7  960.24  5207.7  961.67
  5218.7   960.8  5222.7  956.11  5224.6  955.61    5236  956.11  5237.7  960.81
  5250.8  961.94  5400.9  959.48  5491.3  960.46    5516  964.35  5529.5  958.75
  5540.2  959.04  6172.5 1006.47  6514.6 1003.99  6822.9 1021.23    7011 1038.03
#Mann= 5 ,-1 , 0
  2758.7     .05       0  2823.9     .12       0  2924.4     .05       0
  5222.7    .033       0    5236     .05       0
Bank Sta=5222.7,5236
XS Rating Curve= 0 ,0
Exp/Cntr=0.3,0.1

Type RM Length L Ch R = 1 ,15472   ,204,204,204
BEGIN DESCRIPTION:
MALLARD CREEK 23.0
END DESCRIPTION:
XS GIS Cut Line= 4
      2225387.91      7257034.39      2223472.15      7256800.37
      2223174.37      7256487.51      2221846.21      7255185.39
#Sta/Elev= 30
  2574.5 1040.27  2579.8 1039.78  2660.8 1037.33  2720.3 1035.06  3389.3 1001.15
  3638.9  990.22  3661.4  992.71  3720.5  985.61    3802  991.56    4014  998.09
  4301.3  971.64  4387.8  967.03  4396.9  963.66  4881.8  956.46  4952.6  959.42
  5002.1  958.31  5028.7  950.53  5030.7  950.03  5046.3  950.53  5072.8  959.17
  5143.5  959.89  5256.6  972.07  5490.1  987.81  5617.3  989.47  5730.4  995.82
  5744.6  988.69  5794.1  997.38  6034.6 1009.03  6593.2 1016.65  6796.4 1014.76
#Mann= 6 ,-1 , 0
  2574.5     .12       0  2579.8     .05       0  2660.8     .12       0
  2720.3     .05       0  5028.7    .033       0  5046.3     .05       0
Bank Sta=5028.7,5046.3
XS Rating Curve= 0 ,0
Exp/Cntr=0.3,0.1

Type RM Length L Ch R = 1 ,15268   ,461,461,461
BEGIN DESCRIPTION:
MALLARD CREEK 22.0
END DESCRIPTION:
XS GIS Cut Line= 4
      2225309.81       7256917.2      2223551.97      7256630.74
      2223148.33      7256227.09      2222225.11      7255303.87
#Sta/Elev= 30
  2687.7 1038.02    2878 1032.25  3696.4  993.72  3757.9  986.44  3965.1  985.56
  4065.3  990.62  4208.3  981.67  4329.9  967.74  4439.3  961.83  4549.1  958.44
    4938  956.07  4952.2  958.55  4980.5  952.74  4992.8  948.99  4994.8  948.49
  5010.5  948.99  5015.8  952.22  5178.5  966.48  5249.2  966.92  5256.2  964.38
  5270.4  966.53  5277.5  973.44  5291.6  974.66  5581.5   980.1  5652.2   988.5
  5800.7  998.76  5935.1  998.17  5977.5 1003.39  6111.8 1009.05  6345.2 1008.77
#Mann= 4 ,-1 , 0
  2687.7     .12       0    2878     .05       0  4992.8    .033       0
  5010.5     .05       0
Bank Sta=4980.5,5015.8
XS Rating Curve= 0 ,0
Exp/Cntr=0.3,0.1

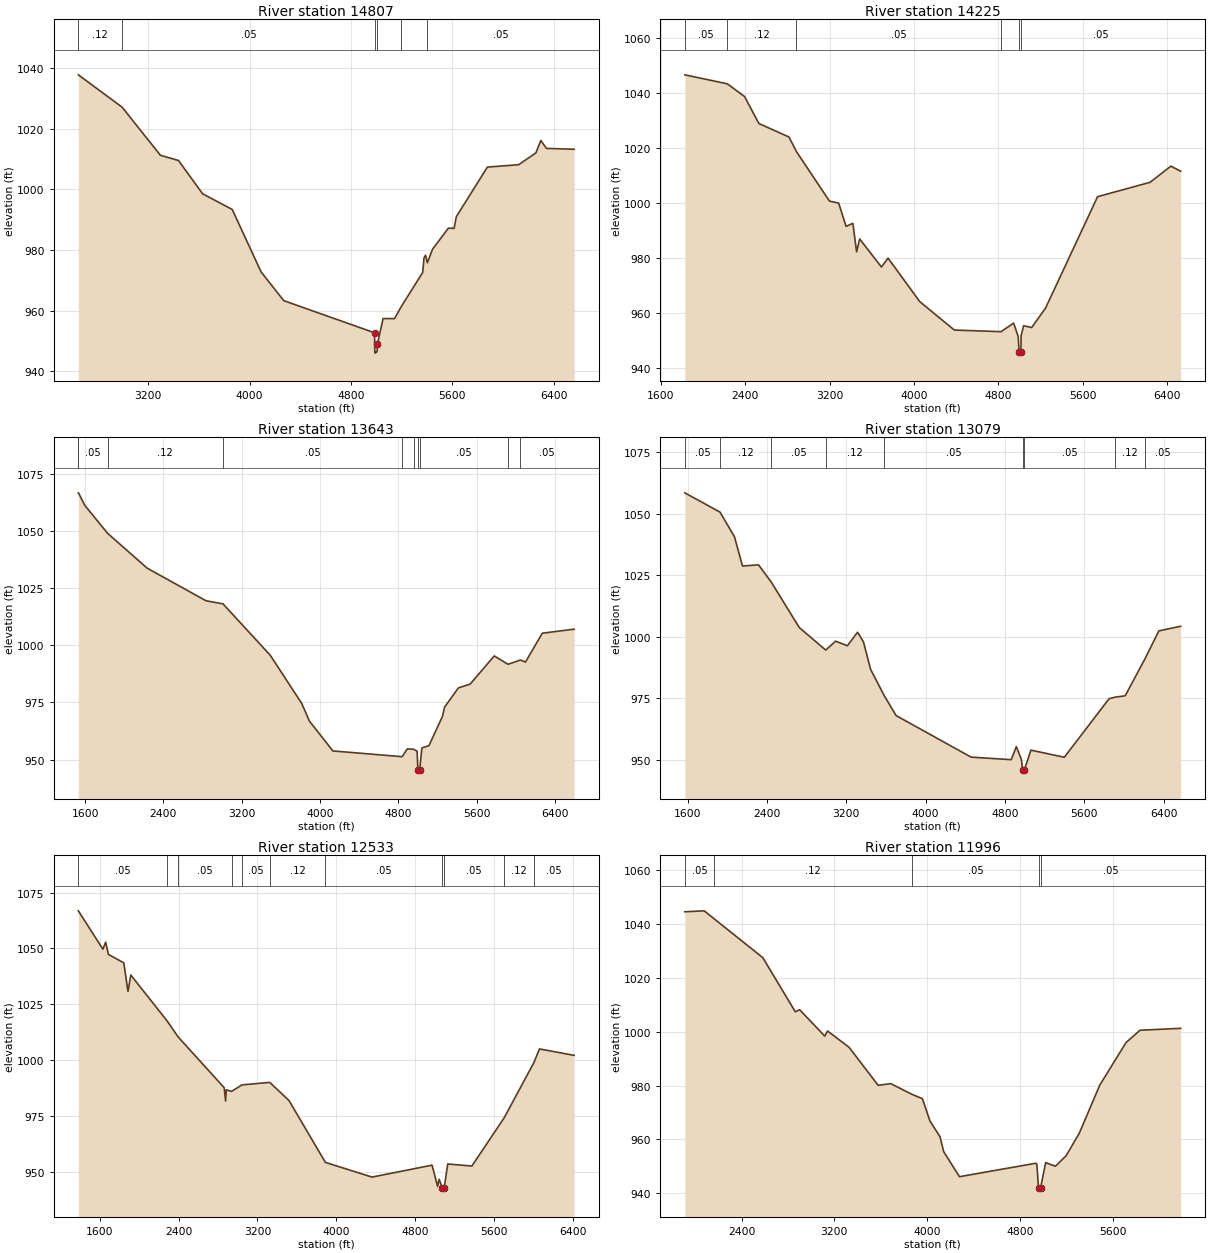
Type RM Length L Ch R = 1 ,14807   ,582,582,582
BEGIN DESCRIPTION:
MALLARD CREEK 21.0
END DESCRIPTION:
XS GIS Cut Line= 3
       2225322.8      7256878.13        2223229.        7255810.
       2221821.9      7255134.16
#Sta/Elev= 30
  2649.5  1037.8  2994.1 1027.15  3296.9 1011.26  3439.6 1009.52  3630.4  998.52
  3863.6  993.36  4091.5  972.73  4270.3  963.25  4986.1  952.65  4988.4  946.43
  4990.4  945.93  5006.1  946.43  5008.6  948.89  5053.8  957.34  5144.2  957.32
  5196.8  961.27  5366.1  972.57  5376.4  977.33  5388.3  978.26  5403.1  975.78
  5443.8  980.24  5568.6  987.17  5613.9  987.12    5631  990.93  5876.4 1007.34
  6123.1 1008.13    6259 1012.02    6298 1016.13  6342.3 1013.51    6561 1013.23
#Mann= 6 ,-1 , 0
  2649.5     .12       0  2994.1     .05       0  4988.4    .033       0
  5006.1     .05       0  5196.8     .12       0  5403.1     .05       0
Bank Sta=4986.1,5008.6
XS Rating Curve= 0 ,0
Exp/Cntr=0.3,0.1

Type RM Length L Ch R = 1 ,14225   ,582,582,582
BEGIN DESCRIPTION:
MALLARD CREEK 20.0
END DESCRIPTION:
XS GIS Cut Line= 3
      2225830.61      7257203.65        2223329.        7255260.
       2221807.2      7255081.26
#Sta/Elev= 30
  1827.3  1046.7  2230.7 1043.43  2394.2  1038.8  2529.1 1029.02  2815.1 1024.09
  2885.1 1018.84  3198.8 1000.79  3285.7 1000.09  3356.2  991.62  3420.5  992.72
  3455.8  982.37  3484.8  987.04  3690.9  976.85  3754.5  980.05  4054.9  964.25
  4382.5  953.92  4825.3  953.33  4944.6  956.44    4988  951.58  4996.5  946.03
  4998.5  945.53  5014.2  946.03  5015.4  951.88  5039.3  955.48  5116.1  954.85
    5247   961.9  5740.3  1002.4  6238.5 1007.64  6435.1  1013.5  6527.5 1011.66
#Mann= 6 ,-1 , 0
  1827.3     .05       0  2230.7     .12       0  2885.1     .05       0
  4825.3     .12       0  4996.5    .033       0  5014.2     .05       0
Bank Sta=4996.5,5014.2
XS Rating Curve= 0 ,0
Exp/Cntr=0.3,0.1

Type RM Length L Ch R = 1 ,13643   ,564,564,564
BEGIN DESCRIPTION:
MALLARD CREEK 19.0
END DESCRIPTION:
XS GIS Cut Line= 3
      2226351.47      7256578.67        2223429.        7254710.
      2221846.27      7254925.01
#Sta/Elev= 30
  1531.2 1066.68  1532.7 1066.68  1596.6 1061.24  1829.5 1049.01  2234.4 1033.74
  2835.6 1019.48    3010  1018.1  3492.8  995.62  3813.1  974.62  3892.9  966.82
  4132.2   953.8  4839.5  951.29  4892.6  954.69  4957.3  954.54  4992.4  953.72
  5001.3  945.47  5003.3  944.97    5019  945.47  5041.3  955.12  5113.8  956.13
  5252.3  968.97  5272.5   972.9  5413.8  981.35  5534.9  983.04  5781.1  995.35
  5921.5   991.7    6048  993.56    6100  992.67  6271.6 1005.28  6597.3 1007.06
#Mann= 10 ,-1 , 0
  1531.2     .12       0  1532.7     .05       0  1829.5     .12       0
    3010     .05       0  4839.5     .12       0  4957.3     .05       0
  5001.3    .033       0    5019     .05       0  5921.5     .12       0
    6048     .05       0
Bank Sta=5001.3,5019
XS Rating Curve= 0 ,0
Exp/Cntr=0.3,0.1

Type RM Length L Ch R = 1 ,13079   ,546,546,546
BEGIN DESCRIPTION:
MALLARD CREEK 18.0
END DESCRIPTION:
XS GIS Cut Line= 3
      2226361.33       7252479.6        2223379.        7254160.
      2221938.07       7254798.7
#Sta/Elev= 30
  1572.3  1058.4  1927.2 1050.58  2073.2 1040.58  2154.2 1028.72    2316 1029.18
  2445.9 1022.08  2726.3 1003.76    2993  994.61  3093.3  998.22  3211.8  996.35
  3314.4 1001.85  3373.6  997.94  3445.9  986.79  3583.7  976.08    3703  968.04
  4458.7  951.19  4863.3  950.14  4915.1  955.43  4965.8   950.3  4978.7     946
  4980.7   945.5  4996.4     946  5061.9  954.02  5398.7  951.13  5850.5  974.88
  5912.8  975.52  6012.7  976.06  6215.6  991.32  6351.8  1002.4  6571.6 1004.26
#Mann= 9 ,-1 , 0
  1572.3     .05       0  1927.2     .12       0  2445.9     .05       0
    2993     .12       0  3583.7     .05       0  4978.7    .033       0
  4996.4     .05       0  5912.8     .12       0  6215.6     .05       0
Bank Sta=4978.7,4996.4
XS Rating Curve= 0 ,0
Exp/Cntr=0.3,0.1

Type RM Length L Ch R = 1 ,12533   ,537,537,537
BEGIN DESCRIPTION:
MALLARD CREEK 17.0
END DESCRIPTION:
XS GIS Cut Line= 3
      2225632.12      7251450.98        2222979.        7253910.
      2221792.53      7254679.14
#Sta/Elev= 30
  1382.4 1066.82  1631.8 1049.66  1659.6  1052.8    1688 1047.31  1843.9 1043.52
  1886.4 1030.75  1914.7 1038.09  2283.1 1017.55  2396.6 1010.31  2862.7  987.64
  2876.9  981.67  2884.2  986.74  2937.2  985.98  3041.6   988.9  3324.7  990.03
  3520.9  981.87  3889.4  954.22  4362.9  947.64  4971.8  952.98  5028.5  943.44
  5043.7  946.69    5077  942.75    5079  942.25  5094.7  942.75  5130.9   953.5
    5376  952.59  5703.2  974.14  6004.8  998.85  6061.7    1005  6413.8 1002.13
#Mann= 11 ,-1 , 0
  1382.4     .05       0  2283.1     .12       0  2396.6     .05       0
  2937.2     .12       0  3041.6     .05       0  3324.7     .12       0
  3889.4     .05       0    5077    .033       0  5094.7     .05       0
  5703.2     .12       0  6004.8     .05       0
Bank Sta=5077,5094.7
XS Rating Curve= 0 ,0
Exp/Cntr=0.3,0.1

Type RM Length L Ch R = 1 ,11996   ,560,560,560
BEGIN DESCRIPTION:
MALLARD CREEK 16.0
END DESCRIPTION:
XS GIS Cut Line= 3
       2223483.7       7250656.7        2222579.        7253610.
      2221739.32      7254445.35
#Sta/Elev= 30
  1911.2 1044.61  2078.8 1044.96    2162 1042.07    2584 1027.53  2863.6 1007.43
  2901.6 1008.18  3117.4  998.38  3141.4 1000.28  3326.6  994.24  3577.6  980.09
  3686.5   980.7  3872.8  976.66    3959  975.13  4024.5  966.77    4111  960.96
  4142.4  955.43  4278.3  946.11  4937.2  951.12  4945.6  950.67  4959.7  941.99
  4961.7  941.49  4977.5  941.99  5021.2  951.32    5106  950.02  5197.9  953.92
  5311.1  962.28  5487.9  980.19  5714.2  995.99  5834.3 1000.56  6184.4 1001.28
#Mann= 5 ,-1 , 0
  1911.2     .05       0    2162     .12       0  3872.8     .05       0
  4959.7    .035       0  4977.5     .05       0
Bank Sta=4959.7,4977.5
XS Rating Curve= 0 ,0
Exp/Cntr=0.3,0.1

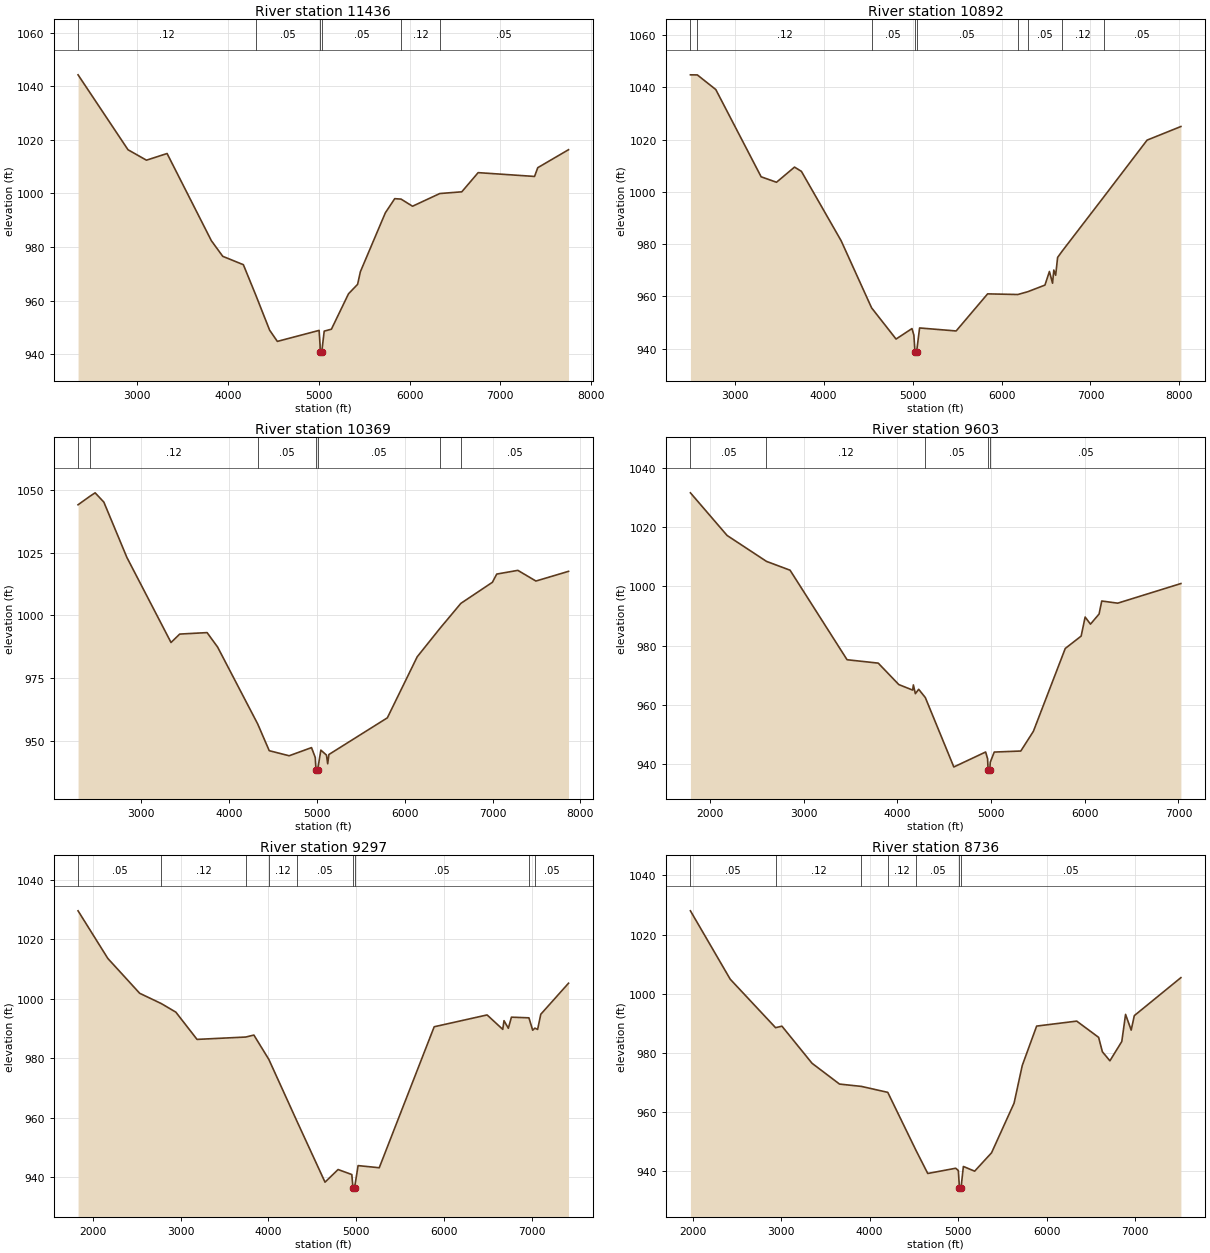
Type RM Length L Ch R = 1 ,11436   ,544,544,544
BEGIN DESCRIPTION:
MALLARD CREEK 15.0
END DESCRIPTION:
XS GIS Cut Line= 4
       2223366.5      7250812.96        2222229.        7253210.
      2221794.25      7253900.93      2221309.22      7255773.88
#Sta/Elev= 30
    2347 1044.28  2897.2 1016.31  3100.6 1012.41  3327.9  1014.9  3815.9  982.35
  3941.1  976.52  4168.4  973.39  4304.5   962.1  4457.9  948.94  4543.1  944.75
  5003.2  948.86  5013.8  943.25  5014.3  940.87  5016.3  940.37  5032.1  940.87
  5059.3  948.59  5138.6   949.3    5327  962.52  5427.1  966.05  5457.7  970.76
  5732.8  992.75  5836.3  998.04  5905.7  997.88  6032.5  995.22  6333.1  999.96
  6575.2  1000.6  6755.6 1007.76  7376.9 1006.34  7412.4 1009.61  7751.3 1016.32
#Mann= 6 ,-1 , 0
    2347     .12       0  4304.5     .05       0  5014.3    .033       0
  5032.1     .05       0  5905.7     .12       0  6333.1     .05       0
Bank Sta=5014.3,5032.1
XS Rating Curve= 0 ,0
Exp/Cntr=0.3,0.1

Type RM Length L Ch R = 1 ,10892   ,523,523,523
BEGIN DESCRIPTION:
MALLARD CREEK 14.0
END DESCRIPTION:
XS GIS Cut Line= 3
      2223405.58      7250708.77        2221979.        7252760.
       2219707.8      7254745.12
#Sta/Elev= 30
  2501.7 1044.76  2579.7 1044.72  2787.1 1039.12  3296.8 1005.74  3469.7 1003.65
  3672.2 1009.45  3749.8 1007.81  4196.3  981.27  4538.9  955.58  4813.9  943.65
  4992.8  947.65    5014  945.19  5026.7  938.76  5028.7  938.26  5044.9  938.76
  5078.5  947.89  5489.5  946.74  5843.6  960.94  6182.9  960.69  6295.9  961.77
  6488.1   964.3  6538.4   969.5  6573.5  965.02  6587.8  970.05  6608.6  968.06
  6630.5  974.88  6681.6  977.28  7148.2  997.97  7636.6 1019.77  8016.7 1024.98
#Mann= 9 ,-1 , 0
  2501.7     .05       0  2579.7     .12       0  4538.9     .05       0
  5026.7    .033       0  5044.9     .05       0  6182.9     .12       0
  6295.9     .05       0  6681.6     .12       0  7148.2     .05       0
Bank Sta=5026.7,5044.9
XS Rating Curve= 0 ,0
Exp/Cntr=0.3,0.1

Type RM Length L Ch R = 1 ,10369   ,766,766,766
BEGIN DESCRIPTION:
MALLARD CREEK 13.0
END DESCRIPTION:
XS GIS Cut Line= 3
      2223392.58      7250578.54        2221529.        7252560.
      2219473.65      7254549.57
#Sta/Elev= 30
  2284.3 1044.15  2420.2 1047.56  2478.7 1048.91  2577.8  1045.2  2839.6 1023.16
  3342.1   989.2  3440.8  992.56  3752.4  993.15  3872.5  987.36  4328.7  956.68
  4459.6  946.04  4686.2  944.02  4940.7  947.27  4983.2  943.34  4991.9  938.39
  4993.9  937.89  5010.1  938.39  5046.8  946.26  5110.5   944.3  5124.7  940.82
  5138.8  944.53  5803.5  959.15  6143.1  983.49    6404  994.92    6640 1004.81
  6998.7 1013.22  7048.3  1016.5  7288.6 1017.98  7493.9 1013.72    7865 1017.59
#Mann= 7 ,-1 , 0
  2284.3     .05       0  2420.2     .12       0  4328.7     .05       0
  4991.9    .033       0  5010.1     .05       0    6404     .12       0
    6640     .05       0
Bank Sta=4991.9,5010.1
XS Rating Curve= 0 ,0
Exp/Cntr=0.3,0.1

Type RM Length L Ch R = 1 ,9603    ,306,306,306
BEGIN DESCRIPTION:
MALLARD CREEK 12.0
END DESCRIPTION:
XS GIS Cut Line= 3
      2223327.46      7249875.43      2221022.76      7252062.95
      2219499.35      7253443.13
#Sta/Elev= 30
  1793.2 1031.53  2184.4 1017.15  2604.6 1008.41  2856.3 1005.43  3464.6  975.23
  3797.1  974.09  4016.4  966.86  4164.8  964.99  4172.1  966.74  4193.2  963.78
  4228.7  965.26  4299.4  962.48  4603.7  939.06  4943.1  944.11  4964.1  941.82
    4969  938.16    4971  937.66  4987.4  938.16  4992.4  940.67    5035  944.09
  5318.2  944.44  5452.6  951.09  5792.6  979.03  5962.2  983.21  6004.8  989.64
  6061.6  987.23  6153.5  990.65  6181.9  995.04  6352.2  994.31  7026.4 1000.93
#Mann= 5 ,-1 , 0
  1793.2     .05       0  2604.6     .12       0  4299.4     .05       0
    4969    .035       0  4987.4     .05       0
Bank Sta=4969,4987.4
XS Rating Curve= 0 ,0
Exp/Cntr=0.3,0.1

Type RM Length L Ch R = 1 ,9297    ,561,561,561
BEGIN DESCRIPTION:
MALLARD CREEK 11.0
END DESCRIPTION:
XS GIS Cut Line= 3
      2223275.37       7249849.4        2220829.        7251860.
      2218979.75      7253416.05
#Sta/Elev= 30
  1832.3 1029.53  2171.2 1013.54  2533.6 1001.85  2780.9  998.37  2945.4  995.51
  3186.7  986.36  3741.4  987.15  3833.9  987.81    4004  979.64  4326.8  958.71
  4643.7  938.42  4792.3  942.66  4948.7  940.98  4961.7  936.58  4963.7  936.08
  4980.1  936.58  5020.3  943.98    5261  943.26  5886.5   990.6  6488.8  994.57
  6666.9  989.73  6681.2  992.65  6730.6  990.09  6765.7  993.82  6965.1   993.6
  7007.6  989.43  7032.7  990.14  7063.8   989.7    7100   994.8  7415.7 1005.22
#Mann= 9 ,-1 , 0
  1832.3     .05       0  2780.9     .12       0  3741.4     .05       0
    4004     .12       0  4326.8     .05       0  4961.7    .035       0
  4980.1     .05       0  6965.1     .12       0  7032.7     .05       0
Bank Sta=4961.7,4980.1
XS Rating Curve= 0 ,0
Exp/Cntr=0.3,0.1

Type RM Length L Ch R = 1 ,8736    ,540,540,540
BEGIN DESCRIPTION:
MALLARD CREEK 10.0
END DESCRIPTION:
XS GIS Cut Line= 3
      2223249.33      7249797.32        2220729.        7251460.
      2218900.75      7253195.39
#Sta/Elev= 30
  1975.4 1028.01  2425.1 1004.89  2937.3  988.51  3009.2  989.02  3349.4  976.47
  3659.5  969.45  3907.4  968.66  4204.5  966.65  4522.4   947.1  4656.1  939.23
  4972.2     941  5001.8  940.21  5013.7  934.44  5015.7  933.94  5032.1  934.44
  5058.5   941.6  5185.9  940.01  5376.8  946.22  5631.3  963.01  5723.5  975.72
  5886.1  989.05  6338.7  990.73  6586.3  985.24  6628.7  980.37  6713.7  977.32
    6848  983.84  6890.5     993    6954   987.7  6989.5  992.59  7515.5 1005.42
#Mann= 7 ,-1 , 0
  1975.4     .05       0  2937.3     .12       0  3907.4     .05       0
  4204.5     .12       0  4522.4     .05       0  5013.7    .033       0
  5032.1     .05       0
Bank Sta=5013.7,5032.1
XS Rating Curve= 0 ,0
Exp/Cntr=0.3,0.1

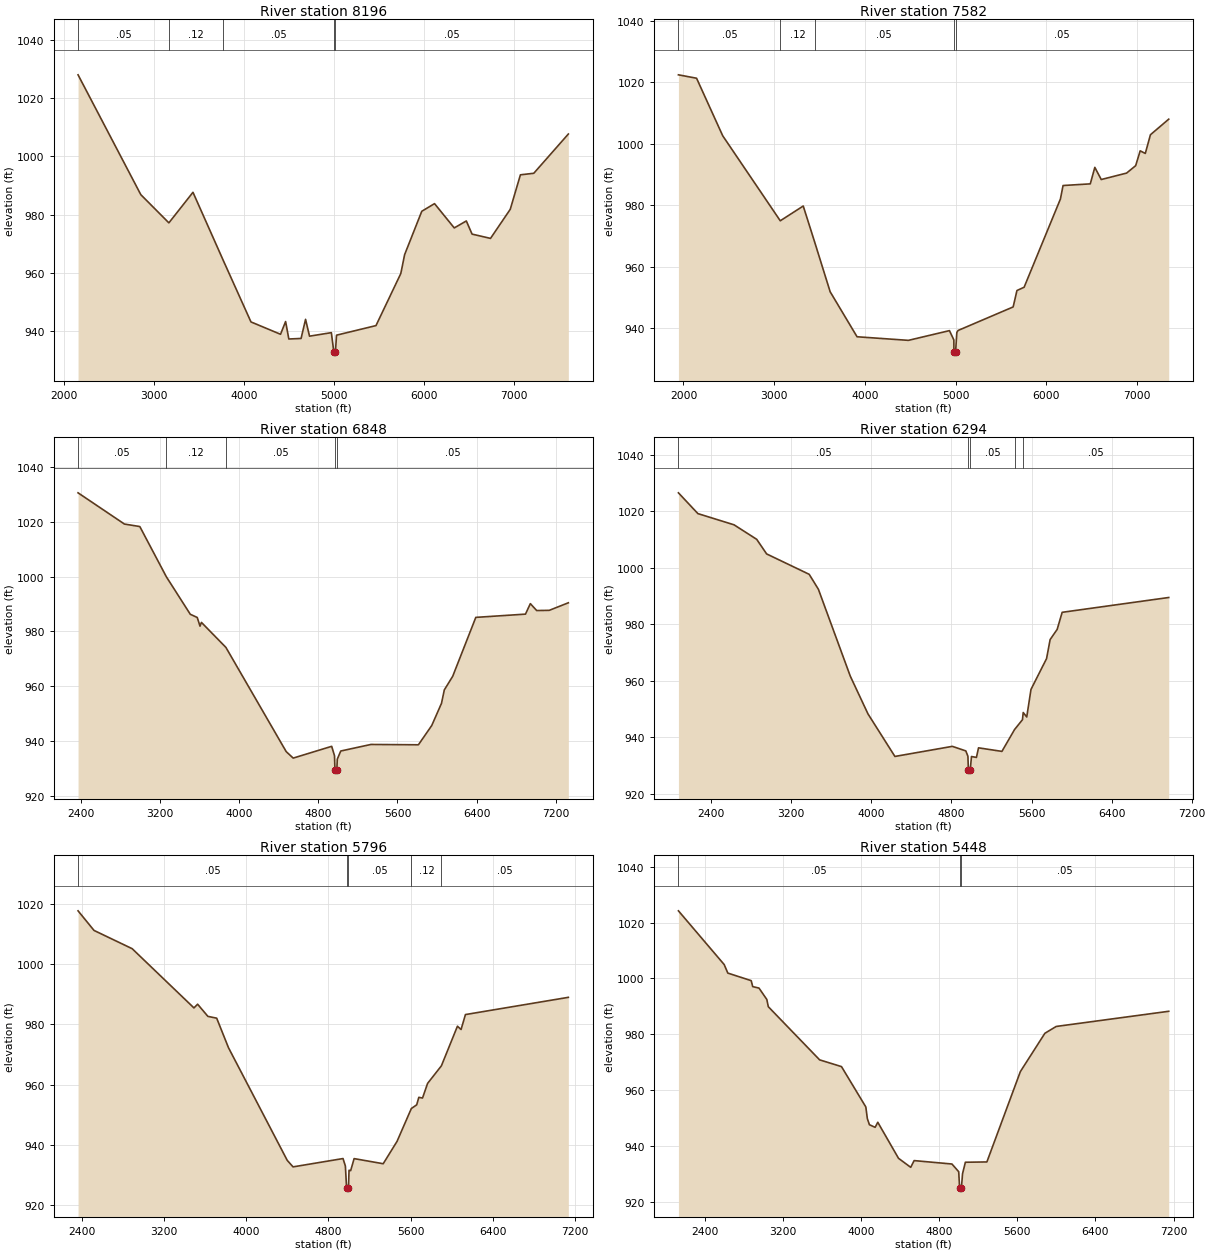
Type RM Length L Ch R = 1 ,8196    ,614,614,614
BEGIN DESCRIPTION:
MALLARD CREEK 9.0
END DESCRIPTION:
XS GIS Cut Line= 3
      2222923.77      7249341.61        2220629.        7251010.
      2218809.23      7252883.25
#Sta/Elev= 30
  2158.7 1027.99  2856.2  986.86  3168.1  977.18  3435.9  987.67  3770.6  964.42
  4080.4  943.18  4408.9  938.94  4465.3  943.31  4501.3  937.32  4637.3   937.5
  4687.1  944.06  4731.2  938.29  4973.8   939.5  5000.7  932.97  5002.7  932.47
  5019.1  932.97  5031.2  938.63  5469.8  941.92  5745.5  959.78    5788  966.27
  5978.8  981.16  6120.3  983.78  6339.5  975.44  6473.8  977.83  6537.5  973.32
  6742.6  971.85  6961.7  981.82  7074.9  993.67  7223.5   994.2  7607.5 1007.67
#Mann= 5 ,-1 , 0
  2158.7     .05       0  3168.1     .12       0  3770.6     .05       0
  5000.7    .033       0  5019.1     .05       0
Bank Sta=5000.7,5019.1
XS Rating Curve= 0 ,0
Exp/Cntr=0.3,0.1

Type RM Length L Ch R = 1 ,7582    ,734,734,734
BEGIN DESCRIPTION:
MALLARD CREEK 8.0
END DESCRIPTION:
XS GIS Cut Line= 3
      2222910.78      7249211.38      2220228.49      7250630.65
      2218327.48       7252049.9
#Sta/Elev= 30
  1944.3 1022.46  2144.4 1021.35  2432.8  1002.6  3067.4  974.91  3320.7  979.72
  3447.1  967.95  3617.4   951.8  3914.2  937.13  4480.6  935.96  4933.1  939.13
  4981.7  936.11  4982.3   932.3  4984.3   931.8  5000.9   932.3  5014.6  938.53
  5028.2  939.18  5635.8  946.85  5677.5  952.19  5756.7  953.27    6157  982.01
  6186.1   986.4  6486.3  986.94  6536.4  992.31  6607.2  988.35  6886.6  990.45
  6986.7  992.86  7036.7   997.7    7093  996.85  7149.7 1002.94  7351.3 1008.01
#Mann= 5 ,-1 , 0
  1944.3     .05       0  3067.4     .12       0  3447.1     .05       0
  4982.3     .04       0  5000.9     .05       0
Bank Sta=4982.3,5000.9
XS Rating Curve= 0 ,0
Exp/Cntr=0.3,0.1

Type RM Length L Ch R = 1 ,6848    ,554,554,554
BEGIN DESCRIPTION:
MALLARD CREEK 7.0
END DESCRIPTION:
XS GIS Cut Line= 3
      2221899.49      7248017.81      2220128.66      7249970.93
      2218427.25      7251550.81
#Sta/Elev= 30
  2370.1 1030.65  2839.3 1019.24  2994.7 1018.33  3262.9  999.99    3505  986.29
  3575.2  985.12  3603.6  981.95  3617.8  983.32  3865.2  974.19  4474.8  936.13
  4545.7  933.75    4935  938.05  4963.4  934.64  4968.3  929.49  4970.3  928.99
  4986.9  929.49  4991.7  933.36  5026.8  936.34  5331.2  938.73    5812  938.61
  5946.9  945.65  6045.6  953.76  6073.9  958.65    6159  963.64  6392.5  985.15
  6894.8  986.34  6944.1  990.17  7008.2  987.65  7135.2  987.72  7328.3  990.48
#Mann= 5 ,-1 , 0
  2370.1     .05       0  3262.9     .12       0  3865.2     .05       0
  4968.3    .033       0  4986.9     .05       0
Bank Sta=4968.3,4986.9
XS Rating Curve= 0 ,0
Exp/Cntr=0.3,0.1

Type RM Length L Ch R = 1 ,6294    ,498,498,498
BEGIN DESCRIPTION:
MALLARD CREEK 6.0
END DESCRIPTION:
XS GIS Cut Line= 3
      2221786.67      7247983.07      2219625.19      7249944.89
      2218166.82      7251281.73
#Sta/Elev= 30
  2072.8 1026.51  2267.3 1019.16  2628.1  1015.2  2854.5 1010.07  2953.9  1004.9
  3378.9  997.69  3470.9   992.4  3789.1   961.7  3966.2  948.32  4235.2  933.27
  4808.9  936.84  4943.4  935.23  4964.3  933.37  4969.2  928.58  4971.2  928.08
  4987.8  928.58  5000.1  933.25  5049.4  932.92  5070.4  936.32  5304.1  935.06
  5430.6   942.8  5509.4  946.27  5516.7  948.81    5552  947.23  5594.5  956.99
  5749.9  967.87  5785.7  974.61    5856  978.22  5905.9  984.25  6970.2  989.49
#Mann= 5 ,-1 , 0
  2072.8     .05       0  4969.2     .04       0  4987.8     .05       0
  5430.6     .12       0  5516.7     .05       0
Bank Sta=4969.2,4987.8
XS Rating Curve= 0 ,0
Exp/Cntr=0.3,0.1

Type RM Length L Ch R = 1 ,5796    ,348,348,348
BEGIN DESCRIPTION:
MALLARD CREEK 5.0
END DESCRIPTION:
XS GIS Cut Line= 3
      2221647.74      7247991.78      2219521.03      7249571.63
      2218088.77      7251134.09
#Sta/Elev= 30
  2365.2 1017.81  2520.4 1011.29  2891.8 1005.21  3492.6  985.51    3528  986.75
  3628.2   982.7  3713.7   982.1  3828.5  972.27    4400  934.79  4456.5  932.63
  4942.4   935.4  4965.4  932.91    4977  925.73    4979  925.23  4995.6  925.73
  5000.9   931.5  5016.8  931.38  5050.4  935.38  5333.4  933.68  5467.8  941.11
  5607.1  952.05    5659  953.27  5679.9  955.77  5715.7  955.53    5765   960.4
  5899.3  966.25  6055.5  979.43  6090.6  978.32  6133.2   983.3  7134.1  989.03
#Mann= 5 ,-1 , 0
  2365.2     .05       0    4977    .033       0  4995.6     .05       0
  5607.1     .12       0  5899.3     .05       0
Bank Sta=4977,4995.6
XS Rating Curve= 0 ,0
Exp/Cntr=0.3,0.1

Type RM Length L Ch R = 1 ,5448    ,532,532,532
BEGIN DESCRIPTION:
MALLARD CREEK 4.0
END DESCRIPTION:
XS GIS Cut Line= 4
      2221795.37      7247844.17        2219329.        7249310.
      2218890.03      7249653.18      2218106.73      7251046.18
#Sta/Elev= 30
  2126.1 1024.26  2595.2 1004.98  2632.3 1001.93  2871.8  999.22  2887.4  997.08
  2951.7  996.55  3031.6  992.49  3047.2  989.87  3573.1  970.81  3797.1  968.39
  4046.5  953.92  4062.1  949.72  4083.5  947.54    4142  946.62  4169.2  948.42
  4381.5   935.5  4506.6  932.27  4541.5  934.68  4928.9  933.46  4998.4  930.69
  5007.6  924.95  5009.6  924.45  5026.2  924.95  5037.7  929.98  5066.6  934.09
  5287.1   934.2  5630.3  966.61  5881.4  980.34  5997.5  982.79  7150.5  988.23
#Mann= 3 ,-1 , 0
  2126.1     .05       0  5007.6    .033       0  5026.2     .05       0
Bank Sta=5007.6,5026.2
XS Rating Curve= 0 ,0
Exp/Cntr=0.3,0.1