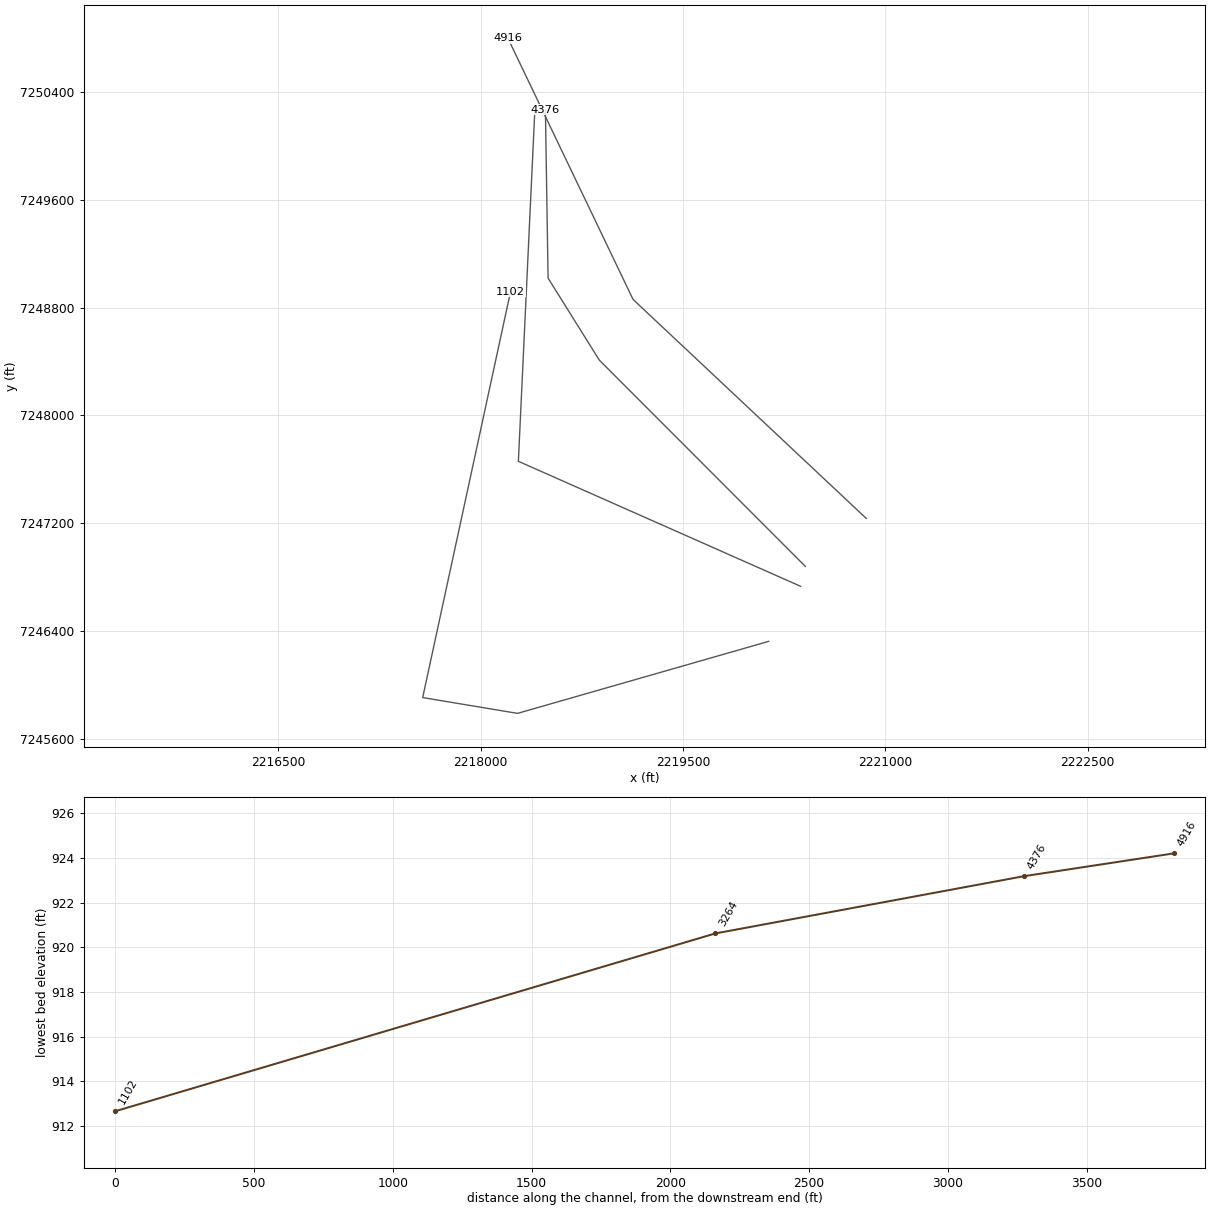
HEC-RAS study MALLARD CREEK.prj: MALLARD CREEK Base Level Engineering

--- MALLARD CREEK.g01 (geometry) --- (continued)

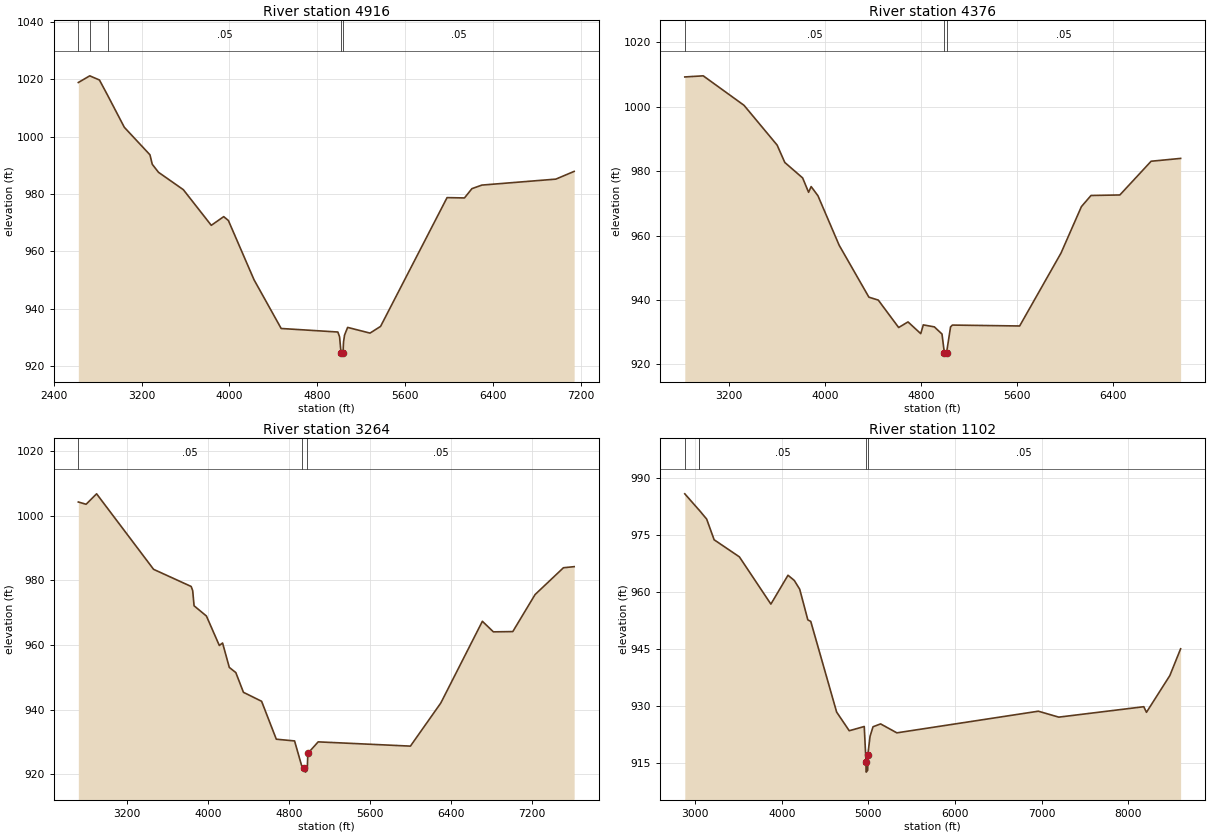
Type RM Length L Ch R = 1 ,4916    ,540,540,540
BEGIN DESCRIPTION:
MALLARD CREEK 3.0
END DESCRIPTION:
XS GIS Cut Line= 3
      2220857.84      7247236.55        2219129.        7248860.
      2218201.71      7250795.32
#Sta/Elev= 30
  2622.8 1018.91  2726.9 1021.24  2815.3 1019.78  2891.2 1014.35  3041.9 1003.29
  3275.4   993.7  3296.4   990.4    3353  987.61  3579.6  981.54  3834.1  969.11
  3947.4  972.14  3989.9   970.8  4223.4  950.15    4471  933.14  4987.3  931.91
    5003  930.25  5016.3   924.7  5018.3   924.2  5034.9   924.7  5038.8  928.35
  5048.3  930.82  5076.5  933.52  5280.4  931.53  5376.6  933.87  5982.4  978.77
    6141  978.66    6209   981.9  6299.6  983.14  6973.4  985.22  7140.4  987.92
#Mann= 5 ,-1 , 0
  2622.8     .05       0  2726.9     .12       0  2891.2     .05       0
  5016.3     .04       0  5034.9     .05       0
Bank Sta=5016.3,5034.9
XS Rating Curve= 0 ,0
Exp/Cntr=0.3,0.1

Type RM Length L Ch R = 1 ,4376    ,1112,1112,1112
BEGIN DESCRIPTION:
MALLARD CREEK 2.0
END DESCRIPTION:
XS GIS Cut Line= 4
      2220406.47      7246880.63        2218879.        7248410.
      2218499.23      7249017.64      2218479.37      7250265.51
#Sta/Elev= 30
  2832.6 1009.24  2985.9 1009.59  3325.3 1000.44  3601.1  988.08  3664.8  982.69
  3813.2  977.89  3862.7  973.43    3884   975.2  3940.5  972.37  4117.3  956.98
  4364.8  940.86  4442.6  939.96  4612.3  931.44  4690.1  933.18  4796.1  929.54
  4817.3  932.26  4909.3  931.64  4972.9  929.42  4992.3  923.68  4994.3  923.18
  5011.2  923.68  5044.2  931.64  5059.6   932.2  5619.1  931.92  5963.1  954.54
  6133.1  968.98  6213.1  972.44  6453.1   972.6  6713.2  983.07  6958.7  983.95
#Mann= 3 ,-1 , 0
  2832.6     .05       0  4992.3     .04       0  5011.2     .05       0
Bank Sta=4992.3,5011.2
XS Rating Curve= 0 ,0
Exp/Cntr=0.3,0.1

Type RM Length L Ch R = 1 ,3264    ,2162,2162,2162
BEGIN DESCRIPTION:
MALLARD CREEK 1.0
END DESCRIPTION:
XS GIS Cut Line= 3
      2220371.75      7246733.07        2218279.        7247660.
      2218401.21      7250265.49
#Sta/Elev= 30
  2717.1 1004.25  2793.6 1003.55  2897.6 1006.78  3460.5   983.4  3831.6   978.1
  3846.6  976.82  3860.4  972.11  3982.3  968.95  4109.6  959.83  4141.9   960.6
  4208.2  953.04  4272.6  951.44  4347.9  945.33  4527.3  942.55  4672.5  930.81
  4852.8  930.28  4921.7  922.74    4945  921.93  4960.8  920.62  4977.7  921.12
  4984.1  926.43    5086  929.99    5997  928.67  6297.4  942.03  6707.8  967.32
  6816.5  964.05  7008.1  964.13  7228.4   975.6  7508.7   983.9  7614.3  984.23
#Mann= 3 ,-1 , 0
  2717.1     .05       0  4921.7     .04       0  4977.7     .05       0
Bank Sta=4945,4984.1
XS Rating Curve= 0 ,0
Exp/Cntr=0.3,0.1

Type RM Length L Ch R = 1 ,1102    ,0,0,0
BEGIN DESCRIPTION:
MALLARD CREEK 0.5
END DESCRIPTION:
XS GIS Cut Line= 4
      2220134.75      7246325.28      2218272.82      7245791.43
      2217569.69      7245908.62      2218220.58      7248915.71
#Sta/Elev= 30
  2879.3  985.85  3037.9  981.74  3039.4  981.73    3132   979.2  3218.2  973.77
  3509.5  969.28  3873.6  956.85  4071.2  964.44    4144  963.07  4206.5  960.76
  4300.3  952.71  4334.1   952.3    4633  928.46  4778.6  923.55  4951.9  924.67
  4972.2   915.3  4972.8  913.17  4974.8  912.67  4991.8  913.17  4992.5  917.07
  5019.1  922.11  5053.3   924.6  5140.8  925.35  5328.3     923  6962.7  928.69
  7198.2  927.13  8180.5  929.87  8211.2   928.4  8481.2  938.06  8605.8   945.1
#Mann= 5 ,-1 , 0
  2879.3     .05       0  3037.9     .12       0  3039.4     .05       0
  4972.8     .04       0  4991.8     .05       0
Bank Sta=4972.2,4992.5
XS Rating Curve= 0 ,0
Exp/Cntr=0.3,0.1

Chan Stop Cuts=-1
Use User Specified Reach Order=0
Composite Channel Slope=5