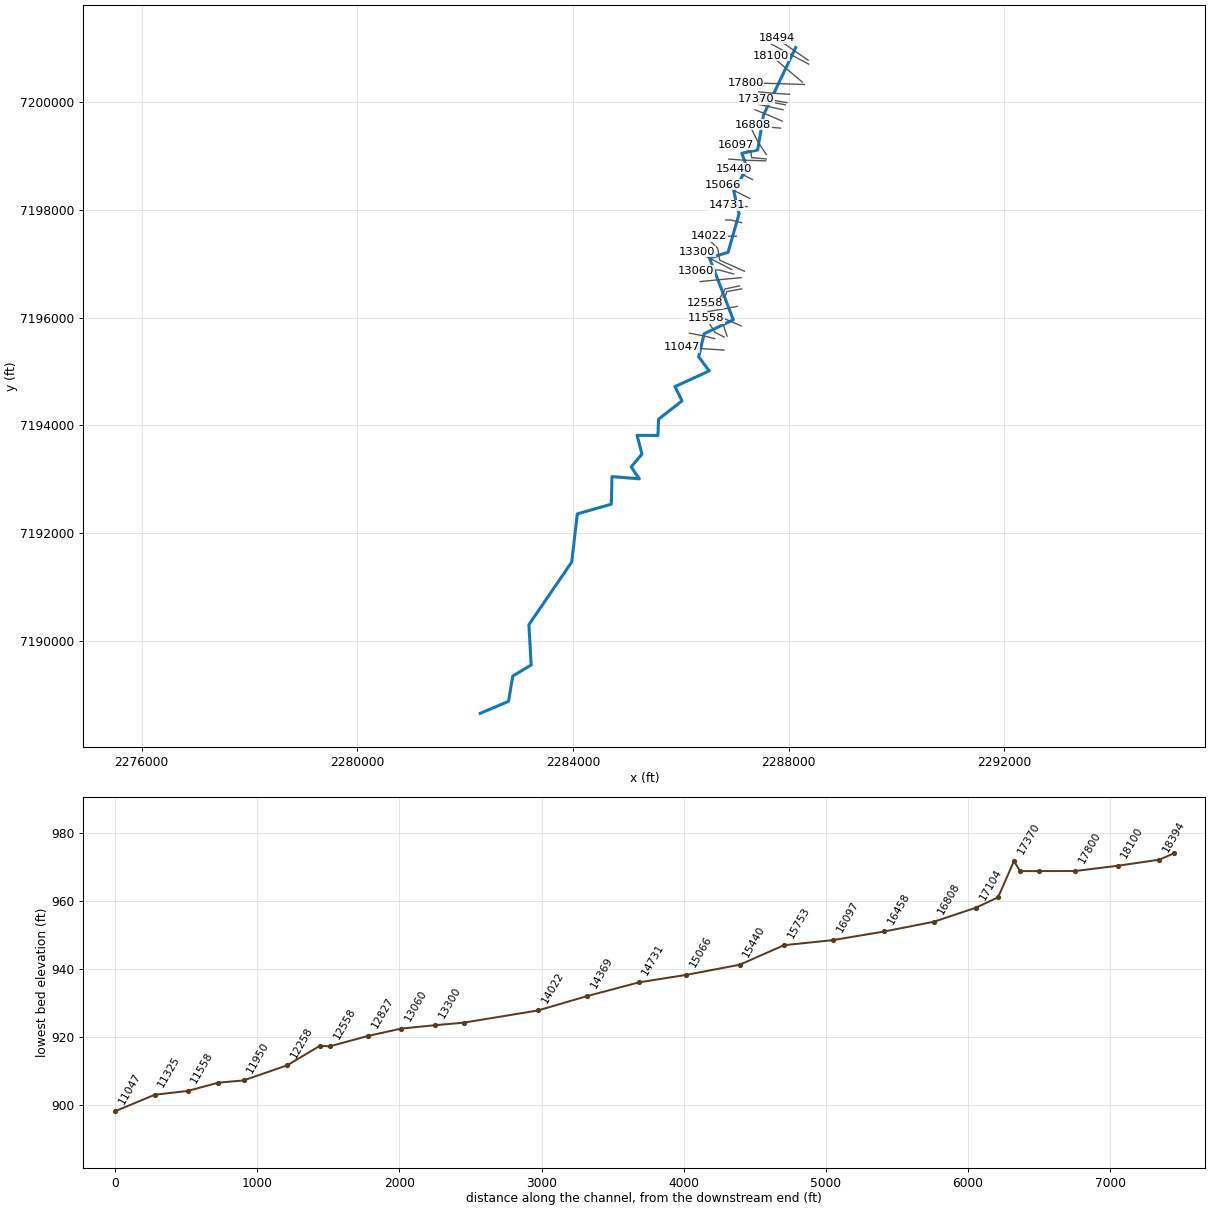
--- Miller Creek.prj (project) ---

Proj Title=Miller Creek Base Level Engineering
Current Plan=p01
Default Exp/Contr=0.3,0.1
English Units
Geom File=g01
Flow File=f01
Plan File=p01
Y Axis Title=Elevation
X Axis Title(PF)=Main Channel Distance
X Axis Title(XS)=Station
BEGIN DESCRIPTION:
Miller Creek
END DESCRIPTION:
DSS File=dss
DSS Export Rating Curves= 0
DSS Export Rating Curve Sorted= 0
DSS Export Volume Flow Curves= 0
DXF OffsetX= 0
DXF OffsetY= 0
DXF ScaleX= 1
DXF ScaleY= 10

--- Miller Creek.p01 (plan) ---

Plan Title=Multiple Run
Program Version=4.10
Short Identifier=Multiple Run
Geom File=g01
Flow File=f01
Subcritical Flow
K Sum by GR= 0
Std Step Tol= 0.01
Critical Tol= 0.01
Num of Std Step Trials= 20
Max Error Tol= 0.3
Flow Tol Ratio= 0.001
Split Flow NTrial= 30
Split Flow Tol= 0.02
Split Flow Ratio= 0.02
Log Output Level= 0
Friction Slope Method= 1
Unsteady Friction Slope Method= 2
Unsteady Bridges Friction Slope Method= 1
Parabolic Critical Depth
Global Vel Dist= 1 , 1 , 1
Global Log Level= 0
CheckData=True
Encroach Param=-1 ,0,0, 0
BEGIN DESCRIPTION:
Multiple Run
END DESCRIPTION:
Computation Interval=1HOUR
Output Interval=1HOUR
Run HTab= 0
Run UNet= 0
Run PostProcess= 0
Run WQNet= 0
UNET Theta= 1
UNET Theta Warmup= 1
UNET ZTol= 0.02
UNET ZSATol= 0.05
UNET MxIter= 20
UNET MaxInSteps= 0
UNET DtIC= 0
UNET DtMin= 0
UNET MaxCRTS= 20
UNET WFStab= 2
UNET SFStab= 1
UNET WFX= 1
UNET SFX= 1
UNET DSS MLevel= 4
UNET DZMax Abort= 100
UNET Convert EG Bridges= 0
UNET Use Existing IB Tables=-1
UNET Froude Reduction=False
UNET Froude Limit= 1
UNET Froude Power= 10
UNET Time Slicing=0,0, 5
UNET Junction Losses=0
Instantaneous Interval=1HOUR
DSS File=dss
Write IC File= 0
Write IC File at Sim End=0
Echo Input=False
Echo Parameters=False
Echo Output=False
Write Detailed= 0
WQ AD Non Conservative
WQ ULTIMATE=-1
WQ Max Comp Step=1HOUR
WQ Output Interval=15MIN
WQ Output Selected Increments= 0
WQ Output face flow=0
WQ Output face velocity=0
WQ Output face area=0
WQ Output face dispersion=0
WQ Output cell volume=0
WQ Output cell surface area=0
WQ Output cell continuity=0
WQ Output cumulative cell continuity=0
WQ Output face conc=0
WQ Output face dconc_dx=0
WQ Output face courant=0
WQ Output face peclet=0
WQ Output face adv mass=0
WQ Output face disp mass=0
WQ Output cell mass=0
WQ Output cell source sink temp=0
WQ Output cell source sink nsm=0
WQ Output MaxMinRange=-1
WQ Daily Max Min Mean=-1
WQ Daily Range=0
WQ Daily Time=0
WQ Create Restart=0
WQ Fixed Restart=0
WQ System Summary=0
WQ Use Fixed Temperature=0
Sorting and Armoring Iterations= 10
XS Update Threshold= 0.02
Hydraulics Update Threshold= 0.02
Energy Slope Method= 1
Volume Change Method= 0
XS Weighting Method= 0
Number of US Weighted Cross Sections= 1
Number of DS Weighted Cross Sections= 1
Upstream XS Weight=0.25
Main XS Weight=0.5
Downstream XS Weight=0.25
Number of DS XS's Weighted with US Boundary= 1
Upstream Boundary Weight= 1
Weight of XSs Associated with US Boundary= 0
Number of US XS's Weighted with DS Boundary= 1
Downstream Boundary Weight= 0.5
Weight of XSs Associated with DS Boundary= 0.5
Sediment Output Level= 4
Mass or Volume Output= 0
Output Increment Type= 1
Profile and TS Output Increment= 10
XS Output Flag= 0
XS Output Increment= 10
Disregard all LS=0
Disregard all Conn=0
Disregard all Breaches=0
Disregard all Pumps=0

--- Miller Creek.f01 (steady flow) ---

Flow Title=Multiple
Program Version=4.10
Number of Profiles= 7
Profile Names=10-year,25-year,50-year,1pct_min,100-year,1pct_plu,500-year
River Rch & RM=Miller Creek,Reach-1         ,18494
     628     865    1061     647    1291    2576    1914
River Rch & RM=Miller Creek,Reach-1         ,13498
     933    1311    1631    1007    2009    4009    3056
River Rch & RM=Miller Creek,Reach-1         ,6842
    1516    2184    2763    1731    3453    6891    5412
River Rch & RM=Miller Creek,Reach-1         ,4860
    1703    2467    3130    1967    3925    7831    6188
River Rch & RM=Miller Creek,Reach-1         ,4126
    1785    2590    3291    2071    4132    8244    6531
Boundary for River Rch & Prof#=Miller Creek,Reach-1         , 1
Up Type= 0
Dn Type= 3
Dn Slope=0.005
Boundary for River Rch & Prof#=Miller Creek,Reach-1         , 2
Up Type= 0
Dn Type= 3
Dn Slope=0.005
Boundary for River Rch & Prof#=Miller Creek,Reach-1         , 3
Up Type= 0
Dn Type= 3
Dn Slope=0.005
Boundary for River Rch & Prof#=Miller Creek,Reach-1         , 4
Up Type= 0
Dn Type= 3
Dn Slope=0.005
Boundary for River Rch & Prof#=Miller Creek,Reach-1         , 5
Up Type= 0
Dn Type= 3
Dn Slope=0.005
Boundary for River Rch & Prof#=Miller Creek,Reach-1         , 6
Up Type= 0
Dn Type= 3
Dn Slope=0.005
Boundary for River Rch & Prof#=Miller Creek,Reach-1         , 7
Up Type= 0
Dn Type= 3
Dn Slope=0.005
DSS Import GetInterval= 0
DSS Import GetPeak= 0
DSS Import FillOption= 0

--- Miller Creek.g01 (geometry) ---

Geom Title=Existing Conditions
Program Version=4.10

River Reach=Miller Creek    ,Reach-1
Reach XY= 30
        2288129.        7201010.      2287532.67      7199758.41
      2287424.01        7199108.      2287130.05      7199048.38
      2287228.75      7198775.22      2286980.26      7198350.29
      2287078.68      7197925.02      2286875.49      7197211.25
      2286530.99      7197104.73      2286971.92      7195959.98
      2286432.31      7195701.98      2286329.47      7195273.71
      2286525.48      7195011.46      2285889.19      7194719.68
      2286021.51      7194456.42      2285586.62       7194116.5
      2285573.59      7193815.17       2285186.8      7193816.21
      2285278.29      7193469.79      2285078.52      7193230.16
        2285229.        7193010.      2284722.46       7193051.1
      2284709.87      7192539.58        2284079.        7192360.
      2283975.85       7191467.7      2283181.09      7190304.74
      2283223.64       7189557.3      2282882.66      7189351.83
      2282802.34      7188883.05        2282279.        7188660.

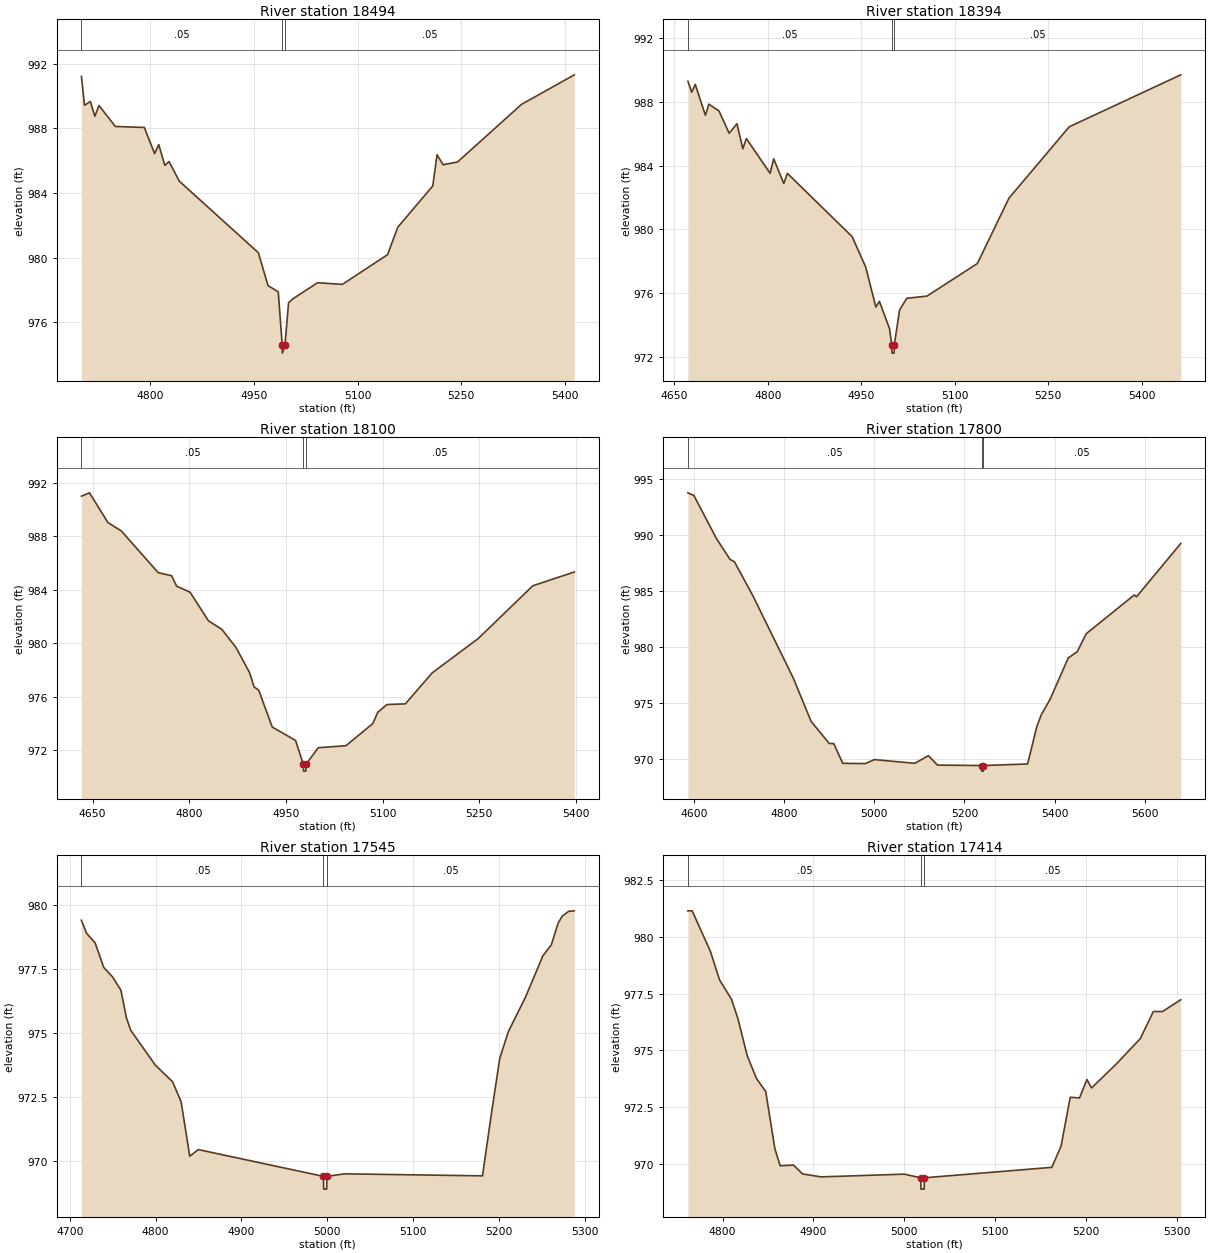
Type RM Length L Ch R = 1 ,18494   ,100,100,100
BEGIN DESCRIPTION:
Miller Creek 44.0
END DESCRIPTION:
XS GIS Cut Line= 2
      2288359.63      7200773.78      2287772.96       7201179.7
#Sta/Elev= 30
  4700.4  991.22  4704.9  989.43  4713.3  989.67  4719.8  988.75  4725.8  989.42
  4749.5  988.12  4791.4  988.06  4806.3  986.44  4812.3     987  4821.1  985.71
  4827.2  985.95  4842.1  984.73  4956.5   980.3  4970.5  978.26  4985.3  977.88
    4991  974.58  4991.3  974.08    4995  974.58  5000.2   977.2  5006.3  977.44
  5042.1  978.44  5078.1  978.34  5143.5  980.18  5158.3  981.88    5209  984.44
  5215.1  986.37  5223.9  985.75  5244.8  985.92  5337.4  989.49  5413.8  991.32
#Mann= 3 ,-1 , 0
  4700.4     .05       0    4991    .033       0    4995     .05       0
Bank Sta=4991,4995
XS Rating Curve= 0 ,0
Exp/Cntr=0.3,0.1

Type RM Length L Ch R = 1 ,18394   ,294,294,294
BEGIN DESCRIPTION:
Miller Creek 43.0
END DESCRIPTION:
XS GIS Cut Line= 2
      2288368.38      7200701.55      2287671.27      7201075.55
#Sta/Elev= 30
  4671.6   989.3  4677.7  988.61  4683.4   989.1  4699.7  987.16  4705.3  987.86
  4721.6  987.43  4737.8  986.03  4750.3  986.63  4759.8  985.06  4765.4   985.7
  4803.6  983.52  4809.3  984.43  4825.5  982.88  4831.2  983.52  4935.2  979.55
  4957.1  977.63  4973.3  975.13    4979  975.49  4995.3  973.77  4998.9  972.74
  4999.2  972.24  5002.7  972.24  5002.9  972.74  5011.3  974.94  5022.9  975.68
  5055.4  975.82  5136.2  977.86  5186.9  981.96  5283.7  986.44  5462.7   989.7
#Mann= 3 ,-1 , 0
  4671.6     .05       0  4998.9    .033       0  5002.9     .05       0
Bank Sta=4998.9,5002.9
XS Rating Curve= 0 ,0
Exp/Cntr=0.3,0.1

Type RM Length L Ch R = 1 ,18100   ,300,300,300
BEGIN DESCRIPTION:
Miller Creek 42.0
END DESCRIPTION:
XS GIS Cut Line= 2
      2288253.58      7200366.98      2287669.39      7200860.41
#Sta/Elev= 30
  4632.7     991  4645.2  991.25  4673.8  989.03  4694.6   988.4  4751.8  985.28
  4772.6  985.05  4780.4  984.27  4801.2  983.82  4829.8  981.68  4850.6  981.04
  4872.7  979.67  4893.5  977.81  4900.5  976.74  4907.8  976.49  4928.7  973.74
    4965  972.73    4977  970.94  4977.3  970.44  4980.8  970.44    4981  970.94
  5000.1  972.19    5043  972.34  5084.7  973.99  5092.4  974.84  5106.7  975.42
  5135.3  975.47    5177  977.79  5248.5  980.36    5333   984.3  5397.4  985.33
#Mann= 3 ,-1 , 0
  4632.7     .05       0    4977    .033       0    4981     .05       0
Bank Sta=4977,4981
XS Rating Curve= 0 ,0
Exp/Cntr=0.3,0.1

Type RM Length L Ch R = 1 ,17800   ,255,255,255
BEGIN DESCRIPTION:
Miller Creek 41.0
END DESCRIPTION:
XS GIS Cut Line= 2
      2288292.29      7200323.75      2287199.44       7200358.2
#Sta/Elev= 30
  4586.5  993.75  4599.8  993.51  4649.8  989.67  4679.8  987.81  4689.8  987.59
  4729.9  984.62  4819.9  977.24  4859.9  973.34    4900  971.37    4910  971.36
    4930   969.6    4980  969.57    5000  969.93    5090   969.6  5120.1  970.28
  5140.1  969.44  5238.1   969.4  5238.4   968.9  5241.9   968.9  5242.1   969.4
  5340.2  969.54  5360.2  972.83  5370.2  973.91  5390.2  975.33  5430.2     979
  5450.2  979.56  5470.2  981.17  5576.8  984.63  5581.8  984.47  5679.9  989.23
#Mann= 3 ,-1 , 0
  4586.5     .05       0  5238.1    .033       0  5242.1     .05       0
Bank Sta=5238.1,5242.1
XS Rating Curve= 0 ,0
Exp/Cntr=0.3,0.1

Type RM Length L Ch R = 1 ,17545   ,131,131,131
BEGIN DESCRIPTION:
Miller Creek 40.0
END DESCRIPTION:
XS GIS Cut Line= 3
      2288014.94      7200141.53        2287729.        7200160.
      2287442.46      7200186.53
#Sta/Elev= 29
  4713.5  979.42  4719.5  978.91  4729.5  978.53  4739.5  977.57  4749.5  977.21
  4759.5  976.68  4765.9   975.6  4770.9  975.11  4799.6  973.74  4819.7  973.09
  4829.7   972.3  4839.7  970.17  4849.7  970.43  4995.5  969.38  4995.8  968.88
  4999.3  968.88  4999.5  969.38  5020.1  969.48  5180.8   969.4  5190.8  971.74
  5200.9     974  5210.9  975.05    5231  976.41  5251.1  978.02  5261.1  978.46
  5268.7  979.29  5273.7  979.58  5281.2  979.77  5287.8  979.79
#Mann= 3 ,-1 , 0
  4713.5     .05       0  4995.5    .033       0  4999.5     .05       0
Bank Sta=4995.5,4999.5
XS Rating Curve= 0 ,0
Exp/Cntr=0.3,0.1

Type RM Length L Ch R = 1 ,17414   ,44,44,44
BEGIN DESCRIPTION:
Miller Creek 39.3
END DESCRIPTION:
XS GIS Cut Line= 2
      2287963.33      7199986.96      2287429.24      7200082.66
#Sta/Elev= 30
  4761.9  981.15  4766.6  981.15  4786.6  979.37  4796.8   978.1  4809.8  977.26
  4817.1  976.38  4827.3  974.75  4837.4  973.76  4847.6  973.18  4857.7  970.65
  4863.5  969.91  4878.1  969.94  4888.2  969.55  4908.5  969.42    5000  969.54
  5018.3  969.38  5018.5  968.88    5022  968.88  5022.3  969.38  5162.5  969.84
  5172.7  970.77  5182.8  972.93    5193   972.9  5201.2  973.71  5206.3  973.34
  5233.6   974.4    5260  975.52  5274.3  976.71  5284.4  976.71  5304.5  977.23
#Mann= 3 ,-1 , 0
  4761.9     .05       0  5018.3    .033       0  5022.3     .05       0
Bank Sta=5018.3,5022.3
XS Rating Curve= 0 ,0
Exp/Cntr=0.3,0.1

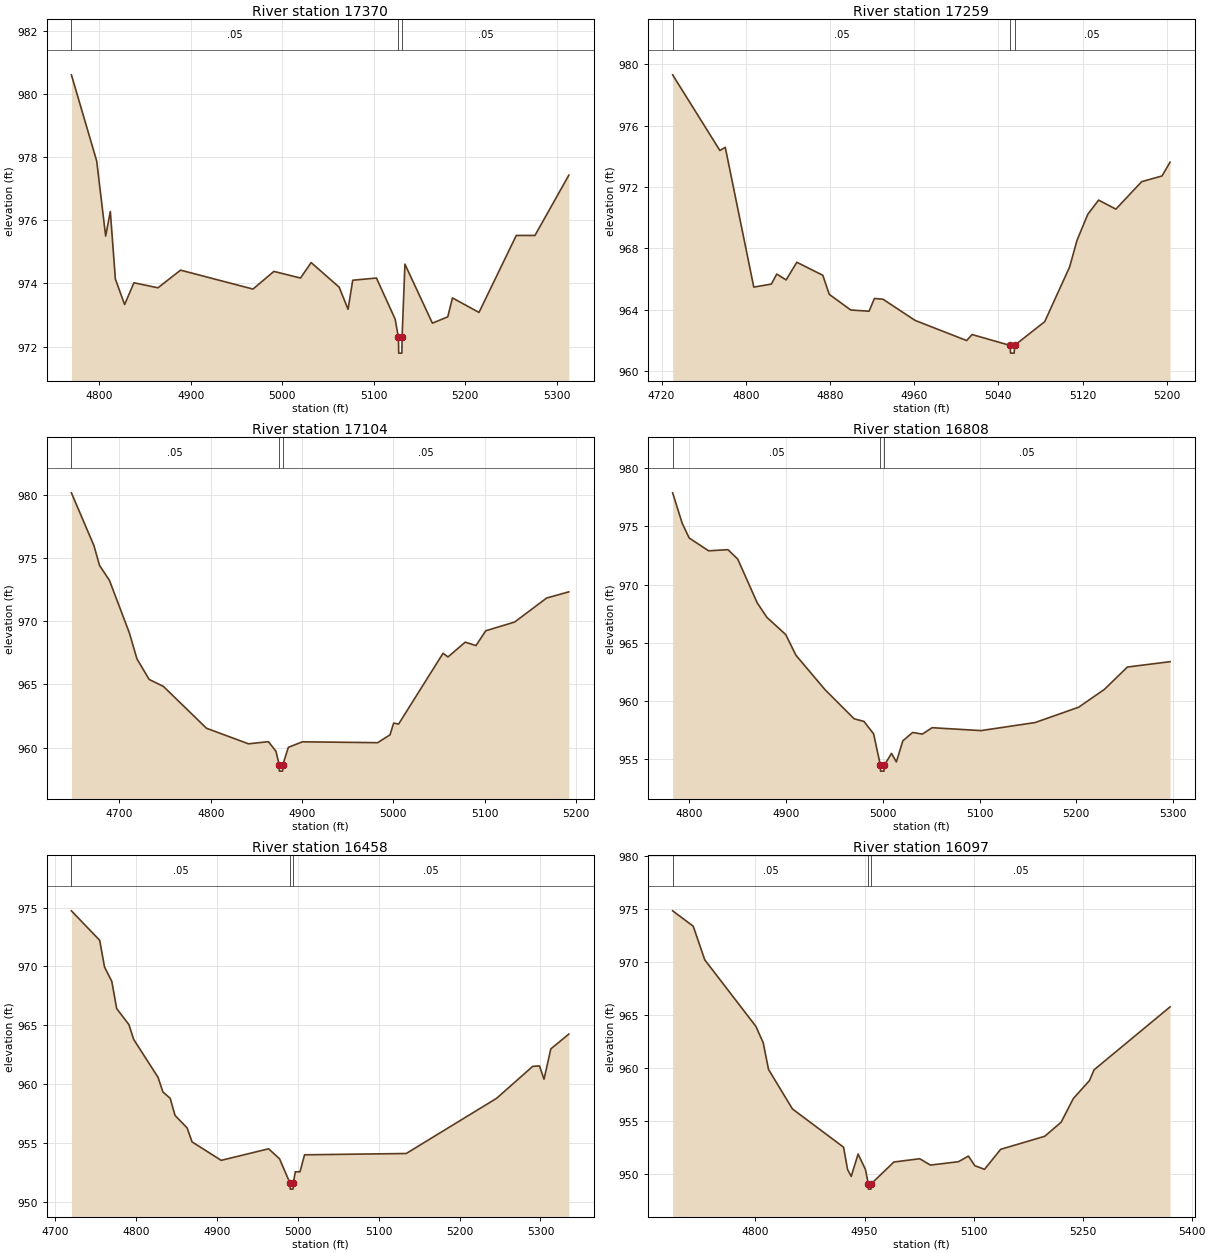
Type RM Length L Ch R = 1 ,17370   ,111,111,111
BEGIN DESCRIPTION:
Miller Creek 39.2
END DESCRIPTION:
XS GIS Cut Line= 2
      2287936.09      7199947.02      2287402.68      7200049.68
#Sta/Elev= 30
  4769.8  980.61  4797.4  977.88  4807.2   975.5  4812.3  976.28  4817.8  974.14
  4827.9  973.33  4838.1  974.02  4864.3  973.86    4889  974.42  4968.1  973.82
  4990.9  974.38    5020  974.17  5031.6  974.66  5062.2  973.88  5071.9  973.18
    5077   974.1  5102.9  974.17  5123.3  972.87  5126.9  972.29  5127.2  971.79
  5130.7  971.79  5130.9  972.29    5134  974.61    5164  972.74  5180.8  972.94
  5185.9  973.54  5214.9  973.08  5255.6  975.52    5276  975.52    5313  977.43
#Mann= 3 ,-1 , 0
  4769.8     .05       0  5126.9    .033       0  5130.9     .05       0
Bank Sta=5126.9,5130.9
XS Rating Curve= 0 ,0
Exp/Cntr=0.3,0.1

Type RM Length L Ch R = 1 ,17259   ,155,155,155
BEGIN DESCRIPTION:
Miller Creek 39.1
END DESCRIPTION:
XS GIS Cut Line= 2
       2287894.3      7199854.63      2287432.66      7199955.81
#Sta/Elev= 30
  4730.5  979.31  4775.4  974.38  4780.5  974.59  4807.6  965.48  4824.3  965.68
  4829.4  966.33  4838.3  965.95  4848.5   967.1  4873.2  966.25  4879.3  965.01
  4899.7  963.99  4917.1  963.91  4922.2  964.74  4930.4  964.69  4960.9  963.31
  5009.8     962    5015  962.39  5051.3  961.68  5051.5  961.18    5055  961.18
  5055.3  961.68    5084  963.23  5107.7   966.8  5114.7  968.53  5124.9  970.22
  5135.2  971.15  5151.6  970.56  5176.1  972.35  5195.4  972.72  5203.1  973.62
#Mann= 3 ,-1 , 0
  4730.5     .05       0  5051.3    .033       0  5055.3     .05       0
Bank Sta=5051.3,5055.3
XS Rating Curve= 0 ,0
Exp/Cntr=0.3,0.1

Type RM Length L Ch R = 1 ,17104   ,296,296,296
BEGIN DESCRIPTION:
Miller Creek 39.0
END DESCRIPTION:
XS GIS Cut Line= 3
      2287877.35      7199645.58      2287556.53      7199783.07
      2287374.41      7199855.15
#Sta/Elev= 30
  4647.4  980.15  4672.1  975.97  4678.2  974.41  4689.1  973.22  4710.9  969.07
  4719.2  967.02  4732.6  965.39  4748.2  964.84  4795.4  961.53  4841.4   960.3
  4863.2  960.47  4871.5  959.71    4875  958.64  4875.2  958.14  4878.7  958.14
    4879  958.64    4885  960.02  4900.5  960.46  4982.9  960.39  4996.4  961.01
  5000.4  961.94  5005.8  961.86  5054.5  967.46  5059.9  967.17  5078.8  968.34
  5090.6  968.07  5101.3  969.24  5132.9  969.93    5168  971.83  5192.3  972.32
#Mann= 3 ,-1 , 0
  4647.4     .05       0    4875    .033       0    4879     .05       0
Bank Sta=4875,4879
XS Rating Curve= 0 ,0
Exp/Cntr=0.3,0.1

Type RM Length L Ch R = 1 ,16808   ,350,350,350
BEGIN DESCRIPTION:
Miller Creek 38.0
END DESCRIPTION:
XS GIS Cut Line= 3
      2287846.01      7199514.31      2287626.17      7199533.77
      2287335.36      7199574.16
#Sta/Elev= 30
  4782.6  977.89  4792.5  975.27  4799.7  974.01  4819.8  972.91  4839.8  973.01
  4849.9   972.2    4870  968.45    4880   967.2  4899.5  965.72  4910.1  963.94
  4940.2  960.98  4970.3  958.48  4980.4  958.26  4990.4  957.19  4997.4  954.49
  4997.6  953.99  5001.1  953.99  5001.4  954.49  5008.9  955.51  5013.9  954.78
  5020.6  956.59  5030.7  957.31  5040.8  957.17  5050.9  957.72  5101.4  957.47
  5157.3  958.16  5202.4  959.48    5229  961.01  5252.8  962.93  5296.9  963.39
#Mann= 3 ,-1 , 0
  4782.6     .05       0  4997.4    .033       0  5001.4     .05       0
Bank Sta=4997.4,5001.4
XS Rating Curve= 0 ,0
Exp/Cntr=0.3,0.1

Type RM Length L Ch R = 1 ,16458   ,361,361,361
BEGIN DESCRIPTION:
Miller Creek 37.0
END DESCRIPTION:
XS GIS Cut Line= 3
      2287584.04      7199026.83        2287429.        7199260.
      2287279.01      7199559.99
#Sta/Elev= 30
  4719.7  974.72  4754.7  972.22  4760.7  969.95  4769.7  968.73  4775.7  966.43
  4790.8  965.08  4796.8  963.81  4826.9   960.6  4832.9  959.36  4841.9  958.82
  4847.9  957.37  4862.9  956.31  4868.9  955.13    4905  953.56  4963.7  954.54
  4977.2  953.69  4990.2  951.62  4990.4  951.12  4993.9  951.12  4994.2  951.62
  4996.7  952.59  5002.5  952.59  5008.1  954.03  5133.9  954.14  5245.7  958.82
  5290.4  961.53  5298.8  961.57  5304.4  960.44  5312.8  963.01  5335.1  964.27
#Mann= 3 ,-1 , 0
  4719.7     .05       0  4990.2    .033       0  4994.2     .05       0
Bank Sta=4990.2,4994.2
XS Rating Curve= 0 ,0
Exp/Cntr=0.3,0.1

Type RM Length L Ch R = 1 ,16097   ,344,344,344
BEGIN DESCRIPTION:
Miller Creek 36.0
END DESCRIPTION:
XS GIS Cut Line= 4
      2287583.03      7198942.43      2287312.33      7198967.88
       2287298.5      7199080.29      2287029.04      7199209.98
#Sta/Elev= 30
  4686.1  974.86  4714.4  973.41  4730.3  970.23  4800.6  963.95  4810.7   962.4
    4818  959.88  4850.9  956.15  4921.2  952.54  4926.7  950.44  4931.7  949.78
  4941.2  951.89  4951.3  950.44  4955.2  949.08  4955.4  948.58  4958.9  948.58
  4959.2  949.08  4990.4  951.14  5025.9  951.45  5040.7  950.85  5079.2  951.17
  5092.9   951.7  5101.8  950.79  5115.1  950.45  5137.3  952.34  5197.9  953.57
  5220.5   954.9  5237.2  957.13  5259.4  958.83  5265.8  959.85  5370.3  965.79
#Mann= 3 ,-1 , 0
  4686.1     .05       0  4955.2    .033       0  4959.2     .05       0
Bank Sta=4955.2,4959.2
XS Rating Curve= 0 ,0
Exp/Cntr=0.3,0.1

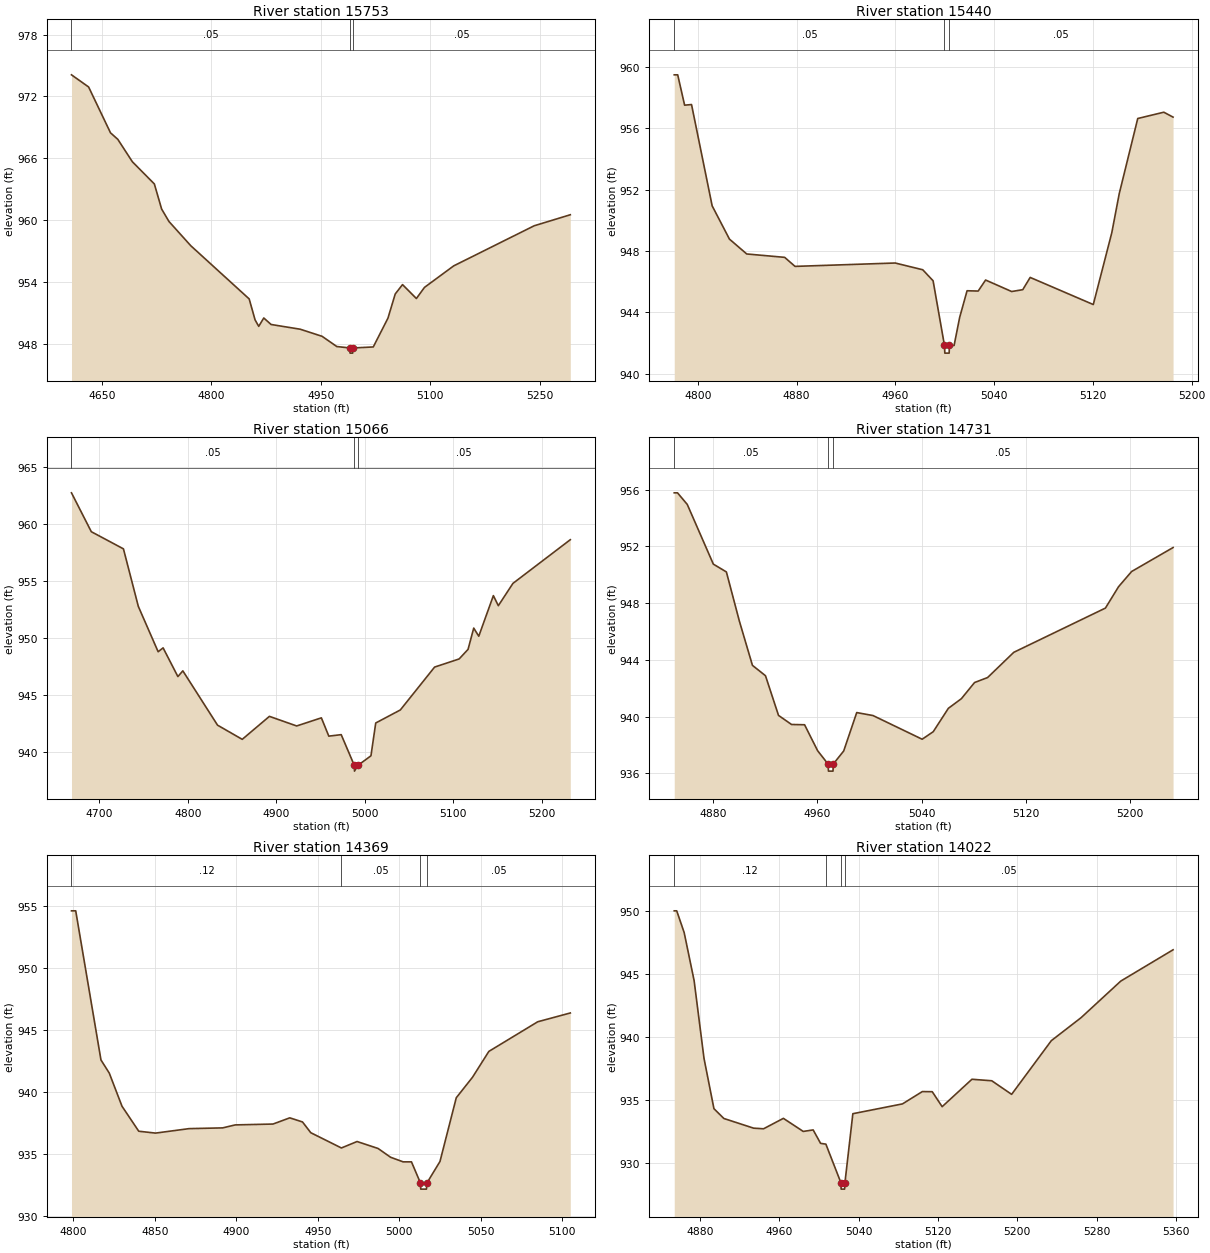
Type RM Length L Ch R = 1 ,15753   ,313,313,313
BEGIN DESCRIPTION:
Miller Creek 35.0
END DESCRIPTION:
XS GIS Cut Line= 3
       2287572.5      7198907.69       2287180.3      7198918.94
      2286889.62      7198939.87
#Sta/Elev= 30
  4608.4   974.1  4631.9  972.92  4661.9  968.47  4671.9  967.84  4691.9  965.66
    4722  963.51    4732  961.07    4742  959.87    4772  957.51    4852  952.35
  4860.1  950.31  4865.1  949.69    4872   950.5    4882  949.87    4922  949.41
    4952  948.72  4972.1  947.73  4990.1  947.59  4990.3  947.09  4993.8  947.09
  4994.1  947.59  5022.1  947.69  5042.2  950.48  5052.2  952.83  5062.2  953.74
  5081.2  952.39  5092.3  953.47  5132.4  955.56  5242.7  959.45  5292.2  960.52
#Mann= 3 ,-1 , 0
  4608.4     .05       0  4990.1    .033       0  4994.1     .05       0
Bank Sta=4990.1,4994.1
XS Rating Curve= 0 ,0
Exp/Cntr=0.3,0.1

Type RM Length L Ch R = 1 ,15440   ,374,374,374
BEGIN DESCRIPTION:
Miller Creek 34.0
END DESCRIPTION:
XS GIS Cut Line= 3
        2287329.        7198560.        2287129.        7198660.
      2286978.99      7198760.01
#Sta/Elev= 30
    4781  959.49  4783.8  959.49  4789.4  957.51    4795  957.55  4811.7  950.94
  4825.7  948.77  4839.7   947.8  4870.4  947.58  4878.8  946.99  4959.9  947.21
  4982.2  946.77  4990.6  946.05  4999.8  941.83  5000.1  941.33  5003.6  941.33
  5003.8  941.83  5007.6  941.83  5012.1  943.66  5018.1   945.4  5027.1  945.38
  5033.1   946.1  5054.2  945.35  5063.2  945.47  5069.2  946.27  5120.3   944.5
  5135.3  949.19  5141.3  951.73  5156.3  956.64  5177.4  957.05  5184.9  956.73
#Mann= 3 ,-1 , 0
    4781     .05       0  4999.8    .033       0  5003.8     .05       0
Bank Sta=4999.8,5003.8
XS Rating Curve= 0 ,0
Exp/Cntr=0.3,0.1

Type RM Length L Ch R = 1 ,15066   ,335,335,335
BEGIN DESCRIPTION:
Miller Creek 33.0
END DESCRIPTION:
XS GIS Cut Line= 3
      2287279.04      7198209.98        2286979.        7198360.
      2286776.41      7198464.71
#Sta/Elev= 30
  4668.6  962.71    4691  959.31  4727.3  957.81  4744.1  952.78  4766.5  948.81
  4772.1  949.15  4788.8  946.64  4794.4  947.14  4833.6  942.39  4861.5  941.15
  4892.2  943.16    4923  942.32  4950.9  943.03  4959.3  941.43  4973.3  941.56
  4988.1  938.87  4988.3  938.37  4992.1  938.87  5006.9  939.71  5012.3  942.58
  5040.1  943.72  5078.8  947.47  5106.5  948.18  5116.6  949.02    5123  950.88
  5128.7  950.17  5145.2  953.72  5150.8  952.84  5167.3  954.79  5232.1  958.61
#Mann= 3 ,-1 , 0
  4668.6     .05       0  4988.1    .033       0  4992.1     .05       0
Bank Sta=4988.1,4992.1
XS Rating Curve= 0 ,0
Exp/Cntr=0.3,0.1

Type RM Length L Ch R = 1 ,14731   ,362,362,362
BEGIN DESCRIPTION:
Miller Creek 32.0
END DESCRIPTION:
XS GIS Cut Line= 3
        2287229.        7198060.        2287079.        7198060.
      2286847.38       7198082.3
#Sta/Elev= 30
  4850.1  955.78  4852.6  955.78  4860.1  954.96  4880.1  950.75  4890.1   950.2
  4900.1  946.72  4910.1  943.61  4920.1  942.88  4930.1  940.08  4940.1  939.44
  4950.1  939.42  4960.1  937.59  4968.1  936.65  4968.4  936.15  4971.9  936.15
  4972.1  936.65  4980.1  937.57  4990.1  940.28  5002.6  940.07  5040.3   938.4
  5048.8  938.93  5060.4  940.58  5070.4  941.26  5080.5   942.4  5090.5  942.75
  5110.6  944.53  5180.9  947.65    5191  949.16    5201  950.23  5232.8  951.92
#Mann= 3 ,-1 , 0
  4850.1     .05       0  4968.1    .033       0  4972.1     .05       0
Bank Sta=4968.1,4972.1
XS Rating Curve= 0 ,0
Exp/Cntr=0.3,0.1

Type RM Length L Ch R = 1 ,14369   ,347,347,347
BEGIN DESCRIPTION:
Miller Creek 31.0
END DESCRIPTION:
XS GIS Cut Line= 3
      2287129.04      7197759.99        2286929.        7197810.
      2286828.99        7197810.
#Sta/Elev= 30
  4798.9  954.59  4801.5  954.59    4817  942.56  4822.1   941.5  4829.9  938.83
  4840.2  936.81  4850.5  936.66  4871.1  937.02  4891.7  937.08  4899.4  937.32
  4922.6  937.39  4932.9  937.89  4940.7  937.56  4945.8  936.69  4964.6  935.46
  4974.2  935.98  4987.1  935.42  4994.8  934.71  5002.5  934.34  5007.6  934.34
  5013.1  932.64  5013.3  932.14  5016.8  932.14  5017.1  932.64  5025.1  934.37
  5035.1  939.51  5045.1  941.17  5055.1  943.25  5085.1  945.64  5105.1  946.35
#Mann= 4 ,-1 , 0
  4798.9     .12       0  4964.6     .05       0  5013.1    .033       0
  5017.1     .05       0
Bank Sta=5013.1,5017.1
XS Rating Curve= 0 ,0
Exp/Cntr=0.3,0.1

Type RM Length L Ch R = 1 ,14022   ,524,524,524
BEGIN DESCRIPTION:
Miller Creek 30.0
END DESCRIPTION:
XS GIS Cut Line= 3
      2287028.96        7197510.        2286879.        7197510.
      2286526.29      7197514.19
#Sta/Elev= 30
  4854.3  950.04  4856.8  950.04  4864.3  948.31  4874.3   944.5  4884.3   938.3
  4894.3   934.3  4904.3  933.52  4934.3  932.75  4944.3   932.7  4964.3  933.53
  4984.3  932.49  4994.3  932.61  5001.8  931.54  5007.1  931.48  5022.3   928.4
  5022.5   927.9    5026   927.9  5026.3   928.4  5034.3   933.9  5084.3  934.68
  5104.3  935.66  5114.3  935.65  5124.3  934.46  5154.3  936.64  5174.3  936.52
  5194.3  935.44  5234.3  939.71  5264.3  941.54  5304.3  944.45    5357  946.94
#Mann= 4 ,-1 , 0
  4854.3     .12       0  5007.1     .05       0  5022.3     .07       0
  5026.3     .05       0
Bank Sta=5022.3,5026.3
XS Rating Curve= 0 ,0
Exp/Cntr=0.3,0.1

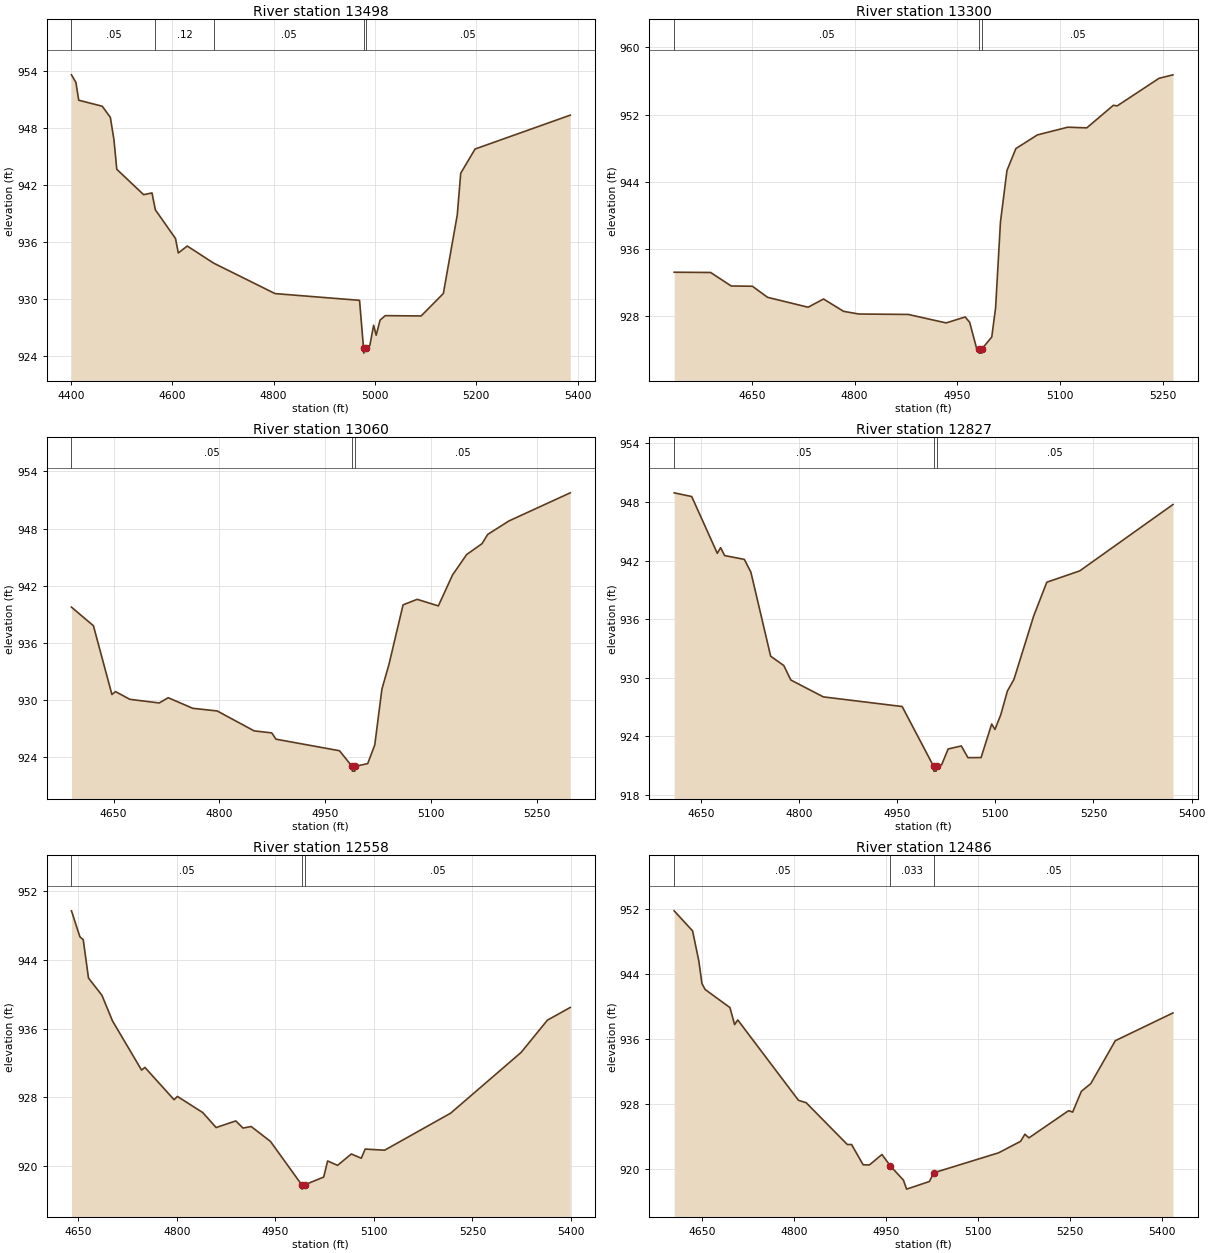
Type RM Length L Ch R = 1 ,13498   ,198,198,198
BEGIN DESCRIPTION:
Miller Creek 29.0
END DESCRIPTION:
XS GIS Cut Line= 4
      2287178.99        7196860.      2286719.48      7197065.89
      2286682.78      7197288.47      2286497.68      7197464.13
#Sta/Elev= 30
  4401.1  953.56  4409.9  952.75  4415.4  950.89  4461.8  950.26  4477.8  949.09
    4485  946.71  4490.5  943.63  4543.5  940.96    4560  941.14  4566.6  939.37
  4606.4  936.35  4611.9  934.83  4629.6  935.56  4681.4  933.77  4802.8  930.56
  4969.6  929.85  4977.5   924.8  4977.9   924.3  4981.9   924.8  4989.9  925.11
  4997.4  927.23  5002.4  926.18  5010.1  927.77  5020.3  928.24  5091.2  928.21
    5135  930.57  5162.4  938.81  5169.3  943.22  5197.6  945.76  5385.4  949.32
#Mann= 5 ,-1 , 0
  4401.1     .05       0  4566.6     .12       0  4681.4     .05       0
  4977.5    .033       0  4981.9     .05       0
Bank Sta=4977.5,4981.9
XS Rating Curve= 0 ,0
Exp/Cntr=0.3,0.1

Type RM Length L Ch R = 1 ,13300   ,240,240,240
BEGIN DESCRIPTION:
Miller Creek 28.1
END DESCRIPTION:
XS GIS Cut Line= 2
      2286943.11      7196891.68      2286294.83      7197223.79
#Sta/Elev= 30
  4536.5  933.21  4589.7  933.18  4619.8  931.57  4650.7  931.54  4672.9  930.22
  4732.1  929.04  4754.6  930.02  4783.9  928.55  4806.1  928.23  4878.3  928.18
  4933.7  927.17  4961.5  927.88  4968.1  927.23  4978.1  924.16  4981.5  924.07
  4981.9  923.57  4985.5  923.57  4985.9  924.07  5000.3  925.49  5005.9  928.95
    5013  939.18  5022.5  945.33  5035.5  947.94  5066.9  949.57  5111.3  950.49
  5139.1  950.41  5177.9   953.1  5183.5  953.03  5244.5  956.31  5264.9  956.73
#Mann= 3 ,-1 , 0
  4536.5     .05       0  4981.5    .033       0  4985.9     .05       0
Bank Sta=4981.5,4985.9
XS Rating Curve= 0 ,0
Exp/Cntr=0.3,0.1

Type RM Length L Ch R = 1 ,13060   ,233,233,233
BEGIN DESCRIPTION:
Miller Creek 28.0
END DESCRIPTION:
XS GIS Cut Line= 3
      2286978.98        7196810.      2286704.95      7196883.93
      2286282.18      7196871.12
#Sta/Elev= 30
  4590.3  939.76  4621.4  937.81  4647.6   930.6  4652.7   930.9  4673.1  930.09
  4714.6  929.71  4727.4  930.26  4762.1  929.15  4796.8  928.87  4849.2  926.78
  4874.1  926.57  4880.1  925.91  4970.1   924.7  4987.9  923.06  4988.3  922.56
  4991.9  922.56  4992.3  923.06  5010.1  923.35  5020.1  925.31  5030.2  931.16
  5040.2  933.75  5060.2     940  5080.2  940.58  5110.2  939.89  5130.2  943.12
  5150.2  945.27  5172.1  946.42  5180.2  947.39  5210.2   948.8  5297.1  951.75
#Mann= 3 ,-1 , 0
  4590.3     .05       0  4987.9    .033       0  4992.3     .05       0
Bank Sta=4987.9,4992.3
XS Rating Curve= 0 ,0
Exp/Cntr=0.3,0.1

Type RM Length L Ch R = 1 ,12827   ,269,269,269
BEGIN DESCRIPTION:
Miller Creek 27.1
END DESCRIPTION:
XS GIS Cut Line= 2
       2287115.7      7196741.71      2286357.22      7196668.52
#Sta/Elev= 30
  4609.4  948.94  4636.2  948.56  4675.3  942.74  4680.3  943.32  4686.5  942.51
  4716.6  942.12  4726.6  940.81  4756.8   932.2  4776.9  931.24  4787.6  929.76
  4837.2  928.03  4957.7  927.04  5005.7  920.92  5006.1  920.42  5009.7  920.42
  5010.2  920.92    5018  921.07    5028  922.69  5048.1     923  5058.2   921.8
  5078.3  921.81  5094.5  925.25  5099.5  924.69  5108.4   926.2  5118.5  928.63
  5128.5  929.82  5158.6  936.31  5178.7  939.78    5229  940.94  5371.4  947.74
#Mann= 3 ,-1 , 0
  4609.4     .05       0  5005.7    .033       0  5010.2     .05       0
Bank Sta=5005.7,5010.2
XS Rating Curve= 0 ,0
Exp/Cntr=0.3,0.1

Type RM Length L Ch R = 1 ,12558   ,72,72,72
BEGIN DESCRIPTION:
Miller Creek 27.0
END DESCRIPTION:
XS GIS Cut Line= 6
      2287084.37      7196588.11      2286820.62      7196531.81
      2286776.45      7196446.53      2286716.35      7196355.89
      2286587.88      7196276.69      2286454.35      7196268.44
#Sta/Elev= 30
  4639.6  949.67  4652.4  946.66  4657.5  946.32  4665.5  941.87    4686  939.86
  4701.9  936.91  4746.3  931.18  4751.4  931.49  4795.8  927.74  4800.9  928.12
  4839.4  926.25  4859.8  924.51  4889.7  925.28  4900.7  924.45  4913.1  924.63
  4942.5   922.9  4990.1  917.86  4990.6  917.36  4994.6  917.86  5023.5  918.76
  5029.5  920.63  5044.6  920.12  5065.6  921.44  5080.7  920.95  5086.7  922.01
  5116.3  921.88  5216.8  926.18    5324  933.23  5364.1  936.98  5398.8  938.45
#Mann= 3 ,-1 , 0
  4639.6     .05       0  4990.1    .033       0  4994.6     .05       0
Bank Sta=4990.1,4994.6
XS Rating Curve= 0 ,0
Exp/Cntr=0.3,0.1

Type RM Length L Ch R = 1 ,12486   ,228,228,228
BEGIN DESCRIPTION:
Miller Creek 26.1
END DESCRIPTION:
XS GIS Cut Line= 6
      2287128.52      7196533.15      2286847.26      7196481.86
      2286833.72      7196419.39      2286738.48      7196321.48
      2286603.13      7196204.12      2286455.02      7196200.92
#Sta/Elev= 30
  4604.9  951.77  4634.9   949.3  4645.1   945.6  4650.2  942.81  4655.3  942.08
  4695.9  939.84  4703.5  937.74  4708.6  938.32  4807.7  928.41  4820.3  928.11
  4887.4  922.96  4894.3  922.96  4913.2  920.46  4923.4  920.44  4943.9  921.73
  4957.8   920.3  4978.9  918.57  4984.1  917.46  5021.3   918.4  5028.3  919.47
  5134.3  921.94    5170  923.35  5177.1  924.23  5183.7  923.78  5248.3  927.13
    5255  926.96  5269.2  929.52  5284.6  930.47  5324.6  935.76  5418.6  939.18
#Mann= 3 , 0 , 0
  4604.9     .05       0  4957.8    .033       0  5028.3     .05       0
Bank Sta=4957.8,5028.3
XS Rating Curve= 0 ,0
Exp/Cntr=0.3,0.1

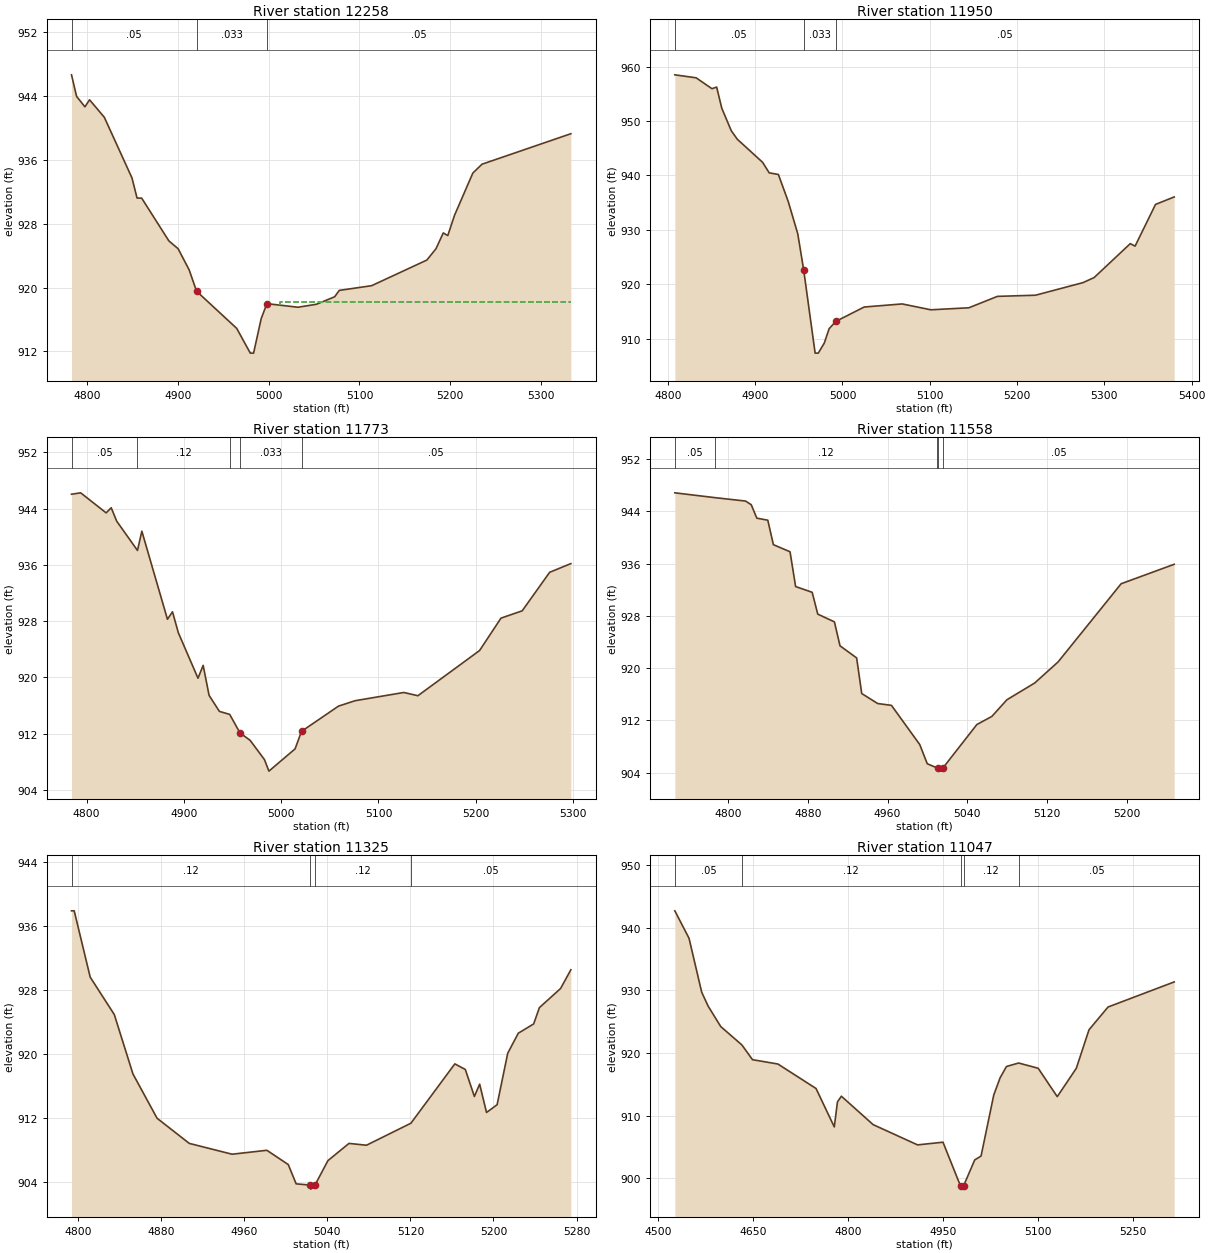
Type RM Length L Ch R = 1 ,12258   ,308,308,308
BEGIN DESCRIPTION:
Miller Creek 26.0
END DESCRIPTION:
XS GIS Cut Line= 3
      2287044.55      7196208.49      2286831.49      7196168.29
      2286502.46      7196111.59
#Sta/Elev= 30
  4782.4  946.65    4788  943.95  4797.2  942.64  4802.3  943.52  4818.6  941.33
  4849.1  933.73  4854.7  931.21  4859.8   931.2  4889.8  925.84    4900  924.86
  4912.2   922.2  4920.3  919.54  4964.6  914.88  4979.6  911.78  4983.2  911.78
  4991.6  916.11  4997.9  917.98  5032.2  917.53  5052.5   917.9  5072.6  918.84
  5077.7  919.64  5113.4  920.23  5174.3  923.44  5184.4  924.87  5192.4  926.84
  5197.4  926.51  5204.7  929.02    5225  934.34  5235.1  935.45  5333.1  939.27
#Mann= 3 , 0 , 0
  4782.4     .05       0  4920.3    .033       0  4997.9     .05       0
#XS Ineff= 2 , 0
       0                  5011.9       0  918.22
Permanent Ineff=
       F       F
Bank Sta=4920.3,4997.9
XS Rating Curve= 0 ,0
Exp/Cntr=0.3,0.1

Type RM Length L Ch R = 1 ,11950   ,177,177,177
BEGIN DESCRIPTION:
Miller Creek 25.1
END DESCRIPTION:
XS GIS Cut Line= 3
      2287118.37      7195846.26       2286884.9      7195946.33
      2286593.23        7196073.
#Sta/Elev= 30
    4808  958.51  4832.4  957.96  4850.5  955.96  4855.9  956.26  4861.7   952.4
  4872.6  948.24  4879.5  946.67  4908.5  942.42  4916.1  940.48  4926.6  940.18
  4937.9   935.2  4948.8  929.28  4955.6  922.61  4968.7  907.32  4972.3  907.32
  4979.2  909.18  4984.7   911.8  4992.3  913.15  5024.9   915.8  5068.4  916.37
  5101.2  915.29  5144.8  915.66  5177.5  917.76  5221.1  917.97  5275.6  920.29
  5288.3  921.22  5329.7  927.46  5335.2     927  5358.6  934.67    5380  936.05
#Mann= 3 , 0 , 0
    4808     .05       0  4955.6    .033       0  4992.3     .05       0
#XS Ineff= 2 , 0
       0                  5068.4       0  916.37
Permanent Ineff=
       F       F
Bank Sta=4955.6,4992.3
XS Rating Curve= 0 ,0
Exp/Cntr=0.3,0.1

Type RM Length L Ch R = 1 ,11773   ,215,215,215
BEGIN DESCRIPTION:
Miller Creek 25.0
END DESCRIPTION:
XS GIS Cut Line= 3
      2286856.93      7195655.99      2286769.01      7195917.04
      2286579.04      7196059.97
#Sta/Elev= 30
  4784.5  946.06  4793.9  946.26  4820.1  943.41  4825.3  944.14  4830.9  942.24
  4852.3  938.06  4856.8   940.8  4883.1  928.27  4888.3  929.33  4894.3  926.35
  4914.5  919.88  4919.8  921.71  4925.9  917.44  4936.5  915.16  4947.1  914.73
  4957.6  912.11  4968.1  911.04  4982.8   908.3  4987.4  906.66  5014.3  909.83
  5020.9  912.32  5058.9  915.91    5076  916.68    5126  917.85  5140.5  917.39
  5203.9  923.82  5225.9  928.43  5247.7  929.47  5275.9  934.95  5297.7  936.19
#Mann= 5 ,-1 , 0
  4784.5     .05       0  4852.3     .12       0  4947.1     .05       0
  4957.6    .033       0  5020.9     .05       0
Bank Sta=4957.6,5020.9
XS Rating Curve= 0 ,0
Exp/Cntr=0.3,0.1

Type RM Length L Ch R = 1 ,11558   ,233,233,233
BEGIN DESCRIPTION:
Miller Creek 24.1
END DESCRIPTION:
XS GIS Cut Line= 3
      2286802.25      7195640.31       2286634.9      7195725.32
      2286463.11      7195986.95
#Sta/Elev= 30
  4746.7  946.84    4787   946.1  4817.6  945.58  4823.3  945.02  4828.9  942.96
  4839.9  942.65  4845.5   938.9  4862.2  937.82  4867.8  932.49  4884.4  931.61
    4890  928.27  4906.7  927.08  4912.3  923.42    4929  921.56  4934.1  916.11
  4950.1  914.58  4963.9   914.3  4992.3  908.29  4999.8  905.36  5009.4  904.74
    5011  904.73  5011.5  904.23  5015.6  904.73  5049.5  911.36  5064.6  912.61
  5079.7  915.16  5107.5  917.72    5131  920.95  5194.2  932.92  5247.4   935.9
#Mann= 5 ,-1 , 0
  4746.7     .05       0    4787     .12       0  5009.4     .05       0
    5011     .07       0  5015.6     .05       0
Bank Sta=5011,5015.6
XS Rating Curve= 0 ,0
Exp/Cntr=0.3,0.1

Type RM Length L Ch R = 1 ,11325   ,278,278,278
BEGIN DESCRIPTION:
Miller Creek 24.0
END DESCRIPTION:
XS GIS Cut Line= 3
      2286628.98      7195610.01        2286429.        7195660.
      2286159.27      7195711.86
#Sta/Elev= 30
  4793.7  937.86  4796.3  937.86  4811.7  929.58  4834.9  924.91  4852.9  917.48
  4876.1  911.96  4907.1  908.82  4948.3  907.47  4981.8  907.96  5002.4  906.18
    5010  903.77  5023.5  903.61    5024  903.11  5028.1  903.61  5040.6  906.67
  5060.9  908.82  5077.7  908.59  5120.5  911.34  5162.8  918.75  5172.9  918.05
  5181.6  914.68  5186.7  916.22  5193.3  912.68  5203.5  913.65  5213.7  920.07
  5223.9  922.58  5238.7  923.74  5244.2  925.77  5264.6  928.16  5274.5   930.5
#Mann= 4 ,-1 , 0
  4793.7     .12       0  5023.5     .07       0  5028.1     .12       0
  5120.5     .05       0
Bank Sta=5023.5,5028.1
XS Rating Curve= 0 ,0
Exp/Cntr=0.3,0.1

Type RM Length L Ch R = 1 ,11047   ,377,377,377
BEGIN DESCRIPTION:
Miller Creek 23.1
END DESCRIPTION:
XS GIS Cut Line= 2
      2286801.35      7195397.89      2286014.82      7195450.69
#Sta/Elev= 30
  4526.2  942.68  4548.6   938.3  4568.6  929.69  4578.7  927.48  4598.7   924.2
    4632  921.28  4648.8  918.92  4688.9  918.23  4749.1  914.32  4777.9  908.19
  4782.9  912.18  4789.1  913.09  4839.3  908.55  4909.4  905.32  4949.5  905.75
  4977.2  898.76  4977.7  898.26  4981.9  898.76  4999.6  902.92  5009.6  903.54
  5029.7   913.3  5039.7  916.03  5049.7  917.83  5068.9  918.39  5099.8  917.55
  5129.9  913.02    5160  917.55    5180  923.69  5210.1  927.33  5314.5  931.33
#Mann= 5 ,-1 , 0
  4526.2     .05       0    4632     .12       0  4977.2     .07       0
  4981.9     .12       0  5068.9     .05       0
Bank Sta=4977.2,4981.9
XS Rating Curve= 0 ,0
Exp/Cntr=0.3,0.1