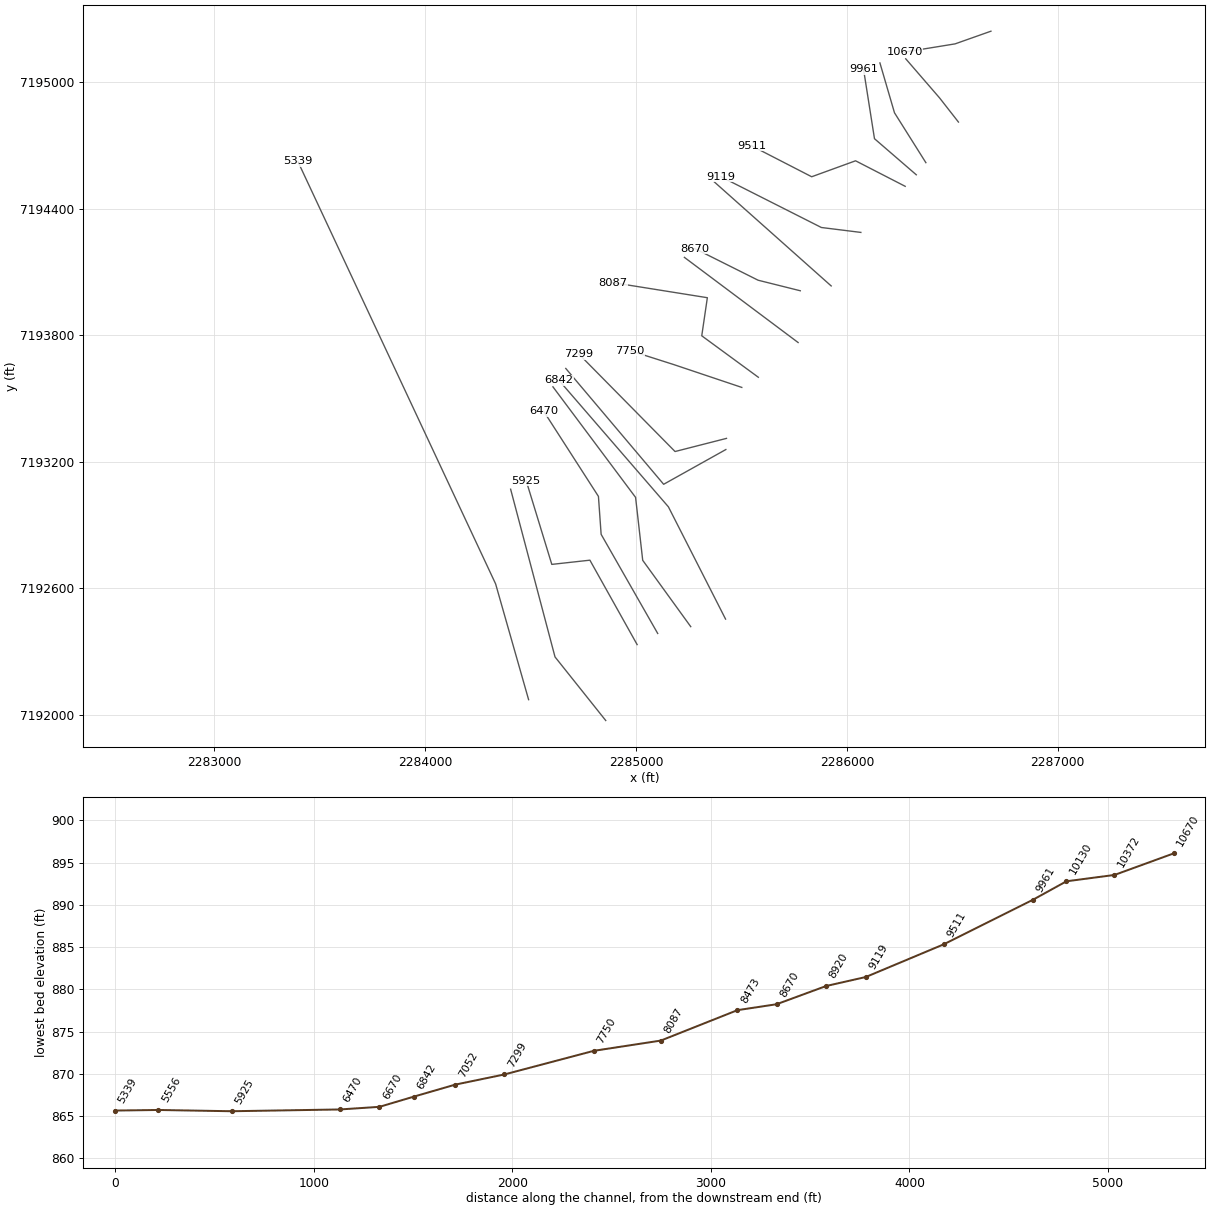
HEC-RAS study Miller Creek.prj: Miller Creek Base Level Engineering

--- Miller Creek.g01 (geometry) --- (continued)

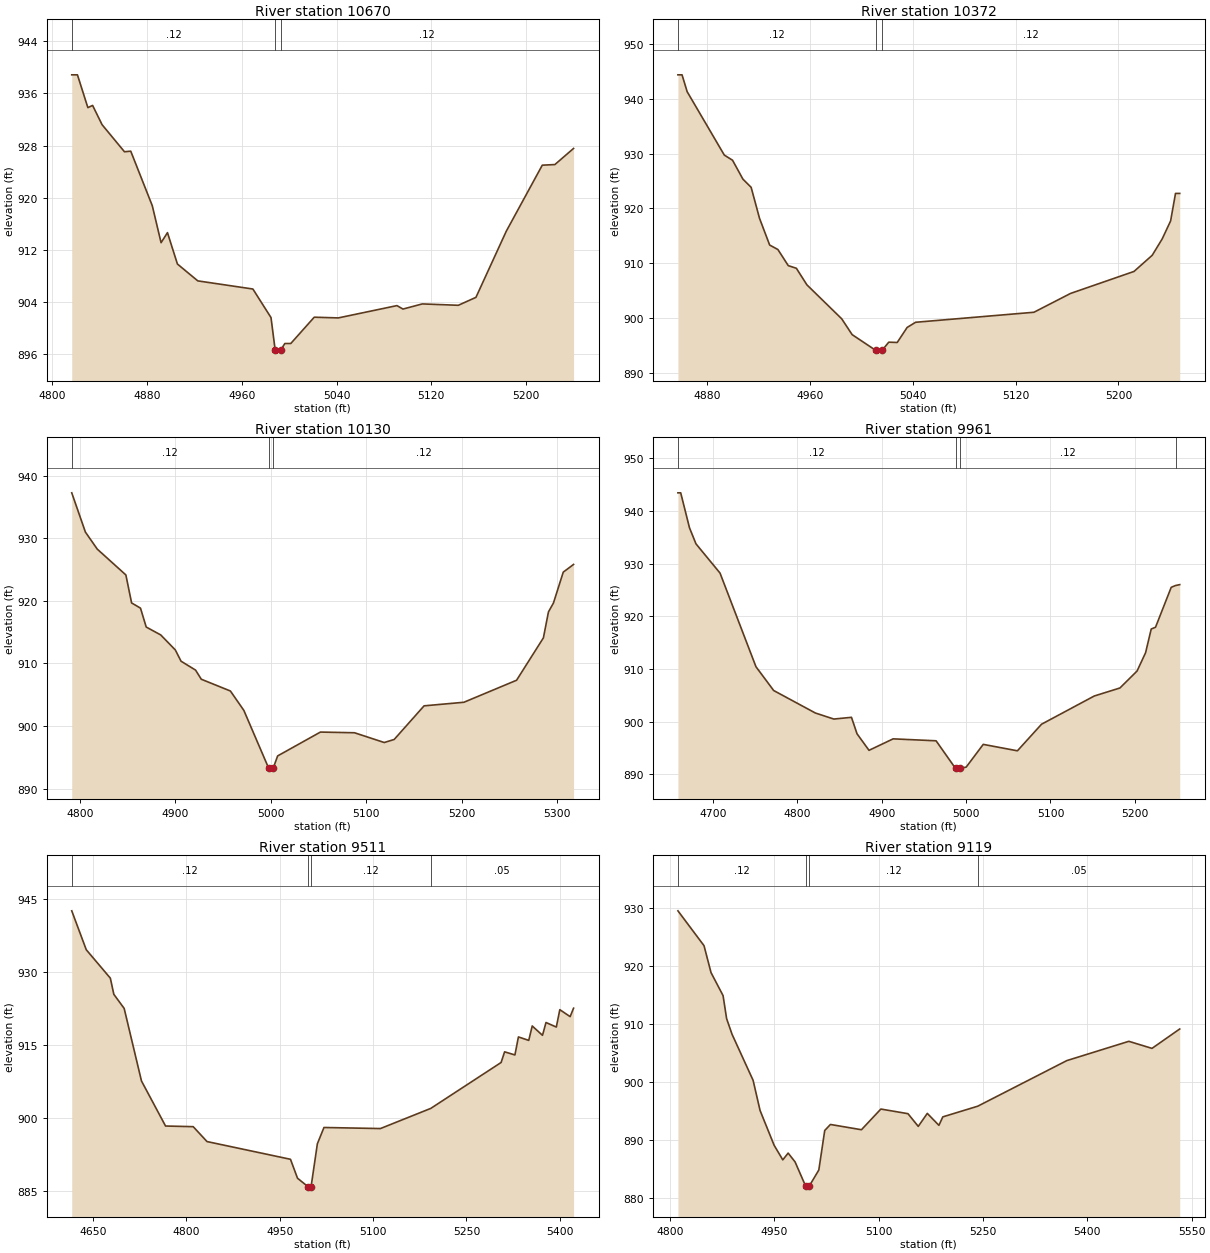
Type RM Length L Ch R = 1 ,10670   ,298,298,298
BEGIN DESCRIPTION:
Miller Creek 23.0
END DESCRIPTION:
XS GIS Cut Line= 3
      2286683.12      7195240.86      2286513.08      7195180.74
      2286272.98      7195141.71
#Sta/Elev= 30
  4816.5  938.86  4821.3  938.86  4830.1  933.82  4834.1  934.16  4842.1   931.2
    4861  927.04  4866.3  927.13  4884.5  918.74  4891.9  913.07  4897.3  914.61
  4905.7  909.79  4922.9   907.2  4969.4  905.95  4984.7  901.56  4988.2   896.6
  4988.7   896.1    4993   896.6  4996.4  897.58  5001.4  897.58  5021.2  901.62
  5041.5  901.51    5091   903.4  5096.1  902.87  5112.4  903.66  5142.8  903.45
  5157.7  904.67  5183.3  914.83  5213.7  924.98  5224.3  925.07  5240.1  927.55
#Mann= 3 ,-1 , 0
  4816.5     .12       0  4988.2     .07       0    4993     .12       0
Bank Sta=4988.2,4993
XS Rating Curve= 0 ,0
Exp/Cntr=0.3,0.1

Type RM Length L Ch R = 1 ,10372   ,242,242,242
BEGIN DESCRIPTION:
Miller Creek 22.0
END DESCRIPTION:
XS GIS Cut Line= 3
      2286528.99      7194810.01      2286439.38       7194924.6
      2286279.01      7195109.99
#Sta/Elev= 30
  4857.1  944.42  4860.3  944.42  4864.3  941.33  4893.2  929.75  4899.6  928.81
  4907.7  925.35  4914.1  923.85  4920.6   918.2  4928.5  913.31  4934.9  912.49
    4943  909.54  4949.3  909.06  4957.5  906.03  4984.6  899.82  4992.7  896.93
  5011.1  894.05  5011.7  893.55    5016  894.05  5021.2  895.55  5027.8   895.5
  5035.5  898.24  5042.1  899.19  5134.2  901.02  5162.7  904.46  5212.1  908.48
  5226.3  911.44    5234  914.41  5240.6  917.71  5244.4  922.74  5247.7  922.74
#Mann= 3 ,-1 , 0
  4857.1     .12       0  5011.1     .07       0    5016     .12       0
Bank Sta=5011.1,5016
XS Rating Curve= 0 ,0
Exp/Cntr=0.3,0.1

Type RM Length L Ch R = 1 ,10130   ,169,169,169
BEGIN DESCRIPTION:
Miller Creek 21.1
END DESCRIPTION:
XS GIS Cut Line= 3
      2286374.51      7194617.42      2286225.74      7194853.86
      2286156.66      7195090.32
#Sta/Elev= 30
  4791.4  937.26  4805.7  930.99  4818.1  928.27  4848.1  924.14  4854.1  919.67
  4863.4  918.84  4869.4  915.82  4884.6  914.56  4899.9  912.16  4905.9  910.36
  4921.1  908.94  4927.1  907.48  4957.6   905.6  4971.7   902.5  4997.6   893.3
  4998.2   892.8  5002.5   893.3  5007.1  895.23  5051.9  899.04  5087.6  898.93
  5118.8  897.37  5129.2  897.86  5160.5  903.23  5202.2   903.8  5257.4  907.32
  5285.5  914.09  5290.8  918.24    5296  919.65  5306.3  924.59  5317.1  925.82
#Mann= 3 ,-1 , 0
  4791.4     .12       0  4997.6     .07       0  5002.5     .12       0
Bank Sta=4997.6,5002.5
XS Rating Curve= 0 ,0
Exp/Cntr=0.3,0.1

Type RM Length L Ch R = 1 ,9961    ,450,450,450
BEGIN DESCRIPTION:
Miller Creek 21.0
END DESCRIPTION:
XS GIS Cut Line= 3
      2286329.01      7194559.99      2286130.85      7194731.07
        2286079.      7195060.02
#Sta/Elev= 30
  4658.4  943.47  4661.7  943.47  4672.1  936.83  4679.8  933.78  4708.3  928.23
  4750.9  910.44  4771.9  905.92  4821.3  901.65  4843.2   900.5  4864.1  900.83
  4870.7   897.7  4884.9  894.56  4913.5  896.74  4964.4  896.37  4987.5  891.11
  4988.1  890.61  4992.4  891.11  5000.1  891.38  5020.3  895.69  5060.8  894.47
  5089.4  899.52  5151.9  904.88  5182.3   906.4  5202.6  909.62  5212.7  913.09
  5219.4   917.6  5224.5  917.94  5243.1  925.52  5248.3  925.87  5253.2  926.03
#Mann= 4 ,-1 , 0
  4658.4     .12       0  4987.5     .07       0  4992.4     .12       0
  5248.3     .05       0
Bank Sta=4987.5,4992.4
XS Rating Curve= 0 ,0
Exp/Cntr=0.3,0.1

Type RM Length L Ch R = 1 ,9511    ,392,392,392
BEGIN DESCRIPTION:
Miller Creek 20.0
END DESCRIPTION:
XS GIS Cut Line= 4
      2286276.47      7194505.26      2286041.12      7194626.29
      2285833.09      7194550.63       2285548.4      7194697.18
#Sta/Elev= 30
  4615.9  942.49  4639.2   934.5  4677.9  928.66  4683.5  925.34  4700.1  922.45
  4727.9  907.55  4766.6  898.29    4811  898.16  4833.2   895.1  4967.3  891.46
  4978.6  887.57  4995.5  885.83  4996.1  885.33  5000.4  885.83  5010.5  894.64
  5021.1  897.99  5111.8  897.77  5192.7  901.91  5305.7  911.34  5311.3  913.53
  5327.9  912.89  5333.5  916.59  5350.1  915.88  5355.7  918.84  5372.2  916.92
  5377.8  919.55  5394.4  918.62    5400  922.19  5416.6  920.76  5422.1  922.49
#Mann= 4 ,-1 , 0
  4615.9     .12       0  4995.5     .07       0  5000.4     .12       0
  5192.7     .05       0
Bank Sta=4995.5,5000.4
XS Rating Curve= 0 ,0
Exp/Cntr=0.3,0.1

Type RM Length L Ch R = 1 ,9119    ,199,199,199
BEGIN DESCRIPTION:
Miller Creek 19.0
END DESCRIPTION:
XS GIS Cut Line= 3
      2286066.25      7194286.71        2285879.        7194310.
       2285403.4      7194550.42
#Sta/Elev= 30
  4811.3   929.5  4848.8  923.49  4858.9  918.84  4876.2  914.87  4881.3   910.9
  4889.1   908.2  4919.4  900.25  4929.4  895.05  4949.6  889.05  4962.1  886.52
  4969.8  887.69  4979.8  886.16    4995  881.97  4995.6  881.47    5000  881.97
  5013.9  884.77  5022.4  891.59  5030.6  892.63  5075.2  891.72  5103.1  895.29
  5142.1  894.49  5156.9   892.3  5169.9  894.54  5186.6  892.48  5192.2  893.94
  5242.4  895.78  5370.5  903.65  5459.7  906.98    5493  905.76  5532.9  909.11
#Mann= 4 ,-1 , 0
  4811.3     .12       0    4995     .07       0    5000     .12       0
  5242.4     .05       0
Bank Sta=4995,5000
XS Rating Curve= 0 ,0
Exp/Cntr=0.3,0.1

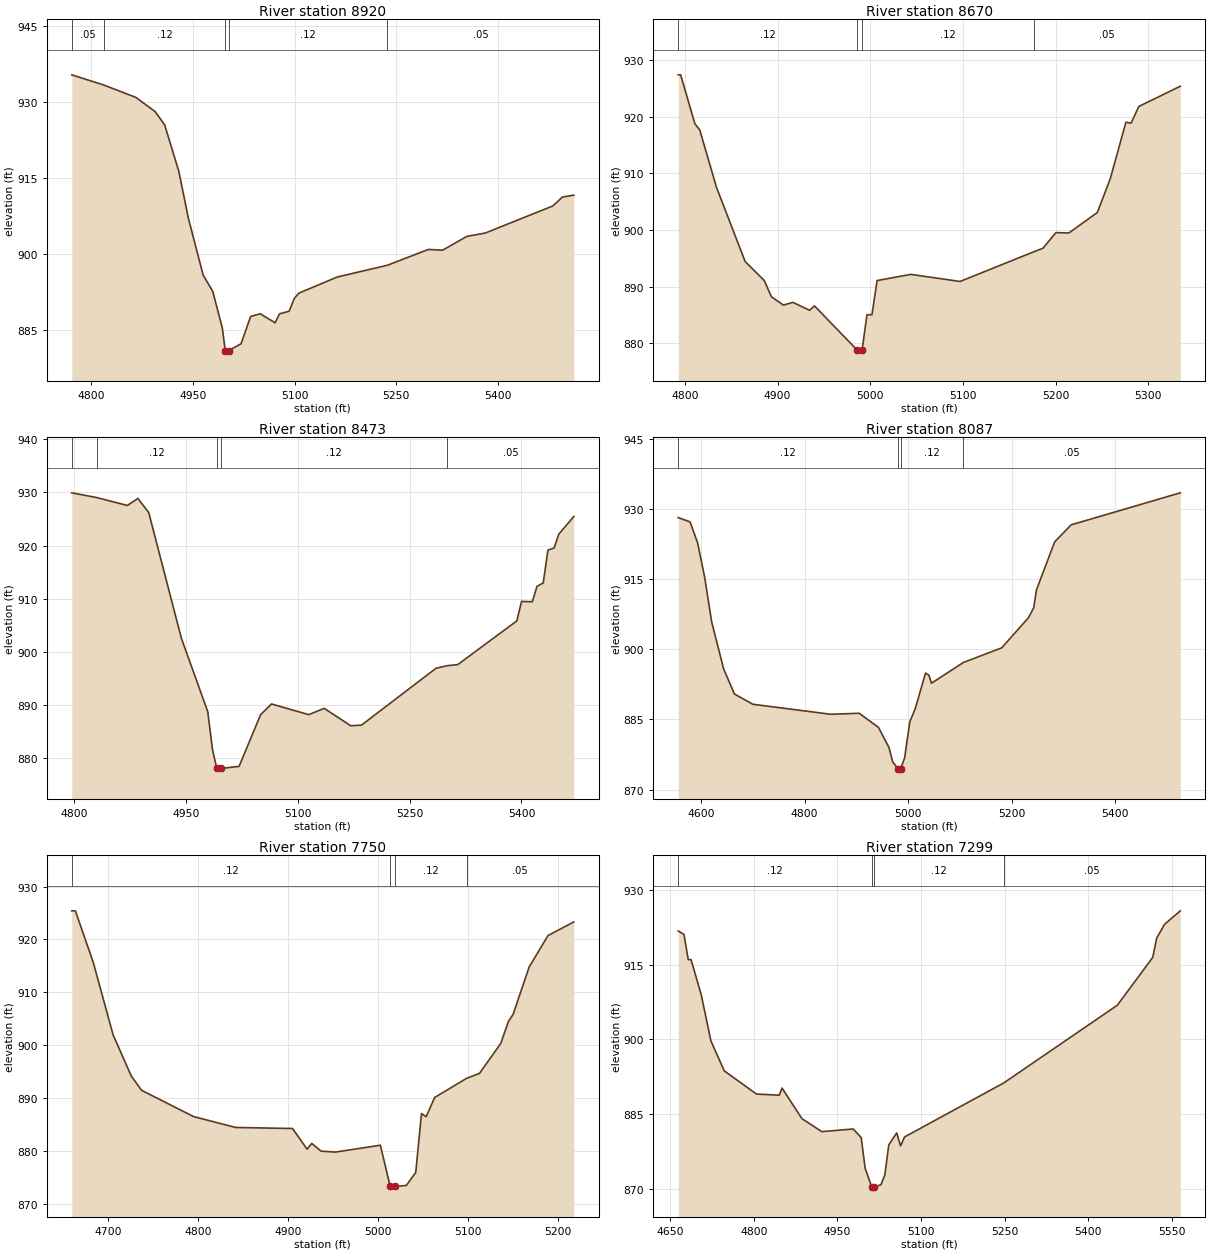
Type RM Length L Ch R = 1 ,8920    ,250,250,250
BEGIN DESCRIPTION:
Miller Creek 18.1
END DESCRIPTION:
XS GIS Cut Line= 2
      2285925.51      7194032.88      2285371.37      7194526.04
#Sta/Elev= 30
  4770.9  935.32  4818.2  933.31  4865.5  930.87  4893.9  928.09  4908.1  925.46
    4929  916.33  4943.2  907.01    4965  895.83  4979.2  892.59  4993.4  885.35
  4997.6  880.91  4998.3  880.41  5002.6  880.91    5021  882.25  5035.2  887.65
  5049.4  888.18  5071.2   886.4  5077.9  888.16  5092.1  888.68  5099.6  891.17
  5106.3  892.24  5163.2  895.43  5237.3  897.75  5297.8  900.87  5318.7  900.71
  5354.6  903.44  5382.2  904.12  5481.7  909.45  5495.9  911.21  5512.7  911.58
#Mann= 5 ,-1 , 0
  4770.9     .05       0  4818.2     .12       0  4997.6     .07       0
  5002.6     .12       0  5237.3     .05       0
Bank Sta=4997.6,5002.6
XS Rating Curve= 0 ,0
Exp/Cntr=0.3,0.1

Type RM Length L Ch R = 1 ,8670    ,197,197,197
BEGIN DESCRIPTION:
Miller Creek 18.0
END DESCRIPTION:
XS GIS Cut Line= 3
        2285779.        7194010.        2285579.        7194060.
      2285278.97      7194210.01
#Sta/Elev= 30
  4792.9  927.38  4795.5  927.38  4810.9  918.72  4816.1  917.66  4834.1  907.55
  4865.1  894.42  4885.7  891.07  4893.4   888.2  4906.3  886.73  4916.6  887.21
  4934.6  885.81  4939.8   886.6  4986.2  878.75  4986.8  878.25  4991.2  878.75
  4996.5  885.03  5001.9  885.03  5007.4  891.06  5043.8  892.15  5096.9   890.9
  5176.9  896.17  5186.3  896.76  5200.3  899.52  5214.3  899.46    5245  903.08
    5259  909.06  5275.8  919.01  5281.4  918.85  5289.7  921.79  5334.5  925.37
#Mann= 4 ,-1 , 0
  4792.9     .12       0  4986.2     .07       0  4991.2     .12       0
  5176.9     .05       0
Bank Sta=4986.2,4991.2
XS Rating Curve= 0 ,0
Exp/Cntr=0.3,0.1

Type RM Length L Ch R = 1 ,8473    ,386,386,386
BEGIN DESCRIPTION:
Miller Creek 17.2
END DESCRIPTION:
XS GIS Cut Line= 2
      2285768.72      7193764.56      2285229.44      7194168.36
#Sta/Elev= 30
  4796.6  929.92  4830.7  929.01  4871.2  927.54  4885.3  928.87  4899.9   926.2
  4943.7  902.54  4979.1  888.73  4985.4  881.61  4991.2  878.05  4991.8  877.55
  4996.2  878.05  5021.1  878.44    5050  888.17  5064.6  890.19  5114.6  888.18
  5135.4  889.36    5171  886.08  5185.4  886.21  5285.4  896.91  5300.3  897.39
  5314.6   897.6  5393.8  905.82  5400.1  909.48  5414.6  909.43  5420.9  912.33
  5429.2  912.95  5435.5  919.15  5443.8  919.53  5450.1  922.14  5470.3  925.47
#Mann= 5 ,-1 , 0
  4796.6     .05       0  4830.7     .12       0  4991.2     .07       0
  4996.2     .12       0  5300.3     .05       0
Bank Sta=4991.2,4996.2
XS Rating Curve= 0 ,0
Exp/Cntr=0.3,0.1

Type RM Length L Ch R = 1 ,8087    ,337,337,337
BEGIN DESCRIPTION:
Miller Creek 17.1
END DESCRIPTION:
XS GIS Cut Line= 4
      2285580.13      7193599.79      2285311.77      7193796.42
      2285338.34      7193977.09      2284889.33      7194048.82
#Sta/Elev= 30
  4555.8  928.13  4578.7  927.21  4593.3   922.7  4606.8  915.42  4620.4  905.83
  4643.5  895.81  4664.4  890.43  4699.9  888.24  4850.4   886.1  4905.5  886.31
  4942.6   883.3  4962.9  879.02  4970.2  875.91  4980.5  874.45  4981.2  873.95
  4985.6  874.45  4993.2   876.8  5003.3  884.53  5013.4  887.19  5033.6   894.9
    5040  894.48    5045  892.73  5106.7  897.17  5180.7  900.29  5232.5  906.74
  5242.6  908.86  5247.8  912.66  5283.1  922.95    5315  926.58  5525.8  933.42
#Mann= 4 ,-1 , 0
  4555.8     .12       0  4980.5     .07       0  4985.6     .12       0
  5106.7     .05       0
Bank Sta=4980.5,4985.6
XS Rating Curve= 0 ,0
Exp/Cntr=0.3,0.1

Type RM Length L Ch R = 1 ,7750    ,451,451,451
BEGIN DESCRIPTION:
Miller Creek 17.0
END DESCRIPTION:
XS GIS Cut Line= 3
      2285501.66       7193551.7        2285179.        7193660.
      2284971.63      7193726.11
#Sta/Elev= 30
  4659.2  925.41  4663.2  925.41  4683.1  915.64  4705.2  901.91  4725.3  894.16
  4736.8  891.44  4794.6  886.47  4841.3  884.41  4904.6  884.21  4920.7   880.3
    4926  881.39  4936.3  879.93  4952.2  879.75  5002.2  881.05  5013.1  873.24
  5013.8  872.74  5018.2  873.24    5031  873.44  5041.5  875.89  5047.9  887.04
  5053.1  886.45  5062.5  890.08  5097.9   893.7  5112.3  894.64    5136  900.32
  5144.5  904.48  5149.7  905.81  5167.5  914.76  5188.5  920.73  5217.2  923.31
#Mann= 4 ,-1 , 0
  4659.2     .12       0  5013.1     .07       0  5018.2     .12       0
  5097.9     .05       0
Bank Sta=5013.1,5018.2
XS Rating Curve= 0 ,0
Exp/Cntr=0.3,0.1

Type RM Length L Ch R = 1 ,7299    ,247,247,247
BEGIN DESCRIPTION:
Miller Creek 16.0
END DESCRIPTION:
XS GIS Cut Line= 3
      2285429.04      7193310.01      2285185.13       7193247.7
      2284728.98      7193710.02
#Sta/Elev= 30
  4664.2   921.8  4674.6   921.1  4682.1  916.05  4687.2  916.04  4705.5  908.98
  4722.9  899.71  4746.8   893.7  4804.6  889.04  4845.5  888.81  4850.6  890.23
  4886.3  884.09  4921.9  881.49  4978.4  882.02  4992.6  880.29  4999.7  874.15
  5011.3  870.44  5011.9  869.94  5016.4  870.44    5028   870.8    5035  872.78
  5042.1  878.82  5056.3  881.24  5063.3  878.63  5070.4  880.42  5248.6  891.28
  5452.3  906.88  5515.9  916.49    5523  920.36  5537.1  923.14  5565.4  925.85
#Mann= 4 ,-1 , 0
  4664.2     .12       0  5011.3     .07       0  5016.4     .12       0
  5248.6     .05       0
Bank Sta=5011.3,5016.4
XS Rating Curve= 0 ,0
Exp/Cntr=0.3,0.1

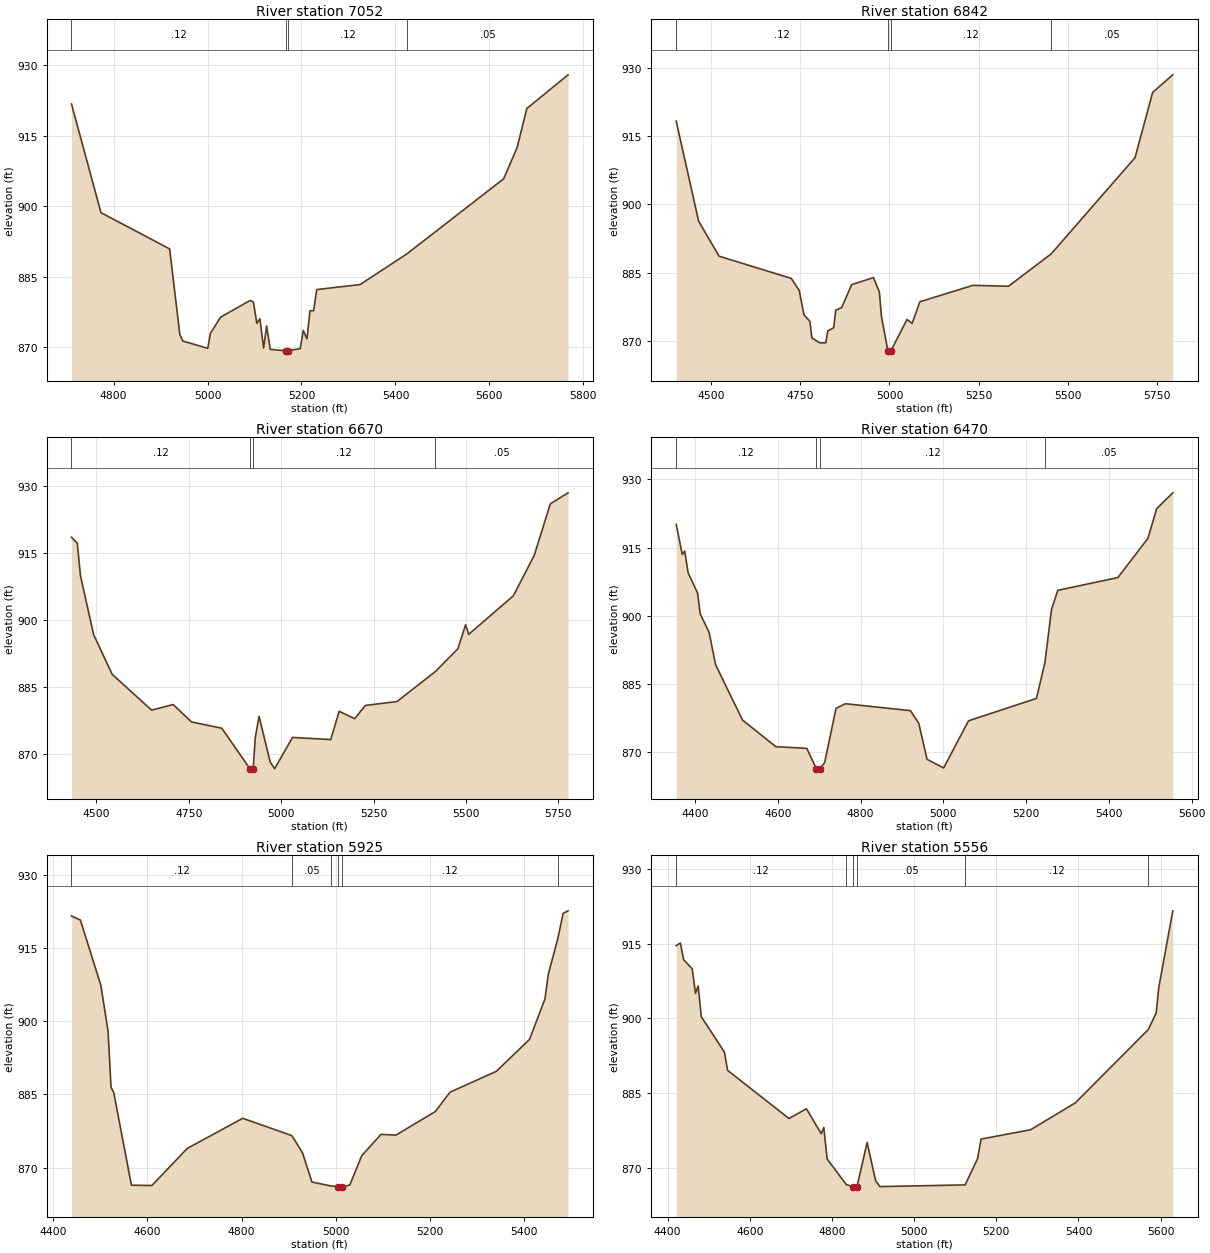
Type RM Length L Ch R = 1 ,7052    ,210,210,210
BEGIN DESCRIPTION:
Miller Creek 15.1
END DESCRIPTION:
XS GIS Cut Line= 3
      2285426.02      7193257.08       2285131.1      7193092.34
        2284667.      7193641.62
#Sta/Elev= 30
  4710.5  921.71  4773.2  898.61  4919.4   890.9  4941.1  872.69  4947.6  871.31
  5000.5  869.76  5006.2  872.96  5027.9  876.39  5090.7  879.94  5097.6  879.61
    5105  875.08  5111.5  876.05  5119.3  869.82  5125.8  874.52  5133.6  869.54
  5166.1  869.24  5166.8  868.74  5171.2  869.24  5197.3  869.69  5203.8  873.58
  5211.6  871.77  5218.1  877.75  5225.9  877.77  5232.4  882.25  5324.7  883.32
  5424.2  889.83  5630.2   905.8  5658.8   912.4  5679.6  920.75  5767.4  927.91
#Mann= 4 ,-1 , 0
  4710.5     .12       0  5166.1     .07       0  5171.2     .12       0
  5424.2     .05       0
Bank Sta=5166.1,5171.2
XS Rating Curve= 0 ,0
Exp/Cntr=0.3,0.1

Type RM Length L Ch R = 1 ,6842    ,172,172,172
BEGIN DESCRIPTION:
Miller Creek 15.0
END DESCRIPTION:
XS GIS Cut Line= 3
      2285424.66      7192453.09      2285153.59      7192985.49
       2284634.9      7193585.01
#Sta/Elev= 30
    4403  918.27  4465.9  896.28    4523   888.6    4725  883.73  4747.4   881.1
  4760.7  875.73  4777.3  874.28  4782.9  870.65  4805.2  869.55  4821.8  869.58
  4827.4  872.19    4844   872.9  4849.6  876.73  4866.3  877.32  4894.1  882.34
  4955.2   883.9  4971.8  880.75  4977.5  875.44  4995.6  867.81  4996.8  867.31
  5003.9  867.81  5049.2   874.7  5063.4  873.84  5085.3  878.59  5233.4  882.19
  5333.2     882    5453  889.12  5687.5  910.24  5736.9  924.57  5793.2  928.43
#Mann= 4 ,-1 , 0
    4403     .12       0  4995.6     .07       0  5003.9     .12       0
    5453     .05       0
Bank Sta=4995.6,5003.9
XS Rating Curve= 0 ,0
Exp/Cntr=0.3,0.1

Type RM Length L Ch R = 1 ,6670    ,200,200,200
BEGIN DESCRIPTION:
Miller Creek 14.1
END DESCRIPTION:
XS GIS Cut Line= 4
      2285259.53      7192417.26      2285031.81      7192731.83
        2284998.       7193030.2      2284606.09       7193554.5
#Sta/Elev= 30
    4433  918.46  4448.7  917.12  4457.2  909.91  4492.8  896.67    4543  887.79
  4649.7  879.76    4708  881.02  4757.4  877.13  4839.6  875.71    4916  866.61
  4917.2  866.11  4924.3  866.61  4930.2  873.64  4940.3  878.39  4970.5  868.14
  4982.5  866.66  5030.8  873.65  5134.2  873.18  5157.1  879.51  5198.8  877.85
    5228  880.81  5313.5  881.69  5417.2   888.4  5478.1   893.5    5499  898.87
  5507.3  896.72  5628.2  905.36  5684.5  914.37  5728.2  925.94  5776.2  928.41
#Mann= 4 ,-1 , 0
    4433     .12       0    4916     .07       0  4924.3     .12       0
  5417.2     .05       0
Bank Sta=4916,4924.3
XS Rating Curve= 0 ,0
Exp/Cntr=0.3,0.1

Type RM Length L Ch R = 1 ,6470    ,545,545,545
BEGIN DESCRIPTION:
Miller Creek 14.0
END DESCRIPTION:
XS GIS Cut Line= 4
      2285102.87      7192385.01      2284834.62      7192855.07
      2284821.84      7193034.95      2284562.93      7193437.65
#Sta/Elev= 30
  4354.1   920.1  4368.8  913.47  4374.6  914.22  4382.9  909.47  4405.9  904.95
    4412  900.45  4433.6  896.33  4449.4   889.2  4514.3  877.05  4594.9  871.18
  4669.8  870.81    4693   866.3  4694.2   865.8  4701.3   866.3    4713   867.7
  4740.4  879.61  4762.8  880.63  4920.3  879.11  4940.4  876.33  4960.4   868.4
  5000.5   866.5  5060.7  876.87  5224.9   881.8  5245.4  889.71  5261.2  901.32
  5276.4  905.57  5421.7  908.39  5494.4  917.03  5515.5  923.54  5554.4  927.03
#Mann= 4 ,-1 , 0
  4354.1     .12       0    4693     .07       0  4701.3     .12       0
  5245.4     .05       0
Bank Sta=4693,4701.3
XS Rating Curve= 0 ,0
Exp/Cntr=0.3,0.1

Type RM Length L Ch R = 1 ,5925    ,369,369,369
BEGIN DESCRIPTION:
Miller Creek 13.0
END DESCRIPTION:
XS GIS Cut Line= 4
      2285005.33      7192332.13      2284781.36      7192732.47
      2284600.72       7192712.5        2284479.      7193110.01
#Sta/Elev= 30
  4438.4  921.59  4457.4  920.74  4500.8  907.38  4516.2  897.96  4522.5  886.45
  4528.2  885.41  4565.9   866.4  4609.3  866.33  4684.6  873.93  4802.6  880.11
  4907.1  876.56  4929.7  873.05  4949.8  867.04  4990.1  866.24    5006  866.09
  5007.2  865.59  5014.3  866.09  5030.3  866.42  5055.8  872.46  5096.9  876.82
  5128.5  876.67  5212.2  881.49  5243.6  885.47  5341.9  889.73  5412.7   896.3
  5445.4  904.57  5452.8  909.75    5473  917.04  5484.1  922.12  5494.6  922.64
#Mann= 6 ,-1 , 0
  4438.4     .12       0  4907.1     .05       0  4990.1     .12       0
    5006     .07       0  5014.3     .12       0    5473     .05       0
Bank Sta=5006,5014.3
XS Rating Curve= 0 ,0
Exp/Cntr=0.3,0.1

Type RM Length L Ch R = 1 ,5556    ,217,217,217
BEGIN DESCRIPTION:
Miller Creek 12.0
END DESCRIPTION:
XS GIS Cut Line= 3
      2284856.41      7191972.16      2284615.94       7192273.7
      2284405.48      7193069.04
#Sta/Elev= 30
  4421.1   914.6  4431.2  915.14  4439.3  911.76  4460.1  909.95  4468.1  905.02
  4474.5  906.52  4482.3  900.33  4538.5  893.23  4546.2  889.57  4695.5  879.92
  4738.1  881.87    4774  876.86  4780.3  878.12  4788.4  871.79  4835.3  866.63
  4852.4  866.24  4853.6  865.74    4861  866.24  4885.7  875.09  4906.4  867.45
  4916.7  866.25  5124.2  866.59  5154.7  871.89    5163  875.78  5283.7  877.66
  5392.6  883.07    5570  897.78  5589.1   901.1  5595.2  906.07  5629.5  921.59
#Mann= 6 ,-1 , 0
  4421.1     .12       0  4835.3     .05       0  4852.4    .033       0
    4861     .05       0  5124.2     .12       0    5570     .05       0
Bank Sta=4852.4,4861
XS Rating Curve= 0 ,0
Exp/Cntr=0.3,0.1

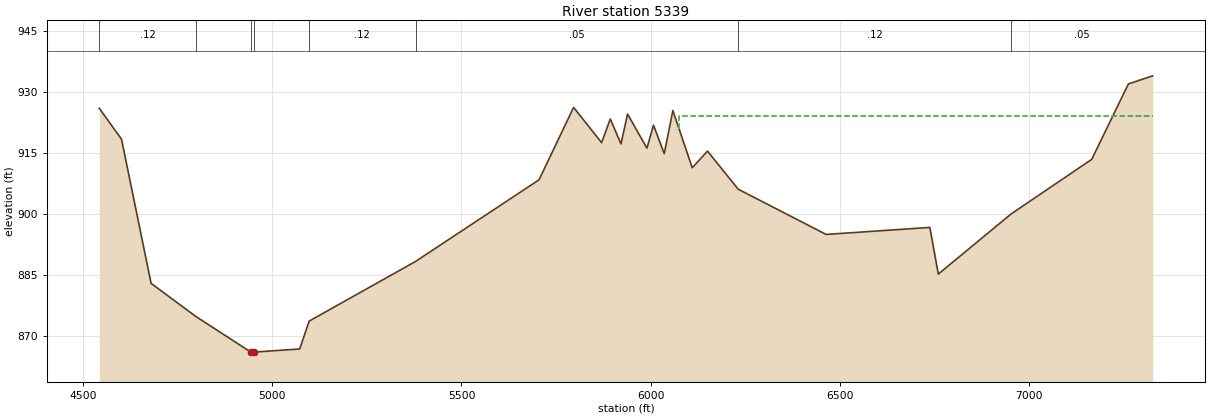
Type RM Length L Ch R = 1 ,5339    ,179,179,179
BEGIN DESCRIPTION:
Miller Creek 11.1
END DESCRIPTION:
XS GIS Cut Line= 3
      2284490.73      7192071.05      2284334.27      7192620.12
      2283396.65      7194622.99
#Sta/Elev= 30
  4543.5  925.92  4602.1  918.35  4680.2  883.02  4798.6  874.89  4943.6  866.17
  4944.9  865.67  4952.3  866.17  5072.7  866.93  5097.8  873.77  5378.6  888.38
  5704.9   908.4  5796.2  926.15  5870.2  917.51  5893.1  923.31  5921.4   917.2
  5938.7  924.52  5989.9  916.16  6007.2  921.79  6035.6  914.82  6058.4  925.38
  6109.6  911.34  6149.8  915.44  6231.1  906.09  6463.2  895.01  6737.2  896.73
  6759.5  885.29  6951.8  900.03  7164.8  913.42  7261.6   931.9  7325.9  933.89
#Mann= 8 ,-1 , 0
  4543.5     .12       0  4798.6     .05       0  4943.6    .033       0
  4952.3     .05       0  5097.8     .12       0  5378.6     .05       0
  6231.1     .12       0  6951.8     .05       0
#XS Ineff= 2 , 0
       0                  6074.9       0  924.05
Permanent Ineff=
       F       F
Bank Sta=4943.6,4952.3
XS Rating Curve= 0 ,0
Exp/Cntr=0.3,0.1