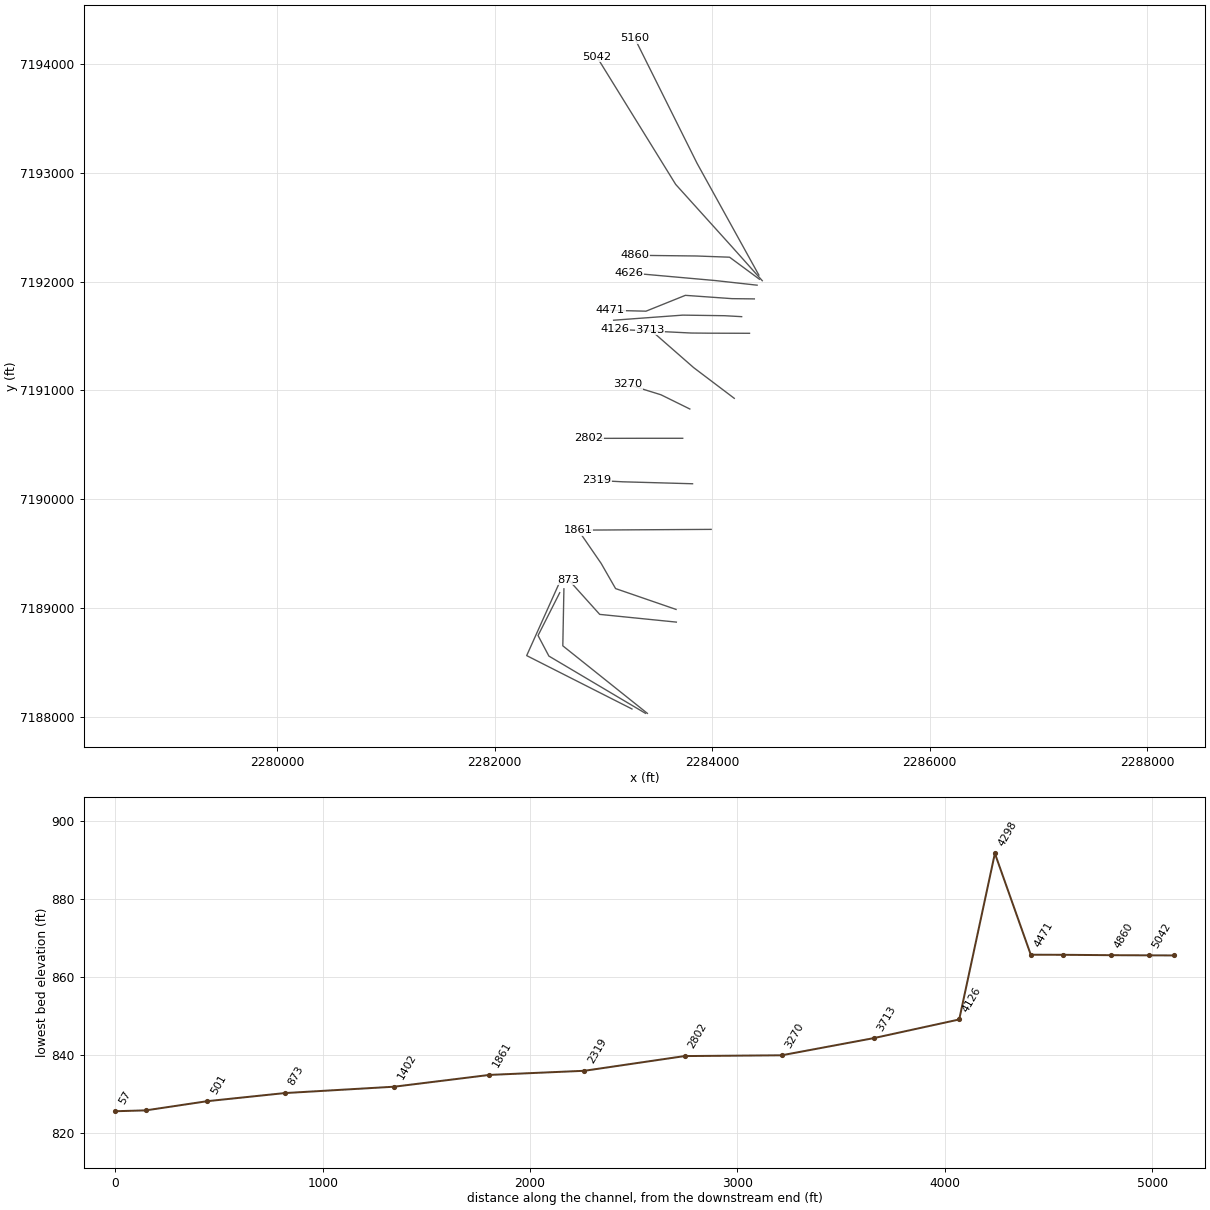
HEC-RAS study Miller Creek.prj: Miller Creek Base Level Engineering

--- Miller Creek.g01 (geometry) --- (continued)

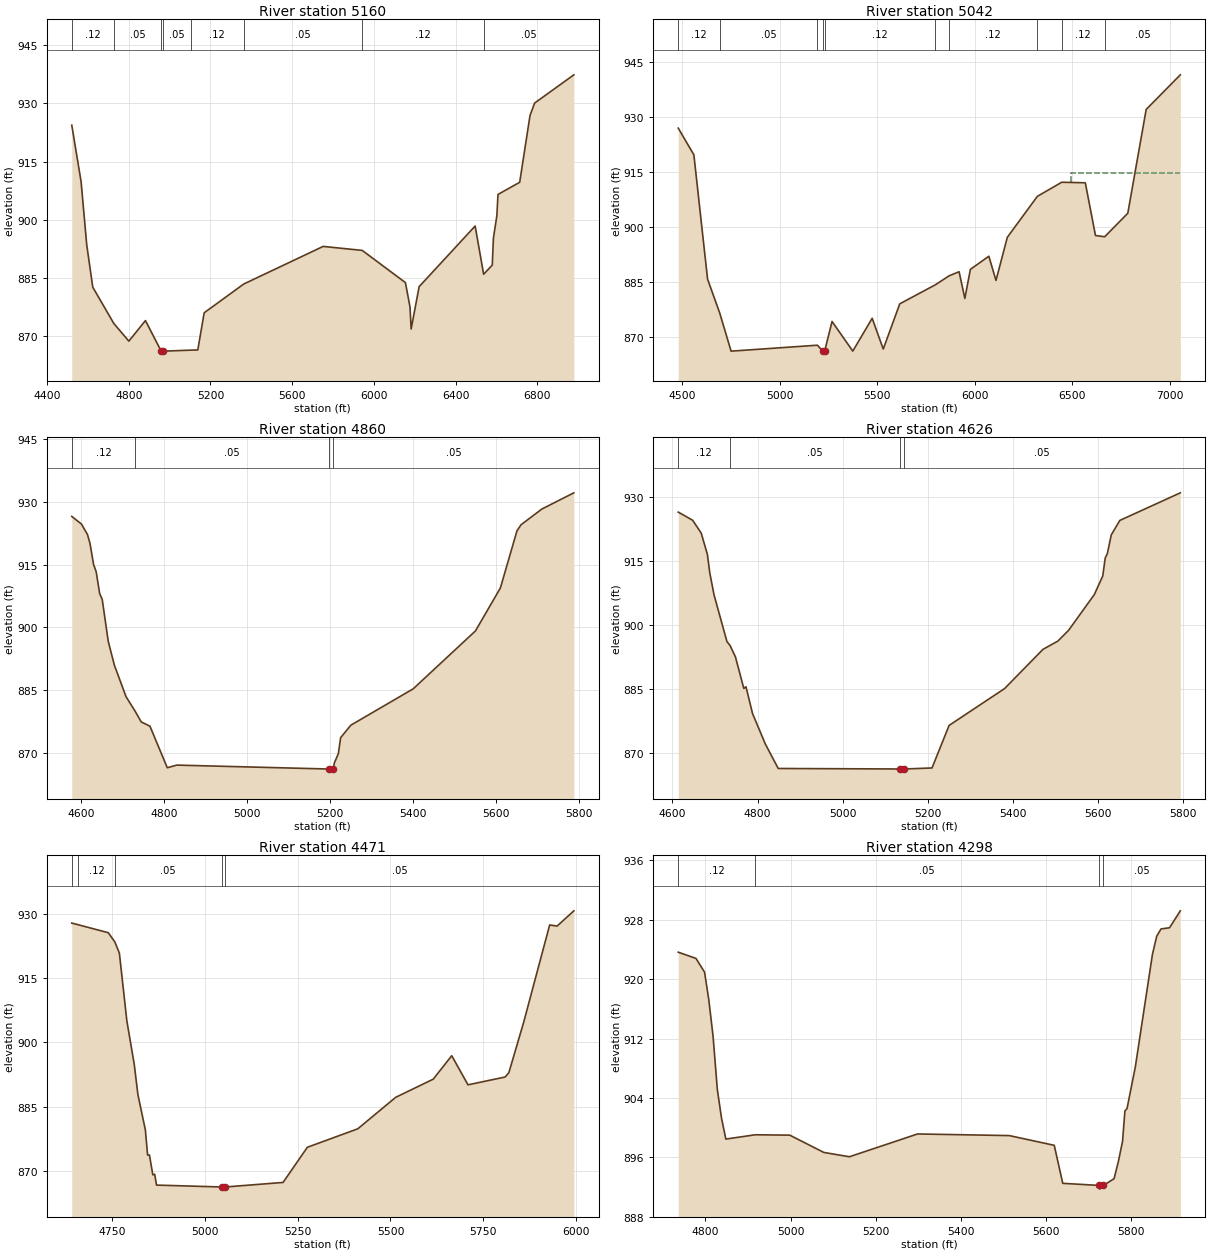
Type RM Length L Ch R = 1 ,5160    ,118,118,118
BEGIN DESCRIPTION:
Miller Creek 11.0
END DESCRIPTION:
XS GIS Cut Line= 3
        2284429.        7192060.      2283860.52      7193088.18
      2283287.97      7194236.71
#Sta/Elev= 30
  4521.2  924.37  4566.9  909.81  4594.5   893.5    4624   882.6  4727.2  873.23
  4800.7  868.68    4882  873.99    4959  866.09  4960.3  865.59  4967.7  866.09
  5103.8  866.36  5138.2   866.4  5169.5  875.99  5363.2  883.41    5752  893.11
  5943.3  892.08  6154.8  883.78  6177.2   877.5  6182.8  871.81    6222  882.73
  6496.1  898.37  6537.8  885.93    6580  888.29  6585.6  895.23  6602.4     901
    6608  906.51  6714.3  909.65  6764.7  926.83  6787.1  930.06  6979.4  937.36
#Mann= 8 ,-1 , 0
  4521.2     .12       0  4727.2     .05       0    4959    .033       0
  4967.7     .05       0  5103.8     .12       0  5363.2     .05       0
  5943.3     .12       0  6537.8     .05       0
#XS Ineff= 2 , 0
       0                  6496.1       0  898.37
Permanent Ineff=
       F       F
Bank Sta=4959,4967.7
XS Rating Curve= 0 ,0
Exp/Cntr=0.3,0.1

Type RM Length L Ch R = 1 ,5042    ,182,182,182
BEGIN DESCRIPTION:
Miller Creek 10.15
END DESCRIPTION:
XS GIS Cut Line= 4
      2284460.32      7192008.64      2284184.19      7192317.62
      2283664.18      7192894.04      2282938.05      7194068.72
#Sta/Elev= 30
  4481.1  926.97  4561.2  919.69  4631.4  885.79  4693.7  876.53  4751.8  866.15
    5194  867.77  5222.1  866.11  5223.4  865.61  5230.8  866.11    5269  874.24
  5375.2  866.16  5474.5  875.11  5531.3  866.72  5615.8  879.05  5797.4  884.22
    5869   886.7  5919.6  887.81  5949.2  880.52  5977.5  888.45  6072.1  892.03
  6108.7  885.43  6166.7  897.19  6320.4  908.35  6445.5  912.21  6566.2  912.06
  6618.3  897.68  6665.6  897.35  6783.9  903.76    6878  932.06  7052.8   941.5
#Mann= 10 ,-1 , 0
  4481.1     .12       0  4693.7     .05       0    5194     .12       0
  5222.1    .033       0  5230.8     .12       0  5797.4     .05       0
    5869     .12       0  6320.4     .05       0  6445.5     .12       0
  6665.6     .05       0
#XS Ineff= 2 , 0
       0                  6492.9       0  914.81
Permanent Ineff=
       F       F
Bank Sta=5222.1,5230.8
XS Rating Curve= 0 ,0
Exp/Cntr=0.3,0.1

Type RM Length L Ch R = 1 ,4860    ,234,234,234
BEGIN DESCRIPTION:
Miller Creek 10.1
END DESCRIPTION:
XS GIS Cut Line= 4
      2284434.05      7192022.25       2284159.7      7192224.76
      2283853.24      7192235.91      2283292.13      7192242.16
#Sta/Elev= 30
  4578.3  926.53  4601.5  924.72  4616.1  922.21  4622.3  920.03  4630.8  915.03
    4637  913.35  4645.4  908.12  4651.6   906.7  4666.2  896.63  4680.9  890.97
  4708.9  883.46  4731.5  879.87  4745.6   877.4  4766.5   876.4  4808.3  866.46
  4831.2  867.09    5198  866.15  5199.4  865.65  5208.1  866.15  5210.2  867.52
  5220.2  869.85  5225.6  873.64  5250.2  876.63  5400.2  885.31  5550.2  899.16
  5610.2  909.42  5650.2  923.09  5660.2  924.56  5710.2   928.3  5787.1  932.17
#Mann= 4 ,-1 , 0
  4578.3     .12       0  4731.5     .05       0    5198    .033       0
  5208.1     .05       0
Bank Sta=5198,5208.1
XS Rating Curve= 0 ,0
Exp/Cntr=0.3,0.1

Type RM Length L Ch R = 1 ,4626    ,155,155,155
BEGIN DESCRIPTION:
Miller Creek 10.0
END DESCRIPTION:
XS GIS Cut Line= 3
      2284412.77      7191967.51        2284029.        7192010.
      2283237.36      7192080.62
#Sta/Elev= 30
  4613.5   926.4  4647.5  924.48  4667.6  921.47  4682.1  916.48  4687.7  912.17
  4697.8  906.98    4728   896.1  4735.5  895.15  4748.1  892.48  4767.8  885.09
  4772.8  885.51  4788.3  879.23  4818.5  872.07  4848.7  866.37  5135.1  866.25
  5136.5  865.75  5145.2  866.25  5210.4  866.49  5250.6  876.45  5381.1  885.08
  5471.5  894.27  5506.3  896.19  5531.7  898.73    5592  907.07    5612  911.43
  5617.8  915.65  5622.8  916.69  5632.1  921.08  5652.2  924.45  5794.4  930.91
#Mann= 4 ,-1 , 0
  4613.5     .12       0  4735.5     .05       0  5135.1    .033       0
  5145.2     .05       0
Bank Sta=5135.1,5145.2
XS Rating Curve= 0 ,0
Exp/Cntr=0.3,0.1

Type RM Length L Ch R = 1 ,4471    ,173,173,173
BEGIN DESCRIPTION:
Miller Creek 9.2
END DESCRIPTION:
XS GIS Cut Line= 5
      2284387.33      7191841.41       2284182.1      7191843.72
      2283753.32      7191874.13       2283391.4      7191728.53
       2283063.9      7191736.41
#Sta/Elev= 30
  4641.3   927.8  4658.8  927.41  4739.6  925.56  4757.4  923.41  4769.6  920.79
  4789.6  905.08  4809.6  894.88  4819.6  887.76  4839.6  879.58  4845.6  873.72
  4850.6  873.72  4859.7   869.1  4864.7  869.24  4869.7  866.71  5045.1  866.27
  5046.5  865.77  5055.2  866.27  5210.6  867.33  5276.1  875.53  5411.9  879.83
    5514  887.17  5615.2  891.41  5665.1  896.88  5708.9  890.09  5808.9  891.91
    5819  892.92    5859   904.7    5929  927.37    5949   927.1  5994.1  930.66
#Mann= 5 ,-1 , 0
  4641.3     .05       0  4658.8     .12       0  4757.4     .05       0
  5045.1    .033       0  5055.2     .05       0
Bank Sta=5045.1,5055.2
XS Rating Curve= 0 ,0
Exp/Cntr=0.3,0.1

Type RM Length L Ch R = 1 ,4298    ,172,172,172
BEGIN DESCRIPTION:
Miller Creek 9.1
END DESCRIPTION:
XS GIS Cut Line= 4
      2284270.68      7191678.12      2284112.65      7191686.95
      2283729.14      7191692.27      2283093.78      7191645.48
#Sta/Elev= 30
  4736.4  923.65  4778.1  922.81  4798.2  920.96  4808.2  917.23  4818.2  912.33
  4828.2  905.15  4838.2  901.24  4848.2  898.48  4917.2  899.06  4998.3  899.01
  5078.3  896.68  5138.3   896.1  5298.4  899.17  5513.7  898.95  5619.3  897.64
  5639.3  892.52  5724.5  892.24  5725.9  891.74  5734.6  892.24  5759.7  893.14
  5769.7  895.41  5779.7  898.19  5785.2  902.26  5790.2  902.59  5809.8  908.24
  5849.9  923.37  5859.9   925.8    5870  926.78    5890  926.94  5915.3  929.22
#Mann= 4 ,-1 , 0
  4736.4     .12       0  4917.2     .05       0  5724.5    .033       0
  5734.6     .05       0
Bank Sta=5724.5,5734.6
XS Rating Curve= 0 ,0
Exp/Cntr=0.3,0.1

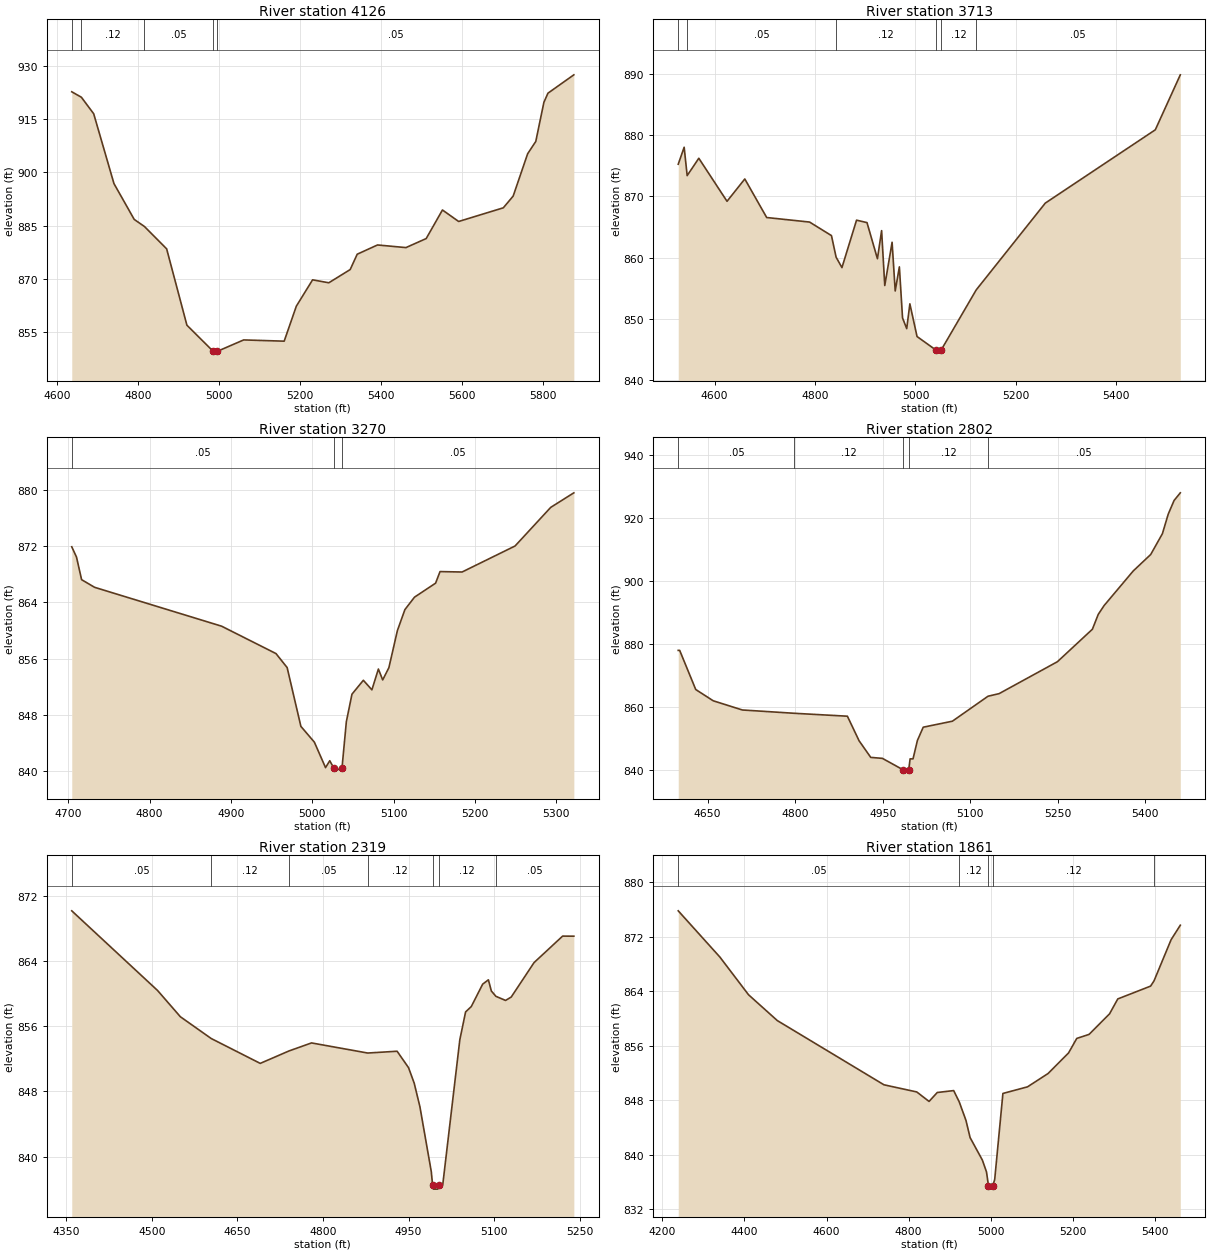
Type RM Length L Ch R = 1 ,4126    ,413,413,413
BEGIN DESCRIPTION:
Miller Creek 9.0
END DESCRIPTION:
XS GIS Cut Line= 4
       2284343.1      7191525.27      2283980.96      7191526.14
      2283806.65      7191527.67      2283105.17      7191562.45
#Sta/Elev= 30
  4636.3  922.62    4660  921.09  4690.4  916.45  4740.4  896.82  4790.4  886.75
  4815.6  884.76  4870.4  878.48  4920.4  857.02  4985.3  849.67  4986.7  849.17
  4995.4  849.67  5060.4  852.88  5160.4  852.53  5190.4  862.37  5230.5  869.77
  5270.5  868.94  5323.2  872.65  5340.6  876.97  5390.7  879.57  5460.8  878.83
  5510.8  881.37  5550.9   889.4  5590.9  886.17  5701.1  890.01  5725.4  893.31
  5761.1   905.2  5781.2  908.67  5801.2  919.66  5811.2  922.23  5875.1  927.39
#Mann= 5 ,-1 , 0
  4636.3     .05       0    4660     .12       0  4815.6     .05       0
  4985.3    .033       0  4995.4     .05       0
Bank Sta=4985.3,4995.4
XS Rating Curve= 0 ,0
Exp/Cntr=0.3,0.1

Type RM Length L Ch R = 1 ,3713    ,443,443,443
BEGIN DESCRIPTION:
Miller Creek 8.0
END DESCRIPTION:
XS GIS Cut Line= 3
      2284202.84      7190927.41        2283829.        7191210.
      2283429.03      7191559.98
#Sta/Elev= 30
  4527.4  875.24  4539.2  878.01  4545.2  873.38  4568.4  876.21  4624.6  869.18
    4660  872.83  4703.6  866.53    4789  865.79  4832.6  863.58  4841.9  860.05
  4853.5  858.35  4882.6   866.1  4903.4   865.7  4924.2   859.8  4932.5  864.39
  4938.8  855.42  4953.4  862.49  4959.6  854.53  4967.9  858.47  4974.2  850.13
  4982.5  848.38  4988.8  852.43  5003.1  847.09  5040.7  844.88  5042.1  844.38
  5051.1  844.88  5120.9   854.7  5258.5  868.88  5477.7  880.86  5527.5  889.84
#Mann= 6 ,-1 , 0
  4527.4     .12       0  4545.2     .05       0  4841.9     .12       0
  5040.7     .07       0  5051.1     .12       0  5120.9     .05       0
#XS Ineff= 2 , 0
       0  4882.6   866.1               0
Permanent Ineff=
       F       F
Bank Sta=5040.7,5051.1
XS Rating Curve= 0 ,0
Exp/Cntr=0.3,0.1

Type RM Length L Ch R = 1 ,3270    ,468,468,468
BEGIN DESCRIPTION:
Miller Creek 7.0
END DESCRIPTION:
XS GIS Cut Line= 3
      2283794.23       7190829.3        2283529.        7190960.
      2283221.91      7191055.55
#Sta/Elev= 30
  4704.3  871.92  4710.1  870.46  4716.4  867.24  4732.4  866.15  4888.5  860.62
  4955.4  856.72  4969.1  854.73    4986  846.36  5002.6  844.11  5016.3  840.49
  5021.5  841.47  5026.2  840.49  5027.7  839.99  5036.6  840.49  5041.9  847.03
  5048.8  850.94  5062.8  852.92  5073.3  851.56  5081.3  854.52  5086.6  852.97
  5094.2  854.72  5104.7  860.01  5113.9  862.98  5125.7  864.75  5151.6  866.74
  5157.1  868.39  5184.2  868.33  5249.3  872.03  5293.2  877.53  5321.6   879.6
#Mann= 3 ,-1 , 0
  4704.3     .05       0  5026.2    .033       0  5036.6     .05       0
Bank Sta=5026.2,5036.6
XS Rating Curve= 0 ,0
Exp/Cntr=0.3,0.1

Type RM Length L Ch R = 1 ,2802    ,483,483,483
BEGIN DESCRIPTION:
Miller Creek 6.0
END DESCRIPTION:
XS GIS Cut Line= 3
        2283729.        7190560.        2283329.        7190560.
       2282868.3      7190559.31
#Sta/Elev= 30
  4599.6  878.02  4602.1  878.02  4629.6  865.63  4659.6  862.06  4709.6  859.15
  4798.9   858.1  4889.6  857.18  4909.6  849.41  4929.6  844.14  4949.6  843.83
  4984.3  840.29  4985.8  839.79  4994.8  840.29  4997.1  843.67  5002.1  843.67
  5009.6  849.49  5019.6   853.7  5069.6   855.6  5130.7  863.51  5149.6  864.32
  5249.6  874.43  5309.6  884.72  5319.6  889.41  5329.6   892.2  5379.6  903.17
  5409.6  908.39  5429.6  914.97  5439.6  921.17  5449.6  925.48  5460.3  927.91
#Mann= 5 ,-1 , 0
  4599.6     .05       0  4798.9     .12       0  4984.3     .07       0
  4994.8     .12       0  5130.7     .05       0
Bank Sta=4984.3,4994.8
XS Rating Curve= 0 ,0
Exp/Cntr=0.3,0.1

Type RM Length L Ch R = 1 ,2319    ,458,458,458
BEGIN DESCRIPTION:
Miller Creek 5.0
END DESCRIPTION:
XS GIS Cut Line= 3
      2283819.43       7190142.1        2283179.        7190160.
      2282939.31      7190172.56
#Sta/Elev= 30
  4359.3  870.15  4509.8  860.38  4549.8  857.16  4603.9  854.49  4689.9  851.44
  4740.5  852.97  4779.9  853.95  4878.4  852.71    4930  852.93    4950  850.92
    4960  849.01    4970  846.12    4990  838.14  4992.2  836.52  4993.7  836.02
  5001.3  836.02  5002.7  836.52    5010  836.53    5040  854.34  5050.1  857.75
  5060.1  858.41  5080.1  861.16  5090.1  861.69  5095.3  860.32  5103.2  859.67
  5120.2  859.16  5130.2  859.58  5170.2   863.8  5220.3  867.05    5240  867.04
#Mann= 7 ,-1 , 0
  4359.3     .05       0  4603.9     .12       0  4740.5     .05       0
  4878.4     .12       0  4992.2     .07       0  5002.7     .12       0
  5103.2     .05       0
Bank Sta=4992.2,5002.7
XS Rating Curve= 0 ,0
Exp/Cntr=0.3,0.1

Type RM Length L Ch R = 1 ,1861    ,459,459,459
BEGIN DESCRIPTION:
Miller Creek 4.0
END DESCRIPTION:
XS GIS Cut Line= 3
      2283990.42      7189722.69      2282910.97      7189716.52
      2282766.65        7189715.
#Sta/Elev= 30
  4238.6  875.77    4340     869    4410  863.46    4480  859.68    4740  850.26
    4820  849.21    4850  847.82    4870  849.13    4910  849.41  4923.5  847.76
    4940  845.03    4950  842.52    4980  839.21    4990  837.48  4994.8  835.46
  4996.2  834.96  5005.3  835.46    5010  836.38    5030  848.99    5090  849.96
    5140  851.91    5190  854.93    5210  857.06    5240  857.65    5290  860.67
    5310  862.85    5390  864.73  5398.4  865.51    5440  871.54  5462.4  873.66
#Mann= 5 ,-1 , 0
  4238.6     .05       0  4923.5     .12       0  4994.8     .07       0
  5005.3     .12       0  5398.4     .05       0
Bank Sta=4994.8,5005.3
XS Rating Curve= 0 ,0
Exp/Cntr=0.3,0.1

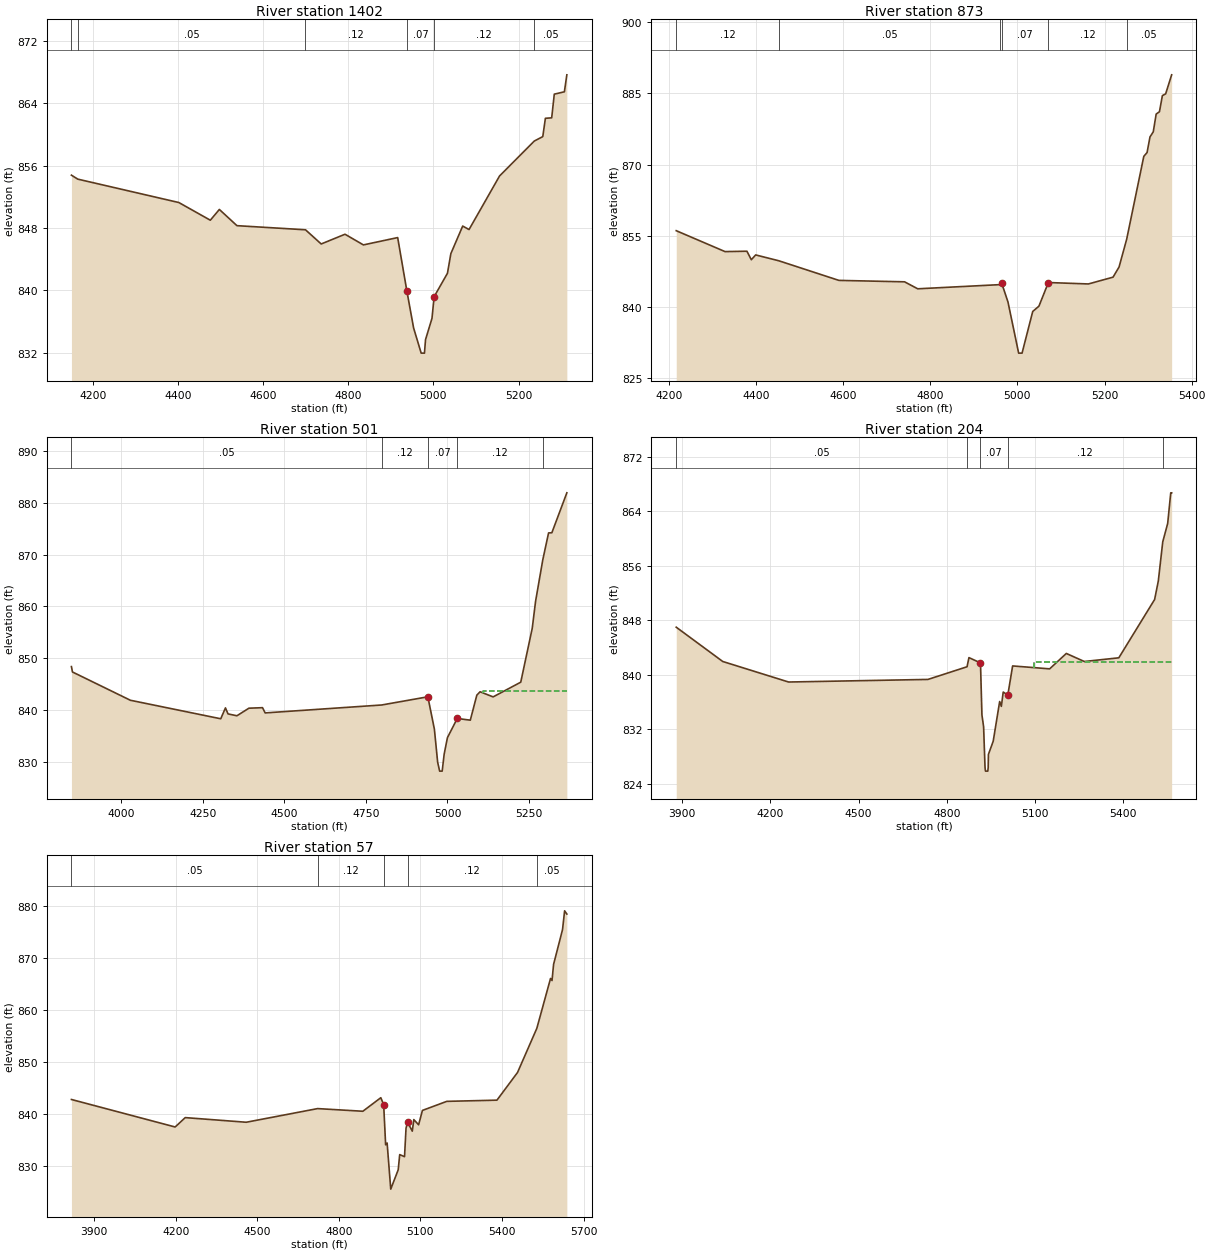
Type RM Length L Ch R = 1 ,1402    ,529,529,529
BEGIN DESCRIPTION:
Miller Creek 3.0
END DESCRIPTION:
XS GIS Cut Line= 4
      2283667.44      7188986.93      2283111.71      7189178.45
        2282979.        7189410.      2282803.88      7189664.35
#Sta/Elev= 30
  4149.9  854.78  4164.9  854.27  4402.1  851.27  4476.1     849  4497.3  850.38
  4538.6   848.3  4699.6  847.77  4736.5  845.95  4792.4   847.2  4835.6  845.83
  4916.1  846.77  4937.7  839.91  4953.5  835.17  4971.3  831.94    4979  831.94
  4981.5  833.67  4996.7  836.41  5001.7  839.18    5033  842.19    5041  844.71
  5068.8  848.25  5083.7   847.8  5155.4  854.68  5236.9  859.16  5256.9  859.73
    5263  862.08  5277.8  862.14  5283.9  865.18  5307.6  865.48  5313.4  867.66
#Mann= 6 ,-1 , 0
  4149.9     .12       0  4164.9     .05       0  4699.6     .12       0
  4937.7     .07       0  5001.7     .12       0  5236.9     .05       0
Bank Sta=4937.7,5001.7
XS Rating Curve= 0 ,0
Exp/Cntr=0.3,0.1

Type RM Length L Ch R = 1 ,873     ,372,372,372
BEGIN DESCRIPTION:
Miller Creek 2.0
END DESCRIPTION:
XS GIS Cut Line= 3
      2283670.39      7188870.24       2282965.9      7188941.24
      2282679.01      7189259.99
#Sta/Elev= 30
  4217.2  856.07  4329.2  851.67  4379.4  851.75  4389.5  849.96  4399.5  850.97
  4452.6  849.74  4590.5  845.61  4741.2  845.31  4771.4  843.84  4960.7  844.72
  4964.3  844.98  4978.5  841.06    5003   830.3  5010.8   830.3  5035.3  839.07
  5049.5  840.18  5071.2  845.16  5163.1  844.86  5219.6  846.29  5233.4  848.42
  5250.9  854.28  5290.2  871.72  5297.7  872.52  5304.4  875.81  5311.9  876.88
  5318.6  880.63  5326.1  881.11  5332.8   884.5  5340.3  884.87  5354.1  888.88
#Mann= 6 ,-1 , 0
  4217.2     .12       0  4452.6     .05       0  4960.7     .12       0
  4964.3     .07       0  5071.2     .12       0  5250.9     .05       0
Bank Sta=4964.3,5071.2
XS Rating Curve= 0 ,0
Exp/Cntr=0.3,0.1

Type RM Length L Ch R = 1 ,501     ,297,297,297
BEGIN DESCRIPTION:
Miller Creek 1.0
END DESCRIPTION:
XS GIS Cut Line= 3
      2283404.12      7188031.24      2282626.64      7188652.21
      2282636.73      7189175.98
#Sta/Elev= 30
  3847.2   848.4  3850.3  847.36    4028   841.9    4305  838.33  4319.4  840.43
  4327.3  839.27  4354.6  838.91  4391.3  840.37  4433.1  840.47  4441.1  839.46
  4798.5  840.99    4940  842.57    4960  836.32    4970  829.95  4976.1  828.23
  4983.9  828.23    4990  831.52    5000  834.69  5030.1  838.39  5070.1  838.06
  5090.1  842.89  5100.1  843.54  5140.1  842.55  5224.8  845.39  5260.1  855.82
  5270.1  860.95  5292.4  869.02  5310.1  874.19  5320.1  874.21  5366.1  881.92
#Mann= 5 ,-1 , 0
  3847.2     .05       0  4798.5     .12       0    4940     .07       0
  5030.1     .12       0  5292.4     .05       0
#XS Ineff= 2 , 0
       0                  5110.1       0  843.76
Permanent Ineff=
       F       F
Bank Sta=4940,5030.1
XS Rating Curve= 0 ,0
Exp/Cntr=0.3,0.1

Type RM Length L Ch R = 1 ,204     ,147,147,147
BEGIN DESCRIPTION:
Miller Creek 0.9
END DESCRIPTION:
XS GIS Cut Line= 4
      2283386.21      7188031.83      2282498.64      7188558.03
      2282398.94      7188746.92      2282598.35      7189140.48
#Sta/Elev= 30
  3879.2  846.98  4037.6  841.95  4261.7  838.94  4736.2  839.32  4869.3  841.18
  4875.7  842.52    4915  841.74  4919.9  834.12  4925.6  832.39  4930.5  826.37
    4932  825.87  4939.8  825.87  4941.2  826.37    4942  828.32  4958.3  830.26
  4980.3  836.08    4986  835.37  4992.4  837.47    5008  837.02  5024.4   841.3
  5150.5  840.87  5207.2  843.13  5268.4  841.95  5385.9  842.49  5507.8  851.04
  5520.4  853.76  5535.5   859.5  5552.3   862.2  5562.7  866.69  5565.8  866.69
#Mann= 5 ,-1 , 0
  3879.2     .05       0  4869.3     .12       0    4915     .07       0
    5008     .12       0  5535.5     .05       0
#XS Ineff= 2 , 0
       0                  5096.1       0  841.89
Permanent Ineff=
       F       F
Bank Sta=4915,5008
XS Rating Curve= 0 ,0
Exp/Cntr=0.3,0.1

Type RM Length L Ch R = 1 ,57      ,0,0,0
BEGIN DESCRIPTION:
Miller Creek 0.8
END DESCRIPTION:
XS GIS Cut Line= 3
      2283262.42       7188071.7      2282294.47      7188562.31
      2282596.42      7189234.52
#Sta/Elev= 30
  3816.6  842.86    4198  837.58  4235.2  839.38  4459.5  838.49    4722  841.11
  4888.4   840.6  4954.5   843.2    4965  841.87  4972.2  834.16  4977.7   834.5
    4991  825.65  5018.5  829.37    5024  832.28  5041.7  831.88  5047.2  837.33
  5052.7  838.52  5070.3  836.78  5075.8     839  5093.5     838  5107.5  840.76
  5197.1   842.5  5381.6  842.73  5457.4  848.05  5528.3  856.52  5578.7  866.09
  5584.2   865.7  5589.9   868.8  5622.8  875.47  5630.5  879.08  5638.7  878.46
#Mann= 5 ,-1 , 0
  3816.6     .05       0    4722     .12       0    4965     .07       0
  5052.7     .12       0  5528.3     .05       0
Bank Sta=4965,5052.7
XS Rating Curve= 0 ,0
Exp/Cntr=0.3,0.1

Chan Stop Cuts=-1
Use User Specified Reach Order=0
Composite Channel Slope=5