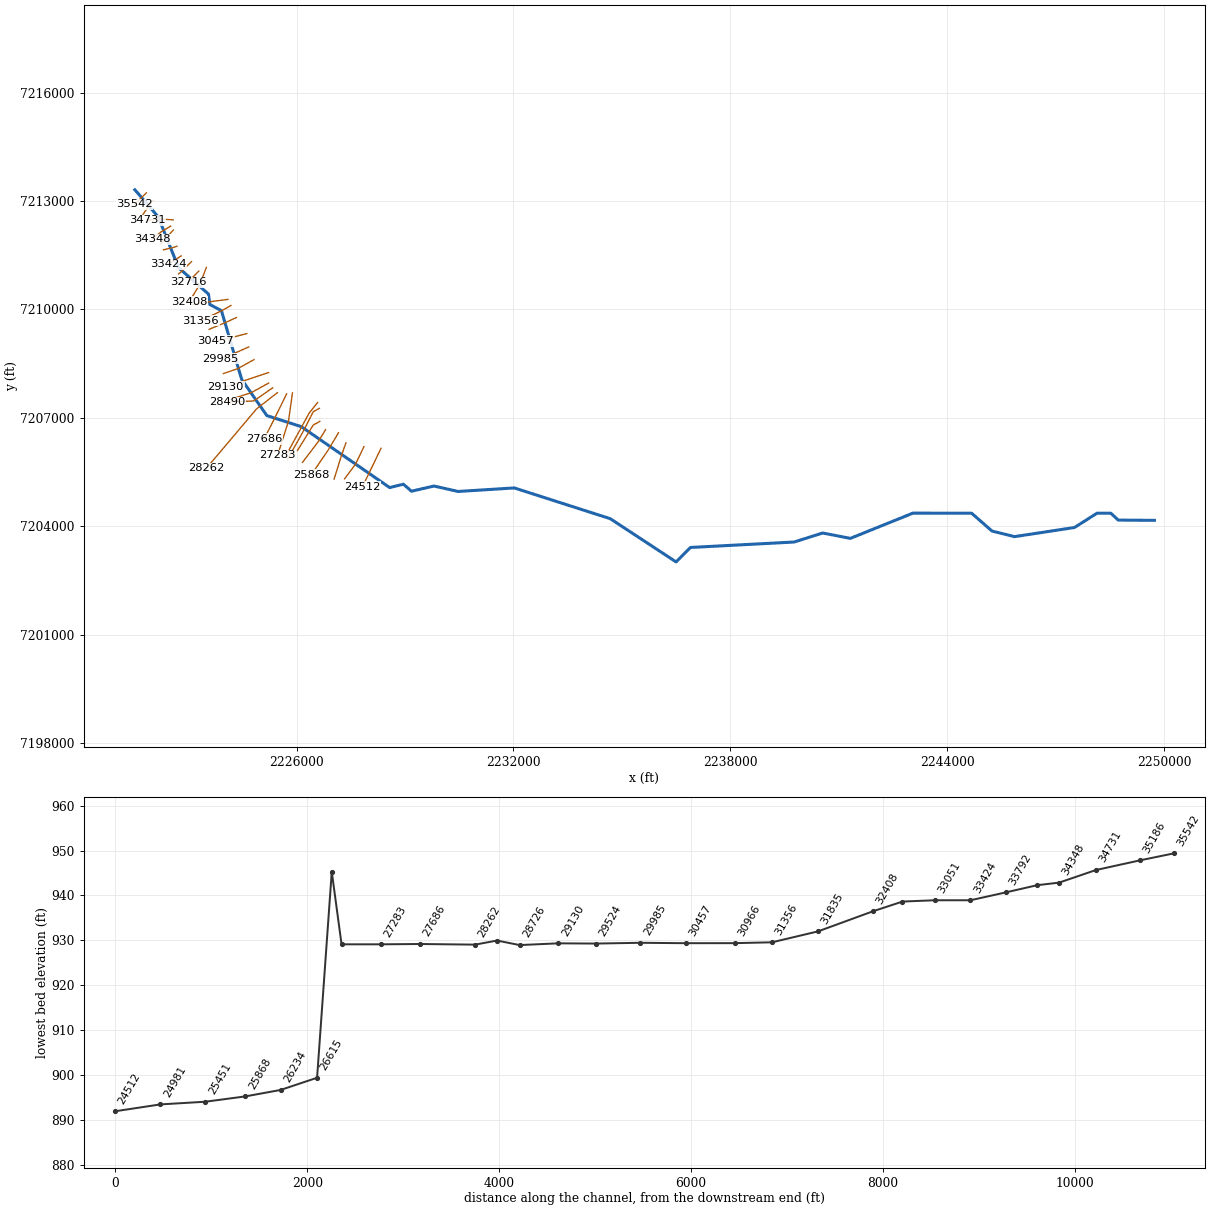
--- Panther Creek.prj (project) ---

Proj Title=Panther Creek Base Level Engineering
Current Plan=p01
Default Exp/Contr=0.3,0.1
English Units
Geom File=g01
Flow File=f01
Plan File=p01
Y Axis Title=Elevation
X Axis Title(PF)=Main Channel Distance
X Axis Title(XS)=Station
BEGIN DESCRIPTION:
Panther Creek
END DESCRIPTION:
DSS Export Rating Curves= 0
DSS Export Rating Curve Sorted= 0
DSS Export Volume Flow Curves= 0
DXF OffsetX= 0
DXF OffsetY= 0
DXF ScaleX= 1
DXF ScaleY= 10

--- Panther Creek.p01 (plan) ---

Plan Title=Multiple Run
Short Identifier=Multiple
Geom File=g01
Flow File=f01
Subcritical Flow
K Sum by GR= 0
Std Step Tol= 0.01
Critical Tol= 0.01
Num of Std Step Trials= 20
Max Error Tol= 0.3
Flow Tol Ratio= 0.001
Split Flow NTrial= 30
Split Flow Tol= 0.02
Split Flow Ratio= 0.02
Log Output Level= 0
Friction Slope Method= 1
Unsteady Friction Slope Method= 2
Unsteady Bridges Friction Slope Method= 1
Parabolic Critical Depth
Global Vel Dist=  1 , 1 , 1
Global Log Level= 0
CheckData=True
Encroach Param= -1, 0, 0, 0
BEGIN DESCRIPTION:
Multiple Run
END DESCRIPTION:

--- Panther Creek.f01 (steady flow) ---

Flow Title=Multiple
Program Version=4.10
Number of Profiles= 7
Profile Names=10-year,25-year,50-year,1pct_min,100-year,1pct_plu,500-year
River Rch & RM=Panther Creek,Reach-1         ,35542
     682     956    1188     733    1463    2919    2225
River Rch & RM=Panther Creek,Reach-1         ,32408
     913    1300    1631    1015    2026    4042    3136
River Rch & RM=Panther Creek,Reach-1         ,30457
     943    1341    1681    1045    2086    4162    3223
River Rch & RM=Panther Creek,Reach-1         ,29130
     994    1416    1776    1105    2204    4397    3407
River Rch & RM=Panther Creek,Reach-1         ,27686
    1399    2025    2568    1613    3218    6421    5074
River Rch & RM=Panther Creek,Reach-1         ,26615
    1525    2219    2824    1779    3550    7083    5635
River Rch & RM=Panther Creek,Reach-1         ,23754
    1693    2473    3155    1993    3976    7933    6339
River Rch & RM=Panther Creek,Reach-1         ,21121
    2052    3010    3852    2438    4865    9708    7792
River Rch & RM=Panther Creek,Reach-1         ,19017
    2537    3753    4829    3072    6129   12230    9913
River Rch & RM=Panther Creek,Reach-1         ,17829
    2792    4147    5351    3412    6809   13585   11069
River Rch & RM=Panther Creek,Reach-1         ,17219
    2879    4265    5494    3496    6975   13916   11288
River Rch & RM=Panther Creek,Reach-1         ,12916
    3113    4604    5924    3763    7508   14981   12111
River Rch & RM=Panther Creek,Reach-1         ,4628
    4572    6712    8594    5437   10849   21647   17362
Boundary for River Rch & Prof#=Panther Creek,Reach-1         , 1
Up Type= 0
Dn Type= 3
Dn Slope=0.002
Boundary for River Rch & Prof#=Panther Creek,Reach-1         , 2
Up Type= 0
Dn Type= 3
Dn Slope=0.002
Boundary for River Rch & Prof#=Panther Creek,Reach-1         , 3
Up Type= 0
Dn Type= 3
Dn Slope=0.002
Boundary for River Rch & Prof#=Panther Creek,Reach-1         , 4
Up Type= 0
Dn Type= 3
Dn Slope=0.002
Boundary for River Rch & Prof#=Panther Creek,Reach-1         , 5
Up Type= 0
Dn Type= 3
Dn Slope=0.002
Boundary for River Rch & Prof#=Panther Creek,Reach-1         , 6
Up Type= 0
Dn Type= 3
Dn Slope=0.002
Boundary for River Rch & Prof#=Panther Creek,Reach-1         , 7
Up Type= 0
Dn Type= 3
Dn Slope=0.002
DSS Import GetInterval= 0
DSS Import GetPeak= 0
DSS Import FillOption= 0

--- Panther Creek.g01 (geometry) ---

Geom Title=Existing Conditions
Program Version=4.10

River Reach=Panther Creek   ,Reach-1
Reach XY= 30
        2221529.        7213310.      2222173.54      7212562.45
      2222737.14      7211153.94      2223565.63      7210423.32
      2223601.81      7210136.13      2223923.99      7209962.54
      2224482.83      7208061.58        2225179.        7207060.
      2226131.29      7206754.15      2228575.67      7205068.01
      2228956.28      7205160.39      2229179.27      7204967.19
        2229804.       7205110.4      2230469.72      7204959.55
      2232023.48      7205057.65       2234677.5      7204206.38
      2236499.24       7203009.5      2236894.16      7203409.61
      2239763.78      7203560.52      2240553.96      7203810.49
       2241318.5       7203661.2      2243049.03      7204359.93
      2244673.07      7204357.76      2245237.49      7203863.53
      2245858.85      7203709.64      2247517.73      7203962.15
      2248142.92      7204359.32      2248523.15      7204357.94
       2248728.9      7204167.32        2249729.        7204160.

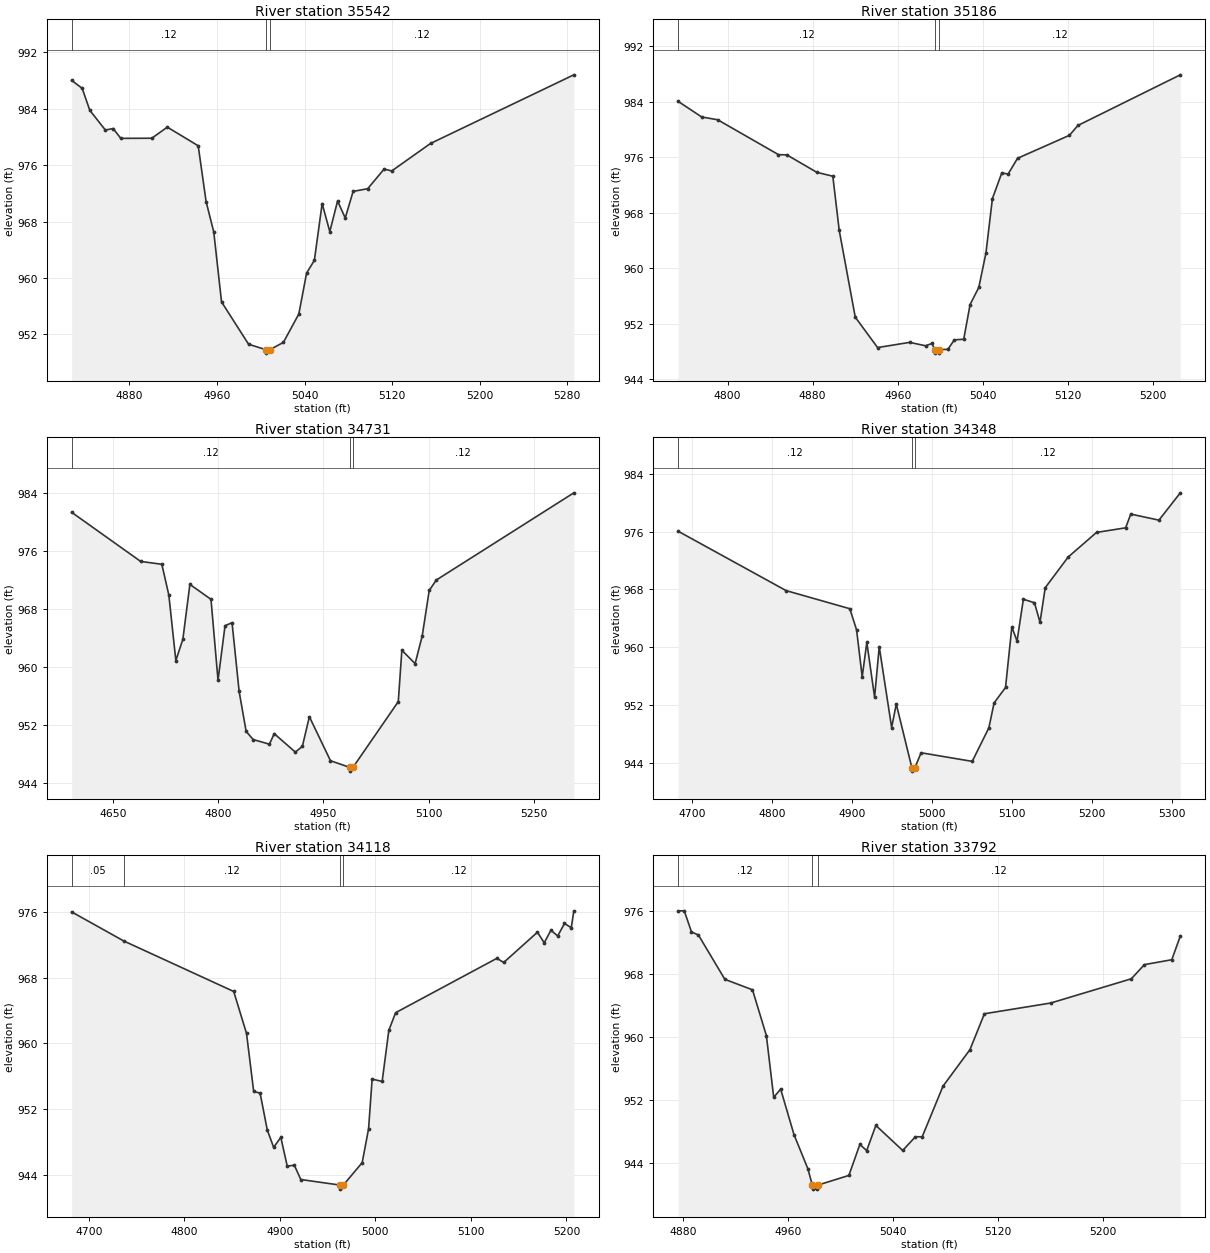
Type RM Length L Ch R = 1 ,35542   ,356,356,356
BEGIN DESCRIPTION:
Panther Creek 70.0
END DESCRIPTION:
XS GIS Cut Line= 3
      2221846.49      7213226.06        2221729.        7213110.
      2221519.79      7212904.07
#Sta/Elev= 30
  4827.3  987.99  4836.9  986.87  4843.9  983.75  4858.1  980.96  4865.2  981.17
  4872.2  979.78  4900.5   979.8  4914.7  981.37  4942.9  978.73  4950.1  970.83
  4957.1  966.52  4964.2  956.62  4988.9  950.62  5004.5  949.86  5004.8  949.36
  5008.5  949.86  5020.7  950.88  5034.8   954.9  5041.9   960.7    5049   962.5
  5056.1  970.54  5063.1  966.57  5070.2  970.91  5077.2   968.5  5084.4  972.27
  5097.7  972.65  5112.7  975.43  5119.7  975.17  5155.1  979.06    5286  988.78
#Mann= 3 ,-1 , 0
  4827.3     .12       0  5004.5     .07       0  5008.5     .12       0
Bank Sta=5004.5,5008.5
XS Rating Curve= 0 ,0
Exp/Cntr=0.3,0.1

Type RM Length L Ch R = 1 ,35186   ,455,455,455
BEGIN DESCRIPTION:
Panther Creek 69.0
END DESCRIPTION:
XS GIS Cut Line= 3
      2222015.07      7213015.27        2221879.        7212810.
      2221750.15       7212624.3
#Sta/Elev= 30
  4753.5  984.04  4775.7  981.79  4790.7  981.39  4847.9  976.37  4855.8  976.33
    4884  973.82    4899  973.26    4905  965.48  4920.1  952.97  4941.1  948.59
  4971.2  949.34  4986.2  948.85  4992.2  949.18  4994.8  948.29    4995  947.79
  4998.5  947.79  4998.8  948.29  5007.2  948.34  5013.3   949.7  5022.1  949.79
  5028.1  954.78  5036.3  957.26    5043   962.2  5049.1  970.05  5057.9  973.73
  5063.9  973.58  5072.7  975.84  5121.5  979.15  5129.5  980.57  5225.8  987.86
#Mann= 3 ,-1 , 0
  4753.5     .12       0  4994.8     .07       0  4998.8     .12       0
Bank Sta=4994.8,4998.8
XS Rating Curve= 0 ,0
Exp/Cntr=0.3,0.1

Type RM Length L Ch R = 1 ,34731   ,383,383,383
BEGIN DESCRIPTION:
Panther Creek 68.0
END DESCRIPTION:
XS GIS Cut Line= 3
      2222587.24      7212478.66      2222184.28      7212502.21
      2221874.28      7212466.53
#Sta/Elev= 30
  4591.4   981.3  4689.8  974.53  4719.9  974.14  4729.9   969.9  4739.9  960.88
  4749.9  963.81  4759.9  971.37    4790  969.31    4800  958.16    4810  965.68
    4820  966.09  4830.1  956.62  4840.1  951.12  4850.1     950  4873.3  949.36
  4880.1  950.81  4910.2  948.27  4920.2  949.06  4930.2  953.14  4960.3  947.08
  4988.2  946.15  4988.4  945.65  4992.2  946.15  5056.9  955.22    5062   962.3
  5080.9  960.46    5091  964.26    5101  970.53  5111.1  971.97  5307.1  983.98
#Mann= 3 ,-1 , 0
  4591.4     .12       0  4988.2     .07       0  4992.2     .12       0
Bank Sta=4988.2,4992.2
XS Rating Curve= 0 ,0
Exp/Cntr=0.3,0.1

Type RM Length L Ch R = 1 ,34348   ,230,230,230
BEGIN DESCRIPTION:
Panther Creek 67.0
END DESCRIPTION:
XS GIS Cut Line= 3
       2222519.6      7212304.96      2222245.16       7212138.3
      2222007.92      7211944.36
#Sta/Elev= 30
    4683  976.04    4818  967.82  4897.5  965.32    4906  962.39    4913   955.9
  4918.8  960.66  4928.5  953.08  4934.3  960.06  4949.8  948.88  4955.6  952.13
    4975  943.35  4975.2  942.85    4979  943.35  4986.6  945.39  5050.5   944.2
  5071.3  948.84  5077.8  952.28  5092.1  954.42    5100  962.79  5106.5  960.84
  5114.4  966.63  5128.3  966.14  5135.2  963.44  5141.7  968.22  5170.4  972.47
  5205.8  975.87  5242.2  976.51  5248.6  978.41  5283.8  977.57  5310.5  981.35
#Mann= 3 ,-1 , 0
    4683     .12       0    4975     .07       0    4979     .12       0
Bank Sta=4975,4979
XS Rating Curve= 0 ,0
Exp/Cntr=0.3,0.1

Type RM Length L Ch R = 1 ,34118   ,326,326,326
BEGIN DESCRIPTION:
Panther Creek 66.0
END DESCRIPTION:
XS GIS Cut Line= 3
      2222592.35      7212195.81        2222379.        7211960.
      2222232.89      7211812.25
#Sta/Elev= 30
    4682  975.99  4736.6  972.45  4851.7  966.31  4865.1   961.2  4872.6  954.15
  4879.3  953.95  4886.8  949.48  4893.5  947.35    4901  948.57  4907.7  945.08
  4915.2  945.17  4921.9  943.44  4962.5  942.77  4962.8  942.27  4966.5  942.77
  4986.2  945.49  4992.9  949.62  4996.6  955.65  5007.1  955.37  5014.1  961.59
  5021.2  963.73  5127.2  970.34  5134.4  969.84  5169.7  973.52  5176.8  972.23
  5183.8  973.76  5190.9  973.06    5198  974.58  5205.1  974.07  5207.8  976.12
#Mann= 4 ,-1 , 0
    4682     .05       0  4736.6     .12       0  4962.5     .07       0
  4966.5     .12       0
Bank Sta=4962.5,4966.5
XS Rating Curve= 0 ,0
Exp/Cntr=0.3,0.1

Type RM Length L Ch R = 1 ,33792   ,368,368,368
BEGIN DESCRIPTION:
Panther Creek 65.0
END DESCRIPTION:
XS GIS Cut Line= 3
      2222692.81      7211748.57        2222579.        7211710.
      2222322.63      7211649.84
#Sta/Elev= 30
  4875.9  976.01  4880.6  976.01  4886.1  973.33  4891.4  972.94  4911.6  967.31
  4932.7  965.98  4943.3  960.17  4948.9  952.33  4954.2  953.37  4964.4  947.59
    4975  943.25  4978.4  941.17  4978.6  940.67  4982.1  940.67  4982.4  941.17
  5006.3  942.41  5014.7  946.35  5019.9  945.56  5026.9  948.76  5047.4  945.58
  5057.1  947.32  5062.3  947.32  5078.2  953.75  5098.8  958.39  5109.8  962.94
  5160.4   964.3    5222  967.38    5232  969.18  5252.9   969.8  5259.4  972.81
#Mann= 3 ,-1 , 0
  4875.9     .12       0  4978.4     .07       0  4982.4     .12       0
Bank Sta=4978.4,4982.4
XS Rating Curve= 0 ,0
Exp/Cntr=0.3,0.1

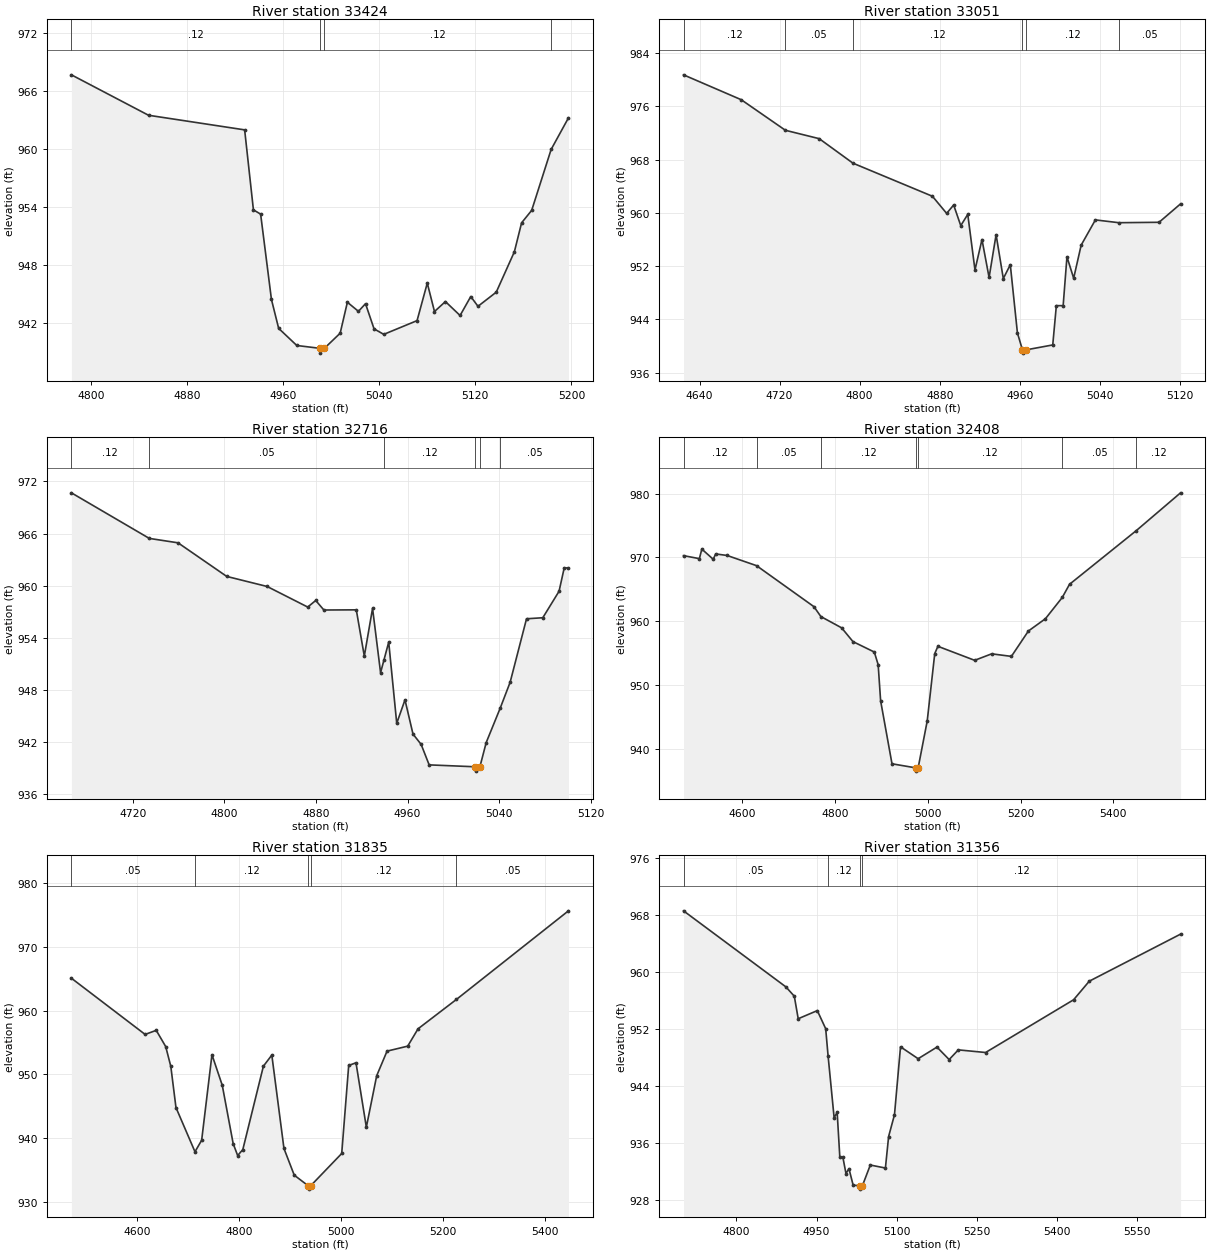
Type RM Length L Ch R = 1 ,33424   ,373,373,373
BEGIN DESCRIPTION:
Panther Creek 64.0
END DESCRIPTION:
XS GIS Cut Line= 3
      2222809.21      7211479.35        2222629.        7211360.
      2222463.34      7211252.38
#Sta/Elev= 30
  4783.8  967.69    4848  963.51    4928     962  4935.3  953.73  4941.3  953.29
  4950.3  944.47  4956.3  941.48  4971.4  939.71  4990.4  939.42  4990.7  938.92
  4994.4  939.42  5007.5  940.98  5013.5  944.18  5022.7  943.24  5028.6  944.03
  5035.7  941.43  5043.8  940.86  5071.5  942.28    5080  946.16    5086  943.22
  5095.1  944.25  5107.3  942.81  5116.2  944.77  5122.2  943.76  5137.4  945.22
  5152.5   949.4  5158.5  952.39  5166.9  953.68  5183.1  959.98  5197.5  963.24
#Mann= 4 ,-1 , 0
  4783.8     .12       0  4990.4     .07       0  4994.4     .12       0
  5183.1     .05       0
Bank Sta=4990.4,4994.4
XS Rating Curve= 0 ,0
Exp/Cntr=0.3,0.1

Type RM Length L Ch R = 1 ,33051   ,335,335,335
BEGIN DESCRIPTION:
Panther Creek 63.0
END DESCRIPTION:
XS GIS Cut Line= 3
      2223097.26      7211323.43        2222829.        7211060.
      2222738.87      7210979.83
#Sta/Elev= 30
    4624  980.72  4681.7  976.98  4725.8  972.39  4759.6  971.13  4793.3  967.45
  4872.7  962.48  4886.9  959.91  4893.9  961.17    4901  958.07    4908  959.76
  4915.2  951.41  4922.2  955.98  4929.3  950.28  4936.3  956.71  4943.5  950.12
  4950.5   952.2  4957.6  941.96  4962.6  939.42  4962.9  938.92  4966.6  939.42
  4992.9  940.15  4996.5  946.05  5003.3  946.05  5007.1  953.39  5013.8  950.17
  5021.3  955.14  5035.5  958.93  5058.9  958.51  5099.1  958.57  5120.6  961.34
#Mann= 6 ,-1 , 0
    4624     .12       0  4725.8     .05       0  4793.3     .12       0
  4962.6     .07       0  4966.6     .12       0  5058.9     .05       0
Bank Sta=4962.6,4966.6
XS Rating Curve= 0 ,0
Exp/Cntr=0.3,0.1

Type RM Length L Ch R = 1 ,32716   ,308,308,308
BEGIN DESCRIPTION:
Panther Creek 62.0
END DESCRIPTION:
XS GIS Cut Line= 3
      2223299.04      7211061.66      2223066.39      7210824.35
      2222999.05      7210748.32
#Sta/Elev= 30
  4666.5  970.69  4734.5  965.44  4759.6  964.93  4802.1  961.06  4837.4   959.9
  4872.8  957.53  4879.8  958.29  4886.9  957.19  4915.2  957.21  4922.2  951.88
  4929.4  957.38  4936.4  949.97  4939.3  951.41  4943.5  953.49  4950.5  944.14
  4957.7  946.84  4964.7   942.9  4971.8  941.71  4978.8  939.35  5019.1  939.13
  5019.3  938.63  5023.1  939.13  5028.6  941.92  5040.9  945.91  5049.5  948.87
  5063.8  956.18    5078   956.3  5092.2  959.35  5096.7  962.04  5100.4  962.04
#Mann= 6 ,-1 , 0
  4666.5     .12       0  4734.5     .05       0  4939.3     .12       0
  5019.1     .07       0  5023.1     .12       0  5040.9     .05       0
Bank Sta=5019.1,5023.1
XS Rating Curve= 0 ,0
Exp/Cntr=0.3,0.1

Type RM Length L Ch R = 1 ,32408   ,573,573,573
BEGIN DESCRIPTION:
Panther Creek 61.0
END DESCRIPTION:
XS GIS Cut Line= 3
       2223508.1      7211162.65      2223316.03      7210672.82
      2223029.02      7210210.04
#Sta/Elev= 30
    4474  970.28  4508.2  969.81  4513.5  971.31    4538  969.71  4543.3  970.55
  4567.8  970.31  4631.3  968.71    4755  962.27  4769.9  960.72  4814.6  958.95
    4839  956.79    4885  955.15  4893.3  953.17  4898.6   947.5  4923.1  937.61
  4975.3  936.96  4975.6  936.46  4979.4  936.96    4999  944.34  5015.2  954.91
    5022  956.05  5101.2  953.85  5137.8  954.87  5180.3  954.47  5216.9  958.45
  5253.6  960.38  5289.9  963.72  5305.5  965.78  5449.5  974.22  5544.7  980.14
#Mann= 7 ,-1 , 0
    4474     .12       0  4631.3     .05       0  4769.9     .12       0
  4975.3     .07       0  4979.4     .12       0  5289.9     .05       0
  5449.5     .12       0
Bank Sta=4975.3,4979.4
XS Rating Curve= 0 ,0
Exp/Cntr=0.3,0.1

Type RM Length L Ch R = 1 ,31835   ,479,479,479
BEGIN DESCRIPTION:
Panther Creek 60.0
END DESCRIPTION:
XS GIS Cut Line= 3
      2224102.39      7210276.14      2223576.67       7210207.4
      2223138.05      7210134.09
#Sta/Elev= 30
  4471.7  965.07  4616.3  956.25  4638.1  956.89  4656.7  954.34  4666.7  951.23
  4676.8  944.78  4714.1  937.84  4727.2  939.65  4747.4  953.07  4767.6  948.27
    4789  939.12  4797.8  937.25  4807.9  938.18  4848.3  951.27  4864.8  953.01
  4888.6  938.36  4908.8  934.17  4936.6  932.48  4936.9  931.98  4940.7  932.48
  5001.9  937.57  5015.6  951.38  5029.9   951.8  5050.2   941.7  5070.5  949.77
  5090.8  953.63  5131.3  954.41  5151.6  957.13  5226.9  961.74  5446.6  975.64
#Mann= 5 ,-1 , 0
  4471.7     .05       0  4714.1     .12       0  4936.6     .07       0
  4940.7     .12       0  5226.9     .05       0
Bank Sta=4936.6,4940.7
XS Rating Curve= 0 ,0
Exp/Cntr=0.3,0.1

Type RM Length L Ch R = 1 ,31356   ,390,390,390
BEGIN DESCRIPTION:
Panther Creek 59.0
END DESCRIPTION:
XS GIS Cut Line= 3
      2224184.95      7210108.31        2223929.        7209960.
      2223354.33      7209688.71
#Sta/Elev= 30
  4700.8   968.6  4892.6  957.93  4908.4  956.62  4915.7  953.46  4951.5   954.6
  4967.2  952.06  4971.7  948.24    4983  939.57  4988.7  940.32  4993.7  934.02
  4999.4  934.02  5005.2  931.74  5010.8  932.42  5018.7  930.09    5031  930.05
  5031.6  929.55  5036.1  930.05  5050.8  932.93  5079.1  932.51  5085.1  936.93
  5096.1  939.99  5107.4  949.52  5140.4  947.85  5175.7  949.48  5198.5  947.73
  5215.7  949.09  5266.8  948.72  5431.7  956.12  5461.1  958.73  5632.1  965.33
#Mann= 4 ,-1 , 0
  4700.8     .05       0  4971.7     .12       0    5031     .07       0
  5036.1     .12       0
Bank Sta=5031,5036.1
XS Rating Curve= 0 ,0
Exp/Cntr=0.3,0.1

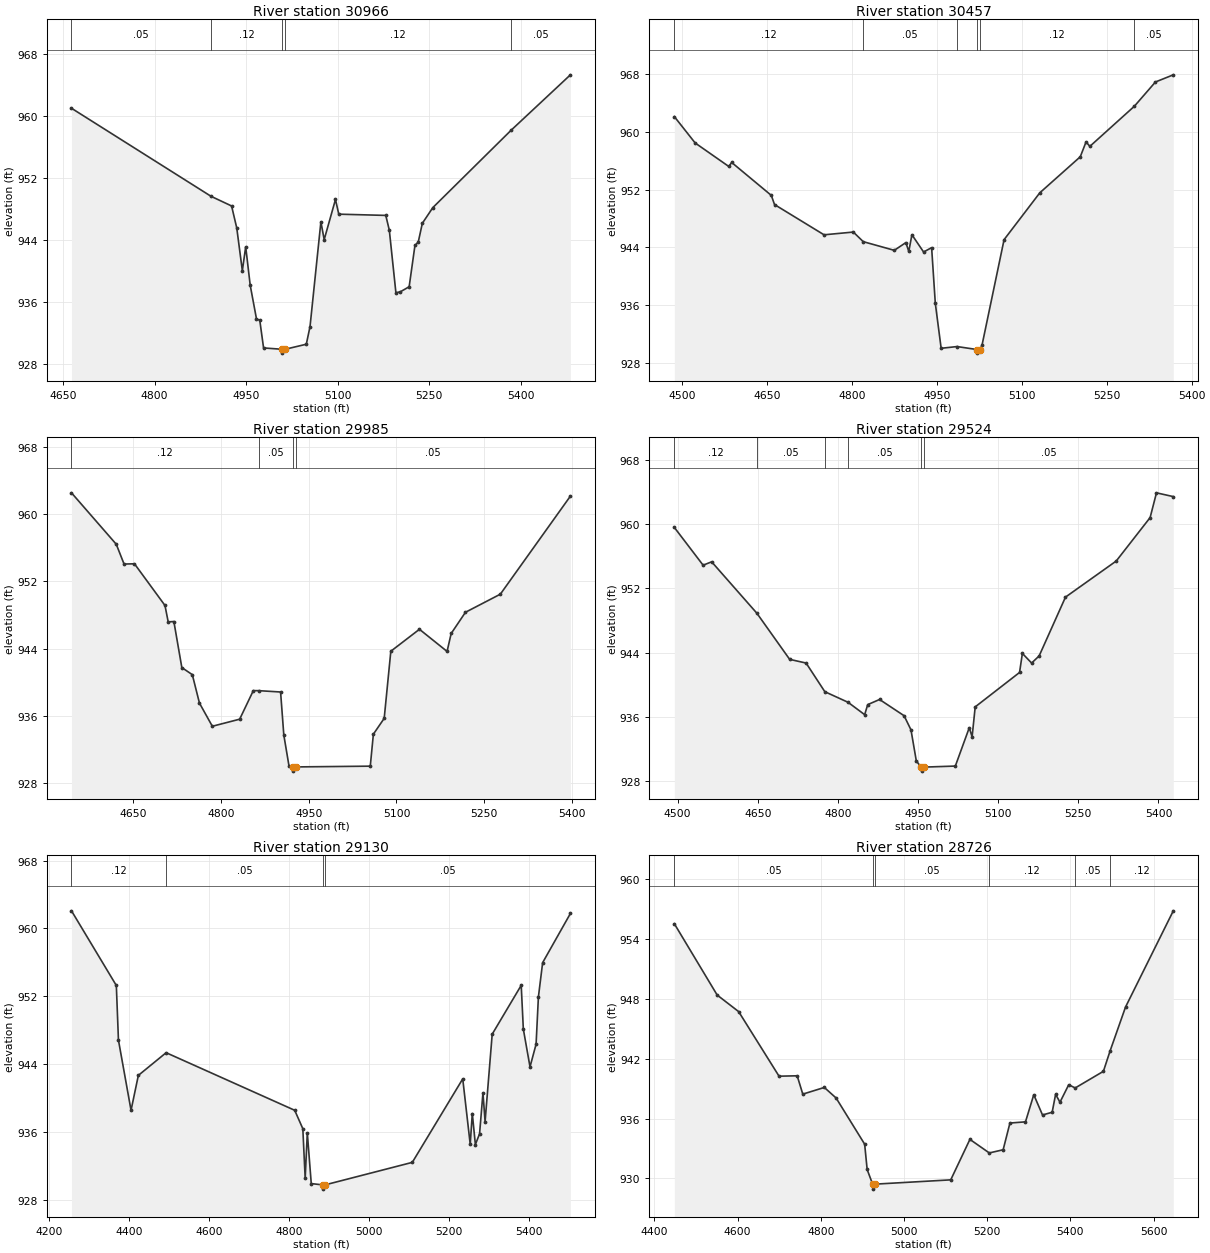
Type RM Length L Ch R = 1 ,30966   ,509,509,509
BEGIN DESCRIPTION:
Panther Creek 58.0
END DESCRIPTION:
XS GIS Cut Line= 3
      2224335.73      7209771.88      2224031.96      7209634.38
      2223584.91      7209449.01
#Sta/Elev= 30
  4663.7  961.01  4892.3  949.63    4926  948.38  4934.5  945.52  4943.6  940.01
  4949.1  943.11  4956.5  938.13  4966.7  933.82  4972.2  933.59  4978.4  930.03
  5008.6  929.86  5009.3  929.36  5013.8  929.86  5048.4  930.51  5054.5  932.79
  5072.3  946.33  5077.7  944.03  5096.2  949.22  5101.6  947.32  5178.6  947.16
  5184.4  945.25  5195.2  937.16  5202.5  937.29  5216.9  937.94  5226.4  943.28
  5231.8  943.71  5238.5  946.14  5255.7  948.17  5384.1  958.18  5481.1  965.33
#Mann= 5 ,-1 , 0
  4663.7     .05       0  4892.3     .12       0  5008.6     .07       0
  5013.8     .12       0  5384.1     .05       0
Bank Sta=5008.6,5013.8
XS Rating Curve= 0 ,0
Exp/Cntr=0.3,0.1

Type RM Length L Ch R = 1 ,30457   ,472,472,472
BEGIN DESCRIPTION:
Panther Creek 57.0
END DESCRIPTION:
XS GIS Cut Line= 3
       2224624.5      7209330.03      2224124.71      7209198.76
      2223768.14      7209125.78
#Sta/Elev= 30
  4486.9  962.11  4523.6  958.46  4582.9  955.21  4588.1  955.76    4658   951.2
  4663.7  949.93  4751.1  945.74  4802.8  946.12  4820.3  944.79  4875.1  943.59
  4895.5  944.66  4900.7  943.44  4906.2  945.75  4926.8  943.36    4941  943.96
  4947.5  936.25  4957.8  930.02  4985.9  930.26  5020.9  929.85  5021.6  929.35
  5026.3  929.85  5029.9  930.43  5068.9  945.07    5132  951.56  5203.4  956.55
  5213.6  958.61  5220.3  957.99  5298.9  963.55  5336.1  966.91  5367.6   967.9
#Mann= 6 ,-1 , 0
  4486.9     .12       0  4820.3     .05       0  4985.9     .12       0
  5020.9     .07       0  5026.3     .12       0  5298.9     .05       0
Bank Sta=5020.9,5026.3
XS Rating Curve= 0 ,0
Exp/Cntr=0.3,0.1

Type RM Length L Ch R = 1 ,29985   ,461,461,461
BEGIN DESCRIPTION:
Panther Creek 56.0
END DESCRIPTION:
XS GIS Cut Line= 3
      2224678.99        7208960.      2224263.08      7208776.49
      2223892.91      7208631.08
#Sta/Elev= 30
  4544.9   962.5  4621.4  956.39  4634.7  954.04  4652.5  954.07  4704.6  949.12
  4710.1  947.17  4719.8  947.21  4733.4  941.74  4751.3   940.9  4763.5  937.52
  4785.5  934.77  4832.2  935.61  4855.5     939  4864.6     939  4902.1  938.84
  4907.6  933.73  4916.5  930.04  4922.7  929.94  4923.5  929.44  4928.2  929.94
  5055.3  930.03  5060.6  933.83  5079.1  935.71  5090.4  943.68  5139.3  946.29
  5186.5  943.66  5193.5  945.79  5217.9  948.31  5277.5  950.46  5397.2  962.11
#Mann= 4 ,-1 , 0
  4544.9     .12       0  4864.6     .05       0  4922.7    .033       0
  4928.2     .05       0
Bank Sta=4922.7,4928.2
XS Rating Curve= 0 ,0
Exp/Cntr=0.3,0.1

Type RM Length L Ch R = 1 ,29524   ,394,394,394
BEGIN DESCRIPTION:
Panther Creek 55.0
END DESCRIPTION:
XS GIS Cut Line= 3
      2224824.05      7208609.56        2224379.        7208360.
      2223977.91      7208223.59
#Sta/Elev= 30
  4493.9  959.57  4547.7  954.88  4563.7   955.3  4648.3  948.91  4709.7  943.17
  4740.5  942.71  4775.5  939.15    4819  937.83  4850.1  936.29  4855.8  937.54
    4878  938.18  4923.9  936.16  4936.8   934.4  4946.8  930.53  4955.8  929.77
  4956.6  929.27  4961.3  929.77  5019.8   929.9  5045.9  934.67  5051.2  933.53
    5057  937.26    5140  941.54  5145.3  943.91  5162.6  942.71  5176.7   943.6
    5226  950.91    5321   955.4  5384.4   960.8  5396.3  963.88  5427.8  963.41
#Mann= 6 ,-1 , 0
  4493.9     .12       0  4648.3     .05       0  4775.5     .12       0
    4819     .05       0  4955.8    .033       0  4961.3     .05       0
Bank Sta=4955.8,4961.3
XS Rating Curve= 0 ,0
Exp/Cntr=0.3,0.1

Type RM Length L Ch R = 1 ,29130   ,404,404,404
BEGIN DESCRIPTION:
Panther Creek 54.0
END DESCRIPTION:
XS GIS Cut Line= 3
      2225227.52      7208251.73      2224523.94      7208014.95
      2224042.89      7207858.22
#Sta/Elev= 30
  4255.2  962.08  4367.4  953.29  4372.7  946.86  4404.2   938.6  4422.5  942.71
    4492  945.38  4813.7   938.6    4834  936.43  4839.9  930.59  4845.2  935.95
  4855.1  929.97  4883.8  929.82  4884.7  929.32  4889.6  929.82  5107.9  932.47
  5234.1   942.3  5252.8   934.6    5258  938.22  5265.7  934.57  5276.2  935.83
  5284.7  940.67    5290  937.26  5307.8  947.56  5380.4  953.31  5385.7  948.16
  5402.4  943.71  5417.6  946.38  5423.4  951.94    5434  955.98  5503.5  961.77
#Mann= 4 ,-1 , 0
  4255.2     .12       0    4492     .05       0  4883.8    .033       0
  4889.6     .05       0
Bank Sta=4883.8,4889.6
XS Rating Curve= 0 ,0
Exp/Cntr=0.3,0.1

Type RM Length L Ch R = 1 ,28726   ,236,236,236
BEGIN DESCRIPTION:
Panther Creek 53.0
END DESCRIPTION:
XS GIS Cut Line= 3
      2225228.98      7207959.99      2224750.79      7207694.69
      2224129.67      7207494.95
#Sta/Elev= 30
    4448  955.55  4550.9   948.4  4602.5  946.74  4699.6  940.26  4743.2   940.3
  4756.7  938.46  4808.5  939.13  4836.8  938.07  4905.4  933.44  4911.4   930.9
  4924.5  929.43  4925.5  928.93  4930.4  929.43  5112.3  929.86  5158.4  933.92
    5205  932.56  5238.3  932.88  5254.6  935.56    5292  935.68  5311.9   938.4
  5332.9  936.37  5356.1  936.64  5364.4  938.44  5374.9  937.65  5395.9   939.4
  5411.5  939.08  5479.3  940.75  5495.4   942.8  5532.5   947.2  5647.3  956.85
#Mann= 6 ,-1 , 0
    4448     .05       0  4924.5    .033       0  4930.4     .05       0
    5205     .12       0  5411.5     .05       0  5495.4     .12       0
Bank Sta=4924.5,4930.4
XS Rating Curve= 0 ,0
Exp/Cntr=0.3,0.1

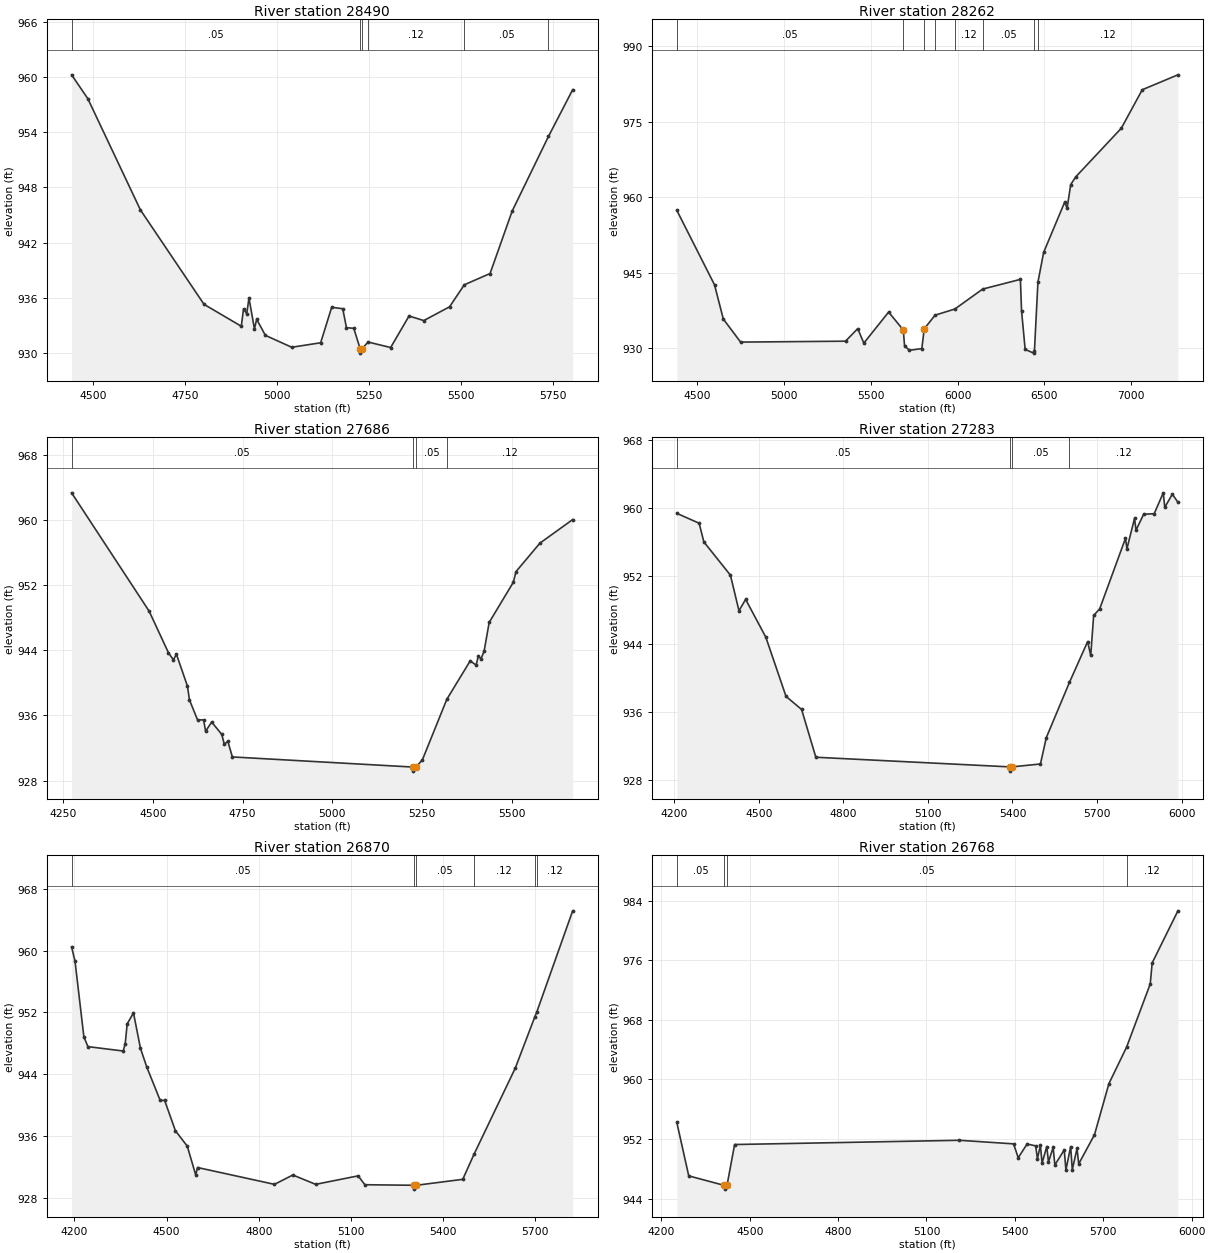
Type RM Length L Ch R = 1 ,28490   ,228,228,228
BEGIN DESCRIPTION:
Panther Creek 52.1
END DESCRIPTION:
XS GIS Cut Line= 3
      2225341.49      7207829.17      2224817.98      7207464.74
      2224094.74      7207433.05
#Sta/Elev= 30
  4442.3  960.28  4486.3  957.69  4629.4  945.55  4802.2  935.26  4903.5  932.87
  4909.6  934.76  4918.3  934.24  4924.4  935.95  4939.2  932.58  4945.3  933.63
  4968.9  931.88  5040.5  930.58  5119.2  931.07  5149.2  934.94  5179.2  934.78
  5189.3  932.72  5209.3  932.64  5226.3  930.44  5227.3  929.94  5232.3  930.44
    5248  931.15  5309.4  930.55  5359.4  933.99  5399.5  933.49  5469.5  934.99
  5509.6  937.39  5579.6  938.62  5639.7  945.43  5738.4  953.57  5804.1  958.66
#Mann= 6 ,-1 , 0
  4442.3     .05       0  5226.3    .033       0  5232.3     .05       0
    5248     .12       0  5509.6     .05       0  5738.4     .12       0
Bank Sta=5226.3,5232.3
XS Rating Curve= 0 ,0
Exp/Cntr=0.3,0.1

Type RM Length L Ch R = 1 ,28262   ,576,576,576
BEGIN DESCRIPTION:
Panther Creek 52.0
END DESCRIPTION:
XS GIS Cut Line= 3
      2225470.34      7207693.42      2224895.92      7207246.51
      2223502.74      7205596.51
#Sta/Elev= 30
  4381.6  957.37  4598.7  942.59  4649.4   935.8    4749  931.22  5353.5   931.4
  5423.9  933.89  5459.1  931.02    5602  937.18  5686.6  933.62  5693.8  930.48
  5721.7  929.59  5793.2  929.93  5807.5  933.87  5869.8  936.57  5983.5  937.78
  6143.7  941.74  6361.3  943.67  6367.9  937.44  6388.7  929.78  6437.3  929.03
  6442.3  929.53  6462.2  943.08  6495.3  949.03  6616.2  958.98  6630.5  957.81
  6651.3  962.49  6679.9  964.01  6942.6  973.66  7063.5  981.31  7268.9  984.27
#Mann= 8 ,-1 , 0
  4381.6     .05       0  5686.6    .033       0  5807.5     .05       0
  5869.8     .05       0  5983.5     .12       0  6143.7     .05       0
  6442.3     .05       0  6462.2     .12       0
Bank Sta=5686.6,5807.5
XS Rating Curve= 0 ,0
Exp/Cntr=0.3,0.1

Type RM Length L Ch R = 1 ,27686   ,403,403,403
BEGIN DESCRIPTION:
Panther Creek 51.0
END DESCRIPTION:
XS GIS Cut Line= 3
       2225727.5      7207662.55      2225406.31      7207007.31
      2225103.12      7206412.57
#Sta/Elev= 30
  4273.2   963.3  4489.4  948.79  4543.3  943.69  4556.9  942.82  4565.6   943.5
  4596.3  939.59  4601.9   937.9  4624.4  935.46  4641.3  935.45  4646.9  934.06
  4663.8  935.19  4691.9  933.68  4699.2  932.45  4708.8  932.84  4721.5  930.91
  5224.8  929.67  5226.1  929.17  5233.4  929.67  5251.3  930.54  5319.5  937.97
  5384.7  942.69  5401.4  942.17    5407  943.23  5415.2  942.97  5423.6   943.9
  5437.7  947.41    5505  952.33  5512.5  953.64  5579.2  957.13  5670.5  960.02
#Mann= 4 ,-1 , 0
  4273.2     .05       0  5224.8    .033       0  5233.4     .05       0
  5319.5     .12       0
Bank Sta=5224.8,5233.4
XS Rating Curve= 0 ,0
Exp/Cntr=0.3,0.1

Type RM Length L Ch R = 1 ,27283   ,413,413,413
BEGIN DESCRIPTION:
Panther Creek 50.0
END DESCRIPTION:
XS GIS Cut Line= 3
      2225887.45      7207688.31        2225779.        7206910.
      2225478.34      7205965.32
#Sta/Elev= 30
  4209.6  959.37  4288.7  958.21  4305.4  956.02  4399.7  952.11    4430  947.93
  4453.6  949.27  4525.2  944.83  4596.8  937.88  4652.1  936.34  4702.6  930.73
  5389.9   929.6  5391.2   929.1  5398.5   929.6  5499.2  929.94  5520.1  933.04
    5602  939.51  5666.6  944.31  5677.6  942.68    5688  947.38  5709.3  948.15
  5800.8  956.43    5806  955.22    5833  958.78  5838.2  957.39  5865.2  959.26
  5902.7  959.33  5934.9  961.78  5940.2  960.08  5967.1  961.62  5986.8  960.67
#Mann= 4 ,-1 , 0
  4209.6     .05       0  5389.9    .033       0  5398.5     .05       0
    5602     .12       0
Bank Sta=5389.9,5398.5
XS Rating Curve= 0 ,0
Exp/Cntr=0.3,0.1

Type RM Length L Ch R = 1 ,26870   ,102,102,102
BEGIN DESCRIPTION:
Panther Creek 49.1
END DESCRIPTION:
XS GIS Cut Line= 4
      2226582.55      7207421.55      2226456.41      7207262.58
      2226348.59      7207126.69      2225747.37       7206026.1
#Sta/Elev= 30
  4191.1  960.48  4202.2  958.64    4231  948.85  4244.1  947.56    4359  946.99
  4365.6  947.95    4372  950.51  4392.5  951.93  4415.2  947.34    4436  944.89
  4479.3   940.6  4493.8  940.59    4529  936.66  4567.5  934.67  4595.1  930.92
  4600.8   931.9  4851.3  929.72    4911  930.93  4985.3  929.72  5123.6  930.82
  5145.4  929.67  5304.1   929.6  5305.4   929.1  5313.2   929.6  5463.9  930.37
  5500.3  933.59  5634.8  944.77  5697.8  951.35  5704.8  952.04  5821.6  965.15
#Mann= 6 ,-1 , 0
  4191.1     .05       0  5304.1    .033       0  5313.2     .05       0
  5500.3     .12       0  5697.8     .05       0  5704.8     .12       0
Bank Sta=5304.1,5313.2
XS Rating Curve= 0 ,0
Exp/Cntr=0.3,0.1

Type RM Length L Ch R = 1 ,26768   ,153,153,153
BEGIN DESCRIPTION:
Panther Creek 49.0
END DESCRIPTION:
XS GIS Cut Line= 4
       2226634.6      7207260.89      2226464.06      7207169.49
      2226196.96      7206642.61      2225747.64      7205843.82
#Sta/Elev= 30
  4252.7  954.22  4293.1  947.05  4413.9  945.77  4415.2  945.27    4423  945.77
  4448.8  951.26    5212  951.83  5395.6  951.35  5411.4  949.49  5441.5  951.33
  5470.7  951.08  5476.5  949.36  5486.7  951.14  5492.4  948.77  5508.3  950.99
  5514.1  948.93    5530  950.88  5535.7  948.51  5567.6  950.54  5573.3  947.85
  5589.3  950.97    5595  947.89    5611  950.73  5616.7  948.66  5670.2  952.57
  5719.3  959.45  5779.2  964.34  5859.5  972.83    5866  975.65  5953.4  982.65
#Mann= 4 ,-1 , 0
  4252.7     .05       0  4413.9    .033       0    4423     .05       0
  5779.2     .12       0
Bank Sta=4413.9,4423
XS Rating Curve= 0 ,0
Exp/Cntr=0.3,0.1

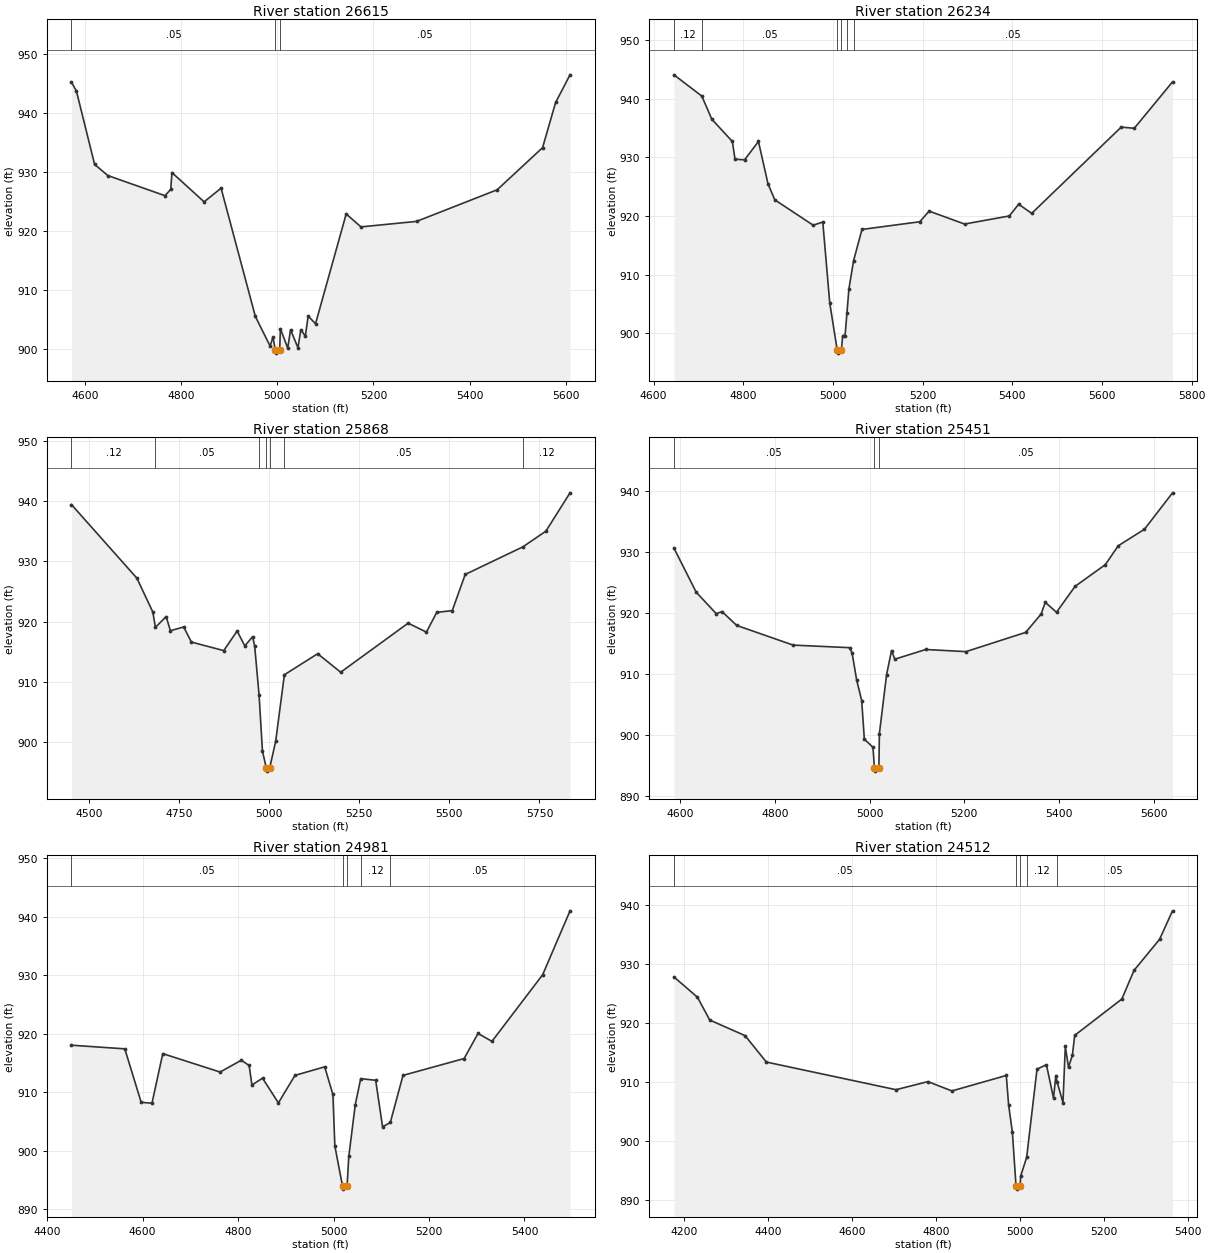
Type RM Length L Ch R = 1 ,26615   ,381,381,381
BEGIN DESCRIPTION:
Panther Creek 48.1
END DESCRIPTION:
XS GIS Cut Line= 3
      2226644.76      7206899.06      2226464.14      7206798.93
      2226025.64      7206093.65
#Sta/Elev= 30
  4571.9   945.2  4582.2   943.7    4620   931.3  4647.5  929.41  4766.5     926
  4778.4  927.08  4780.9  929.91  4847.8  924.96  4883.1  927.27  4954.4  905.56
  4985.1  900.55    4991   902.1  4995.9  899.86  4997.2  899.36    5005  899.86
  5006.4   903.5  5021.7  900.21  5027.6  903.31    5043  900.27  5048.9  903.32
  5058.3  902.23  5064.2  905.62  5079.6  904.34  5143.3  922.91    5174  920.72
  5289.7  921.65  5457.4     927  5551.8  934.13  5578.9  941.77  5608.9  946.45
#Mann= 3 ,-1 , 0
  4571.9     .05       0  4995.9    .033       0    5005     .05       0
Bank Sta=4995.9,5005
XS Rating Curve= 0 ,0
Exp/Cntr=0.3,0.1

Type RM Length L Ch R = 1 ,26234   ,366,366,366
BEGIN DESCRIPTION:
Panther Creek 48.0
END DESCRIPTION:
XS GIS Cut Line= 3
      2226804.15      7206672.23      2226606.14       7206345.9
      2226164.81      7205763.92
#Sta/Elev= 30
  4645.2  944.07  4707.3  940.45  4729.7   936.5  4775.5  932.71  4781.4  929.69
  4802.7  929.58  4833.7  932.71    4855  925.48  4870.1  922.77  4955.8  918.44
  4977.2  918.98  4992.7  905.19  5009.4  897.14  5010.8  896.64  5018.6  897.14
  5021.6  899.63  5026.9  899.63    5031   903.4  5035.5  907.59  5045.9   912.4
  5064.6  917.72  5193.6  919.03  5214.4  920.84  5293.4  918.64  5393.3  920.02
  5414.1  922.02  5443.2  920.46  5642.9  935.16    5672  934.96  5757.3  942.87
#Mann= 6 ,-1 , 0
  4645.2     .12       0  4707.3     .05       0  5009.4    .033       0
  5018.6     .05       0    5031     .12       0  5045.9     .05       0
Bank Sta=5009.4,5018.6
XS Rating Curve= 0 ,0
Exp/Cntr=0.3,0.1

Type RM Length L Ch R = 1 ,25868   ,417,417,417
BEGIN DESCRIPTION:
Panther Creek 47.0
END DESCRIPTION:
XS GIS Cut Line= 3
      2227160.53      7206586.39        2226879.        7206110.
      2226409.69      7205424.76
#Sta/Elev= 30
    4451  939.38  4632.7  927.18  4676.7  921.59  4684.1  919.04  4713.8  920.82
  4725.6  918.48  4762.5   919.1  4783.9   916.6  4873.7  915.18  4910.8  918.43
  4932.2  915.96  4953.7  917.49  4959.5  915.98  4971.8  907.77  4981.1  898.54
  4991.9  895.71  4993.3  895.21  5001.1  895.71  5017.9  900.18    5042  911.18
  5134.4  914.67  5198.3   911.6  5385.5  919.73  5436.3  918.25  5464.9  921.52
    5508  921.81  5543.9   927.8  5704.4  932.39  5767.9  934.98  5834.9  941.33
#Mann= 7 ,-1 , 0
    4451     .12       0  4684.1     .05       0  4971.8     .12       0
  4991.9     .07       0  5001.1     .12       0    5042     .05       0
  5704.4     .12       0
Bank Sta=4991.9,5001.1
XS Rating Curve= 0 ,0
Exp/Cntr=0.3,0.1

Type RM Length L Ch R = 1 ,25451   ,470,470,470
BEGIN DESCRIPTION:
Panther Creek 46.0
END DESCRIPTION:
XS GIS Cut Line= 3
      2227366.03      7206304.43        2227229.        7205910.
       2227040.7      7205303.41
#Sta/Elev= 30
    4587  930.62    4634  923.38  4676.4  919.85  4688.4  920.21  4719.5  917.93
  4838.7   914.7  4957.9  914.28  4963.2  913.39  4972.8  908.96  4983.4  905.61
    4989  899.27  5007.2  897.93  5010.3  894.52  5011.7  894.02  5019.7  894.52
  5020.8  900.19    5036  909.86  5046.4  913.81  5053.4  912.39  5118.6  913.98
  5203.5  913.63  5329.7  916.79  5362.3   919.8    5371  921.72  5394.8  920.09
  5433.9  924.34  5497.8   927.9  5525.1     931  5580.4  933.71  5639.7  939.69
#Mann= 3 ,-1 , 0
    4587     .05       0  5010.3    .033       0  5019.7     .05       0
Bank Sta=5010.3,5019.7
XS Rating Curve= 0 ,0
Exp/Cntr=0.3,0.1

Type RM Length L Ch R = 1 ,24981   ,469,469,469
BEGIN DESCRIPTION:
Panther Creek 45.0
END DESCRIPTION:
XS GIS Cut Line= 3
      2227865.48      7206200.64        2227629.        7205710.
      2227328.97      7205309.97
#Sta/Elev= 30
  4450.8  918.04  4562.5  917.42  4596.9  908.27  4619.5  908.12  4642.1   916.6
  4762.3  913.45  4806.7  915.47  4823.1  914.57  4828.9  911.24  4851.2   912.4
  4884.4  908.17  4919.1  912.88  4981.4  914.34  4998.6  909.62  5002.7   900.8
  5018.8  893.92  5020.2  893.42  5028.3  893.92  5031.9  899.01  5045.5  907.88
  5056.9  912.32  5088.2  912.04  5102.7  904.08  5118.9  904.82  5145.5  912.88
  5273.6  915.76  5302.7  920.05  5331.9   918.7  5438.2  930.11  5495.5  941.03
#Mann= 5 ,-1 , 0
  4450.8     .05       0  5018.8    .033       0  5028.3     .05       0
  5056.9     .12       0  5118.9     .05       0
Bank Sta=5018.8,5028.3
XS Rating Curve= 0 ,0
Exp/Cntr=0.3,0.1

Type RM Length L Ch R = 1 ,24512   ,373,373,373
BEGIN DESCRIPTION:
Panther Creek 44.0
END DESCRIPTION:
XS GIS Cut Line= 3
      2228337.68      7206156.87        2227979.        7205410.
      2227820.07      7205087.79
#Sta/Elev= 30
  4175.8  927.82  4231.9  924.38  4261.1  920.52  4345.1  917.89    4396  913.41
  4704.8  908.73  4780.9   910.1  4837.9  908.52  4967.6  911.14  4973.1  906.17
  4982.1  901.51  4990.8   892.4  4992.2   891.9  5000.7   892.4  5001.6  894.06
  5016.1  897.28  5040.8  912.22  5063.2  912.96  5080.1   907.3  5085.7  911.13
  5088.5   910.1  5102.6  906.54  5108.2  916.05  5115.8  912.54    5125  914.55
  5130.6  917.93  5242.9  924.08  5271.9  928.93  5332.7  934.18  5363.6  939.01
#Mann= 5 ,-1 , 0
  4175.8     .05       0  4990.8    .033       0  5000.7     .05       0
  5016.1     .12       0  5088.5     .05       0
Bank Sta=4990.8,5000.7
XS Rating Curve= 0 ,0
Exp/Cntr=0.3,0.1