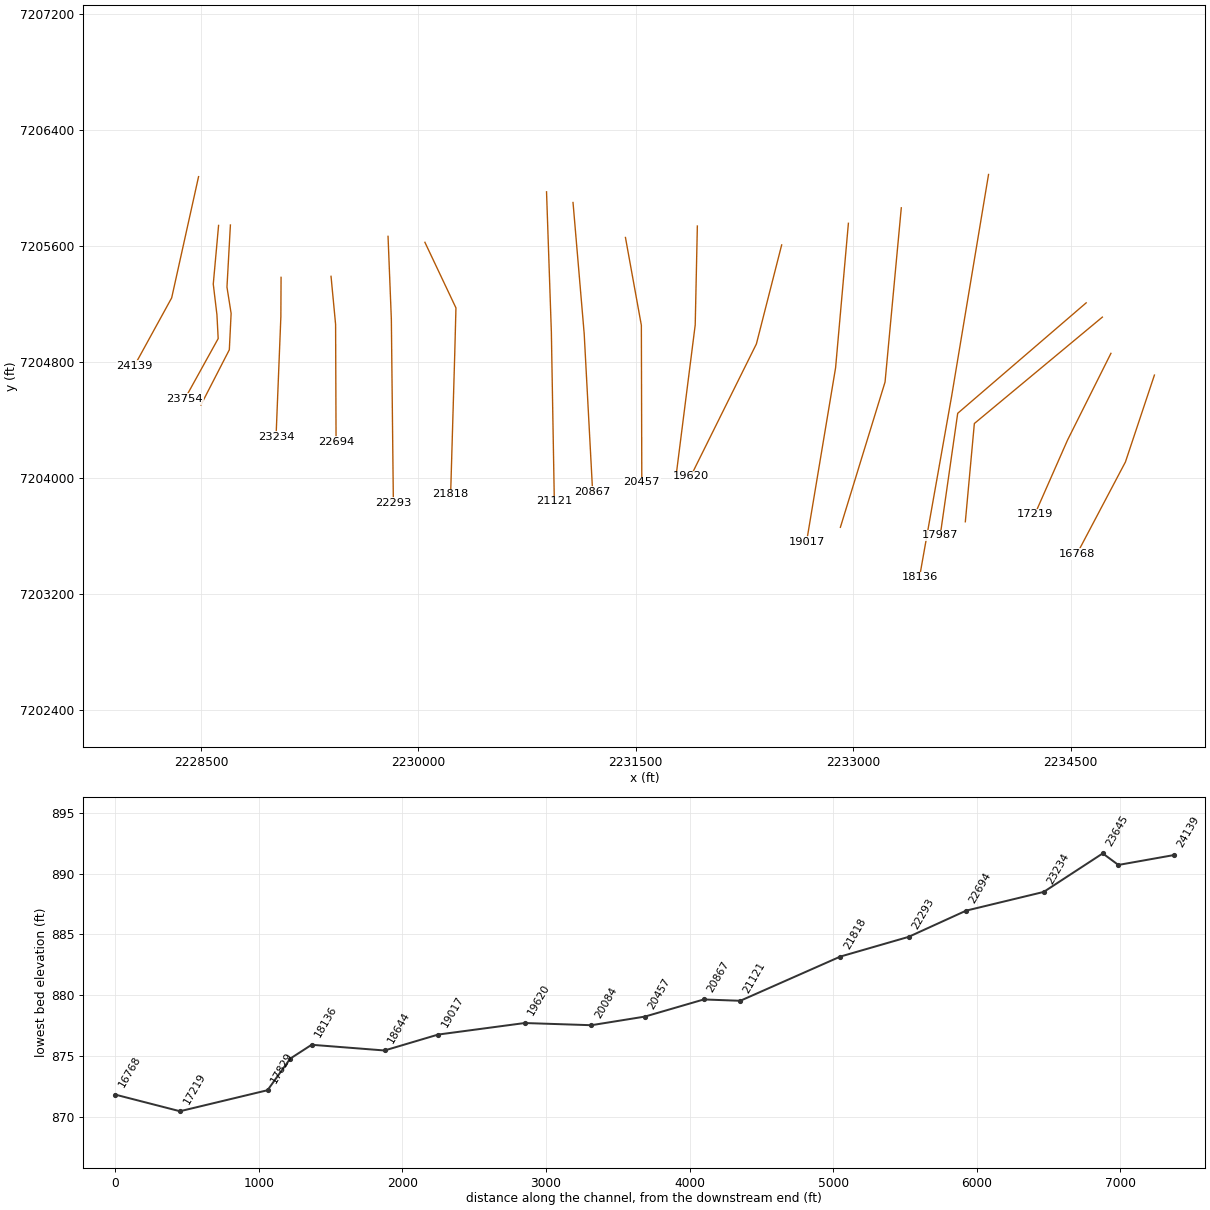
HEC-RAS study Panther Creek.prj: Panther Creek Base Level Engineering

--- Panther Creek.g01 (geometry) --- (continued)

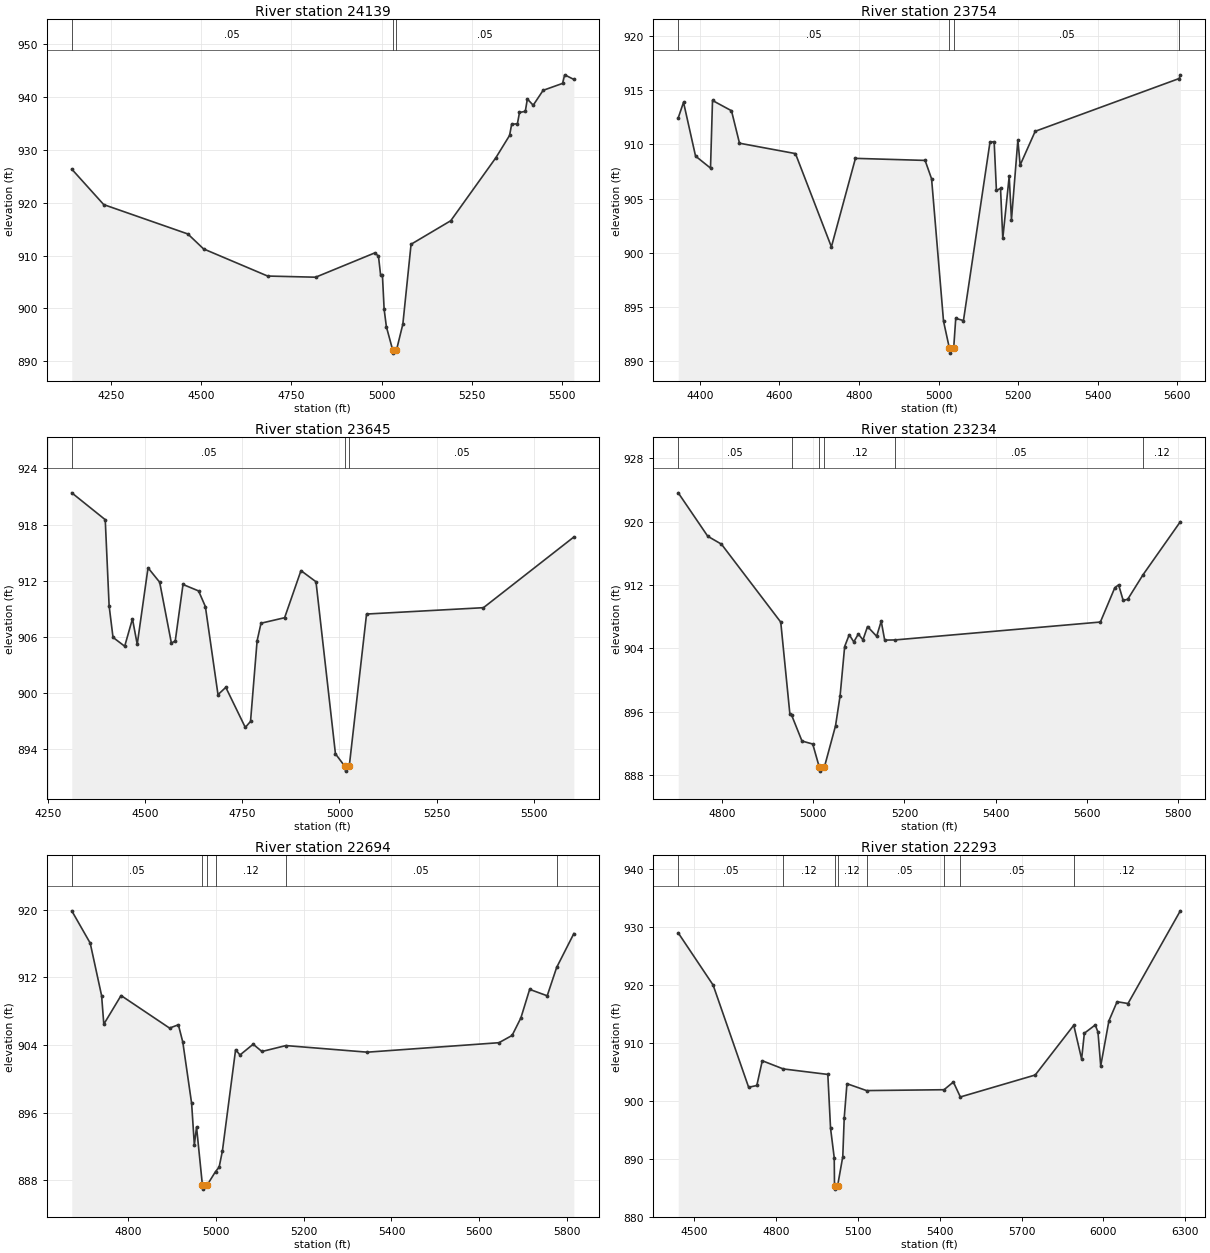
Type RM Length L Ch R = 1 ,24139   ,385,385,385
BEGIN DESCRIPTION:
Panther Creek 43.0
END DESCRIPTION:
XS GIS Cut Line= 3
      2228483.47      7206080.11       2228297.9      7205243.13
       2228040.8       7204774.3
#Sta/Elev= 30
  4140.9  926.37  4229.5  919.65  4462.7  914.09  4506.3  911.26  4683.9  906.12
    4817   905.9  4980.9   910.5  4991.2   909.9  4997.2  906.27  5002.2  906.27
  5006.9  899.85  5013.2  896.51    5031  892.02  5032.4  891.52  5040.9  892.02
  5058.8  897.01  5081.6  912.14  5191.7   916.6  5316.8  928.54  5354.7  932.75
  5360.4  934.84  5376.5  934.98  5382.2   937.1  5398.3  937.31    5404  939.65
  5420.2  938.47  5447.7  941.29  5501.7  942.61  5507.4  944.23  5532.9  943.36
#Mann= 3 ,-1 , 0
  4140.9     .05       0    5031    .033       0  5040.9     .05       0
Bank Sta=5031,5040.9
XS Rating Curve= 0 ,0
Exp/Cntr=0.3,0.1

Type RM Length L Ch R = 1 ,23754   ,109,109,109
BEGIN DESCRIPTION:
Panther Creek 42.1
END DESCRIPTION:
XS GIS Cut Line= 5
      2228621.53      7205743.28      2228584.89      7205338.19
       2228610.2      7205126.28       2228618.8      7204961.85
      2228388.25      7204544.73
#Sta/Elev= 30
    4346  912.45  4359.3  913.89  4389.5  908.92  4427.1  907.81  4432.1  914.06
  4479.8  913.11  4499.9  910.11  4640.5  909.15  4730.8  900.53  4791.2  908.71
  4966.2  908.52  4982.5  906.82  5012.5  893.66    5027  891.21  5028.5  890.71
  5038.1  891.21  5043.2  893.92  5062.6  893.72  5129.2   910.2  5139.7  910.25
  5145.4  905.74  5155.7  905.94  5161.4  901.31  5177.5  907.05  5183.2  903.04
  5199.3  910.41    5205  908.09  5242.8  911.21  5604.6  916.09  5607.4  916.43
#Mann= 4 ,-1 , 0
    4346     .05       0    5027    .033       0  5038.1     .05       0
  5604.6     .12       0
Bank Sta=5027,5038.1
XS Rating Curve= 0 ,0
Exp/Cntr=0.3,0.1

Type RM Length L Ch R = 1 ,23645   ,411,411,411
BEGIN DESCRIPTION:
Panther Creek 42.0
END DESCRIPTION:
XS GIS Cut Line= 5
      2228703.17      7205746.06      2228679.43      7205317.32
      2228708.12      7205135.73      2228695.65      7204884.56
      2228499.89      7204503.52
#Sta/Elev= 30
  4310.6  921.39  4396.8  918.52  4406.8  909.32  4416.8  905.95  4446.9     905
  4466.9  907.93  4479.2   905.2    4507  913.38    4537  911.84  4567.1  905.35
  4577.1  905.56  4597.1   911.6  4637.2  910.91  4654.7  909.24  4687.2  899.83
  4707.3  900.61  4757.5  896.33    4771  896.97  4787.9  905.57    4798  907.46
  4858.8  908.05  4900.9  913.08  4939.6  911.89  4989.7  893.51  5014.1  892.16
  5015.7  891.66  5025.2  892.16  5069.8  908.44  5370.9  909.12  5603.7  916.67
#Mann= 3 ,-1 , 0
  4310.6     .05       0  5014.1    .033       0  5025.2     .05       0
Bank Sta=5014.1,5025.2
XS Rating Curve= 0 ,0
Exp/Cntr=0.3,0.1

Type RM Length L Ch R = 1 ,23234   ,540,540,540
BEGIN DESCRIPTION:
Panther Creek 41.0
END DESCRIPTION:
XS GIS Cut Line= 3
      2229052.73      7205384.74      2229051.32      7205112.01
      2229018.11      7204284.91
#Sta/Elev= 30
  4704.3  923.62    4769  918.14    4799  917.14    4929   907.3    4949   895.7
  4953.1  895.52  4975.5  892.29  4999.1  891.91  5013.5  888.99    5015  888.49
  5024.6  888.99  5049.1  894.22  5059.1  898.01  5069.1  904.22  5079.1  905.71
  5089.1   904.8  5099.1   905.8  5109.2  905.06  5119.2  906.74  5139.2  905.51
  5149.2  907.42  5156.8  905.03  5179.5  905.05  5629.6  907.31  5661.3  911.65
  5669.6     912  5679.6  910.03  5689.6  910.19  5723.1  913.28  5804.8  919.97
#Mann= 6 ,-1 , 0
  4704.3     .05       0  4953.1     .12       0  5013.5     .07       0
  5024.6     .12       0  5179.5     .05       0  5723.1     .12       0
Bank Sta=5013.5,5024.6
XS Rating Curve= 0 ,0
Exp/Cntr=0.3,0.1

Type RM Length L Ch R = 1 ,22694   ,401,401,401
BEGIN DESCRIPTION:
Panther Creek 40.0
END DESCRIPTION:
XS GIS Cut Line= 3
      2229397.48      7205391.83        2229429.        7205060.
      2229432.19      7204249.33
#Sta/Elev= 30
  4671.5  919.87  4713.5  916.05  4739.5  909.83  4744.5  906.46  4783.8  909.85
  4894.3     906  4914.4  906.39  4924.5  904.34  4944.6  897.09  4950.8  892.17
  4955.8  894.31  4969.1  887.45  4970.6  886.95  4980.2  887.45    4999  889.02
  5007.3  889.55  5014.8  891.49  5044.8  903.44  5054.8  902.82  5084.8  904.09
  5104.8  903.23  5159.4  903.93  5344.8  903.15  5644.8  904.27  5674.8  905.13
  5694.8   907.2  5714.8  910.58  5754.8  909.82  5776.3  913.17  5815.5  917.18
#Mann= 6 ,-1 , 0
  4671.5     .05       0  4969.1     .07       0  4980.2     .05       0
    4999     .12       0  5159.4     .05       0  5776.3     .12       0
Bank Sta=4969.1,4980.2
XS Rating Curve= 0 ,0
Exp/Cntr=0.3,0.1

Type RM Length L Ch R = 1 ,22293   ,475,475,475
BEGIN DESCRIPTION:
Panther Creek 39.0
END DESCRIPTION:
XS GIS Cut Line= 3
      2229790.85       7205667.8      2229813.66      7205096.57
      2229827.63      7203828.33
#Sta/Elev= 30
  4441.7  929.02  4569.6  920.01  4699.7  902.37  4729.7  902.68  4749.7  906.95
  4826.5  905.54  4989.9  904.59  4999.9  895.29  5013.4  890.21  5014.4  885.29
  5015.9  884.79  5025.5  885.29  5044.7  890.39    5050  897.09    5060  902.99
  5131.9   901.8  5415.8  901.95    5450  903.28  5475.6   900.7    5750  904.49
  5891.2  913.08    5920  907.24    5930   911.7    5970  913.13    5980  911.88
    5990  906.06    6020  913.83    6050  917.14    6090  916.83  6281.7  932.83
#Mann= 8 ,-1 , 0
  4441.7     .05       0  4826.5     .12       0  5014.4     .07       0
  5025.5     .12       0  5131.9     .05       0  5415.8     .12       0
  5475.6     .05       0  5891.2     .12       0
Bank Sta=5014.4,5025.5
XS Rating Curve= 0 ,0
Exp/Cntr=0.3,0.1

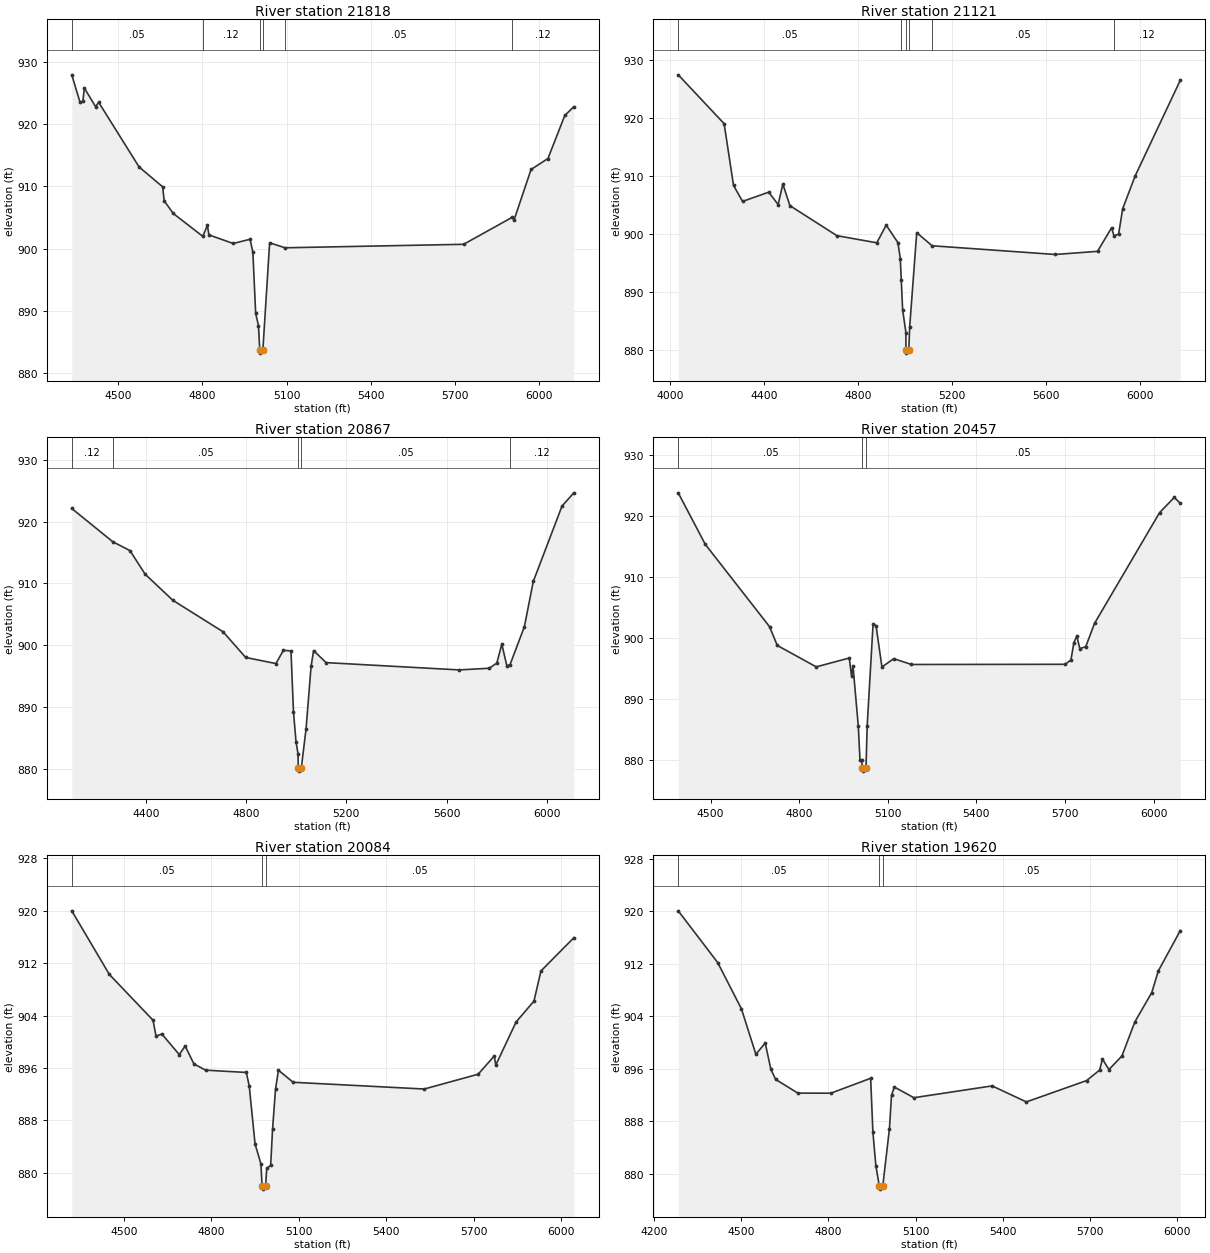
Type RM Length L Ch R = 1 ,21818   ,697,697,697
BEGIN DESCRIPTION:
Panther Creek 38.0
END DESCRIPTION:
XS GIS Cut Line= 4
      2230045.26      7205626.58      2230259.47       7205173.8
      2230251.16      7204857.72      2230222.79      7203887.81
#Sta/Elev= 30
  4335.3  927.95  4364.7  923.53  4374.7  923.67  4380.2  925.82    4420  922.83
  4431.2  923.52  4574.9  913.13  4658.8  909.93  4664.3  907.68  4696.6  905.64
  4801.9  901.96  4818.1  903.73  4823.6   902.2    4910  900.81    4970  901.49
    4980   899.4    4990  889.56    5000   887.6  5004.5  883.67    5006  883.17
  5015.6  883.67  5039.7  900.93  5094.6  900.12  5730.3  900.68  5902.2     905
  5910.4  904.67  5970.4  912.72  6030.5  914.48  6090.5  921.41  6122.7  922.82
#Mann= 6 ,-1 , 0
  4335.3     .05       0  4801.9     .12       0  5004.5     .07       0
  5015.6     .12       0  5094.6     .05       0  5902.2     .12       0
Bank Sta=5004.5,5015.6
XS Rating Curve= 0 ,0
Exp/Cntr=0.3,0.1

Type RM Length L Ch R = 1 ,21121   ,254,254,254
BEGIN DESCRIPTION:
Panther Creek 37.0
END DESCRIPTION:
XS GIS Cut Line= 3
      2230884.46      7205975.39       2230917.8      7205006.03
      2230938.26      7203837.34
#Sta/Elev= 30
  4034.1  927.46  4229.6  919.05  4269.6  908.42  4308.1  905.66  4419.7  907.25
  4459.7  905.11  4479.7  908.65  4509.8  904.93  4709.9  899.76    4880  898.53
    4920  901.58    4970  898.56    4980  895.82  4984.2  892.14  4990.1  886.96
    5004  883.06  5004.1  880.03  5005.7  879.53  5016.1  880.03  5020.1  884.08
  5050.1  900.28  5115.5  898.02  5640.2  896.52  5820.2  897.06  5880.2  901.12
  5890.4  899.72  5910.2  900.05  5927.3  904.38  5980.2  910.02  6172.9  926.53
#Mann= 6 ,-1 , 0
  4034.1     .05       0  4984.2     .12       0  5004.1     .07       0
  5016.1     .12       0  5115.5     .05       0  5890.4     .12       0
#XS Ineff= 2 , 0
       0                  5880.2       0  901.12
Permanent Ineff=
       F       F
Bank Sta=5004.1,5016.1
XS Rating Curve= 0 ,0
Exp/Cntr=0.3,0.1

Type RM Length L Ch R = 1 ,20867   ,410,410,410
BEGIN DESCRIPTION:
Panther Creek 36.0
END DESCRIPTION:
XS GIS Cut Line= 3
      2231067.27      7205901.57      2231144.38       7204994.9
      2231202.61      7203902.99
#Sta/Elev= 30
  4104.4  922.12    4268  916.74  4336.8   915.3    4397   911.5  4507.4  907.28
  4708.1  902.18  4798.5  898.02  4918.9  897.04    4949  899.18  4979.1  899.08
  4989.1  889.23  4999.2   884.4    5007  882.49  5008.3  880.14  5009.9  879.64
  5020.3  880.14  5039.3  886.49  5059.3  896.58  5069.3  899.13  5119.4  897.19
  5650.1  896.01  5770.3  896.28  5800.4  897.11  5820.4  900.17  5840.4  896.68
  5853.1  896.85  5910.5  903.01  5945.9  910.31  6060.7  922.52  6107.8  924.65
#Mann= 5 ,-1 , 0
  4104.4     .12       0    4268     .05       0  5008.3    .033       0
  5020.3     .05       0  5853.1     .12       0
#XS Ineff= 2 , 0
       0                  5820.4       0  900.17
Permanent Ineff=
       F       F
Bank Sta=5008.3,5020.3
XS Rating Curve= 0 ,0
Exp/Cntr=0.3,0.1

Type RM Length L Ch R = 1 ,20457   ,373,373,373
BEGIN DESCRIPTION:
Panther Creek 35.0
END DESCRIPTION:
XS GIS Cut Line= 3
      2231429.01      7205659.97       2231538.8      7205053.54
      2231541.89      7203969.63
#Sta/Elev= 30
  4390.3  923.82  4481.7  915.39  4699.6  901.89  4725.6  898.82  4857.7  895.31
  4969.5  896.76  4977.1  893.83  4982.2  895.42    5000  885.62  5005.8  880.07
  5010.9  880.07  5014.1  878.73  5015.8  878.23  5026.1  878.73  5030.1  885.61
  5050.1  902.31  5060.1  902.05  5080.1  895.29  5120.1  896.65  5180.1   895.7
  5700.1  895.73  5720.1  896.43  5730.1  899.29  5740.1  900.36  5750.1  898.31
  5770.1   898.6  5800.1  902.44  6020.1  920.56  6070.1  923.07  6090.5   922.1
#Mann= 3 ,-1 , 0
  4390.3     .05       0  5014.1    .033       0  5026.1     .05       0
#XS Ineff= 2 , 0
       0                  5740.1       0  900.36
Permanent Ineff=
       F       F
Bank Sta=5014.1,5026.1
XS Rating Curve= 0 ,0
Exp/Cntr=0.3,0.1

Type RM Length L Ch R = 1 ,20084   ,464,464,464
BEGIN DESCRIPTION:
Panther Creek 34.0
END DESCRIPTION:
XS GIS Cut Line= 3
      2231925.17        7205739.      2231910.45      7205056.59
      2231779.65      7204024.21
#Sta/Elev= 30
  4320.9     920  4449.9  910.29    4600  903.29    4610  900.87    4630   901.2
    4690  898.05    4710  899.37    4740  896.64    4780  895.68    4920  895.33
    4930  893.26    4950  884.41    4970   881.4  4974.1  878.02  4975.7  877.52
  4986.1  878.02  4990.1  880.69  5003.5  881.13  5010.1  886.72  5020.2  892.78
  5030.3  895.67  5080.7  893.83  5530.7   892.8  5715.7  895.06    5771  897.85
  5776.2  896.46    5846  903.04  5907.2  906.22  5931.2  910.82  6044.1  915.89
#Mann= 3 ,-1 , 0
  4320.9     .05       0  4974.1    .033       0  4986.1     .05       0
Bank Sta=4974.1,4986.1
XS Rating Curve= 0 ,0
Exp/Cntr=0.3,0.1

Type RM Length L Ch R = 1 ,19620   ,603,603,603
BEGIN DESCRIPTION:
Panther Creek 33.0
END DESCRIPTION:
XS GIS Cut Line= 3
      2232506.97      7205608.69      2232332.57        7204925.
      2231879.01      7204010.03
#Sta/Elev= 30
  4283.5  920.08  4419.2   912.2  4500.9  905.15  4550.5  898.24  4582.7  899.94
  4602.1  895.95  4618.4  894.41  4694.9  892.32  4808.5  892.31  4945.3  894.58
    4953  886.38  4963.3  881.24    4975   878.2  4976.7   877.7    4987   878.2
  5009.9  886.89    5017  891.99  5026.7  893.25    5094  891.62    5363  893.42
  5480.7  890.98    5688  894.23  5732.9  895.83  5742.5  897.51  5764.8  895.91
  5809.4  897.97  5854.1  903.18  5912.2  907.64  5934.7  910.93  6010.3  917.08
#Mann= 3 ,-1 , 0
  4283.5     .05       0    4975    .033       0    4987     .05       0
Bank Sta=4975,4987
XS Rating Curve= 0 ,0
Exp/Cntr=0.3,0.1

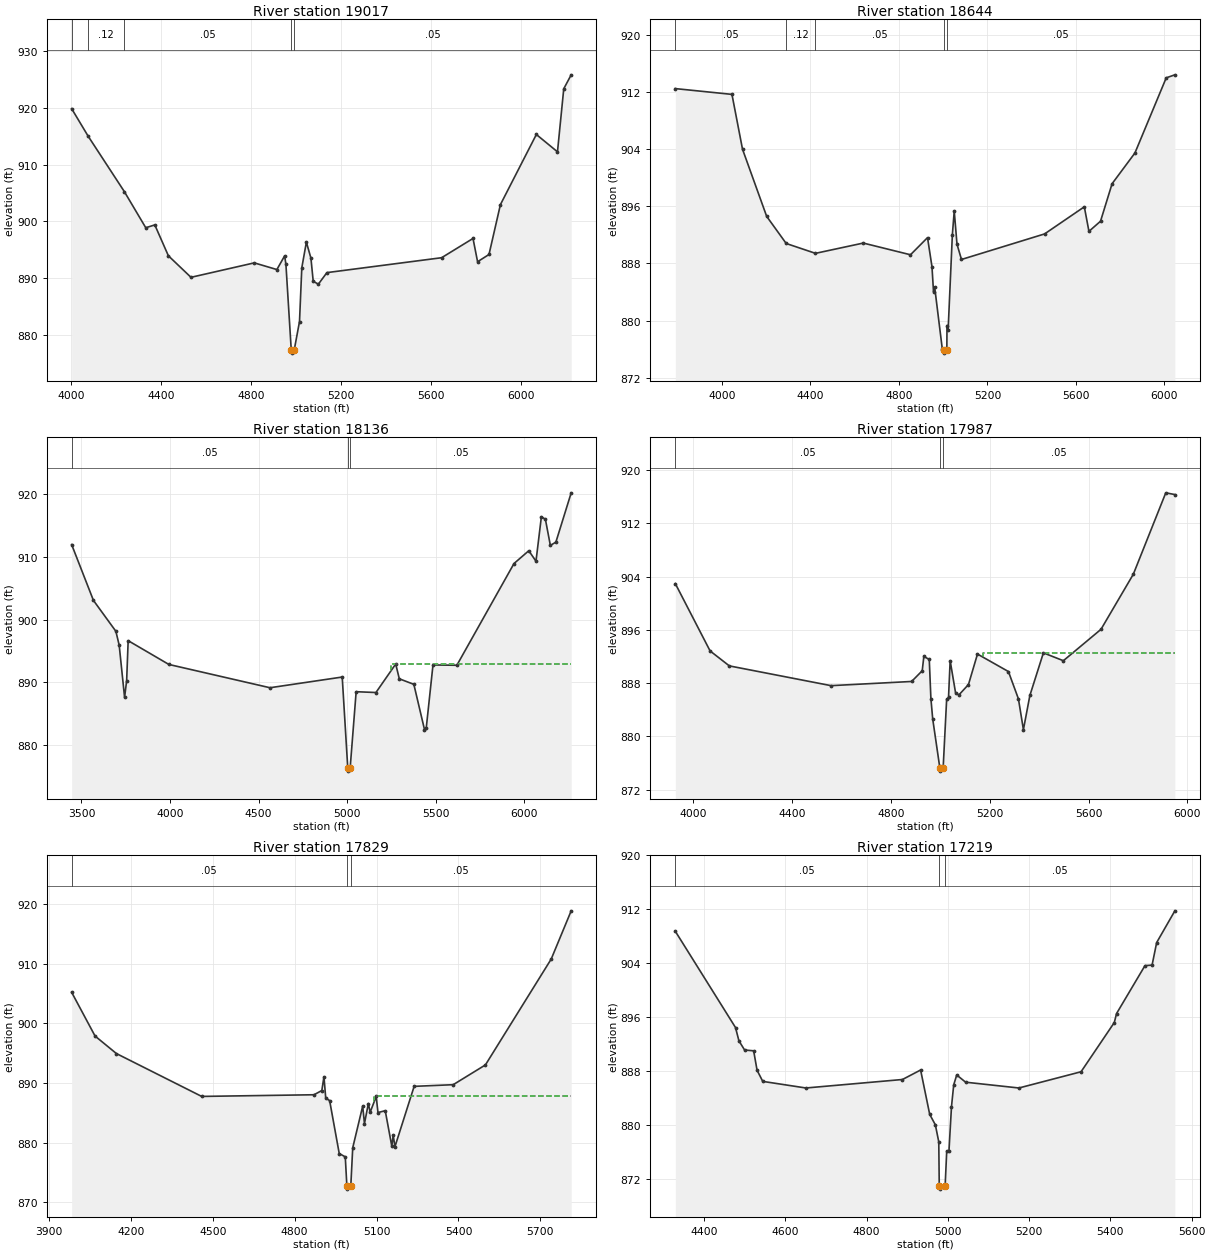
Type RM Length L Ch R = 1 ,19017   ,373,373,373
BEGIN DESCRIPTION:
Panther Creek 32.0
END DESCRIPTION:
XS GIS Cut Line= 3
      2232967.41      7205757.89        2232879.        7204760.
      2232678.99      7203559.95
#Sta/Elev= 30
  4002.6   919.9  4075.9  915.04  4236.6  905.26  4331.8  898.88  4371.9  899.38
  4432.2  893.93  4532.6  890.13  4813.7  892.68    4914   891.5  4948.5  893.92
  4954.2   892.4  4977.9  877.25  4979.7  876.75  4990.8  877.25  5014.5  882.32
  5024.7  891.81    5045  896.34  5065.2  893.52  5075.4  889.43  5098.2  888.92
  5136.2  890.96  5645.6  893.59    5785  896.99  5805.3  892.88    5856  894.16
  5906.7  902.96  6066.3  915.34  6160.1  912.28    6188  923.41    6221  925.87
#Mann= 5 ,-1 , 0
  4002.6     .05       0  4075.9     .12       0  4236.6     .05       0
  4977.9    .033       0  4990.8     .05       0
#XS Ineff= 2 , 0
       0                    5045       0  896.34
Permanent Ineff=
       F       F
Bank Sta=4977.9,4990.8
XS Rating Curve= 0 ,0
Exp/Cntr=0.3,0.1

Type RM Length L Ch R = 1 ,18644   ,508,508,508
BEGIN DESCRIPTION:
Panther Creek 31.0
END DESCRIPTION:
XS GIS Cut Line= 3
      2233332.39      7205864.83      2233220.37       7204662.2
      2232912.14      7203658.81
#Sta/Elev= 30
  3789.4   912.5  4045.3  911.69    4093  904.01  4202.2   894.6  4290.5   890.8
  4422.8  889.42  4638.8  890.86  4852.1  889.22  4929.1  891.62  4949.2  887.56
  4956.2  884.03  4961.2  884.73  4995.8  876.04  5003.5  875.94  5005.3  875.44
  5016.4  875.94  5017.1  879.31  5022.3  878.75  5041.4  892.05  5049.8  895.34
  5062.3   890.7  5082.5  888.56  5458.1  892.14  5637.7  895.94  5658.6   892.5
  5710.9  893.92  5763.1  899.17  5866.4  903.48  6007.8  914.01  6046.9  914.43
#Mann= 5 ,-1 , 0
  3789.4     .05       0  4290.5     .12       0  4422.8     .05       0
  5003.5    .033       0  5016.4     .05       0
#XS Ineff= 2 , 0
       0                  5049.8       0  895.34
Permanent Ineff=
       F       F
Bank Sta=5003.5,5016.4
XS Rating Curve= 0 ,0
Exp/Cntr=0.3,0.1

Type RM Length L Ch R = 1 ,18136   ,149,149,149
BEGIN DESCRIPTION:
Panther Creek 30.0
END DESCRIPTION:
XS GIS Cut Line= 3
      2233934.44       7206094.9        2233679.        7204560.
      2233458.14      7203314.24
#Sta/Elev= 30
  3444.4  911.91  3567.4  903.04  3694.2  898.13  3712.9  895.92  3743.4  887.62
  3755.1  890.31  3763.6  896.64  3993.5  892.86  4564.5  889.16  4972.5  890.86
  5003.8  876.41  5005.8  875.91  5017.3  876.41  5051.2  888.53  5162.9   888.4
  5274.6  892.93  5294.9  890.58    5377   889.7  5437.1  882.52  5447.3  882.83
  5485.1  892.78  5619.9  892.73  5942.7   908.9  6026.2  910.93  6066.8  909.26
  6097.3  916.34  6120.1  915.91    6148  911.77  6179.2   912.3  6265.6  920.13
#Mann= 3 ,-1 , 0
  3444.4     .05       0  5003.8    .033       0  5017.3     .05       0
#XS Ineff= 2 , 0
       0  3763.6  896.64  5246.5       0  892.86
Permanent Ineff=
       F       F
Bank Sta=5003.8,5017.3
XS Rating Curve= 0 ,0
Exp/Cntr=0.3,0.1

Type RM Length L Ch R = 1 ,17987   ,158,158,158
BEGIN DESCRIPTION:
Panther Creek 29.1
END DESCRIPTION:
XS GIS Cut Line= 3
      2234608.15      7205208.73      2233721.61        7204446.
      2233601.02      7203603.58
#Sta/Elev= 30
  3928.7  902.96  4069.3  892.84  4147.2  890.59  4558.6  887.62  4884.5  888.25
  4927.3  889.86  4933.9  892.01  4955.8  891.56  4962.4  885.68  4969.7  882.62
  4998.5  875.27  5000.4  874.77    5012  875.27  5026.1  885.56  5033.7  885.84
  5040.3  891.38  5062.1  886.56  5075.5  886.22  5114.4  887.79  5150.8  892.37
    5276  889.74  5316.4  885.64  5336.6  881.01  5362.7  886.14  5417.4  892.55
  5498.2  891.37  5650.4  896.09  5781.1  904.37  5912.4  916.61  5949.2  916.35
#Mann= 3 ,-1 , 0
  3928.7     .05       0  4998.5    .033       0    5012     .05       0
#XS Ineff= 2 , 0
       0                    5175       0  892.53
Permanent Ineff=
       F       F
Bank Sta=4998.5,5012
XS Rating Curve= 0 ,0
Exp/Cntr=0.3,0.1

Type RM Length L Ch R = 1 ,17829   ,610,610,610
BEGIN DESCRIPTION:
Panther Creek 29.0
END DESCRIPTION:
XS GIS Cut Line= 3
      2234719.71      7205110.12      2233836.52      7204375.53
      2233774.27      7203697.14
#Sta/Elev= 30
    3983  905.23  4068.8  897.88    4147  894.94  4459.4  887.74  4870.8  888.02
  4899.5  888.73  4907.3  891.05  4913.8  887.46  4928.1  887.04  4963.3  878.15
  4985.4  877.59  4991.3  872.67  4993.3  872.17  5005.6  872.67  5012.7  879.11
  5049.2  886.11  5055.7  883.18    5070  886.55  5076.5  885.08  5098.7  887.73
  5105.2  885.03  5131.8  885.34  5155.9  879.37  5160.9  881.24  5167.4   879.3
  5237.7  889.43  5380.8  889.71  5498.8  893.03  5739.8  910.81    5813  918.91
#Mann= 3 ,-1 , 0
    3983     .05       0  4991.3    .033       0  5005.6     .05       0
#XS Ineff= 2 , 0
       0                  5090.8       0  887.86
Permanent Ineff=
       F       F
Bank Sta=4991.3,5005.6
XS Rating Curve= 0 ,0
Exp/Cntr=0.3,0.1

Type RM Length L Ch R = 1 ,17219   ,451,451,451
BEGIN DESCRIPTION:
Panther Creek 28.0
END DESCRIPTION:
XS GIS Cut Line= 3
      2234778.98      7204859.96        2234479.        7204260.
      2234253.87      7203748.64
#Sta/Elev= 30
  4329.2  908.73  4477.3  894.44  4485.7  892.47  4499.7   891.1    4522  890.98
  4530.4  888.09  4544.4  886.44  4650.6  885.46  4888.2  886.72  4932.9  888.13
  4955.3  881.54  4969.2  879.99  4977.6  877.46  4978.8  870.94  4980.8  870.44
  4993.3  870.94  4997.2  876.12  5002.7  876.12  5008.9  882.69  5014.4  885.93
  5021.8  887.39  5043.7  886.32  5174.8  885.46  5327.8  887.87  5409.6  895.18
  5415.2  896.52  5485.1  903.63  5502.6  903.71  5513.9  907.06  5558.7  911.77
#Mann= 3 ,-1 , 0
  4329.2     .05       0  4978.8     .04       0  4993.3     .05       0
Bank Sta=4978.8,4993.3
XS Rating Curve= 0 ,0
Exp/Cntr=0.3,0.1

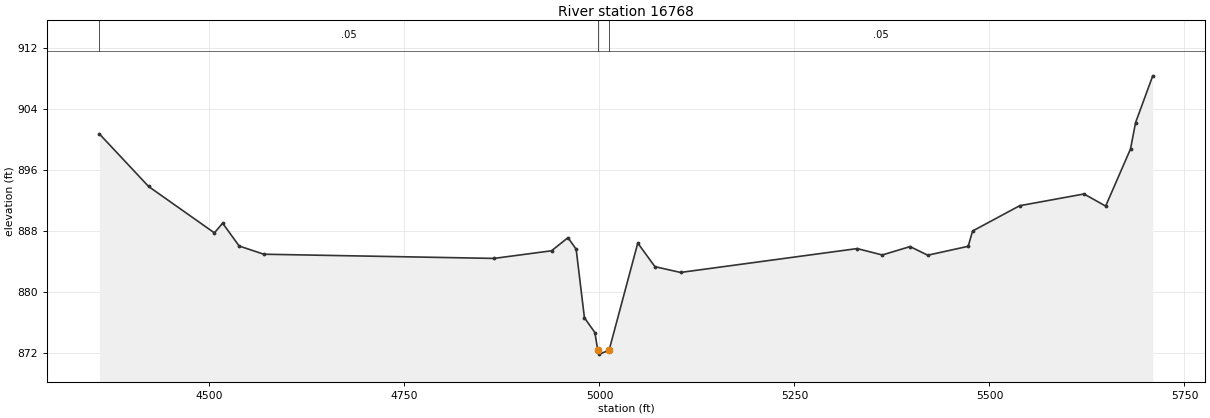
Type RM Length L Ch R = 1 ,16768   ,447,447,447
BEGIN DESCRIPTION:
Panther Creek 27.0
END DESCRIPTION:
XS GIS Cut Line= 3
      2235078.99      7204709.98        2234879.        7204110.
      2234544.09      7203474.82
#Sta/Elev= 30
  4358.8  900.69    4422  893.79  4506.3  887.71  4516.9  888.98    4538  885.99
  4569.6  884.91  4864.7  884.36  4938.5  885.36  4959.6  887.08  4970.1  885.57
  4980.7  876.58  4994.1  874.64  4997.8  872.31  4999.8  871.81  5012.3  872.31
  5049.1  886.37  5071.1  883.28  5103.9  882.52  5330.4  885.65  5362.5  884.81
  5398.2  885.91  5420.8  884.78  5472.7  885.95  5478.3  887.95  5538.7  891.27
  5621.2  892.81  5648.9  891.22  5680.8  898.71  5687.3  902.17  5709.3   908.3
#Mann= 3 ,-1 , 0
  4358.8     .05       0  4997.8    .033       0  5012.3     .05       0
Bank Sta=4997.8,5012.3
XS Rating Curve= 0 ,0
Exp/Cntr=0.3,0.1