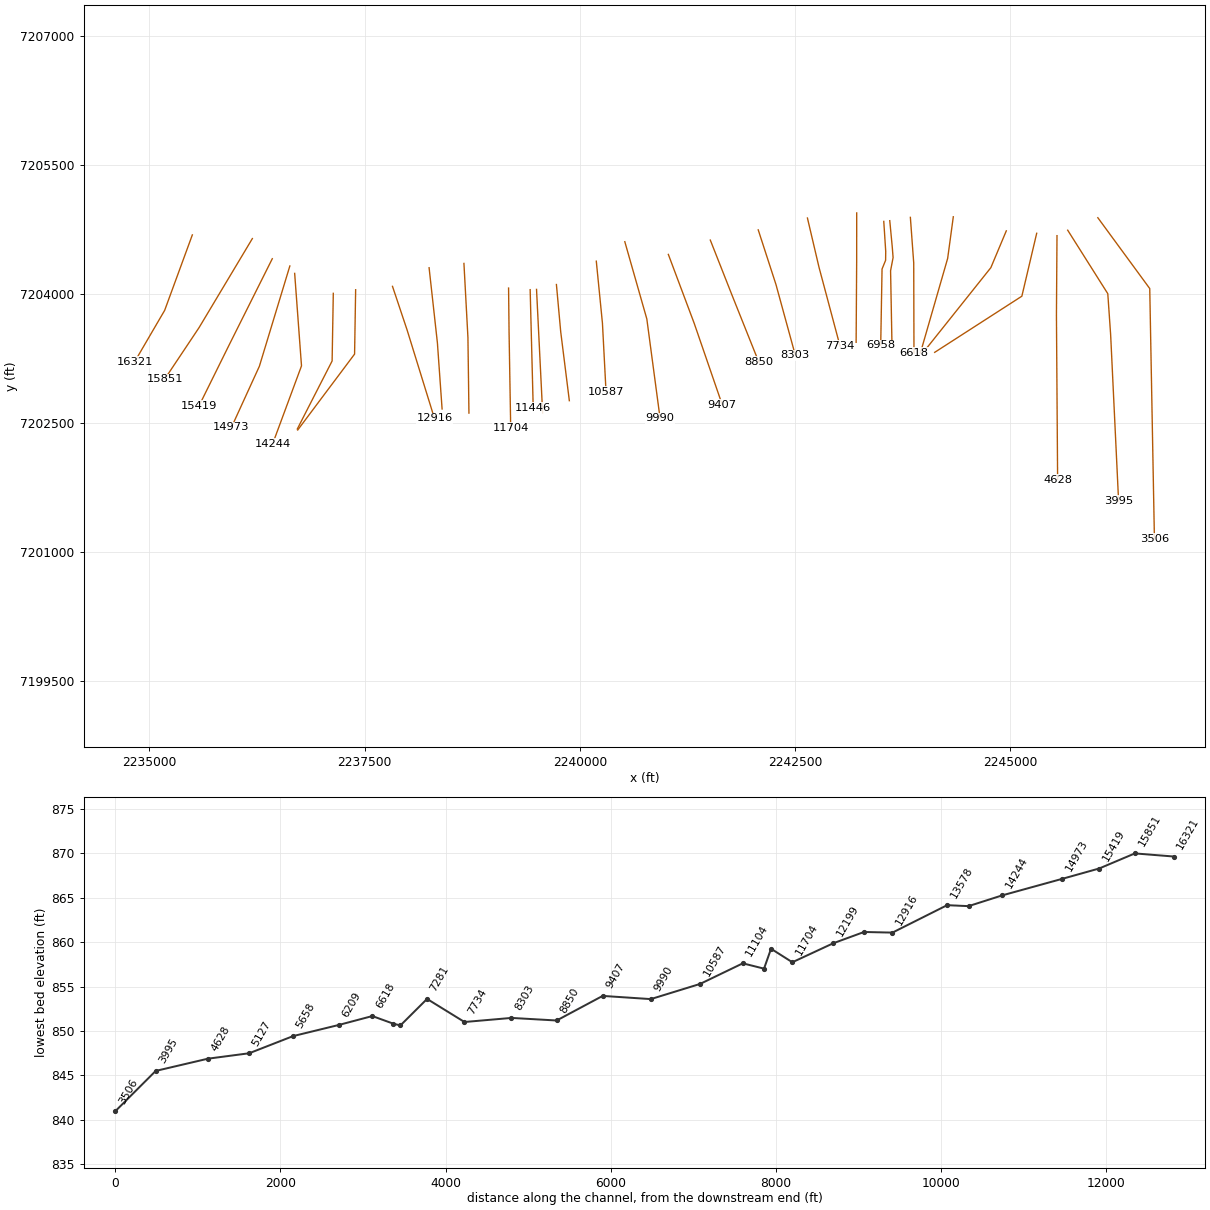
HEC-RAS study Panther Creek.prj: Panther Creek Base Level Engineering

--- Panther Creek.g01 (geometry) --- (continued)

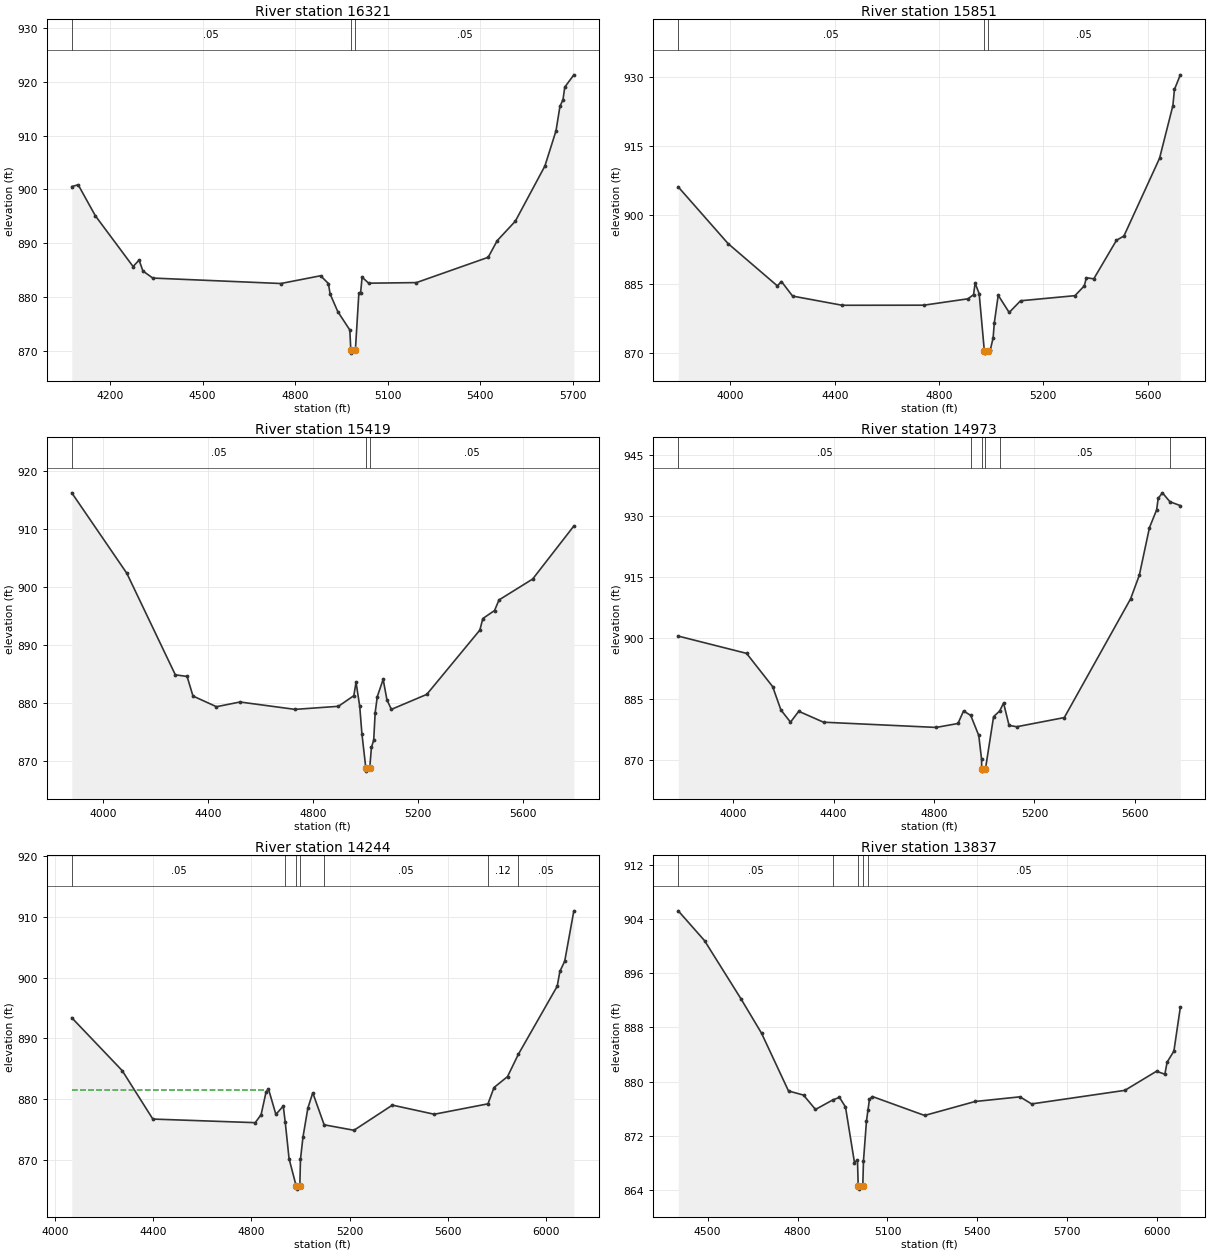
Type RM Length L Ch R = 1 ,16321   ,470,470,470
BEGIN DESCRIPTION:
Panther Creek 26.0
END DESCRIPTION:
XS GIS Cut Line= 3
      2235500.33      7204686.74        2235179.        7203810.
        2234829.      7203209.99
#Sta/Elev= 30
  4075.9  900.54  4096.7  900.87  4152.4  895.12  4274.8  885.71  4294.2   886.9
  4306.7  884.88  4338.7  883.57  4754.1  882.56    4883     884  4908.2  882.56
  4913.8  880.62  4938.7  877.35  4977.7  873.94    4981  870.15    4983  869.65
  4995.7  870.15    5007  880.74  5012.6  880.74  5017.5  883.73    5039  882.62
  5193.7  882.73  5426.4  887.42  5455.8  890.51  5514.5  894.12  5610.4  904.35
  5646.4  910.87  5659.2   915.4  5669.1  916.66  5674.9  918.98  5704.3  921.26
#Mann= 3 ,-1 , 0
  4075.9     .05       0    4981    .033       0  4995.7     .05       0
Bank Sta=4981,4995.7
XS Rating Curve= 0 ,0
Exp/Cntr=0.3,0.1

Type RM Length L Ch R = 1 ,15851   ,432,432,432
BEGIN DESCRIPTION:
Panther Creek 25.0
END DESCRIPTION:
XS GIS Cut Line= 3
      2236197.59       7204644.1        2235579.        7203610.
        2235179.      7203010.01
#Sta/Elev= 30
  3799.6  906.16  3990.8  893.83  4179.9  884.63  4195.5  885.58  4238.3  882.41
  4428.9  880.41    4742  880.43  4911.2  881.82  4932.6  882.73  4938.5  885.22
    4954  882.95  4973.9   870.5  4975.9     870  4988.6   870.5  4996.8   870.7
  5007.6  873.32  5012.1  876.57  5027.1  882.59  5069.2  878.84  5112.8  881.39
  5321.6   882.5  5357.6  884.65  5365.2   886.4  5393.7  886.16  5480.8  894.55
  5509.4  895.48  5646.1  912.39  5697.2  923.84  5703.2  927.36  5725.7  930.54
#Mann= 3 ,-1 , 0
  3799.6     .05       0  4973.9     .04       0  4988.6     .05       0
Bank Sta=4973.9,4988.6
XS Rating Curve= 0 ,0
Exp/Cntr=0.3,0.1

Type RM Length L Ch R = 1 ,15419   ,446,446,446
BEGIN DESCRIPTION:
Panther Creek 24.0
END DESCRIPTION:
XS GIS Cut Line= 3
      2236428.99      7204409.98        2235929.        7203410.
      2235577.87      7202699.55
#Sta/Elev= 30
    3882  916.21  4091.6  902.35  4276.1  884.88  4320.8   884.6  4343.2  881.23
  4432.6  879.39  4522.1   880.2  4731.7  878.93  4896.6  879.46  4955.3  881.29
  4963.7   883.6  4977.7  879.47    4986  874.77    5001   868.8    5003   868.3
  5015.8   868.8  5022.3   872.4  5030.9  873.62  5036.5  878.37  5044.6  881.13
  5066.9   884.1  5081.3  880.57  5098.2  878.93  5232.8  881.51  5434.8  892.58
  5446.2  894.57  5490.8  895.95  5507.7  897.77  5635.8  901.37  5792.5   910.5
#Mann= 3 ,-1 , 0
    3882     .05       0    5001    .033       0  5015.8     .05       0
Bank Sta=5001,5015.8
XS Rating Curve= 0 ,0
Exp/Cntr=0.3,0.1

Type RM Length L Ch R = 1 ,14973   ,729,729,729
BEGIN DESCRIPTION:
Panther Creek 23.0
END DESCRIPTION:
XS GIS Cut Line= 3
       2236632.9      7204325.65        2236279.        7203160.
      2235954.56       7202449.9
#Sta/Elev= 30
  3781.8  900.45  4053.8  896.19  4157.7  887.99  4190.6  882.23  4228.7  879.22
  4261.6   881.9  4360.2  879.21  4808.7  877.92  4895.5  878.89  4917.8  881.99
  4946.4  880.87  4978.3  875.94  4989.5  870.03    4990  867.64    4992  867.14
  5004.8  867.64  5037.3  880.58  5061.6  881.98    5077  883.94  5098.9  878.43
  5129.4  878.09  5318.8  880.35  5582.7  909.63  5617.4  915.45  5657.9  927.21
  5686.5   931.6  5692.6  934.44  5709.5  935.79  5739.4  933.59  5780.7  932.64
#Mann= 6 ,-1 , 0
  3781.8     .05       0  4946.4     .12       0    4990     .07       0
  5004.8     .12       0  5061.6     .05       0  5739.4     .12       0
#XS Ineff= 2 , 0
       0  4261.6   881.9               0
Permanent Ineff=
       F       F
Bank Sta=4990,5004.8
XS Rating Curve= 0 ,0
Exp/Cntr=0.3,0.1

Type RM Length L Ch R = 1 ,14244   ,407,407,407
BEGIN DESCRIPTION:
Panther Creek 22.2
END DESCRIPTION:
XS GIS Cut Line= 3
       2236688.8      7204239.51      2236768.28      7203164.42
      2236432.42      7202256.47
#Sta/Elev= 30
  4068.1   893.4  4273.7  884.72  4398.5  876.77  4815.7  876.18  4839.7  877.49
  4859.8   881.2  4869.8   881.7  4899.9  877.54    4930   878.9  4938.1  876.24
  4953.7  870.25  4982.7  865.77  4984.7  865.27  4997.5  865.77  5000.1  870.14
  5010.2  873.78  5030.2  878.56  5050.3  881.08  5096.6  875.83  5218.1  874.93
  5374.7  879.06  5545.3  877.56  5764.2  879.27  5788.9  881.95  5843.9  883.74
  5887.9  887.39  6046.5  898.58  6057.2     901    6077  902.69  6114.2  910.95
#Mann= 7 ,-1 , 0
  4068.1     .05       0  4938.1     .12       0  4982.7     .07       0
  4997.5     .12       0  5096.6     .05       0  5764.2     .12       0
  5887.9     .05       0
#XS Ineff= 2 , 0
       0 4866.72  881.55               0
Permanent Ineff=
       F       F
Bank Sta=4982.7,4997.5
XS Rating Curve= 0 ,0
Exp/Cntr=0.3,0.1

Type RM Length L Ch R = 1 ,13837   ,259,259,259
BEGIN DESCRIPTION:
Panther Creek 22.1
END DESCRIPTION:
XS GIS Cut Line= 3
      2237137.57      7204007.62      2237123.83      7203221.34
      2236719.56      7202430.93
#Sta/Elev= 30
  4402.3  905.28  4489.9  900.87  4610.9  892.29    4680  887.16    4770   878.6
    4820  877.99    4860  875.86    4918  877.28    4940  877.65    4960  876.23
    4990  867.99    5000  868.39  5002.4  864.56  5004.4  864.06  5017.7  864.56
    5020  868.25    5030  874.15  5035.2  875.82    5040  877.37    5050  877.77
  5223.9  874.97  5392.4  877.04  5541.9  877.73  5580.7  876.68  5891.6  878.69
  5997.1  881.52  6024.9  881.08  6032.6  882.88  6055.1   884.5  6076.5  890.98
#Mann= 5 ,-1 , 0
  4402.3     .05       0    4918     .12       0  5002.4     .07       0
  5017.7     .12       0  5035.2     .05       0
Bank Sta=5002.4,5017.7
XS Rating Curve= 0 ,0
Exp/Cntr=0.3,0.1

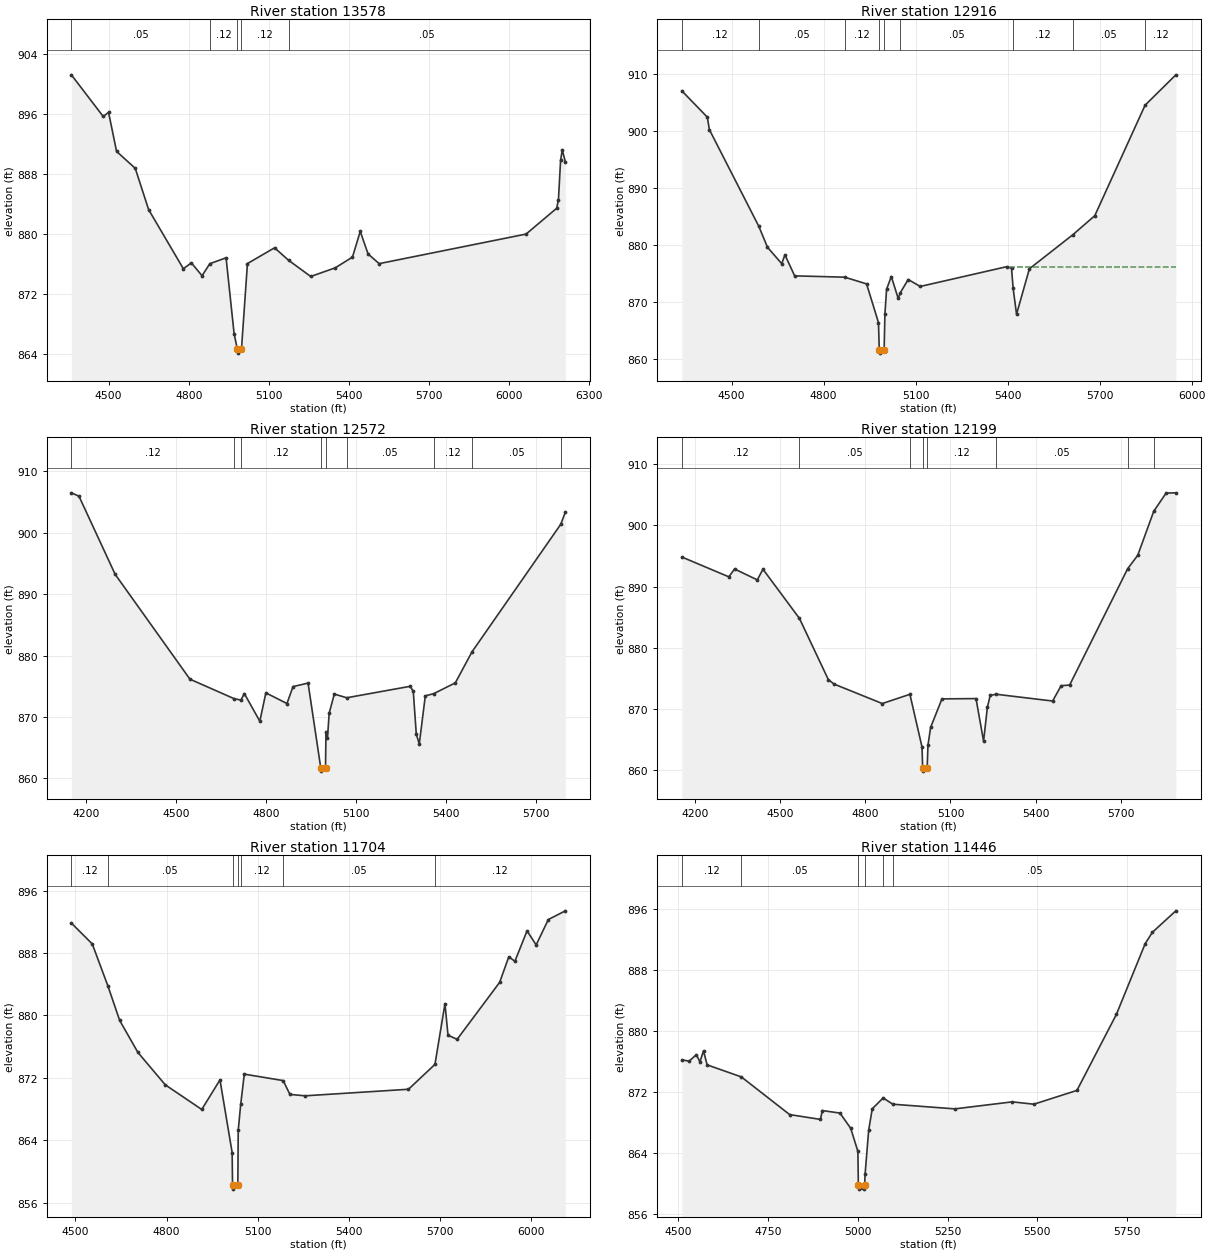
Type RM Length L Ch R = 1 ,13578   ,662,662,662
BEGIN DESCRIPTION:
Panther Creek 22.0
END DESCRIPTION:
XS GIS Cut Line= 3
      2237397.07      7204049.29      2237384.76      7203301.38
       2236724.4      7202419.29
#Sta/Elev= 30
  4360.6  901.24  4479.9  895.69  4499.9  896.24  4529.9  891.04  4599.9  888.78
  4649.9  883.29    4780  875.41    4810  876.19    4850  874.48  4879.1  876.08
    4940  876.87    4970  866.78  4982.3  864.67  4984.3  864.17  4997.6  864.67
    5020   876.1  5121.6   878.2  5173.9  876.54    5257  874.38  5348.7  875.53
  5413.3  876.96  5442.5  880.39  5471.7  877.38  5513.3  876.09  6063.5  880.03
  6178.1  883.47  6184.6  884.58  6192.7  889.84  6198.9  891.23  6210.5  889.66
#Mann= 5 ,-1 , 0
  4360.6     .05       0  4879.1     .12       0  4982.3     .07       0
  4997.6     .12       0  5173.9     .05       0
#XS Ineff= 2 , 0
       0                  5442.5       0  880.39
Permanent Ineff=
       F       F
Bank Sta=4982.3,4997.6
XS Rating Curve= 0 ,0
Exp/Cntr=0.3,0.1

Type RM Length L Ch R = 1 ,12916   ,344,344,344
BEGIN DESCRIPTION:
Panther Creek 21.0
END DESCRIPTION:
XS GIS Cut Line= 3
      2237825.14      7204088.69      2237994.92      7203581.03
      2238312.46      7202553.79
#Sta/Elev= 30
    4338   907.1    4421  902.49  4427.6  900.31  4588.6  883.36  4617.1  879.66
  4663.5  876.78    4674  878.33  4705.7  874.64  4868.9  874.41  4940.2  873.23
    4979  866.43  4981.6  861.58  4983.6  861.08  4997.4  861.58    5000  867.96
  5005.4   872.3  5020.9  874.52  5043.3  870.67  5049.8  871.65  5075.9     874
  5115.1  872.78  5397.7  876.26  5412.7  875.99    5418  872.46  5429.1  867.91
    5471  875.88  5612.7  881.86  5684.2   885.2  5848.2  904.59  5948.5  909.92
#Mann= 9 ,-1 , 0
    4338     .12       0  4588.6     .05       0  4868.9     .12       0
  4981.6     .07       0  4997.4     .12       0  5049.8     .05       0
    5418     .12       0  5612.7     .05       0  5848.2     .12       0
#XS Ineff= 2 , 0
       0                  5407.4       0  876.19
Permanent Ineff=
       F       F
Bank Sta=4981.6,4997.4
XS Rating Curve= 0 ,0
Exp/Cntr=0.3,0.1

Type RM Length L Ch R = 1 ,12572   ,373,373,373
BEGIN DESCRIPTION:
Panther Creek 20.0
END DESCRIPTION:
XS GIS Cut Line= 3
      2238250.17      7204305.28      2238346.83      7203430.75
      2238401.12      7202663.73
#Sta/Elev= 30
  4150.2  906.52  4175.6  905.97  4296.4  893.23    4546  876.14    4694  872.95
  4716.2  872.74  4727.6  873.79  4779.3  869.28  4799.4  873.91  4869.8  872.17
    4890  874.93  4940.3   875.5  4982.7  861.65  4984.7  861.15  4998.5  861.65
    5000  867.59    5005  866.47  5010.7  870.59  5027.9  873.71  5069.3  873.11
  5281.4  874.98  5291.5  874.14  5301.5  867.17  5311.5  865.59  5331.6  873.42
  5359.6  873.78  5431.8  875.54  5487.5   880.6  5783.7  901.39    5799  903.37
#Mann= 9 ,-1 , 0
  4150.2     .12       0    4694     .05       0  4716.2     .12       0
  4982.7     .07       0  4998.5     .12       0  5069.3     .05       0
  5359.6     .12       0  5487.5     .05       0  5783.7     .12       0
#XS Ineff= 2 , 0
       0                  5281.4       0  874.98
Permanent Ineff=
       F       F
Bank Sta=4982.7,4998.5
XS Rating Curve= 0 ,0
Exp/Cntr=0.3,0.1

Type RM Length L Ch R = 1 ,12199   ,495,495,495
BEGIN DESCRIPTION:
Panther Creek 19.0
END DESCRIPTION:
XS GIS Cut Line= 3
      2238654.83       7204355.4      2238701.29      7203493.47
      2238713.05      7202615.63
#Sta/Elev= 30
  4153.4  894.82  4318.9  891.59  4339.1  892.87  4419.2  891.09  4439.2  892.83
  4567.7  884.81  4669.5  874.83  4689.6  874.09  4859.8  870.91  4957.1  872.42
    5000  863.78    5002  860.38    5004  859.88    5018  860.38  5020.8  864.11
  5030.1  867.01  5070.1  871.67  5190.1  871.72  5216.8  864.77  5230.1  870.27
  5240.1  872.23  5260.6  872.43  5460.1  871.32  5490.1  873.82  5520.1  873.93
  5724.6  892.91  5760.1   895.1  5816.6  902.29  5860.1  905.26  5894.5   905.3
#Mann= 8 ,-1 , 0
  4153.4     .12       0  4567.7     .05       0  4957.1     .12       0
    5002     .07       0    5018     .12       0  5260.6     .05       0
  5724.6     .12       0  5816.6     .05       0
#XS Ineff= 2 , 0
       0                  5190.1       0  871.72
Permanent Ineff=
       F       F
Bank Sta=5002,5018
XS Rating Curve= 0 ,0
Exp/Cntr=0.3,0.1

Type RM Length L Ch R = 1 ,11704   ,258,258,258
BEGIN DESCRIPTION:
Panther Creek 18.0
END DESCRIPTION:
XS GIS Cut Line= 3
      2239173.39      7204068.84        2239179.        7203560.
        2239198.      7202444.03
#Sta/Elev= 30
  4486.6  891.84  4555.4  889.16  4607.2  883.74  4645.4  879.37  4705.5  875.26
  4795.5  871.11  4915.5  867.95  4975.5  871.74  5015.5  862.43  5016.8  858.24
  5018.8  857.74  5034.2  858.24  5035.5  865.27  5043.7  868.62  5055.5  872.48
  5183.5  871.65  5205.5  869.88  5255.5   869.7  5595.6  870.54  5682.7  873.73
  5715.6  881.51  5725.6  877.47  5755.6  876.94  5895.6  884.25  5925.6  887.52
  5945.6  886.94  5985.6  890.84  6015.6  889.04  6055.6  892.29  6111.6  893.41
#Mann= 7 ,-1 , 0
  4486.6     .12       0  4607.2     .05       0  5016.8    .033       0
  5034.2     .05       0  5043.7     .12       0  5183.5     .05       0
  5682.7     .12       0
Bank Sta=5016.8,5034.2
XS Rating Curve= 0 ,0
Exp/Cntr=0.3,0.1

Type RM Length L Ch R = 1 ,11446   ,85,85,85
BEGIN DESCRIPTION:
Panther Creek 17.2
END DESCRIPTION:
XS GIS Cut Line= 2
        2239424.      7204050.24      2239459.58       7202674.5
#Sta/Elev= 30
  4509.6   876.2  4529.8  876.04  4549.9  876.88  4559.9  875.94  4569.9  877.39
  4579.9  875.55  4675.3  873.97  4809.9  869.03  4895.7   868.4  4900.7  869.56
    4950  869.23    4980  867.23    5000   864.2  5001.3  859.76  5003.3  859.26
  5016.8  859.26  5018.8  859.76    5020   861.2    5030  866.98    5040  869.79
  5070.3  871.21  5097.4  870.39  5270.1  869.78  5430.2   870.7  5490.2  870.39
  5610.2   872.2  5720.2  882.17  5800.3  891.43  5820.3  892.92  5885.8  895.74
#Mann= 6 ,-1 , 0
  4509.6     .12       0  4675.3     .05       0  5001.3    .033       0
  5018.8     .05       0  5070.3     .12       0  5097.4     .05       0
Bank Sta=5001.3,5018.8
XS Rating Curve= 0 ,0
Exp/Cntr=0.3,0.1

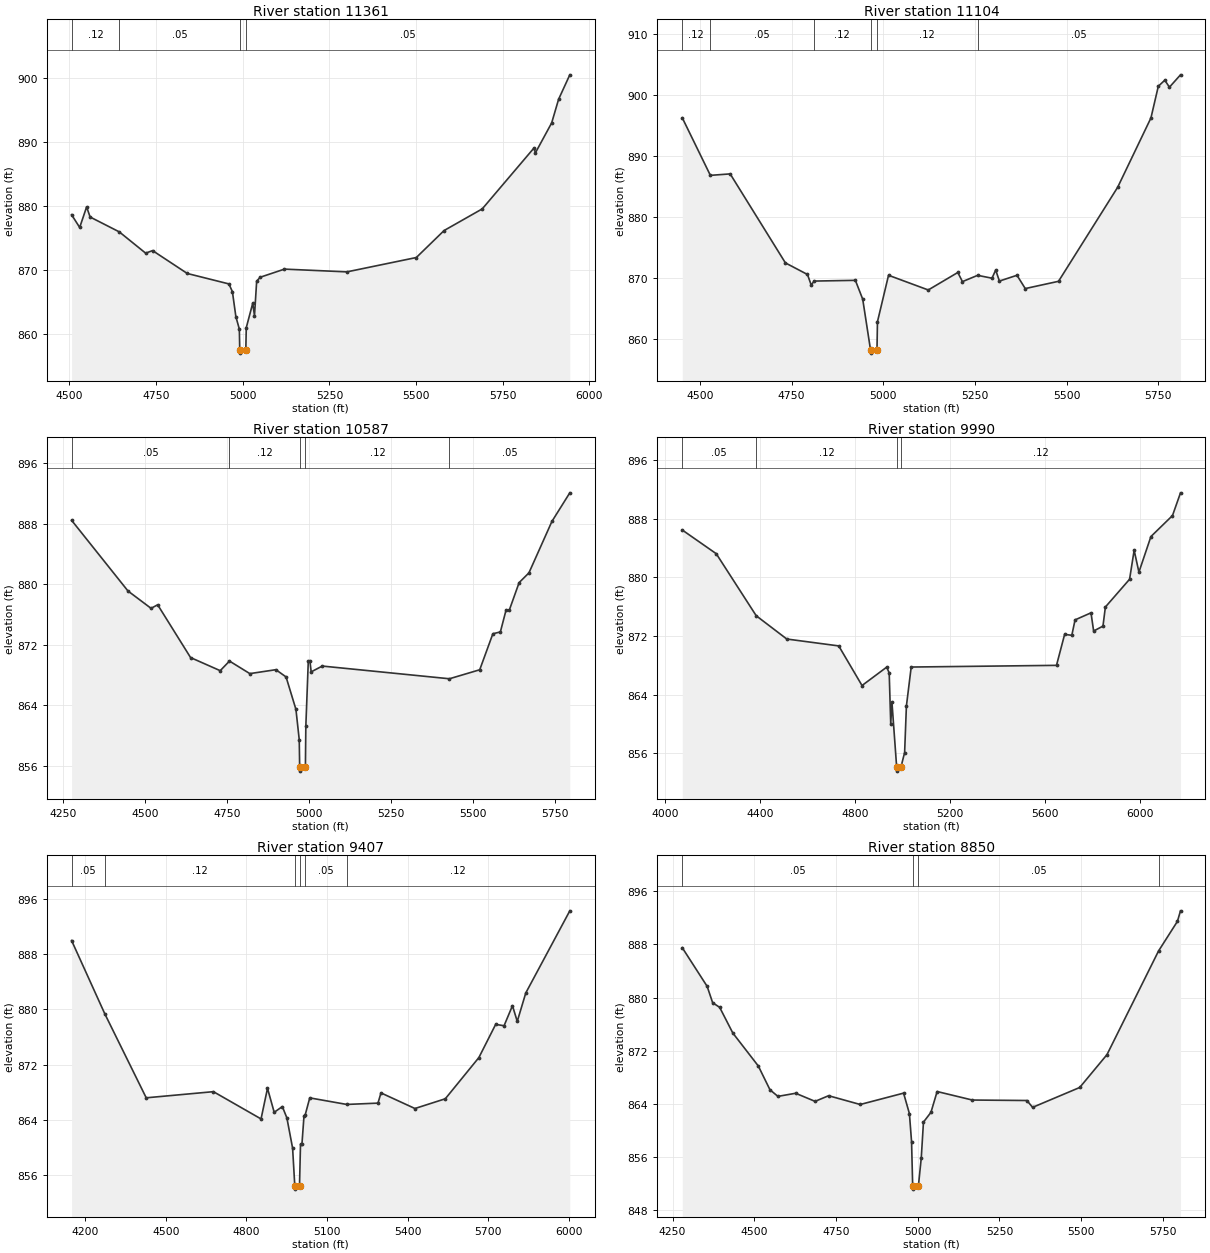
Type RM Length L Ch R = 1 ,11361   ,257,257,257
BEGIN DESCRIPTION:
Panther Creek 17.1
END DESCRIPTION:
XS GIS Cut Line= 2
      2239498.02      7204053.39      2239568.96      7202617.74
#Sta/Elev= 30
    4506  878.62  4529.4  876.63  4549.4  879.84  4559.5  878.26  4643.7  875.94
  4719.7  872.62  4739.7  873.02  4839.8  869.45  4959.9  867.82    4970  866.61
    4980  862.71    4990  860.77  4991.2  857.52  4993.2  857.02  5008.7  857.52
    5010  860.99  5028.7  864.82  5033.7  862.86    5040  868.25  5050.1  868.86
  5120.1  870.13  5300.4   869.7  5500.6  871.94  5580.7  876.15  5690.8  879.53
  5839.4  888.99  5844.4   888.3  5891.1  892.95  5911.1  896.64  5943.4  900.45
#Mann= 4 ,-1 , 0
    4506     .12       0  4643.7     .05       0  4991.2    .033       0
  5008.7     .05       0
Bank Sta=4991.2,5008.7
XS Rating Curve= 0 ,0
Exp/Cntr=0.3,0.1

Type RM Length L Ch R = 1 ,11104   ,517,517,517
BEGIN DESCRIPTION:
Panther Creek 17.0
END DESCRIPTION:
XS GIS Cut Line= 3
        2239729.      7204110.02        2239779.        7203560.
        2239879.      7202760.01
#Sta/Elev= 30
  4452.1  896.22  4528.7  886.78  4582.7  887.02  4733.3  872.42  4793.5  870.52
  4803.6   868.8  4811.7  869.44  4924.1  869.56  4944.1  866.47  4965.5  858.12
  4967.5  857.62    4983  858.12  4984.3  862.77  5014.5  870.39  5122.8  867.98
  5203.4  870.85    5216  869.35  5257.5  870.38  5296.6  869.91  5306.7  871.25
  5316.8  869.44  5364.7  870.39  5387.3  868.21    5478   869.4  5639.3  884.83
    5730   896.2  5750.1   901.4  5767.8  902.39  5780.4  901.24  5810.6  903.27
#Mann= 6 ,-1 , 0
  4452.1     .12       0  4528.7     .05       0  4811.7     .12       0
  4965.5     .07       0    4983     .12       0  5257.5     .05       0
Bank Sta=4965.5,4983
XS Rating Curve= 0 ,0
Exp/Cntr=0.3,0.1

Type RM Length L Ch R = 1 ,10587   ,597,597,597
BEGIN DESCRIPTION:
Panther Creek 16.0
END DESCRIPTION:
XS GIS Cut Line= 3
      2240192.15      7204381.39      2240263.61      7203659.93
      2240305.19       7202865.5
#Sta/Elev= 30
  4274.8  888.46    4447  879.11  4517.4  876.82  4537.5  877.29    4638  870.31
  4728.4  868.58  4756.7  869.85  4818.8  868.19  4898.3  868.71  4929.4  867.75
  4959.5  863.46  4969.6  859.45  4970.9   855.8  4972.9   855.3  4988.4   855.8
  4989.7  861.22  4997.2  869.81  5002.3  869.81    5006  868.42  5039.8  869.19
  5427.9  867.51  5520.4   868.7  5560.5  873.46  5583.4   873.7  5600.5  876.55
  5610.6  876.58  5640.6  880.22  5670.6  881.51  5740.7  888.31  5795.3  892.09
#Mann= 5 ,-1 , 0
  4274.8     .05       0  4756.7     .12       0  4970.9     .07       0
  4988.4     .12       0  5427.9     .05       0
Bank Sta=4970.9,4988.4
XS Rating Curve= 0 ,0
Exp/Cntr=0.3,0.1

Type RM Length L Ch R = 1 ,9990    ,583,583,583
BEGIN DESCRIPTION:
Panther Creek 15.0
END DESCRIPTION:
XS GIS Cut Line= 3
      2240523.44      7204607.58        2240779.        7203710.
      2240932.88      7202556.57
#Sta/Elev= 30
  4073.1  886.46  4216.1  883.23  4384.4  874.77  4512.9   871.6  4731.6  870.66
  4829.6  865.26  4933.6  867.77    4944  866.97  4950.4  860.07  4955.6  862.96
  4975.5  854.09  4977.5  853.59    4993  854.09  5008.9  856.12  5016.4  862.47
  5036.6  867.78  5648.1  868.01  5682.3  872.23  5712.6  872.11  5726.2  874.21
  5793.3  875.17  5804.4  872.69  5843.7  873.36  5853.8  875.96  5955.7  879.75
  5974.9   883.7    5995  880.72  6045.5  885.57  6136.3  888.43    6170  891.53
#Mann= 4 ,-1 , 0
  4073.1     .05       0  4384.4     .12       0  4975.5     .07       0
    4993     .12       0
Bank Sta=4975.5,4993
XS Rating Curve= 0 ,0
Exp/Cntr=0.3,0.1

Type RM Length L Ch R = 1 ,9407    ,557,557,557
BEGIN DESCRIPTION:
Panther Creek 14.0
END DESCRIPTION:
XS GIS Cut Line= 3
      2241029.01      7204459.97        2241329.        7203660.
      2241654.01      7202715.11
#Sta/Elev= 30
  4149.7  889.97  4273.3  879.35  4427.4  867.18  4677.4  868.07  4854.6  864.12
  4878.6  868.56  4903.5  865.08  4933.8  865.91  4950.7  864.27    4972  859.89
  4980.1  854.45  4982.1  853.95  4997.7  854.45  5001.4  860.44  5006.7  860.44
  5014.4  864.56  5018.4  864.64  5035.8  867.17  5173.4  866.22  5289.6  866.41
  5300.8  867.89  5427.1  865.63  5540.1  867.04    5665  873.01  5727.5  877.82
  5758.7  877.62    5790  880.53  5807.8  878.25  5839.5  882.37  6003.3  894.27
#Mann= 6 ,-1 , 0
  4149.7     .05       0  4273.3     .12       0  4980.1     .07       0
  4997.7     .12       0  5018.4     .05       0  5173.4     .12       0
Bank Sta=4980.1,4997.7
XS Rating Curve= 0 ,0
Exp/Cntr=0.3,0.1

Type RM Length L Ch R = 1 ,8850    ,547,547,547
BEGIN DESCRIPTION:
Panther Creek 13.0
END DESCRIPTION:
XS GIS Cut Line= 3
      2241516.37       7204626.4        2241779.        7203960.
      2242079.01      7203209.96
#Sta/Elev= 30
  4279.8  887.49  4355.9  881.68  4372.7  879.22  4394.2  878.52  4434.4  874.66
  4512.4   869.7  4548.1  866.12  4572.4  865.13  4626.6   865.6  4686.1  864.38
  4727.4  865.23  4824.1  863.91  4956.8  865.62  4974.6  862.54  4981.2  858.31
  4984.6  851.68  4986.6  851.18  5002.2  851.68  5010.9  855.88  5017.6  861.26
  5040.5  862.73  5059.4  865.86  5167.1  864.58    5334  864.51  5351.5  863.48
  5495.6  866.47    5579  871.41  5736.6  886.99  5794.4  891.45  5803.9  893.04
#Mann= 4 ,-1 , 0
  4279.8     .05       0  4984.6     .04       0  5002.2     .05       0
  5736.6     .12       0
Bank Sta=4984.6,5002.2
XS Rating Curve= 0 ,0
Exp/Cntr=0.3,0.1

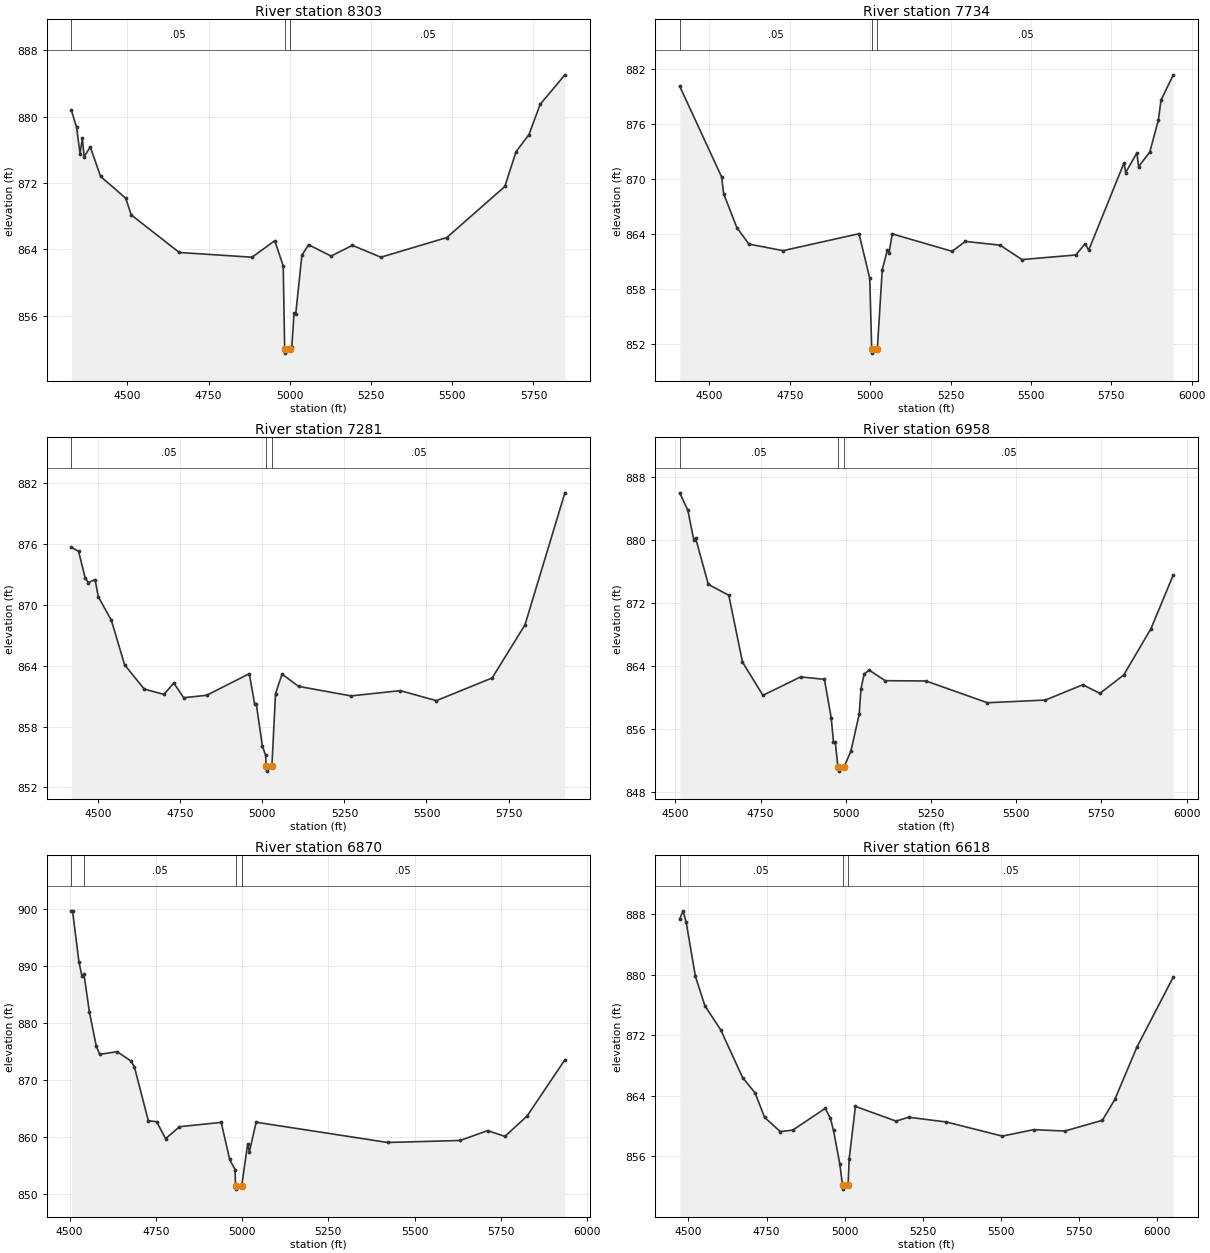
Type RM Length L Ch R = 1 ,8303    ,569,569,569
BEGIN DESCRIPTION:
Panther Creek 12.0
END DESCRIPTION:
XS GIS Cut Line= 3
      2242072.87      7204745.43        2242279.        7204110.
      2242503.46      7203289.37
#Sta/Elev= 30
  4327.8  880.78    4344  878.69  4354.5  875.55  4361.8  877.37  4367.1  875.16
  4386.1  876.35  4417.6   872.8    4495  870.16  4512.2  868.14  4660.1  863.61
  4883.9  863.04  4953.8  865.03  4979.8  861.99  4984.3  851.97  4986.3  851.47
    5002  851.97  5006.2  852.16  5013.1  856.29  5018.3  856.19  5037.3  863.29
    5058  864.54    5127  863.18  5192.8  864.47  5280.5  863.04  5483.1  865.41
  5661.8  871.57  5696.3  875.77    5736  877.83  5770.5  881.48  5846.6  885.04
#Mann= 3 ,-1 , 0
  4327.8     .05       0  4984.3    .033       0    5002     .05       0
Bank Sta=4984.3,5002
XS Rating Curve= 0 ,0
Exp/Cntr=0.3,0.1

Type RM Length L Ch R = 1 ,7734    ,453,453,453
BEGIN DESCRIPTION:
Panther Creek 11.0
END DESCRIPTION:
XS GIS Cut Line= 3
      2242644.45       7204882.8        2242779.        7204310.
      2243023.05      7203395.19
#Sta/Elev= 30
  4407.7   880.1  4537.9  870.22  4544.1  868.41  4585.5  864.68  4622.8   862.9
    4729  862.18  4965.3  864.03  4998.7  859.17  5004.7  851.51  5006.7  851.01
  5022.4  851.51  5037.5  860.08  5053.7  862.27  5058.8  861.94  5068.5  864.01
  5254.8  862.11  5296.2  863.19  5404.2  862.78  5472.2  861.21  5639.6  861.71
  5668.8  862.94  5679.7  862.23  5789.6  871.75  5794.8   870.7  5829.7  872.84
  5834.9  871.33  5869.8  872.94  5896.5  876.42  5904.7  878.59  5942.9  881.35
#Mann= 3 ,-1 , 0
  4407.7     .05       0  5004.7    .033       0  5022.4     .05       0
Bank Sta=5004.7,5022.4
XS Rating Curve= 0 ,0
Exp/Cntr=0.3,0.1

Type RM Length L Ch R = 1 ,7281    ,323,323,323
BEGIN DESCRIPTION:
Panther Creek 10.0
END DESCRIPTION:
XS GIS Cut Line= 3
      2243216.71      7204942.21      2243216.33      7204382.86
        2243210.      7203438.34
#Sta/Elev= 30
  4417.8  875.71    4440  875.28    4460  872.65    4470   872.2    4490  872.51
    4500  870.81    4540  868.47    4580   864.1    4640   861.7    4700  861.18
    4730   862.3    4760  860.85    4830  861.09    4960  863.22  4976.1  860.28
  4981.1  860.28    5000  856.07    5010  855.16  5011.2  854.11  5013.2  853.61
  5028.9  854.11    5040  861.26    5060  863.18    5110  861.97    5270  861.03
    5420  861.55    5530  860.56    5700   862.8    5800  868.03  5921.7  881.06
#Mann= 3 ,-1 , 0
  4417.8     .05       0  5011.2     .04       0  5028.9     .05       0
Bank Sta=5011.2,5028.9
XS Rating Curve= 0 ,0
Exp/Cntr=0.3,0.1

Type RM Length L Ch R = 1 ,6958    ,88,88,88
BEGIN DESCRIPTION:
Panther Creek 9.2
END DESCRIPTION:
XS GIS Cut Line= 5
      2243531.15      7204843.62      2243553.74      7204495.78
      2243552.45      7204391.87      2243511.08      7204290.11
       2243495.6      7203404.69
#Sta/Elev= 30
  4513.1  885.94  4536.8  883.72  4554.4  879.95  4559.4  880.22  4596.9  874.32
    4657  872.94  4697.1  864.46  4757.2  860.24  4867.5  862.58  4937.5  862.27
  4957.5  857.37    4964  854.34  4969.3  854.34  4977.1  851.12  4979.1  850.62
  4994.8  851.12  5015.4  853.19  5039.5  857.85  5044.9   861.1    5054  862.94
  5068.9  863.44  5115.6   862.1  5235.6  862.06  5415.6   859.3  5585.6  859.64
  5695.6  861.58  5745.7  860.49  5815.7  862.83  5895.7  868.72    5961  875.53
#Mann= 3 ,-1 , 0
  4513.1     .05       0  4977.1     .04       0  4994.8     .05       0
Bank Sta=4977.1,4994.8
XS Rating Curve= 0 ,0
Exp/Cntr=0.3,0.1

Type RM Length L Ch R = 1 ,6870    ,252,252,252
BEGIN DESCRIPTION:
Panther Creek 9.1
END DESCRIPTION:
XS GIS Cut Line= 5
      2243600.77      7204852.01      2243629.51      7204548.37
      2243639.29      7204423.79      2243610.12      7204270.29
      2243626.08      7203426.25
#Sta/Elev= 30
  4505.1  899.74  4508.6  899.74  4527.2  890.73  4535.8   888.3  4541.7  888.61
  4557.3     882  4577.4  875.96  4587.5  874.51  4637.7  874.99  4677.9  873.35
  4687.9  872.31  4728.1  862.87  4752.4  862.67  4778.3   859.7  4818.5   861.8
  4939.5  862.56  4963.9  856.05  4979.6  854.27    4981  851.33    4983  850.83
  4998.7  851.33  5016.1  858.77  5021.2  857.42  5040.7  862.59  5421.7  859.03
  5631.7  859.38  5711.7  861.11  5761.7   860.1  5826.1  863.69  5935.5  873.56
#Mann= 4 ,-1 , 0
  4505.1     .12       0  4541.7     .05       0    4981    .033       0
  4998.7     .05       0
Bank Sta=4981,4998.7
XS Rating Curve= 0 ,0
Exp/Cntr=0.3,0.1

Type RM Length L Ch R = 1 ,6618    ,409,409,409
BEGIN DESCRIPTION:
Panther Creek 9.0
END DESCRIPTION:
XS GIS Cut Line= 3
        2243840.      7204890.49        2243879.        7204360.
      2243881.87      7203313.32
#Sta/Elev= 30
  4472.5  887.36    4483  888.42    4493  886.93  4522.6  879.76  4553.2  875.86
  4603.3  872.72  4673.5  866.41  4713.6  864.37  4743.7  861.16  4793.9  859.28
    4834  859.47  4937.7  862.34  4954.3  861.03  4964.3  859.43  4984.4  855.01
  4993.1  852.18  4995.1  851.68  5010.8  852.18  5014.4   855.7  5034.4   862.6
  5164.4  860.66  5204.4  861.17  5324.4  860.55  5504.4  858.68  5604.4  859.53
  5704.4  859.35  5824.4  860.77  5864.4  863.55  5934.4   870.4  6051.1  879.69
#Mann= 3 ,-1 , 0
  4472.5     .05       0  4993.1    .033       0  5010.8     .05       0
Bank Sta=4993.1,5010.8
XS Rating Curve= 0 ,0
Exp/Cntr=0.3,0.1

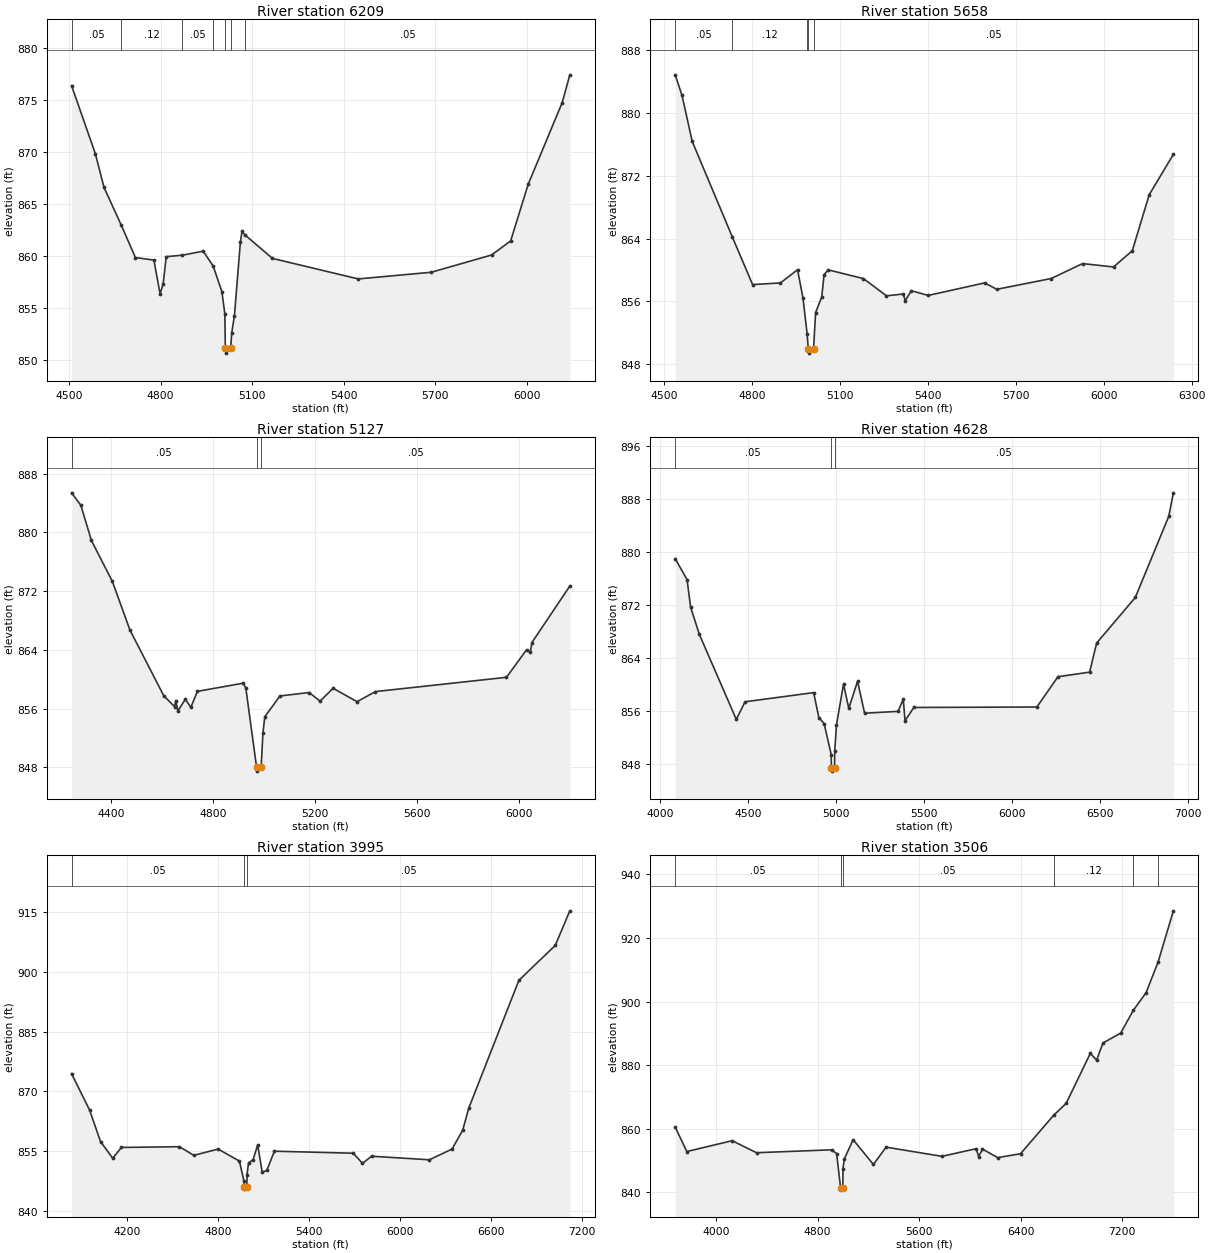
Type RM Length L Ch R = 1 ,6209    ,551,551,551
BEGIN DESCRIPTION:
Panther Creek 8.0
END DESCRIPTION:
XS GIS Cut Line= 3
      2244338.66      7204897.37      2244273.13      7204413.65
      2243956.31       7203313.6
#Sta/Elev= 30
  4508.5  876.37  4586.6  869.81  4614.8  866.59  4671.6  862.95  4717.8  859.85
  4778.3  859.61  4798.5  856.37  4808.6  857.31  4818.7  859.94  4871.8  860.08
  4939.8  860.47  4972.8  859.02  5001.1  856.58  5010.8  854.45  5012.4  851.17
  5014.4  850.67  5030.1  851.17  5033.2   852.6  5042.1  854.25  5061.7  861.33
  5066.9  862.36  5076.3  862.04  5166.9  859.77  5447.9   857.8  5687.3  858.44
    5885   860.1  5947.4  861.45  6004.9  866.89  6116.4  874.74  6141.4  877.41
#Mann= 7 ,-1 , 0
  4508.5     .05       0  4671.6     .12       0  4871.8     .05       0
  4972.8     .12       0  5012.4     .07       0  5030.1     .12       0
  5076.3     .05       0
Bank Sta=5012.4,5030.1
XS Rating Curve= 0 ,0
Exp/Cntr=0.3,0.1

Type RM Length L Ch R = 1 ,5658    ,531,531,531
BEGIN DESCRIPTION:
Panther Creek 7.0
END DESCRIPTION:
XS GIS Cut Line= 3
      2244954.19      7204733.77      2244774.96      7204306.28
      2244003.81      7203338.87
#Sta/Elev= 30
    4537  884.82  4560.4  882.22  4595.3  876.35  4731.6  864.25  4801.4  858.14
  4896.5  858.35  4954.9  860.03  4973.3  856.45  4987.4  851.91  4991.6  849.92
  4993.6  849.42  5009.4  849.92  5016.5  854.58  5037.4  856.56  5045.4  859.41
  5059.7  860.01  5179.9   858.9  5258.4  856.71  5315.5  856.94  5322.4  856.11
  5343.2  857.36  5400.9  856.76  5593.1  858.35  5635.2  857.54  5820.5  858.91
  5927.8  860.81  6033.4  860.38  6097.5  862.45  6155.2  869.57  6237.7  874.71
#Mann= 5 ,-1 , 0
    4537     .05       0  4731.6     .12       0  4987.4     .05       0
  4991.6     .04       0  5009.4     .05       0
Bank Sta=4991.6,5009.4
XS Rating Curve= 0 ,0
Exp/Cntr=0.3,0.1

Type RM Length L Ch R = 1 ,5127    ,499,499,499
BEGIN DESCRIPTION:
Panther Creek 6.0
END DESCRIPTION:
XS GIS Cut Line= 3
      2245307.25      7204705.66      2245134.99      7203974.33
      2244122.69      7203321.86
#Sta/Elev= 30
  4244.1  885.37  4280.7  883.66  4321.8  878.89    4404  873.32  4473.6  866.66
  4605.8  857.76  4648.1  856.28  4653.3   857.1  4660.9  855.67  4690.5  857.27
  4712.2  856.18    4738  858.35  4917.7  859.46    4928  858.81  4970.4  847.99
  4972.4  847.49  4988.2  847.99  4995.1  852.66  5002.6   854.9  5062.1  857.72
  5176.9  858.19  5219.2  857.01  5270.7  858.77  5364.4  856.94    5437  858.32
  5951.2  860.26  6029.8     864    6045  863.67  6050.9  864.99  6199.8  872.68
#Mann= 3 ,-1 , 0
  4244.1     .05       0  4970.4     .04       0  4988.2     .05       0
Bank Sta=4970.4,4988.2
XS Rating Curve= 0 ,0
Exp/Cntr=0.3,0.1

Type RM Length L Ch R = 1 ,4628    ,633,633,633
BEGIN DESCRIPTION:
Panther Creek 5.0
END DESCRIPTION:
XS GIS Cut Line= 3
      2245543.08      7204677.85      2245536.56      7203753.13
      2245550.17      7201843.33
#Sta/Elev= 30
    4084  878.96  4151.9  875.79  4171.9  871.65  4221.9  867.51  4431.9  854.69
  4481.9  857.35  4871.9  858.73  4901.9  854.95  4931.9  854.04  4971.9  849.38
    4973  847.38    4975  846.88  4990.8  847.38  4991.9   849.9  5001.9  853.86
  5041.9  860.02  5071.9  856.36  5121.9  860.45  5161.9  855.62  5351.9   855.9
  5381.9  857.74  5391.9  854.48  5441.9  856.49  6141.9  856.56  6261.9  861.13
  6441.9  861.82  6481.9  866.21  6701.9  873.09  6891.9  885.32  6918.6  888.89
#Mann= 3 ,-1 , 0
    4084     .05       0    4973    .033       0  4990.8     .05       0
Bank Sta=4973,4990.8
XS Rating Curve= 0 ,0
Exp/Cntr=0.3,0.1

Type RM Length L Ch R = 1 ,3995    ,489,489,489
BEGIN DESCRIPTION:
Panther Creek 4.0
END DESCRIPTION:
XS GIS Cut Line= 4
       2245667.4      7204741.25      2246132.99      7204003.44
      2246166.17      7203525.81      2246258.39      7201594.62
#Sta/Elev= 30
  3833.2  874.46  3952.5  865.27  4023.9  857.43  4104.3  853.24    4162  855.95
  4544.5  856.14  4638.8  853.97  4799.3  855.54  4939.6  852.53  4969.7  847.48
  4970.8     846  4972.8   845.5  4988.6     846  4989.8  849.16  4999.8  852.08
  5029.9  852.91  5059.9  856.56    5090  849.77  5120.1  850.18  5170.2  855.01
  5690.8   854.5  5750.9  851.96  5810.9  853.75  6191.8  852.86  6341.5  855.55
  6411.6  860.29  6451.7  865.82    6782  897.85  7021.6   906.6  7117.8  915.27
#Mann= 3 ,-1 , 0
  3833.2     .05       0  4970.8     .04       0  4988.6     .05       0
Bank Sta=4970.8,4988.6
XS Rating Curve= 0 ,0
Exp/Cntr=0.3,0.1

Type RM Length L Ch R = 1 ,3506    ,533,533,533
BEGIN DESCRIPTION:
Panther Creek 3.0
END DESCRIPTION:
XS GIS Cut Line= 3
      2246017.51      7204886.26      2246620.32      7204063.07
      2246674.59      7201154.78
#Sta/Elev= 30
  3676.5  860.54  3768.5  852.79  4125.9   856.2  4318.2  852.42  4909.9  853.33
  4949.9  852.16    4981  841.46    4983  840.96  4998.8  841.46  4999.9  847.31
  5009.9  850.37  5079.9  856.52    5240  848.72    5340  854.17  5780.1  851.28
  6050.1  853.68  6070.1  851.22  6100.1  853.56  6220.1  850.87  6400.2   852.1
  6660.9  864.18  6760.2  867.95  6950.3  883.68  7000.3  881.56  7050.3  886.94
  7190.3  890.07  7289.8  897.25  7390.3  902.78  7485.3  912.47  7605.6  928.54
#Mann= 6 ,-1 , 0
  3676.5     .05       0    4981     .04       0  4998.8     .05       0
  6660.9     .12       0  7289.8     .05       0  7485.3     .12       0
Bank Sta=4981,4998.8
XS Rating Curve= 0 ,0
Exp/Cntr=0.3,0.1