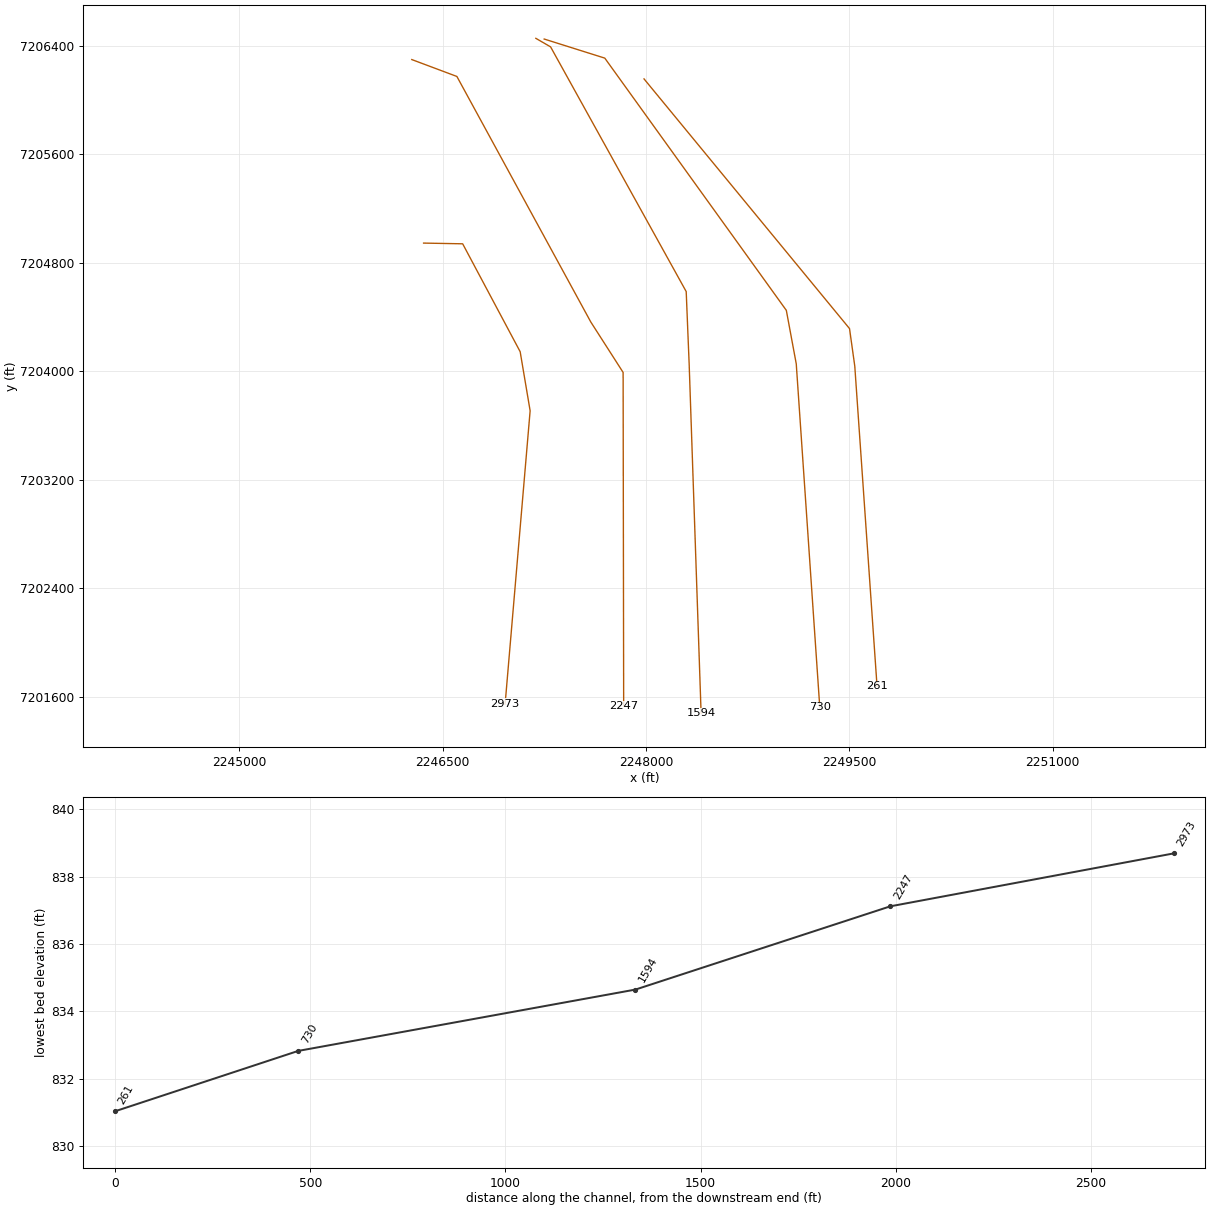
HEC-RAS study Panther Creek.prj: Panther Creek Base Level Engineering

--- Panther Creek.g01 (geometry) --- (continued)

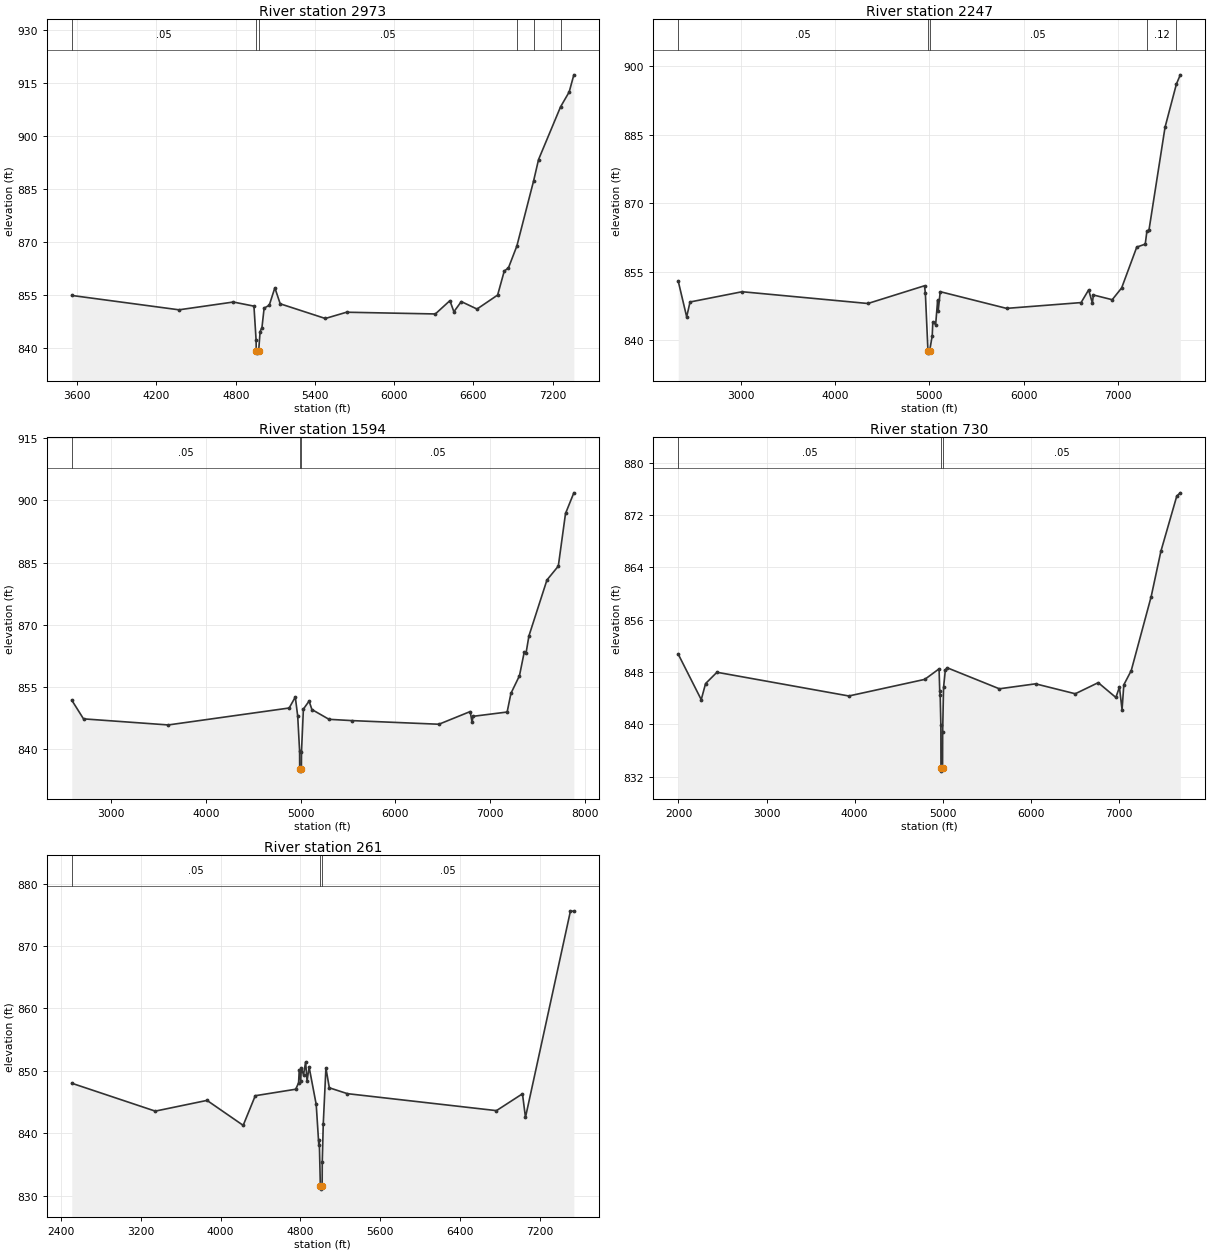
Type RM Length L Ch R = 1 ,2973    ,726,726,726
BEGIN DESCRIPTION:
Panther Creek 2.2
END DESCRIPTION:
XS GIS Cut Line= 5
      2246360.47      7204944.16      2246648.62      7204938.91
      2247072.61      7204143.19      2247146.09      7203707.47
      2246961.62      7201544.93
#Sta/Elev= 30
  3558.5  854.99  4370.4  850.93    4782  853.13  4938.1  851.97  4954.4  842.34
  4955.6  839.19  4957.6  838.69  4973.4  839.19  4984.8  844.79  4998.6  845.89
  5015.2  851.41    5054  852.22  5096.4  857.16  5136.9  852.63  5478.7  848.48
  5639.3  850.25  6311.7  849.76  6422.1  853.52  6452.2  850.38  6508.2  853.26
  6627.3  851.15  6783.4   855.1  6833.6  861.88  6865.4  862.79  6929.1  868.97
  7055.7  887.34  7093.4   893.4  7259.8  908.28  7325.4  912.51  7360.6  917.34
#Mann= 6 ,-1 , 0
  3558.5     .05       0  4955.6    .033       0  4973.4     .05       0
  6929.1     .12       0  7055.7     .05       0  7259.8     .12       0
Bank Sta=4955.6,4973.4
XS Rating Curve= 0 ,0
Exp/Cntr=0.3,0.1

Type RM Length L Ch R = 1 ,2247    ,653,653,653
BEGIN DESCRIPTION:
Panther Creek 2.1
END DESCRIPTION:
XS GIS Cut Line= 5
      2246273.38      7206297.58      2246605.92      7206172.99
      2247593.39      7204362.44      2247831.84      7203990.49
      2247835.87      7201528.25
#Sta/Elev= 30
  2337.9   852.9  2427.4  845.07    2463  848.33  3015.4  850.58  4348.1     848
  4948.3  851.89  4957.3  850.21  4984.7  837.62  4986.7  837.12  5002.6  837.62
    5030  840.95  5035.9  843.88  5066.3  843.39  5087.4  848.72  5093.4  846.42
  5114.6  850.59  5817.7  846.93  6607.7   848.2  6687.7  850.98  6727.7  848.09
  6737.7  849.87  6937.7  848.83  7037.7  851.42  7197.7  860.36  7287.7  861.02
  7304.9  863.79  7327.7  864.15  7497.7  886.65  7618.3  896.13  7659.4  898.13
#Mann= 5 ,-1 , 0
  2337.9     .05       0  4984.7    .033       0  5002.6     .05       0
  7304.9     .12       0  7618.3     .05       0
Bank Sta=4984.7,5002.6
XS Rating Curve= 0 ,0
Exp/Cntr=0.3,0.1

Type RM Length L Ch R = 1 ,1594    ,864,864,864
BEGIN DESCRIPTION:
Panther Creek 2.0
END DESCRIPTION:
XS GIS Cut Line= 5
      2247188.22      7206454.13       2247296.9      7206391.24
      2248297.05      7204586.75      2248319.23       7204041.5
      2248406.97      7201476.09
#Sta/Elev= 30
  2584.4  851.78  2708.3  847.27  3603.2   845.8  4879.9  849.89  4944.5  852.54
    4970  847.95    4990  839.52  4991.1  835.15  4993.1  834.65    5009  835.15
    5010  839.31    5030  849.63  5090.1  851.56  5120.1  849.52  5300.3  847.16
  5540.4  846.85    6461  845.97  6791.1  849.03  6811.2  846.44  6821.2  847.88
  7181.4  848.92  7221.4  853.42  7311.5  857.68  7361.5  863.34  7381.5  863.22
  7411.5   867.3  7601.6  880.79  7721.7  884.15  7797.7  896.85  7885.7  901.84
#Mann= 3 ,-1 , 0
  2584.4     .05       0  4991.1     .04       0    5009     .05       0
Bank Sta=4991.1,5009
XS Rating Curve= 0 ,0
Exp/Cntr=0.3,0.1

Type RM Length L Ch R = 1 ,730     ,469,469,469
BEGIN DESCRIPTION:
Panther Creek 1.0
END DESCRIPTION:
XS GIS Cut Line= 5
      2247249.84      7206448.88       2247696.7      7206308.18
      2249035.43       7204448.1      2249108.57      7204053.94
      2249282.16       7201520.1
#Sta/Elev= 30
  1997.2  850.73  2258.4  843.77  2307.7  846.23  2436.6  847.96  3934.5  844.33
  4796.2  846.87  4958.9  848.48  4966.4  845.07  4971.5  844.46  4979.3  839.84
  4980.5  833.33  4982.5  832.83  4998.4  833.33  4999.6  838.85  5009.8  845.63
  5030.1  848.31  5050.5  848.65  5643.4  845.43  6054.4  846.19  6505.4  844.67
    6766  846.37  6966.5   844.1  7006.6  845.68  7036.7  842.25  7056.7  846.04
  7140.9  848.22  7367.4  859.55  7477.7  866.48  7658.1  874.93  7698.1  875.42
#Mann= 3 ,-1 , 0
  1997.2     .05       0  4980.5     .04       0  4998.4     .05       0
Bank Sta=4980.5,4998.4
XS Rating Curve= 0 ,0
Exp/Cntr=0.3,0.1

Type RM Length L Ch R = 1 ,261     ,0,0,0
BEGIN DESCRIPTION:
Panther Creek 0.9
END DESCRIPTION:
XS GIS Cut Line= 4
      2247985.93      7206155.04      2249501.46      7204313.66
      2249540.18      7204036.94      2249704.39       7201676.5
#Sta/Elev= 30
  2509.6  848.01    3346  843.54  3864.7  845.26    4227  841.26  4348.2  846.01
  4753.5  847.05  4782.2  848.08  4788.7  850.17    4803  848.38  4809.5  850.42
  4831.7  849.35  4852.5  851.42  4866.9  848.38  4887.7  850.59  4958.7  844.61
  4984.5  838.19  4989.5  838.86  5000.3  831.54  5002.3  831.04  5018.2  831.54
  5019.3  835.38  5029.4  841.51  5055.9  850.46    5090  847.28    5271  846.34
  6764.6  843.62  7025.3  846.32  7055.3  842.54  7506.4  875.64    7540  875.55
#Mann= 3 ,-1 , 0
  2509.6     .05       0  5000.3     .04       0  5018.2     .05       0
Bank Sta=5000.3,5018.2
XS Rating Curve= 0 ,0
Exp/Cntr=0.3,0.1

Chan Stop Cuts=-1
Use User Specified Reach Order=0
Composite Channel Slope=5