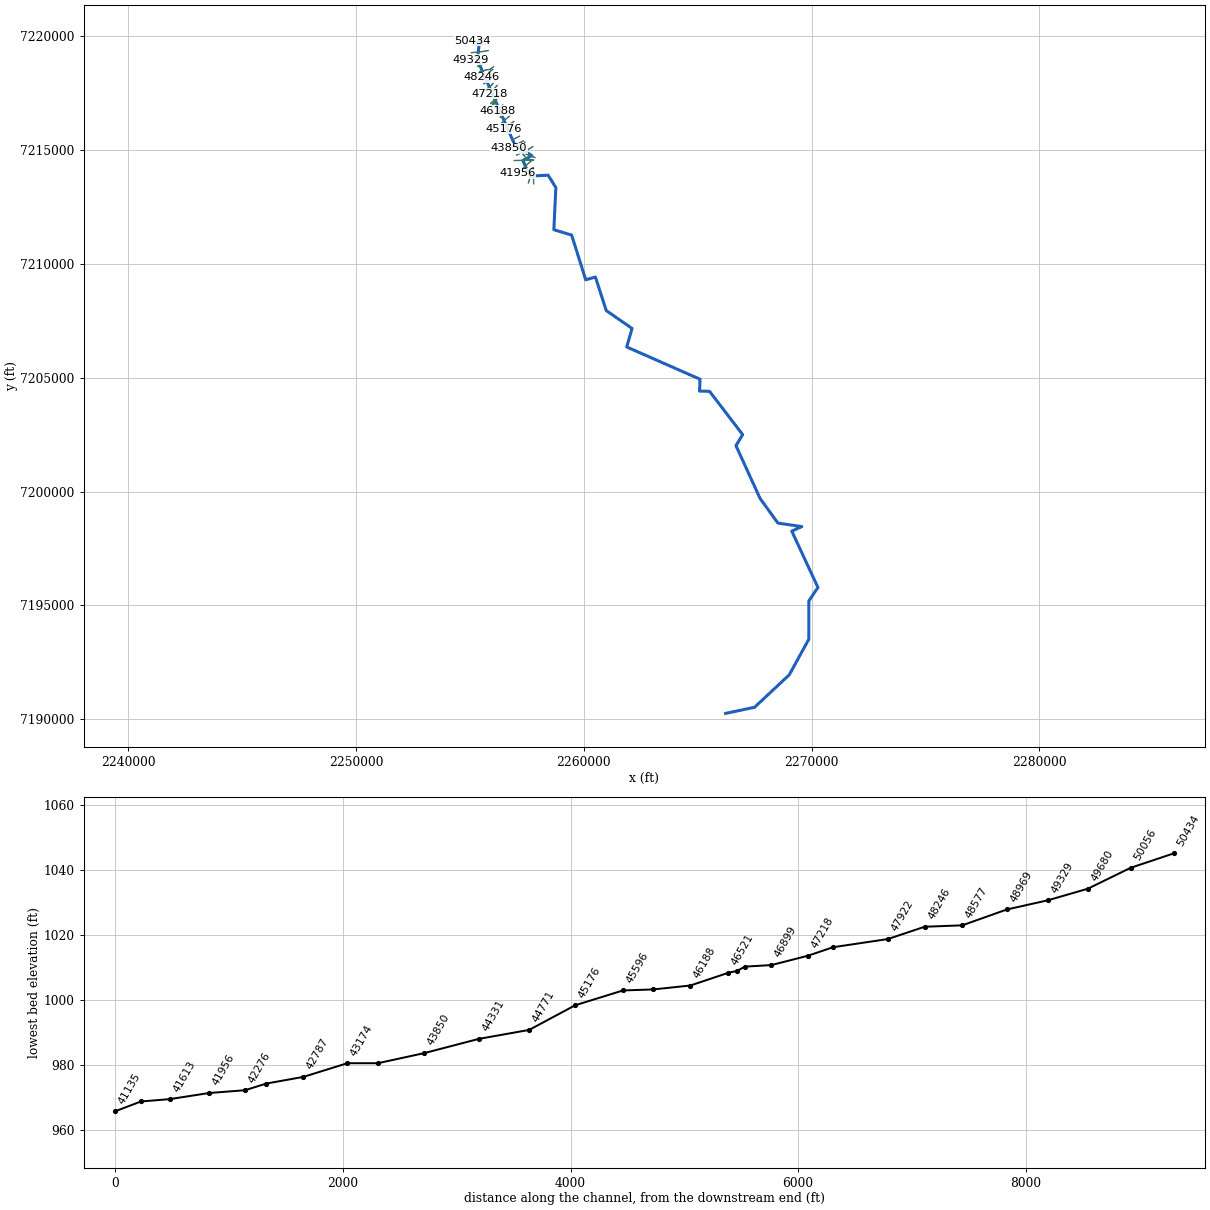
--- Rush Creek.prj (project) ---

Proj Title=Rush Creek Base Level Engineering
Current Plan=p01
Default Exp/Contr=0.3,0.1
English Units
Geom File=g01
Flow File=f01
Plan File=p01
Y Axis Title=Elevation
X Axis Title(PF)=Main Channel Distance
X Axis Title(XS)=Station
BEGIN DESCRIPTION:
Rush Creek
END DESCRIPTION:
DSS Export Rating Curves= 0
DSS Export Rating Curve Sorted= 0
DSS Export Volume Flow Curves= 0
DXF OffsetX= 0
DXF OffsetY= 0
DXF ScaleX= 1
DXF ScaleY= 10

--- Rush Creek.p01 (plan) ---

Plan Title=Multiple Run
Short Identifier=Multiple
Geom File=g01
Flow File=f01
Subcritical Flow
K Sum by GR= 0
Std Step Tol= 0.01
Critical Tol= 0.01
Num of Std Step Trials= 20
Max Error Tol= 0.3
Flow Tol Ratio= 0.001
Split Flow NTrial= 30
Split Flow Tol= 0.02
Split Flow Ratio= 0.02
Log Output Level= 0
Friction Slope Method= 1
Unsteady Friction Slope Method= 2
Unsteady Bridges Friction Slope Method= 1
Parabolic Critical Depth
Global Vel Dist=  1 , 1 , 1
Global Log Level= 0
CheckData=True
Encroach Param= -1, 0, 0, 0
BEGIN DESCRIPTION:
Multiple Run
END DESCRIPTION:

--- Rush Creek.f01 (steady flow) ---

Flow Title=Multiple
Program Version=4.10
Number of Profiles= 7
Profile Names=10-year,25-year,50-year,1pct_min,100-year,1pct_plu,500-year
River Rch & RM=Rush Creek,Reach-1         ,50434
     667     927    1145     702    1400    2794    2101
River Rch & RM=Rush Creek,Reach-1         ,44331
     765    1069    1325     815    1625    3243    2454
River Rch & RM=Rush Creek,Reach-1         ,38583
    1314    1884    2374    1481    2955    5897    4599
River Rch & RM=Rush Creek,Reach-1         ,30517
    1761    2554    3242    2036    4062    8104    6401
River Rch & RM=Rush Creek,Reach-1         ,24398
    2061    3008    3836    2419    4826    9629    7668
River Rch & RM=Rush Creek,Reach-1         ,23513
    2228    3269    4184    2648    5283   10541    8455
River Rch & RM=Rush Creek,Reach-1         ,21704
    2294    3369    4313    2730    5446   10867    8720
River Rch & RM=Rush Creek,Reach-1         ,19752
    2538    3724    4768    3016    6017   12006    9620
River Rch & RM=Rush Creek,Reach-1         ,13591
    2638    3867    4946    3125    6235   12441    9945
River Rch & RM=Rush Creek,Reach-1         ,3791
    2728    4003    5124    3240    6465   12899   10326
Boundary for River Rch & Prof#=Rush Creek,Reach-1         , 1
Up Type= 0
Dn Type= 3
Dn Slope=0.003
Boundary for River Rch & Prof#=Rush Creek,Reach-1         , 2
Up Type= 0
Dn Type= 3
Dn Slope=0.003
Boundary for River Rch & Prof#=Rush Creek,Reach-1         , 3
Up Type= 0
Dn Type= 3
Dn Slope=0.003
Boundary for River Rch & Prof#=Rush Creek,Reach-1         , 4
Up Type= 0
Dn Type= 3
Dn Slope=0.003
Boundary for River Rch & Prof#=Rush Creek,Reach-1         , 5
Up Type= 0
Dn Type= 3
Dn Slope=0.003
Boundary for River Rch & Prof#=Rush Creek,Reach-1         , 6
Up Type= 0
Dn Type= 3
Dn Slope=0.003
Boundary for River Rch & Prof#=Rush Creek,Reach-1         , 7
Up Type= 0
Dn Type= 3
Dn Slope=0.003
DSS Import GetInterval= 0
DSS Import GetPeak= 0
DSS Import FillOption= 0

--- Rush Creek.g01 (geometry) ---

Geom Title=Existing Conditions
Program Version=4.10

River Reach=Rush Creek      ,Reach-1
Reach XY= 30
        2255429.        7219860.      2255336.79      7218956.57
      2256983.97      7215207.41        2257726.      7214758.53
      2257329.03      7214546.08      2257634.48      7213856.97
      2258436.04      7213901.04      2258775.32      7213358.42
      2258688.39      7211503.39      2259468.52       7211269.8
      2260086.69      7209303.52       2260512.8      7209426.71
      2260986.74      7207953.55      2262121.33      7207166.52
      2261886.45      7206353.97      2265102.84      7204937.01
      2265084.41      7204415.17      2265523.43      7204404.43
      2266975.79      7202502.01       2266680.5      7202021.86
      2267736.81      7199703.81      2268522.92      7198618.13
      2269571.24        7198463.      2269130.76      7198266.17
      2270278.93      7195789.97      2269880.36      7195200.35
      2269875.46      7193511.47      2269018.24      7191950.32
      2267495.68      7190526.64        2266229.        7190260.

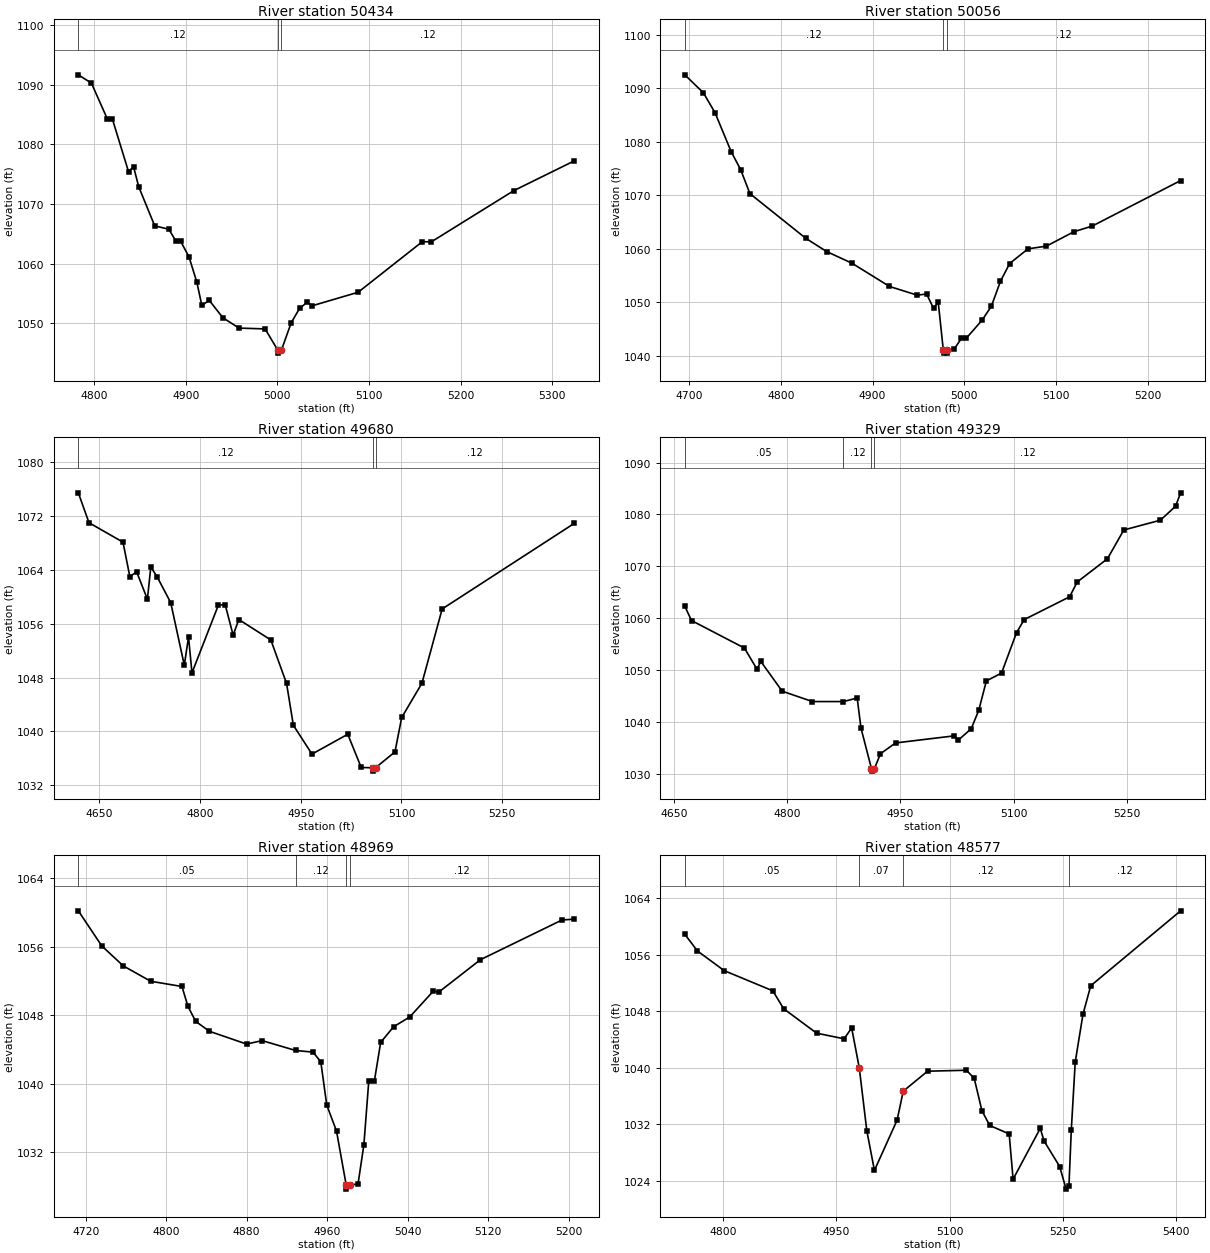
Type RM Length L Ch R = 1 ,50434   ,378,378,378
BEGIN DESCRIPTION:
Rush Creek 110.0
END DESCRIPTION:
XS GIS Cut Line= 3
      2255628.99        7219910.       2255370.9      7219792.18
      2255113.15      7219796.34
#Sta/Elev= 30
  4782.6 1091.64  4796.9 1090.25  4814.4 1084.19  4819.9 1084.17  4837.4 1075.41
  4842.9 1076.24  4848.5 1072.89    4866 1066.32  4881.5 1065.74    4889 1063.79
  4894.5 1063.69  4903.5 1061.09    4912 1056.88  4917.5 1052.96  4925.5 1053.83
  4940.5  1050.9  4958.1 1049.17  4986.6 1049.03  5000.4 1045.47  5000.7 1044.97
  5004.4 1045.47  5015.1 1050.07  5024.4 1052.52  5032.7  1053.5  5038.2 1052.92
  5088.2 1055.18  5158.2 1063.65  5168.2 1063.64  5258.2 1072.22  5324.1  1077.2
#Mann= 3 ,-1 , 0
  4782.6     .12       0  5000.4     .07       0  5004.4     .12       0
Bank Sta=5000.4,5004.4
XS Rating Curve= 0 ,0
Exp/Cntr=0.3,0.1

Type RM Length L Ch R = 1 ,50056   ,376,376,376
BEGIN DESCRIPTION:
Rush Creek 109.0
END DESCRIPTION:
XS GIS Cut Line= 3
      2255679.04      7219660.01        2255379.        7219610.
      2255142.58      7219609.39
#Sta/Elev= 30
  4695.3 1092.52  4715.6 1089.16  4728.3 1085.43    4746 1078.11  4756.2 1074.81
  4766.3 1070.33  4827.1    1062  4849.9 1059.52  4877.8 1057.31  4918.4    1053
  4948.8 1051.36  4958.9 1051.59  4966.5 1048.91  4971.6 1050.08  4977.2 1041.04
  4977.5 1040.54    4981 1040.54  4981.2 1041.04  4989.3 1041.38  4996.9 1043.28
    5002 1043.28  5019.5 1046.71  5029.5 1049.28  5039.5 1053.97  5049.5 1057.28
  5069.5 1060.02  5089.5 1060.52  5119.5 1063.21  5139.5 1064.27  5235.9 1072.77
#Mann= 3 ,-1 , 0
  4695.3     .12       0  4977.2     .07       0  4981.2     .12       0
Bank Sta=4977.2,4981.2
XS Rating Curve= 0 ,0
Exp/Cntr=0.3,0.1

Type RM Length L Ch R = 1 ,49680   ,351,351,351
BEGIN DESCRIPTION:
Rush Creek 108.0
END DESCRIPTION:
XS GIS Cut Line= 3
      2255804.55      7219371.81        2255429.        7219310.
       2255073.3      7219281.99
#Sta/Elev= 30
  4619.4 1075.47  4635.2 1071.03  4685.8 1068.14    4696 1063.02  4706.1 1063.73
  4722.1 1059.66  4727.2 1064.44  4736.5    1063  4756.8 1059.15    4777 1049.85
  4783.3 1054.05  4788.4 1048.71  4827.7 1058.79  4837.8 1058.85  4849.6 1054.32
  4858.1 1056.64  4905.7  1053.6  4929.1 1047.14  4939.2 1040.92  4966.9 1036.64
  5020.1 1039.59  5040.1 1034.65  5057.4 1034.61  5057.7 1034.11  5061.4 1034.61
  5090.3 1036.97  5100.3 1042.08  5130.4 1047.17  5160.5 1058.21  5356.8 1070.92
#Mann= 3 ,-1 , 0
  4619.4     .12       0  5057.4     .07       0  5061.4     .12       0
Bank Sta=5057.4,5061.4
XS Rating Curve= 0 ,0
Exp/Cntr=0.3,0.1

Type RM Length L Ch R = 1 ,49329   ,360,360,360
BEGIN DESCRIPTION:
Rush Creek 107.0
END DESCRIPTION:
XS GIS Cut Line= 3
      2255707.87      7219032.21      2255379.02      7219007.84
      2255052.35      7218977.77
#Sta/Elev= 30
  4663.9 1062.32  4672.8 1059.56    4743 1054.26  4759.7 1050.18  4764.7 1051.69
  4793.1 1045.95  4833.2 1043.95  4874.3 1043.95  4892.6 1044.63  4897.6 1038.87
  4911.5 1031.05  4911.7 1030.55  4915.5 1031.05  4923.5  1033.9  4943.5 1035.98
  5021.7 1037.35  5026.7 1036.52  5043.9 1038.72  5053.9 1042.28    5064 1047.93
  5084.1 1049.44  5104.1 1057.25  5114.2 1059.74  5174.4 1064.13  5184.5 1066.98
  5224.6 1071.46  5246.3    1077  5294.9 1078.89    5315 1081.58  5321.7 1084.16
#Mann= 4 ,-1 , 0
  4663.9     .05       0  4874.3     .12       0  4911.5     .07       0
  4915.5     .12       0
Bank Sta=4911.5,4915.5
XS Rating Curve= 0 ,0
Exp/Cntr=0.3,0.1

Type RM Length L Ch R = 1 ,48969   ,392,392,392
BEGIN DESCRIPTION:
Rush Creek 106.0
END DESCRIPTION:
XS GIS Cut Line= 3
      2255779.02      7218910.01        2255529.        7218760.
      2255344.62       7218679.4
#Sta/Elev= 30
  4712.7 1060.17    4736 1056.08  4757.4 1053.75  4784.6 1051.96  4815.7 1051.35
  4821.6 1049.05  4829.3 1047.29  4842.9 1046.13  4879.9 1044.64  4895.4 1045.04
  4928.7 1043.89    4946  1043.7  4953.7 1042.56  4959.6 1037.53  4969.3  1034.5
  4978.9 1028.23  4979.2 1027.73  4982.9 1028.23  4990.7 1028.33  4996.5 1032.89
  5001.4 1040.38    5007 1040.38  5013.2 1044.84  5026.1 1046.66  5042.1  1047.8
  5065.5 1050.81  5070.9 1050.69  5112.3 1054.47  5193.4  1059.1  5205.5  1059.2
#Mann= 4 ,-1 , 0
  4712.7     .05       0  4928.7     .12       0  4978.9     .07       0
  4982.9     .12       0
Bank Sta=4978.9,4982.9
XS Rating Curve= 0 ,0
Exp/Cntr=0.3,0.1

Type RM Length L Ch R = 1 ,48577   ,331,331,331
BEGIN DESCRIPTION:
Rush Creek 105.0
END DESCRIPTION:
XS GIS Cut Line= 4
      2256040.41      7218662.88      2255884.57      7218544.62
      2255764.95      7218532.72      2255433.41       7218449.8
#Sta/Elev= 30
  4748.9 1058.91  4765.7 1056.55  4801.1 1053.77  4865.6 1050.91  4880.1 1048.37
  4923.7 1044.92  4960.2 1044.12  4970.2 1045.66  4980.3 1040.01  4990.3 1031.11
  5000.4  1025.5  5030.5 1032.62  5038.6 1036.71  5070.9 1039.54  5122.4 1039.67
  5132.7 1038.54    5143 1033.94  5153.3 1031.86  5179.1 1030.66  5184.3 1024.26
  5220.3 1031.44  5225.5 1029.64  5246.1 1026.05  5254.6 1022.85  5258.4 1023.35
  5261.5  1031.2  5266.7 1040.82    5277  1047.6  5287.3 1051.63  5406.5 1062.23
#Mann= 4 ,-1 , 0
  4748.9     .05       0  4980.3     .07       0  5038.6     .12       0
  5258.4     .12       0
#XS Ineff= 2 , 0
       0                  5122.4       0 1039.67
Permanent Ineff=
       F       F
Bank Sta=4980.3,5038.6
XS Rating Curve= 0 ,0
Exp/Cntr=0.3,0.1

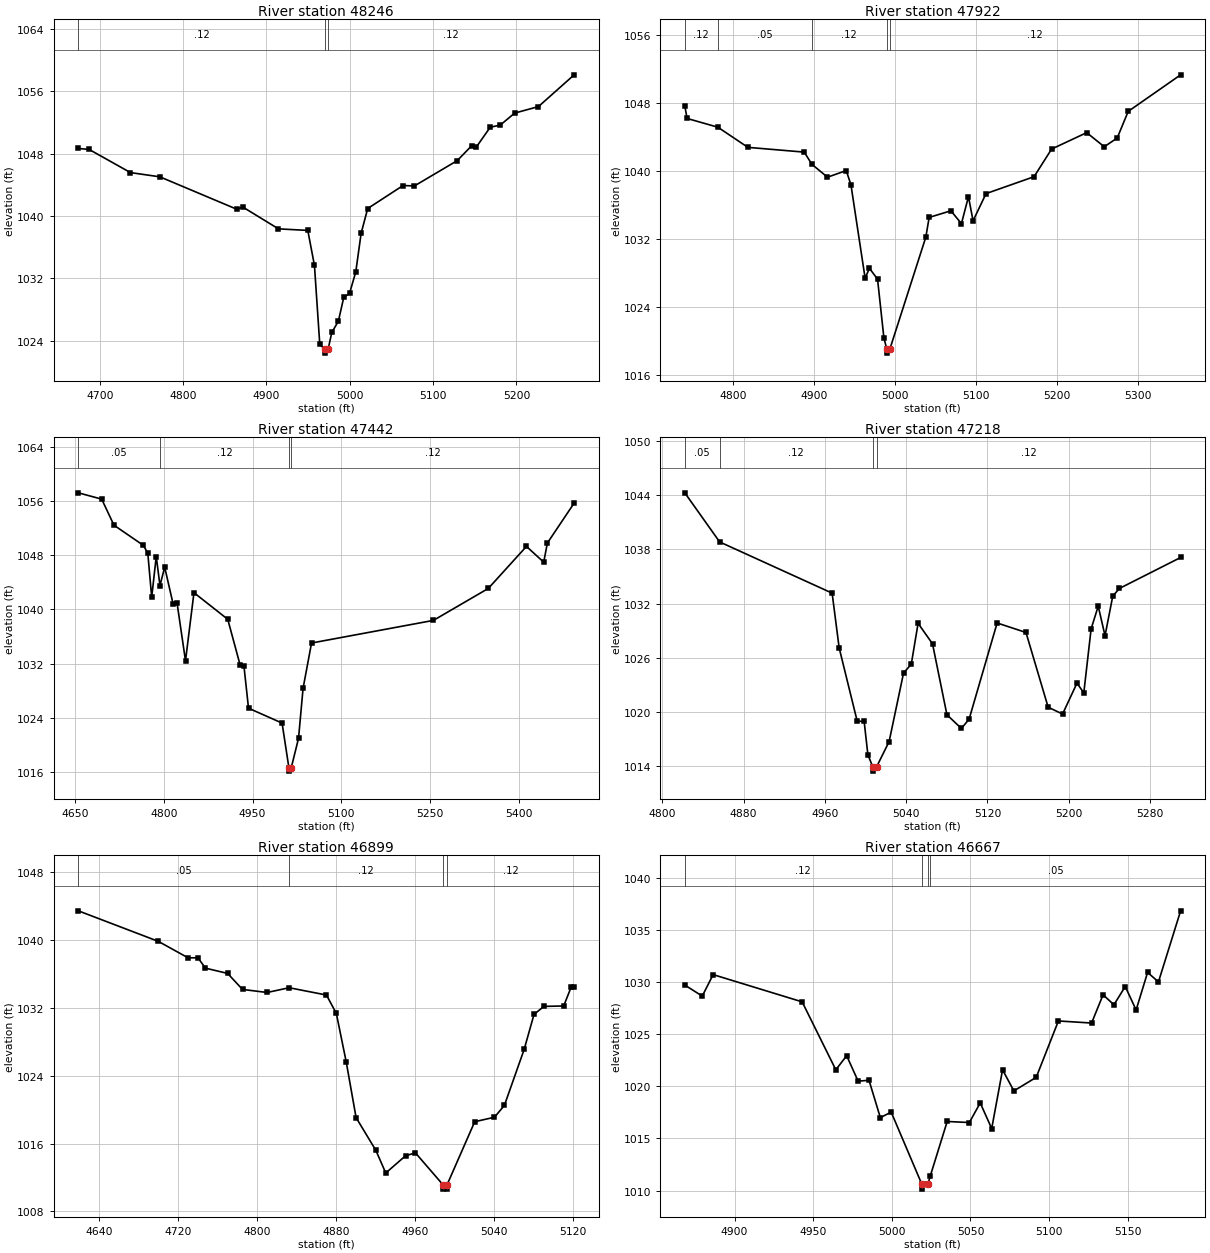
Type RM Length L Ch R = 1 ,48246   ,324,324,324
BEGIN DESCRIPTION:
Rush Creek 104.0
END DESCRIPTION:
XS GIS Cut Line= 3
      2256002.45      7218544.56      2255668.39      7218275.36
      2255517.57      7218205.84
#Sta/Elev= 30
  4674.2 1048.68  4687.2 1048.55  4736.8 1045.58    4772 1045.04  4864.8 1040.86
  4871.3 1041.18  4914.4 1038.36  4949.6 1038.16  4957.6 1033.66    4964 1023.52
    4970 1022.91  4970.2 1022.41    4974 1022.91  4978.4 1025.06  4986.3 1026.51
  4992.8 1029.58  4999.7 1030.07  5007.2 1032.84  5013.6 1037.78  5021.5 1040.97
  5063.9 1043.92  5077.6 1043.87    5129 1047.12  5146.5 1049.05    5152 1048.88
  5168.6 1051.41  5180.5 1051.67  5197.9 1053.22  5226.4 1054.05  5269.3 1058.13
#Mann= 3 ,-1 , 0
  4674.2     .12       0    4970     .07       0    4974     .12       0
Bank Sta=4970,4974
XS Rating Curve= 0 ,0
Exp/Cntr=0.3,0.1

Type RM Length L Ch R = 1 ,47922   ,480,480,480
BEGIN DESCRIPTION:
Rush Creek 103.0
END DESCRIPTION:
XS GIS Cut Line= 3
      2256005.15      7218347.61      2255880.68      7218068.39
      2255612.39      7217918.57
#Sta/Elev= 30
  4739.9 1047.69  4742.7 1046.22  4780.8 1045.19  4817.9 1042.82  4887.6 1042.26
    4897 1040.83  4916.3 1039.31  4939.5 1040.09  4945.3 1038.42  4962.8 1027.45
  4968.2 1028.59  4978.2 1027.32    4986 1020.45  4989.5 1019.12  4989.7 1018.62
  4993.5 1019.12  5037.9 1032.27    5042 1034.58  5068.9 1035.36  5081.9 1033.85
  5090.6 1037.02  5096.3 1034.18  5112.3 1037.38  5171.7 1039.37  5193.4 1042.62
  5236.8 1044.55  5258.5 1042.89  5274.5 1043.92  5288.1 1047.05  5352.9 1051.35
#Mann= 5 ,-1 , 0
  4739.9     .12       0  4780.8     .05       0    4897     .12       0
  4989.5     .07       0  4993.5     .12       0
Bank Sta=4989.5,4993.5
XS Rating Curve= 0 ,0
Exp/Cntr=0.3,0.1

Type RM Length L Ch R = 1 ,47442   ,224,224,224
BEGIN DESCRIPTION:
Rush Creek 102.0
END DESCRIPTION:
XS GIS Cut Line= 3
       2256210.7      7218163.71      2255927.96       7217827.8
      2255609.01      7217586.84
#Sta/Elev= 30
  4655.3  1057.2  4694.8 1056.27  4715.6 1052.42  4765.1 1049.46  4772.8 1048.32
  4779.4 1041.77  4787.1  1047.8  4793.4 1043.52  4801.4 1046.23  4815.7 1040.76
  4822.3 1040.95  4836.6  1032.4  4850.9 1042.46  4908.1 1038.53  4928.9 1031.81
  4935.4 1031.69  4943.2 1025.41    5000 1023.21  5011.5 1016.62  5011.7 1016.12
  5015.5 1016.62  5027.8 1020.96  5035.5 1028.34  5049.8 1035.03    5256 1038.37
  5348.9 1043.09  5413.4 1049.29  5442.6 1046.96  5448.8 1049.79  5494.1 1055.69
#Mann= 4 ,-1 , 0
  4655.3     .05       0  4793.4     .12       0  5011.5     .07       0
  5015.5     .12       0
Bank Sta=5011.5,5015.5
XS Rating Curve= 0 ,0
Exp/Cntr=0.3,0.1

Type RM Length L Ch R = 1 ,47218   ,319,319,319
BEGIN DESCRIPTION:
Rush Creek 101.0
END DESCRIPTION:
XS GIS Cut Line= 3
      2256198.43      7217835.32        2256079.        7217710.
      2255870.53        7217474.
#Sta/Elev= 30
  4822.2 1044.24  4856.5 1038.81  4967.2 1033.15  4974.1 1027.11  4991.9 1018.98
  4998.7 1018.98  5002.4 1015.28  5007.1 1013.97  5007.3 1013.47  5011.1 1013.97
  5023.3 1016.74  5037.5 1024.32  5045.1 1025.29  5051.8 1029.81    5066 1027.55
  5080.2  1019.7  5094.4 1018.19    5102 1019.21  5129.6 1029.85    5158  1028.8
  5179.8 1020.54    5194 1019.78  5208.2  1023.2  5214.9 1022.12  5222.1 1029.19
  5229.1 1031.71  5235.8 1028.44  5243.4 1032.82    5250 1033.67  5310.2 1037.09
#Mann= 4 ,-1 , 0
  4822.2     .05       0  4856.5     .12       0  5007.1     .07       0
  5011.1     .12       0
#XS Ineff= 2 , 0
       0                  5051.8       0 1029.81
Permanent Ineff=
       F       F
Bank Sta=5007.1,5011.1
XS Rating Curve= 0 ,0
Exp/Cntr=0.3,0.1

Type RM Length L Ch R = 1 ,46899   ,232,232,232
BEGIN DESCRIPTION:
Rush Creek 100.0
END DESCRIPTION:
XS GIS Cut Line= 3
      2256459.88       7217380.2      2256293.84      7217386.28
      2255958.42      7217389.99
#Sta/Elev= 30
  4619.2 1043.44  4700.1 1039.84  4730.2  1037.9  4740.2  1037.9  4747.8 1036.68
  4770.2 1036.06  4785.3 1034.17  4810.2 1033.81  4832.5 1034.37  4870.2 1033.51
  4880.2 1031.34  4890.2 1025.63  4900.2 1019.05  4920.2 1015.19  4930.2 1012.52
  4950.2 1014.55  4960.2  1014.9  4988.2 1011.12  4988.5 1010.62    4992 1010.62
  4992.2 1011.12  5020.2 1018.57  5040.2  1019.1  5050.2 1020.49  5070.2 1027.09
  5080.2 1031.23  5090.2 1032.17  5110.2 1032.22    5118 1034.51  5120.8 1034.51
#Mann= 4 ,-1 , 0
  4619.2     .05       0  4832.5     .12       0  4988.2     .07       0
  4992.2     .12       0
#XS Ineff= 2 , 0
       0  4960.2  1014.9               0
Permanent Ineff=
       F       F
Bank Sta=4988.2,4992.2
XS Rating Curve= 0 ,0
Exp/Cntr=0.3,0.1

Type RM Length L Ch R = 1 ,46667   ,71,71,71
BEGIN DESCRIPTION:
Rush Creek 99.2
END DESCRIPTION:
XS GIS Cut Line= 2
      2256152.03      7217272.65      2255923.99      7217055.04
#Sta/Elev= 30
  4868.4  1029.7  4879.5 1028.64  4886.4  1030.7    4943 1028.09  4964.4 1021.58
  4971.3 1022.93  4978.6 1020.49  4985.5 1020.58  4992.7    1017  4999.6 1017.53
    5019 1010.65  5019.3 1010.15    5023 1010.65  5024.5 1011.43  5035.2 1016.63
  5049.3 1016.53  5056.2 1018.41  5063.5 1015.95  5070.4 1021.58  5077.6 1019.56
  5091.8 1020.86  5105.9 1026.26    5127 1026.06  5134.3 1028.77  5141.2 1027.81
  5148.4 1029.56  5155.3 1027.31  5162.6 1030.91  5169.5    1030  5183.6 1036.81
#Mann= 4 ,-1 , 0
  4868.4     .12       0    5019     .07       0    5023     .12       0
  5024.5     .05       0
Bank Sta=5019,5023
XS Rating Curve= 0 ,0
Exp/Cntr=0.3,0.1

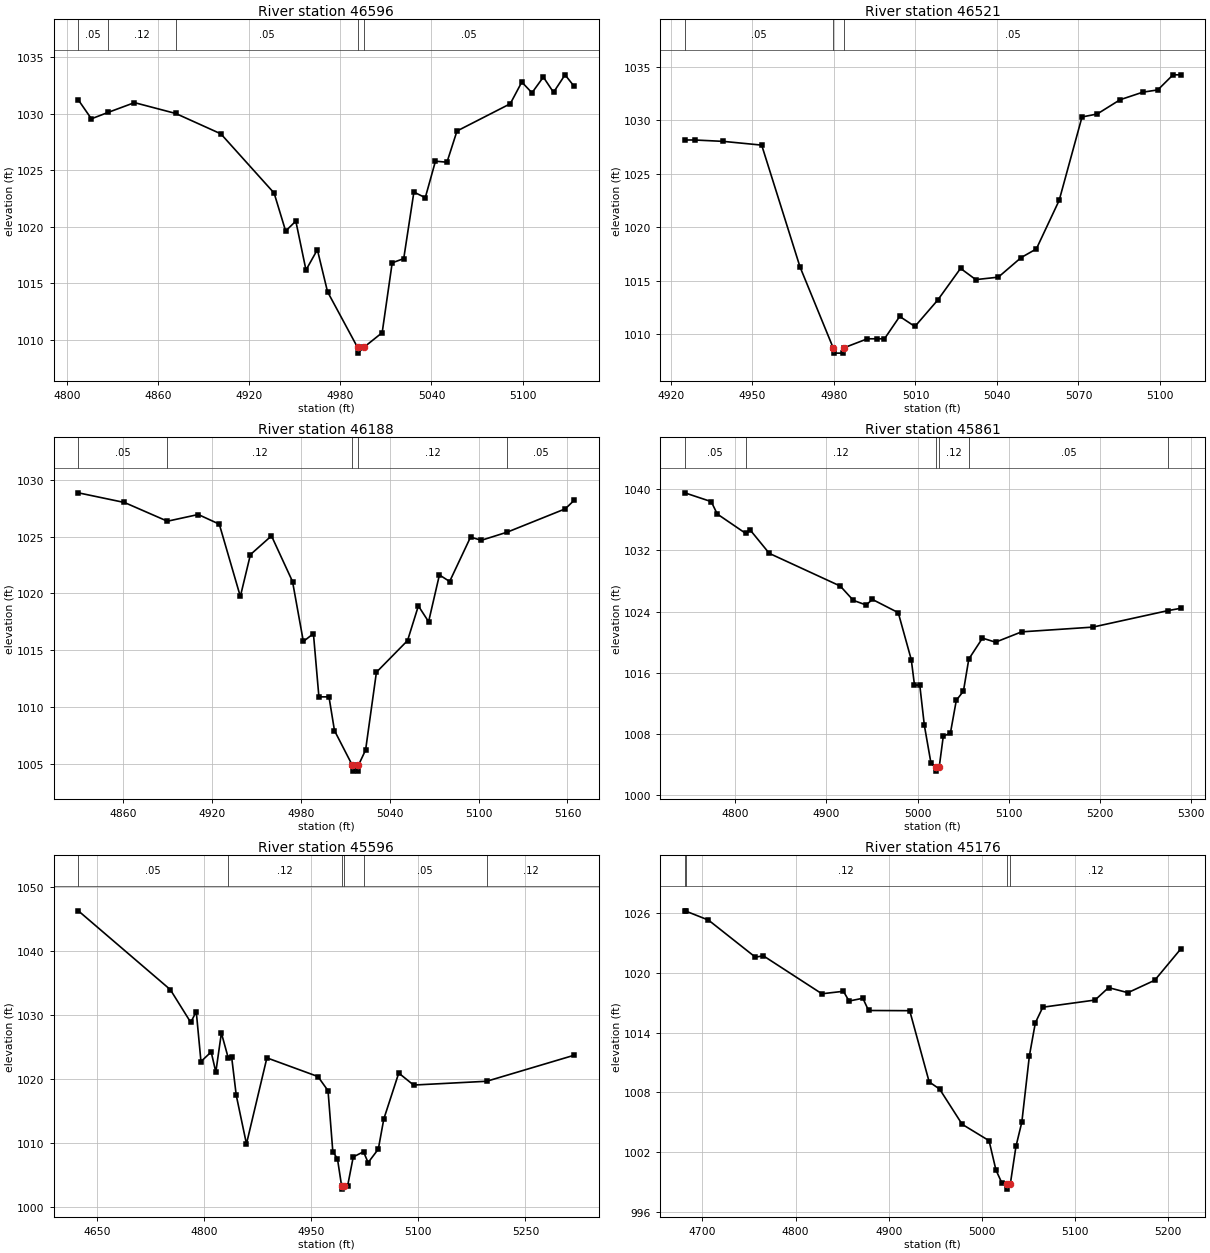
Type RM Length L Ch R = 1 ,46596   ,75,75,75
BEGIN DESCRIPTION:
Rush Creek 99.1
END DESCRIPTION:
XS GIS Cut Line= 2
      2256208.69      7217262.54      2255992.67      7217017.45
#Sta/Elev= 30
  4807.3 1031.22  4815.9 1029.55  4826.8 1030.11  4844.3 1030.98  4871.5 1030.02
  4901.2 1028.22  4936.3 1022.98  4943.9 1019.62  4950.6  1020.5  4957.3 1016.17
  4964.8 1017.97  4971.5 1014.25  4991.3 1009.32  4991.5 1008.82  4995.3 1009.32
  5007.5 1010.63  5014.1 1016.81  5021.7 1017.18  5028.4 1023.07  5035.9 1022.57
  5042.6  1025.8  5050.2 1025.71  5056.8 1028.47  5091.9 1030.88  5099.5  1032.8
  5106.2 1031.85  5113.7 1033.24  5120.4 1031.89    5128 1033.44    5134 1032.42
#Mann= 5 ,-1 , 0
  4807.3     .05       0  4826.8     .12       0  4871.5     .05       0
  4991.3    .033       0  4995.3     .05       0
Bank Sta=4991.3,4995.3
XS Rating Curve= 0 ,0
Exp/Cntr=0.3,0.1

Type RM Length L Ch R = 1 ,46521   ,333,333,333
BEGIN DESCRIPTION:
Rush Creek 99.0
END DESCRIPTION:
XS GIS Cut Line= 3
      2256179.01      7217110.01        2256129.        7217060.
      2256029.03      7217010.01
#Sta/Elev= 28
  4925.1 1028.17  4928.7 1028.17  4939.3 1028.04  4953.4 1027.69  4967.5 1016.31
  4979.7 1008.75  4979.9 1008.25  4983.4 1008.25  4983.7 1008.75  4992.3 1009.59
  4995.8 1009.59  4998.6 1009.59  5004.2 1011.68  5009.8 1010.74  5018.2 1013.21
  5026.6 1016.17  5032.2 1015.12  5040.5 1015.35  5048.9 1017.18  5054.5 1017.99
  5062.9 1022.53  5071.3 1030.32  5076.9  1030.6  5085.3 1031.93  5093.7 1032.64
  5099.2 1032.85  5104.8 1034.26  5107.6 1034.26
#Mann= 3 ,-1 , 0
  4925.1     .05       0  4979.7    .033       0  4983.7     .05       0
Bank Sta=4979.7,4983.7
XS Rating Curve= 0 ,0
Exp/Cntr=0.3,0.1

Type RM Length L Ch R = 1 ,46188   ,327,327,327
BEGIN DESCRIPTION:
Rush Creek 98.0
END DESCRIPTION:
XS GIS Cut Line= 3
      2256441.98      7216981.22        2256329.        7216860.
      2256213.18      7216737.21
#Sta/Elev= 30
    4830 1028.85  4861.1    1028  4890.1 1026.35  4910.9 1026.94  4925.1 1026.09
  4939.3 1019.72  4946.1 1023.41  4960.3 1025.06  4974.5 1021.04  4981.8 1015.76
  4988.6 1016.45  4992.3 1010.88  4999.1 1010.88  5002.8 1007.91  5014.9 1004.84
  5015.2 1004.34  5018.7 1004.34  5018.9 1004.84  5023.8  1006.2  5031.1 1013.05
  5052.1 1015.84  5059.4 1018.89  5066.3  1017.5  5073.6 1021.62  5080.5 1021.04
  5094.6 1024.95  5101.9 1024.67  5119.4 1025.39  5158.5 1027.44  5164.5 1028.19
#Mann= 5 ,-1 , 0
    4830     .05       0  4890.1     .12       0  5014.9     .07       0
  5018.9     .12       0  5119.4     .05       0
Bank Sta=5014.9,5018.9
XS Rating Curve= 0 ,0
Exp/Cntr=0.3,0.1

Type RM Length L Ch R = 1 ,45861   ,265,265,265
BEGIN DESCRIPTION:
Rush Creek 97.0
END DESCRIPTION:
XS GIS Cut Line= 3
      2256753.91      7216795.75      2256561.63      7216630.38
      2256338.58      7216444.45
#Sta/Elev= 30
  4744.6 1039.54  4773.6 1038.39  4780.2 1036.77  4811.2 1034.25  4816.4 1034.67
  4837.3 1031.62  4915.2 1027.34  4929.5 1025.47  4943.7 1024.86  4950.3  1025.6
  4978.8 1023.86  4993.1  1017.7  4996.6 1014.39  5002.4 1014.39  5007.4 1009.14
  5014.7 1004.17  5019.7 1003.63  5019.9 1003.13  5023.7 1003.63  5028.2  1007.7
    5036  1008.1  5042.5  1012.4  5050.3 1013.59  5056.2 1017.79  5071.2 1020.53
  5085.5    1020  5114.1 1021.35  5192.2 1021.97  5274.7 1024.13  5288.6 1024.43
#Mann= 6 ,-1 , 0
  4744.6     .05       0  4811.2     .12       0  5019.7     .07       0
  5023.7     .12       0  5056.2     .05       0  5274.7     .12       0
Bank Sta=5019.7,5023.7
XS Rating Curve= 0 ,0
Exp/Cntr=0.3,0.1

Type RM Length L Ch R = 1 ,45596   ,420,420,420
BEGIN DESCRIPTION:
Rush Creek 96.0
END DESCRIPTION:
XS GIS Cut Line= 3
      2256915.97      7216645.13      2256539.29      7216326.58
      2256395.79      7216186.01
#Sta/Elev= 30
  4624.1 1046.22  4752.9 1033.93  4781.5 1028.82  4789.2 1030.51  4795.8 1022.72
  4810.1 1024.21  4816.6 1021.07  4824.4 1027.17    4834 1023.27  4838.7 1023.46
  4845.2 1017.45  4859.5 1009.87  4888.1 1023.29  4959.5 1020.38  4973.7 1018.17
  4980.4 1008.67  4986.9 1007.55  4992.7 1003.32  4992.9 1002.82  4996.7 1003.32
  5001.2 1003.37    5009 1007.84  5023.4 1008.65  5029.8 1006.95  5044.1 1009.06
  5051.8 1013.76  5072.7 1020.92  5093.5 1019.05  5195.8 1019.64  5318.3  1023.7
#Mann= 6 ,-1 , 0
  4624.1     .05       0    4834     .12       0  4992.7     .07       0
  4996.7     .12       0  5023.4     .05       0  5195.8     .12       0
#XS Ineff= 2 , 0
       0  4888.1 1023.29               0
Permanent Ineff=
       F       F
Bank Sta=4992.7,4996.7
XS Rating Curve= 0 ,0
Exp/Cntr=0.3,0.1

Type RM Length L Ch R = 1 ,45176   ,405,405,405
BEGIN DESCRIPTION:
Rush Creek 95.0
END DESCRIPTION:
XS GIS Cut Line= 3
      2256928.55      7216257.06      2256709.01      7216099.24
      2256503.31      7215936.94
#Sta/Elev= 30
  4681.1 1026.25  4681.9 1026.23  4706.5 1025.32  4756.9 1021.59  4765.4 1021.73
  4828.3 1017.91  4851.4 1018.16  4857.5 1017.18  4872.3 1017.46  4878.4 1016.23
  4922.6 1016.21  4943.5 1009.05  4954.7 1008.33  4978.9 1004.79  5007.8 1003.14
  5015.2 1000.19  5021.6  998.88  5026.6  998.77  5026.8  998.27  5030.6  998.77
  5036.7 1002.57    5043 1005.01  5051.1 1011.67  5057.5 1014.99  5065.5 1016.56
  5121.6 1017.28  5136.1 1018.53  5156.9 1018.02  5185.7 1019.27  5213.5  1022.4
#Mann= 4 ,-1 , 0
  4681.1     .05       0  4681.9     .12       0  5026.6     .07       0
  5030.6     .12       0
Bank Sta=5026.6,5030.6
XS Rating Curve= 0 ,0
Exp/Cntr=0.3,0.1

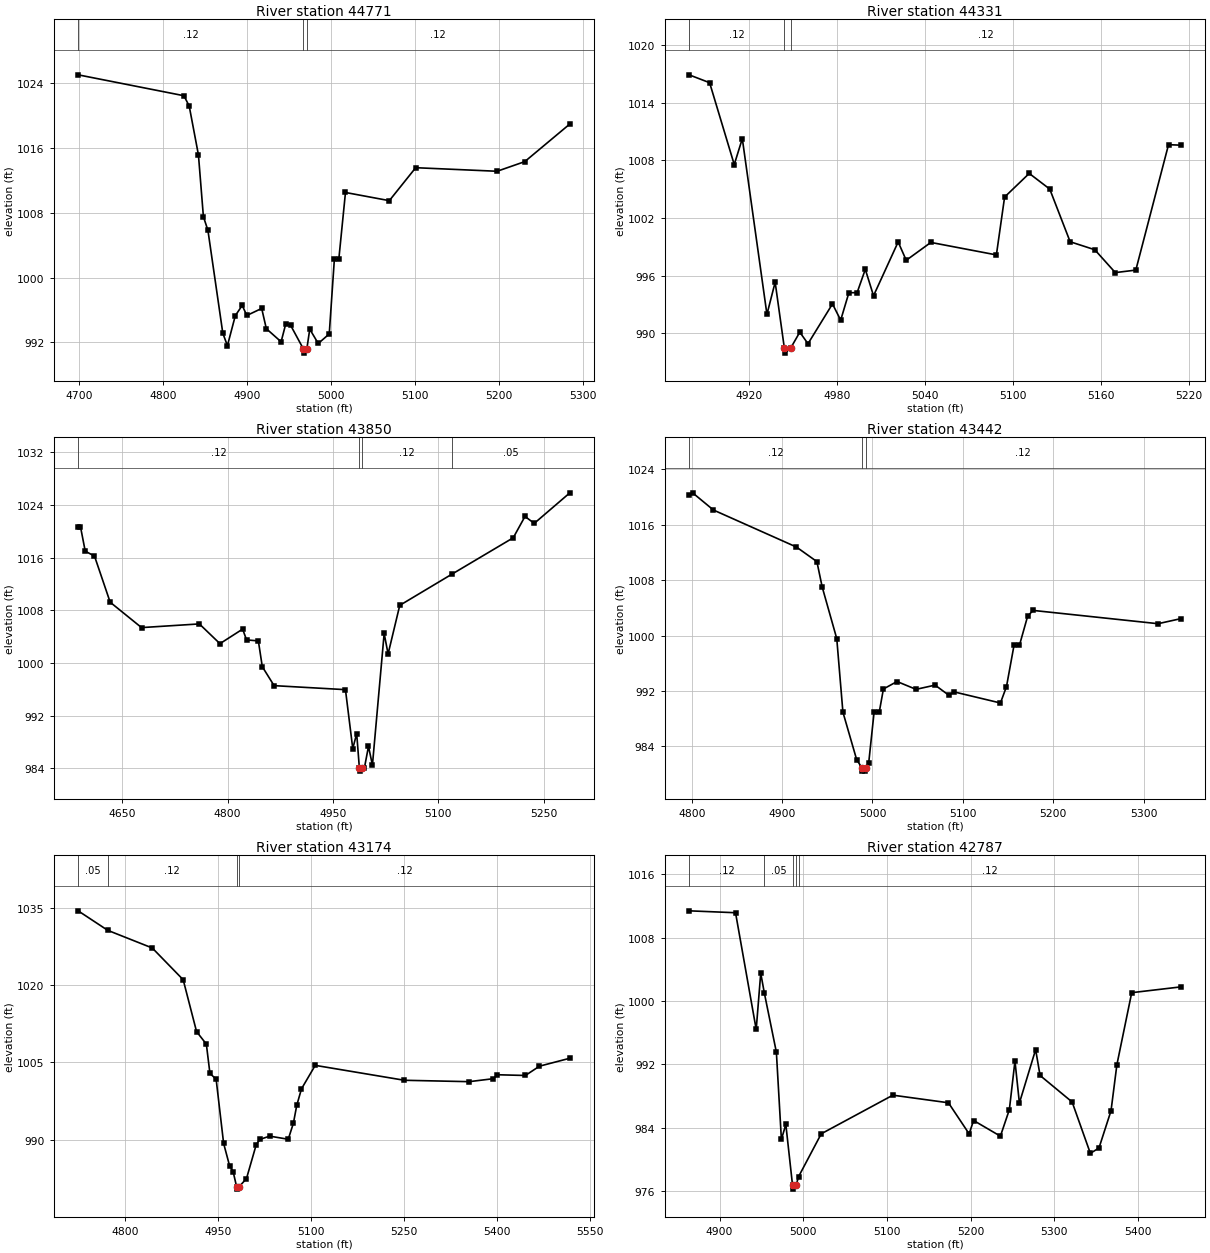
Type RM Length L Ch R = 1 ,44771   ,440,440,440
BEGIN DESCRIPTION:
Rush Creek 94.0
END DESCRIPTION:
XS GIS Cut Line= 3
      2257159.54       7215986.4        2256879.        7215860.
      2256613.46      7215779.09
#Sta/Elev= 30
  4698.9 1025.05  4824.8 1022.47  4831.1  1021.2  4842.1 1015.16    4848 1007.54
  4853.4 1005.84  4871.1  993.15  4876.6   991.6    4886  995.31  4894.2  996.57
  4899.7  995.33  4917.4   996.2  4922.9   993.7  4940.5  992.08    4946  994.28
  4951.8  994.12  4967.1  991.18  4967.4  990.68  4971.1  991.18  4974.6  993.64
  4984.7  991.87  4997.8  993.05  5003.9 1002.29  5009.2 1002.29  5017.1 1010.52
  5069.3 1009.51  5100.7 1013.58  5197.6 1013.14  5230.5 1014.33  5284.2 1018.98
#Mann= 3 ,-1 , 0
  4698.9     .12       0  4967.1     .07       0  4971.1     .12       0
Bank Sta=4967.1,4971.1
XS Rating Curve= 0 ,0
Exp/Cntr=0.3,0.1

Type RM Length L Ch R = 1 ,44331   ,481,481,481
BEGIN DESCRIPTION:
Rush Creek 93.0
END DESCRIPTION:
XS GIS Cut Line= 3
        2257179.        7215610.        2257079.        7215560.
      2256879.01      7215460.01
#Sta/Elev= 30
  4878.9  1016.9  4892.9 1016.08  4909.7 1007.56  4915.2 1010.26    4932  991.97
  4937.6  995.32  4943.9  988.44  4944.2  987.94  4948.1  988.44  4954.4  990.12
    4960  988.92  4976.7  993.06  4982.3  991.37  4987.9  994.23  4993.5  994.23
  4999.1  996.66  5004.7  993.91  5021.5  999.51    5027   997.6  5043.8  999.46
  5088.5  998.16  5094.1 1004.18  5110.9 1006.64  5124.9 1005.01  5138.8  999.53
  5155.6   998.7  5169.6  996.32  5183.6  996.58  5205.9 1009.63  5214.3 1009.58
#Mann= 3 ,-1 , 0
  4878.9     .12       0  4943.9     .07       0  4948.1     .12       0
Bank Sta=4943.9,4948.1
XS Rating Curve= 0 ,0
Exp/Cntr=0.3,0.1

Type RM Length L Ch R = 1 ,43850   ,408,408,408
BEGIN DESCRIPTION:
Rush Creek 92.0
END DESCRIPTION:
XS GIS Cut Line= 3
      2257349.87       7215401.1       2256984.8      7215219.79
      2256723.79       7215087.8
#Sta/Elev= 30
  4587.2 1020.72  4590.5 1020.72  4597.3 1016.97  4610.5 1016.23  4632.8 1009.22
  4677.5 1005.36  4759.8 1005.92  4789.1 1002.92  4821.4 1005.13    4827 1003.49
  4843.8 1003.34  4849.4  999.42  4866.2  996.54  4967.8  995.93  4978.2  986.98
  4983.8  989.25  4987.6  984.05  4987.9  983.55  4991.8  984.05  4994.8  984.05
  5000.6  987.31  5006.2  984.47  5022.9 1004.47  5028.5 1001.35  5045.1 1008.74
    5120 1013.52  5206.7 1019.01  5223.4 1022.25  5236.6  1021.2  5287.3 1025.84
#Mann= 4 ,-1 , 0
  4587.2     .12       0  4987.6     .07       0  4991.8     .12       0
    5120     .05       0
Bank Sta=4987.6,4991.8
XS Rating Curve= 0 ,0
Exp/Cntr=0.3,0.1

Type RM Length L Ch R = 1 ,43442   ,268,268,268
BEGIN DESCRIPTION:
Rush Creek 91.0
END DESCRIPTION:
XS GIS Cut Line= 3
       2257415.7      7215348.47        2257329.        7215160.
      2257143.73      7214878.92
#Sta/Elev= 30
  4797.1 1020.29    4801 1020.63    4824 1018.15  4915.9  1012.8  4938.5  1010.7
  4944.4 1007.02  4960.5  999.57  4967.3  988.96  4982.5   982.1  4988.2  980.94
  4988.5  980.44  4992.1  980.44  4992.5  980.94  4995.8  981.58  5001.8  988.95
  5007.5  988.95  5012.1   992.3  5027.2  993.38  5048.2  992.25  5069.3  992.86
  5084.4  991.41  5090.4  991.88  5141.6  990.28  5148.3  992.65  5156.6  998.59
  5162.6   998.6  5171.7 1002.81  5177.7 1003.65    5316 1001.73  5341.2 1002.46
#Mann= 3 ,-1 , 0
  4797.1     .12       0  4988.2     .07       0  4992.5     .12       0
Bank Sta=4988.2,4992.5
XS Rating Curve= 0 ,0
Exp/Cntr=0.3,0.1

Type RM Length L Ch R = 1 ,43174   ,387,387,387
BEGIN DESCRIPTION:
Rush Creek 90.0
END DESCRIPTION:
XS GIS Cut Line= 3
      2257762.84      7215148.34       2257472.6      7214982.08
      2257057.64      7214784.92
#Sta/Elev= 30
  4724.1 1034.36  4771.9 1030.58  4843.8 1027.16  4893.7 1021.01  4915.3 1010.96
  4931.1 1008.54  4936.9 1002.85  4946.9 1001.75    4959   989.3  4968.5  985.01
  4974.3  983.85  4979.9  980.94  4980.3  980.44  4984.2  980.94  4995.9  982.48
  5011.7  989.08  5017.4  990.06  5033.3  990.71  5063.3   990.1  5071.6  993.19
  5077.1  996.69  5084.7  999.87  5106.9 1004.42  5250.8 1001.53  5355.3 1001.26
  5394.7 1001.84  5400.8  1002.6  5446.2 1002.46  5468.9 1004.26    5518  1005.8
#Mann= 4 ,-1 , 0
  4724.1     .05       0  4771.9     .12       0  4979.9     .07       0
  4984.2     .12       0
Bank Sta=4979.9,4984.2
XS Rating Curve= 0 ,0
Exp/Cntr=0.3,0.1

Type RM Length L Ch R = 1 ,42787   ,327,327,327
BEGIN DESCRIPTION:
Rush Creek 89.1
END DESCRIPTION:
XS GIS Cut Line= 2
      2257856.45       7214675.4      2257307.65      7214885.37
#Sta/Elev= 30
  4863.6 1011.39  4919.1 1011.15  4943.8   996.4  4949.2 1003.51  4953.5 1001.02
  4967.9  993.53  4973.9  982.51  4979.2  984.41  4987.2  976.73  4987.6  976.23
  4991.5  976.73  4994.4   977.8  5021.5  983.22  5107.1   988.1  5173.5  987.14
  5198.2  983.22  5203.6   984.9  5235.6  982.92  5246.3  986.27    5253  992.41
  5258.3  987.11  5277.7  993.86    5283  990.59  5321.3  987.24  5343.1  980.75
  5353.4  981.43  5367.8  986.14  5374.8  991.95  5392.5 1001.05  5451.2 1001.78
#Mann= 5 ,-1 , 0
  4863.6     .12       0  4953.5     .05       0  4987.2     .07       0
  4991.5     .05       0  4994.4     .12       0
#XS Ineff= 2 , 0
       0                    5253       0  992.41
Permanent Ineff=
       F       F
Bank Sta=4987.2,4991.5
XS Rating Curve= 0 ,0
Exp/Cntr=0.3,0.1

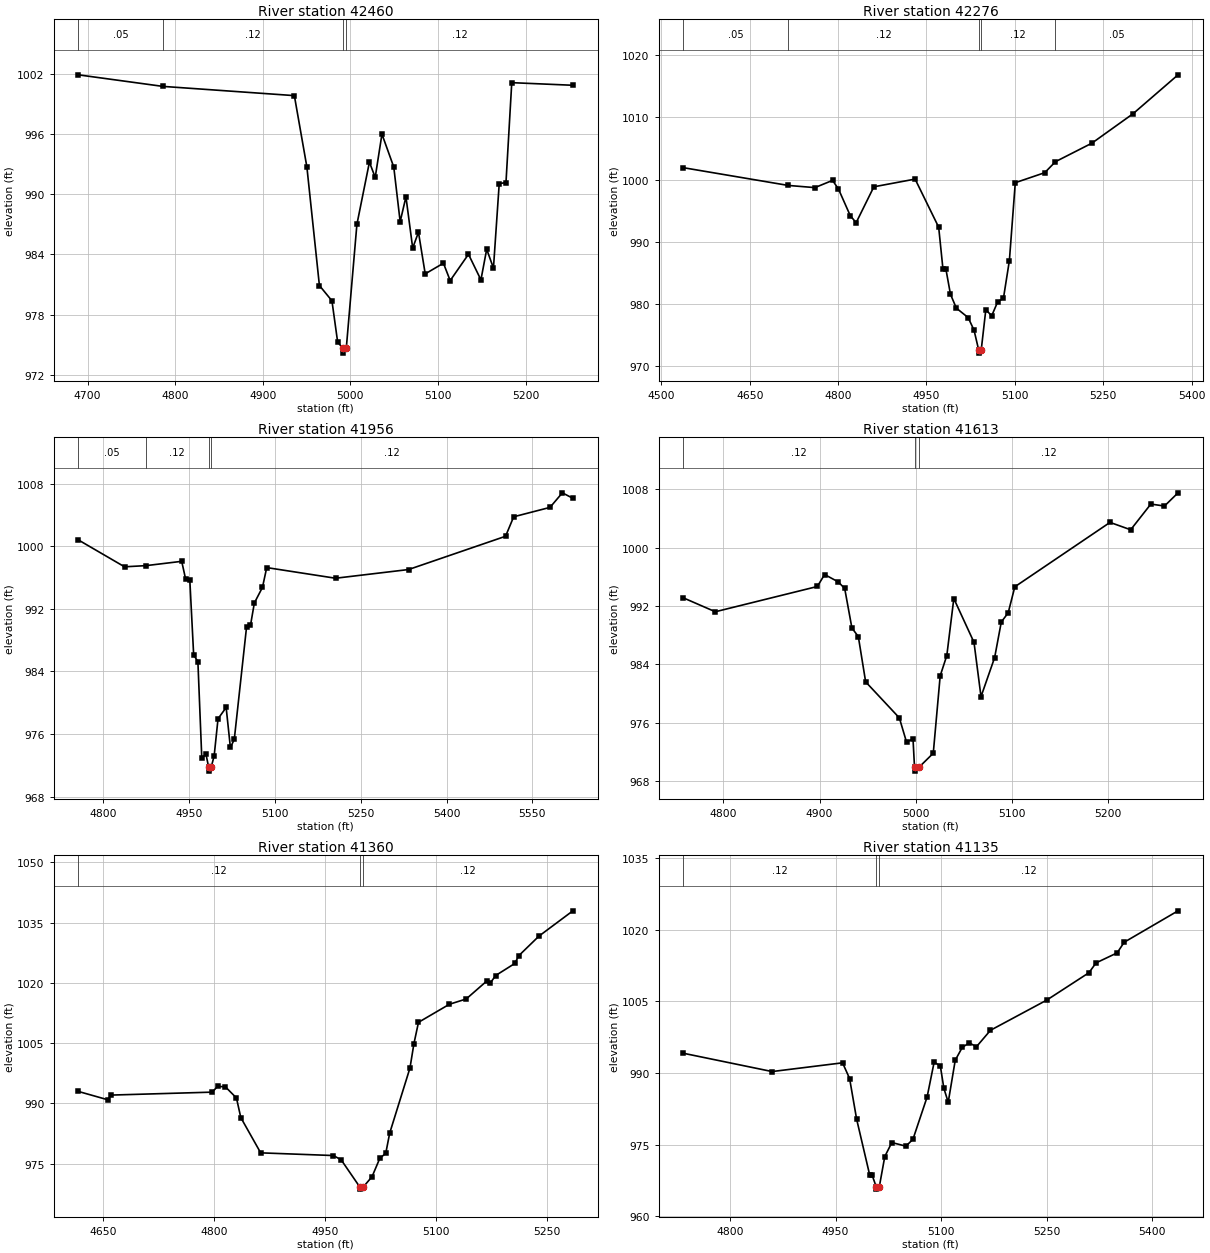
Type RM Length L Ch R = 1 ,42460   ,184,184,184
BEGIN DESCRIPTION:
Rush Creek 89.0
END DESCRIPTION:
XS GIS Cut Line= 3
      2257750.39      7214570.97      2257529.27      7214584.56
      2257306.46      7214845.55
#Sta/Elev= 30
  4689.4 1001.87  4785.9 1000.72  4936.1   999.8  4950.4   992.7  4964.7   980.9
    4979  979.38  4985.5  975.29  4991.1  974.67  4991.4  974.17  4995.4  974.67
  5007.5  986.98  5021.8  993.18  5028.4  991.66  5036.1  995.97  5049.6  992.69
  5056.9  987.25  5063.5  989.73  5071.2  984.63  5077.8   986.2  5085.5  982.06
  5106.3  983.12    5114  981.39  5134.9  984.01  5149.1  981.46  5155.7  984.51
  5163.4  982.63    5170  991.05  5177.7  991.14  5184.3 1001.09  5254.1 1000.83
#Mann= 4 ,-1 , 0
  4689.4     .05       0  4785.9     .12       0  4991.1     .07       0
  4995.4     .12       0
#XS Ineff= 2 , 0
       0                  5036.1       0  995.97
Permanent Ineff=
       F       F
Bank Sta=4991.1,4995.4
XS Rating Curve= 0 ,0
Exp/Cntr=0.3,0.1

Type RM Length L Ch R = 1 ,42276   ,320,320,320
BEGIN DESCRIPTION:
Rush Creek 88.1
END DESCRIPTION:
XS GIS Cut Line= 3
      2257792.06      7214561.71      2257349.42      7214550.79
      2256952.85      7214543.76
#Sta/Elev= 30
  4537.5 1001.93  4715.4  999.08  4760.6  998.73  4790.6  999.89  4800.6  998.51
  4820.6  994.24  4830.6  993.09  4860.7  998.86  4930.7  1000.1  4970.7  992.37
    4978  985.62    4983  985.62  4990.7   981.6  5000.7  979.37  5020.7  977.85
  5030.7  975.83  5038.6  972.64  5038.9  972.14  5042.9  972.64  5050.7  979.11
  5060.7  978.14  5070.7  980.35  5080.7     981  5090.7  987.01  5100.7  999.52
  5150.7 1001.13  5168.8 1002.89  5230.7 1005.87  5300.7 1010.61  5376.9 1016.85
#Mann= 5 ,-1 , 0
  4537.5     .05       0  4715.4     .12       0  5038.6     .07       0
  5042.9     .12       0  5168.8     .05       0
Bank Sta=5038.6,5042.9
XS Rating Curve= 0 ,0
Exp/Cntr=0.3,0.1

Type RM Length L Ch R = 1 ,41956   ,343,343,343
BEGIN DESCRIPTION:
Rush Creek 88.0
END DESCRIPTION:
XS GIS Cut Line= 3
      2257732.01       7214551.3      2257618.83      7214460.03
      2257087.55      7213975.27
#Sta/Elev= 30
  4756.3  1000.8  4837.2  997.36  4874.8  997.51  4937.1  998.06  4943.8  995.84
  4951.3  995.63    4958  986.11  4965.4  985.24  4972.2  972.94  4979.6   973.4
  4984.2  971.76  4984.6  971.26  4988.6  971.76  4993.8  973.19  5000.6  977.95
  5014.8  979.39  5022.2  974.28    5029  975.31  5050.4  989.63  5057.3  989.87
  5064.1  992.74  5078.3  994.74  5085.7  997.26    5206   995.9  5333.6  997.01
  5503.2 1001.26  5517.4 1003.75  5580.9 1004.95  5602.5 1006.81  5620.9 1006.11
#Mann= 4 ,-1 , 0
  4756.3     .05       0  4874.8     .12       0  4984.2     .07       0
  4988.6     .12       0
Bank Sta=4984.2,4988.6
XS Rating Curve= 0 ,0
Exp/Cntr=0.3,0.1

Type RM Length L Ch R = 1 ,41613   ,253,253,253
BEGIN DESCRIPTION:
Rush Creek 87.0
END DESCRIPTION:
XS GIS Cut Line= 3
      2257763.34      7214223.06        2257579.        7214060.
      2257383.72       7213875.3
#Sta/Elev= 30
  4758.3  993.12  4791.5  991.22  4897.7  994.68  4905.3  996.32  4919.5  995.31
  4926.2  994.41  4933.7     989  4940.4  987.81    4948  981.62  4983.1  976.68
  4990.6  973.35  4997.3  973.82  4998.9  969.89  4999.3  969.39  5003.3  969.89
  5018.4  971.84  5025.6  982.44  5032.5  985.22  5039.8  993.03  5060.8  987.03
  5068.1  979.59  5082.3  984.95  5089.2  989.81  5096.4  991.08  5103.3  994.64
  5202.4 1003.46  5223.9 1002.45  5244.9 1005.97  5259.1  1005.7  5273.2 1007.51
#Mann= 3 ,-1 , 0
  4758.3     .12       0  4998.9     .07       0  5003.3     .12       0
Bank Sta=4998.9,5003.3
XS Rating Curve= 0 ,0
Exp/Cntr=0.3,0.1

Type RM Length L Ch R = 1 ,41360   ,225,225,225
BEGIN DESCRIPTION:
Rush Creek 86.1
END DESCRIPTION:
XS GIS Cut Line= 2
      2257766.31      7214200.42       2257570.9      7213560.08
#Sta/Elev= 30
    4616  992.99  4655.6  990.93  4660.8  992.08  4797.3  992.81  4804.6  994.24
  4815.1  994.14  4830.1  991.36    4836  986.48  4862.9   977.7  4961.4  977.03
  4971.9  975.95  4997.2  969.17  4997.6  968.67  5001.6  969.17  5013.7  971.79
  5024.2  976.36  5032.2  977.58  5037.5  982.59    5065  998.84  5070.3 1004.86
  5076.5 1010.19  5118.3 1014.68  5141.1    1016  5168.7 1020.43  5173.9 1020.02
    5181 1021.84  5206.8 1024.83  5212.4  1026.8  5239.6 1031.65  5285.5 1037.94
#Mann= 3 ,-1 , 0
    4616     .12       0  4997.2     .07       0  5001.6     .12       0
Bank Sta=4997.2,5001.6
XS Rating Curve= 0 ,0
Exp/Cntr=0.3,0.1

Type RM Length L Ch R = 1 ,41135   ,437,437,437
BEGIN DESCRIPTION:
Rush Creek 86.0
END DESCRIPTION:
XS GIS Cut Line= 3
      2257778.53       7214225.8      2257791.83      7213958.36
      2257801.18      7213523.53
#Sta/Elev= 30
  4733.8  994.13  4859.8   990.3  4959.9  992.13  4969.9  988.84  4979.9  980.32
  4998.3  968.72  5001.6  968.72  5007.7  966.17  5008.1  965.67  5012.1  966.17
  5019.9   972.5  5029.9  975.43  5049.9  974.67  5059.9  976.11    5080  984.96
    5090  992.27  5098.8  991.49  5103.8  986.81    5110  983.86    5120  992.68
    5130  995.37    5140  996.32    5150  995.48    5170  998.94    5250 1005.27
    5310 1011.01    5320 1013.06    5350 1015.16    5360 1017.39  5436.5 1023.97
#Mann= 3 ,-1 , 0
  4733.8     .12       0  5007.7     .07       0  5012.1     .12       0
Bank Sta=5007.7,5012.1
XS Rating Curve= 0 ,0
Exp/Cntr=0.3,0.1