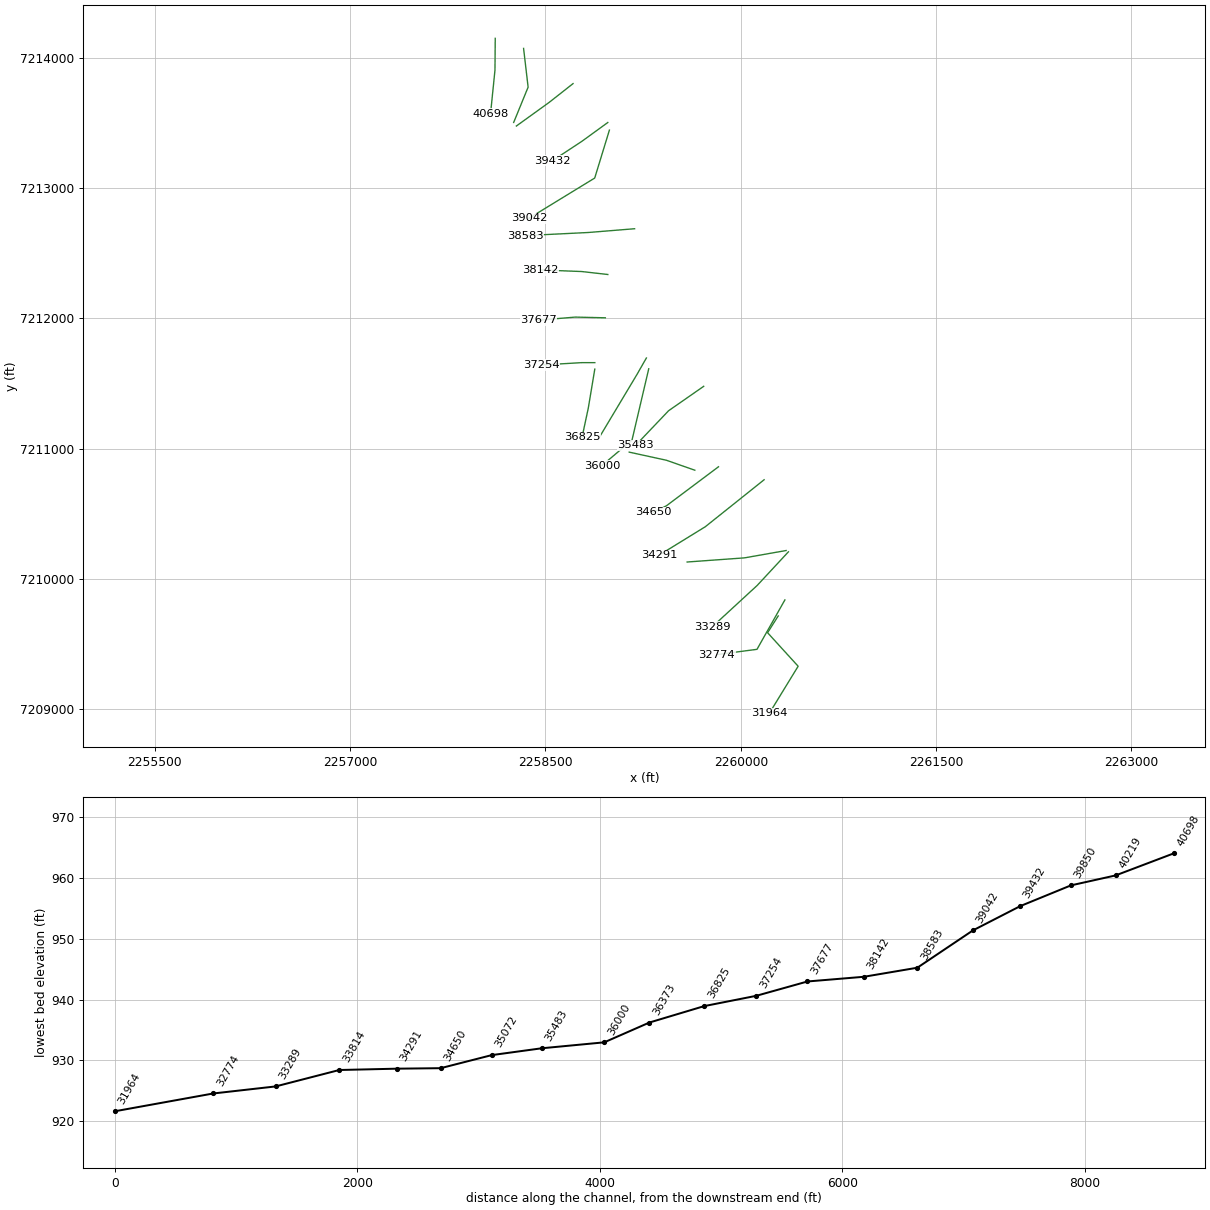
HEC-RAS study Rush Creek.prj: Rush Creek Base Level Engineering

--- Rush Creek.g01 (geometry) --- (continued)

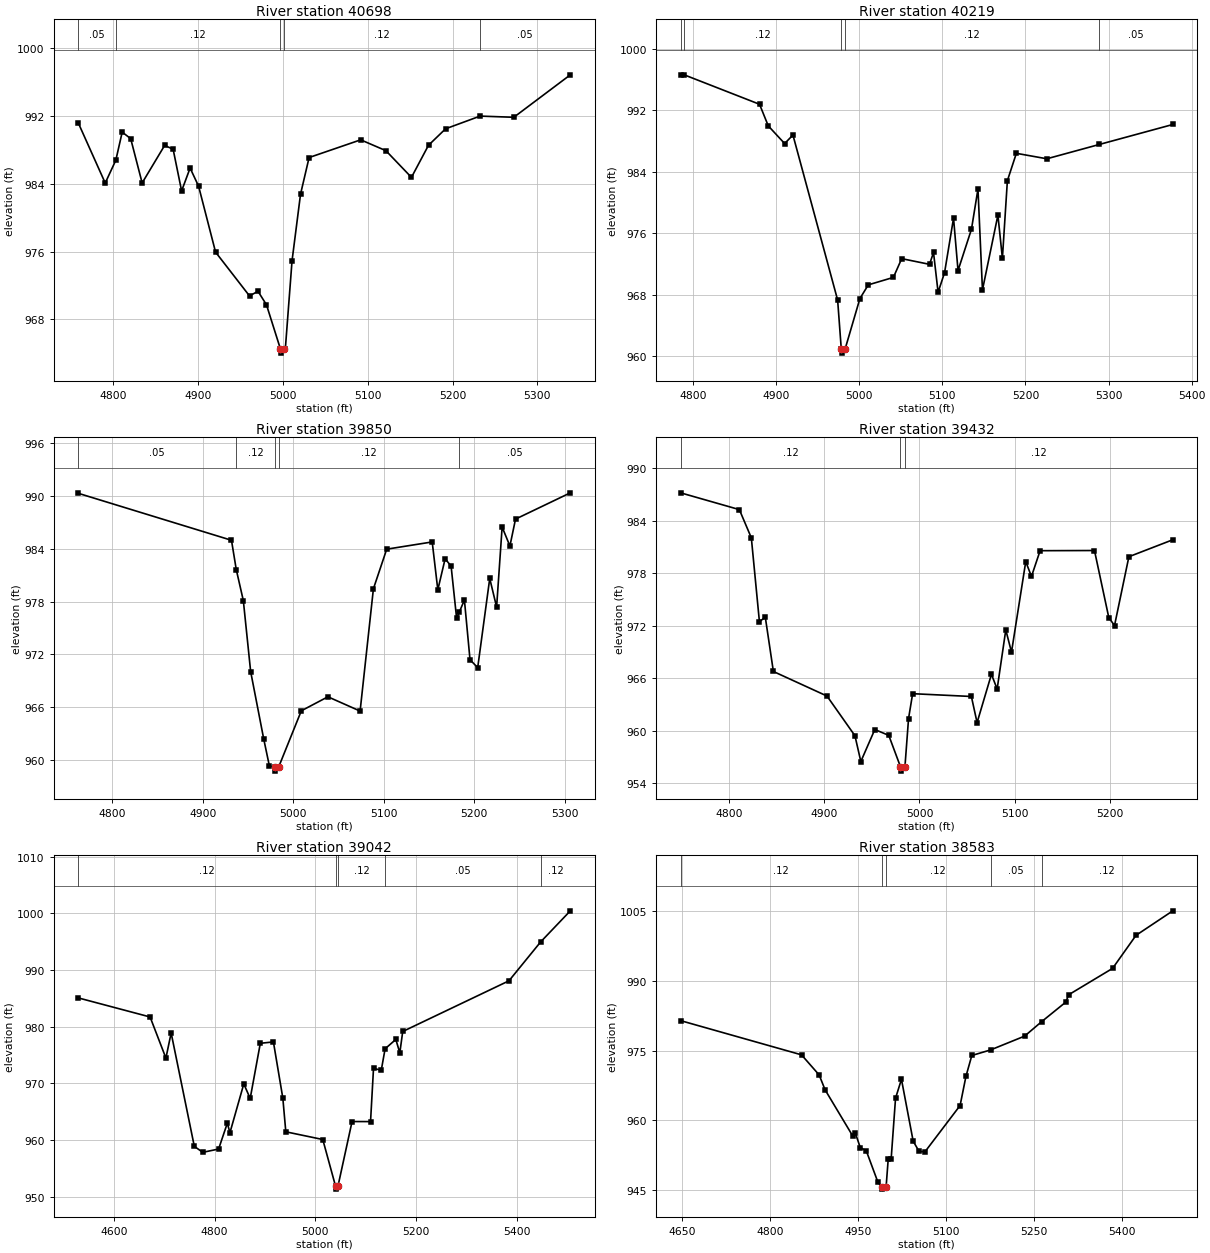
Type RM Length L Ch R = 1 ,40698   ,479,479,479
BEGIN DESCRIPTION:
Rush Creek 85.0
END DESCRIPTION:
XS GIS Cut Line= 3
      2258114.65      7214151.94       2258112.5      7213907.82
      2258078.65      7213573.76
#Sta/Elev= 30
  4758.9  991.23  4790.8   984.1  4803.3   986.8  4810.8  990.11  4820.8  989.34
  4834.3  984.11  4860.8  988.54  4870.8  988.09  4880.8  983.17  4890.8  985.87
  4900.8  983.73  4920.8  975.95  4960.8  970.78  4970.8  971.33  4980.8  969.73
  4997.2  964.53  4997.6  964.03  5001.7  964.53    5003  964.53  5010.9  974.92
  5020.9  982.78    5031  987.11  5091.8   989.2  5121.5  987.92  5151.6  984.77
  5171.7  988.56  5191.8   990.5  5232.5     992  5272.2  991.86  5338.8  996.87
#Mann= 5 ,-1 , 0
  4758.9     .05       0  4803.3     .12       0  4997.2     .07       0
  5001.7     .12       0  5232.5     .05       0
Bank Sta=4997.2,5001.7
XS Rating Curve= 0 ,0
Exp/Cntr=0.3,0.1

Type RM Length L Ch R = 1 ,40219   ,369,369,369
BEGIN DESCRIPTION:
Rush Creek 84.0
END DESCRIPTION:
XS GIS Cut Line= 3
      2258332.34      7214074.34      2258366.97      7213776.78
      2258256.22      7213505.69
#Sta/Elev= 30
  4784.9  996.61  4789.2  996.61  4879.9  992.78  4890.4  989.97  4910.1  987.67
  4920.1  988.78  4973.9  967.31  4978.3  960.91  4978.7  960.41  4982.8  960.91
  5000.7  967.51  5010.8  969.29    5041  970.26    5051   972.7  5084.5  971.96
  5089.3   973.5  5094.8  968.32  5102.6  970.88  5113.4  977.97  5118.8  971.15
    5135  976.54  5142.8  981.76  5148.2  968.63  5166.8  978.36  5172.2  972.75
  5178.2  982.84    5189   986.4  5225.7  985.69  5288.8  987.55  5377.3  990.15
#Mann= 5 ,-1 , 0
  4784.9     .05       0  4789.2     .12       0  4978.3     .07       0
  4982.8     .12       0  5288.8     .05       0
Bank Sta=4978.3,4982.8
XS Rating Curve= 0 ,0
Exp/Cntr=0.3,0.1

Type RM Length L Ch R = 1 ,39850   ,418,418,418
BEGIN DESCRIPTION:
Rush Creek 83.0
END DESCRIPTION:
XS GIS Cut Line= 3
      2258712.21      7213804.18        2258529.        7213660.
      2258276.77      7213478.13
#Sta/Elev= 30
  4762.1  990.28  4931.6  984.95  4936.9  981.62  4944.7  978.11  4952.8  970.06
  4967.2  962.44  4973.6  959.31  4979.3  959.27  4979.8  958.77  4983.9  959.27
  5008.8  965.61  5038.2   967.2  5073.8  965.58  5088.5  979.45  5103.2  983.94
  5153.5  984.76  5159.7  979.33  5167.8  982.86  5174.4  982.01  5180.5  976.09
  5183.4  976.79  5189.1  978.18  5195.3   971.4  5203.8  970.51  5217.1  980.62
  5224.7  977.37  5230.8  986.45  5239.4   984.3  5245.6  987.35  5306.2  990.33
#Mann= 5 ,-1 , 0
  4762.1     .05       0  4936.9     .12       0  4979.3     .07       0
  4983.9     .12       0  5183.4     .05       0
Bank Sta=4979.3,4983.9
XS Rating Curve= 0 ,0
Exp/Cntr=0.3,0.1

Type RM Length L Ch R = 1 ,39432   ,390,390,390
BEGIN DESCRIPTION:
Rush Creek 82.0
END DESCRIPTION:
XS GIS Cut Line= 3
      2258979.01      7213505.25        2258779.        7213360.
      2258553.02      7213211.12
#Sta/Elev= 30
  4748.7   987.2  4810.5  985.28  4823.1  982.05  4831.6  972.46  4837.8  972.97
  4846.3  966.76  4902.7  963.95  4932.1  959.41  4938.3  956.46    4953  960.12
  4967.7  959.45    4980  955.86  4980.5  955.36  4984.7  955.86  4988.5  961.38
  4992.8  964.22  5054.6   963.9  5060.6  960.91  5075.7  966.44  5081.7  964.75
  5090.8  971.52  5096.8  968.97  5111.8  979.33  5117.8  977.63  5126.9  980.58
  5184.1   980.6  5199.2  972.91  5205.2  972.02  5220.3  979.89  5266.5  981.83
#Mann= 3 ,-1 , 0
  4748.7     .12       0    4980     .07       0  4984.7     .12       0
Bank Sta=4980,4984.7
XS Rating Curve= 0 ,0
Exp/Cntr=0.3,0.1

Type RM Length L Ch R = 1 ,39042   ,459,459,459
BEGIN DESCRIPTION:
Rush Creek 81.0
END DESCRIPTION:
XS GIS Cut Line= 3
       2258991.2      7213446.54      2258878.41      7213078.39
      2258373.56      7212769.28
#Sta/Elev= 30
  4529.2   985.1    4672  981.73  4703.4  974.48  4713.8  978.91  4759.8  958.91
  4776.6  957.86    4808  958.44  4825.3     963  4830.5  961.32    4858  969.93
  4870.7  967.36  4890.8  977.09  4916.8  977.33  4935.5  967.42  4941.4  961.48
  5014.8  960.12  5040.2  951.87  5040.7  951.37  5044.9  951.87  5072.9  963.29
  5109.6  963.28  5115.5  972.67  5130.9  972.34  5138.5  976.12  5159.8  977.77
  5167.7   975.4  5173.5  979.17  5384.4  988.11  5447.3  994.97  5506.2 1000.45
#Mann= 5 ,-1 , 0
  4529.2     .12       0  5040.2     .07       0  5044.9     .12       0
  5138.5     .05       0  5447.3     .12       0
Bank Sta=5040.2,5044.9
XS Rating Curve= 0 ,0
Exp/Cntr=0.3,0.1

Type RM Length L Ch R = 1 ,38583   ,441,441,441
BEGIN DESCRIPTION:
Rush Creek 80.0
END DESCRIPTION:
XS GIS Cut Line= 3
      2259184.76      7212688.94        2258829.        7212660.
      2258346.31      7212636.33
#Sta/Elev= 30
  4647.3  981.44  4853.7  974.09  4883.8  969.77  4893.9  966.58  4940.8  956.72
  4945.8  957.19  4954.1  954.12  4964.1  953.52  4984.2  946.69  4990.4  945.73
  4991.6  945.23  4998.1  945.73  5001.7   951.7  5006.7   951.7  5014.2  964.77
  5024.3  968.83  5044.3  955.54  5054.3  953.35  5064.3  953.23  5124.4   963.2
  5134.4  969.47  5144.4  973.95  5176.3  975.14  5234.5  978.11  5263.7  981.23
  5304.6   985.4    5310  987.02  5384.7  992.67  5424.7  999.77  5487.5 1005.04
#Mann= 5 ,-1 , 0
  4647.3     .12       0  4990.4     .07       0  4998.1     .12       0
  5176.3     .05       0  5263.7     .12       0
Bank Sta=4990.4,4998.1
XS Rating Curve= 0 ,0
Exp/Cntr=0.3,0.1

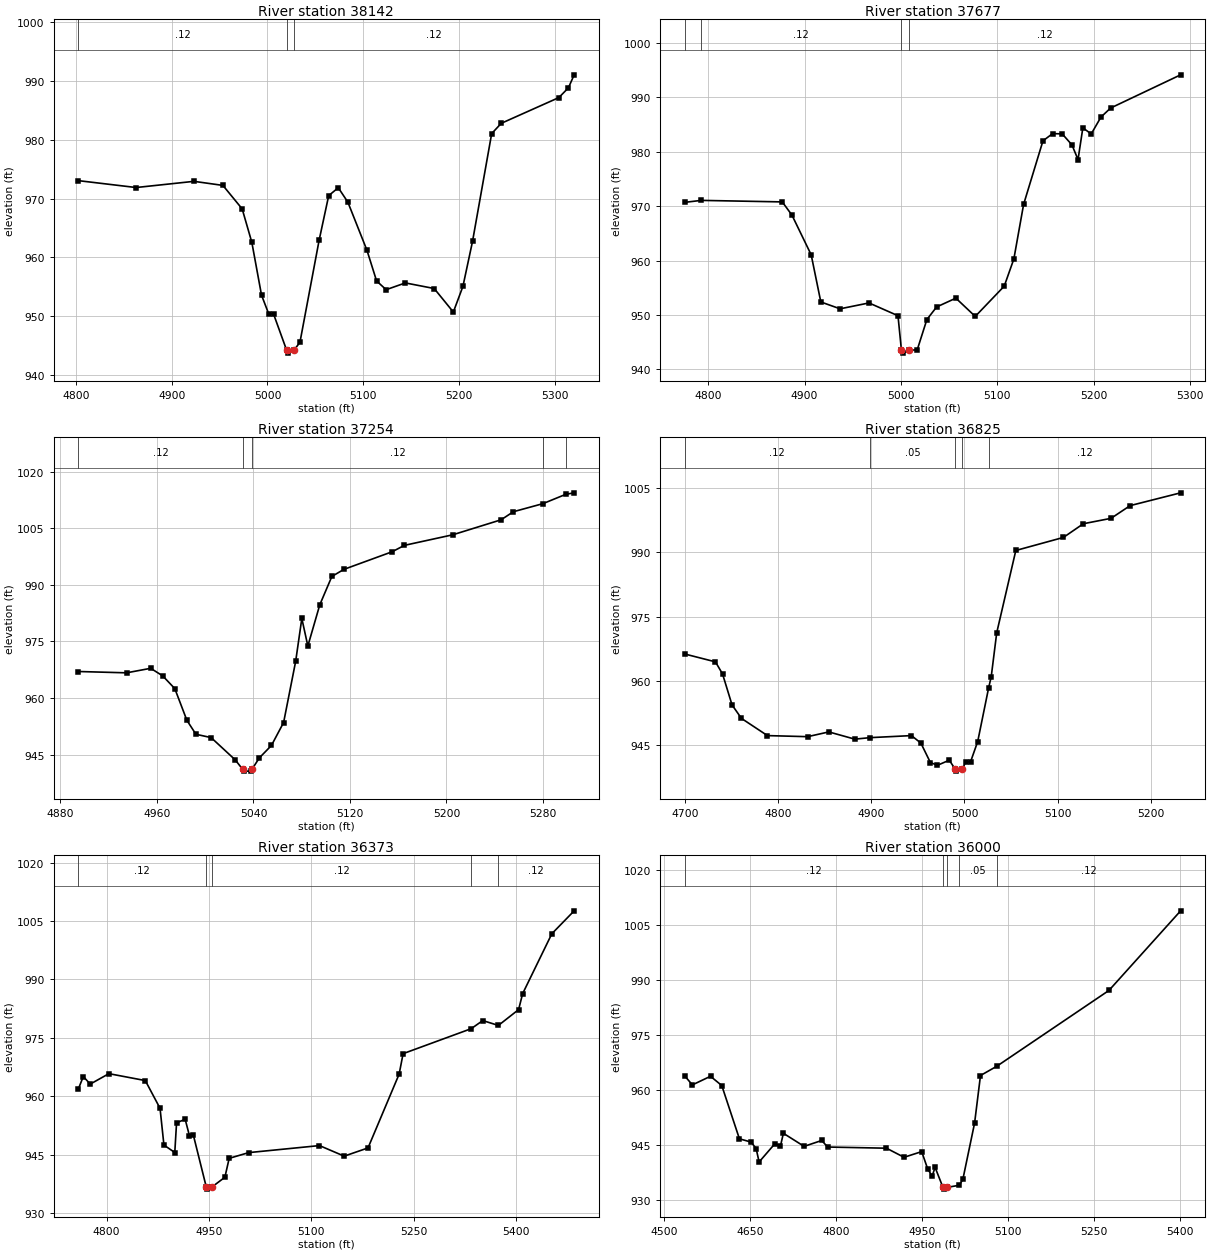
Type RM Length L Ch R = 1 ,38142   ,465,465,465
BEGIN DESCRIPTION:
Rush Creek 79.0
END DESCRIPTION:
XS GIS Cut Line= 3
      2258978.95       7212337.3        2258779.        7212360.
      2258462.98       7212372.4
#Sta/Elev= 30
  4802.6  973.05  4862.9  971.88  4923.3  972.93  4953.5  972.24  4973.6  968.25
  4983.7  962.55  4993.8  953.59  5001.3  950.41  5006.3  950.41    5020  944.24
  5021.2  943.74  5027.7  944.24  5033.9  945.58  5053.9  962.91  5063.9   970.5
  5073.9  971.85  5083.9   969.4  5103.9  961.19  5113.9     956  5123.9  954.52
  5143.9  955.67    5174  954.72    5194  950.72    5204  955.08    5214  962.71
    5234  981.04    5244  982.79  5304.1  987.16  5314.1  988.82  5320.1  991.03
#Mann= 3 ,-1 , 0
  4802.6     .12       0    5020     .07       0  5027.7     .12       0
Bank Sta=5020,5027.7
XS Rating Curve= 0 ,0
Exp/Cntr=0.3,0.1

Type RM Length L Ch R = 1 ,37677   ,423,423,423
BEGIN DESCRIPTION:
Rush Creek 78.0
END DESCRIPTION:
XS GIS Cut Line= 3
      2258960.19      7212004.66        2258729.        7212010.
      2258446.56      7211986.16
#Sta/Elev= 30
  4775.7   970.7  4792.8  971.06  4876.9  970.78  4886.9  968.36  4906.9  961.05
  4916.9  952.38  4936.9  951.12  4966.9   952.2    4997  949.85  5000.6  943.47
  5001.8  942.97  5008.4  943.47    5017  943.59    5027  949.15  5037.1  951.46
  5057.1  953.08  5077.2  949.72  5107.3  955.29  5117.3   960.3  5127.4  970.32
  5147.5  982.01  5157.5  983.34  5167.5  983.29  5177.6  981.26  5183.9  978.56
  5188.9   984.4  5197.6  983.28  5207.7  986.38  5217.7  988.04  5290.4  994.15
#Mann= 4 ,-1 , 0
  4775.7     .05       0  4792.8     .12       0  5000.6     .07       0
  5008.4     .12       0
Bank Sta=5000.6,5008.4
XS Rating Curve= 0 ,0
Exp/Cntr=0.3,0.1

Type RM Length L Ch R = 1 ,37254   ,429,429,429
BEGIN DESCRIPTION:
Rush Creek 77.0
END DESCRIPTION:
XS GIS Cut Line= 3
      2258879.04        7211660.        2258779.        7211660.
      2258468.47      7211641.76
#Sta/Elev= 30
  4894.8  967.02  4934.8  966.67  4954.8  967.87  4964.8  965.85  4974.8  962.48
  4984.8  954.08  4992.3  950.38  5004.9   949.5  5024.9  943.59    5031  941.11
  5032.2  940.61  5037.6  940.61  5038.8  941.11  5044.9  944.13  5054.9  947.41
    5065   953.5    5075  969.73  5080.1  981.08  5085.1  973.78    5095  984.71
    5105  992.22    5115   994.1  5155.1  998.78  5165.1 1000.46  5205.2 1003.26
  5245.3 1007.24  5255.5 1009.38    5280 1011.52    5299    1014  5305.9 1014.39
#Mann= 5 ,-1 , 0
  4894.8     .12       0    5031     .07       0  5038.8     .12       0
    5280     .05       0    5299     .12       0
Bank Sta=5031,5038.8
XS Rating Curve= 0 ,0
Exp/Cntr=0.3,0.1

Type RM Length L Ch R = 1 ,36825   ,452,452,452
BEGIN DESCRIPTION:
Rush Creek 76.0
END DESCRIPTION:
XS GIS Cut Line= 3
        2258879.      7211609.99        2258829.        7211310.
      2258781.26      7211086.98
#Sta/Elev= 30
  4699.8  966.28  4732.7  964.45  4740.3  961.63  4750.5  954.39  4760.6  951.24
  4788.5  947.22  4831.6  946.97  4854.4  948.08  4882.3  946.39  4898.4  946.74
  4943.1  947.22  4953.2  945.47  4963.4  940.93    4971  940.28  4983.7  941.48
  4989.9  939.42    4991  938.92  4997.7  939.42  5001.4  941.08  5006.5  941.08
  5014.2  945.84  5025.8  958.25  5028.7  960.97  5034.6  971.24  5055.1  990.47
  5106.2  993.52  5127.6  996.72  5157.3  997.98  5177.8 1000.95    5232 1003.94
#Mann= 5 ,-1 , 0
  4699.8     .12       0  4898.4     .05       0  4989.9    .033       0
  4997.7     .05       0  5025.8     .12       0
Bank Sta=4989.9,4997.7
XS Rating Curve= 0 ,0
Exp/Cntr=0.3,0.1

Type RM Length L Ch R = 1 ,36373   ,373,373,373
BEGIN DESCRIPTION:
Rush Creek 75.0
END DESCRIPTION:
XS GIS Cut Line= 3
      2259275.08      7211695.79      2259203.66       7211570.5
      2258904.83      7211070.86
#Sta/Elev= 30
  4758.5   961.9  4765.8  965.11  4775.9  963.16  4803.3  965.84  4856.6  964.07
  4878.2  956.95  4883.9  947.53  4899.8  945.61  4902.4  953.21    4915  954.15
  4921.2  949.97    4927  950.09    4946  936.72  4947.2  936.22  4953.9  936.72
  4973.2  939.27  4979.5  944.12  5008.2  945.59  5111.8  947.39    5148  944.68
  5182.9  946.79  5228.5  965.73  5234.3  970.97  5334.1  977.38    5351  979.46
  5373.9  978.21  5403.5  982.27  5409.4  986.35  5452.2 1001.73  5484.9 1007.61
#Mann= 5 ,-1 , 0
  4758.5     .12       0    4946     .07       0  4953.9     .12       0
  5334.1     .05       0  5373.9     .12       0
Bank Sta=4946,4953.9
XS Rating Curve= 0 ,0
Exp/Cntr=0.3,0.1

Type RM Length L Ch R = 1 ,36000   ,517,517,517
BEGIN DESCRIPTION:
Rush Creek 74.0
END DESCRIPTION:
XS GIS Cut Line= 3
      2259293.27      7211612.87       2259164.7      7211064.52
      2258933.38        7210869.
#Sta/Elev= 30
  4535.8  963.84    4549  961.41  4580.7  963.76  4600.4  961.23  4631.2  946.69
  4651.7   945.8  4660.4  944.03  4665.6  940.37  4692.8  945.29  4702.9  944.73
    4708   948.2  4744.2  944.63    4775  946.24  4785.3  944.45  4888.1  944.13
  4918.8  941.65  4949.6   943.2  4959.9  938.55  4967.8   936.5    4973   938.9
  4986.7  933.46  4987.9  932.96  4994.6  933.46  5015.2  934.01  5021.5  935.62
    5042  950.99  5052.3  963.97  5080.8   966.5  5276.7  987.19  5401.9 1008.92
#Mann= 5 ,-1 , 0
  4535.8     .12       0  4986.7     .07       0  4994.6     .12       0
  5015.2     .05       0  5080.8     .12       0
Bank Sta=4986.7,4994.6
XS Rating Curve= 0 ,0
Exp/Cntr=0.3,0.1

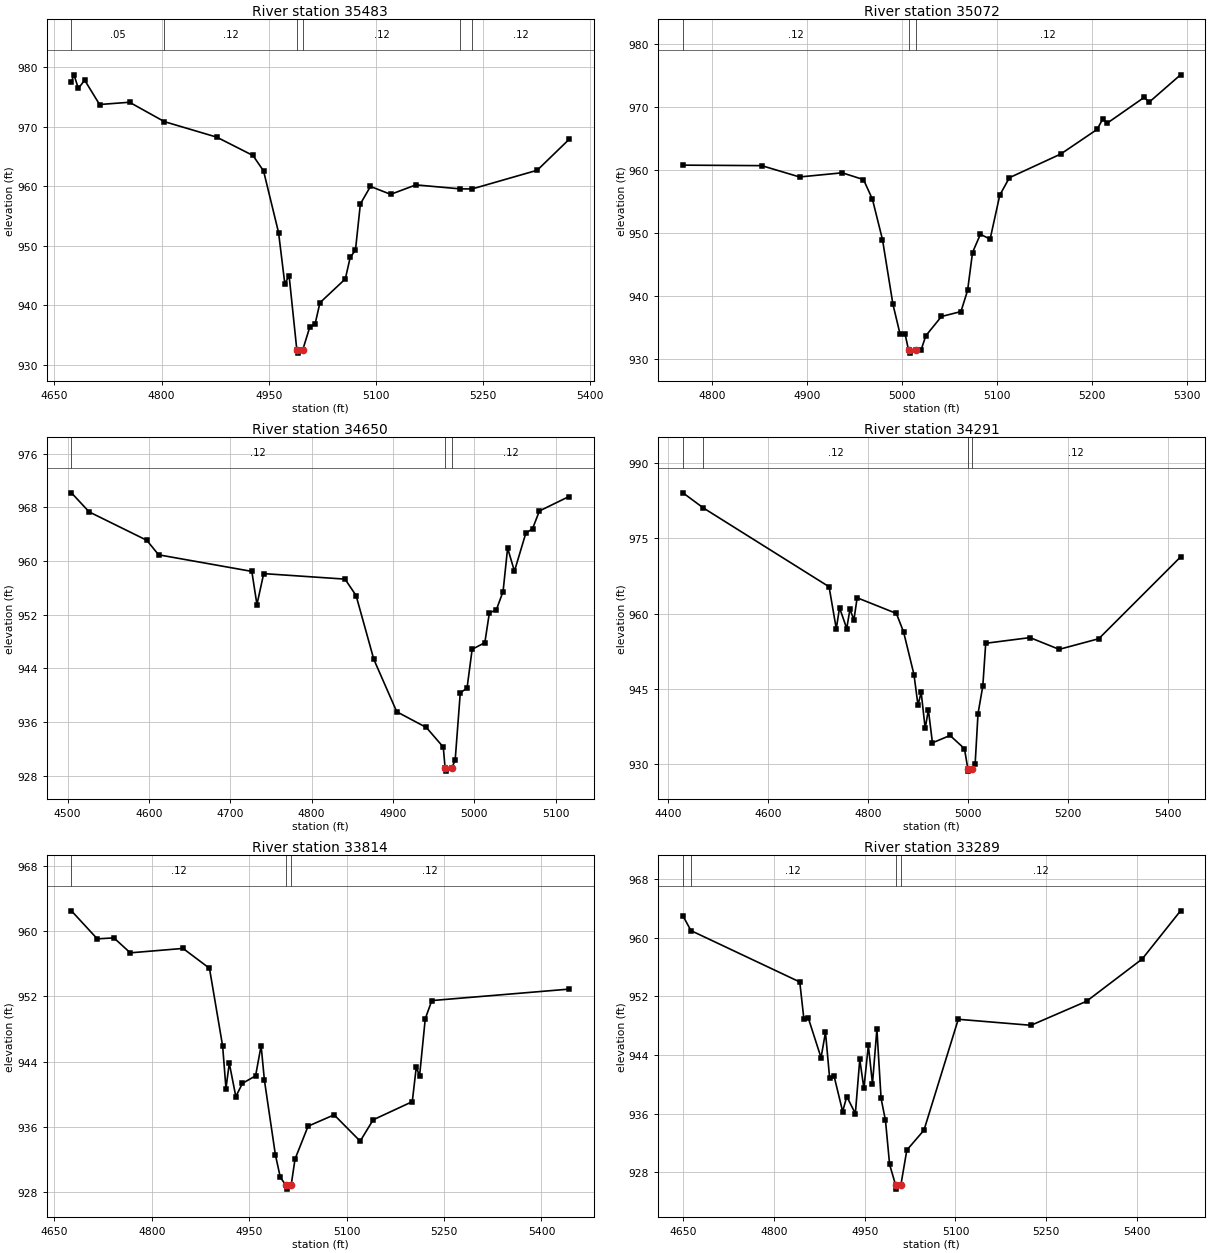
Type RM Length L Ch R = 1 ,35483   ,411,411,411
BEGIN DESCRIPTION:
Rush Creek 73.0
END DESCRIPTION:
XS GIS Cut Line= 3
      2259715.42      7211478.16      2259445.71      7211290.45
      2259192.06      7211024.11
#Sta/Elev= 30
  4673.9   977.6  4677.5  978.76  4683.6  976.47  4692.4  977.87  4713.3  973.77
  4755.2  974.15    4804  970.89  4877.4  968.28    4928   965.2  4942.8   962.6
  4963.8  952.24  4972.5  943.68  4978.6  944.93  4989.4  932.48  4990.6  931.98
  4997.5  932.48  5007.5  936.36  5014.8  936.81  5021.7  940.45  5057.2  944.45
  5064.1   948.1  5071.4  949.27  5078.3  957.06  5092.4     960  5120.7  958.67
    5156  960.26  5217.9  959.59  5234.7  959.58  5325.8  962.72  5370.3   967.9
#Mann= 6 ,-1 , 0
  4673.9     .05       0    4804     .12       0  4989.4     .07       0
  4997.5     .12       0  5217.9     .05       0  5234.7     .12       0
Bank Sta=4989.4,4997.5
XS Rating Curve= 0 ,0
Exp/Cntr=0.3,0.1

Type RM Length L Ch R = 1 ,35072   ,422,422,422
BEGIN DESCRIPTION:
Rush Creek 72.0
END DESCRIPTION:
XS GIS Cut Line= 3
      2259647.25      7210833.42        2259429.        7210910.
      2259143.12      7210972.37
#Sta/Elev= 30
    4769  960.77  4851.9  960.69  4891.8  958.89  4936.7  959.55  4959.1  958.47
  4968.5  955.35  4979.1  948.92  4990.1  938.63  4997.6  933.89  5002.9  933.89
  5006.5  931.36  5007.7  930.86  5014.6  931.36  5019.7  931.36  5024.8  933.64
  5041.2  936.69  5061.7  937.47  5068.7  940.84  5073.9  946.87  5082.2  949.78
  5092.4  948.99  5102.6     956  5112.7  958.77  5166.8  962.54    5205  966.45
  5210.8  968.05  5215.9  967.47  5254.7  971.56  5259.8  970.78  5292.9  975.14
#Mann= 3 ,-1 , 0
    4769     .12       0  5006.5     .07       0  5014.6     .12       0
Bank Sta=5006.5,5014.6
XS Rating Curve= 0 ,0
Exp/Cntr=0.3,0.1

Type RM Length L Ch R = 1 ,34650   ,359,359,359
BEGIN DESCRIPTION:
Rush Creek 71.0
END DESCRIPTION:
XS GIS Cut Line= 3
      2259828.96      7210859.97        2259429.        7210560.
      2259328.96      7210509.98
#Sta/Elev= 30
  4504.6  970.15  4526.4  967.31  4597.3  963.08  4611.8  960.92  4726.4  958.45
  4732.7  953.51    4741  958.12    4841   957.3  4854.6  954.85  4876.4  945.35
  4904.6  937.55    4941  935.21  4961.8  932.29    4964  929.21  4965.2  928.71
  4972.2  929.21  4976.4  930.32  4982.7  940.38    4991  941.06  4997.3  946.85
  5012.9  947.84  5018.5   952.3  5026.9  952.68  5035.3  955.45  5040.9  961.93
  5049.3  958.48  5063.2  964.11  5071.6  964.82    5080  967.45  5116.4   969.6
#Mann= 3 ,-1 , 0
  4504.6     .12       0    4964     .07       0  4972.2     .12       0
Bank Sta=4964,4972.2
XS Rating Curve= 0 ,0
Exp/Cntr=0.3,0.1

Type RM Length L Ch R = 1 ,34291   ,477,477,477
BEGIN DESCRIPTION:
Rush Creek 70.0
END DESCRIPTION:
XS GIS Cut Line= 3
      2260178.98      7210759.99      2259728.16      7210399.51
      2259372.81      7210180.57
#Sta/Elev= 30
  4430.4  984.03  4470.9  981.04  4722.5  965.33  4736.9  956.96  4743.4  961.16
  4757.8  957.02  4764.2  960.84  4772.2  958.76  4778.6  963.14    4857  960.02
  4871.4  956.35  4892.2  947.86  4900.2  941.76  4906.6  944.32  4914.6  937.13
    4921  940.83  4929.1  934.26  4964.3  935.73  4993.1   933.1  4999.8  929.13
    5001  928.63    5008  929.13  5014.4  929.95  5020.2  940.06  5029.8  945.57
  5035.6  954.08  5124.1  955.21  5182.4  952.87  5261.6  954.99    5425  971.26
#Mann= 4 ,-1 , 0
  4430.4     .05       0  4470.9     .12       0  4999.8     .07       0
    5008     .12       0
Bank Sta=4999.8,5008
XS Rating Curve= 0 ,0
Exp/Cntr=0.3,0.1

Type RM Length L Ch R = 1 ,33814   ,525,525,525
BEGIN DESCRIPTION:
Rush Creek 69.0
END DESCRIPTION:
XS GIS Cut Line= 3
      2260348.22      7210216.41        2260029.        7210160.
      2259588.31      7210128.11
#Sta/Elev= 30
  4676.4  962.46  4716.2  959.03  4741.8  959.15    4767  957.32  4848.2  957.86
  4888.9  955.43  4909.2  945.91  4914.3  940.72  4919.4  943.82  4929.5  939.73
  4939.6  941.35  4959.9  942.27  4968.4  945.96  4973.5  941.73  4990.4   932.6
    4998  929.84  5006.4  928.91  5007.7  928.41  5014.7  928.91  5020.6  932.08
  5040.7  936.11  5080.8   937.5  5120.9  934.28  5140.9  936.89  5201.1  939.11
  5207.3  943.36  5212.3  942.24  5221.1  949.26  5231.2  951.48  5442.4  952.88
#Mann= 3 ,-1 , 0
  4676.4     .12       0  5006.4     .07       0  5014.7     .12       0
Bank Sta=5006.4,5014.7
XS Rating Curve= 0 ,0
Exp/Cntr=0.3,0.1

Type RM Length L Ch R = 1 ,33289   ,515,515,515
BEGIN DESCRIPTION:
Rush Creek 68.0
END DESCRIPTION:
XS GIS Cut Line= 3
      2260365.72      7210206.17      2260125.66      7209947.72
      2259780.16      7209629.43
#Sta/Elev= 30
  4649.5  962.97  4662.8  960.96  4842.6  953.96  4849.4  948.93  4856.8  949.02
  4877.8  943.63  4885.1   947.1  4891.9  940.91  4899.3  941.13  4913.5  936.29
  4920.3  938.34  4934.5  936.01  4941.8   943.4  4948.6  939.45    4956  945.31
  4962.8  940.09  4970.1  947.53    4977  938.09  4984.3  935.07  4991.1  929.08
  5001.2  926.21  5002.4  925.71  5009.6  926.21  5019.6  931.03  5047.9  933.75
  5104.6  948.87  5224.8  948.05  5316.7  951.33  5408.6  957.09    5472  963.66
#Mann= 4 ,-1 , 0
  4649.5     .05       0  4662.8     .12       0  5001.2     .07       0
  5009.6     .12       0
Bank Sta=5001.2,5009.6
XS Rating Curve= 0 ,0
Exp/Cntr=0.3,0.1

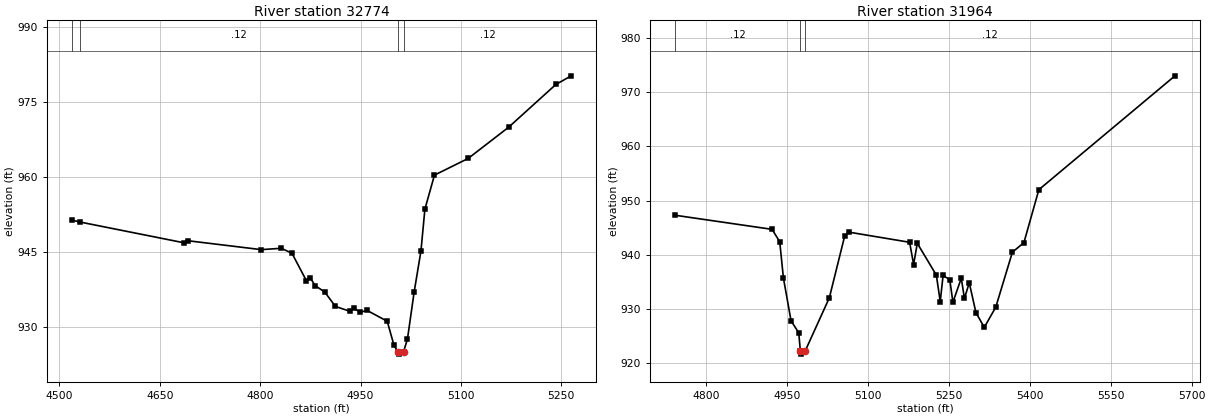
Type RM Length L Ch R = 1 ,32774   ,810,810,810
BEGIN DESCRIPTION:
Rush Creek 67.0
END DESCRIPTION:
XS GIS Cut Line= 3
      2260338.79      7209836.85      2260124.49      7209457.17
      2259816.34      7209416.49
#Sta/Elev= 30
  4518.1   951.4  4530.2     951  4685.8  946.84  4691.5  947.25  4801.6  945.46
  4831.6  945.73  4847.5  944.74  4869.2  939.22  4874.9  939.85  4881.9  938.28
  4896.6  936.97  4912.5  934.09  4934.2  933.12  4939.9  933.73  4949.6  932.93
  4959.6  933.31  4989.9  931.13    5000  926.32  5005.8  925.05    5007  924.55
  5014.3  925.05  5020.1  927.54  5030.2  937.03  5040.3  945.18  5046.2  953.56
  5060.5  960.37  5110.9  963.71  5171.4  969.96    5242  978.52  5264.9  980.24
#Mann= 4 ,-1 , 0
  4518.1     .05       0  4530.2     .12       0  5005.8     .07       0
  5014.3     .12       0
Bank Sta=5005.8,5014.3
XS Rating Curve= 0 ,0
Exp/Cntr=0.3,0.1

Type RM Length L Ch R = 1 ,31964   ,515,515,515
BEGIN DESCRIPTION:
Rush Creek 65.0
END DESCRIPTION:
XS GIS Cut Line= 4
      2260287.46      7209713.67       2260205.9      7209584.82
      2260440.51      7209327.21       2260218.8      7208965.01
#Sta/Elev= 30
  4743.5  947.29  4922.8  944.69    4937   942.4  4943.8  935.72    4958  927.77
  4972.2  925.59  4975.3  922.13  4976.6  921.63  4983.8  922.13  5028.9  932.04
  5057.3  943.45  5064.7  944.18  5177.6   942.3    5185  938.19  5191.8  942.11
  5227.1  936.23  5234.3  931.35  5239.6  936.17    5252  935.37  5257.8  931.22
  5273.3  935.66  5279.1  931.94  5288.1  934.81  5300.4  929.31  5315.9  926.57
  5337.2  930.32    5368  940.48  5389.3  942.23    5417  952.02  5669.1  973.06
#Mann= 3 ,-1 , 0
  4743.5     .12       0  4975.3     .07       0  4983.8     .12       0
Bank Sta=4975.3,4983.8
XS Rating Curve= 0 ,0
Exp/Cntr=0.3,0.1