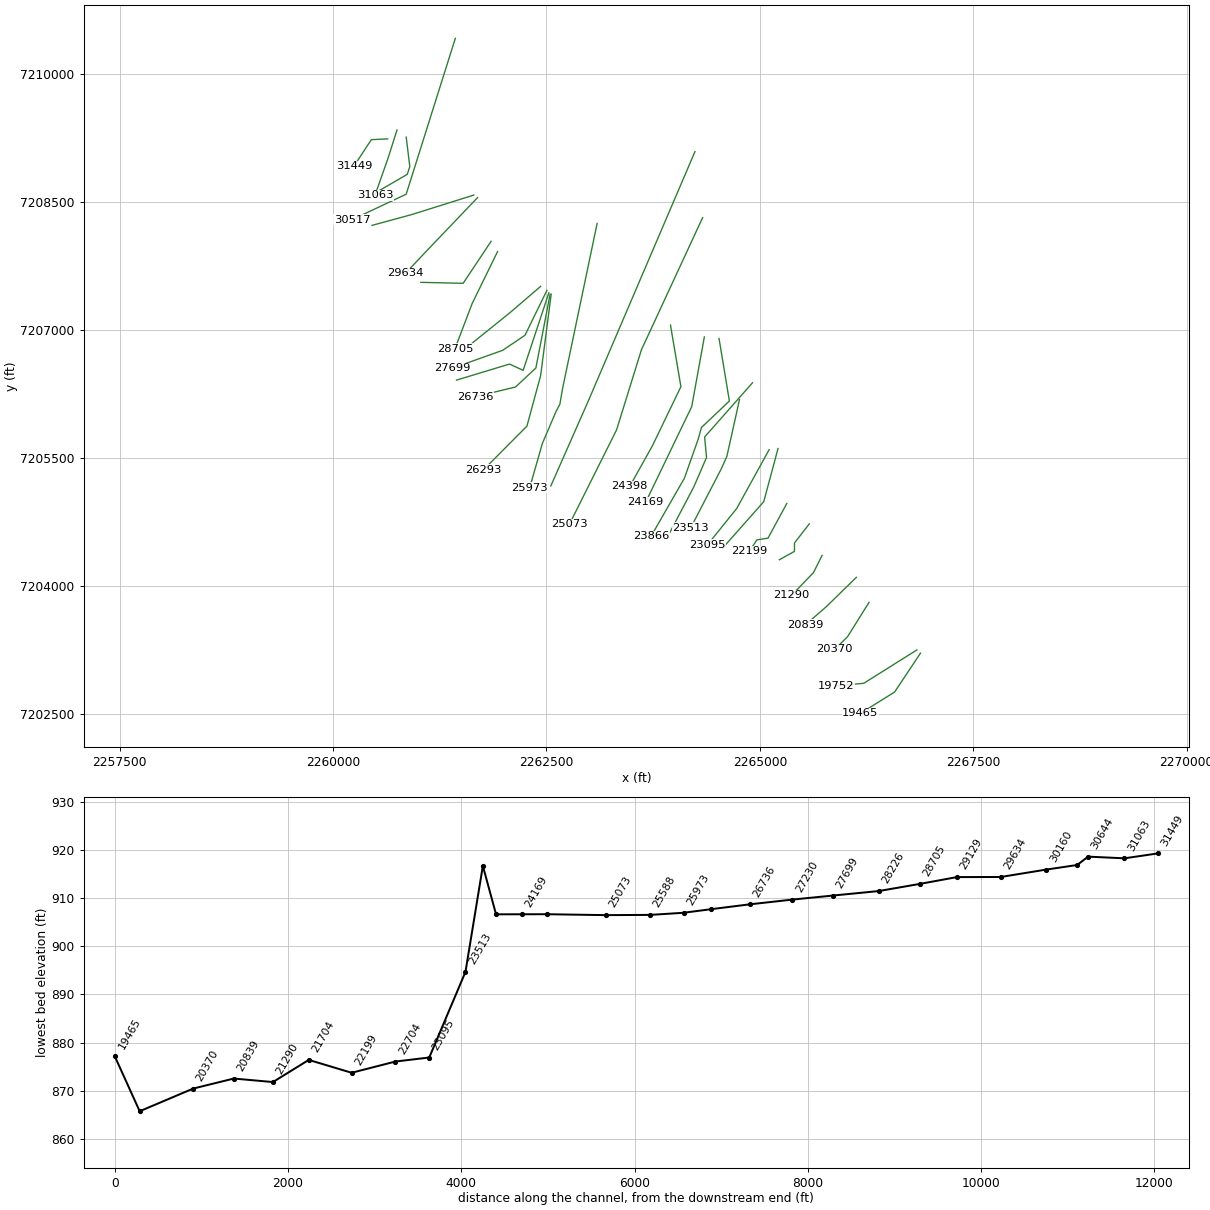
HEC-RAS study Rush Creek.prj: Rush Creek Base Level Engineering

--- Rush Creek.g01 (geometry) --- (continued)

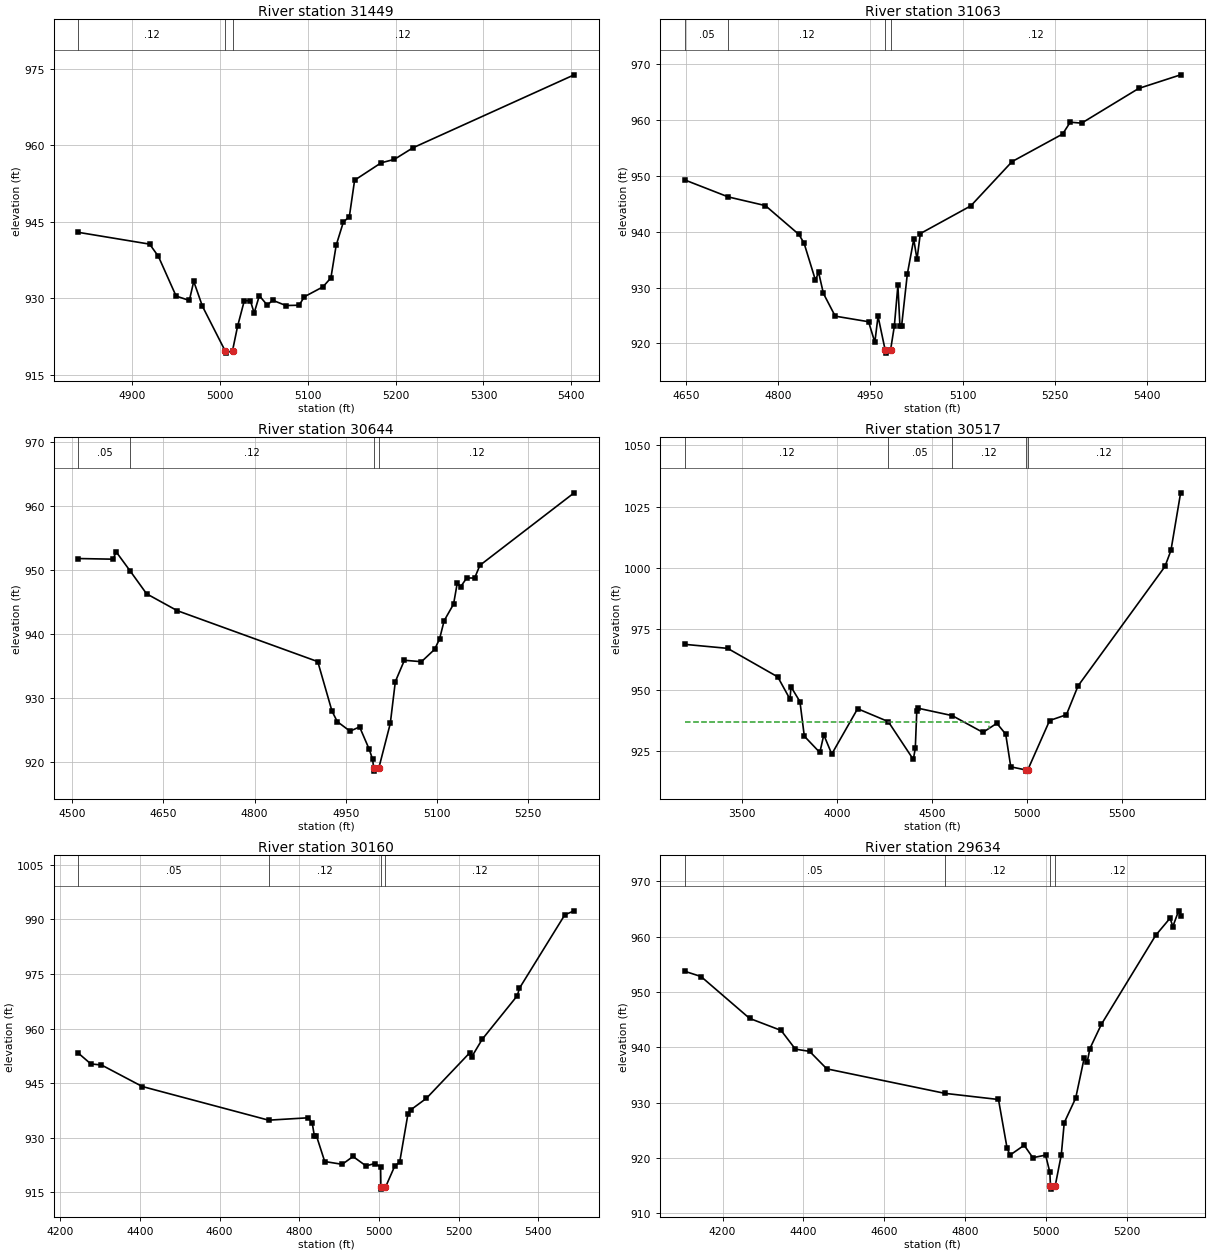
Type RM Length L Ch R = 1 ,31449   ,386,386,386
BEGIN DESCRIPTION:
Rush Creek 64.0
END DESCRIPTION:
XS GIS Cut Line= 3
      2260640.15      7209240.72      2260448.64      7209232.05
      2260243.97      7208920.35
#Sta/Elev= 30
  4838.7  942.93  4919.9  940.62  4929.9  938.21    4950  930.46  4965.1  929.59
  4970.1  933.33    4980  928.46  5005.7  919.78    5007  919.28  5014.3  919.78
    5020  924.51  5027.7  929.55  5034.6  929.55  5038.9  927.14  5044.8  930.52
  5053.9  928.67  5059.9  929.64    5075   928.6  5090.1  928.66  5096.1  930.32
  5117.2  932.25  5126.3  934.01  5132.3  940.39  5140.5  944.95  5147.3     946
  5153.3  953.14  5183.5  956.54  5198.6  957.22  5219.7  959.48  5403.3  973.77
#Mann= 3 ,-1 , 0
  4838.7     .12       0  5005.7     .07       0  5014.3     .12       0
Bank Sta=5005.7,5014.3
XS Rating Curve= 0 ,0
Exp/Cntr=0.3,0.1

Type RM Length L Ch R = 1 ,31063   ,419,419,419
BEGIN DESCRIPTION:
Rush Creek 63.0
END DESCRIPTION:
XS GIS Cut Line= 3
      2260749.25      7209344.88       2260642.3      7209008.71
      2260491.29      7208580.64
#Sta/Elev= 30
  4648.1  949.26  4718.9  946.22  4779.2  944.67  4833.6  939.52  4842.1  937.96
  4860.6  931.34  4865.8  932.72  4873.6  928.95  4892.8  924.88  4947.1  923.88
  4957.3  920.21  4962.5  924.86  4974.2  918.76  4975.5  918.26  4982.8  918.76
    4989  923.08  4994.8  930.38  4998.1  923.17  5000.9  923.17  5010.1  932.38
  5020.6  938.64  5025.9  935.05  5031.3  939.66  5113.4  944.62  5180.6  952.55
  5262.8  957.48  5275.2   959.6  5293.7  959.43  5386.5  965.64  5454.8  968.08
#Mann= 4 ,-1 , 0
  4648.1     .05       0  4718.9     .12       0  4974.2     .07       0
  4982.8     .12       0
Bank Sta=4974.2,4982.8
XS Rating Curve= 0 ,0
Exp/Cntr=0.3,0.1

Type RM Length L Ch R = 1 ,30644   ,127,127,127
BEGIN DESCRIPTION:
Rush Creek 62.0
END DESCRIPTION:
XS GIS Cut Line= 4
      2260857.06      7209261.46        2260899.      7208916.49
      2260869.89      7208825.72      2260547.45      7208638.47
#Sta/Elev= 30
  4509.9  951.77  4567.1  951.67  4572.1  952.82  4595.4   949.8  4622.2  946.27
  4672.6  943.64  4903.8  935.69  4927.2  927.97  4935.9  926.33  4956.9  924.84
  4972.6  925.51  4988.3  922.05  4994.1  920.43  4995.7  919.11    4997  918.61
  5004.3  919.11  5023.1  926.04  5031.4  932.57  5046.3   935.9  5074.4  935.68
  5095.9  937.59  5104.1   939.2  5111.7  942.07  5127.2  944.66  5133.2  947.89
    5139  947.39  5148.9  948.74  5161.9  948.73  5170.5  950.71  5325.6  962.02
#Mann= 4 ,-1 , 0
  4509.9     .05       0  4595.4     .12       0  4995.7     .07       0
  5004.3     .12       0
Bank Sta=4995.7,5004.3
XS Rating Curve= 0 ,0
Exp/Cntr=0.3,0.1

Type RM Length L Ch R = 1 ,30517   ,357,357,357
BEGIN DESCRIPTION:
Rush Creek 61.5
END DESCRIPTION:
XS GIS Cut Line= 3
      2261432.43      7210418.88      2260856.84      7208592.87
       2260224.3      7208294.87
#Sta/Elev= 30
  3196.9   968.7  3422.8  967.06    3687  955.39  3751.4   946.3  3756.9  951.31
  3803.9  945.29  3826.9  931.17  3908.7  924.49  3929.7  931.69  3971.6  923.84
  4107.9  942.38  4269.4  937.12  4401.5  921.65    4412  926.16  4419.8  941.56
  4425.1  942.61  4606.5  939.57  4768.5  932.71  4841.9  936.42  4888.6  931.99
  4915.3  918.63  4993.5  917.37  4995.1  916.87  5004.9  917.37  5120.1  937.56
  5208.6  939.92  5270.1  951.73  5728.1 1000.53  5759.6 1007.09  5810.7 1030.65
#Mann= 5 ,-1 , 0
  3196.9     .12       0  4269.4     .05       0  4606.5     .12       0
  4993.5     .07       0  5004.9     .12       0
#XS Ineff= 2 , 0
       0  4799.9  937.14               0
Permanent Ineff=
       F       F
Bank Sta=4993.5,5004.9
XS Rating Curve= 0 ,0
Exp/Cntr=0.3,0.1

Type RM Length L Ch R = 1 ,30160   ,526,526,526
BEGIN DESCRIPTION:
Rush Creek 61.0
END DESCRIPTION:
XS GIS Cut Line= 3
      2261648.99      7208582.53      2260925.22      7208355.14
      2260456.43       7208227.5
#Sta/Elev= 30
  4245.3  953.25  4276.7  950.29  4303.4     950  4405.8  944.09  4722.9  934.85
  4821.8   935.5  4832.3  934.07  4837.6   930.6  4842.8  930.61  4863.7   923.5
  4907.6  922.73  4934.8  924.88  4967.2   922.3  4989.5  922.95    5004     922
  5004.7  916.42  5006.2  915.92  5016.1  916.42  5039.4  922.24  5051.9  923.35
  5072.6  936.54  5079.2  937.65  5118.9  940.84  5227.9  953.37    5233  952.29
  5259.1  957.07  5347.1  969.02  5352.4  971.06  5466.4  991.23  5489.8  992.32
#Mann= 4 ,-1 , 0
  4245.3     .05       0  4722.9     .12       0  5004.7     .07       0
  5016.1     .12       0
Bank Sta=5004.7,5016.1
XS Rating Curve= 0 ,0
Exp/Cntr=0.3,0.1

Type RM Length L Ch R = 1 ,29634   ,505,505,505
BEGIN DESCRIPTION:
Rush Creek 60.0
END DESCRIPTION:
XS GIS Cut Line= 3
      2261692.86      7208552.66        2261079.        7207910.
      2260847.39      7207664.69
#Sta/Elev= 30
  4106.5  953.75  4146.5  952.81  4266.7  945.24  4344.7  943.06  4379.9  939.68
  4415.1  939.28  4457.6  936.12  4749.7  931.69  4882.2  930.58  4903.2  921.89
  4910.5  920.52  4945.7  922.31  4967.1  920.06  4998.7  920.53  5009.2  917.43
  5010.8  914.88  5012.3  914.38  5022.2  914.88  5037.5  920.57  5044.8  926.39
  5073.1  930.83  5094.1  938.06  5101.4  937.28  5108.3  939.79  5136.6  944.16
  5270.9  960.25  5306.5  963.35  5313.4  961.84  5327.6  964.68  5332.6  963.75
#Mann= 4 ,-1 , 0
  4106.5     .05       0  4749.7     .12       0  5010.8     .07       0
  5022.2     .12       0
Bank Sta=5010.8,5022.2
XS Rating Curve= 0 ,0
Exp/Cntr=0.3,0.1

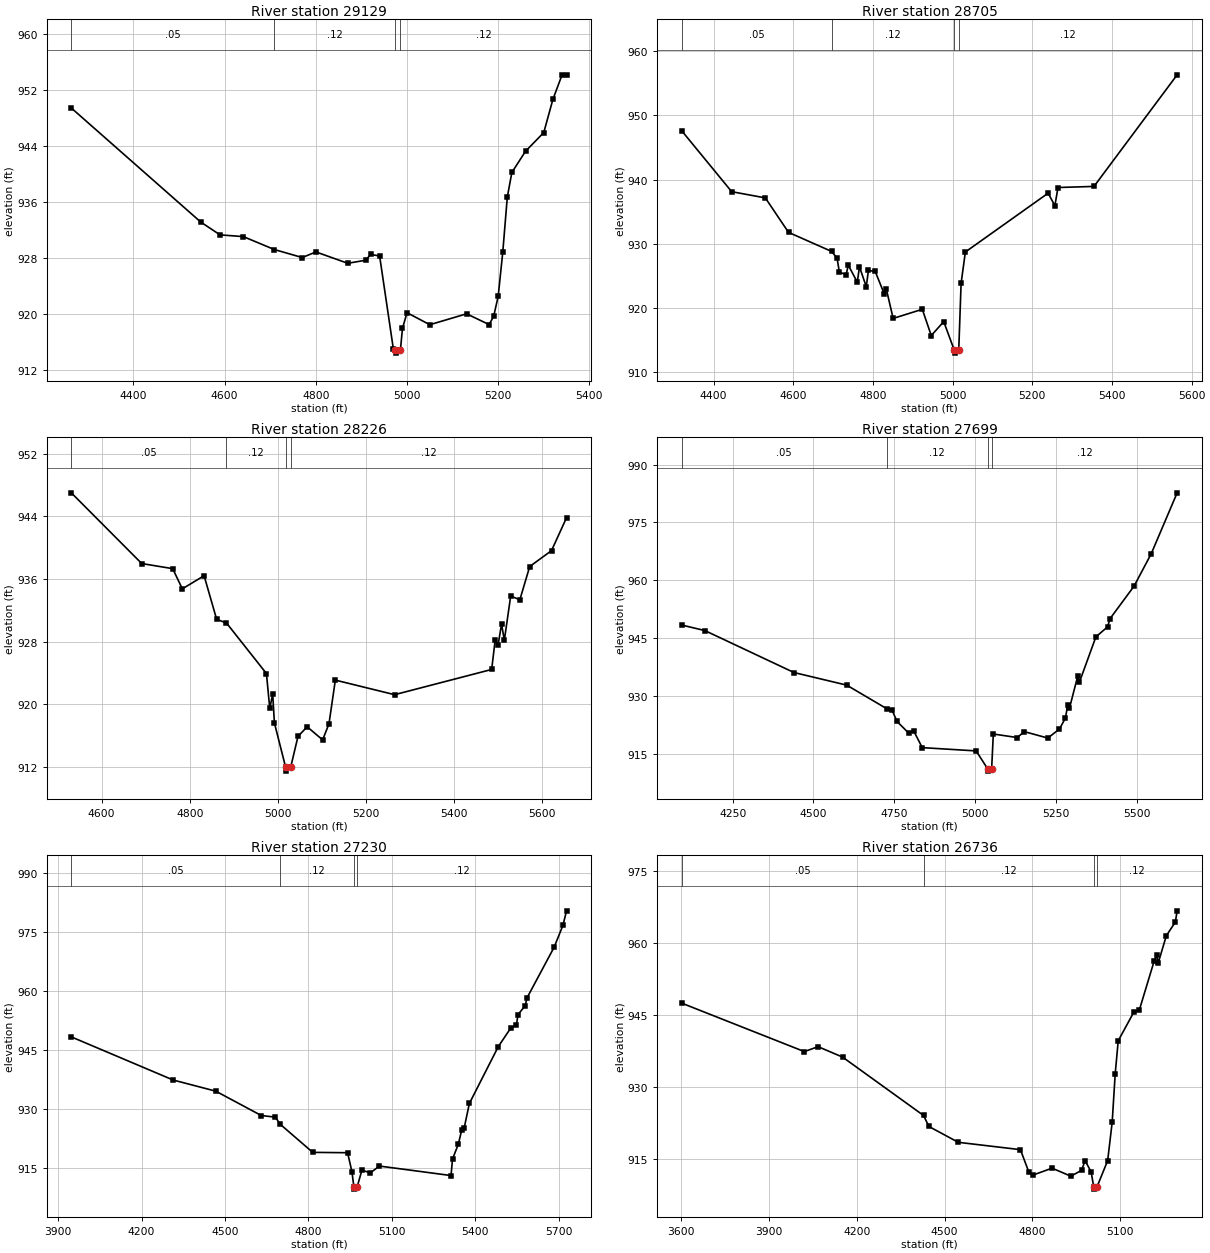
Type RM Length L Ch R = 1 ,29129   ,424,424,424
BEGIN DESCRIPTION:
Rush Creek 59.0
END DESCRIPTION:
XS GIS Cut Line= 3
      2261851.77      7208041.12      2261524.17      7207548.93
      2261029.04        7207560.
#Sta/Elev= 30
  4263.6  949.39  4547.8  933.08  4589.9  931.26    4641  931.01  4709.2  929.16
  4770.2  928.02  4800.3  928.82    4870   927.2    4910  927.64    4920  928.47
    4940  928.24    4970  915.01  4974.3  914.86  4975.9  914.36  4985.7  914.86
  4990.1  917.89  5000.1  920.14  5050.1  918.42  5130.8  919.98  5180.1  918.44
  5190.1   919.6  5200.1  922.48  5210.1  928.75  5220.1  936.66  5230.1  940.18
  5260.1  943.21  5300.1  945.88  5320.1  950.62  5340.1   954.1  5350.1  954.13
#Mann= 4 ,-1 , 0
  4263.6     .05       0  4709.2     .12       0  4974.3     .07       0
  4985.7     .12       0
Bank Sta=4974.3,4985.7
XS Rating Curve= 0 ,0
Exp/Cntr=0.3,0.1

Type RM Length L Ch R = 1 ,28705   ,479,479,479
BEGIN DESCRIPTION:
Rush Creek 58.0
END DESCRIPTION:
XS GIS Cut Line= 3
      2261927.25      7207920.56        2261629.        7207310.
      2261428.54      7206783.16
#Sta/Elev= 30
  4320.4  947.58  4445.4  938.12  4529.9  937.15  4588.1  931.78  4696.2  928.81
    4710  927.76  4715.6  925.62  4732.6  925.15  4738.1  926.67  4760.7  924.02
  4766.2  926.41  4783.2  923.32  4788.7  925.84  4805.7  925.69  4828.2  922.22
  4833.8  922.89  4850.7  918.37  4923.9  919.79  4946.4   915.7  4977.7  917.87
  5003.9  913.46  5005.5  912.96  5015.4  913.46  5021.3  923.84    5032  928.72
  5239.8  937.89  5256.7  935.92  5264.5  938.77  5354.9  938.94  5563.6  956.33
#Mann= 4 ,-1 , 0
  4320.4     .05       0  4696.2     .12       0  5003.9     .07       0
  5015.4     .12       0
Bank Sta=5003.9,5015.4
XS Rating Curve= 0 ,0
Exp/Cntr=0.3,0.1

Type RM Length L Ch R = 1 ,28226   ,527,527,527
BEGIN DESCRIPTION:
Rush Creek 57.0
END DESCRIPTION:
XS GIS Cut Line= 3
      2262431.54      7207512.55        2262079.        7207210.
      2261564.92      7206795.57
#Sta/Elev= 30
    4531  946.99    4691  937.96  4761.3  937.31  4783.2  934.73  4832.6  936.41
  4861.1  930.84  4883.5  930.37  4974.2  923.92  4981.8  919.46  4988.4  921.32
  4992.3  917.62  5017.8  911.96  5019.4  911.46  5029.3  911.96  5045.9   915.9
  5066.7  917.12  5101.9  915.45  5116.3  917.51  5130.7  923.08  5265.3  921.22
  5485.8  924.44  5493.8  928.23  5500.2  927.51  5508.2  930.22  5514.6  928.18
    5529  933.81  5549.8  933.34  5572.2  937.58  5621.7  939.61  5655.9  943.82
#Mann= 4 ,-1 , 0
    4531     .05       0  4883.5     .12       0  5017.8     .07       0
  5029.3     .12       0
Bank Sta=5017.8,5029.3
XS Rating Curve= 0 ,0
Exp/Cntr=0.3,0.1

Type RM Length L Ch R = 1 ,27699   ,469,469,469
BEGIN DESCRIPTION:
Rush Creek 56.0
END DESCRIPTION:
XS GIS Cut Line= 4
      2262505.96      7207466.74      2262248.35      7206939.43
      2261985.49      7206763.04      2261393.41      7206551.98
#Sta/Elev= 30
  4092.9  948.38  4163.7  946.97  4439.5  936.09  4602.7  932.82  4726.4  926.72
  4743.4  926.26  4758.4  923.41  4794.4   920.4  4809.4  921.05  4836.4  916.62
  5003.2  915.77  5039.5  911.03  5041.1  910.53    5051  911.03  5056.3  920.15
  5130.6  919.23  5151.8  920.78  5224.8   919.1  5260.9  921.44  5279.2  924.28
  5286.4   927.6  5291.7   926.8  5317.2   935.1  5322.6  933.58  5373.6  945.33
  5409.7  947.92  5417.3  950.04  5491.5  958.46  5544.7  966.86  5624.9  982.66
#Mann= 4 ,-1 , 0
  4092.9     .05       0  4726.4     .12       0  5039.5     .07       0
    5051     .12       0
Bank Sta=5039.5,5051
XS Rating Curve= 0 ,0
Exp/Cntr=0.3,0.1

Type RM Length L Ch R = 1 ,27230   ,494,494,494
BEGIN DESCRIPTION:
Rush Creek 55.0
END DESCRIPTION:
XS GIS Cut Line= 4
      2262527.99      7207436.58      2262227.18       7206528.9
      2262067.54      7206602.76      2261446.37      7206414.53
#Sta/Elev= 30
  3947.3  948.37  4313.7  937.41  4466.9  934.58  4630.6  928.39  4681.1  927.98
    4699  926.15  4815.6  919.03    4941  918.94  4956.6  914.11  4963.7  910.19
  4965.3  909.69  4975.2  910.19  4992.4  914.51  5022.7  913.83  5055.6  915.55
    5313  913.14  5318.3  917.33  5339.1  921.07  5351.2  924.66    5360  925.12
  5378.9  931.45  5482.8  945.88  5527.2  950.56  5548.1  951.39  5553.9  954.04
  5579.5  956.28  5586.8  958.35    5684  971.18  5715.3  976.69  5728.5   980.4
#Mann= 4 ,-1 , 0
  3947.3     .05       0    4699     .12       0  4963.7     .07       0
  4975.2     .12       0
Bank Sta=4963.7,4975.2
XS Rating Curve= 0 ,0
Exp/Cntr=0.3,0.1

Type RM Length L Ch R = 1 ,26736   ,443,443,443
BEGIN DESCRIPTION:
Rush Creek 54.1
END DESCRIPTION:
XS GIS Cut Line= 4
      2262542.67      7207419.43      2262376.38      7206556.45
      2262137.17      7206333.46      2261663.07      7206219.44
#Sta/Elev= 30
  3601.9  947.46  4020.8  937.37  4067.6   938.4  4151.3  936.23  4428.2  924.06
  4446.6  921.76    4547  918.46  4759.5  916.93  4787.8  912.34    4802  911.62
  4867.6  913.07    4932   911.4  4968.8  912.63  4980.7  914.65  5001.3  912.28
  5010.1   909.2  5011.7   908.7  5021.6   909.2  5057.8  914.65  5073.3  922.66
  5083.6  932.74  5093.9  939.63  5146.9  945.56  5165.9     946  5217.3  956.35
  5225.6  957.46  5230.8  955.87  5258.4  961.52  5289.3  964.39  5295.4  966.72
#Mann= 4 ,-1 , 0
  3601.9     .05       0  4428.2     .12       0  5010.1     .07       0
  5021.6     .12       0
Bank Sta=5010.1,5021.6
XS Rating Curve= 0 ,0
Exp/Cntr=0.3,0.1

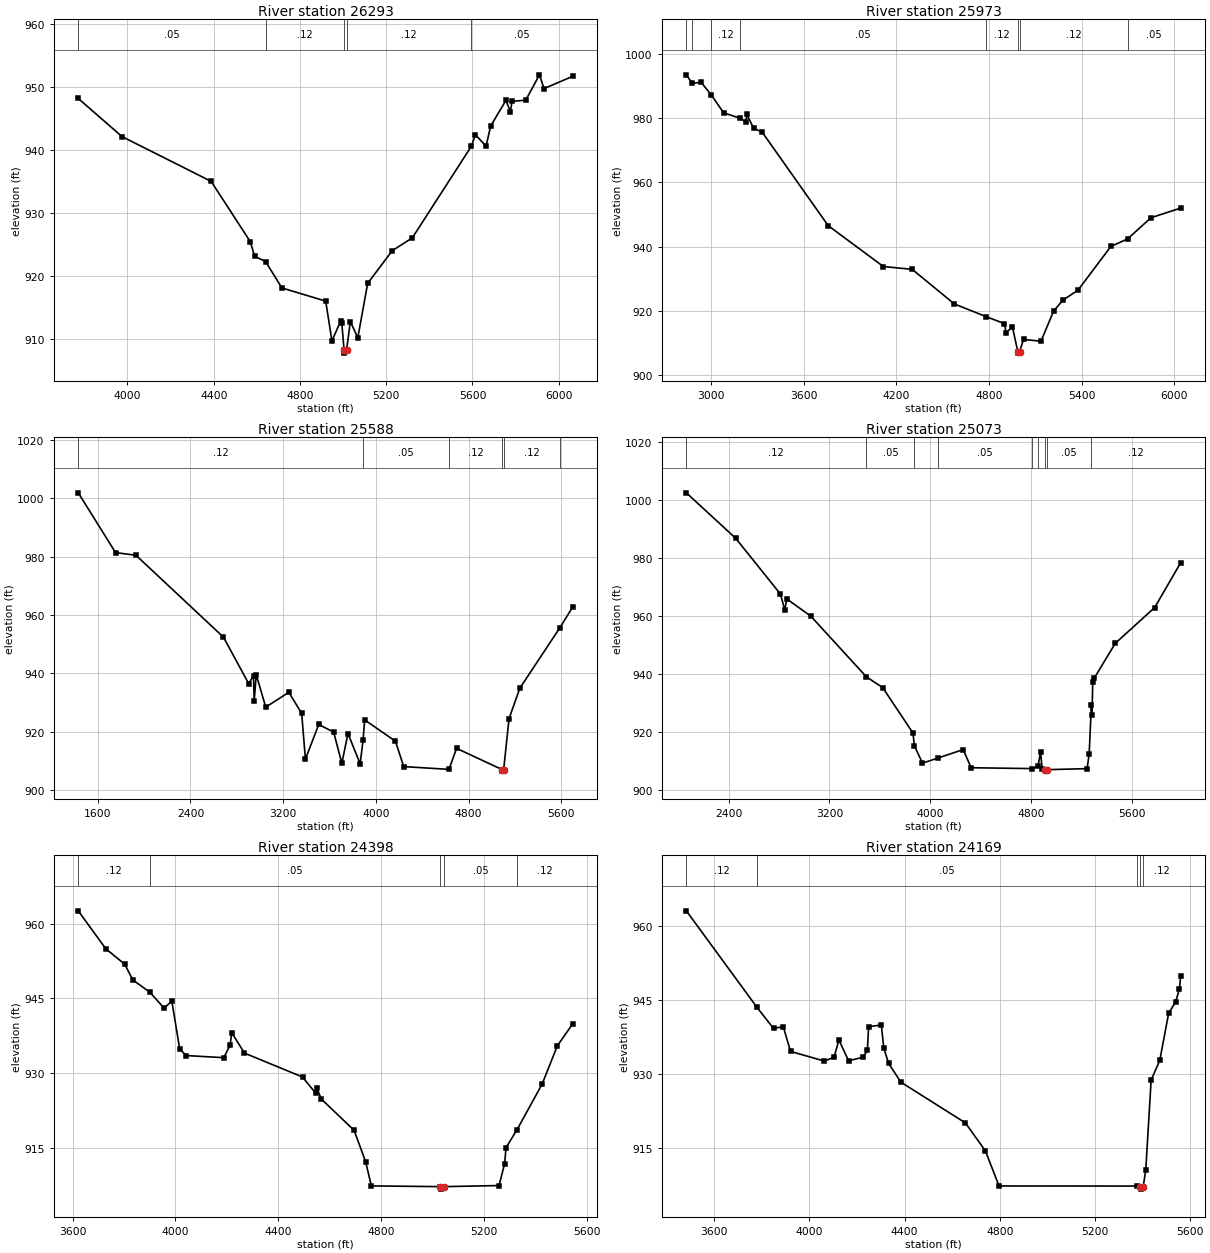
Type RM Length L Ch R = 1 ,26293   ,320,320,320
BEGIN DESCRIPTION:
Rush Creek 54.0
END DESCRIPTION:
XS GIS Cut Line= 4
      2262555.55      7207421.07      2262431.65      7206466.05
      2262271.37      7205875.59      2261765.18      7205366.17
#Sta/Elev= 30
  3771.7   948.2  3974.5  942.14  4387.9  935.02  4569.4  925.44  4589.6  923.11
  4640.9  922.25    4716  918.07  4919.5  915.97  4948.2  909.65  4988.7  912.78
  4993.9  912.52  5004.7   908.2  5006.2   907.7  5016.2   908.2  5033.7  912.71
  5068.4  910.15    5114  918.79    5228  923.99  5321.3  926.04  5594.5  940.57
  5613.8  942.43  5663.3  940.62  5684.5  943.81  5755.2  947.89  5776.5  946.09
  5783.5  947.75  5847.2  947.92  5910.8  951.96    5932  949.77  6064.7  951.72
#Mann= 5 ,-1 , 0
  3771.7     .05       0  4640.9     .12       0  5004.7     .07       0
  5016.2     .12       0  5594.5     .05       0
Bank Sta=5004.7,5016.2
XS Rating Curve= 0 ,0
Exp/Cntr=0.3,0.1

Type RM Length L Ch R = 1 ,25973   ,385,385,385
BEGIN DESCRIPTION:
Rush Creek 53.0
END DESCRIPTION:
XS GIS Cut Line= 6
       2263093.8      7208250.12      2262688.78      7206315.49
      2262657.65      7206132.85      2262613.86      7206050.16
      2262452.32       7205673.1      2262304.14      7205154.47
#Sta/Elev= 30
    2838  993.41  2875.4  990.84  2934.9  991.03    3001  987.09  3079.6  981.62
    3186  979.93  3224.3  978.66  3229.5  981.15  3274.3  976.81  3329.3  975.63
  3757.6  946.56  4115.2  933.86  4302.7  932.97    4575  922.24    4784  918.24
  4899.4  916.14  4911.4  913.33    4952  915.07  4986.8  907.45  4988.4  906.95
  4998.3  907.45  5024.5  911.22  5137.1  910.64  5219.4  920.03  5278.5  923.38
  5377.1  926.51    5590  940.08  5698.9  942.44    5850  949.01    6043  952.01
#Mann= 8 ,-1 , 0
    2838     .12       0  2875.4     .05       0    3001     .12       0
    3186     .05       0    4784     .12       0  4986.8     .07       0
  4998.3     .12       0  5698.9     .05       0
Bank Sta=4986.8,4998.3
XS Rating Curve= 0 ,0
Exp/Cntr=0.3,0.1

Type RM Length L Ch R = 1 ,25588   ,515,515,515
BEGIN DESCRIPTION:
Rush Creek 52.0
END DESCRIPTION:
XS GIS Cut Line= 3
      2264240.15      7209091.85      2262990.97       7206171.3
      2262551.51      7205175.11
#Sta/Elev= 30
  1431.7 1001.81  1753.5  981.34  1929.5  980.43  2684.5  952.38  2902.1  936.48
  2943.9  939.15  2949.3  930.37  2967.3  939.56  3049.1  928.43  3248.7   933.5
  3359.4  926.26  3391.5  910.59  3506.3  922.48  3635.2  919.87  3705.9  909.17
  3758.6  919.38  3863.8  909.04  3888.8  917.03  3902.6  924.05  4168.6  916.75
  4239.4  908.06  4630.6  907.11  4695.7  914.31  5090.3  907.01  5091.9  906.51
  5101.9  907.01  5148.2  924.45  5241.5   934.9  5587.6  955.65    5697   962.7
#Mann= 6 ,-1 , 0
  1431.7     .12       0  3888.8     .05       0  4630.6     .12       0
  5090.3     .07       0  5101.9     .12       0  5587.6     .05       0
#XS Ineff= 2 , 0
       0  3902.6  924.05               0
Permanent Ineff=
       F       F
Bank Sta=5090.3,5101.9
XS Rating Curve= 0 ,0
Exp/Cntr=0.3,0.1

Type RM Length L Ch R = 1 ,25073   ,675,675,675
BEGIN DESCRIPTION:
Rush Creek 51.0
END DESCRIPTION:
XS GIS Cut Line= 4
      2264330.04      7208318.66      2263612.65      7206769.22
      2263321.77      7205831.76      2262769.05      7204725.12
#Sta/Elev= 30
  2063.4 1002.42  2455.9  986.73  2810.7  967.51  2844.6  962.16    2862  965.79
  3050.9  959.94    3493  938.99    3623  935.25  3863.3   919.6  3874.4  915.21
  3938.9  909.21  4063.3     911  4262.1  913.89    4325  907.63  4811.6  907.33
  4855.9  908.12  4876.7  913.01  4888.5  907.34  4915.7  906.96  4917.3  906.46
  4927.3  906.96  5246.2  907.32  5262.6  912.44  5280.1  929.23  5284.9  925.75
  5290.9  937.11  5301.7  938.42  5469.8  950.53  5782.7  962.86  5989.4  978.33
#Mann= 9 ,-1 , 0
  2063.4     .12       0    3493     .05       0  3874.4     .12       0
  4063.3     .05       0  4811.6     .12       0  4855.9     .05       0
  4915.7    .033       0  4927.3     .05       0  5280.1     .12       0
Bank Sta=4915.7,4927.3
XS Rating Curve= 0 ,0
Exp/Cntr=0.3,0.1

Type RM Length L Ch R = 1 ,24398   ,287,287,287
BEGIN DESCRIPTION:
Rush Creek 50.0
END DESCRIPTION:
XS GIS Cut Line= 4
      2263953.31      7207058.92      2264075.44      7206337.95
      2263742.69      7205647.32      2263476.65      7205170.81
#Sta/Elev= 30
  3621.7  962.63  3728.4  955.02  3802.7  951.88  3833.9  948.74    3901  946.23
  3955.5  943.06  3985.8  944.45  4016.2  934.85  4041.3  933.52  4187.9  933.09
  4212.9   935.7  4218.6  938.12  4268.4  934.01  4494.2   929.2  4544.8  925.99
  4550.4   926.9  4567.3  924.77    4695  918.47  4739.7  912.16    4762   907.3
  5030.7  907.15  5032.4  906.65  5043.2  907.15  5258.6  907.37  5280.3  911.74
    5286  915.01  5328.7   918.6  5426.5   927.8  5485.9  935.51    5545  939.87
#Mann= 5 ,-1 , 0
  3621.7     .12       0    3901     .05       0  5030.7    .033       0
  5043.2     .05       0  5328.7     .12       0
Bank Sta=5030.7,5043.2
XS Rating Curve= 0 ,0
Exp/Cntr=0.3,0.1

Type RM Length L Ch R = 1 ,24169   ,303,303,303
BEGIN DESCRIPTION:
Rush Creek 49.1
END DESCRIPTION:
XS GIS Cut Line= 3
      2264350.18      7206920.64      2264202.09      7206104.08
      2263661.28      7204980.88
#Sta/Elev= 30
    3483  963.06  3779.9  943.48  3849.2  939.22  3890.2  939.57  3920.7  934.56
    4063   932.6  4103.6   933.4  4123.9  936.87  4164.6  932.67  4225.6  933.38
  4243.5  934.77  4248.6  939.58    4302  939.91  4312.4  935.24  4332.8  932.12
    4384  928.33  4655.1  920.07  4739.2   914.4  4796.4  907.28  5374.9  907.26
  5389.5  907.14  5391.2  906.64    5402  907.14  5412.8  910.56  5435.4  928.76
  5471.7  932.76  5508.8  942.28  5538.3  944.61  5554.1  947.19  5559.5  949.94
#Mann= 5 ,-1 , 0
    3483     .12       0  3779.9     .05       0  5374.9     .12       0
  5389.5    .033       0    5402     .12       0
Bank Sta=5389.5,5402
XS Rating Curve= 0 ,0
Exp/Cntr=0.3,0.1

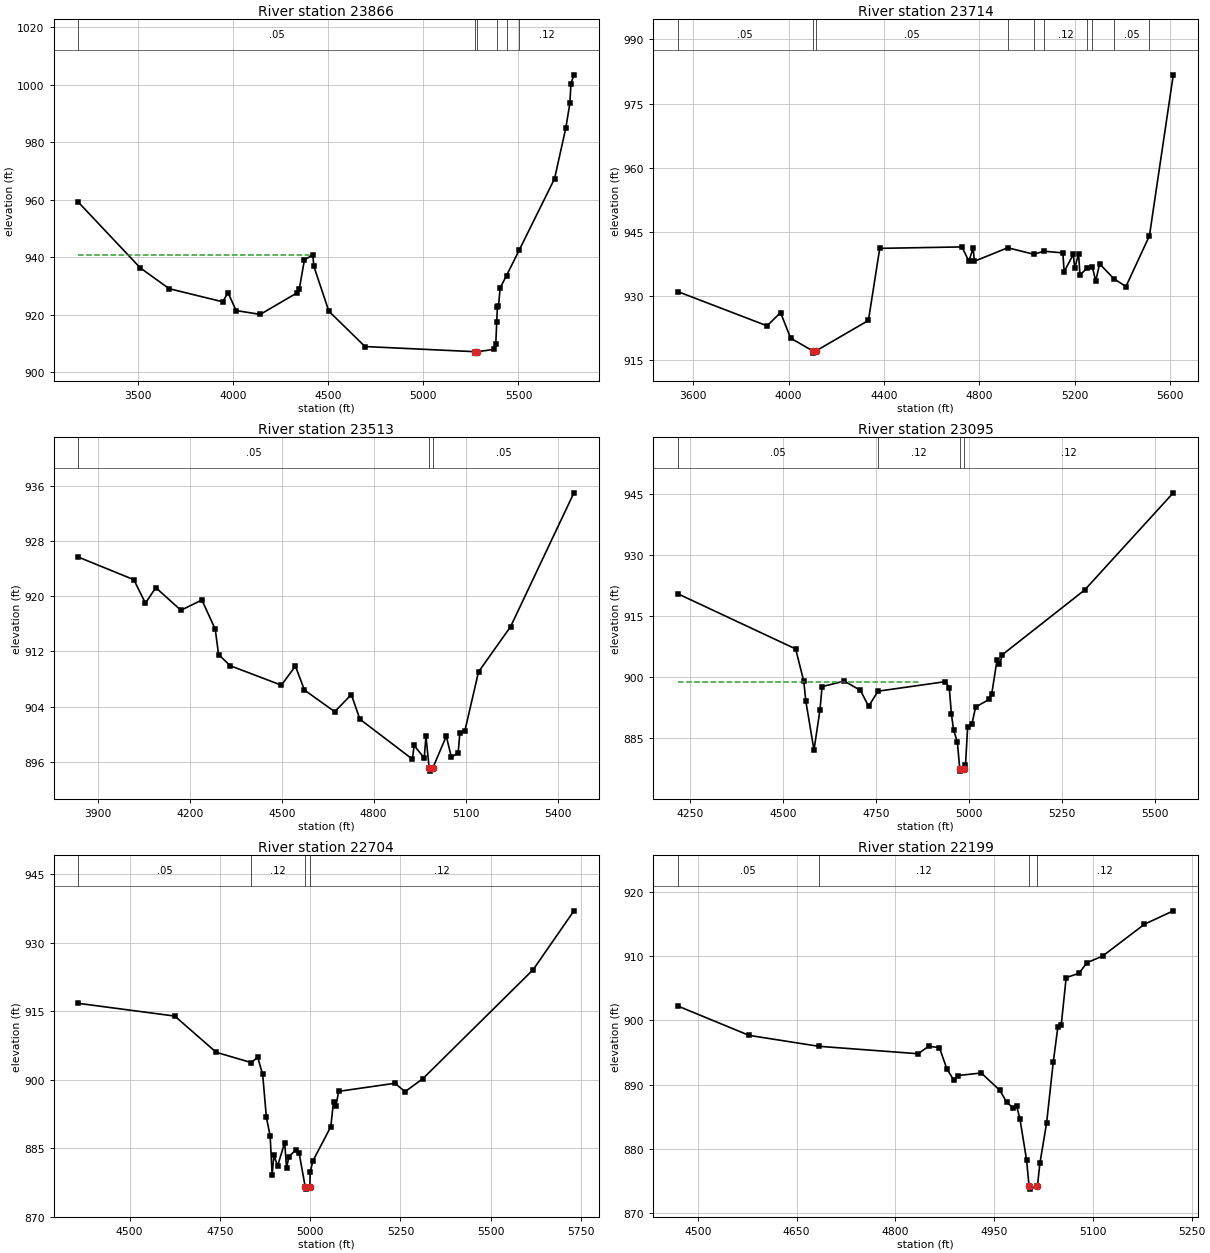
Type RM Length L Ch R = 1 ,23866   ,152,152,152
BEGIN DESCRIPTION:
Rush Creek 49.0
END DESCRIPTION:
XS GIS Cut Line= 6
       2264522.4       7206901.5      2264643.41      7206169.59
      2264315.72      7205859.26      2264278.83      7205725.44
      2264116.79      7205265.92      2263724.91      7204583.68
#Sta/Elev= 30
  3185.7  959.12  3511.6  936.26  3663.6  929.03  3944.6  924.48  3972.9  927.64
  4015.4  921.43  4142.5   920.1  4333.4  927.49  4347.6  928.92  4374.7  939.12
  4418.7  940.76  4423.9  936.87    4503  921.21  4693.1  908.92  5270.9  907.13
  5272.6  906.63  5283.4  907.13  5373.5  907.95  5380.8  909.89  5385.9  917.58
  5389.3  922.71    5395  923.02  5403.8  929.31  5437.2  933.59  5503.8  942.43
  5689.8  967.28  5748.7  984.84  5770.3  993.45    5776 1000.33  5791.7  1003.4
#Mann= 6 ,-1 , 0
  3185.7     .05       0  5270.9    .033       0  5283.4     .05       0
  5385.9     .12       0  5437.2     .05       0  5503.8     .12       0
#XS Ineff= 2 , 0
       0  4398.8  940.84               0
Permanent Ineff=
       F       F
Bank Sta=5270.9,5283.4
XS Rating Curve= 0 ,0
Exp/Cntr=0.3,0.1

Type RM Length L Ch R = 1 ,23714   ,201,201,201
BEGIN DESCRIPTION:
Rush Creek 48.1
END DESCRIPTION:
XS GIS Cut Line= 5
      2264914.21      7206383.39      2264353.13      7205747.83
      2264375.88      7205509.01      2264228.05      7205166.52
      2263941.25      7204620.14
#Sta/Elev= 30
  3534.9  931.07  3909.6  923.06  3966.3  926.15  4008.3   920.2  4101.6  917.18
  4103.4  916.68  4114.1  917.18  4334.6  924.32    4382  941.16  4726.6   941.5
  4755.6  938.17  4773.6  941.16  4779.1  938.15  4918.6   941.3  5027.5  939.79
    5070  940.49  5149.6  940.11  5155.2  935.71  5193.7  939.78  5199.3  936.46
  5215.7  939.89  5221.4  934.95  5251.3  936.53  5273.4  936.81  5287.5  933.55
  5303.9  937.54  5363.2  934.08  5414.2  932.24  5512.7   944.1  5612.7  981.71
#Mann= 10 ,-1 , 0
  3534.9     .05       0  4101.6     .07       0  4114.1     .05       0
  4918.6     .12       0  5027.5     .05       0    5070     .12       0
  5251.3     .05       0  5273.4     .12       0  5363.2     .05       0
  5512.7     .12       0
Bank Sta=4101.6,4114.1
XS Rating Curve= 0 ,0
Exp/Cntr=0.3,0.1

Type RM Length L Ch R = 1 ,23513   ,418,418,418
BEGIN DESCRIPTION:
Rush Creek 48.0
END DESCRIPTION:
XS GIS Cut Line= 4
      2264762.01      7206186.78      2264613.81      7205520.63
      2264546.38      7205371.38      2264191.83      7204686.53
#Sta/Elev= 30
  3836.1  925.64  4017.2  922.37  4055.1  918.97  4088.9  921.22  4170.9  917.94
  4239.4  919.43  4282.9   915.2  4293.8  911.54  4331.6  909.92  4498.7   907.1
  4544.5  909.86  4574.1  906.39  4672.9  903.26  4727.1  905.74  4754.9  902.18
  4926.4  896.39    4932  898.37    4965  896.55  4970.6  899.73  4980.9  895.16
  4982.6  894.66  4993.4  895.16    5037  899.72  5053.5  896.68  5075.7  897.31
  5081.3  900.21  5097.8  900.53  5142.1  909.02  5246.9  915.58  5453.5  934.94
#Mann= 3 ,-1 , 0
  3836.1     .05       0  4980.9    .033       0  4993.4     .05       0
Bank Sta=4980.9,4993.4
XS Rating Curve= 0 ,0
Exp/Cntr=0.3,0.1

Type RM Length L Ch R = 1 ,23095   ,391,391,391
BEGIN DESCRIPTION:
Rush Creek 47.0
END DESCRIPTION:
XS GIS Cut Line= 3
      2265108.85      7205599.14        2264729.        7204910.
      2264387.39      7204485.98
#Sta/Elev= 30
  4217.7  920.49  4534.6  906.92  4556.4  898.99  4562.1  894.01  4583.9  882.07
  4599.9  891.89  4605.6  897.65  4665.3  899.02  4708.8  896.72  4730.6  892.82
  4755.8  896.53  4936.9  898.88  4947.3  897.43    4953  890.97  4958.9     887
  4969.1     884  4975.5  877.39  4977.3  876.89    4988  877.39  4990.9   878.4
  4996.6  887.64  5007.8  888.36  5018.2  892.65    5055  894.55  5061.4   895.9
  5075.8  904.29  5082.2  903.13  5090.2  905.52  5310.9  921.39  5549.1  945.28
#Mann= 4 ,-1 , 0
  4217.7     .05       0  4755.8     .12       0  4975.5     .07       0
    4988     .12       0
#XS Ineff= 2 , 0
       0  4865.9  898.82               0
Permanent Ineff=
       F       F
Bank Sta=4975.5,4988
XS Rating Curve= 0 ,0
Exp/Cntr=0.3,0.1

Type RM Length L Ch R = 1 ,22704   ,505,505,505
BEGIN DESCRIPTION:
Rush Creek 46.0
END DESCRIPTION:
XS GIS Cut Line= 3
      2265213.22      7205613.02      2265046.11      7204990.46
      2264563.72      7204445.36
#Sta/Elev= 30
  4357.9  916.72    4625  913.93  4739.8     906  4837.2  903.74  4854.6  904.94
  4868.4  901.15  4878.7  891.77  4889.1  887.71  4894.6  879.24  4899.8   883.5
  4909.8   881.1  4929.4  886.24  4934.6   880.6  4940.8  883.15  4961.6  884.71
  4969.4  883.95  4986.2  876.55    4988  876.05    4999  876.55  5000.1  879.83
  5007.7  882.27  5057.1  889.71  5064.6  895.18  5071.3  894.18  5078.8  897.45
  5234.4  899.22  5262.9  897.39  5312.2  900.24  5617.4  924.08  5730.4  936.97
#Mann= 4 ,-1 , 0
  4357.9     .05       0  4837.2     .12       0  4986.2     .07       0
    4999     .12       0
Bank Sta=4986.2,4999
XS Rating Curve= 0 ,0
Exp/Cntr=0.3,0.1

Type RM Length L Ch R = 1 ,22199   ,495,495,495
BEGIN DESCRIPTION:
Rush Creek 45.0
END DESCRIPTION:
XS GIS Cut Line= 4
       2265316.2      7204969.39       2265095.8        7204563.
      2264965.32      7204542.74        2264879.      7204409.99
#Sta/Elev= 30
  4469.3  902.24  4577.7  897.66  4683.4  895.96  4834.4   894.8  4850.6  895.96
  4866.8  895.75  4878.1  892.45  4888.6   890.7  4894.3   891.4  4930.5   891.8
  4958.7  889.09  4968.8  887.27  4978.8  886.35  4983.9  886.73  4989.1  884.66
  4999.2  878.25  5002.9  874.22  5004.7  873.72  5015.7  874.22  5019.4  877.73
  5029.6  884.02  5039.7  893.48  5046.8  899.04  5051.9  899.35  5059.3  906.65
  5078.7  907.32  5090.8  908.97  5114.6     910  5178.2  914.96    5222  917.05
#Mann= 4 ,-1 , 0
  4469.3     .05       0  4683.4     .12       0  5002.9     .07       0
  5015.7     .12       0
Bank Sta=5002.9,5015.7
XS Rating Curve= 0 ,0
Exp/Cntr=0.3,0.1

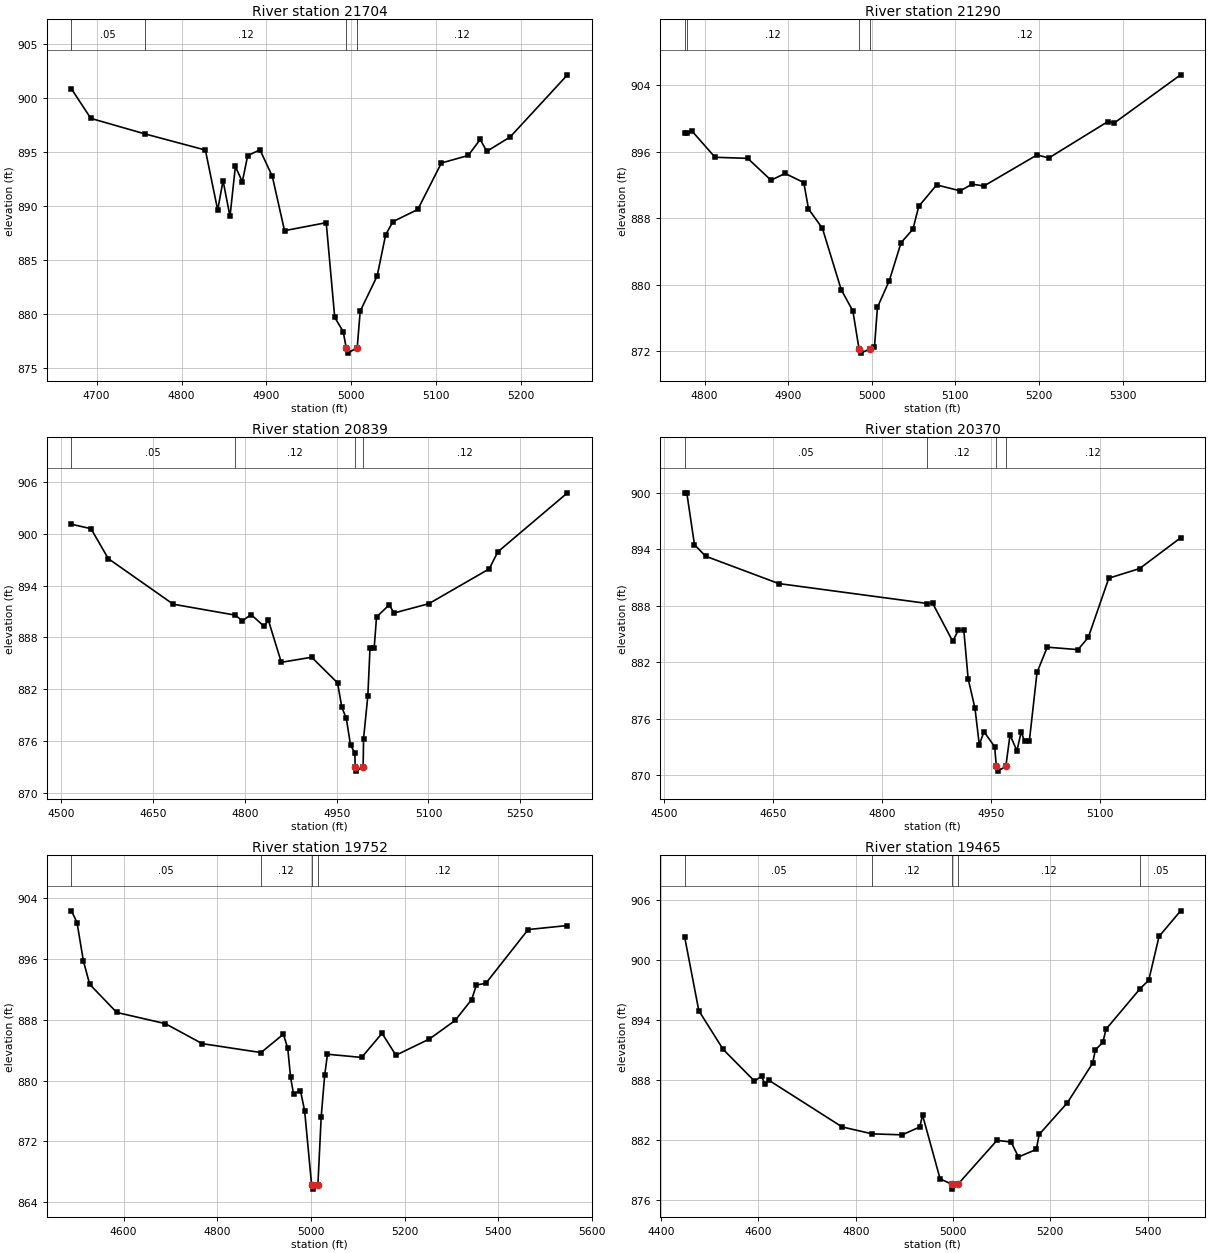
Type RM Length L Ch R = 1 ,21704   ,414,414,414
BEGIN DESCRIPTION:
Rush Creek 44.0
END DESCRIPTION:
XS GIS Cut Line= 4
       2265579.9      7204730.55      2265406.17      7204506.42
      2265405.64      7204407.72      2265229.04      7204310.02
#Sta/Elev= 30
  4670.4  900.84  4693.2  898.11  4757.1  896.67  4828.1  895.18  4842.6  889.63
  4848.9  892.35  4857.1  889.04  4863.4  893.66  4871.6  892.25  4877.9  894.66
  4892.4   895.2  4906.9  892.75  4921.3  887.72  4970.4  888.46  4980.4   879.7
  4990.4  878.38  4993.9  876.89  4995.7  876.39  5006.9  876.89  5010.4  880.27
  5030.4  883.53  5040.4  887.35    5049  888.56  5078.2  889.68    5106  893.98
  5137.7  894.68  5151.7  896.16  5159.5  895.06    5187  896.39  5254.5  902.14
#Mann= 4 ,-1 , 0
  4670.4     .05       0  4757.1     .12       0  4993.9     .07       0
  5006.9     .12       0
Bank Sta=4993.9,5006.9
XS Rating Curve= 0 ,0
Exp/Cntr=0.3,0.1

Type RM Length L Ch R = 1 ,21290   ,451,451,451
BEGIN DESCRIPTION:
Rush Creek 43.0
END DESCRIPTION:
XS GIS Cut Line= 3
      2265729.01      7204360.02        2265629.        7204160.
      2265373.01      7203893.17
#Sta/Elev= 30
  4776.1  898.29  4778.6  898.29  4784.5  898.53  4812.5  895.33  4851.6   895.2
  4879.5  892.57  4896.3  893.39  4918.7  892.29  4924.3  889.13    4941  886.78
  4963.4  879.43  4977.4  876.85  4984.8  872.29  4986.7  871.79  4997.8  872.29
  5003.2  872.48  5006.8   877.3    5021  880.51  5035.1  885.07  5049.3  886.69
  5056.2  889.43  5077.6  892.01  5105.9  891.29    5120   892.1  5134.2  891.88
  5197.7  895.61  5211.9  895.25  5282.6  899.63  5289.8  899.43  5369.5  905.24
#Mann= 4 ,-1 , 0
  4776.1     .05       0  4778.6     .12       0  4984.8     .07       0
  4997.8     .12       0
Bank Sta=4984.8,4997.8
XS Rating Curve= 0 ,0
Exp/Cntr=0.3,0.1

Type RM Length L Ch R = 1 ,20839   ,469,469,469
BEGIN DESCRIPTION:
Rush Creek 42.0
END DESCRIPTION:
XS GIS Cut Line= 3
      2266130.79      7204103.44        2265779.        7203760.
      2265537.73      7203550.76
#Sta/Elev= 30
  4516.3  901.11  4548.2   900.6  4576.5  897.13  4682.7  891.85  4783.8  890.59
  4795.8  889.93    4810  890.65  4831.1   889.3  4838.3  889.98  4859.4  885.12
    4909  885.71  4951.4  882.74  4958.4  879.89  4965.6  878.66  4972.6  875.53
  4979.7  874.64  4980.2  873.02  4982.1  872.52  4993.2  873.02  4993.9  876.29
  5000.9  881.25  5004.4  886.73  5011.2  886.73  5015.1  890.37  5035.9  891.78
  5043.6  890.83  5100.6  891.91  5199.3  895.94  5213.5  897.92  5327.3  904.75
#Mann= 4 ,-1 , 0
  4516.3     .05       0  4783.8     .12       0  4980.2     .07       0
  4993.2     .12       0
Bank Sta=4980.2,4993.2
XS Rating Curve= 0 ,0
Exp/Cntr=0.3,0.1

Type RM Length L Ch R = 1 ,20370   ,618,618,618
BEGIN DESCRIPTION:
Rush Creek 41.0
END DESCRIPTION:
XS GIS Cut Line= 3
      2266279.01      7203810.02        2266029.        7203410.
      2265878.97      7203259.97
#Sta/Elev= 30
  4527.8  900.01  4530.8  900.01  4541.4   894.5  4556.7  893.28  4657.5  890.37
  4862.7  888.25  4869.8  888.27  4897.5  884.23  4905.2  885.42  4912.8  885.39
  4918.7  880.27  4928.2  877.11  4934.1  873.25  4940.6  874.62  4955.3  873.04
  4957.6  870.94  4959.4  870.44  4970.7  870.94  4976.5  874.29    4986   872.6
  4991.9  874.61  4996.6  873.61  5003.1  873.61  5013.7  880.92  5027.8  883.61
  5070.2  883.35  5084.4  884.65  5112.7  890.94  5155.1  891.96  5211.7  895.23
#Mann= 4 ,-1 , 0
  4527.8     .05       0  4862.7     .12       0  4957.6     .07       0
  4970.7     .12       0
Bank Sta=4957.6,4970.7
XS Rating Curve= 0 ,0
Exp/Cntr=0.3,0.1

Type RM Length L Ch R = 1 ,19752   ,287,287,287
BEGIN DESCRIPTION:
Rush Creek 40.0
END DESCRIPTION:
XS GIS Cut Line= 3
      2266840.57      7203253.54      2266218.08      7202862.49
      2265895.31      7202833.53
#Sta/Elev= 30
  4488.7  902.29  4500.6  900.74  4514.2  895.69  4527.7  892.63  4585.4  888.94
  4689.1  887.47    4768  884.84  4893.5  883.67  4941.2  886.08  4950.6  884.22
  4956.5  880.46  4962.9  878.25  4977.7  878.65  4986.6  876.04  5001.6  866.23
  5003.5  865.73  5014.9  866.23    5022  875.25  5029.5  880.75  5035.4  883.45
  5108.4  883.03  5151.9   886.2  5181.5  883.32    5253  885.45    5308  887.89
  5343.4  890.64  5353.4  892.55  5373.5  892.76  5463.9  899.83  5547.9  900.36
#Mann= 4 ,-1 , 0
  4488.7     .05       0  4893.5     .12       0  5001.6     .07       0
  5014.9     .12       0
Bank Sta=5001.6,5014.9
XS Rating Curve= 0 ,0
Exp/Cntr=0.3,0.1

Type RM Length L Ch R = 1 ,19465   ,428,428,428
BEGIN DESCRIPTION:
Rush Creek 39.0
END DESCRIPTION:
XS GIS Cut Line= 3
      2266882.46      7203215.91        2266579.        7202760.
      2266178.97      7202509.98
#Sta/Elev= 30
  4448.3  902.37  4477.5  894.97  4527.5   891.1  4591.7  887.94  4606.8  888.42
  4612.8  887.62  4621.8     888  4772.1  883.34  4833.8  882.65  4895.3  882.55
  4931.4  883.33  4937.4  884.51  4973.4  878.15    4997  877.62  4998.8  877.12
  5010.3  877.62  5090.3     882  5119.2  881.83  5134.5  880.34  5171.1  881.09
    5177  882.59  5234.8  885.75  5286.7   889.7  5292.6  891.06  5307.9   891.8
  5314.4  893.12  5384.6  897.18  5402.2  898.02  5423.4   902.4  5467.7  904.96
#Mann= 5 ,-1 , 0
  4448.3     .05       0  4833.8     .12       0    4997     .07       0
  5010.3     .12       0  5384.6     .05       0
Bank Sta=4997,5010.3
XS Rating Curve= 0 ,0
Exp/Cntr=0.3,0.1