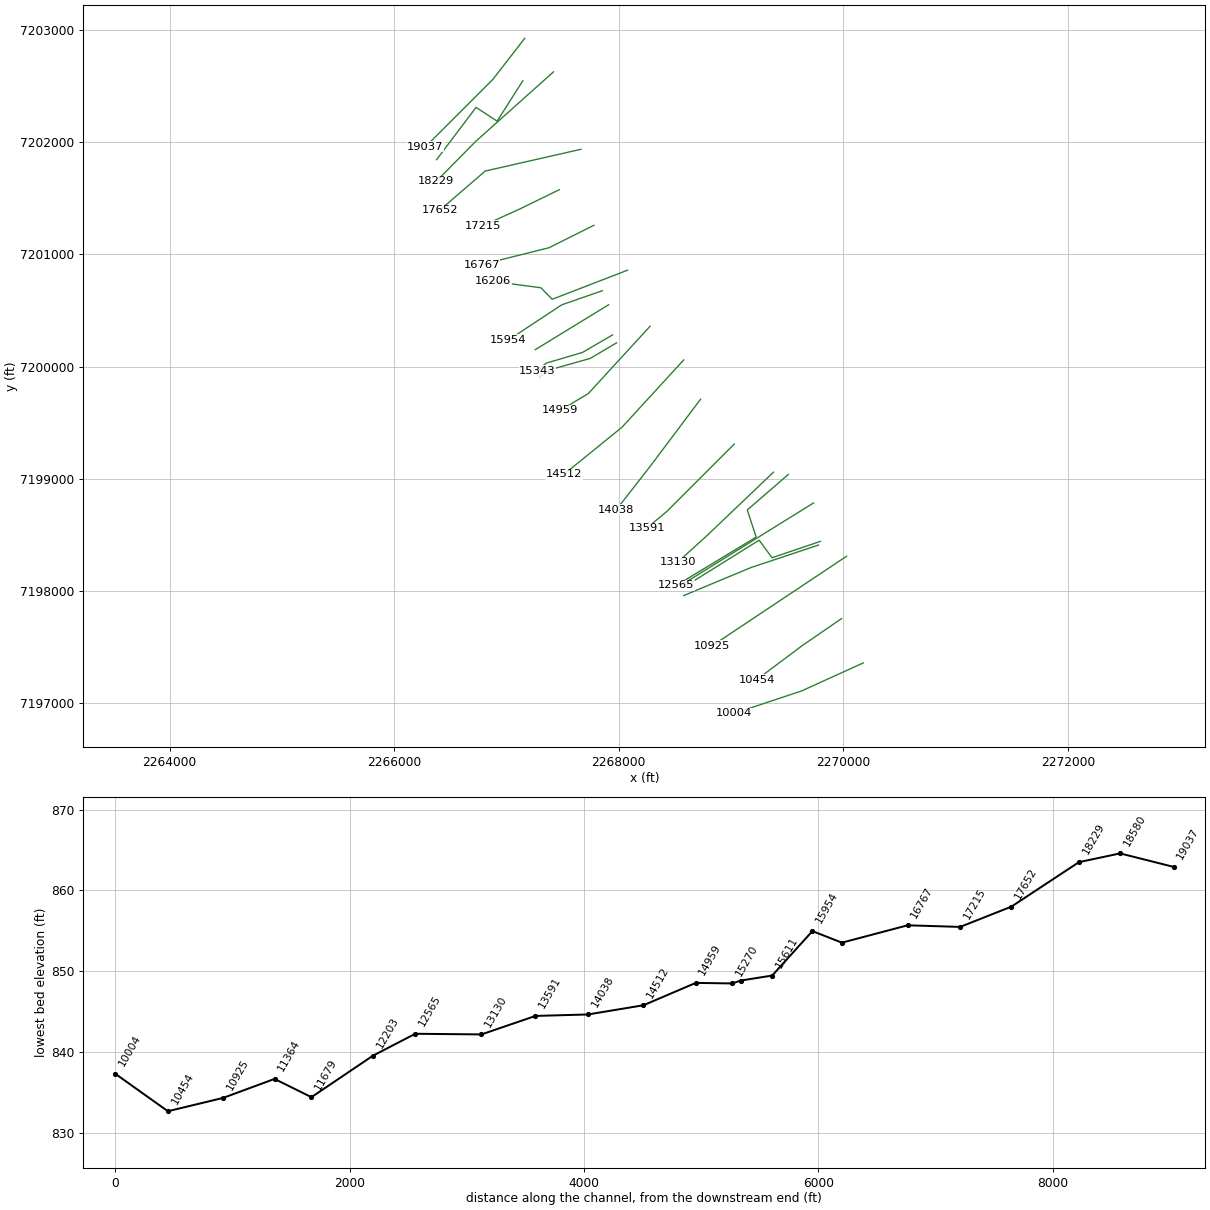
HEC-RAS study Rush Creek.prj: Rush Creek Base Level Engineering

--- Rush Creek.g01 (geometry) --- (continued)

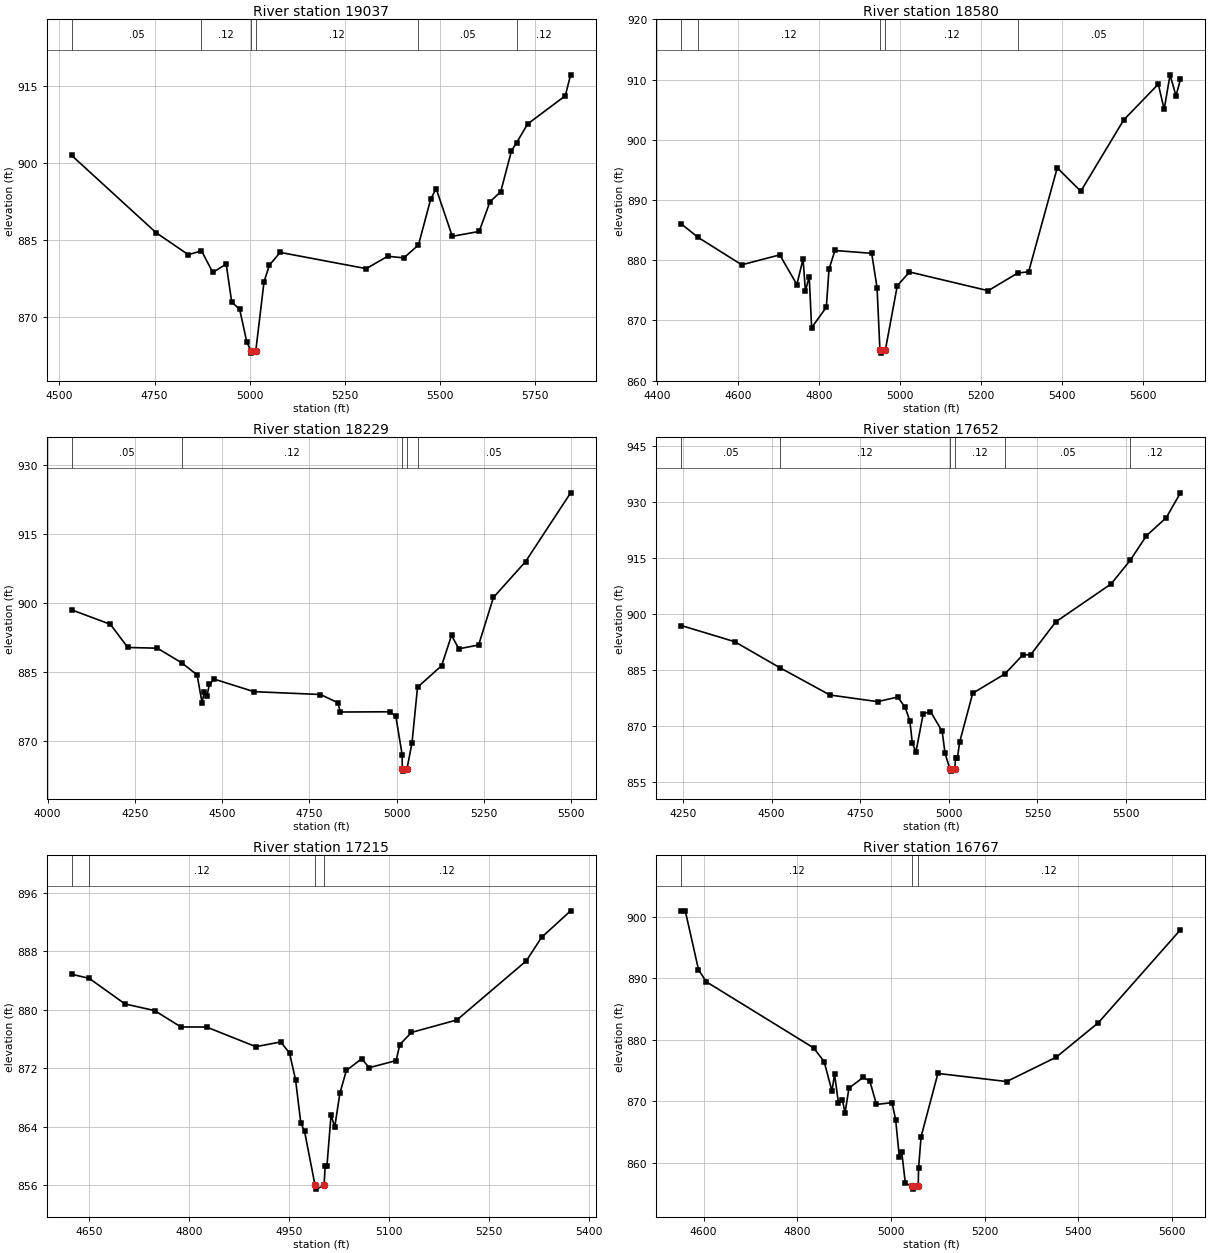
Type RM Length L Ch R = 1 ,19037   ,457,457,457
BEGIN DESCRIPTION:
Rush Creek 38.0
END DESCRIPTION:
XS GIS Cut Line= 3
      2267162.85      7202926.32        2266879.        7202560.
      2266279.03      7201960.03
#Sta/Elev= 30
    4532   901.4  4753.7  886.37  4838.8  882.06  4873.4  882.82  4903.1  878.62
  4938.4  880.24  4952.9  872.82  4973.7  871.46  4992.3  865.15  5002.9   863.4
  5004.8   862.9  5016.3   863.4  5037.8  876.78    5052  880.04  5080.3  882.51
  5306.5  879.35  5363.1  881.76  5405.5  881.44  5443.8  883.96  5476.3  892.93
  5490.4  894.92  5532.8  885.64  5603.5  886.59  5631.8  892.37  5660.1  894.32
  5688.4   902.3  5702.1  903.89  5730.8  907.51  5829.8  912.99  5843.9  917.08
#Mann= 6 ,-1 , 0
    4532     .05       0  4873.4     .12       0  5002.9     .07       0
  5016.3     .12       0  5443.8     .05       0  5702.1     .12       0
Bank Sta=5002.9,5016.3
XS Rating Curve= 0 ,0
Exp/Cntr=0.3,0.1

Type RM Length L Ch R = 1 ,18580   ,351,351,351
BEGIN DESCRIPTION:
Rush Creek 37.1
END DESCRIPTION:
XS GIS Cut Line= 4
      2267145.95      7202547.75      2266917.22      7202188.31
      2266729.32      7202310.85      2266378.02      7201845.17
#Sta/Elev= 30
  4459.4  886.02  4499.8  883.83  4608.5  879.24  4702.4  880.89  4744.8  875.96
    4760  880.21  4765.9  874.89  4775.3  877.28  4781.2   868.8  4817.6  872.19
  4824.2   878.5  4838.8  881.62  4929.7  881.15    4943  875.44  4950.1  865.07
    4952  864.57  4963.5  865.07    4993  875.77  5023.2  878.05  5217.8  874.94
  5290.9  877.88  5317.7  878.08  5388.5  895.35  5446.7  891.46  5552.9  903.32
  5638.3  909.25  5652.8  905.06  5667.4   910.8    5682  907.31  5693.1  910.05
#Mann= 5 ,-1 , 0
  4459.4     .05       0  4499.8     .12       0  4950.1     .07       0
  4963.5     .12       0  5290.9     .05       0
Bank Sta=4950.1,4963.5
XS Rating Curve= 0 ,0
Exp/Cntr=0.3,0.1

Type RM Length L Ch R = 1 ,18229   ,577,577,577
BEGIN DESCRIPTION:
Rush Creek 37.0
END DESCRIPTION:
XS GIS Cut Line= 3
      2267418.91      7202627.38       2266726.6      7202007.92
      2266374.88       7201651.4
#Sta/Elev= 30
  4068.6  898.58  4179.8  895.43  4229.5  890.39  4314.4  890.24  4384.1  887.05
  4428.1  884.43  4442.3  878.39    4449  880.81  4456.5  879.81  4463.2  882.39
  4477.4   883.5  4591.1  880.78  4781.7  880.16  4831.8  878.36  4838.5  876.35
  4980.6   876.4  4997.6  875.39  5015.6  867.08  5016.1  863.99    5018  863.49
  5029.5  863.99  5043.9  869.66  5059.7  881.73  5128.8  886.44  5157.1  893.02
  5178.2   890.1  5234.8  890.94  5277.2  901.28  5369.2  909.07  5498.4  924.04
#Mann= 5 ,-1 , 0
  4068.6     .05       0  4384.1     .12       0  5016.1     .07       0
  5029.5     .12       0  5059.7     .05       0
Bank Sta=5016.1,5029.5
XS Rating Curve= 0 ,0
Exp/Cntr=0.3,0.1

Type RM Length L Ch R = 1 ,17652   ,437,437,437
BEGIN DESCRIPTION:
Rush Creek 36.0
END DESCRIPTION:
XS GIS Cut Line= 3
      2267663.94      7201937.51      2266810.88      7201743.42
      2266407.56      7201395.52
#Sta/Elev= 30
  4245.8  896.92    4396  892.61  4522.5   885.7  4664.5  878.35  4798.8  876.57
  4855.9   877.8  4876.5  875.08    4890  871.46    4897  865.46  4907.2  863.11
  4927.7  873.33  4948.2  873.93  4981.2  868.61  4989.3  862.76    5003  858.48
  5004.9  857.98  5016.5  858.48  5019.1  861.42  5024.3  861.51  5030.3  865.68
  5067.3  878.82  5158.1  883.99  5209.5  889.15  5230.4  889.06  5301.7  897.93
  5457.5  908.05  5511.3  914.35  5557.3  920.95  5613.3   925.8  5653.3  932.44
#Mann= 6 ,-1 , 0
  4245.8     .05       0  4522.5     .12       0    5003     .07       0
  5016.5     .12       0  5158.1     .05       0  5511.3     .12       0
Bank Sta=5003,5016.5
XS Rating Curve= 0 ,0
Exp/Cntr=0.3,0.1

Type RM Length L Ch R = 1 ,17215   ,448,448,448
BEGIN DESCRIPTION:
Rush Creek 35.0
END DESCRIPTION:
XS GIS Cut Line= 3
      2267470.96      7201577.29        2267129.        7201410.
      2266793.63      7201257.28
#Sta/Elev= 30
  4623.9  884.87  4650.3  884.31    4704  880.81  4748.5   879.9    4788  877.66
  4826.5  877.65  4900.5  874.96  4937.8  875.61  4951.1  874.09  4960.1  870.44
    4968  864.51  4973.6   863.4  4989.4  855.97  4991.3  855.47  5002.9  855.97
  5004.6   858.7  5007.3   858.7  5013.4  865.64  5018.9  863.94  5026.6  868.56
  5036.4  871.71  5059.5  873.31  5070.5  872.08  5111.1  873.06  5116.6  875.25
  5134.1  876.91  5202.4  878.62  5306.5   886.7  5329.5  889.92  5373.1  893.55
#Mann= 4 ,-1 , 0
  4623.9     .05       0  4650.3     .12       0  4989.4     .07       0
  5002.9     .12       0
Bank Sta=4989.4,5002.9
XS Rating Curve= 0 ,0
Exp/Cntr=0.3,0.1

Type RM Length L Ch R = 1 ,16767   ,561,561,561
BEGIN DESCRIPTION:
Rush Creek 34.0
END DESCRIPTION:
XS GIS Cut Line= 3
      2267779.01      7201260.01        2267379.        7201060.
      2266778.99        7200910.
#Sta/Elev= 30
  4552.8  900.94  4561.2  900.86  4589.2  891.38  4605.9   889.4  4835.1  878.64
  4857.5  876.42  4874.2  871.62  4879.8  874.36  4888.2  869.62  4896.6  870.11
  4902.2  868.11  4910.6  872.11  4941.3  873.87  4955.3  873.19  4969.3  869.45
  5002.6  869.73  5010.3  866.93  5018.1   860.9  5023.2  861.74    5031  856.59
  5044.8  856.17  5046.7  855.67  5058.4  856.17  5059.3  859.14  5064.5  864.18
  5100.5  874.49  5247.4  873.17  5353.1  877.13  5443.3  882.75  5618.5  897.86
#Mann= 3 ,-1 , 0
  4552.8     .12       0  5044.8     .07       0  5058.4     .12       0
Bank Sta=5044.8,5058.4
XS Rating Curve= 0 ,0
Exp/Cntr=0.3,0.1

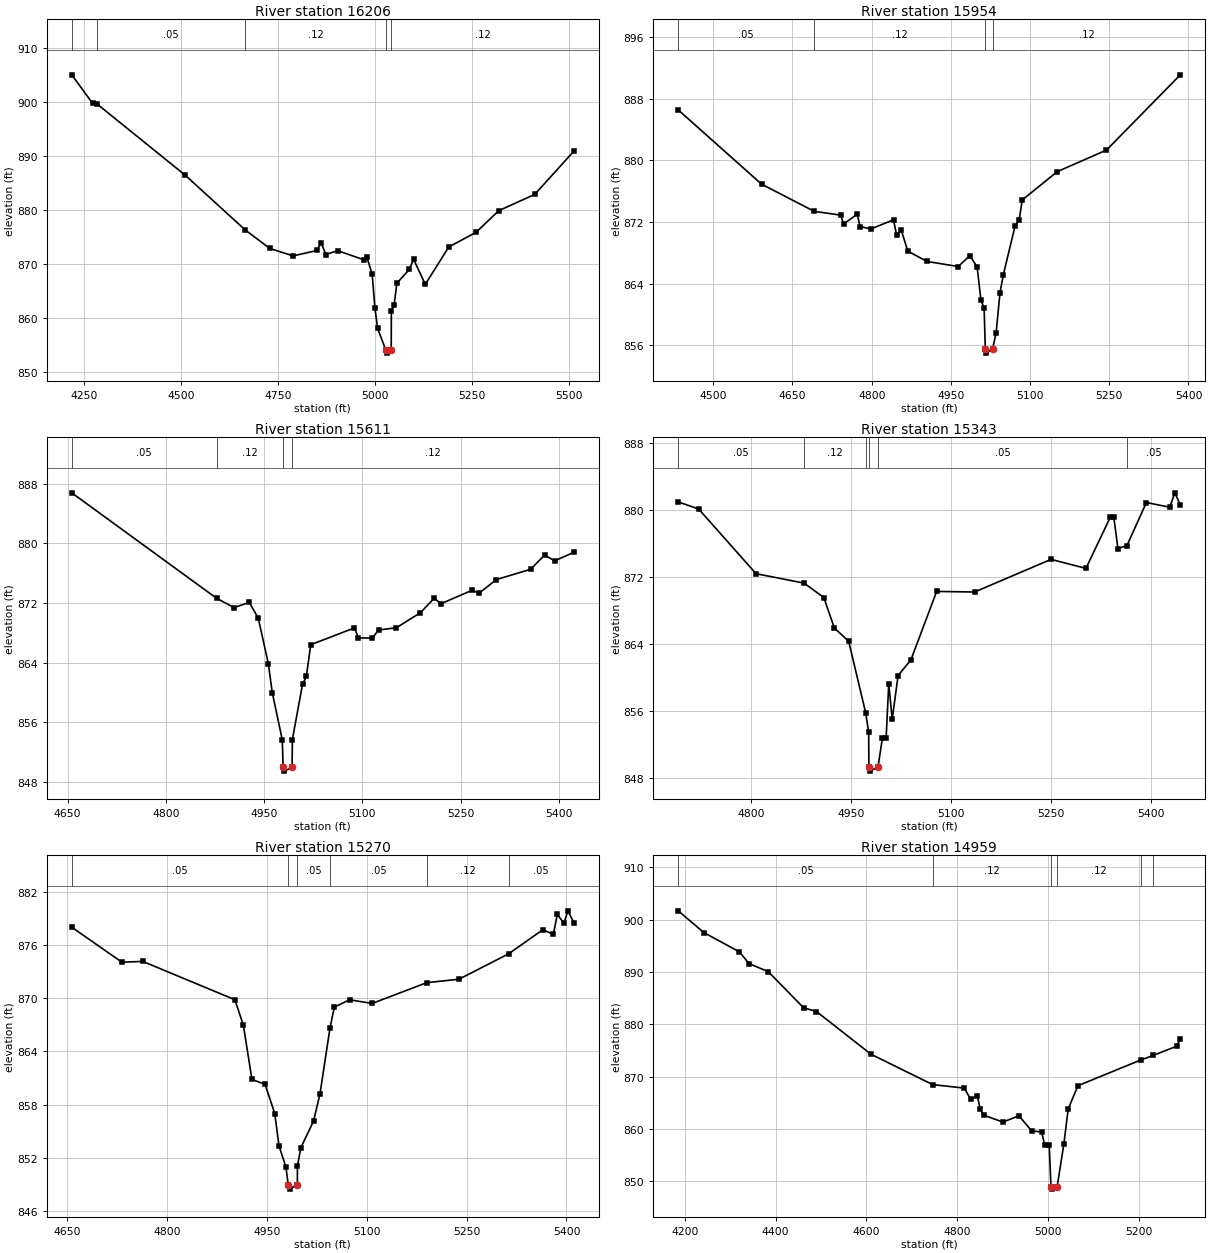
Type RM Length L Ch R = 1 ,16206   ,252,252,252
BEGIN DESCRIPTION:
Rush Creek 33.0
END DESCRIPTION:
XS GIS Cut Line= 4
      2268078.98      7200859.99      2267407.43       7200600.5
      2267306.64      7200703.46      2266878.99        7200760.
#Sta/Elev= 30
  4217.7  904.98  4271.3  899.72  4283.1  899.58  4510.7   886.4  4665.3  876.29
  4728.9  872.87  4788.8   871.5  4850.2   872.5  4860.9  873.96  4873.3  871.75
  4903.8  872.47  4971.5  870.77  4978.7  871.38  4992.8  868.12  4999.8  861.86
  5006.9  858.08  5028.3  854.02  5030.3  853.52  5041.9  854.02  5042.3  861.34
  5049.3  862.34  5056.4  866.44  5088.9  869.02  5099.5   870.9  5129.8  866.24
  5190.3  873.14  5260.9  875.86  5319.4  879.86  5412.2  882.87  5513.1  890.86
#Mann= 5 ,-1 , 0
  4217.7     .12       0  4283.1     .05       0  4665.3     .12       0
  5028.3     .07       0  5041.9     .12       0
Bank Sta=5028.3,5041.9
XS Rating Curve= 0 ,0
Exp/Cntr=0.3,0.1

Type RM Length L Ch R = 1 ,15954   ,343,343,343
BEGIN DESCRIPTION:
Rush Creek 32.0
END DESCRIPTION:
XS GIS Cut Line= 3
       2267853.4      7200676.68      2267492.97      7200551.22
      2267017.81      7200237.72
#Sta/Elev= 30
  4433.6  886.57  4591.3  876.92  4691.2  873.38  4741.5  872.89  4746.8  871.74
  4772.6  873.01  4777.9  871.41  4798.3  871.09  4841.3  872.28  4847.3  870.28
  4855.9  870.97  4868.4  868.21  4904.5  866.87  4963.8  866.21  4985.9  867.62
  4999.7  866.15  5006.9  861.85  5012.9  860.79  5015.2  855.45  5017.1  854.95
  5028.8  855.45  5035.6  857.57    5043  862.79    5049  865.05  5071.6  871.49
  5079.2  872.23  5085.2  874.87  5151.4  878.54  5244.7  881.35  5384.5  891.13
#Mann= 4 ,-1 , 0
  4433.6     .05       0  4691.2     .12       0  5015.2     .07       0
  5028.8     .12       0
Bank Sta=5015.2,5028.8
XS Rating Curve= 0 ,0
Exp/Cntr=0.3,0.1

Type RM Length L Ch R = 1 ,15611   ,268,268,268
BEGIN DESCRIPTION:
Rush Creek 31.1
END DESCRIPTION:
XS GIS Cut Line= 2
      2267909.96      7200551.61       2267256.5      7200151.36
#Sta/Elev= 30
  4656.5  886.77  4877.5  872.63  4904.3  871.38  4927.3  872.08  4941.1  869.98
  4956.5  863.86  4962.5  859.99  4977.8  853.64  4979.1  849.95  4981.1  849.45
  4992.8  849.95  4993.2  853.69  5008.7   861.1  5014.5  862.14  5021.2   866.4
    5088  868.66  5093.9  867.32  5115.2  867.29  5124.7  868.37  5151.9  868.68
  5188.6  870.69  5209.9  872.65  5219.5  871.88    5268  873.72  5277.5  873.27
  5304.7  875.14  5356.9  876.52  5378.2  878.42  5393.6  877.65  5422.8  878.79
#Mann= 4 ,-1 , 0
  4656.5     .05       0  4877.5     .12       0  4979.1     .07       0
  4992.8     .12       0
Bank Sta=4979.1,4992.8
XS Rating Curve= 0 ,0
Exp/Cntr=0.3,0.1

Type RM Length L Ch R = 1 ,15343   ,73,73,73
BEGIN DESCRIPTION:
Rush Creek 31.0
END DESCRIPTION:
XS GIS Cut Line= 4
      2267945.46      7200283.39      2267678.25       7200127.2
      2267353.33       7200031.1      2267275.93      7199961.11
#Sta/Elev= 30
  4691.3     881    4722  880.14  4807.9  872.42    4880  871.29  4909.6  869.57
  4925.3  865.93  4946.8  864.35  4972.2  855.83  4976.8  853.49  4977.1  849.33
  4979.1  848.83  4990.8  849.33  4997.5  852.83    5003  852.83  5006.9  859.26
  5012.1  855.04  5020.9  860.25  5040.2  862.13  5078.7   870.3  5135.6  870.23
  5250.2  874.13  5302.5  873.05  5339.3  879.21  5344.2  879.21  5350.5  875.42
    5364  875.78  5393.1  880.92  5428.2  880.36  5435.7  882.08    5444  880.66
#Mann= 6 ,-1 , 0
  4691.3     .05       0    4880     .12       0  4972.2     .05       0
  4977.1     .07       0  4990.8     .05       0    5364     .05       0
Bank Sta=4977.1,4990.8
XS Rating Curve= 0 ,0
Exp/Cntr=0.3,0.1

Type RM Length L Ch R = 1 ,15270   ,311,311,311
BEGIN DESCRIPTION:
Rush Creek 30.1
END DESCRIPTION:
XS GIS Cut Line= 4
      2267980.62      7200212.29      2267746.82      7200073.73
      2267422.77      7199981.96      2267296.37      7199910.44
#Sta/Elev= 30
  4657.3  877.99  4732.6  874.05  4763.8  874.14  4902.2  869.82  4914.9  866.95
  4927.8  860.84  4947.6  860.27  4962.1  856.98  4968.4  853.36  4978.8  850.95
  4982.3  848.97  4984.3  848.47    4996  848.97  4996.1  851.08  5001.3  853.15
  5020.3  856.14    5030  859.22    5045  866.64  5051.5  868.99  5074.4  869.81
  5108.3   869.4  5190.1  871.74  5238.6  872.13  5313.3     875  5364.5  877.71
  5380.4  877.19  5386.2  879.43  5396.3  878.44  5402.1  879.84  5411.1  878.52
#Mann= 6 ,-1 , 0
  4657.3     .05       0  4982.3     .07       0    4996     .05       0
    5045     .05       0  5190.1     .12       0  5313.3     .05       0
Bank Sta=4982.3,4996
XS Rating Curve= 0 ,0
Exp/Cntr=0.3,0.1

Type RM Length L Ch R = 1 ,14959   ,447,447,447
BEGIN DESCRIPTION:
Rush Creek 30.0
END DESCRIPTION:
XS GIS Cut Line= 3
      2268279.03      7200360.04        2267729.        7199760.
      2267479.03      7199610.02
#Sta/Elev= 30
  4185.5  901.71    4242  897.55  4320.3  893.87  4341.2  891.64  4383.8  890.08
  4461.5  883.19  4489.9  882.47  4610.1   874.3  4745.7  868.51  4815.4  867.84
  4829.6  865.68  4843.8  866.39  4850.6  863.81    4858  862.67  4900.5  861.35
  4935.7  862.55    4964  859.63  4985.6  859.49  4992.4  856.98  5002.4  856.89
  5006.2  849.04  5008.2  848.54  5019.9  849.04  5034.5  857.11  5044.2  863.87
  5065.6   868.3  5203.5   873.2  5230.9  874.07  5283.3  875.86    5291  877.21
#Mann= 6 ,-1 , 0
  4185.5     .05       0  4745.7     .12       0  5006.2     .07       0
  5019.9     .12       0  5203.5     .05       0  5230.9     .12       0
Bank Sta=5006.2,5019.9
XS Rating Curve= 0 ,0
Exp/Cntr=0.3,0.1

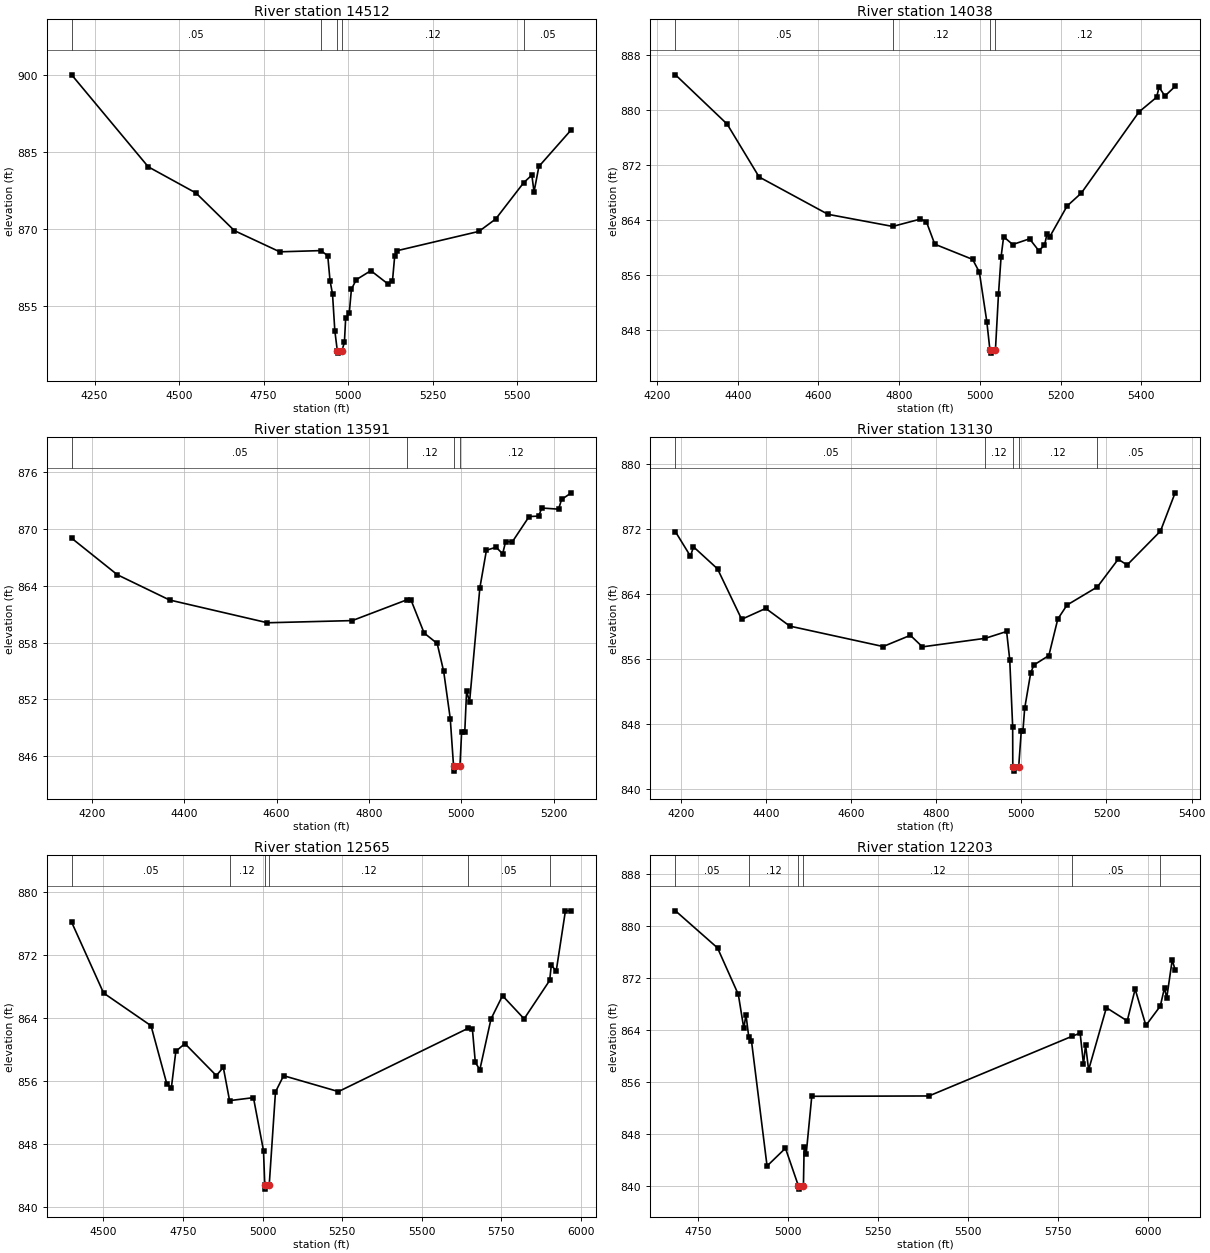
Type RM Length L Ch R = 1 ,14512   ,474,474,474
BEGIN DESCRIPTION:
Rush Creek 29.0
END DESCRIPTION:
XS GIS Cut Line= 3
      2268579.03      7200060.03        2268029.        7199460.
      2267513.39      7199041.43
#Sta/Elev= 30
  4182.1  900.11  4408.7  882.15    4550  877.03  4663.4  869.69  4797.8  865.55
  4919.2  865.79  4939.7  864.79  4946.4  859.93  4953.8  857.32  4960.6  850.17
  4967.9  846.27  4969.9  845.77  4981.7  846.27    4989  847.87  4992.7  852.62
  5003.3  853.56  5009.7  858.25  5024.1  860.11  5067.2  861.87  5116.8  859.33
  5131.1  859.82  5137.8  864.75  5145.5  865.78  5386.9  869.54  5436.4  871.95
  5519.6  879.07  5543.5  880.53  5549.9  877.25  5564.3  882.22  5660.2  889.39
#Mann= 5 ,-1 , 0
  4182.1     .05       0  4919.2     .12       0  4967.9     .07       0
  4981.7     .12       0  5519.6     .05       0
Bank Sta=4967.9,4981.7
XS Rating Curve= 0 ,0
Exp/Cntr=0.3,0.1

Type RM Length L Ch R = 1 ,14038   ,447,447,447
BEGIN DESCRIPTION:
Rush Creek 28.0
END DESCRIPTION:
XS GIS Cut Line= 3
        2268729.        7199710.        2268279.        7199110.
      2267978.58      7198724.93
#Sta/Elev= 30
  4245.6  885.07  4373.7  877.91  4452.9  870.23  4623.7   864.8    4784  863.04
  4852.9  864.11  4867.5  863.73  4888.3  860.46  4982.1  858.25  4998.8   856.4
  5017.3  849.21  5024.9  845.13  5026.8  844.63  5038.7  845.13  5046.2  853.19
  5052.6  858.59    5059  861.54  5081.5  860.41  5123.2  861.24  5145.8  859.54
  5160.2  860.27  5166.6  861.98  5173.2  861.53  5216.3  866.01  5251.6  867.89
  5394.5  879.68  5437.9   881.8  5444.3  883.27  5458.7  881.99    5484  883.39
#Mann= 4 ,-1 , 0
  4245.6     .05       0    4784     .12       0  5024.9     .07       0
  5038.7     .12       0
Bank Sta=5024.9,5038.7
XS Rating Curve= 0 ,0
Exp/Cntr=0.3,0.1

Type RM Length L Ch R = 1 ,13591   ,461,461,461
BEGIN DESCRIPTION:
Rush Creek 27.0
END DESCRIPTION:
XS GIS Cut Line= 3
      2269029.01      7199310.01        2268429.        7198710.
      2268248.71      7198560.74
#Sta/Elev= 30
  4155.8  868.99  4254.8  865.14  4367.9  862.48  4580.1  860.08  4763.9  860.31
  4882.7  862.51  4891.2  862.46  4919.5     859  4947.8   857.9  4961.9  854.95
  4976.1  849.99  4983.3  844.95  4985.2  844.45  4997.1  844.95  5000.8  848.62
  5007.6  848.62  5011.5  852.87    5018  851.77  5040.2  863.74  5054.5  867.72
  5075.3  868.04  5089.7  867.35  5096.1  868.64  5110.5   868.6    5147  871.27
  5167.8  871.32  5174.3  872.17  5210.8  872.05  5217.3  873.07  5238.4  873.77
#Mann= 4 ,-1 , 0
  4155.8     .05       0  4882.7     .12       0  4983.3     .07       0
  4997.1     .12       0
Bank Sta=4983.3,4997.1
XS Rating Curve= 0 ,0
Exp/Cntr=0.3,0.1

Type RM Length L Ch R = 1 ,13130   ,565,565,565
BEGIN DESCRIPTION:
Rush Creek 26.0
END DESCRIPTION:
XS GIS Cut Line= 3
      2269378.97      7199059.97      2268788.47      7198496.55
      2268523.94      7198256.03
#Sta/Elev= 30
  4187.5  871.61  4222.8   868.6  4229.8  869.76  4286.4  867.04    4343  860.84
  4399.6  862.18  4456.2     860  4675.4  857.49  4739.3  858.87  4767.6  857.45
  4915.2   858.5  4965.4  859.34  4972.7  855.87  4979.6  847.64  4979.9  842.66
  4981.9  842.16  4993.7  842.66  4999.8   847.1  5003.7   847.1  5007.8  849.88
    5022  854.26  5029.5  855.22  5064.6  856.38  5085.6  860.87  5107.2  862.59
  5178.7  864.83  5227.5  868.23  5248.4  867.52  5326.8  871.69  5361.2   876.4
#Mann= 5 ,-1 , 0
  4187.5     .05       0  4915.2     .12       0  4979.9     .07       0
  4993.7     .12       0  5178.7     .05       0
Bank Sta=4979.9,4993.7
XS Rating Curve= 0 ,0
Exp/Cntr=0.3,0.1

Type RM Length L Ch R = 1 ,12565   ,362,362,362
BEGIN DESCRIPTION:
Rush Creek 25.3
END DESCRIPTION:
XS GIS Cut Line= 4
      2269510.98      7199039.62      2269145.09      7198722.76
      2269224.32      7198481.08       2268513.2      7198050.64
#Sta/Elev= 30
    4400  876.17  4500.3  867.17  4649.4  863.01  4698.8  855.64    4713  855.05
  4727.3  859.76  4755.8  860.74  4854.5  856.67  4876.4  857.72  4896.1  853.49
  4971.1  853.87  5002.7  847.13  5006.7  842.74  5008.7  842.24  5020.6  842.74
  5040.3   854.6  5065.8  856.66  5238.1  854.64  5644.6  862.67  5658.9  862.57
  5668.1  858.34  5682.3  857.43  5717.3  863.87  5753.5  866.83  5821.4  863.89
  5901.6  868.77  5906.7   870.7  5922.2  869.97  5951.1  877.62  5969.6  877.61
#Mann= 6 ,-1 , 0
    4400     .05       0  4896.1     .12       0  5006.7     .07       0
  5020.6     .12       0  5644.6     .05       0  5901.6     .12       0
Bank Sta=5006.7,5020.6
XS Rating Curve= 0 ,0
Exp/Cntr=0.3,0.1

Type RM Length L Ch R = 1 ,12203   ,524,524,524
BEGIN DESCRIPTION:
Rush Creek 25.2
END DESCRIPTION:
XS GIS Cut Line= 2
      2269735.49      7198785.42      2268554.54      7198052.31
#Sta/Elev= 30
  4686.5   882.3  4803.5   876.6  4861.4  869.44  4876.7  864.22  4882.6  866.35
  4890.3  862.97    4898   862.3  4941.3  843.07  4992.5  845.81  5028.5  840.02
  5030.5  839.52  5042.5  840.02  5044.5  846.03  5050.3  844.99  5065.7  853.79
  5391.6  853.84  5790.4  863.03  5812.3   863.5  5821.6   858.7  5827.4  861.71
  5835.8  857.84  5885.3  867.41  5943.2  865.38  5965.3  870.26  5995.2  864.68
  6035.2  867.65  6047.1  870.49    6053  868.84  6068.4  874.74  6076.5  873.24
#Mann= 6 ,-1 , 0
  4686.5     .05       0  4890.3     .12       0  5028.5     .07       0
  5042.5     .12       0  5790.4     .05       0  6035.2     .12       0
Bank Sta=5028.5,5042.5
XS Rating Curve= 0 ,0
Exp/Cntr=0.3,0.1

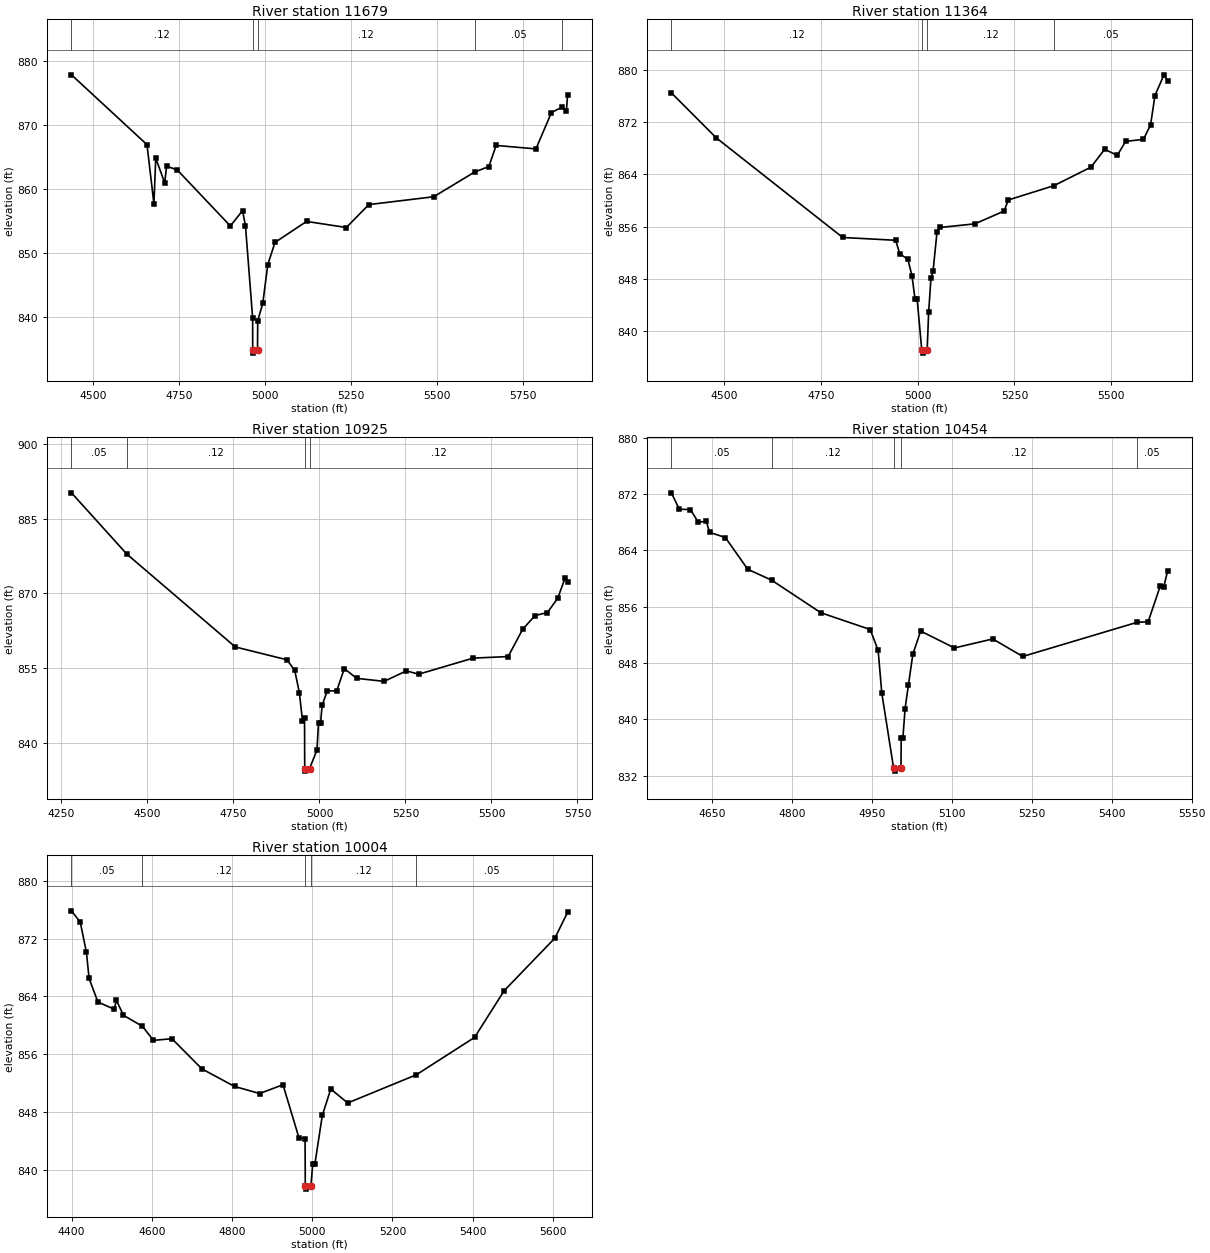
Type RM Length L Ch R = 1 ,11679   ,315,315,315
BEGIN DESCRIPTION:
Rush Creek 25.1
END DESCRIPTION:
XS GIS Cut Line= 4
      2269796.82      7198443.16      2269365.46      7198297.13
      2269250.72      7198453.63      2268579.18      7198034.25
#Sta/Elev= 30
  4437.8   877.9  4657.2  866.98  4677.3  857.74  4682.6  864.87  4708.7  860.99
    4714  863.64  4745.4  863.01  4899.3  854.27  4934.8  856.67  4943.3  854.25
  4964.1  839.88  4964.2  834.89  4966.2  834.39  4978.2  834.89  4978.8  839.44
  4993.5  842.18  5008.1  848.23    5029   851.7  5120.6  854.98  5236.2  854.03
  5301.5  857.61  5490.1  858.84  5609.2  862.71  5650.2  863.56  5671.4  866.86
    5787  866.32    5832     872  5862.6  872.84  5875.4  872.23    5879  874.79
#Mann= 5 ,-1 , 0
  4437.8     .12       0  4964.2     .07       0  4978.2     .12       0
  5609.2     .05       0  5862.6     .12       0
Bank Sta=4964.2,4978.2
XS Rating Curve= 0 ,0
Exp/Cntr=0.3,0.1

Type RM Length L Ch R = 1 ,11364   ,439,439,439
BEGIN DESCRIPTION:
Rush Creek 25.0
END DESCRIPTION:
XS GIS Cut Line= 3
      2269778.99        7198410.        2269179.        7198210.
      2268579.04      7197960.02
#Sta/Elev= 30
  4363.3  876.43  4479.2  869.56    4806  854.33    4943   853.9  4953.6  851.83
  4974.7  850.99  4985.2  848.44  4993.1  844.89  4998.5  844.89  5010.4  837.15
  5012.4  836.65  5024.4  837.15  5028.2  842.88  5034.2  848.09  5039.6  849.17
  5049.9   855.2    5058  855.86  5147.4  856.41  5223.2  858.36  5234.1  860.06
  5352.2  862.25    5448  865.09  5483.2  867.81  5515.7  866.88  5537.4  869.01
  5583.5  869.33  5601.9  871.55  5613.2  876.03  5636.5  879.19  5645.7  878.31
#Mann= 4 ,-1 , 0
  4363.3     .12       0  5010.4     .07       0  5024.4     .12       0
  5352.2     .05       0
Bank Sta=5010.4,5024.4
XS Rating Curve= 0 ,0
Exp/Cntr=0.3,0.1

Type RM Length L Ch R = 1 ,10925   ,471,471,471
BEGIN DESCRIPTION:
Rush Creek 24.0
END DESCRIPTION:
XS GIS Cut Line= 3
      2270028.97      7198309.98        2269429.        7197910.
      2268828.99      7197509.99
#Sta/Elev= 30
  4279.1  890.19  4439.8   877.9  4755.3  859.24  4905.5  856.66  4928.1  854.54
  4941.6  850.04  4950.6  844.41  4956.6  844.97  4957.1   834.8  4959.1   834.3
  4971.1   834.8  4992.7  838.53  4997.2  843.98  5003.2  843.98  5007.7   847.5
  5022.7  850.46  5049.8  850.36  5072.3  854.89  5108.3  852.93    5188  852.33
  5252.6  854.43  5288.6  853.77  5446.4  856.99  5548.5  857.31  5590.6  862.78
  5626.6  865.54  5662.7  866.15  5692.7  869.04  5713.8  873.04  5721.3  872.36
#Mann= 4 ,-1 , 0
  4279.1     .05       0  4439.8     .12       0  4957.1     .07       0
  4971.1     .12       0
Bank Sta=4957.1,4971.1
XS Rating Curve= 0 ,0
Exp/Cntr=0.3,0.1

Type RM Length L Ch R = 1 ,10454   ,450,450,450
BEGIN DESCRIPTION:
Rush Creek 23.0
END DESCRIPTION:
XS GIS Cut Line= 3
      2269984.43      7197754.55        2269629.        7197510.
      2269229.03      7197210.02
#Sta/Elev= 30
  4573.3  872.19  4588.1  869.86    4609  869.81  4623.9     868  4638.8  868.16
  4644.9  866.58  4674.6  865.84  4716.6  861.33  4761.5  859.78  4853.9  855.15
  4946.5  852.77  4961.4  849.81  4968.3  843.73  4990.3  833.15  4992.3  832.65
  5004.3  833.15  5004.7  837.37  5007.9  837.37    5012  841.53  5018.3  844.92
  5026.6  849.27  5041.2  852.55  5104.7  850.15  5176.6  851.43  5232.9  848.94
  5447.5  853.79  5468.3  853.87  5491.2  858.99  5497.4  858.75  5504.7  861.05
#Mann= 5 ,-1 , 0
  4573.3     .05       0  4761.5     .12       0  4990.3     .07       0
  5004.3     .12       0  5447.5     .05       0
Bank Sta=4990.3,5004.3
XS Rating Curve= 0 ,0
Exp/Cntr=0.3,0.1

Type RM Length L Ch R = 1 ,10004   ,430,430,430
BEGIN DESCRIPTION:
Rush Creek 22.0
END DESCRIPTION:
XS GIS Cut Line= 3
      2270178.99      7197359.99        2269629.        7197110.
      2269028.99        7196910.
#Sta/Elev= 30
  4399.9  875.84  4421.9  874.26  4437.2  870.08  4443.8  866.48  4465.8  863.21
  4506.4  862.21  4511.9  863.44  4529.5  861.37  4576.7  859.85  4604.2   857.9
  4650.3  858.13    4725  853.95  4806.3  851.52  4868.9  850.54  4927.1  851.76
  4966.7  844.44  4982.1  844.27  4982.7   837.8  4984.7   837.3  4996.8   837.8
  5001.3  840.82  5006.7  840.82  5025.1   847.5  5046.2  851.16  5088.4  849.23
  5259.6  853.14  5404.6  858.31  5478.4  864.78  5604.9  872.07  5636.5  875.64
#Mann= 5 ,-1 , 0
  4399.9     .05       0  4576.7     .12       0  4982.7     .07       0
  4996.8     .12       0  5259.6     .05       0
Bank Sta=4982.7,4996.8
XS Rating Curve= 0 ,0
Exp/Cntr=0.3,0.1