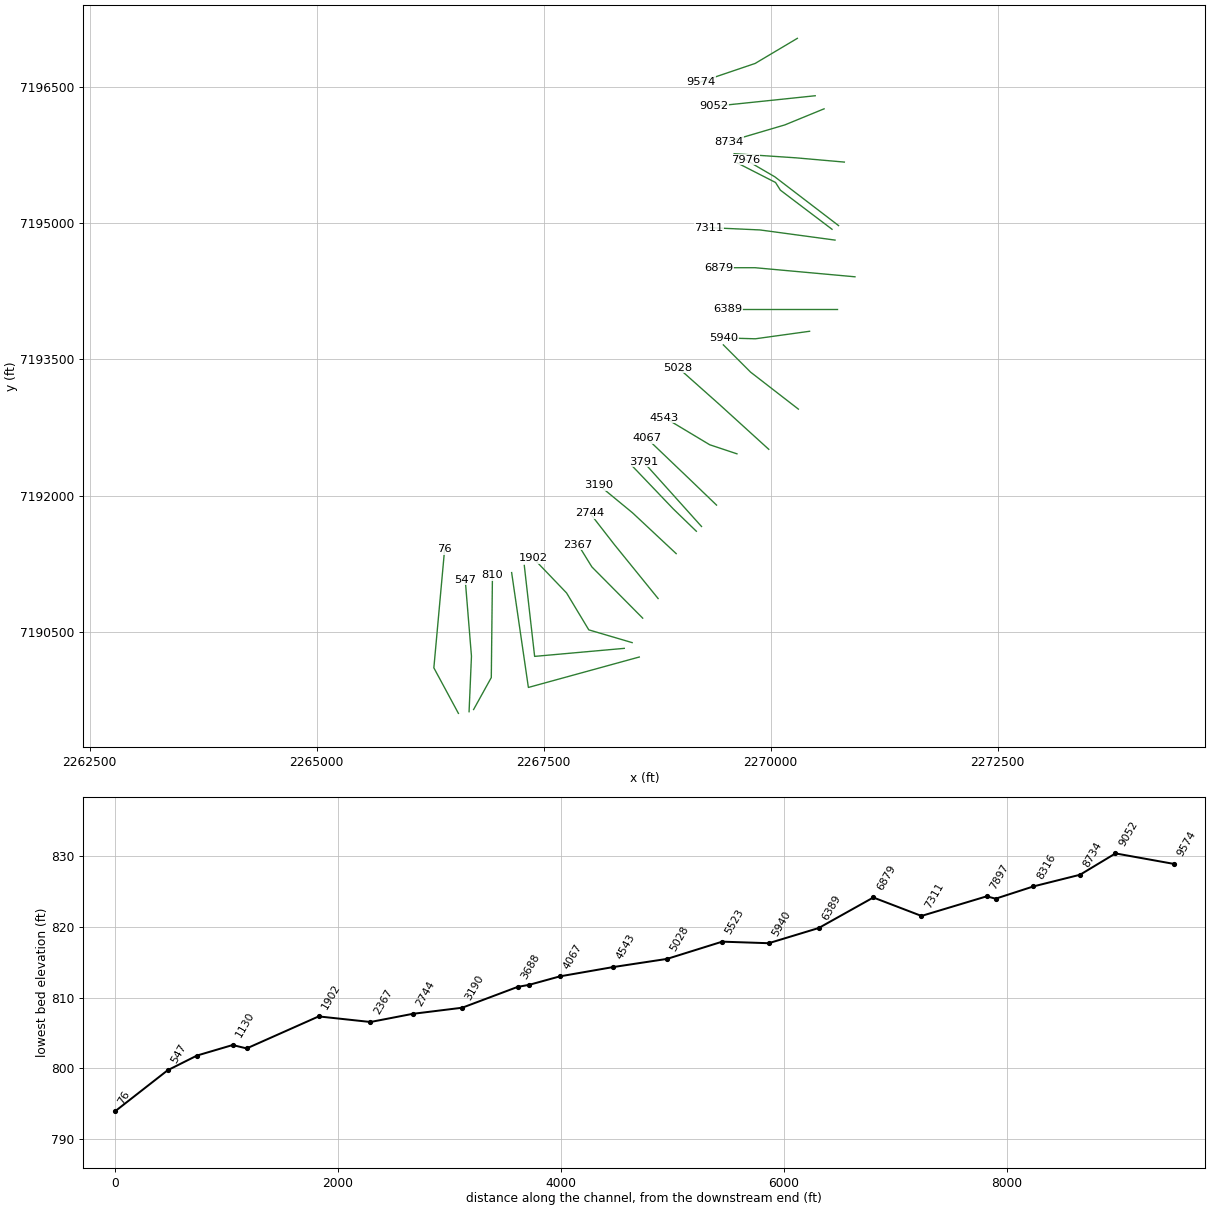
HEC-RAS study Rush Creek.prj: Rush Creek Base Level Engineering

--- Rush Creek.g01 (geometry) --- (continued)

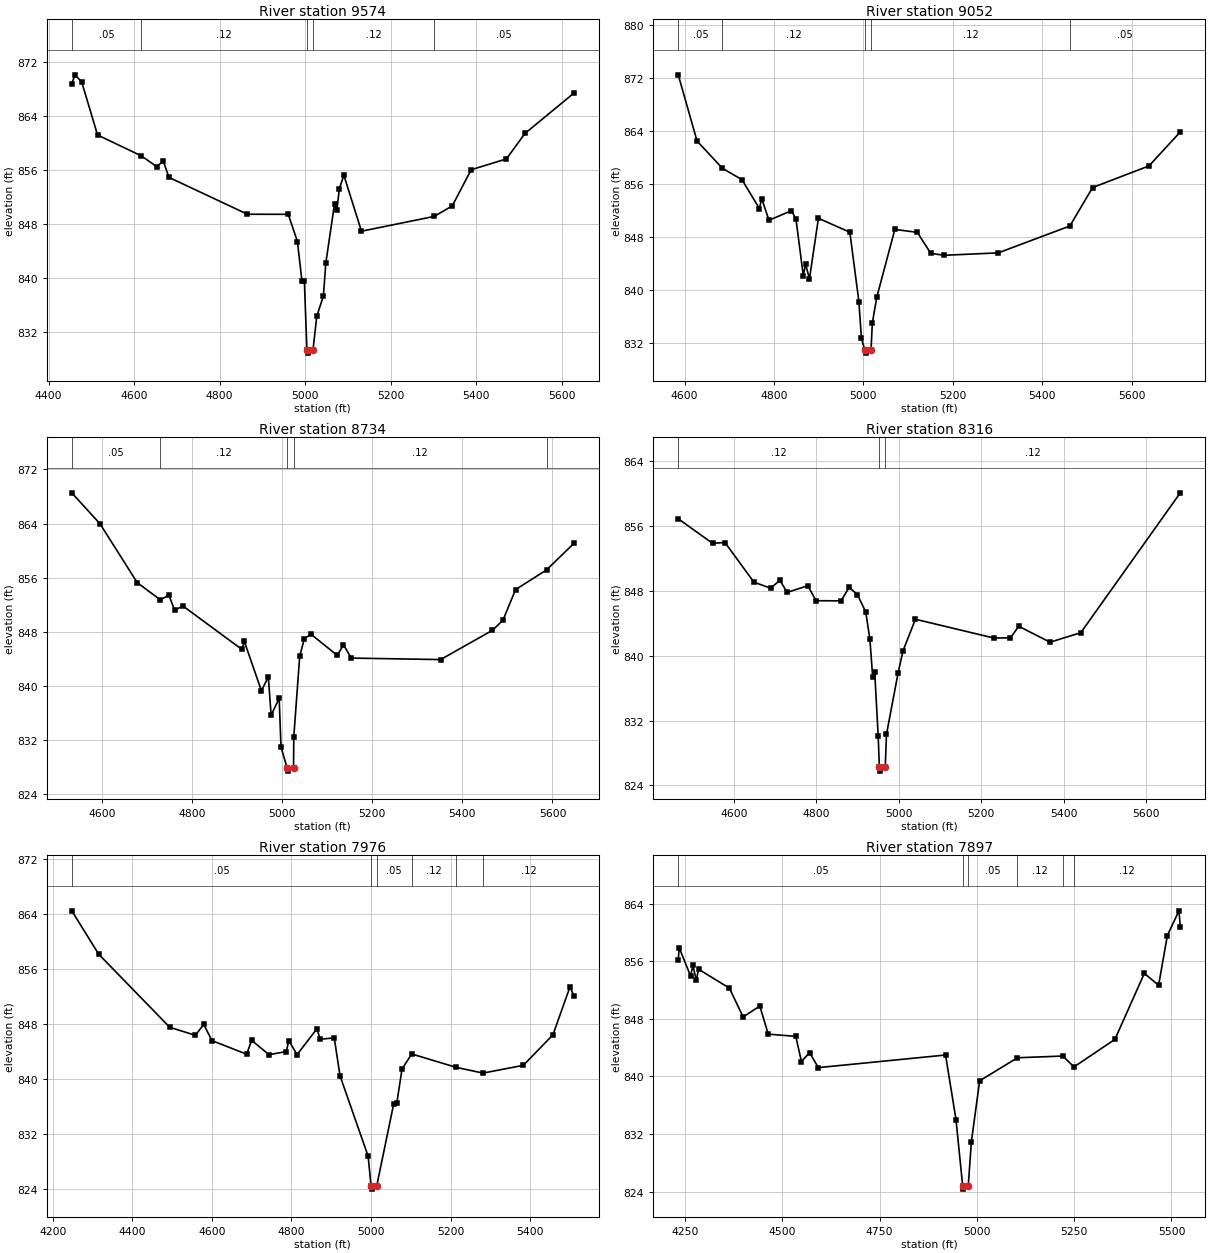
Type RM Length L Ch R = 1 ,9574    ,522,522,522
BEGIN DESCRIPTION:
Rush Creek 21.0
END DESCRIPTION:
XS GIS Cut Line= 3
      2270294.31      7197036.68        2269829.        7196760.
       2269229.6      7196556.99
#Sta/Elev= 30
  4454.1  868.79  4461.7  870.09  4477.3  869.04  4514.4   861.2  4616.5  858.12
  4652.6  856.53  4668.2  857.33  4681.3  854.93    4865  849.48  4960.4  849.47
  4981.8  845.45  4992.5  839.57  4998.1  839.57    5004  829.45    5006  828.95
  5018.3  829.45  5027.1   834.4  5042.6   837.4  5048.2  842.25  5068.7  851.06
    5074  850.07  5079.9  853.27  5090.5  855.24  5131.6  846.97  5301.6  849.16
  5343.9  850.71  5388.2  856.06  5470.6  857.66  5513.9  861.42  5628.3  867.38
#Mann= 5 ,-1 , 0
  4454.1     .05       0  4616.5     .12       0    5004     .07       0
  5018.3     .12       0  5301.6     .05       0
Bank Sta=5004,5018.3
XS Rating Curve= 0 ,0
Exp/Cntr=0.3,0.1

Type RM Length L Ch R = 1 ,9052    ,318,318,318
BEGIN DESCRIPTION:
Rush Creek 20.0
END DESCRIPTION:
XS GIS Cut Line= 3
      2270490.85      7196404.34      2270082.84      7196361.54
      2269373.82      7196287.79
#Sta/Elev= 30
  4585.9  872.41    4628  862.42  4684.7  858.31  4728.5  856.59  4767.5  852.23
  4772.5  853.74  4788.9  850.47  4839.1  851.92  4849.2  850.68  4865.7  842.08
  4870.7  843.88  4879.4  841.63  4899.5  850.77  4969.8  848.67    4990   838.2
  4995.6  832.75  5002.9  830.93  5004.9  830.43  5017.2  830.93  5020.1     835
  5030.2   838.9  5070.4  849.09  5120.7  848.65  5150.8  845.47    5181  845.19
  5301.6  845.55    5462  849.61  5512.8  855.41  5638.9  858.67    5709   863.8
#Mann= 5 ,-1 , 0
  4585.9     .05       0  4684.7     .12       0  5002.9     .07       0
  5017.2     .12       0    5462     .05       0
Bank Sta=5002.9,5017.2
XS Rating Curve= 0 ,0
Exp/Cntr=0.3,0.1

Type RM Length L Ch R = 1 ,8734    ,418,418,418
BEGIN DESCRIPTION:
Rush Creek 19.0
END DESCRIPTION:
XS GIS Cut Line= 3
      2270588.49      7196260.26      2270156.25      7196083.02
      2269535.31      7195899.69
#Sta/Elev= 30
  4532.8  868.55  4595.5  863.97  4678.3  855.26  4729.6  852.73  4748.4  853.43
  4761.1   851.2  4779.6  851.82  4910.4  845.41  4915.8   846.6  4953.8  839.29
  4969.2  841.34  4975.4  835.67  4993.2  838.18  4997.3  830.99  5010.8  827.91
  5012.8  827.41  5025.1  827.91  5025.7   832.5  5038.8  844.38  5049.2  847.01
  5064.2  847.63  5122.2  844.52    5136  846.07  5153.5  844.12  5351.6   843.9
  5466.3  848.21  5489.9   849.7    5518  854.24  5586.7  857.15  5647.4  861.07
#Mann= 5 ,-1 , 0
  4532.8     .05       0  4729.6     .12       0  5010.8     .07       0
  5025.1     .12       0  5586.7     .05       0
Bank Sta=5010.8,5025.1
XS Rating Curve= 0 ,0
Exp/Cntr=0.3,0.1

Type RM Length L Ch R = 1 ,8316    ,340,340,340
BEGIN DESCRIPTION:
Rush Creek 18.0
END DESCRIPTION:
XS GIS Cut Line= 3
      2270811.87      7195673.61      2270277.67      7195720.53
      2269598.25      7195766.09
#Sta/Elev= 30
  4465.2   856.9  4548.4  853.87  4578.5  853.97  4648.8  849.07  4688.9  848.34
  4711.9   849.3  4729.1  847.81  4779.3  848.64  4799.4  846.79  4859.6  846.77
  4879.7  848.43  4899.7  847.54  4919.8  845.39  4929.9  842.02  4936.6  837.34
  4941.6  837.96  4949.9  830.12  4952.8  826.26  4954.8  825.76  4967.1  826.26
    4970  830.28  4998.3   837.9  5010.1   840.6  5040.2   844.5  5230.6  842.18
  5270.7  842.21  5290.8  843.63  5366.6  841.67  5441.1  842.84  5682.4   860.1
#Mann= 3 ,-1 , 0
  4465.2     .12       0  4952.8     .07       0  4967.1     .12       0
Bank Sta=4952.8,4967.1
XS Rating Curve= 0 ,0
Exp/Cntr=0.3,0.1

Type RM Length L Ch R = 1 ,7976    ,79,79,79
BEGIN DESCRIPTION:
Rush Creek 17.1
END DESCRIPTION:
XS GIS Cut Line= 3
      2270748.26       7194974.1      2270046.12      7195511.18
      2269719.29      7195701.87
#Sta/Elev= 30
  4247.7  864.46  4315.5  858.15  4494.2  847.53  4558.6  846.37  4579.4  847.96
  4600.2   845.6  4687.4  843.62    4700  845.64  4743.5  843.56  4787.1  844.01
  4793.4  845.61  4814.2  843.56  4864.1  847.32  4872.3   845.8  4907.7     846
  4922.2  840.48  4992.9   828.8  5000.1  824.52  5002.1  824.02  5014.6  824.52
  5057.3  836.46  5065.1  836.58  5078.1  841.49  5102.4  843.66  5214.5  841.71
  5281.7  840.88  5383.1  842.01  5457.6  846.45  5500.6  853.44  5510.1  852.12
#Mann= 6 ,-1 , 0
  4247.7     .05       0  5000.1    .033       0  5014.6     .05       0
  5102.4     .12       0  5214.5     .05       0  5281.7     .12       0
Bank Sta=5000.1,5014.6
XS Rating Curve= 0 ,0
Exp/Cntr=0.3,0.1

Type RM Length L Ch R = 1 ,7897    ,586,586,586
BEGIN DESCRIPTION:
Rush Creek 17.0
END DESCRIPTION:
XS GIS Cut Line= 4
      2270676.06      7194933.56      2270107.04      7195364.57
      2270053.96      7195448.92      2269629.33      7195665.79
#Sta/Elev= 30
  4232.5  856.19    4235  857.87  4264.1  853.97  4270.4  855.44  4278.6  853.35
  4284.9  854.88    4364  852.27  4399.3  848.26  4442.1  849.78  4463.8  845.88
  4534.6  845.57  4549.1  842.07    4570  843.31  4592.6  841.23  4919.5  842.98
  4946.3  834.02  4963.4  824.86  4965.4  824.36  4977.9  824.86  4985.9  830.96
  5007.1   839.4  5104.3   842.6    5221  842.84  5249.4  841.32  5354.7  845.15
  5430.4  854.32    5467  852.66  5489.5  859.57  5519.3     863  5522.8  860.76
#Mann= 6 ,-1 , 0
  4232.5     .05       0  4963.4    .033       0  4977.9     .05       0
  5104.3     .12       0    5221     .05       0  5249.4     .12       0
Bank Sta=4963.4,4977.9
XS Rating Curve= 0 ,0
Exp/Cntr=0.3,0.1

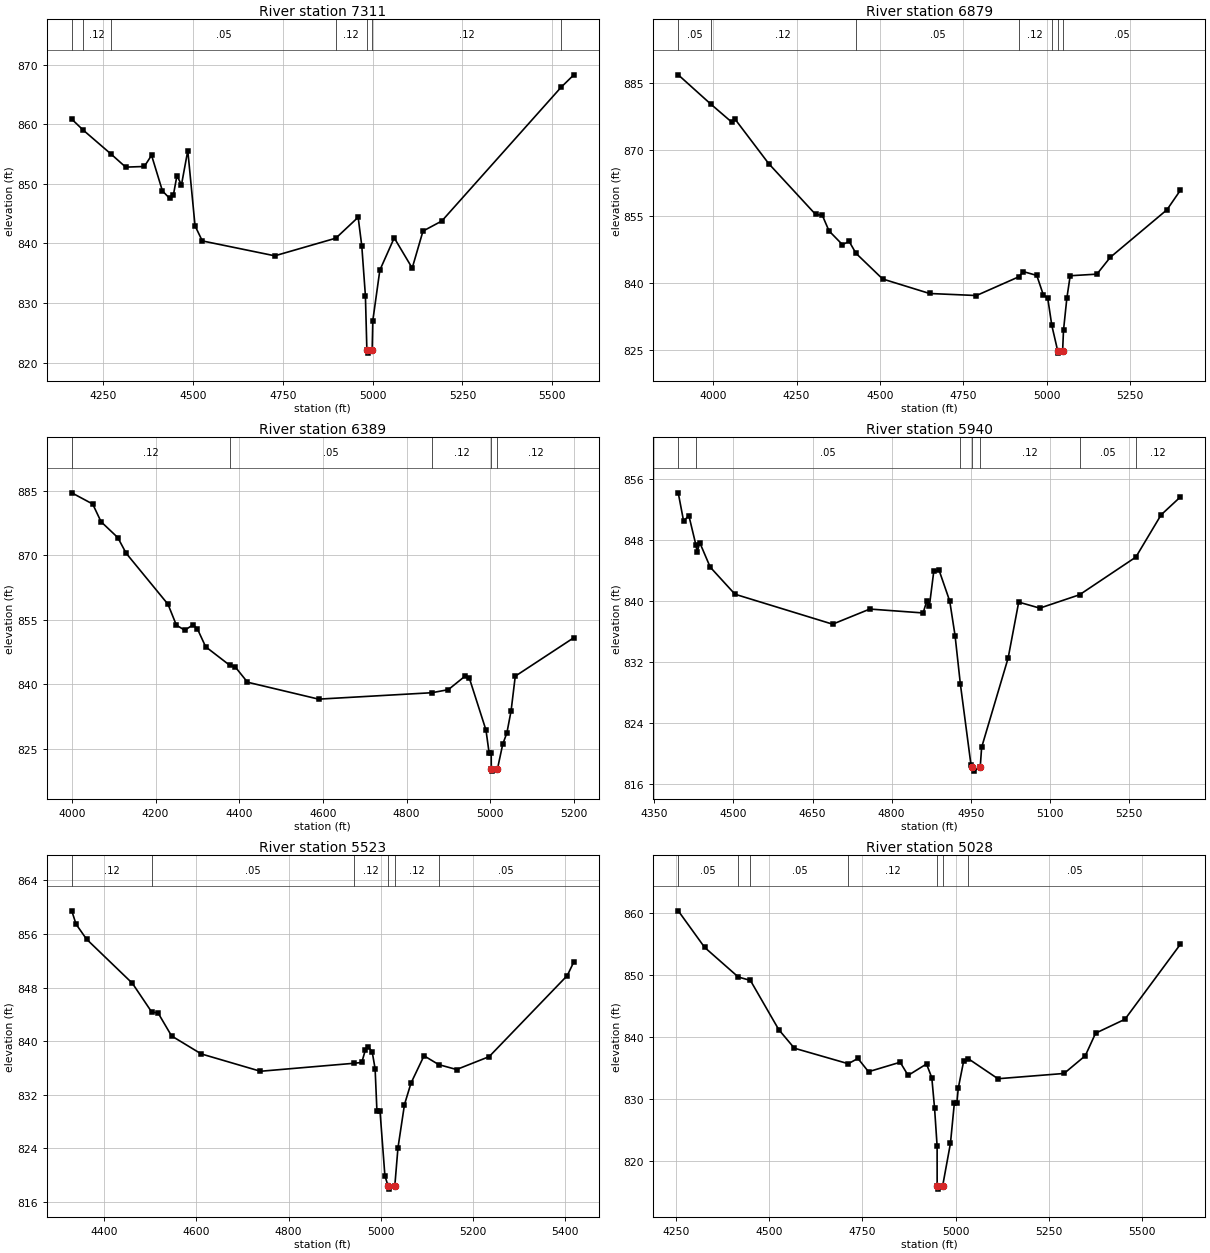
Type RM Length L Ch R = 1 ,7311    ,432,432,432
BEGIN DESCRIPTION:
Rush Creek 16.0
END DESCRIPTION:
XS GIS Cut Line= 3
      2270709.13       7194814.4      2269883.15       7194926.1
      2269319.44      7194951.98
#Sta/Elev= 30
  4162.4  860.84  4193.4  859.05  4272.4  854.95  4312.5  852.79  4364.4   852.9
  4384.5  854.78  4414.8   848.8    4435  847.54  4445.1  848.04  4455.2  851.36
  4467.8  849.82  4485.4  855.57  4505.6  842.94  4525.8  840.41  4727.6  837.91
  4897.6  840.87  4959.7  844.38  4969.8  839.58  4979.9  831.21    4984  822.08
    4986  821.58  4998.7  822.08  5000.5  827.04  5020.1   835.5  5060.1  840.92
  5110.2  835.85  5140.2  842.06  5192.6  843.75  5524.8   866.2  5560.2  868.28
#Mann= 7 ,-1 , 0
  4162.4     .05       0  4193.4     .12       0  4272.4     .05       0
  4897.6     .12       0    4984     .07       0  4998.7     .12       0
  5524.8     .05       0
Bank Sta=4984,4998.7
XS Rating Curve= 0 ,0
Exp/Cntr=0.3,0.1

Type RM Length L Ch R = 1 ,6879    ,490,490,490
BEGIN DESCRIPTION:
Rush Creek 15.0
END DESCRIPTION:
XS GIS Cut Line= 3
      2270928.96        7194410.        2269829.        7194510.
        2269429.        7194510.
#Sta/Elev= 30
  3895.5  886.91  3992.5  880.35  4056.1  876.23  4066.2  876.87  4166.6   866.9
  4307.2  855.44  4327.2  855.26  4347.3  851.74  4387.5  848.64  4407.6  849.37
  4428.1  846.69    4508   840.9  4648.6  837.63  4789.1  837.17    4916  841.39
  4929.7  842.56  4969.9   841.7    4990  837.21  5002.5  836.68    5015  830.42
  5032.6  824.69  5034.6  824.19  5047.3  824.69    5050  829.36    5060  836.57
    5070  841.63    5150  841.99    5190  845.77    5360   856.5    5400  860.87
#Mann= 7 ,-1 , 0
  3895.5     .05       0  3992.5     .12       0  4428.1     .05       0
    4916     .12       0    5015     .05       0  5032.6     .07       0
  5047.3     .05       0
Bank Sta=5032.6,5047.3
XS Rating Curve= 0 ,0
Exp/Cntr=0.3,0.1

Type RM Length L Ch R = 1 ,6389    ,449,449,449
BEGIN DESCRIPTION:
Rush Creek 14.0
END DESCRIPTION:
XS GIS Cut Line= 3
      2270729.02        7194060.        2269729.        7194060.
      2269529.02        7194060.
#Sta/Elev= 30
  3999.6  884.47  4049.6  881.87  4069.6  877.76  4109.6  874.08  4129.6  870.44
  4229.6   858.6  4249.6  853.76  4269.6  852.58  4289.6  853.84  4299.6  852.95
  4319.6  848.74  4377.4  844.42  4389.6  844.14  4419.6  840.51  4589.6  836.58
  4860.3  838.07  4899.6  838.78  4939.6  841.92  4949.6  841.53  4989.6  829.39
  4997.1  824.08  5002.1  824.08  5002.3  820.37  5004.3  819.87    5017  820.37
  5029.6   826.1  5039.6  828.76  5049.6  833.86  5059.6  841.91  5199.6  850.84
#Mann= 5 ,-1 , 0
  3999.6     .12       0  4377.4     .05       0  4860.3     .12       0
  5002.3     .07       0    5017     .12       0
Bank Sta=5002.3,5017
XS Rating Curve= 0 ,0
Exp/Cntr=0.3,0.1

Type RM Length L Ch R = 1 ,5940    ,417,417,417
BEGIN DESCRIPTION:
Rush Creek 13.0
END DESCRIPTION:
XS GIS Cut Line= 3
      2270428.98        7193810.      2269831.67      7193727.18
      2269482.62      7193736.84
#Sta/Elev= 30
  4395.3  854.14  4405.4  850.47  4415.5  851.14  4428.9  847.29  4431.1  846.39
  4436.2  847.61  4455.9  844.42  4502.9  840.87  4688.1  836.95  4758.7  838.93
  4859.7  838.42  4866.7  839.99  4871.7  839.37  4879.9  843.85    4890  844.01
  4910.2  839.97  4920.3  835.46  4930.3  829.16  4950.5  818.54  4953.3  818.22
  4955.3  817.72    4968  818.22  4970.7  820.83    5021  832.53    5041  839.84
    5081  839.05  5156.4   840.8  5263.2  845.73  5311.1  851.26  5347.5  853.59
#Mann= 7 ,-1 , 0
  4395.3     .12       0  4428.9     .05       0  4930.3     .12       0
  4953.3     .07       0    4968     .12       0  5156.4     .05       0
  5263.2     .12       0
Bank Sta=4953.3,4968
XS Rating Curve= 0 ,0
Exp/Cntr=0.3,0.1

Type RM Length L Ch R = 1 ,5523    ,495,495,495
BEGIN DESCRIPTION:
Rush Creek 12.0
END DESCRIPTION:
XS GIS Cut Line= 3
       2270305.5      7192952.46        2269779.        7193360.
      2269478.98      7193660.02
#Sta/Elev= 30
  4329.4  859.45  4338.7  857.46  4361.4  855.23    4461  848.64  4502.6  844.39
  4517.1  844.18  4546.1  840.79  4610.4  838.11    4739  835.52  4941.7  836.71
    4959  836.83  4967.1  838.76  4973.5  839.12  4981.6  838.44    4988   835.9
    4992  829.53  4998.7  829.53  5009.3  819.91  5016.1  818.44  5018.1  817.94
  5030.8  818.44  5037.6  824.08  5051.8  830.56  5065.9  833.75  5094.2  837.83
  5126.2  836.51  5164.9  835.78  5235.6   837.7  5405.3   849.8  5419.5  851.84
#Mann= 6 ,-1 , 0
  4329.4     .12       0  4502.6     .05       0  4941.7     .12       0
  5016.1     .07       0  5030.8     .12       0  5126.2     .05       0
Bank Sta=5016.1,5030.8
XS Rating Curve= 0 ,0
Exp/Cntr=0.3,0.1

Type RM Length L Ch R = 1 ,5028    ,485,485,485
BEGIN DESCRIPTION:
Rush Creek 11.0
END DESCRIPTION:
XS GIS Cut Line= 3
      2269979.03      7192509.97        2269429.        7193010.
      2268979.02      7193409.98
#Sta/Elev= 30
  4256.4  860.35  4327.1  854.46  4417.4  849.68  4449.7  849.14  4525.7  841.21
  4567.6  838.21    4712  835.71  4737.9  836.56  4766.3  834.42  4851.1  835.95
  4872.4  833.83  4921.7  835.67  4935.9  833.45  4943.3  828.54  4950.1  822.44
  4950.2     816  4952.2   815.5  4964.9     816  4985.9   822.9  4996.4  829.44
  5003.1  829.44  5006.9  831.79  5021.1  836.09  5034.1   836.5  5113.1  833.29
  5290.3  834.14  5347.2     837  5374.8  840.63  5453.4  842.87  5601.8  854.94
#Mann= 7 ,-1 , 0
  4256.4     .05       0  4417.4     .12       0  4449.7     .05       0
    4712     .12       0  4950.2     .07       0  4964.9     .12       0
  5034.1     .05       0
Bank Sta=4950.2,4964.9
XS Rating Curve= 0 ,0
Exp/Cntr=0.3,0.1

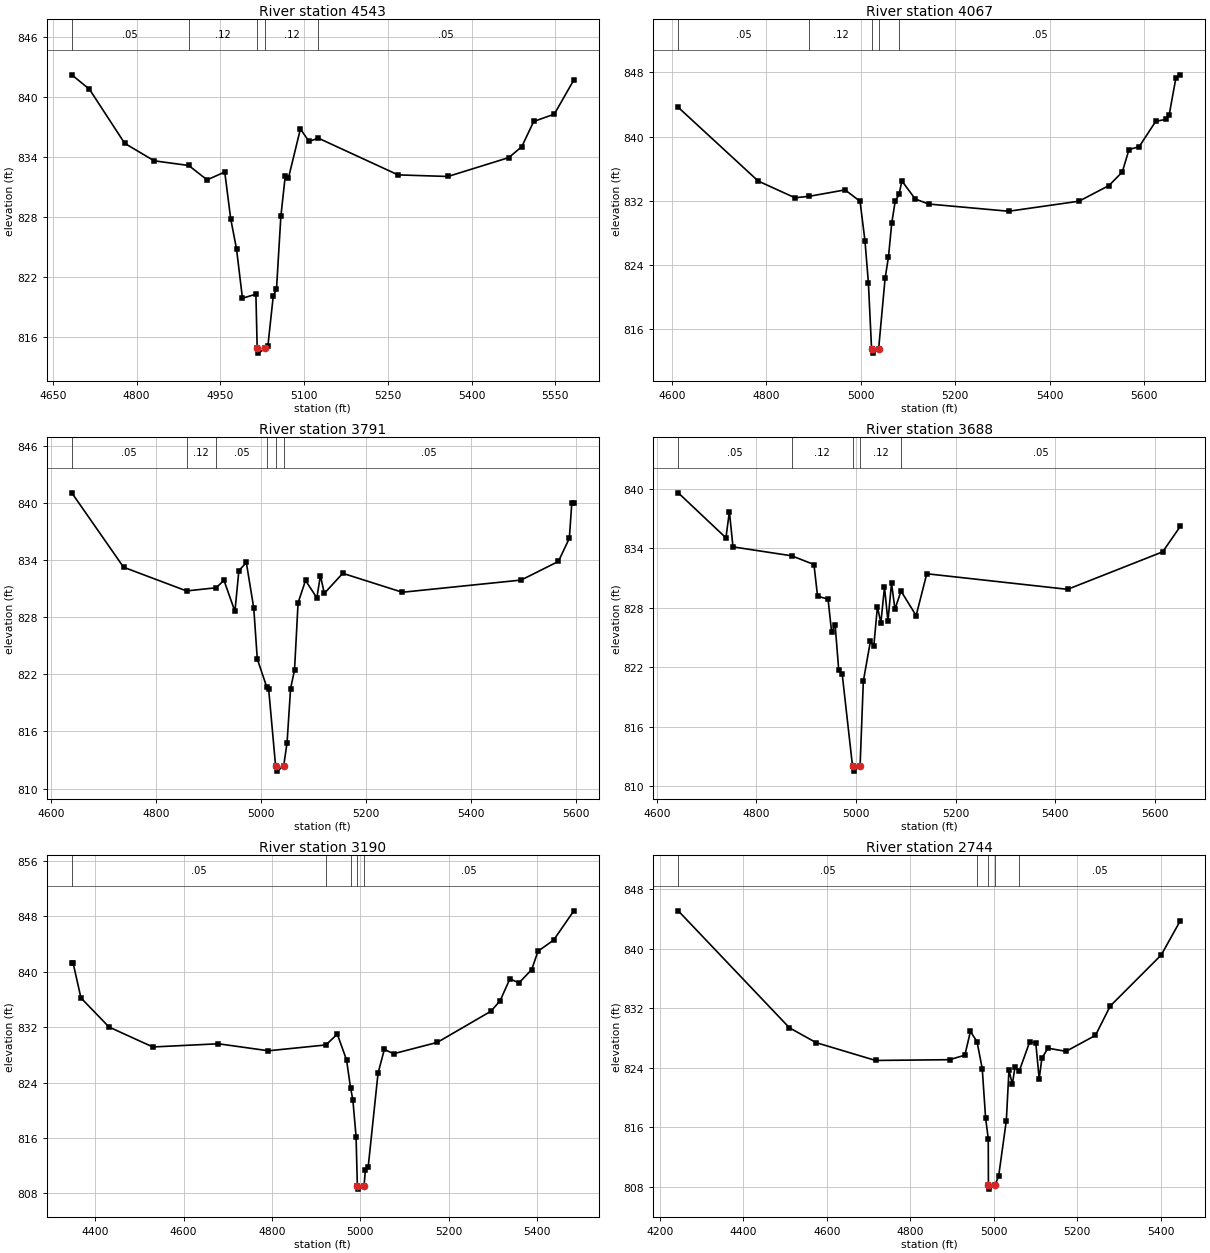
Type RM Length L Ch R = 1 ,4543    ,476,476,476
BEGIN DESCRIPTION:
Rush Creek 10.0
END DESCRIPTION:
XS GIS Cut Line= 3
      2269628.97      7192460.01        2269329.        7192560.
      2268828.99        7192860.
#Sta/Elev= 30
  4683.8  842.21  4715.4  840.77  4778.6  835.35  4831.3   833.6  4893.3  833.13
  4926.2  831.69  4957.8  832.48  4968.4  827.82  4978.9  824.77  4989.5  819.84
  5013.6  820.24  5015.9  814.84  5017.9  814.34  5030.8  814.84    5035  815.01
  5044.7  820.06  5050.5  820.74  5058.3  828.03  5066.1  832.03  5071.9  831.87
  5093.3  836.79  5108.8  835.54  5125.4  835.87  5268.2  832.19  5357.6  832.03
  5466.5  833.92  5489.8  835.01  5511.2  837.54  5548.1  838.27  5583.1   841.7
#Mann= 5 ,-1 , 0
  4683.8     .05       0  4893.3     .12       0  5015.9     .07       0
  5030.8     .12       0  5125.4     .05       0
Bank Sta=5015.9,5030.8
XS Rating Curve= 0 ,0
Exp/Cntr=0.3,0.1

Type RM Length L Ch R = 1 ,4067    ,276,276,276
BEGIN DESCRIPTION:
Rush Creek 9.0
END DESCRIPTION:
XS GIS Cut Line= 3
      2269403.79      7191895.49        2269129.        7192160.
      2268636.18       7192630.7
#Sta/Elev= 30
  4613.6  843.64  4782.9  834.46  4860.6  832.38  4890.8  832.56  4966.8  833.36
  4998.5  831.94    5009  826.97  5016.2  821.76  5022.9  813.53  5024.9  813.03
  5037.8  813.53  5051.5  822.33  5058.7  825.02  5065.6  829.23  5072.9  831.94
  5081.2  832.82    5087  834.48  5115.3  832.23  5143.6   831.6  5313.1   830.7
  5461.9  831.95  5525.4   833.9  5553.7  835.59  5567.9  838.39  5589.3  838.73
  5624.5   841.9  5645.6  842.14  5652.8  842.67    5667  847.25  5676.5  847.69
#Mann= 5 ,-1 , 0
  4613.6     .05       0  4890.8     .12       0  5022.9     .07       0
  5037.8     .12       0  5081.2     .05       0
Bank Sta=5022.9,5037.8
XS Rating Curve= 0 ,0
Exp/Cntr=0.3,0.1

Type RM Length L Ch R = 1 ,3791    ,103,103,103
BEGIN DESCRIPTION:
Rush Creek 8.1
END DESCRIPTION:
XS GIS Cut Line= 2
      2269238.49      7191659.76      2268598.72      7192371.88
#Sta/Elev= 30
  4639.4  841.08  4738.2  833.26  4858.2  830.77  4914.5   831.1  4929.6  831.88
  4950.5  828.62    4958  832.89  4972.2  833.76  4986.4  828.97  4993.1  823.62
  5010.9  820.71  5014.8  820.46  5028.1  812.33  5030.1  811.83  5043.3  812.33
  5049.9  814.82  5056.6  820.51  5064.1  822.44  5070.9  829.52  5085.1  831.87
  5106.7  830.04  5113.5  832.39  5120.9  830.51  5156.1  832.62  5269.7  830.63
  5496.2  831.91  5567.2  833.87  5588.1   836.3  5592.8  840.02  5596.7  840.02
#Mann= 6 ,-1 , 0
  4639.4     .05       0  4858.2     .12       0  4914.5     .05       0
  5010.9     .12       0  5028.1    .033       0  5043.3     .05       0
Bank Sta=5028.1,5043.3
XS Rating Curve= 0 ,0
Exp/Cntr=0.3,0.1

Type RM Length L Ch R = 1 ,3688    ,498,498,498
BEGIN DESCRIPTION:
Rush Creek 8.0
END DESCRIPTION:
XS GIS Cut Line= 3
      2269181.65      7191607.24      2268926.58      7191854.21
      2268475.59       7192326.4
#Sta/Elev= 30
  4642.9   839.6  4738.7  835.06  4745.6  837.71  4752.8  834.15  4870.7  833.25
  4915.4  832.37  4922.6  829.18  4943.7  828.88  4950.9  825.53  4957.9  826.31
  4965.1  821.71    4972  821.36  4992.8  812.04  4994.8  811.54    5008  812.04
  5014.5   820.6  5028.7  824.63  5035.6  824.19  5042.8  828.11  5049.7  826.49
    5057  830.09  5063.9  826.65  5071.1   830.5    5078  827.86  5090.1   829.7
  5120.5  827.22  5141.9  831.44  5424.6  829.87  5615.5  833.65  5650.9  836.22
#Mann= 5 ,-1 , 0
  4642.9     .05       0  4870.7     .12       0  4992.8     .07       0
    5008     .12       0  5090.1     .05       0
Bank Sta=4992.8,5008
XS Rating Curve= 0 ,0
Exp/Cntr=0.3,0.1

Type RM Length L Ch R = 1 ,3190    ,446,446,446
BEGIN DESCRIPTION:
Rush Creek 7.0
END DESCRIPTION:
XS GIS Cut Line= 3
      2268959.31      7191360.84        2268479.        7191810.
      2268109.02      7192114.54
#Sta/Elev= 30
  4346.9  841.24    4350  841.24  4367.7  836.23  4431.3  832.02  4530.4  829.14
  4678.9   829.6  4792.2  828.59  4922.1  829.43  4948.1  830.99  4969.1  827.26
    4978  823.27  4983.3  821.53  4990.6  816.19  4993.5  809.09  4995.5  808.59
  5008.7  809.09  5011.7  811.36  5018.1  811.83  5040.4  825.36  5054.7  828.79
  5075.5  828.16  5174.5   829.8  5295.8   834.3  5316.6   835.8  5338.8  838.98
  5359.6  838.41  5388.3  840.33  5402.6  842.99  5437.8  844.58  5483.7  848.82
#Mann= 5 ,-1 , 0
  4346.9     .05       0  4922.1     .12       0    4978     .05       0
  4993.5     .04       0  5008.7     .05       0
Bank Sta=4993.5,5008.7
XS Rating Curve= 0 ,0
Exp/Cntr=0.3,0.1

Type RM Length L Ch R = 1 ,2744    ,377,377,377
BEGIN DESCRIPTION:
Rush Creek 6.0
END DESCRIPTION:
XS GIS Cut Line= 3
       2268760.3       7190866.3        2268279.        7191460.
       2268009.8      7191806.16
#Sta/Elev= 30
  4244.2  845.07  4510.6  829.37  4574.5  827.38  4716.8  824.99  4894.2  825.09
  4930.9   825.7  4944.1  828.88    4960  827.51  4972.5  823.88  4980.5  817.28
  4986.9  814.48  4987.3  808.22  4989.3  807.72  5002.5  808.22  5011.7  809.42
  5030.2  816.92  5036.5  823.67  5044.7  821.79    5051  824.14  5061.4  823.61
  5086.3   827.5  5100.8  827.33  5108.9  822.51  5115.3  825.26  5129.7  826.64
  5173.2  826.21  5243.8  828.36  5279.1  832.29  5401.2  839.14    5447  843.74
#Mann= 5 ,-1 , 0
  4244.2     .05       0    4960     .12       0  4987.3     .07       0
  5002.5     .12       0  5061.4     .05       0
Bank Sta=4987.3,5002.5
XS Rating Curve= 0 ,0
Exp/Cntr=0.3,0.1

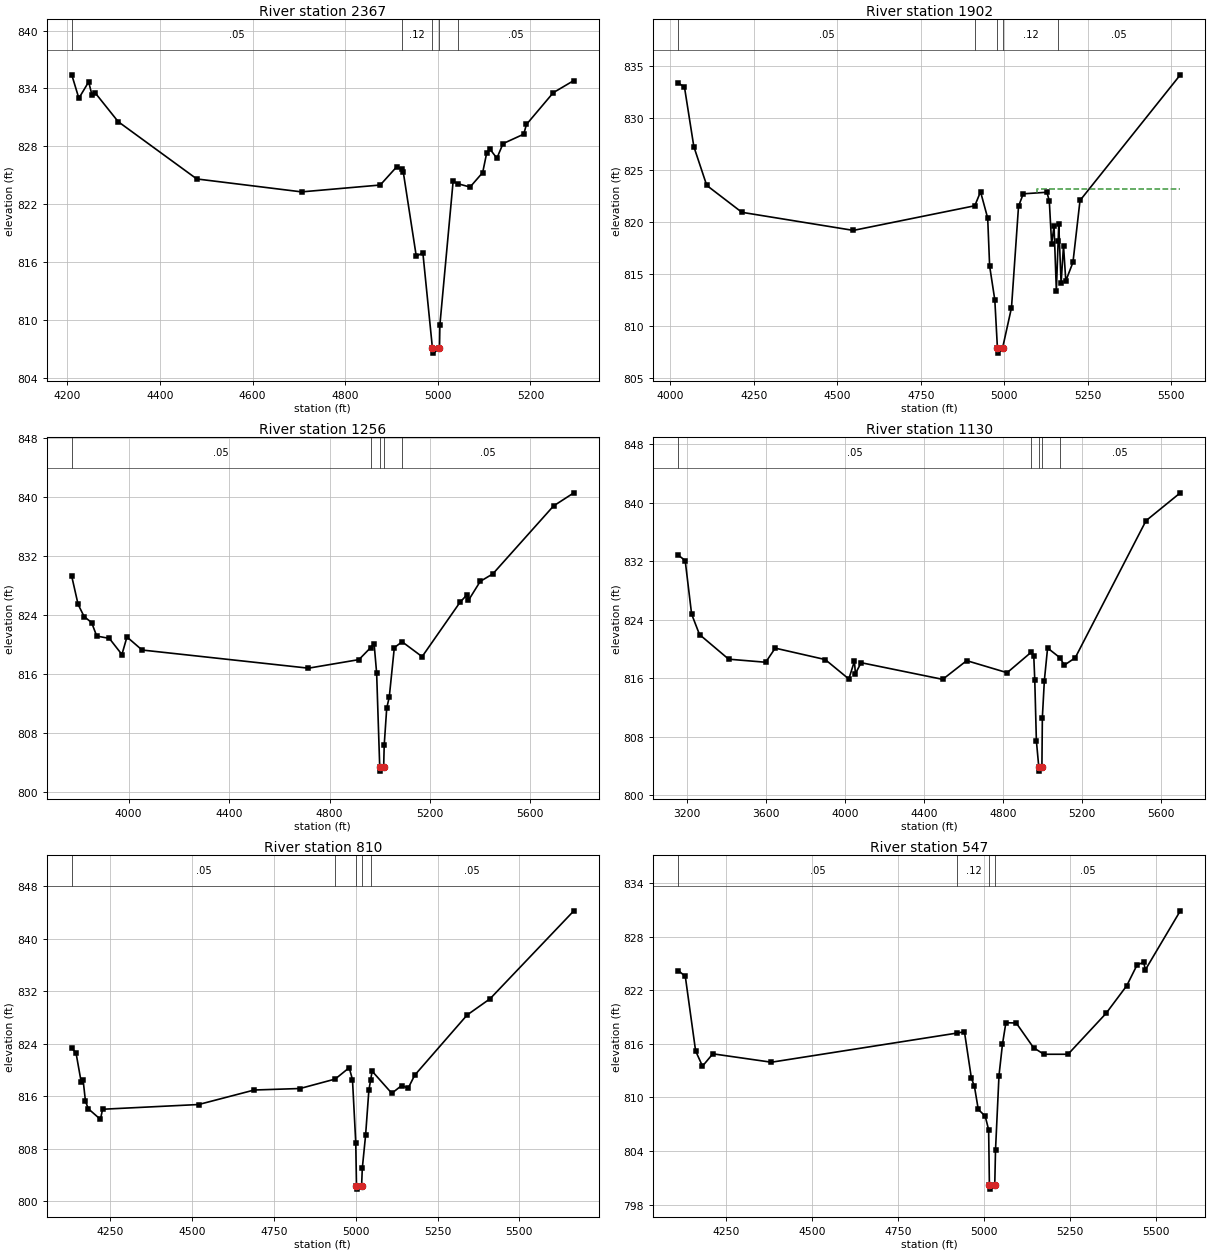
Type RM Length L Ch R = 1 ,2367    ,465,465,465
BEGIN DESCRIPTION:
Rush Creek 5.0
END DESCRIPTION:
XS GIS Cut Line= 3
      2268590.72      7190650.09      2268031.14      7191214.17
      2267878.98      7191460.04
#Sta/Elev= 30
  4209.9  835.41  4225.2  832.98  4246.4  834.68  4253.5  833.31  4260.6  833.53
    4310  830.56  4479.7  824.62    4706  823.28  4875.7  823.99  4911.1  825.87
  4922.1  825.65  4925.3  825.38  4953.5  816.61  4967.7  816.97  4988.4  807.07
  4990.4  806.57  5003.6  807.07  5004.5  809.52    5033  824.36  5044.5  824.11
  5069.6  823.78  5096.8  825.28  5105.4  827.29  5112.2  827.73  5127.5  826.77
  5140.7  828.28  5185.4  829.26  5191.3  830.27  5249.2  833.56  5293.6  834.82
#Mann= 5 ,-1 , 0
  4209.9     .05       0  4922.1     .12       0  4988.4     .07       0
  5003.6     .12       0  5044.5     .05       0
Bank Sta=4988.4,5003.6
XS Rating Curve= 0 ,0
Exp/Cntr=0.3,0.1

Type RM Length L Ch R = 1 ,1902    ,646,646,646
BEGIN DESCRIPTION:
Rush Creek 4.0
END DESCRIPTION:
XS GIS Cut Line= 4
      2268474.45      7190380.51      2267996.89      7190521.18
      2267752.03      7190927.59      2267385.11      7191310.57
#Sta/Elev= 30
  4023.9  833.35  4042.5  832.97  4070.6  827.23  4109.2   823.5  4214.4  820.91
  4548.1  819.17  4911.5  821.54  4928.7  822.89  4950.1  820.35  4955.9  815.74
  4971.4  812.48  4979.2  807.86  4981.2  807.36  4994.7  807.86  5021.3  811.73
  5042.4  821.49  5056.5  822.69  5127.3  822.84  5134.5  822.01  5141.4   817.9
  5148.7  819.59  5155.6  813.38    5161  818.15  5162.8  819.74  5169.8  814.07
    5177  817.69  5183.9  814.31  5205.3   816.1  5226.4  822.05  5526.6  834.14
#Mann= 5 ,-1 , 0
  4023.9     .05       0  4911.5     .12       0  4979.2     .07       0
  4994.7     .12       0    5161     .05       0
#XS Ineff= 2 , 0
       0                    5099       0   823.2
Permanent Ineff=
       F       F
Bank Sta=4979.2,4994.7
XS Rating Curve= 0 ,0
Exp/Cntr=0.3,0.1

Type RM Length L Ch R = 1 ,1256    ,126,126,126
BEGIN DESCRIPTION:
Rush Creek 3.0
END DESCRIPTION:
XS GIS Cut Line= 3
      2268387.92      7190317.35      2267400.31      7190228.91
       2267286.4       7191230.4
#Sta/Elev= 30
  3773.4  829.21  3798.6  825.42  3822.5  823.78  3852.6  822.95  3872.7  821.13
  3922.9  820.82  3973.1  818.63  3993.2  821.01  4053.4  819.24  4716.1  816.78
    4917  817.94  4964.1  819.58  4977.4   820.1  4987.5  816.13  4999.9  803.33
  5001.9  802.83  5015.4  803.33  5017.7  806.36  5027.7  811.38  5037.8  812.86
  5057.9  819.56  5088.9  820.36  5168.6  818.34  5319.6  825.71  5348.2  826.76
  5353.3  825.98  5400.1  828.54  5450.4  829.56    5692  838.76  5772.9  840.54
#Mann= 5 ,-1 , 0
  3773.4     .05       0  4964.1     .12       0  4999.9     .07       0
  5015.4     .12       0  5088.9     .05       0
Bank Sta=4999.9,5015.4
XS Rating Curve= 0 ,0
Exp/Cntr=0.3,0.1

Type RM Length L Ch R = 1 ,1130    ,320,320,320
BEGIN DESCRIPTION:
Rush Creek 2.15
END DESCRIPTION:
XS GIS Cut Line= 3
      2268552.93      7190221.99      2267331.54      7189886.77
      2267147.13      7191151.95
#Sta/Elev= 30
  3154.2  832.85  3189.4  832.11    3222  824.79    3262  821.99  3409.8  818.62
  3597.6   818.2  3645.7  820.13  3899.1  818.57    4019  815.91  4047.3  818.35
  4052.4  816.64  4081.2  818.14  4494.8  815.86  4616.4  818.42  4821.4  816.77
  4943.4  819.57  4956.5  819.05  4961.5  815.77  4969.7  807.46  4982.1  803.81
  4984.1  803.31  4997.7  803.81    5000  810.64  5010.1   815.7  5026.5  820.15
  5088.6  818.83  5111.2   817.8  5166.6  818.81  5525.5  837.56  5699.3  841.37
#Mann= 5 ,-1 , 0
  3154.2     .05       0  4943.4     .12       0  4982.1     .07       0
  4997.7     .12       0  5088.6     .05       0
Bank Sta=4982.1,4997.7
XS Rating Curve= 0 ,0
Exp/Cntr=0.3,0.1

Type RM Length L Ch R = 1 ,810     ,263,263,263
BEGIN DESCRIPTION:
Rush Creek 2.1
END DESCRIPTION:
XS GIS Cut Line= 3
      2266727.99      7189643.41        2266923.      7189995.71
      2266935.71      7191125.76
#Sta/Elev= 30
  4133.4  823.26  4146.2  822.62  4162.3   818.1    4168  818.46  4175.2   815.2
    4184  814.06  4220.9  812.45  4227.5  813.99  4520.7  814.71  4690.4  816.92
  4830.4  817.15  4937.6  818.59  4980.4  820.32  4990.4  818.49  5000.4  808.89
  5002.6  802.32  5004.6  801.82  5018.2  802.32  5020.4  805.01  5030.4  810.02
  5040.4  816.87  5045.7  818.42  5050.4  819.79  5110.4  816.42  5140.4   817.6
  5160.4   817.2  5180.4  819.18  5340.4  828.35  5410.4  830.82  5666.2  844.22
#Mann= 5 ,-1 , 0
  4133.4     .05       0  4937.6     .12       0  5002.6     .07       0
  5018.2     .12       0  5045.7     .05       0
Bank Sta=5002.6,5018.2
XS Rating Curve= 0 ,0
Exp/Cntr=0.3,0.1

Type RM Length L Ch R = 1 ,547     ,471,471,471
BEGIN DESCRIPTION:
Rush Creek 2.0
END DESCRIPTION:
XS GIS Cut Line= 3
      2266678.25      7189619.57      2266704.52      7190231.09
      2266635.68       7191075.2
#Sta/Elev= 30
  4111.1   824.2  4131.6  823.55  4161.6   815.2  4181.6   813.5  4211.6  814.88
  4381.8  813.94  4922.6  817.21  4942.8  817.35  4962.9  812.17  4971.8  811.24
    4983  808.66    5003  807.91  5013.1  806.39  5015.3  800.24  5017.3  799.74
  5030.9  800.24  5033.1  804.13  5043.2  812.45  5053.2  815.93  5063.2  818.36
  5093.3  818.33  5143.5  815.57  5173.6  814.83  5243.8  814.83  5354.2   819.4
  5414.4   822.5  5444.5  824.83  5463.7  825.12  5468.7  824.29  5570.1  830.88
#Mann= 4 ,-1 , 0
  4111.1     .05       0  4922.6     .12       0  5015.3     .07       0
  5030.9     .05       0
Bank Sta=5015.3,5030.9
XS Rating Curve= 0 ,0
Exp/Cntr=0.3,0.1

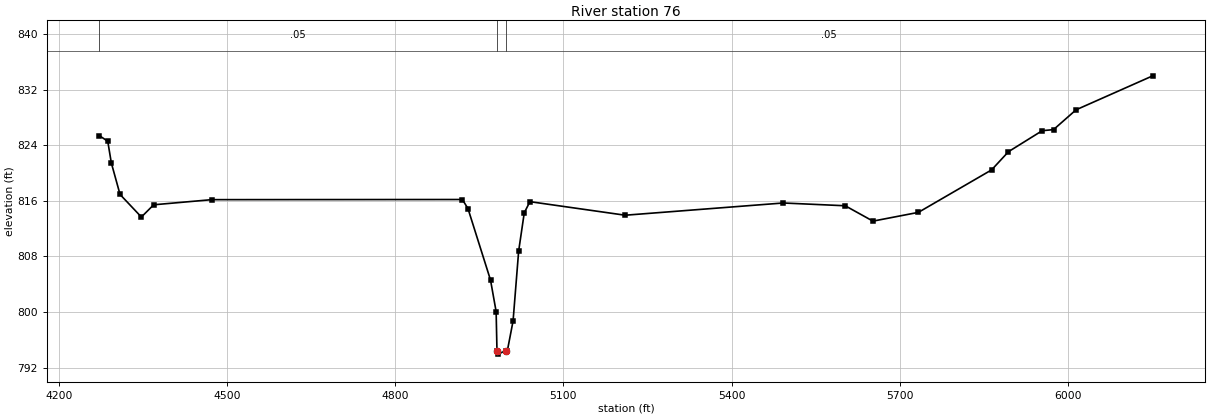
Type RM Length L Ch R = 1 ,76      ,0,0,0
BEGIN DESCRIPTION:
Rush Creek 1.0
END DESCRIPTION:
XS GIS Cut Line= 3
      2266560.79      7189601.15      2266290.29      7190102.56
      2266408.78      7191406.26
#Sta/Elev= 30
  4272.5  825.37  4287.5  824.56  4293.9  821.44  4309.4  816.91  4347.5  813.66
  4369.4  815.42  4473.2  816.16    4920  816.18    4930  814.87  4970.2  804.59
  4980.2  800.06  4981.7  794.44  4983.7  793.94  4997.3  794.44  5000.3  794.46
  5010.4   798.7  5020.4  808.79  5030.4  814.28  5040.5  815.87  5210.4  813.92
  5492.3  815.68  5602.8  815.28  5652.3  813.07  5733.3  814.33  5863.9  820.44
    5894  823.06  5954.2  826.08  5974.3  826.23  6014.5  829.08  6151.3  833.97
#Mann= 3 ,-1 , 0
  4272.5     .05       0  4981.7    .035       0  4997.3     .05       0
Bank Sta=4981.7,4997.3
XS Rating Curve= 0 ,0
Exp/Cntr=0.3,0.1

Chan Stop Cuts=-1
Use User Specified Reach Order=0
Composite Channel Slope=5