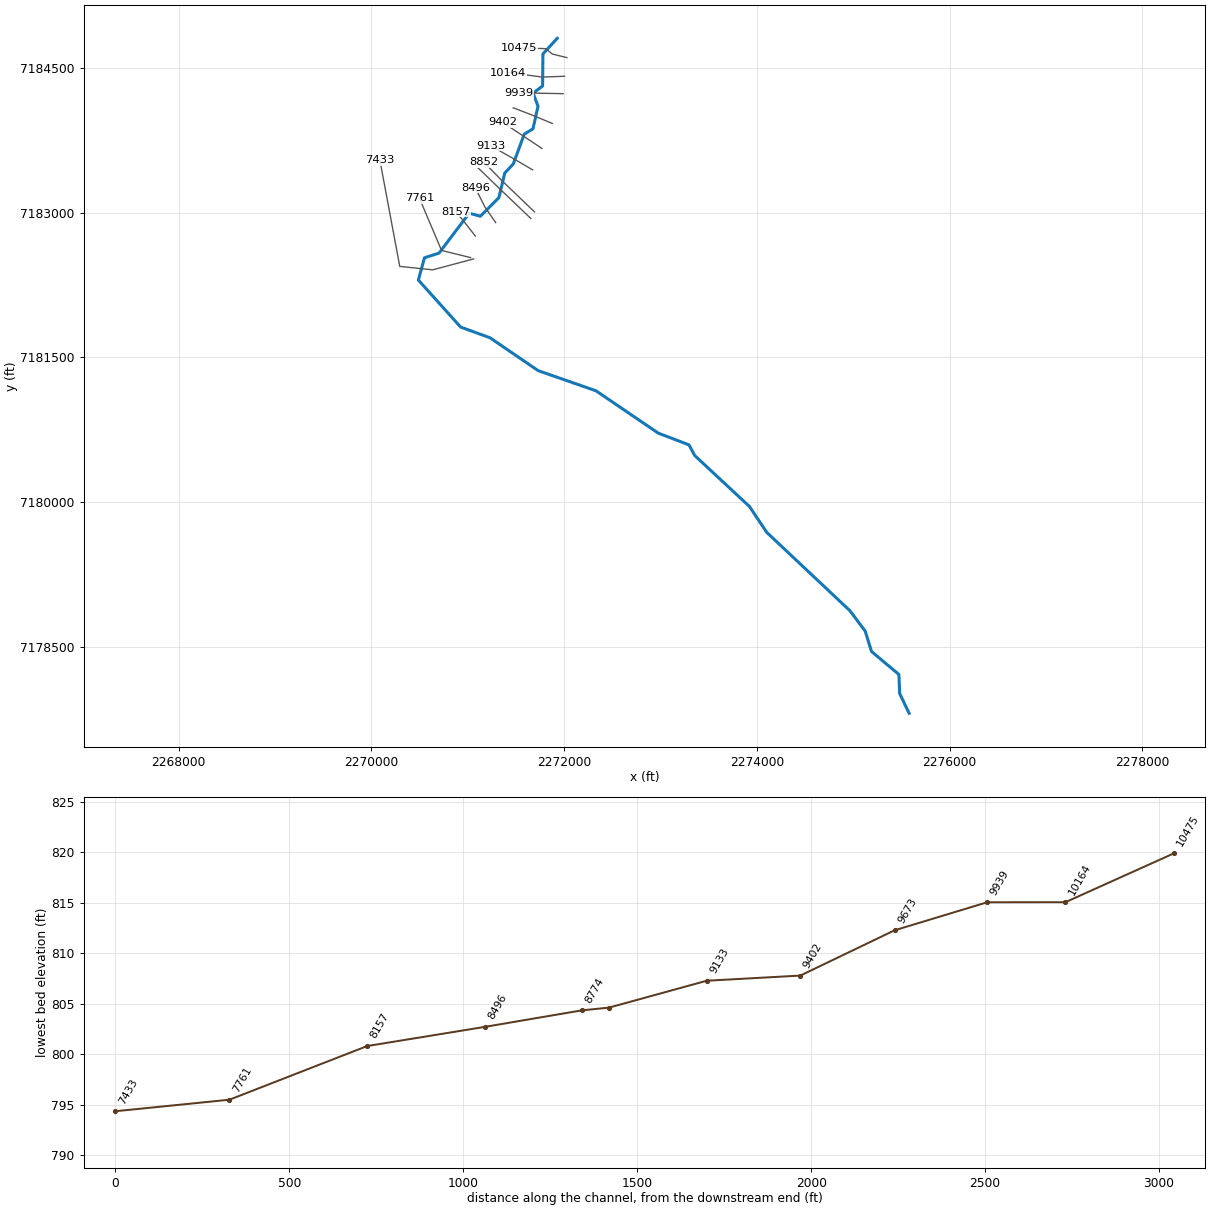
--- Sisal Creek.prj (project) ---

Proj Title=Sisal Creek Base Level Engineering
Current Plan=p01
Default Exp/Contr=0.3,0.1
English Units
Geom File=g01
Flow File=f01
Plan File=p01
Y Axis Title=Elevation
X Axis Title(PF)=Main Channel Distance
X Axis Title(XS)=Station
BEGIN DESCRIPTION:
Sisal Creek
END DESCRIPTION:
DSS Export Rating Curves= 0
DSS Export Rating Curve Sorted= 0
DSS Export Volume Flow Curves= 0
DXF OffsetX= 0
DXF OffsetY= 0
DXF ScaleX= 1
DXF ScaleY= 10

--- Sisal Creek.p01 (plan) ---

Plan Title=Multiple Run
Short Identifier=Multiple
Geom File=g01
Flow File=f01
Subcritical Flow
K Sum by GR= 0
Std Step Tol= 0.01
Critical Tol= 0.01
Num of Std Step Trials= 20
Max Error Tol= 0.3
Flow Tol Ratio= 0.001
Split Flow NTrial= 30
Split Flow Tol= 0.02
Split Flow Ratio= 0.02
Log Output Level= 0
Friction Slope Method= 1
Unsteady Friction Slope Method= 2
Unsteady Bridges Friction Slope Method= 1
Parabolic Critical Depth
Global Vel Dist=  1 , 1 , 1
Global Log Level= 0
CheckData=True
Encroach Param= -1, 0, 0, 0
BEGIN DESCRIPTION:
Multiple Run
END DESCRIPTION:

--- Sisal Creek.f01 (steady flow) ---

Flow Title=Multiple
Program Version=4.10
Number of Profiles= 7
Profile Names=10-year,25-year,50-year,1pct_min,100-year,1pct_plu,500-year
River Rch & RM=Sisal Creek,Reach-1         ,10475
     434     584     707     425     848    1693    1224
Boundary for River Rch & Prof#=Sisal Creek,Reach-1         , 1
Up Type= 0
Dn Type= 3
Dn Slope=0.007
Boundary for River Rch & Prof#=Sisal Creek,Reach-1         , 2
Up Type= 0
Dn Type= 3
Dn Slope=0.007
Boundary for River Rch & Prof#=Sisal Creek,Reach-1         , 3
Up Type= 0
Dn Type= 3
Dn Slope=0.007
Boundary for River Rch & Prof#=Sisal Creek,Reach-1         , 4
Up Type= 0
Dn Type= 3
Dn Slope=0.007
Boundary for River Rch & Prof#=Sisal Creek,Reach-1         , 5
Up Type= 0
Dn Type= 3
Dn Slope=0.007
Boundary for River Rch & Prof#=Sisal Creek,Reach-1         , 6
Up Type= 0
Dn Type= 3
Dn Slope=0.007
Boundary for River Rch & Prof#=Sisal Creek,Reach-1         , 7
Up Type= 0
Dn Type= 3
Dn Slope=0.007
DSS Import GetInterval= 0
DSS Import GetPeak= 0
DSS Import FillOption= 0

--- Sisal Creek.g01 (geometry) ---

Geom Title=Existing Conditions
Program Version=4.10

River Reach=Sisal Creek     ,Reach-1
Reach XY= 30
        2271929.        7184810.      2271780.62      7184648.18
      2271776.99      7184315.68      2271678.86      7184241.26
       2271729.8      7184104.97      2271677.34      7183871.84
      2271586.79      7183816.43      2271473.15      7183507.71
      2271384.54      7183412.42      2271323.58      7183157.33
      2271131.54      7182965.01       2271015.6      7182996.47
      2270702.89      7182582.72      2270551.66      7182534.02
      2270488.15      7182303.27      2270926.57      7181815.52
      2271231.42      7181704.46      2271730.58      7181363.82
       2272331.3      7181154.17      2272976.58      7180715.54
      2273296.05      7180593.51      2273355.27      7180483.12
      2273923.35      7179954.37      2274102.01      7179686.53
      2274965.51      7178873.56      2275123.48      7178662.43
      2275189.74      7178450.29      2275473.54      7178212.45
      2275481.24      7178015.93        2275579.        7177810.

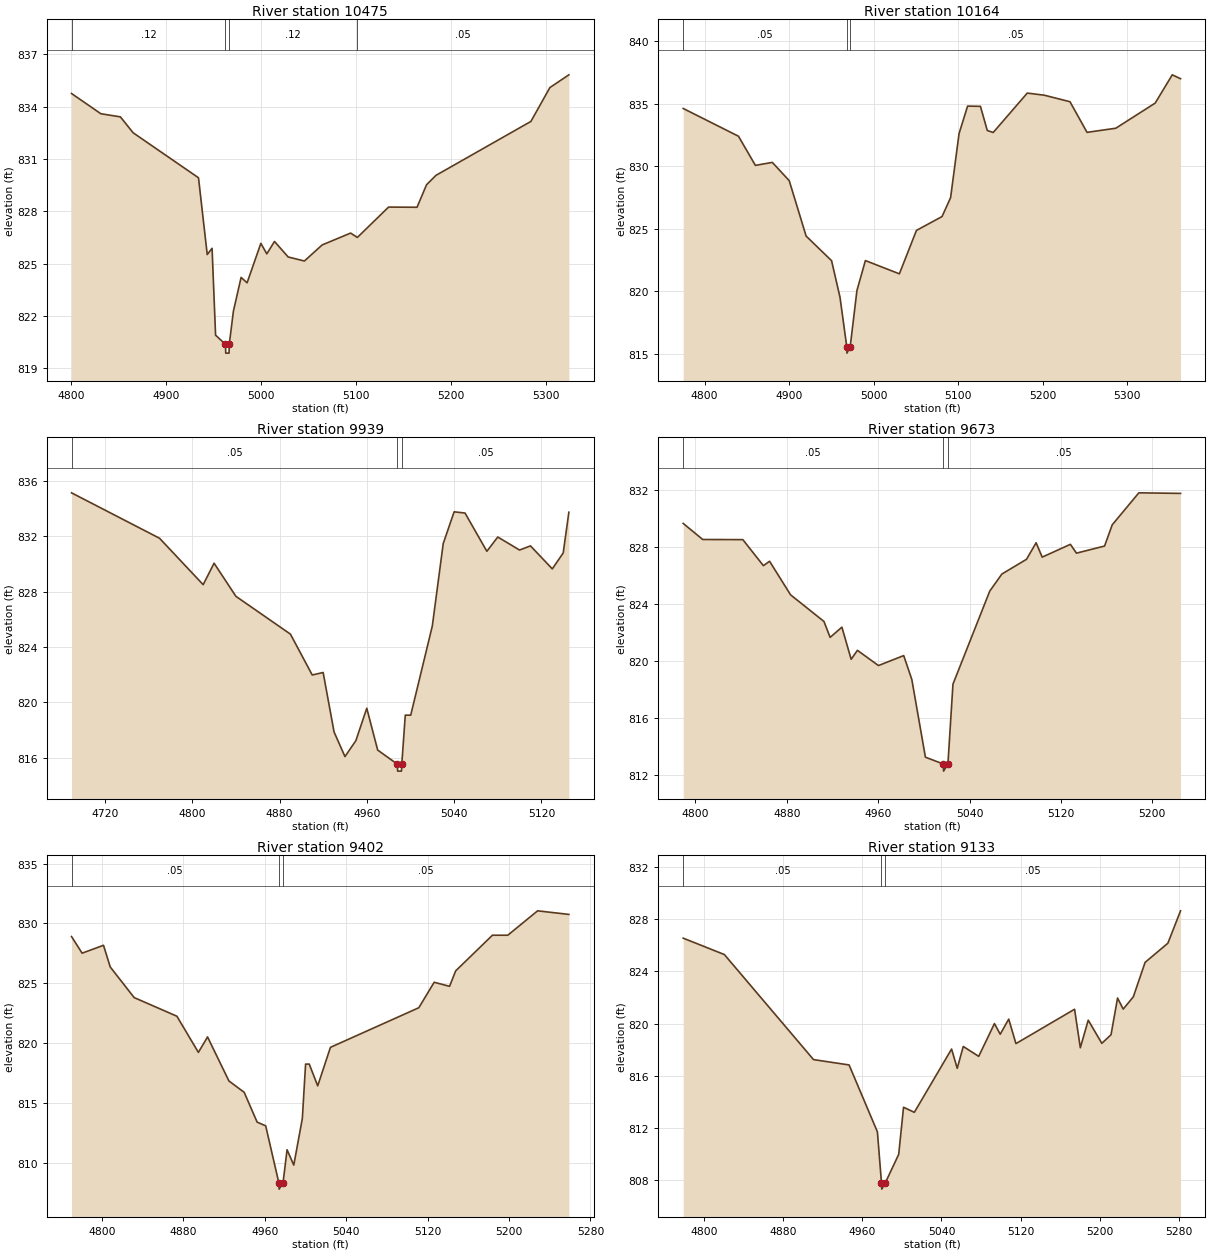
Type RM Length L Ch R = 1 ,10475   ,311,311,311
BEGIN DESCRIPTION:
Sisal Creek 26.0
END DESCRIPTION:
XS GIS Cut Line= 4
      2272028.98      7184610.01      2271879.05      7184646.77
       2271807.7      7184703.23      2271529.04        7184710.
#Sta/Elev= 30
  4800.2  834.75  4831.1  833.59  4851.7  833.41  4865.1   832.5    4934  829.92
  4943.2  825.52  4948.3  825.88    4952   820.9  4962.4  820.37  4962.7  819.87
  4966.2  819.87  4966.4  820.37  4970.8  822.28  4978.9  824.21  4985.2   823.9
  4999.7  826.16    5006  825.56  5014.1  826.27  5028.5  825.38  5045.6  825.15
  5064.3  826.07  5094.3  826.75  5101.4   826.5  5134.3  828.24  5164.3  828.23
  5174.3  829.52  5184.3  830.06  5284.3  833.15  5304.3  835.09  5324.3  835.82
#Mann= 4 ,-1 , 0
  4800.2     .12       0  4962.4     .07       0  4966.4     .12       0
  5101.4     .05       0
Bank Sta=4962.4,4966.4
XS Rating Curve= 0 ,0
Exp/Cntr=0.3,0.1

Type RM Length L Ch R = 1 ,10164   ,225,225,225
BEGIN DESCRIPTION:
Sisal Creek 25.0
END DESCRIPTION:
XS GIS Cut Line= 3
      2272004.35      7184416.79      2271775.62      7184408.13
       2271419.3      7184455.19
#Sta/Elev= 30
  4774.6  834.61    4840  832.39    4860  830.06    4880   830.3    4900  828.84
    4920  824.41  4950.1  822.44  4960.1  819.51  4968.1  815.55  4968.3  815.05
  4972.1  815.55  4980.1  820.05  4990.1  822.45  5030.3  821.39  5050.5  824.86
  5080.8  825.97  5090.9  827.48  5100.9   832.6    5111   834.8  5126.2  834.78
  5134.3  832.85  5141.3  832.69  5181.6  835.84  5201.8  835.67  5232.1  835.15
  5252.3   832.7  5286.3  833.03  5332.9  835.04  5353.1   837.3  5362.9  836.99
#Mann= 3 ,-1 , 0
  4774.6     .05       0  4968.1    .033       0  4972.1     .05       0
Bank Sta=4968.1,4972.1
XS Rating Curve= 0 ,0
Exp/Cntr=0.3,0.1

Type RM Length L Ch R = 1 ,9939    ,266,266,266
BEGIN DESCRIPTION:
Sisal Creek 24.0
END DESCRIPTION:
XS GIS Cut Line= 3
       2271989.7      7184236.13      2271683.53      7184241.86
      2271533.75      7184241.86
#Sta/Elev= 30
  4689.2  835.13  4769.9  831.85  4809.9   828.5  4819.9  830.05  4839.9  827.66
  4889.9  824.93  4909.9  821.98  4919.9  822.16  4929.9  817.87  4939.9  816.09
  4949.9  817.24  4959.9  819.58  4969.9  816.56    4988  815.54  4988.2  815.04
  4991.7  815.04    4992  815.54  4995.2  819.08  5000.2  819.08    5020  825.52
    5030  831.47    5040  833.76    5050  833.67    5070  830.91    5080  831.94
    5100     831    5110   831.3    5130  829.64    5140  830.79  5145.2  833.73
#Mann= 3 ,-1 , 0
  4689.2     .05       0    4988     .04       0    4992     .05       0
Bank Sta=4988,4992
XS Rating Curve= 0 ,0
Exp/Cntr=0.3,0.1

Type RM Length L Ch R = 1 ,9673    ,271,271,271
BEGIN DESCRIPTION:
Sisal Creek 23.0
END DESCRIPTION:
XS GIS Cut Line= 3
      2271877.14      7183927.28        2271679.        7184010.
      2271473.19       7184089.4
#Sta/Elev= 30
  4789.4  829.68  4806.5  828.55  4841.6  828.54  4859.6  826.71    4865  827.02
  4883.4  824.66  4912.6  822.79    4918  821.67  4928.3  822.39  4936.4  820.13
  4941.9  820.76  4960.3  819.69  4982.4  820.39  4989.5  818.71  5001.4  813.25
  5017.1  812.77  5017.3  812.27  5021.1  812.77  5025.5  818.38  5057.7  824.92
  5068.3  826.12  5089.9  827.16  5098.3  828.32  5103.6  827.31  5128.3  828.21
  5133.6  827.59  5158.2  828.09  5164.9  829.58  5188.2  831.83  5224.7  831.79
#Mann= 3 ,-1 , 0
  4789.4     .05       0  5017.1    .033       0  5021.1     .05       0
Bank Sta=5017.1,5021.1
XS Rating Curve= 0 ,0
Exp/Cntr=0.3,0.1

Type RM Length L Ch R = 1 ,9402    ,269,269,269
BEGIN DESCRIPTION:
Sisal Creek 22.0
END DESCRIPTION:
XS GIS Cut Line= 3
      2271770.61      7183667.85      2271578.74      7183795.89
      2271363.35       7183937.6
#Sta/Elev= 30
  4770.3   828.9  4780.7  827.51  4801.7  828.17  4808.3  826.36  4831.8   823.8
  4873.8  822.24  4894.9  819.22  4903.9  820.51  4924.9  816.83  4939.9  815.88
  4952.6  813.39    4961  813.08    4974  808.29  4974.2  807.79    4978  808.29
    4982  811.08  4988.6   809.8    4997  813.69  5000.2  818.24  5003.8  818.24
  5012.1  816.42  5024.6  819.64  5111.4  822.95  5126.5  825.08  5141.6  824.74
  5147.6  826.03  5183.7  829.01  5198.8  829.01  5228.1  831.05  5258.8  830.75
#Mann= 3 ,-1 , 0
  4770.3     .05       0    4974    .033       0    4978     .05       0
Bank Sta=4974,4978
XS Rating Curve= 0 ,0
Exp/Cntr=0.3,0.1

Type RM Length L Ch R = 1 ,9133    ,281,281,281
BEGIN DESCRIPTION:
Sisal Creek 21.0
END DESCRIPTION:
XS GIS Cut Line= 3
      2271673.56      7183446.16        2271479.        7183560.
      2271237.81      7183695.78
#Sta/Elev= 30
  4779.2  826.56  4820.8   825.3  4910.8  817.23  4946.7  816.82  4975.3  811.68
  4979.4  807.78  4979.7  807.28  4983.4  807.78  4996.8  809.95  5001.7  813.57
  5012.6  813.18  5050.2  818.04  5055.9  816.56    5062  818.24  5077.6  817.48
  5093.5     820  5099.3  819.18  5107.9  820.34  5115.2  818.46  5174.4   821.1
  5180.2  818.14  5188.2  820.26  5201.9  818.48  5211.2  819.14  5217.8  821.96
  5223.5  821.11  5233.7  822.05  5245.6   824.7  5268.6  826.17  5281.4  828.66
#Mann= 3 ,-1 , 0
  4779.2     .05       0  4979.4     .04       0  4983.4     .05       0
Bank Sta=4979.4,4983.4
XS Rating Curve= 0 ,0
Exp/Cntr=0.3,0.1

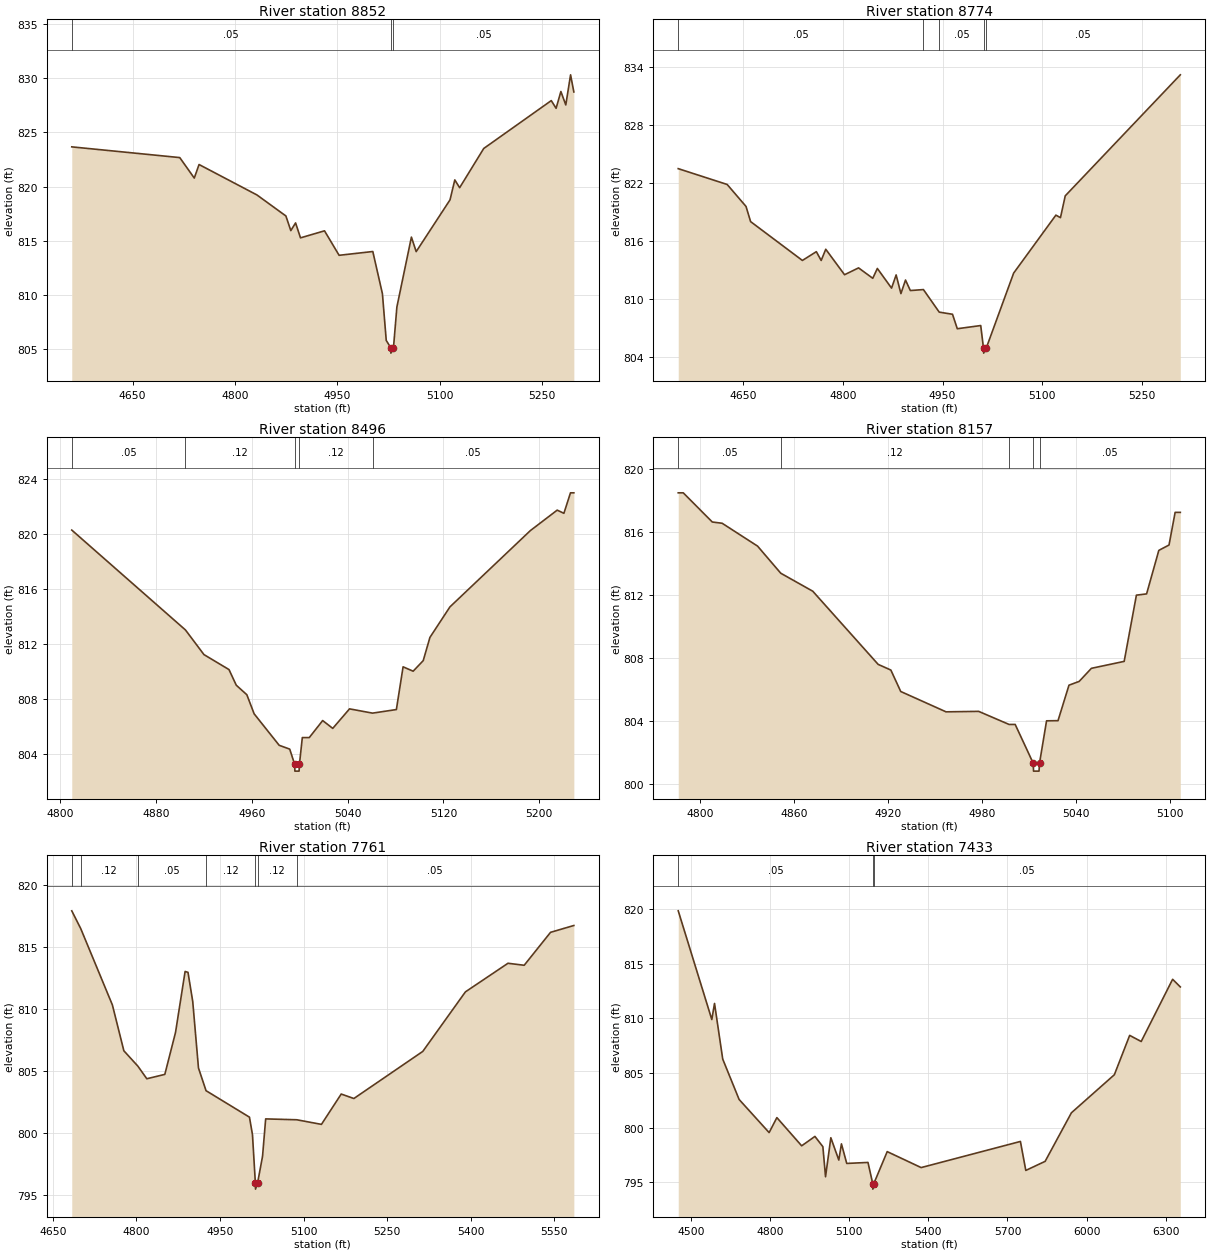
Type RM Length L Ch R = 1 ,8852    ,78,78,78
BEGIN DESCRIPTION:
Sisal Creek 20.0
END DESCRIPTION:
XS GIS Cut Line= 3
      2271692.94      7183009.99      2271356.47      7183332.76
      2271167.62      7183525.37
#Sta/Elev= 30
  4560.8  823.66  4719.1  822.67  4740.4  820.78  4747.4  822.03  4832.3  819.22
  4874.7  817.28  4881.9  815.93  4888.9  816.64  4896.1  815.26  4931.3  815.91
  4952.7  813.65  5002.1     814  5016.2   810.1  5021.8  805.79  5028.4  805.12
  5028.6  804.62  5032.4  805.12  5037.4  808.88  5058.7  815.33  5065.7  813.99
  5115.3  818.77  5122.3  820.61  5129.4  819.89  5164.7  823.51  5263.7  827.93
  5270.8  827.22  5277.8  828.77    5285  827.53    5292  830.31  5296.8  828.73
#Mann= 3 ,-1 , 0
  4560.8     .05       0  5028.4     .04       0  5032.4     .05       0
Bank Sta=5028.4,5032.4
XS Rating Curve= 0 ,0
Exp/Cntr=0.3,0.1

Type RM Length L Ch R = 1 ,8774    ,278,278,278
BEGIN DESCRIPTION:
Sisal Creek 19.1
END DESCRIPTION:
XS GIS Cut Line= 3
      2271654.77      7182941.62      2271317.89      7183263.57
       2271109.2      7183465.25
#Sta/Elev= 30
  4551.8  823.48  4625.5  821.84  4653.9  819.56  4660.8  817.99  4738.8  813.96
  4759.8  814.87  4767.1  813.96    4774  815.12  4802.3  812.48  4823.4  813.19
  4844.8  812.11  4851.7  813.13  4873.1  811.09    4880  812.46  4887.2  810.52
  4894.1  811.93  4901.4  810.84  4921.1  810.94  4944.9   808.6  4964.9  808.38
  4972.1  806.88  5007.4  807.21  5011.6  804.85  5011.8  804.35  5015.6  804.85
    5057  812.65  5120.6  818.66  5127.5   818.4  5134.7  820.66    5308  833.21
#Mann= 5 ,-1 , 0
  4551.8     .05       0  4921.1     .12       0  4944.9     .05       0
  5011.6     .04       0  5015.6     .05       0
Bank Sta=5011.6,5015.6
XS Rating Curve= 0 ,0
Exp/Cntr=0.3,0.1

Type RM Length L Ch R = 1 ,8496    ,339,339,339
BEGIN DESCRIPTION:
Sisal Creek 19.0
END DESCRIPTION:
XS GIS Cut Line= 3
      2271290.11      7182899.23        2271179.        7183060.
      2271079.02      7183259.97
#Sta/Elev= 30
  4809.8  820.26  4904.7  812.99  4920.1   811.2    4941  810.11  4947.1  808.97
  4955.9  808.28    4962  806.89  4982.9   804.6  4991.7  804.32  4995.8  803.22
    4996  802.72  4999.5  802.72  4999.8  803.22  5002.2  805.16    5008  805.16
  5019.2   806.4  5027.6  805.83  5041.6  807.25  5060.8  806.94  5080.7   807.2
  5086.3  810.31  5094.7  809.99  5103.1  810.76  5108.7  812.45  5125.4  814.67
  5192.5  820.22  5214.9  821.71  5220.5  821.48    5226  822.97  5228.8  822.97
#Mann= 5 ,-1 , 0
  4809.8     .05       0  4904.7     .12       0  4995.8     .07       0
  4999.8     .12       0  5060.8     .05       0
Bank Sta=4995.8,4999.8
XS Rating Curve= 0 ,0
Exp/Cntr=0.3,0.1

Type RM Length L Ch R = 1 ,8157    ,396,396,396
BEGIN DESCRIPTION:
Sisal Creek 18.0
END DESCRIPTION:
XS GIS Cut Line= 3
        2271079.        7182760.      2270948.41      7182926.32
      2270878.98      7183010.02
#Sta/Elev= 30
  4786.2  818.47  4789.4  818.47  4807.9  816.62  4814.2  816.54  4836.8  815.09
  4851.6  813.37    4872  812.23  4913.7  807.59  4921.8  807.23  4928.1  805.87
    4957  804.58  4977.8  804.61  4997.2  803.78  5001.1  803.78  5012.6  801.32
  5012.8  800.82  5016.3  800.82  5016.6  801.32  5021.1  804.01  5028.4  804.02
  5035.4  806.27  5041.9  806.51  5049.7  807.34  5070.6  807.78  5078.4  811.98
  5084.9  812.06  5092.7  814.82  5099.2  815.16  5103.1  817.23  5106.4  817.23
#Mann= 5 ,-1 , 0
  4786.2     .05       0  4851.6     .12       0  4997.2     .05       0
  5012.6     .04       0  5016.6     .05       0
Bank Sta=5012.6,5016.6
XS Rating Curve= 0 ,0
Exp/Cntr=0.3,0.1

Type RM Length L Ch R = 1 ,7761    ,328,328,328
BEGIN DESCRIPTION:
Sisal Creek 17.0
END DESCRIPTION:
XS GIS Cut Line= 3
      2271029.82      7182535.98        2270729.        7182610.
      2270498.05      7183154.34
#Sta/Elev= 30
  4683.9   817.9  4699.9  816.48  4756.8  810.33  4777.4  806.64  4802.6   805.4
  4818.6  804.39  4850.9  804.74  4870.1  808.11  4887.3  813.02  4892.5  812.95
    4901  810.61  4911.3  805.26  4924.9  803.43  5002.8   801.3  5008.2   799.9
  5013.4  796.01  5013.7  795.51  5017.4  796.01  5026.3  798.15  5031.9  801.16
  5087.7  801.09    5132  800.72  5167.5  803.16  5190.2   802.8  5313.9  806.59
  5390.4  811.38  5466.8  813.68  5495.9  813.52  5543.2  816.17    5585  816.72
#Mann= 7 ,-1 , 0
  4683.9     .05       0  4699.9     .12       0  4802.6     .05       0
  4924.9     .12       0  5013.4     .07       0  5017.4     .12       0
  5087.7     .05       0
Bank Sta=5013.4,5017.4
XS Rating Curve= 0 ,0
Exp/Cntr=0.3,0.1

Type RM Length L Ch R = 1 ,7433    ,0,0,0
BEGIN DESCRIPTION:
Sisal Creek 16.1
END DESCRIPTION:
XS GIS Cut Line= 4
      2271061.95      7182522.43      2270637.15      7182408.95
      2270295.38       7182444.7      2270089.03       7183545.8
#Sta/Elev= 30
  4451.7  819.82    4579  809.88  4589.3  811.35  4620.4  806.26  4682.5  802.57
  4796.3  799.54  4825.7  800.91  4919.7  798.33    4970  799.19  5000.1  798.25
  5010.2   795.5  5030.3  799.07  5060.5  797.03  5070.5  798.51  5090.6  796.72
  5171.1  796.81  5189.2  794.87  5189.4  794.37  5193.2  794.87    5244   797.8
  5372.7  796.34  5749.1  798.73  5769.5  796.08  5842.8  796.91  5942.4  801.35
  6105.2  804.83  6163.3  808.43    6207  807.87  6326.2  813.56  6355.3  812.86
#Mann= 3 ,-1 , 0
  4451.7     .05       0  5189.2     .04       0  5193.2     .05       0
#XS Ineff= 2 , 0
       0  5070.5  798.51  5749.1       0  798.73
Permanent Ineff=
       F       F
Bank Sta=5189.2,5193.2
XS Rating Curve= 0 ,0
Exp/Cntr=0.3,0.1

Chan Stop Cuts=-1
Use User Specified Reach Order=0
Composite Channel Slope=5