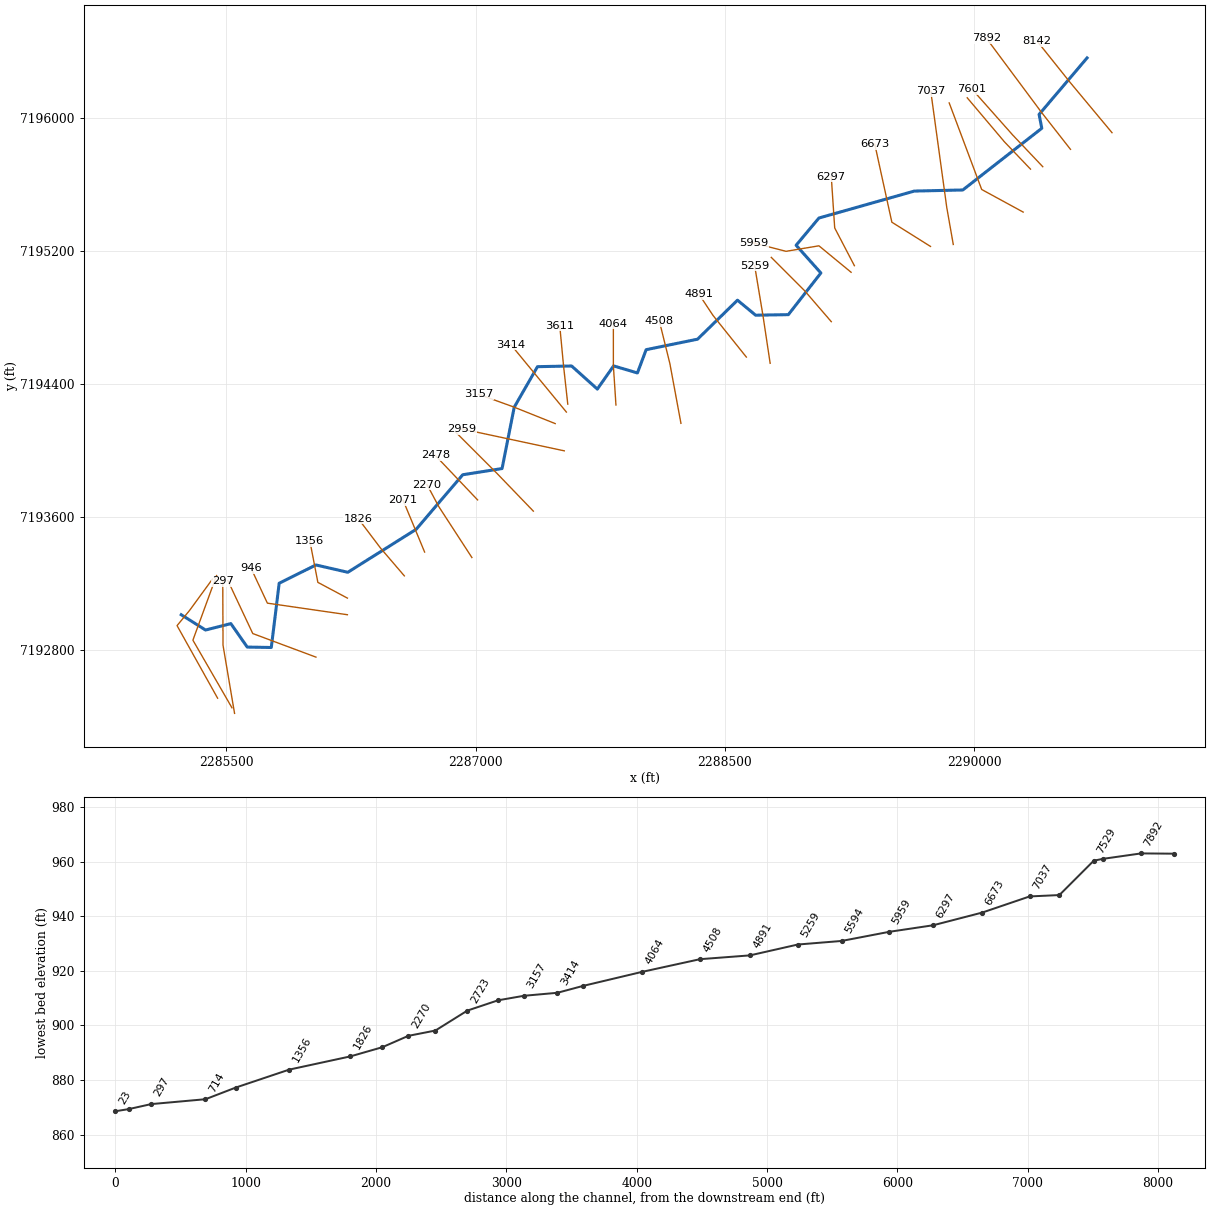
--- UDS St 07.prj (project) ---

Proj Title=UDS St 07 Base Level Engineering
Current Plan=p01
Default Exp/Contr=0.3,0.1
English Units
Geom File=g01
Flow File=f01
Plan File=p01
Y Axis Title=Elevation
X Axis Title(PF)=Main Channel Distance
X Axis Title(XS)=Station
BEGIN DESCRIPTION:
UDS St 07
END DESCRIPTION:
DSS Export Rating Curves= 0
DSS Export Rating Curve Sorted= 0
DSS Export Volume Flow Curves= 0
DXF OffsetX= 0
DXF OffsetY= 0
DXF ScaleX= 1
DXF ScaleY= 10

--- UDS St 07.p01 (plan) ---

Plan Title=Multiple Run
Short Identifier=Multiple
Geom File=g01
Flow File=f01
Subcritical Flow
K Sum by GR= 0
Std Step Tol= 0.01
Critical Tol= 0.01
Num of Std Step Trials= 20
Max Error Tol= 0.3
Flow Tol Ratio= 0.001
Split Flow NTrial= 30
Split Flow Tol= 0.02
Split Flow Ratio= 0.02
Log Output Level= 0
Friction Slope Method= 1
Unsteady Friction Slope Method= 2
Unsteady Bridges Friction Slope Method= 1
Parabolic Critical Depth
Global Vel Dist=  1 , 1 , 1
Global Log Level= 0
CheckData=True
Encroach Param= -1, 0, 0, 0
BEGIN DESCRIPTION:
Multiple Run
END DESCRIPTION:

--- UDS St 07.f01 (steady flow) ---

Flow Title=Multiple
Number of Profiles=7
Profile Names=10-year,25-year,50-year,1pct_min,100-year,1pct_plu,500-year
River Rch & RM= UDS St 07,Reach-1,8142
     711     983    1209     739    1475    2943    2197
River Rch & RM= UDS St 07,Reach-1,4064
     867    1217    1512     933    1861    3714    2827
River Rch & RM= UDS St 07,Reach-1,23
    1516    2184    2763    1731    3453    6891    5412
Boundary for River Rch & Prof#=UDS St 07,Reach-1,1
Up Type=0
Dn Type=3
Dn Slope=0.005
Boundary for River Rch & Prof#=UDS St 07,Reach-1,2
Up Type=0
Dn Type=3
Dn Slope=0.005
Boundary for River Rch & Prof#=UDS St 07,Reach-1,3
Up Type=0
Dn Type=3
Dn Slope=0.005
Boundary for River Rch & Prof#=UDS St 07,Reach-1,4
Up Type=0
Dn Type=3
Dn Slope=0.005
Boundary for River Rch & Prof#=UDS St 07,Reach-1,5
Up Type=0
Dn Type=3
Dn Slope=0.005
Boundary for River Rch & Prof#=UDS St 07,Reach-1,6
Up Type=0
Dn Type=3
Dn Slope=0.005
Boundary for River Rch & Prof#=UDS St 07,Reach-1,7
Up Type=0
Dn Type=3
Dn Slope=0.005

--- UDS St 07.g01 (geometry) ---

Geom Title=Existing Conditions
Program Version=4.10

River Reach=UDS St 07       ,Reach-1
Reach XY= 30
        2290679.        7196360.      2290390.24        7196020.
       2290406.5      7195936.61      2289931.45      7195565.46
       2289639.5      7195558.78      2289065.68      7195396.63
      2288928.43      7195232.79      2289077.46      7195066.02
       2288881.7      7194815.36      2288684.85      7194812.07
      2288575.67      7194902.39      2288335.45      7194667.75
      2288026.27      7194604.65      2287973.75      7194464.63
      2287830.42      7194506.95      2287732.63      7194367.66
      2287577.74      7194506.52      2287372.48      7194502.33
      2287232.55      7194258.53      2287159.42      7193889.42
      2286922.79       7193852.2      2286642.21      7193523.62
      2286231.42      7193265.41      2286039.62      7193309.39
      2285818.48      7193199.49      2285771.08       7192812.9
      2285626.31      7192815.35      2285527.72      7192956.63
      2285375.68      7192918.02        2285229.        7193010.

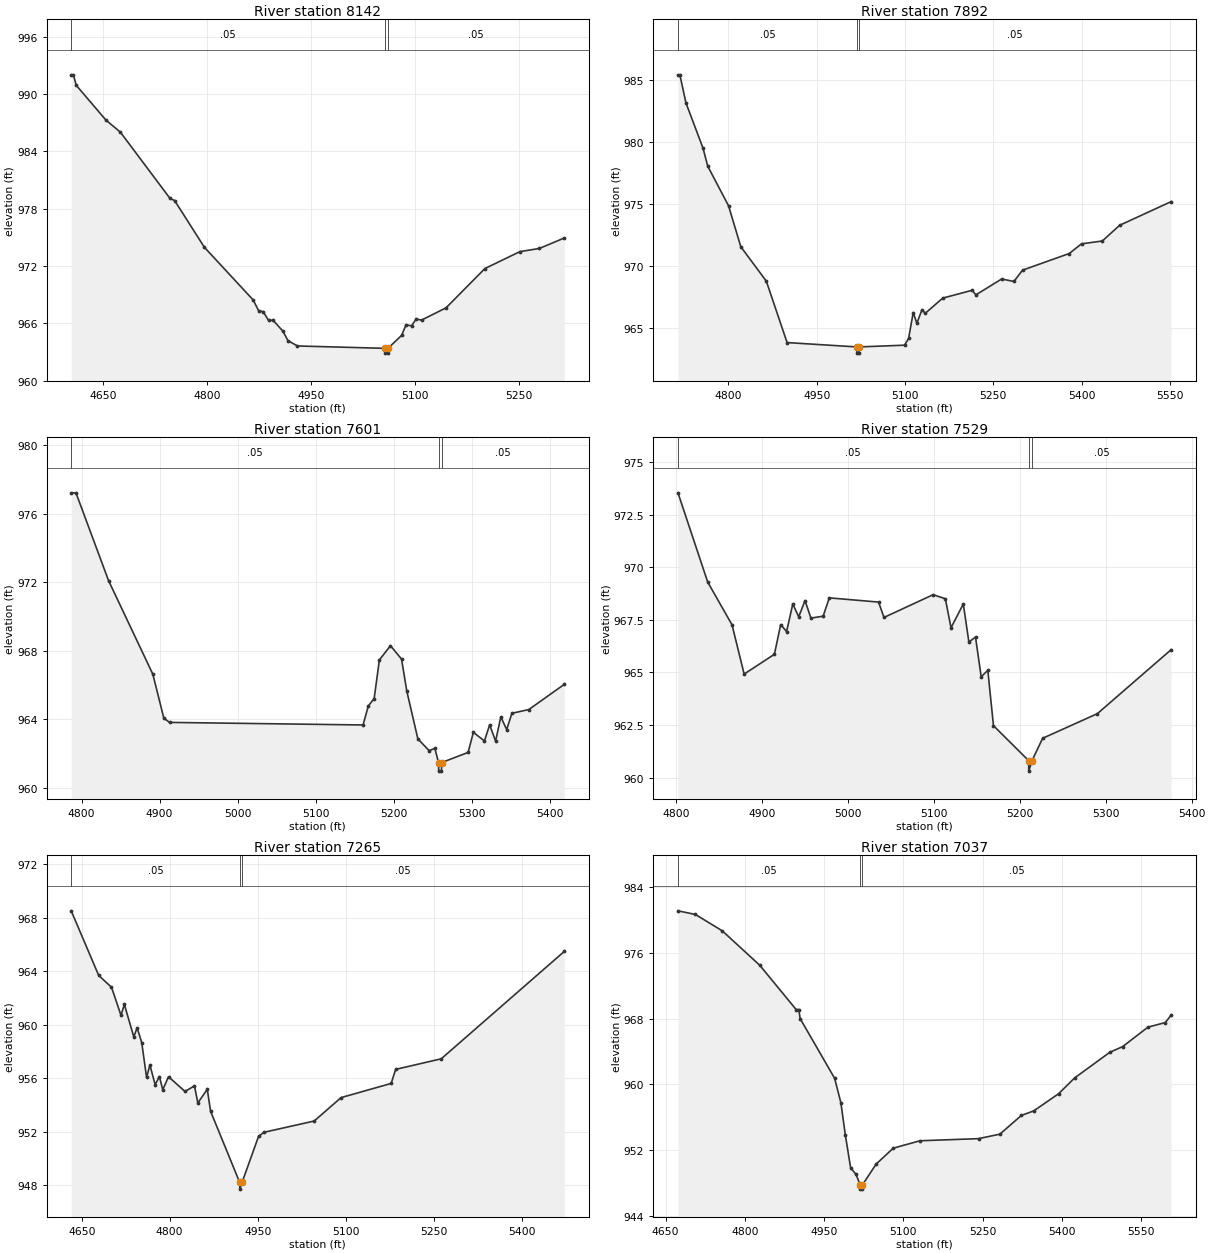
Type RM Length L Ch R = 1 ,8142    ,250,250,250
BEGIN DESCRIPTION:
UDS St 07 20.0
END DESCRIPTION:
XS GIS Cut Line= 3
        2290829.      7195910.01        2290579.        7196210.
      2290378.98      7196460.03
#Sta/Elev= 30
  4604.4  991.99  4607.6  991.99  4611.6   990.9  4654.5  987.25  4675.3  985.99
  4746.9  979.05  4753.4  978.84  4796.4  973.94  4866.7  968.43  4874.5  967.31
    4881  967.21  4888.8   966.3  4895.3  966.31  4909.6  965.16  4916.8  964.17
  4930.5  963.62  5056.9  963.37  5057.2  962.87  5060.7  962.87  5060.9  963.37
  5080.5  964.72  5086.9  965.82    5095  965.73  5101.4  966.43  5109.4  966.33
  5144.6  967.61  5200.6  971.72    5251  973.49    5279  973.82  5315.1  974.92
#Mann= 3 ,-1 , 0
  4604.4     .05       0  5056.9    .033       0  5060.9     .05       0
Bank Sta=5056.9,5060.9
XS Rating Curve= 0 ,0
Exp/Cntr=0.3,0.1

Type RM Length L Ch R = 1 ,7892    ,291,291,291
BEGIN DESCRIPTION:
UDS St 07 19.0
END DESCRIPTION:
XS GIS Cut Line= 3
        2290579.      7195810.01      2290403.32      7196034.28
      2290073.56      7196477.72
#Sta/Elev= 30
  4714.5  985.38  4717.7  985.38  4728.1  983.11    4757  979.48  4765.1  978.02
  4800.4  974.83  4821.2  971.54  4864.6  968.76  4899.8  963.82  5018.1  963.47
  5018.4  962.97  5021.9  962.97  5022.1  963.47  5099.4  963.61  5106.2  964.16
    5114  966.24  5120.2  965.37  5128.6  966.43  5134.8  966.19  5164.1   967.4
  5214.1  968.03  5220.4  967.66  5264.2  968.94    5285  968.74  5299.6  969.65
  5378.9  970.99  5399.8  971.77  5435.2     972  5464.4  973.26    5552  975.17
#Mann= 3 ,-1 , 0
  4714.5     .05       0  5018.1    .033       0  5022.1     .05       0
Bank Sta=5018.1,5022.1
XS Rating Curve= 0 ,0
Exp/Cntr=0.3,0.1

Type RM Length L Ch R = 1 ,7601    ,72,72,72
BEGIN DESCRIPTION:
UDS St 07 18.2
END DESCRIPTION:
XS GIS Cut Line= 3
      2290412.42      7195705.39      2290231.89      7195895.77
      2289986.56      7196172.12
#Sta/Elev= 30
  4786.7  977.21  4792.8  977.21  4834.6  972.09  4891.3  966.64  4905.4  964.08
  4912.7  963.83  5160.7  963.68  5167.4  964.79  5174.9  965.22  5181.6  967.47
  5195.8   968.3    5210  967.52  5216.7  965.66  5230.9  962.87  5245.2  962.19
  5252.7  962.31  5257.4  961.49  5257.6  960.99  5261.1  960.99  5261.4  961.49
  5295.3  962.08    5302  963.25  5316.2  962.75  5322.9  963.69  5330.5  962.74
  5337.2  964.15  5344.7  963.41  5351.4  964.36  5373.1  964.58  5418.6  966.05
#Mann= 3 ,-1 , 0
  4786.7     .05       0  5257.4    .033       0  5261.4     .05       0
Bank Sta=5257.4,5261.4
XS Rating Curve= 0 ,0
Exp/Cntr=0.3,0.1

Type RM Length L Ch R = 1 ,7529    ,264,264,264
BEGIN DESCRIPTION:
UDS St 07 18.1
END DESCRIPTION:
XS GIS Cut Line= 3
       2290338.6      7195690.77      2290181.46      7195855.43
      2289958.04      7196119.88
#Sta/Elev= 30
  4802.3  973.53  4836.9  969.29  4865.2  967.26  4879.3  964.92  4914.5  965.86
  4921.8  967.27  4928.7  966.94  4935.9  968.25  4942.8  967.64  4950.1  968.41
    4957  967.58  4971.2  967.67  4978.4  968.54  5035.7  968.34    5042  967.61
  5099.1  968.69  5113.4   968.5    5120  967.12  5134.3  968.25  5140.8  966.44
  5148.5  966.68  5155.1  964.79  5162.8   965.1  5169.4  962.47  5210.3  960.81
  5210.5  960.31  5214.3  960.81  5226.6  961.87  5290.3  963.04  5376.1  966.08
#Mann= 3 ,-1 , 0
  4802.3     .05       0  5210.3    .033       0  5214.3     .05       0
Bank Sta=5210.3,5214.3
XS Rating Curve= 0 ,0
Exp/Cntr=0.3,0.1

Type RM Length L Ch R = 1 ,7265    ,228,228,228
BEGIN DESCRIPTION:
UDS St 07 18.0
END DESCRIPTION:
XS GIS Cut Line= 3
      2290294.67      7195432.31      2290044.92      7195568.35
      2289849.46      7196089.29
#Sta/Elev= 30
  4632.1  968.52    4679  963.69  4700.8  962.81    4717  960.71  4722.7  961.53
  4738.8   959.1  4744.5  959.78  4752.4  958.67  4760.6  956.07  4766.3     957
  4775.2  955.53  4782.5  956.13  4788.2  955.15    4798  956.12  4826.2  955.02
  4842.3  955.44    4848  954.16  4864.1  955.18  4869.8  953.53  4919.4  948.22
  4919.6  947.72  4923.4  948.22  4951.6  951.67    4961  951.97  5046.4  952.81
  5092.2  954.56  5177.6  955.62  5185.3  956.67    5263  957.46  5472.9  965.49
#Mann= 3 ,-1 , 0
  4632.1     .05       0  4919.4    .033       0  4923.4     .05       0
Bank Sta=4919.4,4923.4
XS Rating Curve= 0 ,0
Exp/Cntr=0.3,0.1

Type RM Length L Ch R = 1 ,7037    ,364,364,364
BEGIN DESCRIPTION:
UDS St 07 17.0
END DESCRIPTION:
XS GIS Cut Line= 3
      2289873.97      7195237.59      2289834.69      7195460.62
      2289738.35      7196160.96
#Sta/Elev= 30
  4673.3  981.12  4706.2  980.68    4757  978.69  4828.1  974.49  4896.9   969.1
    4902   969.1  4904.5     968  4969.8  960.72  4981.6  957.76    4990  953.85
  5000.1  949.81  5010.2  949.03  5018.3  947.72  5018.5  947.22    5022  947.22
  5022.3  947.72  5048.5  950.28  5080.8  952.21  5131.3  953.11  5242.3  953.37
  5282.7  953.92  5323.1  956.19  5346.7  956.75  5393.7  958.84    5424  960.76
  5490.7  963.89  5514.9  964.58  5562.8  966.95  5595.6  967.51  5606.7  968.41
#Mann= 3 ,-1 , 0
  4673.3     .05       0  5018.3    .033       0  5022.3     .05       0
Bank Sta=5018.3,5022.3
XS Rating Curve= 0 ,0
Exp/Cntr=0.3,0.1

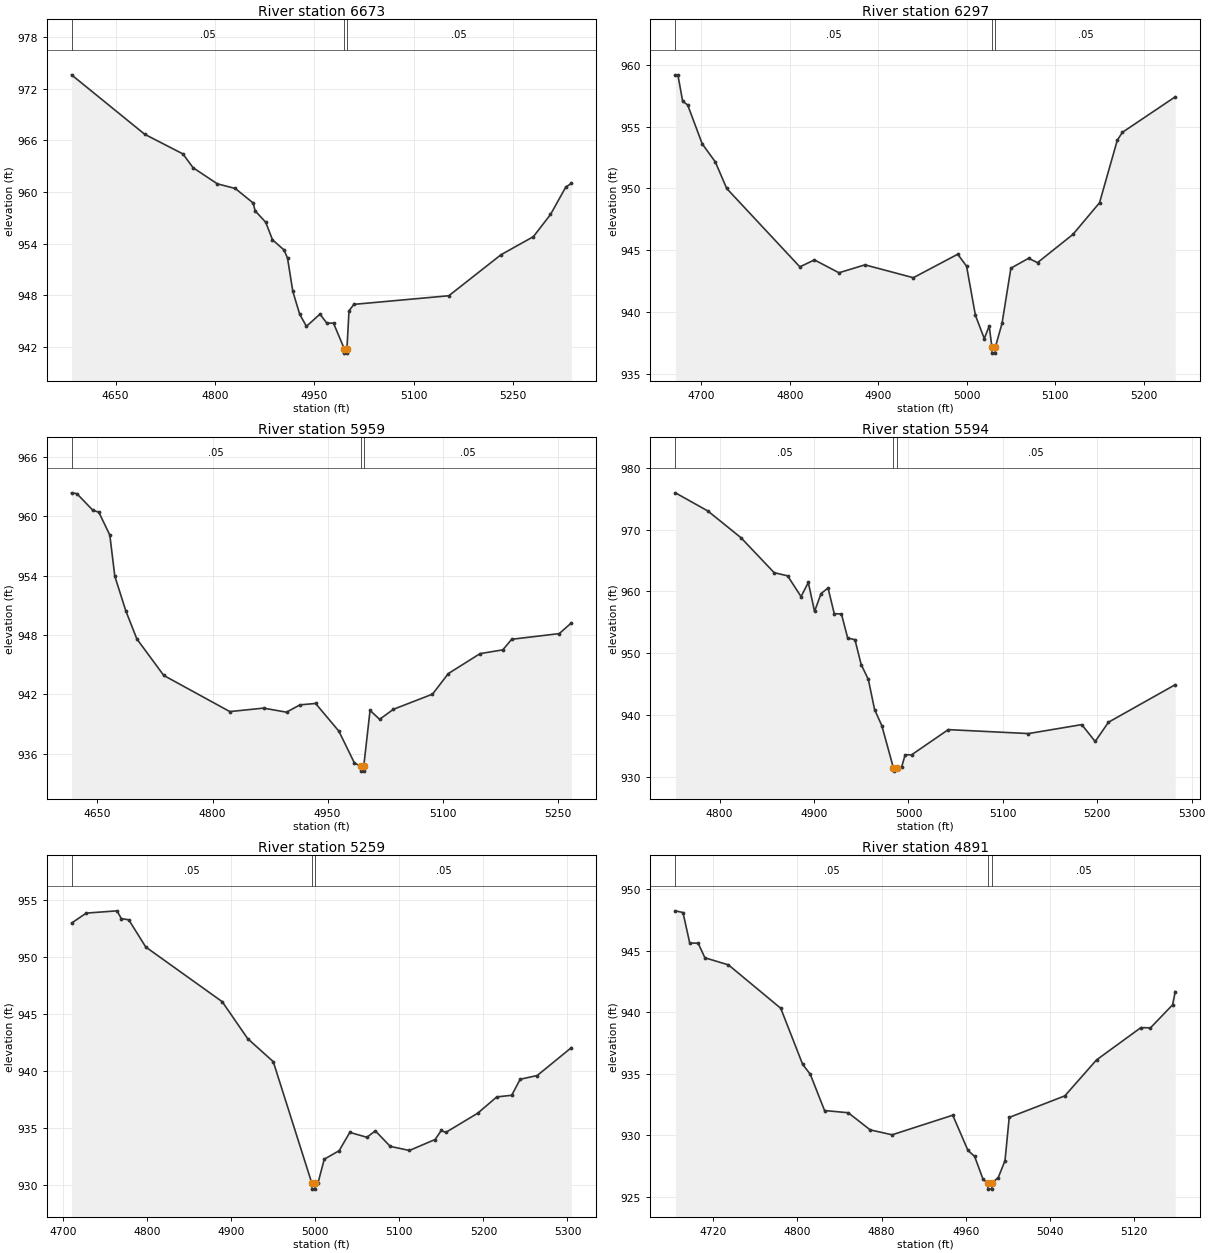
Type RM Length L Ch R = 1 ,6673    ,376,376,376
BEGIN DESCRIPTION:
UDS St 07 16.0
END DESCRIPTION:
XS GIS Cut Line= 3
      2289736.87      7195225.85      2289504.45       7195371.6
      2289401.71      7195840.74
#Sta/Elev= 30
  4583.4  973.61  4693.9  966.71  4751.6  964.43  4766.9  962.83  4803.5  960.96
  4830.6  960.42  4857.7  958.73  4860.5  957.83  4876.6   956.5  4886.8  954.46
  4904.4  953.27  4909.5  952.33  4917.5  948.47  4927.8  945.84    4938  944.42
  4958.5  945.84  4968.7   944.8  4978.9  944.79  4995.2  941.81  4995.4  941.31
  4998.9  941.31  4999.2  941.81  5002.3  946.22  5009.7  946.97    5153  947.97
  5231.8  952.73  5280.7  954.83  5306.5   957.4  5329.7   960.6    5338     961
#Mann= 3 ,-1 , 0
  4583.4     .05       0  4995.2    .033       0  4999.2     .05       0
Bank Sta=4995.2,4999.2
XS Rating Curve= 0 ,0
Exp/Cntr=0.3,0.1

Type RM Length L Ch R = 1 ,6297    ,338,338,338
BEGIN DESCRIPTION:
UDS St 07 15.0
END DESCRIPTION:
XS GIS Cut Line= 3
      2289278.99      7195110.01      2289160.59      7195336.99
       2289140.1       7195645.4
#Sta/Elev= 30
  4670.6  959.18  4673.4  959.18  4678.8  957.05  4684.5  956.74  4700.9   953.6
  4715.7  952.14  4728.6  949.99  4811.3  943.65  4827.8  944.21  4855.5  943.17
  4884.9  943.81  4939.6  942.77  4989.8  944.67  4999.8   943.7  5009.8  939.73
  5019.8  937.85  5025.4  938.86  5028.4  937.17  5028.7  936.67  5032.2  936.67
  5032.4  937.17  5039.9  939.08  5049.9  943.54  5069.9  944.34    5080  943.99
    5120  946.27  5150.1  948.83  5170.2  953.89    5176  954.53  5235.7   957.4
#Mann= 3 ,-1 , 0
  4670.6     .05       0  5028.4    .033       0  5032.4     .05       0
Bank Sta=5028.4,5032.4
XS Rating Curve= 0 ,0
Exp/Cntr=0.3,0.1

Type RM Length L Ch R = 1 ,5959    ,365,365,365
BEGIN DESCRIPTION:
UDS St 07 14.0
END DESCRIPTION:
XS GIS Cut Line= 4
       2289259.1      7195070.45      2289065.81      7195229.54
       2288867.9       7195196.4      2288673.73      7195246.35
#Sta/Elev= 30
  4616.2  962.35  4623.1  962.27  4643.9   960.6  4651.8  960.39  4666.1  958.09
  4672.6  953.94  4686.9  950.45  4701.3  947.61  4736.4  943.92  4822.5  940.27
  4866.5  940.62  4896.4  940.21    4914  940.95  4934.3  941.09  4964.7  938.29
    4985  935.07  4993.1  934.76  4993.4  934.26  4996.9  934.26  4997.1  934.76
  5005.3  940.39  5017.8  939.49  5035.7   940.5  5086.7  942.03  5107.4  944.11
  5148.7  946.12  5178.3   946.5    5190  947.57  5251.9  948.14  5267.7  949.22
#Mann= 3 ,-1 , 0
  4616.2     .05       0  4993.1    .033       0  4997.1     .05       0
Bank Sta=4993.1,4997.1
XS Rating Curve= 0 ,0
Exp/Cntr=0.3,0.1

Type RM Length L Ch R = 1 ,5594    ,335,335,335
BEGIN DESCRIPTION:
UDS St 07 13.0
END DESCRIPTION:
XS GIS Cut Line= 3
      2289140.08      7194773.16        2288979.        7194960.
      2288779.02      7195159.98
#Sta/Elev= 30
  4753.1  975.97  4787.5  973.03  4822.6   968.7  4857.7  963.05    4872  962.53
  4886.2  959.17  4893.9  961.46  4900.5  956.77  4907.4  959.66  4914.8  960.57
  4921.4   956.4    4929  956.37  4935.6  952.47  4943.3   952.2  4949.9  948.18
  4957.5  945.76  4964.1  940.89  4971.8  938.27  4984.1  931.42  4984.3  930.92
  4988.1  931.42  4992.7  931.55  4996.5  933.56  5003.3  933.56  5042.2  937.64
  5127.1     937  5183.6  938.45  5197.8  935.72  5211.9  938.84  5282.6  944.91
#Mann= 3 ,-1 , 0
  4753.1     .05       0  4984.1    .033       0  4988.1     .05       0
Bank Sta=4984.1,4988.1
XS Rating Curve= 0 ,0
Exp/Cntr=0.3,0.1

Type RM Length L Ch R = 1 ,5259    ,368,368,368
BEGIN DESCRIPTION:
UDS St 07 12.0
END DESCRIPTION:
XS GIS Cut Line= 3
      2288772.24      7194522.71        2288729.        7194810.
      2288678.99      7195110.03
#Sta/Elev= 30
  4709.9  953.01  4727.4  953.89    4764  954.09  4769.1  953.41    4778   953.3
  4798.2  950.91  4889.2   946.1  4919.5  942.85  4949.9  940.83  4995.9  930.12
  4996.2  929.62  4999.7  929.62  4999.9  930.12    5003  930.12  5010.6  932.25
  5028.3     933    5041  934.61  5061.3  934.18  5071.4  934.74  5089.1  933.38
  5111.9  933.02  5142.4  933.98    5150  934.79    5155   934.6  5193.1  936.29
  5215.9  937.73  5233.6  937.87  5243.7  939.28    5264  939.61  5304.6  942.06
#Mann= 3 ,-1 , 0
  4709.9     .05       0  4995.9    .033       0  4999.9     .05       0
Bank Sta=4995.9,4999.9
XS Rating Curve= 0 ,0
Exp/Cntr=0.3,0.1

Type RM Length L Ch R = 1 ,4891    ,383,383,383
BEGIN DESCRIPTION:
UDS St 07 11.0
END DESCRIPTION:
XS GIS Cut Line= 3
      2288628.98      7194560.02        2288429.        7194810.
      2288343.65      7194938.63
#Sta/Elev= 30
  4684.3  948.23  4691.5  948.09  4697.9  945.62  4705.9   945.6  4712.3  944.42
  4734.7  943.84  4784.3  940.32  4805.1  935.77  4812.3  934.97  4825.9  932.02
  4848.4  931.84  4869.2  930.45    4890  930.05  4947.6  931.64    4962  928.79
  4968.4  928.29  4976.4  926.43  4980.8  926.14  4981.1  925.64  4984.6  925.64
  4984.8  926.14  4990.8  926.58  4997.2  927.95  5001.2  931.46    5054  933.21
  5084.1  936.13  5126.2  938.75  5135.3  938.73  5156.3   940.6  5158.8  941.67
#Mann= 3 ,-1 , 0
  4684.3     .05       0  4980.8    .033       0  4984.8     .05       0
Bank Sta=4980.8,4984.8
XS Rating Curve= 0 ,0
Exp/Cntr=0.3,0.1

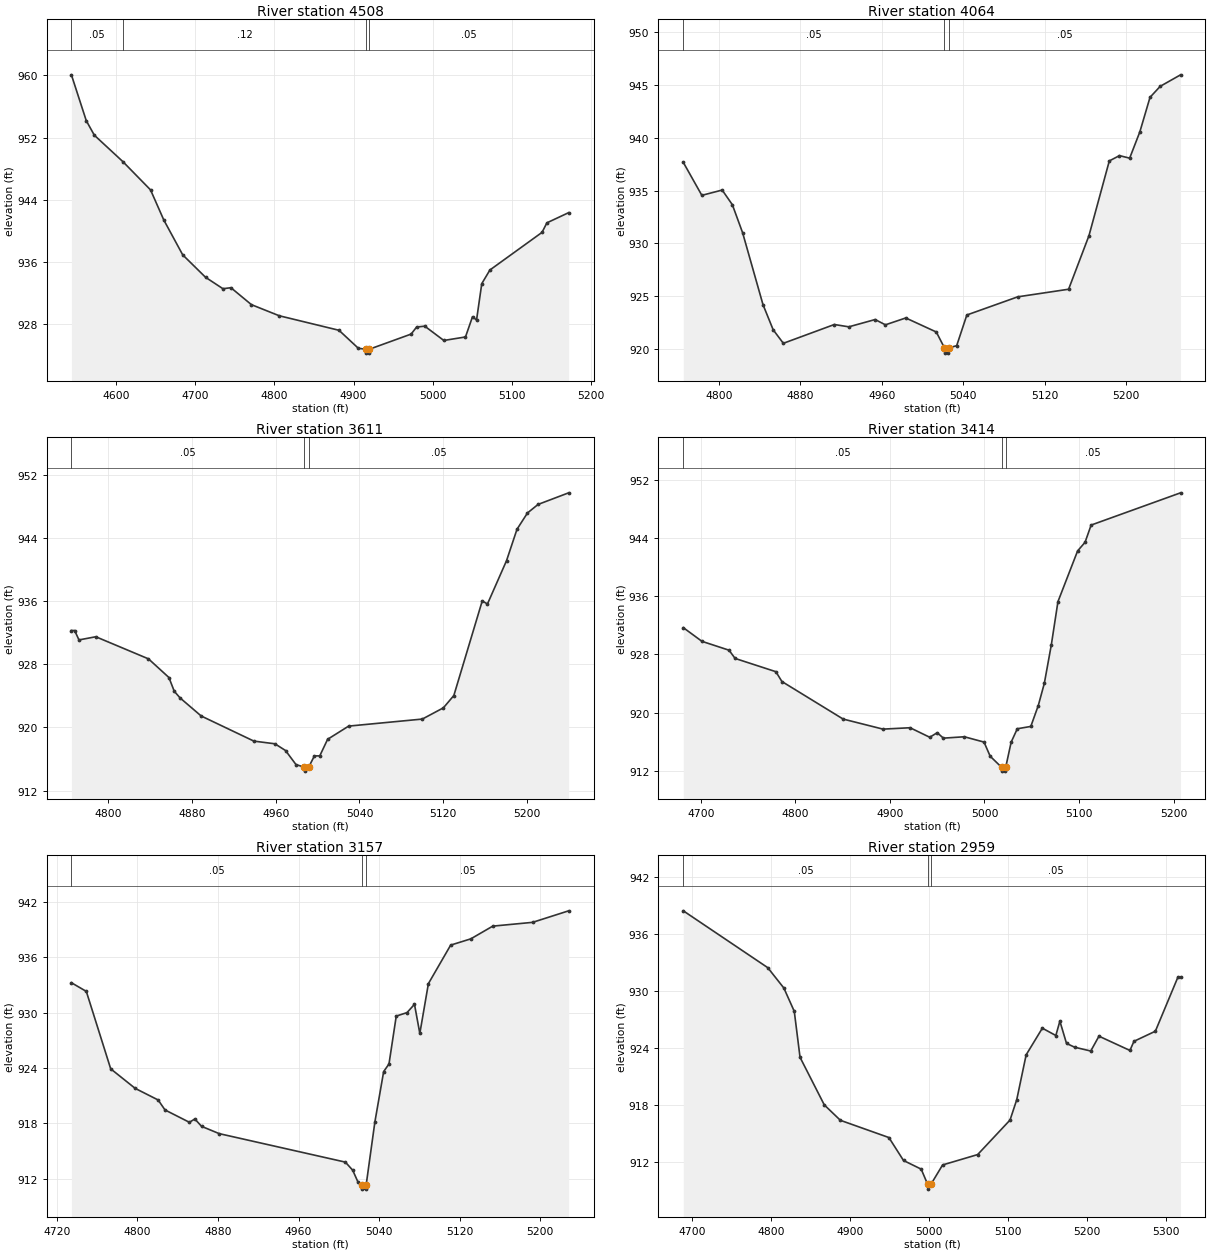
Type RM Length L Ch R = 1 ,4508    ,444,444,444
BEGIN DESCRIPTION:
UDS St 07 10.0
END DESCRIPTION:
XS GIS Cut Line= 3
      2288235.56      7194161.53      2288168.79      7194521.89
      2288105.65      7194776.69
#Sta/Elev= 30
  4543.1  960.07  4561.9  954.17  4572.1   952.3  4608.3  948.89  4643.2  945.26
    4660  941.38  4683.9   936.9  4712.8  934.01  4734.8  932.54  4744.9  932.67
  4770.8  930.49    4806  929.06  4881.6  927.19  4906.1  924.87  4915.9  924.75
  4916.2  924.25  4919.7  924.25  4919.9  924.75  4972.8   926.7  4979.8  927.61
  4990.1  927.72  5014.2  925.88  5041.6  926.33  5050.5  928.94  5055.6  928.51
  5062.2  933.19  5072.5  934.95  5138.4  939.79  5144.6  941.02  5172.1  942.33
#Mann= 4 ,-1 , 0
  4543.1     .05       0  4608.3     .12       0  4915.9    .033       0
  4919.9     .05       0
Bank Sta=4915.9,4919.9
XS Rating Curve= 0 ,0
Exp/Cntr=0.3,0.1

Type RM Length L Ch R = 1 ,4064    ,453,453,453
BEGIN DESCRIPTION:
UDS St 07 9.0
END DESCRIPTION:
XS GIS Cut Line= 3
       2287844.5      7194271.87        2287829.        7194510.
        2287829.      7194759.96
#Sta/Elev= 30
    4765  937.67  4783.2  934.55  4803.2  935.05  4813.2  933.66  4823.3     931
  4843.3   924.2  4853.3  921.82  4863.3  920.54  4913.4  922.32  4927.6   922.1
  4953.5  922.79  4963.6  922.29  4983.6  922.94  5013.6  921.61  5021.6  920.11
  5021.9  919.61  5025.4  919.61  5025.6  920.11  5033.6  920.31  5043.6  923.22
  5093.6  924.94  5143.6  925.66  5163.6  930.73  5183.6  937.81  5193.6  938.31
  5203.6  938.07  5213.6  940.56  5223.6  943.83  5233.6  944.87  5253.6  945.96
#Mann= 3 ,-1 , 0
    4765     .05       0  5021.6    .033       0  5025.6     .05       0
Bank Sta=5021.6,5025.6
XS Rating Curve= 0 ,0
Exp/Cntr=0.3,0.1

Type RM Length L Ch R = 1 ,3611    ,197,197,197
BEGIN DESCRIPTION:
UDS St 07 8.0
END DESCRIPTION:
XS GIS Cut Line= 3
      2287554.69      7194276.85        2287529.        7194510.
      2287506.42      7194749.08
#Sta/Elev= 30
    4765  932.27  4768.1  932.27  4772.2  931.08  4788.3  931.48  4838.6  928.68
  4858.1  926.32  4863.2  924.58  4868.8  923.73  4888.9  921.45  4939.2  918.27
  4959.3  917.93  4969.4  917.08  4979.4   915.3  4987.4  914.97  4987.7  914.47
  4991.5  914.97    4997   916.4  5002.1   916.4  5009.6   918.5  5029.7  920.17
    5100  921.06  5120.1  922.48  5130.1  924.04  5157.2  936.01  5162.2  935.63
  5180.4  941.11  5190.4  945.09  5200.4  947.15  5210.5  948.23  5239.7   949.7
#Mann= 3 ,-1 , 0
    4765     .05       0  4987.4    .033       0  4991.5     .05       0
Bank Sta=4987.4,4991.5
XS Rating Curve= 0 ,0
Exp/Cntr=0.3,0.1

Type RM Length L Ch R = 1 ,3414    ,257,257,257
BEGIN DESCRIPTION:
UDS St 07 7.1
END DESCRIPTION:
XS GIS Cut Line= 2
      2287546.23      7194229.47      2287211.84       7194635.5
#Sta/Elev= 30
  4681.4  931.66  4701.1  929.78  4729.8  928.56  4736.2  927.43  4779.3  925.61
  4785.7  924.26  4850.5   919.1  4892.6  917.72  4921.3  917.91  4942.1   916.6
    4950  917.23  4956.5  916.48  4978.7  916.67  4999.5  915.94    5006     914
  5018.3  912.45  5018.6  911.95  5022.1  911.95  5022.4  912.45  5028.2  915.93
  5034.7  917.77    5049  918.09  5056.9  920.96  5063.3  924.01  5070.7   929.3
  5077.7  935.23  5098.5   942.2  5106.4  943.39  5112.8  945.75  5207.4  950.18
#Mann= 3 ,-1 , 0
  4681.4     .05       0  5018.3    .033       0  5022.4     .05       0
Bank Sta=5018.3,5022.4
XS Rating Curve= 0 ,0
Exp/Cntr=0.3,0.1

Type RM Length L Ch R = 1 ,3157    ,198,198,198
BEGIN DESCRIPTION:
UDS St 07 7.0
END DESCRIPTION:
XS GIS Cut Line= 3
      2287478.99      7194160.01        2287229.        7194260.
      2287018.16      7194336.42
#Sta/Elev= 30
  4734.6  933.24  4749.4   932.3  4773.6   923.9  4797.9  921.78  4820.7  920.52
  4827.5  919.44  4851.7   918.1  4857.1  918.46  4863.8  917.66  4881.3  916.87
  5006.5  913.78  5013.8   912.9  5019.2  911.57  5023.1  911.35  5023.4  910.85
  5026.9  910.85  5027.2  911.35  5035.8  918.14  5044.5   923.6  5049.8  924.43
    5057  929.62  5067.7     930  5075.1   930.9  5080.4  927.74  5088.9  933.14
    5111  937.32    5131     938  5152.8  939.38  5192.3  939.79  5228.1  941.04
#Mann= 3 ,-1 , 0
  4734.6     .05       0  5023.1    .033       0  5027.2     .05       0
Bank Sta=5023.1,5027.2
XS Rating Curve= 0 ,0
Exp/Cntr=0.3,0.1

Type RM Length L Ch R = 1 ,2959    ,236,236,236
BEGIN DESCRIPTION:
UDS St 07 6.1
END DESCRIPTION:
XS GIS Cut Line= 2
      2287533.53      7193996.09      2286917.83      7194127.63
#Sta/Elev= 30
    4689  938.44  4795.9  932.47  4816.3  930.33  4829.5  927.88  4836.8  923.05
  4867.5  918.05  4887.9  916.43  4949.3  914.62  4967.8  912.21  4990.2   911.3
  4998.4   909.7  4998.7   909.2  5002.5   909.7  5017.3  911.74  5061.7  912.83
  5102.7  916.46  5111.2   918.6  5123.1  923.31  5143.6  926.11  5160.7  925.34
  5165.8  926.85  5174.2  924.51  5184.5  924.11  5204.9  923.71  5215.3  925.27
  5254.5  923.77  5259.6  924.73  5286.7  925.79  5315.4   931.5  5318.6   931.5
#Mann= 3 ,-1 , 0
    4689     .05       0  4998.4    .033       0  5002.5     .05       0
Bank Sta=4998.4,5002.5
XS Rating Curve= 0 ,0
Exp/Cntr=0.3,0.1

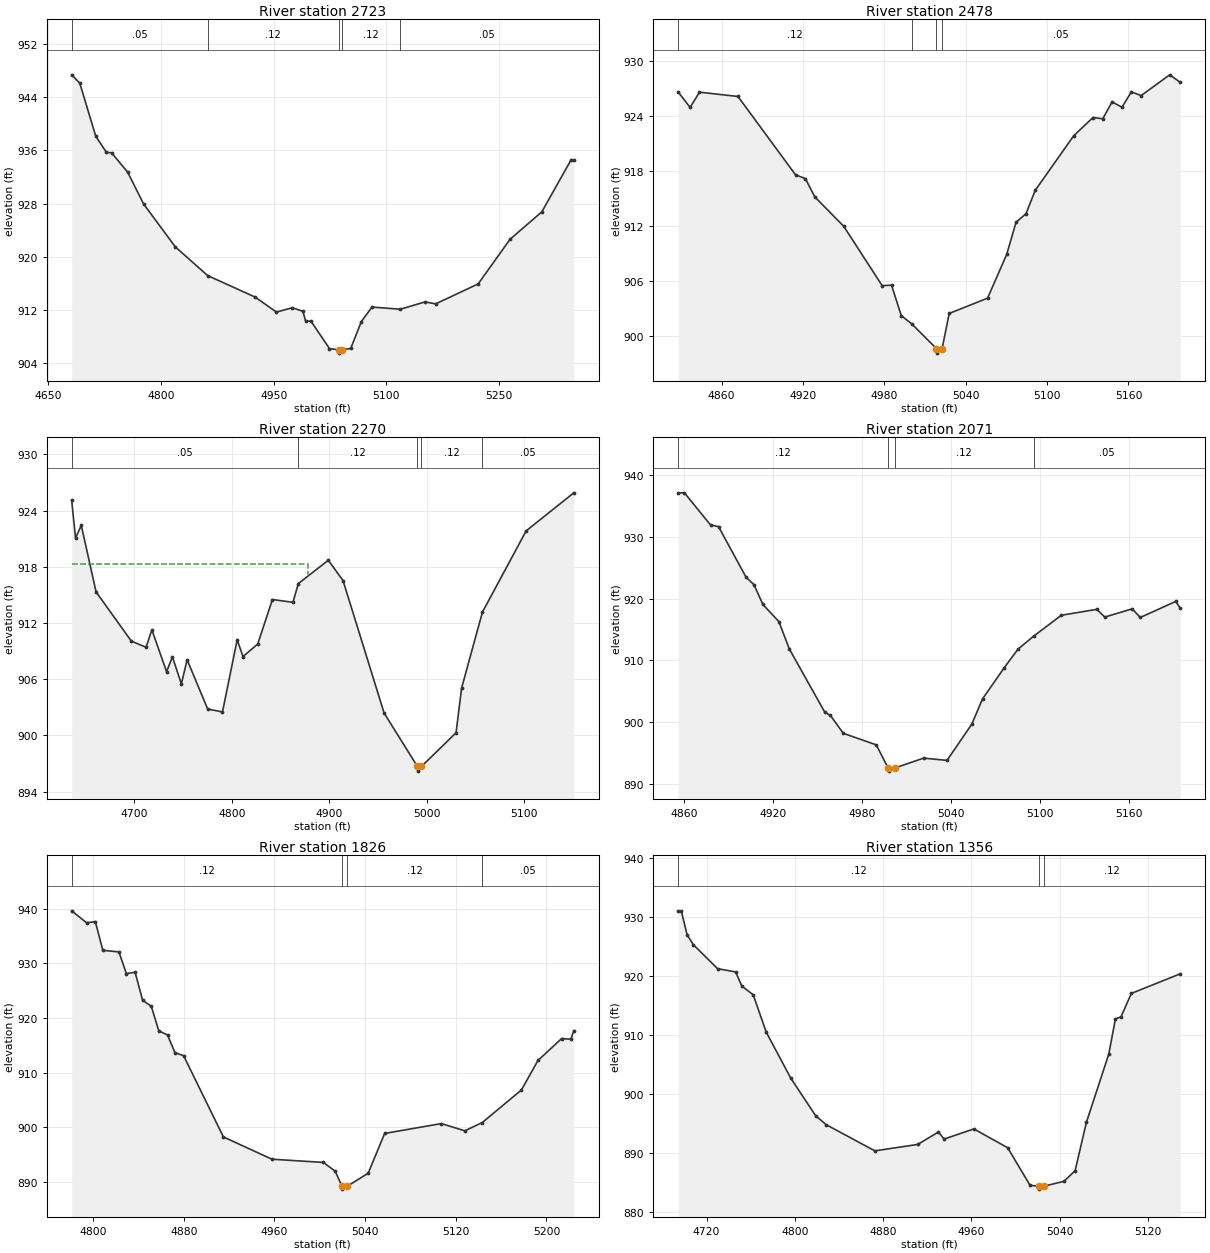
Type RM Length L Ch R = 1 ,2723    ,245,245,245
BEGIN DESCRIPTION:
UDS St 07 6.0
END DESCRIPTION:
XS GIS Cut Line= 3
       2287347.6       7193633.2        2287129.        7193860.
      2286878.97      7194110.03
#Sta/Elev= 30
  4680.9  947.41  4691.7  946.16    4713  938.15  4727.2  935.72  4734.1  935.65
  4755.5  932.72  4776.6  927.95    4819  921.45  4862.1  917.12  4925.3  913.88
  4953.6  911.62  4974.7  912.28  4988.8  911.74  4992.4  910.27  4999.4  910.27
  5024.2  906.12  5036.3  905.93  5036.6  905.43  5040.4  905.93  5052.5  906.13
  5066.6  910.18  5080.8  912.38  5118.5  912.05  5151.5  913.16  5165.6  912.86
  5222.2  915.87  5264.6   922.6    5307  926.75  5345.9  934.59  5349.5  934.59
#Mann= 5 ,-1 , 0
  4680.9     .05       0  4862.1     .12       0  5036.3     .07       0
  5040.4     .12       0  5118.5     .05       0
Bank Sta=5036.3,5040.4
XS Rating Curve= 0 ,0
Exp/Cntr=0.3,0.1

Type RM Length L Ch R = 1 ,2478    ,208,208,208
BEGIN DESCRIPTION:
UDS St 07 5.1
END DESCRIPTION:
XS GIS Cut Line= 2
      2287012.17      7193700.77      2286757.13       7193969.1
#Sta/Elev= 30
    4828  926.58  4836.8   924.9  4843.7  926.56  4872.1  926.09  4914.5  917.56
  4921.8  917.14  4928.7  915.16  4950.1  911.94  4978.4  905.48  4985.3  905.53
  4992.5  902.21  5000.2  901.32  5018.4  898.63  5018.8  898.13  5022.6  898.63
  5027.8  902.45  5056.1  904.12  5070.2  908.88  5077.1  912.39  5084.4  913.31
  5091.3  915.88  5119.6  921.81  5133.8   923.8    5141  923.66  5147.9   925.5
  5155.2  924.92  5162.1  926.59  5169.3  926.19  5190.4  928.45  5198.2  927.63
#Mann= 4 ,-1 , 0
    4828     .12       0  5000.2     .05       0  5018.4     .07       0
  5022.6     .05       0
Bank Sta=5018.4,5022.6
XS Rating Curve= 0 ,0
Exp/Cntr=0.3,0.1

Type RM Length L Ch R = 1 ,2270    ,199,199,199
BEGIN DESCRIPTION:
UDS St 07 5.0
END DESCRIPTION:
XS GIS Cut Line= 3
      2286977.81      7193354.22        2286779.        7193660.
      2286707.68      7193793.06
#Sta/Elev= 30
  4635.5  925.12  4639.5  921.06  4645.4  922.42  4660.6  915.31  4696.8  910.06
  4711.9   909.4  4717.9  911.26    4733   906.8    4739  908.38  4748.2  905.49
  4754.1  908.07  4775.2  902.81  4790.4   902.5  4805.5   910.2  4811.5  908.41
  4826.6  909.75  4841.7   914.5  4862.8   914.2  4868.3   916.2  4899.1  918.69
  4914.2  916.53  4956.4  902.38  4990.6  896.68  4990.9  896.18  4994.8  896.68
  5030.3  900.28    5036  905.05  5057.4  913.16  5102.3  921.83  5151.2  925.89
#Mann= 5 ,-1 , 0
  4635.5     .05       0  4868.3     .12       0  4990.6     .07       0
  4994.8     .12       0  5057.4     .05       0
#XS Ineff= 2 , 0
       0    4878  918.27               0
Permanent Ineff=
       F       F
Bank Sta=4990.6,4994.8
XS Rating Curve= 0 ,0
Exp/Cntr=0.3,0.1

Type RM Length L Ch R = 1 ,2071    ,245,245,245
BEGIN DESCRIPTION:
UDS St 07 4.1
END DESCRIPTION:
XS GIS Cut Line= 2
      2286693.35      7193387.25      2286563.57      7193699.78
#Sta/Elev= 30
  4855.9  937.15  4860.1  937.15  4877.7  931.94  4883.1  931.67  4901.6  923.49
    4907  922.25    4913  919.05  4923.8  916.26  4930.8  911.84  4954.7  901.59
  4958.5  901.05  4967.2  898.16  4989.4  896.29  4997.4  892.53  4997.8  892.03
  5001.8  892.53  5021.3  894.14  5037.1  893.77  5053.8  899.66    5061  903.74
  5075.4  908.72  5084.9   911.8  5095.4   913.9  5114.1   917.3    5138  918.26
  5143.4  917.01  5161.9  918.34  5167.3  916.94  5191.2  919.54  5194.3  918.42
#Mann= 4 ,-1 , 0
  4855.9     .12       0  4997.4     .07       0  5001.8     .12       0
  5095.4     .05       0
Bank Sta=4997.4,5001.8
XS Rating Curve= 0 ,0
Exp/Cntr=0.3,0.1

Type RM Length L Ch R = 1 ,1826    ,470,470,470
BEGIN DESCRIPTION:
UDS St 07 4.0
END DESCRIPTION:
XS GIS Cut Line= 3
       2286571.5       7193243.7        2286429.        7193410.
      2286293.79       7193588.7
#Sta/Elev= 30
    4781  939.63  4794.2  937.44  4801.9  937.66  4808.5   932.4  4822.7  932.11
  4829.3  928.13    4837  928.38  4843.6  923.26  4851.3  922.14  4857.9  917.64
  4865.6   916.9  4872.1  913.68  4879.8   913.1  4914.9  898.23  4957.7  894.15
  5003.1  893.56  5013.6  891.96  5019.6  889.17    5020  888.67    5024  889.17
  5042.7  891.59  5057.2  898.87  5107.2  900.67    5128  899.35  5143.4  900.87
  5177.9  906.83  5192.5  912.23  5213.3  916.23  5221.6  916.14  5224.1  917.69
#Mann= 4 ,-1 , 0
    4781     .12       0  5019.6     .07       0    5024     .12       0
  5143.4     .05       0
Bank Sta=5019.6,5024
XS Rating Curve= 0 ,0
Exp/Cntr=0.3,0.1

Type RM Length L Ch R = 1 ,1356    ,410,410,410
BEGIN DESCRIPTION:
UDS St 07 3.0
END DESCRIPTION:
XS GIS Cut Line= 3
      2286228.97      7193110.01       2286051.2      7193204.76
        2286003.      7193453.59
#Sta/Elev= 30
  4694.3  931.02  4697.1  931.02  4702.4  926.95  4708.1  925.27    4730  921.21
  4746.3  920.66    4752  918.25  4762.3  916.78    4774  910.47  4796.3  902.64
  4818.9  896.25  4828.5  894.74  4872.5  890.31  4911.3   891.4  4930.1  893.51
  4935.2  892.31  4962.2  894.03  4992.8  890.84  5013.1  884.46  5021.1  884.32
  5021.5  883.82  5025.6  884.32  5043.8  885.14  5053.9  886.95  5064.1  895.13
  5084.4  906.72  5090.4  912.69  5095.5  913.04  5104.8  917.01  5149.2  920.34
#Mann= 3 ,-1 , 0
  4694.3     .12       0  5021.1     .07       0  5025.6     .12       0
Bank Sta=5021.1,5025.6
XS Rating Curve= 0 ,0
Exp/Cntr=0.3,0.1

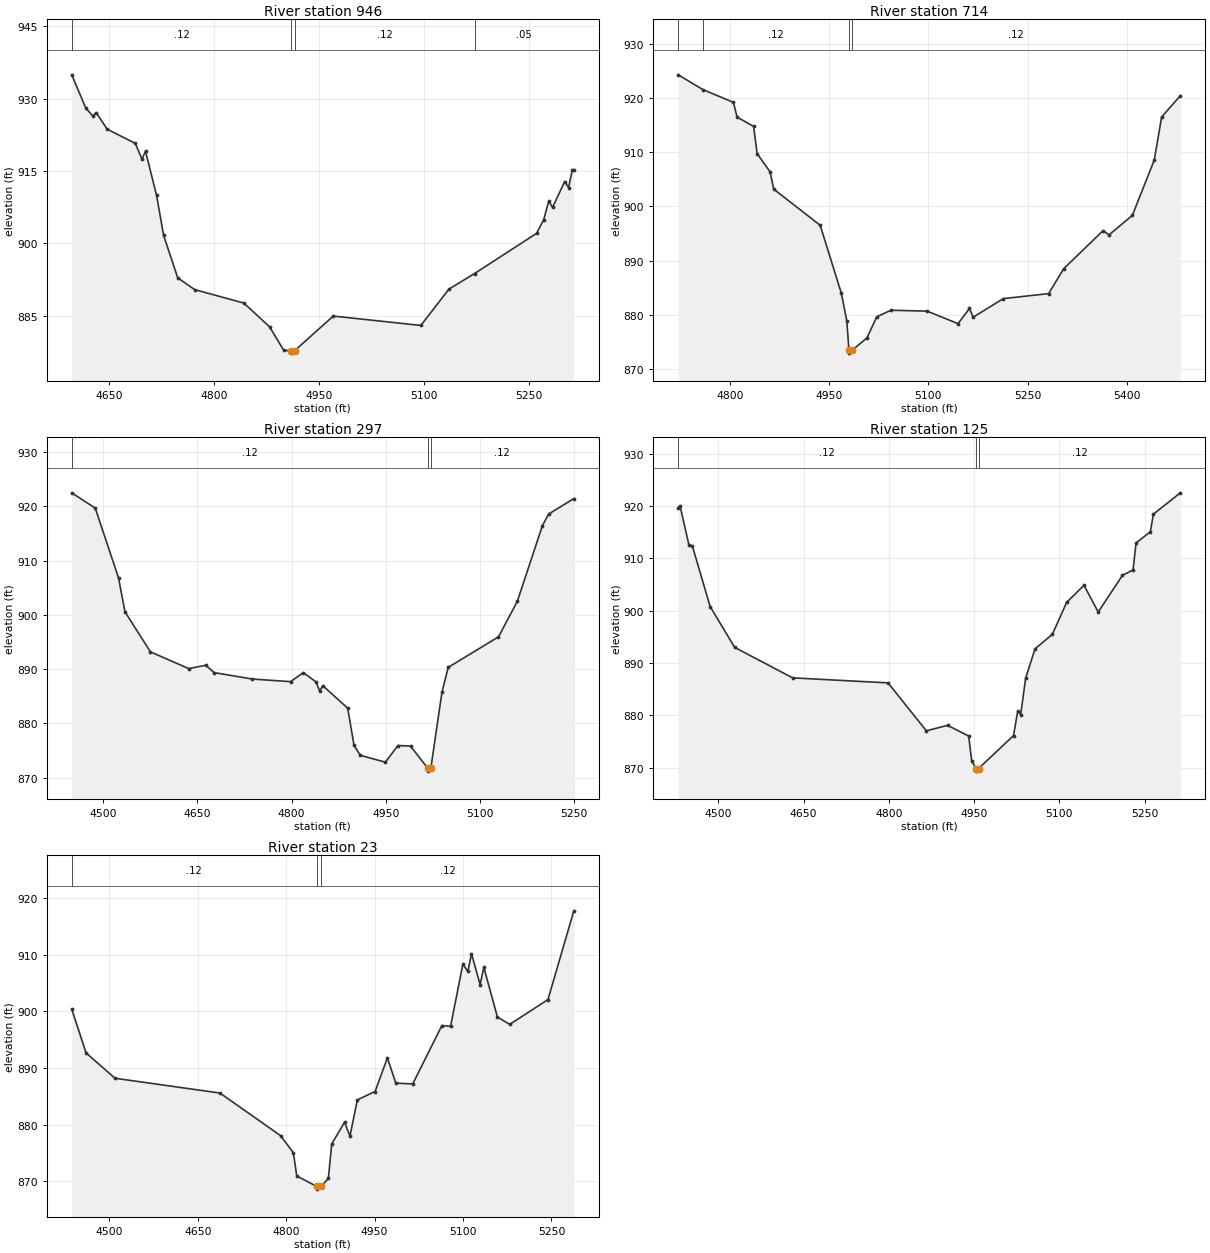
Type RM Length L Ch R = 1 ,946     ,232,232,232
BEGIN DESCRIPTION:
UDS St 07 2.0
END DESCRIPTION:
XS GIS Cut Line= 3
      2286228.96      7193010.01      2285747.43      7193079.67
      2285649.51      7193289.07
#Sta/Elev= 30
  4596.6  934.93  4616.8  927.99  4626.6  926.43  4631.7  927.08  4647.1  923.68
  4687.5  920.71  4696.9  917.46    4702  919.11  4717.8  909.96  4727.9  901.64
  4748.1  892.85  4772.3  890.41  4842.6  887.63  4879.5  882.68  4899.7  877.81
  4910.6  877.75    4911  877.25  4915.1  877.75  4970.4  884.93  5095.6  882.99
  5135.8  890.52  5172.3  893.74  5261.1  902.08  5271.2   904.9  5278.4  908.72
  5283.9  907.46  5301.2   912.8  5306.8  911.56  5312.1  915.26  5314.3  915.26
#Mann= 4 ,-1 , 0
  4596.6     .12       0  4910.6     .07       0  4915.1     .12       0
  5172.3     .05       0
Bank Sta=4910.6,4915.1
XS Rating Curve= 0 ,0
Exp/Cntr=0.3,0.1

Type RM Length L Ch R = 1 ,714     ,417,417,417
BEGIN DESCRIPTION:
UDS St 07 1.1
END DESCRIPTION:
XS GIS Cut Line= 3
      2286039.77      7192754.91      2285659.59      7192896.86
      2285509.66      7193215.54
#Sta/Elev= 30
  4722.3  924.24  4759.7  921.51  4805.7  919.16  4811.1  916.46  4836.1  914.73
  4841.4  909.72    4861  906.38  4866.4   903.2  4936.6  896.53  4968.6     884
  4976.9  878.84    4980  873.49  4980.4  872.99  4984.5  873.49  5007.2  875.78
    5022  879.68  5043.4  880.89  5098.1  880.72  5144.7  878.42    5162  881.21
  5167.5   879.6  5213.1  883.03  5281.5  883.95  5304.3  888.54  5363.7  895.55
  5372.7  894.76  5407.9  898.36    5441  908.55  5452.1  916.48  5480.3  920.39
#Mann= 4 ,-1 , 0
  4722.3     .05       0  4759.7     .12       0    4980     .07       0
  4984.5     .12       0
Bank Sta=4980,4984.5
XS Rating Curve= 0 ,0
Exp/Cntr=0.3,0.1

Type RM Length L Ch R = 1 ,297     ,172,172,172
BEGIN DESCRIPTION:
UDS St 07 1.0
END DESCRIPTION:
XS GIS Cut Line= 3
      2285549.96      7192416.54      2285480.63       7192826.1
        2285479.      7193210.01
#Sta/Elev= 30
  4449.9  922.52  4487.3  919.69  4524.4  906.81  4534.5   900.6  4575.1   893.2
    4636  890.11  4663.3  890.72  4676.5  889.37  4737.4  888.18  4798.2   887.7
  4818.5  889.36  4838.8  887.65  4844.5  885.98  4849.6  886.96  4889.2   882.8
  4899.2  875.99  4909.2  874.11  4949.2  872.85  4969.2  875.92  4989.2  875.83
  5016.8   871.7  5017.3   871.2  5021.5   871.7  5039.2  885.73  5049.2  890.33
  5129.2  895.96  5159.2   902.5  5199.2  916.48  5209.2  918.61  5249.2  921.46
#Mann= 3 ,-1 , 0
  4449.9     .12       0  5016.8     .07       0  5021.5     .12       0
Bank Sta=5016.8,5021.5
XS Rating Curve= 0 ,0
Exp/Cntr=0.3,0.1

Type RM Length L Ch R = 1 ,125     ,102,102,102
BEGIN DESCRIPTION:
UDS St 07 0.9
END DESCRIPTION:
XS GIS Cut Line= 3
      2285534.36       7192450.2      2285299.41      7192856.94
      2285441.68       7193245.7
#Sta/Elev= 30
  4429.2  919.69  4432.3  920.07  4448.1  912.51  4453.9  912.41  4485.4  900.79
  4528.5     893  4630.5  887.18  4798.5  886.22  4865.9  877.07  4903.2  878.11
  4940.4  876.07  4945.7  871.37  4953.1  869.87  4953.6  869.37  4957.8  869.87
  5019.3  876.15  5026.7  880.81    5032  880.16  5040.6  887.08  5057.2  892.72
  5087.7  895.49  5112.9   901.6  5143.4  904.86  5168.4  899.75    5211  906.75
  5229.7  907.78    5235  912.94  5260.2  915.09  5265.5  918.43  5312.9  922.51
#Mann= 3 ,-1 , 0
  4429.2     .12       0  4953.1     .07       0  4957.8     .12       0
Bank Sta=4953.1,4957.8
XS Rating Curve= 0 ,0
Exp/Cntr=0.3,0.1

Type RM Length L Ch R = 1 ,23      ,0,0,0
BEGIN DESCRIPTION:
UDS St 07 0.8
END DESCRIPTION:
XS GIS Cut Line= 4
      2285448.08      7192507.87      2285204.11      7192944.43
      2285279.45      7193036.08      2285417.02      7193224.44
#Sta/Elev= 30
  4436.1  900.38  4460.3  892.67  4509.5  888.18  4687.6  885.57  4790.4  878.04
  4812.1  875.03  4817.9  870.92  4851.4  869.09  4852.6  868.59  4859.7  869.09
  4871.5   870.5  4877.3   876.6    4899   880.4  4908.2  877.96  4920.7  884.36
  4950.8  885.84  4971.7  891.79    4986  887.32  5014.7  887.18  5064.2   897.5
  5078.9  897.35  5099.8  908.36  5108.2  907.05  5114.4  910.18  5129.1  904.73
  5135.3   907.8  5158.4     899  5179.3   897.7  5244.2  902.09  5288.1  917.77
#Mann= 3 ,-1 , 0
  4436.1     .12       0  4851.4     .07       0  4859.7     .12       0
Bank Sta=4851.4,4859.7
XS Rating Curve= 0 ,0
Exp/Cntr=0.3,0.1

Chan Stop Cuts=-1
Use User Specified Reach Order=0
Composite Channel Slope=5