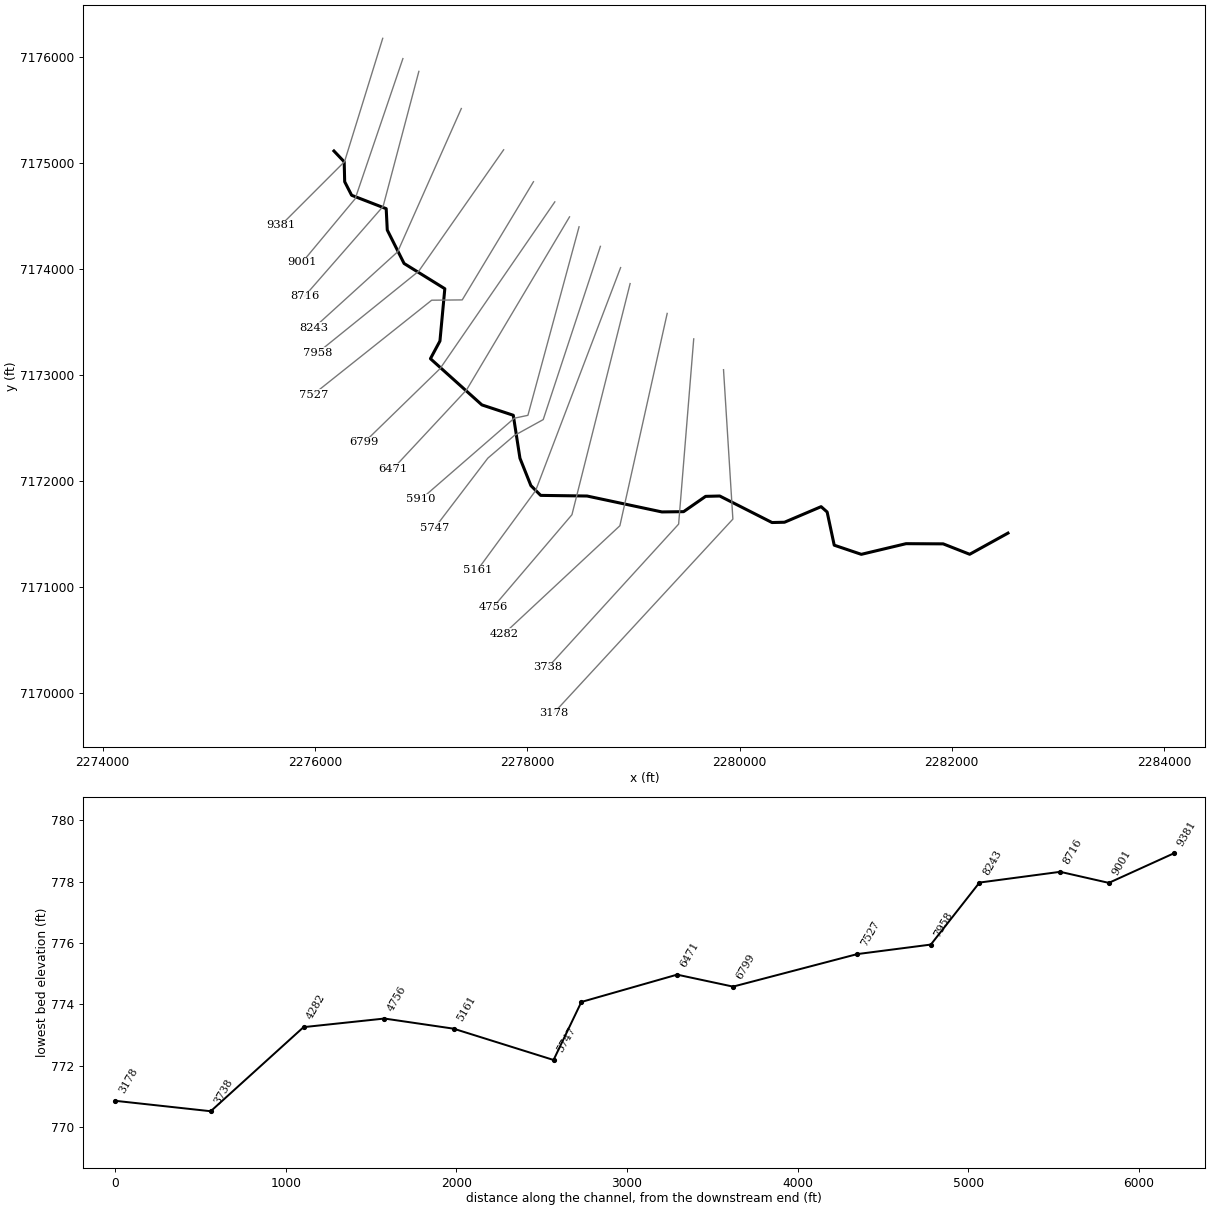
--- UDS St 11.prj (project) ---

Proj Title=UDS St 11 Base Level Engineering
Current Plan=p01
Default Exp/Contr=0.3,0.1
English Units
Geom File=g01
Flow File=f01
Plan File=p01
BEGIN DESCRIPTION:
UDS St 11
END DESCRIPTION:

--- UDS St 11.p01 (plan) ---

Plan Title=Multiple Run
Short Identifier=Multiple
Geom File=g01
Flow File=f01
Subcritical Flow
K Sum by GR= 0
Std Step Tol= 0.01
Critical Tol= 0.01
Num of Std Step Trials= 20
Max Error Tol= 0.3
Flow Tol Ratio= 0.001
Split Flow NTrial= 30
Split Flow Tol= 0.02
Split Flow Ratio= 0.02
Log Output Level= 0
Friction Slope Method= 1
Unsteady Friction Slope Method= 2
Unsteady Bridges Friction Slope Method= 1
Parabolic Critical Depth
Global Vel Dist=  1 , 1 , 1
Global Log Level= 0
CheckData=True
Encroach Param= -1, 0, 0, 0
BEGIN DESCRIPTION:
Multiple Run
END DESCRIPTION:

--- UDS St 11.f01 (steady flow) ---

Flow Title=Multiple
Number of Profiles=7
Profile Names=10-year,25-year,50-year,1pct_min,100-year,1pct_plu,500-year
River Rch & RM= UDS St 11,Reach-1,9381
     726    1009    1247     766    1528    3048    2295
River Rch & RM= UDS St 11,Reach-1,5747
     945    1326    1648    1015    2026    4043    3070
Boundary for River Rch & Prof#=UDS St 11,Reach-1,1
Up Type=0
Dn Type=3
Dn Slope=0.005
Boundary for River Rch & Prof#=UDS St 11,Reach-1,2
Up Type=0
Dn Type=3
Dn Slope=0.005
Boundary for River Rch & Prof#=UDS St 11,Reach-1,3
Up Type=0
Dn Type=3
Dn Slope=0.005
Boundary for River Rch & Prof#=UDS St 11,Reach-1,4
Up Type=0
Dn Type=3
Dn Slope=0.005
Boundary for River Rch & Prof#=UDS St 11,Reach-1,5
Up Type=0
Dn Type=3
Dn Slope=0.005
Boundary for River Rch & Prof#=UDS St 11,Reach-1,6
Up Type=0
Dn Type=3
Dn Slope=0.005
Boundary for River Rch & Prof#=UDS St 11,Reach-1,7
Up Type=0
Dn Type=3
Dn Slope=0.005

--- UDS St 11.g01 (geometry) ---

Geom Title=Existing Conditions

River Reach=UDS St 11,Reach-1
Reach XY= 30
      2276179.00      7175110.00      2276275.52      7175008.56
      2276280.20      7174820.50      2276345.48      7174692.94
      2276671.33      7174566.52      2276681.35      7174365.52
      2276839.76      7174050.30      2277223.55      7173812.47
      2277177.64      7173319.65      2277088.11      7173153.27
      2277572.83      7172717.86      2277868.68      7172620.17
      2277931.44      7172215.56      2278034.52      7171957.56
      2278126.53      7171865.45      2278563.78      7171859.48
      2279268.81      7171709.55      2279473.14      7171712.06
      2279680.56      7171856.26      2279813.78      7171859.50
      2280306.03      7171609.70      2280423.47      7171612.34
      2280768.69      7171759.14      2280825.49      7171708.75
      2280892.20      7171396.26      2281147.33      7171310.06
      2281568.81      7171410.45      2281918.50      7171408.78
      2282168.38      7171310.60      2282529.00      7171510.00

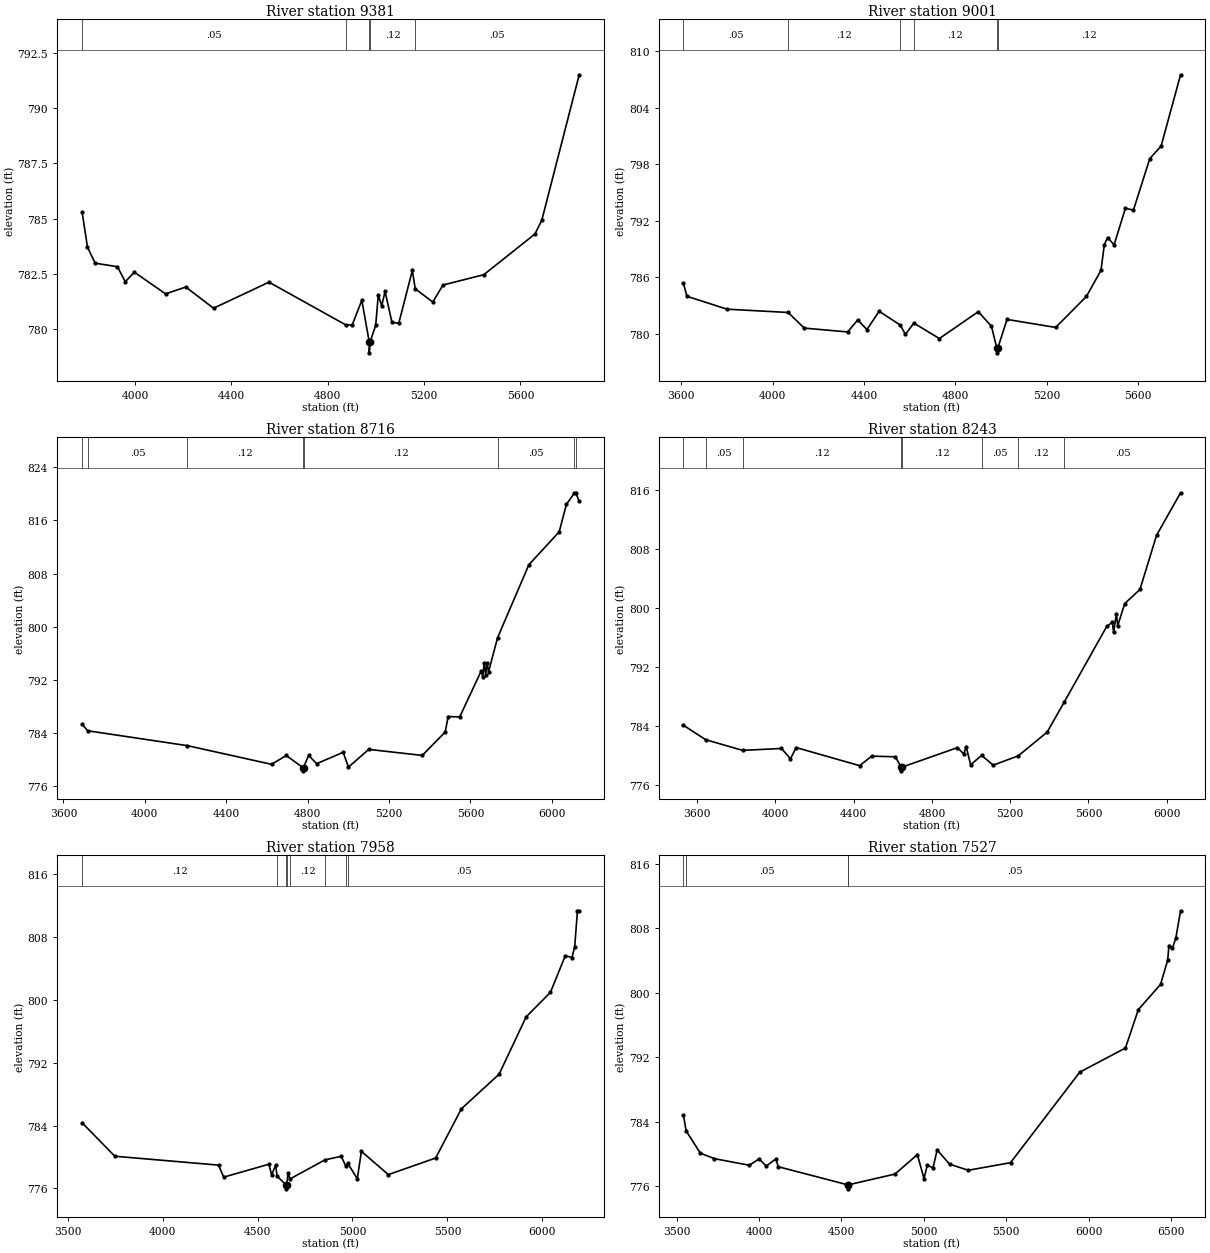
Type RM Length L Ch R = 1,9381,380,380,380
BEGIN DESCRIPTION:
UDS St 11 13.0
END DESCRIPTION:
XS GIS Cut Line= 3
      2276638.55      7176171.32      2276279.00      7175010.00
      2275679.02      7174410.02
#Sta/Elev= 30
  3780.1  785.30  3802.4  783.71  3834.2  782.98  3926.8  782.82  3959.4  782.14
  3997.2  782.57  4126.9  781.59  4210.7  781.90  4325.8  780.94  4556.1  782.12
  4874.1  780.19  4901.6  780.18  4941.7  781.30  4972.3  779.42  4972.5  778.92
  4976.3  779.42  4999.3  780.17  5009.9  781.54  5024.1  781.05  5038.2  781.70
  5066.5  780.31  5094.8  780.25  5151.4  782.65  5163.4  781.82  5236.2  781.22
  5278.6  781.99  5448.4  782.46  5660.5  784.30  5688.8  784.92  5844.3  791.51
#Mann=5,-1,0
  3780.1    0.05       0  4874.1    0.12       0  4972.3    0.07       0
  4976.3    0.12       0  5163.4    0.05       0
Bank Sta=4972.3,4976.3
Exp/Cntr=0.3,0.1

Type RM Length L Ch R = 1,9001,285,285,285
BEGIN DESCRIPTION:
UDS St 11 12.0
END DESCRIPTION:
XS GIS Cut Line= 3
      2276828.64      7175980.46      2276379.00      7174660.00
      2275879.03      7174060.03
#Sta/Elev= 30
  3609.2  785.35  3624.6  783.97  3799.8  782.60  4067.6  782.25  4137.9  780.59
  4328.0  780.18  4371.9  781.45  4412.5  780.44  4465.9  782.38  4558.3  780.91
  4580.8  779.92  4617.6  781.12  4729.5  779.48  4899.6  782.33  4957.1  780.80
  4981.0  778.46  4981.2  777.96  4985.0  778.46  5025.6  781.51  5238.4  780.66
  5373.2  783.96  5436.9  786.73  5451.3  789.44  5465.6  790.21  5494.2  789.44
  5543.7  793.32  5578.8  793.13  5650.4  798.60  5699.9  799.93  5785.1  807.51
#Mann=6,-1,0
  3609.2    0.05       0  4067.6    0.12       0  4558.3    0.05       0
  4617.6    0.12       0  4981.0    0.07       0  4985.0    0.12       0
Bank Sta=4981,4985
Exp/Cntr=0.3,0.1

Type RM Length L Ch R = 1,8716,473,473,473
BEGIN DESCRIPTION:
UDS St 11 11.0
END DESCRIPTION:
XS GIS Cut Line= 3
      2276979.01      7175860.04      2276642.29      7174588.17
      2275900.54      7173739.52
#Sta/Elev= 30
  3691.9  785.33  3719.6  784.35  4209.6  782.11  4622.9  779.30  4695.4  780.63
  4776.1  778.82  4776.4  778.32  4780.1  778.82  4804.8  780.63  4845.0  779.40
  4974.7  781.11  5000.7  778.88  5100.5  781.55  5363.4  780.64  5476.3  784.16
  5490.6  786.49  5547.5  786.44  5653.8  793.39  5660.5  792.41  5668.1  794.62
  5674.7  792.78  5682.3  794.58  5689.0  793.21  5733.7  798.37  5887.3  809.34
  6036.4  814.30  6071.5  818.41  6110.0  820.10  6117.3  820.17  6134.7  818.90
#Mann=8,-1,0
  3691.9    0.12       0  3719.6    0.05       0  4209.6    0.12       0
  4776.1    0.07       0  4780.1    0.12       0  5733.7    0.05       0
  6110.0    0.12       0  6117.3    0.05       0
Bank Sta=4776.1,4780.1
Exp/Cntr=0.3,0.1

Type RM Length L Ch R = 1,8243,285,285,285
BEGIN DESCRIPTION:
UDS St 11 10.0
END DESCRIPTION:
XS GIS Cut Line= 3
      2277379.00      7175510.01      2276779.00      7174160.00
      2275990.99      7173444.67
#Sta/Elev= 30
  3529.3  784.14  3642.7  782.19  3831.7  780.74  4030.6  781.00  4076.5  779.60
  4105.9  781.12  4430.1  778.67  4492.3  779.96  4612.7  779.87  4642.8  778.47
  4643.1  777.97  4646.8  778.47  4930.0  781.11  4962.9  780.26  4974.5  781.26
  4997.7  778.79  5053.6  780.06  5113.1  778.74  5241.1  780.00  5388.8  783.21
  5476.9  787.31  5693.6  797.52  5721.9  798.07  5728.7  796.71  5742.9  799.24
  5749.6  797.61  5785.5  800.61  5863.2  802.52  5948.3  809.86  6070.9  815.61
#Mann=8,-1,0
  3529.3    0.12       0  3642.7    0.05       0  3831.7    0.12       0
  4642.8    0.07       0  4646.8    0.12       0  5053.6    0.05       0
  5241.1    0.12       0  5476.9    0.05       0
Bank Sta=4642.8,4646.8
Exp/Cntr=0.3,0.1

Type RM Length L Ch R = 1,7958,431,431,431
BEGIN DESCRIPTION:
UDS St 11 9.1
END DESCRIPTION:
XS GIS Cut Line= 3
      2277777.75      7175121.25      2276977.63      7173977.52
      2276026.08      7173209.72
#Sta/Elev= 30
  3575.9  784.36  3748.3  780.10  4294.5  778.97  4321.9  777.44  4559.6  779.08
  4574.4  777.75  4595.4  778.97  4603.0  777.56  4650.0  776.45  4650.3  775.95
  4654.0  776.45  4660.8  778.02  4670.6  777.20  4855.2  779.64  4940.7  780.09
  4965.6  778.81  4975.8  779.19  5025.6  777.22  5047.1  780.73  5188.8  777.76
  5438.2  779.87  5573.9  786.14  5772.5  790.54  5914.8  797.84  6042.8  800.96
  6121.1  805.62  6156.3  805.39  6170.7  806.79  6185.1  811.34  6194.4  811.32
#Mann=8,-1,0
  3575.9    0.12       0  4603.0    0.05       0  4650.0    0.04       0
  4654.0    0.05       0  4670.6    0.12       0  4855.2    0.05       0
  4965.6    0.12       0  4975.8    0.05       0
Bank Sta=4650,4654
Exp/Cntr=0.3,0.1

Type RM Length L Ch R = 1,7527,728,728,728
BEGIN DESCRIPTION:
UDS St 11 9.0
END DESCRIPTION:
XS GIS Cut Line= 4
      2278058.74      7174820.29      2277387.58      7173707.05
      2277099.85      7173704.28      2275983.73      7172815.84
#Sta/Elev= 30
  3542.0  784.83  3558.3  782.84  3644.8  780.07  3730.2  779.39  3941.9  778.57
  4000.1  779.36  4044.4  778.47  4102.8  779.37  4116.6  778.39  4537.8  776.14
  4538.1  775.64  4541.8  776.14  4825.2  777.48  4960.5  779.90  5000.5  776.92
  5020.5  778.56  5055.3  778.25  5080.5  780.48  5155.3  778.71  5269.0  777.95
  5525.2  778.89  5944.9  790.14  6221.9  793.14  6300.4  797.92  6435.0  801.05
  6478.2  804.07  6485.6  805.88  6507.1  805.53  6527.9  806.85  6556.2  810.20
#Mann=4,-1,0
  3542.0    0.12       0  3558.3    0.05       0  4537.8    0.04       0
  4541.8    0.05       0
Bank Sta=4537.8,4541.8
Exp/Cntr=0.3,0.1

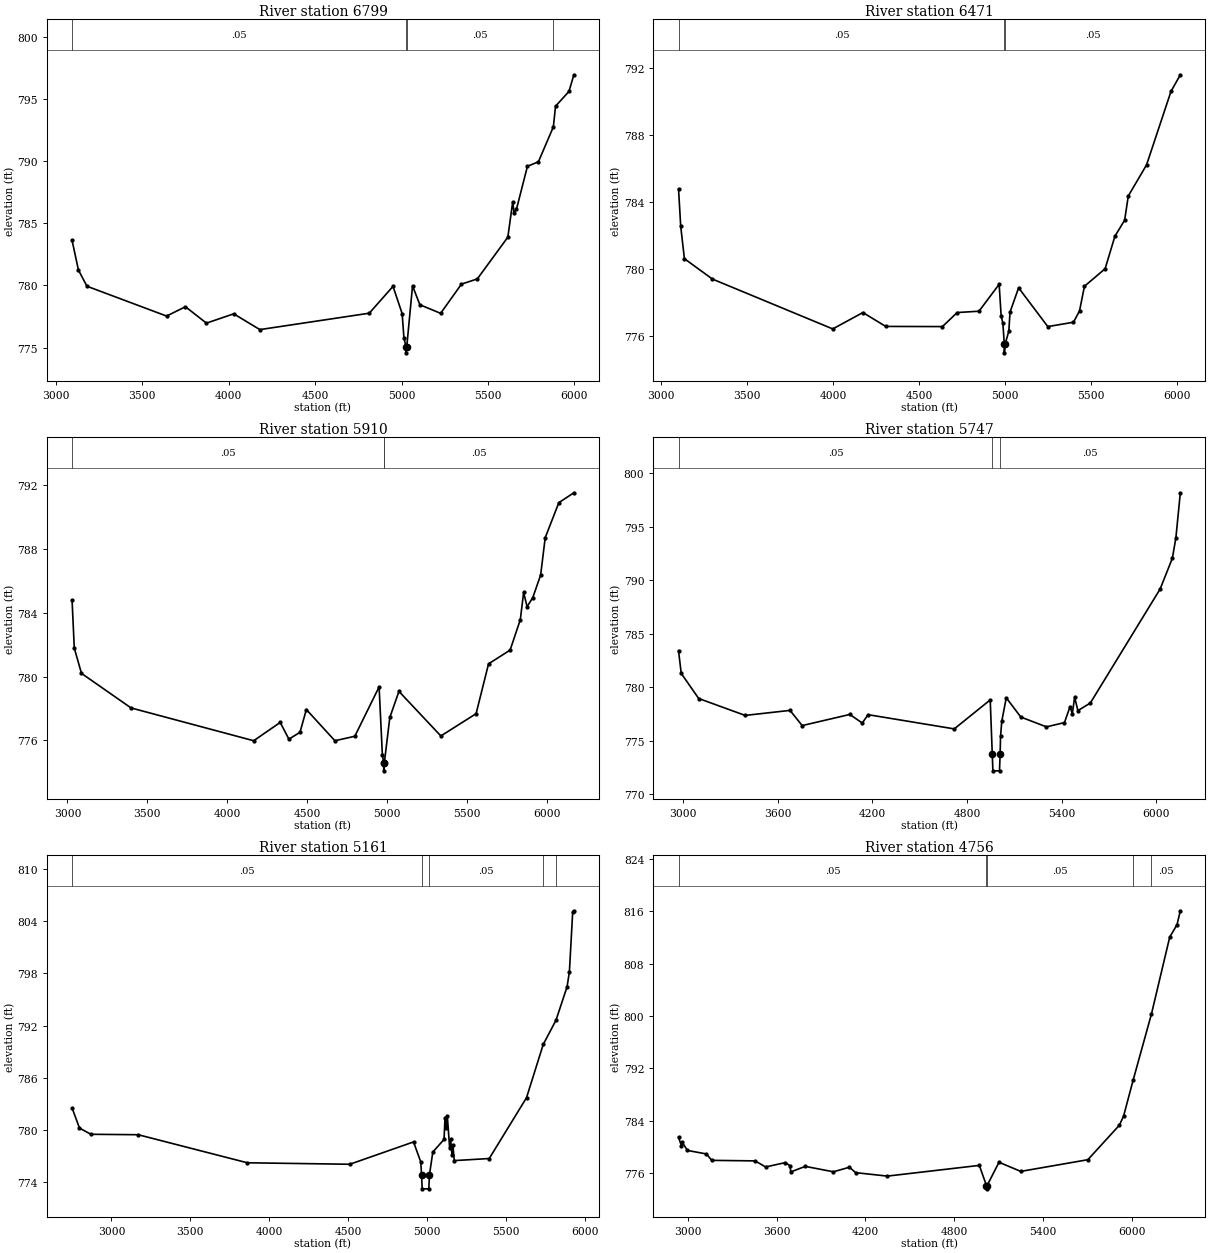
Type RM Length L Ch R = 1,6799,328,328,328
BEGIN DESCRIPTION:
UDS St 11 8.0
END DESCRIPTION:
XS GIS Cut Line= 3
      2278259.83      7174630.50      2277179.00      7173060.00
      2276464.49      7172364.49
#Sta/Elev= 30
  3093.3  783.63  3130.3  781.24  3179.5  779.94  3640.2  777.54  3749.4  778.29
  3870.8  776.97  4028.6  777.72  4180.0  776.45  4813.1  777.77  4950.4  779.93
  5003.3  777.74  5013.8  775.75  5026.0  775.08  5026.2  774.58  5030.0  775.08
  5063.4  779.97  5105.9  778.45  5226.0  777.76  5346.4  780.11  5438.2  780.53
  5614.9  783.89  5643.2  786.74  5650.4  785.86  5664.5  786.12  5728.1  789.59
  5791.9  789.96  5878.3  792.77  5890.9  794.43  5968.6  795.62  5996.9  796.96
#Mann=4,-1,0
  3093.3    0.05       0  5026.0   0.033       0  5030.0    0.05       0
  5878.3    0.12       0
Bank Sta=5026,5030
Exp/Cntr=0.3,0.1

Type RM Length L Ch R = 1,6471,561,561,561
BEGIN DESCRIPTION:
UDS St 11 7.0
END DESCRIPTION:
XS GIS Cut Line= 3
      2278398.45      7174489.29      2277429.00      7172860.00
      2276735.78      7172116.40
#Sta/Elev= 30
  3104.1  784.77  3116.8  782.53  3138.2  780.60  3301.1  779.38  3999.3  776.40
  4174.2  777.38  4306.7  776.55  4635.8  776.54  4721.5  777.38  4848.1  777.46
  4965.0  779.07  4976.7  777.17  4986.4  776.76  4995.1  775.47  4995.3  774.97
  4999.1  775.47  5021.2  776.27  5028.1  777.40  5077.9  778.86  5247.4  776.54
  5396.5  776.80  5431.6  777.48  5460.0  778.95  5580.1  780.00  5636.8  781.94
  5693.5  782.91  5714.5  784.35  5820.5  786.21  5962.2  790.60  6016.6  791.60
#Mann=3,-1,0
  3104.1    0.05       0  4995.1    0.04       0  4999.1    0.05       0
Bank Sta=4995.1,4999.1
Exp/Cntr=0.3,0.1

Type RM Length L Ch R = 1,5910,163,163,163
BEGIN DESCRIPTION:
UDS St 11 6.0
END DESCRIPTION:
XS GIS Cut Line= 4
      2278488.32      7174395.81      2278006.38      7172619.67
      2277878.02      7172592.46      2276998.09      7171828.15
#Sta/Elev= 30
  3029.3  784.80  3043.1  781.79  3088.1  780.20  3398.0  778.03  4164.7  775.97
  4330.5  777.12  4384.9  776.07  4454.2  776.50  4494.0  777.93  4672.4  775.97
  4796.8  776.25  4948.8  779.35  4969.2  775.10  4977.4  774.58  4977.7  774.08
  4981.5  774.58  5015.8  777.43  5072.8  779.07  5334.9  776.27  5555.2  777.67
  5633.1  780.80  5767.8  781.66  5831.6  783.57  5852.4  785.28  5873.8  784.39
  5909.4  784.95  5958.8  786.38  5987.3  788.72  6072.5  790.92  6166.4  791.54
#Mann=3,-1,0
  3029.3    0.05       0  4977.4    0.04       0  4981.5    0.05       0
Bank Sta=4977.4,4981.5
Exp/Cntr=0.3,0.1

Type RM Length L Ch R = 1,5747,586,586,586
BEGIN DESCRIPTION:
UDS St 11 5.0
END DESCRIPTION:
XS GIS Cut Line= 5
      2278689.24      7174211.42      2278150.65      7172579.50
      2277877.42      7172428.82      2277628.76      7172216.04
      2277129.00      7171560.00
#Sta/Elev= 30
  2971.0  783.42  2988.0  781.30  3098.9  778.95  3393.7  777.37  3678.0  777.84
  3755.3  776.42  4057.1  777.46  4136.2  776.66  4173.3  777.44  4719.7  776.11
  4947.8  778.82  4960.7  773.79  4964.7  772.19  5006.7  772.19  5010.7  773.79
  5013.3  775.40  5021.0  776.82  5049.5  779.02  5141.7  777.22  5304.2  776.30
  5418.6  776.70  5454.0  778.19  5468.5  777.51  5483.1  779.07  5503.9  777.82
  5582.8  778.53  6025.6  789.19  6103.2  792.07  6125.4  793.98  6153.5  798.18
#Mann=3,-1,0
  2971.0    0.05       0  4960.7   0.033       0  5010.7    0.05       0
Bank Sta=4960.7,5010.7
Exp/Cntr=0.3,0.1

Type RM Length L Ch R = 1,5161,405,405,405
BEGIN DESCRIPTION:
UDS St 11 4.0
END DESCRIPTION:
XS GIS Cut Line= 3
      2278879.66      7174011.34      2278079.00      7171910.00
      2277528.98      7171159.97
#Sta/Elev= 30
  2750.8  782.52  2797.6  780.21  2869.9  779.49  3169.6  779.44  3860.9  776.21
  4510.3  776.04  4913.9  778.61  4959.7  776.31  4964.8  774.81  4968.8  773.21
  5010.8  773.21  5014.8  774.81  5036.1  777.45  5107.2  778.90  5113.4  781.42
  5121.8  780.23  5128.0  781.57  5142.7  777.95  5148.9  778.90  5157.3  777.16
  5163.5  778.24  5172.0  776.46  5393.5  776.70  5629.7  783.70  5735.5  789.83
  5816.6  792.63  5886.7  796.48  5901.4  798.20  5922.2  805.08  5929.6  805.22
#Mann=5,-1,0
  2750.8    0.05       0  4964.8   0.033       0  5014.8    0.05       0
  5735.5    0.12       0  5816.6    0.05       0
Bank Sta=4964.8,5014.8
Exp/Cntr=0.3,0.1

Type RM Length L Ch R = 1,4756,474,474,474
BEGIN DESCRIPTION:
UDS St 11 3.0
END DESCRIPTION:
XS GIS Cut Line= 3
      2278969.32      7173860.75      2278421.27      7171683.36
      2277677.55      7170810.41
#Sta/Elev= 30
  2936.9  781.42  2955.9  780.17  2961.1  780.70  2997.0  779.42  3125.5  778.88
  3161.5  777.90  3454.4  777.82  3525.4  776.89  3659.9  777.56  3690.4  777.06
  3695.9  776.13  3793.6  776.98  3983.6  776.15  4092.6  776.85  4133.9  776.02
  4348.4  775.49  4970.2  777.13  5018.5  774.04  5018.9  773.54  5022.8  774.04
  5103.2  777.61  5250.4  776.21  5703.9  778.00  5916.9  783.28  5945.5  784.68
  6009.4  790.13  6134.1  800.33  6257.3  812.08  6306.7  813.98  6329.0  816.11
#Mann=5,-1,0
  2936.9    0.05       0  5018.5   0.033       0  5022.8    0.05       0
  6009.4    0.12       0  6134.1    0.05       0
Bank Sta=5018.5,5022.8
Exp/Cntr=0.3,0.1

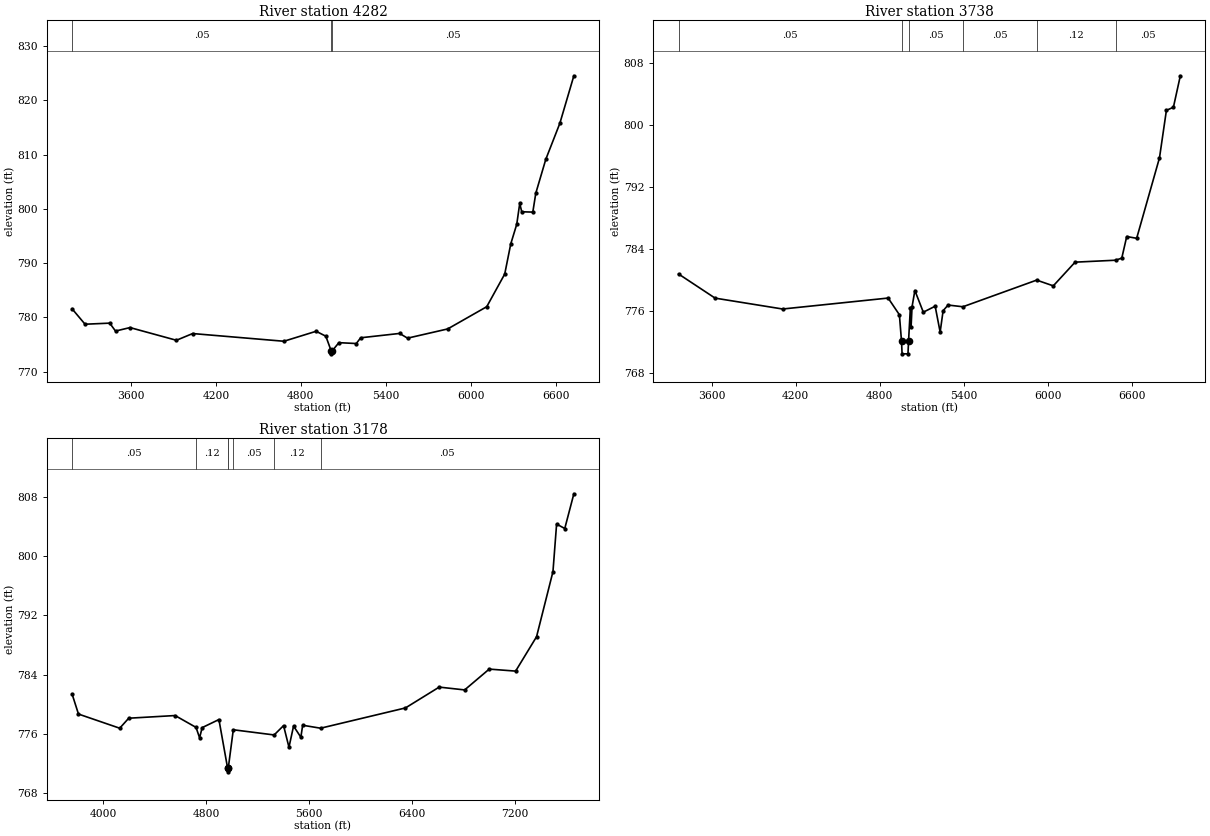
Type RM Length L Ch R = 1,4282,544,544,544
BEGIN DESCRIPTION:
UDS St 11 2.0
END DESCRIPTION:
XS GIS Cut Line= 3
      2279318.53      7173579.49      2278872.83      7171579.50
      2277779.02      7170560.02
#Sta/Elev= 30
  3184.6  781.56  3276.3  778.72  3450.5  778.92  3491.4  777.46  3593.9  778.10
  3921.7  775.76  4036.3  777.00  4680.8  775.58  4908.4  777.42  4977.0  776.51
  5015.5  773.76  5016.1  773.26  5020.4  773.76  5069.2  775.32  5192.2  775.16
  5222.9  776.22  5498.0  777.02  5554.2  776.15  5837.6  777.85  6113.6  781.95
  6240.6  787.97  6283.1  793.52  6325.6  797.16  6346.6  800.99  6360.8  799.45
  6439.0  799.39  6460.0  802.87  6530.8  809.13  6630.0  815.76  6728.9  824.52
#Mann=3,-1,0
  3184.6    0.05       0  5015.5   0.033       0  5020.4    0.05       0
Bank Sta=5015.5,5020.4
Exp/Cntr=0.3,0.1

Type RM Length L Ch R = 1,3738,560,560,560
BEGIN DESCRIPTION:
UDS St 11 1.0
END DESCRIPTION:
XS GIS Cut Line= 3
      2279568.54      7173339.92      2279426.31      7171594.86
      2278194.25      7170244.79
#Sta/Elev= 30
  3364.2  780.80  3625.0  777.69  4106.6  776.29  4859.1  777.70  4939.3  775.55
  4954.5  772.12  4958.5  770.52  5000.5  770.52  5004.5  772.12  5017.5  776.44
  5022.5  773.93  5029.6  776.58  5049.7  778.67  5109.9  775.88  5194.4  776.65
  5229.9  773.32  5251.1  776.07  5286.3  776.80  5392.3  776.58  5918.3  780.01
  6036.8  779.27  6192.3  782.32  6480.8  782.57  6525.3  782.84  6560.5  785.62
  6631.4  785.39  6794.2  795.75  6843.5  801.86  6893.5  802.26  6942.8  806.31
#Mann=6,-1,0
  3364.2    0.05       0  4954.5    0.07       0  5004.5    0.05       0
  5392.3    0.05       0  5918.3    0.12       0  6480.8    0.05       0
Bank Sta=4954.5,5004.5
Exp/Cntr=0.3,0.1

Type RM Length L Ch R = 1,3178,0,0,0
BEGIN DESCRIPTION:
UDS St 11 0.9
END DESCRIPTION:
XS GIS Cut Line= 3
      2279849.25      7173049.66      2279937.42      7171641.92
      2278247.32      7169811.72
#Sta/Elev= 30
  3757.9  781.37  3807.7  778.66  4128.3  776.75  4198.4  778.10  4559.1  778.46
  4721.8  776.86  4749.5  775.45  4769.5  776.83  4899.8  777.92  4967.3  771.36
  4968.0  770.86  4972.5  771.36  5011.5  776.54  5329.1  775.84  5402.4  777.10
  5444.4  774.18  5480.1  777.04  5536.8  775.53  5551.0  777.15  5690.3  776.75
  6350.5  779.49  6612.5  782.30  6810.4  781.92  7001.5  784.73  7206.8  784.46
  7369.5  789.10  7497.1  797.89  7525.4  804.31  7588.9  803.71  7659.6  808.40
#Mann=7,-1,0
  3757.9    0.05       0  4721.8    0.12       0  4967.3    0.07       0
  4972.5    0.12       0  5011.5    0.05       0  5329.1    0.12       0
  5690.3    0.05       0
Bank Sta=4967.3,4972.5
Exp/Cntr=0.3,0.1

Chan Stop Cuts=-1