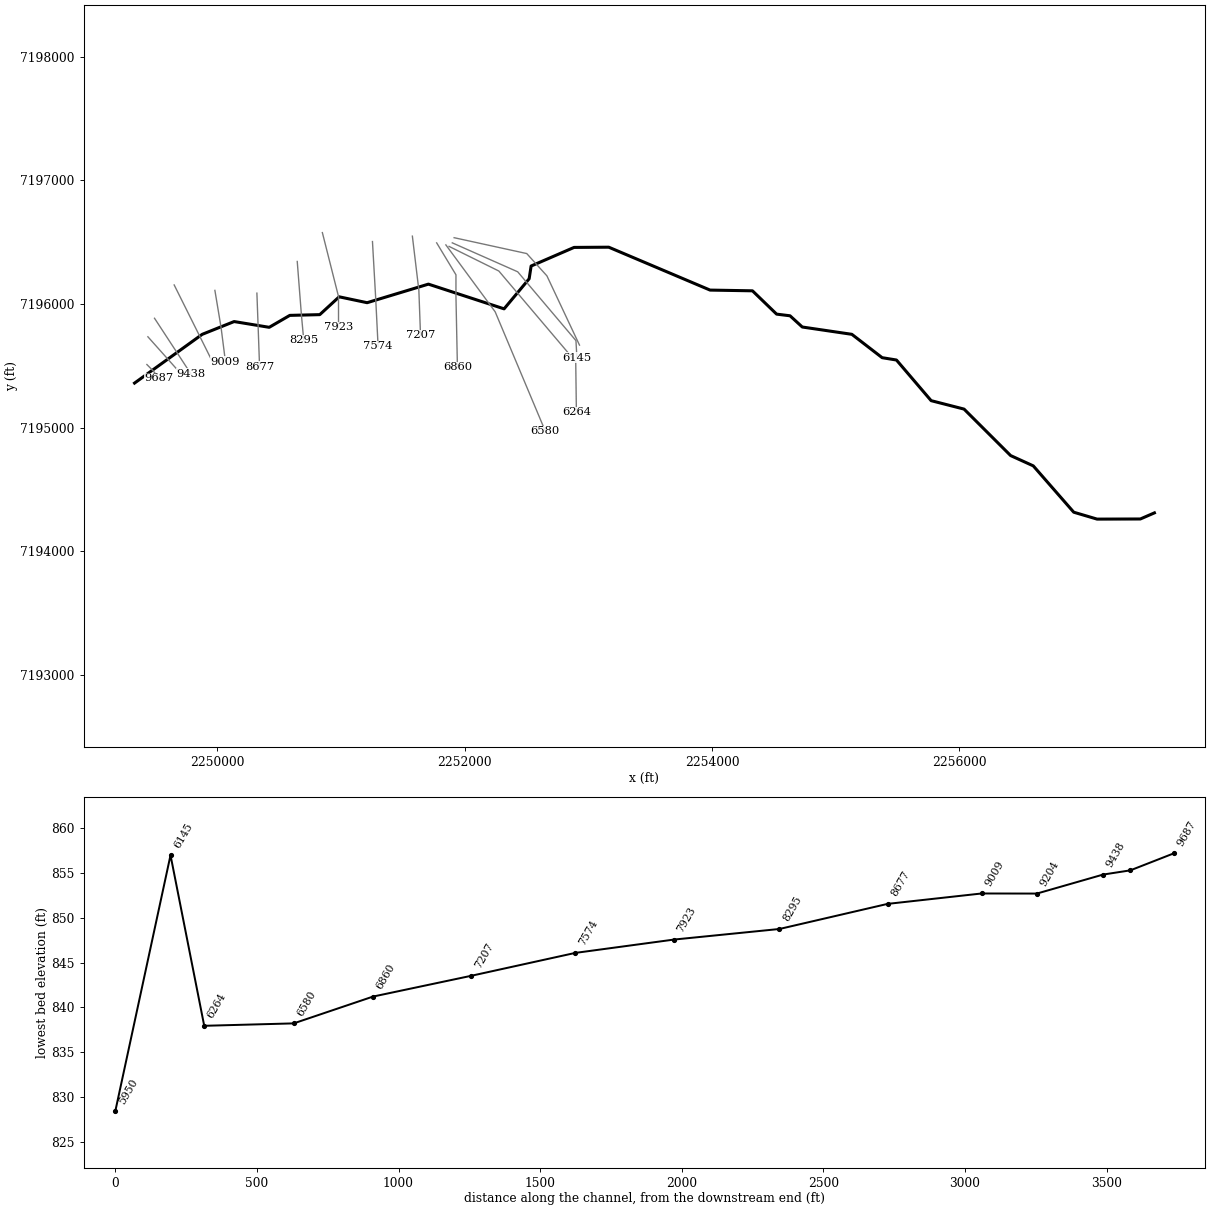
--- UDS St 35.prj (project) ---

Proj Title=UDS St 35 Base Level Engineering
Current Plan=p01
Default Exp/Contr=0.3,0.1
English Units
Geom File=g01
Flow File=f01
Plan File=p01
Y Axis Title=Elevation
X Axis Title(PF)=Main Channel Distance
X Axis Title(XS)=Station
BEGIN DESCRIPTION:
UDS St 35
END DESCRIPTION:
DSS Export Rating Curves= 0
DSS Export Rating Curve Sorted= 0
DSS Export Volume Flow Curves= 0
DXF OffsetX= 0
DXF OffsetY= 0
DXF ScaleX= 1
DXF ScaleY= 10

--- UDS St 35.p01 (plan) ---

Plan Title=Multiple Run
Short Identifier=Multiple
Geom File=g01
Flow File=f01
Subcritical Flow
K Sum by GR= 0
Std Step Tol= 0.01
Critical Tol= 0.01
Num of Std Step Trials= 20
Max Error Tol= 0.3
Flow Tol Ratio= 0.001
Split Flow NTrial= 30
Split Flow Tol= 0.02
Split Flow Ratio= 0.02
Log Output Level= 0
Friction Slope Method= 1
Unsteady Friction Slope Method= 2
Unsteady Bridges Friction Slope Method= 1
Parabolic Critical Depth
Global Vel Dist=  1 , 1 , 1
Global Log Level= 0
CheckData=True
Encroach Param= -1, 0, 0, 0
BEGIN DESCRIPTION:
Multiple Run
END DESCRIPTION:

--- UDS St 35.f01 (steady flow) ---

Flow Title=Multiple
Number of Profiles=7
Profile Names=10-year,25-year,50-year,1pct_min,100-year,1pct_plu,500-year
River Rch & RM= UDS St 35,Reach-1,9687
     472     648     794     484     967    1928    1434
River Rch & RM= UDS St 35,Reach-1,9204
     705     989    1229     759    1514    3022    2306
River Rch & RM= UDS St 35,Reach-1,6264
     944    1347    1694    1058    2110    4210    3284
Boundary for River Rch & Prof#=UDS St 35,Reach-1,1
Up Type=0
Dn Type=3
Dn Slope=0.005
Boundary for River Rch & Prof#=UDS St 35,Reach-1,2
Up Type=0
Dn Type=3
Dn Slope=0.005
Boundary for River Rch & Prof#=UDS St 35,Reach-1,3
Up Type=0
Dn Type=3
Dn Slope=0.005
Boundary for River Rch & Prof#=UDS St 35,Reach-1,4
Up Type=0
Dn Type=3
Dn Slope=0.005
Boundary for River Rch & Prof#=UDS St 35,Reach-1,5
Up Type=0
Dn Type=3
Dn Slope=0.005
Boundary for River Rch & Prof#=UDS St 35,Reach-1,6
Up Type=0
Dn Type=3
Dn Slope=0.005
Boundary for River Rch & Prof#=UDS St 35,Reach-1,7
Up Type=0
Dn Type=3
Dn Slope=0.005

--- UDS St 35.g01 (geometry) ---

Geom Title=Existing Conditions

River Reach=UDS St 35,Reach-1
Reach XY= 30
      2249329.00      7195360.00      2249876.58      7195754.46
      2250134.56      7195857.74      2250418.50      7195811.19
      2250584.93      7195907.76      2250827.48      7195913.74
      2250984.31      7196057.98      2251210.25      7196010.35
      2251706.25      7196160.50      2252318.39      7195960.59
      2252521.10      7196203.89      2252537.01      7196306.97
      2252884.53      7196457.62      2253165.08      7196459.32
      2253984.52      7196112.35      2254327.54      7196106.46
      2254522.83      7195917.86      2254631.42      7195904.46
      2254730.50      7195813.62      2255131.45      7195754.53
      2255376.58      7195565.54      2255492.33      7195546.61
      2255772.83      7195217.86      2256039.08      7195149.56
      2256415.79      7194773.62      2256599.09      7194690.22
      2256926.33      7194315.42      2257115.18      7194259.56
      2257465.11      7194260.60      2257579.00      7194310.00

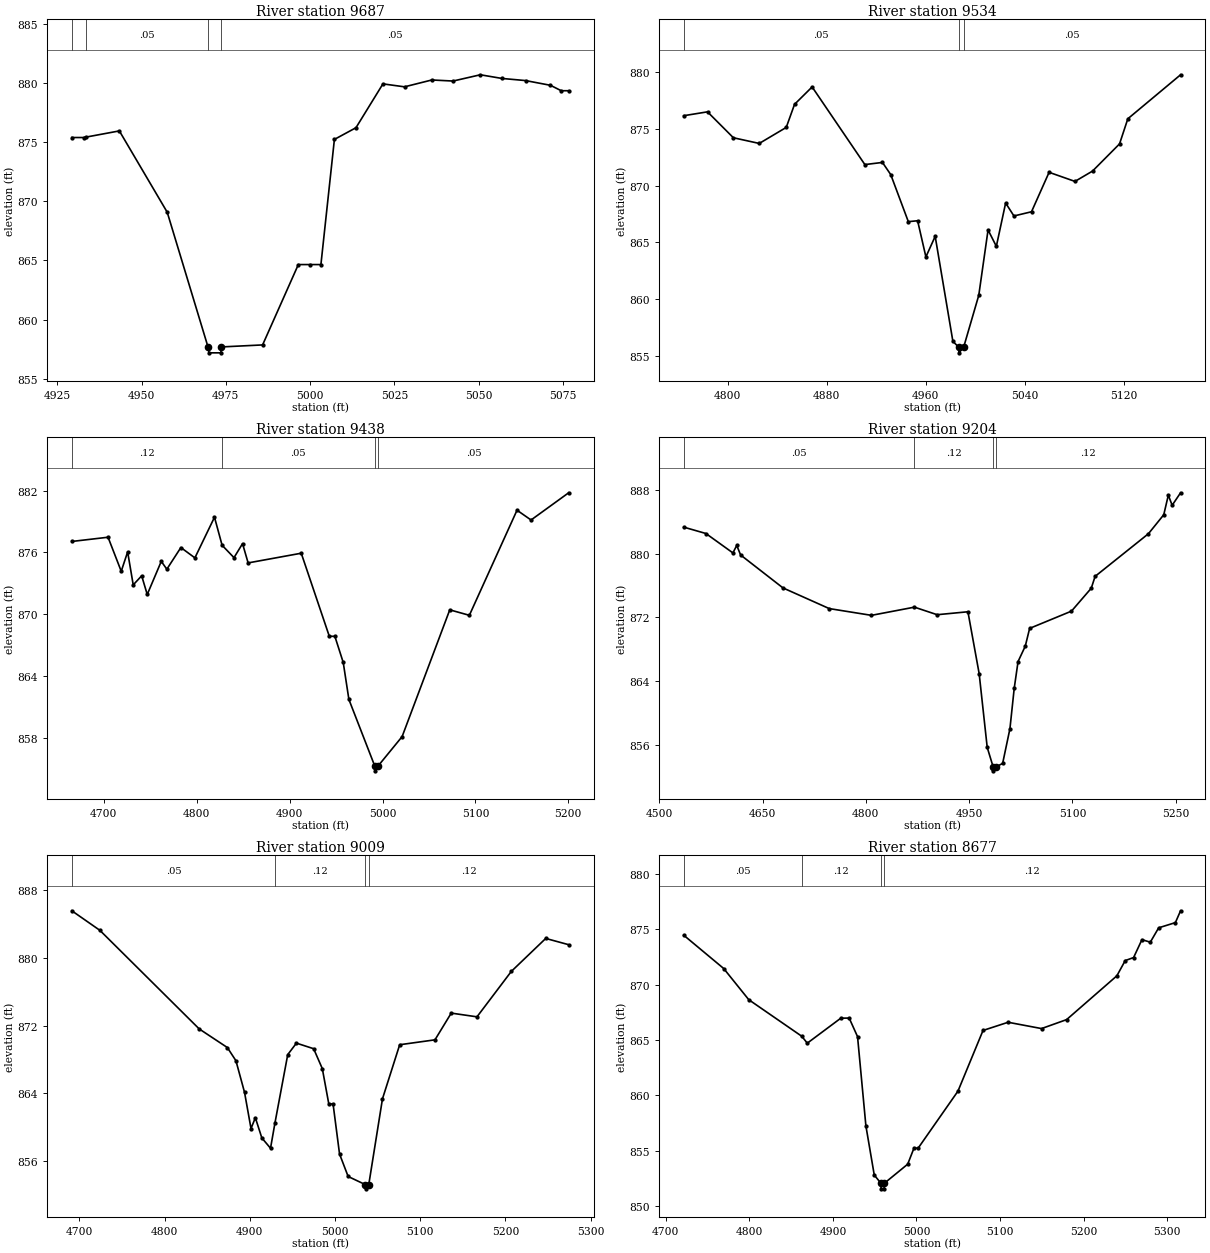
Type RM Length L Ch R = 1,9687,153,153,153
BEGIN DESCRIPTION:
UDS St 35 21.0
END DESCRIPTION:
XS GIS Cut Line= 3
      2249429.00      7195510.00      2249479.00      7195460.00
      2249526.74      7195399.98
#Sta/Elev= 25
  4929.3  875.40  4932.8  875.40  4933.4  875.43  4943.4  875.96  4957.6  869.08
  4969.7  857.68  4970.0  857.18  4973.5  857.18  4973.7  857.68  4985.9  857.85
  4996.5  864.65  5000.0  864.65  5003.2  864.65  5007.2  875.24  5013.6  876.23
  5021.6  879.94  5028.0  879.69  5036.1  880.27  5042.4  880.18  5050.5  880.71
  5056.9  880.40  5063.9  880.22  5071.3  879.82  5074.5  879.36  5076.7  879.36
#Mann=4,-1,0
  4929.3    0.12       0  4933.4    0.05       0  4969.7   0.033       0
  4973.7    0.05       0
Bank Sta=4969.7,4973.7
Exp/Cntr=0.3,0.1

Type RM Length L Ch R = 1,9534,96,96,96
BEGIN DESCRIPTION:
UDS St 35 20.2
END DESCRIPTION:
XS GIS Cut Line= 2
      2249437.05      7195734.67      2249704.27      7195435.28
#Sta/Elev= 30
  4764.6  876.15  4783.8  876.49  4804.7  874.21  4825.6  873.71  4847.4  875.12
  4854.1  877.15  4868.3  878.68  4910.9  871.85  4925.1  872.04  4931.8  870.97
  4946.0  866.83  4953.5  866.91  4960.2  863.73  4967.7  865.54  4982.0  856.30
  4986.7  855.79  4986.9  855.29  4990.7  855.79  5002.9  860.35  5010.4  866.10
  5017.1  864.66  5024.6  868.47  5031.3  867.33  5045.5  867.70  5059.7  871.17
  5080.6  870.37  5094.8  871.28  5116.6  873.67  5123.3  875.88  5165.9  879.75
#Mann=3,-1,0
  4764.6    0.05       0  4986.7   0.033       0  4990.7    0.05       0
Bank Sta=4986.7,4990.7
Exp/Cntr=0.3,0.1

Type RM Length L Ch R = 1,9438,234,234,234
BEGIN DESCRIPTION:
UDS St 35 20.1
END DESCRIPTION:
XS GIS Cut Line= 2
      2249490.56      7195884.49      2249783.45      7195436.90
#Sta/Elev= 30
  4665.5  877.06  4704.5  877.47  4718.7  874.17  4725.6  876.05  4731.6  872.85
  4740.7  873.73  4746.7  871.92  4761.8  875.13  4767.8  874.37  4782.9  876.47
  4798.0  875.47  4819.1  879.41  4827.3  876.69  4840.1  875.49  4849.3  876.85
  4855.3  874.98  4912.5  875.92  4942.7  867.87  4948.7  867.86  4957.7  865.33
  4963.8  861.74  4991.5  855.32  4991.8  854.82  4995.5  855.32  5021.1  858.14
  5072.4  870.43  5093.5  869.90  5144.8  880.09  5159.9  879.14  5200.4  881.78
#Mann=4,-1,0
  4665.5    0.12       0  4827.3    0.05       0  4991.5   0.033       0
  4995.5    0.05       0
Bank Sta=4991.5,4995.5
Exp/Cntr=0.3,0.1

Type RM Length L Ch R = 1,9204,195,195,195
BEGIN DESCRIPTION:
UDS St 35 20.0
END DESCRIPTION:
XS GIS Cut Line= 2
      2249649.67      7196153.95      2249971.48      7195508.19
#Sta/Elev= 30
  4535.6  883.34  4567.8  882.54  4607.0  880.10  4612.6  881.04  4618.2  879.84
  4679.7  875.70  4746.9  873.10  4808.2  872.25  4870.6  873.28  4903.6  872.33
  4948.3  872.70  4964.6  864.93  4976.3  855.65  4984.9  853.20  4985.2  852.70
  4988.9  853.20  4998.7  853.63  5009.3  858.00  5015.5  863.06  5021.1  866.44
  5031.6  868.38  5037.9  870.61  5098.7  872.78  5127.4  875.66  5133.0  877.15
  5210.4  882.51  5232.7  884.90  5239.3  887.36  5244.9  886.09  5257.1  887.66
#Mann=4,-1,0
  4535.6    0.05       0  4870.6    0.12       0  4984.9    0.07       0
  4988.9    0.12       0
Bank Sta=4984.9,4988.9
Exp/Cntr=0.3,0.1

Type RM Length L Ch R = 1,9009,332,332,332
BEGIN DESCRIPTION:
UDS St 35 19.0
END DESCRIPTION:
XS GIS Cut Line= 3
      2249979.00      7196109.98      2250029.00      7195810.00
      2250064.40      7195533.28
#Sta/Elev= 30
  4691.1  885.59  4724.0  883.28  4840.6  871.62  4873.6  869.42  4883.7  867.86
  4893.8  864.12  4901.4  859.84  4906.5  861.12  4914.1  858.73  4924.3  857.51
  4929.5  860.50  4944.5  868.58  4954.7  869.94  4974.9  869.28  4985.1  866.92
  4992.7  862.75  4997.7  862.75  5005.3  856.83  5015.4  854.17  5035.6  853.21
  5035.9  852.71  5039.6  853.21  5055.7  863.36  5075.9  869.75  5117.3  870.33
  5136.4  873.49  5166.6  873.05  5206.9  878.42  5247.3  882.32  5274.2  881.58
#Mann=4,-1,0
  4691.1    0.05       0  4929.5    0.12       0  5035.6    0.07       0
  5039.6    0.12       0
Bank Sta=5035.6,5039.6
Exp/Cntr=0.3,0.1

Type RM Length L Ch R = 1,8677,382,382,382
BEGIN DESCRIPTION:
UDS St 35 18.0
END DESCRIPTION:
XS GIS Cut Line= 3
      2250318.80      7196087.74      2250329.00      7195810.00
      2250340.33      7195493.83
#Sta/Elev= 30
  4721.6  874.48  4769.4  871.47  4799.4  868.65  4862.7  865.35  4869.4  864.72
  4909.5  866.98  4919.5  866.99  4929.5  865.31  4939.5  857.24  4949.5  852.80
  4957.5  852.05  4957.7  851.55  4961.2  851.55  4961.5  852.05  4989.5  853.78
  4997.0  855.23  5002.0  855.23  5049.6  860.38  5079.6  865.87  5109.6  866.61
  5149.6  866.04  5179.6  866.85  5239.7  870.81  5249.7  872.19  5259.7  872.46
  5269.7  874.08  5279.7  873.85  5289.7  875.15  5309.7  875.62  5315.9  876.69
#Mann=4,-1,0
  4721.6    0.05       0  4862.7    0.12       0  4957.5    0.07       0
  4961.5    0.12       0
Bank Sta=4957.5,4961.5
Exp/Cntr=0.3,0.1

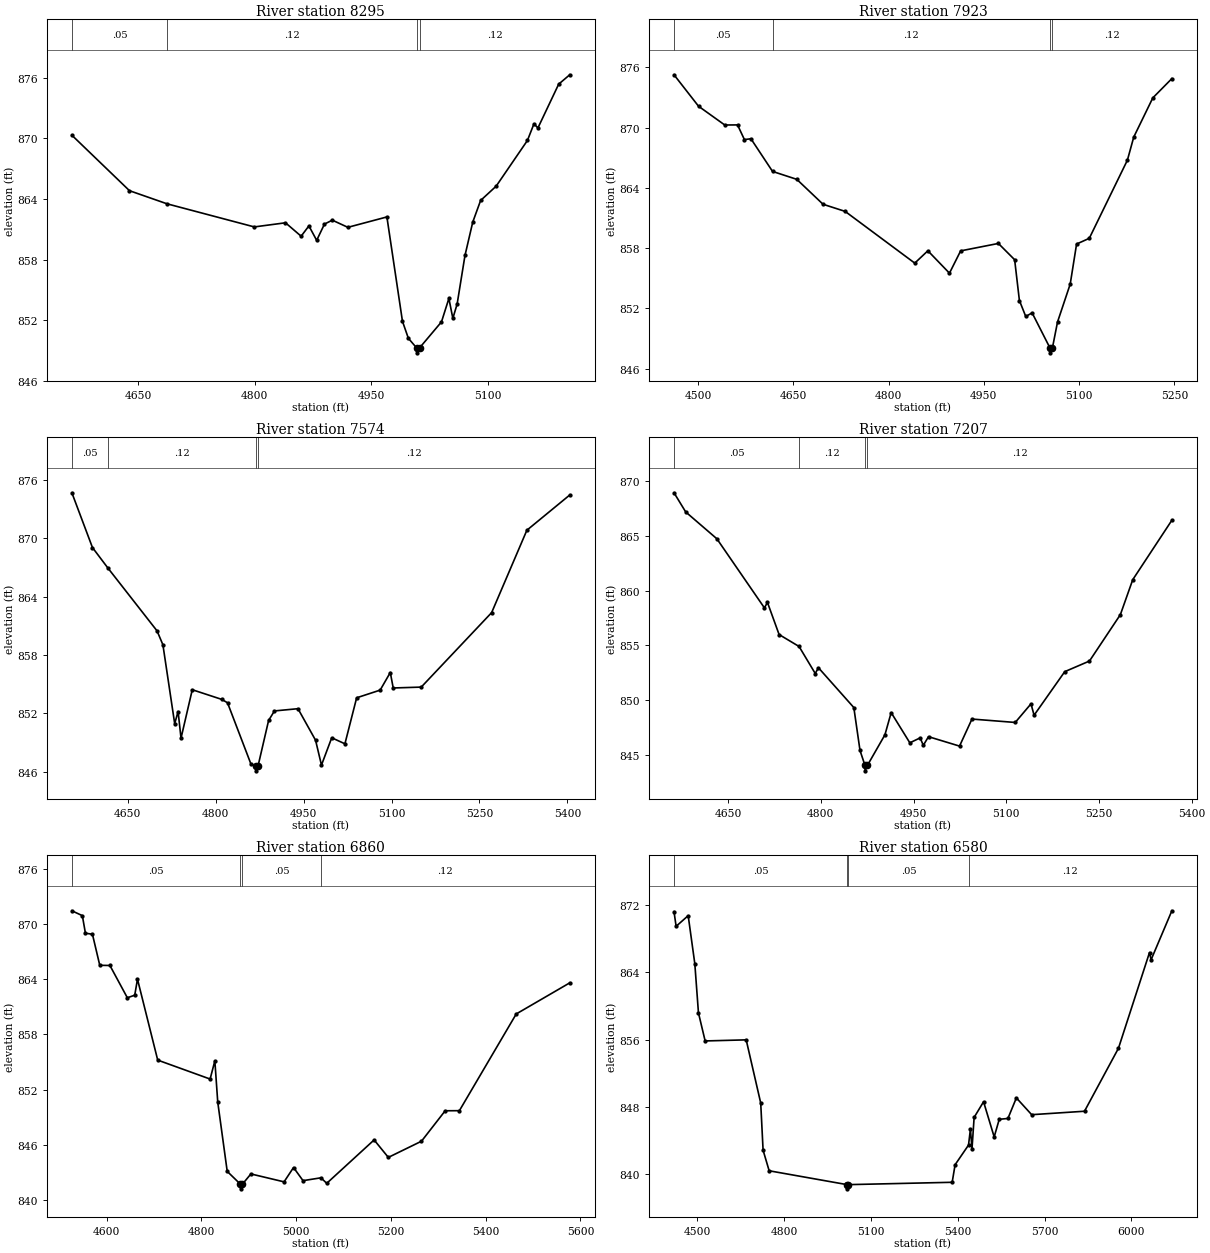
Type RM Length L Ch R = 1,8295,372,372,372
BEGIN DESCRIPTION:
UDS St 35 17.0
END DESCRIPTION:
XS GIS Cut Line= 3
      2250645.12      7196343.86      2250679.00      7195910.00
      2250697.93      7195705.85
#Sta/Elev= 30
  4564.9  870.32  4639.0  864.82  4687.3  863.52  4799.5  861.23  4839.6  861.64
  4859.7  860.31  4869.7  861.33  4879.7  859.90  4889.7  861.51  4899.8  861.90
  4919.8  861.19  4970.0  862.22  4990.0  851.88  4997.6  850.19  5008.1  849.25
  5008.4  848.75  5012.1  849.25  5040.2  851.82  5049.7  854.14  5054.8  852.17
  5060.3  853.58  5070.4  858.40  5080.4  861.71  5090.5  863.85  5110.5  865.27
  5150.7  869.80  5159.1  871.45  5164.2  871.04  5190.9  875.38  5205.1  876.31
#Mann=4,-1,0
  4564.9    0.05       0  4687.3    0.12       0  5008.1    0.07       0
  5012.1    0.12       0
Bank Sta=5008.1,5012.1
Exp/Cntr=0.3,0.1

Type RM Length L Ch R = 1,7923,349,349,349
BEGIN DESCRIPTION:
UDS St 35 16.0
END DESCRIPTION:
XS GIS Cut Line= 3
      2250848.36      7196577.43      2250979.00      7196060.00
      2250979.00      7195809.97
#Sta/Elev= 30
  4462.3  875.25  4500.9  872.12  4542.2  870.25  4562.3  870.26  4573.1  868.80
  4583.4  868.88  4617.4  865.63  4655.6  864.84  4696.9  862.36  4731.7  861.65
  4841.3  856.50  4861.9  857.73  4895.9  855.50  4913.5  857.72  4972.9  858.46
  4998.5  856.84  5006.0  852.78  5016.0  851.19  5026.0  851.55  5054.0  848.07
  5054.2  847.57  5058.0  848.07  5066.0  850.64  5086.0  854.42  5096.0  858.40
  5116.0  858.97  5176.0  866.75  5186.0  869.05  5216.0  872.95  5246.0  874.87
#Mann=4,-1,0
  4462.3    0.05       0  4617.4    0.12       0  5054.0    0.07       0
  5058.0    0.12       0
Bank Sta=5054,5058
Exp/Cntr=0.3,0.1

Type RM Length L Ch R = 1,7574,367,367,367
BEGIN DESCRIPTION:
UDS St 35 15.0
END DESCRIPTION:
XS GIS Cut Line= 3
      2251253.64      7196505.07      2251279.00      7196060.00
      2251299.25      7195657.00
#Sta/Elev= 30
  4554.7  874.67  4589.8  869.04  4616.2  866.93  4700.0  860.47  4710.0  859.04
  4730.1  850.93  4735.9  852.18  4740.9  849.44  4760.1  854.42  4810.2  853.43
  4820.2  853.08  4860.3  846.76  4868.3  846.58  4868.5  846.08  4872.3  846.58
  4890.3  851.26  4900.3  852.24  4940.4  852.47  4970.4  849.23  4980.5  846.67
  4998.0  849.48  5020.5  848.86  5040.5  853.59  5080.6  854.38  5097.9  856.19
  5102.9  854.60  5150.7  854.69  5270.8  862.35  5330.9  870.82  5404.0  874.44
#Mann=4,-1,0
  4554.7    0.05       0  4616.2    0.12       0  4868.3    0.07       0
  4872.3    0.12       0
Bank Sta=4868.3,4872.3
Exp/Cntr=0.3,0.1

Type RM Length L Ch R = 1,7207,347,347,347
BEGIN DESCRIPTION:
UDS St 35 14.0
END DESCRIPTION:
XS GIS Cut Line= 3
      2251576.45      7196548.79      2251629.00      7196110.00
      2251642.35      7195746.77
#Sta/Elev= 30
  4562.5  868.93  4581.4  867.18  4631.8  864.73  4708.7  858.42  4713.7  858.91
  4732.5  855.98  4764.8  854.89  4791.0  852.42  4796.1  852.95  4853.4  849.31
  4863.4  845.39  4871.4  844.03  4871.6  843.53  4875.4  844.03  4903.7  846.82
  4913.8  848.85  4944.0  846.09  4960.7  846.54  4965.8  845.86  4974.2  846.65
  5024.4  845.79  5044.5  848.26  5114.5  847.95  5140.0  849.65  5145.0  848.61
  5194.6  852.59  5234.6  853.56  5284.6  857.80  5304.6  860.99  5367.9  866.42
#Mann=4,-1,0
  4562.5    0.05       0  4764.8    0.12       0  4871.4    0.07       0
  4875.4    0.12       0
Bank Sta=4871.4,4875.4
Exp/Cntr=0.3,0.1

Type RM Length L Ch R = 1,6860,280,280,280
BEGIN DESCRIPTION:
UDS St 35 13.0
END DESCRIPTION:
XS GIS Cut Line= 4
      2251772.94      7196494.46      2251929.00      7196236.10
      2251929.00      7196060.00      2251940.91      7195487.16
#Sta/Elev= 30
  4526.6  871.45  4548.7  870.92  4555.2  869.01  4570.0  868.90  4585.5  865.52
  4606.9  865.50  4643.7  861.99  4659.3  862.27  4665.1  864.01  4707.8  855.21
  4818.4  853.15  4828.4  855.13  4834.5  850.65  4854.5  843.11  4882.5  841.71
  4882.8  841.21  4886.5  841.71  4904.5  842.83  4974.5  841.97  4994.5  843.53
  5014.5  842.10  5052.4  842.41  5064.6  841.81  5164.6  846.53  5194.6  844.63
  5264.6  846.39  5314.6  849.70  5344.6  849.71  5464.6  860.23  5577.5  863.61
#Mann=4,-1,0
  4526.6    0.05       0  4882.5   0.033       0  4886.5    0.05       0
  5052.4    0.12       0
Bank Sta=4882.5,4886.5
Exp/Cntr=0.3,0.1

Type RM Length L Ch R = 1,6580,316,316,316
BEGIN DESCRIPTION:
UDS St 35 12.0
END DESCRIPTION:
XS GIS Cut Line= 3
      2251847.46      7196477.88      2252246.27      7195936.57
      2252652.33      7194969.85
#Sta/Elev= 30
  4419.0  871.22  4426.3  869.48  4468.0  870.75  4490.9  865.03  4503.5  859.17
  4526.6  855.83  4668.5  855.96  4718.7  848.44  4726.9  842.82  4747.9  840.37
  5017.4  838.72  5017.7  838.22  5021.4  838.72  5380.5  839.00  5390.6  841.09
  5437.0  843.43  5443.6  845.33  5449.0  842.98  5456.4  846.73  5489.0  848.59
  5525.7  844.40  5543.2  846.50  5573.2  846.60  5602.4  849.05  5655.3  847.05
  5837.9  847.46  5955.3  854.96  6062.6  866.36  6068.0  865.49  6139.9  871.33
#Mann=4,-1,0
  4419.0    0.05       0  5017.4   0.033       0  5021.4    0.05       0
  5437.0    0.12       0
Bank Sta=5017.4,5021.4
Exp/Cntr=0.3,0.1

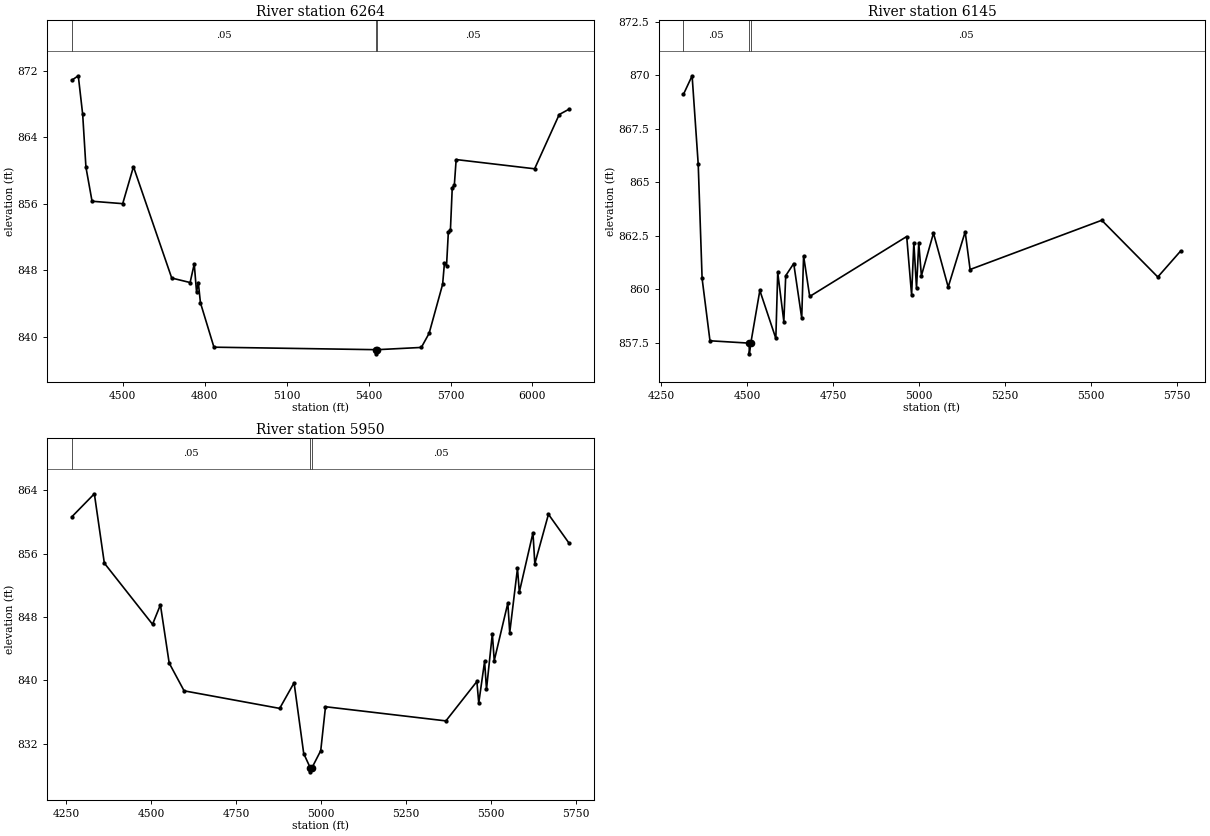
Type RM Length L Ch R = 1,6264,119,119,119
BEGIN DESCRIPTION:
UDS St 35 11.2
END DESCRIPTION:
XS GIS Cut Line= 4
      2251873.41      7196465.74      2252275.92      7196266.56
      2252897.87      7195532.62      2252903.30      7195124.27
#Sta/Elev= 30
  4314.0  870.84  4337.6  871.37  4353.7  866.73  4365.6  860.38  4388.0  856.29
  4500.2  856.00  4539.5  860.44  4679.6  847.06  4746.9  846.52  4762.0  848.76
  4770.4  845.40  4776.9  846.52  4784.7  844.09  4834.1  838.75  5427.0  838.45
  5427.6  837.95  5431.8  838.45  5593.2  838.72  5621.7  840.42  5671.1  846.31
  5677.7  848.84  5685.4  848.54  5692.0  852.55  5699.7  852.88  5706.3  857.90
  5714.0  858.25  5720.6  861.30  6007.8  860.19  6097.8  866.71  6133.5  867.35
#Mann=3,-1,0
  4314.0    0.05       0  5427.0   0.033       0  5431.8    0.05       0
Bank Sta=5427,5431.8
Exp/Cntr=0.3,0.1

Type RM Length L Ch R = 1,6145,195,195,195
BEGIN DESCRIPTION:
UDS St 35 11.9
END DESCRIPTION:
XS GIS Cut Line= 4
      2251899.29      7196494.54      2252428.57      7196260.25
      2252899.69      7195703.40      2252907.41      7195564.14
#Sta/Elev= 30
  4313.9  869.10  4339.2  869.97  4357.0  865.83  4368.3  860.50  4391.2  857.59
  4505.3  857.48  4505.8  856.98  4510.1  857.48  4536.4  859.94  4583.0  857.70
  4588.5  860.78  4606.3  858.49  4611.8  860.63  4635.1  861.20  4658.4  858.65
  4663.8  861.56  4681.6  859.66  4964.1  862.46  4978.4  859.72  4984.9  862.17
  4992.7  860.05  4999.2  862.16  5006.9  860.63  5042.1  862.62  5084.9  860.10
  5134.4  862.68  5148.7  860.92  5532.1  863.22  5695.3  860.57  5761.6  861.78
#Mann=3,-1,0
  4313.9    0.05       0  4505.3   0.033       0  4510.1    0.05       0
Bank Sta=4505.3,4510.1
Exp/Cntr=0.3,0.1

Type RM Length L Ch R = 1,5950,0,0,0
BEGIN DESCRIPTION:
UDS St 35 11.0
END DESCRIPTION:
XS GIS Cut Line= 4
      2251914.19      7196536.22      2252501.63      7196407.87
      2252664.79      7196227.51      2252928.32      7195667.30
#Sta/Elev= 30
  4266.7  860.66  4333.0  863.57  4362.4  854.80  4504.3  847.07  4527.5  849.53
  4553.3  842.17  4597.2  838.66  4878.6  836.44  4921.0  839.68  4949.4  830.73
  4968.7  828.92  4969.2  828.42  4973.5  828.92  4999.5  831.10  5013.5  836.65
  5368.0  834.86  5459.2  839.84  5464.7  837.12  5481.9  842.39  5487.5  838.87
  5504.7  845.87  5510.3  842.48  5550.3  849.75  5555.9  846.02  5578.7  854.13
  5584.2  851.15  5624.3  858.63  5629.8  854.72  5669.9  860.98  5730.3  857.34
#Mann=3,-1,0
  4266.7    0.05       0  4968.7    0.04       0  4973.5    0.05       0
Bank Sta=4968.7,4973.5
Exp/Cntr=0.3,0.1

Chan Stop Cuts=-1