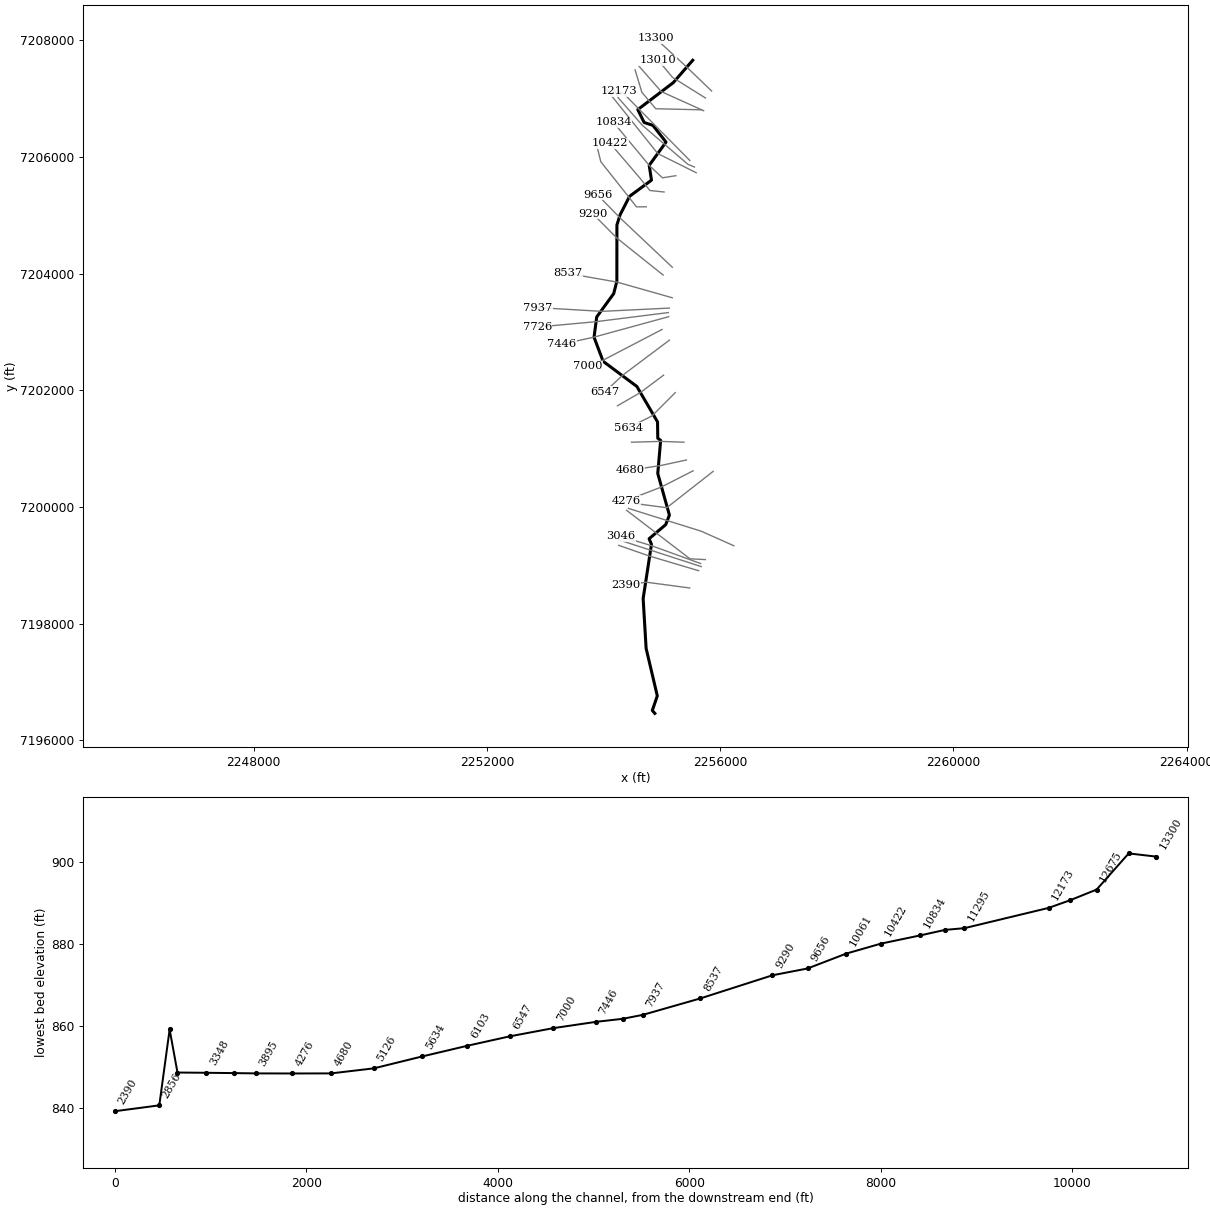
--- UDS St 36.prj (project) ---

Proj Title=UDS St 36 Base Level Engineering
Current Plan=p01
Default Exp/Contr=0.3,0.1
English Units
Geom File=g01
Flow File=f01
Plan File=p01
Y Axis Title=Elevation
X Axis Title(PF)=Main Channel Distance
X Axis Title(XS)=Station
BEGIN DESCRIPTION:
UDS St 36
END DESCRIPTION:
DSS Export Rating Curves= 0
DSS Export Rating Curve Sorted= 0
DSS Export Volume Flow Curves= 0
DXF OffsetX= 0
DXF OffsetY= 0
DXF ScaleX= 1
DXF ScaleY= 10

--- UDS St 36.p01 (plan) ---

Plan Title=Multiple Run
Short Identifier=Multiple
Geom File=g01
Flow File=f01
Subcritical Flow
K Sum by GR= 0
Std Step Tol= 0.01
Critical Tol= 0.01
Num of Std Step Trials= 20
Max Error Tol= 0.3
Flow Tol Ratio= 0.001
Split Flow NTrial= 30
Split Flow Tol= 0.02
Split Flow Ratio= 0.02
Log Output Level= 0
Friction Slope Method= 1
Unsteady Friction Slope Method= 2
Unsteady Bridges Friction Slope Method= 1
Parabolic Critical Depth
Global Vel Dist=  1 , 1 , 1
Global Log Level= 0
CheckData=True
Encroach Param= -1, 0, 0, 0
BEGIN DESCRIPTION:
Multiple Run
END DESCRIPTION:

--- UDS St 36.f01 (steady flow) ---

Flow Title=Multiple
Number of Profiles=7
Profile Names=10-year,25-year,50-year,1pct_min,100-year,1pct_plu,500-year
River Rch & RM= UDS St 36,Reach-1,13300
     680     954    1186     733    1463    2918    2230
River Rch & RM= UDS St 36,Reach-1,8537
     828    1175    1471     915    1825    3642    2818
River Rch & RM= UDS St 36,Reach-1,7726
    1050    1505    1896    1186    2366    4721    3696
River Rch & RM= UDS St 36,Reach-1,3348
    1465    2136    2724    1721    3434    6851    5478
River Rch & RM= UDS St 36,Reach-1,2856
    1528    2232    2850    1803    3597    7176    5751
Boundary for River Rch & Prof#=UDS St 36,Reach-1,1
Up Type=0
Dn Type=3
Dn Slope=0.005
Boundary for River Rch & Prof#=UDS St 36,Reach-1,2
Up Type=0
Dn Type=3
Dn Slope=0.005
Boundary for River Rch & Prof#=UDS St 36,Reach-1,3
Up Type=0
Dn Type=3
Dn Slope=0.005
Boundary for River Rch & Prof#=UDS St 36,Reach-1,4
Up Type=0
Dn Type=3
Dn Slope=0.005
Boundary for River Rch & Prof#=UDS St 36,Reach-1,5
Up Type=0
Dn Type=3
Dn Slope=0.005
Boundary for River Rch & Prof#=UDS St 36,Reach-1,6
Up Type=0
Dn Type=3
Dn Slope=0.005
Boundary for River Rch & Prof#=UDS St 36,Reach-1,7
Up Type=0
Dn Type=3
Dn Slope=0.005

--- UDS St 36.g01 (geometry) ---

Geom Title=Existing Conditions
Program Version=4.10

River Reach=UDS St 36       ,Reach-1
Reach XY= 30
        2255529.        7207660.      2255195.67      7207276.65
      2254586.77      7206813.41      2254695.45      7206592.87
      2254845.79      7206543.56      2255070.99      7206256.72
      2254782.54      7205858.53      2254821.64      7205603.66
      2254445.46      7205326.75      2254282.83      7205008.42
       2254228.8      7204835.08      2254227.78       7203870.5
      2254173.53      7203657.55      2253882.55      7203258.53
      2253836.56        7202910.      2253992.61      7202496.76
      2254570.87      7202066.07      2254925.45      7201458.53
      2254929.51      7201178.68      2254978.65      7201141.25
      2254929.25       7200574.1        2255129.        7199860.
       2255065.6      7199696.69      2254780.69      7199454.54
      2254821.41      7199360.01      2254678.61      7198428.34
      2254729.68      7197573.92      2254921.44        7196760.
      2254835.91      7196509.86        2254879.        7196460.

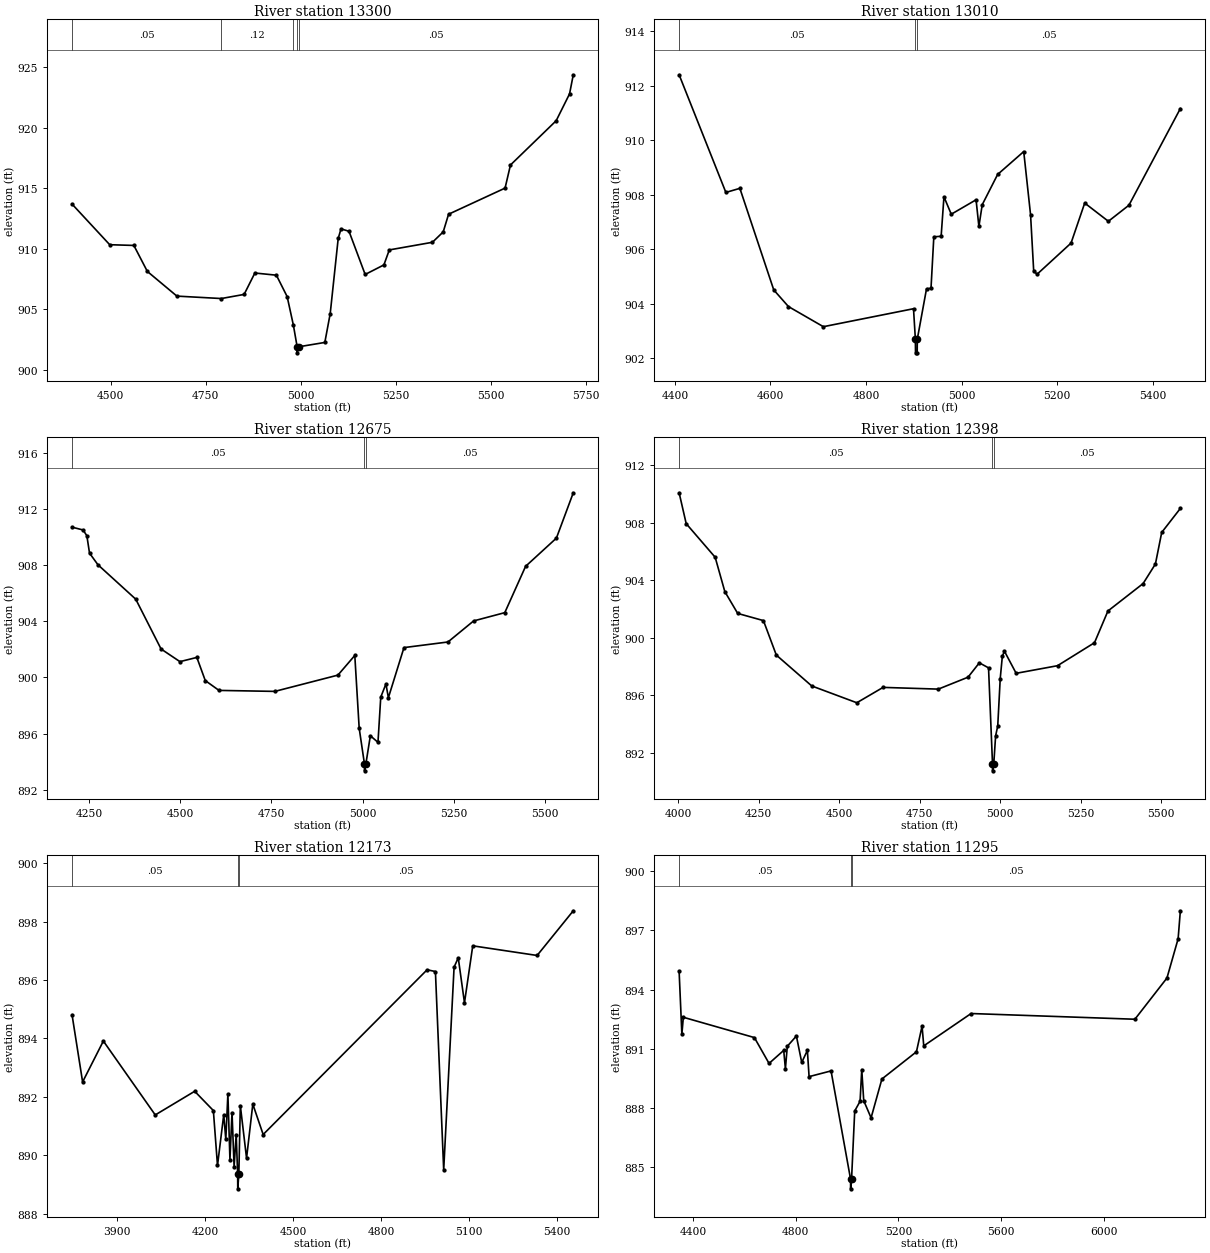
Type RM Length L Ch R = 1 ,13300   ,290,290,290
BEGIN DESCRIPTION:
UDS St 36 27.0
END DESCRIPTION:
XS GIS Cut Line= 3
      2255852.35       7207133.4       2255415.2      7207552.89
      2254891.23      7208035.77
#Sta/Elev= 30
  4398.7   913.7  4497.8  910.34  4561.3  910.28  4596.8  908.13  4674.5  906.09
  4791.3  905.89  4851.3  906.23  4879.6     908  4936.2  907.82  4964.5  906.05
  4980.9  903.69  4990.8   901.9    4991   901.4  4994.8   901.9  5063.6  902.26
  5077.8  904.65  5098.8  910.86  5106.2  911.65  5127.2  911.45  5169.7  907.88
    5219  908.67  5233.2  909.91  5346.6  910.54    5375   911.4  5389.1  912.86
  5537.7  915.02  5551.9  916.93  5672.1  920.59  5707.3  922.81  5717.1  924.39
#Mann= 5 ,-1 , 0
  4398.7     .05       0  4791.3     .12       0  4980.9     .05       0
  4990.8    .033       0  4994.8     .05       0
Bank Sta=4990.8,4994.8
XS Rating Curve= 0 ,0
Exp/Cntr=0.3,0.1

Type RM Length L Ch R = 1 ,13010   ,335,335,335
BEGIN DESCRIPTION:
UDS St 36 26.0
END DESCRIPTION:
XS GIS Cut Line= 3
      2255746.72      7207012.99      2255181.69      7207366.39
      2254937.32      7207660.33
#Sta/Elev= 30
  4408.9   912.4  4506.7  908.08    4536  908.23  4606.9   904.5  4637.6  903.89
  4710.7  903.15  4899.3  903.81  4903.2  902.69  4903.5  902.19    4907  902.19
  4907.2  902.69  4926.5  904.54  4935.9  904.56  4941.8  906.45  4957.1  906.47
    4963  907.92  4978.3  907.28  5030.2  907.81  5036.1  906.83  5043.1  907.63
  5075.3  908.74  5129.9  909.58  5144.2  907.26  5150.8  905.18  5158.1  905.08
  5228.9  906.22  5257.5  907.69    5307  907.02    5350  907.61  5457.6  911.16
#Mann= 3 ,-1 , 0
  4408.9     .05       0  4903.2    .033       0  4907.2     .05       0
Bank Sta=4903.2,4907.2
XS Rating Curve= 0 ,0
Exp/Cntr=0.3,0.1

Type RM Length L Ch R = 1 ,12675   ,277,277,277
BEGIN DESCRIPTION:
UDS St 36 25.0
END DESCRIPTION:
XS GIS Cut Line= 3
      2255715.97      7206794.56      2254987.88       7207123.1
      2254609.93      7207555.53
#Sta/Elev= 30
  4203.8   910.7    4234   910.5  4244.4  910.09  4251.7  908.85  4274.8  908.02
  4378.3  905.57  4447.7  902.02  4499.4  901.12  4545.7  901.42  4568.8  899.77
  4606.4  899.07  4759.3     899  4932.2  900.16  4978.4  901.56  4990.4  896.38
  5004.8  893.84    5005  893.34  5008.8  893.84    5021  895.84  5041.9  895.37
  5049.5  898.59  5063.7  899.53  5070.4  898.55  5113.1  902.12  5233.6  902.52
  5303.9  904.02  5389.3  904.61  5446.3  907.91  5530.7  909.92  5576.9  913.15
#Mann= 3 ,-1 , 0
  4203.8     .05       0  5004.8    .033       0  5008.8     .05       0
Bank Sta=5004.8,5008.8
XS Rating Curve= 0 ,0
Exp/Cntr=0.3,0.1

Type RM Length L Ch R = 1 ,12398   ,225,225,225
BEGIN DESCRIPTION:
UDS St 36 24.3
END DESCRIPTION:
XS GIS Cut Line= 4
      2255680.95      7206809.83      2254894.69      7206828.76
      2254656.99      7207109.75      2254540.41      7207495.38
#Sta/Elev= 30
  4002.6  910.09  4024.6  907.94  4114.6   905.6  4144.6  903.21  4184.6  901.69
  4264.6  901.19  4304.6  898.79  4414.7  896.64  4554.7  895.47  4636.3  896.54
    4808  896.42  4900.3  897.25  4935.4  898.25    4964   897.9  4976.3  891.23
  4976.5  890.73  4980.3  891.23    4986  893.17  4992.6  893.85  5000.3  897.15
  5006.9  898.71  5013.4  899.06  5049.8  897.52  5178.3  898.05  5293.2  899.65
    5335  901.86  5444.3  903.77  5482.5  905.13  5502.1  907.33    5560     909
#Mann= 3 ,-1 , 0
  4002.6     .05       0  4976.3    .033       0  4980.3     .05       0
Bank Sta=4976.3,4980.3
XS Rating Curve= 0 ,0
Exp/Cntr=0.3,0.1

Type RM Length L Ch R = 1 ,12173   ,878,878,878
BEGIN DESCRIPTION:
UDS St 36 24.2
END DESCRIPTION:
XS GIS Cut Line= 3
      2255479.89        7205940.      2254362.27      7207070.89
      2254260.08      7207129.56
#Sta/Elev= 30
  3747.2  894.81  3783.2  892.51  3853.9  893.91  4030.7  891.38  4165.1  892.19
  4228.7  891.53  4242.8  889.65  4264.1  891.39  4271.1  890.54  4278.2   892.1
  4285.2  889.85  4292.3  891.46  4299.4  889.61  4306.5  890.71  4311.5  889.35
  4311.8  888.85  4315.5  889.35  4320.6   891.7  4341.8   889.9  4363.1  891.75
  4398.4  890.71    4957  896.35  4985.3  896.29  5013.5   889.5  5048.9  896.44
  5063.1  896.76  5084.3  895.22  5112.5  897.17  5331.8  896.84    5455  898.37
#Mann= 3 ,-1 , 0
  3747.2     .05       0  4311.5    .033       0  4315.5     .05       0
Bank Sta=4311.5,4315.5
XS Rating Curve= 0 ,0
Exp/Cntr=0.3,0.1

Type RM Length L Ch R = 1 ,11295   ,204,204,204
BEGIN DESCRIPTION:
UDS St 36 24.1
END DESCRIPTION:
XS GIS Cut Line= 5
      2255558.93      7205828.59      2255447.29      7205874.97
       2254666.4      7206543.31      2254255.73       7207011.5
      2254168.22      7207169.81
#Sta/Elev= 30
  4345.9  894.93  4356.6  891.74  4362.3   892.6  4639.1  891.57  4696.2  890.26
  4753.3  890.92  4759.9  889.99  4767.3  891.13  4802.7  891.65  4823.5  890.31
  4845.5  890.92  4852.1  889.59  4937.7  889.88  5013.6   884.4  5013.9   883.9
  5017.6   884.4  5029.9  887.85  5050.8  888.34  5057.3  889.95    5065  888.37
  5093.6   887.5  5135.8  889.47  5270.3  890.85  5292.2  892.15  5298.8  891.15
  5483.2  892.79  6121.2   892.5  6246.1  894.59  6289.6  896.58  6298.3     898
#Mann= 3 ,-1 , 0
  4345.9     .05       0  5013.6    .033       0  5017.6     .05       0
Bank Sta=5013.6,5017.6
XS Rating Curve= 0 ,0
Exp/Cntr=0.3,0.1

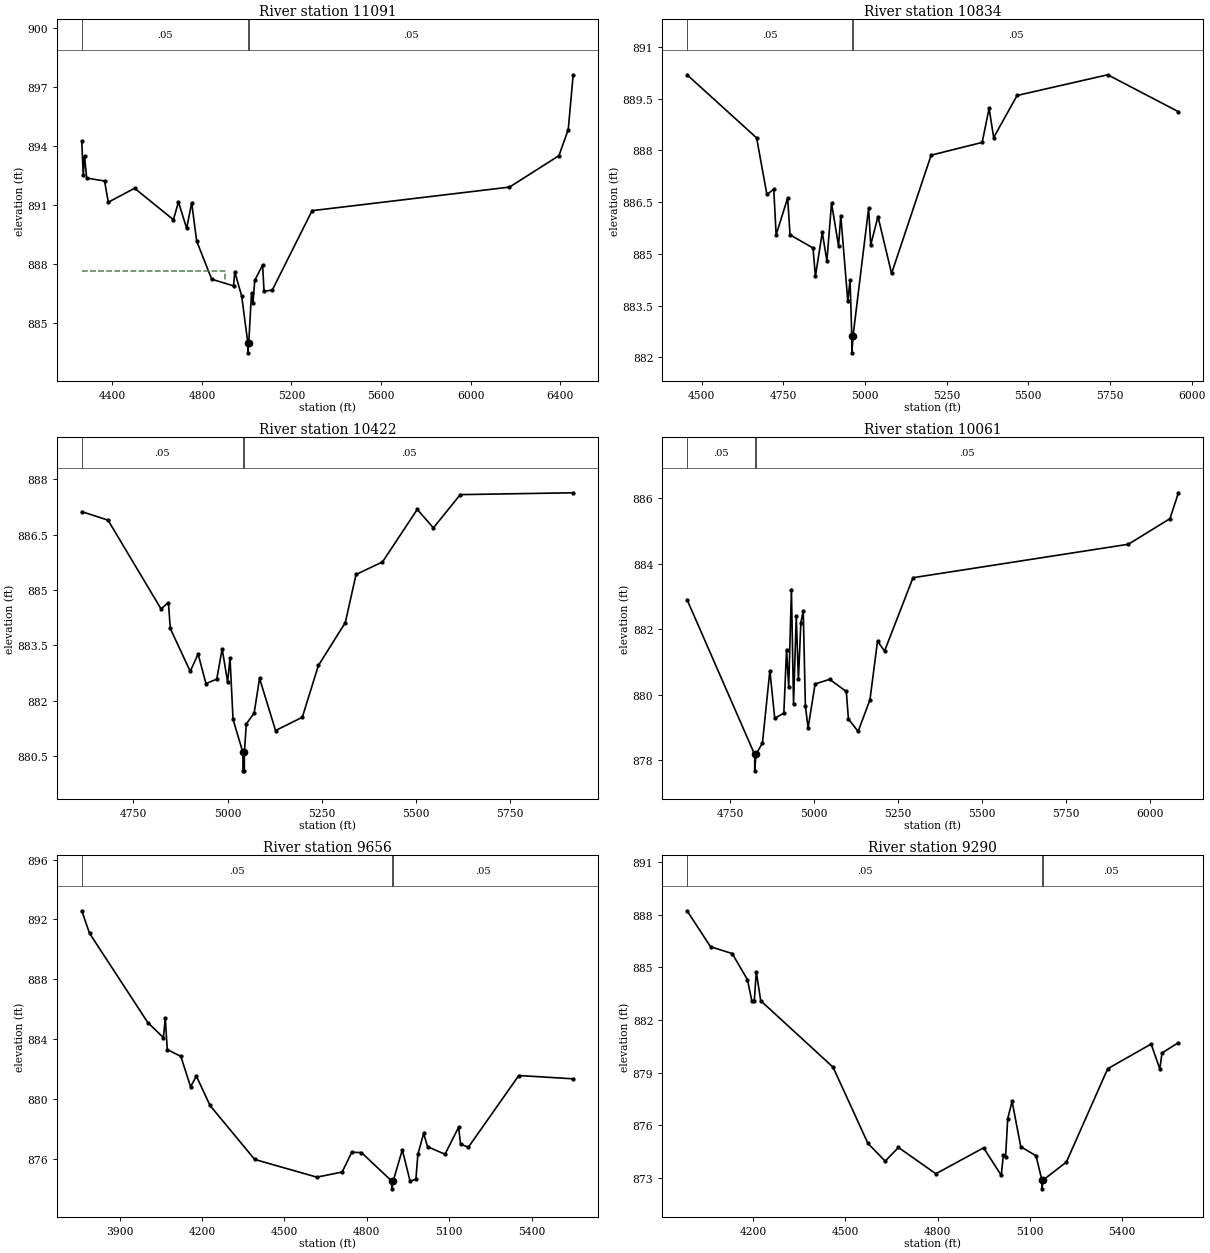
Type RM Length L Ch R = 1 ,11091   ,257,257,257
BEGIN DESCRIPTION:
UDS St 36 24.0
END DESCRIPTION:
XS GIS Cut Line= 3
      2255588.48      7205731.45        2254929.        7206060.
      2254018.14      7207199.63
#Sta/Elev= 30
    4263  894.24  4269.5  892.51  4275.1   893.5  4284.8  892.37  4364.6  892.22
  4381.4  891.14  4498.9  891.85  4672.4  890.25  4694.8  891.15  4731.7  889.81
    4754  891.11  4776.3  889.16  4843.4  887.22    4941  886.88  4946.6  887.59
  4977.4  886.36    5005  883.97  5005.2  883.47    5009  883.97  5021.4  886.53
  5027.8     886  5035.8  887.16    5071  887.94  5077.4   886.6  5114.3  886.67
    5292  890.71  6174.1  891.91    6395  893.51  6436.6  894.84  6458.7  897.63
#Mann= 3 ,-1 , 0
    4263     .05       0    5005     .04       0    5009     .05       0
#XS Ineff= 2 , 0
       0 4901.78  887.64    5071       0  887.94
Permanent Ineff=
       F       F
Bank Sta=5005,5009
XS Rating Curve= 0 ,0
Exp/Cntr=0.3,0.1

Type RM Length L Ch R = 1 ,10834   ,412,412,412
BEGIN DESCRIPTION:
UDS St 36 23.0
END DESCRIPTION:
XS GIS Cut Line= 4
      2255239.34      7205680.21      2255009.41      7205644.18
      2254784.84      7205854.51      2254169.32        7206596.
#Sta/Elev= 30
  4455.5  890.19  4668.4  888.36  4699.9  886.72  4720.9  886.87  4728.2  885.55
  4763.4  886.62  4770.7  885.55    4841  885.17  4848.4  884.35  4869.4  885.62
  4883.5  884.79  4897.7  886.47  4919.2  885.23    4926  886.11  4947.5  883.63
  4954.4  884.23  4959.7  882.63  4959.9  882.13  4963.7  882.63  5011.2  886.32
  5017.7  885.26  5039.9  886.08  5081.5  884.43  5202.6  887.86  5358.9  888.23
    5380  889.22    5394  888.37  5465.7  889.59  5743.1  890.19  5959.6  889.12
#Mann= 3 ,-1 , 0
  4455.5     .05       0  4959.7     .04       0  4963.7     .05       0
#XS Ineff= 2 , 0
       0  4897.7  886.47               0
Permanent Ineff=
       F       F
Bank Sta=4959.7,4963.7
XS Rating Curve= 0 ,0
Exp/Cntr=0.3,0.1

Type RM Length L Ch R = 1 ,10422   ,361,361,361
BEGIN DESCRIPTION:
UDS St 36 22.0
END DESCRIPTION:
XS GIS Cut Line= 4
       2255038.2      7205400.69      2254794.78      7205426.08
      2254624.92      7205636.93      2254112.27       7206236.3
#Sta/Elev= 30
    4613  887.12  4682.6  886.89  4823.3  884.49  4842.9  884.66  4847.9  883.96
  4900.8   882.8  4921.7  883.27  4942.5  882.47  4971.2  882.59  4985.6  883.41
    5000  882.51  5006.4  883.16  5014.4   881.5  5040.6  880.61  5040.8  880.11
  5044.3  880.11  5044.6  880.61  5049.6  881.38  5070.4  881.67  5084.8  882.61
  5127.3   881.2  5198.3  881.56    5241  882.96  5312.4  884.12  5340.9  885.42
  5411.1  885.76  5503.4  887.18  5546.2  886.68  5617.5  887.58  5917.2  887.63
#Mann= 3 ,-1 , 0
    4613     .05       0  5040.6     .04       0  5044.6     .05       0
#XS Ineff= 2 , 0
       0  4985.6  883.41               0
Permanent Ineff=
       F       F
Bank Sta=5040.6,5044.6
XS Rating Curve= 0 ,0
Exp/Cntr=0.3,0.1

Type RM Length L Ch R = 1 ,10061   ,405,405,405
BEGIN DESCRIPTION:
UDS St 36 21.0
END DESCRIPTION:
XS GIS Cut Line= 5
      2254732.42      7205146.89      2254564.59      7205145.39
      2254426.88       7205320.7      2253952.48      7205920.24
      2253877.85      7206219.58
#Sta/Elev= 30
  4620.9   882.9  4822.2  878.18  4822.5  877.68  4826.2  878.18  4845.5  878.53
  4867.6  880.74    4882  879.28  4909.2  879.44  4917.3  881.38  4923.7  880.23
  4931.8  883.21  4938.1  879.72  4946.2  882.39  4952.6  880.47  4959.9   882.2
    4967  882.56  4973.4  879.65  4981.5  878.99  5002.3  880.33  5045.6  880.47
  5095.3   880.1  5101.6  879.26  5130.5  878.88  5165.8  879.85  5188.3  881.64
  5209.1  881.33    5294  883.57  5935.5  884.59  6059.3  885.37  6084.7  886.16
#Mann= 3 ,-1 , 0
  4620.9     .05       0  4822.2     .04       0  4826.2     .05       0
#XS Ineff= 2 , 0
       0                  4931.8       0  883.21
Permanent Ineff=
       F       F
Bank Sta=4822.2,4826.2
XS Rating Curve= 0 ,0
Exp/Cntr=0.3,0.1

Type RM Length L Ch R = 1 ,9656    ,366,366,366
BEGIN DESCRIPTION:
UDS St 36 20.0
END DESCRIPTION:
XS GIS Cut Line= 3
      2255178.97      7204110.03        2254279.        7204960.
      2253894.01      7205355.02
#Sta/Elev= 30
  3762.1  892.58  3790.2  891.08  4002.6  885.12  4059.2  884.12  4066.1  885.42
  4073.4  883.32  4122.7  882.87  4158.3  880.84  4179.4  881.55  4229.1  879.59
  4391.8  875.99  4617.9  874.81  4710.1  875.15  4745.3  876.47  4780.5  876.45
  4891.8  874.53  4892.1  874.03  4895.8  874.53  4929.4  876.63  4957.7  874.54
  4978.8  874.67    4986  876.33  5007.1  877.73  5021.2  876.84  5084.8  876.34
  5134.4  878.14  5141.4  877.02  5169.7   876.8  5353.6  881.59  5551.6  881.37
#Mann= 3 ,-1 , 0
  3762.1     .05       0  4891.8     .04       0  4895.8     .05       0
#XS Ineff= 2 , 0
       0  4745.3  876.47  5007.1       0  877.13
Permanent Ineff=
       F       F
Bank Sta=4891.8,4895.8
XS Rating Curve= 0 ,0
Exp/Cntr=0.3,0.1

Type RM Length L Ch R = 1 ,9290    ,753,753,753
BEGIN DESCRIPTION:
UDS St 36 19.0
END DESCRIPTION:
XS GIS Cut Line= 3
      2255022.17      7203976.05        2254229.        7204610.
      2253818.11      7205024.74
#Sta/Elev= 30
  3984.6  888.23    4061  886.18  4131.5  885.79  4181.1   884.3  4195.5  883.08
  4203.5   883.1  4209.9  884.75  4224.3   883.1  4459.7  879.31  4573.3  874.96
  4629.4  873.95  4672.6  874.73  4794.3  873.23  4949.6  874.71  5007.1  873.14
  5014.1   874.3  5021.2  874.19  5028.2  876.38  5042.4  877.36  5070.7  874.77
  5120.2  874.26  5139.4  872.87  5139.6  872.37  5143.4  872.87  5219.2   873.9
  5353.5  879.22  5494.9  880.63  5523.2  879.21  5530.3  880.12  5583.8  880.71
#Mann= 3 ,-1 , 0
  3984.6     .05       0  5139.4     .04       0  5143.4     .05       0
#XS Ineff= 2 , 0
       0  5042.4  877.36               0
Permanent Ineff=
       F       F
Bank Sta=5139.4,5143.4
XS Rating Curve= 0 ,0
Exp/Cntr=0.3,0.1

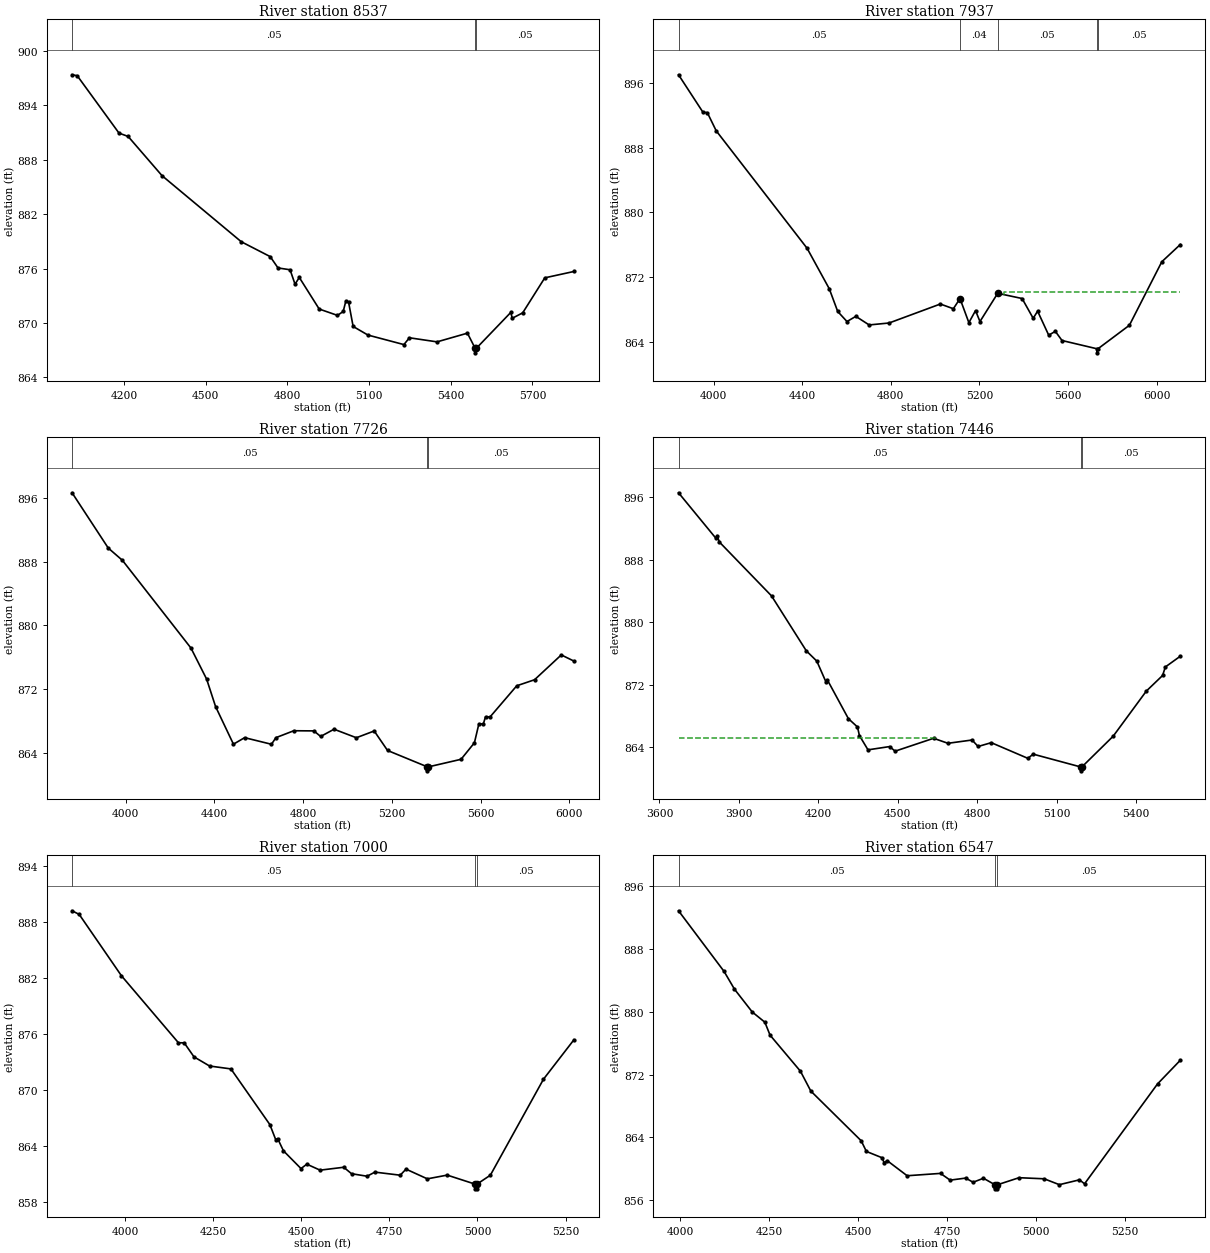
Type RM Length L Ch R = 1 ,8537    ,600,600,600
BEGIN DESCRIPTION:
UDS St 36 18.0
END DESCRIPTION:
XS GIS Cut Line= 3
      2255177.16      7203587.23      2254223.25      7203857.67
      2253383.81      7204004.54
#Sta/Elev= 30
  4008.5  897.37  4027.4  897.27  4180.9  890.94  4214.5  890.57  4339.2  886.24
  4630.2  878.96  4736.5  877.32  4765.2  876.07  4809.5  875.87  4827.7  874.28
  4843.4  875.02  4916.5  871.54  4983.6  870.84  5004.7  871.27  5014.5  872.43
  5024.6  872.28  5041.2  869.62  5095.6  868.67  5227.7  867.62    5248  868.37
  5349.5  867.92  5461.2  868.88  5489.5  867.21  5489.8  866.71  5493.8  867.21
  5620.6  871.17  5625.7  870.52  5664.2  871.12  5745.4  874.98  5852.2  875.68
#Mann= 3 ,-1 , 0
  4008.5     .05       0  5489.5     .04       0  5493.8     .05       0
Bank Sta=5489.5,5493.8
XS Rating Curve= 0 ,0
Exp/Cntr=0.3,0.1

Type RM Length L Ch R = 1 ,7937    ,211,211,211
BEGIN DESCRIPTION:
UDS St 36 17.0
END DESCRIPTION:
XS GIS Cut Line= 3
      2255128.96        7203410.      2253971.12      7203353.84
      2252865.41      7203418.49
#Sta/Elev= 30
  3840.8  896.98  3950.9  892.37  3970.9  892.31    4011  890.07  4421.4  875.59
  4521.6   870.6  4559.9  867.79  4601.7  866.55  4641.7  867.19  4701.8  866.13
  4791.9  866.37  5023.5  868.71  5082.3  868.13  5112.3  869.38  5152.4  866.41
  5182.4   867.9  5202.5  866.55  5282.6  870.03  5392.8  869.39  5442.9  866.95
  5462.9  867.83    5513  864.87    5543  865.34  5573.1  864.21  5731.2  863.19
  5731.6  862.69  5735.5  863.19  5877.5  866.09  6023.9  873.92  6107.6  876.05
#Mann= 5 ,-1 , 0
  3840.8     .05       0  5112.3     .04       0  5282.6     .05       0
  5731.2     .04       0  5735.5     .05       0
#XS Ineff= 2 , 0
       0                  5312.7       0  870.19
Permanent Ineff=
       F       F
Bank Sta=5112.3,5282.6
XS Rating Curve= 0 ,0
Exp/Cntr=0.3,0.1

Type RM Length L Ch R = 1 ,7726    ,280,280,280
BEGIN DESCRIPTION:
UDS St 36 16.5
END DESCRIPTION:
XS GIS Cut Line= 3
      2255110.92      7203333.13      2253866.53      7203176.57
      2252862.53      7203084.65
#Sta/Elev= 30
  3758.2  896.67  3921.4  889.72  3985.2  888.18  4294.3  877.15  4364.9  873.25
  4405.2   869.8  4485.8  865.07  4536.2  865.89  4657.2  865.06  4677.3  865.89
  4757.9  866.76  4848.6  866.74  4878.9  866.04  4939.4  866.95    5040  865.88
  5120.4  866.73  5180.6  864.28  5360.2  862.22  5360.7  861.72  5364.9  862.22
    5512  863.17  5572.3  865.25  5592.3  867.62  5612.4  867.62  5622.5  868.52
  5642.6  868.49  5763.1  872.41  5843.4  873.17  5963.9  876.29  6020.6  875.52
#Mann= 3 ,-1 , 0
  3758.2     .05       0  5360.2    .033       0  5364.9     .05       0
#XS Ineff= 2 , 0
       0  4939.4  866.95               0
Permanent Ineff=
       F       F
Bank Sta=5360.2,5364.9
XS Rating Curve= 0 ,0
Exp/Cntr=0.3,0.1

Type RM Length L Ch R = 1 ,7446    ,446,446,446
BEGIN DESCRIPTION:
UDS St 36 16.0
END DESCRIPTION:
XS GIS Cut Line= 3
      2255117.46      7203262.82        2253829.        7202910.
      2253283.61      7202791.98
#Sta/Elev= 30
  3672.3   896.6  3813.1  890.78  3818.3  891.11  3826.2   890.3  4023.2  883.39
  4154.5  876.35  4194.2  875.03  4228.7  872.36  4233.9  872.63  4313.5  867.65
  4347.7  866.59    4355  865.49  4387.4  863.66    4469  864.08  4489.8  863.49
  4634.9  865.14  4689.2   864.5  4780.1  864.92    4803  864.09  4852.7  864.58
  4990.9  862.57  5010.7  863.11    5190  861.47  5190.5  860.97  5194.7  861.47
  5312.8  865.41  5437.9  871.19  5499.3  873.19  5509.7  874.28  5566.2  875.66
#Mann= 3 ,-1 , 0
  3672.3     .05       0    5190    .035       0  5194.7     .05       0
#XS Ineff= 2 , 0
       0  4643.9  865.14               0
Permanent Ineff=
       F       F
Bank Sta=5190,5194.7
XS Rating Curve= 0 ,0
Exp/Cntr=0.3,0.1

Type RM Length L Ch R = 1 ,7000    ,453,453,453
BEGIN DESCRIPTION:
UDS St 36 15.0
END DESCRIPTION:
XS GIS Cut Line= 3
      2255003.33      7203043.65        2253979.        7202510.
      2253728.97      7202409.99
#Sta/Elev= 30
  3849.3   889.2  3869.6  888.81  3989.5  882.24  4151.2  875.07  4167.6  875.06
  4195.4  873.56  4239.6  872.58  4300.2  872.27  4410.7  866.31  4427.2  864.71
  4432.8  864.81  4449.3   863.5  4499.1   861.6  4515.6  862.07  4553.3  861.43
  4620.4  861.74  4642.5  861.05  4686.7  860.78  4708.8  861.22  4780.7  860.89
  4797.2  861.54  4857.7   860.5  4914.1   860.9  4993.6  859.93  4994.2  859.43
  4997.9  859.43  4998.5  859.93  5036.6  860.89  5187.4  871.17  5273.6  875.38
#Mann= 3 ,-1 , 0
  3849.3     .05       0  4993.6    .035       0  4998.5     .05       0
Bank Sta=4993.6,4998.5
XS Rating Curve= 0 ,0
Exp/Cntr=0.3,0.1

Type RM Length L Ch R = 1 ,6547    ,444,444,444
BEGIN DESCRIPTION:
UDS St 36 14.0
END DESCRIPTION:
XS GIS Cut Line= 3
      2255128.99        7202860.        2254329.        7202260.
      2254029.09      7201979.41
#Sta/Elev= 30
  3995.1  892.89  4123.2  885.15  4152.4  882.89  4202.4  879.98  4237.8  878.68
  4252.4  877.03  4337.8  872.43    4367   869.9  4508.6  863.56  4523.2   862.2
    4567   861.4  4573.2  860.76  4581.6  861.03  4637.8   859.1  4731.6   859.4
  4758.6  858.54  4802.4   858.8  4823.2  858.27  4852.4  858.78  4885.4  857.93
    4886  857.43  4889.7  857.43  4890.3  857.93  4952.4  858.85  5023.2  858.71
  5065.7  857.96  5122.3  858.58  5136.5  858.07  5341.7  870.81  5405.8  873.83
#Mann= 3 ,-1 , 0
  3995.1     .05       0  4885.4    .035       0  4890.3     .05       0
Bank Sta=4885.4,4890.3
XS Rating Curve= 0 ,0
Exp/Cntr=0.3,0.1

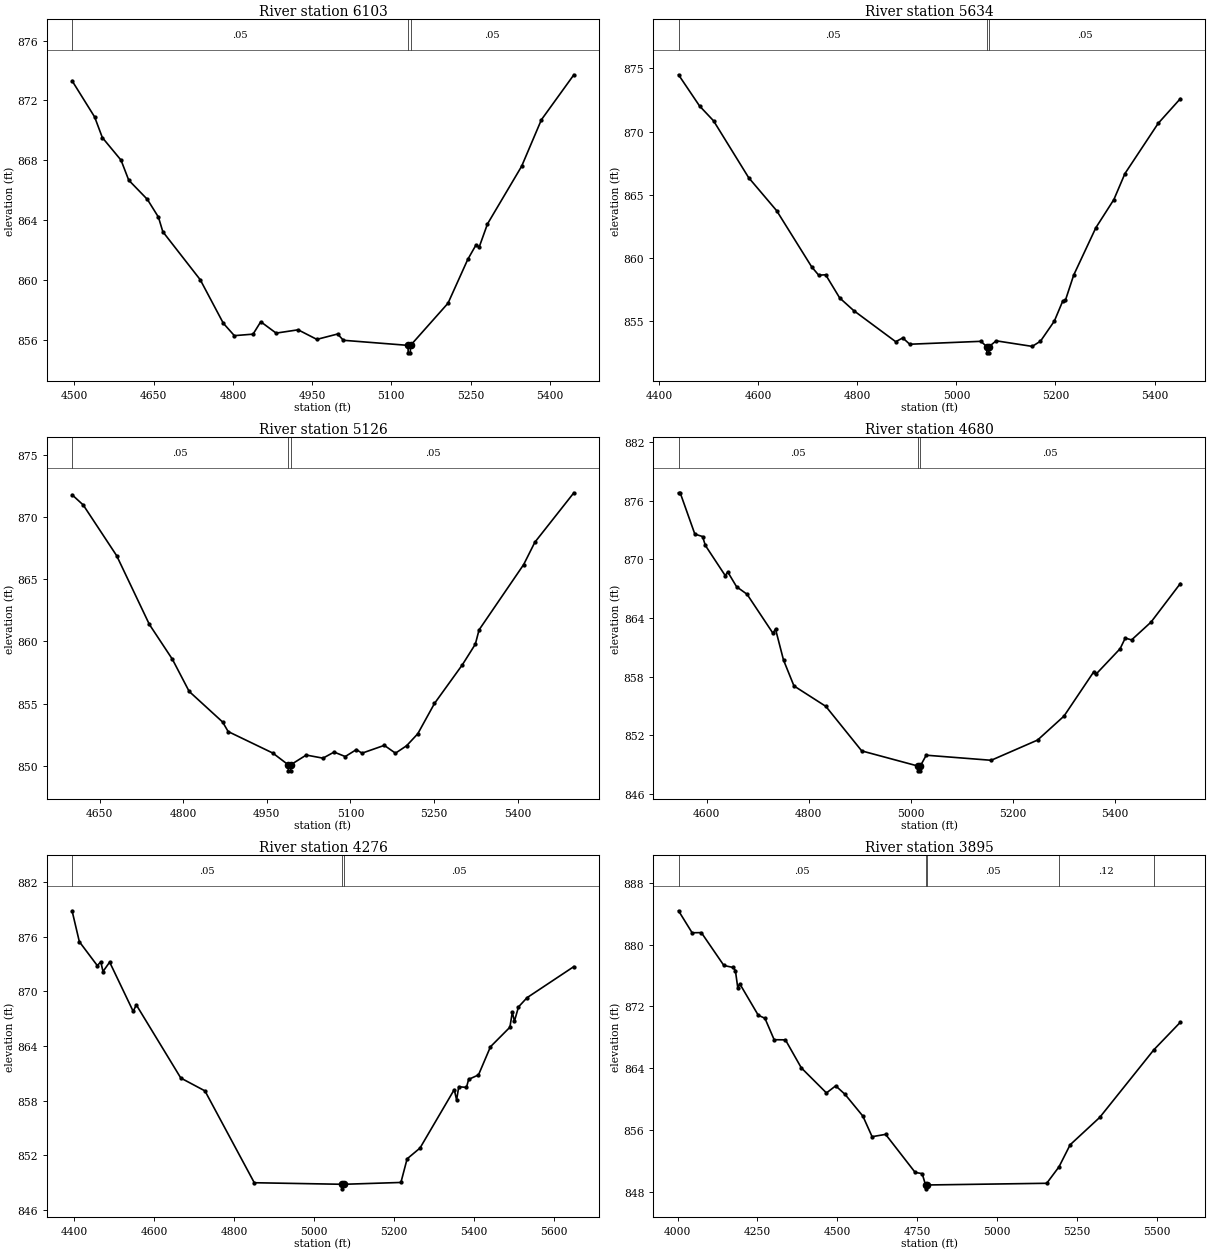
Type RM Length L Ch R = 1 ,6103    ,469,469,469
BEGIN DESCRIPTION:
UDS St 36 13.0
END DESCRIPTION:
XS GIS Cut Line= 3
      2255028.99      7202259.99        2254629.        7201960.
      2254238.84      7201735.36
#Sta/Elev= 30
  4495.4  873.32  4538.1   870.9  4552.7  869.52  4588.1  868.01  4602.7  866.67
  4638.1  865.38  4658.9   864.2  4667.3  863.22  4738.1  860.01  4781.8   857.1
  4802.7  856.27  4838.1  856.37  4852.7   857.2  4881.8  856.44  4923.5  856.66
  4958.9  856.02  4998.3  856.38  5009.1  855.96  5131.4  855.62    5132  855.12
  5135.8  855.12  5136.4  855.62  5207.3  858.44  5244.7  861.37  5260.5  862.35
  5266.3  862.19    5282  863.74  5346.7   867.6  5384.1  870.71  5445.6  873.72
#Mann= 3 ,-1 , 0
  4495.4     .05       0  5131.4     .04       0  5136.4     .05       0
Bank Sta=5131.4,5136.4
XS Rating Curve= 0 ,0
Exp/Cntr=0.3,0.1

Type RM Length L Ch R = 1 ,5634    ,508,508,508
BEGIN DESCRIPTION:
UDS St 36 12.0
END DESCRIPTION:
XS GIS Cut Line= 3
      2255229.03      7201960.03        2254829.        7201560.
      2254429.03      7201360.02
#Sta/Elev= 30
  4439.1   874.5  4481.6  872.03  4509.8  870.86  4580.6  866.37  4637.1  863.76
  4707.8  859.32    4722  858.66  4736.1  858.69  4764.4  856.86  4792.7  855.86
  4877.5   853.4  4891.7   853.7  4905.8   853.2  5049.5  853.43  5060.9  853.02
  5061.6  852.52  5065.4  852.52  5066.1  853.02  5080.3  853.47    5153  853.03
  5169.7  853.44  5197.7  855.03  5214.5   856.6    5220  856.67  5236.8  858.67
  5281.5  862.41  5317.9  864.64  5340.2  866.69  5407.3  870.66    5452  872.61
#Mann= 3 ,-1 , 0
  4439.1     .05       0  5060.9     .04       0  5066.1     .05       0
Bank Sta=5060.9,5066.1
XS Rating Curve= 0 ,0
Exp/Cntr=0.3,0.1

Type RM Length L Ch R = 1 ,5126    ,446,446,446
BEGIN DESCRIPTION:
UDS St 36 11.0
END DESCRIPTION:
XS GIS Cut Line= 3
      2255378.95        7201110.       2254979.8      7201124.02
        2254479.        7201110.
#Sta/Elev= 30
  4600.6   871.8  4620.6  870.98  4680.6   866.9  4739.3  861.37  4780.7  858.56
  4810.7  855.98  4870.7  853.52  4880.7  852.75  4960.8  851.02  4988.1  850.09
  4988.9  849.59  4992.7  849.59  4993.4  850.09  5020.8  850.86  5050.8  850.61
  5070.8   851.1  5090.8  850.74  5110.8   851.3  5120.8  851.01  5160.9  851.64
  5180.9  851.01  5200.9  851.61  5220.9  852.57  5250.9  855.01  5300.9  858.12
  5324.2  859.78  5330.9  860.93    5411  866.19    5431  867.98    5501  871.96
#Mann= 3 ,-1 , 0
  4600.6     .05       0  4988.1    .033       0  4993.4     .05       0
Bank Sta=4988.1,4993.4
XS Rating Curve= 0 ,0
Exp/Cntr=0.3,0.1

Type RM Length L Ch R = 1 ,4680    ,404,404,404
BEGIN DESCRIPTION:
UDS St 36 10.0
END DESCRIPTION:
XS GIS Cut Line= 3
      2255420.31      7200804.91        2254979.        7200710.
       2254452.2      7200630.27
#Sta/Elev= 30
  4544.6  876.82  4547.8  876.82  4576.6  872.59  4591.8  872.34  4597.1  871.44
  4636.1  868.35  4641.2  868.71  4658.5   867.2  4678.9  866.44  4729.7  862.45
  4734.8  862.87  4750.5   859.7    4771  857.05  4833.5  854.96  4903.9   850.4
  5013.5  848.86  5014.3  848.36  5018.1  848.36  5018.9  848.86  5030.4  849.96
  5157.8  849.44  5248.8  851.51  5300.6  853.96  5359.3  858.52  5364.3   858.3
  5410.7  860.86  5420.8  861.95  5433.2  861.76  5471.3  863.58  5528.8  867.53
#Mann= 3 ,-1 , 0
  4544.6     .05       0  5013.5    .033       0  5018.9     .05       0
Bank Sta=5013.5,5018.9
XS Rating Curve= 0 ,0
Exp/Cntr=0.3,0.1

Type RM Length L Ch R = 1 ,4276    ,381,381,381
BEGIN DESCRIPTION:
UDS St 36 9.0
END DESCRIPTION:
XS GIS Cut Line= 3
      2255535.24      7200618.93      2254984.49      7200338.67
       2254389.7      7200109.98
#Sta/Elev= 30
  4394.1  878.83  4412.3  875.44  4457.2  872.82  4465.9  873.23  4471.5  872.17
  4488.1   873.2    4547   867.8  4554.8  868.51  4666.1  860.49  4726.5  859.08
  4849.9  849.01  5068.8  848.84  5069.6  848.34  5074.2  848.84  5216.7  849.04
  5232.2  851.63  5264.4  852.81  5350.1  859.22    5356  858.09  5361.4  859.54
  5380.7  859.46    5386  860.34  5410.7  860.83  5440.7  863.92  5489.3  866.06
  5495.3   867.7  5500.7  866.73  5510.8  868.29  5532.2   869.3  5649.3  872.71
#Mann= 3 ,-1 , 0
  4394.1     .05       0  5068.8    .033       0  5074.2     .05       0
Bank Sta=5068.8,5074.2
XS Rating Curve= 0 ,0
Exp/Cntr=0.3,0.1

Type RM Length L Ch R = 1 ,3895    ,225,225,225
BEGIN DESCRIPTION:
UDS St 36 8.0
END DESCRIPTION:
XS GIS Cut Line= 3
        2255879.        7200610.      2255083.48      7199986.32
      2254529.01        7200060.
#Sta/Elev= 30
  4003.1   884.4  4045.6  881.55  4074.5  881.57    4145  877.31    4174  877.05
    4181  876.65  4188.4  874.45  4194.8  874.93  4252.6  870.86  4273.4  870.47
  4302.3  867.69  4337.6  867.67  4387.3  864.04    4466  860.79  4494.9  861.71
  4523.8  860.62  4579.9  857.79  4608.8  855.12  4651.1  855.42  4743.5  850.49
  4765.5  850.33  4776.1  848.86  4776.8  848.36  4781.5  848.86  5155.2  849.08
  5193.6  851.21  5228.5  854.07  5321.1  857.62  5490.4  866.38  5573.3  869.95
#Mann= 5 ,-1 , 0
  4003.1     .05       0  4776.1    .033       0  4781.5     .05       0
  5193.6     .12       0  5490.4     .05       0
Bank Sta=4776.1,4781.5
XS Rating Curve= 0 ,0
Exp/Cntr=0.3,0.1

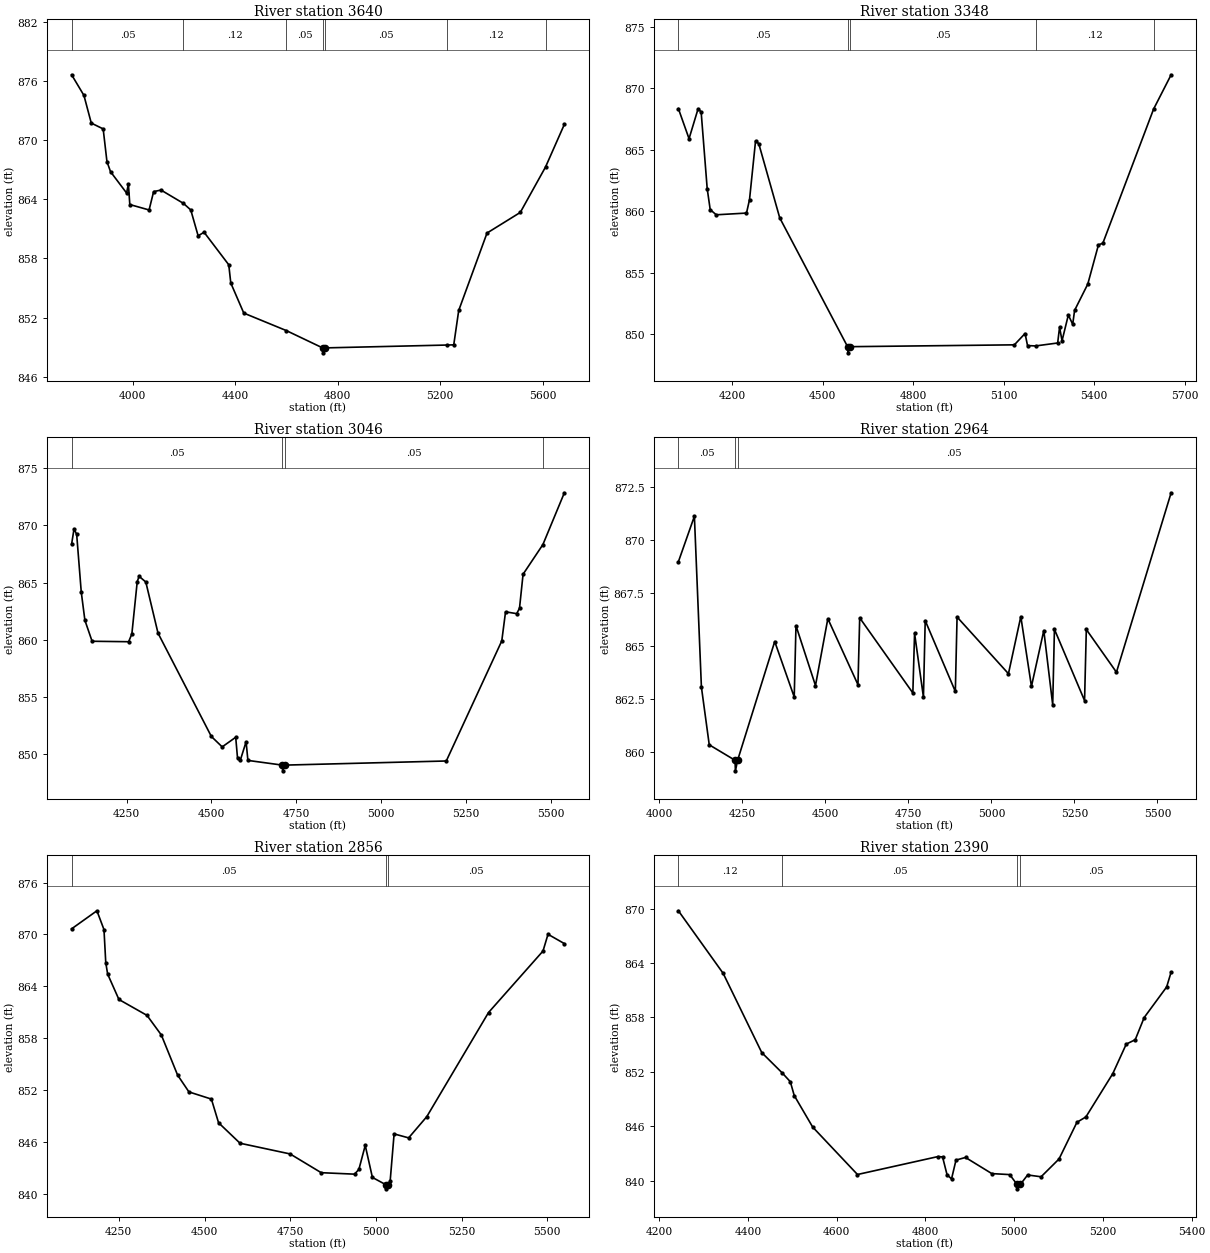
Type RM Length L Ch R = 1 ,3640    ,292,292,292
BEGIN DESCRIPTION:
UDS St 36 7.2
END DESCRIPTION:
XS GIS Cut Line= 3
      2256234.84      7199334.15      2255674.97      7199583.68
       2254425.7      7199975.06
#Sta/Elev= 30
  3762.5  876.63  3810.5  874.54  3839.2  871.73  3885.6  871.14  3900.3  867.83
  3914.3   866.8  3976.9  864.64    3984  865.55  3989.5  863.47  4064.7  862.92
  4082.4  864.78  4111.1  864.94  4198.6  863.59  4227.3  862.92    4256   860.3
  4279.2  860.66  4375.5  857.36  4383.4  855.51  4434.1  852.46  4599.8  850.69
  4741.7  848.93  4742.9  848.43  4749.4  848.93    5225  849.22  5253.1  849.24
  5272.5  852.73  5382.9  860.58  5512.7  862.67  5611.2  867.28  5684.6   871.6
#Mann= 7 ,-1 , 0
  3762.5     .05       0  4198.6     .12       0  4599.8     .05       0
  4741.7    .033       0  4749.4     .05       0    5225     .12       0
  5611.2     .05       0
Bank Sta=4741.7,4749.4
XS Rating Curve= 0 ,0
Exp/Cntr=0.3,0.1

Type RM Length L Ch R = 1 ,3348    ,302,302,302
BEGIN DESCRIPTION:
UDS St 36 7.1
END DESCRIPTION:
XS GIS Cut Line= 3
      2255744.28      7199097.29      2255482.01      7199110.52
      2254394.21      7199942.35
#Sta/Elev= 30
  4022.6  868.34  4057.9   865.9    4088  868.34    4098  868.07    4118  861.85
    4128  860.14    4148  859.72  4248.2  859.86  4258.2  860.95  4278.2  865.72
  4288.9  865.49  4358.3  859.47    4583  849.01  4584.2  848.51  4590.7  849.01
  5135.4  849.16  5170.8  850.08    5179   849.1  5205.6  849.07  5278.8  849.31
  5285.1  850.59  5293.3  849.49  5314.1  851.58  5328.6  850.83  5334.9  851.96
  5378.5  854.09  5413.9  857.28  5428.4  857.41  5596.6  868.31  5654.6  871.09
#Mann= 5 ,-1 , 0
  4022.6     .05       0    4583    .033       0  4590.7     .05       0
  5205.6     .12       0  5596.6     .05       0
Bank Sta=4583,4590.7
XS Rating Curve= 0 ,0
Exp/Cntr=0.3,0.1

Type RM Length L Ch R = 1 ,3046    ,82,82,82
BEGIN DESCRIPTION:
UDS St 36 7.0
END DESCRIPTION:
XS GIS Cut Line= 3
      2255665.71      7199029.06      2254828.74      7199333.25
       2254292.7       7199496.9
#Sta/Elev= 30
  4088.3  868.36  4095.4  869.69  4103.2  869.21  4116.7  864.17  4127.4  861.71
  4148.6  859.88  4256.2  859.84  4265.7  860.52  4281.5  865.08    4287  865.55
  4306.8  865.05  4342.7  860.59  4499.8  851.57  4531.7  850.66  4571.5   851.5
  4576.8   849.7  4584.9  849.48  4602.1  851.11  4607.4  849.48  4708.7  849.07
  4709.9  848.57  4716.5  849.07  5191.6  849.43    5355  859.91  5366.1  862.45
  5398.9  862.29  5407.2  862.76  5417.7  865.73  5476.1  868.32  5539.3  872.84
#Mann= 4 ,-1 , 0
  4088.3     .05       0  4708.7    .033       0  4716.5     .05       0
  5476.1     .12       0
Bank Sta=4708.7,4716.5
XS Rating Curve= 0 ,0
Exp/Cntr=0.3,0.1

Type RM Length L Ch R = 1 ,2964    ,108,108,108
BEGIN DESCRIPTION:
UDS St 36 6.1
END DESCRIPTION:
XS GIS Cut Line= 2
      2255674.88      7198977.19      2254263.88      7199434.64
#Sta/Elev= 30
  4057.8  868.99    4106  871.14  4127.1  863.07  4150.7  860.34  4228.3  859.61
  4229.5  859.11  4236.1  859.61  4347.8  865.22  4406.5   862.6  4411.8  865.97
  4470.5  863.14  4507.7   866.3  4598.4  863.18  4603.6  866.34  4763.6  862.79
  4768.8  865.61  4795.5  862.59  4800.8  866.21  4891.5  862.86  4896.7  866.38
  5051.4   863.7  5088.6   866.4  5120.6   863.1  5157.8  865.74  5184.6  862.23
  5189.8   865.8  5280.5  862.43  5285.8  865.79  5376.5  863.77  5541.1  872.25
#Mann= 3 ,-1 , 0
  4057.8     .05       0  4228.3    .033       0  4236.1     .05       0
Bank Sta=4228.3,4236.1
XS Rating Curve= 0 ,0
Exp/Cntr=0.3,0.1

Type RM Length L Ch R = 1 ,2856    ,466,466,466
BEGIN DESCRIPTION:
UDS St 36 6.0
END DESCRIPTION:
XS GIS Cut Line= 3
      2255629.77      7198906.66        2254779.        7199160.
      2254260.21      7199341.15
#Sta/Elev= 30
  4112.4  870.64  4186.2  872.73  4206.8  870.55    4212  866.72  4217.5   865.4
  4250.4  862.46  4332.3  860.62  4374.1  858.35  4421.5  853.71  4454.6  851.76
  4520.1  850.93    4541  848.19  4603.6  845.82  4749.7  844.58  4840.4  842.41
  4937.5  842.24  4950.3  842.79  4968.8  845.57  4989.7  841.86    5028  841.04
  5029.2  840.54  5035.8  841.04  5041.4  841.39    5053   846.9  5095.4  846.44
  5148.4   848.9  5328.4  860.95  5487.3  868.07  5501.9  870.01  5549.6  868.93
#Mann= 3 ,-1 , 0
  4112.4     .05       0    5028    .033       0  5035.8     .05       0
Bank Sta=5028,5035.8
XS Rating Curve= 0 ,0
Exp/Cntr=0.3,0.1

Type RM Length L Ch R = 1 ,2390    ,466,466,466
BEGIN DESCRIPTION:
UDS St 36 5.0
END DESCRIPTION:
XS GIS Cut Line= 3
      2255478.97        7198610.        2254729.        7198710.
      2254378.96      7198659.99
#Sta/Elev= 30
  4243.4  869.76  4344.3  862.86  4431.3  854.12  4477.8  851.86  4495.6  850.91
  4504.4  849.39    4546  845.91  4646.9  840.68  4828.5  842.66  4838.6  842.62
  4848.7  840.66  4858.8  840.19  4868.9  842.27  4890.3  842.56  4949.6  840.78
  4989.9  840.67  5006.2   839.6  5007.4   839.1  5014.1   839.6  5030.3  840.63
  5060.6  840.43    5101  842.39  5141.4  846.44  5161.6  847.03  5222.2  851.81
  5252.5  855.06  5272.7  855.54  5292.9  857.99  5343.5  861.36  5353.6     863
#Mann= 4 ,-1 , 0
  4243.4     .12       0  4477.8     .05       0  5006.2    .033       0
  5014.1     .05       0
Bank Sta=5006.2,5014.1
XS Rating Curve= 0 ,0
Exp/Cntr=0.3,0.1