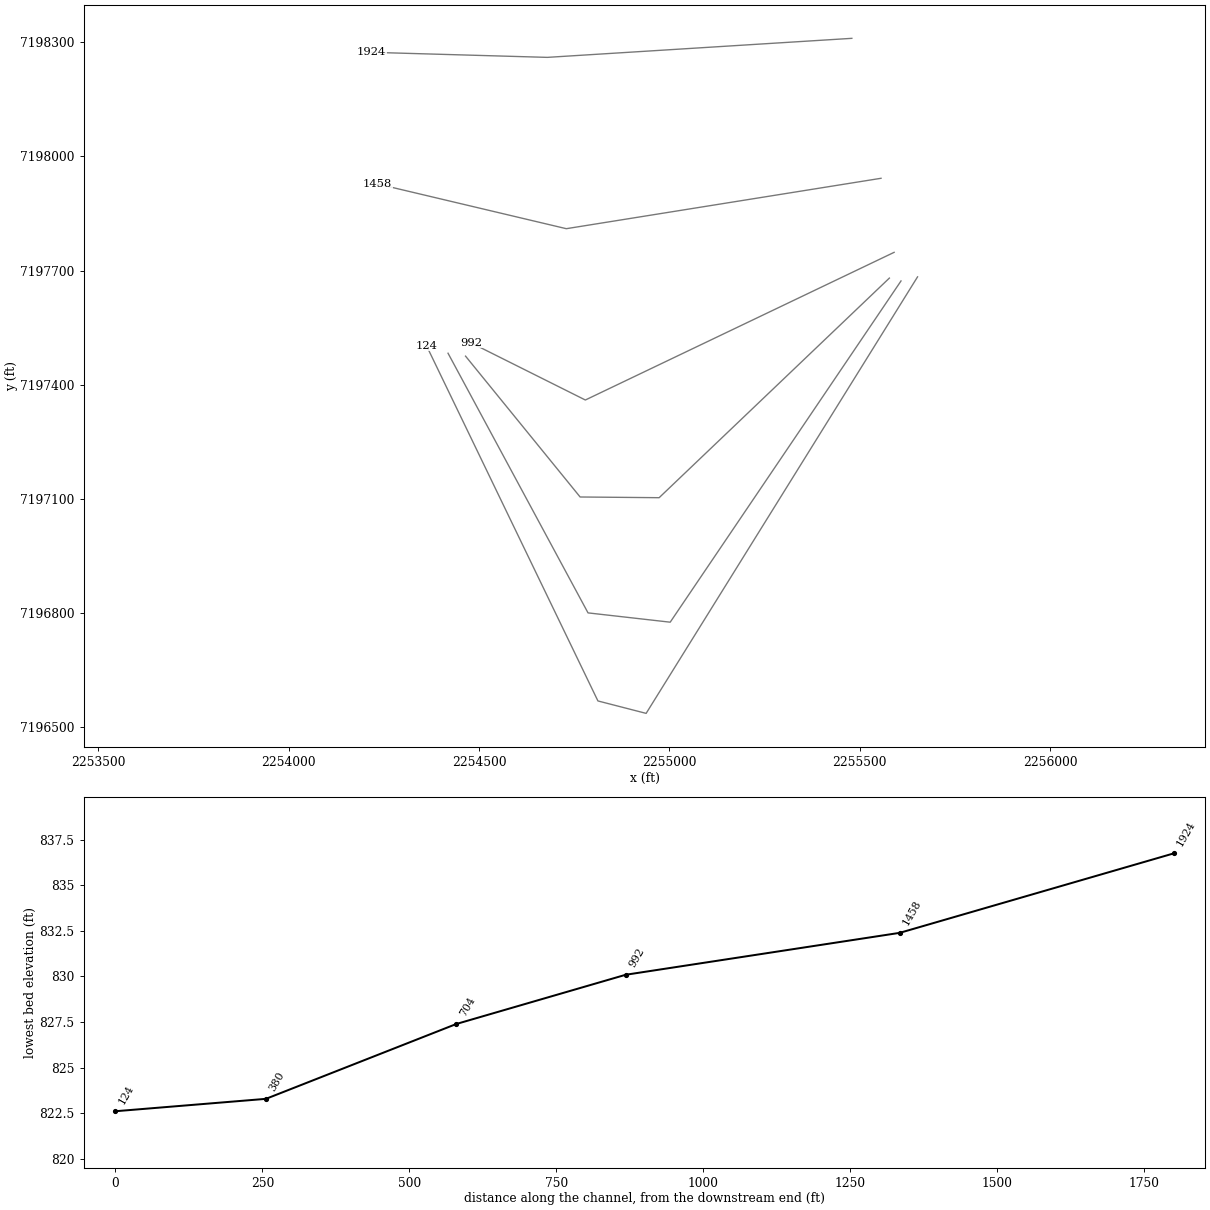
HEC-RAS study UDS St 36.prj: UDS St 36 Base Level Engineering

--- UDS St 36.g01 (geometry) --- (continued)

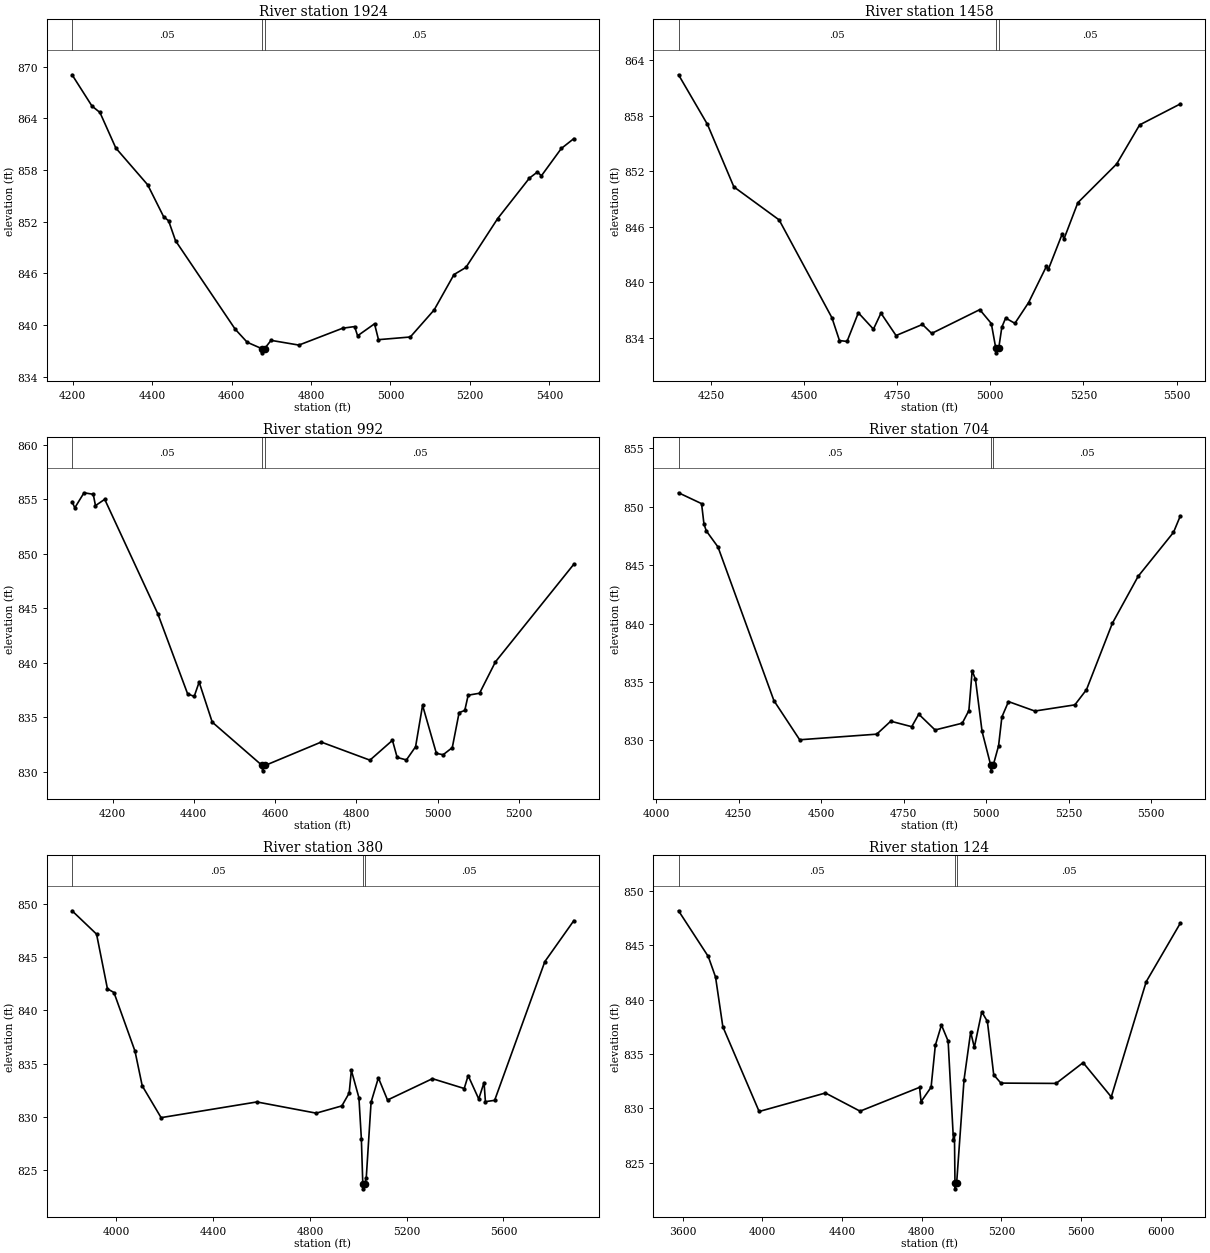
Type RM Length L Ch R = 1 ,1924    ,466,466,466
BEGIN DESCRIPTION:
UDS St 36 4.0
END DESCRIPTION:
XS GIS Cut Line= 3
      2255479.02        7198310.        2254679.        7198260.
      2254217.37      7198273.27
#Sta/Elev= 30
  4198.4  869.04  4248.5  865.41  4268.6  864.66  4308.6  860.53  4388.8  856.26
  4428.9  852.56  4441.4  852.09  4458.9  849.77  4609.2  839.49  4639.3  837.98
  4675.4  837.25  4676.6  836.75  4683.3  837.25  4699.4   838.2  4769.5  837.65
  4879.7  839.61  4909.8   839.8  4917.3  838.73  4959.9  840.12  4969.9  838.28
    5050  838.59    5110  841.73    5160  845.84  5190.1  846.67  5270.1  852.35
  5350.1  857.05  5370.1  857.75  5380.1  857.31  5430.2  860.48  5461.8  861.63
#Mann= 3 ,-1 , 0
  4198.4     .05       0  4675.4    .033       0  4683.3     .05       0
Bank Sta=4675.4,4683.3
XS Rating Curve= 0 ,0
Exp/Cntr=0.3,0.1

Type RM Length L Ch R = 1 ,1458    ,466,466,466
BEGIN DESCRIPTION:
UDS St 36 3.0
END DESCRIPTION:
XS GIS Cut Line= 3
      2255555.69      7197942.38        2254729.        7197810.
      2254232.67      7197927.63
#Sta/Elev= 30
  4162.8  862.45  4240.5  857.08  4311.4  850.33  4432.9  846.76  4574.7  836.18
  4594.9  833.72  4615.2  833.62  4645.6  836.72  4686.1  834.95  4706.3  836.68
  4746.8  834.26  4817.7  835.46  4842.5  834.49  4971.6  837.06  5002.6  835.56
  5014.6  832.89  5015.8  832.39  5022.5  832.89  5030.9  835.17  5041.1  836.15
  5065.9  835.58  5102.8  837.83  5150.4  841.73  5155.6   841.4  5192.6   845.2
  5197.8  844.71  5234.9  848.62  5339.2  852.81  5400.8  857.03  5510.1   859.3
#Mann= 3 ,-1 , 0
  4162.8     .05       0  5014.6    .033       0  5022.5     .05       0
Bank Sta=5014.6,5022.5
XS Rating Curve= 0 ,0
Exp/Cntr=0.3,0.1

Type RM Length L Ch R = 1 ,992     ,288,288,288
BEGIN DESCRIPTION:
UDS St 36 2.0
END DESCRIPTION:
XS GIS Cut Line= 3
      2255590.08      7197747.89        2254779.        7197360.
      2254478.98      7197510.01
#Sta/Elev= 30
  4100.5  854.78  4107.2  854.22  4129.9   855.6  4152.6  855.46  4158.1  854.42
  4180.8     855  4311.3  844.51  4384.8  837.15    4401  836.92  4413.1  838.23
  4445.3  834.56  4567.8  830.59    4569  830.09  4575.8  830.59  4713.4  832.73
  4833.3  831.07  4888.7  832.89  4900.3  831.32    4923  831.09  4945.6   832.3
  4962.8   836.1  4996.8  831.69  5013.5  831.57  5035.9  832.22  5052.7  835.43
  5066.6  835.63    5075  837.03    5103  837.21  5142.1  840.09    5335  849.05
#Mann= 3 ,-1 , 0
  4100.5     .05       0  4567.8    .033       0  4575.8     .05       0
Bank Sta=4567.8,4575.8
XS Rating Curve= 0 ,0
Exp/Cntr=0.3,0.1

Type RM Length L Ch R = 1 ,704     ,324,324,324
BEGIN DESCRIPTION:
UDS St 36 1.2
END DESCRIPTION:
XS GIS Cut Line= 4
      2255577.59      7197680.23      2254972.83       7197103.4
      2254765.29      7197105.25      2254464.34      7197475.22
#Sta/Elev= 30
  4068.1   851.2  4137.9  850.27  4145.1  848.53  4152.1  847.94  4187.6  846.56
  4357.1   833.4  4435.1  830.05  4668.5  830.53    4711  831.64  4774.5  831.17
  4795.9  832.24  4845.3  830.89  4927.7  831.47  4947.7  832.55  4957.7  835.96
  4967.7  835.22  4987.7  830.76  5013.7  827.89  5014.9  827.39  5021.7  827.89
  5037.7  829.54  5047.7     832  5067.7  833.32  5147.4  832.51  5268.8  833.04
    5304  834.34  5382.3  840.02  5460.6  844.05  5567.6  847.81  5588.3  849.22
#Mann= 3 ,-1 , 0
  4068.1     .05       0  5013.7    .033       0  5021.7     .05       0
Bank Sta=5013.7,5021.7
XS Rating Curve= 0 ,0
Exp/Cntr=0.3,0.1

Type RM Length L Ch R = 1 ,380     ,256,256,256
BEGIN DESCRIPTION:
UDS St 36 0.8
END DESCRIPTION:
XS GIS Cut Line= 4
      2255608.18      7197672.75      2255001.89       7196776.4
      2254786.04      7196800.83      2254418.33      7197482.85
#Sta/Elev= 30
  3816.9  849.33  3918.2  847.14  3963.1  842.02  3990.1  841.67    4077  836.18
  4106.9  832.93  4184.9  829.95  4580.8  831.42  4826.1  830.37  4932.1  831.05
  4962.3  832.25  4971.4  834.38  5002.6  831.82  5012.7  827.99  5018.6  823.78
  5019.8  823.28  5026.8  823.78  5032.8  824.26  5052.9   831.4  5083.1  833.68
  5120.8   831.6  5306.5   833.6  5437.9  832.68  5454.1  833.89  5497.9   831.7
  5519.8  833.24  5525.5  831.45  5563.6  831.57  5771.2  844.57  5891.1  848.41
#Mann= 3 ,-1 , 0
  3816.9     .05       0  5018.6    .035       0  5026.8     .05       0
Bank Sta=5018.6,5026.8
XS Rating Curve= 0 ,0
Exp/Cntr=0.3,0.1

Type RM Length L Ch R = 1 ,124     ,0,0,0
BEGIN DESCRIPTION:
UDS St 36 0.7
END DESCRIPTION:
XS GIS Cut Line= 4
      2255651.61      7197683.46      2254938.68      7196536.87
      2254812.04      7196569.51       2254361.5      7197503.15
#Sta/Elev= 30
    3580  848.16  3729.1  843.96  3765.7  842.07  3802.3   837.5  3984.4  829.71
    4317  831.41  4490.8  829.74  4789.3  831.93  4796.9  830.61  4847.1  831.94
  4868.4  835.79  4899.1  837.66  4932.6  836.18  4959.2  827.12  4964.3  827.64
    4967   823.1  4968.2   822.6  4975.2   823.1  5012.4  832.62  5045.7  837.02
    5064   835.6  5101.4  838.87  5129.6  837.99  5161.4  833.08  5197.4  832.32
  5474.2  832.29  5609.9   834.2  5751.1  831.05  5926.4  841.64  6097.6  847.02
#Mann= 3 ,-1 , 0
    3580     .05       0    4967    .033       0  4975.2     .05       0
Bank Sta=4967,4975.2
XS Rating Curve= 0 ,0
Exp/Cntr=0.3,0.1

Chan Stop Cuts=-1
Use User Specified Reach Order=0
Composite Channel Slope=5