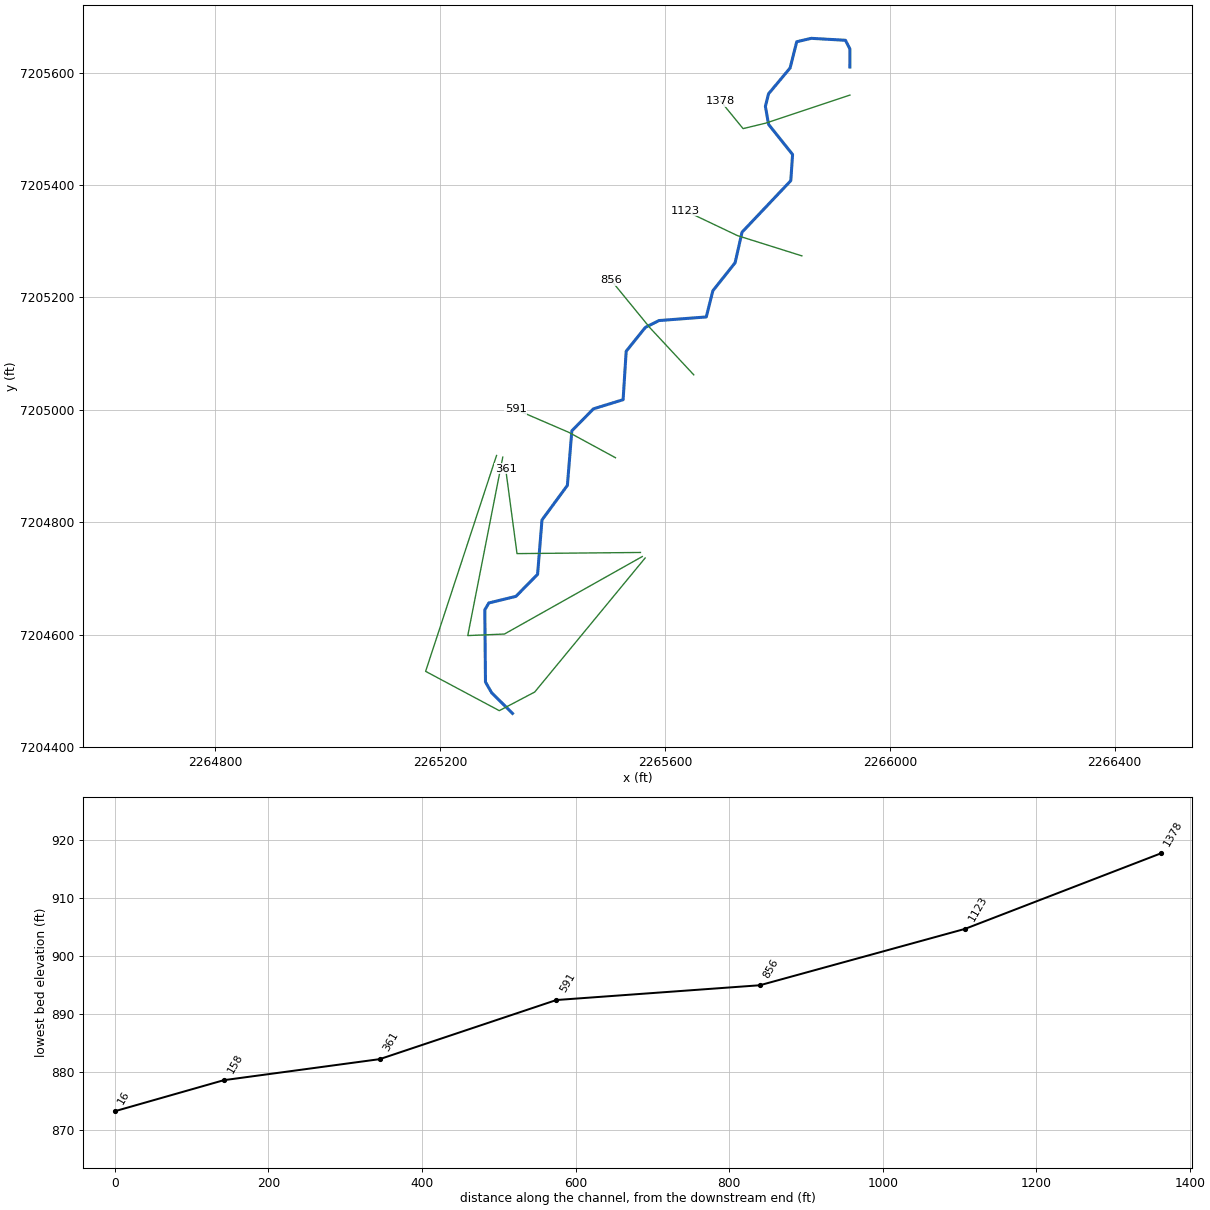
--- UDS St 45.prj (project) ---

Proj Title=UDS St 45 Base Level Engineering
Current Plan=p01
Default Exp/Contr=0.3,0.1
English Units
Geom File=g01
Flow File=f01
Plan File=p01
Y Axis Title=Elevation
X Axis Title(PF)=Main Channel Distance
X Axis Title(XS)=Station
BEGIN DESCRIPTION:
UDS St 45
END DESCRIPTION:
DSS Export Rating Curves= 0
DSS Export Rating Curve Sorted= 0
DSS Export Volume Flow Curves= 0
DXF OffsetX= 0
DXF OffsetY= 0
DXF ScaleX= 1
DXF ScaleY= 10

--- UDS St 45.p01 (plan) ---

Plan Title=Multiple Run
Short Identifier=Multiple
Geom File=g01
Flow File=f01
Subcritical Flow
K Sum by GR= 0
Std Step Tol= 0.01
Critical Tol= 0.01
Num of Std Step Trials= 20
Max Error Tol= 0.3
Flow Tol Ratio= 0.001
Split Flow NTrial= 30
Split Flow Tol= 0.02
Split Flow Ratio= 0.02
Log Output Level= 0
Friction Slope Method= 1
Unsteady Friction Slope Method= 2
Unsteady Bridges Friction Slope Method= 1
Parabolic Critical Depth
Global Vel Dist=  1 , 1 , 1
Global Log Level= 0
CheckData=True
Encroach Param= -1, 0, 0, 0
BEGIN DESCRIPTION:
Multiple Run
END DESCRIPTION:

--- UDS St 45.f01 (steady flow) ---

Flow Title=Multiple
Number of Profiles=7
Profile Names=10-year,25-year,50-year,1pct_min,100-year,1pct_plu,500-year
River Rch & RM= UDS St 45,Reach-1,1378
     247     327     390     233     465     927     658
River Rch & RM= UDS St 45,Reach-1,16
    2294    3369    4313    2730    5446   10867    8720
Boundary for River Rch & Prof#=UDS St 45,Reach-1,1
Up Type=0
Dn Type=3
Dn Slope=0.005
Boundary for River Rch & Prof#=UDS St 45,Reach-1,2
Up Type=0
Dn Type=3
Dn Slope=0.005
Boundary for River Rch & Prof#=UDS St 45,Reach-1,3
Up Type=0
Dn Type=3
Dn Slope=0.005
Boundary for River Rch & Prof#=UDS St 45,Reach-1,4
Up Type=0
Dn Type=3
Dn Slope=0.005
Boundary for River Rch & Prof#=UDS St 45,Reach-1,5
Up Type=0
Dn Type=3
Dn Slope=0.005
Boundary for River Rch & Prof#=UDS St 45,Reach-1,6
Up Type=0
Dn Type=3
Dn Slope=0.005
Boundary for River Rch & Prof#=UDS St 45,Reach-1,7
Up Type=0
Dn Type=3
Dn Slope=0.005

--- UDS St 45.g01 (geometry) ---

Geom Title=Existing Conditions
Program Version=4.10

River Reach=UDS St 45       ,Reach-1
Reach XY= 30
        2265929.        7205610.      2265929.03      7205642.03
      2265921.11      7205657.49      2265860.47      7205660.95
      2265834.44      7205654.95      2265822.67      7205608.21
      2265784.32      7205562.24      2265778.71      7205539.84
      2265784.41      7205507.81      2265827.07      7205454.28
      2265823.89      7205407.71      2265737.16      7205316.05
      2265724.83       7205261.7      2265685.26       7205211.8
      2265673.55      7205165.25      2265589.42      7205158.86
      2265565.31      7205146.75      2265531.11      7205104.22
      2265525.65      7205018.06      2265472.97      7205001.83
      2265434.46      7204962.66      2265426.53      7204865.57
      2265381.36      7204804.02      2265373.54      7204707.34
      2265335.03      7204668.17      2265286.84      7204656.44
      2265279.66      7204644.16      2265280.87       7204515.8
      2265291.91       7204496.5        2265329.        7204460.

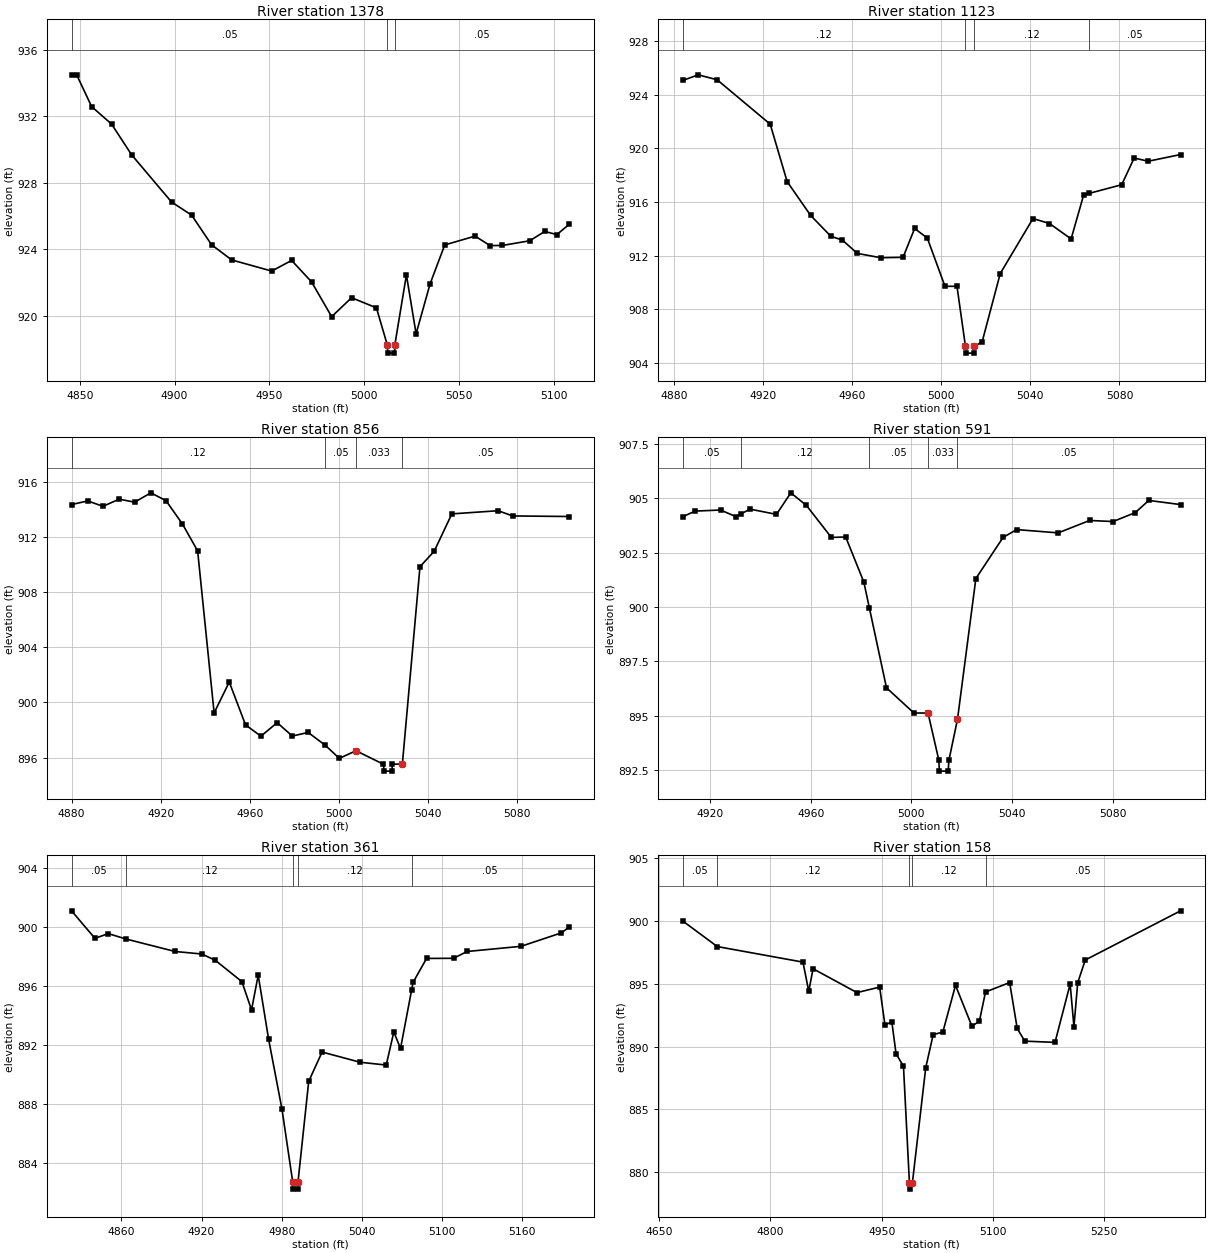
Type RM Length L Ch R = 1 ,1378    ,255,255,255
BEGIN DESCRIPTION:
UDS St 45 5.0
END DESCRIPTION:
XS GIS Cut Line= 4
      2265929.04      7205560.01        2265779.        7205510.
      2265739.02      7205500.32      2265699.23      7205549.04
#Sta/Elev= 30
  4845.7  934.48  4848.4  934.48  4856.3  932.57  4866.8  931.52  4877.4  929.67
  4898.4  926.84    4909  926.05  4919.5  924.27  4930.1  923.36  4951.2  922.69
  4961.7  923.33  4972.2  922.04  4982.8  919.95  4993.3  921.09  5006.4  920.48
  5012.1  918.26  5012.4  917.76  5015.9  917.76  5016.1  918.26  5022.2  922.46
  5027.3  918.92  5034.7  921.93  5042.4  924.26  5058.4  924.79  5066.3  924.22
  5072.8  924.23  5087.2  924.51  5095.1  925.07  5101.5  924.88  5107.9  925.49
#Mann= 3 ,-1 , 0
  4845.7     .05       0  5012.1    .033       0  5016.1     .05       0
Bank Sta=5012.1,5016.1
XS Rating Curve= 0 ,0
Exp/Cntr=0.3,0.1

Type RM Length L Ch R = 1 ,1123    ,267,267,267
BEGIN DESCRIPTION:
UDS St 45 4.0
END DESCRIPTION:
XS GIS Cut Line= 3
      2265843.59      7205273.96        2265729.        7205310.
      2265635.93       7205354.3
#Sta/Elev= 30
  4884.2  925.06    4891  925.47  4899.5   925.1  4923.3  921.79  4930.9  917.51
  4941.4     915  4950.5  913.44  4955.7  913.15  4962.4  912.16  4972.9  911.84
  4982.9  911.87  4988.1  914.02  4993.8   913.3  5001.7  909.71  5007.1  909.71
  5010.9  905.23  5011.2  904.73  5014.7  904.73  5014.9  905.23  5018.4  905.58
  5026.5  910.66  5041.2  914.76  5048.6  914.39  5058.3  913.24  5063.9   916.5
  5066.5  916.64    5081  917.28  5086.6  919.27  5092.9  919.03  5107.4  919.53
#Mann= 4 ,-1 , 0
  4884.2     .12       0  5010.9     .07       0  5014.9     .12       0
  5066.5     .05       0
#XS Ineff= 2 , 0
       0  4988.1  914.02               0
Permanent Ineff=
       F       F
Bank Sta=5010.9,5014.9
XS Rating Curve= 0 ,0
Exp/Cntr=0.3,0.1

Type RM Length L Ch R = 1 ,856     ,265,265,265
BEGIN DESCRIPTION:
UDS St 45 3.0
END DESCRIPTION:
XS GIS Cut Line= 3
      2265651.35      7205062.24      2265573.46      7205145.92
       2265504.5      7205230.31
#Sta/Elev= 30
    4880  914.38  4887.3  914.64  4894.1  914.25  4901.4  914.77  4908.3  914.55
  4915.6  915.23  4922.4  914.66  4929.8  912.96  4936.6  911.01    4944  899.24
  4950.8  901.48  4958.1  898.37    4965  897.55  4972.3  898.53  4979.1  897.56
  4986.2  897.82  4993.8   896.9  5000.2  895.94  5007.7  896.49    5020  895.51
  5020.3  895.01  5023.8  895.01    5024  895.51  5028.5  895.53  5036.4  909.86
  5042.8  910.99  5050.7   913.7  5071.5  913.93    5078  913.55  5103.3  913.51
#Mann= 4 ,-1 , 0
    4880     .12       0  4993.8     .05       0  5007.7    .033       0
  5028.5     .05       0
#XS Ineff= 2 , 0
       0  4950.8  901.48               0
Permanent Ineff=
       F       F
Bank Sta=5007.7,5028.5
XS Rating Curve= 0 ,0
Exp/Cntr=0.3,0.1

Type RM Length L Ch R = 1 ,591     ,230,230,230
BEGIN DESCRIPTION:
UDS St 45 2.0
END DESCRIPTION:
XS GIS Cut Line= 3
      2265512.06      7204914.84        2265429.        7204960.
      2265334.38      7205000.83
#Sta/Elev= 30
  4909.3  904.16  4914.1  904.41  4924.2  904.46  4930.2  904.16  4932.4  904.29
  4935.9   904.5  4946.4  904.26  4952.1  905.25  4958.3  904.67  4968.2   903.2
  4973.9  903.22  4981.1  901.15  4983.3  899.96  4990.1  896.29    5001  895.13
  5006.6  895.13  5010.9  892.96  5011.1  892.46  5014.6  892.46  5014.9  892.96
  5018.3  894.84  5025.6  901.31  5036.4   903.2  5041.8  903.56  5058.3  903.41
  5070.8  903.98  5080.1  903.93  5088.9  904.34  5094.3   904.9  5106.9  904.71
#Mann= 5 ,-1 , 0
  4909.3     .05       0  4932.4     .12       0  4983.3     .05       0
  5006.6    .033       0  5018.3     .05       0
Bank Sta=5006.6,5018.3
XS Rating Curve= 0 ,0
Exp/Cntr=0.3,0.1

Type RM Length L Ch R = 1 ,361     ,203,203,203
BEGIN DESCRIPTION:
UDS St 45 1.0
END DESCRIPTION:
XS GIS Cut Line= 3
       2265556.5      7204746.27      2265336.95      7204744.23
      2265316.69      7204895.62
#Sta/Elev= 30
  4822.7  901.08  4840.2  899.22  4850.2  899.54  4863.6  899.17  4900.2  898.33
  4920.2  898.16  4930.2  897.74  4950.2  896.29  4957.4  894.38  4962.4  896.73
  4970.2  892.39  4980.2  887.66  4988.2  882.76  4988.5  882.26    4992  882.26
  4992.2  882.76  5000.2  889.55  5010.2  891.53  5038.7  890.84  5058.2  890.65
  5063.9  892.89  5068.9  891.77  5077.2  895.72  5078.3  896.24  5088.4  897.86
  5108.6  897.87  5118.7  898.33  5159.1  898.68  5189.3  899.59    5195  899.97
#Mann= 5 ,-1 , 0
  4822.7     .05       0  4863.6     .12       0  4988.2     .07       0
  4992.2     .12       0  5077.2     .05       0
Bank Sta=4988.2,4992.2
XS Rating Curve= 0 ,0
Exp/Cntr=0.3,0.1

Type RM Length L Ch R = 1 ,158     ,142,142,142
BEGIN DESCRIPTION:
UDS St 45 0.9
END DESCRIPTION:
XS GIS Cut Line= 4
      2265559.77      7204739.03      2265314.69      7204601.17
      2265249.38       7204598.4      2265311.64      7204915.89
#Sta/Elev= 30
  4682.5  899.99  4728.6  897.97    4844  896.73  4851.8   894.4  4857.6   896.2
  4916.8   894.3  4947.3  894.74  4954.4  891.73  4963.7  891.96  4969.4  889.43
  4979.4  888.42  4987.4  879.13  4987.7  878.63  4991.4  879.13  5009.4  888.32
  5019.4  890.95  5032.4  891.15  5049.5  894.88  5071.5  891.63  5081.6  892.01
  5089.9  894.35  5122.4   895.1  5132.6  891.44  5142.8  890.43  5183.5  890.33
  5203.9  894.98    5209  891.59  5214.1  895.09  5224.3   896.9  5352.6  900.82
#Mann= 5 ,-1 , 0
  4682.5     .05       0  4728.6     .12       0  4987.4     .07       0
  4991.4     .12       0  5089.9     .05       0
Bank Sta=4987.4,4991.4
XS Rating Curve= 0 ,0
Exp/Cntr=0.3,0.1

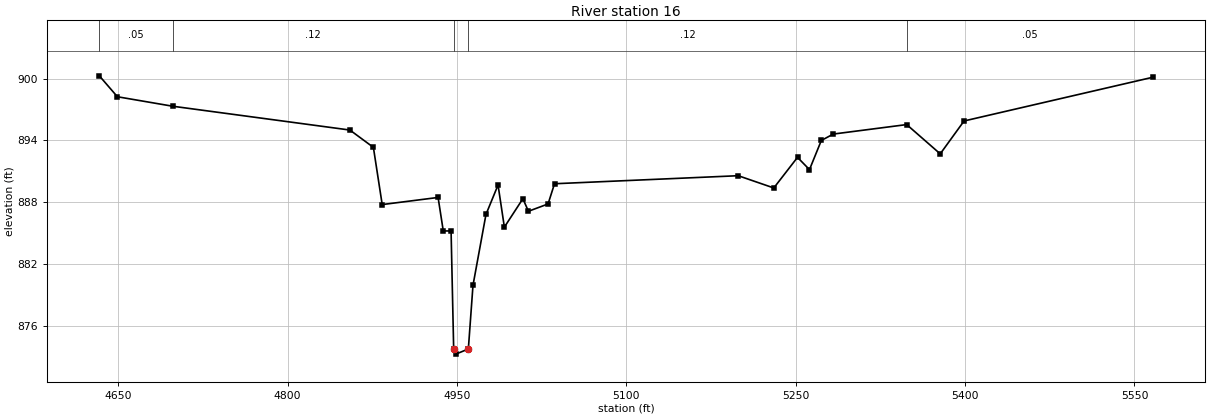
Type RM Length L Ch R = 1 ,16      ,0,0,0
BEGIN DESCRIPTION:
UDS St 45 0.8
END DESCRIPTION:
XS GIS Cut Line= 5
      2265564.85      7204736.47      2265368.45      7204497.97
      2265305.45      7204464.84       2265174.4      7204534.77
      2265300.53       7204918.8
#Sta/Elev= 30
  4633.3  900.27  4649.3  898.24  4698.3  897.32  4855.2  895.01    4876  893.33
  4883.8  887.78  4933.3  888.47  4937.9  885.22  4944.8  885.22  4947.1  873.77
    4949  873.27  4960.1  873.77  4964.2  879.94  4975.7  886.82  4986.4  889.68
    4992  885.59  5008.4  888.35  5013.3  887.13  5030.7  887.84  5036.4   889.8
  5199.1  890.58  5230.6  889.39  5251.6  892.36  5262.2  891.17  5272.7     894
  5283.3  894.62  5348.3  895.54    5378   892.7  5399.1  895.89  5566.2  900.13
#Mann= 5 ,-1 , 0
  4633.3     .05       0  4698.3     .12       0  4947.1     .07       0
  4960.1     .12       0  5348.3     .05       0
#XS Ineff= 2 , 0
       0                  5348.3       0  895.54
Permanent Ineff=
       F       F
Bank Sta=4947.1,4960.1
XS Rating Curve= 0 ,0
Exp/Cntr=0.3,0.1

Chan Stop Cuts=-1
Use User Specified Reach Order=0
Composite Channel Slope=5