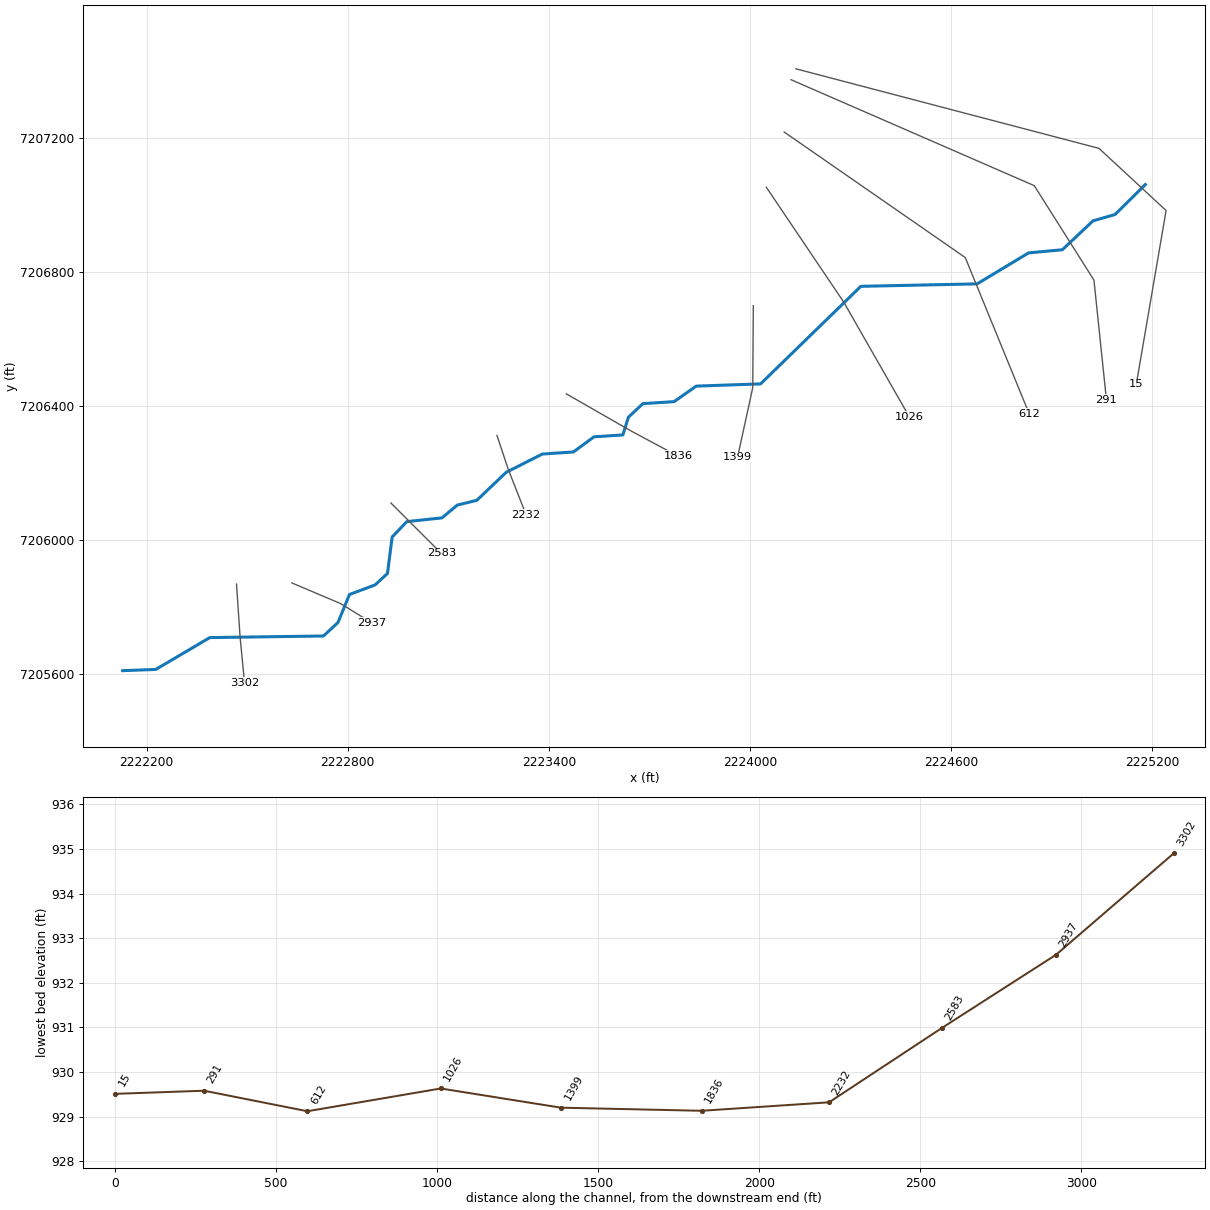
--- UDS St 48.prj (project) ---

Proj Title=UDS St 48 Base Level Engineering
Current Plan=p01
Default Exp/Contr=0.3,0.1
English Units
Geom File=g01
Flow File=f01
Plan File=p01
BEGIN DESCRIPTION:
UDS St 48
END DESCRIPTION:

--- UDS St 48.p01 (plan) ---

Plan Title=Multiple Run
Short Identifier=Multiple
Geom File=g01
Flow File=f01
Subcritical Flow
K Sum by GR= 0
Std Step Tol= 0.01
Critical Tol= 0.01
Num of Std Step Trials= 20
Max Error Tol= 0.3
Flow Tol Ratio= 0.001
Split Flow NTrial= 30
Split Flow Tol= 0.02
Split Flow Ratio= 0.02
Log Output Level= 0
Friction Slope Method= 1
Unsteady Friction Slope Method= 2
Unsteady Bridges Friction Slope Method= 1
Parabolic Critical Depth
Global Vel Dist=  1 , 1 , 1
Global Log Level= 0
CheckData=True
Encroach Param= -1, 0, 0, 0
BEGIN DESCRIPTION:
Multiple Run
END DESCRIPTION:

--- UDS St 48.f01 (steady flow) ---

Flow Title=Multiple
Number of Profiles=7
Profile Names=10-year,25-year,50-year,1pct_min,100-year,1pct_plu,500-year
River Rch & RM= UDS St 48,Reach-1,3302
     668     936    1161     716    1429    2851    2170
River Rch & RM= UDS St 48,Reach-1,1026
     647     903    1117     686    1370    2733    2066
River Rch & RM= UDS St 48,Reach-1,15
    1399    2025    2568    1613    3218    6421    5074
Boundary for River Rch & Prof#=UDS St 48,Reach-1,1
Up Type=0
Dn Type=3
Dn Slope=0.005
Boundary for River Rch & Prof#=UDS St 48,Reach-1,2
Up Type=0
Dn Type=3
Dn Slope=0.005
Boundary for River Rch & Prof#=UDS St 48,Reach-1,3
Up Type=0
Dn Type=3
Dn Slope=0.005
Boundary for River Rch & Prof#=UDS St 48,Reach-1,4
Up Type=0
Dn Type=3
Dn Slope=0.005
Boundary for River Rch & Prof#=UDS St 48,Reach-1,5
Up Type=0
Dn Type=3
Dn Slope=0.005
Boundary for River Rch & Prof#=UDS St 48,Reach-1,6
Up Type=0
Dn Type=3
Dn Slope=0.005
Boundary for River Rch & Prof#=UDS St 48,Reach-1,7
Up Type=0
Dn Type=3
Dn Slope=0.005

--- UDS St 48.g01 (geometry) ---

Geom Title=Existing Conditions

River Reach=UDS St 48,Reach-1
Reach XY= 30
      2222129.00      7205610.00      2222227.50      7205613.63
      2222388.65      7205708.64      2222727.75      7205713.45
      2222770.97      7205753.64      2222805.17      7205837.13
      2222881.55      7205865.75      2222918.61      7205899.90
      2222932.52      7206008.74      2222976.29      7206054.59
      2223081.32      7206065.77      2223126.83      7206103.86
      2223185.05      7206118.16      2223272.95      7206201.84
      2223380.58      7206256.17      2223473.03      7206262.35
      2223534.65      7206307.49      2223620.65      7206313.19
      2223637.17      7206366.03      2223680.30      7206406.45
      2223773.43      7206412.47      2223839.50      7206458.78
      2224031.45      7206465.46      2224330.46      7206756.46
      2224677.45      7206763.75      2224830.59      7206856.17
      2224931.42      7206865.54      2225022.96      7206951.83
      2225088.70      7206970.72      2225179.00      7207060.00

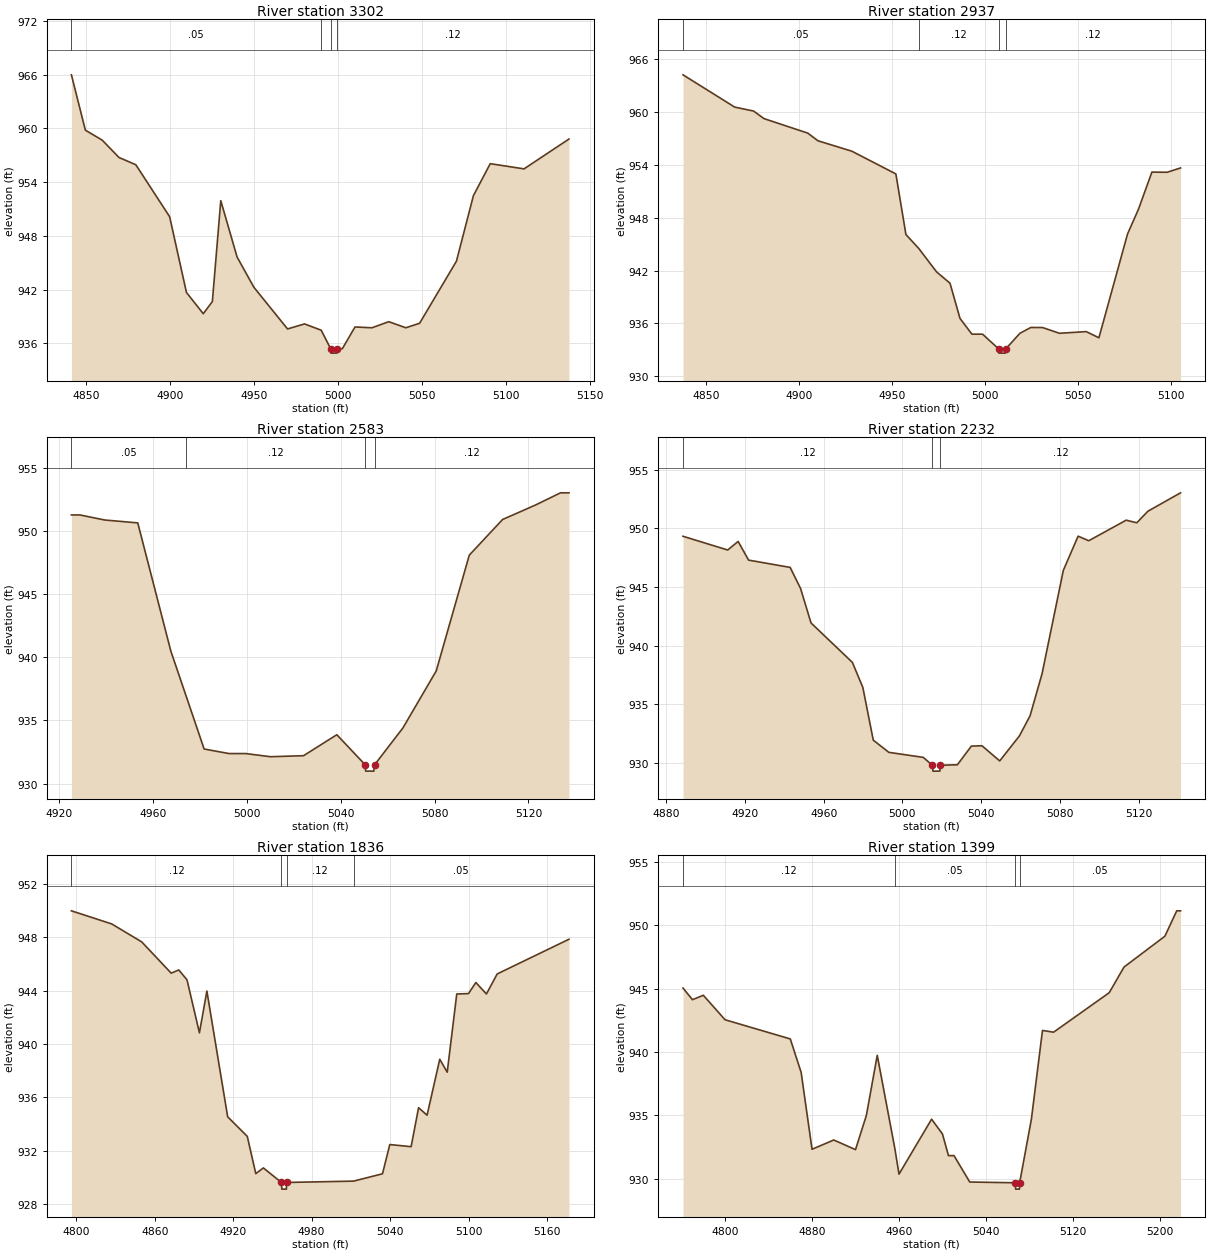
Type RM Length L Ch R = 1,3302,365,365,365
BEGIN DESCRIPTION:
UDS St 48 8.0
END DESCRIPTION:
XS GIS Cut Line= 3
      2222468.35      7205868.24      2222479.00      7205710.00
      2222492.32      7205573.45
#Sta/Elev= 30
  4841.5  965.97  4849.8  959.79  4859.8  958.68  4869.8  956.74  4879.8  955.93
  4899.9  950.13  4909.9  941.67  4919.9  939.30  4925.3  940.66  4930.3  951.92
  4940.0  945.63  4950.0  942.25  4970.0  937.60  4980.1  938.16  4990.0  937.46
  4995.6  935.40  4995.8  934.90  4999.3  934.90  4999.6  935.40  5002.6  935.40
  5010.1  937.82  5020.2  937.73  5030.2  938.41  5040.3  937.73  5048.5  938.23
  5070.4  945.16  5080.5  952.48  5090.5  956.05  5110.6  955.47  5137.3  958.80
#Mann=4,-1,0
  4841.5    0.05       0  4990.0    0.12       0  4995.6    0.07       0
  4999.6    0.12       0
Bank Sta=4995.6,4999.6
Exp/Cntr=0.3,0.1

Type RM Length L Ch R = 1,2937,354,354,354
BEGIN DESCRIPTION:
UDS St 48 7.0
END DESCRIPTION:
XS GIS Cut Line= 3
      2222633.44      7205871.73      2222779.00      7205810.00
      2222872.12      7205752.41
#Sta/Elev= 30
  4837.6  964.19  4865.4  960.53  4875.6  960.08  4881.1  959.23  4904.7  957.58
  4910.2  956.71  4928.4  955.53  4952.1  952.95  4957.5  946.08  4964.4  944.50
  4974.0  941.84  4981.2  940.56  4986.6  936.56  4993.0  934.78  4998.7  934.78
  5007.3  933.13  5007.5  932.63  5011.0  932.63  5011.3  933.13  5018.8  934.88
  5024.7  935.54  5031.0  935.53  5040.1  934.88  5054.5  935.07  5061.3  934.37
  5076.7  946.14  5082.6  948.96  5089.8  953.16  5098.0  953.14  5105.2  953.63
#Mann=4,-1,0
  4837.6    0.05       0  4964.4    0.12       0  5007.3    0.07       0
  5011.3    0.12       0
Bank Sta=5007.3,5011.3
Exp/Cntr=0.3,0.1

Type RM Length L Ch R = 1,2583,351,351,351
BEGIN DESCRIPTION:
UDS St 48 6.0
END DESCRIPTION:
XS GIS Cut Line= 3
      2222928.99      7206110.01      2222979.00      7206060.00
      2223079.03      7205959.97
#Sta/Elev= 23
  4925.1  951.26  4928.7  951.26  4939.3  950.86  4953.4  950.63  4967.5  940.49
  4973.9  937.00  4981.7  932.74  4992.3  932.38  4999.4  932.38  5010.0  932.13
  5024.1  932.21  5038.3  933.87  5050.4  931.49  5050.6  930.99  5054.1  930.99
  5054.4  931.49  5066.5  934.41  5080.7  938.92  5094.8  948.08  5109.0  950.90
  5123.1  952.05  5133.7  953.01  5137.3  953.01
#Mann=4,-1,0
  4925.1    0.05       0  4973.9    0.12       0  5050.4    0.07       0
  5054.4    0.12       0
Bank Sta=5050.4,5054.4
Exp/Cntr=0.3,0.1

Type RM Length L Ch R = 1,2232,396,396,396
BEGIN DESCRIPTION:
UDS St 48 5.0
END DESCRIPTION:
XS GIS Cut Line= 3
      2223245.17      7206311.63      2223279.00      7206210.00
      2223332.20      7206074.59
#Sta/Elev= 30
  4888.6  949.32  4911.3  948.15  4916.6  948.88  4921.9  947.29  4943.0  946.67
  4948.3  944.87  4953.6  941.94  4974.6  938.58  4979.9  936.45  4985.2  931.96
  4993.1  930.92  5010.6  930.49  5015.2  929.82  5015.5  929.32  5019.0  929.32
  5019.2  929.82  5027.9  929.86  5035.0  931.45  5040.4  931.48  5049.4  930.19
  5059.4  932.32  5064.8  934.03  5070.9  937.62  5081.7  946.42  5089.2  949.33
  5094.6  948.94  5113.6  950.69  5119.0  950.47  5124.6  951.45  5141.2  953.02
#Mann=3,-1,0
  4888.6    0.12       0  5015.2    0.07       0  5019.2    0.12       0
Bank Sta=5015.2,5019.2
Exp/Cntr=0.3,0.1

Type RM Length L Ch R = 1,1836,437,437,437
BEGIN DESCRIPTION:
UDS St 48 4.0
END DESCRIPTION:
XS GIS Cut Line= 3
      2223452.32      7206435.55      2223644.23      7206325.45
      2223784.60      7206250.24
#Sta/Elev= 30
  4796.3  949.98  4827.1  949.00  4850.1  947.65  4872.6  945.31  4878.4  945.55
  4884.7  944.81  4894.2  940.84  4899.9  943.97  4915.8  934.55  4930.8  933.08
  4937.3  930.29  4943.1  930.72  4956.9  929.63  4957.2  929.13  4960.7  929.13
  4960.9  929.63  5012.1  929.73  5034.2  930.28  5039.8  932.47  5056.1  932.31
  5061.8  935.23  5068.3  934.67  5078.0  938.86  5083.7  937.89  5091.0  943.75
  5100.0  943.78  5105.6  944.61  5113.7  943.75  5121.9  945.25  5176.8  947.85
#Mann=4,-1,0
  4796.3    0.12       0  4956.9    0.07       0  4960.9    0.12       0
  5012.1    0.05       0
Bank Sta=4956.9,4960.9
Exp/Cntr=0.3,0.1

Type RM Length L Ch R = 1,1399,373,373,373
BEGIN DESCRIPTION:
UDS St 48 3.0
END DESCRIPTION:
XS GIS Cut Line= 3
      2224009.71      7206698.70      2224008.03      7206454.06
      2223962.51      7206245.93
#Sta/Elev= 30
  4761.2  945.04  4769.9  944.12  4779.9  944.47  4799.9  942.54  4859.9  941.03
  4869.9  938.39  4879.9  932.34  4899.9  933.07  4919.9  932.31  4929.9  935.01
  4939.9  939.74  4956.1  932.39  4959.9  930.38  4989.9  934.71  4999.9  933.54
  5005.4  931.84  5010.5  931.84  5025.0  929.76  5066.9  929.70  5067.2  929.20
  5070.7  929.20  5070.9  929.70  5081.7  934.71  5091.9  941.70  5102.1  941.56
  5153.3  944.67  5166.9  946.69  5204.5  949.12  5215.4  951.12  5218.9  951.12
#Mann=4,-1,0
  4761.2    0.12       0  4956.1    0.05       0  5066.9   0.033       0
  5070.9    0.05       0
Bank Sta=5066.9,5070.9
Exp/Cntr=0.3,0.1

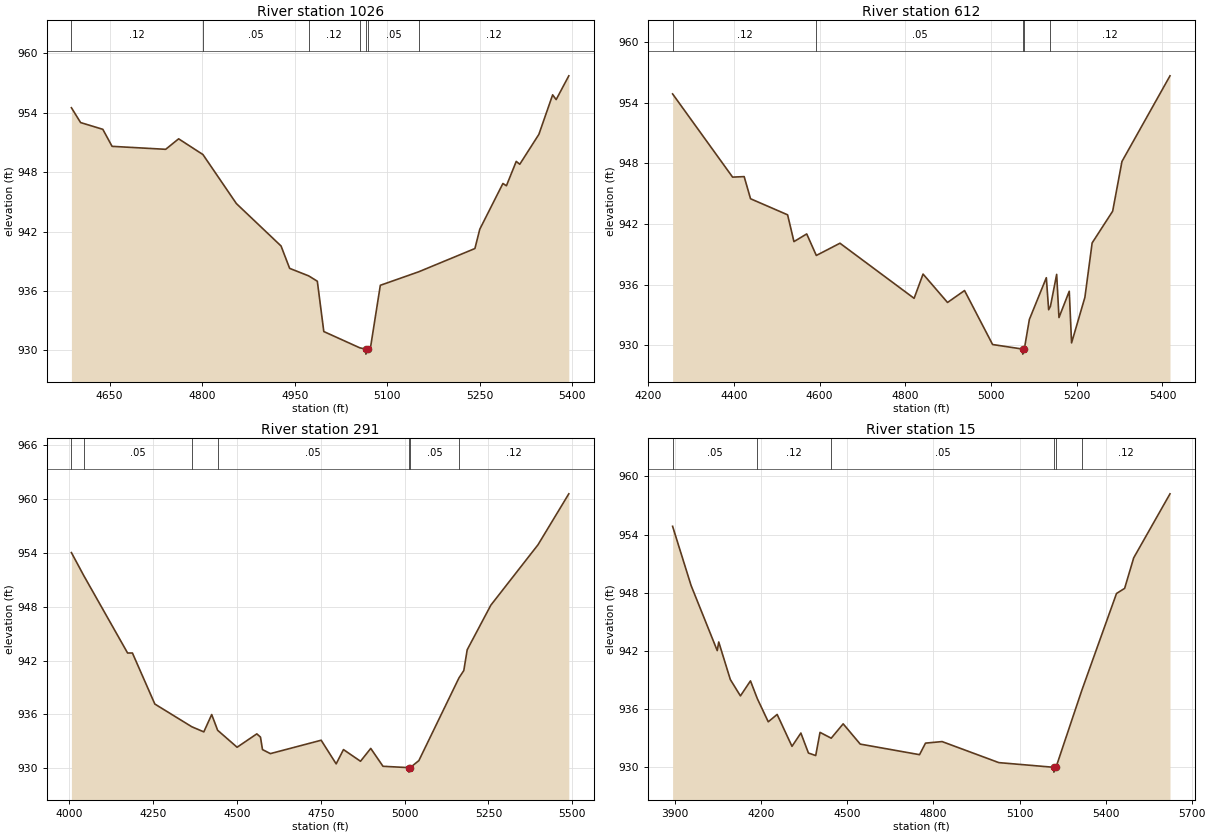
Type RM Length L Ch R = 1,1026,414,414,414
BEGIN DESCRIPTION:
UDS St 48 2.0
END DESCRIPTION:
XS GIS Cut Line= 3
      2224048.64      7207051.77      2224279.00      7206710.00
      2224474.53      7206367.90
#Sta/Elev= 30
  4588.1  954.51  4603.0  953.01  4639.0  952.33  4654.0  950.61  4740.9  950.31
  4761.9  951.37  4801.3  949.78  4855.5  944.83  4927.9  940.55  4941.8  938.29
  4972.7  937.53  4986.7  936.99  4997.2  931.91  5055.4  930.27  5065.2  930.13
  5065.4  929.63  5069.2  930.13  5073.0  930.34  5088.8  936.58  5150.9  937.94
  5242.1  940.29  5250.0  942.24  5287.5  946.86  5293.2  946.63  5309.1  949.09
  5314.8  948.80  5345.8  951.82  5368.1  955.81  5373.8  955.33  5394.3  957.73
#Mann=7,-1,0
  4588.1    0.12       0  4801.3    0.05       0  4972.7    0.12       0
  5055.4    0.05       0  5065.2    0.07       0  5069.2    0.05       0
  5150.9    0.12       0
Bank Sta=5065.2,5069.2
Exp/Cntr=0.3,0.1

Type RM Length L Ch R = 1,612,321,321,321
BEGIN DESCRIPTION:
UDS St 48 1.0
END DESCRIPTION:
XS GIS Cut Line= 3
      2224101.74      7207216.72      2224641.90      7206842.23
      2224832.55      7206376.20
#Sta/Elev= 30
  4256.8  954.86  4396.8  946.63  4423.8  946.68  4438.7  944.49  4525.2  942.90
  4540.0  940.25  4569.8  941.01  4592.2  938.88  4647.4  940.09  4820.4  934.64
  4841.3  937.04  4898.4  934.23  4938.1  935.41  5003.6  930.07  5073.6  929.62
  5073.9  929.12  5077.6  929.62  5089.4  932.55  5129.0  936.68  5134.4  933.51
  5138.6  933.85  5153.1  937.01  5158.5  932.74  5182.5  935.34  5187.9  930.23
  5219.0  934.74  5235.9  940.12  5283.8  943.26  5305.5  948.18  5417.6  956.65
#Mann=5,-1,0
  4256.8    0.12       0  4592.2    0.05       0  5073.6   0.033       0
  5077.6    0.05       0  5138.6    0.12       0
Bank Sta=5073.6,5077.6
Exp/Cntr=0.3,0.1

Type RM Length L Ch R = 1,291,276,276,276
BEGIN DESCRIPTION:
UDS St 48 0.9
END DESCRIPTION:
XS GIS Cut Line= 4
      2224122.26      7207372.72      2224847.66      7207056.72
      2225025.70      7206774.82      2225062.80      7206418.70
#Sta/Elev= 30
  4006.8  954.02  4043.6  951.46  4174.3  942.84  4188.7  942.84  4255.5  937.16
  4365.7  934.63  4401.5  934.06  4425.0  935.99  4442.7  934.24  4500.7  932.35
  4559.5  933.84  4570.4  933.48  4576.4  932.09  4599.9  931.64  4751.3  933.13
  4796.0  930.50  4817.8  932.09  4868.6  930.79  4899.1  932.22  4935.6  930.23
  5012.4  930.08  5012.7  929.58  5016.5  930.08  5042.5  930.86  5162.1  940.07
  5176.5  940.89  5186.6  943.20  5257.0  948.16  5397.7  954.89  5489.5  960.56
#Mann=7,-1,0
  4006.8    0.12       0  4043.6    0.05       0  4365.7    0.12       0
  4442.7    0.05       0  5012.4   0.033       0  5016.5    0.05       0
  5162.1    0.12       0
Bank Sta=5012.4,5016.5
Exp/Cntr=0.3,0.1

Type RM Length L Ch R = 1,15,0,0,0
BEGIN DESCRIPTION:
UDS St 48 0.8
END DESCRIPTION:
XS GIS Cut Line= 4
      2224136.51      7207405.30      2225040.54      7207168.00
      2225240.84      7206982.54      2225151.97      7206464.13
#Sta/Elev= 30
  3890.9  954.86  3955.5  948.74  4046.5  942.04  4051.7  942.93  4092.1  939.06
  4127.3  937.37  4162.3  938.92  4186.3  937.08  4224.3  934.70  4255.3  935.46
  4307.0  932.17  4338.0  933.54  4364.3  931.48  4389.7  931.22  4404.7  933.61
  4443.7  933.01  4485.4  934.49  4544.8  932.40  4751.6  931.31  4772.3  932.50
  4830.1  932.66  5028.0  930.49  5218.6  930.01  5219.8  929.51  5227.2  930.01
  5316.6  937.90  5438.0  947.93  5466.4  948.46  5498.0  951.61  5624.5  958.21
#Mann=6,-1,0
  3890.9    0.05       0  4186.3    0.12       0  4443.7    0.05       0
  5218.6   0.033       0  5227.2    0.05       0  5316.6    0.12       0
Bank Sta=5218.6,5227.2
Exp/Cntr=0.3,0.1

Chan Stop Cuts=-1