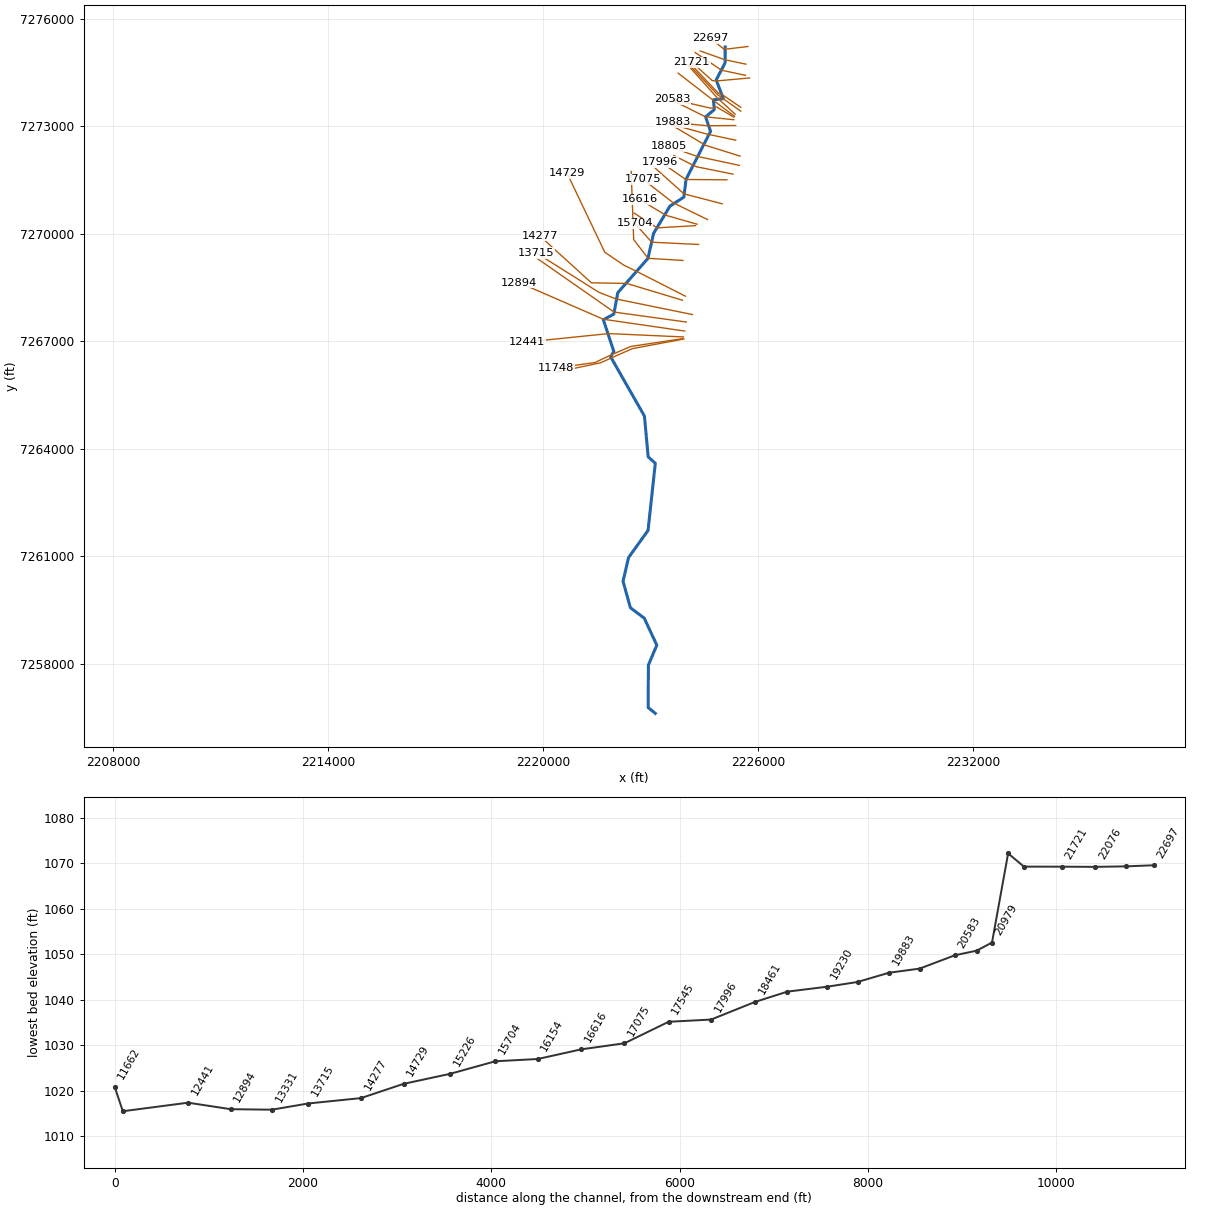
--- STEELMAN BRANCH.prj (project) ---

Proj Title=STEELMAN BRANCH Base Level Engineering
Current Plan=p01
Default Exp/Contr=0.3,0.1
English Units
Geom File=g01
Flow File=f01
Plan File=p01
Y Axis Title=Elevation
X Axis Title(PF)=Main Channel Distance
X Axis Title(XS)=Station
BEGIN DESCRIPTION:
STEELMAN BRANCH
END DESCRIPTION:
DSS Export Rating Curves= 0
DSS Export Rating Curve Sorted= 0
DSS Export Volume Flow Curves= 0
DXF OffsetX= 0
DXF OffsetY= 0
DXF ScaleX= 1
DXF ScaleY= 10

--- STEELMAN BRANCH.p01 (plan) ---

Plan Title=Multiple Run
Short Identifier=Multiple
Geom File=g01
Flow File=f01
Subcritical Flow
K Sum by GR= 0
Std Step Tol= 0.01
Critical Tol= 0.01
Num of Std Step Trials= 20
Max Error Tol= 0.3
Flow Tol Ratio= 0.001
Split Flow NTrial= 30
Split Flow Tol= 0.02
Split Flow Ratio= 0.02
Log Output Level= 0
Friction Slope Method= 1
Unsteady Friction Slope Method= 2
Unsteady Bridges Friction Slope Method= 1
Parabolic Critical Depth
Global Vel Dist=  1 , 1 , 1
Global Log Level= 0
CheckData=True
Encroach Param= -1, 0, 0, 0
BEGIN DESCRIPTION:
Multiple Run
END DESCRIPTION:

--- STEELMAN BRANCH.f01 (steady flow) ---

Flow Title=Multiple
Program Version=4.10
Number of Profiles= 7
Profile Names=10-year,25-year,50-year,1pct_min,100-year,1pct_plu,500-year
River Rch & RM=STEELMAN BRANCH,Reach-1         ,22697
     733    1032    1285     796    1588    3168    2428
River Rch & RM=STEELMAN BRANCH,Reach-1         ,17996
     842    1190    1485     921    1837    3666    2819
River Rch & RM=STEELMAN BRANCH,Reach-1         ,13715
    1214    1750    2215    1390    2773    5533    4361
River Rch & RM=STEELMAN BRANCH,Reach-1         ,12894
    1517    2206    2808    1770    3531    7045    5605
River Rch & RM=STEELMAN BRANCH,Reach-1         ,6951
    1700    2476    3155    1989    3969    7919    6306
Boundary for River Rch & Prof#=STEELMAN BRANCH,Reach-1         , 1
Up Type= 0
Dn Type= 3
Dn Slope=0.0019
Boundary for River Rch & Prof#=STEELMAN BRANCH,Reach-1         , 2
Up Type= 0
Dn Type= 3
Dn Slope=0.0019
Boundary for River Rch & Prof#=STEELMAN BRANCH,Reach-1         , 3
Up Type= 0
Dn Type= 3
Dn Slope=0.0019
Boundary for River Rch & Prof#=STEELMAN BRANCH,Reach-1         , 4
Up Type= 0
Dn Type= 3
Dn Slope=0.0019
Boundary for River Rch & Prof#=STEELMAN BRANCH,Reach-1         , 5
Up Type= 0
Dn Type= 3
Dn Slope=0.0019
Boundary for River Rch & Prof#=STEELMAN BRANCH,Reach-1         , 6
Up Type= 0
Dn Type= 3
Dn Slope=0.0019
Boundary for River Rch & Prof#=STEELMAN BRANCH,Reach-1         , 7
Up Type= 0
Dn Type= 3
Dn Slope=0.0019
DSS Import GetInterval= 0
DSS Import GetPeak= 0
DSS Import FillOption= 0

--- STEELMAN BRANCH.g01 (geometry) ---

Geom Title=Existing Conditions
Program Version=4.10

River Reach=STEELMAN BRANCH ,Reach-1
Reach XY= 30
        2225079.        7275210.      2225076.93      7274765.86
      2224828.72      7274289.82      2225027.31      7273765.23
      2224751.65      7273734.03      2224775.96      7273461.42
      2224531.95      7273257.99      2224671.33      7272856.34
      2223988.15      7271516.73      2223925.92      7271017.62
       2223536.8      7270766.21      2223082.76      7270008.44
      2222923.17       7269307.7       2222082.1      7268351.69
       2221971.2      7267753.79      2221679.24       7267594.8
       2221971.4      7266713.34      2221882.11      7266561.65
      2222825.24      7264908.44      2222930.34      7263769.64
      2223128.96      7263589.82      2222926.76      7261715.93
      2222384.47      7260962.45      2222228.34      7260299.41
      2222434.46      7259557.55      2222821.32      7259266.52
      2223170.96      7258513.32      2222936.56        7257960.
      2222929.41      7256773.91        2223129.        7256610.

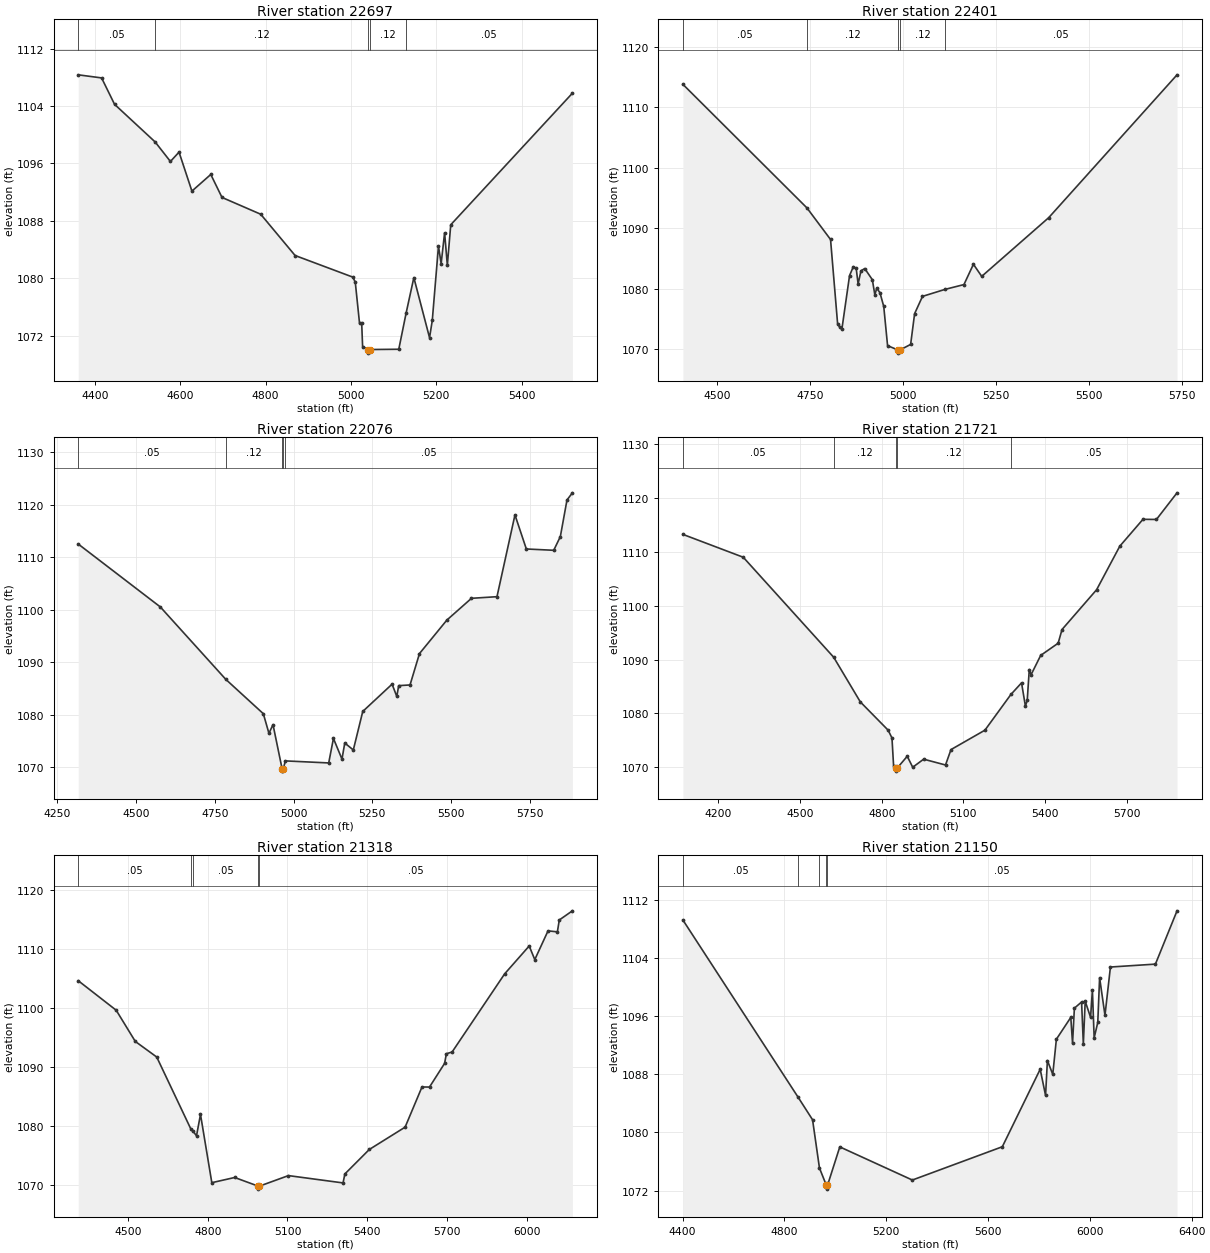
Type RM Length L Ch R = 1 ,22697   ,296,296,296
BEGIN DESCRIPTION:
STEELMAN BRANCH 47.5
END DESCRIPTION:
XS GIS Cut Line= 3
      2225713.48      7275222.16      2225054.01      7275142.41
      2224667.63      7275449.93
#Sta/Elev= 30
  4360.9 1108.35  4415.6 1107.92    4446 1104.24  4541.1    1099  4576.9 1096.28
  4597.1 1097.58  4627.3 1092.15  4671.5 1094.47  4697.8 1091.27  4788.5 1088.93
  4869.1 1083.18  5004.3 1080.17  5010.1 1079.48  5020.1 1073.75  5025.2 1073.75
  5027.3  1070.5  5039.7 1070.08  5039.9 1069.58  5043.7 1070.08  5112.1 1070.12
  5129.4 1075.19  5147.4  1080.1  5184.2 1071.73  5190.6 1074.13  5205.1 1084.49
  5211.4 1082.05  5219.5 1086.35  5225.9 1081.82  5233.9 1087.46    5519 1105.79
#Mann= 5 ,-1 , 0
  4360.9     .05       0  4541.1     .12       0  5039.7     .07       0
  5043.7     .12       0  5129.4     .05       0
Bank Sta=5039.7,5043.7
XS Rating Curve= 0 ,0
Exp/Cntr=0.3,0.1

Type RM Length L Ch R = 1 ,22401   ,325,325,325
BEGIN DESCRIPTION:
STEELMAN BRANCH 47.0
END DESCRIPTION:
XS GIS Cut Line= 3
       2225657.7      7274729.45      2225079.12      7274849.95
       2224384.1      7275096.65
#Sta/Elev= 30
    4409 1113.81  4742.6 1093.36    4806 1088.14    4825 1074.18  4830.1 1073.68
  4836.7  1073.4  4857.1 1082.17  4867.3 1083.65    4875 1083.35  4880.1 1080.78
  4887.8 1082.96    4898 1083.33  4918.4 1081.48  4925.1 1078.97  4930.2 1080.09
  4938.8 1079.34    4949 1077.07  4959.3 1070.58  4987.9 1069.84  4988.2 1069.34
  4991.9 1069.84  5021.3 1070.78    5032 1075.87  5053.2 1078.73    5114 1079.89
  5164.6 1080.68  5190.1 1084.04  5212.4 1082.04  5392.7 1091.76  5737.5 1115.38
#Mann= 5 ,-1 , 0
    4409     .05       0  4742.6     .12       0  4987.9     .07       0
  4991.9     .12       0    5114     .05       0
Bank Sta=4987.9,4991.9
XS Rating Curve= 0 ,0
Exp/Cntr=0.3,0.1

Type RM Length L Ch R = 1 ,22076   ,355,355,355
BEGIN DESCRIPTION:
STEELMAN BRANCH 46.0
END DESCRIPTION:
XS GIS Cut Line= 3
      2225643.75      7274418.02        2224979.        7274560.
        2224240.      7275054.82
#Sta/Elev= 30
  4316.2  1112.5  4576.7 1100.52  4784.8 1086.71  4903.9 1080.17  4921.7 1076.43
  4934.6 1078.09  4963.3 1069.73  4963.5 1069.23  4967.3 1069.73    4974 1071.18
  5111.5 1070.79  5126.5 1075.46  5153.6 1071.52  5162.5 1074.59  5189.6 1073.26
  5219.6  1080.6  5312.7  1085.8  5327.7 1083.46  5333.7 1085.52  5369.7 1085.65
  5399.7 1091.63  5486.8 1098.02  5564.8 1102.16  5645.8 1102.47  5702.9 1118.05
    5739 1111.56    5826 1111.31    5847 1113.92  5868.1  1120.9  5885.3 1122.26
#Mann= 5 ,-1 , 0
  4316.2     .05       0  4784.8     .12       0  4963.3    .033       0
  4967.3     .12       0    4974     .05       0
Bank Sta=4963.3,4967.3
XS Rating Curve= 0 ,0
Exp/Cntr=0.3,0.1

Type RM Length L Ch R = 1 ,21721   ,403,403,403
BEGIN DESCRIPTION:
STEELMAN BRANCH 45.0
END DESCRIPTION:
XS GIS Cut Line= 4
      2225759.94      7274343.65        2224829.        7274260.
      2224718.77      7274269.28      2224147.13      7274785.15
#Sta/Elev= 30
  4069.4 1113.26  4291.2 1109.01  4623.4 1090.43  4721.3 1082.13  4823.4 1076.88
  4837.5 1075.43  4843.4  1070.3  4851.5 1069.77  4851.7 1069.27  4855.5 1069.77
  4893.6 1072.03  4913.7 1069.99  4953.9 1071.49  5034.2 1070.41  5054.3 1073.27
    5179 1076.88  5274.5 1083.52  5313.5 1085.67  5327.7 1081.34  5334.4 1082.42
  5341.9 1088.15  5348.6 1087.19  5383.8 1090.77    5448 1093.04  5462.2 1095.58
  5589.3 1102.98  5674.5 1111.07  5759.6 1116.06    5809 1116.03  5884.7 1120.98
#Mann= 5 ,-1 , 0
  4069.4     .05       0  4623.4     .12       0  4851.5     .07       0
  4855.5     .12       0  5274.5     .05       0
Bank Sta=4851.5,4855.5
XS Rating Curve= 0 ,0
Exp/Cntr=0.3,0.1

Type RM Length L Ch R = 1 ,21318   ,168,168,168
BEGIN DESCRIPTION:
STEELMAN BRANCH 44.0
END DESCRIPTION:
XS GIS Cut Line= 4
      2225513.64      7273525.55      2224972.43      7273895.77
      2224907.83      7273899.46      2224123.87      7274724.73
#Sta/Elev= 30
  4313.1 1104.56  4455.9 1099.56  4527.7 1094.28  4608.3 1091.64  4736.6 1079.46
  4744.7 1079.11  4757.9  1078.3  4772.9 1081.93  4815.5 1070.37  4901.5 1071.25
  4990.3 1069.78  4990.5 1069.28  4994.3 1069.78  5103.7 1071.57  5309.1 1070.33
    5316 1071.85  5407.8 1075.99  5542.5 1079.77    5606 1086.57  5634.3 1086.56
    5691 1090.56  5697.8  1092.2  5719.3 1092.49  5917.1 1105.73  6009.3 1110.44
  6030.3 1108.13  6080.1    1113  6115.3 1112.83  6122.5 1114.84  6171.8 1116.39
#Mann= 5 ,-1 , 0
  4313.1     .05       0  4736.6     .12       0  4744.7     .05       0
  4990.3    .033       0  4994.3     .05       0
Bank Sta=4990.3,4994.3
XS Rating Curve= 0 ,0
Exp/Cntr=0.3,0.1

Type RM Length L Ch R = 1 ,21150   ,171,171,171
BEGIN DESCRIPTION:
STEELMAN BRANCH 43.6
END DESCRIPTION:
XS GIS Cut Line= 3
      2225515.07      7273417.04      2224869.25      7273875.36
      2224077.55      7274708.73
#Sta/Elev= 30
  4401.2 1109.21  4854.3 1084.81  4910.7 1081.73  4937.8 1075.09  4965.2 1072.69
  4965.5 1072.19  4969.2 1072.69  5017.7    1078  5302.7 1073.44  5656.2 1078.02
    5805 1088.68  5826.1 1085.07  5833.3 1089.88  5854.4 1087.98  5868.6 1092.81
  5925.2 1095.81  5932.1 1092.25  5939.3 1097.08  5967.6 1097.93  5974.5 1092.15
  5981.8 1098.04  6002.9 1095.82  6010.1 1099.56    6017    1093  6031.2 1095.11
  6038.4 1101.28  6059.5 1096.09  6080.9 1102.74  6257.7 1103.14  6342.6 1110.47
#Mann= 5 ,-1 , 0
  4401.2     .05       0  4854.3     .12       0  4937.8     .05       0
  4965.2    .033       0  4969.2     .05       0
Bank Sta=4965.2,4969.2
XS Rating Curve= 0 ,0
Exp/Cntr=0.3,0.1

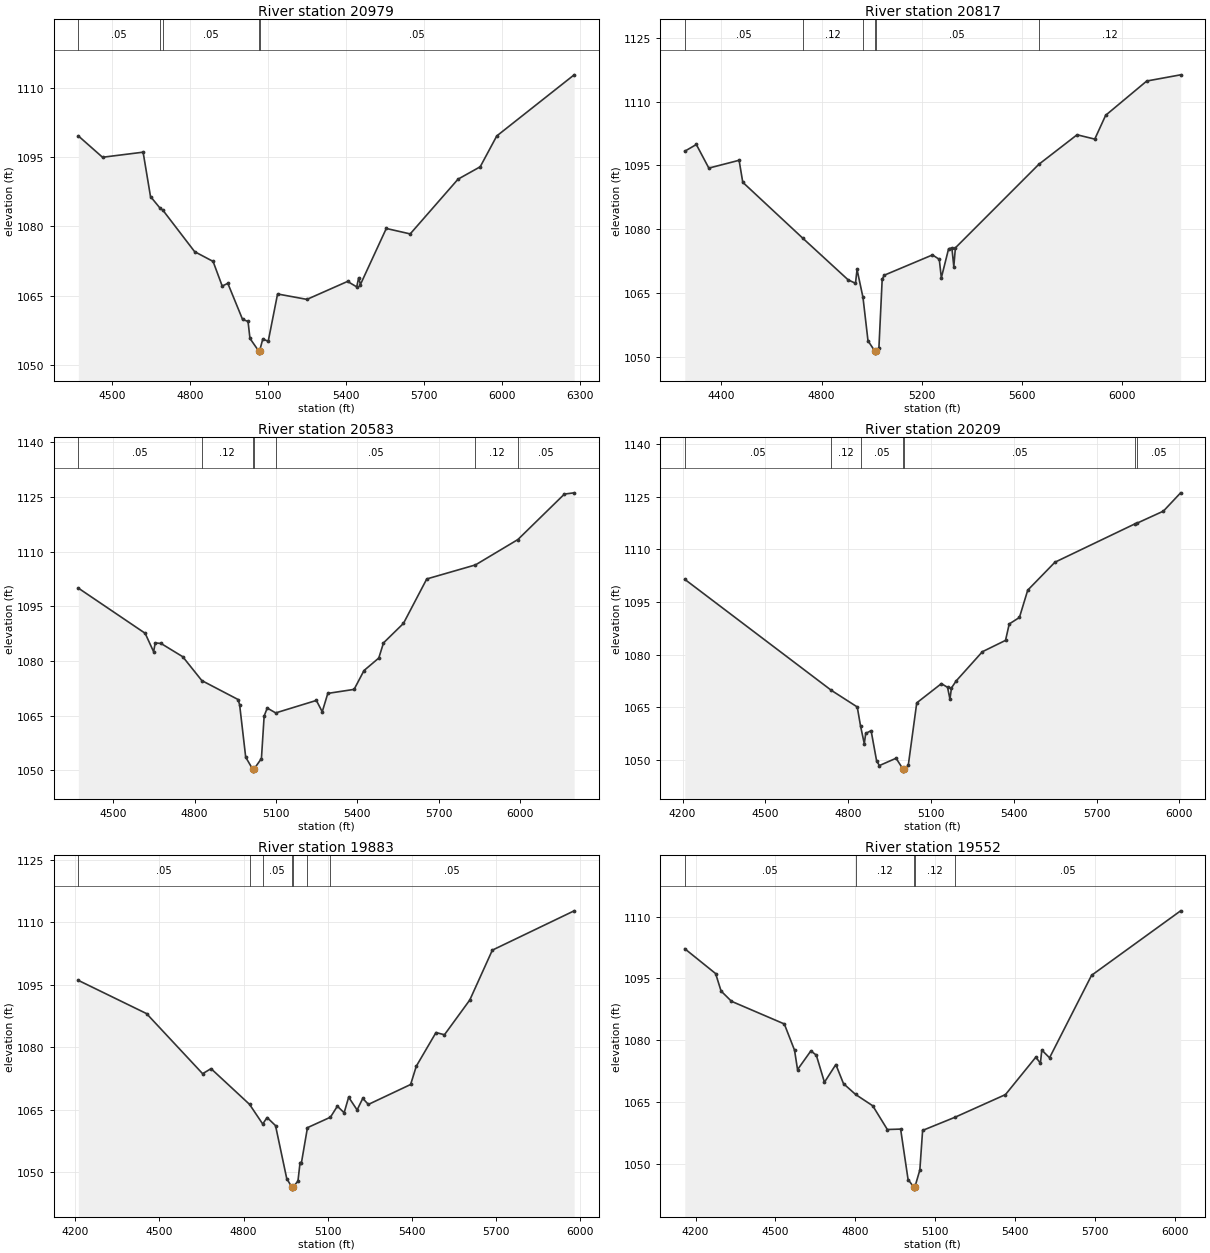
Type RM Length L Ch R = 1 ,20979   ,162,162,162
BEGIN DESCRIPTION:
STEELMAN BRANCH 43.5
END DESCRIPTION:
XS GIS Cut Line= 3
       2225355.6      7273334.96      2224851.88      7273796.09
      2224035.01      7274706.13
#Sta/Elev= 30
  4369.9  1099.6  4462.9 1094.98  4618.9 1096.08  4647.3 1086.48  4682.2 1084.09
  4695.5 1083.48  4816.9 1074.55  4887.8 1072.44  4922.9 1067.11  4944.5 1067.69
  5001.2 1059.88  5022.2 1059.45  5029.6 1055.77  5062.7 1053.09    5063 1052.59
  5066.7 1053.09  5078.9 1055.64  5099.8 1055.16  5135.7 1065.39  5248.6 1064.22
  5404.8 1068.11    5440 1066.92  5447.4 1068.91  5454.2 1067.44  5553.6 1079.57
  5645.5 1078.39  5829.4 1090.24  5914.6 1092.92  5978.2 1099.59  6275.7 1112.82
#Mann= 5 ,-1 , 0
  4369.9     .05       0  4682.2     .12       0  4695.5     .05       0
  5062.7    .033       0  5066.7     .05       0
Bank Sta=5062.7,5066.7
XS Rating Curve= 0 ,0
Exp/Cntr=0.3,0.1

Type RM Length L Ch R = 1 ,20817   ,234,234,234
BEGIN DESCRIPTION:
STEELMAN BRANCH 43.0
END DESCRIPTION:
XS GIS Cut Line= 3
      2225337.97      7273275.28      2224742.19      7273723.74
      2223766.81      7274477.52
#Sta/Elev= 30
  4254.3 1098.36  4300.3 1099.94  4350.2 1094.38    4471 1096.22  4485.6 1091.04
  4724.7 1077.89  4906.2 1068.05  4935.4 1067.25  4941.6  1070.5  4965.3 1063.91
  4985.3  1053.7  5012.4  1051.3  5012.6  1050.8  5016.4  1051.3  5028.9 1052.09
  5041.9 1068.18  5049.7 1069.14  5242.6 1073.93  5269.7 1072.89  5277.9 1068.53
  5306.9 1075.38    5320 1075.59  5327.7 1071.17    5334  1075.6  5666.7 1095.26
  5819.5 1102.23  5890.1 1101.21  5933.6 1106.82  6097.5 1114.89  6232.7 1116.35
#Mann= 6 ,-1 , 0
  4254.3     .05       0  4724.7     .12       0  4965.3     .05       0
  5012.4    .033       0  5016.4     .05       0  5666.7     .12       0
Bank Sta=5012.4,5016.4
XS Rating Curve= 0 ,0
Exp/Cntr=0.3,0.1

Type RM Length L Ch R = 1 ,20583   ,374,374,374
BEGIN DESCRIPTION:
STEELMAN BRANCH 42.0
END DESCRIPTION:
XS GIS Cut Line= 5
      2225318.47      7273251.38      2224832.35      7273537.85
      2224771.58      7273507.47      2224665.25      7273503.13
      2223604.03      7273746.18
#Sta/Elev= 30
  4371.8 1099.97    4618 1087.58  4649.3 1082.51  4655.1 1084.94  4676.6 1084.78
  4756.6 1081.15    4827  1074.6  4960.7  1069.4  4966.3 1067.94  4988.6  1053.6
  5014.6 1050.27  5014.8 1049.77  5018.6 1050.27  5046.6 1053.23  5056.6 1064.89
    5068 1067.07  5099.2 1065.74  5249.1 1069.16  5270.7 1066.05  5291.2 1071.09
  5388.1 1072.19  5424.6 1077.36  5479.1 1080.79  5496.4 1084.94    5570 1090.29
  5655.9 1102.48  5835.4 1106.33  5991.8 1113.29  6163.2 1125.76  6199.1  1126.1
#Mann= 7 ,-1 , 0
  4371.8     .05       0    4827     .12       0  5014.6     .07       0
  5018.6     .12       0  5099.2     .05       0  5835.4     .12       0
  5991.8     .05       0
Bank Sta=5014.6,5018.6
XS Rating Curve= 0 ,0
Exp/Cntr=0.3,0.1

Type RM Length L Ch R = 1 ,20209   ,326,326,326
BEGIN DESCRIPTION:
STEELMAN BRANCH 41.0
END DESCRIPTION:
XS GIS Cut Line= 3
       2225320.6      7273177.61        2224529.        7273260.
      2223633.16      7273706.67
#Sta/Elev= 30
  4207.9 1101.45  4738.9 1069.85  4832.9 1065.11  4844.8 1059.69  4858.4 1054.64
  4863.5 1057.58  4883.1 1058.36  4903.2 1049.69  4913.3 1048.43  4973.6 1050.51
  4999.3 1047.34  4999.5 1046.84  5003.3 1047.34  5017.8 1048.49  5048.5 1066.28
  5137.9 1071.76  5160.2 1070.69  5168.8 1067.35  5174.4 1070.54  5191.2 1072.51
  5286.3 1080.84  5370.2 1084.07  5383.7 1088.75  5420.6  1090.6  5450.7 1098.37
  5549.3 1106.33  5839.4 1117.26  5845.5  1117.4  5942.4 1120.88  6004.8 1126.09
#Mann= 7 ,-1 , 0
  4207.9     .05       0  4738.9     .12       0  4844.8     .05       0
  4999.3    .033       0  5003.3     .05       0  5839.4     .12       0
  5845.5     .05       0
Bank Sta=4999.3,5003.3
XS Rating Curve= 0 ,0
Exp/Cntr=0.3,0.1

Type RM Length L Ch R = 1 ,19883   ,331,331,331
BEGIN DESCRIPTION:
STEELMAN BRANCH 40.0
END DESCRIPTION:
XS GIS Cut Line= 3
      2225372.28      7273016.84        2224579.        7273010.
      2223608.56       7273105.2
#Sta/Elev= 30
  4210.9 1096.06  4454.2 1088.08  4654.2 1073.65  4684.2 1074.86  4821.5 1066.29
  4868.5 1061.57  4884.2 1063.13  4914.2 1061.18  4954.2 1048.46  4972.2 1046.43
  4972.5 1045.93  4976.2 1046.43  4994.2 1047.84  5001.7  1052.3  5006.7  1052.3
  5028.1 1060.69    5110  1063.2  5134.8 1065.85  5158.9 1064.26    5175 1068.01
  5205.2 1064.94  5225.3 1067.72  5245.4 1066.27  5396.1 1071.06  5416.2 1075.44
  5486.5 1083.53  5516.7    1083  5607.1 1091.35  5687.5 1103.32  5979.3 1112.76
#Mann= 7 ,-1 , 0
  4210.9     .05       0  4821.5     .12       0  4868.5     .05       0
  4972.2    .033       0  4976.2     .05       0  5028.1     .12       0
    5110     .05       0
Bank Sta=4972.2,4976.2
XS Rating Curve= 0 ,0
Exp/Cntr=0.3,0.1

Type RM Length L Ch R = 1 ,19552   ,322,322,322
BEGIN DESCRIPTION:
STEELMAN BRANCH 39.0
END DESCRIPTION:
XS GIS Cut Line= 3
      2225372.31      7272607.98      2224549.36      7272782.47
      2223564.79      7273055.24
#Sta/Elev= 30
  4159.6 1102.21  4275.4 1096.19  4295.9 1091.96  4334.9 1089.47  4533.5 1083.97
  4571.9 1077.61  4583.2  1072.9  4633.2 1077.43  4653.7 1076.41  4684.3 1069.83
  4727.1 1074.13  4755.9 1069.49  4801.4 1066.87  4865.8 1064.12  4920.6 1058.37
  4970.5 1058.47  4998.5 1046.23    5020 1044.41  5020.2 1043.91    5024 1044.41
  5042.7 1048.55  5053.1 1058.15  5174.6 1061.34  5364.4 1066.84  5478.5 1075.92
  5495.7 1074.44  5500.9 1077.65    5530 1075.76  5687.9 1095.77  6022.5 1111.41
#Mann= 5 ,-1 , 0
  4159.6     .05       0  4801.4     .12       0    5020     .07       0
    5024     .12       0  5174.6     .05       0
Bank Sta=5020,5024
XS Rating Curve= 0 ,0
Exp/Cntr=0.3,0.1

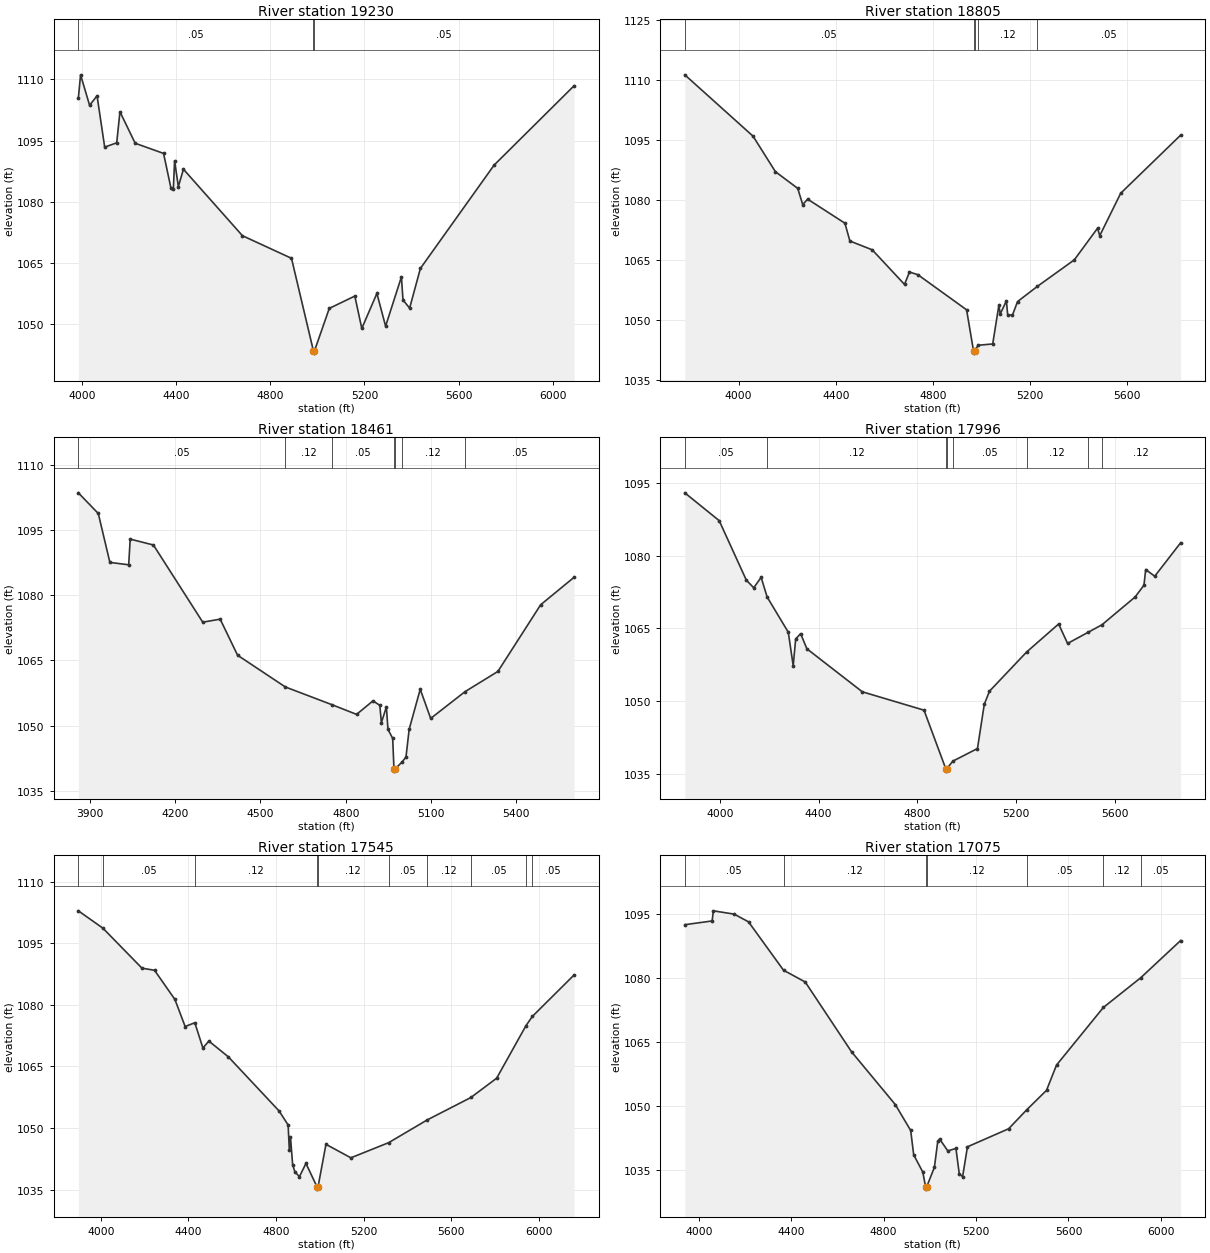
Type RM Length L Ch R = 1 ,19230   ,425,425,425
BEGIN DESCRIPTION:
STEELMAN BRANCH 38.0
END DESCRIPTION:
XS GIS Cut Line= 3
      2225494.67      7272162.68      2224531.13      7272464.76
      2223588.38      7273027.28
#Sta/Elev= 30
  3983.9 1105.31  3993.4 1111.11  4031.8 1103.63  4063.5 1105.98  4095.9 1093.38
    4147 1094.44  4160.8 1102.05  4225.6 1094.33  4346.2 1091.84  4377.6 1083.32
  4387.8 1083.11  4393.1 1090.04    4409 1083.71  4430.7 1087.96  4681.5 1071.66
    4890 1066.12  4983.4 1043.37  4983.7 1042.87  4987.4 1043.37  5050.6 1053.84
  5159.2 1056.86  5188.8 1048.92    5253 1057.51    5290 1049.48  5357.2 1061.55
    5364  1055.9  5392.1  1053.9  5437.9 1063.64  5751.3 1088.98  6091.5 1108.45
#Mann= 3 ,-1 , 0
  3983.9     .05       0  4983.4    .033       0  4987.4     .05       0
Bank Sta=4983.4,4987.4
XS Rating Curve= 0 ,0
Exp/Cntr=0.3,0.1

Type RM Length L Ch R = 1 ,18805   ,344,344,344
BEGIN DESCRIPTION:
STEELMAN BRANCH 37.0
END DESCRIPTION:
XS GIS Cut Line= 3
      2225473.83      7271904.86        2224279.        7272160.
      2223506.65      7272435.55
#Sta/Elev= 30
  3778.2 1111.21  4059.2 1095.91  4151.3 1087.05  4243.3 1082.88  4263.7 1078.84
  4284.2 1080.19  4437.6 1074.19    4458 1069.75  4550.1 1067.55    4683 1058.92
  4703.4 1062.01  4737.9 1061.35  4938.6 1052.59  4967.3 1042.28  4967.5 1041.78
  4971.3 1042.28    4986 1043.74  5046.2 1044.07  5071.7 1053.78    5077 1051.55
  5102.5  1054.8  5107.8 1051.36  5127.4 1051.26  5148.6 1054.65  5230.5 1058.45
  5382.2 1065.05  5477.8 1072.93    5487 1071.09  5573.3 1081.67    5820 1096.16
#Mann= 5 ,-1 , 0
  3778.2     .05       0  4967.3     .07       0  4971.3     .05       0
    4986     .12       0  5230.5     .05       0
Bank Sta=4967.3,4971.3
XS Rating Curve= 0 ,0
Exp/Cntr=0.3,0.1

Type RM Length L Ch R = 1 ,18461   ,465,465,465
BEGIN DESCRIPTION:
STEELMAN BRANCH 36.0
END DESCRIPTION:
XS GIS Cut Line= 4
      2225297.67      7271660.06      2224276.79       7271865.8
        2224179.        7271910.      2223649.18       7272178.3
#Sta/Elev= 30
  3860.3 1103.51  3930.4 1098.76  3971.2 1087.51  4037.3 1086.96  4042.6 1092.87
  4124.2 1091.51  4297.6 1073.76  4358.8 1074.46    4420 1066.16    4588 1058.86
  4753.5 1054.74  4838.2 1052.56    4896 1055.67  4919.9 1054.63  4925.4 1050.66
    4943 1054.28  4948.5 1049.11  4965.1 1047.05  4969.6 1040.01  4969.9 1039.51
  4973.6 1040.01  4996.8 1041.53  5011.8 1042.73    5023 1049.12  5061.9 1058.33
  5098.7 1051.63    5219 1057.77  5334.8 1062.43  5485.2 1077.77  5602.9  1084.1
#Mann= 7 ,-1 , 0
  3860.3     .05       0    4588     .12       0  4753.5     .05       0
  4969.6     .07       0  4973.6     .05       0  4996.8     .12       0
    5219     .05       0
Bank Sta=4969.6,4973.6
XS Rating Curve= 0 ,0
Exp/Cntr=0.3,0.1

Type RM Length L Ch R = 1 ,17996   ,451,451,451
BEGIN DESCRIPTION:
STEELMAN BRANCH 35.0
END DESCRIPTION:
XS GIS Cut Line= 3
      2225128.32      7271501.22        2223979.        7271510.
      2223272.81      7272000.36
#Sta/Elev= 30
    3858  1092.9  3997.3 1087.18  4107.3 1074.94  4137.3 1073.36  4167.3 1075.51
  4191.6 1071.47  4277.3 1064.22  4297.3 1057.32  4307.3 1062.83  4327.3 1063.93
  4352.7 1060.81  4577.3 1051.96  4827.3 1048.18  4915.4 1036.14  4915.6 1035.64
  4919.4 1036.14  4944.1 1037.69  5043.9 1040.29  5071.5 1049.38  5092.6 1052.09
  5243.1 1060.15  5372.7 1065.91  5409.1 1061.91  5491.8 1064.19  5548.3 1065.75
  5682.7 1071.47  5718.5 1073.89  5725.6 1077.12  5762.2 1075.74  5867.1 1082.62
#Mann= 8 ,-1 , 0
    3858     .05       0  4191.6     .12       0  4915.4    .033       0
  4919.4     .12       0  4944.1     .05       0  5243.1     .12       0
  5491.8     .05       0  5548.3     .12       0
Bank Sta=4915.4,4919.4
XS Rating Curve= 0 ,0
Exp/Cntr=0.3,0.1

Type RM Length L Ch R = 1 ,17545   ,470,470,470
BEGIN DESCRIPTION:
STEELMAN BRANCH 34.0
END DESCRIPTION:
XS GIS Cut Line= 3
      2224995.54      7270831.95        2223929.        7271110.
      2223063.62       7271883.7
#Sta/Elev= 30
  3897.4 1102.88  4009.5 1098.66  4187.7 1088.93  4245.2 1088.41  4338.2 1081.31
  4384.9 1074.72  4429.1 1075.65  4465.9  1069.5  4493.2 1071.18  4582.2 1067.34
  4813.6 1054.18  4854.9 1050.77  4860.5 1044.61  4865.6  1047.9  4875.6 1041.06
  4885.9 1039.35  4906.6 1038.19  4936.3 1041.41  4987.2 1035.65  4987.5 1035.15
  4991.3 1035.65  5027.6 1046.06  5141.3 1042.77  5313.9 1046.46  5489.3 1051.98
  5689.1 1057.45  5806.7 1062.15  5940.4 1074.92  5969.6 1077.18  6160.4 1087.29
#Mann= 10 ,-1 , 0
  3897.4     .12       0  4009.5     .05       0  4429.1     .12       0
  4987.2     .07       0  4991.3     .12       0  5313.9     .05       0
  5489.3     .12       0  5689.1     .05       0  5940.4     .12       0
  5969.6     .05       0
Bank Sta=4987.2,4991.3
XS Rating Curve= 0 ,0
Exp/Cntr=0.3,0.1

Type RM Length L Ch R = 1 ,17075   ,459,459,459
BEGIN DESCRIPTION:
STEELMAN BRANCH 33.0
END DESCRIPTION:
XS GIS Cut Line= 3
      2224587.24      7270391.62        2223629.        7270860.
      2222776.82      7271522.03
#Sta/Elev= 30
  3939.6 1092.58  4057.8 1093.46  4063.4 1095.84  4153.5 1095.06  4215.4 1093.25
  4366.8 1081.88  4460.8 1079.11  4661.1 1062.71  4850.4 1050.31  4917.1 1044.21
  4930.2 1038.48  4969.6 1034.42  4981.8 1030.92  4982.1 1030.42    4986 1030.92
  5019.8 1035.55  5034.2 1041.62  5042.4  1042.2  5077.7 1039.41    5113 1039.98
  5127.5 1033.96  5141.9 1033.37  5162.8 1040.37    5341 1044.61    5420 1049.11
  5504.9 1053.64  5548.3 1059.59  5750.9 1073.12  5912.9 1080.12  6085.3 1088.86
#Mann= 7 ,-1 , 0
  3939.6     .05       0  4366.8     .12       0  4981.8     .07       0
    4986     .12       0    5420     .05       0  5750.9     .12       0
  5912.9     .05       0
Bank Sta=4981.8,4986
XS Rating Curve= 0 ,0
Exp/Cntr=0.3,0.1

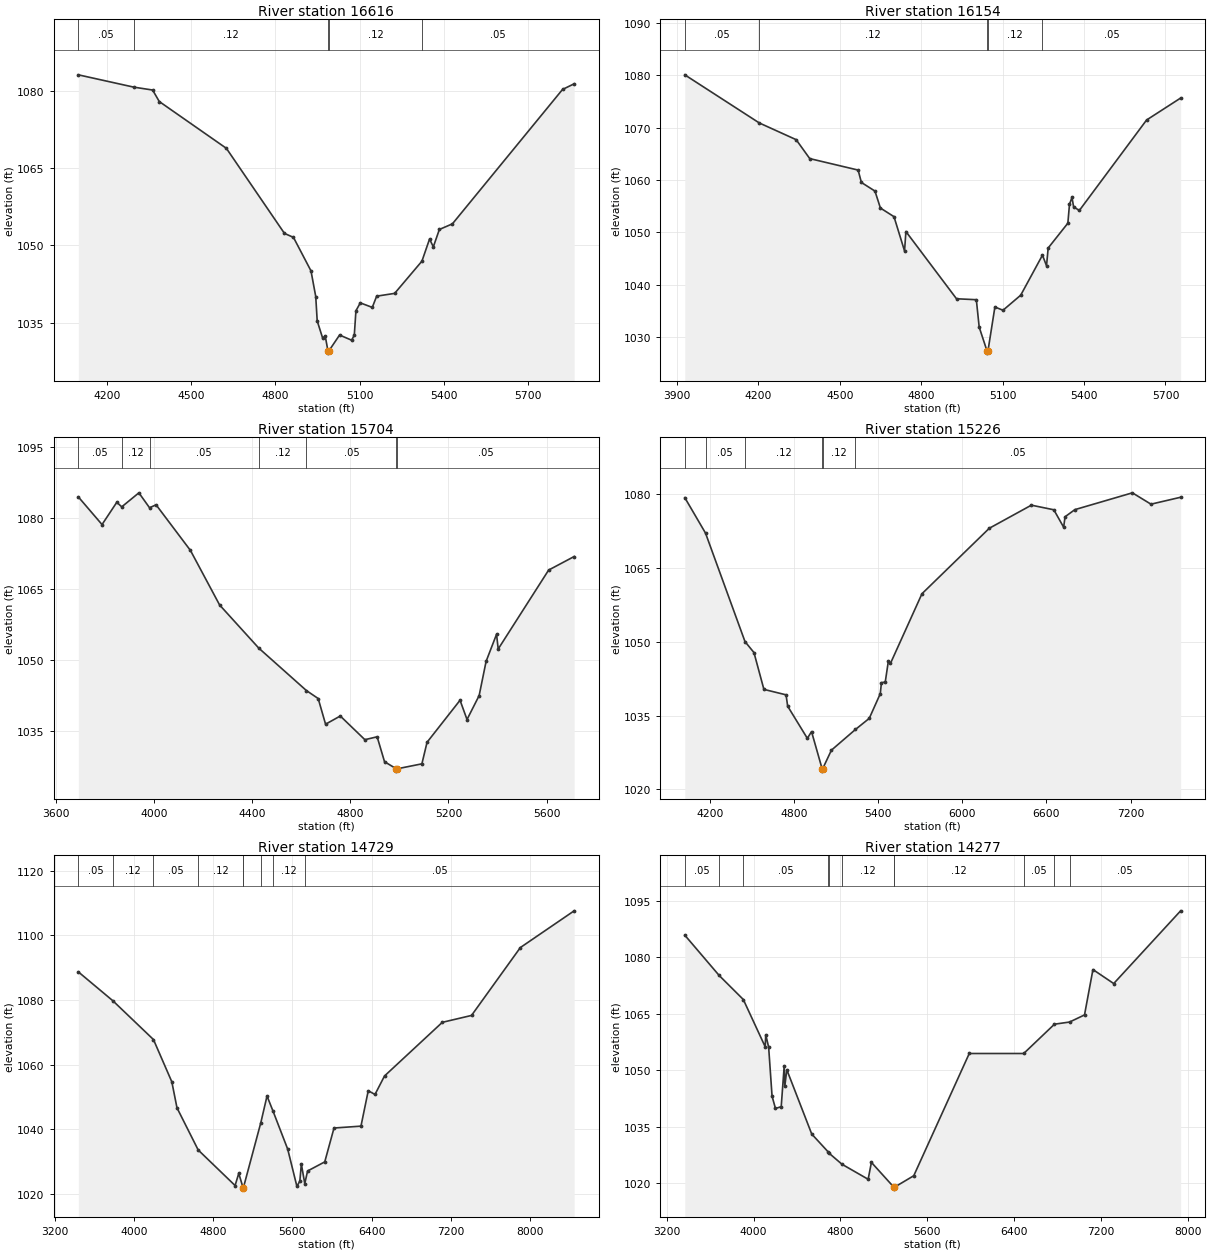
Type RM Length L Ch R = 1 ,16616   ,462,462,462
BEGIN DESCRIPTION:
STEELMAN BRANCH 32.0
END DESCRIPTION:
XS GIS Cut Line= 3
      2224296.46       7270261.4        2223429.        7270510.
       2222686.9      7270955.44
#Sta/Elev= 30
  4097.4 1083.07  4295.2 1080.68  4362.3 1080.12    4386 1077.89  4625.3 1068.81
  4832.3 1052.31  4864.5 1051.53    4927 1045.03  4943.9 1040.06  4949.1 1035.33
  4968.6 1031.98  4977.7 1032.41  4987.2 1029.58  4987.6 1029.08  4991.5 1029.58
  5028.9 1032.59  5071.7 1031.59  5081.4 1032.57  5087.2  1037.3  5102.8 1038.83
  5145.5 1037.95  5161.1 1040.13  5225.2 1040.67  5322.5 1046.92  5349.7 1051.21
  5363.2  1049.7  5384.7 1053.07  5431.2 1054.16  5823.8 1080.23  5865.3 1081.33
#Mann= 5 ,-1 , 0
  4097.4     .05       0  4295.2     .12       0  4987.2     .07       0
  4991.5     .12       0  5322.5     .05       0
Bank Sta=4987.2,4991.5
XS Rating Curve= 0 ,0
Exp/Cntr=0.3,0.1

Type RM Length L Ch R = 1 ,16154   ,450,450,450
BEGIN DESCRIPTION:
STEELMAN BRANCH 31.0
END DESCRIPTION:
XS GIS Cut Line= 3
      2224248.68      7270222.34        2223179.        7270160.
      2222543.47      7270569.25
#Sta/Elev= 30
  3928.5 1080.05    4203 1070.87  4338.9 1067.68    4389 1064.07  4567.3 1061.88
  4579.3 1059.52  4629.4 1057.87  4649.4 1054.64  4699.5 1052.99  4738.4 1046.45
  4743.4 1050.16  4929.9 1037.33    5003 1037.15  5013.5 1031.92  5041.8 1027.46
  5042.1 1026.96  5046.1 1027.46  5071.4 1035.76  5101.3 1035.14  5166.5 1038.01
  5246.7 1045.65  5261.7 1043.62  5267.7 1047.01  5340.3 1051.75  5346.3 1055.36
  5355.5 1056.65  5361.5 1054.87  5382.6 1054.17  5630.4 1071.43  5755.9 1075.62
#Mann= 5 ,-1 , 0
  3928.5     .05       0    4203     .12       0  5041.8     .07       0
  5046.1     .12       0  5246.7     .05       0
Bank Sta=5041.8,5046.1
XS Rating Curve= 0 ,0
Exp/Cntr=0.3,0.1

Type RM Length L Ch R = 1 ,15704   ,478,478,478
BEGIN DESCRIPTION:
STEELMAN BRANCH 30.0
END DESCRIPTION:
XS GIS Cut Line= 3
      2224335.51      7269697.17        2223029.        7269760.
      2222552.81      7270290.51
#Sta/Elev= 30
  3691.4 1084.37    3788 1078.53  3848.1 1083.23  3868.4 1082.27  3938.2 1085.23
  3981.6 1082.08  4008.3  1082.7  4148.4 1073.06  4267.2 1061.55    4427 1052.43
  4620.9 1043.48    4669 1041.79  4699.1 1036.37  4759.1  1038.1  4859.3  1033.1
  4909.3 1033.71  4939.4 1028.45  4987.2 1026.96  4987.6 1026.46  4991.6 1026.96
  5091.7    1028  5112.7 1032.55  5247.2 1041.43  5275.6 1037.36    5325 1042.41
  5353.4 1049.64    5396 1055.36  5402.7 1052.25  5608.3 1068.92  5712.3 1071.78
#Mann= 7 ,-1 , 0
  3691.4     .05       0  3868.4     .12       0  3981.6     .05       0
    4427     .12       0  4620.9     .05       0  4987.2    .033       0
  4991.6     .05       0
Bank Sta=4987.2,4991.6
XS Rating Curve= 0 ,0
Exp/Cntr=0.3,0.1

Type RM Length L Ch R = 1 ,15226   ,497,497,497
BEGIN DESCRIPTION:
STEELMAN BRANCH 29.0
END DESCRIPTION:
XS GIS Cut Line= 4
      2223901.48       7269251.2        2222929.        7269310.
      2222525.63       7269832.8      2222456.19      7271733.85
#Sta/Elev= 30
  4020.6 1079.35  4168.3 1072.14  4449.9 1050.07    4514 1047.83  4584.9 1040.34
  4742.9 1039.23  4754.4 1036.92  4894.7 1030.38  4924.7 1031.75  4999.9 1024.21
  5000.3 1023.71  5004.4 1024.21  5066.4 1027.97  5238.1 1032.19  5336.3 1034.44
  5415.1 1039.47  5423.3  1041.7  5450.5 1041.84  5473.1 1046.17  5487.4 1045.61
  5712.4  1059.8  6192.7 1073.12  6492.9 1077.82    6653 1076.88  6723.1 1073.33
  6733.1 1075.46  6803.1 1076.91  7213.4 1080.33    7346 1078.02  7557.5 1079.43
#Mann= 6 ,-1 , 0
  4020.6     .12       0  4168.3     .05       0  4449.9     .12       0
  4999.9     .07       0  5004.4     .12       0  5238.1     .05       0
Bank Sta=4999.9,5004.4
XS Rating Curve= 0 ,0
Exp/Cntr=0.3,0.1

Type RM Length L Ch R = 1 ,14729   ,452,452,452
BEGIN DESCRIPTION:
STEELMAN BRANCH 28.0
END DESCRIPTION:
XS GIS Cut Line= 5
      2223970.91      7268252.96        2222579.        7268960.
      2222247.86      7269120.99      2221718.34      7269481.24
      2220667.98      7271681.78
#Sta/Elev= 30
  3438.8 1088.71  3788.4 1079.75  4197.7 1067.77  4383.1  1054.7  4435.3 1046.64
  4649.5  1033.6  5022.2  1022.6  5059.2 1026.37    5102 1021.99  5102.4 1021.49
  5106.6 1021.99  5282.5  1042.1  5344.7  1050.3  5405.3 1045.63  5553.7 1033.85
  5646.5 1022.35  5676.4 1023.98  5691.3 1029.27  5726.1 1023.19  5754.3  1027.1
  5927.8 1029.92  6021.3  1040.4  6293.6 1040.98  6367.2 1051.94  6435.2 1050.78
  6531.5  1056.5  7115.3  1073.1  7410.3 1075.23  7903.4 1096.23    8447  1107.6
#Mann= 9 ,-1 , 0
  3438.8     .05       0  3788.4     .12       0  4197.7     .05       0
  4649.5     .12       0    5102     .07       0  5106.6     .12       0
  5282.5     .05       0  5405.3     .12       0  5726.1     .05       0
Bank Sta=5102,5106.6
XS Rating Curve= 0 ,0
Exp/Cntr=0.3,0.1

Type RM Length L Ch R = 1 ,14277   ,562,562,562
BEGIN DESCRIPTION:
STEELMAN BRANCH 27.0
END DESCRIPTION:
XS GIS Cut Line= 4
      2223888.53      7268140.08        2222329.        7268610.
      2221345.08       7268626.2      2219899.78      7269941.29
#Sta/Elev= 30
  3366.9 1085.86  3683.4 1075.15  3905.8 1068.76  4107.3  1056.2  4112.5 1059.41
  4139.3 1056.07  4170.6 1043.07  4201.9  1039.8  4254.9 1040.27  4282.7 1051.18
  4287.9 1045.64  4306.4  1050.1  4536.1    1033  4686.3 1028.29  4697.1 1027.88
  4814.2 1024.98  5055.7 1020.98  5085.7 1025.47  5292.8 1018.86  5293.2 1018.36
  5297.4 1018.86  5475.8 1021.92    5987 1054.41  6488.6 1054.41  6771.8  1062.2
  6910.9 1062.77  7048.5 1064.66  7126.2 1076.72  7317.5    1073  7933.8 1092.33
#Mann= 11 ,-1 , 0
  3366.9     .05       0  3683.4     .12       0  3905.8     .05       0
  4686.3     .12       0  4697.1     .05       0  4814.2     .12       0
  5292.8     .07       0  5297.4     .12       0  6488.6     .05       0
  6771.8     .12       0  6910.9     .05       0
Bank Sta=5292.8,5297.4
XS Rating Curve= 0 ,0
Exp/Cntr=0.3,0.1

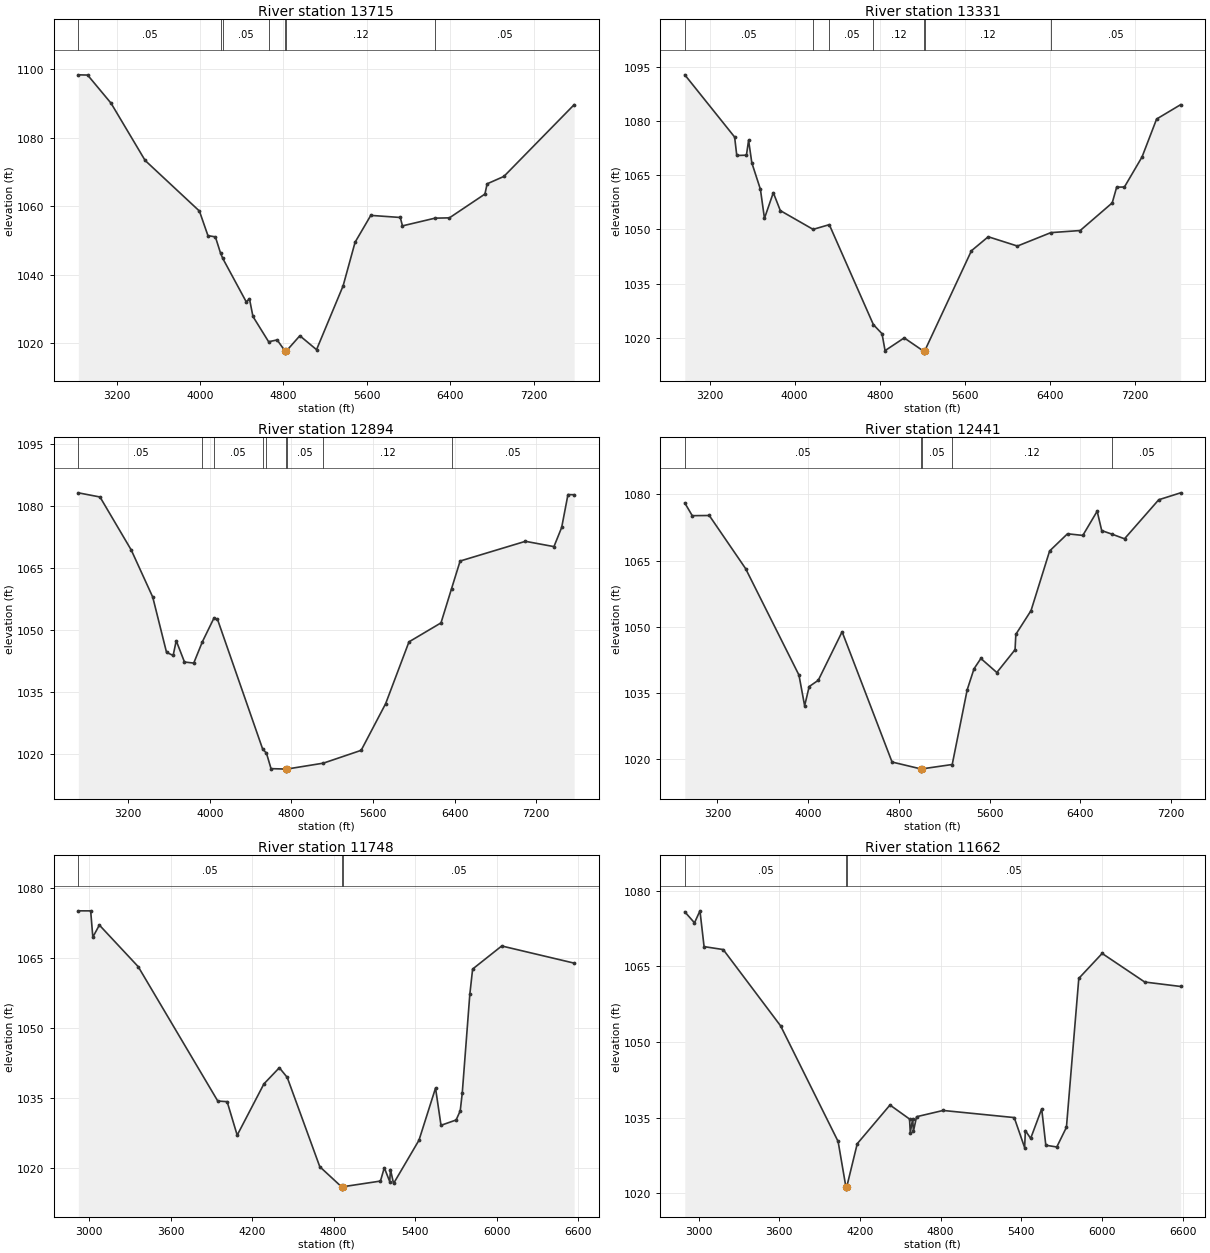
Type RM Length L Ch R = 1 ,13715   ,384,384,384
BEGIN DESCRIPTION:
STEELMAN BRANCH 26.0
END DESCRIPTION:
XS GIS Cut Line= 4
      2224166.29      7267740.78      2222039.52      7268174.81
      2221562.09       7268357.1      2219808.61      7269459.54
#Sta/Elev= 30
  2833.8 1098.37  2922.9  1098.3  3147.4 1090.09    3474 1073.39  3994.5 1058.62
  4076.2 1051.45  4147.6 1051.09  4196.7 1046.37  4218.8 1044.78  4443.6 1032.12
  4474.2 1033.03  4507.6 1027.87  4657.9 1020.49  4739.6 1021.02  4818.1 1017.67
  4819.1 1017.17  4824.4 1017.67  4957.2 1022.24  5117.2 1018.18  5371.8 1036.79
  5486.8 1049.53  5637.2 1057.36  5919.8 1056.75    5941  1054.3  6252.9 1056.55
  6390.9 1056.64  6731.3 1063.58  6752.5 1066.57  6912.9 1068.72  7586.7 1089.66
#Mann= 7 ,-1 , 0
  2833.8     .05       0  4196.7     .12       0  4218.8     .05       0
  4657.9     .12       0  4818.1     .07       0  4824.4     .12       0
  6252.9     .05       0
Bank Sta=4818.1,4824.4
XS Rating Curve= 0 ,0
Exp/Cntr=0.3,0.1

Type RM Length L Ch R = 1 ,13331   ,437,437,437
BEGIN DESCRIPTION:
STEELMAN BRANCH 25.0
END DESCRIPTION:
XS GIS Cut Line= 3
      2223992.69      7267532.45        2221979.        7267810.
      2219825.96      7269311.98
#Sta/Elev= 30
  2967.7 1092.74  3435.8 1075.54    3456 1070.44  3546.8 1070.53    3567 1074.66
  3597.3 1068.42    3678  1061.1  3716.1 1053.07  3799.2 1060.17    3865 1055.21
    4173 1050.02  4325.1 1051.32  4739.3 1023.69  4820.6 1021.17    4849  1016.5
  5028.8 1020.02  5213.2 1016.31  5214.2 1015.81  5219.6 1016.31  5660.4 1044.11
  5818.3 1047.98  6092.3 1045.41  6406.6 1049.12    6682  1049.7    6983 1057.34
  7024.8 1061.69  7097.6 1061.73    7263 1070.03    7400 1080.52  7625.6 1084.49
#Mann= 7 ,-1 , 0
  2967.7     .05       0    4173    .075       0  4325.1     .05       0
  4739.3     .12       0  5213.2     .07       0  5219.6     .12       0
  6406.6     .05       0
Bank Sta=5213.2,5219.6
XS Rating Curve= 0 ,0
Exp/Cntr=0.3,0.1

Type RM Length L Ch R = 1 ,12894   ,453,453,453
BEGIN DESCRIPTION:
STEELMAN BRANCH 24.0
END DESCRIPTION:
XS GIS Cut Line= 3
      2223949.29      7267280.71        2221679.        7267610.
       2219323.3      7268634.54
#Sta/Elev= 30
  2709.9 1083.24  2922.4 1082.23    3229  1069.4  3439.6 1058.02    3575 1044.65
  3639.8  1043.9  3670.1 1047.46    3751 1042.31  3841.9 1042.06  3926.8 1047.23
  4038.2 1052.85  4074.3 1052.67  4517.1  1021.3  4555.2 1020.25  4599.8 1016.52
  4747.8 1016.42  4748.9 1015.92  4754.8 1016.42    5113 1017.85  5483.8 1020.95
  5723.8 1032.23  5952.7 1047.19  6266.8 1051.78  6370.1 1060.04  6454.3 1066.74
  7094.9 1071.51  7374.6 1070.23  7450.3 1074.86  7512.1 1082.82  7572.8 1082.78
#Mann= 9 ,-1 , 0
  2709.9     .05       0  3926.8    .075       0  4038.2     .05       0
  4517.1     .12       0  4555.2     .05       0  4747.8    .033       0
  4754.8     .05       0    5113     .12       0  6370.1     .05       0
Bank Sta=4747.8,4754.8
XS Rating Curve= 0 ,0
Exp/Cntr=0.3,0.1

Type RM Length L Ch R = 1 ,12441   ,693,693,693
BEGIN DESCRIPTION:
STEELMAN BRANCH 23.0
END DESCRIPTION:
XS GIS Cut Line= 3
      2223914.57      7267115.78        2221829.        7267210.
      2219556.92       7266976.9
#Sta/Elev= 30
  2912.4 1078.05    2978 1075.17  3128.2 1075.21  3448.5 1063.19    3919 1039.09
    3969 1032.14  4009.1 1036.49  4089.2 1037.91  4299.4 1048.89  4739.8 1019.41
  4994.1 1017.85  4995.2 1017.35  5001.1 1017.85  5270.3 1018.85  5402.2 1035.75
  5462.5 1040.52  5522.8 1042.85  5663.6 1039.67  5824.4 1044.84  5831.2 1048.31
  5965.1 1053.68    6129 1067.18  6286.8 1071.07  6421.7  1070.7  6548.2 1076.18
  6588.4 1071.79  6679.6 1070.98  6789.4 1069.94    7091 1078.77  7284.1 1080.34
#Mann= 5 ,-1 , 0
  2912.4     .05       0  4994.1    .033       0  5001.1     .05       0
  5270.3     .12       0  6679.6     .05       0
Bank Sta=4994.1,5001.1
XS Rating Curve= 0 ,0
Exp/Cntr=0.3,0.1

Type RM Length L Ch R = 1 ,11748   ,86,86,86
BEGIN DESCRIPTION:
STEELMAN BRANCH 22.0
END DESCRIPTION:
XS GIS Cut Line= 5
      2223894.55      7267068.39      2222441.43      7266849.64
      2221873.72      7266604.85      2221446.64      7266401.72
      2220368.52      7266250.68
#Sta/Elev= 30
  2921.5 1075.17  3012.3 1075.16  3028.2 1069.52  3076.2 1072.12    3362  1063.2
  3947.7 1034.37  4016.7 1034.23  4090.7 1027.04  4287.5 1038.05  4400.9 1041.51
    4459 1039.44  4698.6 1020.28  4858.8 1015.97  4859.9 1015.47  4865.9 1015.97
  5145.2  1017.2  5173.4 1020.06  5213.3  1017.1  5218.9 1019.67  5241.6 1016.68
  5428.8 1025.97  5550.5 1037.15  5590.8 1029.16  5701.9  1030.3  5732.2 1032.25
  5747.1 1036.04  5802.9 1057.26  5823.5 1062.68  6037.7 1067.63  6570.8 1063.95
#Mann= 3 ,-1 , 0
  2921.5     .05       0  4858.8    .033       0  4865.9     .05       0
Bank Sta=4858.8,4865.9
XS Rating Curve= 0 ,0
Exp/Cntr=0.3,0.1

Type RM Length L Ch R = 1 ,11662   ,99,99,99
BEGIN DESCRIPTION:
STEELMAN BRANCH 21.5
END DESCRIPTION:
XS GIS Cut Line= 5
       2223929.9      7267059.27      2222488.91       7266789.3
      2221968.07      7266560.13      2221600.02      7266393.46
      2220377.75      7266136.51
#Sta/Elev= 30
    2897 1075.82  2969.1 1073.64  3009.8 1076.02  3040.4 1068.92  3182.8 1068.34
  3610.1 1053.19  4037.4 1030.28  4094.9 1021.33    4096 1020.83    4102 1021.33
  4179.8 1029.84  4423.2 1037.51  4568.7 1034.73  4574.2 1032.02  4592.1 1034.81
  4597.5 1032.28  4620.9 1035.19  4818.5 1036.43  5347.4 1035.02  5424.9 1029.06
  5430.1 1032.44  5469.7 1030.89  5551.7 1036.75  5582.4 1029.53    5664 1029.19
  5735.7 1033.09  5827.7 1062.62  6001.4 1067.57  6318.1  1061.9  6585.1 1061.02
#Mann= 3 ,-1 , 0
    2897     .05       0  4094.9    .033       0    4102     .05       0
Bank Sta=4094.9,4102
XS Rating Curve= 0 ,0
Exp/Cntr=0.3,0.1