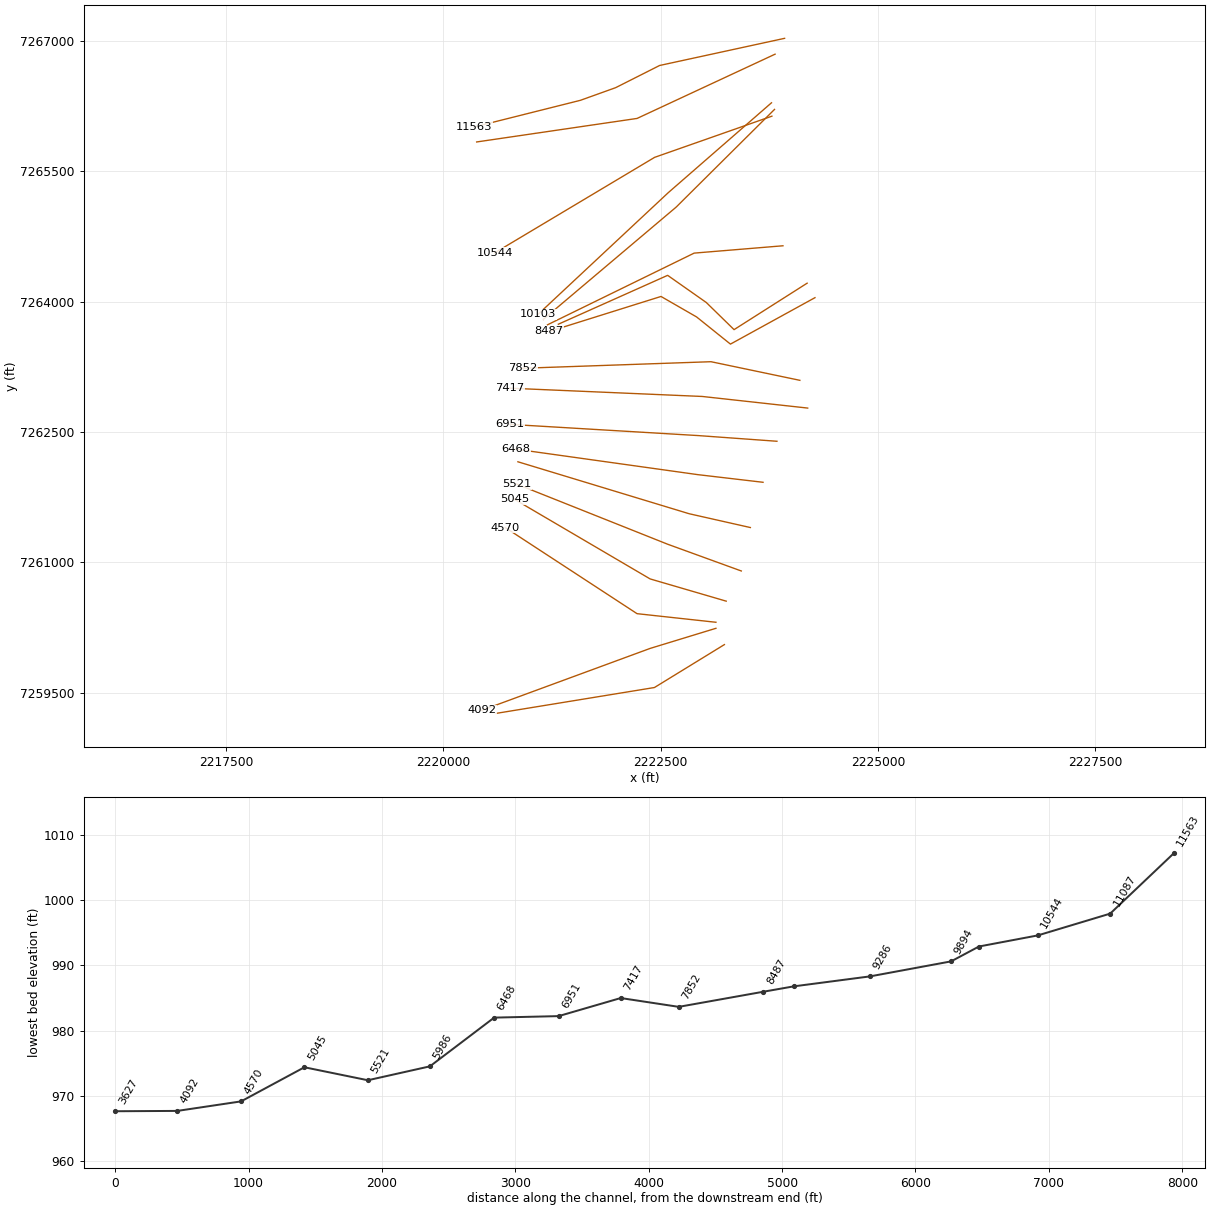
HEC-RAS study STEELMAN BRANCH.prj: STEELMAN BRANCH Base Level Engineering

--- STEELMAN BRANCH.g01 (geometry) --- (continued)

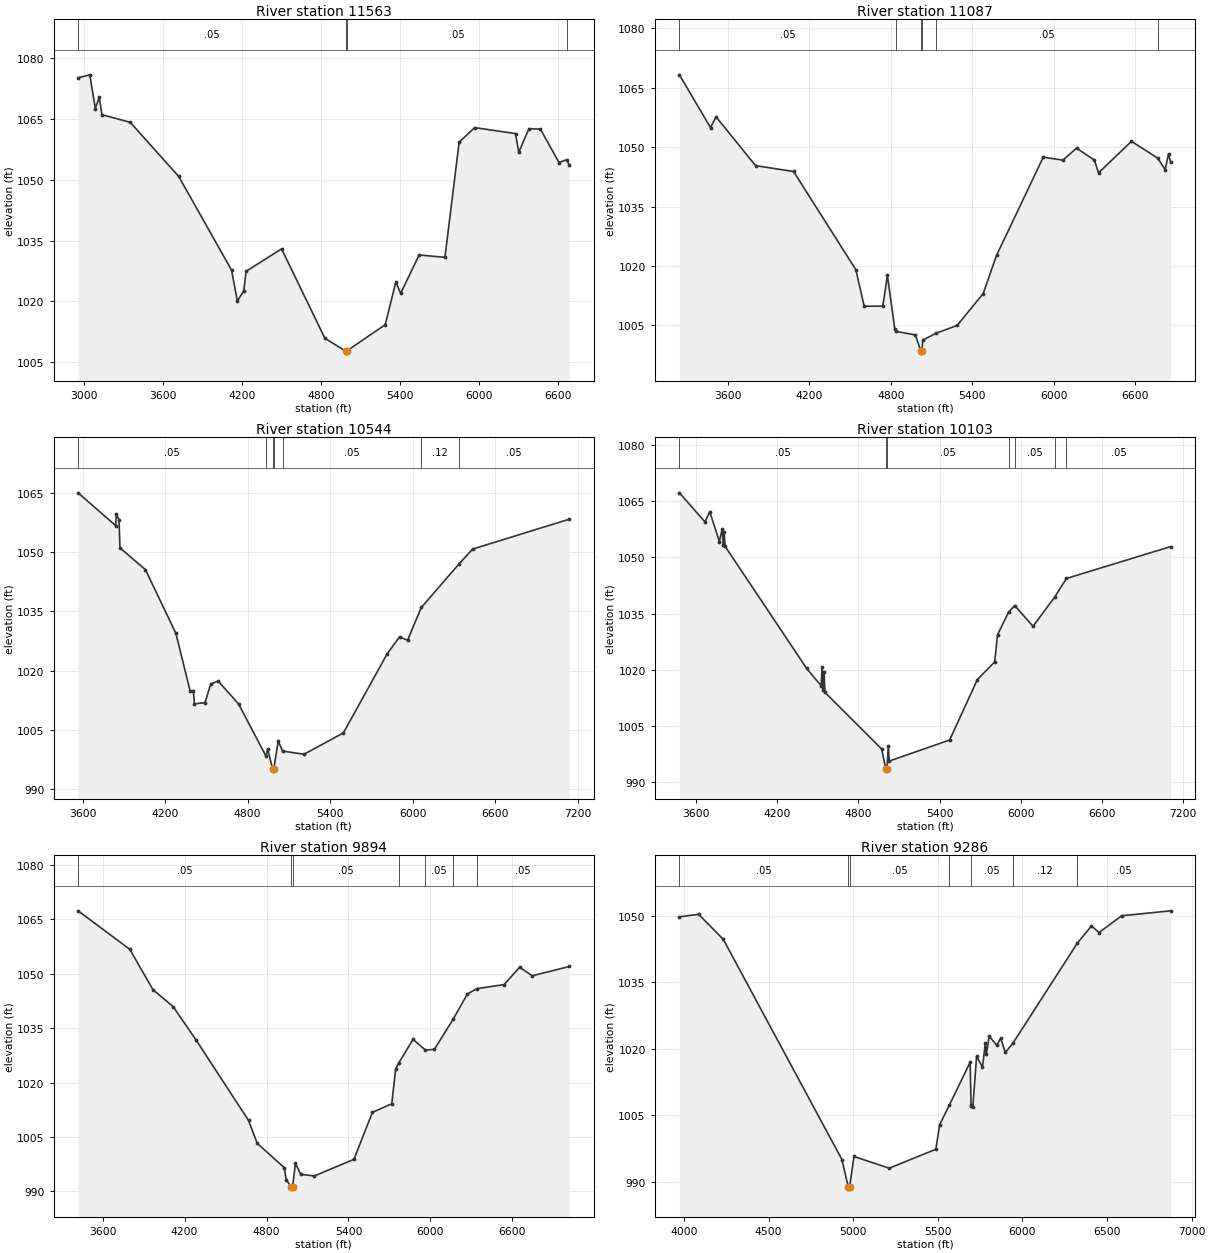
Type RM Length L Ch R = 1 ,11563   ,476,476,476
BEGIN DESCRIPTION:
STEELMAN BRANCH 21.0
END DESCRIPTION:
XS GIS Cut Line= 5
      2223925.83      7267031.94      2222488.31      7266719.43
       2221983.1      7266464.22      2221576.85      7266318.39
      2220353.46      7266011.24
#Sta/Elev= 30
  2952.8 1075.22  3041.7 1075.95  3083.7 1067.61  3113.3 1070.47  3133.8 1066.11
  3348.7 1064.21  3717.1 1050.83  4118.3 1027.69  4162.3 1020.05  4211.4  1022.6
  4228.8 1027.41  4498.1 1032.94  4826.4 1010.88    4985 1007.68  4986.1 1007.18
  4992.1 1007.68    5285  1014.2  5366.1 1024.75  5402.6 1021.96    5543 1031.44
  5738.9 1030.85  5846.7 1059.32    5965 1062.91  6275.1 1061.42  6299.4 1056.81
  6376.5 1062.65    6464 1062.54    6605 1054.27  6663.7 1054.99  6682.9 1053.64
#Mann= 4 ,-1 , 0
  2952.8     .05       0    4985    .033       0  4992.1     .05       0
  6663.7     .12       0
Bank Sta=4985,4992.1
XS Rating Curve= 0 ,0
Exp/Cntr=0.3,0.1

Type RM Length L Ch R = 1 ,11087   ,543,543,543
BEGIN DESCRIPTION:
STEELMAN BRANCH 20.0
END DESCRIPTION:
XS GIS Cut Line= 3
      2223816.45      7266849.65        2222229.        7266110.
      2220384.18      7265839.23
#Sta/Elev= 30
  3244.2 1068.29  3473.4 1054.93  3513.7 1057.69  3804.7 1045.34  4084.6 1043.86
  4543.2 1019.02  4604.4  1009.8  4741.6 1009.84  4775.5 1017.59    4830 1003.99
  4841.8 1003.42  4981.3 1002.56  5021.7  998.45  5022.8  997.95    5029  998.45
  5035.9 1001.24    5134 1002.99  5288.6 1004.94  5480.7 1013.01  5578.8 1022.66
  5922.7 1047.47  6067.4 1046.73  6167.9 1049.76  6299.3 1046.74  6329.7 1043.51
  6572.2 1051.48  6765.7 1047.23  6820.1 1044.33  6845.1 1048.31  6860.1 1046.27
#Mann= 6 ,-1 , 0
  3244.2     .05       0  4841.8     .12       0  5021.7     .07       0
    5029     .12       0    5134     .05       0  6765.7     .12       0
Bank Sta=5021.7,5029
XS Rating Curve= 0 ,0
Exp/Cntr=0.3,0.1

Type RM Length L Ch R = 1 ,10544   ,441,441,441
BEGIN DESCRIPTION:
STEELMAN BRANCH 19.0
END DESCRIPTION:
XS GIS Cut Line= 3
      2223779.99       7266136.1      2222431.02      7265662.14
      2220592.45      7264563.16
#Sta/Elev= 30
  3566.8 1064.96  3839.9 1056.67  3845.2 1059.52  3864.6 1058.09  3870.9 1051.07
  4056.8 1045.52    4278 1029.44  4381.7 1014.84  4405.2 1014.97  4412.7 1011.61
    4490 1011.93  4531.3 1016.64  4585.4 1017.38  4733.8 1011.59    4933  998.41
  4945.8 1000.18  4981.4  995.11  4982.6  994.61  4989.4  995.11  5022.3 1002.19
  5054.4  999.68    5210  998.88    5496 1004.27    5815 1024.29  5904.5 1028.55
  5962.8  1027.7  6062.7 1035.98  6334.8  1046.9  6435.6 1050.74  7138.6 1058.29
#Mann= 7 ,-1 , 0
  3566.8     .05       0    4933     .12       0  4981.4     .07       0
  4989.4     .12       0  5054.4     .05       0  6062.7     .12       0
  6334.8     .05       0
Bank Sta=4981.4,4989.4
XS Rating Curve= 0 ,0
Exp/Cntr=0.3,0.1

Type RM Length L Ch R = 1 ,10103   ,209,209,209
BEGIN DESCRIPTION:
STEELMAN BRANCH 18.0
END DESCRIPTION:
XS GIS Cut Line= 3
      2223775.17      7266290.15       2222587.7      7265255.46
      2221088.97      7263853.87
#Sta/Elev= 30
    3479 1067.27  3667.9 1059.49    3703 1062.25  3774.2 1054.25  3795.1 1057.68
  3802.7 1053.29  3809.3 1056.74  3816.9 1052.94  4418.8 1020.34  4525.2 1015.76
  4532.8 1020.66  4539.4 1014.64    4547 1019.52  4553.6 1013.96  4972.3  998.83
  5003.4  993.41  5004.6  992.91  5011.6  993.41  5021.7  999.67  5028.3   995.6
  5474.5 1001.23  5679.7 1017.39  5806.7 1022.07  5828.2 1029.34  5910.7 1035.45
  5955.4 1037.14    6090 1031.61  6249.2 1039.36  6336.8 1044.38    7106  1052.9
#Mann= 7 ,-1 , 0
    3479     .05       0  5003.4    .033       0  5011.6     .05       0
  5910.7     .12       0  5955.4     .05       0  6249.2     .12       0
  6336.8     .05       0
Bank Sta=5003.4,5011.6
XS Rating Curve= 0 ,0
Exp/Cntr=0.3,0.1

Type RM Length L Ch R = 1 ,9894    ,608,608,608
BEGIN DESCRIPTION:
STEELMAN BRANCH 17.0
END DESCRIPTION:
XS GIS Cut Line= 3
      2223809.89      7266213.76      2222677.98      7265088.79
      2221150.19      7263797.12
#Sta/Elev= 30
  3420.4 1067.29  3798.5  1056.7  3968.2 1045.59  4116.6 1040.89  4286.4 1031.59
  4668.2 1009.57  4731.9 1003.25  4929.9  996.56    4944  993.28  4982.3  991.13
  4983.5  990.63  4990.5  991.13    5012  997.74  5050.4  994.73  5149.2  994.24
  5440.4  998.84  5575.6 1011.78  5717.3 1014.14  5745.9  1023.8  5766.7 1025.28
  5873.3 1031.88  5963.8 1028.93  6029.3 1029.12    6166 1037.39  6271.1 1044.39
  6340.9 1045.86  6540.3 1046.97  6653.4 1051.77  6745.7 1049.39  7016.9 1051.96
#Mann= 7 ,-1 , 0
  3420.4     .05       0  4982.3     .05       0  4990.5     .05       0
  5766.7     .12       0  5963.8     .05       0    6166     .12       0
  6340.9     .05       0
Bank Sta=4982.3,4990.5
XS Rating Curve= 0 ,0
Exp/Cntr=0.3,0.1

Type RM Length L Ch R = 1 ,9286    ,572,572,572
BEGIN DESCRIPTION:
STEELMAN BRANCH 16.0
END DESCRIPTION:
XS GIS Cut Line= 3
      2223907.18      7264644.35      2222885.94        7264560.
      2221199.19      7263734.81
#Sta/Elev= 30
  3972.9 1049.83  4086.5 1050.39    4232 1044.75  4933.1  995.02  4970.3  988.83
  4971.6  988.33  4978.6  988.83  5004.4   995.7  5212.5  993.05  5488.2  997.33
  5510.7 1002.88  5568.2 1007.31  5690.8 1016.98  5696.4 1007.26  5697.8  1007.2
  5706.7 1006.83    5729 1018.32  5763.9 1015.91  5780.9 1021.41  5786.4 1018.77
  5803.4 1022.88  5848.4  1020.8  5870.9 1022.42    5899 1019.19  5945.2 1021.37
  6324.5 1043.89    6408 1047.77  6452.6 1046.28  6586.2 1050.06  6875.4 1051.18
#Mann= 7 ,-1 , 0
  3972.9     .05       0  4970.3    .035       0  4978.6     .05       0
  5568.2     .12       0  5697.8     .05       0  5945.2     .12       0
  6324.5     .05       0
Bank Sta=4970.3,4978.6
XS Rating Curve= 0 ,0
Exp/Cntr=0.3,0.1

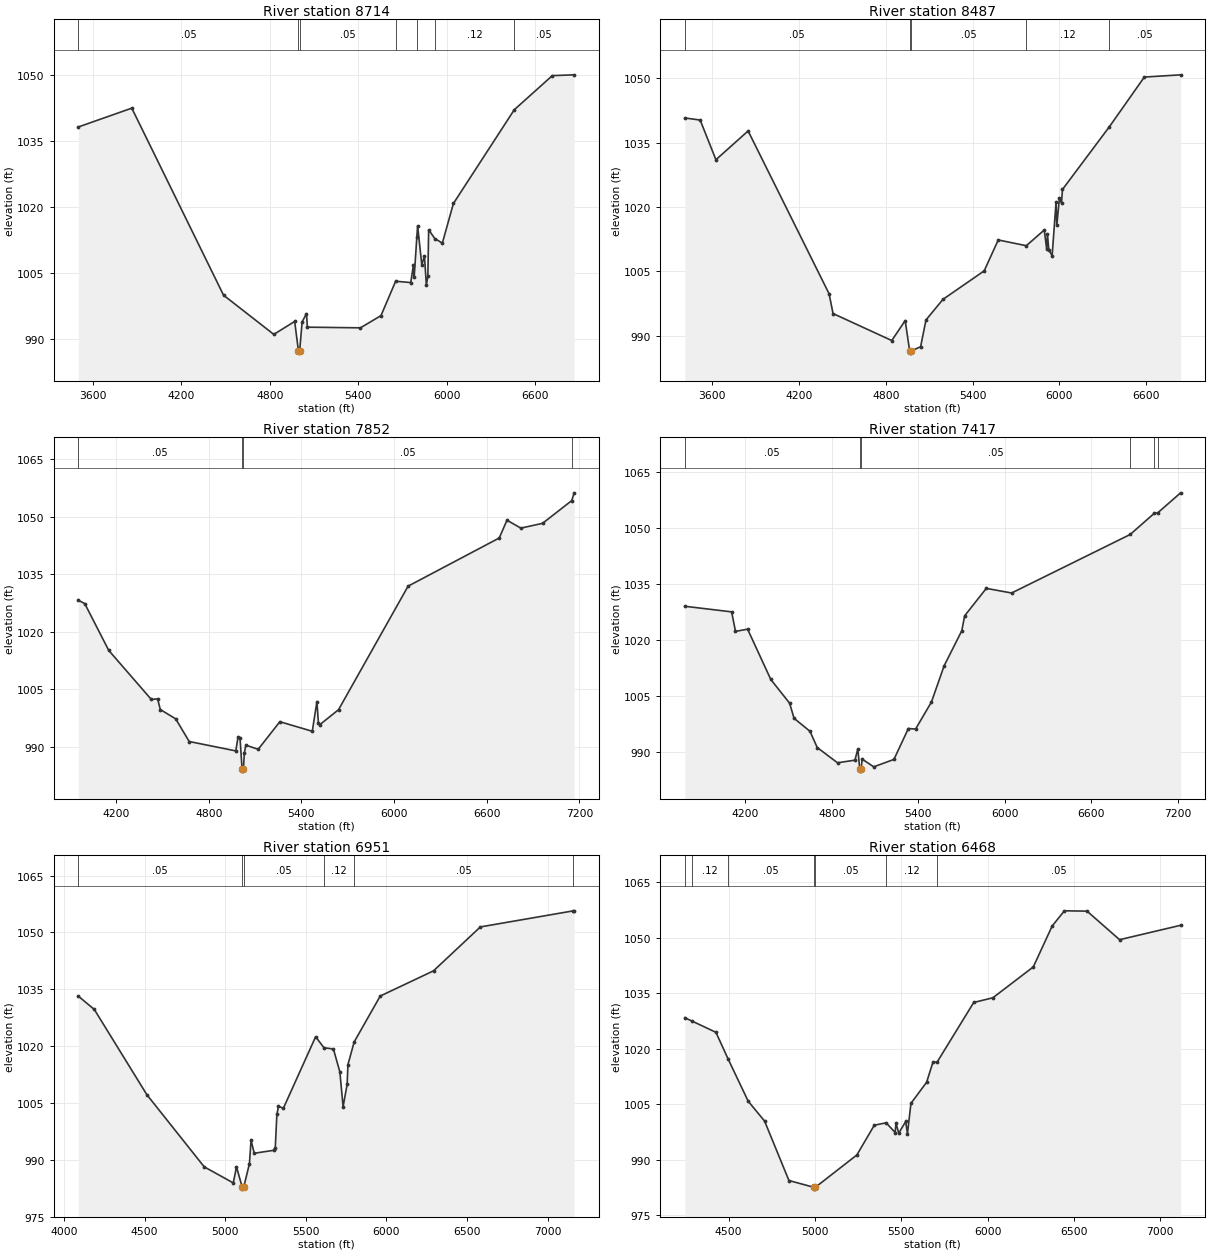
Type RM Length L Ch R = 1 ,8714    ,227,227,227
BEGIN DESCRIPTION:
STEELMAN BRANCH 15.0
END DESCRIPTION:
XS GIS Cut Line= 5
      2224184.93      7264213.79      2223344.64      7263679.07
       2223025.2      7263991.57      2222580.75      7264304.07
      2221323.86      7263741.59
#Sta/Elev= 30
    3501 1038.11  3863.6 1042.38  4485.9  999.95  4826.9  991.05  4968.5  993.99
    4994   987.3  4995.2   986.8  5002.3   987.3    5019   993.9  5048.6  995.76
  5054.8  992.69  5414.6  992.54  5553.9  995.31  5653.3 1003.11  5755.9 1002.81
  5773.6 1006.71  5779.1 1004.06  5797.1 1013.14  5802.3  1015.7  5830.9 1006.81
  5848.6 1008.88  5861.6 1002.27  5871.8 1004.21  5877.3 1014.79  5918.6  1012.8
  5970.1 1011.76  6045.2 1020.75  6458.1 1042.02  6716.1 1049.76  6864.2 1049.94
#Mann= 7 ,-1 , 0
    3501     .05       0    4994    .033       0  5002.3     .05       0
  5653.3     .12       0  5797.1     .05       0  5918.6     .12       0
  6458.1     .05       0
Bank Sta=4994,5002.3
XS Rating Curve= 0 ,0
Exp/Cntr=0.3,0.1

Type RM Length L Ch R = 1 ,8487    ,635,635,635
BEGIN DESCRIPTION:
STEELMAN BRANCH 14.0
END DESCRIPTION:
XS GIS Cut Line= 5
      2224275.23      7264047.14       2223303.1      7263512.55
      2222914.09       7263824.9      2222504.37      7264061.01
      2221219.62      7263658.23
#Sta/Elev= 30
  3410.2 1040.71  3516.4 1040.23  3625.3 1030.99  3847.9 1037.69  4407.6   999.8
  4435.1  995.19    4841  988.91  4933.8  993.56  4964.6  986.48  4965.9  985.98
  4973.4  986.48  5040.2  987.46  5077.6  993.71  5195.4  998.51  5479.8 1005.12
    5577 1012.32  5771.1 1010.98  5895.3 1014.64  5911.8  1010.2    5917 1013.66
  5926.7 1010.04  5949.5 1008.64  5976.7 1021.17  5981.9 1015.75  6000.1  1022.1
  6014.3 1020.86    6021 1024.07    6346  1038.7  6586.9 1050.23  6837.8 1050.75
#Mann= 5 ,-1 , 0
  3410.2     .05       0  4964.6    .033       0  4973.4     .05       0
  5771.1     .12       0    6346     .05       0
Bank Sta=4964.6,4973.4
XS Rating Curve= 0 ,0
Exp/Cntr=0.3,0.1

Type RM Length L Ch R = 1 ,7852    ,435,435,435
BEGIN DESCRIPTION:
STEELMAN BRANCH 13.0
END DESCRIPTION:
XS GIS Cut Line= 3
       2224101.6      7263095.73        2223079.        7263310.
      2220914.12      7263234.62
#Sta/Elev= 30
  3955.2 1028.27    3997 1027.37    4152 1015.18  4427.8 1002.37  4468.7 1002.52
    4486  999.74  4585.9   997.3  4673.1  991.39    4975  988.94  4989.8  992.63
  5002.5  992.22  5015.6  984.16  5016.9  983.66  5024.4  984.16    5030   988.3
    5040  990.44  5120.1  989.36  5260.2  996.56  5470.3  994.06  5500.3 1001.83
  5510.3  996.11  5520.3  995.83  5640.4   999.7  6090.7 1031.94    6681 1044.51
  6731.1 1049.15  6821.1 1047.09  6961.2 1048.33  7150.8 1054.28  7166.2  1056.3
#Mann= 4 ,-1 , 0
  3955.2     .05       0  5015.6    .033       0  5024.4     .05       0
  7150.8     .12       0
Bank Sta=5015.6,5024.4
XS Rating Curve= 0 ,0
Exp/Cntr=0.3,0.1

Type RM Length L Ch R = 1 ,7417    ,466,466,466
BEGIN DESCRIPTION:
STEELMAN BRANCH 12.0
END DESCRIPTION:
XS GIS Cut Line= 3
      2224191.84      7262776.29        2222979.        7262910.
      2220762.64       7263005.4
#Sta/Elev= 30
  3779.8 1029.15  4104.6 1027.65  4131.4 1022.42  4215.3 1023.02  4376.2 1009.55
    4507 1003.18  4537.2  999.17  4647.9  995.68  4698.2  991.33    4839  987.24
  4959.7  987.95  4979.9  990.97  4993.1  985.51  4994.4  985.01  5001.9  985.51
    5010  988.22  5090.1  986.16  5230.2  988.15  5330.3  996.42  5380.3  996.27
  5490.4 1003.52  5578.4 1013.22  5700.6 1022.58  5720.7  1026.6  5870.8 1033.94
  6046.2  1032.7  6868.7 1048.37  7036.2 1054.06  7059.5 1054.16  7218.4 1059.52
#Mann= 6 ,-1 , 0
  3779.8     .05       0  4993.1    .033       0  5001.9     .05       0
  6868.7     .12       0  7036.2     .05       0  7059.5     .12       0
Bank Sta=4993.1,5001.9
XS Rating Curve= 0 ,0
Exp/Cntr=0.3,0.1

Type RM Length L Ch R = 1 ,6951    ,483,483,483
BEGIN DESCRIPTION:
STEELMAN BRANCH 11.0
END DESCRIPTION:
XS GIS Cut Line= 3
      2223837.66      7262394.35        2222929.        7262460.
      2220768.26      7262588.79
#Sta/Elev= 30
    4089 1033.19  4187.9 1029.69  4514.1 1007.17  4869.7  988.13  5050.1  983.88
  5070.1   988.1  5105.7  982.74    5107  982.24  5114.8  982.74  5150.3  988.94
  5160.3  995.11  5180.3  991.71  5300.6  992.49  5310.6  993.17  5320.6 1001.96
  5330.6 1004.13  5360.7 1003.58    5561 1022.48  5612.8 1019.55  5671.2 1019.25
  5711.3 1013.18  5731.3 1004.01  5756.4 1009.88  5761.4 1015.12  5800.1 1021.11
  5961.7 1033.22  6292.3 1039.88  6582.8 1051.47    7160 1055.72  7164.6 1055.65
#Mann= 6 ,-1 , 0
    4089     .05       0  5105.7    .033       0  5114.8     .05       0
  5612.8     .12       0  5800.1     .05       0    7160     .12       0
Bank Sta=5105.7,5114.8
XS Rating Curve= 0 ,0
Exp/Cntr=0.3,0.1

Type RM Length L Ch R = 1 ,6468    ,482,482,482
BEGIN DESCRIPTION:
STEELMAN BRANCH 10.0
END DESCRIPTION:
XS GIS Cut Line= 3
      2223677.94      7261922.13        2222929.        7262010.
      2220832.37      7262303.84
#Sta/Elev= 30
    4246 1028.38  4288.1 1027.46  4426.2 1024.43  4497.4 1017.15  4613.2 1005.79
  4708.1 1000.41    4849  984.34    4993  982.51  4994.3  982.01  5002.1  982.51
  5242.4  991.25  5343.4   999.3  5412.2  999.95    5464  997.32    5469  999.85
  5484.8  997.15  5525.2 1000.31  5535.3  996.99  5555.5  1005.2  5646.3 1010.92
  5683.1 1016.36  5706.9 1016.35    5919  1032.5    6030 1033.77  6264.1 1042.12
  6373.4 1053.19  6444.1 1057.29  6575.3 1057.21  6763.7 1049.48  7117.2 1053.38
#Mann= 7 ,-1 , 0
    4246     .05       0  4288.1     .12       0  4497.4     .05       0
    4993    .033       0  5002.1     .05       0  5412.2     .12       0
  5706.9     .05       0
Bank Sta=4993,5002.1
XS Rating Curve= 0 ,0
Exp/Cntr=0.3,0.1

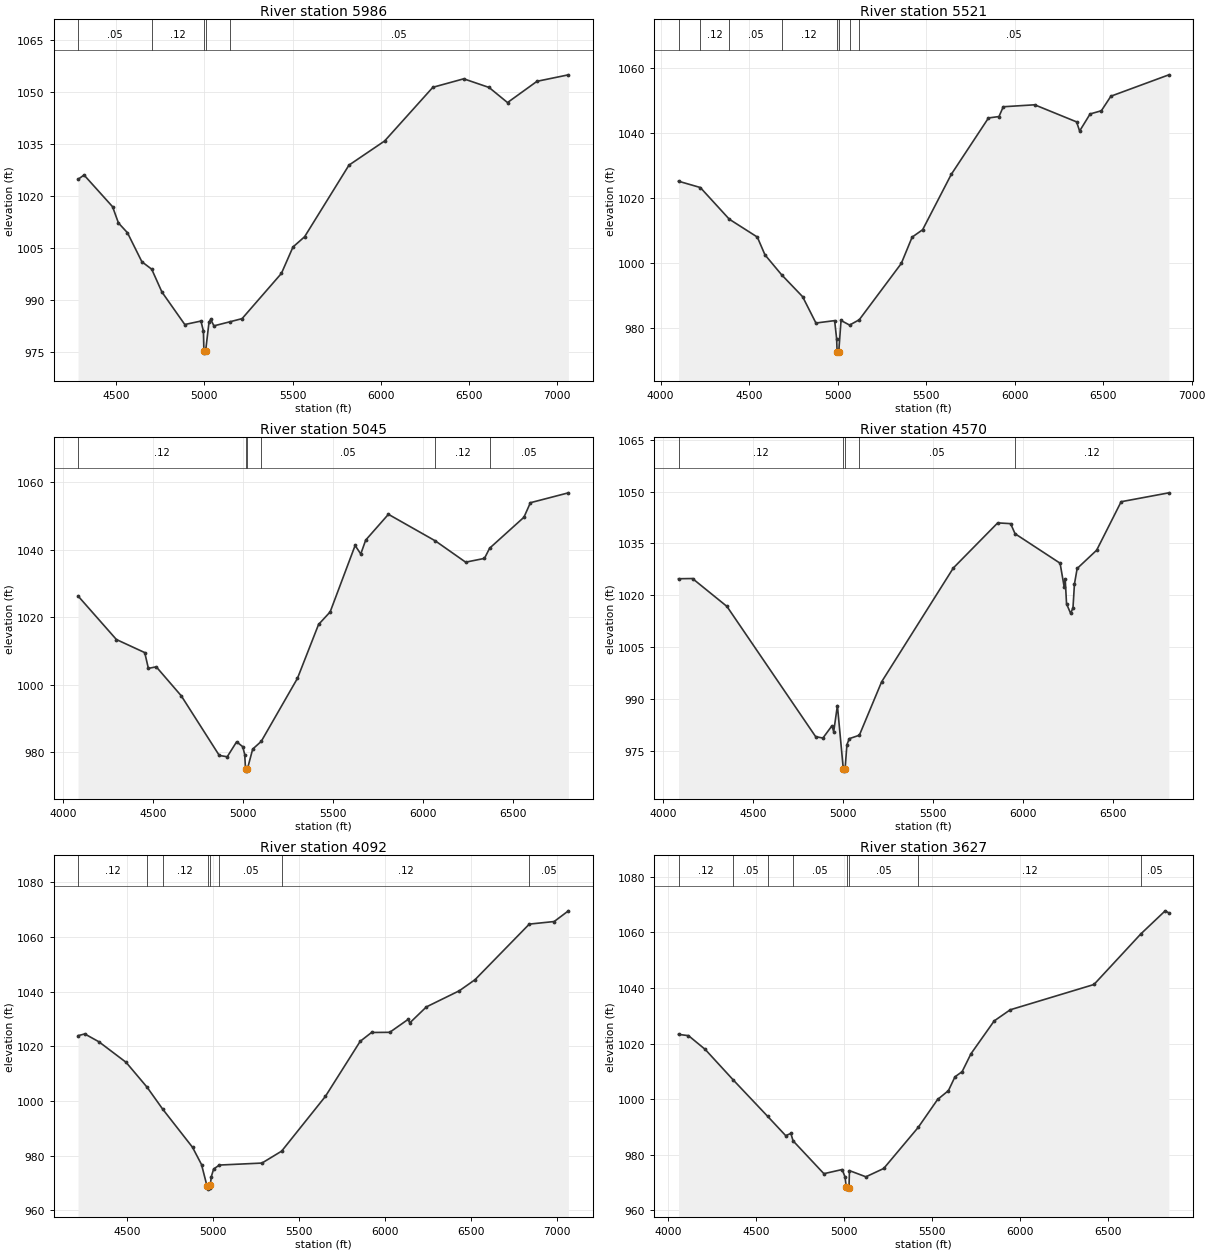
Type RM Length L Ch R = 1 ,5986    ,465,465,465
BEGIN DESCRIPTION:
STEELMAN BRANCH 9.0
END DESCRIPTION:
XS GIS Cut Line= 3
      2223532.16      7261401.28        2222829.        7261560.
      2220858.56      7262158.22
#Sta/Elev= 30
  4283.8 1024.73  4317.8 1025.96  4479.5 1016.81  4512.6 1012.13  4563.8  1009.3
  4645.8 1000.91  4701.4  998.77  4759.3  992.18  4888.9   982.8  4980.5   983.8
  4994.4  980.92  4997.4  975.04  4998.7  974.54  5006.7  975.04  5026.3  983.52
    5036  984.29    5054  982.41  5146.1  983.61  5213.7   984.5  5436.6  997.55
  5502.4 1005.19  5568.2 1008.14  5819.8 1028.82  6021.9 1035.79  6295.4 1051.29
  6470.3 1053.74  6614.1 1051.24  6718.6 1046.88  6885.8 1053.02  7063.9 1054.89
#Mann= 5 ,-1 , 0
  4283.8     .05       0  4701.4     .12       0  4997.4     .07       0
  5006.7     .12       0  5146.1     .05       0
Bank Sta=4997.4,5006.7
XS Rating Curve= 0 ,0
Exp/Cntr=0.3,0.1

Type RM Length L Ch R = 1 ,5521    ,476,476,476
BEGIN DESCRIPTION:
STEELMAN BRANCH 8.0
END DESCRIPTION:
XS GIS Cut Line= 3
      2223427.99      7260901.28        2222579.        7261210.
      2220844.67      7261901.28
#Sta/Elev= 30
  4100.8 1025.24    4224  1023.3  4387.8 1013.56    4546 1008.08  4589.2 1002.62
  4682.8  996.52    4802  989.75  4877.2  981.66  4982.9   982.4  4994.2  976.78
  4996.8  972.91  4998.2  972.41  5006.2  972.91    5019  982.45  5067.3  981.03
  5121.9  982.66  5359.4  999.96  5420.7 1008.06    5480 1010.33  5641.8 1027.34
  5852.1 1044.68  5911.4 1045.11  5935.7 1048.12    6113 1048.72  6349.8 1043.47
    6367 1040.66  6426.3 1045.91  6489.8 1046.89  6543.6 1051.36  6871.2 1057.93
#Mann= 8 ,-1 , 0
  4100.8     .05       0    4224     .12       0  4387.8     .05       0
  4682.8     .12       0  4996.8    .033       0  5006.2     .12       0
  5067.3     .12       0  5121.9     .05       0
Bank Sta=4996.8,5006.2
XS Rating Curve= 0 ,0
Exp/Cntr=0.3,0.1

Type RM Length L Ch R = 1 ,5045    ,475,475,475
BEGIN DESCRIPTION:
STEELMAN BRANCH 7.0
END DESCRIPTION:
XS GIS Cut Line= 3
      2223254.38      7260554.06        2222379.        7260810.
      2220816.83       7261727.7
#Sta/Elev= 30
  4083.8 1026.27  4296.8 1013.38  4454.1 1009.51  4474.4 1004.84  4518.3 1005.29
  4657.3  996.69  4868.3  979.04  4912.5  978.66  4964.6  983.09  4998.7  981.63
  5009.5   979.3  5014.3   974.9  5015.6   974.4  5023.8   974.9  5053.8  980.93
  5101.2   983.2  5302.5 1001.89  5419.7 1017.84  5484.1 1021.56  5622.8 1041.24
  5654.2 1038.71  5681.4 1042.82  5807.7 1050.47  6068.2  1042.6  6236.8 1036.29
  6341.2 1037.41    6370 1040.43  6560.6  1049.6  6596.3  1053.9  6807.6 1056.83
#Mann= 6 ,-1 , 0
  4083.8     .12       0  5014.3     .07       0  5023.8     .12       0
  5101.2     .05       0  6068.2     .12       0    6370     .05       0
Bank Sta=5014.3,5023.8
XS Rating Curve= 0 ,0
Exp/Cntr=0.3,0.1

Type RM Length L Ch R = 1 ,4570    ,478,478,478
BEGIN DESCRIPTION:
STEELMAN BRANCH 6.0
END DESCRIPTION:
XS GIS Cut Line= 3
      2223136.27      7260311.02        2222229.        7260410.
      2220713.31      7261400.89
#Sta/Elev= 30
  4087.3  1024.8    4165 1024.86  4356.2  1016.8  4849.1  979.13  4889.3  978.74
  4939.6  982.28  4949.2  980.57  4969.8  988.13  5002.8  969.67  5004.1  969.17
  5012.3  969.67  5022.6   976.8  5035.8  978.56  5091.7  979.55  5215.5     995
  5613.7 1027.91  5860.2 1040.95  5931.8 1040.73  5956.6 1037.81  6206.6 1029.29
    6229 1022.54    6235  1024.8  6242.5 1017.54  6265.2 1014.78  6278.3 1016.39
  6286.3 1023.23  6301.4 1027.76  6409.7 1033.05  6545.7 1047.07  6810.8 1049.64
#Mann= 5 ,-1 , 0
  4087.3     .12       0  5002.8     .07       0  5012.3     .12       0
  5091.7     .05       0  5956.6     .12       0
Bank Sta=5002.8,5012.3
XS Rating Curve= 0 ,0
Exp/Cntr=0.3,0.1

Type RM Length L Ch R = 1 ,4092    ,465,465,465
BEGIN DESCRIPTION:
STEELMAN BRANCH 5.0
END DESCRIPTION:
XS GIS Cut Line= 3
      2223136.34      7260241.57        2222379.        7260010.
      2220442.89       7259297.5
#Sta/Elev= 30
  4212.2 1023.88  4251.2 1024.52  4333.5 1021.65  4491.8 1014.13    4614 1005.02
  4704.5  997.03  4878.7  983.02    4931  976.71  4962.3  969.02  4967.8  968.21
  4969.2  967.71  4977.8  968.21  4982.5  969.28  4987.8  972.21  5001.5  975.07
  5034.8  976.52  5282.9  977.25  5397.5  981.62  5652.2 1001.65  5854.8 1021.81
    5921 1025.05  6026.9 1025.11  6133.6 1029.83  6143.4 1028.55  6240.2 1034.41
    6432 1040.32  6523.4 1044.37  6839.4 1064.72  6984.2 1065.66  7067.2 1069.58
#Mann= 8 ,-1 , 0
  4212.2     .12       0    4614     .05       0  4704.5     .12       0
  4967.8     .07       0  4977.8     .12       0  5034.8     .05       0
  5397.5     .12       0  6839.4     .05       0
Bank Sta=4962.3,4982.5
XS Rating Curve= 0 ,0
Exp/Cntr=0.3,0.1

Type RM Length L Ch R = 1 ,3627    ,448,448,448
BEGIN DESCRIPTION:
STEELMAN BRANCH 4.0
END DESCRIPTION:
XS GIS Cut Line= 3
      2223233.53      7260054.06        2222429.        7259560.
      2220608.58      7259262.41
#Sta/Elev= 30
  4059.8 1023.28  4116.6 1022.82  4211.3  1017.9  4370.2 1006.96  4566.1  993.87
  4669.5  986.88  4698.8  987.68  4711.2  985.03  4886.6  973.21  4990.3   974.7
  5006.5   972.1  5014.1  968.33  5019.1  968.16  5020.5  967.66  5029.2  968.16
  5032.1  974.31  5125.5  972.09  5226.8  975.08  5423.1  989.86  5533.3  999.89
  5594.7 1003.05  5632.1 1008.03  5672.7 1009.88  5723.3 1016.34  5855.1 1028.12
  5946.3 1032.12  6422.5 1041.21  6689.2  1059.4  6827.6 1067.69  6848.5 1066.94
#Mann= 8 ,-1 , 0
  4059.8     .12       0  4370.2     .05       0  4566.1     .12       0
  4711.2     .05       0  5019.1    .033       0  5029.2     .05       0
  5423.1     .12       0  6689.2     .05       0
Bank Sta=5014.1,5029.2
XS Rating Curve= 0 ,0
Exp/Cntr=0.3,0.1