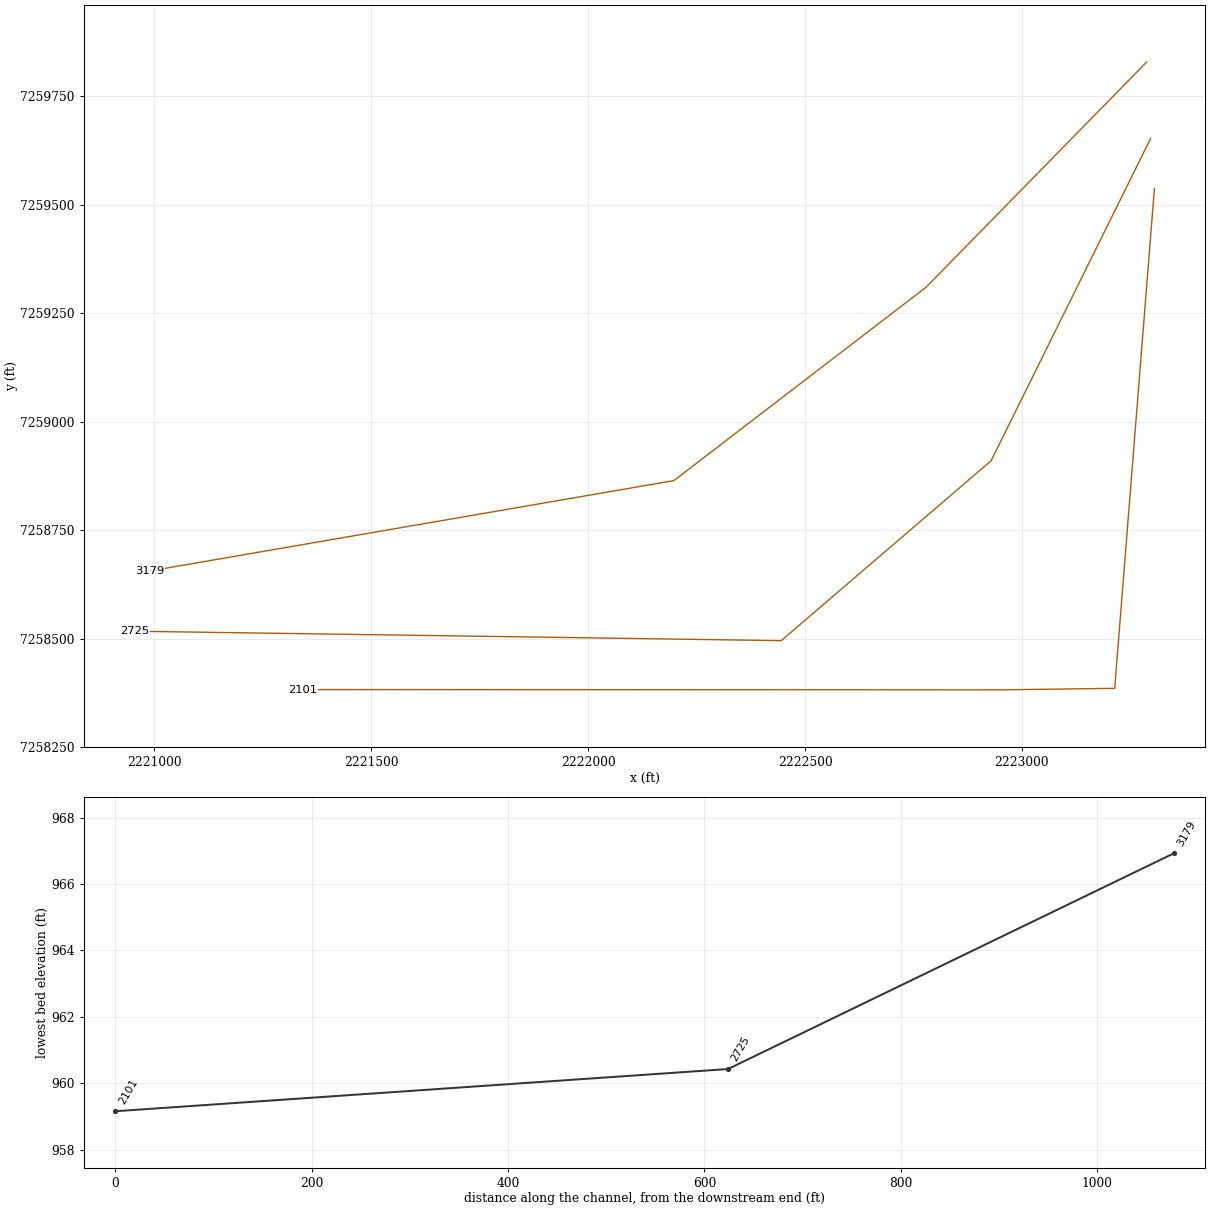
HEC-RAS study STEELMAN BRANCH.prj: STEELMAN BRANCH Base Level Engineering

--- STEELMAN BRANCH.g01 (geometry) --- (continued)

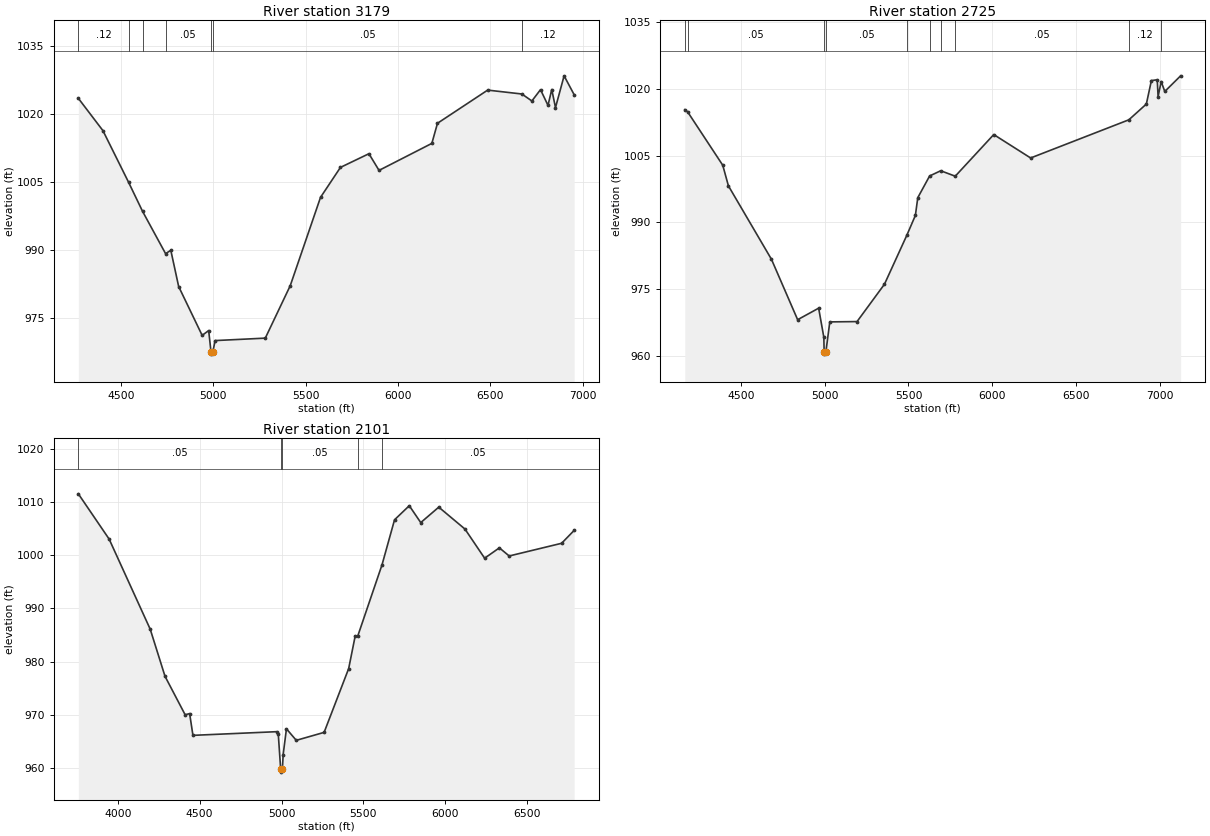
Type RM Length L Ch R = 1 ,3179    ,454,454,454
BEGIN DESCRIPTION:
STEELMAN BRANCH 3.0
END DESCRIPTION:
XS GIS Cut Line= 4
      2223287.94      7259829.54        2222779.        7259310.
      2222197.65      7258864.25      2220989.33      7258655.92
#Sta/Elev= 30
  4268.2 1023.38  4401.5 1016.24  4540.4 1004.85  4615.9  998.45  4740.8   989.1
  4769.2  989.83  4811.7  981.84    4939  971.06  4974.3  972.12  4986.9  967.42
  4988.3  966.92  4997.1  967.42    5009  969.91    5281  970.45  5416.1  982.02
  5580.2 1001.52  5688.1 1008.13  5842.4 1011.15  5897.2 1007.47  6183.3 1013.43
  6213.8 1017.87  6485.7 1025.19  6670.9 1024.33  6725.2 1022.79  6771.9 1025.29
  6812.5 1021.82  6832.8 1025.32  6853.1 1021.33  6899.7 1028.34  6954.2 1024.17
#Mann= 7 ,-1 , 0
  4268.2     .12       0  4540.4     .05       0  4615.9     .12       0
  4740.8     .05       0  4986.9    .033       0  4997.1     .05       0
  6670.9     .12       0
Bank Sta=4986.9,4997.1
XS Rating Curve= 0 ,0
Exp/Cntr=0.3,0.1

Type RM Length L Ch R = 1 ,2725    ,624,624,624
BEGIN DESCRIPTION:
STEELMAN BRANCH 2.0
END DESCRIPTION:
XS GIS Cut Line= 4
      2223296.77      7259653.14        2222929.        7258910.
       2222445.2      7258495.32      2220954.62      7258517.03
#Sta/Elev= 30
    4166 1015.33  4182.9 1014.84  4392.4 1002.85  4426.1  998.22  4682.8  981.73
    4839  968.16  4964.3  970.75  4995.2  964.22  4997.1  960.93  4998.6  960.43
  5007.4  960.93  5030.8  967.67  5193.3  967.74  5356.8  976.13  5490.4  987.14
  5541.2  991.58  5555.5  995.56  5626.1 1000.44  5692.2 1001.61    5779 1000.39
  6008.6 1009.74  6228.6 1004.48  6814.2 1013.05  6918.7 1016.59  6948.7 1021.86
  6983.7 1022.05  6988.7 1018.27  7007.1 1021.64  7028.7 1019.42  7123.1 1022.93
#Mann= 10 ,-1 , 0
    4166     .12       0  4182.9     .05       0  4997.1    .033       0
  5007.4     .05       0  5490.4     .12       0  5626.1     .05       0
  5692.2     .12       0    5779     .05       0  6814.2     .12       0
  7007.1     .05       0
Bank Sta=4997.1,5007.4
XS Rating Curve= 0 ,0
Exp/Cntr=0.3,0.1

Type RM Length L Ch R = 1 ,2101    ,0,0,0
BEGIN DESCRIPTION:
STEELMAN BRANCH 1.0
END DESCRIPTION:
XS GIS Cut Line= 4
      2223305.48      7259537.49       2223213.9       7258385.4
      2222953.48      7258381.93      2221342.45      7258382.48
#Sta/Elev= 30
  3759.4  1011.6  3947.5 1003.07  4198.3  986.09  4288.6  977.22  4411.5  969.97
    4439  970.19  4459.1  966.09    4970  966.78    4980   966.4  4994.9  959.66
  4996.3  959.16  5005.2  959.66    5010  962.48    5030  967.32    5090  965.15
    5260  966.65    5410  978.68    5450  984.85  5464.8  984.75  5613.6  998.23
    5690 1006.71    5780 1009.36    5850 1006.18    5960 1009.09    6120 1004.96
    6240  999.47    6330 1001.42    6390  999.89    6710 1002.28  6786.6 1004.71
#Mann= 5 ,-1 , 0
  3759.4     .05       0  4994.9    .033       0  5005.2     .05       0
  5464.8     .12       0  5613.6     .05       0
Bank Sta=4994.9,5005.2
XS Rating Curve= 0 ,0
Exp/Cntr=0.3,0.1

Chan Stop Cuts=-1
Use User Specified Reach Order=0
Composite Channel Slope=5