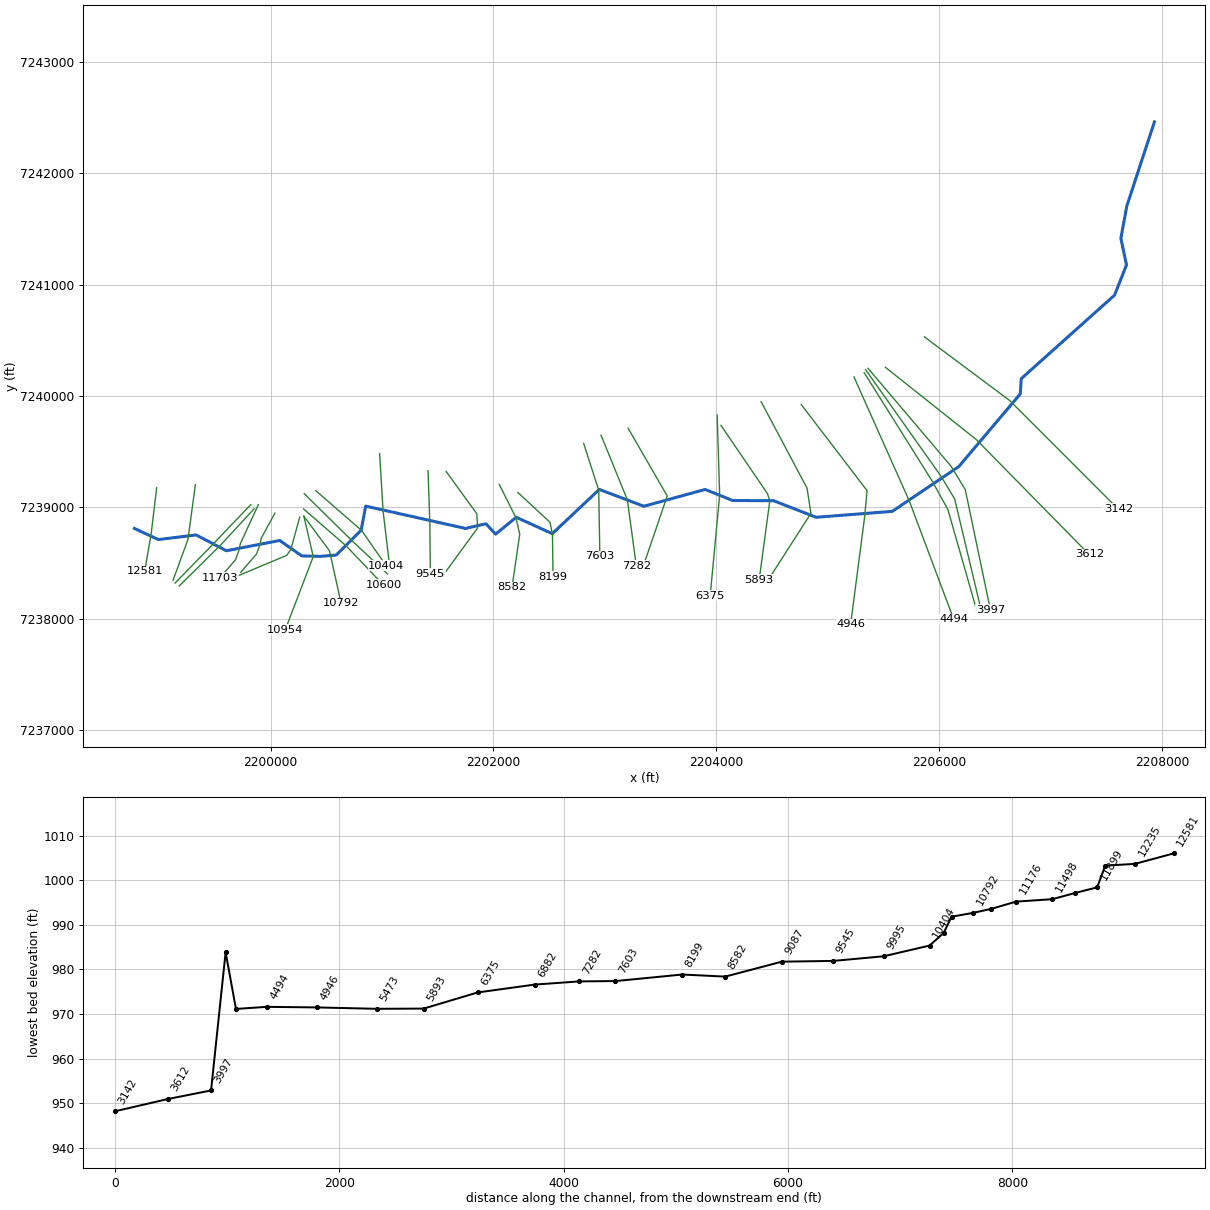
--- STILLHOUSE CREEK.prj (project) ---

Proj Title=STILLHOUSE CREEK Base Level Engineering
Current Plan=p01
Default Exp/Contr=0.3,0.1
English Units
Geom File=g01
Flow File=f01
Plan File=p01
BEGIN DESCRIPTION:
STILLHOUSE CREEK
END DESCRIPTION:

--- STILLHOUSE CREEK.p01 (plan) ---

Plan Title=Multiple Run
Short Identifier=Multiple
Geom File=g01
Flow File=f01
Subcritical Flow
K Sum by GR= 0
Std Step Tol= 0.01
Critical Tol= 0.01
Num of Std Step Trials= 20
Max Error Tol= 0.3
Flow Tol Ratio= 0.001
Split Flow NTrial= 30
Split Flow Tol= 0.02
Split Flow Ratio= 0.02
Log Output Level= 0
Friction Slope Method= 1
Unsteady Friction Slope Method= 2
Unsteady Bridges Friction Slope Method= 1
Parabolic Critical Depth
Global Vel Dist=  1 , 1 , 1
Global Log Level= 0
CheckData=True
Encroach Param= -1, 0, 0, 0
BEGIN DESCRIPTION:
Multiple Run
END DESCRIPTION:

--- STILLHOUSE CREEK.f01 (steady flow) ---

Flow Title=Multiple
Number of Profiles=7
Profile Names=10-year,25-year,50-year,1pct_min,100-year,1pct_plu,500-year
River Rch & RM= STILLHOUSE CREEK,Reach-1,12581
     635     885    1094     672    1341    2676    2020
River Rch & RM= STILLHOUSE CREEK,Reach-1,9995
     905    1277    1592     983    1962    3914    2992
River Rch & RM= STILLHOUSE CREEK,Reach-1,4219
    1040    1478    1852    1149    2293    4575    3530
Boundary for River Rch & Prof#=STILLHOUSE CREEK,Reach-1,1
Up Type=0
Dn Type=3
Dn Slope=0.005
Boundary for River Rch & Prof#=STILLHOUSE CREEK,Reach-1,2
Up Type=0
Dn Type=3
Dn Slope=0.005
Boundary for River Rch & Prof#=STILLHOUSE CREEK,Reach-1,3
Up Type=0
Dn Type=3
Dn Slope=0.005
Boundary for River Rch & Prof#=STILLHOUSE CREEK,Reach-1,4
Up Type=0
Dn Type=3
Dn Slope=0.005
Boundary for River Rch & Prof#=STILLHOUSE CREEK,Reach-1,5
Up Type=0
Dn Type=3
Dn Slope=0.005
Boundary for River Rch & Prof#=STILLHOUSE CREEK,Reach-1,6
Up Type=0
Dn Type=3
Dn Slope=0.005
Boundary for River Rch & Prof#=STILLHOUSE CREEK,Reach-1,7
Up Type=0
Dn Type=3
Dn Slope=0.005

--- STILLHOUSE CREEK.g01 (geometry) ---

Geom Title=Existing Conditions

River Reach=STILLHOUSE CREEK,Reach-1
Reach XY= 30
      2198779.00      7238810.00      2198994.22      7238710.52
      2199332.32      7238751.96      2199603.88      7238609.88
      2200082.41      7238702.19      2200280.55      7238563.75
      2200449.18      7238559.71      2200589.00      7238571.24
      2200812.57      7238793.24      2200853.67      7239010.62
      2201749.30      7238810.28      2201932.65      7238852.27
      2202018.83      7238758.93      2202203.92      7238910.61
      2202527.37      7238763.13      2202949.06      7239160.51
      2203349.18      7239009.71      2203899.15      7239160.36
      2204144.96      7239060.96      2204513.04      7239059.04
      2204894.22      7238910.50      2205577.50      7238963.62
      2206173.86      7239365.18      2206725.91      7240018.31
      2206734.18      7240154.58      2207570.86      7240903.94
      2207678.50      7241175.22      2207628.19      7241415.03
      2207681.26      7241704.06      2207929.00      7242460.00

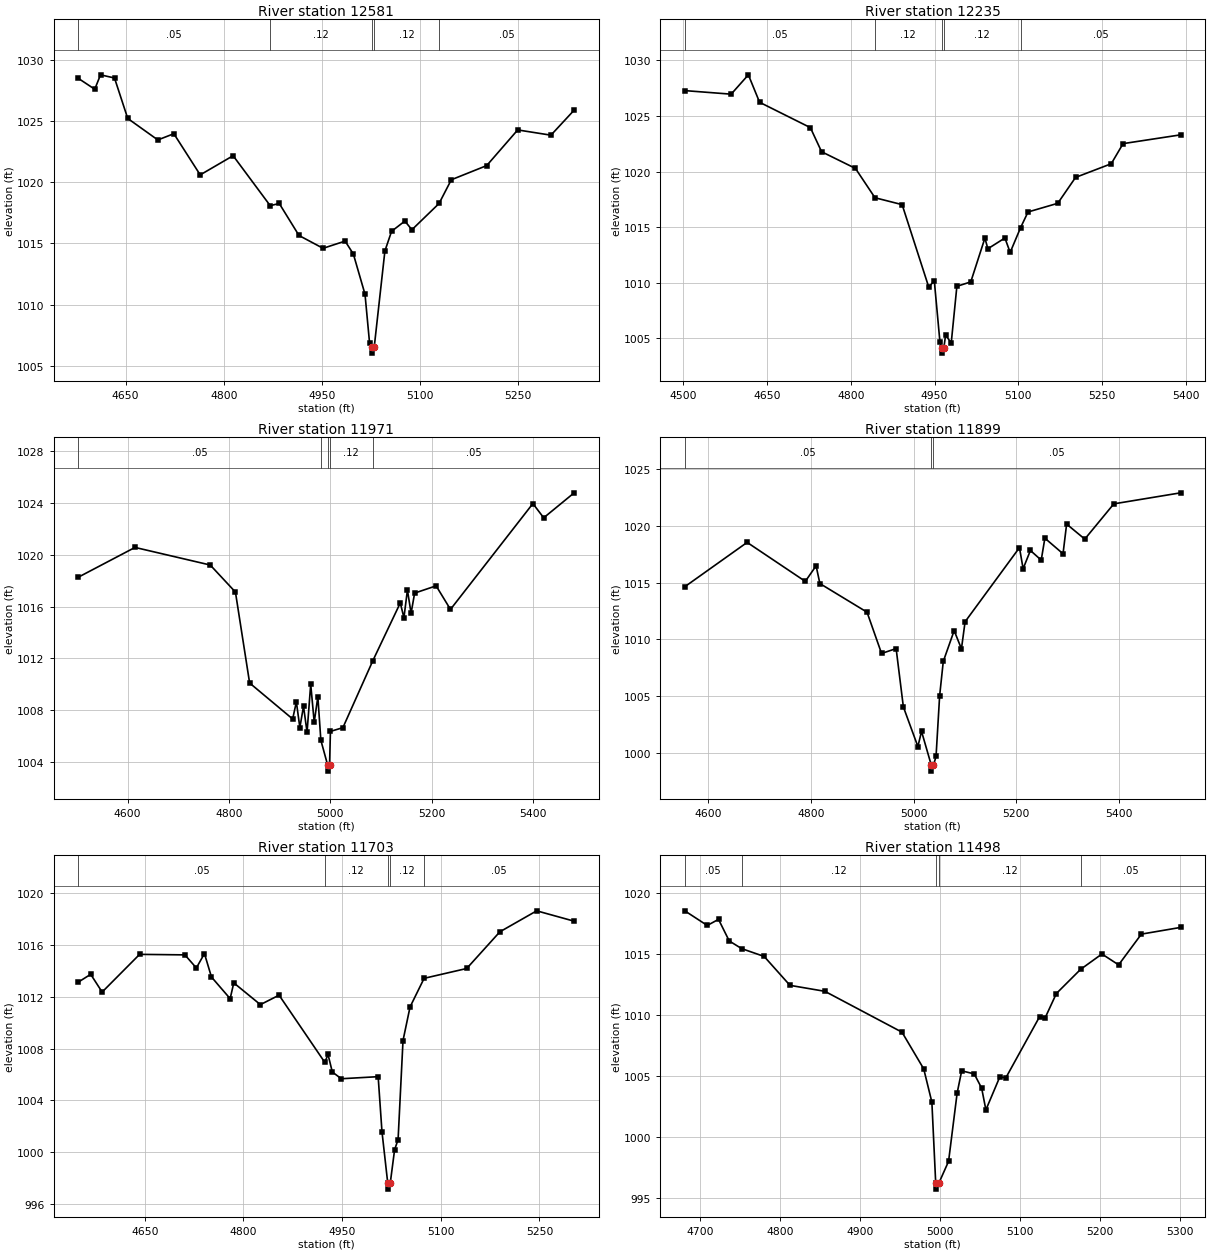
Type RM Length L Ch R = 1,12581,346,346,346
BEGIN DESCRIPTION:
STILLHOUSE CREEK 29.0
END DESCRIPTION:
XS GIS Cut Line= 3
      2198978.46      7239174.94      2198929.00      7238760.00
      2198870.83      7238424.99
#Sta/Elev= 30
  4577.8 1028.51  4602.9 1027.62  4611.7 1028.80  4633.1 1028.54  4653.3 1025.23
  4699.3 1023.47  4723.8 1023.98  4764.1 1020.61  4814.4 1022.18  4871.1 1018.09
  4884.9 1018.27  4915.1 1015.65  4951.9 1014.60  4985.6 1015.19  4998.2 1014.13
  5016.0 1010.84  5023.0 1006.83  5026.1 1006.52  5026.3 1006.02  5030.1 1006.52
  5046.4 1014.38  5056.6 1015.99  5076.9 1016.83  5087.7 1016.12  5129.2 1018.27
  5147.9 1020.21  5202.0 1021.37  5249.4 1024.29  5300.2 1023.86  5335.7 1025.91
#Mann=5,-1,0
  4577.8    0.05       0  4871.1    0.12       0  5026.1    0.07       0
  5030.1    0.12       0  5129.2    0.05       0
Bank Sta=5026.1,5030.1
Exp/Cntr=0.3,0.1

Type RM Length L Ch R = 1,12235,264,264,264
BEGIN DESCRIPTION:
STILLHOUSE CREEK 28.0
END DESCRIPTION:
XS GIS Cut Line= 3
      2199325.68      7239202.74      2199259.71      7238713.16
      2199124.89      7238343.27
#Sta/Elev= 30
  4502.8 1027.29  4585.8 1026.97  4616.6 1028.71  4636.7 1026.24  4727.6 1023.96
  4747.7 1021.79  4808.3 1020.29  4843.3 1017.65  4891.9 1017.03  4939.5 1009.62
  4949.5 1010.17  4959.6 1004.67  4962.7 1004.17  4962.9 1003.67  4966.7 1004.17
  4969.7 1005.30  4979.8 1004.58  4989.9 1009.68  5014.8 1010.08  5040.1 1014.02
  5045.4 1013.06  5075.9 1014.03  5085.3 1012.73  5103.9 1014.95  5117.3 1016.37
  5170.5 1017.15  5202.4 1019.48  5266.3 1020.71  5287.5 1022.52  5390.5 1023.31
#Mann=5,-1,0
  4502.8    0.05       0  4843.3    0.12       0  4962.7    0.07       0
  4966.7    0.12       0  5103.9    0.05       0
Bank Sta=4962.7,4966.7
Exp/Cntr=0.3,0.1

Type RM Length L Ch R = 1,11971,72,72,72
BEGIN DESCRIPTION:
STILLHOUSE CREEK 27.5
END DESCRIPTION:
XS GIS Cut Line= 3
      2199822.85      7239024.13      2199478.90      7238663.90
      2199143.83      7238320.16
#Sta/Elev= 30
  4502.7 1018.27  4614.5 1020.57  4762.9 1019.21  4812.6 1017.12  4840.6 1010.09
  4925.5 1007.31  4932.8 1008.63  4939.7 1006.65  4946.9 1008.29  4953.9 1006.29
  4961.1 1010.00  4968.0 1007.06  4975.2 1009.03  4981.1 1005.67  4994.3 1003.78
  4994.6 1003.28  4998.3 1003.78  5000.0 1006.35  5024.6 1006.64  5083.6 1011.81
  5137.8 1016.28  5145.0 1015.14  5151.9 1017.28  5159.1 1015.48  5166.1 1017.04
  5208.5 1017.60  5236.8 1015.78  5399.4 1023.96  5420.7 1022.86  5480.8 1024.79
#Mann=5,-1,0
  4502.7    0.05       0  4981.1    0.12       0  4994.3    0.07       0
  4998.3    0.12       0  5083.6    0.05       0
Bank Sta=4994.3,4998.3
Exp/Cntr=0.3,0.1

Type RM Length L Ch R = 1,11899,196,196,196
BEGIN DESCRIPTION:
STILLHOUSE CREEK 27.0
END DESCRIPTION:
XS GIS Cut Line= 3
      2199853.49      7238987.50      2199552.68      7238661.73
      2199180.82      7238293.98
#Sta/Elev= 30
  4554.2 1014.63  4675.7 1018.53  4789.1 1015.10  4810.1 1016.47  4817.5 1014.91
  4909.4 1012.39  4937.7 1008.76  4966.1 1009.19  4980.2 1004.06  5008.5 1000.57
  5015.6 1001.91  5034.8  998.91  5035.0  998.41  5038.8  998.91  5043.9  999.71
  5050.9 1005.04  5058.0 1008.06  5079.2 1010.77  5093.4 1009.17  5100.5 1011.55
  5206.5 1018.07  5213.6 1016.21  5227.8 1017.82  5248.9 1016.97  5256.0 1018.90
  5291.4 1017.53  5298.4 1020.14  5333.8 1018.82  5390.4 1021.92  5520.6 1022.89
#Mann=3,-1,0
  4554.2    0.05       0  5034.8   0.033       0  5038.8    0.05       0
Bank Sta=5034.8,5038.8
Exp/Cntr=0.3,0.1

Type RM Length L Ch R = 1,11703,205,205,205
BEGIN DESCRIPTION:
STILLHOUSE CREEK 26.5
END DESCRIPTION:
XS GIS Cut Line= 5
      2199890.87      7239024.17      2199728.46      7238671.49
      2199715.44      7238609.65      2199685.06      7238528.26
      2199544.21      7238364.83
#Sta/Elev= 30
  4548.8 1013.13  4567.6 1013.73  4585.0 1012.36  4642.0 1015.27  4710.9 1015.23
  4728.3 1014.22  4740.6 1015.33  4751.3 1013.52  4779.7 1011.85  4785.2 1013.07
  4825.7 1011.39  4854.1 1012.12  4923.7 1006.93  4928.5 1007.55  4935.1 1006.19
  4948.8 1005.67  5004.8 1005.83  5010.6 1001.59  5019.3  997.65  5019.5  997.15
  5023.3  997.65  5029.8 1000.19  5035.1 1000.97  5042.6 1008.62  5053.3 1011.21
  5074.7 1013.42  5139.5 1014.18  5189.9 1017.01  5245.9 1018.63  5302.9 1017.83
#Mann=5,-1,0
  4548.8    0.05       0  4923.7    0.12       0  5019.3    0.07       0
  5023.3    0.12       0  5074.7    0.05       0
Bank Sta=5019.3,5023.3
Exp/Cntr=0.3,0.1

Type RM Length L Ch R = 1,11498,322,322,322
BEGIN DESCRIPTION:
STILLHOUSE CREEK 26.0
END DESCRIPTION:
XS GIS Cut Line= 5
      2200038.79      7238947.10      2199917.26      7238723.58
      2199904.24      7238661.73      2199873.86      7238580.35
      2199732.84      7238416.73
#Sta/Elev= 30
  4680.7 1018.57  4708.8 1017.37  4722.9 1017.87  4736.3 1016.10  4751.9 1015.47
  4780.0 1014.83  4812.3 1012.46  4856.0 1011.97  4952.5 1008.62  4979.7 1005.61
  4989.9 1002.88  4994.7  996.25  4994.9  995.75  4998.7  996.25  5010.8  998.03
  5021.5 1003.62  5027.2 1005.45  5042.9 1005.20  5052.2 1004.03  5057.5 1002.25
  5074.9 1004.95  5082.5 1004.88  5124.8 1009.90  5131.4 1009.76  5145.7 1011.79
  5176.0 1013.77  5202.7 1015.03  5223.6 1014.14  5252.1 1016.66  5301.2 1017.21
#Mann=5,-1,0
  4680.7    0.05       0  4751.9    0.12       0  4994.7    0.07       0
  4998.7    0.12       0  5176.0    0.05       0
Bank Sta=4994.7,4998.7
Exp/Cntr=0.3,0.1

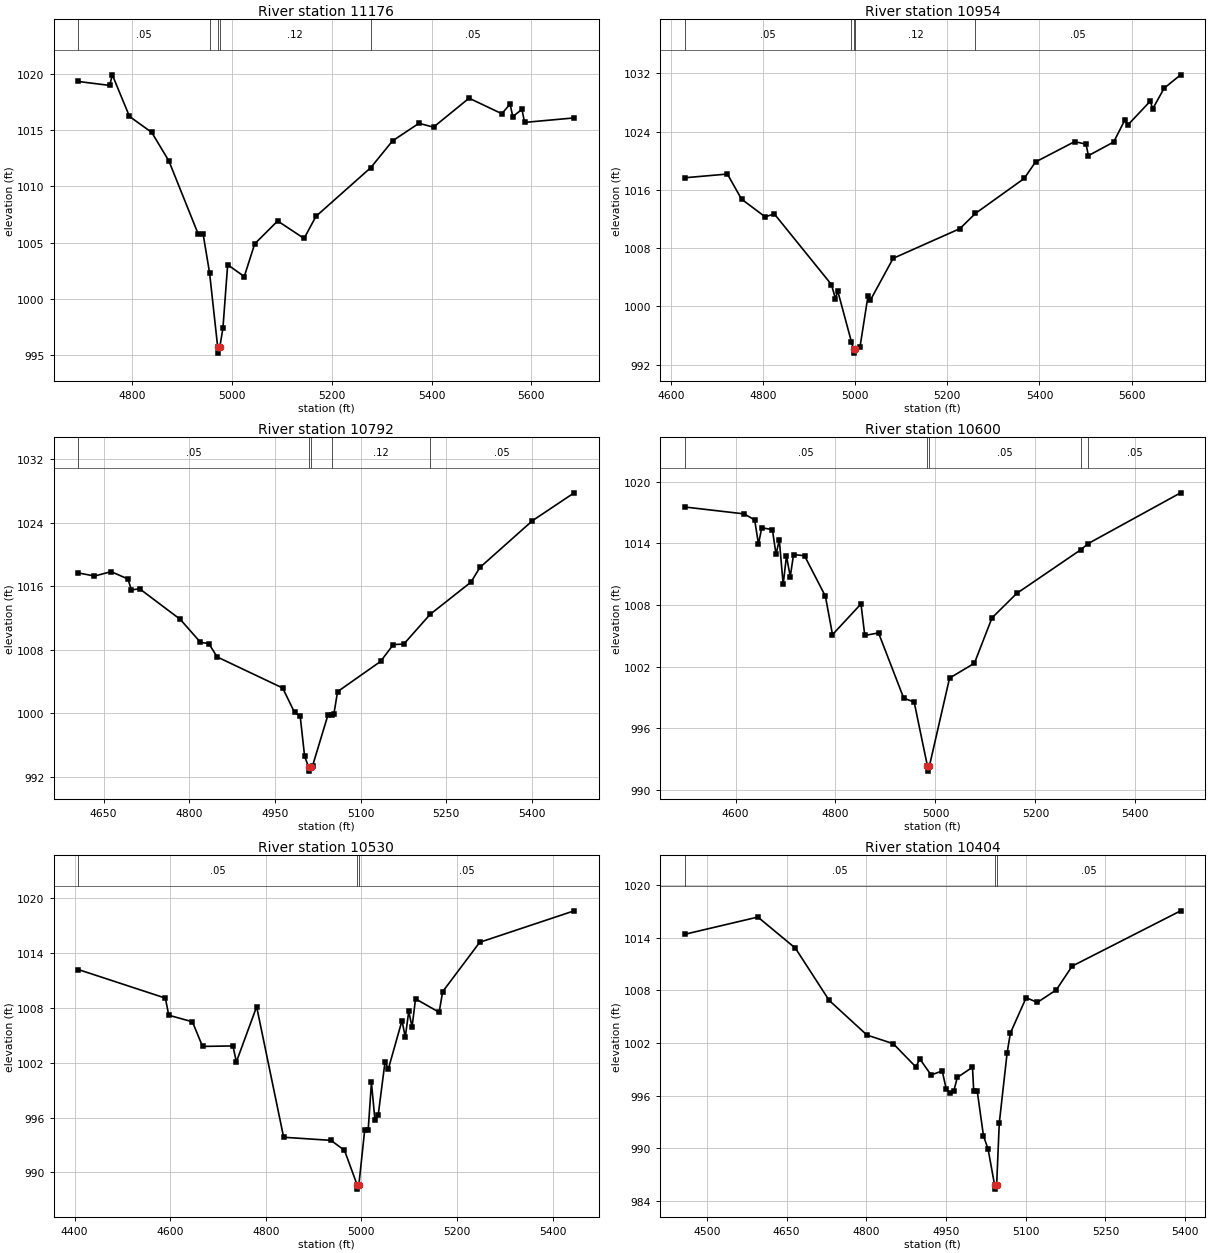
Type RM Length L Ch R = 1,11176,222,222,222
BEGIN DESCRIPTION:
STILLHOUSE CREEK 25.0
END DESCRIPTION:
XS GIS Cut Line= 4
      2200261.95      7238911.30      2200181.66      7238620.50
      2200144.77      7238568.41      2199565.38      7238325.38
#Sta/Elev= 30
  4691.9 1019.30  4754.8 1018.95  4760.0 1019.89  4794.4 1016.20  4839.1 1014.78
  4873.4 1012.25  4931.9 1005.80  4942.1 1005.75  4955.0 1002.31  4971.3  995.71
  4971.6  995.21  4975.3  995.71  4981.7  997.41  4991.2 1003.05  5024.5 1002.00
  5045.4 1004.90  5091.4 1006.93  5144.4 1005.38  5168.2 1007.34  5278.3 1011.67
  5321.6 1014.03  5374.6 1015.59  5403.8 1015.25  5475.1 1017.82  5540.8 1016.44
  5557.2 1017.30  5562.7 1016.19  5581.0 1016.82  5586.4 1015.67  5685.7 1016.07
#Mann=5,-1,0
  4691.9    0.05       0  4955.0    0.12       0  4971.3    0.07       0
  4975.3    0.12       0  5278.3    0.05       0
Bank Sta=4971.3,4975.3
Exp/Cntr=0.3,0.1

Type RM Length L Ch R = 1,10954,162,162,162
BEGIN DESCRIPTION:
STILLHOUSE CREEK 24.5
END DESCRIPTION:
XS GIS Cut Line= 3
      2200298.85      7238919.95      2200383.48      7238557.56
      2200131.76      7237900.04
#Sta/Elev= 30
  4630.2 1017.67  4722.6 1018.18  4753.4 1014.73  4804.7 1012.30  4824.4 1012.71
  4948.5 1003.00  4957.1 1001.07  4962.3 1002.08  4991.9  995.13  4996.5  994.08
  4996.8  993.58  5000.5  994.08  5010.4  994.39  5027.7 1001.38  5033.0 1000.85
  5082.4 1006.60  5227.3 1010.68  5261.0 1012.77  5366.8 1017.57  5391.5 1019.84
  5476.3 1022.63  5501.0 1022.29  5506.3 1020.71  5561.1 1022.58  5585.8 1025.66
  5591.1 1024.87  5640.5 1028.19  5645.9 1027.15  5670.6 1029.97  5706.4 1031.81
#Mann=5,-1,0
  4630.2    0.05       0  4991.9    0.12       0  4996.5    0.07       0
  5000.5    0.12       0  5261.0    0.05       0
Bank Sta=4996.5,5000.5
Exp/Cntr=0.3,0.1

Type RM Length L Ch R = 1,10792,192,192,192
BEGIN DESCRIPTION:
STILLHOUSE CREEK 24.0
END DESCRIPTION:
XS GIS Cut Line= 3
      2200298.82      7238920.00      2200529.00      7238610.00
      2200633.04      7238138.76
#Sta/Elev= 30
  4605.6 1017.67  4633.9 1017.28  4663.1 1017.83  4692.4 1016.91  4698.6 1015.54
  4713.2 1015.66  4784.1 1011.82  4819.6 1008.92  4834.2 1008.76  4848.8 1007.08
  4963.6 1003.16  4984.4 1000.08  4994.3  999.61  5002.0  994.58  5009.0  993.18
  5009.2  992.68  5013.0  993.18  5016.1  993.37  5042.9  999.75  5050.6  999.81
  5053.2  999.83  5059.8 1002.70  5135.1 1006.51  5157.4 1008.63  5176.0 1008.71
  5222.0 1012.45  5293.5 1016.51  5309.2 1018.36  5401.3 1024.26  5474.3 1027.77
#Mann=5,-1,0
  4605.6    0.05       0  5009.0   0.033       0  5013.0    0.05       0
  5050.6    0.12       0  5222.0    0.05       0
Bank Sta=5009,5013
Exp/Cntr=0.3,0.1

Type RM Length L Ch R = 1,10600,70,70,70
BEGIN DESCRIPTION:
STILLHOUSE CREEK 23.5
END DESCRIPTION:
XS GIS Cut Line= 3
      2200296.67      7238985.08      2200674.28      7238657.39
      2201014.53      7238301.97
#Sta/Elev= 30
  4498.5 1017.52  4617.4 1016.85  4638.3 1016.26  4645.9 1013.92  4652.5 1015.50
  4673.7 1015.32  4681.0 1012.93  4687.6 1014.30  4695.3 1009.99  4701.9 1012.74
  4709.5 1010.75  4716.1 1012.89  4738.0 1012.78  4779.8 1008.84  4794.0 1005.10
  4851.0 1008.09  4858.6 1005.02  4886.1 1005.27  4936.5  998.92  4957.4  998.54
  4983.9  992.32  4984.1  991.82  4987.9  992.32  5028.2 1000.87  5077.9 1002.32
  5113.1 1006.73  5162.5 1009.11  5291.3 1013.38  5305.5 1013.96  5490.5 1018.90
#Mann=5,-1,0
  4498.5    0.05       0  4983.9   0.033       0  4987.9    0.05       0
  5291.3    0.12       0  5305.5    0.05       0
Bank Sta=4983.9,4987.9
Exp/Cntr=0.3,0.1

Type RM Length L Ch R = 1,10530,126,126,126
BEGIN DESCRIPTION:
STILLHOUSE CREEK 23.4
END DESCRIPTION:
XS GIS Cut Line= 3
      2200303.22      7239121.77      2200724.75      7238705.75
      2201049.68      7238401.34
#Sta/Elev= 30
  4407.7 1012.18  4589.8 1009.06  4596.9 1007.19  4646.4 1006.47  4667.6 1003.78
  4731.2 1003.83  4738.4 1002.09  4780.8 1008.12  4837.3  993.85  4936.3  993.51
  4964.6  992.42  4990.8  988.68  4991.1  988.18  4994.8  988.68  5006.8  994.59
  5014.2  994.64  5021.0  999.84  5028.3  995.77  5035.2  996.29  5049.3 1002.03
  5056.6 1001.35  5085.0 1006.61  5091.8 1004.77  5099.1 1007.63  5106.0 1005.90
  5113.3 1008.98  5162.7 1007.51  5170.0 1009.76  5247.6 1015.16  5445.2 1018.60
#Mann=3,-1,0
  4407.7    0.05       0  4990.8   0.033       0  4994.8    0.05       0
Bank Sta=4990.8,4994.8
Exp/Cntr=0.3,0.1

Type RM Length L Ch R = 1,10404,409,409,409
BEGIN DESCRIPTION:
STILLHOUSE CREEK 23.0
END DESCRIPTION:
XS GIS Cut Line= 3
      2200405.22      7239149.98      2200817.51      7238791.94
      2201038.16      7238473.95
#Sta/Elev= 30
  4458.5 1014.37  4596.0 1016.33  4666.6 1012.79  4730.2 1006.84  4801.4 1002.89
  4850.8 1001.91  4893.5  999.25  4900.6 1000.19  4922.0  998.35  4942.9  998.81
  4950.5  996.75  4957.2  996.33  4964.8  996.54  4971.4  998.07  4999.9  999.23
  5002.2  996.53  5008.8  996.53  5020.6  991.41  5029.3  989.90  5041.4  985.85
  5041.7  985.35  5045.4  985.85  5050.3  992.86  5065.1 1000.87  5071.2 1003.11
  5100.9 1007.15  5121.9 1006.61  5157.7 1008.04  5187.4 1010.74  5391.6 1017.04
#Mann=3,-1,0
  4458.5    0.05       0  5041.4   0.033       0  5045.4    0.05       0
Bank Sta=5041.4,5045.4
Exp/Cntr=0.3,0.1

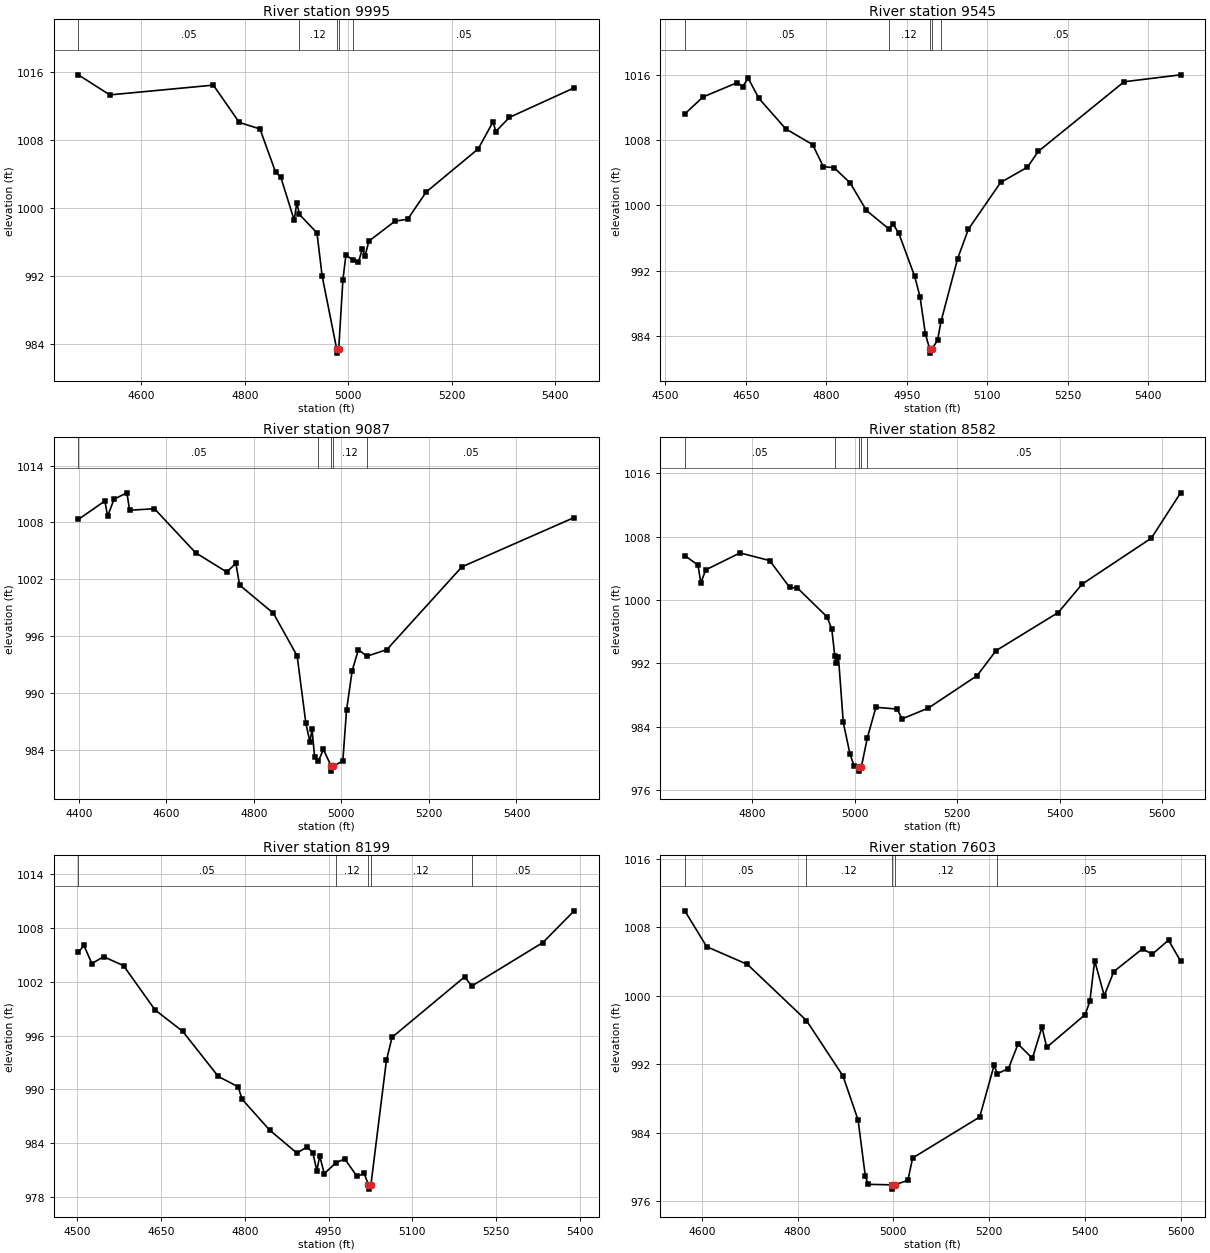
Type RM Length L Ch R = 1,9995,450,450,450
BEGIN DESCRIPTION:
STILLHOUSE CREEK 22.0
END DESCRIPTION:
XS GIS Cut Line= 3
      2200978.76      7239480.66      2201010.02      7238963.29
      2201062.10      7238525.79
#Sta/Elev= 30
  4478.0 1015.67  4538.8 1013.31  4739.1 1014.46  4789.2 1010.08  4829.3 1009.30
  4859.4 1004.24  4869.4 1003.66  4895.5  998.58  4900.5 1000.63  4905.7  999.25
  4939.5  997.09  4949.5  992.02  4977.6  983.45  4977.8  982.95  4981.6  983.45
  4989.6  991.53  4995.5  994.47  5008.8  993.91  5019.8  993.65  5027.4  995.25
  5032.4  994.35  5039.9  996.12  5090.3  998.46  5115.0  998.70  5150.7 1001.89
  5251.4 1006.97  5280.2 1010.17  5285.2 1009.00  5311.8 1010.67  5436.9 1014.14
#Mann=5,-1,0
  4478.0    0.05       0  4905.7    0.12       0  4977.6    0.07       0
  4981.6    0.12       0  5008.8    0.05       0
Bank Sta=4977.6,4981.6
Exp/Cntr=0.3,0.1

Type RM Length L Ch R = 1,9545,458,458,458
BEGIN DESCRIPTION:
STILLHOUSE CREEK 21.0
END DESCRIPTION:
XS GIS Cut Line= 3
      2201412.79      7239327.87      2201429.00      7238860.00
      2201433.62      7238404.67
#Sta/Elev= 30
  4536.5 1011.18  4570.4 1013.25  4634.4 1015.01  4644.4 1014.50  4654.4 1015.56
  4674.5 1013.08  4724.5 1009.35  4774.5 1007.43  4794.5 1004.73  4814.5 1004.60
  4844.6 1002.73  4874.6  999.38  4916.0  997.14  4924.6  997.66  4934.6  996.65
  4964.6  991.32  4974.6  988.80  4984.6  984.26  4992.6  982.41  4992.9  981.91
  4996.7  982.41  5007.2  983.47  5013.8  985.81  5044.7  993.48  5064.7  997.07
  5124.7 1002.79  5174.7 1004.66  5194.7 1006.58  5354.7 1015.11  5460.0 1015.96
#Mann=5,-1,0
  4536.5    0.05       0  4916.0    0.12       0  4992.6    0.07       0
  4996.7    0.12       0  5013.8    0.05       0
Bank Sta=4992.6,4996.7
Exp/Cntr=0.3,0.1

Type RM Length L Ch R = 1,9087,505,505,505
BEGIN DESCRIPTION:
STILLHOUSE CREEK 20.0
END DESCRIPTION:
XS GIS Cut Line= 4
      2201576.01      7239320.90      2201850.65      7238941.79
      2201857.24      7238813.99      2201541.25      7238379.93
#Sta/Elev= 30
  4398.8 1008.32  4459.5 1010.27  4465.7 1008.65  4480.4 1010.46  4509.8 1011.13
  4516.0 1009.29  4572.8 1009.45  4666.8 1004.80  4737.9 1002.77  4758.8 1003.68
  4767.3 1001.39  4844.6  998.41  4898.8  993.91  4918.8  986.77  4927.9  984.85
  4932.9  986.14  4938.8  983.22  4947.2  982.78  4958.8  984.04  4976.8  982.24
  4977.1  981.74  4980.9  982.24  5003.2  982.83  5011.7  988.19  5024.6  992.36
  5038.8  994.58  5057.9  993.87  5103.7  994.57  5275.2 1003.31  5531.8 1008.52
#Mann=5,-1,0
  4398.8    0.05       0  4947.2    0.12       0  4976.8    0.07       0
  4980.9    0.12       0  5057.9    0.05       0
Bank Sta=4976.8,4980.9
Exp/Cntr=0.3,0.1

Type RM Length L Ch R = 1,8582,383,383,383
BEGIN DESCRIPTION:
STILLHOUSE CREEK 19.0
END DESCRIPTION:
XS GIS Cut Line= 4
      2202051.68      7239206.36      2202200.99      7238907.74
      2202235.71      7238758.43      2202166.44      7238283.92
#Sta/Elev= 30
  4669.1 1005.62  4694.8 1004.42  4700.4 1002.15  4709.7 1003.81  4776.8 1005.96
  4834.6 1004.99  4873.7 1001.59  4888.6 1001.53  4946.4  997.88  4955.7  996.33
  4961.5  992.96  4963.1  992.03  4968.7  992.76  4978.1  984.54  4991.1  980.57
  4998.9  979.09  5008.7  978.89  5009.1  978.39  5013.2  978.89  5025.0  982.60
  5041.7  986.46  5082.8  986.23  5093.0  985.00  5144.0  986.36  5238.9  990.45
  5275.9  993.61  5397.2  998.43  5443.8 1002.02  5578.8 1007.83  5635.8 1013.55
#Mann=5,-1,0
  4669.1    0.05       0  4961.5    0.12       0  5008.7    0.07       0
  5013.2    0.12       0  5025.0    0.05       0
Bank Sta=5008.7,5013.2
Exp/Cntr=0.3,0.1

Type RM Length L Ch R = 1,8199,596,596,596
BEGIN DESCRIPTION:
STILLHOUSE CREEK 18.0
END DESCRIPTION:
XS GIS Cut Line= 4
      2202218.34      7239133.44      2202506.54      7238866.07
      2202529.00      7238760.00      2202534.31      7238373.98
#Sta/Elev= 30
  4502.1 1005.32  4512.2 1006.06  4526.3 1004.04  4547.3 1004.81  4583.0 1003.81
  4639.4  998.87  4689.0  996.47  4752.6  991.44  4788.3  990.28  4795.1  988.91
  4844.4  985.46  4893.5  982.88  4911.6  983.58  4921.9  982.92  4929.1  980.91
  4934.2  982.57  4942.3  980.59  4962.6  981.76  4978.8  982.25  5001.1  980.27
  5013.6  980.64  5021.4  979.36  5021.8  978.86  5025.9  979.36  5053.6  993.23
  5063.7  995.81  5193.7 1002.56  5206.3 1001.53  5333.7 1006.39  5389.7 1009.93
#Mann=5,-1,0
  4502.1    0.05       0  4962.6    0.12       0  5021.4    0.07       0
  5025.9    0.12       0  5206.3    0.05       0
Bank Sta=5021.4,5025.9
Exp/Cntr=0.3,0.1

Type RM Length L Ch R = 1,7603,321,321,321
BEGIN DESCRIPTION:
STILLHOUSE CREEK 17.0
END DESCRIPTION:
XS GIS Cut Line= 3
      2202808.63      7239574.39      2202944.04      7239154.26
      2202954.46      7238560.56
#Sta/Elev= 30
  4564.5 1009.92  4610.2 1005.73  4695.2 1003.66  4818.5  997.10  4894.8  990.61
  4926.3  985.47  4941.3  978.94  4947.3  977.95  4997.4  977.89  4998.0  977.39
  5002.4  977.89  5030.2  978.41  5040.2  981.03  5180.2  985.82  5210.2  991.85
  5217.1  990.90  5240.2  991.47  5260.2  994.34  5290.2  992.69  5310.2  996.32
  5320.2  993.97  5400.2  997.78  5410.2  999.34  5420.2 1004.10  5440.2 1000.00
  5460.2 1002.82  5520.2 1005.49  5540.3 1004.84  5574.4 1006.49  5599.7 1004.04
#Mann=5,-1,0
  4564.5    0.05       0  4818.5    0.12       0  4997.4    0.07       0
  5002.4    0.12       0  5217.1    0.05       0
Bank Sta=4997.4,5002.4
Exp/Cntr=0.3,0.1

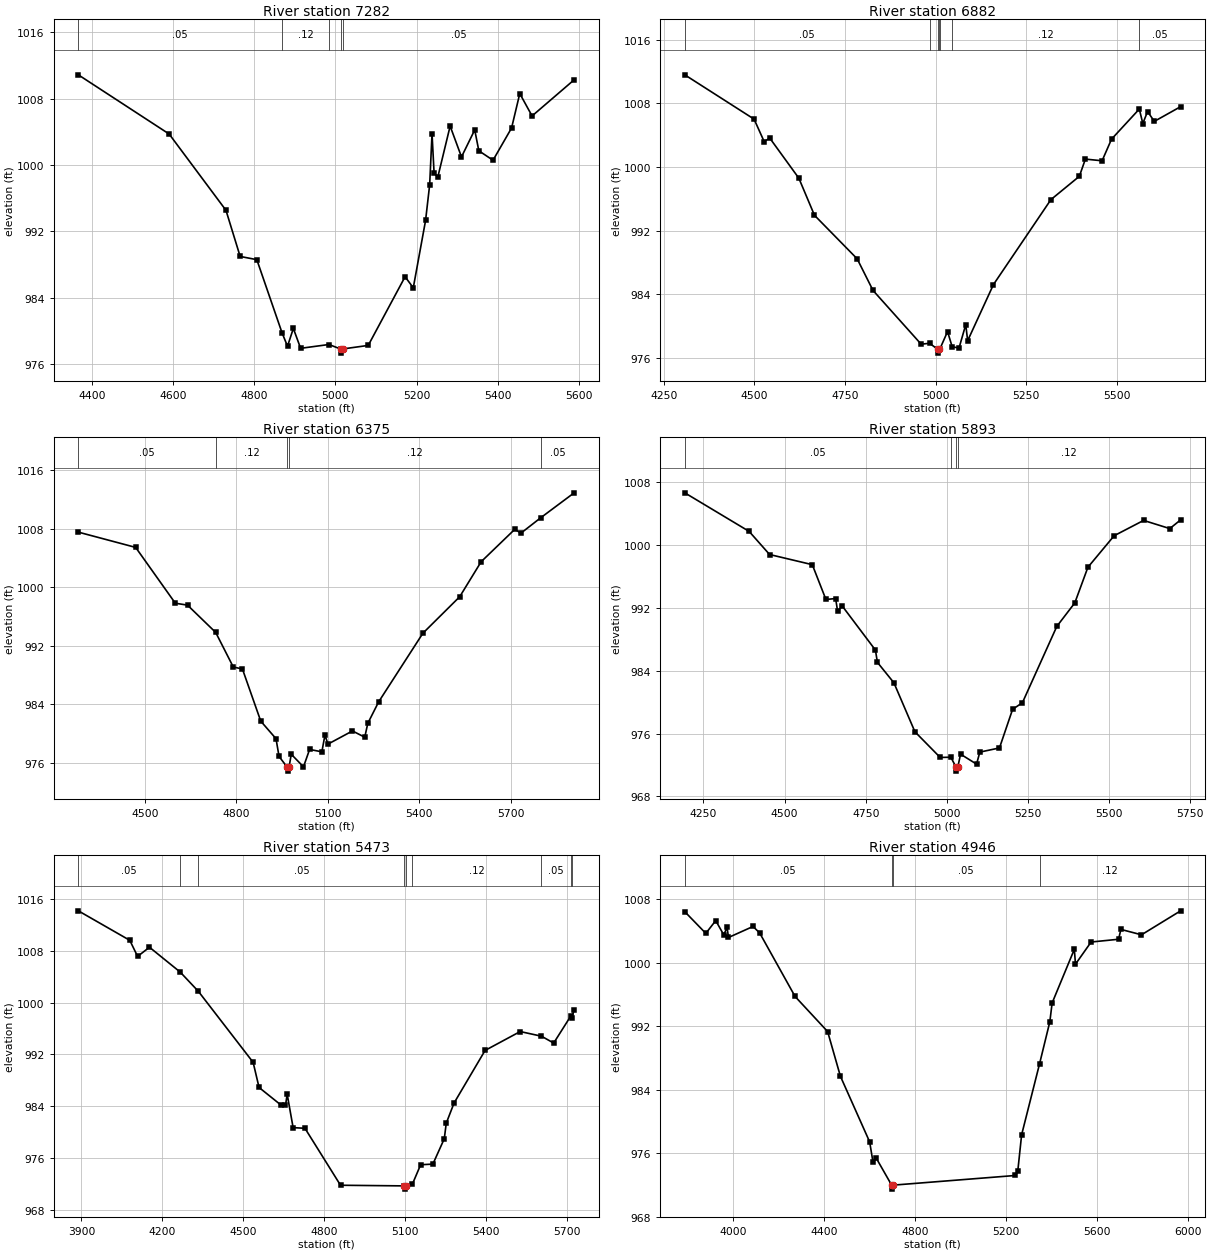
Type RM Length L Ch R = 1,7282,400,400,400
BEGIN DESCRIPTION:
STILLHOUSE CREEK 16.0
END DESCRIPTION:
XS GIS Cut Line= 3
      2202964.88      7239647.30      2203200.99      7239067.46
      2203280.85      7238477.20
#Sta/Elev= 30
  4366.6 1010.88  4590.4 1003.74  4730.4  994.54  4765.3  988.98  4806.4  988.59
  4868.4  979.79  4882.0  978.15  4896.4  980.30  4914.3  977.90  4984.1  978.36
  5012.7  977.82  5013.4  977.32  5017.7  977.82  5080.9  978.25  5171.7  986.53
  5191.9  985.20  5222.2  993.32  5232.3  997.64  5238.1 1003.77  5243.2  999.00
  5252.5  998.58  5282.7 1004.70  5310.7 1000.98  5343.3 1004.24  5353.4 1001.72
  5388.4 1000.58  5434.1 1004.47  5454.3 1008.62  5484.6 1005.92  5588.3 1010.28
#Mann=5,-1,0
  4366.6    0.05       0  4868.4    0.12       0  4984.1    0.05       0
  5012.7   0.033       0  5017.7    0.05       0
Bank Sta=5012.7,5017.7
Exp/Cntr=0.3,0.1

Type RM Length L Ch R = 1,6882,507,507,507
BEGIN DESCRIPTION:
STILLHOUSE CREEK 15.0
END DESCRIPTION:
XS GIS Cut Line= 3
      2203207.95      7239709.79      2203558.63      7239102.18
      2203343.69      7238471.23
#Sta/Elev= 30
  4307.7 1011.57  4498.9 1006.00  4526.8 1003.17  4542.0 1003.63  4622.4  998.58
  4665.5  993.92  4783.3  988.45  4827.0  984.48  4959.9  977.72  4982.9  977.84
  5005.1  977.10  5005.7  976.60  5010.1  977.10  5011.3  977.10  5032.7  979.31
  5045.5  977.39  5064.4  977.25  5082.9  980.18  5088.2  978.16  5159.4  985.22
  5317.9  995.89  5396.4  998.82  5413.0 1000.98  5459.1 1000.77  5485.2 1003.49
  5561.8 1007.27  5571.5 1005.45  5584.6 1006.96  5603.2 1005.72  5675.8 1007.57
#Mann=7,-1,0
  4307.7    0.05       0  4982.9    0.12       0  5005.1    0.07       0
  5010.1    0.12       0  5011.3    0.05       0  5045.5    0.12       0
  5561.8    0.05       0
Bank Sta=5005.1,5010.1
Exp/Cntr=0.3,0.1

Type RM Length L Ch R = 1,6375,482,482,482
BEGIN DESCRIPTION:
STILLHOUSE CREEK 14.0
END DESCRIPTION:
XS GIS Cut Line= 3
      2204006.54      7239827.86      2204029.00      7239110.00
      2203944.04      7238206.30
#Sta/Elev= 30
  4281.5 1007.55  4469.5 1005.46  4599.5  997.82  4639.5  997.56  4732.0  993.82
  4789.6  989.09  4819.6  988.82  4879.7  981.68  4929.7  979.28  4939.7  976.85
  4967.1  975.34  4967.8  974.84  4972.3  975.34  4979.7  977.15  5019.8  975.43
  5039.9  977.81  5080.1  977.48  5090.1  979.76  5100.2  978.54  5180.5  980.34
  5220.7  979.48  5230.7  981.38  5266.3  984.32  5411.5  993.72  5532.1  998.71
  5602.4 1003.50  5712.8 1007.94  5732.9 1007.41  5797.2 1009.50  5907.4 1012.93
#Mann=5,-1,0
  4281.5    0.05       0  4732.0    0.12       0  4967.1    0.07       0
  4972.3    0.12       0  5797.2    0.05       0
Bank Sta=4967.1,4972.3
Exp/Cntr=0.3,0.1

Type RM Length L Ch R = 1,5893,420,420,420
BEGIN DESCRIPTION:
STILLHOUSE CREEK 13.0
END DESCRIPTION:
XS GIS Cut Line= 4
      2204040.40      7239735.85      2204457.06      7239123.88
      2204479.00      7239060.00      2204383.28      7238346.99
#Sta/Elev= 30
  4192.6 1006.63  4390.8 1001.72  4453.8  998.78  4585.3  997.49  4627.3  993.06
  4657.2  993.18  4663.2  991.59  4678.1  992.20  4779.8  986.62  4785.9  985.06
  4836.7  982.46  4901.4  976.23  4979.3  972.96  5012.1  972.99  5028.1  971.72
  5028.8  971.22  5033.5  971.72  5042.0  973.38  5091.3  972.11  5101.4  973.64
  5161.9  974.17  5202.3  979.08  5232.6  979.93  5338.6  989.64  5394.0  992.63
  5434.3  997.16  5515.1 1001.17  5605.9 1003.12  5686.6 1002.08  5719.9 1003.19
#Mann=4,-1,0
  4192.6    0.05       0  5012.1    0.12       0  5028.1   0.033       0
  5033.5    0.12       0
Bank Sta=5028.1,5033.5
Exp/Cntr=0.3,0.1

Type RM Length L Ch R = 1,5473,527,527,527
BEGIN DESCRIPTION:
STILLHOUSE CREEK 12.0
END DESCRIPTION:
XS GIS Cut Line= 4
      2204400.64      7239948.54      2204812.97      7239171.62
      2204847.69      7238945.93      2204453.38      7238330.64
#Sta/Elev= 30
  3888.5 1014.21  4079.3 1009.65  4108.3 1007.16  4152.3 1008.58  4266.2 1004.74
  4333.4 1001.77  4536.7  990.78  4558.7  986.89  4641.0  984.14  4656.7  984.11
  4663.0  985.84  4685.0  980.68  4728.9  980.58  4860.8  971.77  5097.4  971.67
  5098.2  971.17  5102.9  971.67  5126.8  971.89  5157.9  974.94  5203.3  975.04
  5245.6  978.97  5252.9  981.37  5281.9  984.49  5396.9  992.62  5527.1  995.54
  5606.0  994.82  5651.3  993.76  5714.1  997.90  5718.7  997.71  5727.2  998.93
#Mann=9,-1,0
  3888.5    0.05       0  4266.2    0.12       0  4333.4    0.05       0
  5097.4   0.033       0  5102.9    0.05       0  5126.8    0.12       0
  5606.0    0.05       0  5714.1    0.12       0  5718.7    0.05       0
Bank Sta=5097.4,5102.9
Exp/Cntr=0.3,0.1

Type RM Length L Ch R = 1,4946,452,452,452
BEGIN DESCRIPTION:
STILLHOUSE CREEK 11.0
END DESCRIPTION:
XS GIS Cut Line= 4
      2204760.86      7239922.53      2205351.16      7239149.92
      2205329.00      7238910.00      2205203.80      7237949.27
#Sta/Elev= 30
  3786.6 1006.43  3879.1 1003.70  3922.7 1005.31  3958.1 1003.51  3972.6 1004.45
  3978.9 1003.18  4086.9 1004.57  4115.9 1003.76  4271.9  995.75  4415.2  991.33
  4471.4  985.70  4600.2  977.43  4614.7  974.90  4629.2  975.38  4697.0  971.98
  4697.9  971.48  4702.8  971.98  5241.9  973.20  5252.0  973.74  5268.9  978.32
  5347.8  987.26  5393.1  992.57  5403.2  994.93  5500.9 1001.69  5506.0  999.82
  5574.7 1002.61  5695.7 1002.96  5705.8 1004.20  5796.5 1003.52  5968.7 1006.54
#Mann=4,-1,0
  3786.6    0.05       0  4697.0   0.033       0  4702.8    0.05       0
  5347.8    0.12       0
Bank Sta=4697,4702.8
Exp/Cntr=0.3,0.1

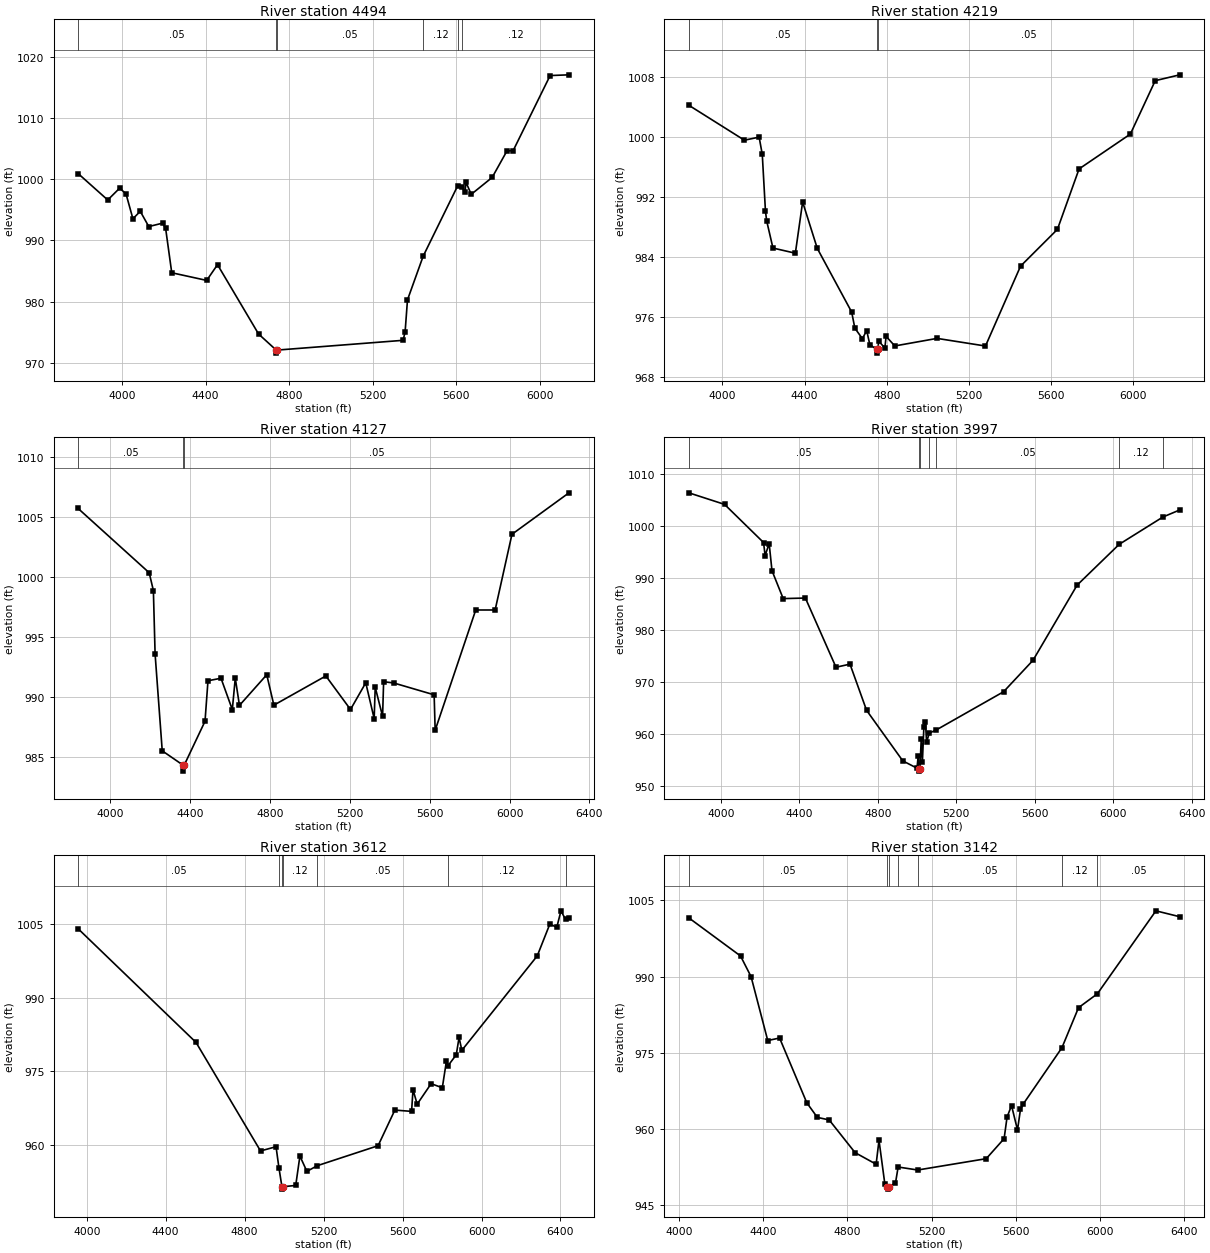
Type RM Length L Ch R = 1,4494,275,275,275
BEGIN DESCRIPTION:
STILLHOUSE CREEK 10.0
END DESCRIPTION:
XS GIS Cut Line= 3
      2205233.96      7240169.92      2205729.00      7239060.00
      2206128.06      7237995.45
#Sta/Elev= 30
  3789.0 1000.93  3931.1  996.61  3988.5  998.55  4018.9  997.58  4051.7  993.54
  4086.9  994.76  4127.8  992.27  4194.0  992.83  4208.5  991.97  4237.8  984.73
  4405.2  983.48  4457.1  986.05  4653.9  974.73  4738.3  972.11  4739.3  971.61
  4744.2  972.11  5346.1  973.70  5355.9  975.02  5367.4  980.30  5442.5  987.43
  5608.2  998.94  5627.6  998.79  5642.5  997.86  5647.9  999.49  5672.8  997.53
  5773.2 1000.29  5843.7 1004.60  5874.0 1004.68  6050.9 1016.92  6141.2 1017.04
#Mann=6,-1,0
  3789.0    0.05       0  4738.3   0.033       0  4744.2    0.05       0
  5442.5    0.12       0  5608.2    0.05       0  5627.6    0.12       0
Bank Sta=4738.3,4744.2
Exp/Cntr=0.3,0.1

Type RM Length L Ch R = 1,4219,92,92,92
BEGIN DESCRIPTION:
STILLHOUSE CREEK 9.5
END DESCRIPTION:
XS GIS Cut Line= 4
      2205325.09      7240208.99      2205937.10      7239232.39
      2206075.99      7238980.65      2206336.41      7238069.16
#Sta/Elev= 30
  3837.3 1004.28  4107.5  999.61  4179.2 1000.02  4194.5  997.70  4209.9  990.14
  4215.8  988.83  4246.4  985.19  4355.4  984.50  4390.8  991.35  4462.1  985.14
  4629.4  976.63  4644.8  974.48  4681.3  973.08  4702.5  974.14  4717.8  972.27
  4751.3  971.64  4752.3  971.14  4757.4  971.64  4760.3  972.76  4790.9  971.82
  4796.8  973.38  4839.2  972.10  5044.7  973.11  5280.3  972.09  5450.9  982.77
  5630.3  987.69  5735.6  995.77  5985.2 1000.43  6106.1 1007.57  6225.3 1008.35
#Mann=3,-1,0
  3837.3    0.05       0  4751.3   0.033       0  4757.4    0.05       0
Bank Sta=4751.3,4757.4
Exp/Cntr=0.3,0.1

Type RM Length L Ch R = 1,4127,130,130,130
BEGIN DESCRIPTION:
STILLHOUSE CREEK 9.4
END DESCRIPTION:
XS GIS Cut Line= 4
      2205338.12      7240235.02      2206010.88      7239284.47
      2206136.75      7239076.14      2206379.81      7238056.15
#Sta/Elev= 30
  3840.8 1005.72  4196.6 1000.37  4217.6  998.89  4226.2  993.60  4261.9  985.55
  4365.9  984.36  4366.9  983.86  4372.0  984.36  4476.0  988.01  4490.8  991.38
  4556.0  991.59  4612.6  988.98  4627.4  991.60  4648.3  989.33  4784.9  991.88
  4820.6  989.35  5080.7  991.78  5204.0  988.99  5280.4  991.21  5322.5  988.23
  5327.7  990.84  5364.6  988.42  5369.8  991.30  5419.5  991.20  5622.6  990.21
  5627.7  987.26  5830.7  997.27  5927.8  997.27  6012.0 1003.57  6297.3 1007.02
#Mann=3,-1,0
  3840.8    0.05       0  4365.9   0.033       0  4372.0    0.05       0
Bank Sta=4365.9,4372
Exp/Cntr=0.3,0.1

Type RM Length L Ch R = 1,3997,385,385,385
BEGIN DESCRIPTION:
STILLHOUSE CREEK 9.0
END DESCRIPTION:
XS GIS Cut Line= 4
      2205359.86      7240247.99      2206106.37      7239366.94
      2206232.24      7239158.60      2206457.93      7238077.90
#Sta/Elev= 30
  3837.2 1006.32  4019.2 1004.10  4218.0  996.77  4225.8  994.28  4246.6  996.56
  4260.9  991.37  4318.1  986.00  4431.2  986.11  4587.2  972.82  4658.6  973.41
  4743.1  964.54  4927.7  954.83  5000.1  953.43  5006.3  955.79  5009.1  953.36
  5010.1  952.86  5015.2  953.36  5021.8  959.12  5027.7  954.67  5035.1  961.25
  5043.2  962.34  5049.0  958.42  5062.5  960.15  5098.8  960.78  5441.5  968.11
  5591.5  974.15  5816.3  988.59  6030.9  996.43  6253.5 1001.67  6339.4 1003.03
#Mann=7,-1,0
  3837.2    0.05       0  5009.1    0.04       0  5015.2    0.05       0
  5062.5    0.12       0  5098.8    0.05       0  6030.9    0.12       0
  6253.5    0.05       0
Bank Sta=5009.1,5015.2
Exp/Cntr=0.3,0.1

Type RM Length L Ch R = 1,3612,470,470,470
BEGIN DESCRIPTION:
STILLHOUSE CREEK 8.0
END DESCRIPTION:
XS GIS Cut Line= 3
      2205516.09      7240256.69      2206329.00      7239610.00
      2207343.34      7238577.02
#Sta/Elev= 30
  3956.4 1004.09  4553.9  980.88  4880.6  958.73  4959.1  959.60  4973.6  955.34
  4988.9  951.44  4989.9  950.94  4995.0  951.44  5058.8  951.69  5080.0  957.69
  5115.4  954.56  5167.7  955.72  5476.0  959.80  5560.9  967.07  5645.7  966.81
  5652.9  971.24  5674.0  968.28  5744.7  972.46  5801.3  971.63  5822.5  977.14
  5828.7  976.04  5872.0  978.36  5886.2  981.89  5900.3  979.27  6282.2  998.54
  6345.8 1005.02  6381.2 1004.38  6402.4 1007.74  6425.6 1005.97  6442.9 1006.31
#Mann=7,-1,0
  3956.4    0.05       0  4973.6    0.12       0  4988.9    0.07       0
  4995.0    0.12       0  5167.7    0.05       0  5828.7    0.12       0
  6425.6    0.05       0
Bank Sta=4988.9,4995
Exp/Cntr=0.3,0.1

Type RM Length L Ch R = 1,3142,301,301,301
BEGIN DESCRIPTION:
STILLHOUSE CREEK 7.0
END DESCRIPTION:
XS GIS Cut Line= 3
      2205865.05      7240530.26      2206629.00      7239960.00
      2207603.53      7238984.49
#Sta/Elev= 30
  4047.1 1001.55  4292.6  994.06  4342.7  989.99  4421.9  977.43  4478.2  977.92
  4607.4  965.19  4657.5  962.31  4713.8  961.81  4836.8  955.38  4936.8  953.10
  4950.5  957.79  4978.5  949.13  4990.0  948.70  4991.0  948.20  4996.3  948.70
  5028.7  949.37  5041.4  952.55  5134.3  951.96  5460.0  954.19  5544.9  958.13
  5559.0  962.39  5580.2  964.63  5608.5  959.84  5622.7  963.91  5636.8  965.00
  5819.7  976.02  5898.4  983.89  5987.9  986.62  6266.1 1002.94  6379.3 1001.78
#Mann=7,-1,0
  4047.1    0.05       0  4990.0    0.04       0  4996.3    0.05       0
  5041.4    0.12       0  5134.3    0.05       0  5819.7    0.12       0
  5987.9    0.05       0
Bank Sta=4990,4996.3
Exp/Cntr=0.3,0.1