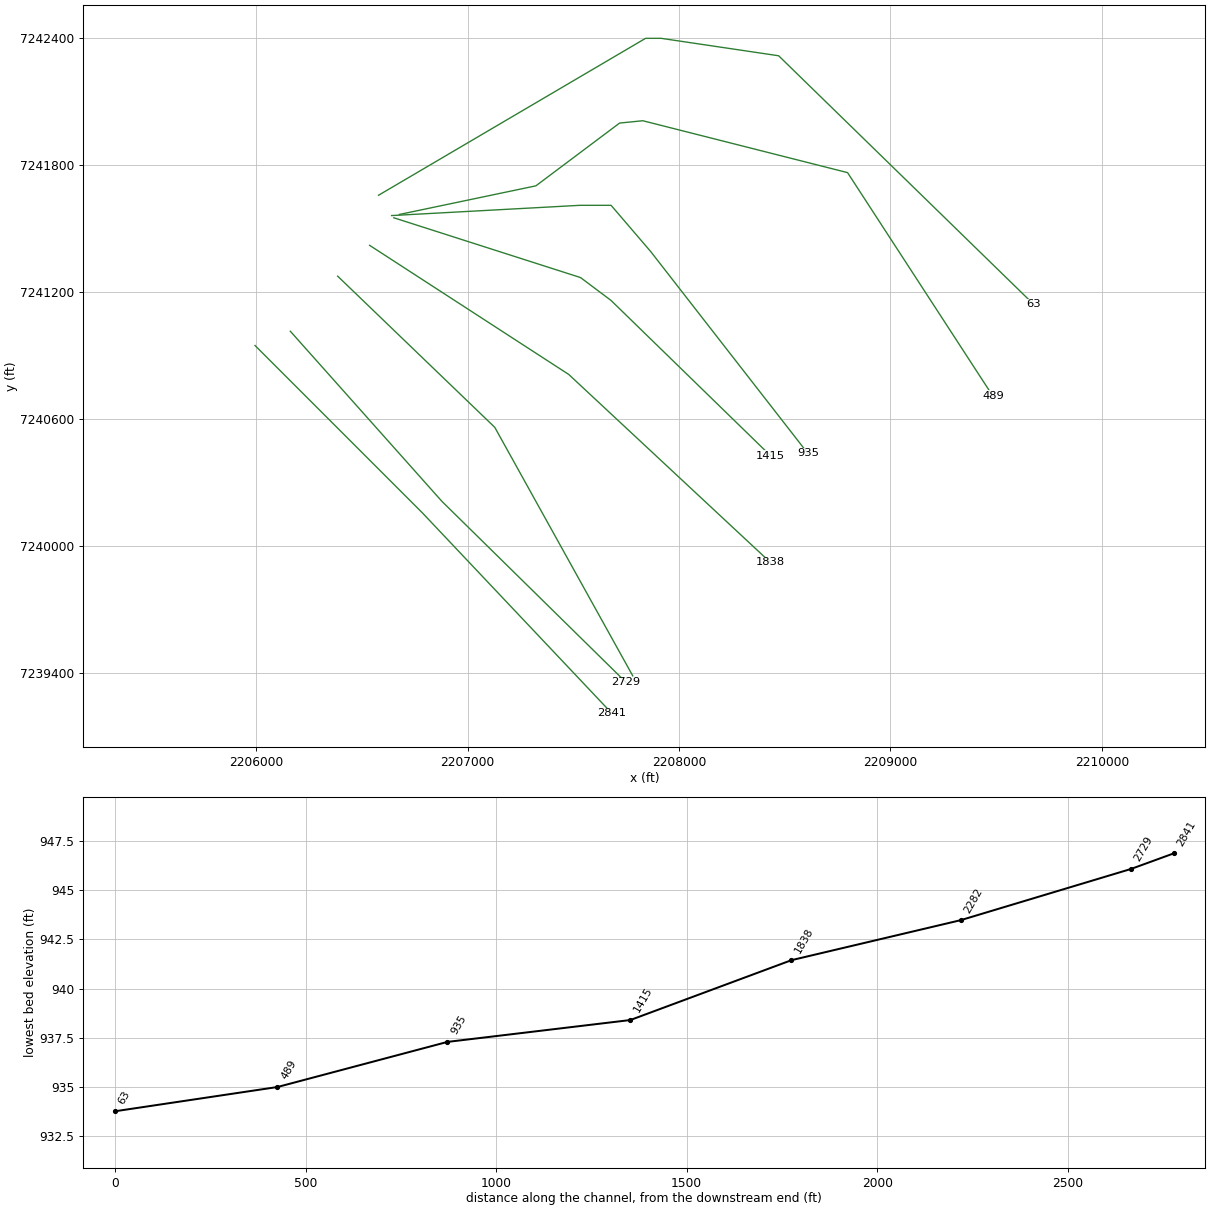
HEC-RAS study STILLHOUSE CREEK.prj: STILLHOUSE CREEK Base Level Engineering

--- STILLHOUSE CREEK.g01 (geometry) --- (continued)

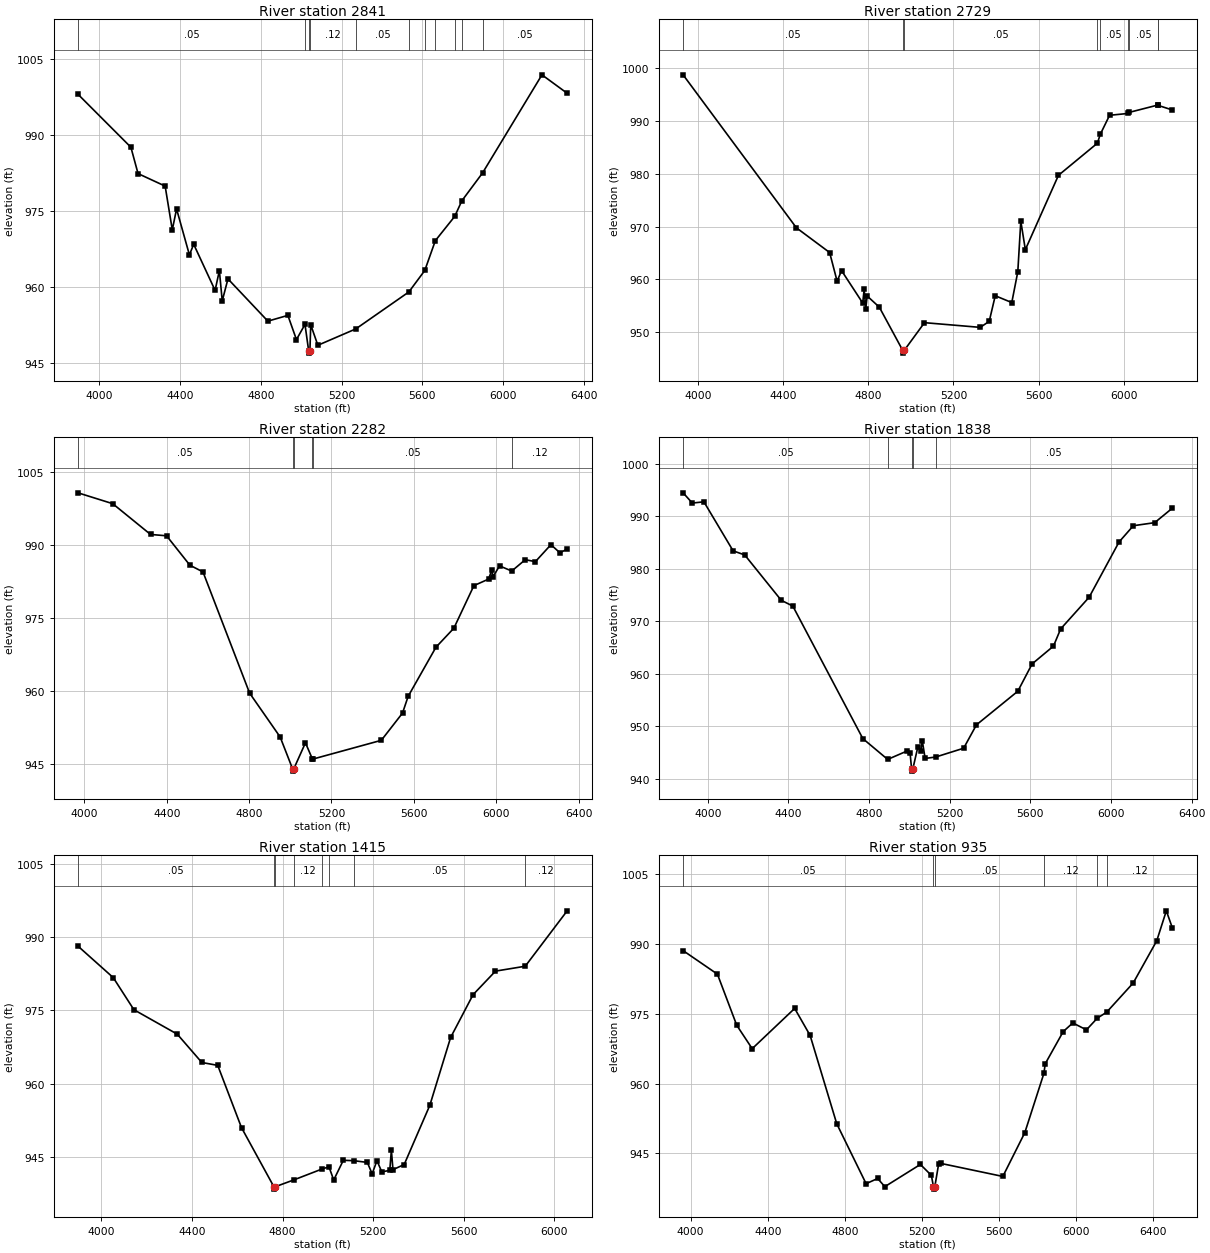
Type RM Length L Ch R = 1,2841,112,112,112
BEGIN DESCRIPTION:
STILLHOUSE CREEK 6.5
END DESCRIPTION:
XS GIS Cut Line= 3
      2205995.24      7240946.94      2206786.92      7240155.26
      2207682.79      7239207.31
#Sta/Elev= 30
  3893.7  997.94  4155.8  987.49  4191.2  982.29  4325.5  979.82  4360.9  971.19
  4382.1  975.31  4445.7  966.25  4467.0  968.34  4573.0  959.24  4594.2  963.15
  4608.4  957.16  4636.7  961.51  4834.6  953.17  4933.6  954.31  4976.1  949.53
  5018.4  952.53  5036.5  947.36  5037.6  946.86  5042.8  947.36  5047.0  952.44
  5082.2  948.41  5270.3  951.64  5533.0  958.93  5612.0  963.17  5664.4  969.06
  5760.3  973.84  5795.8  976.93  5898.0  982.40  6192.6 1001.78  6317.6  998.14
#Mann=11,-1,0
  3893.7    0.05       0  5018.4    0.12       0  5036.5    0.04       0
  5042.8    0.12       0  5270.3    0.05       0  5533.0    0.12       0
  5612.0    0.05       0  5664.4    0.12       0  5760.3    0.05       0
  5795.8    0.12       0  5898.0    0.05       0
Bank Sta=5036.5,5042.8
Exp/Cntr=0.3,0.1

Type RM Length L Ch R = 1,2729,447,447,447
BEGIN DESCRIPTION:
STILLHOUSE CREEK 6.0
END DESCRIPTION:
XS GIS Cut Line= 3
      2206161.90      7241014.66      2206879.00      7240210.00
      2207749.57      7239354.05
#Sta/Elev= 30
  3929.8  998.69  4462.1  969.77  4618.4  965.09  4653.5  959.67  4674.4  961.67
  4773.9  955.54  4780.6  958.12  4788.1  954.46  4794.8  956.87  4851.7  954.77
  4962.1  946.57  4963.2  946.07  4968.6  946.57  5064.1  951.83  5325.9  950.94
  5368.3  952.08  5396.6  956.92  5474.3  955.63  5502.6  961.46  5516.7  971.03
  5538.0  965.63  5693.6  979.69  5876.5  985.76  5890.3  987.45  5933.9  991.04
  6019.2  991.38  6026.2  991.59  6161.8  992.99  6162.8  992.90  6228.5  992.05
#Mann=9,-1,0
  3929.8    0.05       0  4962.1   0.033       0  4968.6    0.05       0
  5876.5    0.12       0  5890.3    0.05       0  6019.2    0.12       0
  6026.2    0.05       0  6161.8    0.12       0  6162.8    0.05       0
Bank Sta=4962.1,4968.6
Exp/Cntr=0.3,0.1

Type RM Length L Ch R = 1,2282,444,444,444
BEGIN DESCRIPTION:
STILLHOUSE CREEK 5.0
END DESCRIPTION:
XS GIS Cut Line= 3
      2206385.91      7241275.02      2207129.00      7240560.00
      2207781.54      7239384.74
#Sta/Elev= 30
  3969.0 1000.65  4137.5  998.42  4321.2  992.10  4399.1  991.82  4512.3  985.78
  4575.9  984.40  4802.3  959.50  4950.7  950.48  5010.7  943.97  5011.8  943.47
  5017.2  943.97  5073.5  949.29  5107.0  945.99  5110.7  945.96  5441.9  949.80
  5544.8  955.39  5572.3  958.84  5707.3  968.93  5794.3  972.84  5891.5  981.58
  5962.5  982.92  5978.5  984.78  5984.2  983.40  6016.2  985.64  6075.3  984.58
  6140.9  986.91  6190.1  986.51  6265.6  990.00  6309.1  988.33  6344.5  989.09
#Mann=6,-1,0
  3969.0    0.05       0  5010.7    0.04       0  5017.2    0.05       0
  5107.0    0.12       0  5110.7    0.05       0  6075.3    0.12       0
Bank Sta=5010.7,5017.2
Exp/Cntr=0.3,0.1

Type RM Length L Ch R = 1,1838,423,423,423
BEGIN DESCRIPTION:
STILLHOUSE CREEK 4.0
END DESCRIPTION:
XS GIS Cut Line= 3
      2206536.95      7241420.86      2207479.00      7240810.00
      2208432.77      7239920.87
#Sta/Elev= 30
  3877.2  994.42  3923.0  992.47  3980.4  992.71  4125.4  983.37  4182.8  982.60
  4364.1  973.96  4421.5  972.86  4768.9  947.63  4892.0  943.67  4986.4  945.24
  5003.4  944.80  5010.5  941.94  5011.6  941.44  5017.3  941.94  5042.2  946.12
  5056.4  945.23  5063.7  947.21  5077.9  943.86  5129.8  944.12  5268.9  945.80
  5332.4  950.25  5537.6  956.65  5608.5  961.85  5714.5  965.24  5750.1  968.51
  5891.3  974.54  6039.8  985.06  6110.7  988.16  6216.7  988.74  6303.9  991.49
#Mann=5,-1,0
  3877.2    0.05       0  4892.0    0.12       0  5010.5    0.07       0
  5017.3    0.12       0  5129.8    0.05       0
Bank Sta=5010.5,5017.3
Exp/Cntr=0.3,0.1

Type RM Length L Ch R = 1,1415,480,480,480
BEGIN DESCRIPTION:
STILLHOUSE CREEK 3.0
END DESCRIPTION:
XS GIS Cut Line= 4
      2206651.50      7241551.09      2207534.51      7241268.36
      2207679.00      7241160.00      2208432.75      7240426.10
#Sta/Elev= 30
  3896.5  988.13  4052.1  981.69  4143.3  975.12  4334.9  970.11  4443.2  964.32
  4513.4  963.73  4618.4  950.98  4761.2  938.90  4762.3  938.40  4768.0  938.90
  4849.5  940.29  4975.8  942.55  5004.6  942.96  5025.5  940.27  5067.9  944.30
  5114.2  944.22  5173.9  943.87  5195.2  941.53  5216.4  944.22  5237.7  941.94
  5273.0  942.23  5280.1  946.39  5287.1  942.38  5336.7  943.44  5449.9  955.56
  5541.7  969.44  5640.8  978.20  5739.8  983.02  5871.1  984.02  6056.3  995.36
#Mann=8,-1,0
  3896.5    0.05       0  4761.2   0.033       0  4768.0    0.05       0
  4849.5    0.12       0  4975.8    0.05       0  5004.6    0.12       0
  5114.2    0.05       0  5871.1    0.12       0
Bank Sta=4761.2,4768
Exp/Cntr=0.3,0.1

Type RM Length L Ch R = 1,935,446,446,446
BEGIN DESCRIPTION:
STILLHOUSE CREEK 2.0
END DESCRIPTION:
XS GIS Cut Line= 5
      2206641.12      7241561.51      2207531.72      7241610.00
      2207679.00      7241610.00      2207865.95      7241391.89
      2208609.84      7240436.51
#Sta/Elev= 30
  3960.8  988.61  4138.9  983.54  4239.1  972.54  4319.2  967.51  4539.5  976.17
  4619.6  970.36  4757.8  951.35  4910.0  938.46  4970.0  939.58  5007.1  937.82
  5191.5  942.60  5248.6  940.25  5259.4  937.79  5260.5  937.29  5266.3  937.79
  5285.8  942.59  5298.2  942.82  5619.2  940.02  5733.2  949.44  5832.1  962.18
  5839.2  964.27  5932.4  971.19  5982.2  973.05  6052.8  971.56  6109.6  974.09
  6157.4  975.35  6295.2  981.63  6417.4  990.71  6467.2  997.17  6498.1  993.54
#Mann=6,-1,0
  3960.8    0.05       0  5259.4   0.033       0  5266.3    0.05       0
  5832.1    0.12       0  6109.6    0.05       0  6157.4    0.12       0
Bank Sta=5259.4,5266.3
Exp/Cntr=0.3,0.1

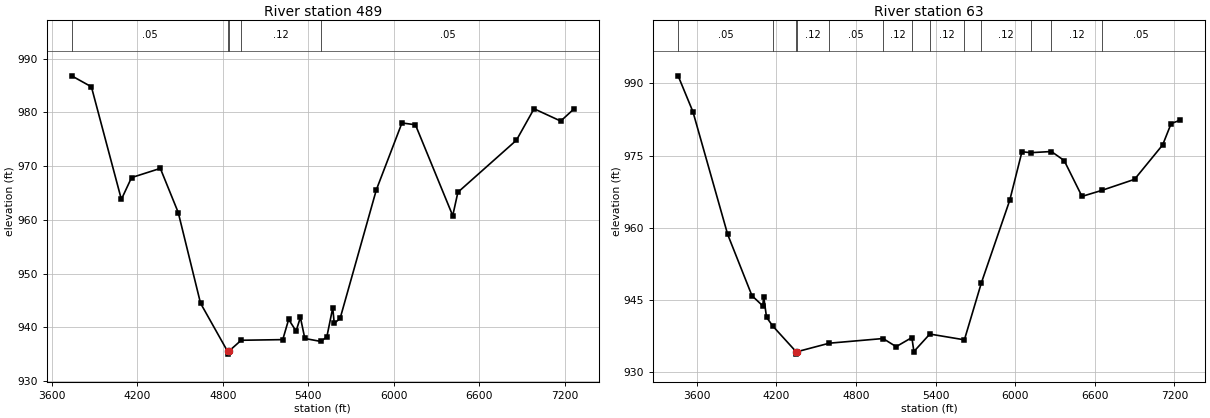
Type RM Length L Ch R = 1,489,426,426,426
BEGIN DESCRIPTION:
STILLHOUSE CREEK 1.0
END DESCRIPTION:
XS GIS Cut Line= 6
      2206677.56      7241566.72      2207323.38      7241702.13
      2207719.22      7241999.01      2207829.00      7242010.00
      2208797.34      7241764.63      2209484.41      7240708.01
#Sta/Elev= 30
  3739.8  986.80  3878.4  984.76  4088.7  963.80  4160.2  967.86  4362.2  969.57
  4487.9  961.35  4644.2  944.48  4834.4  935.50  4835.5  935.00  4841.3  935.50
  4929.5  937.58  5221.4  937.70  5262.7  941.46  5314.8  939.29  5345.2  941.84
  5376.2  937.91  5488.9  937.36  5530.9  938.24  5572.2  943.63  5582.5  940.73
  5623.8  941.64  5878.3  965.60  6057.8  978.03  6152.4  977.69  6414.2  960.77
  6450.4  965.13  6861.0  974.81  6984.8  980.67  7171.9  978.38  7264.1  980.62
#Mann=5,-1,0
  3739.8    0.05       0  4834.4    0.07       0  4841.3    0.05       0
  4929.5    0.12       0  5488.9    0.05       0
Bank Sta=4834.4,4841.3
Exp/Cntr=0.3,0.1

Type RM Length L Ch R = 1,63,0,0,0
BEGIN DESCRIPTION:
STILLHOUSE CREEK 0.5
END DESCRIPTION:
XS GIS Cut Line= 5
      2206579.12      7241657.53      2207842.12      7242399.71
      2207915.91      7242399.71      2208471.46      7242317.24
      2209678.06      7241141.02
#Sta/Elev= 30
  3459.4  991.57  3571.1  984.11  3832.8  958.64  4016.0  945.91  4097.2  943.80
  4104.4  945.73  4125.9  941.41  4174.9  939.54  4348.9  934.27  4350.0  933.77
  4355.8  934.27  4598.5  936.04  5004.4  937.01  5102.8  935.32  5221.3  937.21
  5236.7  934.31  5356.7  937.94  5617.3  936.74  5745.6  948.60  5959.2  965.73
  6051.1  975.80  6117.9  975.61  6273.0  975.85  6369.3  973.98  6503.7  966.53
  6653.3  967.78  6899.6  970.07  7111.8  977.22  7175.6  981.65  7244.8  982.37
#Mann=13,-1,0
  3459.4    0.05       0  4174.9    0.12       0  4348.9   0.033       0
  4355.8    0.12       0  4598.5    0.05       0  5004.4    0.12       0
  5221.3    0.05       0  5356.7    0.12       0  5617.3    0.05       0
  5745.6    0.12       0  6117.9    0.05       0  6273.0    0.12       0
  6653.3    0.05       0
Bank Sta=4348.9,4355.8
Exp/Cntr=0.3,0.1

Chan Stop Cuts=-1