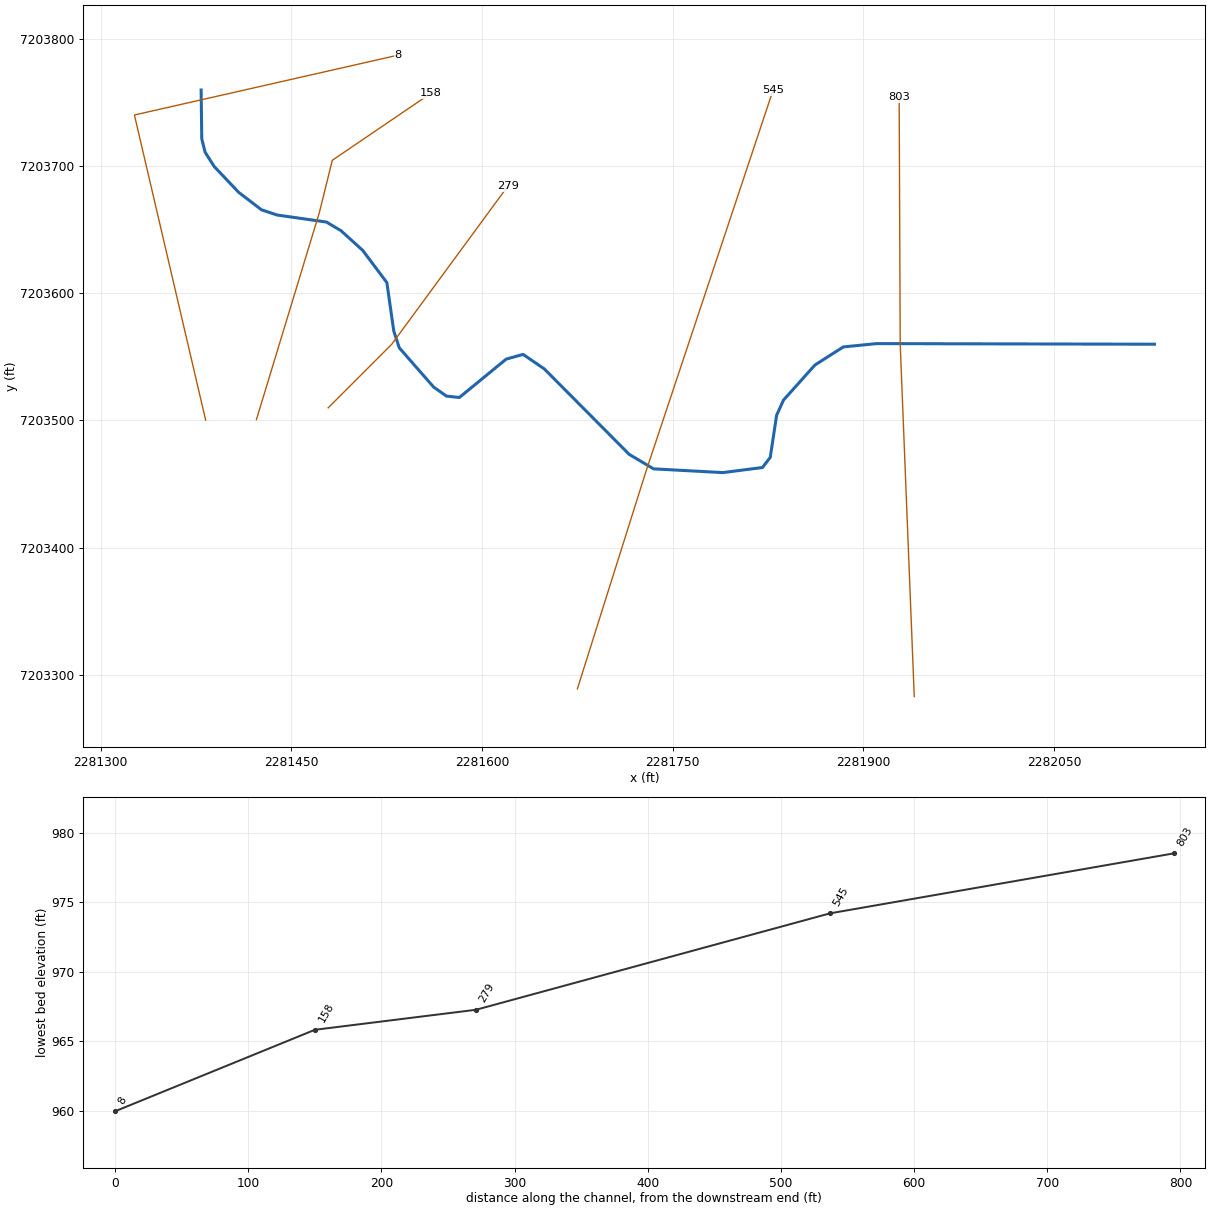
--- UDS St 02.prj (project) ---

Proj Title=UDS St 02 Base Level Engineering
Current Plan=p01
Default Exp/Contr=0.3,0.1
English Units
Geom File=g01
Flow File=f01
Plan File=p01
Y Axis Title=Elevation
X Axis Title(PF)=Main Channel Distance
X Axis Title(XS)=Station
BEGIN DESCRIPTION:
UDS St 02
END DESCRIPTION:
DSS Export Rating Curves= 0
DSS Export Rating Curve Sorted= 0
DSS Export Volume Flow Curves= 0
DXF OffsetX= 0
DXF OffsetY= 0
DXF ScaleX= 1
DXF ScaleY= 10

--- UDS St 02.p01 (plan) ---

Plan Title=Multiple Run
Short Identifier=Multiple
Geom File=g01
Flow File=f01
Subcritical Flow
K Sum by GR= 0
Std Step Tol= 0.01
Critical Tol= 0.01
Num of Std Step Trials= 20
Max Error Tol= 0.3
Flow Tol Ratio= 0.001
Split Flow NTrial= 30
Split Flow Tol= 0.02
Split Flow Ratio= 0.02
Log Output Level= 0
Friction Slope Method= 1
Unsteady Friction Slope Method= 2
Unsteady Bridges Friction Slope Method= 1
Parabolic Critical Depth
Global Vel Dist=  1 , 1 , 1
Global Log Level= 0
CheckData=True
Encroach Param= -1, 0, 0, 0
BEGIN DESCRIPTION:
Multiple Run
END DESCRIPTION:

--- UDS St 02.f01 (steady flow) ---

Flow Title=Multiple
Program Version=4.10
Number of Profiles= 7
Profile Names=10-year,25-year,50-year,1pct_min,100-year,1pct_plu,500-year
River Rch & RM=UDS St 02,Reach-1         ,803
     214     276     325     191     380     759     521
River Rch & RM=UDS St 02,Reach-1         ,8
    1075    1527    1911    1187    2368    4724    3643
Boundary for River Rch & Prof#=UDS St 02,Reach-1         , 1
Up Type= 0
Dn Type= 3
Dn Slope=0.007
Boundary for River Rch & Prof#=UDS St 02,Reach-1         , 2
Up Type= 0
Dn Type= 3
Dn Slope=0.007
Boundary for River Rch & Prof#=UDS St 02,Reach-1         , 3
Up Type= 0
Dn Type= 3
Dn Slope=0.007
Boundary for River Rch & Prof#=UDS St 02,Reach-1         , 4
Up Type= 0
Dn Type= 3
Dn Slope=0.007
Boundary for River Rch & Prof#=UDS St 02,Reach-1         , 5
Up Type= 0
Dn Type= 3
Dn Slope=0.007
Boundary for River Rch & Prof#=UDS St 02,Reach-1         , 6
Up Type= 0
Dn Type= 3
Dn Slope=0.007
Boundary for River Rch & Prof#=UDS St 02,Reach-1         , 7
Up Type= 0
Dn Type= 3
Dn Slope=0.007
DSS Import GetInterval= 0
DSS Import GetPeak= 0
DSS Import FillOption= 0

--- UDS St 02.g01 (geometry) ---

Geom Title=Existing Conditions
Program Version=4.10

River Reach=UDS St 02       ,Reach-1
Reach XY= 30
        2282129.        7203560.      2281910.57      7203560.48
      2281884.27      7203557.88       2281861.9      7203543.64
      2281837.17      7203516.02      2281831.75      7203504.08
      2281826.76      7203470.99      2281820.65        7203463.
      2281789.44        7203459.      2281734.98      7203461.94
      2281715.73      7203473.38      2281648.98      7203540.58
      2281632.32      7203551.98      2281618.98      7203548.28
      2281582.15      7203518.08      2281572.05      7203519.19
      2281561.96      7203526.24      2281534.87      7203557.19
      2281530.57      7203570.36      2281525.11      7203608.51
      2281506.14      7203633.82      2281488.99      7203649.36
      2281477.56      7203656.13      2281438.72      7203661.67
      2281426.52      7203665.72      2281408.54      7203679.51
      2281389.33      7203699.75      2281382.14      7203711.03
       2281379.5      7203721.62        2281379.        7203760.

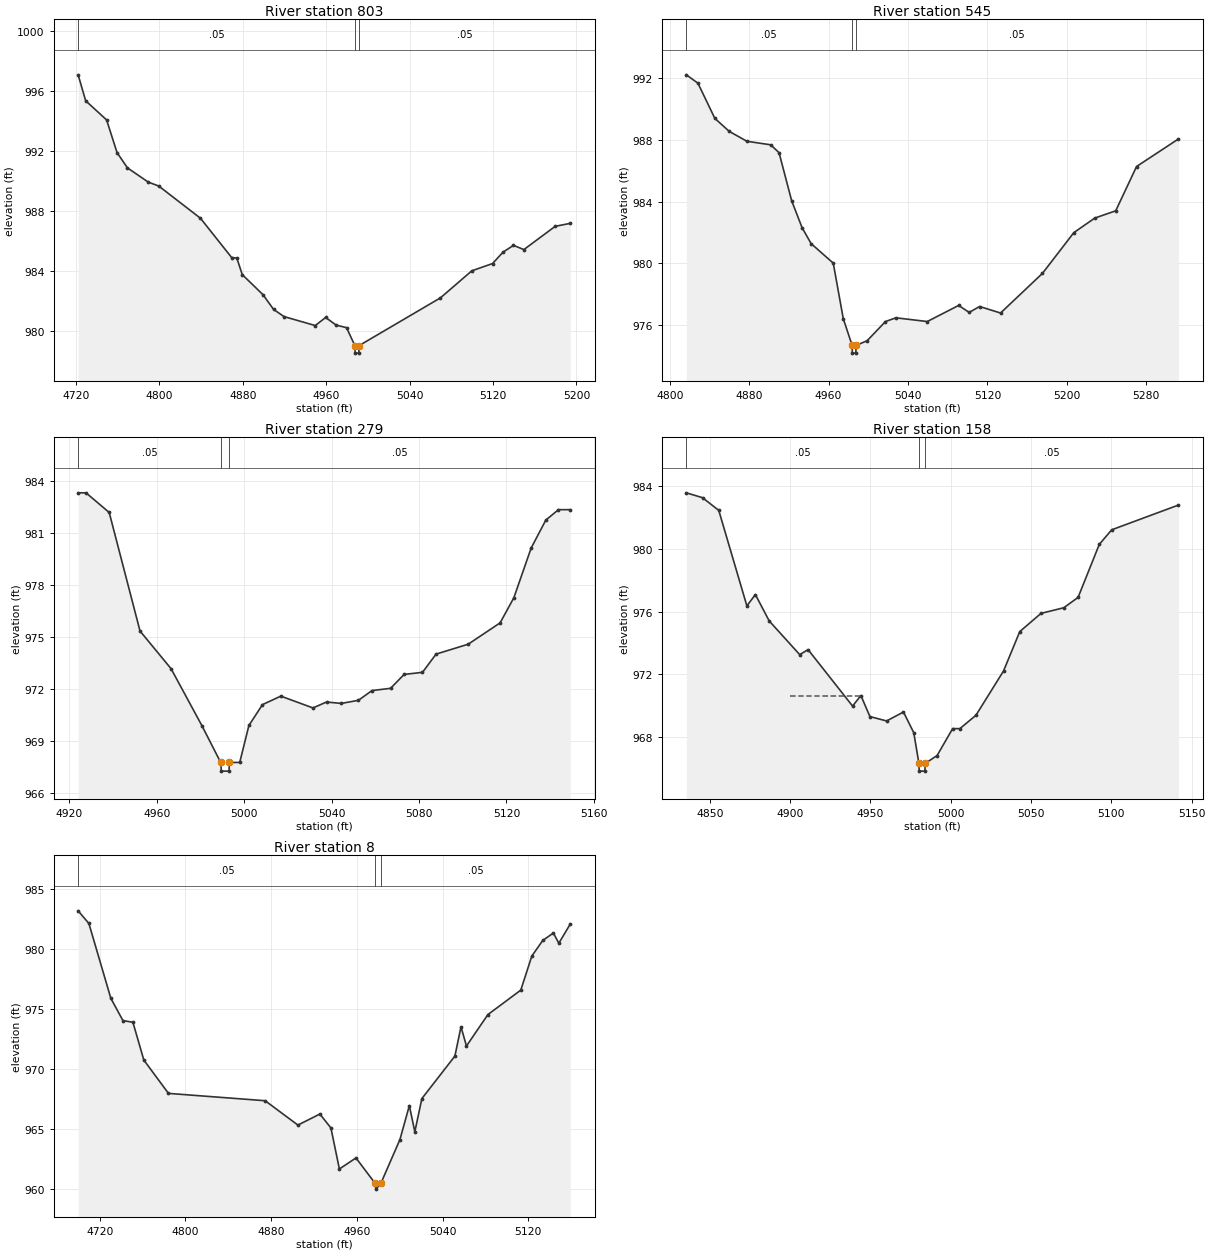
Type RM Length L Ch R = 1 ,803     ,258,258,258
BEGIN DESCRIPTION:
UDS St 02 3.0
END DESCRIPTION:
XS GIS Cut Line= 3
      2281940.05      7203282.77        2281929.        7203560.
      2281928.18      7203754.55
#Sta/Elev= 30
  4722.1  997.09  4729.3  995.36  4749.4  994.08  4759.4   991.9  4769.4  990.88
  4789.4  989.93  4799.4  989.67  4839.4  987.52  4869.3   984.9  4874.3  984.86
  4879.5  983.76  4899.5  982.41  4909.5  981.44  4919.5  980.96  4949.5  980.36
  4959.5   980.9  4969.5  980.39  4979.5  980.22  4987.5  979.02  4987.8  978.52
  4991.3  978.52  4991.5  979.02  5069.6  982.21  5099.6  984.01  5119.6   984.5
  5129.6  985.26  5139.6  985.71  5149.6  985.43  5179.6  986.98  5194.1  987.18
#Mann= 3 ,-1 , 0
  4722.1     .05       0  4987.5    .033       0  4991.5     .05       0
Bank Sta=4987.5,4991.5
XS Rating Curve= 0 ,0
Exp/Cntr=0.3,0.1

Type RM Length L Ch R = 1 ,545     ,266,266,266
BEGIN DESCRIPTION:
UDS St 02 2.0
END DESCRIPTION:
XS GIS Cut Line= 3
      2281675.01      7203288.84        2281729.        7203460.
        2281829.        7203760.
#Sta/Elev= 30
  4816.7  992.18  4828.4  991.64  4845.4  989.37  4859.9  988.53  4877.7  987.89
  4901.8  987.66  4910.1  987.15  4922.8  984.05  4933.3  982.31  4942.4  981.28
  4964.7  980.02  4974.8  976.43  4983.7  974.71  4983.9  974.21  4987.4  974.21
  4987.7  974.71  4998.8  975.01  5017.3  976.25  5027.8  976.49  5059.4  976.25
    5091  977.29  5101.6  976.84  5112.1  977.22  5133.2   976.8  5175.4  979.36
    5207  981.99  5228.1  982.93  5249.2   983.4  5270.2  986.26  5312.4  988.04
#Mann= 3 ,-1 , 0
  4816.7     .05       0  4983.7    .033       0  4987.7     .05       0
Bank Sta=4983.7,4987.7
XS Rating Curve= 0 ,0
Exp/Cntr=0.3,0.1

Type RM Length L Ch R = 1 ,279     ,121,121,121
BEGIN DESCRIPTION:
UDS St 02 1.0
END DESCRIPTION:
XS GIS Cut Line= 3
      2281478.97      7203509.97        2281529.        7203560.
      2281620.34      7203684.42
#Sta/Elev= 30
  4924.1   983.3  4927.7   983.3  4938.3  982.17  4952.4  975.34  4966.6  973.17
  4980.7  969.89  4989.3  967.77  4989.6  967.27  4993.1  967.27  4993.3  967.77
    4998  967.77  5002.2   969.9  5008.4   971.1  5016.8  971.59  5031.5  970.91
  5037.7  971.25  5044.5  971.17  5052.3  971.35  5058.5  971.91    5067  972.04
  5073.2  972.84  5081.6  972.96  5087.8  974.01  5102.5  974.58  5117.1  975.81
  5123.4  977.26  5131.3  980.12    5138  981.73  5143.8  982.33  5149.2  982.33
#Mann= 3 ,-1 , 0
  4924.1     .05       0  4989.3    .033       0  4993.3     .05       0
#XS Ineff= 2 , 0
       0                  5016.8       0  971.59
Permanent Ineff=
       F       F
Bank Sta=4989.3,4993.3
XS Rating Curve= 0 ,0
Exp/Cntr=0.3,0.1

Type RM Length L Ch R = 1 ,158     ,150,150,150
BEGIN DESCRIPTION:
UDS St 02 0.8
END DESCRIPTION:
XS GIS Cut Line= 4
      2281422.49      7203500.68      2281472.03      7203663.65
      2281482.19      7203704.69      2281559.75      7203757.42
#Sta/Elev= 30
  4835.4  983.58  4845.5  983.27  4855.6  982.46  4873.1  976.37  4878.4  977.09
    4887  975.41    4906  973.26  4911.2  973.58  4938.9  969.98  4944.1  970.65
  4949.7  969.31  4960.1  969.03  4970.6   969.6    4977  968.28  4980.2  966.33
  4980.4  965.83  4983.9  965.83  4984.2  966.33  4991.5  966.82  5001.2  968.54
  5005.7  968.54  5015.7  969.39  5032.9  972.22    5043  974.73  5056.2  975.89
  5070.4  976.25  5079.3  976.91  5092.5  980.29  5100.2  981.22  5141.8   982.8
#Mann= 3 ,-1 , 0
  4835.4     .05       0  4980.2    .033       0  4984.2     .05       0
#XS Ineff= 2 ,-1
    4900    4944  970.65    4944  4970.6   969.6
Permanent Ineff=
       F       F
Bank Sta=4980.2,4984.2
XS Rating Curve= 0 ,0
Exp/Cntr=0.3,0.1

Type RM Length L Ch R = 1 ,8       ,0,0,0
BEGIN DESCRIPTION:
UDS St 02 0.9
END DESCRIPTION:
XS GIS Cut Line= 3
      2281382.55      7203500.28      2281326.51      7203740.34
      2281534.02      7203787.45
#Sta/Elev= 30
  4699.9  983.17  4709.9  982.12  4730.4  975.88  4741.7  974.02    4751  973.88
  4761.2  970.73  4784.2  967.95  4874.4  967.34    4905  965.31  4925.5  966.23
  4935.8  965.07  4943.7  961.65  4959.2  962.57  4976.9  960.47  4977.8  959.97
  4982.5  960.47  5000.2   964.1    5009  966.93  5014.1  964.75  5020.7  967.52
  5051.5  971.06  5057.2   973.5  5062.3   971.9  5082.3  974.52    5113  976.56
  5123.3   979.4  5133.5   980.7  5143.4  981.32  5148.5  980.47  5159.2  982.07
#Mann= 3 ,-1 , 0
  4699.9     .05       0  4976.9    .033       0  4982.5     .05       0
#XS Ineff= 2 , 0
       0  4925.5  966.23    5009       0  966.93
Permanent Ineff=
       F       F
Bank Sta=4976.9,4982.5
XS Rating Curve= 0 ,0
Exp/Cntr=0.3,0.1

Chan Stop Cuts=-1
Use User Specified Reach Order=0
Composite Channel Slope=5