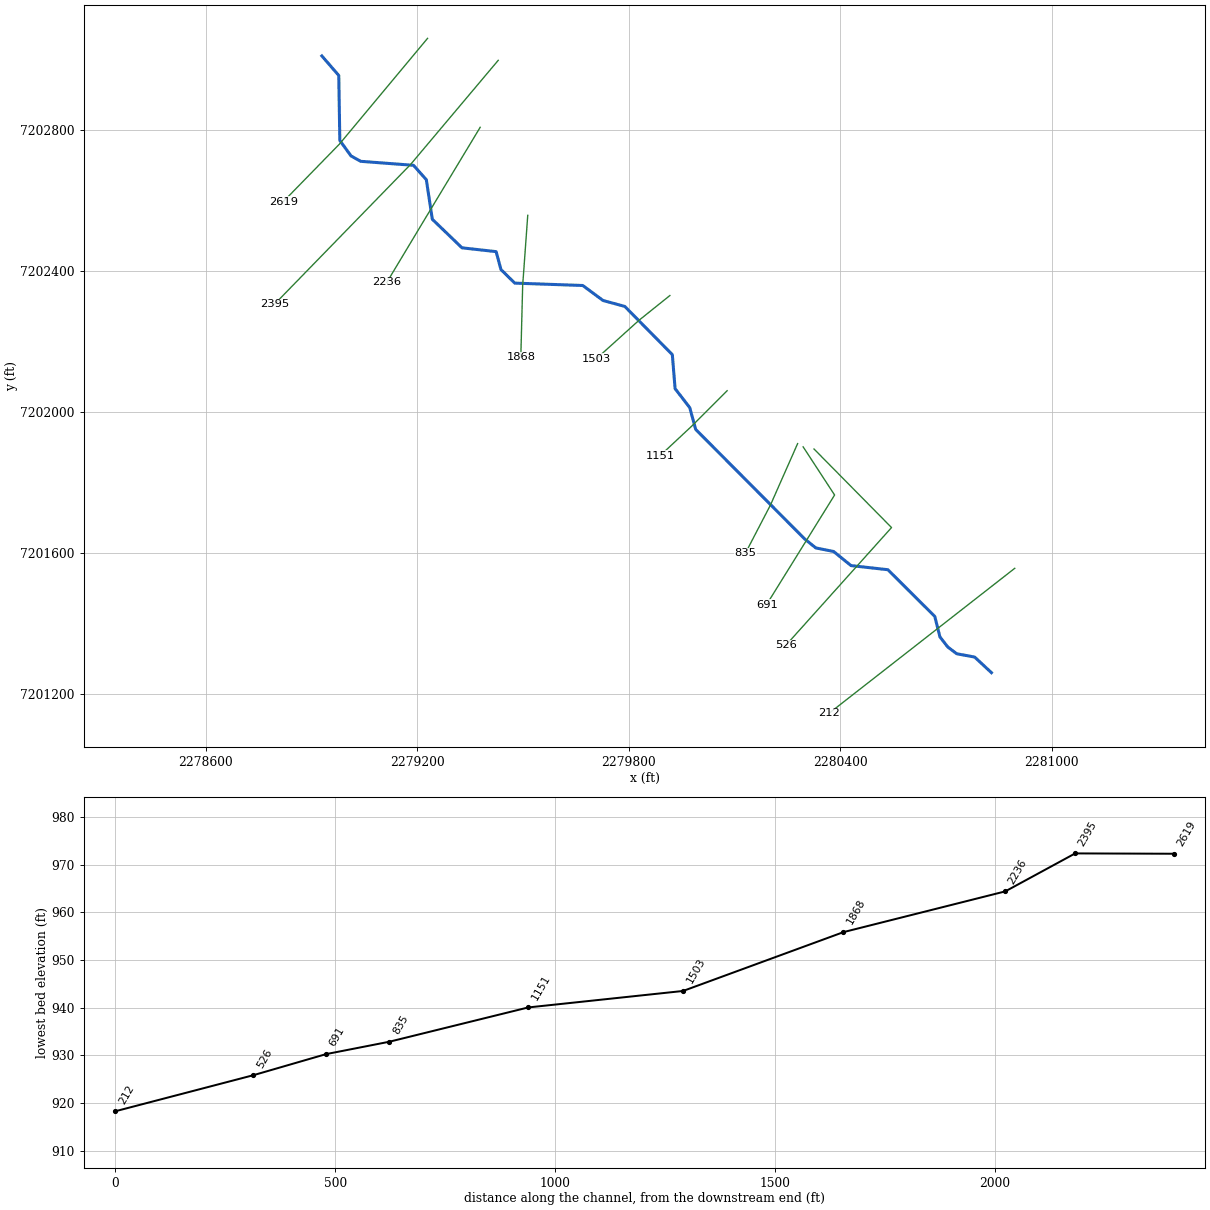
--- UDS St 03.prj (project) ---

Proj Title=UDS St 03 Base Level Engineering
Current Plan=p01
Default Exp/Contr=0.3,0.1
English Units
Geom File=g01
Flow File=f01
Plan File=p01
BEGIN DESCRIPTION:
UDS St 03
END DESCRIPTION:

--- UDS St 03.p01 (plan) ---

Plan Title=Multiple Run
Short Identifier=Multiple
Geom File=g01
Flow File=f01
Subcritical Flow
K Sum by GR= 0
Std Step Tol= 0.01
Critical Tol= 0.01
Num of Std Step Trials= 20
Max Error Tol= 0.3
Flow Tol Ratio= 0.001
Split Flow NTrial= 30
Split Flow Tol= 0.02
Split Flow Ratio= 0.02
Log Output Level= 0
Friction Slope Method= 1
Unsteady Friction Slope Method= 2
Unsteady Bridges Friction Slope Method= 1
Parabolic Critical Depth
Global Vel Dist=  1 , 1 , 1
Global Log Level= 0
CheckData=True
Encroach Param= -1, 0, 0, 0
BEGIN DESCRIPTION:
Multiple Run
END DESCRIPTION:

--- UDS St 03.f01 (steady flow) ---

Flow Title=Multiple
Number of Profiles=7
Profile Names=10-year,25-year,50-year,1pct_min,100-year,1pct_plu,500-year
River Rch & RM= UDS St 03,Reach-1,2619
     505     690     842     512    1022    2038    1504
Boundary for River Rch & Prof#=UDS St 03,Reach-1,1
Up Type=0
Dn Type=3
Dn Slope=0.005
Boundary for River Rch & Prof#=UDS St 03,Reach-1,2
Up Type=0
Dn Type=3
Dn Slope=0.005
Boundary for River Rch & Prof#=UDS St 03,Reach-1,3
Up Type=0
Dn Type=3
Dn Slope=0.005
Boundary for River Rch & Prof#=UDS St 03,Reach-1,4
Up Type=0
Dn Type=3
Dn Slope=0.005
Boundary for River Rch & Prof#=UDS St 03,Reach-1,5
Up Type=0
Dn Type=3
Dn Slope=0.005
Boundary for River Rch & Prof#=UDS St 03,Reach-1,6
Up Type=0
Dn Type=3
Dn Slope=0.005
Boundary for River Rch & Prof#=UDS St 03,Reach-1,7
Up Type=0
Dn Type=3
Dn Slope=0.005

--- UDS St 03.g01 (geometry) ---

Geom Title=Existing Conditions

River Reach=UDS St 03,Reach-1
Reach XY= 30
      2278929.00      7203010.00      2278977.00      7202954.63
      2278979.98      7202770.26      2279011.77      7202726.24
      2279039.27      7202710.99      2279189.17      7202699.67
      2279225.49      7202658.75      2279242.39      7202546.67
      2279326.62      7202465.54      2279423.51      7202454.71
      2279437.17      7202403.97      2279476.32      7202365.40
      2279669.35      7202358.64      2279726.83      7202316.14
      2279788.68      7202299.24      2279923.48      7202162.43
      2279931.33      7202065.97      2279972.86      7202012.17
      2279989.76      7201950.32      2280298.84      7201639.61
      2280330.63      7201613.94      2280381.17      7201603.86
      2280430.59      7201563.83      2280535.17      7201552.14
      2280668.22      7201419.66      2280682.88      7201361.43
      2280705.14      7201332.83      2280730.34      7201313.71
      2280781.32      7201304.28      2280829.00      7201260.00

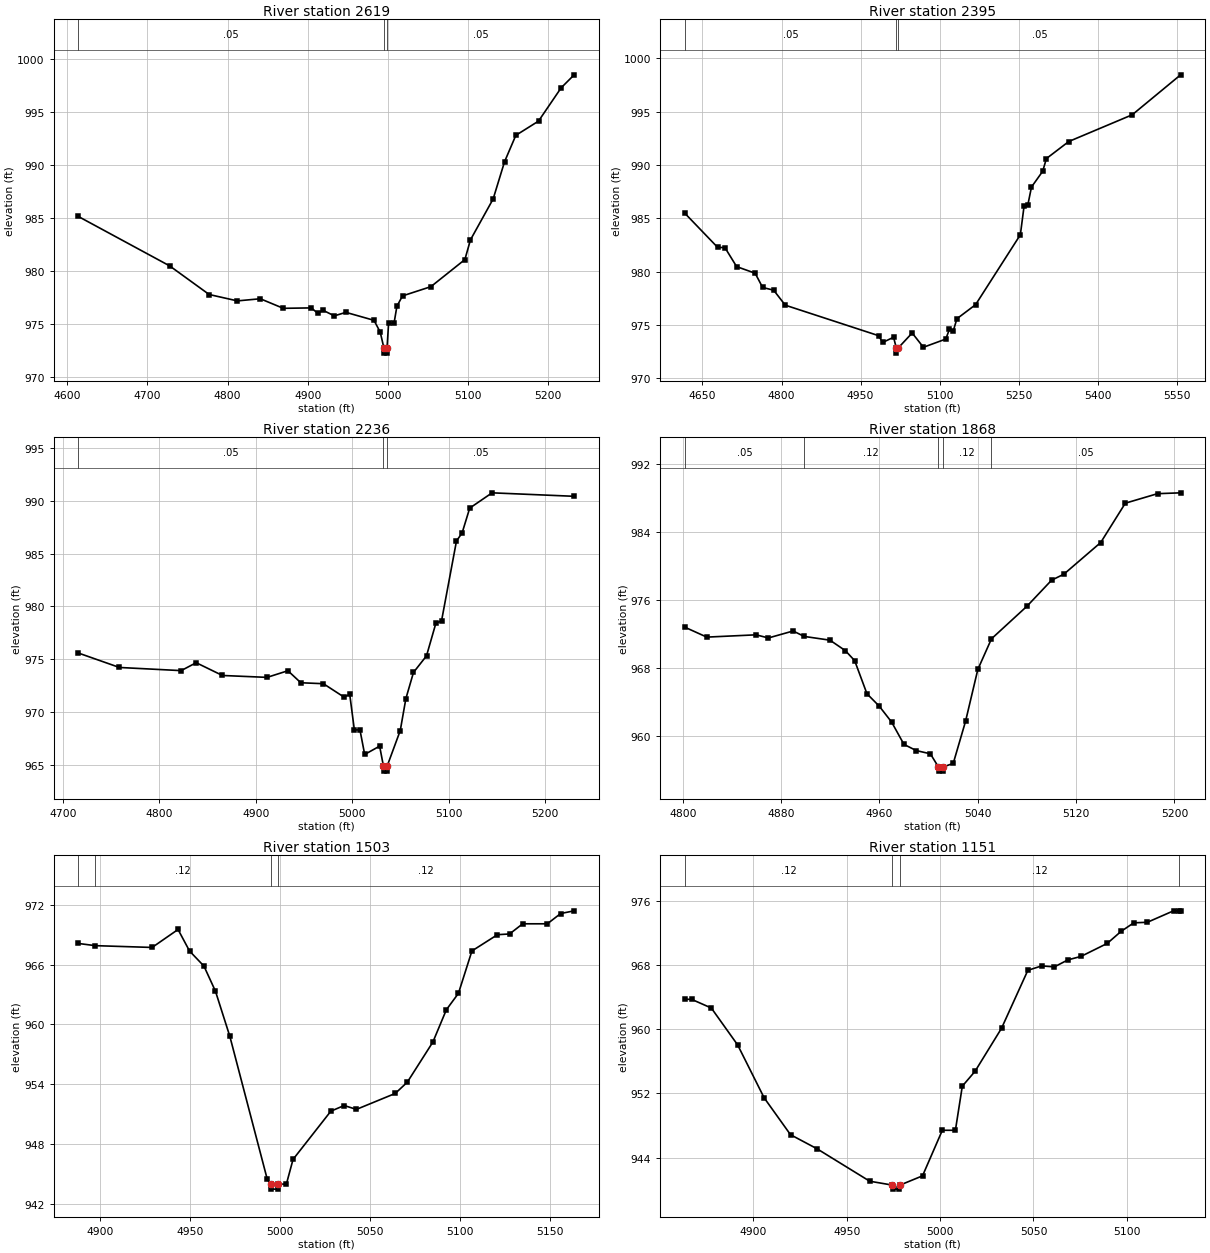
Type RM Length L Ch R = 1,2619,224,224,224
BEGIN DESCRIPTION:
UDS St 03 6.0
END DESCRIPTION:
XS GIS Cut Line= 3
      2279228.99      7203059.98      2278979.00      7202760.00
      2278819.56      7202596.59
#Sta/Elev= 30
  4613.8  985.14  4727.7  980.49  4777.1  977.79  4812.3  977.19  4840.9  977.39
  4869.6  976.49  4904.7  976.53  4912.5  976.02  4919.0  976.31  4933.3  975.78
  4947.7  976.11  4982.8  975.36  4990.6  974.24  4995.1  972.77  4995.4  972.27
  4998.9  972.27  4999.1  972.77  5001.0  975.08  5007.8  975.08  5011.4  976.69
  5018.4  977.66  5053.8  978.53  5096.2  981.08  5103.2  982.94  5131.5  986.79
  5145.7  990.29  5159.8  992.78  5188.1  994.12  5216.4  997.26  5232.6  998.48
#Mann=3,-1,0
  4613.8    0.05       0  4995.1   0.033       0  4999.1    0.05       0
Bank Sta=4995.1,4999.1
Exp/Cntr=0.3,0.1

Type RM Length L Ch R = 1,2395,159,159,159
BEGIN DESCRIPTION:
UDS St 03 5.5
END DESCRIPTION:
XS GIS Cut Line= 3
      2279429.45      7202997.58      2279181.11      7202702.52
      2278794.13      7202304.92
#Sta/Elev= 30
  4616.5  985.47  4678.7  982.27  4692.7  982.24  4714.8  980.46  4749.9  979.84
  4764.2  978.50  4785.0  978.25  4807.1  976.84  4984.0  973.98  4991.8  973.34
  5012.5  973.83  5017.6  972.84  5017.9  972.34  5021.6  972.84  5047.8  974.23
  5069.1  972.89  5111.5  973.66  5118.5  974.58  5125.7  974.42  5132.7  975.57
  5168.1  976.89  5253.0  983.45  5260.0  986.12  5267.1  986.23  5274.1  987.93
  5295.4  989.41  5302.4  990.60  5344.8  992.20  5465.2  994.71  5557.0  998.46
#Mann=3,-1,0
  4616.5    0.05       0  5017.6   0.033       0  5021.6    0.05       0
Bank Sta=5017.6,5021.6
Exp/Cntr=0.3,0.1

Type RM Length L Ch R = 1,2236,368,368,368
BEGIN DESCRIPTION:
UDS St 03 5.0
END DESCRIPTION:
XS GIS Cut Line= 3
      2279378.31      7202807.59      2279229.00      7202560.00
      2279113.10      7202367.18
#Sta/Elev= 30
  4716.0  975.58  4758.6  974.21  4822.6  973.91  4838.2  974.66  4865.4  973.45
  4911.7  973.27  4933.3  973.90  4946.7  972.76  4970.1  972.67  4991.5  971.40
  4997.4  971.66  5002.2  968.29  5008.0  968.29  5012.9  965.96  5028.4  966.75
  5032.3  964.88  5032.5  964.38  5036.0  964.38  5036.3  964.88  5049.8  968.23
  5055.6  971.25  5063.5  973.74  5077.0  975.31  5086.7  978.40  5092.6  978.63
  5108.1  986.21  5113.9  986.96  5121.8  989.32  5145.0  990.77  5230.1  990.44
#Mann=3,-1,0
  4716.0    0.05       0  5032.3   0.033       0  5036.3    0.05       0
Bank Sta=5032.3,5036.3
Exp/Cntr=0.3,0.1

Type RM Length L Ch R = 1,1868,365,365,365
BEGIN DESCRIPTION:
UDS St 03 4.0
END DESCRIPTION:
XS GIS Cut Line= 3
      2279513.23      7202557.83      2279498.83      7202358.55
      2279493.54      7202155.02
#Sta/Elev= 30
  4801.6  972.79  4819.5  971.62  4859.6  971.89  4869.6  971.52  4889.7  972.34
  4898.8  971.70  4919.7  971.26  4932.2  970.03  4939.8  968.85  4949.8  964.95
  4959.8  963.49  4969.9  961.61  4979.9  958.99  4989.9  958.26  5001.4  957.88
  5007.9  956.34  5008.2  955.84  5011.7  955.84  5011.9  956.34  5020.0  956.75
  5030.0  961.70  5040.0  967.81  5051.1  971.42  5080.0  975.26  5100.0  978.32
  5110.0  979.03  5140.0  982.76  5160.0  987.39  5186.2  988.51  5205.0  988.61
#Mann=5,-1,0
  4801.6    0.05       0  4898.8    0.12       0  5007.9    0.07       0
  5011.9    0.12       0  5051.1    0.05       0
Bank Sta=5007.9,5011.9
Exp/Cntr=0.3,0.1

Type RM Length L Ch R = 1,1503,352,352,352
BEGIN DESCRIPTION:
UDS St 03 3.0
END DESCRIPTION:
XS GIS Cut Line= 3
      2279916.58      7202330.16      2279829.00      7202260.00
      2279707.76      7202150.63
#Sta/Elev= 30
  4888.0  968.12  4897.4  967.90  4929.0  967.72  4943.4  969.52  4949.8  967.36
  4957.8  965.85  4964.2  963.33  4972.2  958.80  4993.0  944.47  4995.0  944.00
  4995.3  943.50  4998.8  943.50  4999.0  944.00  5003.6  944.00  5007.3  946.48
  5028.3  951.31  5035.7  951.88  5042.5  951.49  5064.1  953.09  5070.8  954.22
  5085.0  958.24  5092.5  961.48  5099.2  963.12  5106.7  967.37  5120.9  969.00
  5127.6  969.07  5134.9  970.09  5148.6  970.09  5156.0  971.12  5163.5  971.39
#Mann=4,-1,0
  4888.0    0.05       0  4897.4    0.12       0  4995.0    0.07       0
  4999.0    0.12       0
Bank Sta=4995,4999
Exp/Cntr=0.3,0.1

Type RM Length L Ch R = 1,1151,316,316,316
BEGIN DESCRIPTION:
UDS St 03 2.0
END DESCRIPTION:
XS GIS Cut Line= 3
      2280079.03      7202060.03      2279979.00      7201960.00
      2279888.34      7201875.36
#Sta/Elev= 30
  4863.3  963.76  4866.9  963.76  4877.5  962.67  4891.6  958.06  4905.8  951.45
  4919.9  946.85  4934.1  945.09  4962.3  941.04  4974.5  940.55  4974.7  940.05
  4978.2  940.05  4978.5  940.55  4990.6  941.71  5001.2  947.40  5008.2  947.40
  5011.9  952.91  5018.7  954.76  5032.9  960.14  5047.0  967.38  5054.4  967.93
  5061.2  967.81  5068.5  968.69  5075.4  969.11  5089.5  970.74  5096.9  972.24
  5103.7  973.31  5111.0  973.38  5125.0  974.81  5128.0  974.81  5128.8  974.81
#Mann=4,-1,0
  4863.3    0.12       0  4974.5    0.07       0  4978.5    0.12       0
  5128.0    0.05       0
Bank Sta=4974.5,4978.5
Exp/Cntr=0.3,0.1

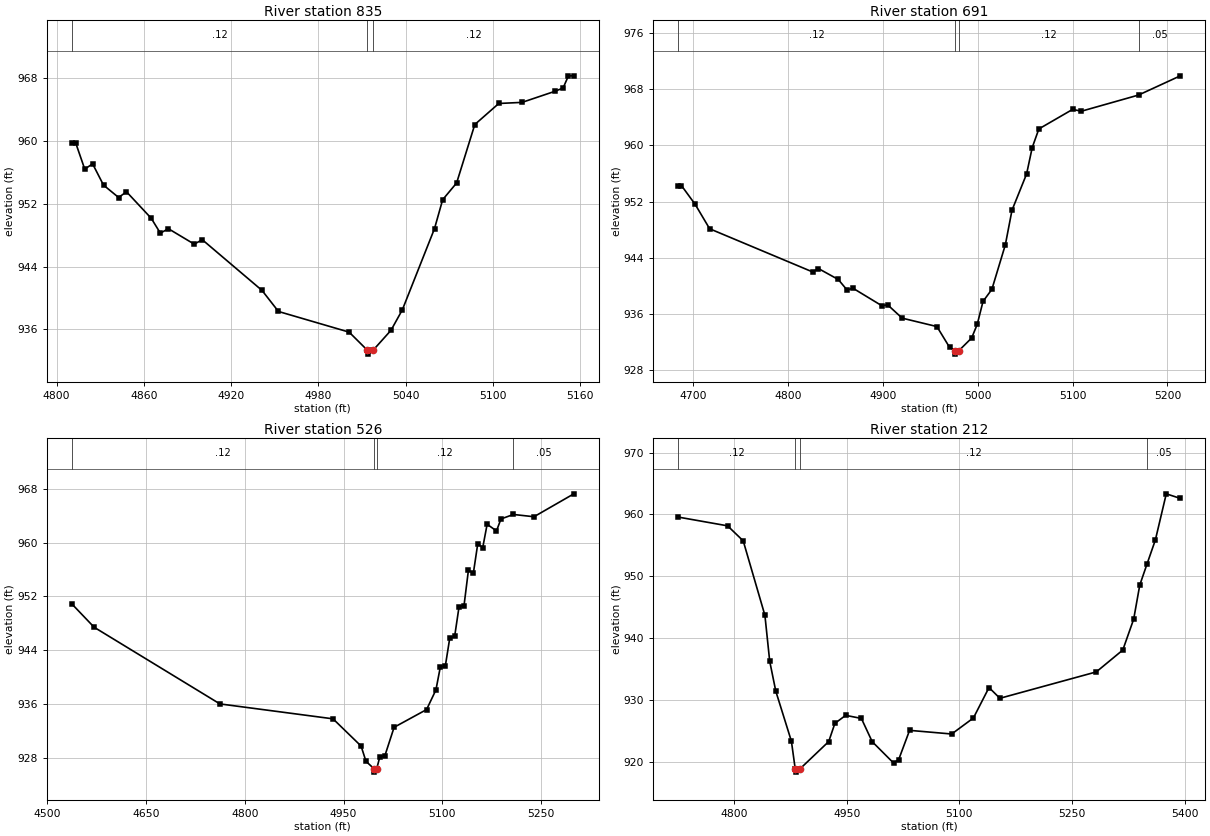
Type RM Length L Ch R = 1,835,144,144,144
BEGIN DESCRIPTION:
UDS St 03 1.0
END DESCRIPTION:
XS GIS Cut Line= 3
      2280279.02      7201910.03      2280201.85      7201735.51
      2280130.58      7201598.46
#Sta/Elev= 30
  4810.4  959.74  4813.2  959.74  4819.4  956.41  4824.8  957.09  4832.3  954.38
  4842.7  952.80  4848.1  953.53  4865.1  950.16  4871.4  948.26  4876.9  948.83
  4894.7  946.86  4900.2  947.43  4941.3  940.97  4952.6  938.29  5001.2  935.66
  5013.7  933.36  5013.9  932.86  5017.7  933.36  5030.0  935.90  5037.8  938.51
  5059.9  948.84  5065.5  952.52  5075.1  954.65  5087.6  962.09  5104.1  964.77
  5120.1  964.91  5142.7  966.32  5148.3  966.74  5152.0  968.29  5155.7  968.29
#Mann=3,-1,0
  4810.4    0.12       0  5013.7    0.07       0  5017.7    0.12       0
Bank Sta=5013.7,5017.7
Exp/Cntr=0.3,0.1

Type RM Length L Ch R = 1,691,165,165,165
BEGIN DESCRIPTION:
UDS St 03 0.9
END DESCRIPTION:
XS GIS Cut Line= 3
      2280294.64      7201900.89      2280383.93      7201764.13
      2280191.08      7201453.45
#Sta/Elev= 30
  4684.5  954.29  4688.0  954.29  4702.5  951.60  4717.7  948.13  4826.3  941.97
  4832.3  942.46  4853.2  940.90  4862.6  939.38  4868.5  939.67  4899.2  937.15
  4905.1  937.30  4920.5  935.39  4957.1  934.19  4970.4  931.24  4976.3  930.76
  4976.6  930.26  4980.3  930.76  4993.7  932.56  4999.6  934.51  5005.7  937.78
  5015.0  939.49  5029.2  945.85  5036.2  950.77  5051.6  955.95  5057.5  959.70
  5064.5  962.36  5100.0  965.14  5109.4  964.89  5169.5  967.19  5213.5  969.93
#Mann=4,-1,0
  4684.5    0.12       0  4976.3    0.07       0  4980.3    0.12       0
  5169.5    0.05       0
Bank Sta=4976.3,4980.3
Exp/Cntr=0.3,0.1

Type RM Length L Ch R = 1,526,314,314,314
BEGIN DESCRIPTION:
UDS St 03 0.8
END DESCRIPTION:
XS GIS Cut Line= 3
      2280325.52      7201894.74      2280545.51      7201671.76
      2280245.62      7201337.64
#Sta/Elev= 30
  4537.3  950.91  4571.4  947.41  4762.3  936.00  4934.0  933.78  4976.6  929.73
  4984.0  927.46  4996.3  926.35  4996.5  925.85  5000.3  926.35  5005.0  928.11
  5012.5  928.23  5026.7  932.52  5076.0  935.16  5090.2  938.09  5096.9  941.52
  5104.4  941.61  5111.1  945.75  5118.6  946.05  5125.3  950.48  5132.8  950.62
  5139.5  955.89  5147.0  955.46  5153.7  959.85  5161.2  959.24  5167.9  962.73
  5182.1  961.74  5188.9  963.52  5207.8  964.19  5239.0  963.85  5299.5  967.26
#Mann=4,-1,0
  4537.3    0.12       0  4996.3    0.07       0  5000.3    0.12       0
  5207.8    0.05       0
Bank Sta=4996.3,5000.3
Exp/Cntr=0.3,0.1

Type RM Length L Ch R = 1,212,0,0,0
BEGIN DESCRIPTION:
UDS St 03 0.7
END DESCRIPTION:
XS GIS Cut Line= 2
      2280895.15      7201556.14      2280367.91      7201144.51
#Sta/Elev= 30
  4725.5  959.57  4791.4  958.15  4812.2  955.72  4841.1  943.67  4847.5  936.23
  4855.6  931.39  4876.4  923.29  4881.5  918.79  4882.5  918.29  4887.6  918.79
  4926.1  923.24  4934.3  926.18  4948.7  927.48  4969.6  926.98  4984.0  923.22
  5012.4  919.77  5019.3  920.32  5033.8  925.05  5089.9  924.46  5118.8  927.05
  5139.6  931.98  5154.1  930.24  5282.5  934.51  5317.8  938.05  5332.3  943.05
  5340.4  948.56  5350.0  951.95  5361.2  955.87  5375.7  963.33  5394.4  962.59
#Mann=4,-1,0
  4725.5    0.12       0  4881.5    0.07       0  4887.6    0.12       0
  5350.0    0.05       0
Bank Sta=4881.5,4887.6
Exp/Cntr=0.3,0.1

Chan Stop Cuts=-1