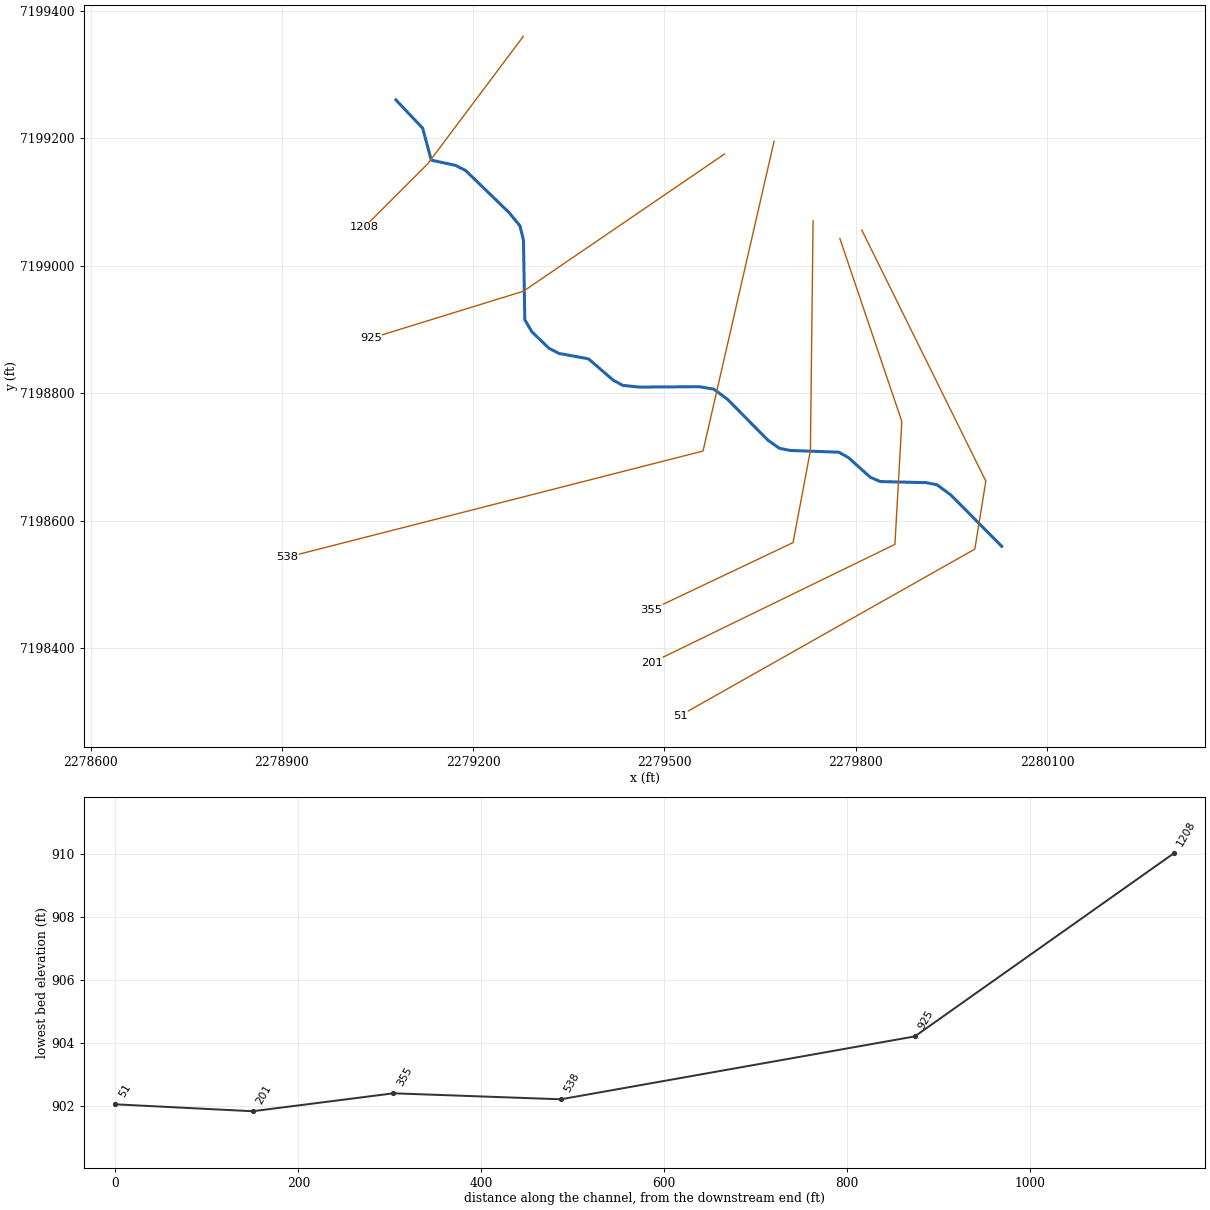
--- UDS St 04.prj (project) ---

Proj Title=UDS St 04 Base Level Engineering
Current Plan=p01
Default Exp/Contr=0.3,0.1
English Units
Geom File=g01
Flow File=f01
Plan File=p01
BEGIN DESCRIPTION:
UDS St 04
END DESCRIPTION:

--- UDS St 04.p01 (plan) ---

Plan Title=Multiple Run
Short Identifier=Multiple
Geom File=g01
Flow File=f01
Subcritical Flow
K Sum by GR= 0
Std Step Tol= 0.01
Critical Tol= 0.01
Num of Std Step Trials= 20
Max Error Tol= 0.3
Flow Tol Ratio= 0.001
Split Flow NTrial= 30
Split Flow Tol= 0.02
Split Flow Ratio= 0.02
Log Output Level= 0
Friction Slope Method= 1
Unsteady Friction Slope Method= 2
Unsteady Bridges Friction Slope Method= 1
Parabolic Critical Depth
Global Vel Dist=  1 , 1 , 1
Global Log Level= 0
CheckData=True
Encroach Param= -1, 0, 0, 0
BEGIN DESCRIPTION:
Multiple Run
END DESCRIPTION:

--- UDS St 04.f01 (steady flow) ---

Flow Title=Multiple
Number of Profiles=7
Profile Names=10-year,25-year,50-year,1pct_min,100-year,1pct_plu,500-year
River Rch & RM= UDS St 04,Reach-1,1208
     439     597     727     441     880    1755    1289
Boundary for River Rch & Prof#=UDS St 04,Reach-1,1
Up Type=0
Dn Type=3
Dn Slope=0.005
Boundary for River Rch & Prof#=UDS St 04,Reach-1,2
Up Type=0
Dn Type=3
Dn Slope=0.005
Boundary for River Rch & Prof#=UDS St 04,Reach-1,3
Up Type=0
Dn Type=3
Dn Slope=0.005
Boundary for River Rch & Prof#=UDS St 04,Reach-1,4
Up Type=0
Dn Type=3
Dn Slope=0.005
Boundary for River Rch & Prof#=UDS St 04,Reach-1,5
Up Type=0
Dn Type=3
Dn Slope=0.005
Boundary for River Rch & Prof#=UDS St 04,Reach-1,6
Up Type=0
Dn Type=3
Dn Slope=0.005
Boundary for River Rch & Prof#=UDS St 04,Reach-1,7
Up Type=0
Dn Type=3
Dn Slope=0.005

--- UDS St 04.g01 (geometry) ---

Geom Title=Existing Conditions

River Reach=UDS St 04,Reach-1
Reach XY= 30
      2279079.00      7199260.00      2279120.88      7199215.70
      2279134.44      7199165.51      2279172.59      7199157.34
      2279188.45      7199149.14      2279256.16      7199083.58
      2279273.54      7199062.46      2279279.02      7199040.01
      2279281.10      7198915.26      2279292.23      7198896.33
      2279318.94      7198870.61      2279334.42      7198862.52
      2279381.14      7198853.85      2279419.33      7198820.80
      2279434.52      7198812.36      2279460.67      7198809.64
      2279554.11      7198810.27      2279577.53      7198806.44
      2279599.14      7198790.35      2279662.26      7198726.49
      2279680.50      7198713.62      2279697.29      7198710.25
      2279773.43      7198707.53      2279788.63      7198699.11
      2279822.96      7198668.19      2279838.71      7198661.49
      2279910.72      7198659.76      2279927.52      7198656.44
      2279949.20      7198640.48      2280029.00      7198560.00

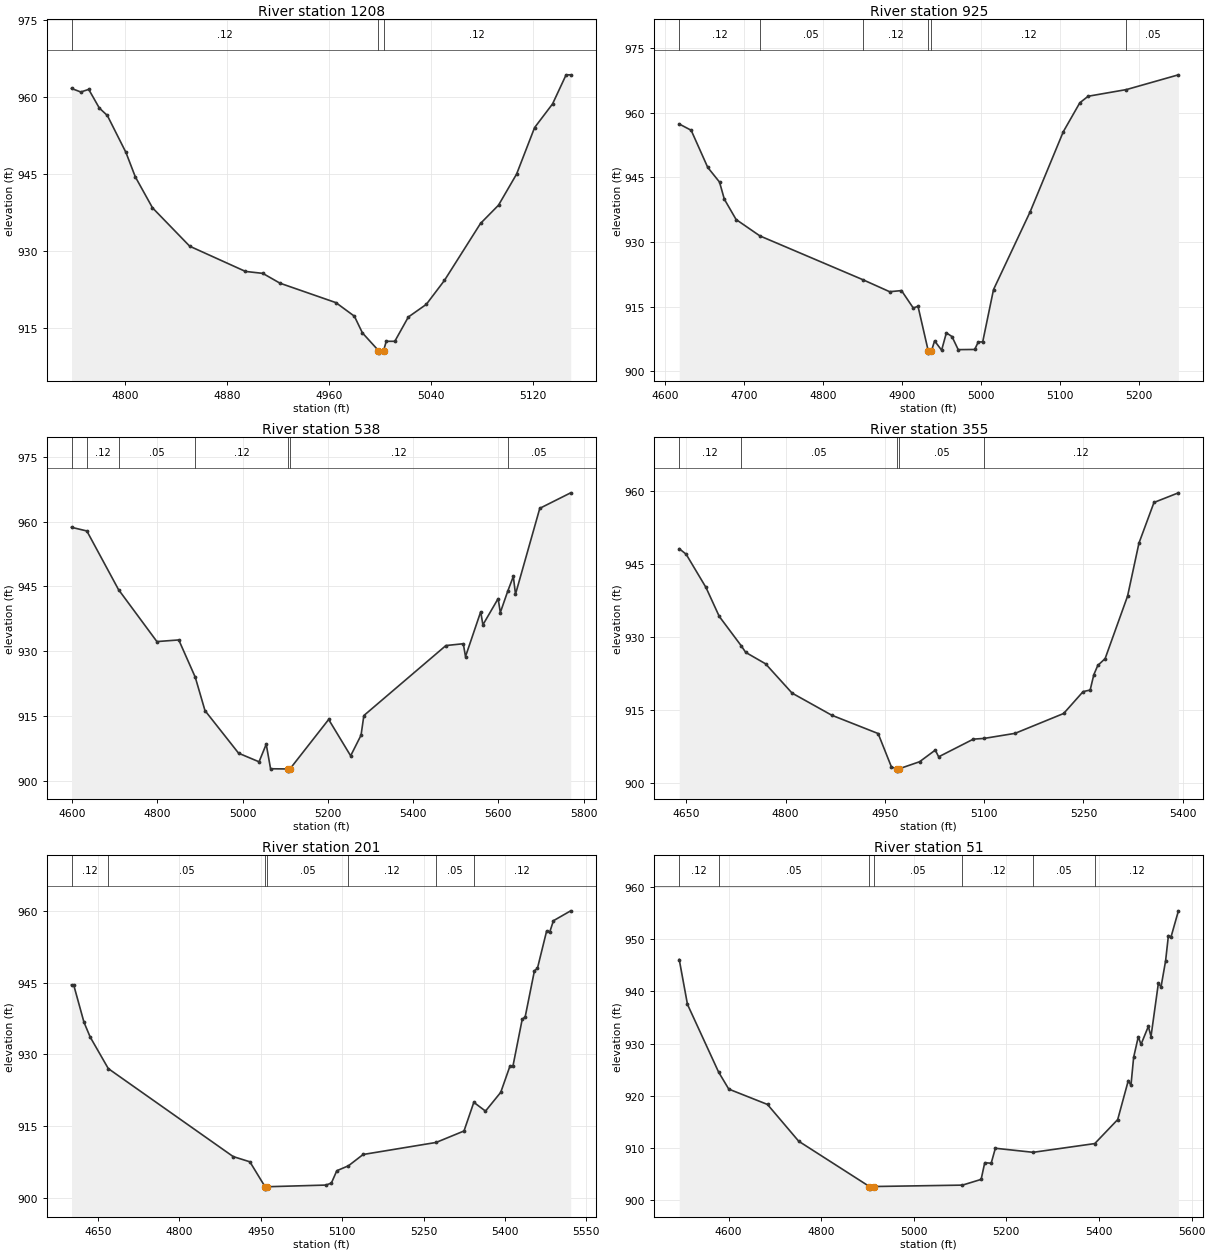
Type RM Length L Ch R = 1,1208,283,283,283
BEGIN DESCRIPTION:
UDS St 04 4.0
END DESCRIPTION:
XS GIS Cut Line= 3
      2279278.98      7199359.97      2279129.00      7199160.00
      2279028.99      7199059.99
#Sta/Elev= 30
  4758.0  961.69  4765.3  961.00  4771.5  961.51  4779.8  957.87  4786.1  956.41
  4800.7  949.19  4808.0  944.45  4821.5  938.39  4850.7  930.89  4894.4  925.97
  4908.0  925.59  4921.5  923.67  4965.3  919.88  4979.8  917.23  4986.1  913.97
  4998.7  910.52  4998.9  910.02  5002.7  910.52  5004.8  912.33  5011.5  912.33
  5022.1  917.07  5036.2  919.54  5050.4  924.21  5078.7  935.34  5092.8  938.90
  5107.0  944.98  5121.1  954.05  5135.2  958.68  5145.8  964.35  5149.4  964.35
#Mann=3,-1,0
  4758.0    0.12       0  4998.7    0.07       0  5002.7    0.12       0
Bank Sta=4998.7,5002.7
Exp/Cntr=0.3,0.1

Type RM Length L Ch R = 1,925,387,387,387
BEGIN DESCRIPTION:
UDS St 04 3.0
END DESCRIPTION:
XS GIS Cut Line= 3
      2279594.22      7199175.09      2279279.00      7198960.00
      2279039.75      7198886.16
#Sta/Elev= 30
  4618.0  957.36  4633.1  955.91  4654.1  947.29  4669.0  943.89  4675.1  939.92
  4690.0  935.20  4720.2  931.39  4850.2  921.26  4884.4  918.45  4899.4  918.71
  4914.3  914.67  4920.3  915.07  4933.3  904.70  4933.5  904.20  4937.3  904.70
  4941.3  907.04  4950.2  904.88  4956.2  908.90  4963.3  908.05  4971.2  905.01
  4992.1  905.05  4996.6  906.80  5002.2  906.80  5015.9  918.94  5062.4  937.04
  5104.3  955.59  5125.2  962.29  5135.7  963.80  5184.2  965.35  5250.0  968.77
#Mann=6,-1,0
  4618.0    0.12       0  4720.2    0.05       0  4850.2    0.12       0
  4933.3    0.07       0  4937.3    0.12       0  5184.2    0.05       0
Bank Sta=4933.3,4937.3
Exp/Cntr=0.3,0.1

Type RM Length L Ch R = 1,538,183,183,183
BEGIN DESCRIPTION:
UDS St 04 2.0
END DESCRIPTION:
XS GIS Cut Line= 3
      2279672.08      7199195.30      2279560.63      7198709.40
      2278908.78      7198542.91
#Sta/Elev= 30
  4598.5  958.70  4634.5  957.85  4708.8  944.27  4798.9  932.22  4850.2  932.60
  4888.9  923.96  4911.7  916.23  4990.6  906.35  5038.6  904.36  5055.4  908.44
  5065.6  902.75  5107.0  902.70  5107.3  902.20  5111.0  902.70  5201.9  914.17
  5253.5  905.75  5277.9  910.53  5284.5  915.08  5477.0  931.30  5517.8  931.72
  5523.0  928.74  5558.7  939.14  5563.8  936.10  5599.5  942.17  5604.7  938.95
  5621.9  943.84  5635.2  947.32  5640.3  943.20  5697.3  963.10  5769.8  966.69
#Mann=7,-1,0
  4598.5    0.05       0  4634.5    0.12       0  4708.8    0.05       0
  4888.9    0.12       0  5107.0    0.07       0  5111.0    0.12       0
  5621.9    0.05       0
Bank Sta=5107,5111
Exp/Cntr=0.3,0.1

Type RM Length L Ch R = 1,355,154,154,154
BEGIN DESCRIPTION:
UDS St 04 1.0
END DESCRIPTION:
XS GIS Cut Line= 4
      2279733.20      7199070.43      2279729.00      7198710.00
      2279701.80      7198565.75      2279478.97      7198459.99
#Sta/Elev= 30
  4639.5  948.07  4649.9  946.95  4679.9  940.11  4699.9  934.18  4733.1  928.14
  4739.9  926.78  4769.9  924.43  4809.9  918.42  4869.9  913.87  4939.9  910.11
  4960.0  903.24  4968.0  902.89  4968.2  902.39  4972.0  902.89  5002.5  904.32
  5026.2  906.71  5031.3  905.33  5083.7  908.96  5100.0  909.11  5146.7  910.15
  5220.1  914.23  5249.5  918.73  5260.1  919.04  5265.6  922.18  5271.6  924.09
  5282.7  925.50  5316.6  938.34  5333.8  949.22  5356.5  957.57  5393.4  959.55
#Mann=5,-1,0
  4639.5    0.12       0  4733.1    0.05       0  4968.0   0.033       0
  4972.0    0.05       0  5100.0    0.12       0
Bank Sta=4968,4972
Exp/Cntr=0.3,0.1

Type RM Length L Ch R = 1,201,150,150,150
BEGIN DESCRIPTION:
UDS St 04 0.9
END DESCRIPTION:
XS GIS Cut Line= 4
      2279775.23      7199042.63      2279872.40      7198755.72
      2279861.57      7198562.97      2279480.37      7198377.47
#Sta/Elev= 30
  4601.1  944.57  4605.1  944.57  4624.1  936.75  4635.5  933.66  4668.9  927.05
  4899.1  908.63  4929.8  907.54  4957.8  902.32  4958.1  901.82  4961.8  902.32
  5070.0  902.67  5080.0  903.09  5090.0  905.67  5111.5  906.71  5138.5  909.07
  5273.0  911.59  5324.4  913.99  5342.5  919.99  5364.0  918.15  5392.1  922.08
  5409.1  927.58  5414.6  927.57  5431.6  937.33  5437.2  937.91  5454.2  947.53
  5459.7  948.02  5476.7  955.86  5482.3  955.59  5489.2  958.00  5521.0  960.07
#Mann=7,-1,0
  4601.1    0.12       0  4668.9    0.05       0  4957.8   0.033       0
  4961.8    0.05       0  5111.5    0.12       0  5273.0    0.05       0
  5342.5    0.12       0
Bank Sta=4957.8,4961.8
Exp/Cntr=0.3,0.1

Type RM Length L Ch R = 1,51,0,0,0
BEGIN DESCRIPTION:
UDS St 04 0.8
END DESCRIPTION:
XS GIS Cut Line= 4
      2279809.59      7199055.96      2280004.12      7198662.15
      2279986.89      7198555.53      2279524.84      7198294.54
#Sta/Elev= 30
  4493.6  946.14  4511.4  937.52  4578.6  924.52  4600.6  921.25  4684.2  918.30
  4751.6  911.24  4904.3  902.54  4905.6  902.04  4913.1  902.54  5105.2  902.81
  5145.5  903.91  5153.3  907.12  5167.2  907.01  5176.2  909.89  5257.8  909.11
  5390.9  910.79  5440.4  915.40  5463.3  922.90  5469.0  921.96  5474.8  927.35
  5484.9  931.32  5490.7  929.83  5506.6  933.30  5512.3  931.35  5528.2  941.57
  5534.0  940.89  5543.8  945.87  5549.9  950.74  5555.6  950.49  5571.5  955.49
#Mann=7,-1,0
  4493.6    0.12       0  4578.6    0.05       0  4904.3   0.033       0
  4913.1    0.05       0  5105.2    0.12       0  5257.8    0.05       0
  5390.9    0.12       0
Bank Sta=4904.3,4913.1
Exp/Cntr=0.3,0.1

Chan Stop Cuts=-1