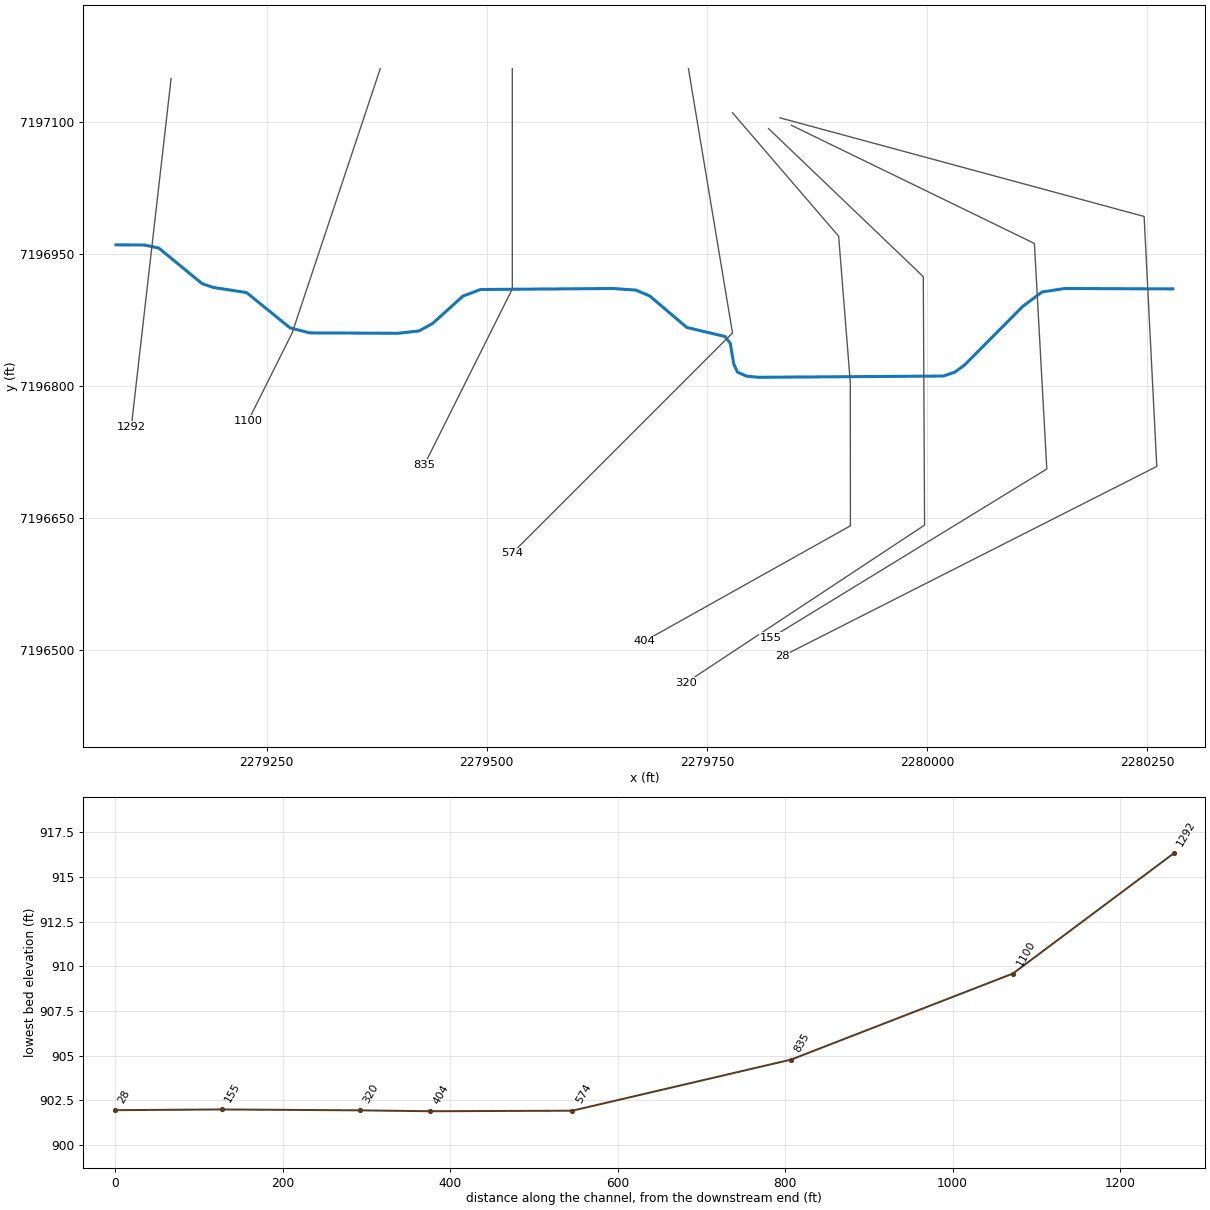
--- UDS St 05.prj (project) ---

Proj Title=UDS St 05 Base Level Engineering
Current Plan=p01
Default Exp/Contr=0.3,0.1
English Units
Geom File=g01
Flow File=f01
Plan File=p01
BEGIN DESCRIPTION:
UDS St 05
END DESCRIPTION:

--- UDS St 05.p01 (plan) ---

Plan Title=Multiple Run
Short Identifier=Multiple
Geom File=g01
Flow File=f01
Subcritical Flow
K Sum by GR= 0
Std Step Tol= 0.01
Critical Tol= 0.01
Num of Std Step Trials= 20
Max Error Tol= 0.3
Flow Tol Ratio= 0.001
Split Flow NTrial= 30
Split Flow Tol= 0.02
Split Flow Ratio= 0.02
Log Output Level= 0
Friction Slope Method= 1
Unsteady Friction Slope Method= 2
Unsteady Bridges Friction Slope Method= 1
Parabolic Critical Depth
Global Vel Dist=  1 , 1 , 1
Global Log Level= 0
CheckData=True
Encroach Param= -1, 0, 0, 0
BEGIN DESCRIPTION:
Multiple Run
END DESCRIPTION:

--- UDS St 05.f01 (steady flow) ---

Flow Title=Multiple
Number of Profiles=7
Profile Names=10-year,25-year,50-year,1pct_min,100-year,1pct_plu,500-year
River Rch & RM= UDS St 05,Reach-1,1292
     192     245     286     167     333     664     450
Boundary for River Rch & Prof#=UDS St 05,Reach-1,1
Up Type=0
Dn Type=3
Dn Slope=0.005
Boundary for River Rch & Prof#=UDS St 05,Reach-1,2
Up Type=0
Dn Type=3
Dn Slope=0.005
Boundary for River Rch & Prof#=UDS St 05,Reach-1,3
Up Type=0
Dn Type=3
Dn Slope=0.005
Boundary for River Rch & Prof#=UDS St 05,Reach-1,4
Up Type=0
Dn Type=3
Dn Slope=0.005
Boundary for River Rch & Prof#=UDS St 05,Reach-1,5
Up Type=0
Dn Type=3
Dn Slope=0.005
Boundary for River Rch & Prof#=UDS St 05,Reach-1,6
Up Type=0
Dn Type=3
Dn Slope=0.005
Boundary for River Rch & Prof#=UDS St 05,Reach-1,7
Up Type=0
Dn Type=3
Dn Slope=0.005

--- UDS St 05.g01 (geometry) ---

Geom Title=Existing Conditions

River Reach=UDS St 05,Reach-1
Reach XY= 30
      2279079.00      7196960.00      2279110.81      7196959.90
      2279127.51      7196956.40      2279176.75      7196915.95
      2279189.67      7196911.61      2279227.27      7196905.83
      2279276.65      7196865.70      2279299.03      7196860.04
      2279399.13      7196859.61      2279423.06      7196862.25
      2279438.64      7196870.85      2279472.94      7196901.86
      2279492.92      7196909.32      2279642.82      7196910.45
      2279669.36      7196908.65      2279685.12      7196901.92
      2279727.13      7196866.22      2279770.64      7196855.93
      2279776.46      7196848.17      2279780.41      7196824.97
      2279784.59      7196815.55      2279794.94      7196810.92
      2279808.63      7196809.62      2280018.56      7196811.06
      2280031.45      7196815.47      2280042.31      7196823.40
      2280108.85      7196890.35      2280130.45      7196906.49
      2280156.09      7196910.45      2280279.00      7196910.00

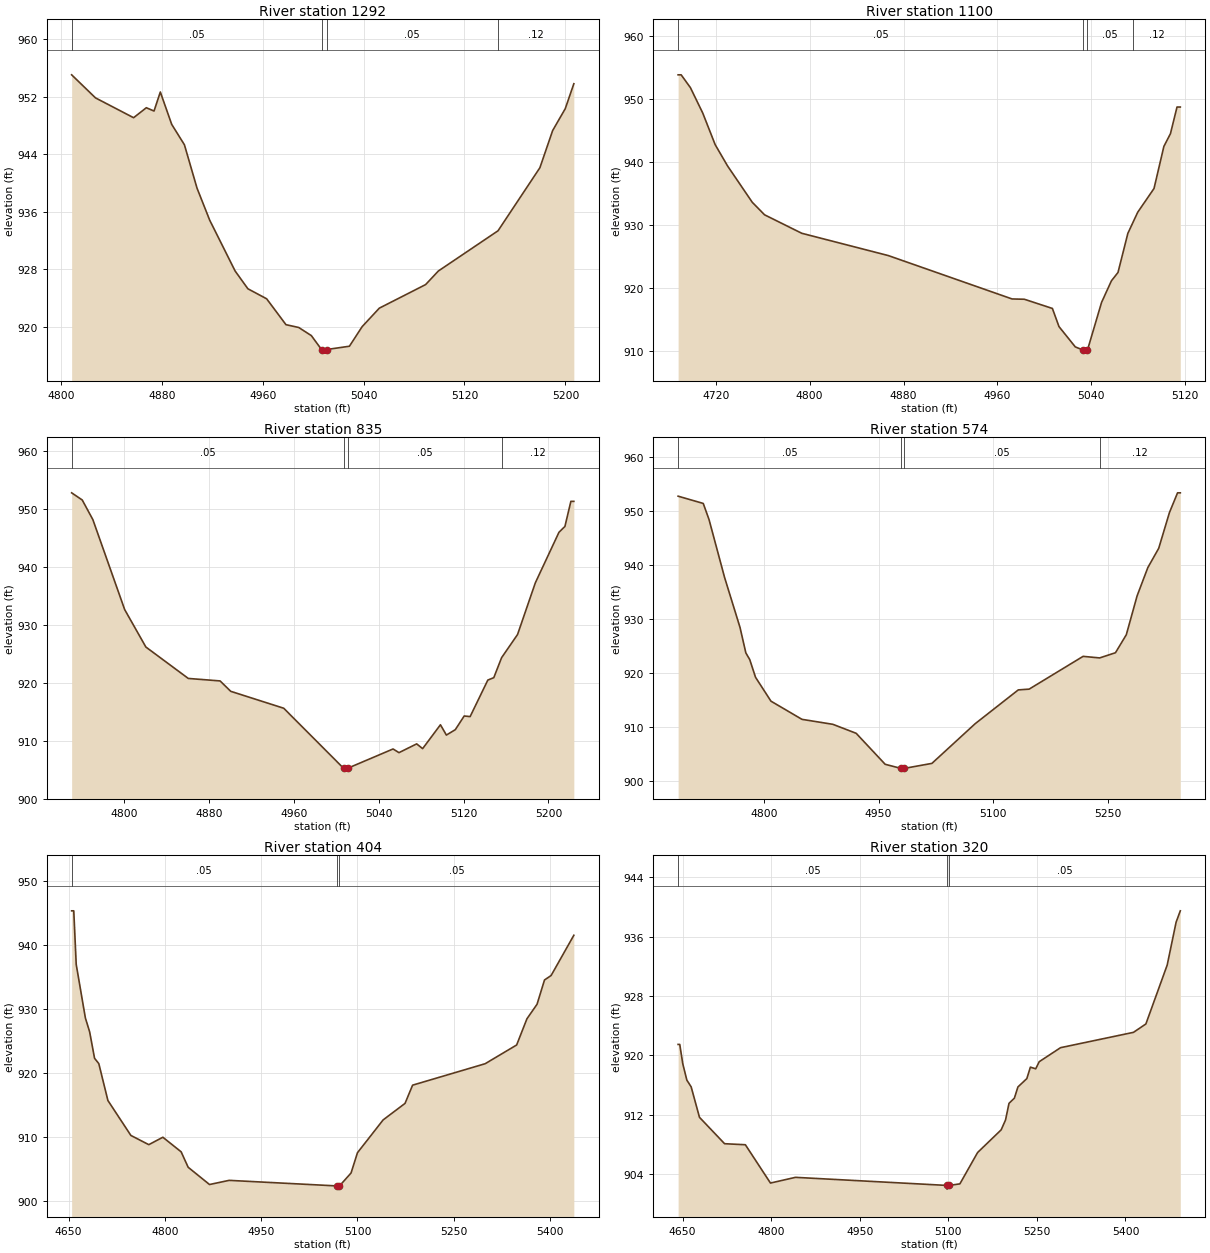
Type RM Length L Ch R = 1,1292,192,192,192
BEGIN DESCRIPTION:
UDS St 05 4.1
END DESCRIPTION:
XS GIS Cut Line= 2
      2279141.53      7197148.80      2279096.33      7196753.27
#Sta/Elev= 30
  4808.6  955.06  4827.5  951.85  4857.7  949.09  4867.8  950.48  4873.9  950.02
  4878.9  952.67  4887.9  948.17  4898.0  945.32  4908.0  939.28  4918.1  934.80
  4938.2  927.75  4948.3  925.28  4963.2  923.88  4978.5  920.28  4988.6  919.89
  4998.6  918.76  5006.7  916.82  5006.9  916.32  5010.4  916.32  5010.7  916.82
  5028.8  917.28  5038.9  920.01  5052.5  922.58  5089.2  925.86  5099.3  927.75
  5146.6  933.35  5179.8  942.13  5189.9  947.30  5199.9  950.35  5206.7  953.82
#Mann=4,-1,0
  4808.6    0.05       0  5006.7   0.033       0  5010.7    0.05       0
  5146.6    0.12       0
Bank Sta=5006.7,5010.7
Exp/Cntr=0.3,0.1

Type RM Length L Ch R = 1,1100,265,265,265
BEGIN DESCRIPTION:
UDS St 05 4.0
END DESCRIPTION:
XS GIS Cut Line= 3
      2279378.99      7197159.96      2279279.00      7196860.00
      2279228.99      7196759.99
#Sta/Elev= 30
  4687.9  953.76  4690.5  953.76  4698.4  951.72  4708.9  947.69  4719.5  942.67
  4730.0  939.31  4751.1  933.53  4761.6  931.54  4793.3  928.61  4867.1  925.07
  4972.5  918.19  4983.0  918.14  5006.9  916.68  5012.5  913.80  5026.4  910.58
  5032.8  910.09  5033.1  909.59  5036.6  909.59  5036.8  910.09  5048.8  917.64
  5057.2  921.07  5062.8  922.39  5071.2  928.60  5075.6  930.35  5079.6  931.95
  5093.5  935.72  5101.9  942.40  5107.5  944.42  5113.1  948.65  5115.9  948.65
#Mann=4,-1,0
  4687.9    0.05       0  5032.8   0.033       0  5036.8    0.05       0
  5075.6    0.12       0
Bank Sta=5032.8,5036.8
Exp/Cntr=0.3,0.1

Type RM Length L Ch R = 1,835,261,261,261
BEGIN DESCRIPTION:
UDS St 05 3.0
END DESCRIPTION:
XS GIS Cut Line= 3
      2279529.00      7197159.98      2279529.00      7196910.00
      2279428.99      7196709.99
#Sta/Elev= 30
  4750.4  952.78  4760.4  951.54  4770.4  948.16  4800.4  932.64  4820.4  926.18
  4860.4  920.76  4890.4  920.33  4900.4  918.54  4950.4  915.62  5006.8  905.27
  5007.0  904.77  5010.8  905.27  5053.5  908.59  5059.1  907.96  5075.8  909.47
  5081.4  908.65  5098.2  912.77  5103.8  910.99  5112.2  911.92  5120.6  914.28
  5126.2  914.18  5142.9  920.48  5148.5  920.89  5155.9  924.35  5170.9  928.33
  5187.7  937.26  5210.0  945.98  5215.6  946.98  5221.2  951.31  5224.0  951.31
#Mann=4,-1,0
  4750.4    0.05       0  5006.8   0.033       0  5010.8    0.05       0
  5155.9    0.12       0
Bank Sta=5006.8,5010.8
Exp/Cntr=0.3,0.1

Type RM Length L Ch R = 1,574,170,170,170
BEGIN DESCRIPTION:
UDS St 05 2.0
END DESCRIPTION:
XS GIS Cut Line= 3
      2279729.00      7197159.98      2279779.00      7196860.00
      2279528.98      7196609.98
#Sta/Elev= 30
  4687.5  952.72  4720.4  951.38  4728.0  948.40  4748.3  937.73  4768.6  928.45
  4776.2  923.76  4781.3  922.53  4788.9  919.25  4809.1  914.84  4849.7  911.48
  4890.2  910.56  4920.7  908.90  4958.7  903.17  4979.5  902.41  4979.7  901.91
  4983.5  902.41  5019.9  903.34  5076.5  910.67  5133.0  916.92  5147.2  917.06
  5217.9  923.12  5239.6  922.83  5260.3  923.79  5274.5  927.12  5288.6  934.29
  5302.7  939.53  5316.9  943.08  5331.0  949.70  5341.6  953.34  5345.2  953.34
#Mann=4,-1,0
  4687.5    0.05       0  4979.5   0.033       0  4983.5    0.05       0
  5239.6    0.12       0
Bank Sta=4979.5,4983.5
Exp/Cntr=0.3,0.1

Type RM Length L Ch R = 1,404,84,84,84
BEGIN DESCRIPTION:
UDS St 05 1.0
END DESCRIPTION:
XS GIS Cut Line= 5
      2279778.99      7197110.01      2279899.55      7196969.85
      2279912.78      7196803.75      2279912.91      7196640.98
      2279678.97      7196509.98
#Sta/Elev= 30
  4654.7  945.38  4658.0  945.38  4661.8  937.01  4676.1  928.63  4682.7  926.48
  4690.4  922.33  4697.0  921.50  4711.2  915.73  4747.0  910.27  4774.9  908.83
  4796.8  909.99  4825.3  907.71  4836.2  905.30  4869.5  902.60  4900.1  903.25
  5068.0  902.38  5068.2  901.88  5072.0  902.38  5090.0  904.40  5100.0  907.57
  5140.0  912.70  5174.1  915.28  5185.9  918.13  5298.9  921.48  5348.0  924.41
  5364.0  928.50  5379.8  930.78  5391.4  934.57  5401.7  935.27  5437.1  941.56
#Mann=3,-1,0
  4654.7    0.05       0  5068.0   0.033       0  5072.0    0.05       0
Bank Sta=5068,5072
Exp/Cntr=0.3,0.1

Type RM Length L Ch R = 1,320,165,165,165
BEGIN DESCRIPTION:
UDS St 05 0.9
END DESCRIPTION:
XS GIS Cut Line= 4
      2279819.91      7197092.05      2279995.68      7196923.93
      2279997.13      7196641.80      2279725.86      7196462.55
#Sta/Elev= 30
  4642.4  921.46  4645.2  921.46  4650.3  918.85  4657.2  916.64  4664.5  915.73
  4678.6  911.62  4721.1  908.06  4756.3  907.92  4798.8  902.75  4841.2  903.52
  5097.6  902.43  5097.8  901.93  5101.6  902.43  5119.6  902.64  5149.6  906.87
  5189.5  909.93  5196.9  911.26  5202.8  913.51  5211.9  914.21  5217.9  915.72
  5233.0  916.85  5239.0  918.39  5248.0  918.17  5254.0  919.13  5290.1  921.02
  5413.6  923.09  5434.6  924.22  5470.7  932.17  5485.8  937.96  5492.9  939.49
#Mann=3,-1,0
  4642.4    0.05       0  5097.6   0.033       0  5101.6    0.05       0
Bank Sta=5097.6,5101.6
Exp/Cntr=0.3,0.1

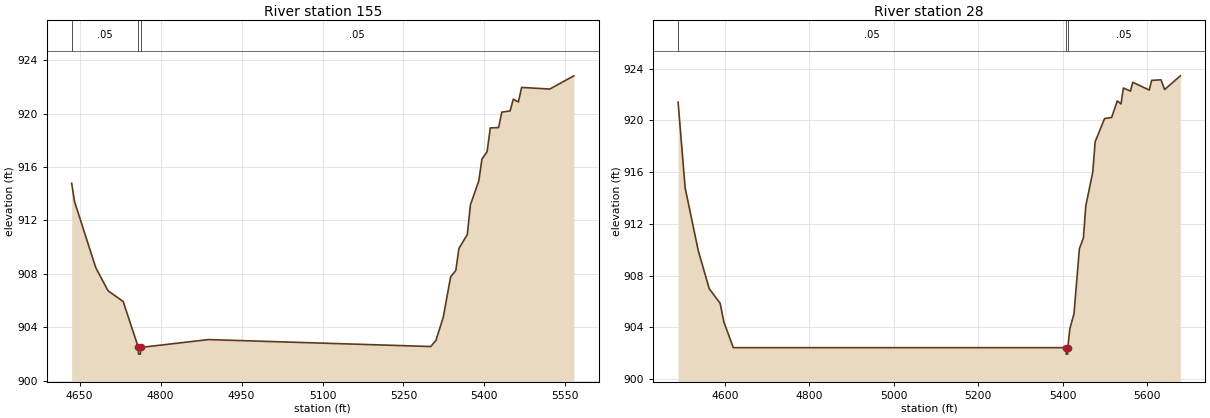
Type RM Length L Ch R = 1,155,127,127,127
BEGIN DESCRIPTION:
UDS St 05 0.8
END DESCRIPTION:
XS GIS Cut Line= 4
      2279846.03      7197095.75      2280121.83      7196961.62
      2280135.93      7196705.48      2279822.68      7196513.71
#Sta/Elev= 30
  4635.2  914.78  4640.5  913.41  4680.0  908.45  4702.6  906.73  4730.7  905.92
  4758.8  902.48  4759.1  901.98  4762.6  901.98  4762.8  902.48  4888.6  903.07
  5300.6  902.55  5310.2  903.01  5323.8  904.75  5337.4  907.77  5347.0  908.25
  5352.8  909.90  5368.3  910.94  5374.1  913.17  5389.6  914.96  5395.4  916.59
  5405.0  917.15  5410.9  918.93  5426.3  918.95  5432.2  920.11  5447.6  920.20
  5453.5  921.08  5463.0  920.87  5468.9  921.96  5521.1  921.84  5565.7  922.83
#Mann=3,-1,0
  4635.2    0.05       0  4758.8   0.033       0  4762.8    0.05       0
Bank Sta=4758.8,4762.8
Exp/Cntr=0.3,0.1

Type RM Length L Ch R = 1,28,0,0,0
BEGIN DESCRIPTION:
UDS St 05 0.7
END DESCRIPTION:
XS GIS Cut Line= 4
      2279832.92      7197104.26      2280246.42      7196992.27
      2280260.80      7196708.43      2279835.88      7196493.02
#Sta/Elev= 30
  4489.3  921.41  4506.0  914.78  4537.0  909.94  4563.0  907.00  4588.8  905.87
  4597.6  904.43  4619.9  902.44  5407.9  902.44  5408.2  901.94  5411.7  901.94
  5411.9  902.44  5416.9  903.92  5426.6  905.06  5439.4  910.09  5448.9  910.92
  5454.5  913.39  5471.1  916.02  5476.7  918.35  5499.0  920.15  5515.7  920.23
  5529.1  921.51  5537.9  921.28  5543.6  922.51  5560.2  922.27  5565.8  922.95
  5604.8  922.35  5610.4  923.10  5632.6  923.14  5641.2  922.39  5678.3  923.45
#Mann=3,-1,0
  4489.3    0.05       0  5407.9   0.033       0  5411.9    0.05       0
Bank Sta=5407.9,5411.9
Exp/Cntr=0.3,0.1

Chan Stop Cuts=-1