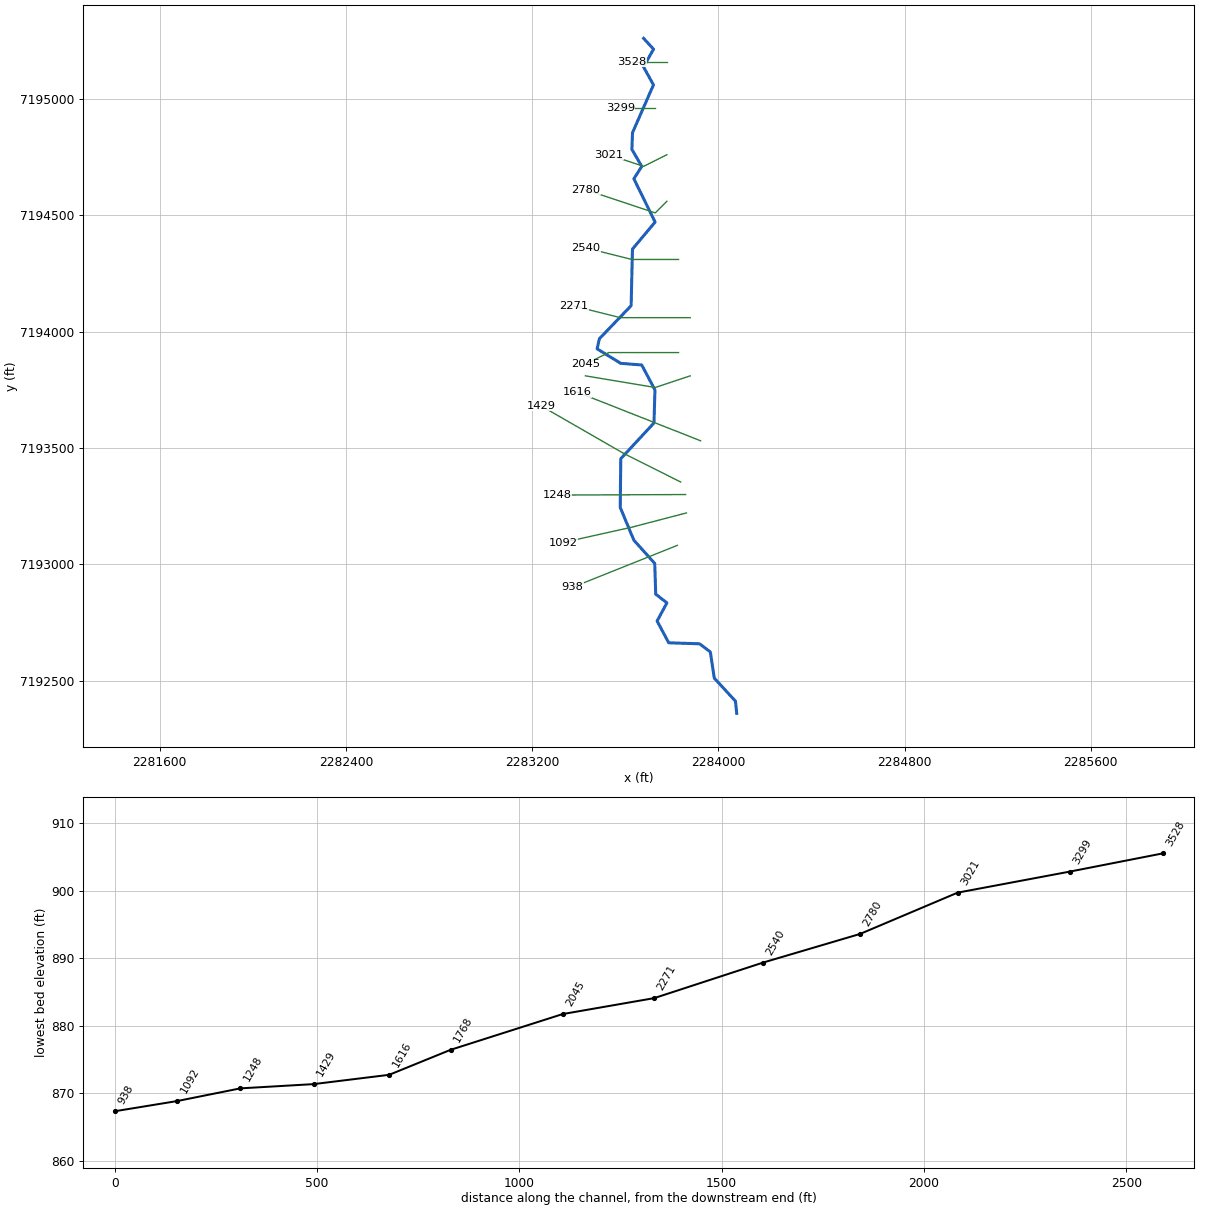
--- UDS St 08.prj (project) ---

Proj Title=UDS St 08 Base Level Engineering
Current Plan=p01
Default Exp/Contr=0.3,0.1
English Units
Geom File=g01
Flow File=f01
Plan File=p01
BEGIN DESCRIPTION:
UDS St 08
END DESCRIPTION:

--- UDS St 08.p01 (plan) ---

Plan Title=Multiple Run
Short Identifier=Multiple
Geom File=g01
Flow File=f01
Subcritical Flow
K Sum by GR= 0
Std Step Tol= 0.01
Critical Tol= 0.01
Num of Std Step Trials= 20
Max Error Tol= 0.3
Flow Tol Ratio= 0.001
Split Flow NTrial= 30
Split Flow Tol= 0.02
Split Flow Ratio= 0.02
Log Output Level= 0
Friction Slope Method= 1
Unsteady Friction Slope Method= 2
Unsteady Bridges Friction Slope Method= 1
Parabolic Critical Depth
Global Vel Dist=  1 , 1 , 1
Global Log Level= 0
CheckData=True
Encroach Param= -1, 0, 0, 0
BEGIN DESCRIPTION:
Multiple Run
END DESCRIPTION:

--- UDS St 08.f01 (steady flow) ---

Flow Title=Multiple
Number of Profiles=7
Profile Names=10-year,25-year,50-year,1pct_min,100-year,1pct_plu,500-year
River Rch & RM= UDS St 08,Reach-1,3528
     476     647     787     477     952    1899    1392
Boundary for River Rch & Prof#=UDS St 08,Reach-1,1
Up Type=0
Dn Type=3
Dn Slope=0.005
Boundary for River Rch & Prof#=UDS St 08,Reach-1,2
Up Type=0
Dn Type=3
Dn Slope=0.005
Boundary for River Rch & Prof#=UDS St 08,Reach-1,3
Up Type=0
Dn Type=3
Dn Slope=0.005
Boundary for River Rch & Prof#=UDS St 08,Reach-1,4
Up Type=0
Dn Type=3
Dn Slope=0.005
Boundary for River Rch & Prof#=UDS St 08,Reach-1,5
Up Type=0
Dn Type=3
Dn Slope=0.005
Boundary for River Rch & Prof#=UDS St 08,Reach-1,6
Up Type=0
Dn Type=3
Dn Slope=0.005
Boundary for River Rch & Prof#=UDS St 08,Reach-1,7
Up Type=0
Dn Type=3
Dn Slope=0.005

--- UDS St 08.g01 (geometry) ---

Geom Title=Existing Conditions

River Reach=UDS St 08,Reach-1
Reach XY= 30
      2283679.00      7195260.00      2283721.73      7195213.44
      2283678.75      7195137.20      2283721.41      7195060.01
      2283631.29      7194854.43      2283628.82      7194782.72
      2283671.20      7194709.90      2283637.24      7194656.77
      2283728.40      7194470.63      2283631.18      7194354.55
      2283625.46      7194111.46      2283489.06      7193969.41
      2283479.16      7193926.02      2283580.62      7193863.85
      2283670.98      7193856.69      2283727.82      7193749.52
      2283723.55      7193607.55      2283581.06      7193454.15
      2283578.56      7193244.82      2283637.16      7193103.95
      2283726.92      7193004.13      2283731.03      7192871.95
      2283779.23      7192835.00      2283737.06      7192756.68
      2283786.96      7192663.24      2283919.57      7192658.85
      2283965.77      7192623.73      2283982.62      7192511.50
      2284073.67      7192412.51      2284079.00      7192360.00

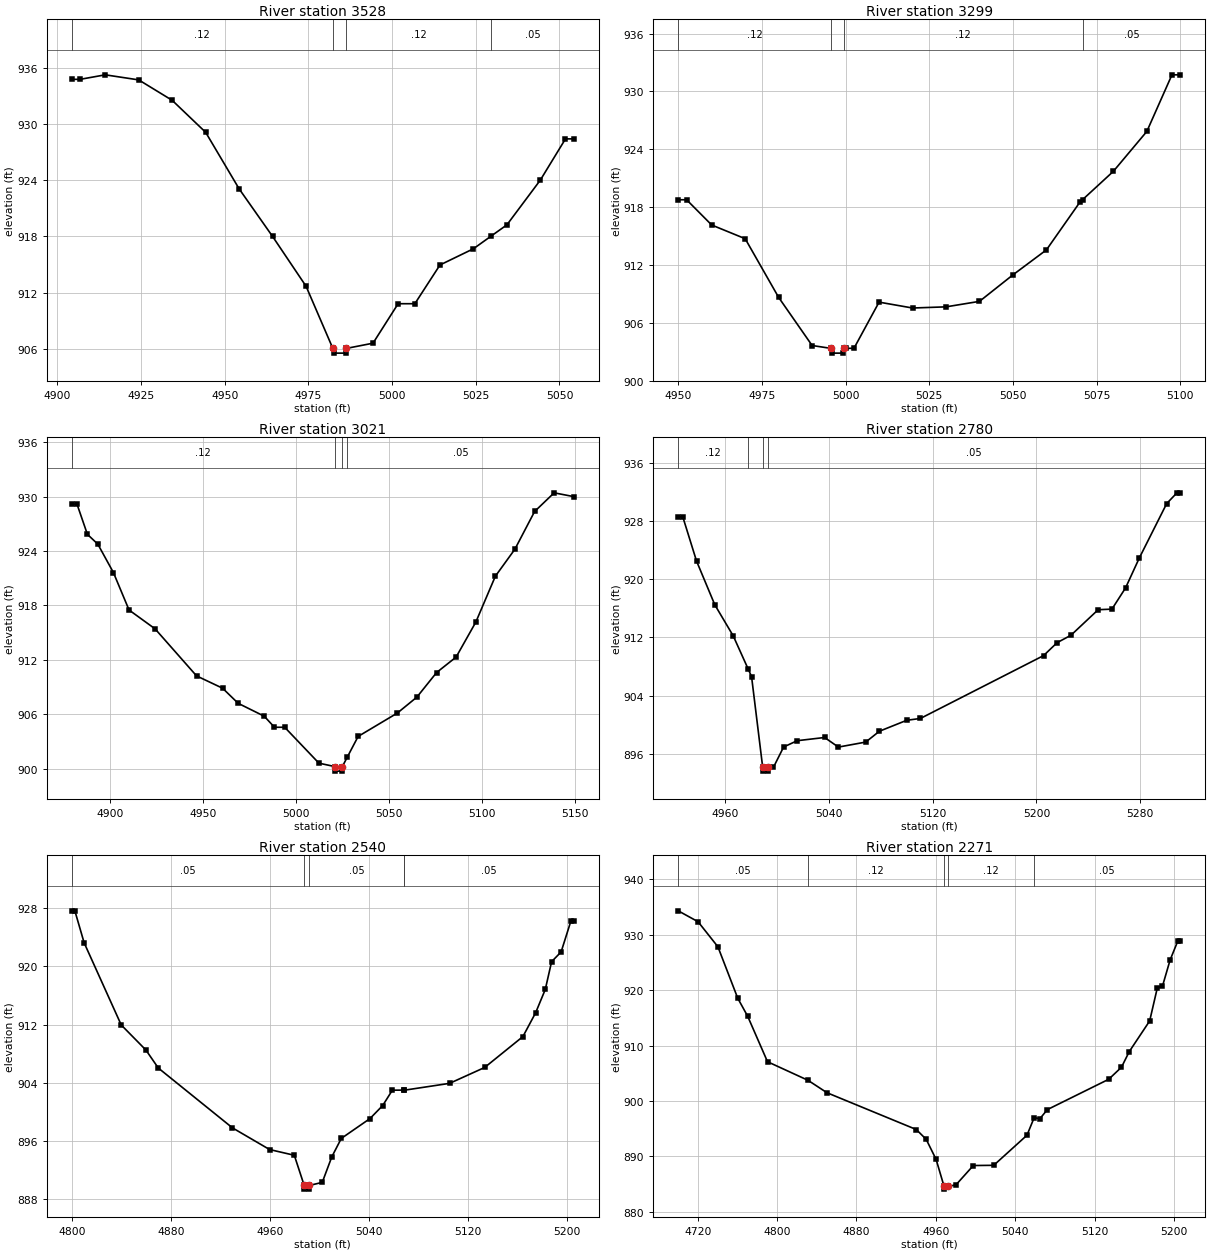
Type RM Length L Ch R = 1,3528,229,229,229
BEGIN DESCRIPTION:
UDS St 08 12.0
END DESCRIPTION:
XS GIS Cut Line= 3
      2283779.03      7195160.00      2283679.00      7195160.00
      2283629.03      7195160.00
#Sta/Elev= 23
  4904.3  934.74  4906.8  934.74  4914.3  935.22  4924.3  934.68  4934.3  932.50
  4944.3  929.09  4954.3  923.06  4964.3  917.98  4974.3  912.67  4982.3  906.04
  4982.6  905.54  4986.1  905.54  4986.3  906.04  4994.3  906.60  5001.8  910.81
  5006.8  910.81  5014.3  914.94  5024.3  916.67  5029.5  918.00  5034.3  919.22
  5044.3  924.00  5051.8  928.39  5054.3  928.39
#Mann=4,-1,0
  4904.3    0.12       0  4982.3    0.07       0  4986.3    0.12       0
  5029.5    0.05       0
Bank Sta=4982.3,4986.3
Exp/Cntr=0.3,0.1

Type RM Length L Ch R = 1,3299,278,278,278
BEGIN DESCRIPTION:
UDS St 08 11.0
END DESCRIPTION:
XS GIS Cut Line= 3
      2283729.05      7194960.00      2283679.00      7194960.00
      2283579.05      7194960.00
#Sta/Elev= 24
  4950.0  918.76  4952.5  918.76  4960.0  916.14  4970.0  914.72  4980.0  908.63
  4990.0  903.64  4995.5  903.35  4995.8  902.85  4999.3  902.85  4999.5  903.35
  5000.0  903.35  5002.5  903.35  5010.0  908.14  5020.0  907.53  5030.0  907.65
  5040.0  908.22  5050.0  910.97  5060.0  913.56  5070.0  918.51  5070.8  918.77
  5080.0  921.71  5090.0  925.85  5097.5  931.72  5100.0  931.72
#Mann=4,-1,0
  4950.0    0.12       0  4995.5    0.07       0  4999.5    0.12       0
  5070.8    0.05       0
Bank Sta=4995.5,4999.5
Exp/Cntr=0.3,0.1

Type RM Length L Ch R = 1,3021,241,241,241
BEGIN DESCRIPTION:
UDS St 08 10.0
END DESCRIPTION:
XS GIS Cut Line= 3
      2283779.04      7194760.02      2283679.00      7194710.00
      2283528.96      7194760.01
#Sta/Elev= 30
  4879.5  929.19  4882.3  929.19  4887.9  925.85  4893.5  924.77  4901.9  921.63
  4910.3  917.50  4924.3  915.42  4946.6  910.23  4960.6  908.87  4969.0  907.20
  4983.0  905.78  4988.5  904.56  4994.0  904.56  5012.4  900.60  5021.0  900.22
  5021.2  899.72  5024.7  899.72  5025.0  900.22  5027.7  901.28  5033.5  903.55
  5054.6  906.13  5065.1  907.89  5075.7  910.60  5086.2  912.31  5096.8  916.17
  5107.3  921.23  5117.8  924.21  5128.4  928.37  5138.9  930.43  5149.5  930.01
#Mann=4,-1,0
  4879.5    0.12       0  5021.0    0.07       0  5025.0    0.12       0
  5027.7    0.05       0
Bank Sta=5021,5025
Exp/Cntr=0.3,0.1

Type RM Length L Ch R = 1,2780,240,240,240
BEGIN DESCRIPTION:
UDS St 08 9.0
END DESCRIPTION:
XS GIS Cut Line= 3
      2283778.97      7194559.97      2283729.00      7194510.00
      2283428.99      7194610.00
#Sta/Elev= 30
  4924.0  928.61  4927.5  928.61  4938.1  922.52  4952.2  916.49  4966.4  912.21
  4977.8  907.69  4980.5  906.62  4989.1  894.10  4989.4  893.60  4992.9  893.60
  4993.1  894.10  4997.3  894.10  5005.2  896.92  5015.7  897.79  5036.8  898.23
  5047.4  896.91  5068.5  897.60  5079.0  899.09  5100.1  900.60  5110.6  900.85
  5205.5  909.50  5216.0  911.29  5226.6  912.30  5247.6  915.82  5258.2  915.90
  5268.7  918.82  5279.3  922.94  5300.4  930.43  5308.3  931.91  5310.9  931.91
#Mann=4,-1,0
  4924.0    0.12       0  4977.8    0.05       0  4989.1   0.033       0
  4993.1    0.05       0
Bank Sta=4989.1,4993.1
Exp/Cntr=0.3,0.1

Type RM Length L Ch R = 1,2540,269,269,269
BEGIN DESCRIPTION:
UDS St 08 8.0
END DESCRIPTION:
XS GIS Cut Line= 3
      2283828.99      7194310.00      2283629.00      7194310.00
      2283429.04      7194359.99
#Sta/Elev= 30
  4799.6  927.66  4802.1  927.66  4809.6  923.26  4839.6  911.95  4859.6  908.49
  4869.6  906.02  4929.6  897.78  4959.6  894.80  4979.6  894.01  4987.6  889.85
  4987.8  889.35  4991.3  889.35  4991.6  889.85  5002.2  890.28  5009.9  893.78
  5017.6  896.33  5040.8  899.06  5051.1  900.86  5058.9  902.97  5068.4  902.98
  5068.7  902.97  5105.2  903.91  5133.6  906.10  5164.5  910.35  5174.8  913.63
  5182.6  916.84  5187.7  920.66  5195.4  922.00  5203.2  926.20  5205.7  926.20
#Mann=5,-1,0
  4799.6    0.05       0  4987.6   0.033       0  4991.6    0.05       0
  5068.4    0.12       0  5068.7    0.05       0
Bank Sta=4987.6,4991.6
Exp/Cntr=0.3,0.1

Type RM Length L Ch R = 1,2271,226,226,226
BEGIN DESCRIPTION:
UDS St 08 7.0
END DESCRIPTION:
XS GIS Cut Line= 3
      2283879.04      7194060.00      2283579.00      7194060.00
      2283379.00      7194110.00
#Sta/Elev= 30
  4700.3  934.32  4720.3  932.35  4740.3  927.83  4760.3  918.54  4770.3  915.29
  4790.3  907.08  4831.1  903.73  4850.3  901.48  4940.3  894.84  4950.3  893.07
  4960.3  889.44  4968.3  884.58  4968.6  884.08  4972.3  884.58  4980.3  884.85
  4997.8  888.34  5018.4  888.38  5051.9  893.81  5059.2  897.00  5064.8  896.77
  5072.5  898.44  5134.3  903.91  5147.2  906.09  5155.0  908.90  5175.6  914.44
  5183.3  920.40  5188.5  920.71  5196.2  925.44  5203.9  928.84  5206.5  928.84
#Mann=5,-1,0
  4700.3    0.05       0  4831.1    0.12       0  4968.3    0.07       0
  4972.3    0.12       0  5059.2    0.05       0
Bank Sta=4968.3,4972.3
Exp/Cntr=0.3,0.1

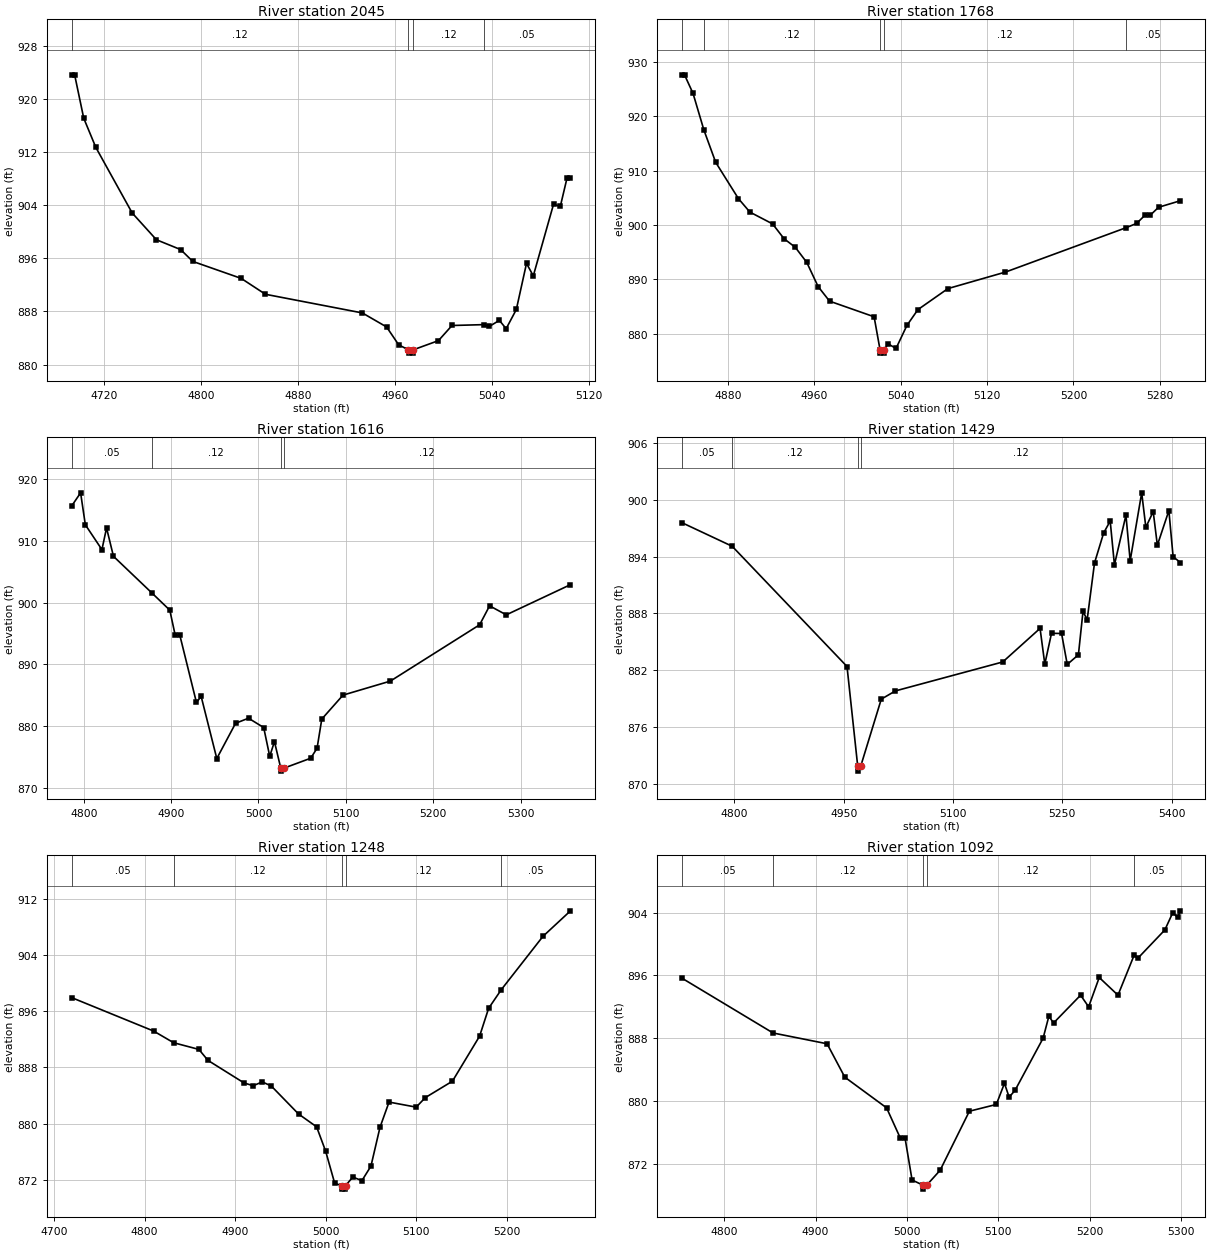
Type RM Length L Ch R = 1,2045,277,277,277
BEGIN DESCRIPTION:
UDS St 08 6.0
END DESCRIPTION:
XS GIS Cut Line= 3
      2283829.02      7193910.00      2283529.00      7193910.00
      2283429.02      7193860.01
#Sta/Elev= 30
  4693.1  923.62  4695.6  923.62  4703.1  917.09  4713.1  912.69  4743.1  902.82
  4763.1  898.79  4783.1  897.31  4793.1  895.53  4833.1  892.97  4853.1  890.58
  4933.1  887.77  4953.1  885.66  4963.1  882.97  4971.1  882.22  4971.4  881.72
  4974.9  881.72  4975.1  882.22  4995.9  883.60  5007.1  885.88  5033.4  886.01
  5037.8  885.73  5046.2  886.65  5051.8  885.40  5060.2  888.29  5068.6  895.23
  5074.2  893.35  5090.9  904.13  5096.5  903.81  5102.1  908.12  5104.9  908.12
#Mann=4,-1,0
  4693.1    0.12       0  4971.1    0.07       0  4975.1    0.12       0
  5033.4    0.05       0
Bank Sta=4971.1,4975.1
Exp/Cntr=0.3,0.1

Type RM Length L Ch R = 1,1768,152,152,152
BEGIN DESCRIPTION:
UDS St 08 5.0
END DESCRIPTION:
XS GIS Cut Line= 3
      2283879.02      7193810.01      2283729.00      7193760.00
      2283428.97      7193810.00
#Sta/Elev= 30
  4836.9  927.65  4839.6  927.65  4847.5  924.23  4857.6  917.47  4868.5  911.54
  4889.6  904.85  4900.2  902.38  4921.2  900.21  4931.8  897.49  4942.3  895.89
  4952.9  893.12  4963.4  888.68  4974.0  885.99  5015.3  883.11  5020.9  876.92
  5021.2  876.42  5024.7  876.42  5024.9  876.92  5028.0  878.16  5035.6  877.28
  5045.7  881.52  5055.9  884.43  5083.7  888.30  5137.0  891.34  5248.8  899.51
  5258.6  900.30  5266.2  901.79  5271.3  901.83  5278.9  903.27  5299.2  904.48
#Mann=5,-1,0
  4836.9    0.05       0  4857.6    0.12       0  5020.9    0.07       0
  5024.9    0.12       0  5248.8    0.05       0
Bank Sta=5020.9,5024.9
Exp/Cntr=0.3,0.1

Type RM Length L Ch R = 1,1616,187,187,187
BEGIN DESCRIPTION:
UDS St 08 4.1
END DESCRIPTION:
XS GIS Cut Line= 2
      2283923.59      7193531.25      2283392.28      7193740.67
#Sta/Elev= 30
  4786.1  915.64  4796.4  917.78  4801.8  912.61  4820.8  908.58  4826.1  912.09
  4834.0  907.50  4878.1  901.55  4898.5  898.78  4904.7  894.71  4910.0  894.71
  4929.0  883.83  4934.4  884.81  4952.3  874.75  4973.8  880.46  4988.6  881.28
  5006.0  879.77  5012.9  875.11  5018.3  877.49  5025.5  873.21  5025.8  872.71
  5029.5  873.21  5059.8  874.80  5067.1  876.42  5072.5  881.14  5096.8  885.02
  5151.0  887.29  5253.2  896.41  5264.6  899.48  5283.7  898.02  5357.2  902.91
#Mann=4,-1,0
  4786.1    0.05       0  4878.1    0.12       0  5025.5    0.07       0
  5029.5    0.12       0
Bank Sta=5025.5,5029.5
Exp/Cntr=0.3,0.1

Type RM Length L Ch R = 1,1429,181,181,181
BEGIN DESCRIPTION:
UDS St 08 4.0
END DESCRIPTION:
XS GIS Cut Line= 3
      2283838.22      7193353.99      2283592.79      7193477.13
      2283237.66      7193681.44
#Sta/Elev= 30
  4727.7  897.61  4797.1  895.10  4954.6  882.39  4969.3  871.83  4969.6  871.33
  4973.3  871.83  5001.6  878.94  5021.0  879.81  5168.2  882.87  5219.4  886.42
  5225.9  882.64  5235.1  885.90  5248.9  885.88  5256.7  882.61  5272.0  883.63
  5278.3  888.22  5284.0  887.33  5294.1  893.34  5306.6  896.50  5315.6  897.77
  5321.4  893.14  5337.2  898.38  5343.0  893.58  5358.8  900.75  5364.5  897.11
  5374.6  898.76  5380.3  895.21  5396.1  898.87  5401.9  893.99  5412.0  893.38
#Mann=4,-1,0
  4727.7    0.05       0  4797.1    0.12       0  4969.3    0.07       0
  4973.3    0.12       0
Bank Sta=4969.3,4973.3
Exp/Cntr=0.3,0.1

Type RM Length L Ch R = 1,1248,156,156,156
BEGIN DESCRIPTION:
UDS St 08 3.1
END DESCRIPTION:
XS GIS Cut Line= 2
      2283859.57      7193300.10      2283308.58      7193297.93
#Sta/Elev= 30
  4719.3  897.94  4809.9  893.18  4832.0  891.52  4859.9  890.57  4869.9  889.01
  4909.9  885.79  4919.9  885.41  4929.9  885.95  4939.9  885.36  4969.9  881.39
  4989.9  879.56  4999.9  876.09  5009.9  871.52  5017.9  871.20  5018.1  870.70
  5021.6  870.70  5021.9  871.20  5029.9  872.42  5039.9  871.90  5049.9  873.97
  5059.9  879.49  5069.9  883.08  5099.9  882.36  5109.9  883.71  5139.9  886.05
  5169.9  892.45  5179.9  896.42  5194.0  899.09  5239.9  906.65  5270.3  910.28
#Mann=5,-1,0
  4719.3    0.05       0  4832.0    0.12       0  5017.9    0.07       0
  5021.9    0.12       0  5194.0    0.05       0
Bank Sta=5017.9,5021.9
Exp/Cntr=0.3,0.1

Type RM Length L Ch R = 1,1092,154,154,154
BEGIN DESCRIPTION:
UDS St 08 3.0
END DESCRIPTION:
XS GIS Cut Line= 3
      2283863.06      7193221.12      2283629.00      7193160.00
      2283332.27      7193093.98
#Sta/Elev= 30
  4753.4  895.68  4853.5  888.68  4912.6  887.31  4932.0  883.06  4977.7  879.16
  4992.7  875.32  4997.9  875.32  5005.6  869.98  5017.6  869.32  5017.9  868.82
  5021.6  869.32  5036.3  871.22  5068.3  878.73  5097.8  879.59  5106.7  882.28
  5111.8  880.52  5118.2  881.37  5149.0  888.02  5155.3  890.82  5160.4  889.95
  5190.0  893.49  5198.8  892.01  5210.4  895.74  5230.9  893.49  5248.6  898.58
  5252.6  898.18  5282.2  901.79  5290.9  903.99  5296.1  903.39  5299.3  904.22
#Mann=5,-1,0
  4753.4    0.05       0  4853.5    0.12       0  5017.6    0.07       0
  5021.6    0.12       0  5248.6    0.05       0
Bank Sta=5017.6,5021.6
Exp/Cntr=0.3,0.1

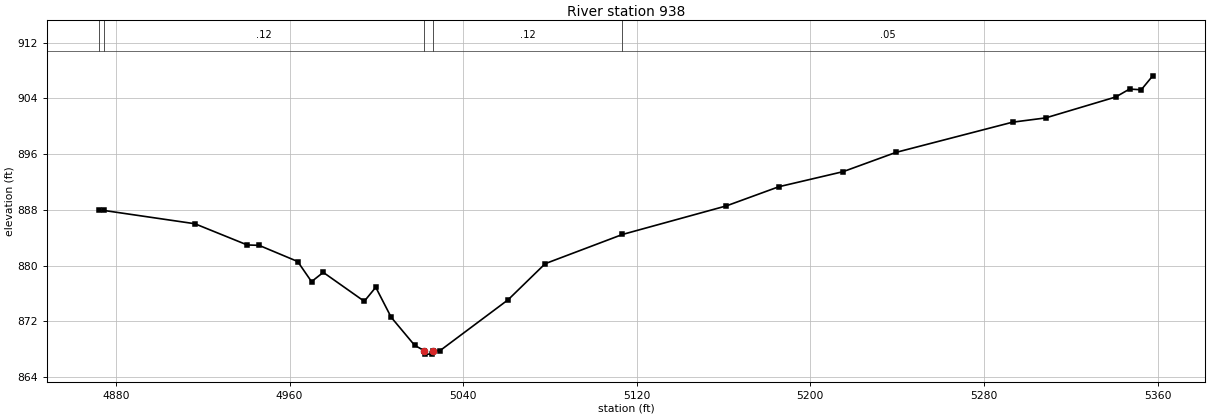
Type RM Length L Ch R = 1,938,0,0,0
BEGIN DESCRIPTION:
UDS St 08 2.1
END DESCRIPTION:
XS GIS Cut Line= 2
      2283823.88      7193081.71      2283373.11      7192901.40
#Sta/Elev= 30
  4872.3  887.92  4874.5  887.92  4916.3  886.02  4940.5  882.97  4945.9  882.92
  4963.7  880.60  4970.1  877.71  4975.5  879.04  4994.4  874.89  4999.7  876.90
  5006.8  872.60  5017.6  868.58  5022.0  867.81  5022.2  867.31  5025.7  867.31
  5026.0  867.81  5029.4  867.83  5060.7  875.11  5077.8  880.29  5113.4  884.48
  5161.3  888.58  5185.5  891.33  5215.1  893.49  5239.4  896.25  5293.2  900.59
  5308.4  901.20  5340.7  904.20  5347.1  905.34  5352.5  905.24  5357.8  907.24
#Mann=5,-1,0
  4872.3    0.05       0  4874.5    0.12       0  5022.0    0.07       0
  5026.0    0.12       0  5113.4    0.05       0
Bank Sta=5022,5026
Exp/Cntr=0.3,0.1

Chan Stop Cuts=-1