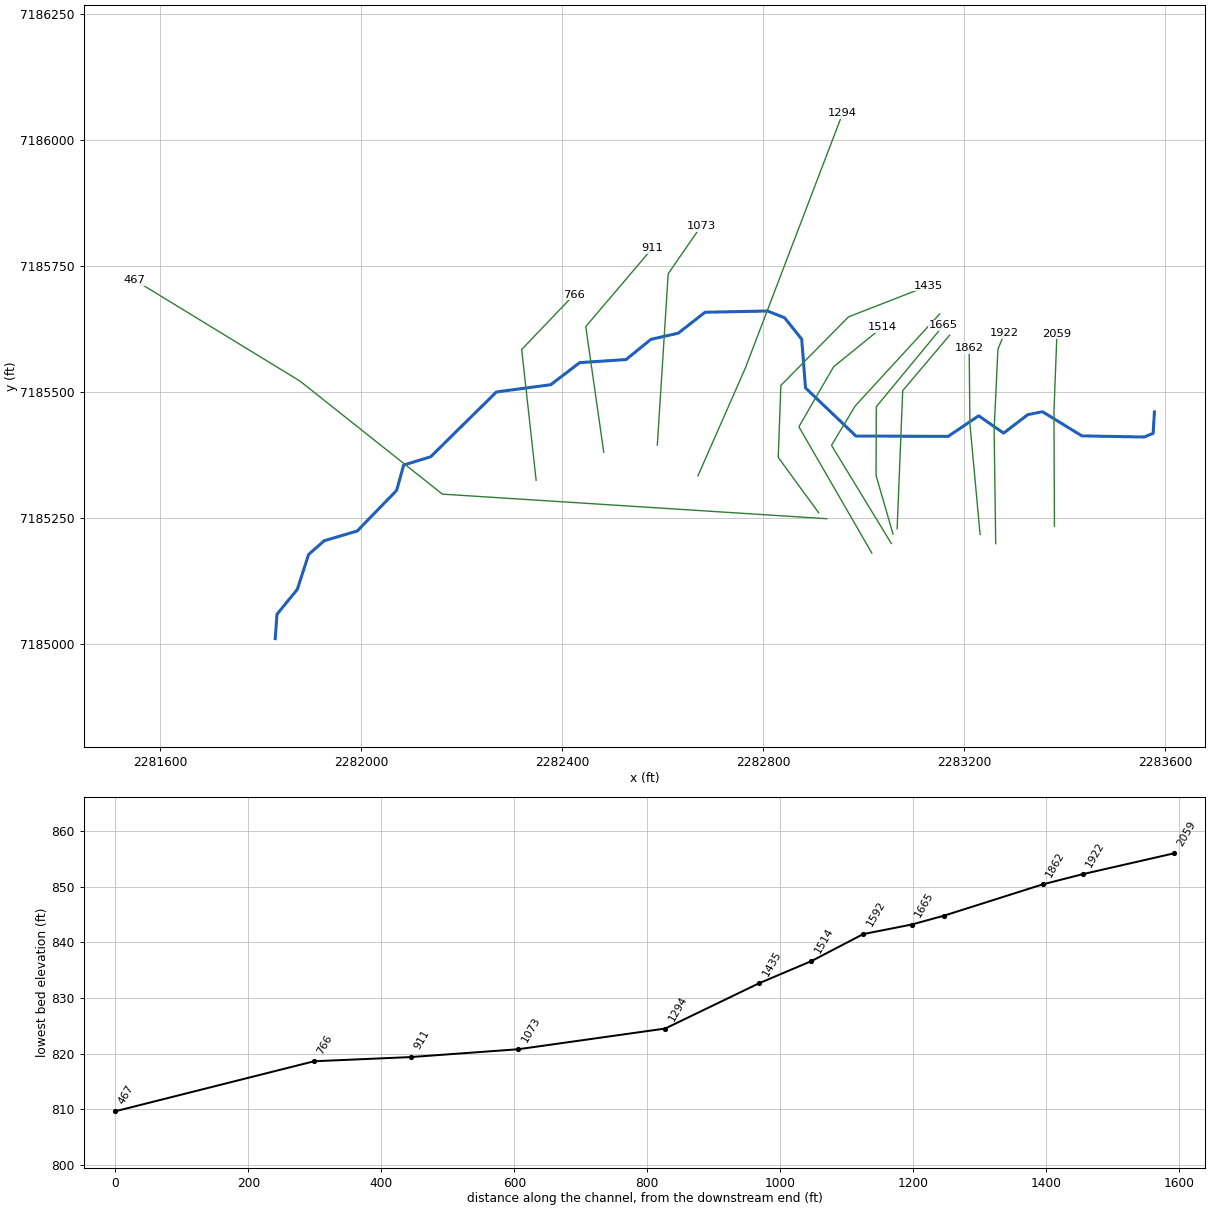
--- UDS St 09.prj (project) ---

Proj Title=UDS St 09 Base Level Engineering
Current Plan=p01
Default Exp/Contr=0.3,0.1
English Units
Geom File=g01
Flow File=f01
Plan File=p01
BEGIN DESCRIPTION:
UDS St 09
END DESCRIPTION:

--- UDS St 09.p01 (plan) ---

Plan Title=Multiple Run
Short Identifier=Multiple
Geom File=g01
Flow File=f01
Subcritical Flow
K Sum by GR= 0
Std Step Tol= 0.01
Critical Tol= 0.01
Num of Std Step Trials= 20
Max Error Tol= 0.3
Flow Tol Ratio= 0.001
Split Flow NTrial= 30
Split Flow Tol= 0.02
Split Flow Ratio= 0.02
Log Output Level= 0
Friction Slope Method= 1
Unsteady Friction Slope Method= 2
Unsteady Bridges Friction Slope Method= 1
Parabolic Critical Depth
Global Vel Dist=  1 , 1 , 1
Global Log Level= 0
CheckData=True
Encroach Param= -1, 0, 0, 0
BEGIN DESCRIPTION:
Multiple Run
END DESCRIPTION:

--- UDS St 09.f01 (steady flow) ---

Flow Title=Multiple
Number of Profiles=7
Profile Names=10-year,25-year,50-year,1pct_min,100-year,1pct_plu,500-year
River Rch & RM= UDS St 09,Reach-1,2059
     140     175     201     116     231     462     305
Boundary for River Rch & Prof#=UDS St 09,Reach-1,1
Up Type=0
Dn Type=3
Dn Slope=0.005
Boundary for River Rch & Prof#=UDS St 09,Reach-1,2
Up Type=0
Dn Type=3
Dn Slope=0.005
Boundary for River Rch & Prof#=UDS St 09,Reach-1,3
Up Type=0
Dn Type=3
Dn Slope=0.005
Boundary for River Rch & Prof#=UDS St 09,Reach-1,4
Up Type=0
Dn Type=3
Dn Slope=0.005
Boundary for River Rch & Prof#=UDS St 09,Reach-1,5
Up Type=0
Dn Type=3
Dn Slope=0.005
Boundary for River Rch & Prof#=UDS St 09,Reach-1,6
Up Type=0
Dn Type=3
Dn Slope=0.005
Boundary for River Rch & Prof#=UDS St 09,Reach-1,7
Up Type=0
Dn Type=3
Dn Slope=0.005

--- UDS St 09.g01 (geometry) ---

Geom Title=Existing Conditions

River Reach=UDS St 09,Reach-1
Reach XY= 30
      2283579.00      7185460.00      2283576.45      7185417.45
      2283558.88      7185410.08      2283434.53      7185412.39
      2283356.16      7185460.30      2283326.70      7185454.37
      2283278.92      7185417.83      2283229.10      7185452.21
      2283168.57      7185411.37      2282984.84      7185412.05
      2282884.52      7185507.56      2282876.93      7185604.31
      2282842.73      7185646.81      2282809.12      7185660.11
      2282684.52      7185657.66      2282631.18      7185616.12
      2282576.82      7185603.89      2282527.42      7185563.83
      2282434.97      7185557.65      2282377.40      7185513.86
      2282269.21      7185499.48      2282138.42      7185370.89
      2282084.62      7185354.38      2282070.72      7185304.23
      2281992.22      7185223.63      2281926.46      7185204.25
      2281895.48      7185177.06      2281873.01      7185107.79
      2281832.60      7185058.51      2281829.00      7185010.00

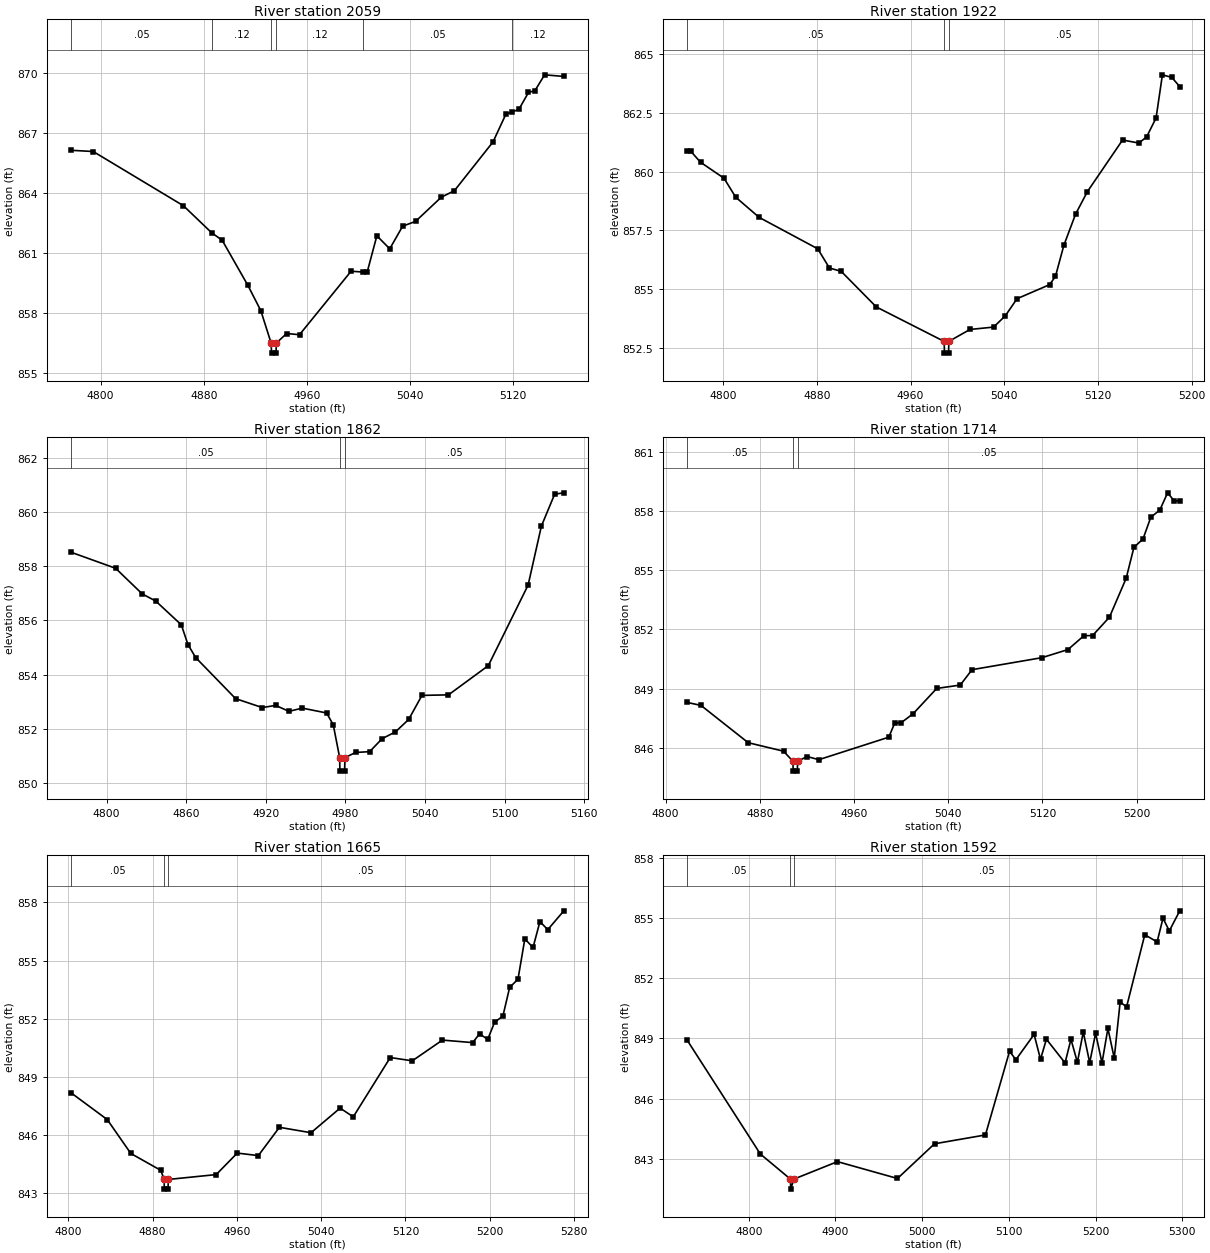
Type RM Length L Ch R = 1,2059,137,137,137
BEGIN DESCRIPTION:
UDS St 09 2.0
END DESCRIPTION:
XS GIS Cut Line= 3
      2283379.99      7185233.00      2283379.00      7185460.00
      2283384.96      7185614.88
#Sta/Elev= 30
  4777.3  866.13  4794.3  866.07  4864.3  863.36  4886.2  862.01  4894.3  861.64
  4914.3  859.38  4924.3  858.12  4932.3  856.50  4932.6  856.00  4936.1  856.00
  4936.3  856.50  4944.3  856.98  4954.3  856.92  4994.3  860.09  5003.7  860.05
  5006.8  860.05  5014.3  861.86  5024.3  861.21  5034.3  862.34  5044.3  862.58
  5064.3  863.79  5074.4  864.11  5104.4  866.55  5114.4  867.94  5119.2  868.05
  5124.4  868.17  5131.9  869.02  5136.9  869.11  5144.4  869.90  5159.3  869.82
#Mann=6,-1,0
  4777.3    0.05       0  4886.2    0.12       0  4932.3    0.07       0
  4936.3    0.12       0  5003.7    0.05       0  5119.2    0.12       0
Bank Sta=4932.3,4936.3
Exp/Cntr=0.3,0.1

Type RM Length L Ch R = 1,1922,60,60,60
BEGIN DESCRIPTION:
UDS St 09 1.1
END DESCRIPTION:
XS GIS Cut Line= 4
      2283263.08      7185198.59      2283259.95      7185424.74
      2283267.47      7185583.91      2283280.48      7185616.28
#Sta/Elev= 30
  4769.4  860.86  4772.6  860.86  4780.8  860.40  4800.8  859.72  4810.8  858.91
  4830.8  858.05  4880.8  856.71  4890.8  855.89  4900.8  855.75  4930.8  854.23
  4988.7  852.76  4989.0  852.26  4992.5  852.26  4992.7  852.76  5010.8  853.27
  5030.9  853.37  5040.9  853.85  5050.9  854.58  5078.7  855.18  5083.7  855.53
  5090.9  856.86  5100.9  858.19  5111.0  859.15  5141.0  861.35  5154.9  861.22
  5161.5  861.48  5169.6  862.29  5175.0  864.13  5183.0  864.02  5189.8  863.63
#Mann=3,-1,0
  4769.4    0.05       0  4988.7   0.033       0  4992.7    0.05       0
Bank Sta=4988.7,4992.7
Exp/Cntr=0.3,0.1

Type RM Length L Ch R = 1,1862,148,148,148
BEGIN DESCRIPTION:
UDS St 09 1.0
END DESCRIPTION:
XS GIS Cut Line= 3
      2283232.03      7185216.70      2283211.72      7185436.18
      2283210.24      7185586.85
#Sta/Elev= 30
  4773.4  858.52  4806.8  857.93  4826.9  856.98  4837.0  856.72  4856.3  855.84
  4861.3  855.11  4867.1  854.63  4897.2  853.11  4917.3  852.78  4927.4  852.86
  4937.4  852.64  4947.4  852.76  4965.8  852.58  4970.8  852.14  4975.6  850.93
  4975.8  850.43  4979.3  850.43  4979.6  850.93  4987.6  851.12  4998.2  851.15
  5007.6  851.63  5017.6  851.88  5027.6  852.34  5037.6  853.23  5057.6  853.25
  5087.6  854.33  5117.6  857.31  5127.6  859.49  5137.6  860.67  5144.5  860.72
#Mann=3,-1,0
  4773.4    0.05       0  4975.6   0.033       0  4979.6    0.05       0
Bank Sta=4975.6,4979.6
Exp/Cntr=0.3,0.1

Type RM Length L Ch R = 1,1714,49,49,49
BEGIN DESCRIPTION:
UDS St 09 0.9
END DESCRIPTION:
XS GIS Cut Line= 3
      2283066.89      7185228.29      2283077.99      7185502.08
      2283171.34      7185612.09
#Sta/Elev= 30
  4818.3  848.30  4830.0  848.15  4870.1  846.26  4900.1  845.83  4908.1  845.32
  4908.3  844.82  4911.8  844.82  4912.1  845.32  4920.1  845.56  4930.1  845.40
  4989.5  846.54  4994.5  847.25  5000.2  847.28  5010.2  847.73  5030.2  849.01
  5050.2  849.18  5060.2  849.96  5119.7  850.57  5141.7  850.98  5155.2  851.68
  5162.6  851.69  5176.9  852.62  5191.1  854.59  5197.7  856.16  5205.4  856.58
  5212.0  857.68  5219.7  858.05  5226.3  858.92  5231.9  858.51  5236.6  858.51
#Mann=3,-1,0
  4818.3    0.05       0  4908.1   0.033       0  4912.1    0.05       0
Bank Sta=4908.1,4912.1
Exp/Cntr=0.3,0.1

Type RM Length L Ch R = 1,1665,73,73,73
BEGIN DESCRIPTION:
UDS St 09 0.82
END DESCRIPTION:
XS GIS Cut Line= 4
      2283058.75      7185217.28      2283024.92      7185333.83
      2283025.40      7185470.19      2283159.12      7185631.69
#Sta/Elev= 30
  4802.9  848.17  4837.0  846.80  4859.4  845.05  4887.8  844.18  4891.0  843.71
  4891.2  843.21  4894.7  843.21  4895.0  843.71  4940.4  843.96  4960.4  845.07
  4980.4  844.94  5000.4  846.40  5030.4  846.12  5058.0  847.39  5070.5  846.94
  5105.6  850.00  5126.5  849.83  5155.1  850.90  5183.8  850.77  5190.3  851.22
  5198.1  850.94  5204.6  851.82  5212.5  852.14  5218.9  853.62  5226.8  854.04
  5233.3  856.12  5241.1  855.68  5247.6  857.01  5255.1  856.60  5270.3  857.57
#Mann=3,-1,0
  4802.9    0.05       0  4891.0   0.033       0  4895.0    0.05       0
Bank Sta=4891,4895
Exp/Cntr=0.3,0.1

Type RM Length L Ch R = 1,1592,78,78,78
BEGIN DESCRIPTION:
UDS St 09 0.81
END DESCRIPTION:
XS GIS Cut Line= 4
      2283055.32      7185198.81      2282936.26      7185393.56
      2282983.61      7185471.95      2283151.61      7185654.32
#Sta/Elev= 30
  4729.1  848.91  4813.4  843.24  4848.1  841.99  4848.4  841.49  4852.1  841.99
  4902.3  842.86  4971.5  842.02  5014.2  843.75  5072.9  844.19  5100.7  848.36
  5108.0  847.94  5129.0  849.20  5136.4  847.96  5143.2  848.96  5164.7  847.78
  5171.5  848.96  5178.9  847.81  5185.7  849.32  5193.1  847.79  5199.9  849.26
  5207.3  847.78  5214.1  849.50  5221.4  848.02  5228.2  850.82  5235.6  850.57
  5256.6  854.17  5270.8  853.81  5277.6  854.99  5284.9  854.36  5296.9  855.36
#Mann=3,-1,0
  4729.1    0.05       0  4848.1   0.033       0  4852.1    0.05       0
Bank Sta=4848.1,4852.1
Exp/Cntr=0.3,0.1

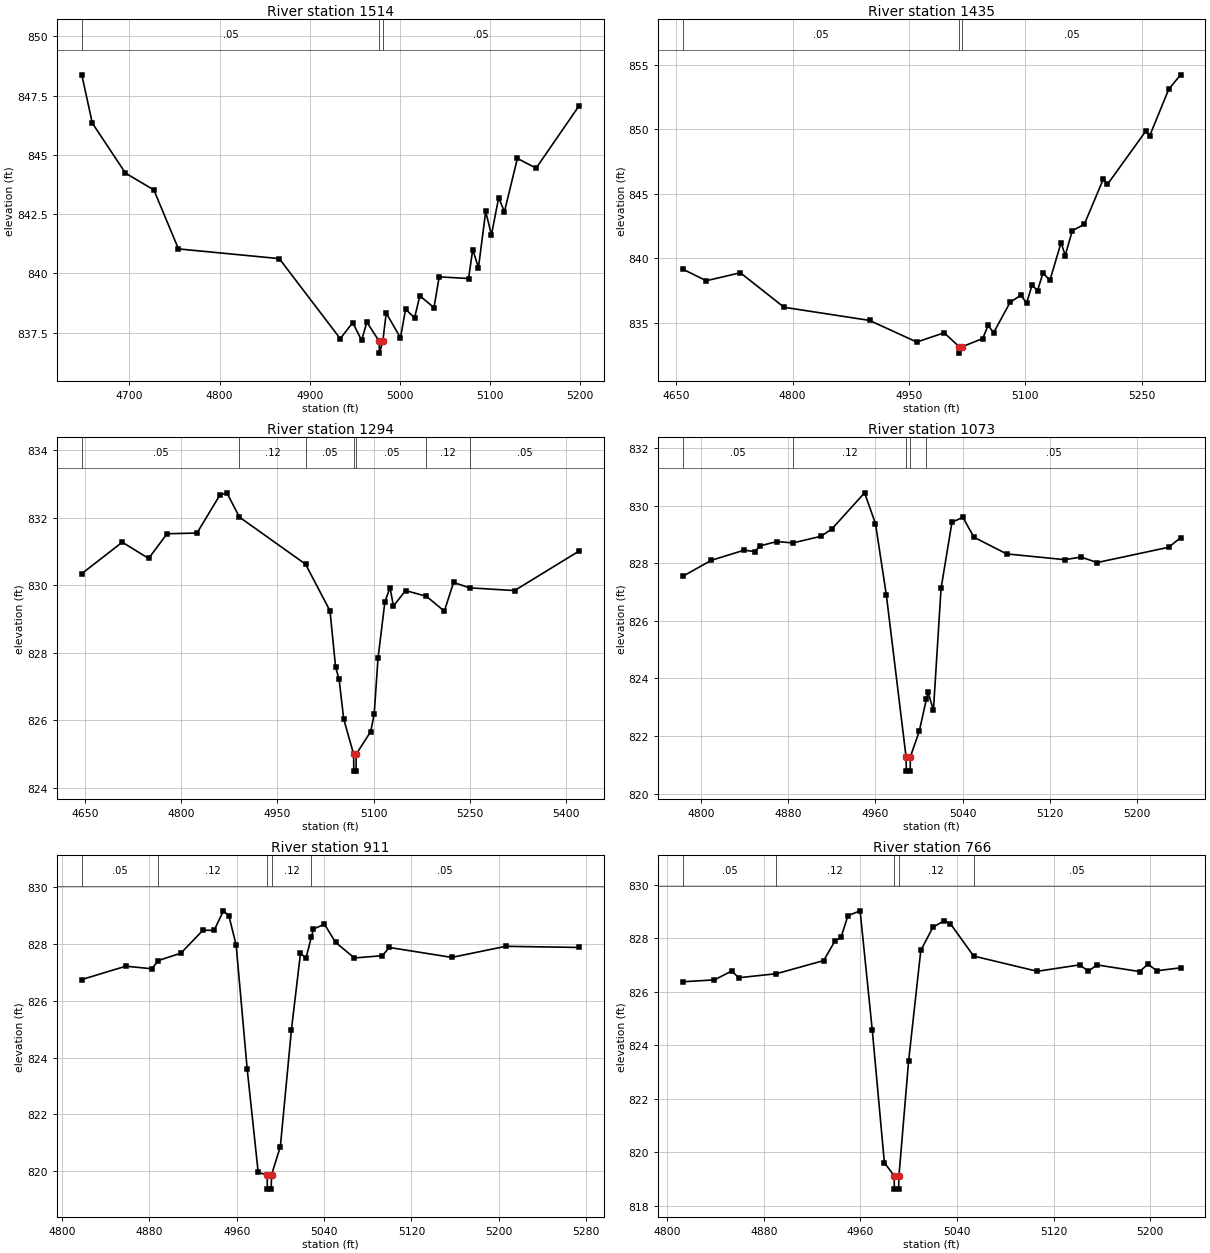
Type RM Length L Ch R = 1,1514,79,79,79
BEGIN DESCRIPTION:
UDS St 09 0.8
END DESCRIPTION:
XS GIS Cut Line= 4
      2283016.48      7185179.88      2282871.32      7185430.40
      2282940.24      7185549.22      2283037.49      7185628.06
#Sta/Elev= 30
  4647.1  848.38  4658.8  846.34  4695.6  844.23  4727.1  843.52  4754.4  841.03
  4866.3  840.62  4934.0  837.24  4947.8  837.92  4957.7  837.17  4963.5  837.94
  4977.2  837.13  4977.5  836.63  4981.2  837.13  4985.0  838.32  5000.8  837.28
  5006.5  838.48  5016.5  838.12  5022.3  839.05  5038.0  838.55  5043.8  839.85
  5076.4  839.78  5081.0  841.00  5087.4  840.24  5095.4  842.61  5101.8  841.62
  5109.8  843.19  5116.2  842.60  5130.6  844.85  5151.4  844.44  5199.2  847.08
#Mann=3,-1,0
  4647.1    0.05       0  4977.2   0.033       0  4981.2    0.05       0
Bank Sta=4977.2,4981.2
Exp/Cntr=0.3,0.1

Type RM Length L Ch R = 1,1435,141,141,141
BEGIN DESCRIPTION:
UDS St 09 0.75
END DESCRIPTION:
XS GIS Cut Line= 5
      2282910.64      7185259.82      2282830.24      7185369.67
      2282835.48      7185512.54      2282970.03      7185648.44
      2283128.90      7185710.24
#Sta/Elev= 30
  4659.1  839.14  4688.8  838.25  4732.8  838.87  4789.2  836.19  4899.2  835.17
  4960.1  833.49  4995.4  834.21  5014.7  833.13  5014.9  832.63  5018.7  833.13
  5045.0  833.76  5052.0  834.78  5059.1  834.22  5080.3  836.57  5094.4  837.14
  5101.5  836.50  5108.6  837.91  5115.7  837.49  5122.7  838.86  5131.6  838.28
  5146.0  841.21  5151.3  840.21  5160.5  842.14  5175.9  842.63  5200.4  846.14
  5205.7  845.73  5254.8  849.84  5260.2  849.51  5284.7  853.12  5299.9  854.24
#Mann=3,-1,0
  4659.1    0.05       0  5014.7   0.033       0  5018.7    0.05       0
Bank Sta=5014.7,5018.7
Exp/Cntr=0.3,0.1

Type RM Length L Ch R = 1,1294,221,221,221
BEGIN DESCRIPTION:
UDS St 09 0.7
END DESCRIPTION:
XS GIS Cut Line= 3
      2282670.42      7185333.07      2282764.57      7185546.46
      2282958.64      7186052.91
#Sta/Elev= 30
  4645.0  830.34  4708.1  831.27  4749.2  830.79  4778.0  831.52  4824.6  831.54
  4860.2  832.66  4871.2  832.73  4890.9  832.01  4993.9  830.62  5032.0  829.24
  5040.8  827.57  5046.2  827.22  5053.4  826.04  5068.9  825.00  5069.1  824.50
  5072.6  824.50  5072.9  825.00  5095.5  825.67  5100.9  826.18  5106.9  827.84
  5117.6  829.50  5125.6  829.93  5130.9  829.38  5149.8  829.84  5182.4  829.67
  5210.3  829.23  5224.7  830.08  5249.8  829.92  5319.8  829.84  5420.6  831.01
#Mann=7,-1,0
  4645.0    0.05       0  4890.9    0.12       0  4993.9    0.05       0
  5068.9   0.033       0  5072.9    0.05       0  5182.4    0.12       0
  5249.8    0.05       0
Bank Sta=5068.9,5072.9
Exp/Cntr=0.3,0.1

Type RM Length L Ch R = 1,1073,162,162,162
BEGIN DESCRIPTION:
UDS St 09 0.6
END DESCRIPTION:
XS GIS Cut Line= 3
      2282589.55      7185394.07      2282611.20      7185734.11
      2282676.84      7185828.75
#Sta/Elev= 30
  4783.7  827.55  4809.7  828.10  4839.7  828.45  4849.3  828.40  4854.3  828.60
  4869.8  828.75  4884.2  828.70  4909.9  828.93  4919.9  829.18  4950.0  830.44
  4960.0  829.37  4970.0  826.88  4988.0  821.28  4988.3  820.78  4991.8  820.78
  4992.0  821.28  5000.1  822.16  5006.6  823.27  5008.1  823.53  5013.1  822.89
  5020.1  827.12  5030.1  829.42  5040.1  829.59  5050.2  828.90  5080.2  828.32
  5133.5  828.12  5148.4  828.21  5163.2  828.02  5228.7  828.55  5239.6  828.88
#Mann=5,-1,0
  4783.7    0.05       0  4884.2    0.12       0  4988.0    0.07       0
  4992.0    0.12       0  5006.6    0.05       0
Bank Sta=4988,4992
Exp/Cntr=0.3,0.1

Type RM Length L Ch R = 1,911,145,145,145
BEGIN DESCRIPTION:
UDS St 09 0.5
END DESCRIPTION:
XS GIS Cut Line= 3
      2282482.90      7185380.09      2282447.15      7185629.30
      2282579.30      7185784.23
#Sta/Elev= 30
  4818.2  826.75  4858.5  827.22  4882.3  827.13  4888.4  827.42  4909.0  827.68
  4929.2  828.49  4939.3  828.48  4947.9  829.17  4952.9  828.99  4959.5  827.97
  4969.6  823.61  4979.7  819.96  4987.9  819.87  4988.1  819.37  4991.6  819.37
  4991.9  819.87  5000.0  820.87  5010.1  824.97  5018.4  827.67  5023.5  827.51
  5028.4  828.25  5030.3  828.53  5040.4  828.70  5050.5  828.06  5067.8  827.51
  5093.3  827.59  5099.8  827.88  5156.9  827.53  5206.3  827.92  5273.6  827.88
#Mann=5,-1,0
  4818.2    0.05       0  4888.4    0.12       0  4987.9    0.07       0
  4991.9    0.12       0  5028.4    0.05       0
Bank Sta=4987.9,4991.9
Exp/Cntr=0.3,0.1

Type RM Length L Ch R = 1,766,299,299,299
BEGIN DESCRIPTION:
UDS St 09 0.4
END DESCRIPTION:
XS GIS Cut Line= 3
      2282348.35      7185324.20      2282319.56      7185583.73
      2282424.16      7185692.88
#Sta/Elev= 30
  4813.0  826.37  4839.0  826.44  4853.2  826.77  4859.1  826.52  4890.3  826.67
  4929.5  827.16  4938.8  827.89  4943.9  828.03  4949.6  828.84  4959.7  829.02
  4969.8  824.55  4979.8  819.61  4987.9  819.12  4988.1  818.62  4991.6  818.62
  4991.9  819.12  4999.9  823.41  5010.0  827.54  5020.1  828.41  5029.5  828.65
  5034.5  828.54  5053.8  827.33  5106.5  826.76  5141.7  827.00  5149.0  826.76
  5155.9  827.00  5191.4  826.75  5198.3  827.03  5205.6  826.78  5225.3  826.89
#Mann=5,-1,0
  4813.0    0.05       0  4890.3    0.12       0  4987.9    0.07       0
  4991.9    0.12       0  5053.8    0.05       0
Bank Sta=4987.9,4991.9
Exp/Cntr=0.3,0.1

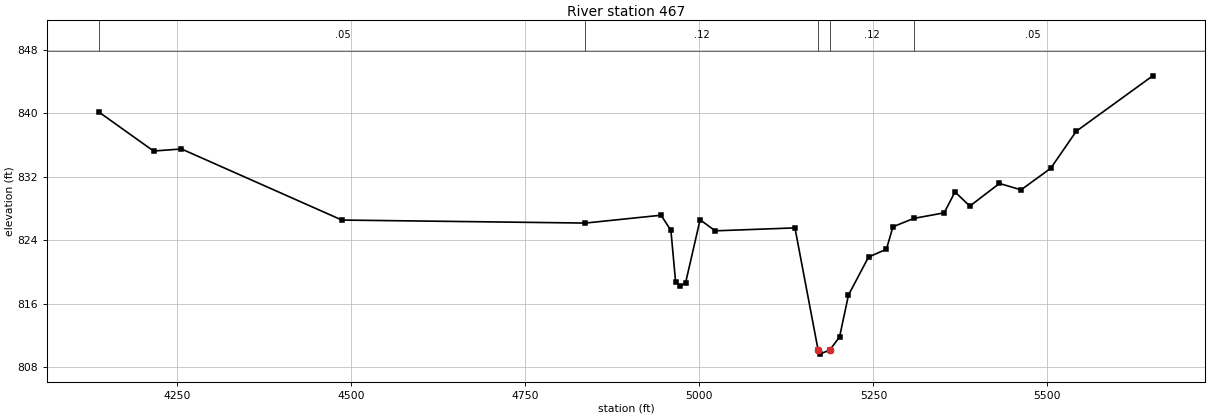
Type RM Length L Ch R = 1,467,0,0,0
BEGIN DESCRIPTION:
UDS St 09 0.3
END DESCRIPTION:
XS GIS Cut Line= 4
      2282926.74      7185248.00      2282161.75      7185296.78
      2281878.08      7185521.27      2281549.25      7185721.52
#Sta/Elev= 30
  4138.0  840.14  4215.9  835.26  4256.0  835.52  4486.4  826.55  4836.3  826.17
  4945.0  827.16  4959.1  825.24  4965.8  818.79  4972.2  818.18  4980.2  818.63
  5001.0  826.58  5022.8  825.19  5137.3  825.56  5170.6  810.13  5172.6  809.63
  5187.2  810.13  5201.4  811.80  5214.2  817.09  5243.0  821.88  5268.7  822.87
  5278.1  825.70  5308.1  826.76  5351.7  827.46  5367.2  830.10  5388.5  828.31
  5431.1  831.17  5462.1  830.36  5504.7  833.08  5541.5  837.76  5651.3  844.75
#Mann=5,-1,0
  4138.0    0.05       0  4836.3    0.12       0  5170.6    0.07       0
  5187.2    0.12       0  5308.1    0.05       0
Bank Sta=5170.6,5187.2
Exp/Cntr=0.3,0.1

Chan Stop Cuts=-1