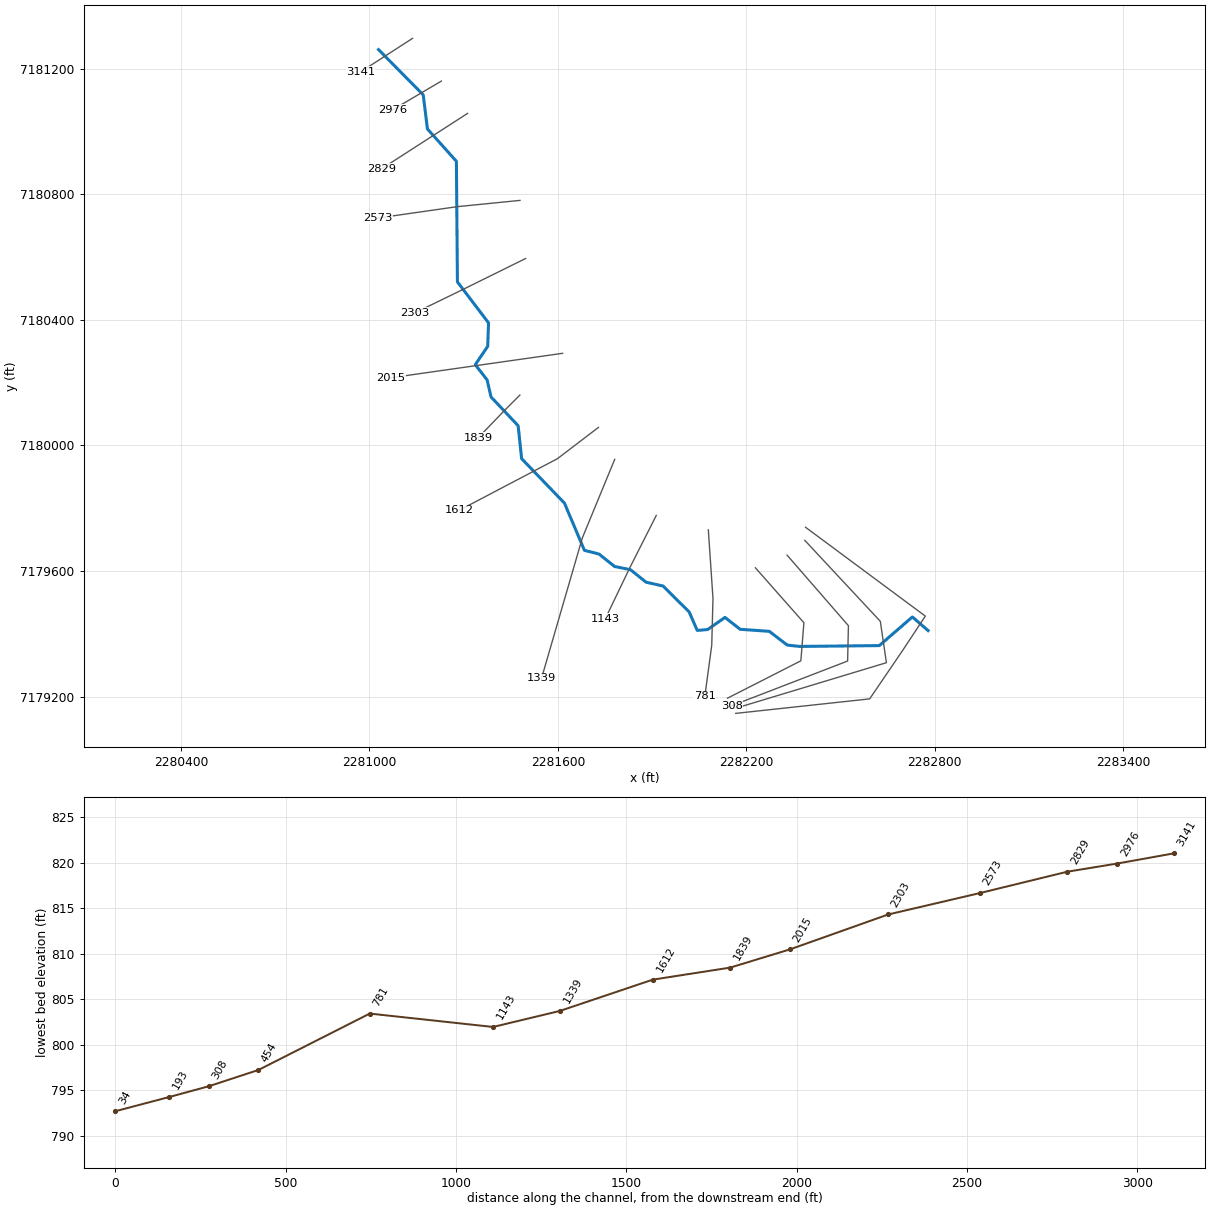
--- UDS St 10.prj (project) ---

Proj Title=UDS St 10 Base Level Engineering
Current Plan=p01
Default Exp/Contr=0.3,0.1
English Units
Geom File=g01
Flow File=f01
Plan File=p01
Y Axis Title=Elevation
X Axis Title(PF)=Main Channel Distance
X Axis Title(XS)=Station
BEGIN DESCRIPTION:
UDS St 10
END DESCRIPTION:
DSS Export Rating Curves= 0
DSS Export Rating Curve Sorted= 0
DSS Export Volume Flow Curves= 0
DXF OffsetX= 0
DXF OffsetY= 0
DXF ScaleX= 1
DXF ScaleY= 10

--- UDS St 10.p01 (plan) ---

Plan Title=Multiple Run
Short Identifier=Multiple
Geom File=g01
Flow File=f01
Subcritical Flow
K Sum by GR= 0
Std Step Tol= 0.01
Critical Tol= 0.01
Num of Std Step Trials= 20
Max Error Tol= 0.3
Flow Tol Ratio= 0.001
Split Flow NTrial= 30
Split Flow Tol= 0.02
Split Flow Ratio= 0.02
Log Output Level= 0
Friction Slope Method= 1
Unsteady Friction Slope Method= 2
Unsteady Bridges Friction Slope Method= 1
Parabolic Critical Depth
Global Vel Dist=  1 , 1 , 1
Global Log Level= 0
CheckData=True
Encroach Param= -1, 0, 0, 0
BEGIN DESCRIPTION:
Multiple Run
END DESCRIPTION:

--- UDS St 10.f01 (steady flow) ---

Flow Title=Multiple
Program Version=4.10
Number of Profiles= 7
Profile Names=10-year,25-year,50-year,1pct_min,100-year,1pct_plu,500-year
River Rch & RM=UDS St 10,Reach-1         ,3141
     555     757     924     561    1118    2231    1641
River Rch & RM=UDS St 10,Reach-1         ,34
    3363    4965    6384    4053    8086   16134   13016
Boundary for River Rch & Prof#=UDS St 10,Reach-1         , 1
Up Type= 0
Dn Type= 3
Dn Slope=0.015
Boundary for River Rch & Prof#=UDS St 10,Reach-1         , 2
Up Type= 0
Dn Type= 3
Dn Slope=0.015
Boundary for River Rch & Prof#=UDS St 10,Reach-1         , 3
Up Type= 0
Dn Type= 3
Dn Slope=0.015
Boundary for River Rch & Prof#=UDS St 10,Reach-1         , 4
Up Type= 0
Dn Type= 3
Dn Slope=0.015
Boundary for River Rch & Prof#=UDS St 10,Reach-1         , 5
Up Type= 0
Dn Type= 3
Dn Slope=0.015
Boundary for River Rch & Prof#=UDS St 10,Reach-1         , 6
Up Type= 0
Dn Type= 3
Dn Slope=0.015
Boundary for River Rch & Prof#=UDS St 10,Reach-1         , 7
Up Type= 0
Dn Type= 3
Dn Slope=0.015
DSS Import GetInterval= 0
DSS Import GetPeak= 0
DSS Import FillOption= 0

--- UDS St 10.g01 (geometry) ---

Geom Title=Existing Conditions

River Reach=UDS St 10,Reach-1
Reach XY= 30
      2281029.00      7181260.00      2281171.14      7181116.17
      2281184.54      7181007.58      2281276.82      7180904.55
      2281280.06      7180520.44      2281379.20      7180389.94
      2281376.52      7180315.49      2281337.04      7180256.68
      2281374.55      7180208.35      2281387.14      7180153.96
      2281473.46      7180062.42      2281484.52      7179957.57
      2281620.86      7179816.05      2281684.58      7179665.58
      2281730.85      7179653.76      2281780.69      7179614.15
      2281831.19      7179603.92      2281880.74      7179564.19
      2281935.07      7179551.86      2282018.12      7179469.35
      2282043.91      7179410.50      2282076.99      7179413.42
      2282132.27      7179451.89      2282180.50      7179414.09
      2282273.43      7179407.53      2282330.56      7179363.78
      2282369.72      7179359.55      2282623.56      7179362.18
      2282729.01      7179453.41      2282779.00      7179410.00

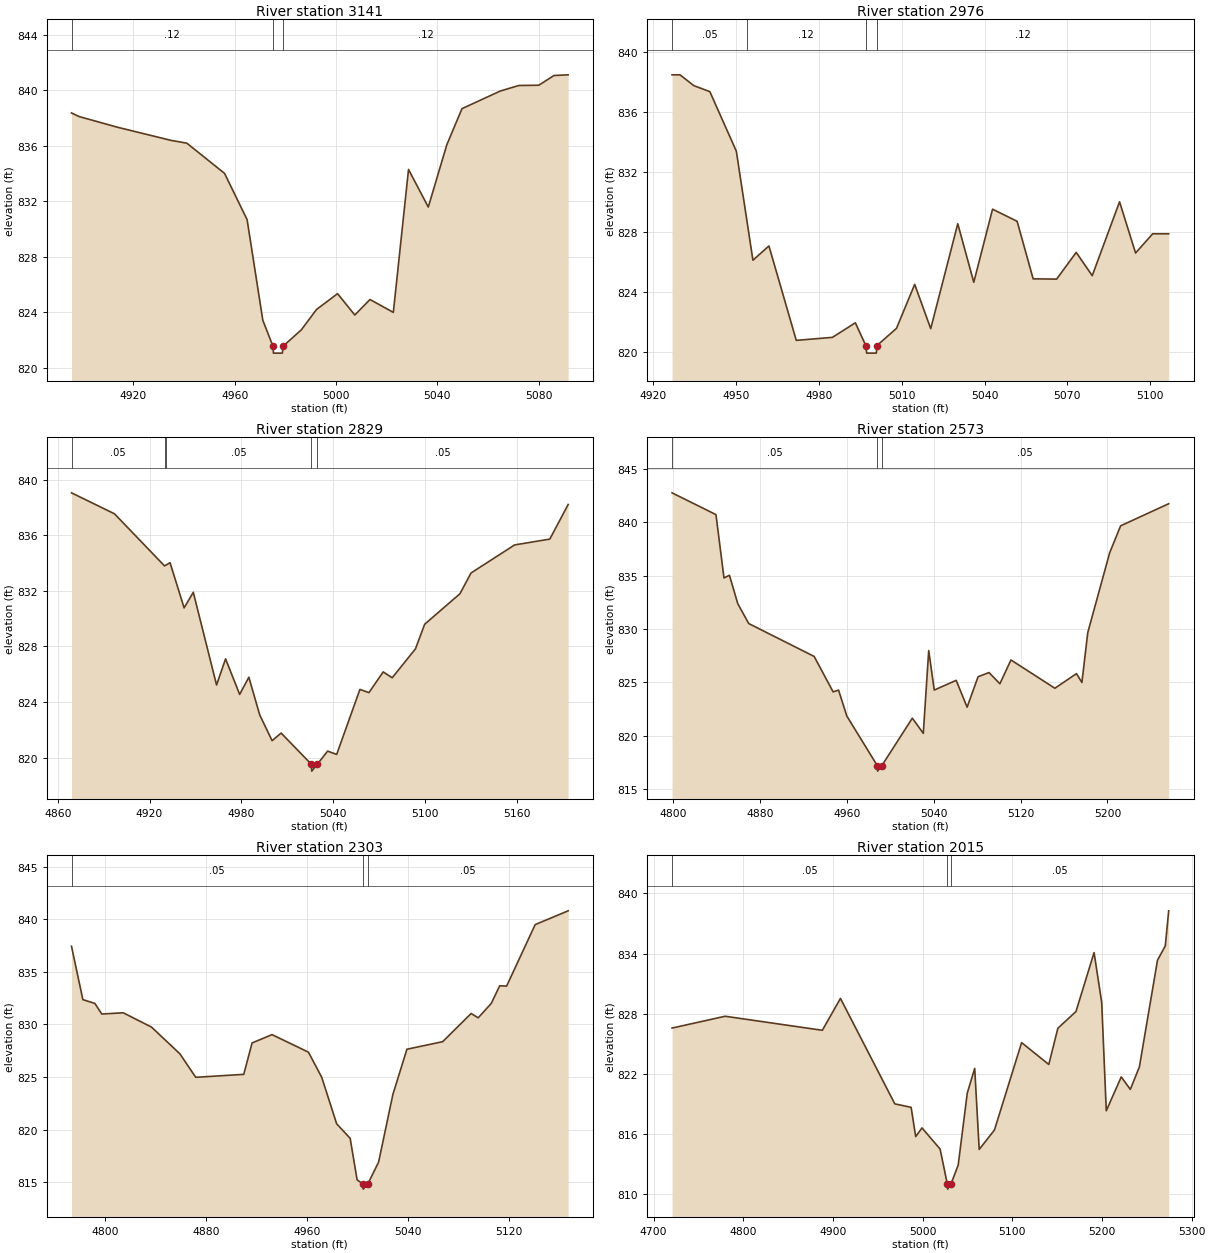
Type RM Length L Ch R = 1,3141,165,165,165
BEGIN DESCRIPTION:
UDS St 10 8.1
END DESCRIPTION:
XS GIS Cut Line= 2
      2281137.24      7181296.13      2280972.59      7181189.79
#Sta/Elev= 27
  4895.6  838.37  4898.6  838.11  4913.7  837.34  4934.9  836.39  4941.1  836.19
  4956.0  834.01  4964.9  830.67  4971.1  823.41  4975.1  821.54  4975.3  821.04
  4978.8  821.04  4979.1  821.54  4986.3  822.72  4992.3  824.19  5000.6  825.33
  5007.4  823.79  5013.4  824.91  5022.6  823.98  5028.6  834.29  5036.4  831.58
  5043.7  836.07  5049.7  838.68  5064.8  839.95  5072.1  840.35  5080.0  840.37
  5086.0  841.07  5091.6  841.12
#Mann=3,-1,0
  4895.6    0.12       0  4975.1    0.07       0  4979.1    0.12       0
Bank Sta=4975.1,4979.1
Exp/Cntr=0.3,0.1

Type RM Length L Ch R = 1,2976,147,147,147
BEGIN DESCRIPTION:
UDS St 10 8.0
END DESCRIPTION:
XS GIS Cut Line= 2
      2281229.04      7181160.02      2281074.06      7181068.67
#Sta/Elev= 30
  4926.8  838.47  4929.7  838.47  4934.7  837.75  4940.5  837.35  4950.1  833.38
  4953.9  828.78  4956.1  826.12  4961.9  827.07  4971.8  820.78  4984.9  820.98
  4993.2  821.95  4997.0  820.43  4997.3  819.93  5000.8  819.93  5001.0  820.43
  5008.1  821.58  5014.7  824.51  5020.5  821.56  5030.3  828.55  5036.1  824.65
  5042.9  829.52  5051.8  828.71  5057.6  824.88  5066.1  824.86  5073.2  826.64
  5079.0  825.09  5088.9  830.01  5094.7  826.60  5100.9  827.88  5106.7  827.88
#Mann=4,-1,0
  4926.8    0.05       0  4953.9    0.12       0  4997.0    0.07       0
  5001.0    0.12       0
Bank Sta=4997,5001
Exp/Cntr=0.3,0.1

Type RM Length L Ch R = 1,2829,256,256,256
BEGIN DESCRIPTION:
UDS St 10 7.1
END DESCRIPTION:
XS GIS Cut Line= 2
      2281312.42      7181057.12      2281039.55      7180881.32
#Sta/Elev= 30
  4869.0  839.06  4897.1  837.55  4929.8  833.80  4930.8  833.86  4933.4  834.03
  4942.6  830.78  4948.6  831.90  4963.8  825.23  4969.7  827.11  4978.9  824.55
  4984.9  825.79  4992.0  823.08  5000.1  821.22  5006.0  821.77  5025.7  819.53
  5026.0  819.03  5029.7  819.53  5036.4  820.47  5042.3  820.23  5057.5  824.91
  5063.4  824.68  5072.7  826.17  5078.6  825.75  5093.8  827.83  5099.8  829.60
  5122.9  831.80  5130.1  833.29  5158.6  835.31  5181.6  835.73  5193.6  838.22
#Mann=5,-1,0
  4869.0    0.05       0  4929.8    0.12       0  4930.8    0.05       0
  5025.7    0.04       0  5029.7    0.05       0
Bank Sta=5025.7,5029.7
Exp/Cntr=0.3,0.1

Type RM Length L Ch R = 1,2573,270,270,270
BEGIN DESCRIPTION:
UDS St 10 7.0
END DESCRIPTION:
XS GIS Cut Line= 3
      2281479.33      7180779.99      2281279.00      7180760.00
      2281025.12      7180723.61
#Sta/Elev= 30
  4798.7  842.75  4839.2  840.71  4846.6  834.78  4851.6  835.03  4859.3  832.37
  4869.4  830.51  4929.7  827.43  4947.2  824.11  4952.2  824.28  4959.8  821.85
  4988.0  817.19  4988.2  816.69  4992.0  817.19  5020.2  821.65  5030.3  820.23
  5035.3  827.98  5040.4  824.28  5060.6  825.19  5070.7  822.68  5080.8  825.53
  5090.9  825.92  5100.9  824.87  5111.1  827.10  5151.6  824.45  5171.5  825.82
  5176.5  824.99  5181.9  829.66  5202.1  837.14  5212.2  839.66  5256.5  841.73
#Mann=3,-1,0
  4798.7    0.05       0  4988.0   0.033       0  4992.0    0.05       0
Bank Sta=4988,4992
Exp/Cntr=0.3,0.1

Type RM Length L Ch R = 1,2303,288,288,288
BEGIN DESCRIPTION:
UDS St 10 6.0
END DESCRIPTION:
XS GIS Cut Line= 3
      2281497.11      7180594.87      2281293.25      7180494.20
      2281144.30      7180421.75
#Sta/Elev= 30
  4773.7  837.44  4782.7  832.36  4792.2  832.00  4797.7  830.99  4814.6  831.11
  4837.0  829.75  4859.5  827.20  4872.0  824.97  4910.0  825.25  4916.6  828.24
  4932.4  829.03  4961.2  827.36  4971.7  824.97  4983.5  820.55  4994.2  819.16
  4999.7  815.21  5004.2  814.83  5004.5  814.33  5008.2  814.83  5016.7  816.90
  5028.0  823.34  5039.1  827.64  5067.4  828.36  5089.9  831.04  5095.5  830.63
  5105.9  832.01  5112.5  833.68  5118.0  833.65  5140.6  839.50  5166.7  840.81
#Mann=3,-1,0
  4773.7    0.05       0  5004.2   0.033       0  5008.2    0.05       0
Bank Sta=5004.2,5008.2
Exp/Cntr=0.3,0.1

Type RM Length L Ch R = 1,2015,176,176,176
BEGIN DESCRIPTION:
UDS St 10 5.1
END DESCRIPTION:
XS GIS Cut Line= 2
      2281614.92      7180293.02      2281066.64      7180214.97
#Sta/Elev= 30
  4720.6  826.57  4779.8  827.75  4888.2  826.35  4908.4  829.53  4969.0  819.01
  4987.2  818.66  4992.3  815.74  4999.3  816.61  5019.5  814.50  5027.6  811.00
  5027.9  810.50  5031.6  811.00  5039.7  812.91  5049.8  820.08  5058.1  822.55
  5063.1  814.46  5080.1  816.40  5110.4  825.12  5140.7  822.94  5150.8  826.55
  5171.0  828.22  5191.2  834.10  5199.7  829.13  5204.8  818.32  5221.5  821.70
  5231.6  820.45  5241.7  822.69  5261.9  833.34  5270.6  834.77  5274.4  838.27
#Mann=3,-1,0
  4720.6    0.05       0  5027.6   0.033       0  5031.6    0.05       0
Bank Sta=5027.6,5031.6
Exp/Cntr=0.3,0.1

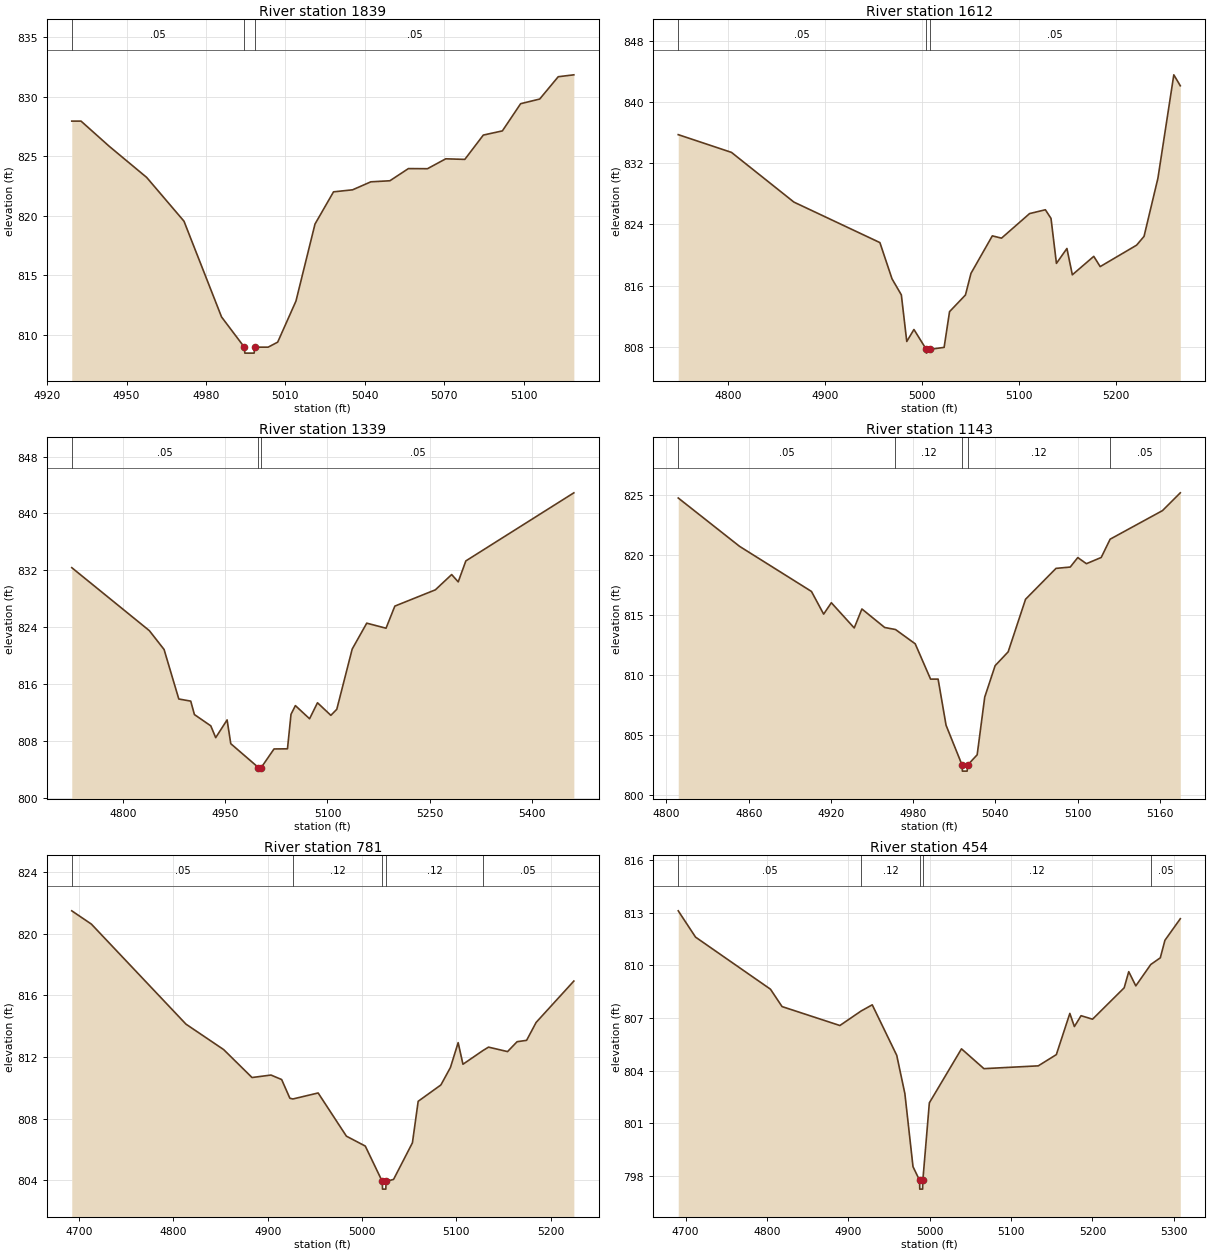
Type RM Length L Ch R = 1,1839,227,227,227
BEGIN DESCRIPTION:
UDS St 10 5.0
END DESCRIPTION:
XS GIS Cut Line= 3
      2281479.01      7180160.01      2281429.00      7180110.00
      2281346.40      7180024.36
#Sta/Elev= 29
  4929.3  827.94  4932.8  827.94  4943.5  825.82  4957.6  823.22  4971.7  819.55
  4985.9  811.52  4994.5  808.99  4994.7  808.49  4998.2  808.49  4998.5  808.99
  5000.0  808.99  5003.5  808.99  5007.1  809.41  5014.0  812.85  5021.2  819.31
  5028.2  822.01  5035.4  822.18  5042.3  822.85  5049.5  822.94  5056.5  823.96
  5063.7  823.95  5070.6  824.78  5077.8  824.73  5084.8  826.77  5092.0  827.12
  5098.9  829.40  5106.1  829.79  5113.1  831.66  5119.0  831.82
#Mann=3,-1,0
  4929.3    0.05       0  4994.5   0.033       0  4998.5    0.05       0
Bank Sta=4994.5,4998.5
Exp/Cntr=0.3,0.1

Type RM Length L Ch R = 1,1612,273,273,273
BEGIN DESCRIPTION:
UDS St 10 4.1
END DESCRIPTION:
XS GIS Cut Line= 3
      2281729.22      7180057.10      2281598.53      7179957.36
      2281285.88      7179793.04
#Sta/Elev= 30
  4748.7  835.73  4803.6  833.41  4868.0  826.91  4956.6  821.62  4969.1  816.88
  4978.7  814.79  4984.3  808.69  4991.7  810.26  5004.4  807.67  5004.6  807.17
  5008.4  807.67  5022.8  807.92  5028.4  812.59  5044.8  814.77  5050.5  817.60
  5072.5  822.50  5082.0  822.20  5110.9  825.41  5127.2  825.91  5133.0  824.78
  5138.6  818.90  5149.4  820.85  5155.0  817.41  5177.1  819.82  5183.7  818.48
  5221.2  821.28  5228.9  822.43  5243.2  830.02  5259.6  843.55  5266.3  842.12
#Mann=3,-1,0
  4748.7    0.05       0  5004.4   0.033       0  5008.4    0.05       0
Bank Sta=5004.4,5008.4
Exp/Cntr=0.3,0.1

Type RM Length L Ch R = 1,1339,196,196,196
BEGIN DESCRIPTION:
UDS St 10 4.0
END DESCRIPTION:
XS GIS Cut Line= 3
      2281780.88      7179955.12      2281677.96      7179705.16
      2281547.92      7179258.01
#Sta/Elev= 30
  4725.2  832.36  4838.9  823.50  4860.5  820.85  4882.1  813.88  4899.6  813.58
  4905.0  811.69  4929.0  810.10  4936.2  808.44  4952.9  810.94  4958.3  807.59
  4998.9  804.23  4999.1  803.73  5002.9  804.23  5021.7  806.85  5041.4  806.87
  5046.6  811.73  5053.0  812.95  5073.8  811.10  5085.4  813.35  5105.0  811.58
  5113.7  812.43  5136.3  820.91  5157.6  824.55  5185.9  823.84  5198.8  826.95
  5258.2  829.24  5282.1  831.39  5291.7  830.36  5302.9  833.31  5461.2  842.89
#Mann=3,-1,0
  4725.2    0.05       0  4998.9   0.033       0  5002.9    0.05       0
Bank Sta=4998.9,5002.9
Exp/Cntr=0.3,0.1

Type RM Length L Ch R = 1,1143,362,362,362
BEGIN DESCRIPTION:
UDS St 10 3.0
END DESCRIPTION:
XS GIS Cut Line= 3
      2281913.38      7179776.73      2281829.00      7179610.00
      2281751.29      7179448.27
#Sta/Elev= 30
  4808.6  824.71  4853.4  820.68  4905.8  816.93  4914.7  815.04  4920.3  815.99
  4937.0  813.89  4942.6  815.47  4959.2  813.93  4967.1  813.76  4981.5  812.57
  4992.7  809.63  4998.2  809.63  5004.0  805.79  5015.7  802.47  5015.9  801.97
  5019.4  801.97  5019.7  802.47  5026.7  803.33  5032.2  808.13  5039.8  810.75
  5049.3  811.90  5062.0  816.28  5084.2  818.85  5094.6  818.96  5100.1  819.75
  5106.4  819.24  5117.2  819.76  5123.7  821.28  5161.9  823.66  5174.9  825.14
#Mann=5,-1,0
  4808.6    0.05       0  4967.1    0.12       0  5015.7    0.07       0
  5019.7    0.12       0  5123.7    0.05       0
Bank Sta=5015.7,5019.7
Exp/Cntr=0.3,0.1

Type RM Length L Ch R = 1,781,327,327,327
BEGIN DESCRIPTION:
UDS St 10 2.0
END DESCRIPTION:
XS GIS Cut Line= 4
      2282079.11      7179730.77      2282093.96      7179512.26
      2282089.97      7179362.88      2282067.95      7179200.32
#Sta/Elev= 30
  4692.2  821.47  4713.0  820.61  4813.3  814.13  4853.3  812.48  4883.4  810.67
  4903.5  810.83  4914.8  810.54  4923.5  809.33  4926.7  809.28  4953.5  809.67
  4983.5  806.87  5003.5  806.23  5021.5  803.94  5021.8  803.44  5025.3  803.44
  5025.5  803.94  5033.5  804.07  5053.5  806.44  5059.6  809.13  5083.7  810.19
  5093.8  811.32  5102.0  812.93  5107.1  811.53  5128.1  812.41  5134.2  812.64
  5154.4  812.35  5164.5  812.99  5174.6  813.08  5184.7  814.24  5224.7  816.92
#Mann=5,-1,0
  4692.2    0.05       0  4926.7    0.12       0  5021.5    0.07       0
  5025.5    0.12       0  5128.1    0.05       0
Bank Sta=5021.5,5025.5
Exp/Cntr=0.3,0.1

Type RM Length L Ch R = 1,454,146,146,146
BEGIN DESCRIPTION:
UDS St 10 1.0
END DESCRIPTION:
XS GIS Cut Line= 4
      2282228.99      7179610.01      2282383.51      7179435.01
      2282373.80      7179313.71      2282140.27      7179194.80
#Sta/Elev= 30
  4690.9  813.11  4712.2  811.61  4804.3  808.64  4818.5  807.65  4889.6  806.57
  4915.8  807.40  4929.4  807.75  4959.5  804.87  4969.5  802.69  4979.5  798.52
  4987.6  797.74  4987.8  797.24  4991.3  797.24  4991.6  797.74  4999.6  802.16
  5039.1  805.24  5066.7  804.11  5133.5  804.27  5155.7  804.91  5172.3  807.26
  5177.9  806.51  5186.1  807.13  5200.2  806.93  5239.1  808.72  5244.7  809.64
  5253.4  808.83  5271.8  810.05  5283.5  810.43  5289.2  811.43  5308.1  812.66
#Mann=5,-1,0
  4690.9    0.05       0  4915.8    0.12       0  4987.6    0.07       0
  4991.6    0.12       0  5271.8    0.05       0
Bank Sta=4987.6,4991.6
Exp/Cntr=0.3,0.1

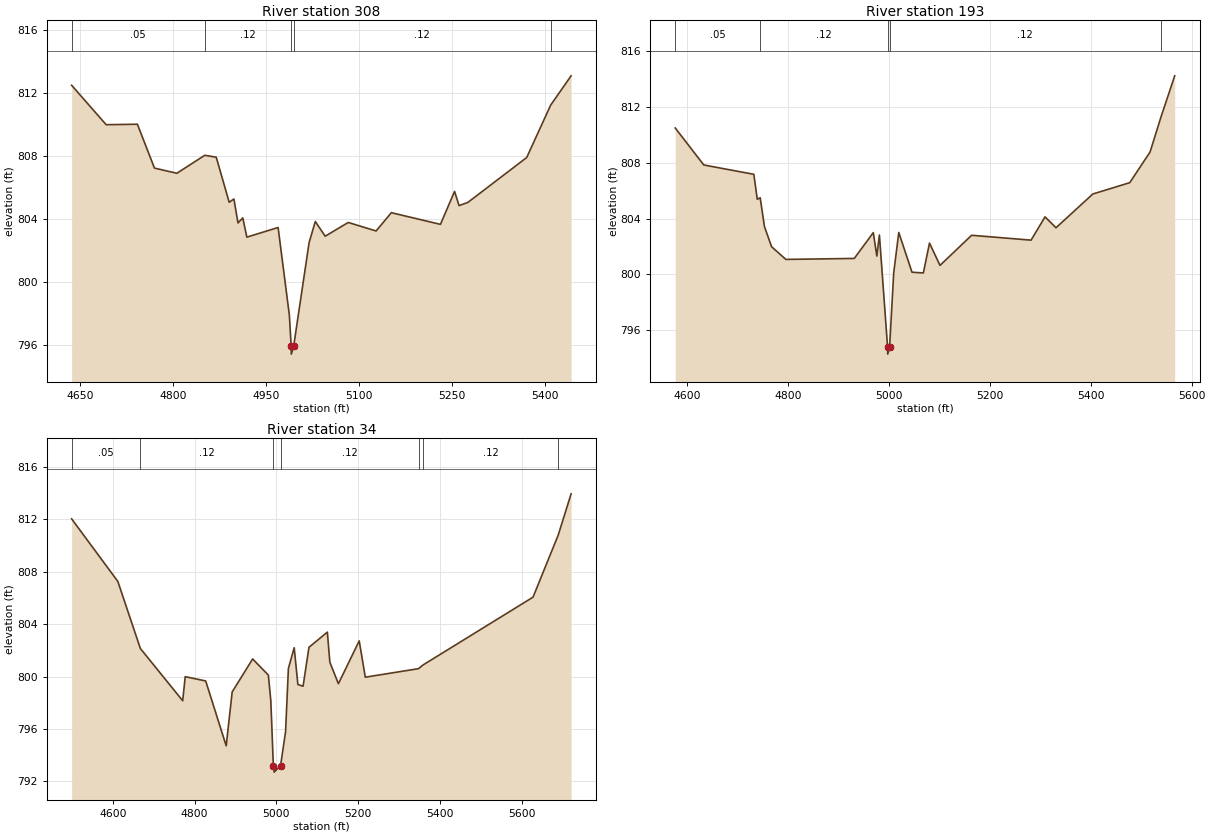
Type RM Length L Ch R = 1,308,115,115,115
BEGIN DESCRIPTION:
UDS St 10 0.9
END DESCRIPTION:
XS GIS Cut Line= 4
      2282330.06      7179650.10      2282525.27      7179425.58
      2282522.74      7179313.00      2282153.58      7179170.63
#Sta/Elev= 30
  4636.8  812.50  4692.5  810.00  4742.9  810.03  4770.4  807.25  4806.5  806.92
  4851.6  808.06  4870.1  807.94  4891.0  805.08  4898.6  805.29  4905.2  803.77
  4912.9  804.09  4919.5  802.87  4969.9  803.48  4988.0  797.94  4991.0  795.95
  4991.2  795.45  4995.0  795.95  5019.9  802.52  5029.9  803.86  5045.9  802.93
  5083.1  803.80  5128.0  803.26  5152.6  804.42  5231.8  803.68  5254.6  805.77
  5261.8  804.87  5276.0  805.07  5371.0  807.92  5409.6  811.24  5442.6  813.10
#Mann=5,-1,0
  4636.8    0.05       0  4851.6    0.12       0  4991.0    0.07       0
  4995.0    0.12       0  5409.6    0.05       0
Bank Sta=4991,4995
Exp/Cntr=0.3,0.1

Type RM Length L Ch R = 1,193,159,159,159
BEGIN DESCRIPTION:
UDS St 10 0.8
END DESCRIPTION:
XS GIS Cut Line= 4
      2282386.30      7179697.37      2282626.85      7179439.56
      2282646.31      7179307.72      2282163.71      7179162.00
#Sta/Elev= 30
  4576.4  810.49  4633.0  807.84  4732.2  807.17  4739.0  805.38  4744.8  805.49
  4753.2  803.43  4767.4  801.98  4795.7  801.07  4931.3  801.14  4969.0  802.99
  4976.0  801.31  4981.1  802.82  4997.3  794.78  4997.6  794.28  5001.3  794.78
  5009.4  800.09  5019.5  803.00  5045.7  800.15  5068.2  800.10  5080.4  802.24
  5101.2  800.64  5163.9  802.80  5281.7  802.45  5309.4  804.12  5331.1  803.34
  5404.2  805.76  5477.3  806.57  5517.6  808.77  5539.4  811.30  5566.4  814.23
#Mann=5,-1,0
  4576.4    0.05       0  4744.8    0.12       0  4997.3    0.07       0
  5001.3    0.12       0  5539.4    0.05       0
Bank Sta=4997.3,5001.3
Exp/Cntr=0.3,0.1

Type RM Length L Ch R = 1,34,0,0,0
BEGIN DESCRIPTION:
UDS St 10 0.7
END DESCRIPTION:
XS GIS Cut Line= 5
      2282388.79      7179738.97      2282770.18      7179456.11
      2282696.80      7179345.01      2282592.94      7179192.48
      2282166.45      7179146.34
#Sta/Elev= 30
  4499.4  812.05  4612.4  807.27  4667.5  802.15  4771.0  798.16  4777.2  800.00
  4827.3  799.67  4877.4  794.72  4892.0  798.83  4942.1  801.35  4980.5  800.12
  4986.5  798.17  4992.7  793.21  4994.7  792.71  5010.4  793.21  5022.6  795.80
  5029.5  800.62  5043.7  802.21  5052.7  799.40  5065.4  799.27  5079.8  802.24
  5124.8  803.40  5130.9  801.10  5151.8  799.46  5202.7  802.73  5217.6  799.96
  5347.8  800.61  5358.2  800.88  5627.8  806.07  5689.4  810.81  5720.9  813.96
#Mann=7,-1,0
  4499.4    0.05       0  4667.5    0.12       0  4992.7    0.07       0
  5010.4    0.12       0  5347.8    0.05       0  5358.2    0.12       0
  5689.4    0.05       0
Bank Sta=4992.7,5010.4
Exp/Cntr=0.3,0.1

Chan Stop Cuts=-1