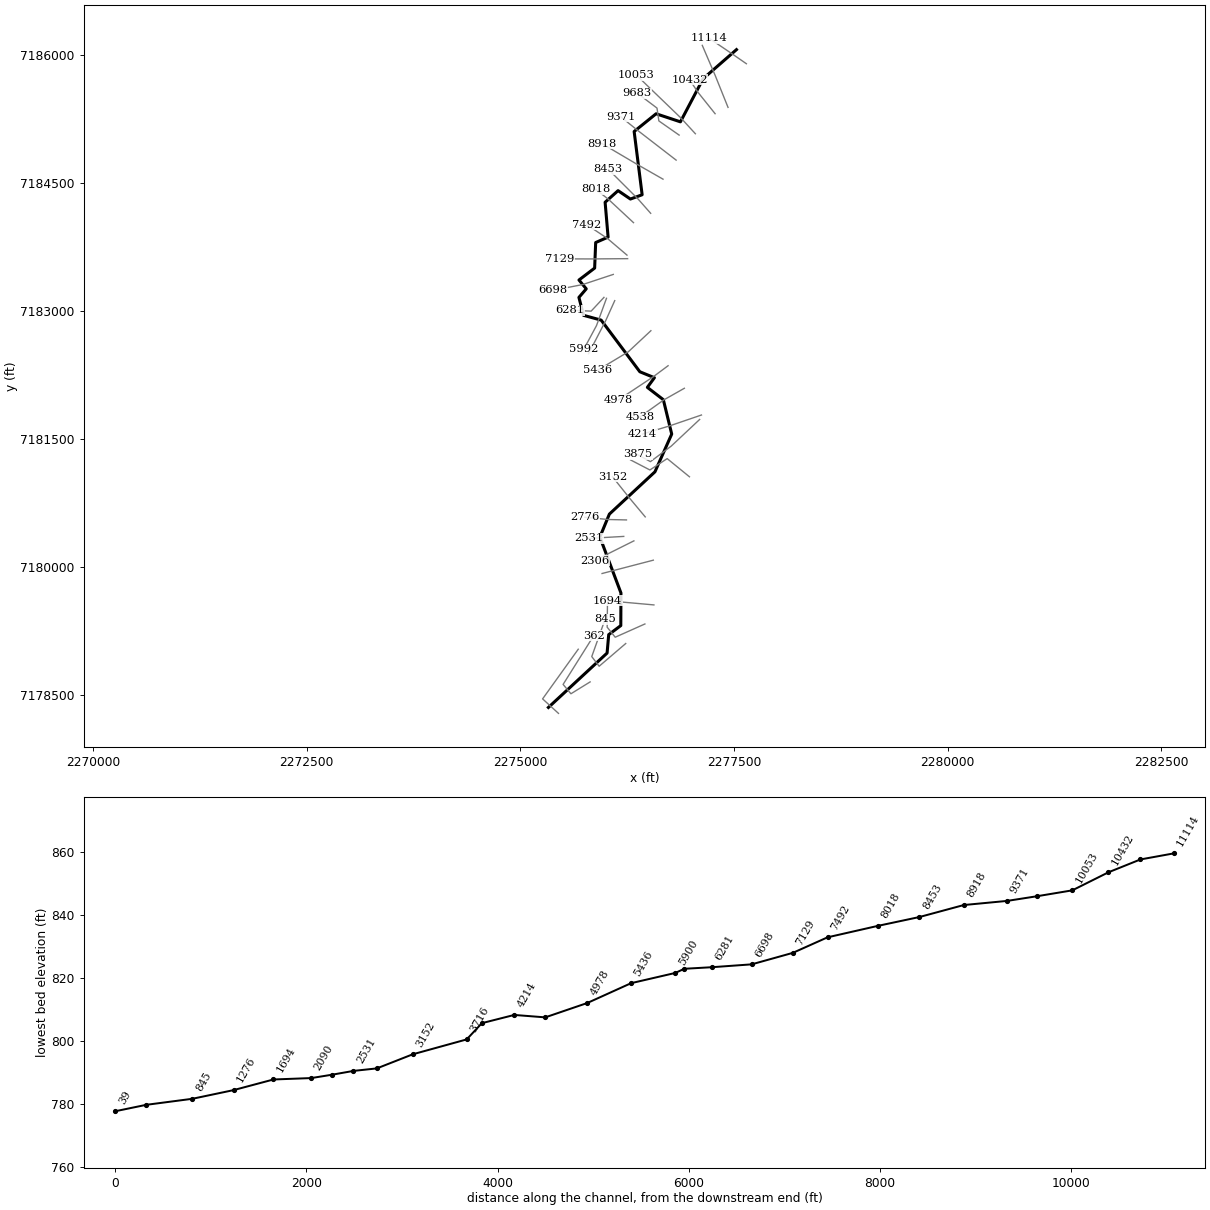
--- UDS St 17.prj (project) ---

Proj Title=UDS St 17 Base Level Engineering
Current Plan=p01
Default Exp/Contr=0.3,0.1
English Units
Geom File=g01
Flow File=f01
Plan File=p01
Y Axis Title=Elevation
X Axis Title(PF)=Main Channel Distance
X Axis Title(XS)=Station
BEGIN DESCRIPTION:
UDS St 17
END DESCRIPTION:
DSS Export Rating Curves= 0
DSS Export Rating Curve Sorted= 0
DSS Export Volume Flow Curves= 0
DXF OffsetX= 0
DXF OffsetY= 0
DXF ScaleX= 1
DXF ScaleY= 10

--- UDS St 17.p01 (plan) ---

Plan Title=Multiple Run
Short Identifier=Multiple
Geom File=g01
Flow File=f01
Subcritical Flow
K Sum by GR= 0
Std Step Tol= 0.01
Critical Tol= 0.01
Num of Std Step Trials= 20
Max Error Tol= 0.3
Flow Tol Ratio= 0.001
Split Flow NTrial= 30
Split Flow Tol= 0.02
Split Flow Ratio= 0.02
Log Output Level= 0
Friction Slope Method= 1
Unsteady Friction Slope Method= 2
Unsteady Bridges Friction Slope Method= 1
Parabolic Critical Depth
Global Vel Dist=  1 , 1 , 1
Global Log Level= 0
CheckData=True
Encroach Param= -1, 0, 0, 0
BEGIN DESCRIPTION:
Multiple Run
END DESCRIPTION:

--- UDS St 17.f01 (steady flow) ---

Flow Title=Multiple
Number of Profiles=7
Profile Names=10-year,25-year,50-year,1pct_min,100-year,1pct_plu,500-year
River Rch & RM= UDS St 17,Reach-1,11114
     695     962    1186     726    1448    2890    2165
River Rch & RM= UDS St 17,Reach-1,8918
     916    1285    1595     983    1961    3914    2972
Boundary for River Rch & Prof#=UDS St 17,Reach-1,1
Up Type=0
Dn Type=3
Dn Slope=0.005
Boundary for River Rch & Prof#=UDS St 17,Reach-1,2
Up Type=0
Dn Type=3
Dn Slope=0.005
Boundary for River Rch & Prof#=UDS St 17,Reach-1,3
Up Type=0
Dn Type=3
Dn Slope=0.005
Boundary for River Rch & Prof#=UDS St 17,Reach-1,4
Up Type=0
Dn Type=3
Dn Slope=0.005
Boundary for River Rch & Prof#=UDS St 17,Reach-1,5
Up Type=0
Dn Type=3
Dn Slope=0.005
Boundary for River Rch & Prof#=UDS St 17,Reach-1,6
Up Type=0
Dn Type=3
Dn Slope=0.005
Boundary for River Rch & Prof#=UDS St 17,Reach-1,7
Up Type=0
Dn Type=3
Dn Slope=0.005

--- UDS St 17.g01 (geometry) ---

Geom Title=Existing Conditions
Program Version=4.10

River Reach=UDS St 17       ,Reach-1
Reach XY= 30
        2277529.        7186060.      2277139.36      7185720.16
      2276873.38      7185214.74       2276588.8       7185309.2
      2276332.07       7185101.7      2276425.57      7184361.22
      2276288.64      7184311.09      2276144.02      7184409.35
      2275992.52      7184273.41      2276027.35      7183865.42
      2275882.03      7183801.99      2275869.99      7183502.98
       2275686.6      7183363.35      2275771.88        7183260.
      2275686.04       7183159.8      2275740.09      7182949.92
      2275946.16      7182893.89      2276398.59      7182289.43
      2276569.09      7182219.79      2276486.44      7182106.59
      2276673.55      7181962.47       2276771.5        7181560.
      2276575.33      7181118.19       2276042.4      7180623.31
      2275931.26      7180354.44      2276177.64      7179700.35
      2276175.93       7179318.3      2276034.46      7179212.47
      2276015.63      7178996.68        2275329.        7178360.

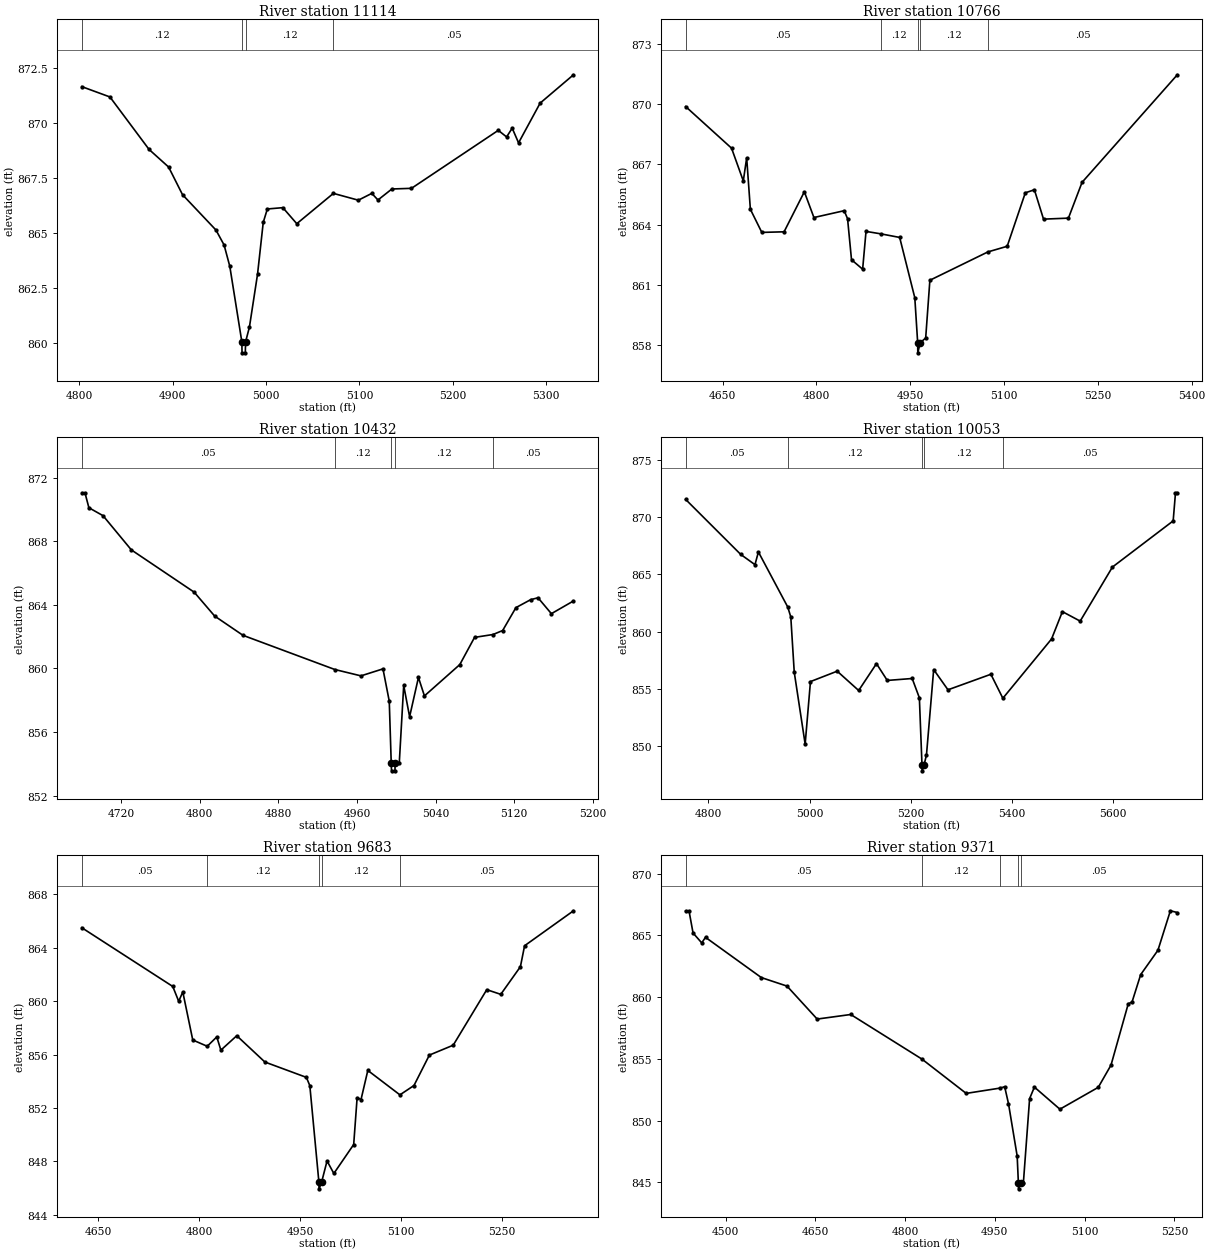
Type RM Length L Ch R = 1 ,11114   ,348,348,348
BEGIN DESCRIPTION:
UDS St 17 22.0
END DESCRIPTION:
XS GIS Cut Line= 3
      2277644.68      7185895.04        2277479.        7186010.
      2277210.29      7186192.19
#Sta/Elev= 30
  4802.8  871.67  4832.9   871.2  4874.8  868.81  4895.7  868.01  4910.6  866.75
  4946.4  865.14  4955.1  864.46  4961.2  863.49  4974.1  860.05  4974.3  859.55
  4977.8  859.55  4978.1  860.05  4982.2  860.72  4990.9  863.13    4997  865.49
  5001.4   866.1    5018  866.16  5032.9  865.43  5072.1  866.81  5098.8   866.5
  5113.2  866.81  5119.8  866.51  5134.7  867.01  5155.7  867.04  5248.6  869.68
  5257.5  869.38  5263.5  869.78  5270.3  869.11  5293.4  870.92  5329.1  872.21
#Mann= 4 ,-1 , 0
  4802.8     .12       0  4974.1     .07       0  4978.1     .12       0
  5072.1     .05       0
Bank Sta=4974.1,4978.1
XS Rating Curve= 0 ,0
Exp/Cntr=0.3,0.1

Type RM Length L Ch R = 1 ,10766   ,334,334,334
BEGIN DESCRIPTION:
UDS St 17 21.0
END DESCRIPTION:
XS GIS Cut Line= 3
       2277430.2      7185383.93        2277279.        7185760.
      2277129.01      7186109.98
#Sta/Elev= 30
  4590.9  869.88  4664.3  867.81  4683.1  866.18  4688.5  867.33  4694.4  864.77
  4712.7  863.62  4748.3  863.65  4780.7  865.64    4796  864.36  4844.4   864.7
  4849.8   864.3  4856.1  862.26  4873.9  861.79  4879.3  863.67  4902.7  863.55
  4933.1  863.37  4957.3  860.37  4961.9  858.13  4962.1  857.63  4965.9  858.13
  4974.7  858.37  4981.4  861.24  5074.2  862.65    5105  862.93    5134  865.59
  5148.5  865.74  5163.1  864.28  5202.9  864.33  5224.7  866.11    5377  871.46
#Mann= 5 ,-1 , 0
  4590.9     .05       0  4902.7     .12       0  4961.9     .07       0
  4965.9     .12       0  5074.2     .05       0
Bank Sta=4961.9,4965.9
XS Rating Curve= 0 ,0
Exp/Cntr=0.3,0.1

Type RM Length L Ch R = 1 ,10432   ,379,379,379
BEGIN DESCRIPTION:
UDS St 17 20.0
END DESCRIPTION:
XS GIS Cut Line= 3
      2277278.97      7185310.03        2277079.        7185560.
      2276978.99      7185710.01
#Sta/Elev= 30
  4679.9  871.04  4683.1  871.04  4687.1   870.1  4701.5   869.6  4730.3  867.45
  4794.3  864.79  4815.1  863.29  4843.9  862.08  4937.4  859.93    4964  859.53
  4986.4  859.97  4992.8  857.94  4994.8  854.06  4995.1  853.56  4998.6  853.56
  4998.8  854.06    5003  854.06  5007.5  858.93  5013.5  856.96  5022.5  859.43
  5028.6  858.27  5064.6  860.24  5079.6  861.95  5098.4  862.13  5108.2  862.38
  5121.7  863.82  5136.7  864.32  5144.2  864.44  5157.8  863.44  5180.3  864.24
#Mann= 5 ,-1 , 0
  4679.9     .05       0  4937.4     .12       0  4994.8     .07       0
  4998.8     .12       0  5098.4     .05       0
Bank Sta=4994.8,4998.8
XS Rating Curve= 0 ,0
Exp/Cntr=0.3,0.1

Type RM Length L Ch R = 1 ,10053   ,370,370,370
BEGIN DESCRIPTION:
UDS St 17 19.0
END DESCRIPTION:
XS GIS Cut Line= 3
      2277048.22      7185075.45        2276879.        7185260.
      2276358.83      7185761.45
#Sta/Elev= 30
  4754.9  871.57  4863.8  866.76  4892.1  865.86  4898.9  866.97    4957  862.15
    4963  861.28  4969.8  856.46  4991.4  850.16  5001.9  855.63  5054.8  856.54
  5097.3  854.85  5132.5   857.2  5153.9  855.73  5203.2   855.9  5217.4  854.21
  5222.6  848.32  5222.8  847.82  5226.6  848.32  5231.5  849.23  5245.7  856.68
    5274  854.91  5358.9  856.27  5382.6  854.17    5479  859.36  5500.4  861.75
  5535.6  860.92  5599.4  865.65  5719.6  869.69  5724.2  872.15  5727.8  872.15
#Mann= 5 ,-1 , 0
  4754.9     .05       0    4957     .12       0  5222.6     .07       0
  5226.6     .12       0  5382.6     .05       0
Bank Sta=5222.6,5226.6
XS Rating Curve= 0 ,0
Exp/Cntr=0.3,0.1

Type RM Length L Ch R = 1 ,9683    ,312,312,312
BEGIN DESCRIPTION:
UDS St 17 18.0
END DESCRIPTION:
XS GIS Cut Line= 4
      2276858.06      7185059.77      2276621.08      7185225.48
       2276599.3      7185375.92      2276368.07      7185550.33
#Sta/Elev= 30
  4625.2  865.51  4760.4  861.11  4769.2     860  4775.3   860.7  4790.1   857.1
  4811.6  856.63  4825.8  857.33  4831.9  856.34  4855.5  857.42  4897.3  855.45
    4959   854.3  4964.1  853.68  4977.6  846.45  4977.8  845.95  4981.6  846.45
  4989.7  848.04  4999.8   847.1  5029.3  849.27  5034.4  852.78  5040.2  852.64
  5050.3  854.82    5098  852.99  5118.9  853.69  5141.8  855.97  5177.2  856.71
  5227.1  860.87  5247.9  860.52  5277.1  862.59  5283.3  864.16    5356  866.78
#Mann= 5 ,-1 , 0
  4625.2     .05       0  4811.6     .12       0  4977.6     .07       0
  4981.6     .12       0    5098     .05       0
Bank Sta=4977.6,4981.6
XS Rating Curve= 0 ,0
Exp/Cntr=0.3,0.1

Type RM Length L Ch R = 1 ,9371    ,453,453,453
BEGIN DESCRIPTION:
UDS St 17 17.0
END DESCRIPTION:
XS GIS Cut Line= 3
      2276823.06      7184766.83        2276379.        7185110.
      2276176.07      7185273.16
#Sta/Elev= 30
  4433.3  866.97    4439  866.97  4445.7  865.19  4460.2  864.39  4466.5  864.84
  4559.8  861.58  4602.7  860.89  4653.1  858.22  4709.2  858.59  4828.1  854.98
  4902.1   852.2  4958.8  852.63  4966.4  852.74  4972.8  851.37  4987.3  847.13
  4989.3  844.97  4989.6  844.47  4993.3  844.97  4997.7  844.97  5008.1  851.78
  5016.1  852.71  5058.7  850.92  5122.8  852.69  5144.1  854.49  5172.9  859.45
  5179.3  859.61  5193.7  861.82  5222.5  863.79  5243.3  866.99  5254.9  866.85
#Mann= 5 ,-1 , 0
  4433.3     .05       0  4828.1     .12       0  4958.8     .05       0
  4989.3    .033       0  4993.3     .05       0
Bank Sta=4989.3,4993.3
XS Rating Curve= 0 ,0
Exp/Cntr=0.3,0.1

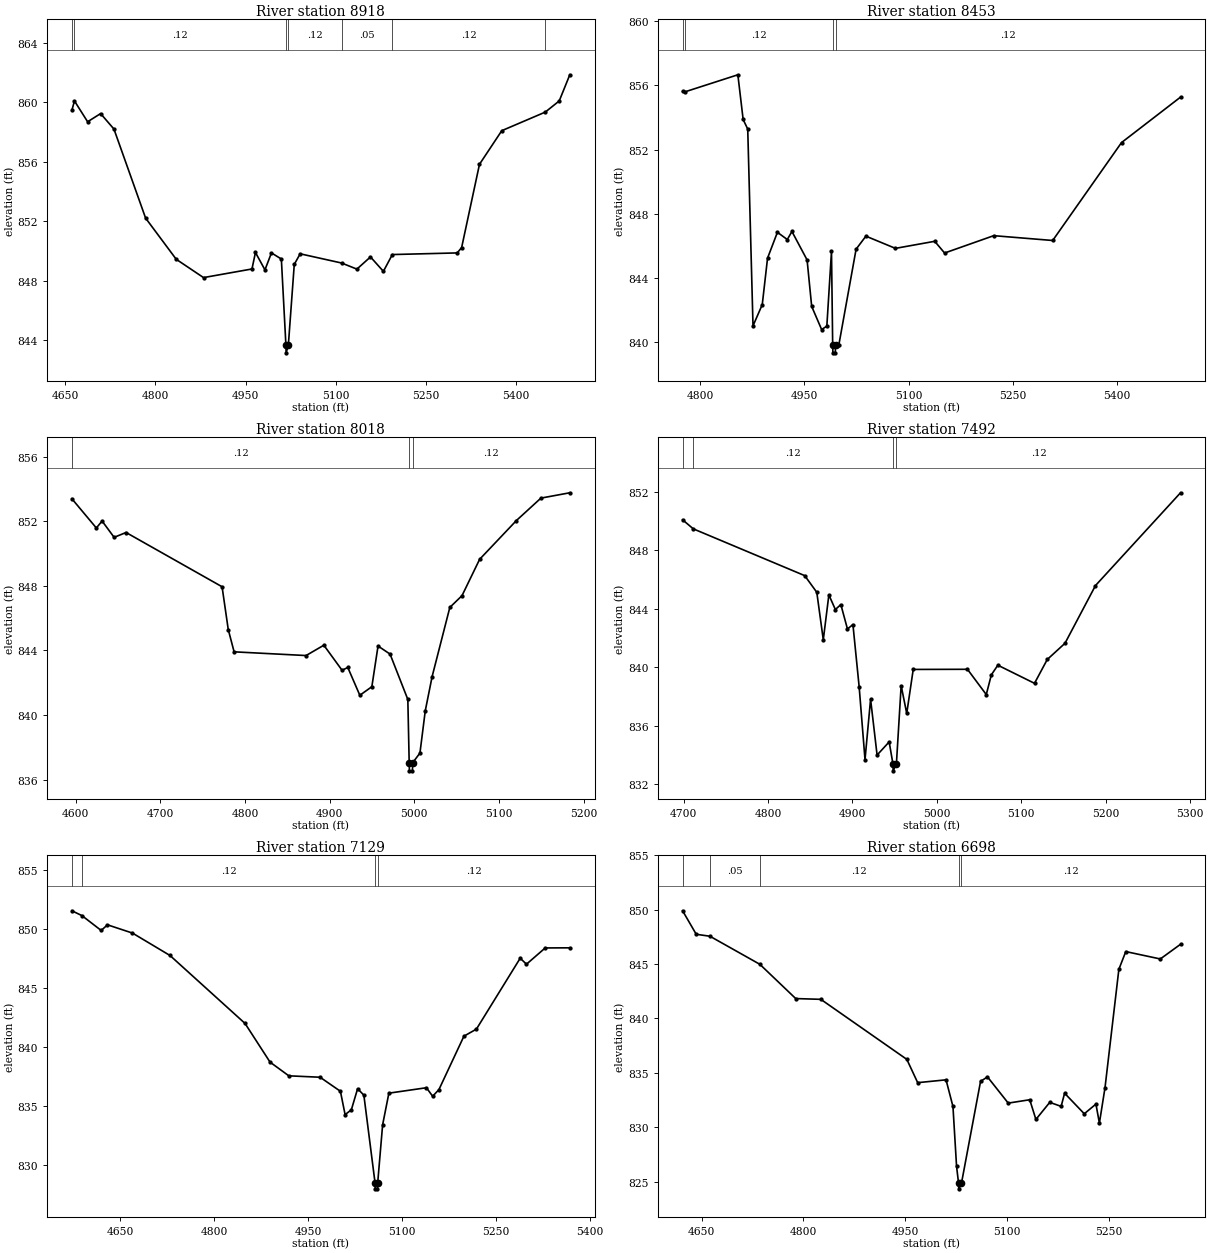
Type RM Length L Ch R = 1 ,8918    ,465,465,465
BEGIN DESCRIPTION:
UDS St 17 16.0
END DESCRIPTION:
XS GIS Cut Line= 3
      2276669.79       7184543.7        2276379.        7184710.
      2275953.97      7184961.02
#Sta/Elev= 30
    4661  859.47  4665.3   860.1  4687.2   858.7  4708.8  859.25    4731  858.21
  4783.7  852.22  4834.7  849.45  4880.1  848.22  4960.7   848.8  4966.5  849.91
  4982.3  848.74  4993.1  849.88  5009.6  849.47  5017.2  843.66  5017.5  843.16
  5021.2  843.66  5031.1  849.11  5040.9  849.82  5109.9   849.2  5135.3  848.79
  5157.9  849.61  5179.4  848.64  5194.3  849.77  5302.3  849.88  5309.6  850.24
  5339.3  855.84  5376.4   858.1  5448.8  859.35    5472   860.1  5489.6  861.86
#Mann= 7 ,-1 , 0
    4661     .05       0  4665.3     .12       0  5017.2     .07       0
  5021.2     .12       0  5109.9     .05       0  5194.3     .12       0
  5448.8     .05       0
Bank Sta=5017.2,5021.2
XS Rating Curve= 0 ,0
Exp/Cntr=0.3,0.1

Type RM Length L Ch R = 1 ,8453    ,435,435,435
BEGIN DESCRIPTION:
UDS St 17 15.0
END DESCRIPTION:
XS GIS Cut Line= 3
      2276525.43      7184144.05        2276379.        7184310.
      2276028.99      7184660.01
#Sta/Elev= 30
  4774.7  855.61  4777.5  855.58  4854.2  856.65  4861.8  853.87  4868.4  853.27
    4876  841.03  4889.3  842.35  4896.9  845.24  4911.1  846.85  4925.3   846.4
    4932   846.9  4953.8  845.13  4960.4  842.24  4974.7   840.8  4982.2  841.01
  4988.9  845.66  4990.6  839.85  4990.9  839.35  4994.4  839.35  4994.7  839.85
  4999.5  839.85  5024.3   845.8  5038.4  846.61  5080.9  845.85  5137.4  846.29
  5151.6  845.56  5222.3  846.64  5307.1  846.34  5406.1  852.43    5491  855.26
#Mann= 4 ,-1 , 0
  4774.7     .05       0  4777.5     .12       0  4990.6     .07       0
  4994.7     .12       0
Bank Sta=4990.6,4994.7
XS Rating Curve= 0 ,0
Exp/Cntr=0.3,0.1

Type RM Length L Ch R = 1 ,8018    ,526,526,526
BEGIN DESCRIPTION:
UDS St 17 14.0
END DESCRIPTION:
XS GIS Cut Line= 3
      2276324.53      7184034.77        2276029.        7184310.
      2275883.77       7184423.4
#Sta/Elev= 30
  4595.6  853.39  4624.5  851.58  4631.3  852.01  4645.5     851  4659.6   851.3
    4773  847.94  4780.3  845.29  4787.2  843.91  4872.2  843.68  4893.2  844.32
  4914.7  842.77  4921.5  842.94  4935.7  841.22  4949.9  841.75  4957.2  844.27
  4971.4  843.77  4992.4  840.96    4994  837.04  4994.3  836.54  4997.8  836.54
  4998.1  837.04  5006.7  837.64    5013  840.26  5021.1  842.38    5042  846.66
  5056.4  847.39  5077.2  849.64  5120.6  852.04  5149.6  853.43  5183.7  853.76
#Mann= 3 ,-1 , 0
  4595.6     .12       0    4994     .07       0  4998.1     .12       0
Bank Sta=4994,4998.1
XS Rating Curve= 0 ,0
Exp/Cntr=0.3,0.1

Type RM Length L Ch R = 1 ,7492    ,363,363,363
BEGIN DESCRIPTION:
UDS St 17 13.0
END DESCRIPTION:
XS GIS Cut Line= 3
      2276248.28      7183654.82      2276016.82      7183851.74
      2275778.96      7184010.02
#Sta/Elev= 30
  4698.9  850.09  4711.6  849.47  4843.5  846.27  4857.8  845.13  4865.5  841.88
  4872.1  844.95  4879.8  843.95  4886.3  844.29  4894.1  842.62  4900.6  842.92
    4908  838.64  4914.9  833.68  4921.5  837.81  4929.2  833.99  4943.5  834.89
  4947.9  833.41  4948.3  832.91  4952.1  833.41  4957.7  838.74  4964.3  836.84
    4972  839.85  5036.2  839.86  5058.5  838.13  5064.5  839.48  5072.2  840.14
  5115.6   838.9  5130.7  840.53  5151.7  841.64  5187.8  845.59  5288.5  851.94
#Mann= 4 ,-1 , 0
  4698.9     .05       0  4711.6     .12       0  4947.9     .07       0
  4952.1     .12       0
Bank Sta=4947.9,4952.1
XS Rating Curve= 0 ,0
Exp/Cntr=0.3,0.1

Type RM Length L Ch R = 1 ,7129    ,431,431,431
BEGIN DESCRIPTION:
UDS St 17 12.0
END DESCRIPTION:
XS GIS Cut Line= 3
      2276255.92      7183613.35        2275829.        7183610.
      2275459.74      7183610.91
#Sta/Elev= 30
  4572.3  851.55  4588.4  851.14  4619.2  849.88  4629.2  850.36  4669.2  849.66
  4729.2  847.76  4849.2     842  4889.2  838.72  4919.2  837.56  4969.2  837.44
  5001.7  836.25  5009.2  834.27  5019.2  834.68  5029.2  836.47  5039.2  835.92
  5057.1  828.48  5057.4  827.98    5061  827.98  5061.3  828.48  5069.2  833.41
  5079.2  836.09  5139.2  836.55  5149.2  835.83  5159.2  836.39  5199.2  840.92
  5219.2  841.52  5289.2  847.53  5299.2  847.02  5329.2   848.4  5368.5  848.41
#Mann= 4 ,-1 , 0
  4572.3     .05       0  4588.4     .12       0  5057.1     .07       0
  5061.3     .12       0
Bank Sta=5057.1,5061.3
XS Rating Curve= 0 ,0
Exp/Cntr=0.3,0.1

Type RM Length L Ch R = 1 ,6698    ,417,417,417
BEGIN DESCRIPTION:
UDS St 17 11.0
END DESCRIPTION:
XS GIS Cut Line= 3
      2276088.04      7183428.83        2275729.        7183310.
      2275379.78      7183241.32
#Sta/Elev= 30
  4621.8  849.89  4641.9  847.73  4662.1  847.55  4735.7  844.97  4788.6  841.82
  4825.6  841.75  4952.4  836.23  4968.4  834.09  5010.2  834.35  5020.4   831.9
  5025.7  826.41  5028.7  824.83    5029  824.33  5032.9  824.83  5061.1  834.21
  5071.3  834.62  5101.9  832.21  5133.6  832.52  5142.7  830.71  5163.1  832.28
  5179.9  831.91    5185  833.12    5214  831.23  5231.2  832.12  5236.3  830.37
  5244.6  833.64    5265  844.51  5275.2  846.14  5326.1  845.46  5355.9  846.81
#Mann= 5 ,-1 , 0
  4621.8     .12       0  4662.1     .05       0  4735.7     .12       0
  5028.7     .07       0  5032.9     .12       0
Bank Sta=5028.7,5032.9
XS Rating Curve= 0 ,0
Exp/Cntr=0.3,0.1

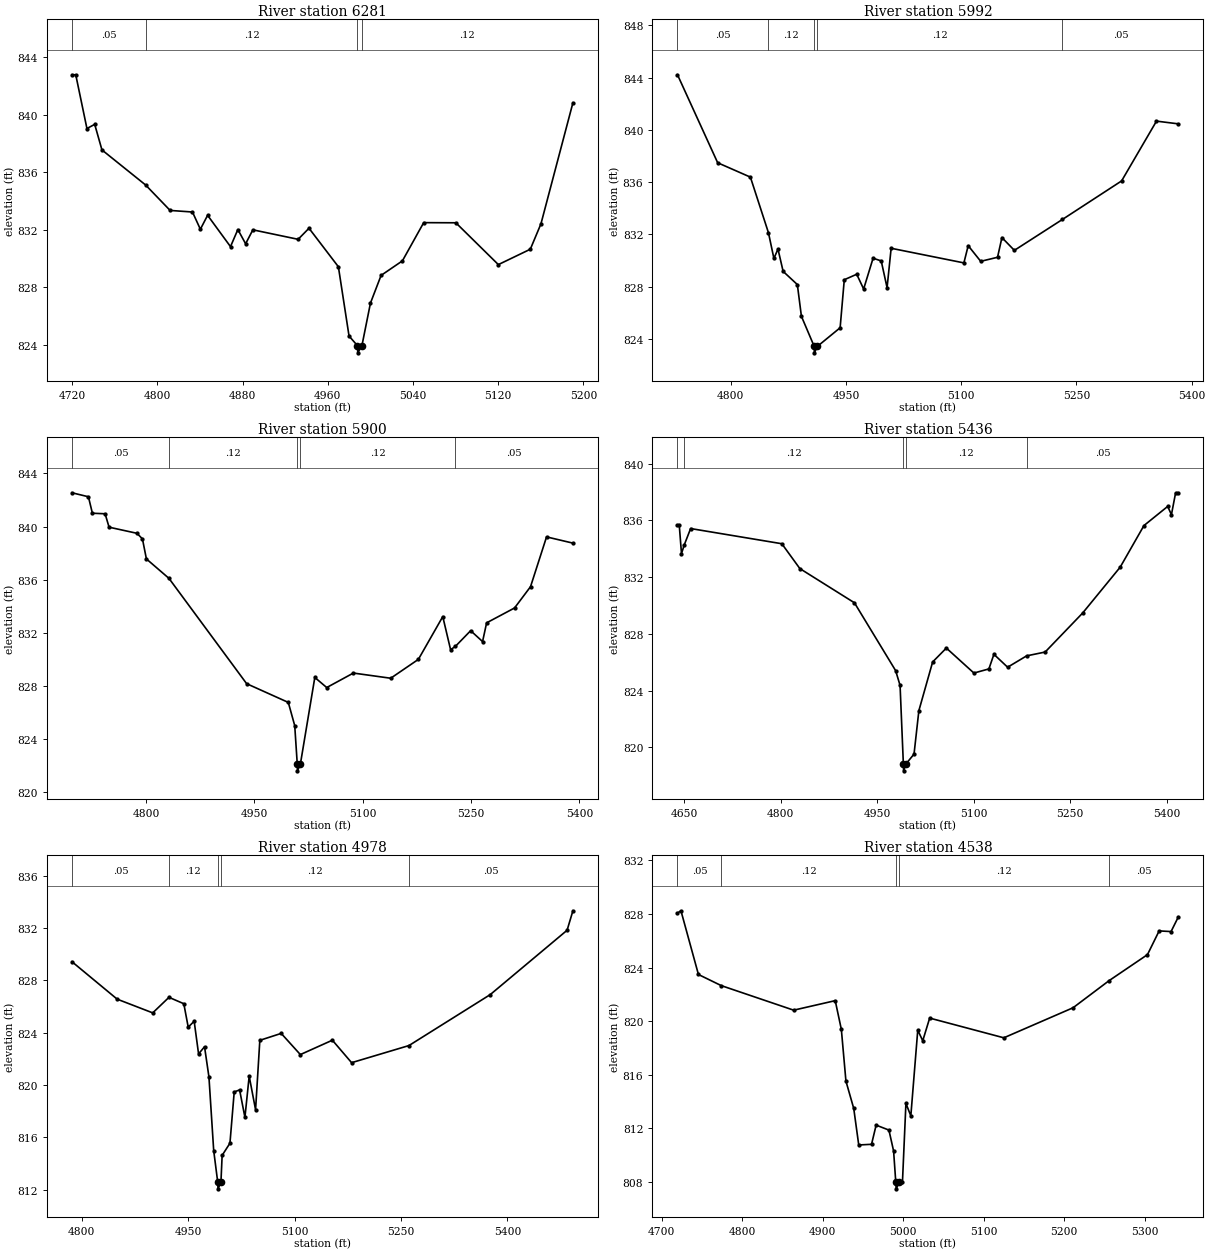
Type RM Length L Ch R = 1 ,6281    ,289,289,289
BEGIN DESCRIPTION:
UDS St 17 10.0
END DESCRIPTION:
XS GIS Cut Line= 3
      2275979.03      7183160.03      2275829.22       7182999.1
      2275579.03        7183010.
#Sta/Elev= 30
  4719.8  842.77  4723.3  842.77  4733.8  839.03  4741.1  839.32  4747.9  837.54
  4788.9   835.1  4811.9  833.33  4832.9  833.22  4840.3  832.02  4847.1  832.99
  4868.6  830.81  4875.5     832  4882.8  831.01  4889.6  831.98  4932.1  831.32
  4942.3  832.09  4969.9  829.41  4979.9  824.59  4987.8  823.92  4988.1  823.42
    4992  823.92    5000  826.88    5010  828.81    5030  829.82    5050  832.48
  5080.2  832.47  5120.1  829.56  5150.1  830.63  5160.1   832.4  5190.1  840.82
#Mann= 4 ,-1 , 0
  4719.8     .05       0  4788.9     .12       0  4987.8     .07       0
    4992     .12       0
Bank Sta=4987.8,4992
XS Rating Curve= 0 ,0
Exp/Cntr=0.3,0.1

Type RM Length L Ch R = 1 ,5992    ,92,92,92
BEGIN DESCRIPTION:
UDS St 17 9.1
END DESCRIPTION:
XS GIS Cut Line= 3
      2276008.49      7183149.09      2275891.69      7182829.78
      2275744.06      7182554.92
#Sta/Elev= 30
  4730.7  844.22    4783  837.48  4825.6  836.38  4849.1  832.12  4856.2  830.15
  4861.5  830.87  4868.2  829.16  4886.7  828.15    4892  825.72  4908.6  823.42
  4908.9  822.92  4912.9  823.42  4942.4  824.84  4947.8  828.52    4964  828.94
    4973  827.81  4985.3  830.17  4995.9  829.96  5003.5  827.91  5008.8  830.93
  5103.5  829.81  5109.1  831.13  5125.4  829.93  5147.3  830.24    5153  831.75
  5169.2  830.77  5231.8  833.14  5308.8  836.09  5354.2  840.67  5382.7  840.46
#Mann= 5 ,-1 , 0
  4730.7     .05       0  4849.1     .12       0  4908.6     .07       0
  4912.9     .12       0  5231.8     .05       0
Bank Sta=4908.6,4912.9
XS Rating Curve= 0 ,0
Exp/Cntr=0.3,0.1

Type RM Length L Ch R = 1 ,5900    ,464,464,464
BEGIN DESCRIPTION:
UDS St 17 9.0
END DESCRIPTION:
XS GIS Cut Line= 3
      2276105.02      7183121.91      2276000.97      7182891.44
      2275798.61      7182499.92
#Sta/Elev= 30
  4697.5  842.54  4720.2  842.24  4725.7     841  4743.3  840.96  4748.8  839.95
  4787.4  839.49    4795  839.07  4800.5  837.56  4831.7   836.1  4939.3  828.17
    4997  826.76  5005.9  825.01  5009.4  822.11  5009.7  821.61  5013.7  822.11
  5033.7  828.64  5050.2  827.88  5087.1  828.97  5138.8  828.58  5177.1     830
  5210.9  833.22  5221.7  830.73  5228.4  830.98  5249.5  832.16    5266  831.34
  5271.6  832.75  5310.3  833.87  5332.4  835.47  5354.6  839.22  5391.1  838.75
#Mann= 5 ,-1 , 0
  4697.5     .05       0  4831.7     .12       0  5009.4     .07       0
  5013.7     .12       0  5228.4     .05       0
Bank Sta=5009.4,5013.7
XS Rating Curve= 0 ,0
Exp/Cntr=0.3,0.1

Type RM Length L Ch R = 1 ,5436    ,458,458,458
BEGIN DESCRIPTION:
UDS St 17 8.0
END DESCRIPTION:
XS GIS Cut Line= 3
      2276527.91      7182769.88       2276263.3      7182522.75
      2275906.68       7182308.3
#Sta/Elev= 30
  4639.8  835.68  4642.5  835.68    4646  833.66  4650.5  834.29  4660.2  835.42
  4801.9  834.35  4829.9   832.6  4914.7  830.19  4978.7  825.41  4985.6  824.37
  4990.7  818.85  4991.1  818.35    4995  818.85  5007.3  819.53  5014.8  822.59
  5036.2  826.02  5057.5     827  5100.3  825.24  5123.6  825.53  5131.4  826.56
  5152.7  825.65  5182.2  826.45    5211  826.72  5269.3  829.47  5327.6   832.7
  5364.5  835.63  5401.4  836.98  5407.2   836.4  5413.7  837.94    5418  837.94
#Mann= 5 ,-1 , 0
  4639.8     .05       0  4650.5     .12       0  4990.7     .07       0
    4995     .12       0  5182.2     .05       0
Bank Sta=4990.7,4995
XS Rating Curve= 0 ,0
Exp/Cntr=0.3,0.1

Type RM Length L Ch R = 1 ,4978    ,440,440,440
BEGIN DESCRIPTION:
UDS St 17 7.0
END DESCRIPTION:
XS GIS Cut Line= 3
      2276729.03      7182360.02      2276557.58      7182232.29
      2276147.93      7181959.97
#Sta/Elev= 30
  4786.5  829.43  4850.1  826.57  4900.2  825.52  4923.1  826.71    4944  826.22
  4950.2  824.43  4958.6  824.88  4964.8  822.38  4973.2  822.93  4979.4  820.62
  4986.1  814.99  4991.8  812.56  4992.2  812.06  4996.3  812.56    4998  814.62
    5009  815.55    5015  819.47  5022.6  819.63  5030.1  817.53  5036.1  820.68
  5045.1  818.11  5051.1  823.42  5081.2  823.95  5108.2  822.33  5153.3  823.43
  5180.4  821.71  5261.2  823.02  5375.8  826.92    5484  831.84  5492.2  833.33
#Mann= 5 ,-1 , 0
  4786.5     .05       0  4923.1     .12       0  4991.8     .07       0
  4996.3     .12       0  5261.2     .05       0
Bank Sta=4991.8,4996.3
XS Rating Curve= 0 ,0
Exp/Cntr=0.3,0.1

Type RM Length L Ch R = 1 ,4538    ,324,324,324
BEGIN DESCRIPTION:
UDS St 17 6.0
END DESCRIPTION:
XS GIS Cut Line= 3
      2276919.43      7182096.18        2276679.        7181960.
      2276397.73      7181758.88
#Sta/Elev= 30
  4719.7  828.06    4724  828.23  4745.7  823.48  4774.1  822.65    4864  820.82
  4915.6  821.53  4923.2  819.39  4928.9  815.53  4938.6  813.49  4944.8  810.77
  4960.7  810.82  4966.4  812.25  4982.3  811.88  4988.1  810.32  4990.8     808
  4991.3   807.5  4995.4     808  4999.1     808  5003.4  813.87  5009.5  812.94
  5018.1  819.33  5024.3  818.54  5032.9  820.23    5125  818.76    5211     821
  5255.7  823.02  5303.4  824.96  5317.9  826.73  5332.7  826.68  5341.8  827.78
#Mann= 5 ,-1 , 0
  4719.7     .05       0  4774.1     .12       0  4990.8     .07       0
  4995.4     .12       0  5255.7     .05       0
Bank Sta=4990.8,4995.4
XS Rating Curve= 0 ,0
Exp/Cntr=0.3,0.1

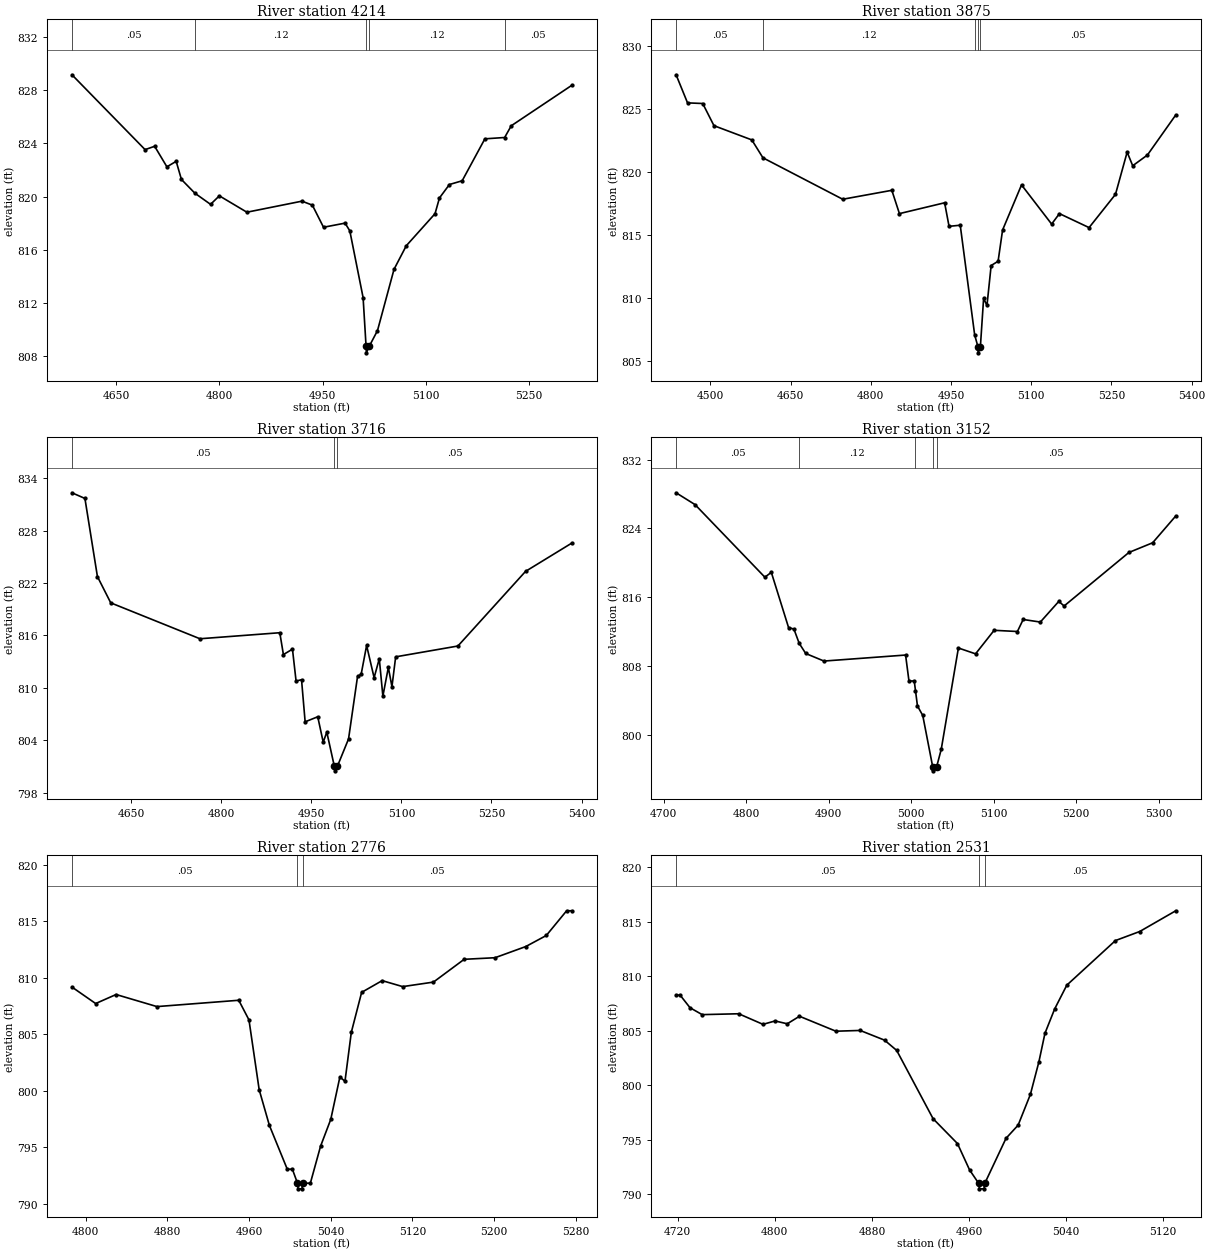
Type RM Length L Ch R = 1 ,4214    ,339,339,339
BEGIN DESCRIPTION:
UDS St 17 5.0
END DESCRIPTION:
XS GIS Cut Line= 3
      2277119.51      7181783.17      2276741.12      7181653.98
        2276429.        7181560.
#Sta/Elev= 30
  4585.7  829.15  4691.9  823.53  4705.8  823.78  4723.6  822.24  4737.1  822.65
  4744.7  821.29  4764.2  820.26    4787  819.42  4799.8  820.06  4839.8  818.83
  4919.8  819.66  4934.9  819.36  4951.1   817.7  4982.4  818.01  4989.3  817.43
  5008.6  812.42  5012.9  808.77  5013.4  808.27  5017.6  808.77  5029.5  809.94
  5053.5  814.54  5071.3  816.31  5113.1  818.72  5119.5   819.9    5134  820.91
  5152.5  821.19  5185.5  824.34  5214.2  824.44  5223.8  825.32  5311.5  828.35
#Mann= 5 ,-1 , 0
  4585.7     .05       0  4764.2     .12       0  5012.9     .07       0
  5017.6     .12       0  5214.2     .05       0
Bank Sta=5012.9,5017.6
XS Rating Curve= 0 ,0
Exp/Cntr=0.3,0.1

Type RM Length L Ch R = 1 ,3875    ,159,159,159
BEGIN DESCRIPTION:
UDS St 17 4.1
END DESCRIPTION:
XS GIS Cut Line= 4
       2277098.2      7181731.03      2276766.08      7181419.38
      2276522.64      7181237.39      2276369.24      7181321.43
#Sta/Elev= 30
  4435.9  827.73  4457.3   825.5  4485.7  825.45  4506.7  823.69  4577.5  822.56
  4598.3  821.14  4747.5  817.85  4839.3  818.56  4853.5  816.71    4938  817.57
  4946.3   815.7  4967.2  815.79  4994.2  807.08  5000.2  806.16  5000.7  805.66
  5004.9  806.16  5010.9  809.98  5017.2  809.42    5025  812.59    5038  812.93
  5046.4  815.41  5081.8  818.99  5138.1  815.88  5152.7  816.71  5208.1   815.6
  5257.5  818.24  5279.3  821.59  5289.7  820.51  5317.2  821.36  5370.2  824.54
#Mann= 5 ,-1 , 0
  4435.9     .05       0  4598.3     .12       0  4994.2     .05       0
  5000.2    .033       0  5004.9     .05       0
Bank Sta=5000.2,5004.9
XS Rating Curve= 0 ,0
Exp/Cntr=0.3,0.1

Type RM Length L Ch R = 1 ,3716    ,564,564,564
BEGIN DESCRIPTION:
UDS St 17 4.0
END DESCRIPTION:
XS GIS Cut Line= 4
      2276979.01      7181059.99      2276718.45      7181272.82
      2276516.31      7181139.93      2276290.86      7181256.82
#Sta/Elev= 30
  4551.2  832.33  4572.8  831.68  4593.6  822.74  4615.8  819.73  4764.4  815.62
  4897.4  816.31  4903.4  813.81  4918.5  814.43  4924.5  810.78  4933.6  810.93
  4939.6  806.11  4960.6  806.69  4969.7  803.78  4975.7  804.93  4988.3     801
  4988.9   800.5  4993.2     801  5011.9  804.15  5026.9  811.31  5032.9  811.55
    5042  814.85  5054.5  811.16  5063.1  813.33  5069.1  809.05  5078.2  812.34
  5084.2  810.13  5090.4  813.55  5194.1  814.79  5306.7  823.33  5383.5  826.56
#Mann= 3 ,-1 , 0
  4551.2     .05       0  4988.3    .033       0  4993.2     .05       0
Bank Sta=4988.3,4993.2
XS Rating Curve= 0 ,0
Exp/Cntr=0.3,0.1

Type RM Length L Ch R = 1 ,3152    ,376,376,376
BEGIN DESCRIPTION:
UDS St 17 3.0
END DESCRIPTION:
XS GIS Cut Line= 3
      2276461.63      7180590.74      2276278.84      7180809.73
      2276079.01      7181059.99
#Sta/Elev= 30
  4715.1  828.15  4738.1  826.77  4822.7  818.32  4830.5  818.89  4851.4  812.46
  4857.9  812.28  4864.3  810.62  4872.2  809.44  4894.3  808.56  4993.2  809.26
  4997.3  806.24  5003.7  806.24  5005.2  805.12  5007.6  803.33    5014  802.23
    5026  796.28  5026.6  795.78  5030.9  796.28  5036.4  798.28  5057.2  810.08
    5078   809.4  5100.5  812.14  5128.7     812  5135.7   813.4  5156.5   813.1
  5178.9  815.51  5185.3  814.97  5263.8   821.2  5292.6  822.33  5320.6  825.45
#Mann= 5 ,-1 , 0
  4715.1     .05       0  4864.3     .12       0  5005.2     .05       0
    5026     .07       0  5030.9     .05       0
Bank Sta=5026,5030.9
XS Rating Curve= 0 ,0
Exp/Cntr=0.3,0.1

Type RM Length L Ch R = 1 ,2776    ,245,245,245
BEGIN DESCRIPTION:
UDS St 17 2.0
END DESCRIPTION:
XS GIS Cut Line= 3
      2276242.21      7180555.06        2276029.        7180560.
       2275754.3      7180586.09
#Sta/Elev= 30
  4786.7  809.18  4809.9  807.72  4829.9  808.52  4869.9  807.45    4950  808.01
    4960  806.27    4970  800.08    4980  796.92  4997.5  793.04  5002.5  793.04
  5007.5   791.8  5008.1   791.3  5011.9   791.3  5012.5   791.8  5020.1   791.8
  5030.1  795.08  5040.1  797.46    5049  801.21    5054  800.83  5060.2  805.17
  5070.3  808.71  5090.4  809.75  5110.5  809.22  5140.6  809.62  5170.7  811.64
  5200.9  811.78    5231  812.77  5251.1  813.75    5271  815.94  5275.9  815.94
#Mann= 3 ,-1 , 0
  4786.7     .05       0  5007.5    .033       0  5012.5     .05       0
Bank Sta=5007.5,5012.5
XS Rating Curve= 0 ,0
Exp/Cntr=0.3,0.1

Type RM Length L Ch R = 1 ,2531    ,225,225,225
BEGIN DESCRIPTION:
UDS St 17 1.1
END DESCRIPTION:
XS GIS Cut Line= 2
      2276210.49      7180362.12      2275799.35       7180338.7
#Sta/Elev= 30
  4718.6  808.26  4721.9  808.26  4730.1   807.1  4740.1  806.47  4770.2  806.55
  4790.2  805.58  4800.2  805.89  4810.2  805.63  4820.3  806.32  4850.3  804.95
  4870.3  805.02  4890.4  804.13  4900.4  803.19  4930.4  796.93  4950.5  794.65
  4960.5  792.23    4968     791  4968.6   790.5  4972.4   790.5    4973     791
  4990.5  795.13  5000.5  796.34  5010.6  799.16  5017.6  802.14  5022.6  804.76
  5030.6  806.99  5040.6  809.17  5080.7  813.26  5100.7  814.09  5130.4  815.99
#Mann= 3 ,-1 , 0
  4718.6     .05       0    4968    .033       0    4973     .05       0
Bank Sta=4968,4973
XS Rating Curve= 0 ,0
Exp/Cntr=0.3,0.1

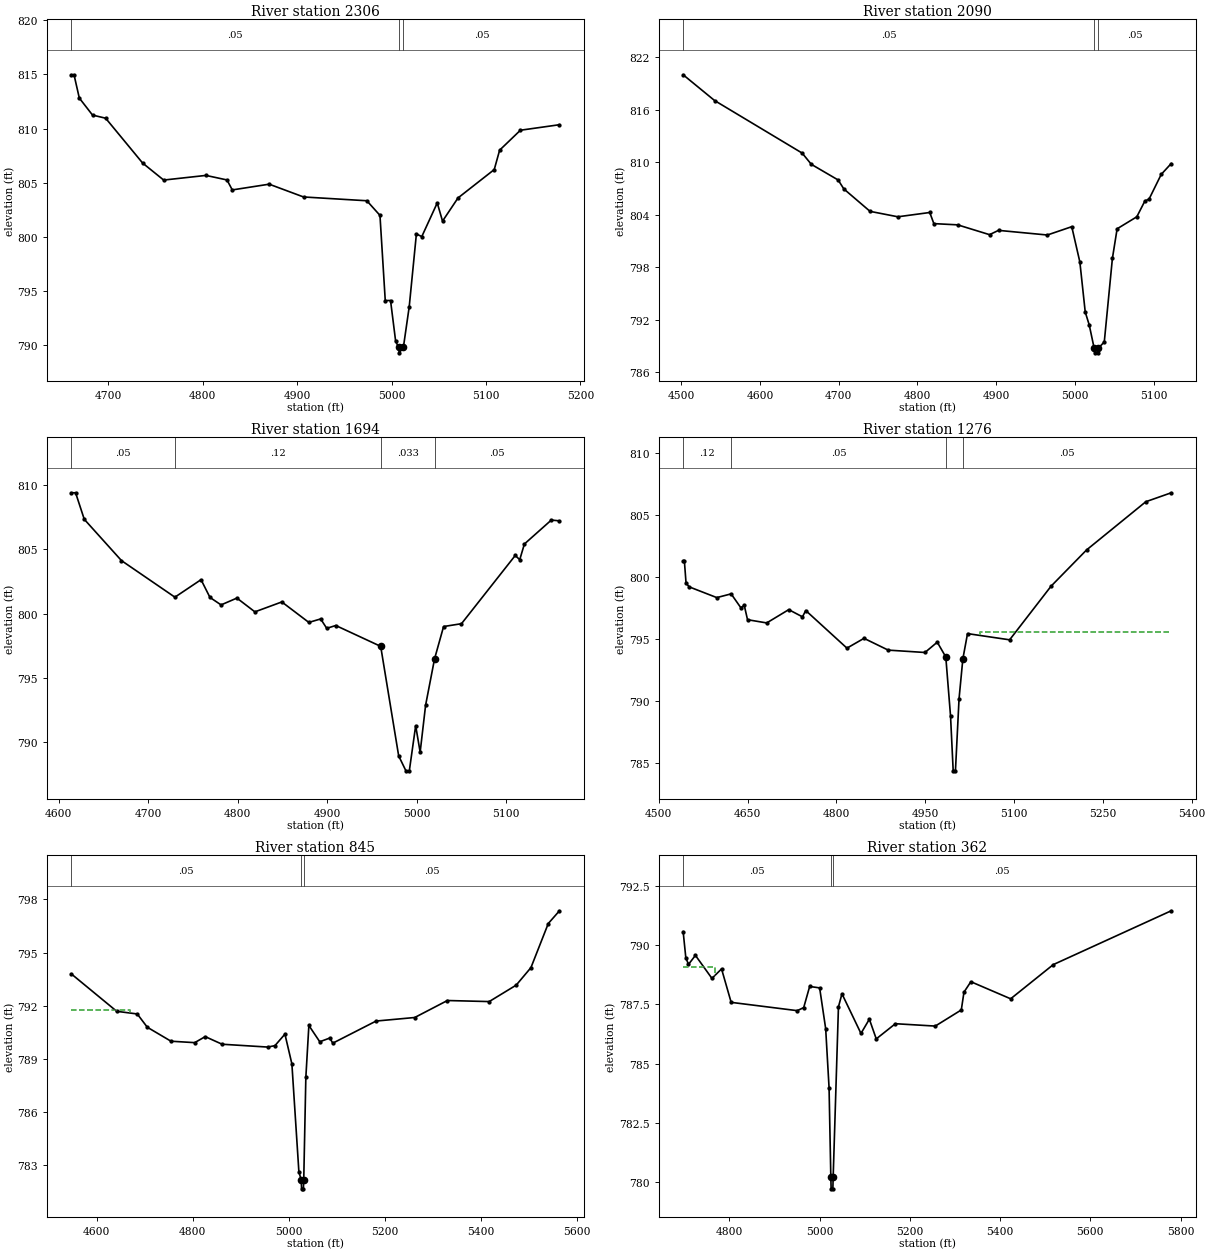
Type RM Length L Ch R = 1 ,2306    ,216,216,216
BEGIN DESCRIPTION:
UDS St 17 1.0
END DESCRIPTION:
XS GIS Cut Line= 3
        2276329.        7180310.        2276029.        7180160.
      2275868.15       7180075.3
#Sta/Elev= 30
  4660.7  814.96  4663.5  814.96  4669.1  812.81  4683.1  811.24    4697  810.95
  4736.2  806.81  4758.5  805.24  4803.3  805.67  4825.6  805.25  4831.2  804.33
  4870.3  804.86  4906.7  803.68  4973.8  803.33  4987.7  801.98  4993.3  794.12
  4998.9  794.12  5004.3  790.37  5007.5  789.79  5008.1  789.29  5012.5  789.79
  5018.7  793.55  5026.3  800.27    5032  800.02  5048.4  803.13    5054  801.45
  5070.4  803.59  5108.8  806.21  5114.5     808  5136.5  809.84  5177.9  810.35
#Mann= 3 ,-1 , 0
  4660.7     .05       0  5007.5    .033       0  5012.5     .05       0
#XS Ineff= 2 , 0
       0                  5048.4       0  803.13
Permanent Ineff=
       F       F
Bank Sta=5007.5,5012.5
XS Rating Curve= 0 ,0
Exp/Cntr=0.3,0.1

Type RM Length L Ch R = 1 ,2090    ,396,396,396
BEGIN DESCRIPTION:
UDS St 17 0.9
END DESCRIPTION:
XS GIS Cut Line= 2
      2276556.45      7180084.06      2275956.75      7179927.88
#Sta/Elev= 30
  4502.5  819.97  4542.4  817.03  4653.6  811.03  4665.2  809.75  4699.3  807.96
  4706.5  806.94  4739.8  804.38  4775.1  803.76  4815.6  804.25  4820.8  802.98
    4851  802.84  4891.5  801.72  4902.9  802.21  4964.9  801.68  4995.9  802.63
  5006.2  798.59    5013  792.89  5018.1  791.41  5024.4  788.73    5025  788.23
  5028.8  788.23  5029.4  788.73  5037.2  789.48  5047.5  799.01  5053.5  802.39
  5078.5  803.76  5088.8  805.57    5094  805.77  5109.5   808.6  5122.2  809.84
#Mann= 3 ,-1 , 0
  4502.5     .05       0  5024.4    .033       0  5029.4     .05       0
Bank Sta=5024.4,5029.4
XS Rating Curve= 0 ,0
Exp/Cntr=0.3,0.1

Type RM Length L Ch R = 1 ,1694    ,418,418,418
BEGIN DESCRIPTION:
UDS St 17 0.8
END DESCRIPTION:
XS GIS Cut Line= 2
      2276563.31      7179560.32      2276019.98      7179608.98
#Sta/Elev= 30
  4614.2  809.38  4618.9  809.38  4628.6  807.32  4670.2  804.11  4729.9  801.27
  4759.1  802.63  4769.1  801.25  4781.5  800.67  4799.2   801.2  4819.3  800.13
  4849.4   800.9  4879.6  799.31  4892.8  799.58  4899.6  798.85  4909.7  799.07
  4959.9  797.45    4980  788.94  4988.1  787.78  4991.9  787.78    4999  791.29
    5004  789.23  5010.1  792.88  5020.1  796.48  5030.2  798.99  5050.2  799.21
  5110.3  804.51  5115.3  804.18  5120.5   805.4  5150.6  807.26  5159.7   807.2
#Mann= 4 ,-1 , 0
  4614.2     .05       0  4729.9     .12       0  4959.9    .033       0
  5020.1     .05       0
Bank Sta=4959.9,5020.1
XS Rating Curve= 0 ,0
Exp/Cntr=0.3,0.1

Type RM Length L Ch R = 1 ,1276    ,431,431,431
BEGIN DESCRIPTION:
UDS St 17 0.7
END DESCRIPTION:
XS GIS Cut Line= 4
      2276457.85      7179337.26      2276110.49      7179182.11
      2276016.42       7179299.7      2276020.26      7179592.85
#Sta/Elev= 30
  4541.2  801.27  4543.3  801.27  4546.1  799.51  4551.6  799.21    4598  798.35
  4622.2  798.65  4638.5  797.54  4644.4  797.72  4649.9  796.57  4682.3  796.31
  4719.5  797.38  4742.7   796.8  4748.2  797.31  4817.8  794.28  4846.6  795.07
  4887.5  794.12  4949.5  793.93  4970.3  794.76  4984.7  793.57  4992.7  788.83
  4997.2   784.4    5001   784.4  5007.1  790.21  5013.5  793.41  5021.4  795.45
  5092.5  794.95  5162.5  799.27  5222.5  802.19  5322.5  806.07  5365.4  806.79
#Mann= 4 ,-1 , 0
  4541.2     .12       0  4622.2     .05       0  4984.7    .033       0
  5013.5     .05       0
#XS Ineff= 2 , 0
       0  4748.2  797.31  5042.3       0  795.55
Permanent Ineff=
       F       F
Bank Sta=4984.7,5013.5
XS Rating Curve= 0 ,0
Exp/Cntr=0.3,0.1

Type RM Length L Ch R = 1 ,845     ,483,483,483
BEGIN DESCRIPTION:
UDS St 17 0.6
END DESCRIPTION:
XS GIS Cut Line= 4
      2276233.55       7179108.4      2275922.77      7178842.42
      2275836.19      7178955.53      2275992.88      7179393.96
#Sta/Elev= 30
  4547.2  793.79  4641.7  791.68  4684.5  791.53  4705.4  790.78  4754.8  789.99
  4804.2  789.91  4826.1  790.25  4861.3  789.82  4956.3  789.66  4971.4  789.74
  4992.2  790.39  5006.7  788.71  5021.3  782.61  5026.2  782.15  5026.9  781.65
  5030.7  781.65  5031.4  782.15  5035.8  787.95  5042.1  790.88  5064.8  789.96
  5085.7  790.17  5091.9  789.88  5182.2  791.13  5262.7  791.33  5330.8  792.29
  5417.9  792.23  5474.2  793.16  5504.9  794.15    5541  796.64  5564.3  797.36
#Mann= 3 ,-1 , 0
  4547.2     .05       0  5026.2    .033       0  5031.4     .05       0
#XS Ineff= 2 , 0
       0  4670.3  791.74               0
Permanent Ineff=
       F       F
Bank Sta=5026.2,5031.4
XS Rating Curve= 0 ,0
Exp/Cntr=0.3,0.1

Type RM Length L Ch R = 1 ,362     ,323,323,323
BEGIN DESCRIPTION:
UDS St 17 0.5
END DESCRIPTION:
XS GIS Cut Line= 4
      2275817.22      7178659.24      2275592.57      7178520.28
      2275501.06      7178629.79      2275859.98      7179201.39
#Sta/Elev= 30
  4697.6  790.57  4703.5  789.47  4709.4  789.19  4724.8  789.57  4761.4   788.6
  4782.7     789    4804  787.59  4950.5  787.24  4964.8  787.37    4978  788.26
  5000.1   788.2  5013.5  786.48    5021  783.99  5024.9  780.23  5025.6  779.73
  5029.4  779.73  5030.1  780.23  5041.8   787.4  5049.6  787.95  5091.7  786.28
  5110.3  786.88  5125.6  786.05    5168  786.69  5256.4  786.59  5314.1  787.27
    5320  788.02  5335.3  788.46  5423.5  787.74  5517.9  789.18  5779.4  791.45
#Mann= 3 ,-1 , 0
  4697.6     .05       0  5024.9     .04       0  5030.1     .05       0
#XS Ineff= 2 , 0
       0  4767.3  789.07               0
Permanent Ineff=
       F       F
Bank Sta=5024.9,5030.1
XS Rating Curve= 0 ,0
Exp/Cntr=0.3,0.1

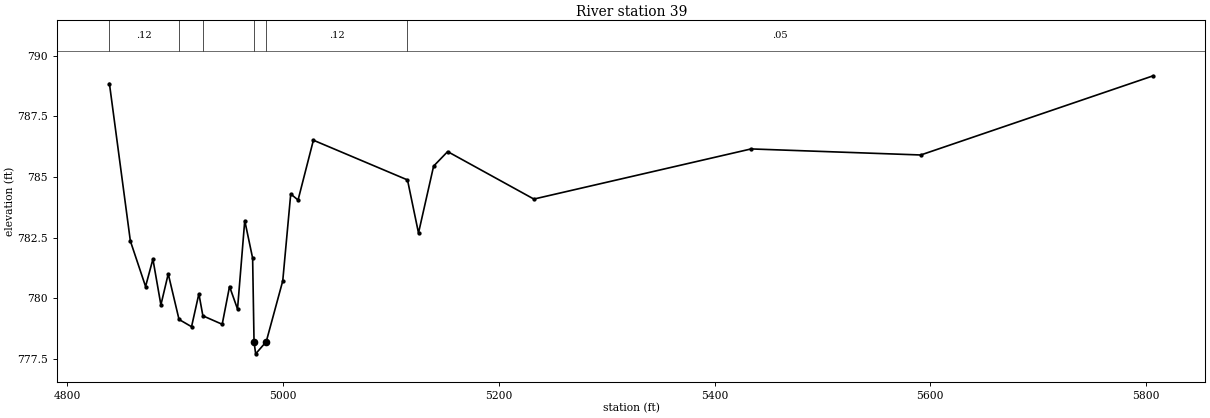
Type RM Length L Ch R = 1 ,39      ,0,0,0
BEGIN DESCRIPTION:
UDS St 17 0.4
END DESCRIPTION:
XS GIS Cut Line= 3
      2275446.99      7178290.75      2275261.13      7178460.37
      2275678.24       7179041.8
#Sta/Elev= 30
  4839.3  788.86  4858.7  782.36  4872.8  780.48  4879.6  781.61    4887  779.72
  4893.8     781  4903.8  779.12  4915.4  778.82  4922.2  780.18  4925.9  779.27
  4943.8  778.92  4950.6  780.48    4958  779.55  4964.7   783.2    4972  781.65
  4973.3   778.2  4974.8   777.7  4984.6   778.2  4999.9  780.71  5007.3   784.3
  5014.1  784.05  5028.3  786.52  5115.5  784.88  5125.7  782.69  5139.7  785.45
  5152.7  786.05  5232.6  784.09  5433.9  786.16  5591.1  785.91  5806.5  789.18
#Mann= 6 ,-1 , 0
  4839.3     .12       0  4903.8     .05       0  4925.9     .12       0
  4973.3     .07       0  4984.6     .12       0  5115.5     .05       0
Bank Sta=4973.3,4984.6
XS Rating Curve= 0 ,0
Exp/Cntr=0.3,0.1

Chan Stop Cuts=-1
Use User Specified Reach Order=0
Composite Channel Slope=5