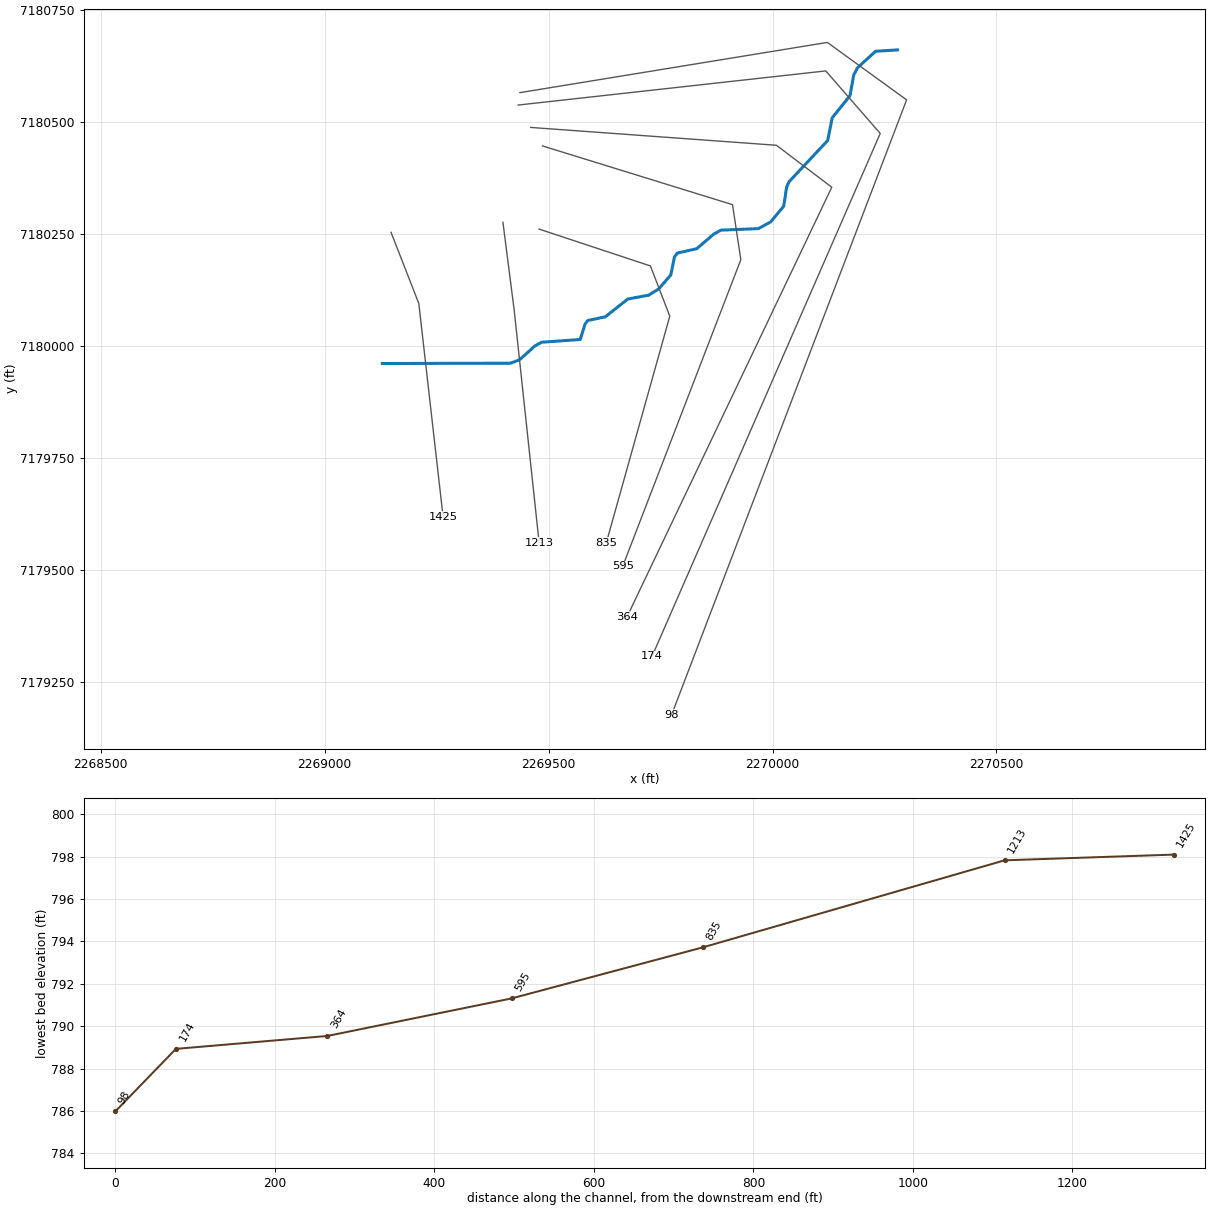
--- UDS St 19.prj (project) ---

Proj Title=UDS St 19 Base Level Engineering
Current Plan=p01
Default Exp/Contr=0.3,0.1
English Units
Geom File=g01
Flow File=f01
Plan File=p01
Y Axis Title=Elevation
X Axis Title(PF)=Main Channel Distance
X Axis Title(XS)=Station
BEGIN DESCRIPTION:
UDS St 19
END DESCRIPTION:
DSS Export Rating Curves= 0
DSS Export Rating Curve Sorted= 0
DSS Export Volume Flow Curves= 0
DXF OffsetX= 0
DXF OffsetY= 0
DXF ScaleX= 1
DXF ScaleY= 10

--- UDS St 19.p01 (plan) ---

Plan Title=Multiple Run
Short Identifier=Multiple
Geom File=g01
Flow File=f01
Subcritical Flow
K Sum by GR= 0
Std Step Tol= 0.01
Critical Tol= 0.01
Num of Std Step Trials= 20
Max Error Tol= 0.3
Flow Tol Ratio= 0.001
Split Flow NTrial= 30
Split Flow Tol= 0.02
Split Flow Ratio= 0.02
Log Output Level= 0
Friction Slope Method= 1
Unsteady Friction Slope Method= 2
Unsteady Bridges Friction Slope Method= 1
Parabolic Critical Depth
Global Vel Dist=  1 , 1 , 1
Global Log Level= 0
CheckData=True
Encroach Param= -1, 0, 0, 0
BEGIN DESCRIPTION:
Multiple Run
END DESCRIPTION:

--- UDS St 19.f01 (steady flow) ---

Flow Title=Multiple
Number of Profiles=7
Profile Names=10-year,25-year,50-year,1pct_min,100-year,1pct_plu,500-year
River Rch & RM= UDS St 19,Reach-1,1425
     512     705     865     528    1054    2103    1567
Boundary for River Rch & Prof#=UDS St 19,Reach-1,1
Up Type=0
Dn Type=3
Dn Slope=0.005
Boundary for River Rch & Prof#=UDS St 19,Reach-1,2
Up Type=0
Dn Type=3
Dn Slope=0.005
Boundary for River Rch & Prof#=UDS St 19,Reach-1,3
Up Type=0
Dn Type=3
Dn Slope=0.005
Boundary for River Rch & Prof#=UDS St 19,Reach-1,4
Up Type=0
Dn Type=3
Dn Slope=0.005
Boundary for River Rch & Prof#=UDS St 19,Reach-1,5
Up Type=0
Dn Type=3
Dn Slope=0.005
Boundary for River Rch & Prof#=UDS St 19,Reach-1,6
Up Type=0
Dn Type=3
Dn Slope=0.005
Boundary for River Rch & Prof#=UDS St 19,Reach-1,7
Up Type=0
Dn Type=3
Dn Slope=0.005

--- UDS St 19.g01 (geometry) ---

Geom Title=Existing Conditions
Program Version=4.10

River Reach=UDS St 19       ,Reach-1
Reach XY= 30
        2269129.        7179960.      2269415.08      7179960.68
      2269435.06      7179968.14      2269469.41      7179999.09
      2269484.65       7180007.5      2269570.81      7180013.66
      2269581.54      7180048.18      2269587.64       7180056.1
      2269626.94      7180064.26       2269676.8       7180103.9
      2269723.54      7180112.56      2269746.02      7180126.57
      2269773.11       7180157.8      2269781.14      7180197.94
      2269787.49      7180206.47      2269830.84      7180216.27
      2269869.29      7180249.19      2269884.95      7180257.67
      2269968.67       7180261.1      2269996.13       7180276.3
      2270025.13       7180311.4      2270031.56      7180353.91
      2270037.19      7180366.02      2270123.15      7180457.71
      2270133.19      7180508.27      2270172.91      7180557.82
      2270181.42      7180604.11      2270189.55      7180619.98
      2270230.03      7180656.86        2270279.        7180660.

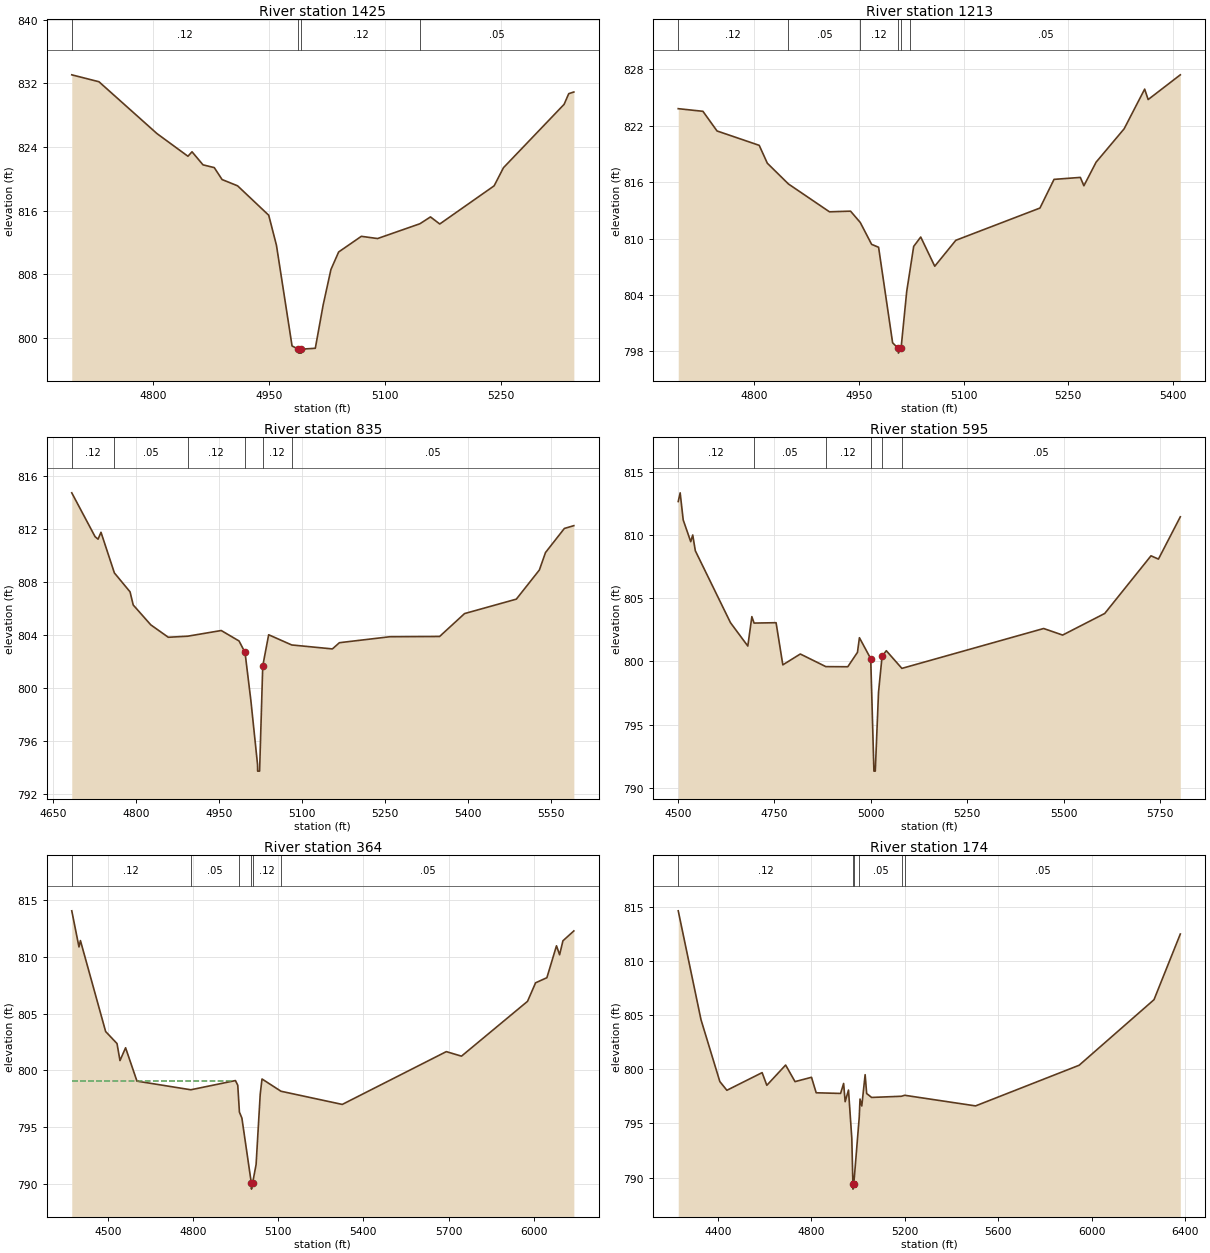
Type RM Length L Ch R = 1 ,1425    ,212,212,212
BEGIN DESCRIPTION:
UDS St 19 2.1
END DESCRIPTION:
XS GIS Cut Line= 3
      2269148.44      7180252.75      2269210.41      7180093.93
      2269264.64      7179617.49
#Sta/Elev= 30
  4694.7  833.09  4729.9  832.22    4805   825.7  4845.1  822.85  4850.4  823.41
  4864.6  821.77  4879.2  821.42  4889.3  819.92  4909.4  819.13  4949.7  815.43
  4959.7  811.65  4979.9  798.99  4988.1  798.59  4988.4  798.09  4991.9  798.09
  4992.1  798.59    5010   798.7  5020.1  804.12  5030.2   808.6  5040.2  810.81
  5069.6  812.78  5090.6   812.5  5145.4  814.36  5159.1  815.22  5171.1  814.33
  5241.5  819.13  5253.6  821.41  5332.1  829.38  5338.1  830.72  5344.7  830.93
#Mann= 4 ,-1 , 0
  4694.7     .12       0  4988.1     .07       0  4992.1     .12       0
  5145.4     .05       0
Bank Sta=4988.1,4992.1
XS Rating Curve= 0 ,0
Exp/Cntr=0.3,0.1

Type RM Length L Ch R = 1 ,1213    ,378,378,378
BEGIN DESCRIPTION:
UDS St 19 2.0
END DESCRIPTION:
XS GIS Cut Line= 3
      2269398.18      7180275.11      2269423.26      7180079.68
        2269479.      7179559.99
#Sta/Elev= 30
  4690.9  823.82  4726.3  823.54  4746.5  821.45    4807  819.92  4818.6  818.02
  4848.9  815.81  4907.7  812.85  4937.9  812.92  4951.8  811.72  4968.1  809.39
  4978.1  809.08  4998.2  798.92  5006.3  798.32  5006.5  797.82  5010.3  798.32
  5018.4  804.37  5023.7  806.91  5028.4  809.17  5038.5  810.17  5058.6  807.06
  5088.8  809.82  5209.4  813.25  5229.6   816.3  5267.3  816.51  5272.4  815.62
  5289.9  818.13  5330.1  821.68  5359.5   825.9  5364.5  824.79  5410.6  827.42
#Mann= 6 ,-1 , 0
  4690.9     .12       0  4848.9     .05       0  4951.8     .12       0
  5006.3     .07       0  5010.3     .12       0  5023.7     .05       0
Bank Sta=5006.3,5010.3
XS Rating Curve= 0 ,0
Exp/Cntr=0.3,0.1

Type RM Length L Ch R = 1 ,835     ,240,240,240
BEGIN DESCRIPTION:
UDS St 19 1.0
END DESCRIPTION:
XS GIS Cut Line= 4
      2269479.04      7180259.99      2269727.48      7180177.78
      2269770.67      7180065.63      2269628.99      7179559.96
#Sta/Elev= 30
  4684.3  814.74  4726.4  811.43  4731.8  811.24  4737.1  811.76  4761.3  808.69
  4789.6  807.26  4795.3  806.27    4827  804.77  4858.7  803.83  4893.6  803.91
  4954.3  804.34  4986.5  803.55  4997.3  802.68  5007.9  799.04  5019.9  794.22
  5020.1  793.72  5023.6  793.72  5029.3  801.66    5040  804.02  5081.6  803.25
  5155.1  802.95  5167.8  803.42  5258.9  803.87  5348.8  803.89  5393.9  805.62
  5487.4  806.71    5529  808.91  5540.1  810.23  5574.2  812.05  5591.3  812.26
#Mann= 6 ,-1 , 0
  4684.3     .12       0  4761.3     .05       0  4893.6     .12       0
  4997.3     .07       0  5029.3     .12       0  5081.6     .05       0
Bank Sta=4997.3,5029.3
XS Rating Curve= 0 ,0
Exp/Cntr=0.3,0.1

Type RM Length L Ch R = 1 ,595     ,231,231,231
BEGIN DESCRIPTION:
UDS St 19 0.9
END DESCRIPTION:
XS GIS Cut Line= 4
      2269486.63      7180445.65      2269910.72      7180314.56
      2269929.31      7180191.79       2269665.5      7179507.12
#Sta/Elev= 30
    4501  812.67    4506  813.36  4513.9  811.21  4533.4  809.49  4538.6  810.02
  4545.3  808.77  4636.5  803.07  4681.4  801.22  4691.9  803.55  4697.6  803.04
  4754.7  803.07  4772.2  799.73  4817.5  800.59  4883.7  799.59  4940.6  799.58
  4965.7  800.72  4970.8  801.88  5000.1  800.22  5008.4  791.31  5011.9  791.31
  5020.3  797.55  5029.5   800.4  5040.5  800.85  5080.9  799.45  5448.4  802.61
  5497.7  802.09  5606.8   803.8  5726.8  808.37  5746.1  808.11  5802.8  811.46
#Mann= 6 ,-1 , 0
    4501     .12       0  4697.6     .05       0  4883.7     .12       0
  5000.1     .07       0  5029.5     .12       0  5080.9     .05       0
#XS Ineff= 2 , 0
       0  4970.8  801.88               0
Permanent Ineff=
       F       F
Bank Sta=5000.1,5029.5
XS Rating Curve= 0 ,0
Exp/Cntr=0.3,0.1

Type RM Length L Ch R = 1 ,364     ,190,190,190
BEGIN DESCRIPTION:
UDS St 19 0.8
END DESCRIPTION:
XS GIS Cut Line= 4
      2269460.09      7180486.95      2270008.81      7180447.12
      2270132.35      7180353.47      2269675.35      7179394.82
#Sta/Elev= 30
  4373.4  814.05  4398.8  810.87  4403.9  811.43  4492.6  803.42  4532.7  802.36
  4543.1  800.86  4562.8  801.99  4602.9  799.05  4792.5  798.29  4949.4   799.1
  4957.7  798.69  4963.5  796.32  4972.2   795.8  5005.6  790.04  5005.9  789.54
  5009.6  790.04  5022.2  791.71  5036.7  797.89    5043  799.24  5109.8  798.16
  5325.5     797  5691.7  801.65  5745.1  801.25  5977.6  806.08  6005.9  807.71
  6045.7  808.16  6079.5  810.97  6090.5  810.18  6102.2  811.41  6140.6  812.28
#Mann= 6 ,-1 , 0
  4373.4     .12       0  4792.5     .05       0  4963.5     .12       0
  5005.6     .07       0  5009.6     .12       0  5109.8     .05       0
#XS Ineff= 2 , 0
       0  4943.1   799.1               0
Permanent Ineff=
       F       F
Bank Sta=5005.6,5009.6
XS Rating Curve= 0 ,0
Exp/Cntr=0.3,0.1

Type RM Length L Ch R = 1 ,174     ,76,76,76
BEGIN DESCRIPTION:
UDS St 19 0.7
END DESCRIPTION:
XS GIS Cut Line= 4
       2269432.1       7180536.9      2270118.92      7180613.09
      2270240.51       7180473.5       2269731.3      7179306.85
#Sta/Elev= 30
  4230.5  814.61    4328  804.56  4408.5  798.86  4438.7  798.05  4589.6  799.68
  4609.7  798.51  4690.2  800.38  4730.4  798.85  4800.9  799.25    4821  797.82
  4925.4  797.76  4938.4  798.68    4945     797  4959.3  798.07  4973.5   793.6
  4978.1  789.43  4978.4  788.93  4982.1  789.43  5005.3  795.57  5008.6  797.24
  5016.2   796.6  5030.5  799.49  5037.1  797.75  5058.3  797.39  5186.3   797.5
  5199.7  797.59  5503.3  796.61  5946.5  800.36    6267  806.41  6379.6  812.47
#Mann= 6 ,-1 , 0
  4230.5     .12       0  4978.1     .07       0  4982.1     .12       0
  5005.3     .05       0  5186.3     .12       0  5199.7     .05       0
#XS Ineff= 2 , 0
       0  4938.4  798.68               0
Permanent Ineff=
       F       F
Bank Sta=4978.1,4982.1
XS Rating Curve= 0 ,0
Exp/Cntr=0.3,0.1

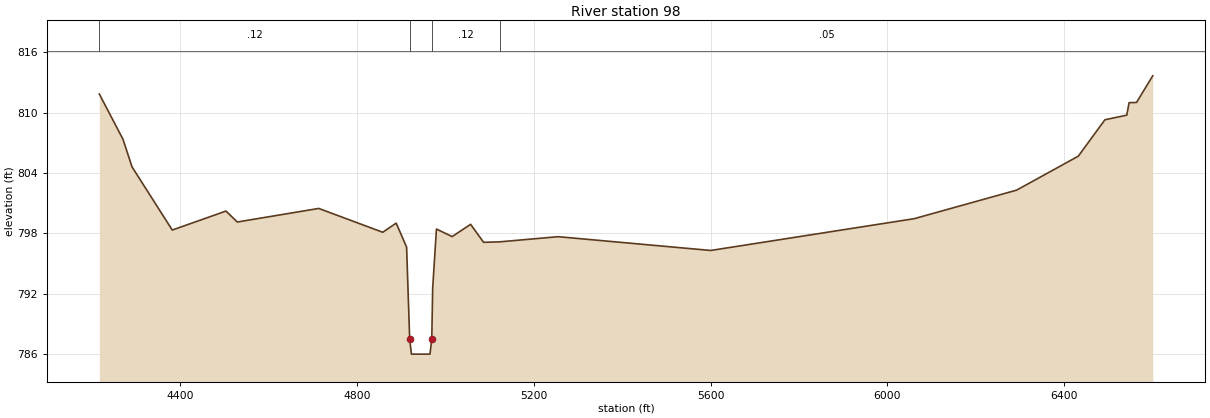
Type RM Length L Ch R = 1 ,98      ,0,0,0
BEGIN DESCRIPTION:
UDS St 19 0.6
END DESCRIPTION:
XS GIS Cut Line= 4
      2269436.11      7180564.63      2270122.36      7180676.71
      2270299.38      7180548.51      2269774.68      7179175.67
#Sta/Elev= 30
  4216.6  811.85  4270.2  807.34  4290.5  804.61  4381.6  798.32  4503.2  800.21
  4528.8  799.12  4713.1  800.47  4857.9   798.1  4888.3  799.01  4911.9  796.62
  4918.8  787.48  4922.8  785.98  4964.8  785.98  4968.8  787.48  4970.9  792.55
  4979.4  798.42  5014.9  797.67  5056.7  798.89  5086.1   797.1    5123  797.15
  5254.8  797.66    5600  796.29  6060.3  799.45  6292.2  802.29  6431.8  805.67
    6492  809.29  6541.4  809.75  6546.7  810.99  6563.5  811.01  6600.2  813.66
#Mann= 4 ,-1 , 0
  4216.6     .12       0  4918.8     .07       0  4968.8     .12       0
    5123     .05       0
Bank Sta=4918.8,4968.8
XS Rating Curve= 0 ,0
Exp/Cntr=0.3,0.1

Chan Stop Cuts=-1
Use User Specified Reach Order=0
Composite Channel Slope=5