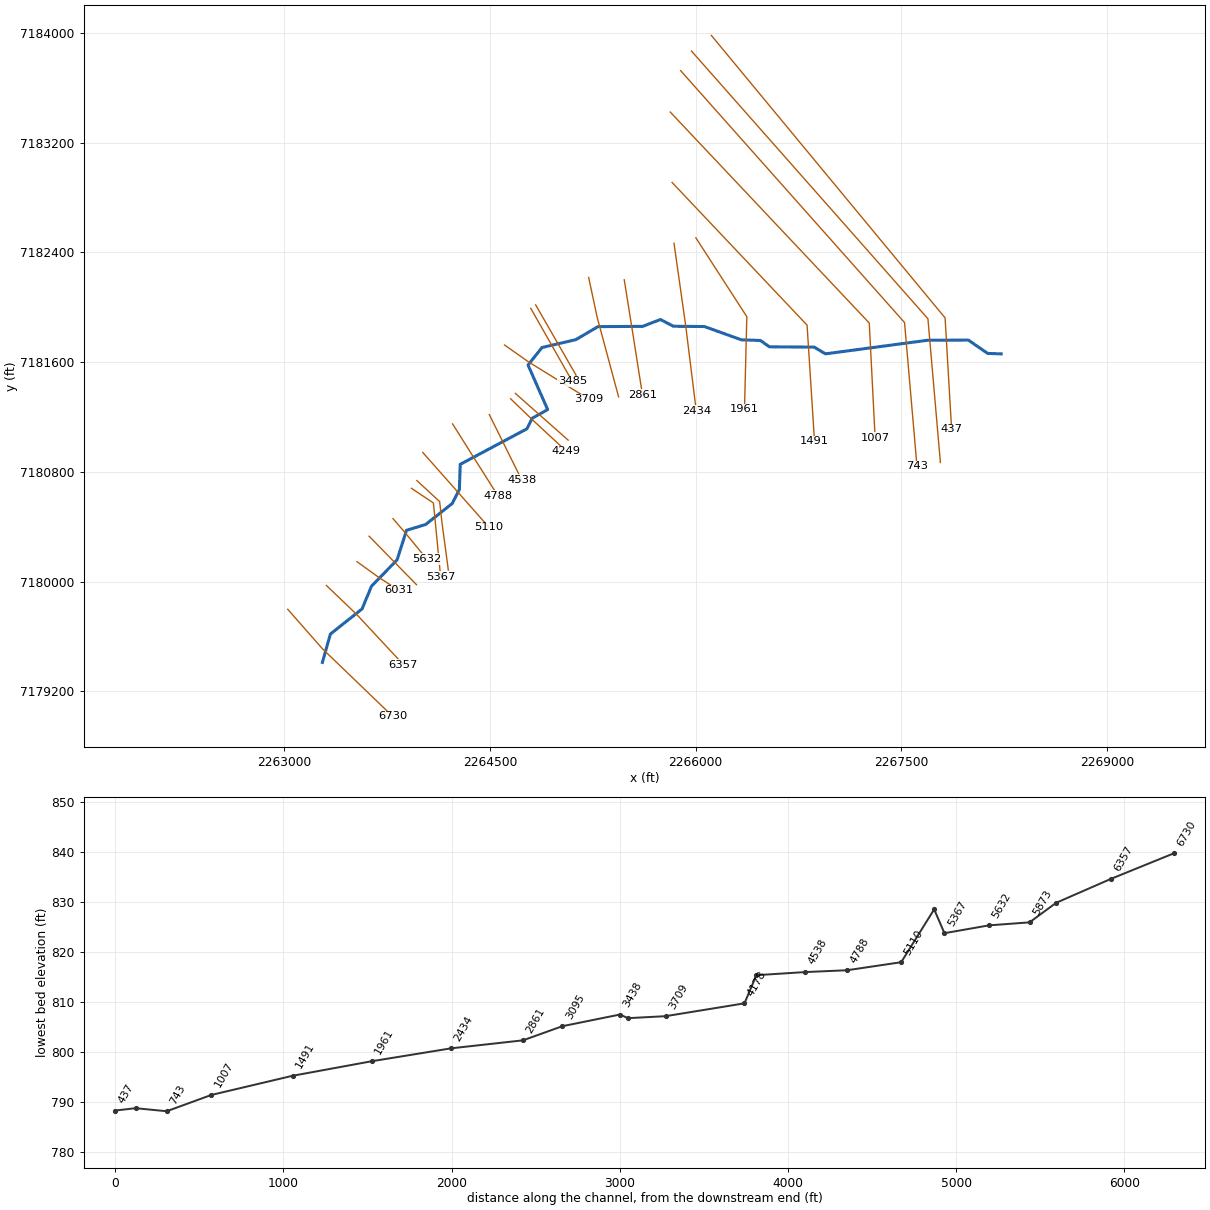
--- UDS St 20.prj (project) ---

Proj Title=UDS St 20 Base Level Engineering
Current Plan=p01
Default Exp/Contr=0.3,0.1
English Units
Geom File=g01
Flow File=f01
Plan File=p01
Y Axis Title=Elevation
X Axis Title(PF)=Main Channel Distance
X Axis Title(XS)=Station
BEGIN DESCRIPTION:
UDS St 20
END DESCRIPTION:
DSS Export Rating Curves= 0
DSS Export Rating Curve Sorted= 0
DSS Export Volume Flow Curves= 0
DXF OffsetX= 0
DXF OffsetY= 0
DXF ScaleX= 1
DXF ScaleY= 10

--- UDS St 20.p01 (plan) ---

Plan Title=Multiple Run
Short Identifier=Multiple
Geom File=g01
Flow File=f01
Subcritical Flow
K Sum by GR= 0
Std Step Tol= 0.01
Critical Tol= 0.01
Num of Std Step Trials= 20
Max Error Tol= 0.3
Flow Tol Ratio= 0.001
Split Flow NTrial= 30
Split Flow Tol= 0.02
Split Flow Ratio= 0.02
Log Output Level= 0
Friction Slope Method= 1
Unsteady Friction Slope Method= 2
Unsteady Bridges Friction Slope Method= 1
Parabolic Critical Depth
Global Vel Dist=  1 , 1 , 1
Global Log Level= 0
CheckData=True
Encroach Param= -1, 0, 0, 0
BEGIN DESCRIPTION:
Multiple Run
END DESCRIPTION:

--- UDS St 20.f01 (steady flow) ---

Flow Title=Multiple
Program Version=4.10
Number of Profiles= 7
Profile Names=10-year,25-year,50-year,1pct_min,100-year,1pct_plu,500-year
River Rch & RM=UDS St 20,Reach-1         ,6730
     928    1331    1682    1056    2107    4204    3314
River Rch & RM=UDS St 20,Reach-1         ,5110
    1322    1924    2451    1550    3093    6171    4938
Boundary for River Rch & Prof#=UDS St 20,Reach-1         , 1
Up Type= 0
Dn Type= 3
Dn Slope=0.006
Boundary for River Rch & Prof#=UDS St 20,Reach-1         , 2
Up Type= 0
Dn Type= 3
Dn Slope=0.006
Boundary for River Rch & Prof#=UDS St 20,Reach-1         , 3
Up Type= 0
Dn Type= 3
Dn Slope=0.006
Boundary for River Rch & Prof#=UDS St 20,Reach-1         , 4
Up Type= 0
Dn Type= 3
Dn Slope=0.006
Boundary for River Rch & Prof#=UDS St 20,Reach-1         , 5
Up Type= 0
Dn Type= 3
Dn Slope=0.006
Boundary for River Rch & Prof#=UDS St 20,Reach-1         , 6
Up Type= 0
Dn Type= 3
Dn Slope=0.006
Boundary for River Rch & Prof#=UDS St 20,Reach-1         , 7
Up Type= 0
Dn Type= 3
Dn Slope=0.006
DSS Import GetInterval= 0
DSS Import GetPeak= 0
DSS Import FillOption= 0

--- UDS St 20.g01 (geometry) ---

Geom Title=Existing Conditions
Program Version=4.10

River Reach=UDS St 20       ,Reach-1
Reach XY= 30
        2263279.        7179410.      2263337.02      7179616.34
      2263568.24      7179800.32      2263637.14      7179966.06
      2263823.48      7180157.57      2263892.45      7180373.63
      2264031.42      7180415.53      2264225.49      7180568.48
      2264277.81      7180670.48      2264284.18      7180854.56
       2264770.8       7181113.7      2264808.58      7181190.27
      2264921.64      7181253.66      2264778.74      7181578.46
      2264880.48      7181706.39      2265127.42      7181763.83
      2265288.65      7181858.64      2265615.08      7181860.69
      2265744.06      7181910.71      2265838.66      7181861.38
      2266065.08      7181859.32      2266334.53      7181762.39
      2266473.06      7181757.73      2266538.66      7181711.38
      2266865.08      7181709.32      2266947.27      7181660.21
      2267694.22      7181759.48      2267989.21       7181760.5
      2268130.41      7181663.39        2268229.        7181660.

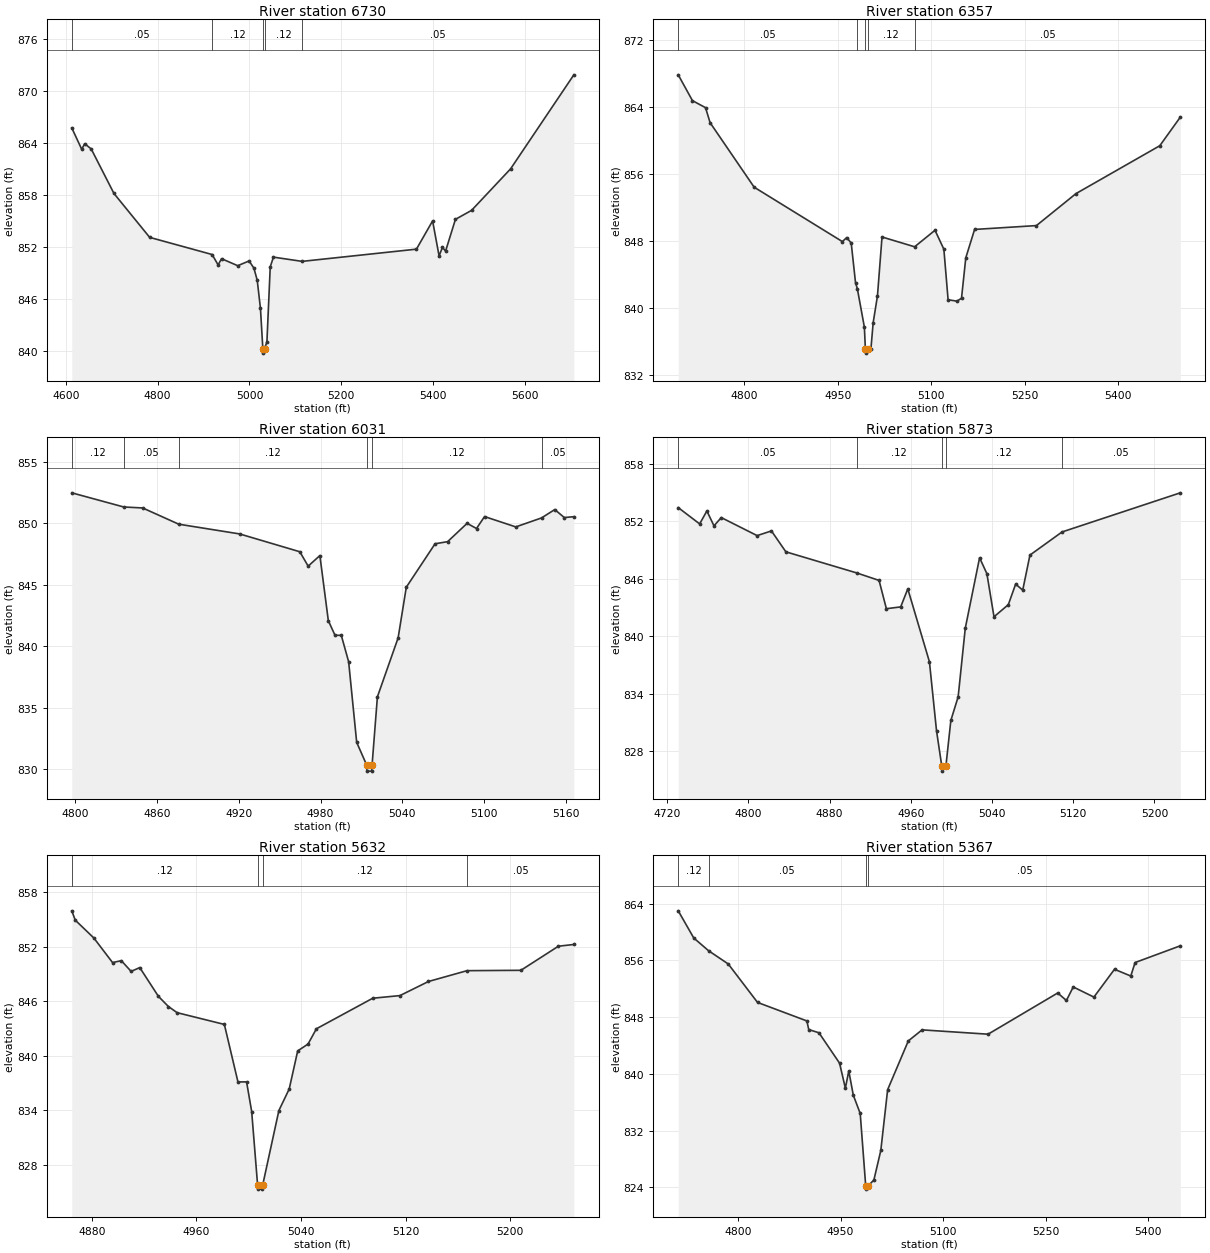
Type RM Length L Ch R = 1 ,6730    ,373,373,373
BEGIN DESCRIPTION:
UDS St 20 15.0
END DESCRIPTION:
XS GIS Cut Line= 3
      2263026.37      7179797.33        2263279.        7179510.
      2263790.95      7179017.34
#Sta/Elev= 30
  4613.1  865.75  4634.7  863.28  4641.3  863.92  4655.5  863.31  4704.9  858.18
  4782.7  853.11  4918.7  851.13  4931.7  849.93  4939.2  850.65  4974.4  849.84
  4999.2  850.39  5009.7  849.55  5016.9  848.15  5023.9  844.91  5029.1  840.25
  5029.3  839.75  5033.1  840.25    5038  841.08  5045.2  849.71  5052.2  850.83
  5114.6  850.34  5363.5  851.75  5398.7  855.01  5412.8  850.97  5420.1  851.95
    5427  851.53  5448.4  855.19  5483.6  856.23  5568.5  861.02  5706.2  871.87
#Mann= 5 ,-1 , 0
  4613.1     .05       0  4918.7     .12       0  5029.1     .07       0
  5033.1     .12       0  5114.6     .05       0
Bank Sta=5029.1,5033.1
XS Rating Curve= 0 ,0
Exp/Cntr=0.3,0.1

Type RM Length L Ch R = 1 ,6357    ,326,326,326
BEGIN DESCRIPTION:
UDS St 20 14.0
END DESCRIPTION:
XS GIS Cut Line= 3
      2263308.15      7179971.29        2263529.        7179760.
      2263869.53      7179394.22
#Sta/Elev= 30
  4694.1  867.86  4716.9  864.78  4737.9  863.94  4745.2  862.15  4815.9  854.45
  4957.4  847.96  4964.4  848.44  4971.6  847.78  4978.5  843.05  4981.4  842.34
  4992.7  837.75  4994.3  835.15  4994.5  834.65  4998.3  835.15  5003.2  835.15
  5006.8  838.28  5013.7  841.49    5021  848.51  5073.3  847.34    5106  849.31
  5120.2  847.05    5127  841.02  5141.2  840.85  5148.5   841.2  5155.4  846.03
  5169.5  849.41  5268.7  849.87  5332.2  853.69  5466.6   859.4  5499.5  862.81
#Mann= 5 ,-1 , 0
  4694.1     .05       0  4981.4     .12       0  4994.3     .07       0
  4998.3     .12       0  5073.3     .05       0
Bank Sta=4994.3,4998.3
XS Rating Curve= 0 ,0
Exp/Cntr=0.3,0.1

Type RM Length L Ch R = 1 ,6031    ,158,158,158
BEGIN DESCRIPTION:
UDS St 20 13.0
END DESCRIPTION:
XS GIS Cut Line= 3
      2263531.02      7180144.78      2263691.38      7180029.16
      2263834.87      7179936.88
#Sta/Elev= 30
  4797.5  852.47  4835.6  851.32  4849.5  851.24    4876  849.92  4920.6  849.13
  4964.8  847.68  4970.9  846.51  4979.5  847.37  4985.7  842.08  4990.6  840.89
  4995.2  840.89  5000.6  838.74  5006.5  832.19  5013.8  830.35    5014  829.85
  5017.5  829.85  5017.8  830.35  5021.7  835.89  5036.9  840.68  5042.9   844.8
    5064  848.33  5073.2   848.5  5087.5  849.99  5094.4  849.57  5100.3  850.54
  5123.2   849.7  5142.1  850.43  5151.8  851.11  5158.8  850.46  5165.8  850.53
#Mann= 6 ,-1 , 0
  4797.5     .12       0  4835.6     .05       0    4876     .12       0
  5013.8     .07       0  5017.8     .12       0  5142.1     .05       0
Bank Sta=5013.8,5017.8
XS Rating Curve= 0 ,0
Exp/Cntr=0.3,0.1

Type RM Length L Ch R = 1 ,5873    ,241,241,241
BEGIN DESCRIPTION:
UDS St 20 12.1
END DESCRIPTION:
XS GIS Cut Line= 2
       2263619.6      7180330.43      2263965.22      7179976.77
#Sta/Elev= 30
    4731  853.41  4752.1  851.71  4759.2  853.06  4766.2  851.51  4773.4  852.37
  4808.7  850.49  4822.8  850.98    4837   848.8  4906.8   846.6  4928.8  845.82
    4936  842.87  4950.1  843.06  4957.1  844.94  4978.4  837.34  4985.4  830.14
  4990.6  826.44  4990.8  825.94  4994.6  826.44  4999.5  831.22  5006.7  833.69
  5013.7  840.83  5027.8  848.18    5035  846.52    5042  842.03  5056.1  843.29
  5063.3  845.43  5070.3  844.81  5077.4  848.46    5109  850.87  5225.5  854.95
#Mann= 5 ,-1 , 0
    4731     .05       0  4906.8     .12       0  4990.6     .07       0
  4994.6     .12       0    5109     .05       0
Bank Sta=4990.6,4994.6
XS Rating Curve= 0 ,0
Exp/Cntr=0.3,0.1

Type RM Length L Ch R = 1 ,5632    ,265,265,265
BEGIN DESCRIPTION:
UDS St 20 12.0
END DESCRIPTION:
XS GIS Cut Line= 3
      2263793.67      7180458.66        2263879.        7180360.
      2264040.01      7180164.13
#Sta/Elev= 30
  4864.7  855.94  4867.4  854.91  4881.6  852.95  4895.9  850.25  4902.6  850.46
  4910.1  849.28  4916.7   849.7    4931  846.53  4938.6  845.42  4945.3  844.74
  4981.4  843.45  4991.8  837.13  4998.4  837.13  5002.3  833.87  5006.8  825.84
    5007  825.34  5010.5  825.34  5010.8  825.84  5023.1  833.98    5031  836.35
  5037.5  840.54  5045.4  841.29  5051.8  842.97  5094.9  846.33  5115.7  846.62
  5137.5  848.17    5167  849.36  5208.2   849.4  5236.9  852.05  5248.7  852.24
#Mann= 4 ,-1 , 0
  4864.7     .12       0  5006.8     .07       0  5010.8     .12       0
    5167     .05       0
Bank Sta=5006.8,5010.8
XS Rating Curve= 0 ,0
Exp/Cntr=0.3,0.1

Type RM Length L Ch R = 1 ,5367    ,61,61,61
BEGIN DESCRIPTION:
UDS St 20 11.2
END DESCRIPTION:
XS GIS Cut Line= 3
      2263928.18      7180679.62      2264088.67      7180572.85
      2264141.15      7180034.26
#Sta/Elev= 30
  4712.7     863  4735.4  859.17    4757  857.38  4785.8  855.51  4828.6  850.09
  4900.7  847.48  4903.5  846.26  4918.4  845.81  4948.5  841.53    4957     838
    4962  840.43  4968.6  837.01  4978.7  834.44  4986.7  824.27  4986.9  823.77
  4990.7  824.27  4998.7  825.06  5008.8  829.22  5018.8  837.79    5049  844.66
  5069.1  846.22  5165.6  845.61  5267.4  851.42  5280.1  850.36  5290.1  852.27
  5320.3  850.84  5350.4  854.76  5374.2  853.81  5380.5  855.71  5446.6  858.07
#Mann= 4 ,-1 , 0
  4712.7     .12       0    4757     .05       0  4986.7    .033       0
  4990.7     .05       0
Bank Sta=4986.7,4990.7
XS Rating Curve= 0 ,0
Exp/Cntr=0.3,0.1

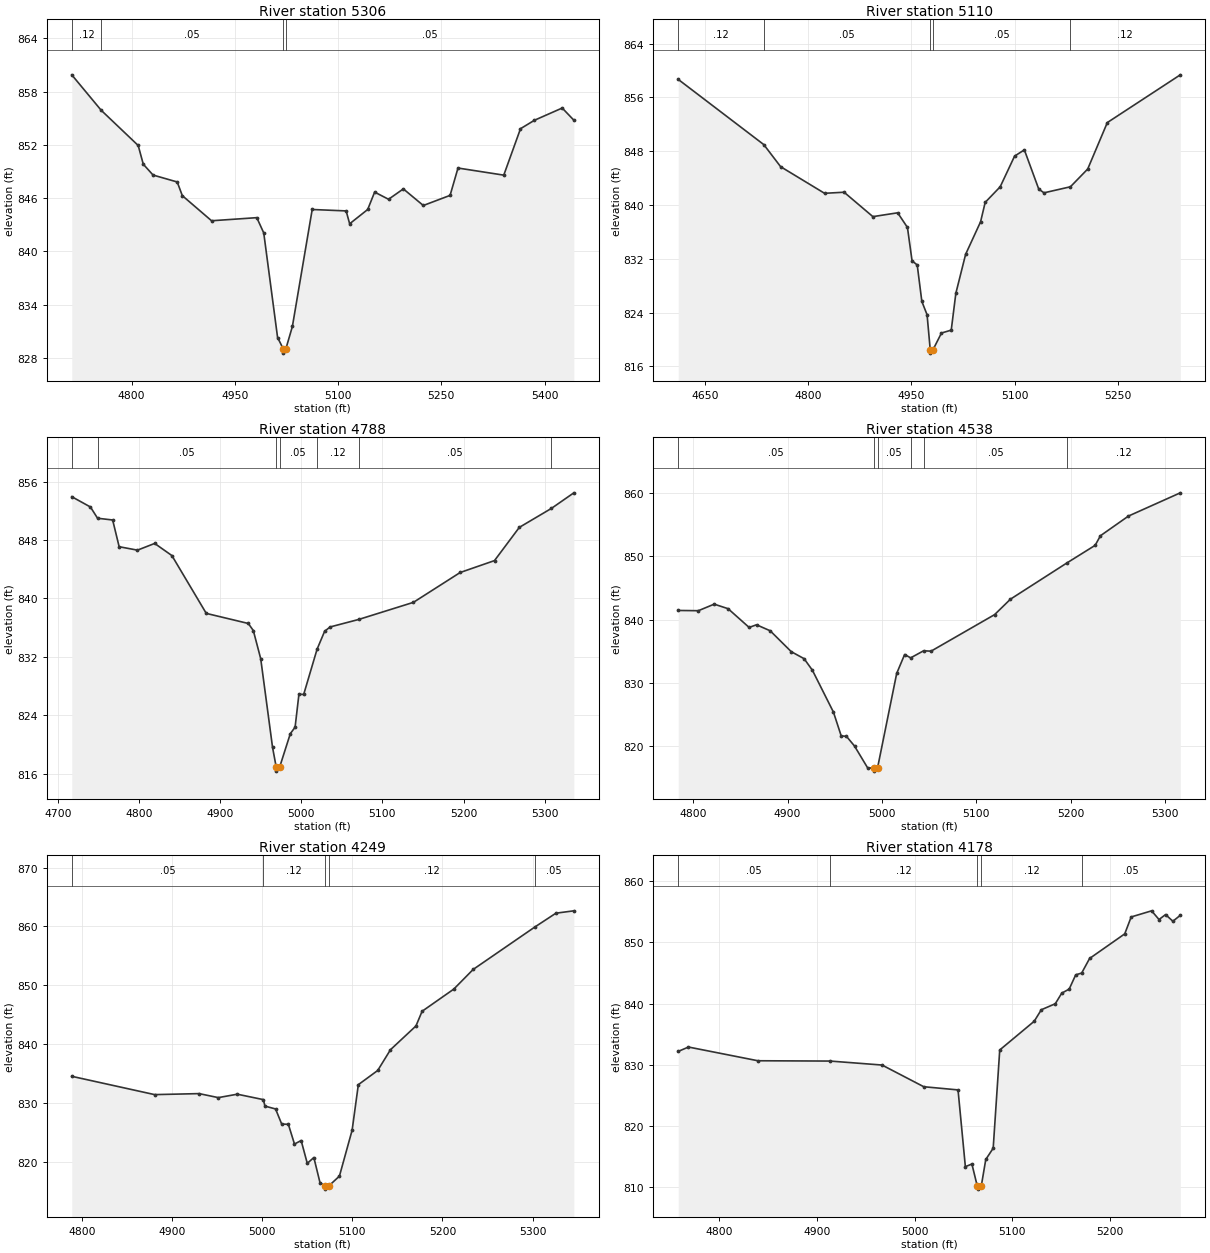
Type RM Length L Ch R = 1 ,5306    ,196,196,196
BEGIN DESCRIPTION:
UDS St 20 11.1
END DESCRIPTION:
XS GIS Cut Line= 4
      2263968.04      7180735.78      2264133.98        7180583.
      2264150.62       7180432.3      2264197.39       7180083.2
#Sta/Elev= 30
  4713.1   859.9  4755.8  855.91  4809.6  851.94    4817  849.83  4831.2  848.61
  4866.3  847.83  4873.7  846.29  4916.2  843.46  4981.9  843.81    4992  842.09
  5012.1  830.31  5020.2  829.05  5020.4  828.55  5024.2  829.05  5033.6  831.55
  5062.4  844.73  5111.7  844.57  5116.8  843.12    5143  844.73  5153.1  846.69
  5173.3  845.88  5194.8  847.05  5223.8  845.18  5262.7  846.32  5274.2   849.4
  5340.7   848.6    5365  853.83  5385.2  854.78  5425.6  856.16  5442.5  854.79
#Mann= 4 ,-1 , 0
  4713.1     .12       0  4755.8     .05       0  5020.2    .033       0
  5024.2     .05       0
Bank Sta=5020.2,5024.2
XS Rating Curve= 0 ,0
Exp/Cntr=0.3,0.1

Type RM Length L Ch R = 1 ,5110    ,322,322,322
BEGIN DESCRIPTION:
UDS St 20 11.0
END DESCRIPTION:
XS GIS Cut Line= 2
       2264010.8      7180941.39       2264493.9      7180395.17
#Sta/Elev= 30
  4611.4  858.67  4735.7  848.97  4760.1  845.69  4823.9  841.73  4852.3  841.89
  4894.1  838.26  4930.1  838.83  4944.3  836.65    4951  831.69  4958.5  831.07
  4965.2  825.65  4972.8  823.67  4977.4  818.46  4977.7  817.96  4981.4  818.46
  4993.7  820.95  5007.9  821.38  5014.6  826.86  5028.8  832.66  5050.5  837.49
  5057.2  840.38    5079   842.7  5099.9  847.26  5114.1  848.19    5135  842.36
  5142.6   841.8    5181   842.7  5206.1  845.34  5234.6  852.25  5340.6  859.35
#Mann= 5 ,-1 , 0
  4611.4     .12       0  4735.7     .05       0  4977.4    .033       0
  4981.4     .05       0    5181     .12       0
Bank Sta=4977.4,4981.4
XS Rating Curve= 0 ,0
Exp/Cntr=0.3,0.1

Type RM Length L Ch R = 1 ,4788    ,250,250,250
BEGIN DESCRIPTION:
UDS St 20 10.0
END DESCRIPTION:
XS GIS Cut Line= 3
      2264228.28      7181149.44        2264379.        7180910.
       2264558.6      7180626.06
#Sta/Elev= 30
  4717.1  853.93  4740.1  852.52  4748.9  850.98  4767.5  850.74  4775.5  847.08
  4798.1  846.61  4819.3  847.53  4840.5  845.87  4882.9  837.95  4934.7  836.57
  4940.9   835.6    4950  831.75  4964.6   819.6  4969.2  816.85  4969.4  816.35
  4973.2  816.85  4986.5  821.48  4992.4  822.37  4997.1  826.86    5003  826.86
  5019.5  833.05  5028.8   835.5  5035.5  836.09  5070.8  837.12  5138.2  839.46
  5195.9  843.55  5238.2  845.18  5268.8  849.73  5308.4  852.33    5336  854.46
#Mann= 7 ,-1 , 0
  4717.1     .12       0  4748.9     .05       0  4969.2    .033       0
  4973.2     .05       0  5019.5     .12       0  5070.8     .05       0
  5308.4     .12       0
Bank Sta=4969.2,4973.2
XS Rating Curve= 0 ,0
Exp/Cntr=0.3,0.1

Type RM Length L Ch R = 1 ,4538    ,289,289,289
BEGIN DESCRIPTION:
UDS St 20 9.1
END DESCRIPTION:
XS GIS Cut Line= 2
      2264496.15      7181217.27      2264732.43      7180740.85
#Sta/Elev= 30
  4784.2  841.44  4805.5   841.4  4822.3  842.44    4837  841.72  4859.3  838.75
  4867.1  839.17  4881.6  838.22  4903.9  834.91  4917.5   833.8  4926.3  831.97
  4948.6  825.33  4956.8  821.57  4962.4  821.49  4970.9  819.96  4984.8   816.5
  4991.2  816.48  4991.5  815.98  4995.3  816.48  5015.6  831.47    5024  834.46
  5030.4  833.93  5044.1  835.05    5052  834.99  5119.3  840.78  5136.1  843.23
  5196.1  848.99  5225.8  851.76  5231.4  853.28  5261.1   856.4    5316  860.08
#Mann= 6 ,-1 , 0
  4784.2     .05       0  4991.2    .033       0  4995.3     .05       0
  5030.4     .12       0  5044.1     .05       0  5196.1     .12       0
Bank Sta=4991.2,4995.3
XS Rating Curve= 0 ,0
Exp/Cntr=0.3,0.1

Type RM Length L Ch R = 1 ,4249    ,71,71,71
BEGIN DESCRIPTION:
UDS St 20 9.0
END DESCRIPTION:
XS GIS Cut Line= 3
       2264651.6      7181332.54      2264807.35      7181182.49
      2265057.59       7180950.5
#Sta/Elev= 30
  4788.4  834.53  4880.4  831.42  4929.8  831.59  4951.1  830.91  4972.2  831.49
  5001.1  830.57  5002.9  829.47  5014.7  828.98  5021.5  826.42  5028.9  826.37
  5035.7  823.02  5043.1  823.62  5049.9  819.74  5057.2  820.73    5064  816.48
  5069.4  815.86  5069.7  815.36  5073.5  815.86  5085.6  817.57  5099.7  825.37
  5106.6  833.11  5128.1  835.52  5142.3  839.05  5170.6  843.09  5177.4  845.58
  5212.6  849.35  5234.1  852.69  5302.5  859.89    5326  862.25  5345.9  862.65
#Mann= 5 ,-1 , 0
  4788.4     .05       0  5001.1     .12       0  5069.4    .033       0
  5073.5     .12       0  5302.5     .05       0
Bank Sta=5069.4,5073.5
XS Rating Curve= 0 ,0
Exp/Cntr=0.3,0.1

Type RM Length L Ch R = 1 ,4178    ,469,469,469
BEGIN DESCRIPTION:
UDS St 20 8.1
END DESCRIPTION:
XS GIS Cut Line= 2
      2264686.06      7181371.87      2265071.02      7181031.14
#Sta/Elev= 30
  4757.8  832.21  4768.3  832.92  4839.4  830.68  4913.4  830.63  4966.5  829.98
  5009.2  826.44  5044.3  825.92  5051.8  813.39  5058.5  813.82    5064  810.22
  5064.3  809.72  5068.1  810.22  5072.7  814.56  5080.3   816.4    5087  832.44
  5122.3  837.13  5129.6  839.01  5143.9  839.99  5150.5  841.72  5158.1  842.38
  5164.8  844.71  5170.9     845    5179  847.38    5215   851.4  5221.6  854.16
  5242.5  855.16  5250.1  853.74  5256.8  854.55  5264.3  853.46  5271.9  854.43
#Mann= 5 ,-1 , 0
  4757.8     .05       0  4913.4     .12       0    5064     .07       0
  5068.1     .12       0  5170.9     .05       0
Bank Sta=5064,5068.1
XS Rating Curve= 0 ,0
Exp/Cntr=0.3,0.1

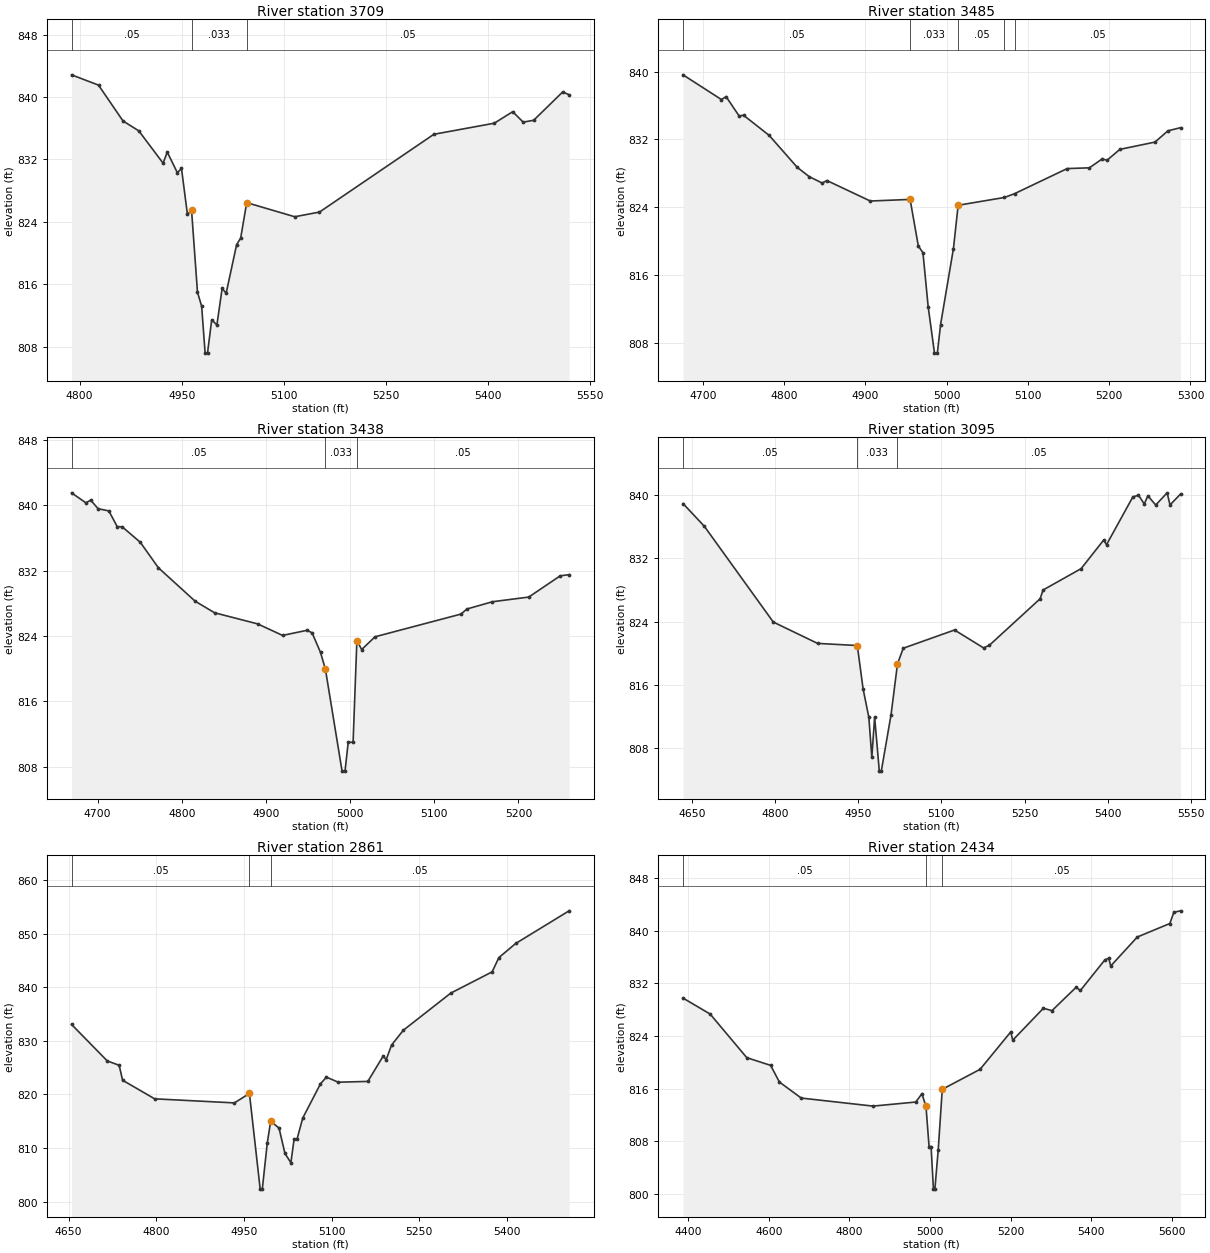
Type RM Length L Ch R = 1 ,3709    ,224,224,224
BEGIN DESCRIPTION:
UDS St 20 8.0
END DESCRIPTION:
XS GIS Cut Line= 3
      2264607.27      7181724.79      2264781.68      7181601.73
      2265221.88      7181329.95
#Sta/Elev= 30
  4788.2  842.86  4827.8  841.54  4863.8  836.94    4887  835.67  4922.7  831.52
  4928.8  832.95  4943.6   830.3  4949.7  830.85  4958.4  824.96  4964.5  825.46
  4973.2  814.95  4979.3  813.18  4984.4  807.15  4987.9  807.15  4994.1  811.43
  5001.7  810.76  5009.4  815.45  5015.3  814.84  5030.7  821.08  5036.6   821.9
  5045.5  826.46    5116  824.65  5152.4  825.25  5320.4  835.23  5409.1  836.65
  5436.2  838.13  5451.6  836.79    5467  837.03  5509.6  840.66    5519  840.31
#Mann= 3 , 0 , 0
  4788.2     .05       0  4964.5    .033       0  5045.5     .05       0
Bank Sta=4964.5,5045.5
XS Rating Curve= 0 ,0
Exp/Cntr=0.3,0.1

Type RM Length L Ch R = 1 ,3485    ,47,47,47
BEGIN DESCRIPTION:
UDS St 20 7.1
END DESCRIPTION:
XS GIS Cut Line= 2
      2264798.44       7181992.2      2265100.81        7181460.
#Sta/Elev= 30
  4675.7  839.61    4723  836.69  4728.7  837.04  4744.6  834.77  4750.3  834.83
  4781.7  832.46  4816.2  828.69  4831.1  827.58    4847  826.83  4852.7  827.13
  4906.1  824.71  4955.1   824.9  4965.2   819.4  4970.9  818.61  4977.3  812.25
  4985.1  806.75  4988.6  806.75  4992.6  810.13  5008.4  819.09  5014.2  824.21
  5071.2  825.13  5083.9  825.59  5148.3  828.54  5175.7  828.63  5191.5  829.69
  5197.3  829.52  5213.2  830.81  5256.4  831.67  5272.3     833  5287.8  833.37
#Mann= 5 ,-1 , 0
  4675.7     .05       0  4955.1    .033       0  5014.2     .05       0
  5071.2     .12       0  5083.9     .05       0
Bank Sta=4955.1,5014.2
XS Rating Curve= 0 ,0
Exp/Cntr=0.3,0.1

Type RM Length L Ch R = 1 ,3438    ,343,343,343
BEGIN DESCRIPTION:
UDS St 20 7.0
END DESCRIPTION:
XS GIS Cut Line= 3
      2264834.12      7182017.28      2264999.53      7181729.71
      2265128.55      7181504.73
#Sta/Elev= 30
    4669  841.52    4686   840.3  4691.8  840.62  4700.5  839.58  4713.3  839.31
  4723.3  837.38  4729.1  837.37  4750.7  835.47  4772.2  832.35  4815.8  828.27
  4838.9  826.85  4890.1  825.49  4919.7  824.08    4949  824.71  4954.8  824.39
  4964.8     822  4970.6  819.95  4990.4  807.48  4993.9  807.48  4997.7  811.01
  5003.5  811.01    5008  823.45  5013.7  822.35  5029.5  823.91  5131.7  826.69
  5138.7  827.31  5169.1   828.2  5212.2  828.77  5249.6  831.37  5260.1  831.51
#Mann= 3 , 0 , 0
    4669     .05       0  4970.6    .033       0    5008     .05       0
#XS Ineff= 2 , 0
       0                    5008       0  823.45
Permanent Ineff=
       F       F
Bank Sta=4970.6,5008
XS Rating Curve= 0 ,0
Exp/Cntr=0.3,0.1

Type RM Length L Ch R = 1 ,3095    ,234,234,234
BEGIN DESCRIPTION:
UDS St 20 6.0
END DESCRIPTION:
XS GIS Cut Line= 3
      2265220.57       7182217.5      2265283.22      7181924.54
      2265438.96      7181346.75
#Sta/Elev= 30
  4633.6  838.89    4672  836.03  4796.6  823.94  4876.5  821.25  4948.2  820.98
  4958.6  815.53    4969  811.93  4974.4   806.9  4979.5  811.94  4987.9  805.14
  4991.5  805.14  5009.1  812.25  5020.7  818.65  5031.1  820.64  5123.7  822.94
  5176.1  820.68  5186.5  821.01  5278.2  826.88  5283.4  827.98  5352.2  830.68
  5392.8  834.28    5398   833.7  5445.4  839.71  5455.7  839.95  5466.1  838.84
  5472.7  839.86  5486.8   838.7  5507.4  840.24  5512.6  838.71  5531.6  840.09
#Mann= 3 , 0 , 0
  4633.6     .05       0  4948.2    .033       0  5020.7     .05       0
Bank Sta=4948.2,5020.7
XS Rating Curve= 0 ,0
Exp/Cntr=0.3,0.1

Type RM Length L Ch R = 1 ,2861    ,427,427,427
BEGIN DESCRIPTION:
UDS St 20 5.1
END DESCRIPTION:
XS GIS Cut Line= 3
      2265480.08      7182200.36      2265540.23      7181824.32
      2265613.19      7181360.04
#Sta/Elev= 30
  4655.2  833.04  4716.3  826.23  4736.6  825.42  4742.5  822.63  4797.3  819.16
  4933.7   818.4  4959.4  820.16  4977.8  802.31  4981.4  802.31  4989.8  810.83
  4995.7  814.97    5010   813.7  5020.1  808.98  5030.3  807.23  5035.7  811.59
  5040.7  811.59  5050.5  815.56  5080.9  821.96    5091  823.21  5111.3  822.26
  5161.9  822.41  5188.2  827.16  5193.2  826.45  5202.4  829.19  5222.6  831.96
  5303.6  838.88  5374.4  842.85    5386  845.52  5414.9  848.16    5506  854.24
#Mann= 3 , 0 , 0
  4655.2     .05       0  4959.4    .033       0  4995.7     .05       0
#XS Ineff= 2 , 0
       0                  4995.7       0  814.97
Permanent Ineff=
       F       F
Bank Sta=4959.4,4995.7
XS Rating Curve= 0 ,0
Exp/Cntr=0.3,0.1

Type RM Length L Ch R = 1 ,2434    ,473,473,473
BEGIN DESCRIPTION:
UDS St 20 5.0
END DESCRIPTION:
XS GIS Cut Line= 3
      2265843.02      7182466.65        2265929.        7181860.
      2266005.31      7181243.62
#Sta/Elev= 30
  4387.2  829.75  4454.5  827.32  4545.4  820.69  4604.5  819.52  4626.2  816.99
  4680.5  814.55  4858.5  813.33  4964.4  813.95  4979.7  815.21  4989.8  813.27
  4997.4  807.17  5002.4  807.17  5008.2  800.71  5011.8  800.71  5020.1  806.67
  5030.1  815.88  5123.9  818.92  5199.9   824.6  5204.9  823.35  5280.9   828.2
  5302.2  827.84  5361.9  831.38  5372.7  830.91  5433.2  835.54  5442.9  835.81
  5447.9  834.63  5513.8  839.03  5594.4  841.08  5604.5  842.79    5621  843.01
#Mann= 3 , 0 , 0
  4387.2     .05       0  4989.8    .033       0  5030.1     .05       0
Bank Sta=4989.8,5030.1
XS Rating Curve= 0 ,0
Exp/Cntr=0.3,0.1

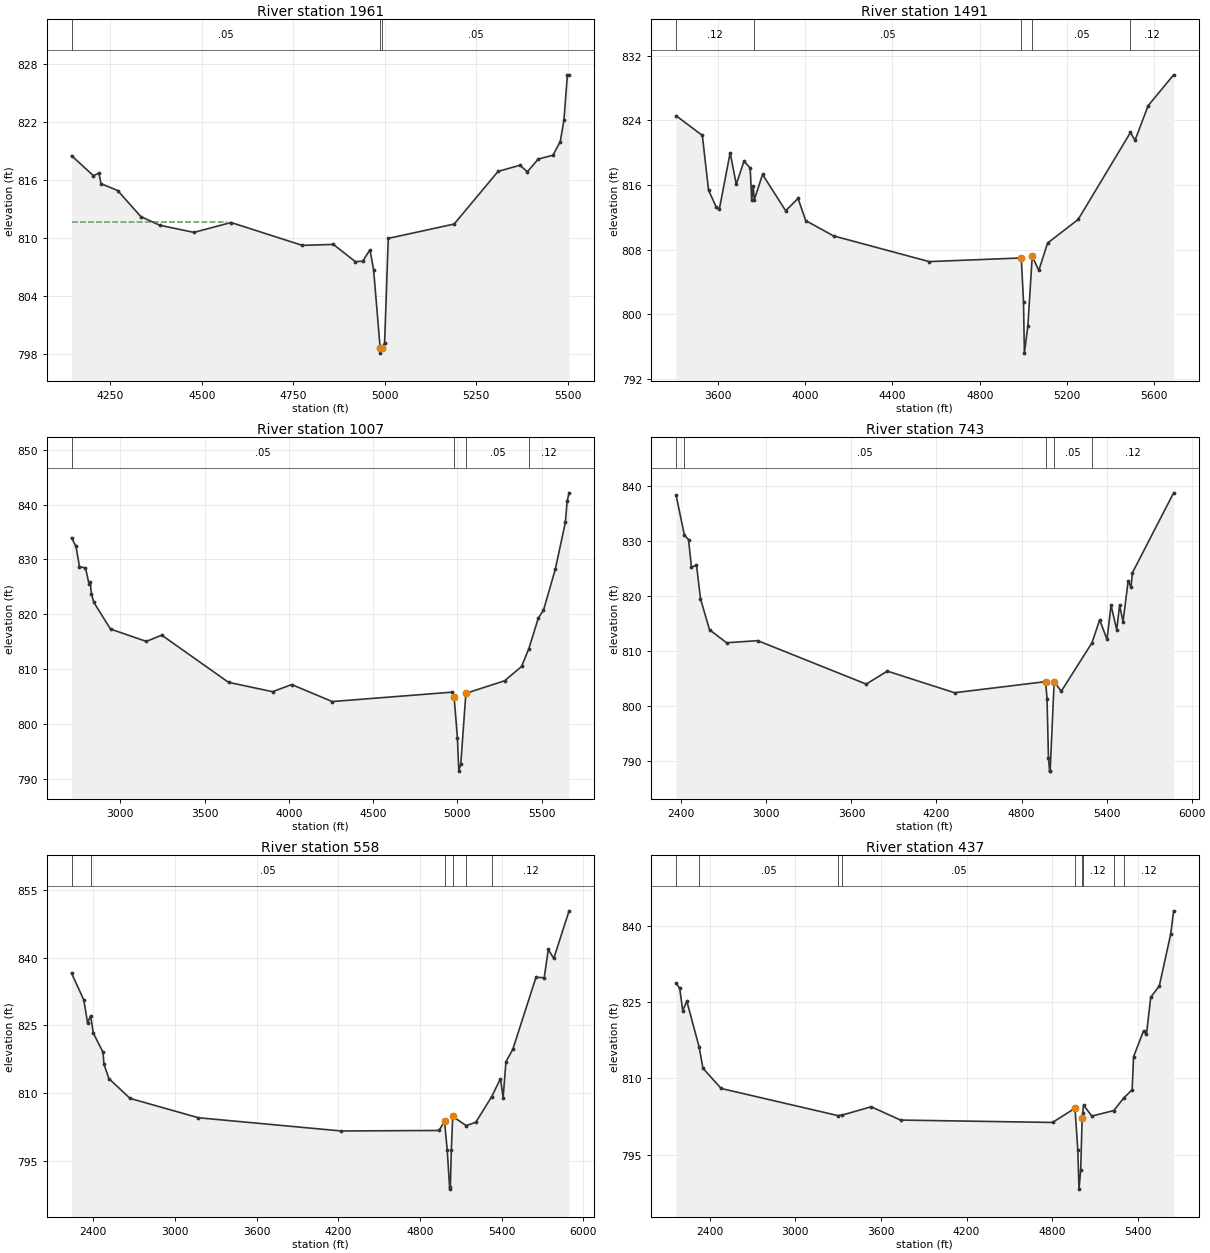
Type RM Length L Ch R = 1 ,1961    ,470,470,470
BEGIN DESCRIPTION:
UDS St 20 4.0
END DESCRIPTION:
XS GIS Cut Line= 3
      2266002.49      7182506.19      2266373.94      7181931.33
      2266356.97      7181255.87
#Sta/Elev= 30
  4143.8   818.5  4203.3  816.44  4218.5  816.68  4224.4  815.61  4269.9   814.9
  4333.3  812.21  4384.7  811.32  4478.4  810.58  4579.8   811.6  4774.6  809.24
  4859.6  809.34  4919.6  807.56  4939.6  807.61  4959.6  808.78  4969.6  806.71
  4987.5  798.62  4987.8  798.12  4991.8  798.62  4999.6  799.18  5009.6  809.96
  5189.7  811.44  5309.7  816.87  5369.7  817.51  5389.7  816.83  5419.7  818.15
  5459.8  818.54  5479.8  819.95  5489.8  822.15  5499.3  826.84  5503.9  826.84
#Mann= 3 ,-1 , 0
  4143.8     .05       0  4987.5    .033       0  4991.8     .05       0
#XS Ineff= 2 , 0
       0  4566.2  811.62               0
Permanent Ineff=
       F       F
Bank Sta=4987.5,4991.8
XS Rating Curve= 0 ,0
Exp/Cntr=0.3,0.1

Type RM Length L Ch R = 1 ,1491    ,484,484,484
BEGIN DESCRIPTION:
UDS St 20 3.0
END DESCRIPTION:
XS GIS Cut Line= 3
        2265829.        7182910.       2266813.3      7181869.61
      2266867.57      7181023.37
#Sta/Elev= 30
  3408.2  824.57  3528.5  822.14  3556.9  815.37  3592.1  813.28  3606.2  812.98
    3656     820  3683.9  816.09  3719.5  818.95  3747.8   818.1  3754.7  814.15
    3762  815.83  3766.3  814.16  3804.4  817.31  3910.4  812.82  3967.1  814.34
  4002.3   811.6  4129.7  809.71  4568.2  806.53  4990.3  806.98  5000.4  801.59
  5004.5  795.21  5020.4  798.58  5040.4   807.2  5070.5  805.43  5110.6  808.82
  5250.9  811.74  5490.7  822.51  5511.4  821.53  5571.5  825.81  5688.4  829.63
#Mann= 5 ,-1 , 0
  3408.2     .12       0  3766.3     .05       0  4990.3    .033       0
  5040.4     .05       0  5490.7     .12       0
Bank Sta=4990.3,5040.4
XS Rating Curve= 0 ,0
Exp/Cntr=0.3,0.1

Type RM Length L Ch R = 1 ,1007    ,264,264,264
BEGIN DESCRIPTION:
UDS St 20 2.0
END DESCRIPTION:
XS GIS Cut Line= 3
      2265815.54      7183423.49      2267266.86      7181884.92
      2267309.58      7181048.28
#Sta/Elev= 30
  2710.2  833.97  2736.4  832.41  2757.4  828.68    2793  828.46    2814  825.53
  2821.3   825.8  2828.2  823.75  2842.4  822.17  2941.5  817.29  3153.9  815.04
  3245.7  816.18  3641.8  807.57  3903.5  805.86  4016.8  807.16  4257.1  804.06
  4970.4  805.78  4980.4  804.94  5000.4  797.42  5008.5  791.36  5020.4  792.71
  5050.5  805.56  5280.8  807.86  5380.9  810.46  5424.4  813.73    5481  819.35
  5511.1  820.72  5581.2  828.21  5641.2  836.81  5651.3  840.62    5663  842.16
#Mann= 4 ,-1 , 0
  2710.2     .05       0  4980.4    .033       0  5050.5     .05       0
  5424.4     .12       0
Bank Sta=4980.4,5050.5
XS Rating Curve= 0 ,0
Exp/Cntr=0.3,0.1

Type RM Length L Ch R = 1 ,743     ,185,185,185
BEGIN DESCRIPTION:
UDS St 20 1.0
END DESCRIPTION:
XS GIS Cut Line= 3
      2265891.17      7183725.51      2267524.01      7181888.54
       2267614.9      7180840.24
#Sta/Elev= 30
  2362.9   838.3  2421.6  831.02  2450.6  830.24  2471.6  825.15  2506.7  825.64
  2535.1  819.46  2598.7  813.83  2719.1  811.46    2939  811.84  3704.2  803.94
    3853   806.3  4327.1  802.37  4969.8  804.39  4979.8  801.31  4989.8  790.56
  4997.9  788.11  5001.8  788.11    5030  804.39  5080.2  802.64  5296.6  811.44
  5351.2  815.62  5402.9  812.09  5431.5  818.27  5471.6  813.82  5491.7  818.28
    5516  815.29  5551.9  822.66    5572  821.59  5582.1  824.19  5872.9  838.73
#Mann= 5 ,-1 , 0
  2362.9     .12       0  2421.6     .05       0  4969.8    .033       0
    5030     .05       0  5296.6     .12       0
Bank Sta=4969.8,5030
XS Rating Curve= 0 ,0
Exp/Cntr=0.3,0.1

Type RM Length L Ch R = 1 ,558     ,121,121,121
BEGIN DESCRIPTION:
UDS St 20 1.15
END DESCRIPTION:
XS GIS Cut Line= 3
      2265970.39      7183868.21      2267694.61      7181916.11
      2267785.51      7180867.78
#Sta/Elev= 30
  2239.1  836.59  2329.3  830.64  2356.9  825.57  2379.1  827.14  2399.5  823.27
  2470.7  819.04  2477.3  816.42  2513.3  813.23  2668.9  808.83  3171.7  804.54
  4220.7  801.61  4940.1  801.72  4980.3  803.76  5000.3  797.44  5018.5  788.72
  5023.2  789.22  5030.4  797.35  5040.5  804.82  5140.6  802.79  5211.1  803.57
  5327.3  809.23  5391.8  813.21  5411.1  808.95  5431.9  816.96  5482.1  819.68
  5652.8  835.69    5713  835.56  5743.1  841.83  5783.3  839.85  5895.9   850.4
#Mann= 6 ,-1 , 0
  2239.1     .12       0  2379.1     .05       0  4980.3    .033       0
  5040.5     .12       0  5140.6     .05       0  5327.3     .12       0
Bank Sta=4980.3,5040.5
XS Rating Curve= 0 ,0
Exp/Cntr=0.3,0.1

Type RM Length L Ch R = 1 ,437     ,0,0,0
BEGIN DESCRIPTION:
UDS St 20 0.9
END DESCRIPTION:
XS GIS Cut Line= 3
      2266115.47      7183982.09      2267819.76      7181922.31
      2267867.38      7181109.75
#Sta/Elev= 30
    2164  828.72  2189.6  827.65  2210.5  823.29  2239.1  825.16  2324.6  816.24
  2352.4  811.98  2480.1  808.01  3298.1  802.69  3329.7   802.8  3531.2  804.42
  3737.2  801.81  4802.5  801.34    4960  804.14    4980  795.84  4988.1  788.25
    5000  791.98  5010.1  802.14  5014.1  803.19  5020.1  804.76    5078  802.59
    5232  803.68  5300.9  806.12  5360.7  807.76  5370.7  814.26  5440.8  819.34
  5460.8  818.61  5490.9  825.92    5551  828.13  5631.1  838.36  5651.4  842.89
#Mann= 9 ,-1 , 0
    2164     .12       0  2324.6     .05       0  3298.1     .12       0
  3329.7     .05       0    4960    .033       0  5010.1     .05       0
  5014.1     .12       0    5232     .05       0  5300.9     .12       0
Bank Sta=4960,5010.1
XS Rating Curve= 0 ,0
Exp/Cntr=0.3,0.1

Chan Stop Cuts=-1
Use User Specified Reach Order=0
Composite Channel Slope=5