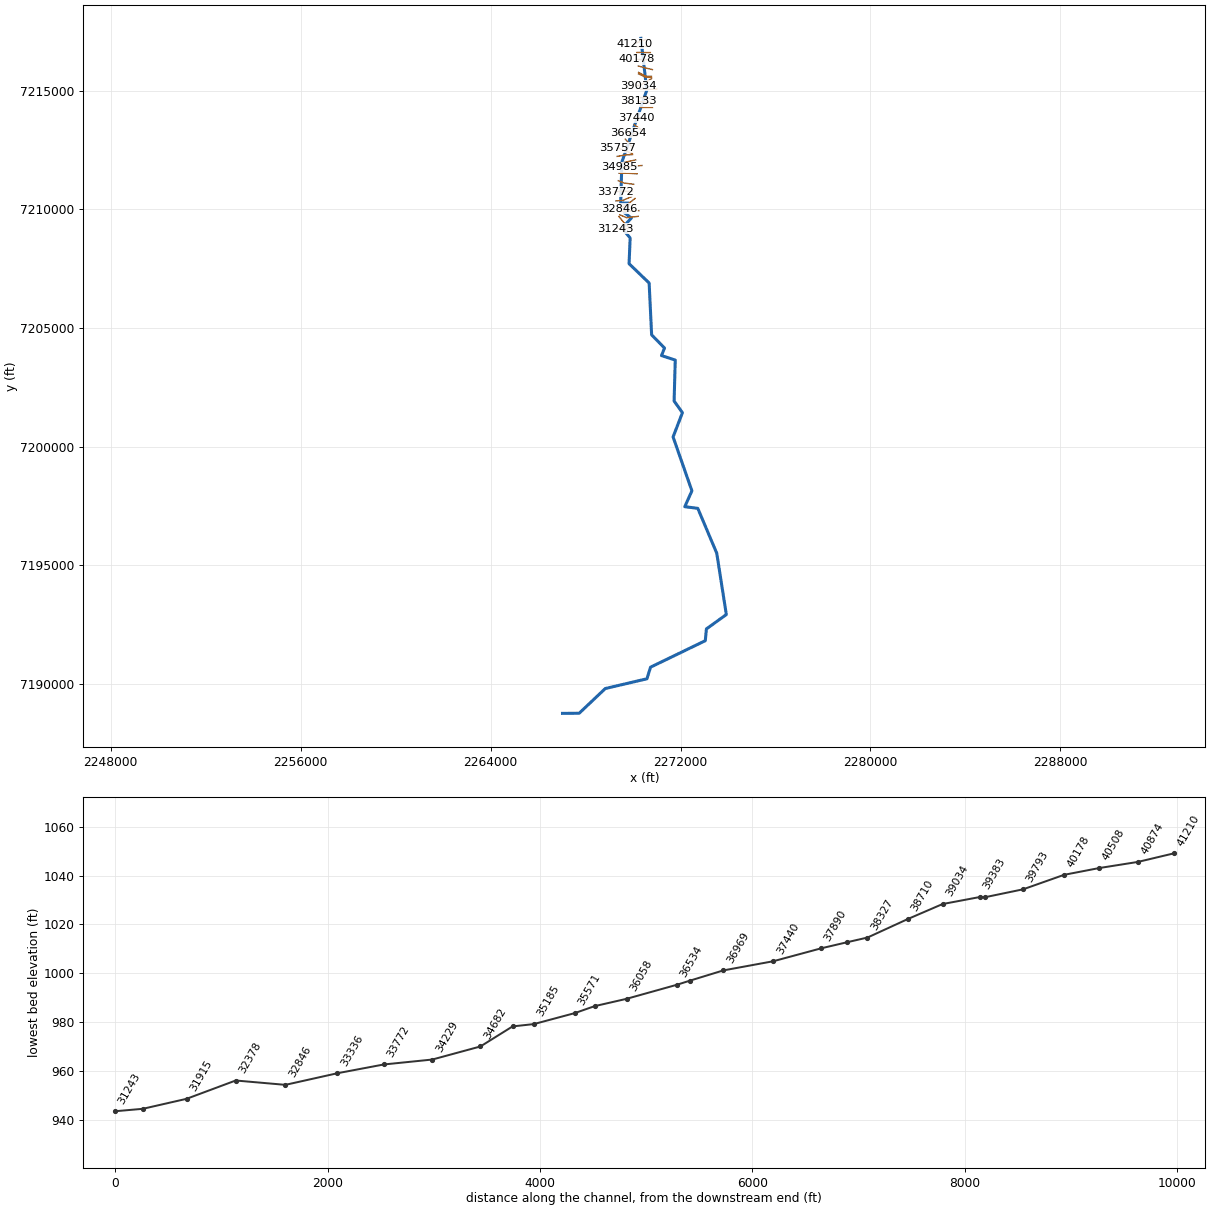
--- UDS St 21.prj (project) ---

Proj Title=UDS St 21 Base Level Engineering
Current Plan=p01
Default Exp/Contr=0.3,0.1
English Units
Geom File=g01
Flow File=f01
Plan File=p01
Y Axis Title=Elevation
X Axis Title(PF)=Main Channel Distance
X Axis Title(XS)=Station
BEGIN DESCRIPTION:
UDS St 21
END DESCRIPTION:
DSS Export Rating Curves= 0
DSS Export Rating Curve Sorted= 0
DSS Export Volume Flow Curves= 0
DXF OffsetX= 0
DXF OffsetY= 0
DXF ScaleX= 1
DXF ScaleY= 10

--- UDS St 21.p01 (plan) ---

Plan Title=Multiple Run
Short Identifier=Multiple
Geom File=g01
Flow File=f01
Subcritical Flow
K Sum by GR= 0
Std Step Tol= 0.01
Critical Tol= 0.01
Num of Std Step Trials= 20
Max Error Tol= 0.3
Flow Tol Ratio= 0.001
Split Flow NTrial= 30
Split Flow Tol= 0.02
Split Flow Ratio= 0.02
Log Output Level= 0
Friction Slope Method= 1
Unsteady Friction Slope Method= 2
Unsteady Bridges Friction Slope Method= 1
Parabolic Critical Depth
Global Vel Dist=  1 , 1 , 1
Global Log Level= 0
CheckData=True
Encroach Param= -1, 0, 0, 0
BEGIN DESCRIPTION:
Multiple Run
END DESCRIPTION:

--- UDS St 21.f01 (steady flow) ---

Flow Title=Multiple
Program Version=4.10
Number of Profiles= 7
Profile Names=10-year,25-year,50-year,1pct_min,100-year,1pct_plu,500-year
River Rch & RM=UDS St 21,Reach-1         ,41210
     442     598     726     439     875    1746    1272
River Rch & RM=UDS St 21,Reach-1         ,38710
     810    1140    1420     878    1751    3493    2672
River Rch & RM=UDS St 21,Reach-1         ,35185
    1260    1810    2285    1429    2852    5690    4458
River Rch & RM=UDS St 21,Reach-1         ,31083
    1410    2040    2586    1625    3242    6468    5112
River Rch & RM=UDS St 21,Reach-1         ,26731
    1636    2370    3008    1890    3770    7522    5945
River Rch & RM=UDS St 21,Reach-1         ,20102
    2165    3168    4048    2558    5103   10182    8142
River Rch & RM=UDS St 21,Reach-1         ,16595
    2224    3261    4173    2641    5269   10514    8431
River Rch & RM=UDS St 21,Reach-1         ,13709
    2424    3561    4564    2891    5768   11509    9248
River Rch & RM=UDS St 21,Reach-1         ,9004
    2661    3908    5008    3171    6327   12624   10134
River Rch & RM=UDS St 21,Reach-1         ,4291
    2692    3964    5087    3225    6435   12840   10337
Boundary for River Rch & Prof#=UDS St 21,Reach-1         , 1
Up Type= 0
Dn Type= 3
Dn Slope=0.004
Boundary for River Rch & Prof#=UDS St 21,Reach-1         , 2
Up Type= 0
Dn Type= 3
Dn Slope=0.004
Boundary for River Rch & Prof#=UDS St 21,Reach-1         , 3
Up Type= 0
Dn Type= 3
Dn Slope=0.004
Boundary for River Rch & Prof#=UDS St 21,Reach-1         , 4
Up Type= 0
Dn Type= 3
Dn Slope=0.004
Boundary for River Rch & Prof#=UDS St 21,Reach-1         , 5
Up Type= 0
Dn Type= 3
Dn Slope=0.004
Boundary for River Rch & Prof#=UDS St 21,Reach-1         , 6
Up Type= 0
Dn Type= 3
Dn Slope=0.004
Boundary for River Rch & Prof#=UDS St 21,Reach-1         , 7
Up Type= 0
Dn Type= 3
Dn Slope=0.004
DSS Import GetInterval= 0
DSS Import GetPeak= 0
DSS Import FillOption= 0

--- UDS St 21.g01 (geometry) ---

Geom Title=Existing Conditions
Program Version=4.10

River Reach=UDS St 21       ,Reach-1
Reach XY= 30
        2270329.        7217210.      2270578.48      7215025.22
       2269530.1      7212000.36      2269479.77      7210274.35
      2269821.28       7210266.5      2269637.02      7209856.65
      2269929.57      7209637.21      2269536.49      7209210.03
      2269878.25      7208795.24      2269832.16       7207712.1
      2270677.52      7206898.52      2270782.75      7204711.55
      2271325.34      7204158.45      2271198.21      7203839.43
      2271777.15      7203649.56       2271729.4      7201923.91
      2272079.32      7201432.25      2271686.29      7200409.91
      2272478.93      7198139.97      2272179.53      7197470.69
      2272726.51      7197401.85      2273525.52      7195508.74
      2273928.47      7192923.86      2273089.48       7192319.8
      2273042.75       7191823.2      2270737.01      7190706.97
      2270585.39        7190218.      2268830.46      7189806.46
      2267731.43      7188765.52        2267029.        7188760.

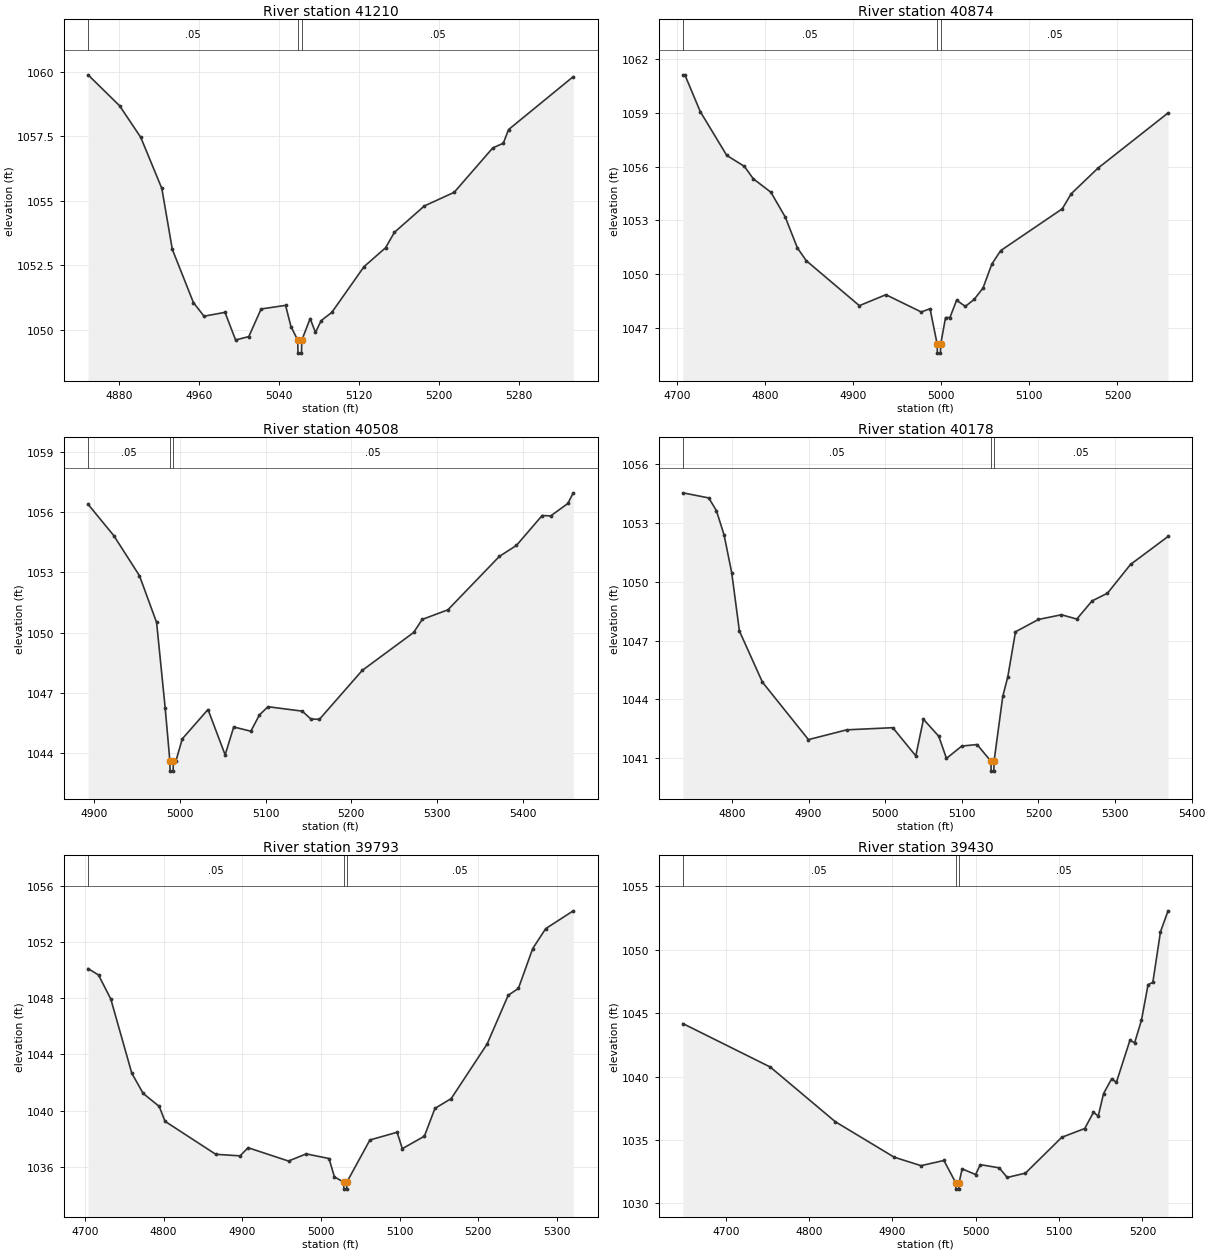
Type RM Length L Ch R = 1 ,41210   ,336,336,336
BEGIN DESCRIPTION:
UDS St 21 89.0
END DESCRIPTION:
XS GIS Cut Line= 3
      2270529.01        7217160.        2270379.        7217110.
      2270073.93      7216991.52
#Sta/Elev= 30
  4849.1 1059.88  4880.7 1058.68  4901.8 1057.46  4922.9 1055.48  4933.4 1053.12
  4954.5 1051.06  4965.1 1050.53  4986.1 1050.68  4996.7 1049.61  5009.9 1049.74
  5022.2 1050.81  5046.7 1050.95  5052.1 1050.13  5058.9  1049.6  5059.1  1049.1
  5062.6  1049.1  5062.9  1049.6  5071.3 1050.44  5076.6  1049.9  5082.3 1050.36
    5093 1050.68  5125.2 1052.45  5146.7 1053.18  5155.6 1053.78  5185.5  1054.8
  5215.4 1055.33    5254 1057.05  5264.5 1057.23  5269.8 1057.76  5334.5 1059.81
#Mann= 3 ,-1 , 0
  4849.1     .05       0  5058.9    .033       0  5062.9     .05       0
Bank Sta=5058.9,5062.9
XS Rating Curve= 0 ,0
Exp/Cntr=0.3,0.1

Type RM Length L Ch R = 1 ,40874   ,366,366,366
BEGIN DESCRIPTION:
UDS St 21 88.0
END DESCRIPTION:
XS GIS Cut Line= 3
       2270678.6      7216884.62        2270379.        7216860.
      2270129.01        7216860.
#Sta/Elev= 30
  4706.8  1061.1  4709.1  1061.1  4726.5 1059.06  4756.6 1056.62  4776.6 1056.01
  4786.7 1055.32  4806.7 1054.57    4823 1053.19  4836.8 1051.47  4846.9 1050.76
  4907.1 1048.26  4937.2 1048.87  4977.3 1047.91  4987.3 1048.09  4995.4 1046.12
  4995.6 1045.62  4999.1 1045.62  4999.4 1046.12  5004.9  1047.6  5009.9  1047.6
  5017.4 1048.56  5027.4 1048.22  5037.4 1048.61  5047.4 1049.24  5057.4 1050.57
  5067.4 1051.32  5137.4 1053.65  5147.4 1054.48  5177.4 1055.89  5257.4 1058.98
#Mann= 3 ,-1 , 0
  4706.8     .05       0  4995.4    .033       0  4999.4     .05       0
Bank Sta=4995.4,4999.4
XS Rating Curve= 0 ,0
Exp/Cntr=0.3,0.1

Type RM Length L Ch R = 1 ,40508   ,330,330,330
BEGIN DESCRIPTION:
UDS St 21 87.0
END DESCRIPTION:
XS GIS Cut Line= 3
        2270729.        7216610.        2270629.        7216610.
      2270162.73       7216614.8
#Sta/Elev= 30
  4892.7  1056.4  4922.7 1054.84  4952.7 1052.84  4972.7 1050.51  4982.7 1046.26
  4988.2  1043.6  4988.5  1043.1    4992  1043.1  4992.2  1043.6  4995.2  1043.6
  5002.7 1044.71  5032.7 1046.17  5052.7 1043.91  5062.7  1045.3  5082.7 1045.09
  5092.7  1045.9  5102.7 1046.31  5142.7 1046.09  5152.7  1045.7  5162.7 1045.68
  5212.7 1048.12  5272.7 1050.01  5282.7 1050.66  5312.7 1051.14  5372.7  1053.8
  5392.7 1054.35  5422.7 1055.84  5432.7 1055.82  5452.7 1056.44    5459 1056.97
#Mann= 3 ,-1 , 0
  4892.7     .05       0  4988.2    .033       0  4992.2     .05       0
Bank Sta=4988.2,4992.2
XS Rating Curve= 0 ,0
Exp/Cntr=0.3,0.1

Type RM Length L Ch R = 1 ,40178   ,385,385,385
BEGIN DESCRIPTION:
UDS St 21 86.0
END DESCRIPTION:
XS GIS Cut Line= 3
      2270792.75      7216321.19        2270529.        7216310.
      2270159.98      7216322.15
#Sta/Elev= 30
    4736 1054.55  4769.8 1054.29  4779.8 1053.64  4789.8  1052.4  4799.8 1050.46
  4809.8 1047.49  4839.8 1044.88  4899.9 1041.94  4949.9 1042.44    5010 1042.55
    5040 1041.11    5050 1042.98    5070 1042.11    5080 1040.98    5100 1041.61
    5120 1041.69  5138.1 1040.83  5138.3 1040.33  5141.8 1040.33  5142.1 1040.83
  5153.5 1044.15  5160.1 1045.16  5170.1 1047.45  5200.1 1048.08  5230.1 1048.32
  5250.1  1048.1  5270.1 1049.03  5290.1 1049.42  5320.2 1050.89  5369.2 1052.32
#Mann= 3 ,-1 , 0
    4736     .05       0  5138.1    .033       0  5142.1     .05       0
#XS Ineff= 2 , 0
       0    5050 1042.98               0
Permanent Ineff=
       F       F
Bank Sta=5138.1,5142.1
XS Rating Curve= 0 ,0
Exp/Cntr=0.3,0.1

Type RM Length L Ch R = 1 ,39793   ,363,363,363
BEGIN DESCRIPTION:
UDS St 21 85.0
END DESCRIPTION:
XS GIS Cut Line= 3
      2270817.09      7215891.99        2270529.        7215960.
      2270219.17      7216043.92
#Sta/Elev= 30
  4703.9 1050.12  4717.2 1049.66  4732.8 1047.95  4759.5 1042.67  4773.9 1041.23
  4794.4  1040.3  4801.8 1039.24  4866.3 1036.89  4897.2 1036.78  4907.4 1037.36
  4958.8 1036.41  4981.3 1036.92  5010.3 1036.59  5017.2 1035.28    5029 1034.91
  5029.2 1034.41  5032.7 1034.41    5033 1034.91  5062.3 1037.91  5096.9 1038.46
  5103.5 1037.29  5131.6 1038.18    5145 1040.16  5165.7 1040.86  5211.3 1044.74
  5238.2 1048.22  5251.1  1048.7  5269.3 1051.54  5285.8 1052.96  5320.9 1054.23
#Mann= 3 ,-1 , 0
  4703.9     .05       0    5029    .033       0    5033     .05       0
#XS Ineff= 2 , 0
       0                  5096.9       0 1038.46
Permanent Ineff=
       F       F
Bank Sta=5029,5033
XS Rating Curve= 0 ,0
Exp/Cntr=0.3,0.1

Type RM Length L Ch R = 1 ,39430   ,47,47,47
BEGIN DESCRIPTION:
UDS St 21 84.1
END DESCRIPTION:
XS GIS Cut Line= 4
      2270773.85      7215609.15      2270587.85      7215608.96
      2270497.08      7215630.44      2270231.01      7215775.45
#Sta/Elev= 30
  4648.5 1044.19  4753.4 1040.76  4831.4 1036.45  4902.1 1033.65  4934.3 1032.98
  4961.8 1033.39    4976 1031.63  4976.2 1031.13  4979.7 1031.13    4980 1031.63
  4983.7 1032.73  4999.8 1032.28  5005.5 1033.06  5028.1 1032.81  5037.8 1032.05
  5059.6 1032.39  5103.3 1035.22  5130.8 1035.91  5141.3 1037.19    5147 1036.89
  5153.4 1038.67  5163.1 1039.83  5168.8 1039.56    5185 1042.86  5190.7 1042.68
  5198.9 1044.46  5206.8 1047.26  5212.5 1047.43  5221.7 1051.43  5230.8 1053.08
#Mann= 3 ,-1 , 0
  4648.5     .05       0    4976    .033       0    4980     .05       0
Bank Sta=4976,4980
XS Rating Curve= 0 ,0
Exp/Cntr=0.3,0.1

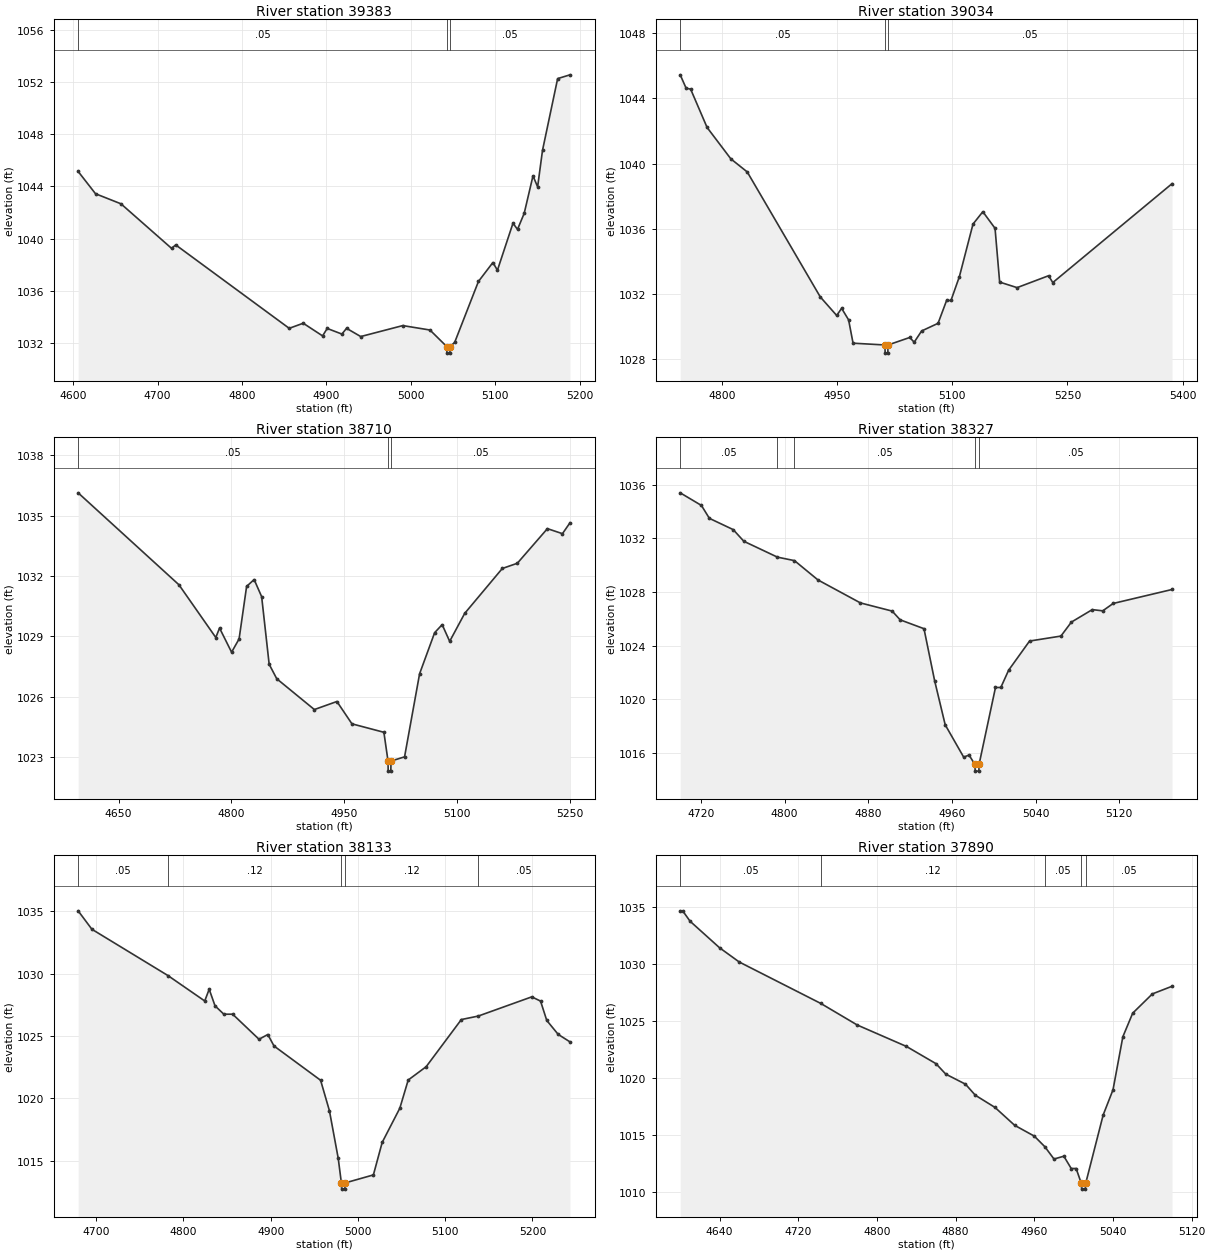
Type RM Length L Ch R = 1 ,39383   ,349,349,349
BEGIN DESCRIPTION:
UDS St 21 84.0
END DESCRIPTION:
XS GIS Cut Line= 5
      2270779.62      7215560.89      2270525.52      7215569.93
      2270451.17      7215604.55      2270354.88      7215657.15
      2270229.02      7215709.99
#Sta/Elev= 30
    4606 1045.15  4626.6 1043.44  4656.7 1042.67  4716.6 1039.26  4721.6 1039.52
    4856 1033.13  4872.6 1033.52  4895.5 1032.55    4901 1033.12  4918.4 1032.69
  4923.9 1033.13  4940.7  1032.5  4990.5 1033.34  5022.7    1033  5042.6 1031.73
  5042.8 1031.23  5046.3 1031.23  5046.6 1031.73    5052 1032.06  5080.1 1036.72
  5097.2 1038.17  5102.6 1037.58    5121 1041.18  5126.4 1040.71  5134.3 1041.94
  5144.7 1044.81  5150.2 1043.97    5156 1046.77  5173.9 1052.26  5188.5 1052.55
#Mann= 3 ,-1 , 0
    4606     .05       0  5042.6    .033       0  5046.6     .05       0
Bank Sta=5042.6,5046.6
XS Rating Curve= 0 ,0
Exp/Cntr=0.3,0.1

Type RM Length L Ch R = 1 ,39034   ,324,324,324
BEGIN DESCRIPTION:
UDS St 21 83.0
END DESCRIPTION:
XS GIS Cut Line= 3
      2270778.98      7215509.99      2270479.89       7215329.5
      2270213.93      7215210.97
#Sta/Elev= 30
  4745.7 1045.45  4753.4 1044.63  4759.3 1044.57  4780.7 1042.22  4811.7 1040.29
    4833 1039.49  4928.1 1031.82  4949.5 1030.68  4955.9 1031.12    4965 1030.41
  4970.8 1028.98  5012.3 1028.87  5012.6 1028.37  5016.1 1028.37  5016.3 1028.87
  5044.6 1029.33  5050.4 1029.04  5060.1 1029.73  5081.5  1030.2  5092.6  1031.6
  5098.3  1031.6  5109.3 1033.07    5127 1036.29  5139.8 1037.05  5155.7 1036.03
  5161.7 1032.73  5184.4 1032.39  5225.4 1033.12  5230.9  1032.7  5386.2 1038.77
#Mann= 3 ,-1 , 0
  4745.7     .05       0  5012.3    .033       0  5016.3     .05       0
#XS Ineff= 2 , 0
       0  4955.9 1031.12               0
Permanent Ineff=
       F       F
Bank Sta=5012.3,5016.3
XS Rating Curve= 0 ,0
Exp/Cntr=0.3,0.1

Type RM Length L Ch R = 1 ,38710   ,383,383,383
BEGIN DESCRIPTION:
UDS St 21 82.0
END DESCRIPTION:
XS GIS Cut Line= 3
      2270983.08      7215069.31        2270579.        7215060.
      2270328.99        7215060.
#Sta/Elev= 30
  4596.2 1036.13  4730.3 1031.56  4779.3 1028.94  4784.3 1029.41  4800.3 1028.21
  4810.3 1028.87  4820.3 1031.48  4830.3 1031.82  4840.3 1030.97  4850.3 1027.61
  4860.4 1026.89  4910.4 1025.36  4940.4 1025.76  4960.4 1024.65  5002.9 1024.23
  5008.4  1022.8  5008.6  1022.3  5012.1  1022.3  5012.4  1022.8  5030.4 1023.01
  5050.4 1027.14  5070.4 1029.18  5080.4 1029.58  5090.4 1028.75  5110.4 1030.14
  5160.4 1032.37  5180.4 1032.63  5220.4 1034.35  5240.4  1034.1  5250.4 1034.64
#Mann= 3 ,-1 , 0
  4596.2     .05       0  5008.4    .033       0  5012.4     .05       0
Bank Sta=5008.4,5012.4
XS Rating Curve= 0 ,0
Exp/Cntr=0.3,0.1

Type RM Length L Ch R = 1 ,38327   ,194,194,194
BEGIN DESCRIPTION:
UDS St 21 81.0
END DESCRIPTION:
XS GIS Cut Line= 3
      2270779.04      7214659.99        2270479.        7214710.
      2270312.71      7214713.17
#Sta/Elev= 30
  4700.1 1035.39  4720.4 1034.45    4728 1033.49  4750.8 1032.65    4761 1031.78
  4793.1  1030.6  4809.4 1030.34  4831.9  1028.9  4872.5 1027.19  4902.9 1026.58
  4910.5 1025.93  4933.3 1025.27  4943.5 1021.39  4953.6 1018.11  4971.3  1015.7
  4976.4 1015.86    4982 1015.16  4982.3 1014.66  4985.8 1014.66    4986 1015.16
  5001.7 1020.89  5006.8 1020.89  5014.3 1022.18  5034.3 1024.35  5064.3 1024.72
  5074.3 1025.76  5094.3 1026.69  5104.3  1026.6  5114.3 1027.15  5170.6 1028.19
#Mann= 5 ,-1 , 0
  4700.1     .05       0  4793.1     .12       0  4809.4     .05       0
    4982     .05       0    4986     .05       0
Bank Sta=4982,4986
XS Rating Curve= 0 ,0
Exp/Cntr=0.3,0.1

Type RM Length L Ch R = 1 ,38133   ,243,243,243
BEGIN DESCRIPTION:
UDS St 21 80.1
END DESCRIPTION:
XS GIS Cut Line= 2
      2270764.63        7214486.      2270205.56      7214558.14
#Sta/Elev= 30
  4679.3 1035.04  4695.1 1033.56  4782.2 1029.85  4824.4 1027.81  4829.5 1028.75
  4836.2 1027.42  4846.3 1026.75  4856.4 1026.75  4886.6 1024.74  4896.7 1025.12
  4903.8  1024.2  4957.2 1021.45  4967.3 1019.01  4977.4 1015.19    4981 1013.22
  4981.4 1012.72    4985 1012.72  4985.4 1013.22  5017.7 1013.86  5027.8 1016.47
    5048 1019.21  5057.6 1021.47  5078.2 1022.54  5118.5 1026.32  5137.9  1026.6
  5199.2 1028.14  5209.3  1027.8  5216.4 1026.25  5229.5 1025.13    5243 1024.53
#Mann= 5 ,-1 , 0
  4679.3     .05       0  4782.2     .12       0    4981     .07       0
  4985.4     .12       0  5137.9     .05       0
Bank Sta=4981,4985.4
XS Rating Curve= 0 ,0
Exp/Cntr=0.3,0.1

Type RM Length L Ch R = 1 ,37890   ,450,450,450
BEGIN DESCRIPTION:
UDS St 21 80.0
END DESCRIPTION:
XS GIS Cut Line= 3
      2270778.97        7214310.        2270379.        7214310.
      2270278.97        7214310.
#Sta/Elev= 30
    4600 1034.66  4602.5 1034.66    4610 1033.75    4640 1031.42    4660 1030.17
    4743 1026.53    4780 1024.64    4830 1022.76    4860 1021.25    4870 1020.33
    4890 1019.45    4900 1018.48    4920 1017.41    4940 1015.84    4960 1014.89
  4970.7 1013.96    4980 1012.88    4990 1013.13  4997.5 1012.05  5002.5 1012.05
  5007.8 1010.74  5008.2 1010.24  5011.8 1010.24  5012.2 1010.74    5030 1016.75
    5040 1018.96    5050 1023.61    5060 1025.68    5080 1027.37    5100 1028.04
#Mann= 5 ,-1 , 0
    4600     .05       0    4743     .12       0  4970.7     .05       0
  5007.8    .033       0  5012.2     .05       0
Bank Sta=5007.8,5012.2
XS Rating Curve= 0 ,0
Exp/Cntr=0.3,0.1

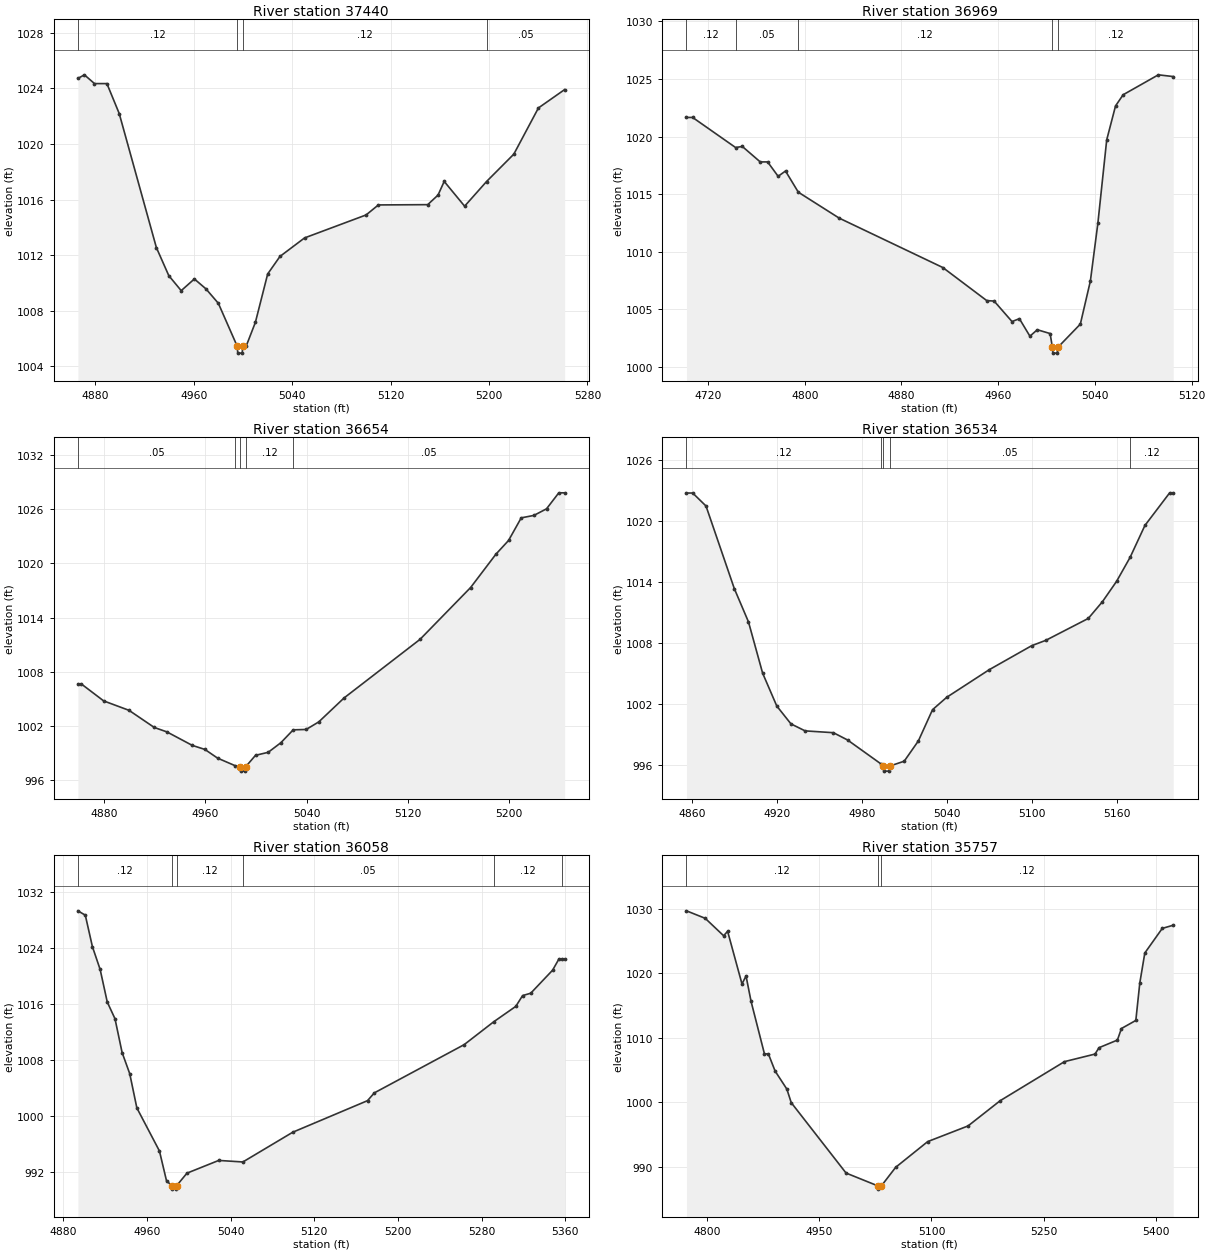
Type RM Length L Ch R = 1 ,37440   ,471,471,471
BEGIN DESCRIPTION:
UDS St 21 79.0
END DESCRIPTION:
XS GIS Cut Line= 3
      2270512.42      7213875.25        2270379.        7213860.
      2270117.72      7213868.07
#Sta/Elev= 30
  4865.8  1024.7  4871.1 1024.96  4879.3 1024.33  4889.4 1024.33  4899.4 1022.18
  4929.6 1012.55  4939.7 1010.53  4949.8 1009.45  4960.5 1010.29  4969.9 1009.58
    4980 1008.54  4995.3 1005.46  4995.8 1004.96  4999.4 1004.96  4999.8 1005.46
  5002.6 1005.46  5010.1 1007.17  5020.1 1010.65  5030.1 1011.91  5050.1 1013.24
  5100.1 1014.89  5110.1 1015.61  5150.2 1015.63  5158.6 1016.32  5163.6  1017.3
  5180.2 1015.52    5198 1017.29  5220.2 1019.26  5240.2 1022.58  5261.5  1023.9
#Mann= 4 ,-1 , 0
  4865.8     .12       0  4995.3     .07       0  4999.8     .12       0
    5198     .05       0
Bank Sta=4995.3,4999.8
XS Rating Curve= 0 ,0
Exp/Cntr=0.3,0.1

Type RM Length L Ch R = 1 ,36969   ,315,315,315
BEGIN DESCRIPTION:
UDS St 21 78.0
END DESCRIPTION:
XS GIS Cut Line= 3
      2270372.38      7213338.86        2270129.        7213510.
      2270045.04      7213573.01
#Sta/Elev= 30
  4702.2 1021.66  4707.3 1021.66  4742.8 1019.05  4748.4 1019.14  4763.2  1017.8
  4769.3  1017.8    4778 1016.55  4784.1 1017.01  4794.7 1015.17  4828.5 1012.92
  4914.2 1008.63  4950.5 1005.76  4956.6 1005.72  4971.4 1003.94  4977.5 1004.19
  4986.2 1002.67  4992.3 1003.23  5002.9  1002.9  5004.8  1001.7  5005.2  1001.2
  5008.8  1001.2  5009.3  1001.7  5027.9 1003.72  5036.2 1007.46  5042.4 1012.48
  5049.7 1019.71    5057 1022.66  5063.3 1023.63  5092.4 1025.36  5104.7 1025.21
#Mann= 5 ,-1 , 0
  4702.2     .12       0  4742.8     .05       0  4794.7     .12       0
  5004.8     .07       0  5009.3     .12       0
Bank Sta=5004.8,5009.3
XS Rating Curve= 0 ,0
Exp/Cntr=0.3,0.1

Type RM Length L Ch R = 1 ,36654   ,120,120,120
BEGIN DESCRIPTION:
UDS St 21 77.1
END DESCRIPTION:
XS GIS Cut Line= 2
      2270169.44      7213229.45      2269784.74      7213229.45
#Sta/Elev= 30
  4859.2 1006.65  4861.9 1006.65  4879.6 1004.77  4899.6 1003.73  4919.6 1001.83
  4929.6 1001.34  4949.6  999.85  4959.6   999.4  4969.6  998.44  4983.5   997.6
  4987.3   997.5  4987.8     997  4991.5     997  4991.9   997.5  4999.6  998.75
  5009.6  999.08  5019.6 1000.14  5029.4 1001.57  5039.6 1001.61  5049.6 1002.45
  5069.6  1005.1  5129.6 1011.58  5169.6 1017.32  5189.6 1021.01  5199.6 1022.53
  5209.6 1025.03  5219.6  1025.3  5229.6 1026.03  5239.3  1027.8  5243.9  1027.8
#Mann= 5 ,-1 , 0
  4859.2     .05       0  4983.5     .12       0  4987.3     .07       0
  4991.9     .12       0  5029.4     .05       0
Bank Sta=4987.3,4991.9
XS Rating Curve= 0 ,0
Exp/Cntr=0.3,0.1

Type RM Length L Ch R = 1 ,36534   ,476,476,476
BEGIN DESCRIPTION:
UDS St 21 77.0
END DESCRIPTION:
XS GIS Cut Line= 3
      2270172.76      7213111.88        2270029.        7213110.
      2269828.97        7213110.
#Sta/Elev= 30
  4856.2 1022.78  4860.6 1022.78    4870  1021.5    4890 1013.35    4900 1010.07
    4910 1005.01    4920 1001.77    4930 1000.01    4940  999.32    4960  999.14
    4970  998.42  4993.6  996.06  4995.2  995.85  4995.6  995.35  4999.3  995.35
  4999.8  995.85    5010  996.33    5020  998.33    5030 1001.41    5040 1002.63
    5070 1005.35    5100 1007.72    5110 1008.25    5140 1010.41    5150 1012.06
    5160 1014.07  5169.6 1016.45    5180 1019.58  5197.5  1022.8    5200  1022.8
#Mann= 5 ,-1 , 0
  4856.2     .12       0  4993.6     .05       0  4995.2    .033       0
  4999.8     .05       0  5169.6     .12       0
Bank Sta=4995.2,4999.8
XS Rating Curve= 0 ,0
Exp/Cntr=0.3,0.1

Type RM Length L Ch R = 1 ,36058   ,301,301,301
BEGIN DESCRIPTION:
UDS St 21 76.0
END DESCRIPTION:
XS GIS Cut Line= 3
      2269979.01      7212609.99      2269906.75       7212688.6
      2269676.28      7212963.48
#Sta/Elev= 30
  4893.9 1029.33    4901 1028.71  4907.8 1024.21  4915.2 1020.95    4922  1016.3
  4929.4 1013.91  4936.2 1009.08  4943.5 1006.06  4950.3 1001.17  4971.9  995.02
  4978.7  990.74  4983.8  990.07  4984.2  989.57  4987.9  989.57  4988.4  990.07
  4998.2  991.85  5028.6  993.67  5051.7  993.45  5099.4   997.7  5170.9 1002.21
  5177.4 1003.32  5263.3 1010.21  5291.6 1013.48  5312.7 1015.68  5319.2 1017.22
    5327 1017.56  5347.9 1020.85  5353.9 1022.44  5356.5 1022.44  5359.4 1022.44
#Mann= 6 ,-1 , 0
  4893.9     .12       0  4983.8     .07       0  4988.4     .12       0
  5051.7     .05       0  5291.6     .12       0  5356.5     .05       0
Bank Sta=4983.8,4988.4
XS Rating Curve= 0 ,0
Exp/Cntr=0.3,0.1

Type RM Length L Ch R = 1 ,35757   ,186,186,186
BEGIN DESCRIPTION:
UDS St 21 75.1
END DESCRIPTION:
XS GIS Cut Line= 2
      2269969.34      7212356.74      2269363.68      7212591.58
#Sta/Elev= 30
    4773 1029.68    4798 1028.52  4822.6 1025.82  4827.9 1026.51  4847.1 1018.35
  4852.5 1019.59  4859.2 1015.66    4877 1007.55  4882.4 1007.49  4891.3 1004.86
    4907 1002.06  4912.8  999.97    4986  989.06  5028.5  987.07  5028.9  986.57
  5033.1  987.07  5052.2  989.95  5094.9  993.93  5148.8  996.36  5191.7 1000.27
  5277.5 1006.32  5318.2 1007.49  5323.6 1008.48  5348.1 1009.66  5353.5 1011.45
  5372.7  1012.7    5378  1018.5  5384.7 1023.15    5408 1026.96  5422.6 1027.45
#Mann= 3 ,-1 , 0
    4773     .12       0  5028.5     .07       0  5033.1     .12       0
Bank Sta=5028.5,5033.1
XS Rating Curve= 0 ,0
Exp/Cntr=0.3,0.1

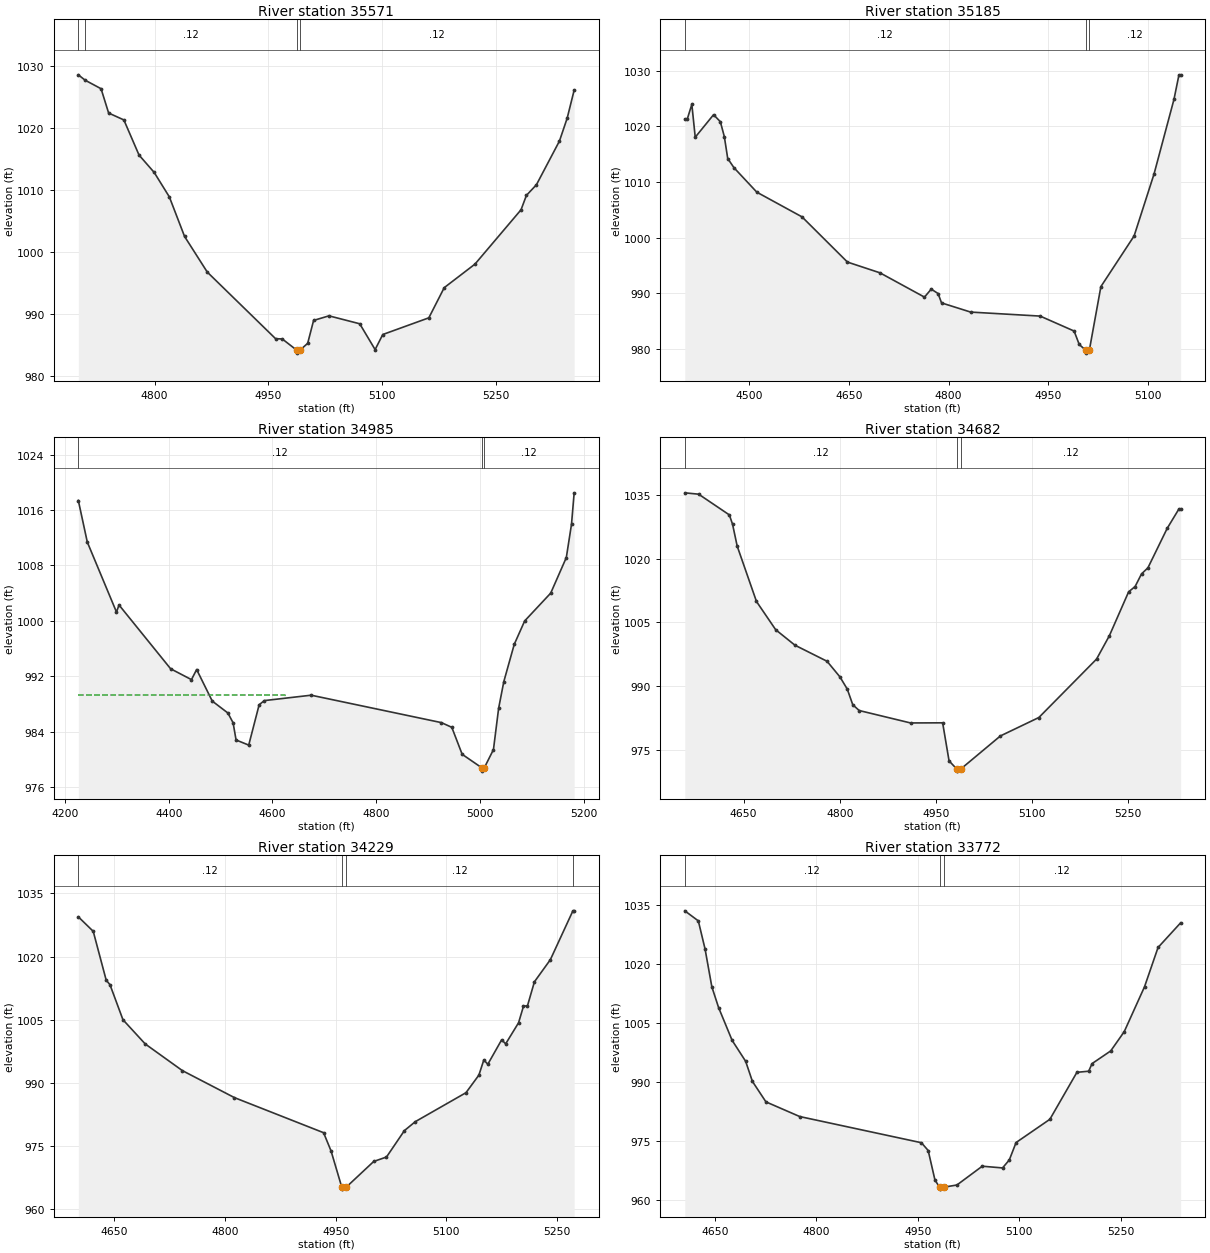
Type RM Length L Ch R = 1 ,35571   ,386,386,386
BEGIN DESCRIPTION:
UDS St 21 75.0
END DESCRIPTION:
XS GIS Cut Line= 3
      2269978.96        7212310.      2269676.77      7212293.36
      2269329.92      7212234.85
#Sta/Elev= 30
  4699.4 1028.59  4708.3 1027.73  4729.4 1026.35  4739.4 1022.43  4759.5 1021.32
  4779.5 1015.66  4799.5 1012.86  4819.5 1008.92  4839.6 1002.54  4869.6  996.79
  4959.8  986.05  4968.5  986.02  4987.4  984.23  4987.9  983.73  4992.1  984.23
  5002.1  985.31  5009.9     989  5030.2  989.74  5070.8  988.46  5091.1   984.3
  5101.2  986.73    5162  989.42  5182.3  994.28  5222.9  998.08  5283.7 1006.84
  5290.8 1009.16    5304 1010.87  5334.4 1017.92  5344.6 1021.61  5353.8 1026.12
#Mann= 4 ,-1 , 0
  4699.4     .05       0  4708.3     .12       0  4987.4     .07       0
  4992.1     .12       0
Bank Sta=4987.4,4992.1
XS Rating Curve= 0 ,0
Exp/Cntr=0.3,0.1

Type RM Length L Ch R = 1 ,35185   ,200,200,200
BEGIN DESCRIPTION:
UDS St 21 74.0
END DESCRIPTION:
XS GIS Cut Line= 3
       2270111.3      7212087.93        2269529.        7211960.
      2269378.98        7211960.
#Sta/Elev= 30
    4403 1021.35  4406.8 1021.35  4413.6 1023.95  4418.7 1018.05  4446.3  1022.1
  4456.5 1020.84  4462.5 1018.16  4467.6 1014.22    4477 1012.57  4511.4 1008.17
  4579.4 1003.73  4647.8   995.6  4696.7  993.67  4763.7   989.3  4773.9  990.74
  4784.2  989.94  4789.4  988.26  4833.2  986.61  4937.8  985.89  4988.9   983.2
  4996.6  980.79  5006.5  979.73  5007.3  979.23  5011.8  979.73  5029.2  991.19
  5079.2  1000.3  5109.2 1011.44  5139.2 1024.86  5146.7 1029.27  5149.2 1029.27
#Mann= 3 ,-1 , 0
    4403     .12       0  5006.5     .07       0  5011.8     .12       0
Bank Sta=5006.5,5011.8
XS Rating Curve= 0 ,0
Exp/Cntr=0.3,0.1

Type RM Length L Ch R = 1 ,34985   ,303,303,303
BEGIN DESCRIPTION:
UDS St 21 73.1
END DESCRIPTION:
XS GIS Cut Line= 2
      2270376.24      7211851.46      2269423.94      7211768.48
#Sta/Elev= 30
  4225.7 1017.38    4243 1011.37  4299.2 1001.27  4304.2 1002.28  4403.6  993.07
  4443.8   991.5  4453.8  992.96  4483.9   988.4    4514  986.68  4524.1  985.26
  4529.8  982.78  4554.2  982.04  4574.3  987.87  4584.3  988.47  4674.6  989.25
  4925.6  985.29  4945.7  984.61  4965.7  980.71  5003.2  978.78    5004  978.28
  5008.5  978.78    5026  981.39    5036  987.36    5046  991.22  5066.1   996.6
  5086.2  999.98  5136.4    1004  5166.5 1009.14  5176.5 1013.96  5181.6 1018.49
#Mann= 3 ,-1 , 0
  4225.7     .12       0  5003.2     .07       0  5008.5     .12       0
#XS Ineff= 2 , 0
       0  4624.4   989.3               0
Permanent Ineff=
       F       F
Bank Sta=5003.2,5008.5
XS Rating Curve= 0 ,0
Exp/Cntr=0.3,0.1

Type RM Length L Ch R = 1 ,34682   ,453,453,453
BEGIN DESCRIPTION:
UDS St 21 73.0
END DESCRIPTION:
XS GIS Cut Line= 3
      2270170.58      7211500.93      2269723.23      7211526.16
      2269397.97      7211533.49
#Sta/Elev= 30
  4558.2 1035.46  4579.8 1035.14  4627.7 1030.27  4632.7 1028.07  4639.9 1022.95
    4670 1009.93    4700 1003.29    4730  999.66  4780.1  995.88  4800.2  992.21
  4811.6  989.35  4820.2  985.67  4830.2  984.31  4910.3  981.39  4960.4  981.42
  4970.4  972.48  4982.4  970.57  4983.5  970.07  4988.7  970.57  5050.5  978.34
  5110.5  982.67  5200.5   996.4  5220.5  1001.9  5250.5  1012.2  5260.6 1013.44
  5270.6 1016.41  5280.6 1017.84  5310.6  1027.1  5328.6 1031.58  5331.6 1031.58
#Mann= 3 ,-1 , 0
  4558.2     .12       0  4982.4     .07       0  4988.7     .12       0
Bank Sta=4982.4,4988.7
XS Rating Curve= 0 ,0
Exp/Cntr=0.3,0.1

Type RM Length L Ch R = 1 ,34229   ,457,457,457
BEGIN DESCRIPTION:
UDS St 21 72.0
END DESCRIPTION:
XS GIS Cut Line= 3
      2270029.03        7211060.        2269629.        7211110.
        2269379.        7211210.
#Sta/Elev= 30
    4601 1029.44  4621.2    1026  4638.8 1014.38  4643.9 1013.32  4661.5 1004.99
  4691.7  999.23  4742.1  992.89  4812.7  986.47  4933.6  978.13  4943.7  973.81
  4958.2  965.22  4959.2  964.72  4964.5  965.22  5001.6   971.3  5018.9  972.35
  5043.2  978.63    5058  980.76  5126.7  987.64  5144.2  991.82  5150.9  995.43
  5156.3   994.4  5175.1 1000.22  5180.5  999.25    5198 1004.26  5204.7 1008.21
  5210.1  1008.3  5219.5    1014  5241.1 1019.25  5271.7 1030.87  5273.4 1030.87
#Mann= 4 ,-1 , 0
    4601     .12       0  4958.2     .07       0  4964.5     .12       0
  5271.7     .05       0
Bank Sta=4958.2,4964.5
XS Rating Curve= 0 ,0
Exp/Cntr=0.3,0.1

Type RM Length L Ch R = 1 ,33772   ,436,436,436
BEGIN DESCRIPTION:
UDS St 21 71.0
END DESCRIPTION:
XS GIS Cut Line= 3
      2269978.95        7210760.        2269579.        7210760.
      2269245.65      7210751.65
#Sta/Elev= 30
  4605.3  1033.6  4625.3 1031.04  4635.3 1023.85  4645.3 1014.24  4655.3 1008.95
  4675.3  1000.6  4695.3  995.27  4705.3  990.15  4725.3  984.93  4775.3  981.19
  4955.3  974.52  4965.3  972.54  4975.3  965.03  4982.1   963.2  4983.1   962.7
  4988.5   963.2  5007.8  963.75  5045.3  968.54  5075.3   968.1  5085.3  970.14
  5095.3  974.57  5145.3  980.49  5185.3  992.46  5202.7  992.74  5207.7  994.68
  5235.3  997.91  5255.3 1002.82  5285.3 1014.25  5305.3 1024.26  5338.7 1030.54
#Mann= 3 ,-1 , 0
  4605.3     .12       0  4982.1     .07       0  4988.5     .12       0
Bank Sta=4982.1,4988.5
XS Rating Curve= 0 ,0
Exp/Cntr=0.3,0.1

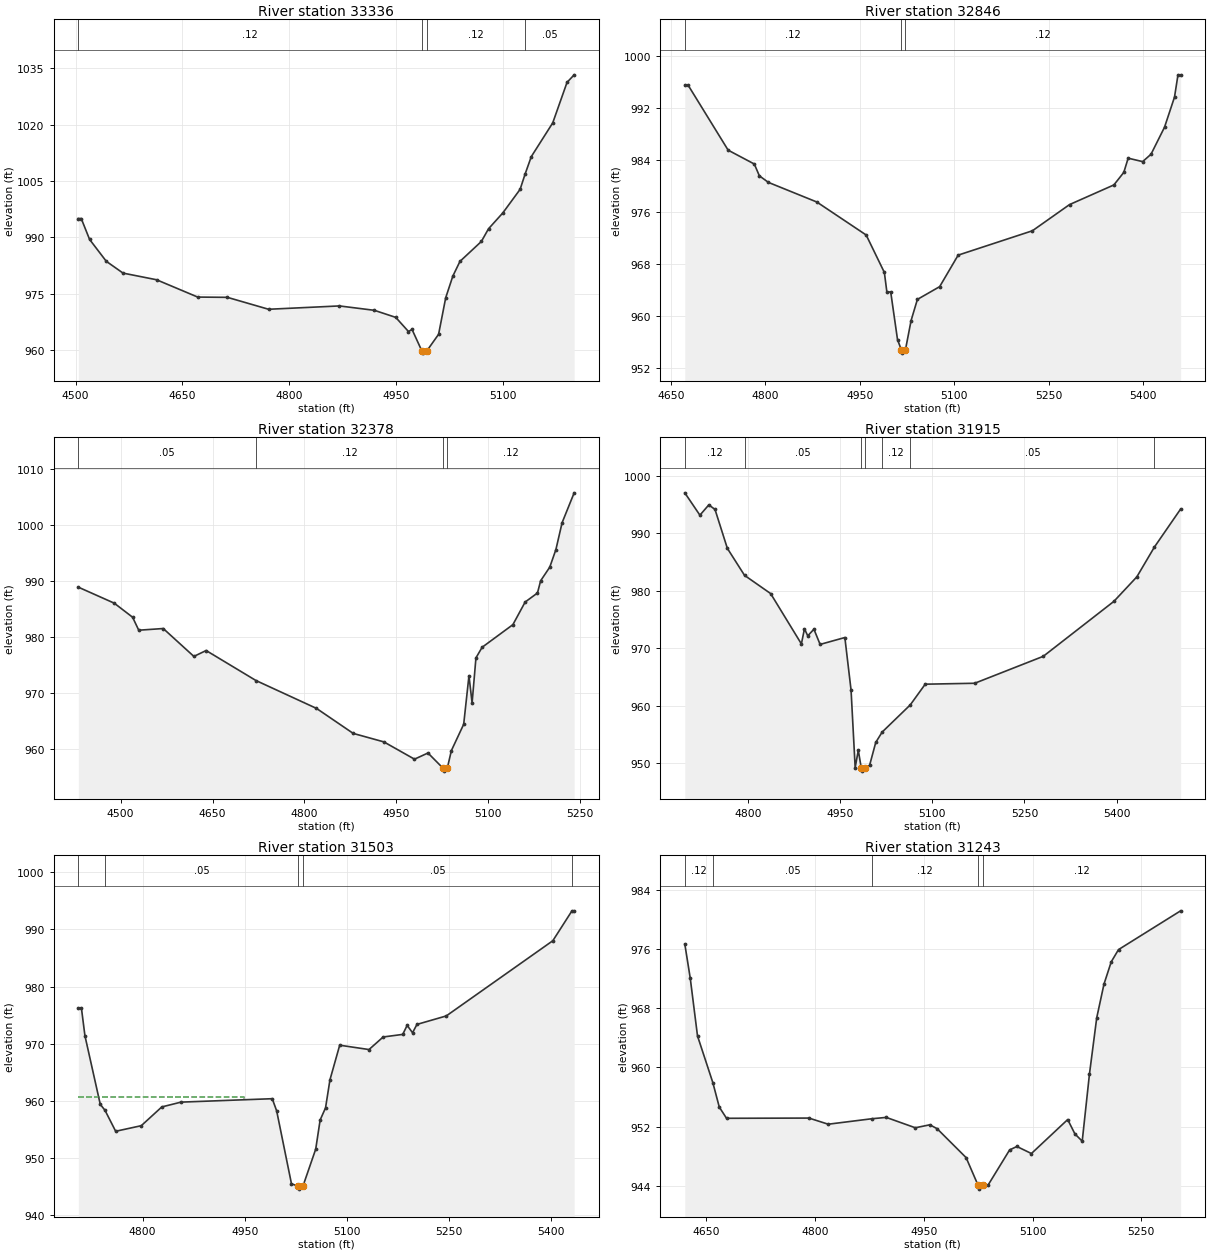
Type RM Length L Ch R = 1 ,33336   ,490,490,490
BEGIN DESCRIPTION:
UDS St 21 70.0
END DESCRIPTION:
XS GIS Cut Line= 3
      2269941.46      7210540.01      2269568.47      7210378.93
      2269278.98        7210360.
#Sta/Elev= 30
  4503.8  994.99  4507.9  994.99  4519.6  989.43  4543.1  983.59  4566.6  980.45
  4613.6  978.68  4671.5  974.06  4713.1  973.99    4771  970.81  4870.5   971.7
  4919.6  970.53  4949.6  968.65  4967.5  964.88  4972.5  965.43  4986.5  959.62
  4987.6  959.12  4992.9  959.62  5009.8  964.14  5019.8  973.89  5029.8  979.65
  5039.8  983.57  5069.9  988.89  5079.9  992.26    5100  996.49  5124.3 1002.78
  5131.3 1006.85    5140  1011.5  5170.1 1020.49  5190.2 1031.29  5200.2  1033.3
#Mann= 4 ,-1 , 0
  4503.8     .12       0  4986.5     .07       0  4992.9     .12       0
  5131.3     .05       0
Bank Sta=4986.5,4992.9
XS Rating Curve= 0 ,0
Exp/Cntr=0.3,0.1

Type RM Length L Ch R = 1 ,32846   ,468,468,468
BEGIN DESCRIPTION:
UDS St 21 69.0
END DESCRIPTION:
XS GIS Cut Line= 3
      2270083.06      7210461.72        2269829.        7210260.
      2269426.61      7210029.56
#Sta/Elev= 30
  4671.8  995.49  4677.2  995.49  4740.7  985.53  4782.3   983.4  4790.3  981.59
  4804.7  980.58  4881.6  977.57  4960.1   972.5    4989  966.75    4993  963.75
  4999.1  963.75  5009.9  956.44    5016  954.86    5017  954.36  5022.5  954.86
  5031.5  959.37  5041.5  962.61  5076.9  964.57  5106.3  969.41  5224.3  973.15
  5283.3  977.17  5353.8  980.19  5369.6  982.12  5376.5   984.3  5399.5  983.77
  5412.8   984.9  5434.3  989.05  5450.2  993.69  5455.7   997.1  5459.9   997.1
#Mann= 3 ,-1 , 0
  4671.8     .12       0    5016     .07       0  5022.5     .12       0
Bank Sta=5016,5022.5
XS Rating Curve= 0 ,0
Exp/Cntr=0.3,0.1

Type RM Length L Ch R = 1 ,32378   ,463,463,463
BEGIN DESCRIPTION:
UDS St 21 68.0
END DESCRIPTION:
XS GIS Cut Line= 3
      2270247.55      7209945.49       2269680.1      7209931.49
      2269439.36      7209910.19
#Sta/Elev= 30
  4430.9  988.92  4489.5  986.07  4519.5  983.56  4529.5  981.25  4569.5  981.55
  4619.5  976.58  4639.5  977.63  4720.9  972.28  4819.6  967.32  4879.6  962.86
  4929.6  961.35  4979.6  958.27  5001.6  959.37  5026.4  956.64  5027.4  956.14
  5033.1  956.64  5039.8   959.8  5059.9  964.49  5068.5  973.15  5073.6  968.29
  5079.9  976.32    5090  978.21  5140.2  982.24  5160.2  986.27  5180.3  987.88
  5185.5  990.06  5200.4  992.49  5210.4  995.62  5220.5  1000.4  5240.2 1005.73
#Mann= 4 ,-1 , 0
  4430.9     .05       0  4720.9     .12       0  5026.4     .07       0
  5033.1     .12       0
Bank Sta=5026.4,5033.1
XS Rating Curve= 0 ,0
Exp/Cntr=0.3,0.1

Type RM Length L Ch R = 1 ,31915   ,412,412,412
BEGIN DESCRIPTION:
UDS St 21 67.0
END DESCRIPTION:
XS GIS Cut Line= 3
      2270217.86      7209707.98      2269727.75      7209649.69
      2269439.11       7209773.4
#Sta/Elev= 30
  4696.8  997.07  4721.4  993.18  4735.9  994.97    4746  994.18  4766.1  987.41
  4794.1  982.71  4836.6  979.54  4886.7  970.78  4891.7  973.41  4897.1  972.18
  4907.1  973.34  4917.2  970.69  4957.5  971.89  4967.6  962.75  4974.3  949.26
  4979.4  952.27  4984.3  949.14  4985.4  948.64  4991.1  949.14  4997.8  949.65
  5007.8  953.63  5018.2  955.43    5064  960.16  5088.4  963.77    5169  963.93
  5280.7  968.62  5395.7  978.18  5433.1  982.45  5461.8  987.65  5504.4  994.25
#Mann= 7 ,-1 , 0
  4696.8     .12       0  4794.1     .05       0  4984.3    .033       0
  4991.1     .05       0  5018.2     .12       0    5064     .05       0
  5461.8     .12       0
Bank Sta=4984.3,4991.1
XS Rating Curve= 0 ,0
Exp/Cntr=0.3,0.1

Type RM Length L Ch R = 1 ,31503   ,260,260,260
BEGIN DESCRIPTION:
UDS St 21 66.0
END DESCRIPTION:
XS GIS Cut Line= 3
      2269932.08      7209220.46       2269711.9      7209327.47
      2269405.02      7209700.31
#Sta/Elev= 30
  4705.7  976.26  4710.2  976.26  4715.4  971.38  4737.9  959.38  4744.8  958.35
  4760.5  954.67  4798.1  955.65  4828.2  958.93  4856.3  959.77  4990.3  960.37
  4996.8  958.23  5018.5  945.49  5028.5  945.05  5029.6  944.55  5035.3  945.05
  5054.1  951.55  5060.6  956.65  5068.5  958.76    5075  963.68  5089.3  969.73
  5132.3  968.97  5153.1  971.17  5181.8  971.62  5188.3   973.2  5196.2  971.91
  5202.7  973.37  5245.7  974.85  5402.1  988.01  5430.2  993.24  5433.4  993.24
#Mann= 5 ,-1 , 0
  4705.7     .12       0  4744.8     .05       0  5028.5    .033       0
  5035.3     .05       0  5430.2     .12       0
#XS Ineff= 2 , 0
       0  4949.3  960.74               0
Permanent Ineff=
       F       F
Bank Sta=5028.5,5035.3
XS Rating Curve= 0 ,0
Exp/Cntr=0.3,0.1

Type RM Length L Ch R = 1 ,31243   ,160,160,160
BEGIN DESCRIPTION:
UDS St 21 65.1
END DESCRIPTION:
XS GIS Cut Line= 2
      2269926.53      7209197.88      2269243.43      7209186.27
#Sta/Elev= 30
  4620.9  976.68  4628.4  972.07  4638.4  964.26  4659.5  957.96  4668.4  954.65
  4678.4  953.13    4792  953.16  4818.5  952.33  4878.7  953.07  4898.5  953.25
  4938.5  951.85  4958.5  952.25  4968.5  951.73  5008.5  947.82  5025.1  944.06
  5026.1  943.56  5031.9  944.06  5038.5  944.06  5068.5  948.86  5078.5  949.32
  5098.5  948.37  5148.5  952.96  5158.5  951.01  5168.5  950.04  5178.5  959.12
  5188.5  966.71  5198.5  971.26  5208.5  974.27  5218.5  975.92  5304.1  981.16
#Mann= 5 ,-1 , 0
  4620.9     .12       0  4659.5     .05       0  4878.7     .12       0
  5025.1     .07       0  5031.9     .12       0
#XS Ineff= 2 , 0
       0                  5148.5       0  952.96
Permanent Ineff=
       F       F
Bank Sta=5025.1,5031.9
XS Rating Curve= 0 ,0
Exp/Cntr=0.3,0.1