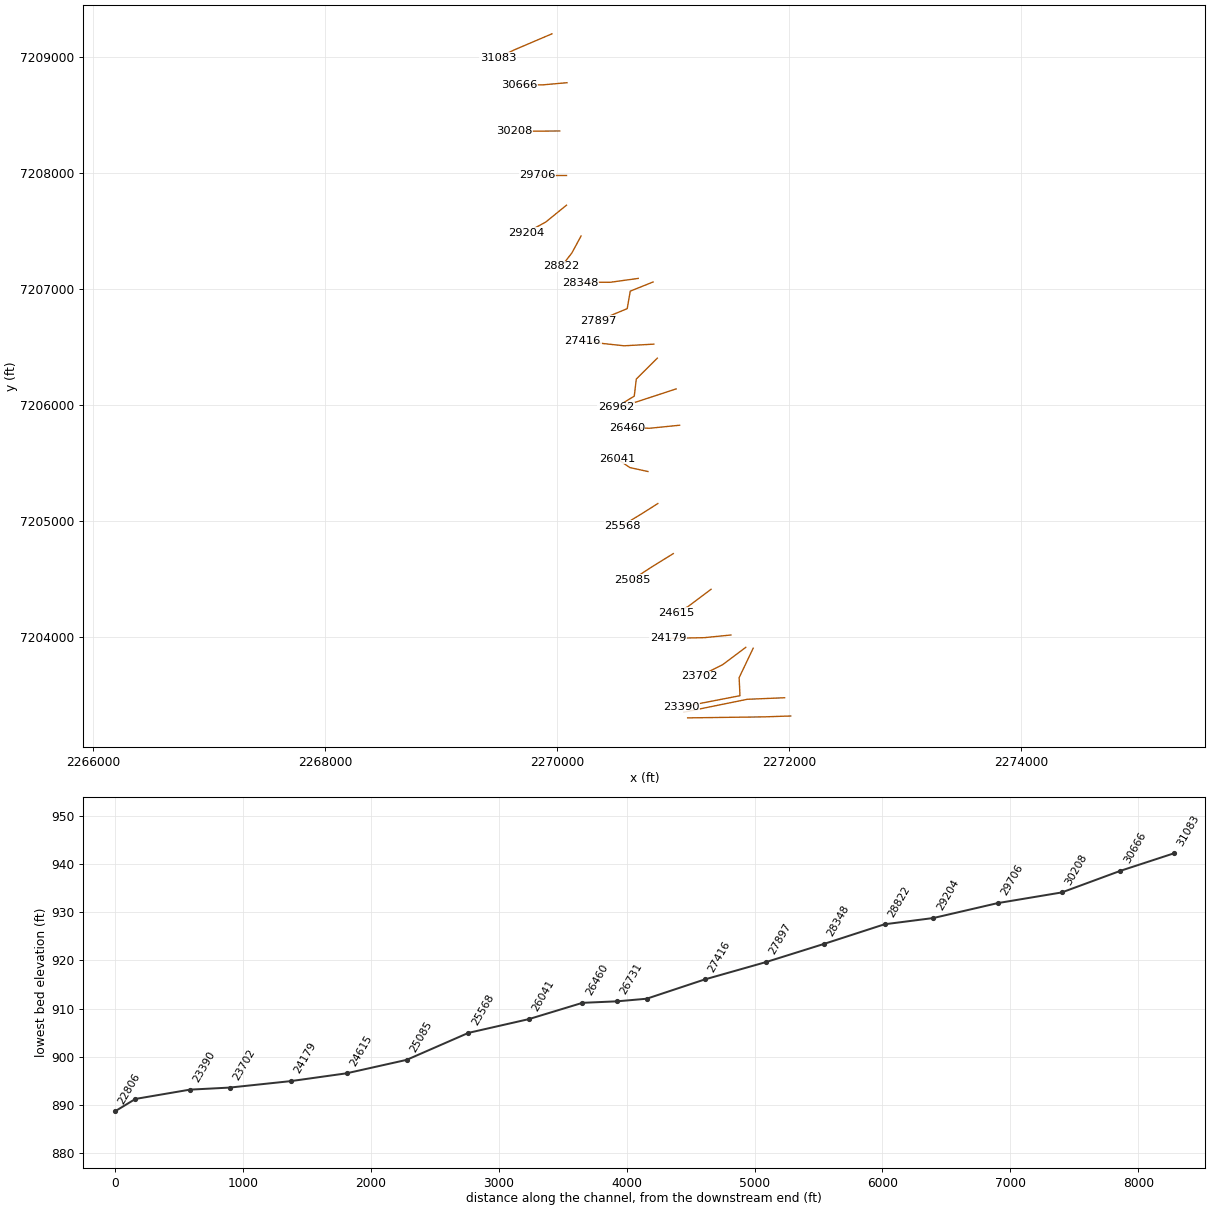
HEC-RAS study UDS St 21.prj: UDS St 21 Base Level Engineering

--- UDS St 21.g01 (geometry) --- (continued)

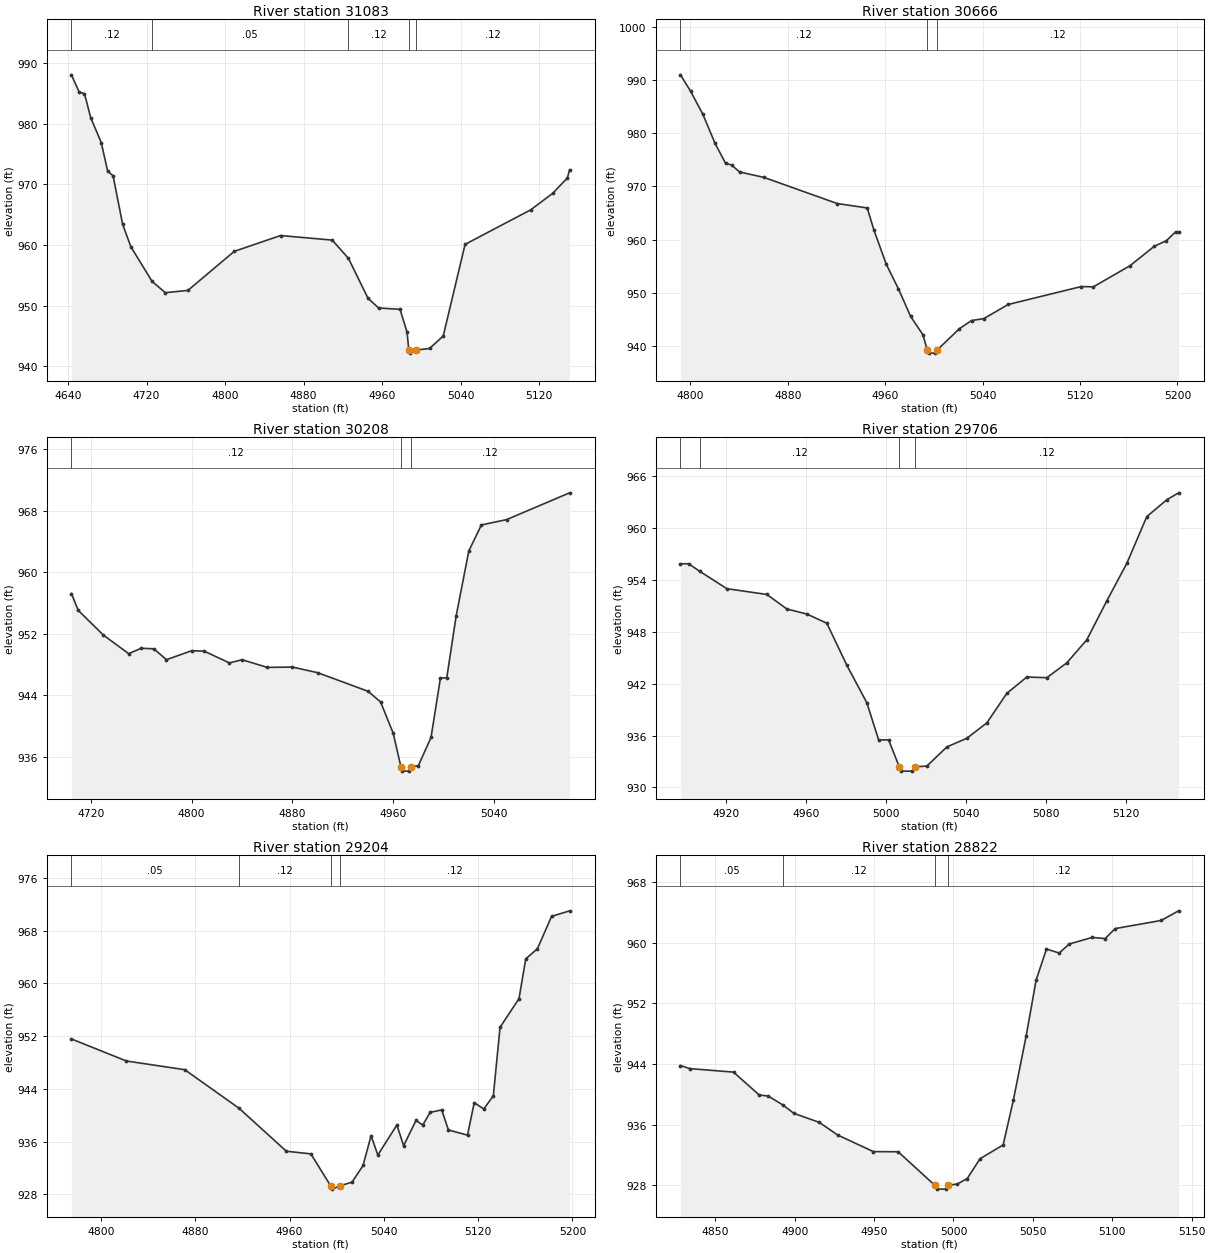
Type RM Length L Ch R = 1 ,31083   ,417,417,417
BEGIN DESCRIPTION:
UDS St 21 65.0
END DESCRIPTION:
XS GIS Cut Line= 3
        2269957.      7209199.91        2269629.        7209060.
      2269493.46       7208993.2
#Sta/Elev= 30
  4643.4  988.07  4651.3  985.21  4656.7  984.97    4663  981.02  4673.8   976.9
  4680.3  972.19  4685.8  971.44  4695.6  963.41    4704  959.72  4725.6  954.02
  4739.1  952.16  4762.1  952.54  4809.3  958.97  4856.5  961.58  4909.2  960.83
  4925.7  957.82  4945.6  951.26  4956.4  949.64  4978.3  949.42  4985.5  945.62
  4987.2   942.7  4988.3   942.2  4994.7   942.7  5008.4  942.97  5022.3  945.02
  5044.6  960.13  5111.5  965.82  5133.8  968.53  5148.8  971.06  5151.1  972.42
#Mann= 5 ,-1 , 0
  4643.4     .12       0  4725.6     .05       0  4925.7     .12       0
  4987.2     .07       0  4994.7     .12       0
#XS Ineff= 2 , 0
       0  4856.5  961.58               0
Permanent Ineff=
       F       F
Bank Sta=4987.2,4994.7
XS Rating Curve= 0 ,0
Exp/Cntr=0.3,0.1

Type RM Length L Ch R = 1 ,30666   ,458,458,458
BEGIN DESCRIPTION:
UDS St 21 64.0
END DESCRIPTION:
XS GIS Cut Line= 3
      2270087.28      7208778.62        2269879.        7208760.
      2269679.02        7208760.
#Sta/Elev= 30
  4791.9  991.05  4800.2  987.96  4810.3  983.61  4820.3  978.13  4828.9  974.39
    4834  974.03  4840.4  972.74  4860.5  971.71  4920.7  966.78  4945.3  965.95
  4950.8  961.77  4960.9  955.34  4970.9   950.7  4980.9  945.51    4991  942.04
  4994.7  939.08  4995.9  938.58  5001.2  938.58  5002.3  939.08    5021  943.19
    5031  944.73    5041  945.08    5061  947.75    5121  951.13    5131  951.08
    5161  955.05    5181  958.72    5191  959.79  5198.5  961.45    5201  961.45
#Mann= 3 ,-1 , 0
  4791.9     .12       0  4994.7     .07       0  5002.3     .12       0
Bank Sta=4994.7,5002.3
XS Rating Curve= 0 ,0
Exp/Cntr=0.3,0.1

Type RM Length L Ch R = 1 ,30208   ,502,502,502
BEGIN DESCRIPTION:
UDS St 21 63.0
END DESCRIPTION:
XS GIS Cut Line= 3
      2270024.36      7208362.44        2269729.        7208360.
      2269628.97        7208360.
#Sta/Elev= 30
  4704.6  957.22    4710  955.03    4730  951.81    4750   949.4    4760   950.1
    4770  950.03    4780  948.61    4800  949.78    4810  949.72    4830  948.19
    4840  948.61    4860  947.61    4880  947.65    4900  946.92    4940   944.5
    4950   943.1    4960  939.03  4966.2   934.6  4967.3   934.1  4972.6   934.1
  4973.8   934.6    4980  934.83    4990  938.48  4997.5  946.24  5002.5  946.24
    5010  954.35    5020  962.77    5030  966.16    5050  966.85    5100  970.34
#Mann= 3 ,-1 , 0
  4704.6     .12       0  4966.2     .07       0  4973.8     .12       0
Bank Sta=4966.2,4973.8
XS Rating Curve= 0 ,0
Exp/Cntr=0.3,0.1

Type RM Length L Ch R = 1 ,29706   ,502,502,502
BEGIN DESCRIPTION:
UDS St 21 62.0
END DESCRIPTION:
XS GIS Cut Line= 3
      2270082.21      7207982.32      2269982.16      7207982.32
      2269833.11      7207982.32
#Sta/Elev= 30
  4897.4  955.87  4901.5  955.87  4907.1  954.99  4920.6  952.99  4940.6  952.32
  4950.6  950.64  4960.6  950.06  4970.6  948.99  4980.6  944.13  4990.6  939.79
  4996.5  935.49  5001.5  935.49  5006.8  932.38  5007.9  931.88  5013.3  931.88
  5014.5  932.38  5020.6  932.46  5030.6  934.68  5040.6  935.68  5050.6  937.46
  5060.6  940.88  5070.6  942.77  5080.6  942.69  5090.6  944.41  5100.6  947.08
  5110.6  951.59  5120.6  955.92  5130.6  961.33  5140.6  963.28  5146.5  964.08
#Mann= 4 ,-1 , 0
  4897.4     .05       0  4907.1     .12       0  5006.8     .07       0
  5014.5     .12       0
Bank Sta=5006.8,5014.5
XS Rating Curve= 0 ,0
Exp/Cntr=0.3,0.1

Type RM Length L Ch R = 1 ,29204   ,382,382,382
BEGIN DESCRIPTION:
UDS St 21 61.0
END DESCRIPTION:
XS GIS Cut Line= 3
      2270082.69      7207722.31      2269904.02       7207576.9
      2269735.03      7207485.26
#Sta/Elev= 30
    4775  951.57  4821.6  948.23  4871.1  946.91  4917.1  941.07  4957.3  934.54
  4978.1  934.14  4994.9  929.29  4996.1  928.79  5002.9  929.29  5013.1  929.86
  5022.4  932.38  5029.2  936.91  5034.9  933.96  5051.1  938.52  5056.8  935.37
  5067.3  939.22    5073  938.51  5079.3  940.43  5089.1  940.81  5094.8  937.77
    5111  936.98  5116.7  941.91  5124.8  940.95  5132.9  942.94  5138.6  953.34
  5154.7   957.7  5160.4  963.72  5170.3  965.26  5182.3  970.17  5197.6  971.01
#Mann= 4 ,-1 , 0
    4775     .05       0  4917.1     .12       0  4994.9     .07       0
  5002.9     .12       0
Bank Sta=4994.9,5002.9
XS Rating Curve= 0 ,0
Exp/Cntr=0.3,0.1

Type RM Length L Ch R = 1 ,28822   ,474,474,474
BEGIN DESCRIPTION:
UDS St 21 60.0
END DESCRIPTION:
XS GIS Cut Line= 3
      2270208.59      7207456.86        2270129.        7207310.
      2270038.78      7207194.38
#Sta/Elev= 30
  4828.1   943.8    4834  943.39  4861.5  942.93  4877.7  939.91  4883.4  939.77
  4892.7  938.58  4899.6  937.48  4915.5   936.3  4927.1  934.63  4949.6  932.44
  4965.2  932.42  4988.3  927.99  4989.5  927.49  4995.1  927.49  4996.3  927.99
  5002.4  928.16  5008.7  928.89  5016.8  931.51  5031.3  933.32  5037.7   939.2
  5045.8   947.7  5052.1   955.1  5058.6  959.17  5066.6  958.64  5072.9  959.83
  5087.4   960.7  5095.5  960.55  5101.9  961.87  5130.8  962.94  5141.8  964.21
#Mann= 4 ,-1 , 0
  4828.1     .05       0  4892.7     .12       0  4988.3     .07       0
  4996.3     .12       0
Bank Sta=4988.3,4996.3
XS Rating Curve= 0 ,0
Exp/Cntr=0.3,0.1

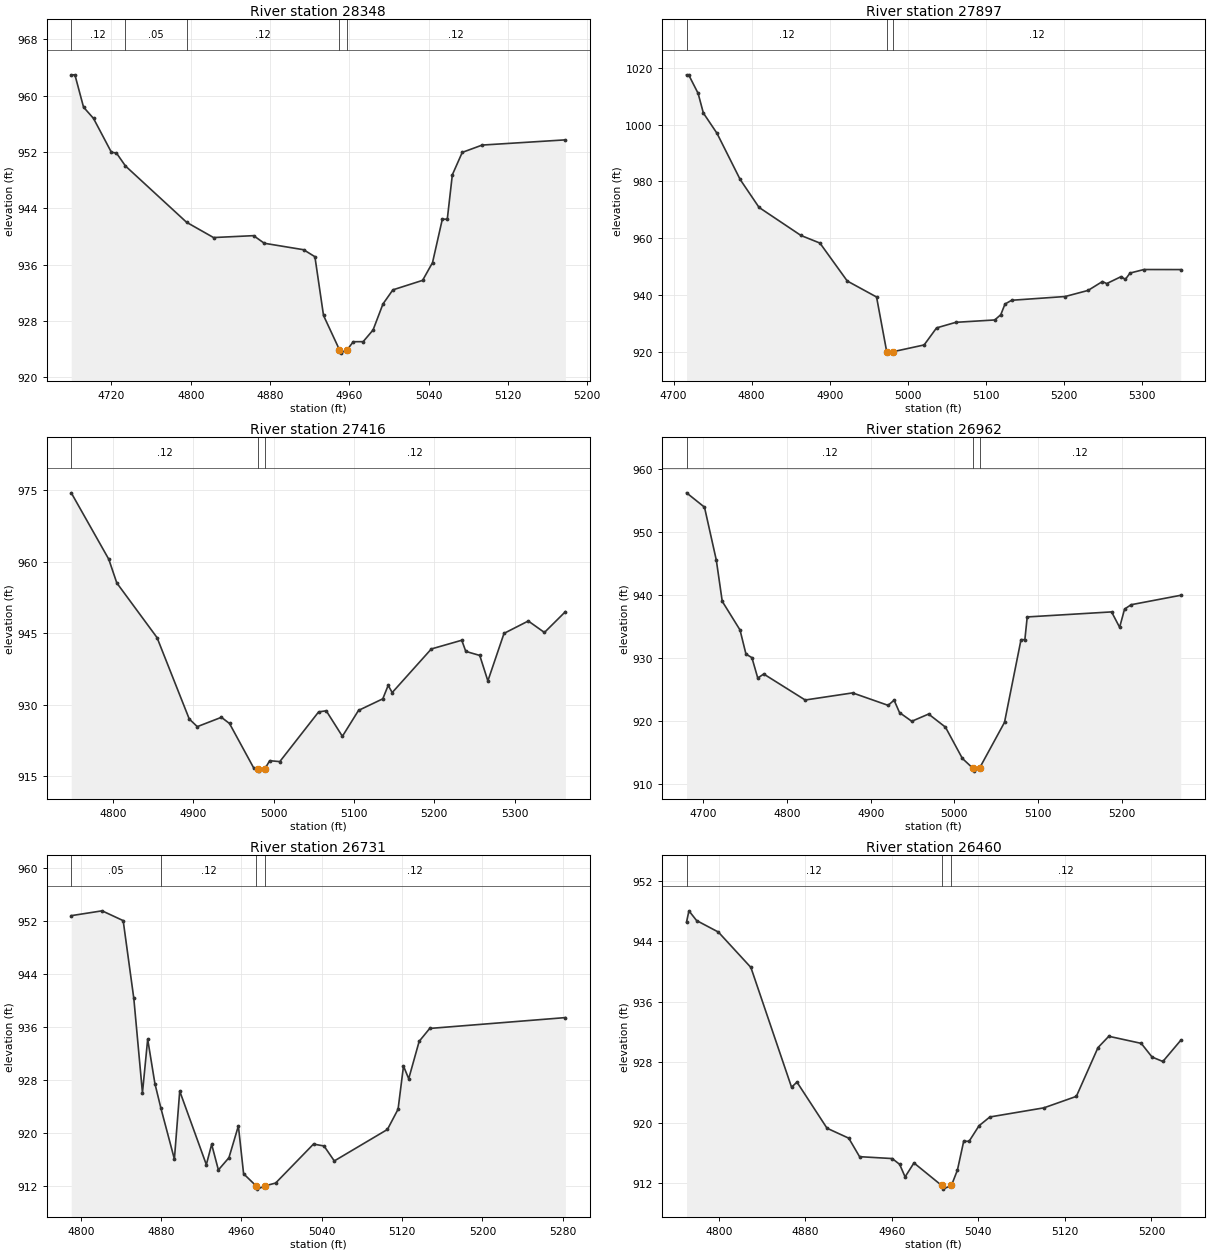
Type RM Length L Ch R = 1 ,28348   ,451,451,451
BEGIN DESCRIPTION:
UDS St 21 59.0
END DESCRIPTION:
XS GIS Cut Line= 4
      2270701.31      7207090.91      2270457.68      7207057.44
      2270324.12      7207057.91      2270205.17      7207049.87
#Sta/Elev= 30
  4679.4  962.95  4683.1  962.95  4691.8  958.36  4701.9  956.75  4719.9  951.95
    4725  951.84  4734.1     950  4795.8     942    4823  939.83  4863.4   940.1
  4874.2  939.02  4913.9   938.1  4925.3  937.11    4934  928.76    4950  923.91
  4951.2  923.41    4958  923.91    4964  925.03    4974  925.04    4984   926.7
    4994   930.4    5004   932.4    5034  933.75    5044  936.27  5053.9  942.44
  5058.9  942.44    5064  948.75    5074  951.93  5094.1  952.97  5178.1  953.71
#Mann= 5 ,-1 , 0
  4679.4     .12       0  4734.1     .05       0  4795.8     .12       0
    4950     .07       0    4958     .12       0
Bank Sta=4950,4958
XS Rating Curve= 0 ,0
Exp/Cntr=0.3,0.1

Type RM Length L Ch R = 1 ,27897   ,481,481,481
BEGIN DESCRIPTION:
UDS St 21 58.0
END DESCRIPTION:
XS GIS Cut Line= 4
      2270828.99        7207060.      2270632.62      7206981.16
      2270606.46      7206830.27      2270359.21      7206727.52
#Sta/Elev= 30
  4716.7 1017.49  4719.4 1017.49  4731.5 1010.97  4738.2 1004.07  4755.7  996.92
  4785.3  980.71  4809.5  970.88  4863.2  961.01  4887.4  958.35  4922.4  945.01
  4959.9  939.39  4972.9  920.16  4974.2  919.66    4981  920.16  5020.8  922.54
  5036.7  928.53  5061.4  930.49  5111.2  931.32  5118.9  933.17  5124.3  936.91
  5132.8  938.24  5201.3  939.56  5230.6   941.7    5249  944.83  5254.5  944.11
  5272.9  946.55  5278.3  945.58  5284.4  947.81  5302.2  949.05  5349.2  949.03
#Mann= 3 ,-1 , 0
  4716.7     .12       0  4972.9     .07       0    4981     .12       0
Bank Sta=4972.9,4981
XS Rating Curve= 0 ,0
Exp/Cntr=0.3,0.1

Type RM Length L Ch R = 1 ,27416   ,454,454,454
BEGIN DESCRIPTION:
UDS St 21 57.0
END DESCRIPTION:
XS GIS Cut Line= 3
      2270835.66       7206524.2        2270579.        7206510.
      2270223.04      7206548.62
#Sta/Elev= 30
  4748.1  974.47  4794.8  960.53  4804.8  955.55  4854.9  944.07    4895  926.98
    4905  925.38    4935  927.34  4945.1  926.04  4975.1  916.74    4981  916.54
  4982.2  916.04  4989.2  916.54  4995.1  918.23  5007.7  918.04    5056  928.47
  5065.5  928.71  5085.6  923.35  5105.7  928.79  5135.9  931.22  5142.6  934.05
  5147.6  932.53  5196.3  941.69  5234.2  943.52  5239.2  941.18  5256.6  940.33
  5266.7  934.98  5286.8  944.96    5317  947.56  5337.1  945.15  5363.2  949.52
#Mann= 3 ,-1 , 0
  4748.1     .12       0    4981     .07       0  4989.2     .12       0
Bank Sta=4981,4989.2
XS Rating Curve= 0 ,0
Exp/Cntr=0.3,0.1

Type RM Length L Ch R = 1 ,26962   ,231,231,231
BEGIN DESCRIPTION:
UDS St 21 56.0
END DESCRIPTION:
XS GIS Cut Line= 4
      2270865.98      7206403.26      2270684.77      7206223.22
      2270667.29      7206075.87      2270508.47      7205979.12
#Sta/Elev= 30
  4680.3  956.26  4701.7  953.98  4715.8  945.58  4722.9  939.02  4744.1  934.47
  4751.2  930.64  4758.3  930.07  4765.3  926.83  4772.4  927.47  4821.9  923.34
  4878.5  924.47  4920.9  922.49    4928  923.32  4934.5  921.34  4949.1  919.96
  4969.2  921.11  4989.3  919.03  5009.5  914.06  5021.7  912.54  5022.9  912.04
  5030.1  912.54  5059.8  919.79  5079.5  932.93  5084.1  932.93  5086.9  936.54
  5187.6  937.34  5197.2  934.89  5203.1  937.79  5210.9  938.48  5270.1  939.98
#Mann= 3 ,-1 , 0
  4680.3     .12       0  5021.7     .07       0  5030.1     .12       0
Bank Sta=5021.7,5030.1
XS Rating Curve= 0 ,0
Exp/Cntr=0.3,0.1

Type RM Length L Ch R = 1 ,26731   ,271,271,271
BEGIN DESCRIPTION:
UDS St 21 55.1
END DESCRIPTION:
XS GIS Cut Line= 2
      2271028.17      7206138.13      2270560.67      7205984.81
#Sta/Elev= 30
  4790.6  952.84  4821.3  953.57  4842.3  952.09  4852.9  940.32  4861.5  926.06
  4866.7  934.17  4873.9  927.45  4879.9  923.71  4893.3  916.04  4898.6  926.32
  4925.1   915.2  4930.4  918.27  4937.1   914.4  4947.6  916.25    4957  921.05
  4962.2  913.82  4974.6     912  4975.9   911.5  4983.7     912  4994.1  912.42
  5031.8  918.31  5042.3  918.02  5052.5  915.76  5105.4  920.52    5116  923.58
  5121.4   930.1  5126.6  928.19    5137  933.84  5147.5  935.79  5282.6  937.43
#Mann= 4 ,-1 , 0
  4790.6     .05       0  4879.9     .12       0  4974.6     .07       0
  4983.7     .12       0
Bank Sta=4974.6,4983.7
XS Rating Curve= 0 ,0
Exp/Cntr=0.3,0.1

Type RM Length L Ch R = 1 ,26460   ,419,419,419
BEGIN DESCRIPTION:
UDS St 21 55.0
END DESCRIPTION:
XS GIS Cut Line= 3
      2271058.22      7205825.01      2270802.35      7205799.14
      2270602.53      7205801.21
#Sta/Elev= 30
  4770.1  946.58  4772.3  948.06  4779.4  946.77  4799.5  945.25  4829.6  940.56
  4867.2  924.69  4872.2  925.37    4900  919.26  4920.1  917.94  4930.1  915.49
  4960.3  915.24  4967.2  914.47  4972.2  912.81  4980.4  914.66  5005.9  911.69
  5007.3  911.19  5015.1  911.69  5020.6  913.71  5026.4  917.53  5031.4  917.53
  5040.6  919.59  5050.6  920.75  5100.6  921.96  5130.6  923.48  5150.6  929.94
  5160.6  931.44  5190.6   930.5  5200.6  928.69  5210.6   928.1  5227.1   930.9
#Mann= 3 ,-1 , 0
  4770.1     .12       0  5005.9     .07       0  5015.1     .12       0
Bank Sta=5005.9,5015.1
XS Rating Curve= 0 ,0
Exp/Cntr=0.3,0.1

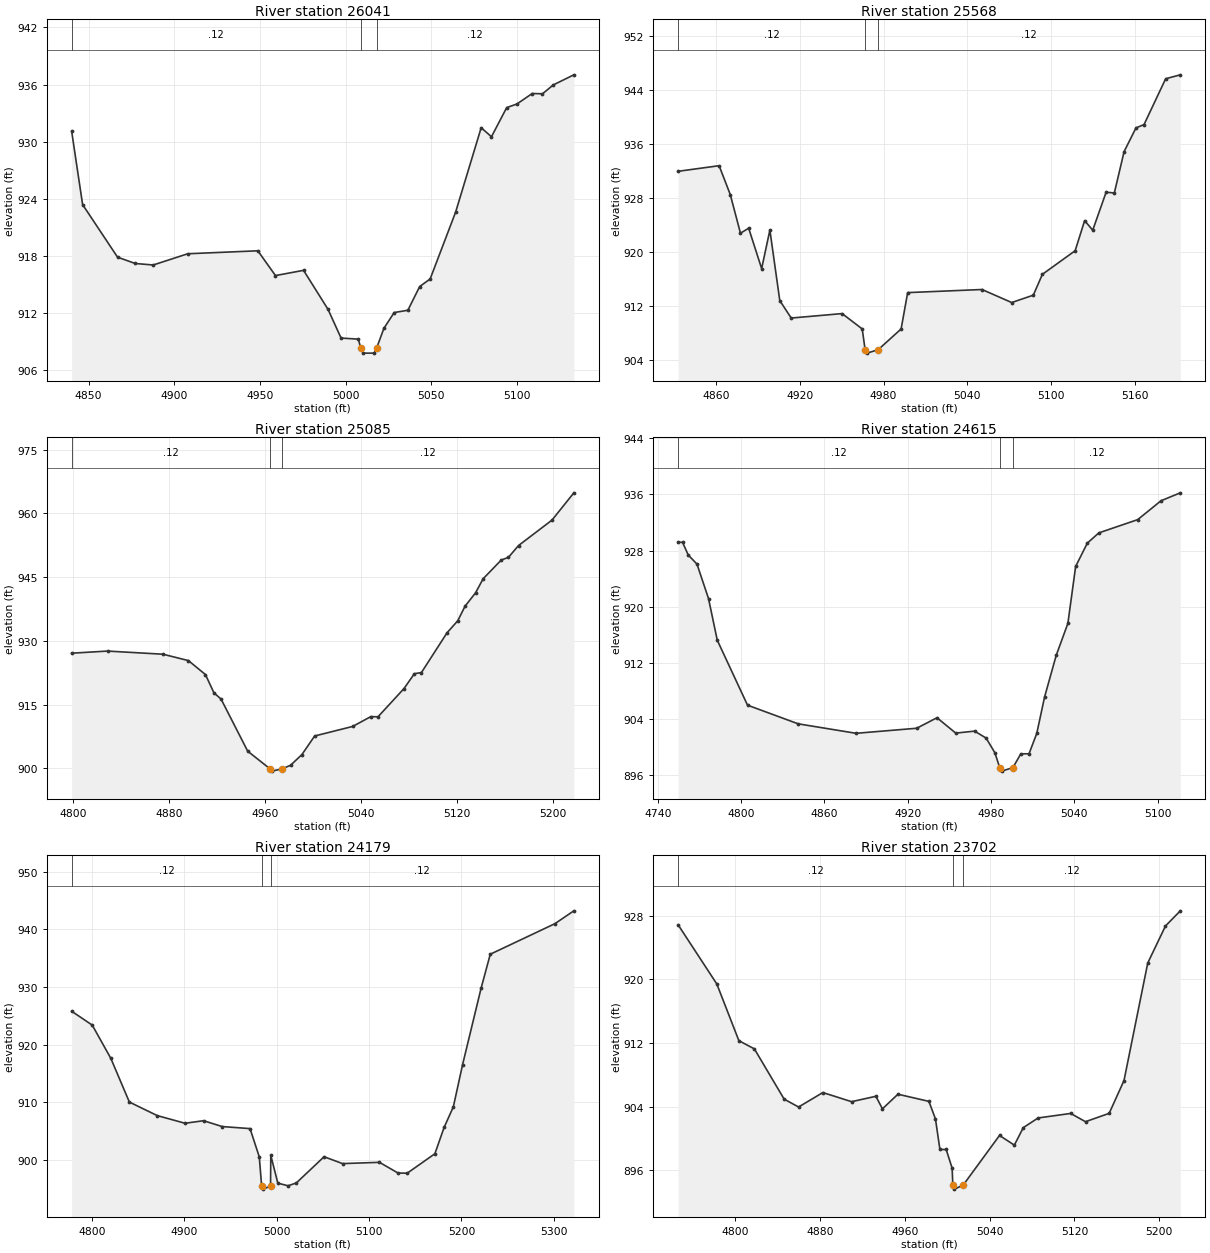
Type RM Length L Ch R = 1 ,26041   ,473,473,473
BEGIN DESCRIPTION:
UDS St 21 54.0
END DESCRIPTION:
XS GIS Cut Line= 3
      2270785.23       7205425.9        2270629.        7205460.
      2270519.14      7205535.49
#Sta/Elev= 30
  4840.1   931.1  4846.5   923.4  4866.9  917.88  4877.2  917.22  4887.7  917.06
  4907.9  918.24  4948.8  918.55  4959.1  915.95  4975.5   916.5  4989.8   912.4
  4997.4  909.39  5007.5  909.28  5008.9  908.31  5010.2  907.81  5016.8  907.81
  5018.1  908.31  5022.4  910.41  5028.4  912.07  5036.4  912.31  5043.3   914.8
  5049.4  915.59  5064.3  922.62  5079.2  931.47  5085.2  930.52  5094.1  933.58
  5100.1  933.96    5109  935.06    5115  935.03  5121.3  935.96  5133.3  937.02
#Mann= 3 ,-1 , 0
  4840.1     .12       0  5008.9     .07       0  5018.1     .12       0
Bank Sta=5008.9,5018.1
XS Rating Curve= 0 ,0
Exp/Cntr=0.3,0.1

Type RM Length L Ch R = 1 ,25568   ,483,483,483
BEGIN DESCRIPTION:
UDS St 21 53.0
END DESCRIPTION:
XS GIS Cut Line= 3
      2270870.56      7205149.64        2270729.        7205060.
      2270564.59      7204959.77
#Sta/Elev= 30
  4832.7   931.9  4862.1  932.73  4870.1  928.45  4877.4  922.73  4883.3  923.46
  4892.6  917.48  4898.5  923.19  4905.6  912.74  4913.8  910.15  4950.3  910.81
  4964.7  908.54  4966.8  905.45  4968.1  904.95  4976.1  905.45  4992.6  908.53
  4997.3  913.92  5050.6  914.38  5071.9  912.45  5087.4  913.54  5093.9  916.63
  5117.4  920.13  5124.2  924.59    5130  923.17  5139.6   928.8  5145.5  928.69
  5152.5  934.82    5161  938.33  5166.8  938.83  5182.3  945.62  5192.8   946.2
#Mann= 3 ,-1 , 0
  4832.7     .12       0  4966.8     .07       0  4976.1     .12       0
Bank Sta=4966.8,4976.1
XS Rating Curve= 0 ,0
Exp/Cntr=0.3,0.1

Type RM Length L Ch R = 1 ,25085   ,470,470,470
BEGIN DESCRIPTION:
UDS St 21 52.0
END DESCRIPTION:
XS GIS Cut Line= 3
      2271003.82      7204717.99        2270829.        7204610.
      2270650.34      7204494.01
#Sta/Elev= 30
  4798.9  927.11  4828.8  927.61    4875  926.87  4896.2  925.37  4910.4  922.08
  4917.5  917.77  4923.4  916.32  4945.6  904.05  4964.4  899.85  4965.7  899.35
  4973.9  899.85  4981.3  900.72  4990.8  903.25  5001.4  907.62  5033.1  909.87
  5048.2  912.18  5054.2  912.14  5075.9   918.8  5084.5  922.28  5090.4  922.56
  5111.7   931.9  5120.7  934.76  5126.7  938.16  5135.5  941.32  5141.8  944.63
  5156.9  949.04  5162.9  949.67  5171.3  952.45  5199.2  958.44  5217.4  964.86
#Mann= 3 ,-1 , 0
  4798.9     .12       0  4964.4     .07       0  4973.9     .12       0
Bank Sta=4964.4,4973.9
XS Rating Curve= 0 ,0
Exp/Cntr=0.3,0.1

Type RM Length L Ch R = 1 ,24615   ,436,436,436
BEGIN DESCRIPTION:
UDS St 21 51.0
END DESCRIPTION:
XS GIS Cut Line= 3
      2271329.03      7204410.02        2271129.        7204260.
      2271029.04      7204210.02
#Sta/Elev= 30
  4754.6  929.17  4757.8  929.17  4761.9  927.36  4768.2  926.06  4776.5  921.15
  4782.8  915.22  4804.6  905.96  4841.1   903.3  4882.8  901.95  4926.5  902.67
  4941.1  904.17  4954.6  901.98  4968.2  902.26  4976.5  901.27  4982.8  899.18
  4986.3  897.06  4987.7  896.56  4995.8  897.06  5001.5  899.03  5007.4  899.03
    5013  901.94  5018.6  907.11    5027  913.06  5035.4  917.61    5041  925.73
  5049.4  929.05  5057.7  930.51  5085.7   932.4  5102.5  935.09  5116.4  936.22
#Mann= 3 ,-1 , 0
  4754.6     .12       0  4986.3     .07       0  4995.8     .12       0
Bank Sta=4986.3,4995.8
XS Rating Curve= 0 ,0
Exp/Cntr=0.3,0.1

Type RM Length L Ch R = 1 ,24179   ,477,477,477
BEGIN DESCRIPTION:
UDS St 21 50.0
END DESCRIPTION:
XS GIS Cut Line= 3
      2271501.23      7204016.22      2271272.05      7203993.28
      2270958.54      7203986.85
#Sta/Elev= 30
  4777.8  925.81  4800.1   923.4  4820.2  917.64  4840.3  910.05  4870.5   907.7
  4900.6  906.37  4920.7  906.81  4940.8   905.8    4971  905.44    4981  900.55
  4983.6  895.44    4985  894.94  4993.2  895.44  4993.5  900.79  5001.1  895.98
  5012.2  895.52  5021.2  896.02  5051.2  900.56  5071.2  899.37  5111.2  899.59
  5131.2  897.74  5141.2   897.7  5171.2  901.08  5181.2  905.65  5191.2  909.22
  5201.2  916.54  5221.2  929.77  5231.2   935.7  5301.2     941  5321.7  943.23
#Mann= 3 ,-1 , 0
  4777.8     .12       0  4983.6     .07       0  4993.2     .12       0
Bank Sta=4983.6,4993.2
XS Rating Curve= 0 ,0
Exp/Cntr=0.3,0.1

Type RM Length L Ch R = 1 ,23702   ,312,312,312
BEGIN DESCRIPTION:
UDS St 21 49.0
END DESCRIPTION:
XS GIS Cut Line= 3
      2271629.01      7203910.01        2271429.        7203760.
      2271229.02      7203660.01
#Sta/Elev= 30
  4746.3  926.88  4782.8  919.43  4803.6  912.29  4818.2  911.26  4846.3  904.93
  4859.9  903.94  4882.8  905.76  4909.9  904.61  4932.8  905.29    4939  903.71
  4953.6  905.55  4982.8  904.65    4989  902.44  4993.2  898.59  4999.1  898.59
  5004.7  896.25  5005.4   894.1  5006.8   893.6  5015.1   894.1  5049.4  900.36
  5063.4  899.14  5071.8  901.34  5085.8  902.56  5116.5  903.13  5130.5  902.09
  5152.8  903.14  5166.8  907.27  5189.2  922.07  5205.9  926.73  5219.9  928.64
#Mann= 3 ,-1 , 0
  4746.3     .12       0  5005.4     .07       0  5015.1     .12       0
Bank Sta=5005.4,5015.1
XS Rating Curve= 0 ,0
Exp/Cntr=0.3,0.1

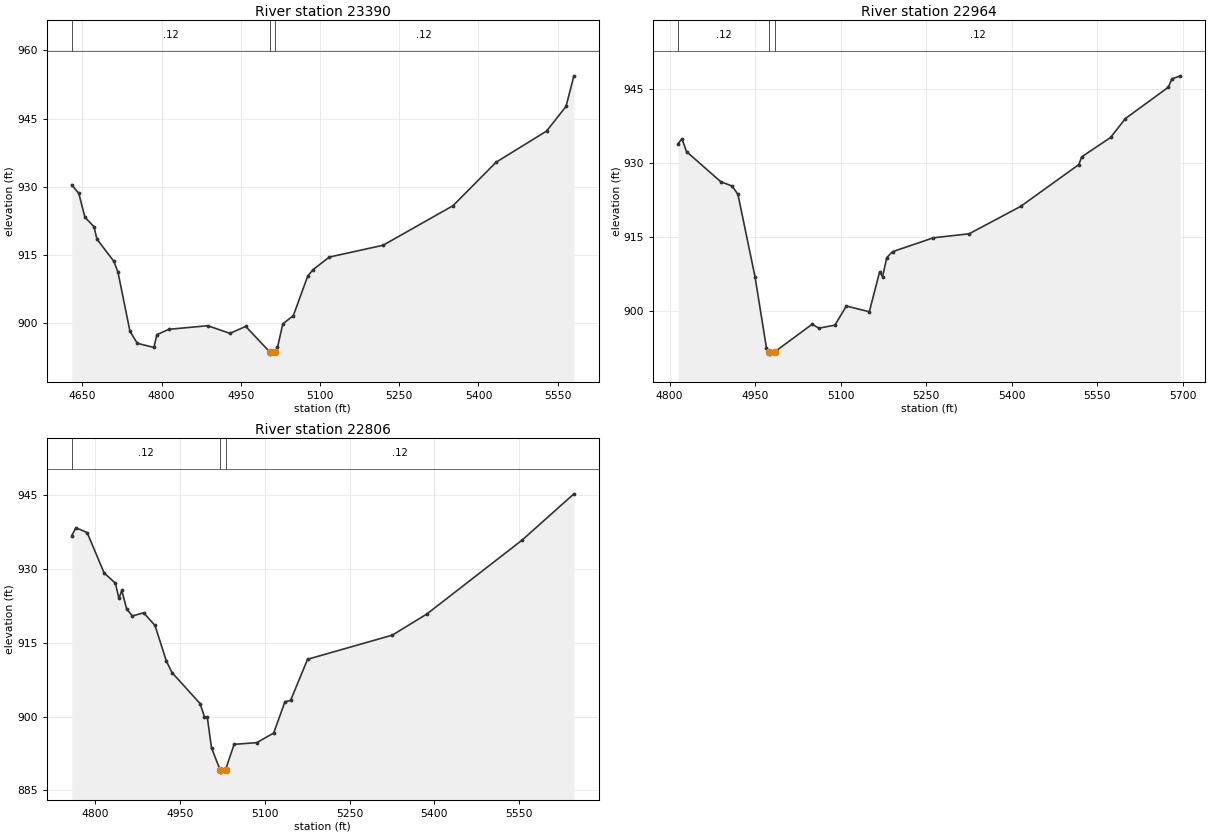
Type RM Length L Ch R = 1 ,23390   ,426,426,426
BEGIN DESCRIPTION:
UDS St 21 48.0
END DESCRIPTION:
XS GIS Cut Line= 4
      2271692.53      7203902.04      2271571.51      7203648.06
      2271578.82      7203492.74      2271074.35      7203394.95
#Sta/Elev= 30
    4630  930.41  4643.3  928.53  4654.9  923.28  4672.1  921.21  4677.6  918.48
  4709.8  913.56  4717.5  911.18  4740.2  898.18  4754.1  895.55  4785.6  894.64
  4791.1  897.45  4813.8  898.63  4887.4  899.42  4929.4  897.74  4959.4  899.26
  5004.7  893.67    5006  893.17  5014.4  893.67  5019.5  894.63  5029.5  899.81
  5049.5  901.64  5076.8  910.36    5087  911.77  5117.6  914.52  5219.4  917.12
  5351.9  925.83  5433.4  935.39    5529  942.24  5565.8  947.67  5580.7  954.39
#Mann= 3 ,-1 , 0
    4630     .12       0  5004.7     .07       0  5014.4     .12       0
Bank Sta=5004.7,5014.4
XS Rating Curve= 0 ,0
Exp/Cntr=0.3,0.1

Type RM Length L Ch R = 1 ,22964   ,158,158,158
BEGIN DESCRIPTION:
UDS St 21 47.1
END DESCRIPTION:
XS GIS Cut Line= 3
      2271963.68      7203475.14      2271641.51      7203461.71
      2271094.52      7203350.61
#Sta/Elev= 30
  4815.2  933.96  4821.8  934.94  4829.9  932.33  4889.9  926.22    4910  925.34
    4920  923.65    4950  906.91    4970  892.53  4975.1  891.74  4976.5  891.24
  4984.9  891.74  5050.1   897.3  5061.9  896.51  5090.1  897.12  5110.1     901
  5150.4  899.84  5168.5  907.95  5173.6  906.94    5181  910.82  5191.2  912.03
  5262.7  914.84  5325.5  915.66  5415.7  921.21  5517.8   929.7  5522.9  931.27
  5573.6  935.21  5599.4  939.03  5674.8   945.4    5681  947.08  5695.8  947.71
#Mann= 3 ,-1 , 0
  4815.2     .12       0  4975.1     .07       0  4984.9     .12       0
Bank Sta=4975.1,4984.9
XS Rating Curve= 0 ,0
Exp/Cntr=0.3,0.1

Type RM Length L Ch R = 1 ,22806   ,138,138,138
BEGIN DESCRIPTION:
UDS St 21 47.0
END DESCRIPTION:
XS GIS Cut Line= 3
      2272016.17      7203317.78        2271779.        7203310.
      2271127.66      7203301.58
#Sta/Elev= 30
  4758.4  936.78  4765.6  938.41  4785.6  937.43  4815.6  929.23  4835.6  927.13
  4841.9  924.03  4846.9  925.66  4855.6  921.86  4865.6  920.46  4885.6   921.1
  4905.7  918.53  4925.7  911.32  4935.7  908.95  4985.7  902.61  4993.2  899.93
  4998.2  899.93  5005.7  893.61  5020.8  889.19  5022.2  888.69  5030.6  889.19
  5045.7  894.34  5085.7  894.69  5115.7  896.64  5135.7  903.01  5145.7  903.28
  5175.7  911.65  5325.7  916.56  5386.7  920.85  5555.7  935.92  5647.1  945.31
#Mann= 3 ,-1 , 0
  4758.4     .12       0  5020.8     .07       0  5030.6     .12       0
Bank Sta=5020.8,5030.6
XS Rating Curve= 0 ,0
Exp/Cntr=0.3,0.1