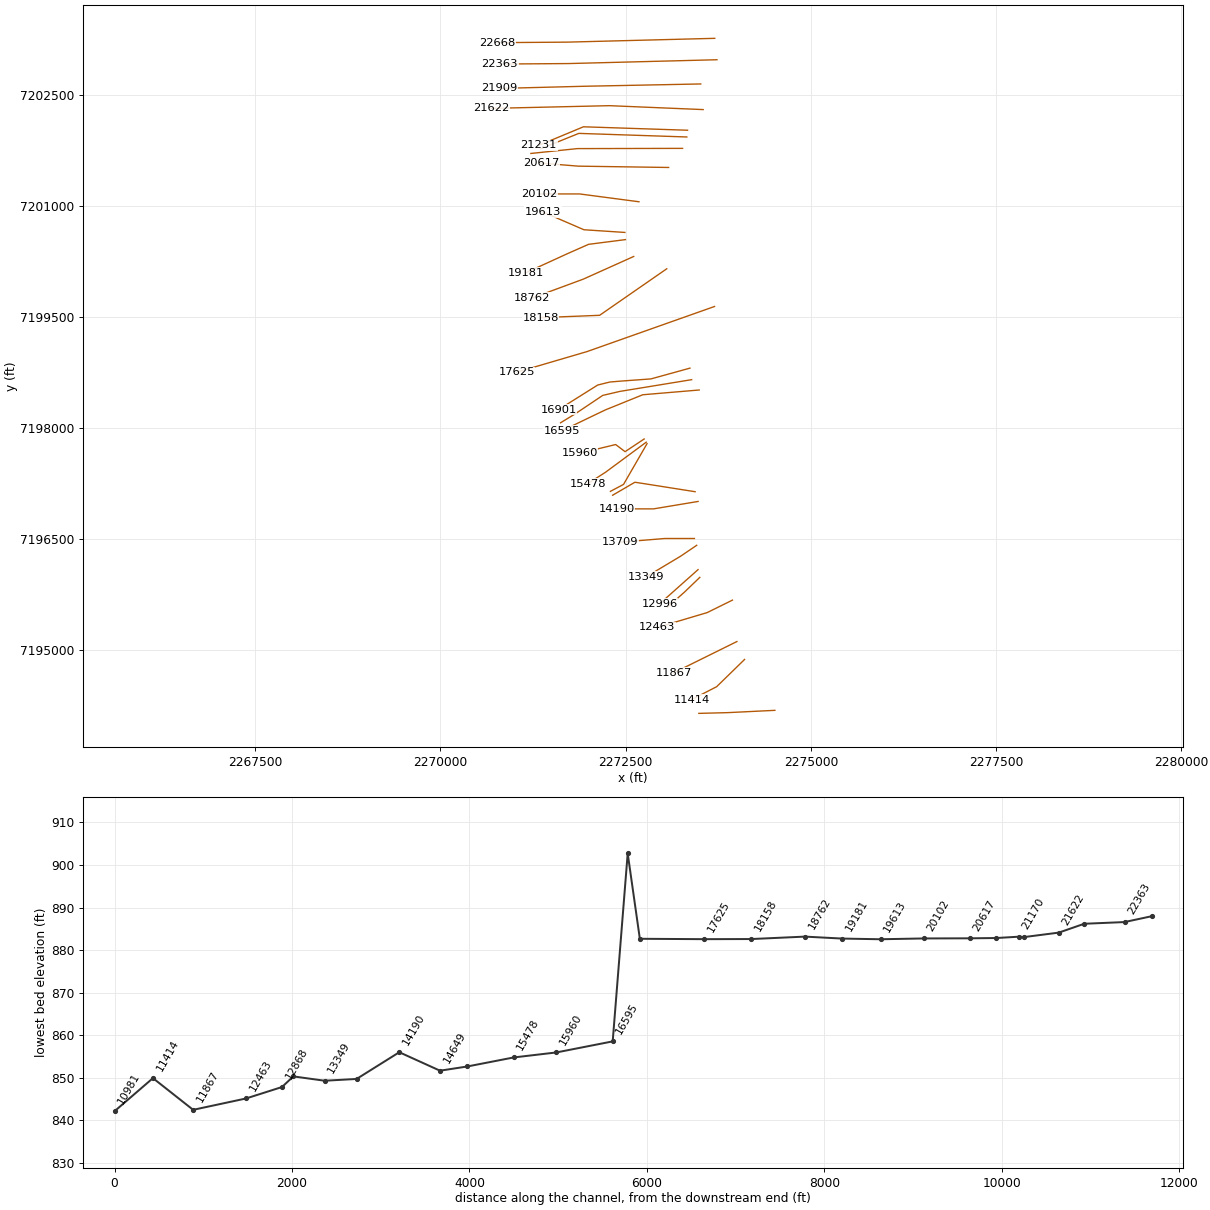
HEC-RAS study UDS St 21.prj: UDS St 21 Base Level Engineering

--- UDS St 21.g01 (geometry) --- (continued)

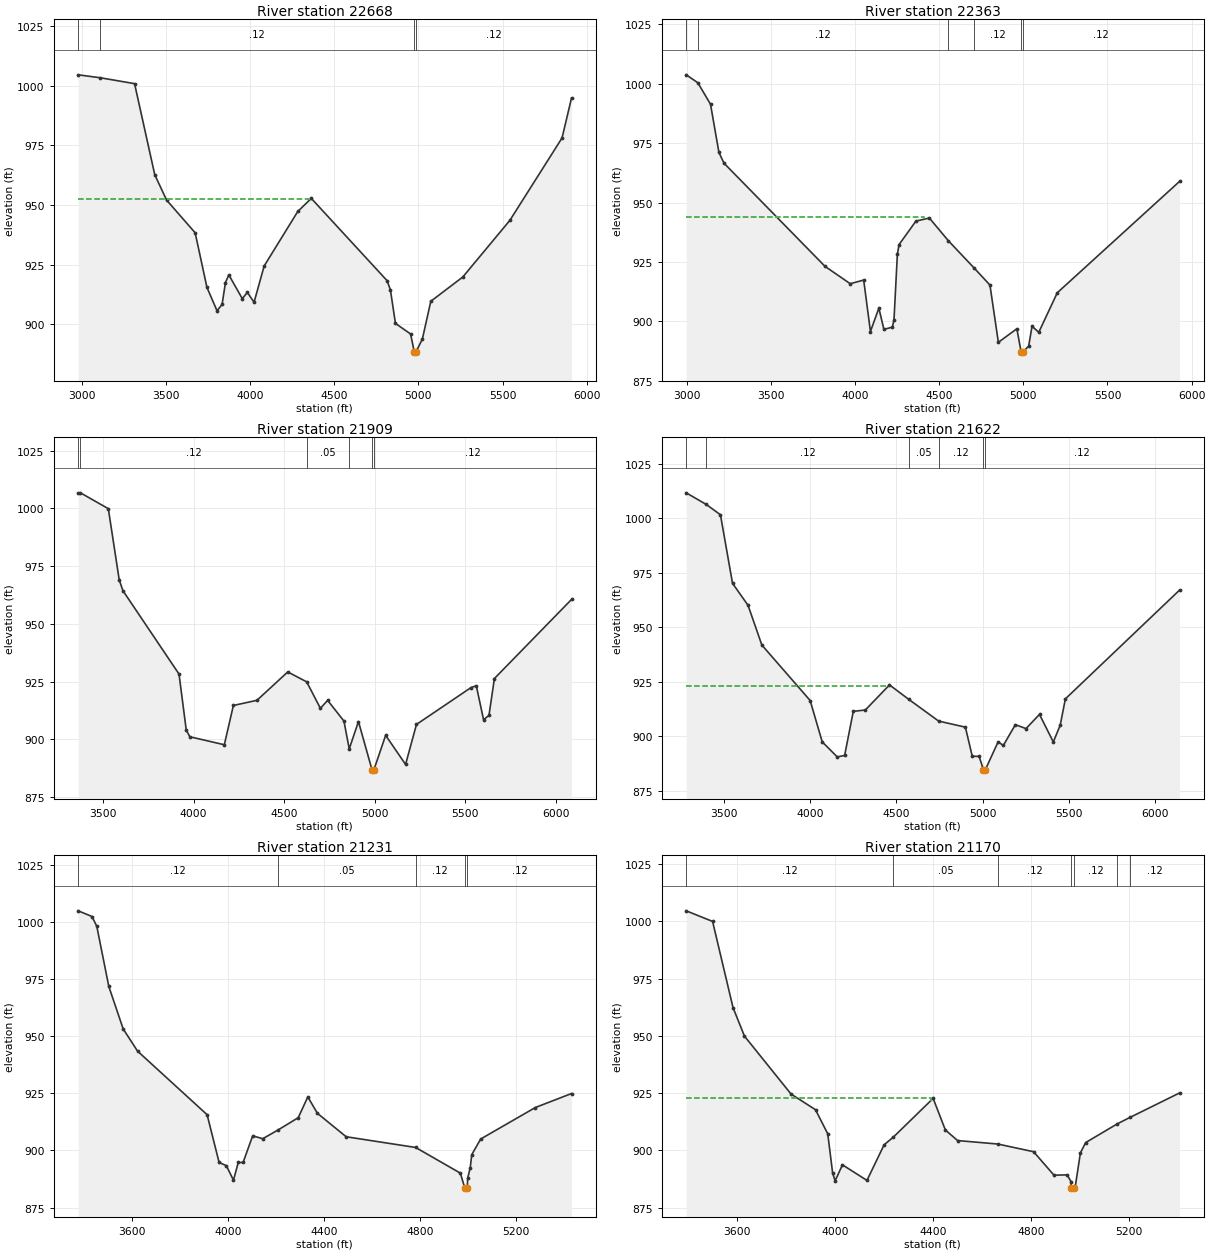
Type RM Length L Ch R = 1 ,22668   ,305,305,305
BEGIN DESCRIPTION:
UDS St 21 46.5
END DESCRIPTION:
XS GIS Cut Line= 3
      2273703.79      7203259.89      2271700.26      7203208.38
      2270772.68       7203201.8
#Sta/Elev= 30
    2978 1004.49  3110.2 1003.25  3312.9  1000.8  3432.9  962.67    3503  952.06
    3673  938.35    3743  915.49  3803.1  905.67  3833.1  908.34  3853.1  917.51
  3873.1  920.72  3953.1  910.76  3983.1  913.38  4023.1  909.25  4083.2  924.45
  4283.2  947.29  4363.2  952.75  4813.4  918.32  4833.4  914.46  4863.4  900.39
  4953.4  895.97  4975.4  888.45  4976.8  887.95  4985.2  888.45  5023.5  893.86
  5073.5  909.66  5263.5  919.82  5543.5  943.56  5853.5  978.06  5909.8  994.79
#Mann= 4 ,-1 , 0
    2978     .05       0  3110.2     .12       0  4975.4     .07       0
  4985.2     .12       0
#XS Ineff= 2 , 0
       0  4353.2  952.55               0
Permanent Ineff=
       F       F
Bank Sta=4975.4,4985.2
XS Rating Curve= 0 ,0
Exp/Cntr=0.3,0.1

Type RM Length L Ch R = 1 ,22363   ,454,454,454
BEGIN DESCRIPTION:
UDS St 21 46.0
END DESCRIPTION:
XS GIS Cut Line= 3
       2273733.4        7202971.      2271729.86      7202919.49
      2270802.48      7202912.91
#Sta/Elev= 30
  2996.6 1003.78  3065.6 1000.45    3141  991.39  3191.1  971.07  3221.1  966.57
  3821.3  923.13  3971.3  915.81  4051.3  917.35  4091.4  895.68  4141.4  905.51
  4171.4  896.61  4221.4   897.5  4231.4  900.63  4251.4  928.21  4261.4  932.28
  4361.5  942.17  4441.5  943.48  4555.2  933.85  4704.8  922.64  4801.6  915.25
  4851.6  891.13  4961.6  896.85  4986.8  887.08  4988.1  886.58  4996.6  887.08
  5031.7  889.52  5051.7  897.89  5091.7  895.35  5201.7     912  5928.2  958.89
#Mann= 6 ,-1 , 0
  2996.6     .05       0  3065.6     .12       0  4555.2     .05       0
  4704.8     .12       0  4986.8     .07       0  4996.6     .12       0
#XS Ineff= 2 , 0
       0  4411.5  943.85               0
Permanent Ineff=
       F       F
Bank Sta=4986.8,4996.6
XS Rating Curve= 0 ,0
Exp/Cntr=0.3,0.1

Type RM Length L Ch R = 1 ,21909   ,287,287,287
BEGIN DESCRIPTION:
UDS St 21 45.0
END DESCRIPTION:
XS GIS Cut Line= 3
      2273515.16      7202644.25       2271955.3      7202613.31
      2270793.64      7202583.84
#Sta/Elev= 30
  3363.4 1006.72  3375.8 1006.77  3529.6   999.9  3589.6  969.11  3609.6  964.43
  3919.7  928.24  3959.7  903.93  3979.7  901.06  4169.7  897.61  4219.7  914.63
  4349.8  916.87  4519.8  929.16  4624.3  924.86  4699.8  913.39  4739.8  916.85
  4829.8  907.87    4859  895.81  4909.9  907.67  4984.9  886.68  4986.3  886.18
  4994.8  886.68  5059.9  901.69  5169.9  889.08    5230  906.42  5530.1  922.34
  5560.1  923.19  5600.1  908.47  5630.1  910.33  5660.1  926.31  6085.6  960.57
#Mann= 6 ,-1 , 0
  3363.4     .05       0  3375.8     .12       0  4624.3     .05       0
    4859     .12       0  4984.9     .07       0  4994.8     .12       0
#XS Ineff= 2 , 0
       0  4519.8  929.16               0
Permanent Ineff=
       F       F
Bank Sta=4984.9,4994.8
XS Rating Curve= 0 ,0
Exp/Cntr=0.3,0.1

Type RM Length L Ch R = 1 ,21622   ,391,391,391
BEGIN DESCRIPTION:
UDS St 21 44.0
END DESCRIPTION:
XS GIS Cut Line= 3
      2273547.42      7202298.24       2272283.7      7202351.17
      2270686.85      7202314.43
#Sta/Elev= 30
  3280.5 1011.69  3396.9 1006.36  3479.1 1001.63  3549.2   970.2  3639.2  960.12
  3719.3  941.91  3999.5  916.48  4069.6  897.51  4156.8  890.62  4199.7  891.31
  4249.8   911.5  4319.8  912.13  4459.9  923.63  4571.6  917.01    4745  907.04
  4900.1  904.26  4940.1  890.92  4980.1  890.87  5005.2   884.6  5006.6   884.1
  5015.1   884.6  5090.2  897.54  5120.2  895.85  5190.2   905.4  5251.7   903.6
  5330.2   910.1  5410.3  897.48  5450.3  905.15  5480.3  917.23  6142.6  967.08
#Mann= 6 ,-1 , 0
  3280.5     .05       0  3396.9     .12       0  4571.6     .05       0
    4745     .12       0  5005.2     .07       0  5015.1     .12       0
#XS Ineff= 2 , 0
       0  4449.9  923.26               0
Permanent Ineff=
       F       F
Bank Sta=5005.2,5015.1
XS Rating Curve= 0 ,0
Exp/Cntr=0.3,0.1

Type RM Length L Ch R = 1 ,21231   ,61,61,61
BEGIN DESCRIPTION:
UDS St 21 43.2
END DESCRIPTION:
XS GIS Cut Line= 3
      2273336.59      7202019.69      2271931.35       7202066.1
      2271329.03      7201815.18
#Sta/Elev= 30
  3374.2  1004.8  3431.8 1002.31  3451.8     998  3501.9  971.71  3561.9  953.12
  3621.9  943.42  3912.1  915.61  3962.1  894.72  3992.1  893.34  4022.1  886.96
  4042.1  894.71  4062.2   894.7  4102.2  906.38  4144.1   905.1  4207.4  908.88
  4292.3   914.3  4332.3   923.4  4372.3  916.22  4492.4  905.96  4782.2  901.28
  4968.7  890.05  4987.4  883.55  4988.9  883.05  4997.6  883.55  4999.4  887.83
  5010.2  892.46  5016.4  898.13  5053.6  904.97  5281.8  918.76  5432.7  924.87
#Mann= 5 ,-1 , 0
  3374.2     .12       0  4207.4     .05       0  4782.2     .12       0
  4987.4     .07       0  4997.6     .12       0
#XS Ineff= 2 , 0
       0  4332.3   923.4               0
Permanent Ineff=
       F       F
Bank Sta=4987.4,4997.6
XS Rating Curve= 0 ,0
Exp/Cntr=0.3,0.1

Type RM Length L Ch R = 1 ,21170   ,250,250,250
BEGIN DESCRIPTION:
UDS St 21 43.1
END DESCRIPTION:
XS GIS Cut Line= 3
      2273326.62      7201928.69      2271869.02       7201977.2
      2271353.69      7201768.76
#Sta/Elev= 30
  3391.5 1004.56  3499.2  999.93  3582.7  962.31  3629.3   949.9  3819.4  924.64
  3919.4  917.79  3969.4  907.27  3989.5  890.06  3999.5  886.77  4029.5  893.74
  4129.5  886.94  4199.6  902.48  4237.5  905.85  4399.7  922.73  4449.7  908.93
  4499.7  904.33  4663.5  902.82  4809.9  899.46  4893.1  889.23    4947  889.36
  4962.8   886.4  4963.5  883.64  4964.9  883.14  4973.7  883.64  4979.4  883.78
    5001  898.92  5022.5  903.45  5151.8  911.62  5203.8  914.44  5405.8   925.1
#Mann= 7 ,-1 , 0
  3391.5     .12       0  4237.5     .05       0  4663.5     .12       0
  4963.5     .07       0  4973.7     .12       0  5151.8     .05       0
  5203.8     .12       0
#XS Ineff= 2 , 0
       0  4389.7  922.69               0
Permanent Ineff=
       F       F
Bank Sta=4963.5,4973.7
XS Rating Curve= 0 ,0
Exp/Cntr=0.3,0.1

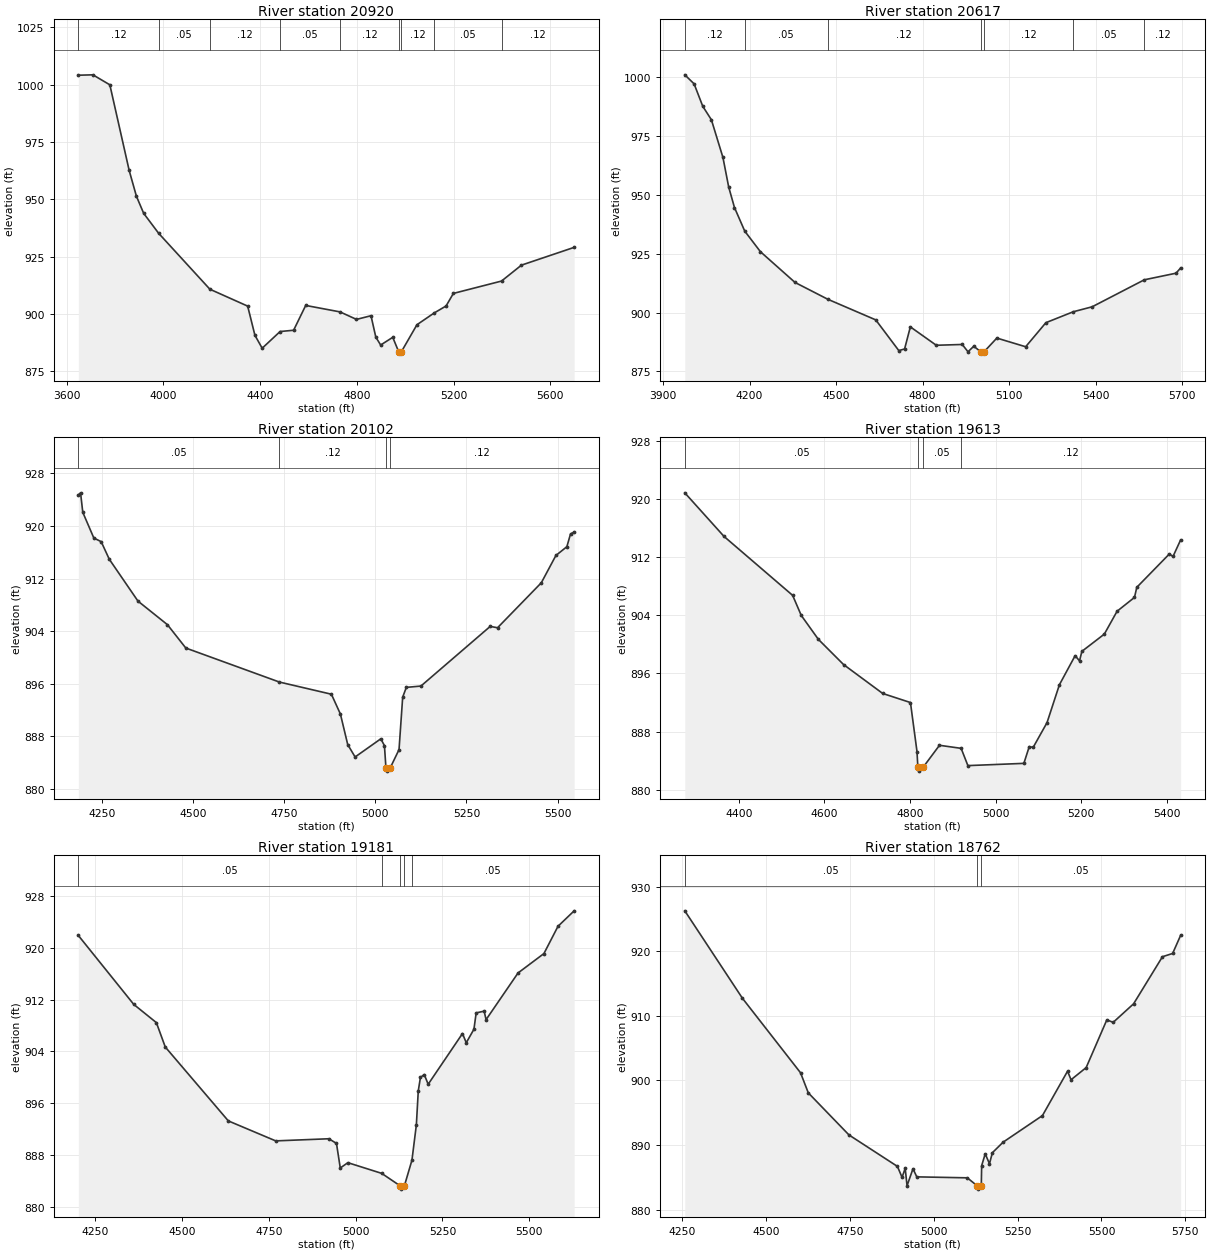
Type RM Length L Ch R = 1 ,20920   ,303,303,303
BEGIN DESCRIPTION:
UDS St 21 43.0
END DESCRIPTION:
XS GIS Cut Line= 3
      2273269.29       7201774.9      2271849.19      7201771.82
       2271222.2      7201706.33
#Sta/Elev= 30
  3648.4 1004.15  3708.7 1004.32  3778.7  999.96  3858.7  962.56  3888.7   951.3
  3918.7  943.84  3980.5  935.15  4192.4  910.73  4348.7  903.35  4378.7  890.61
  4408.7  884.97  4482.8  892.26  4538.7  892.82  4588.7  903.65  4730.7  900.83
  4798.7  897.55  4858.7  899.16  4878.7   889.8  4898.7  886.37  4948.7  889.73
  4973.6  883.33    4975  882.83  4983.8  883.33  5048.7  895.22  5120.3  900.38
  5169.2  903.41  5199.4   908.9  5398.5  914.29  5480.9  921.24  5698.9     929
#Mann= 9 ,-1 , 0
  3648.4     .12       0  3980.5     .05       0  4192.4     .12       0
  4482.8     .05       0  4730.7     .12       0  4973.6     .07       0
  4983.8     .12       0  5120.3     .05       0  5398.5     .12       0
#XS Ineff= 2 , 0
       0  4588.7  903.65               0
Permanent Ineff=
       F       F
Bank Sta=4973.6,4983.8
XS Rating Curve= 0 ,0
Exp/Cntr=0.3,0.1

Type RM Length L Ch R = 1 ,20617   ,515,515,515
BEGIN DESCRIPTION:
UDS St 21 42.0
END DESCRIPTION:
XS GIS Cut Line= 3
      2273081.28      7201517.19      2271863.75       7201534.9
      2271363.16      7201575.55
#Sta/Elev= 30
  3975.3 1001.07  4007.6  997.23  4037.6   987.7  4067.6  981.95  4107.6  965.94
  4127.6  953.35  4147.6  944.65  4183.3  934.62  4237.6  925.88  4357.6  912.81
  4471.2  905.67  4637.7  896.89  4717.7  883.83  4737.7  884.53  4757.7  893.92
  4847.7   886.1  4937.7  886.44  4957.7  883.33  4977.7  885.69  5002.6  883.26
    5004  882.76  5012.8  883.26  5057.7  889.16  5157.7  885.47  5227.8   895.7
  5322.9  900.35  5388.4  902.46  5569.2  913.93  5679.3  916.74  5695.2  918.97
#Mann= 7 ,-1 , 0
  3975.3     .12       0  4183.3     .05       0  4471.2     .12       0
  5002.6     .07       0  5012.8     .12       0  5322.9     .05       0
  5569.2     .12       0
#XS Ineff= 2 , 0
       0  4757.7  893.92               0
Permanent Ineff=
       F       F
Bank Sta=5002.6,5012.8
XS Rating Curve= 0 ,0
Exp/Cntr=0.3,0.1

Type RM Length L Ch R = 1 ,20102   ,489,489,489
BEGIN DESCRIPTION:
UDS St 21 41.0
END DESCRIPTION:
XS GIS Cut Line= 3
      2272681.11      7201054.33        2271879.        7201160.
      2271329.04        7201160.
#Sta/Elev= 30
  4186.1   924.7  4192.2  925.03  4198.3  922.07  4228.6  918.16  4248.7  917.61
  4270.9  914.94  4349.6  908.57  4430.3  904.99  4480.7  901.44  4737.1  896.27
  4879.7  894.42  4904.4  891.41  4924.5  886.76  4944.7  884.88  5015.1  887.64
  5025.1  886.61  5029.2  883.23  5030.9  882.73    5041  883.23  5065.1     886
  5075.1  893.97  5085.1  895.46  5125.1  895.66  5315.1  904.73  5335.1  904.52
  5455.1  911.36  5495.1  915.51  5525.1  916.84  5535.1  918.77  5545.1  919.07
#Mann= 4 ,-1 , 0
  4186.1     .05       0  4737.1     .12       0  5029.2     .07       0
    5041     .12       0
Bank Sta=5029.2,5041
XS Rating Curve= 0 ,0
Exp/Cntr=0.3,0.1

Type RM Length L Ch R = 1 ,19613   ,432,432,432
BEGIN DESCRIPTION:
UDS St 21 40.0
END DESCRIPTION:
XS GIS Cut Line= 3
      2272490.47      7200640.41       2271938.3      7200676.73
       2271382.7      7200916.76
#Sta/Elev= 30
  4273.6  920.89  4365.3  914.88  4525.6  906.76  4545.7     904  4585.7   900.7
  4644.5  897.23  4736.1  893.24  4800.9  891.99  4816.2  885.23  4818.2  883.04
  4819.8  882.54  4830.1  883.04  4868.7   886.1  4919.3  885.68  4935.1   883.3
  5065.9  883.61  5078.5  885.92  5087.6  885.81    5120  889.22    5149  894.45
  5185.7  898.45    5196  897.73  5201.4  899.04  5253.9  901.42  5283.7  904.57
  5324.4  906.48  5329.8  907.87  5405.8  912.46  5414.4  912.12  5432.2   914.4
#Mann= 4 ,-1 , 0
  4273.6     .05       0  4818.2     .07       0  4830.1     .05       0
  4919.3     .12       0
Bank Sta=4818.2,4830.1
XS Rating Curve= 0 ,0
Exp/Cntr=0.3,0.1

Type RM Length L Ch R = 1 ,19181   ,419,419,419
BEGIN DESCRIPTION:
UDS St 21 39.0
END DESCRIPTION:
XS GIS Cut Line= 4
      2272497.21      7200543.51      2272001.15      7200479.93
        2271729.        7200360.      2271156.78      7200097.94
#Sta/Elev= 30
  4202.1  921.93  4361.6  911.27  4426.7  908.45  4452.3  904.68  4633.8  893.25
  4770.1  890.16  4923.1  890.49    4945  889.77  4955.9  885.97  4977.8  886.79
    5075  885.14  5128.5   883.2  5130.1   882.7  5140.4   883.2  5162.2  887.18
  5174.9  892.64  5180.4   897.9  5186.6  899.97  5197.6  900.42  5208.9  898.92
  5307.6  906.76  5318.5  905.34  5340.6  907.43    5347  909.96    5370  910.22
  5375.5  908.91  5467.5  916.13    5542  919.13  5582.5  923.35    5629  925.74
#Mann= 5 ,-1 , 0
  4202.1     .05       0    5075     .12       0  5128.5    .033       0
  5140.4     .12       0  5162.2     .05       0
Bank Sta=5128.5,5140.4
XS Rating Curve= 0 ,0
Exp/Cntr=0.3,0.1

Type RM Length L Ch R = 1 ,18762   ,604,604,604
BEGIN DESCRIPTION:
UDS St 21 38.0
END DESCRIPTION:
XS GIS Cut Line= 3
      2272609.66      7200315.99        2271929.        7200010.
      2271242.65      7199756.37
#Sta/Elev= 30
    4258  926.26  4429.9  912.71    4603  901.18  4626.1  898.07  4747.4  891.55
  4891.8  886.68  4905.6  884.99    4915  886.38  4920.5  883.68  4938.2  886.32
  4949.5  885.06  5100.1  884.91  5129.9  883.66  5131.5  883.16  5141.8  883.66
  5142.9  886.79  5153.5  888.63  5166.2  887.09  5174.9   888.8  5206.8  890.43
  5324.1  894.55  5398.9  901.42  5409.4   900.1  5454.4  901.98    5516  909.37
    5535  908.99  5595.8  911.86  5681.8  919.15  5712.2  919.66    5736  922.46
#Mann= 3 ,-1 , 0
    4258     .05       0  5129.9    .033       0  5141.8     .05       0
Bank Sta=5129.9,5141.8
XS Rating Curve= 0 ,0
Exp/Cntr=0.3,0.1

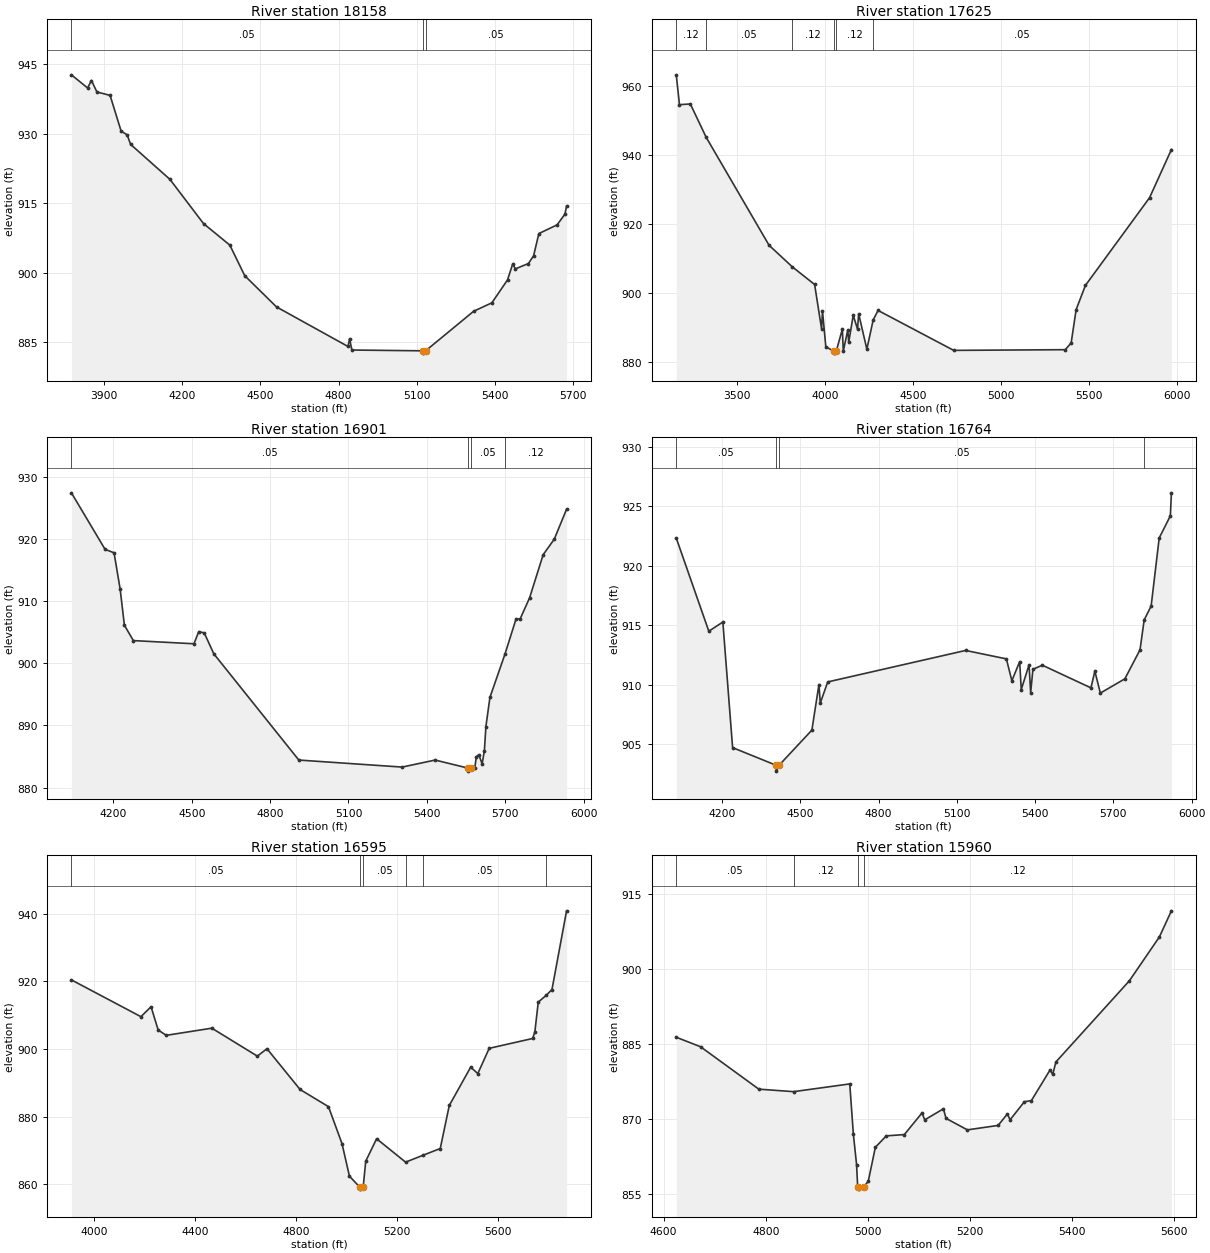
Type RM Length L Ch R = 1 ,18158   ,533,533,533
BEGIN DESCRIPTION:
UDS St 21 37.0
END DESCRIPTION:
XS GIS Cut Line= 3
      2273055.54      7200149.87      2272149.63      7199522.04
      2271352.66       7199490.3
#Sta/Elev= 30
  3774.6  942.76  3836.6  939.92  3851.4  941.53  3872.4  939.06    3923  938.31
  3965.1  930.62  3988.6  929.76  4001.6  927.73  4152.7  920.15  4281.4   910.6
  4382.4  905.94  4439.6  899.33  4561.5  892.58  4835.7  884.03  4841.8  885.71
  4850.6  883.26  5121.7  883.09  5123.3  882.59  5133.6  883.09  5317.8  891.64
  5387.8  893.47  5447.9  898.43  5467.9   901.9  5477.9  900.81  5527.9  901.96
    5548  903.65    5568  908.44    5638  910.32  5668.1  912.64  5674.4  914.39
#Mann= 3 ,-1 , 0
  3774.6     .05       0  5121.7    .033       0  5133.6     .05       0
Bank Sta=5121.7,5133.6
XS Rating Curve= 0 ,0
Exp/Cntr=0.3,0.1

Type RM Length L Ch R = 1 ,17625   ,724,724,724
BEGIN DESCRIPTION:
UDS St 21 36.0
END DESCRIPTION:
XS GIS Cut Line= 3
      2273700.67      7199641.26      2271979.22      7199032.31
      2271029.87      7198753.61
#Sta/Elev= 30
  3155.6  963.33  3173.8  954.67  3235.6  954.87    3326  945.17  3683.3  913.86
  3815.7  907.59  3942.3  902.48  3981.7  889.66    3987  894.72    4006  884.42
    4053  883.06  4054.7  882.56    4065  883.06    4100  889.53  4105.3  883.14
  4130.9   889.3  4136.2  885.71  4161.8  893.54  4186.3  889.52  4192.7     894
  4239.3   883.7  4275.1  892.16    4303  894.95  4733.1  883.36  5367.6  883.56
    5401  885.53  5429.2  895.18  5482.1  902.22  5846.8  927.67    5971  941.65
#Mann= 6 ,-1 , 0
  3155.6     .12       0    3326     .05       0  3815.7     .12       0
    4053    .033       0    4065     .12       0  4275.1     .05       0
Bank Sta=4053,4065
XS Rating Curve= 0 ,0
Exp/Cntr=0.3,0.1

Type RM Length L Ch R = 1 ,16901   ,137,137,137
BEGIN DESCRIPTION:
UDS St 21 35.0
END DESCRIPTION:
XS GIS Cut Line= 6
      2273368.89      7198809.14      2272843.12      7198663.88
      2272431.99      7198633.73      2272286.89      7198621.53
      2272123.91      7198581.02      2271595.18      7198249.18
#Sta/Elev= 30
  4039.5  927.38  4168.4  918.29  4202.7  917.74  4226.1  911.89  4242.3   906.1
  4276.6  903.63  4508.6  903.12    4527  905.07  4548.1  904.86  4584.5  901.51
    4910  884.43  5305.5   883.3  5431.8  884.43  5556.5  883.15  5558.2  882.65
  5568.8  883.15  5583.8  883.23  5589.7  884.96  5599.1  885.29  5611.7  883.82
  5620.3   885.9  5626.2  889.82  5641.6   894.5  5699.1  901.45  5741.7  907.12
    5757  907.09  5793.5  910.51  5845.4  917.44  5887.8  919.92    5935  924.75
#Mann= 4 ,-1 , 0
  4039.5     .05       0  5556.5    .033       0  5568.8     .05       0
  5699.1     .12       0
Bank Sta=5556.5,5568.8
XS Rating Curve= 0 ,0
Exp/Cntr=0.3,0.1

Type RM Length L Ch R = 1 ,16764   ,169,169,169
BEGIN DESCRIPTION:
UDS St 21 34.1
END DESCRIPTION:
XS GIS Cut Line= 5
      2273392.13      7198653.51      2272425.68      7198495.57
      2272192.39      7198441.41      2271820.09        7198192.
      2271622.45      7198071.63
#Sta/Elev= 30
  4024.1  922.34  4148.9   914.5  4202.7  915.27  4240.1   904.7  4406.2  903.22
  4407.9  902.72  4418.5  903.22    4544  906.17  4571.1  910.01  4576.2  908.45
  4604.8  910.23  5133.4  912.88  5289.7  912.17  5310.7  910.33  5340.7  911.94
  5346.7  909.59  5376.7  911.67  5382.8  909.32  5391.4  911.29  5427.5  911.64
  5613.9  909.73  5628.9  911.14  5649.9  909.29  5743.9  910.49    5802  912.93
    5818  915.45  5844.7  916.62  5875.6  922.35  5918.3  924.21  5922.4  926.15
#Mann= 4 ,-1 , 0
  4024.1     .05       0  4406.2    .033       0  4418.5     .05       0
    5818     .12       0
Bank Sta=4406.2,4418.5
XS Rating Curve= 0 ,0
Exp/Cntr=0.3,0.1

Type RM Length L Ch R = 1 ,16595   ,635,635,635
BEGIN DESCRIPTION:
UDS St 21 34.0
END DESCRIPTION:
XS GIS Cut Line= 5
      2273493.62      7198514.22      2272731.89      7198449.84
      2272233.44      7198247.87      2272070.07      7198170.13
      2271637.87      7197961.73
#Sta/Elev= 30
  3908.7  920.42  4184.3  909.54  4224.4  912.48  4252.6   905.6  4284.7  904.02
  4465.3  906.14  4645.9  897.87  4683.9  900.06  4815.2     888  4927.8  882.92
  4981.4  871.98  5010.9  862.36  5052.9  859.03  5054.6  858.53  5065.2  859.03
  5075.5   866.8  5118.6  873.43  5233.5  866.51  5303.3  868.57  5370.9  870.54
  5406.7  883.27  5491.6  894.62  5519.8   892.7    5565  900.18  5737.2  903.09
  5745.9  904.99  5759.4  913.85  5790.8  915.85  5813.8  917.57  5871.7  940.85
#Mann= 6 ,-1 , 0
  3908.7     .05       0  5052.9    .033       0  5065.2     .05       0
  5233.5     .12       0  5303.3     .05       0  5790.8     .12       0
Bank Sta=5052.9,5065.2
XS Rating Curve= 0 ,0
Exp/Cntr=0.3,0.1

Type RM Length L Ch R = 1 ,15960   ,482,482,482
BEGIN DESCRIPTION:
UDS St 21 33.0
END DESCRIPTION:
XS GIS Cut Line= 4
      2272751.02      7197853.12      2272493.39      7197681.83
      2272366.14      7197778.02      2271879.03      7197660.01
#Sta/Elev= 30
  4624.8   886.3  4672.4   884.4  4786.6  875.92  4854.7  875.42  4964.7  876.97
  4971.8   866.9  4978.1   860.8  4980.2  856.43  4981.9  855.93  4992.5  856.43
  5000.9  857.48  5014.9   864.3  5036.3  866.58  5071.7  866.84  5106.4  871.18
  5111.5  869.78  5148.2  871.99  5153.3  870.08  5195.1  867.78  5255.4  868.67
  5273.6  870.98  5278.8  869.79  5306.8   873.4  5320.6  873.64  5357.2  879.77
  5362.4  878.88  5368.6  881.36  5512.6   897.6  5571.4  906.37  5594.9  911.58
#Mann= 4 ,-1 , 0
  4624.8     .05       0  4854.7     .12       0  4980.2     .07       0
  4992.5     .12       0
Bank Sta=4980.2,4992.5
XS Rating Curve= 0 ,0
Exp/Cntr=0.3,0.1

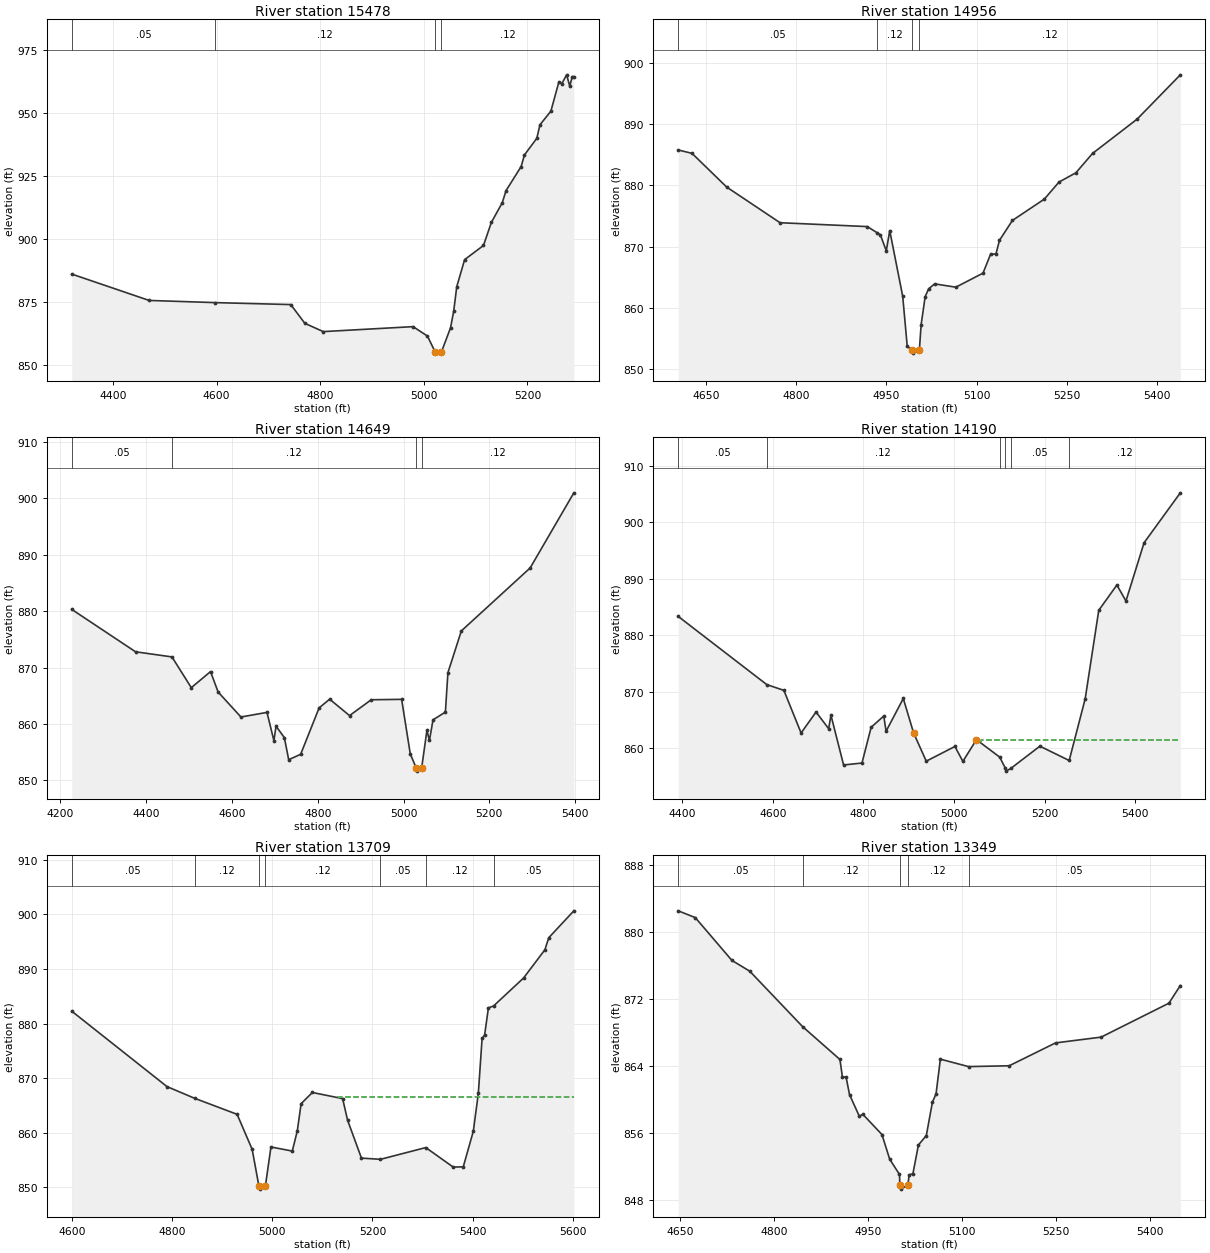
Type RM Length L Ch R = 1 ,15478   ,522,522,522
BEGIN DESCRIPTION:
UDS St 21 32.0
END DESCRIPTION:
XS GIS Cut Line= 3
      2272779.02      7197810.01      2272229.18        7197404.
      2271988.81      7197249.76
#Sta/Elev= 30
  4320.4  886.09  4469.7  875.64  4596.7  874.78  4743.1     874  4770.3  866.56
  4805.8  863.28  4979.2  865.25    5007   861.5  5021.7  855.25  5023.4  854.75
    5034  855.25  5051.6  864.86  5057.6  871.39  5063.5   881.1  5078.7  891.82
  5115.1  897.44  5130.3  906.57  5151.4  914.42  5158.6  919.18  5187.7   928.7
  5194.2  933.34    5218  939.91  5224.1  945.28  5245.2  950.69  5260.4  962.12
  5266.4  961.63  5275.6  965.09  5281.6  960.58  5286.4  964.36  5289.5  964.36
#Mann= 4 ,-1 , 0
  4320.4     .05       0  4596.7     .12       0  5021.7     .07       0
    5034     .12       0
Bank Sta=5021.7,5034
XS Rating Curve= 0 ,0
Exp/Cntr=0.3,0.1

Type RM Length L Ch R = 1 ,14956   ,307,307,307
BEGIN DESCRIPTION:
UDS St 21 31.0
END DESCRIPTION:
XS GIS Cut Line= 3
       2272789.7      7197789.82      2272472.53      7197240.08
      2272295.55      7197146.43
#Sta/Elev= 30
  4603.9  885.75  4626.8   885.2  4684.5   879.7  4773.2  873.89  4918.3  873.26
  4935.2  872.22  4939.9  871.94  4949.9  869.31  4955.6  872.61  4977.2  861.88
  4984.7  853.75  4992.6  853.13  4994.3  852.63  5004.9  853.13  5007.8  857.26
  5014.5  861.83  5020.3  863.12  5030.3  863.92  5065.5  863.38  5110.7  865.67
  5123.2  868.73  5132.3  868.81  5138.1  871.02  5159.6  874.26  5212.7  877.74
  5237.1  880.52  5265.2  882.03  5292.8  885.18    5367  890.78  5438.8     898
#Mann= 4 ,-1 , 0
  4603.9     .05       0  4935.2     .12       0  4992.6     .07       0
  5004.9     .12       0
Bank Sta=4992.6,5004.9
XS Rating Curve= 0 ,0
Exp/Cntr=0.3,0.1

Type RM Length L Ch R = 1 ,14649   ,459,459,459
BEGIN DESCRIPTION:
UDS St 21 30.0
END DESCRIPTION:
XS GIS Cut Line= 4
      2273438.46      7197141.47      2272733.08      7197252.72
      2272625.46      7197269.02      2272325.48      7197094.09
#Sta/Elev= 30
  4226.7   880.3  4375.3  872.79  4460.2  871.88  4505.3  866.43  4550.1  869.28
  4567.8  865.66    4621  861.23  4681.7  862.05  4697.8  857.04  4702.8   859.6
  4722.2  857.58  4732.3  853.66  4760.2  854.63  4803.2  862.85  4827.8  864.39
  4874.1  861.48  4924.7  864.29  4995.5  864.36  5015.7  854.68  5029.8  852.14
  5031.5  851.64  5042.1  852.14  5054.5  858.89  5060.3  857.07  5068.7  860.73
  5097.5   862.1  5103.4  869.09  5134.7  876.49  5295.1  887.65  5396.9  900.96
#Mann= 4 ,-1 , 0
  4226.7     .05       0  4460.2     .12       0  5029.8     .07       0
  5042.1     .12       0
#XS Ineff= 2 , 0
       0  4827.8  864.39               0
Permanent Ineff=
       F       F
Bank Sta=5029.8,5042.1
XS Rating Curve= 0 ,0
Exp/Cntr=0.3,0.1

Type RM Length L Ch R = 1 ,14190   ,481,481,481
BEGIN DESCRIPTION:
UDS St 21 29.0
END DESCRIPTION:
XS GIS Cut Line= 3
      2273479.05      7197010.01        2272879.        7196910.
      2272379.03        7196910.
#Sta/Elev= 30
  4391.3  883.33  4586.7  871.28  4624.5  870.26  4662.5  862.72  4695.5  866.43
  4723.4  863.48  4728.4  865.87  4756.3  857.07  4796.9  857.41  4817.1  863.73
    4845  865.72  4850.1  863.03  4888.1  868.82  4910.9  862.72  4938.8  857.74
  5002.1  860.34  5019.6   857.7  5049.6  861.54  5100.9  858.46  5113.5  856.48
  5115.2  855.98  5125.8  856.48  5189.6  860.39  5254.3  857.86  5289.6  868.76
  5319.6  884.41  5359.6  888.88  5379.6  886.06  5419.6  896.35  5499.6  905.18
#Mann= 6 ,-1 , 0
  4391.3     .05       0  4586.7     .12       0  5100.9     .05       0
  5113.5     .07       0  5125.8     .05       0  5254.3     .12       0
#XS Ineff= 2 , 0
       0  4888.1  868.82  5059.6       0  861.42
Permanent Ineff=
       F       F
Bank Sta=4910.9,5049.6
XS Rating Curve= 0 ,0
Exp/Cntr=0.3,0.1

Type RM Length L Ch R = 1 ,13709   ,360,360,360
BEGIN DESCRIPTION:
UDS St 21 28.0
END DESCRIPTION:
XS GIS Cut Line= 3
      2273428.97        7196510.        2273029.        7196510.
      2272429.05        7196460.
#Sta/Elev= 30
    4600  882.29    4790  868.48  4845.6  866.32    4930   863.4    4960  856.99
  4973.6   850.2  4975.4   849.7  4986.3   850.2  4997.5  857.42  5040.1  856.67
  5050.1  860.37  5057.7  865.35  5080.2   867.4  5140.5  866.28  5150.5  862.31
  5178.1  855.38  5216.1  855.16  5306.5  857.31  5361.2  853.74  5381.3  853.78
  5401.4  860.31  5411.4  867.24  5418.9  877.32  5423.9  877.91  5431.5   882.9
  5441.7  883.24  5501.7  888.37  5544.3  893.55  5551.9  895.74    5602  900.67
#Mann= 7 ,-1 , 0
    4600     .05       0  4845.6     .12       0  4973.6     .07       0
  4986.3     .12       0  5216.1     .05       0  5306.5     .12       0
  5441.7     .05       0
#XS Ineff= 2 , 0
       0                  5130.4       0  866.66
Permanent Ineff=
       F       F
Bank Sta=4973.6,4986.3
XS Rating Curve= 0 ,0
Exp/Cntr=0.3,0.1

Type RM Length L Ch R = 1 ,13349   ,353,353,353
BEGIN DESCRIPTION:
UDS St 21 27.0
END DESCRIPTION:
XS GIS Cut Line= 3
      2273459.84      7196418.05      2273241.99      7196270.56
      2272780.65      7195994.33
#Sta/Elev= 30
    4647  882.51  4674.2   881.7  4732.6  876.59  4761.1   875.3  4845.4  868.68
  4904.9  864.76  4908.9  862.66  4914.7  862.66  4920.2  860.57  4935.7     858
  4941.5  858.21  4971.9   855.8  4984.3  852.85  4999.9  851.03  5000.5  849.78
  5002.3  849.28  5013.2  849.78  5015.4  850.99  5021.3  851.12  5030.1  854.55
  5042.7  855.68  5052.4  859.66  5058.2  860.65  5065.1   864.8    5110  863.91
  5174.9  864.01  5248.8  866.74  5321.5  867.43  5429.6  871.48  5447.8  873.59
#Mann= 5 ,-1 , 0
    4647     .05       0  4845.4     .12       0  5000.5     .07       0
  5013.2     .12       0    5110     .05       0
Bank Sta=5000.5,5013.2
XS Rating Curve= 0 ,0
Exp/Cntr=0.3,0.1

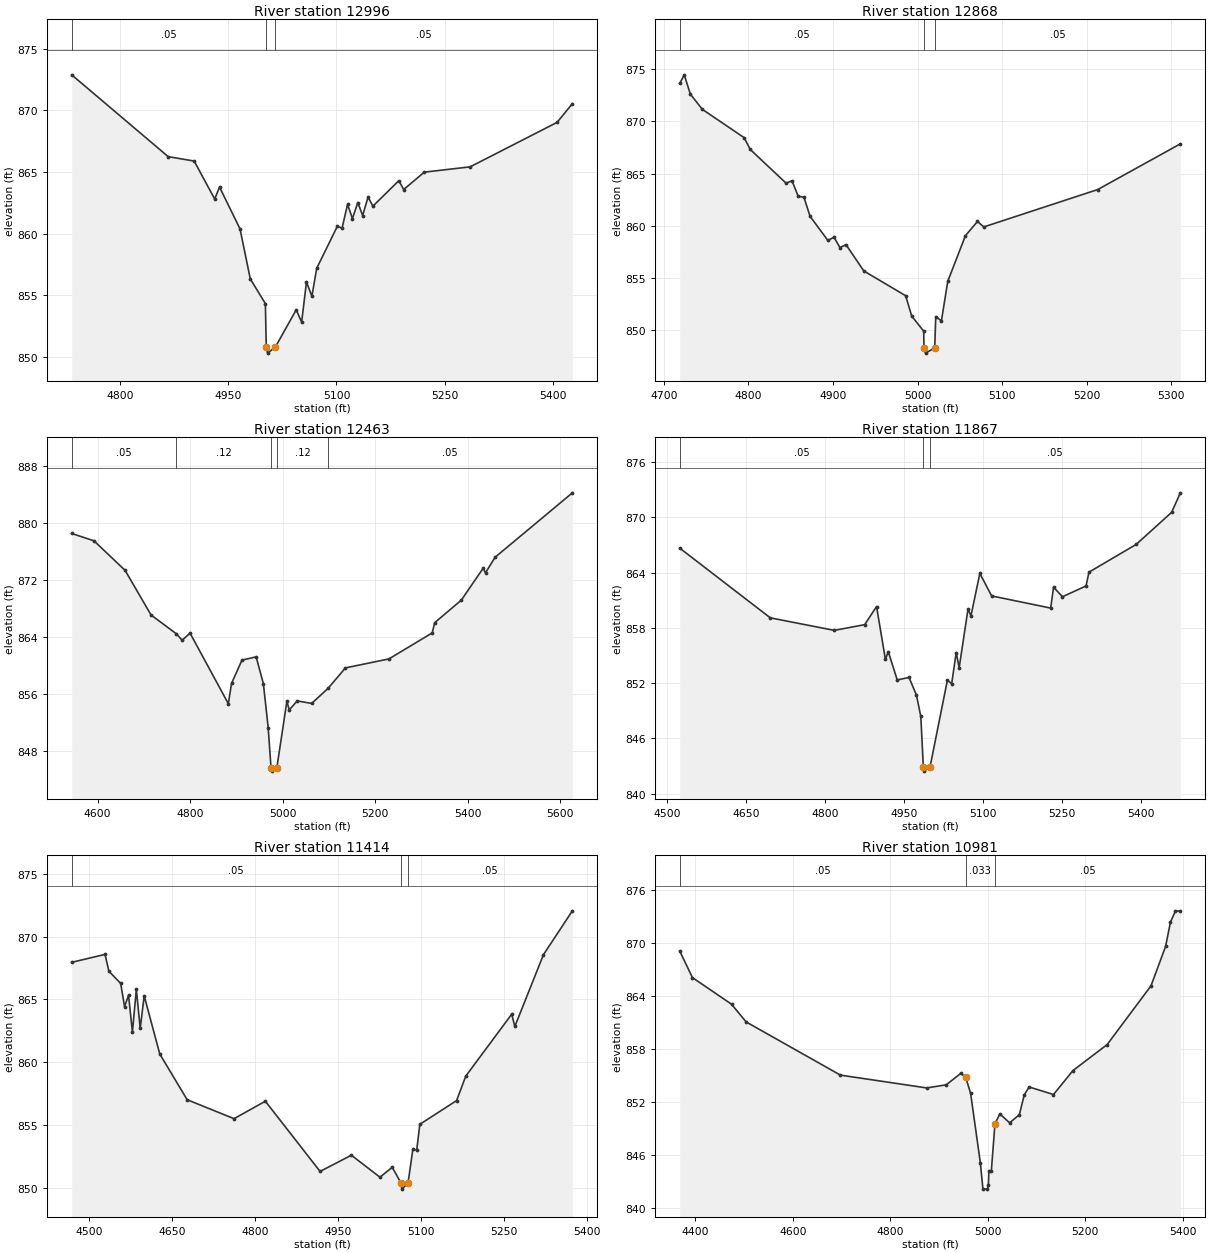
Type RM Length L Ch R = 1 ,12996   ,128,128,128
BEGIN DESCRIPTION:
UDS St 21 26.1
END DESCRIPTION:
XS GIS Cut Line= 2
      2273478.24      7196089.89      2272960.18      7195629.15
#Sta/Elev= 30
  4733.4  872.89    4867  866.25    4903  865.89  4931.4  862.81  4938.1  863.78
  4966.5  860.38  4980.7  856.32  5001.6  854.32  5002.8   850.8  5004.6   850.3
  5015.5   850.8  5044.3  853.82  5051.8  852.82  5058.5  856.07    5066  854.92
  5072.7  857.19  5101.2  860.59  5107.8  860.45  5115.4  862.38  5122.1  861.22
  5129.6  862.52  5136.3  861.47  5143.8  862.97  5150.5  862.23  5186.4   864.3
  5193.1  863.58  5221.6  864.99  5285.1  865.42  5405.5  869.03  5426.7  870.55
#Mann= 3 ,-1 , 0
  4733.4     .05       0  5002.8    .033       0  5015.5     .05       0
Bank Sta=5002.8,5015.5
XS Rating Curve= 0 ,0
Exp/Cntr=0.3,0.1

Type RM Length L Ch R = 1 ,12868   ,405,405,405
BEGIN DESCRIPTION:
UDS St 21 26.0
END DESCRIPTION:
XS GIS Cut Line= 3
      2273501.61      7195985.18      2273295.78      7195787.52
      2273066.66       7195583.9
#Sta/Elev= 30
  4718.7  873.63  4724.1  874.46  4731.3  872.61  4745.5  871.15  4794.9  868.44
  4802.1  867.31  4844.5  864.08  4851.5  864.31  4858.7  862.84  4865.6  862.72
  4872.8  860.91  4893.9  858.59  4901.1  858.91  4908.1  857.91  4915.3  858.19
  4936.4  855.67  4985.8   853.3    4993  851.35  5007.2   849.9  5007.5   848.3
  5009.3   847.8  5020.2   848.3  5021.4   851.3  5028.1  850.89  5035.6  854.68
  5056.5  859.05  5070.7  860.41  5078.2  859.89  5212.9  863.47  5310.6  867.85
#Mann= 3 ,-1 , 0
  4718.7     .05       0  5007.5    .033       0  5020.2     .05       0
Bank Sta=5007.5,5020.2
XS Rating Curve= 0 ,0
Exp/Cntr=0.3,0.1

Type RM Length L Ch R = 1 ,12463   ,596,596,596
BEGIN DESCRIPTION:
UDS St 21 25.0
END DESCRIPTION:
XS GIS Cut Line= 3
      2273942.51      7195678.59      2273602.11      7195510.42
      2272928.99        7195310.
#Sta/Elev= 30
  4544.2  878.49  4592.3  877.46  4659.6  873.31  4715.7  867.04  4770.4   864.4
    4783  863.49  4799.9   864.5  4882.7  854.58  4889.6  857.42  4912.1   860.7
  4942.8  861.16  4958.4   857.4  4968.8  851.22  4974.9  845.61  4976.7  845.11
  4987.6  845.61  5009.2  854.91  5014.4  853.71  5031.5  854.97  5062.8  854.62
  5098.3  856.74  5135.8  859.61  5229.7  860.87  5323.4  864.53  5328.6  865.96
  5386.2  869.13  5433.3   873.6  5438.5  872.97  5459.2  875.15  5626.2   884.2
#Mann= 5 ,-1 , 0
  4544.2     .05       0  4770.4     .12       0  4974.9     .07       0
  4987.6     .12       0  5098.3     .05       0
Bank Sta=4974.9,4987.6
XS Rating Curve= 0 ,0
Exp/Cntr=0.3,0.1

Type RM Length L Ch R = 1 ,11867   ,453,453,453
BEGIN DESCRIPTION:
UDS St 21 24.0
END DESCRIPTION:
XS GIS Cut Line= 3
       2274002.3      7195119.35        2273579.        7194910.
      2273149.47       7194697.4
#Sta/Elev= 30
  4523.2  866.65  4695.4  859.08  4816.9  857.72  4874.8  858.34  4897.3  860.31
  4914.1  854.58  4919.7  855.39  4936.6  852.34    4959  852.61  4973.1   850.7
  4981.4  848.38  4986.2  842.94    4988  842.44  4999.1  842.94  5031.9   852.3
  5040.1  851.94  5048.7  855.31  5054.3  853.66  5071.1  860.03  5076.7   859.3
  5093.6   863.9    5116  861.46  5228.2  860.14  5233.7  862.41  5250.6  861.37
  5295.4  862.54    5301  864.04  5390.7  867.05    5458  870.53  5474.7  872.65
#Mann= 3 ,-1 , 0
  4523.2     .05       0  4986.2    .033       0  4999.1     .05       0
Bank Sta=4986.2,4999.1
XS Rating Curve= 0 ,0
Exp/Cntr=0.3,0.1

Type RM Length L Ch R = 1 ,11414   ,433,433,433
BEGIN DESCRIPTION:
UDS St 21 23.0
END DESCRIPTION:
XS GIS Cut Line= 3
      2274106.33      7194877.96        2273729.        7194510.
       2273392.5      7194336.79
#Sta/Elev= 30
  4468.6  867.95  4528.9  868.58  4535.9  867.24  4557.2  866.27  4564.2  864.42
  4571.4  865.33  4578.4   862.4  4585.5  865.79  4592.5  862.69  4599.7  865.28
  4627.9  860.65  4677.4  857.01  4762.2   855.5  4818.8  856.89  4917.8   851.3
  4974.4  852.59  5026.1  850.84  5048.3  851.63    5064  850.39  5065.8  849.89
  5076.9  850.39  5085.6  853.06  5092.6     853  5098.2  855.05  5164.7  856.94
  5181.3  858.89  5264.4  863.82    5270  862.84  5321.8  868.56  5374.1  872.05
#Mann= 3 ,-1 , 0
  4468.6     .05       0    5064    .033       0  5076.9     .05       0
Bank Sta=5064,5076.9
XS Rating Curve= 0 ,0
Exp/Cntr=0.3,0.1

Type RM Length L Ch R = 1 ,10981   ,482,482,482
BEGIN DESCRIPTION:
UDS St 21 22.0
END DESCRIPTION:
XS GIS Cut Line= 3
      2274515.15      7194190.94        2273879.        7194160.
      2273488.73      7194149.99
#Sta/Elev= 30
    4368   869.1  4394.2  866.08  4474.3  863.07  4504.3  861.06  4697.8  855.03
  4874.7  853.58  4914.8  853.93  4944.8  855.23  4954.8  854.78  4964.9  852.97
  4984.9  845.08  4990.2  842.11  4999.5  842.11  5001.4  842.61  5002.4  844.17
  5007.4  844.17  5014.9  849.53  5024.9  850.63  5044.9  849.63  5064.9  850.54
  5074.9  852.78  5084.9  853.69  5134.9  852.83    5175  855.55    5245  858.49
    5335  865.15    5365  869.62    5375  872.39    5385   873.6  5395.3  873.65
#Mann= 3 , 0 , 0
    4368     .05       0  4954.8    .033       0  5014.9     .05       0
#XS Ineff= 2 , 0
       0                  5084.9       0  853.69
Permanent Ineff=
       F       F
Bank Sta=4954.8,5014.9
XS Rating Curve= 0 ,0
Exp/Cntr=0.3,0.1