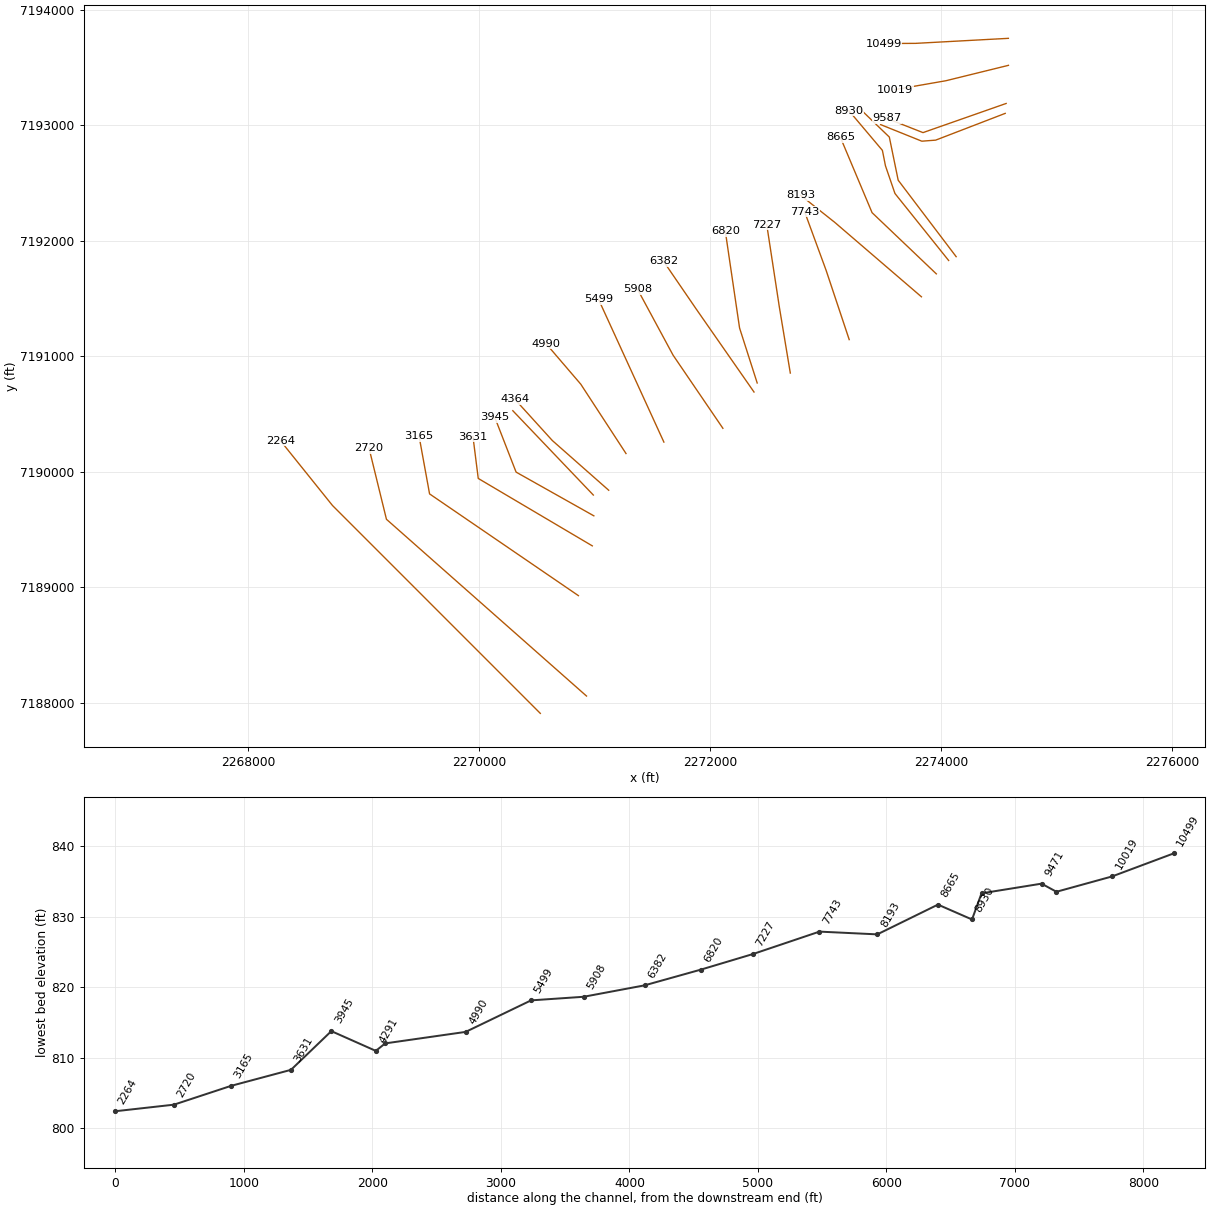
HEC-RAS study UDS St 21.prj: UDS St 21 Base Level Engineering

--- UDS St 21.g01 (geometry) --- (continued)

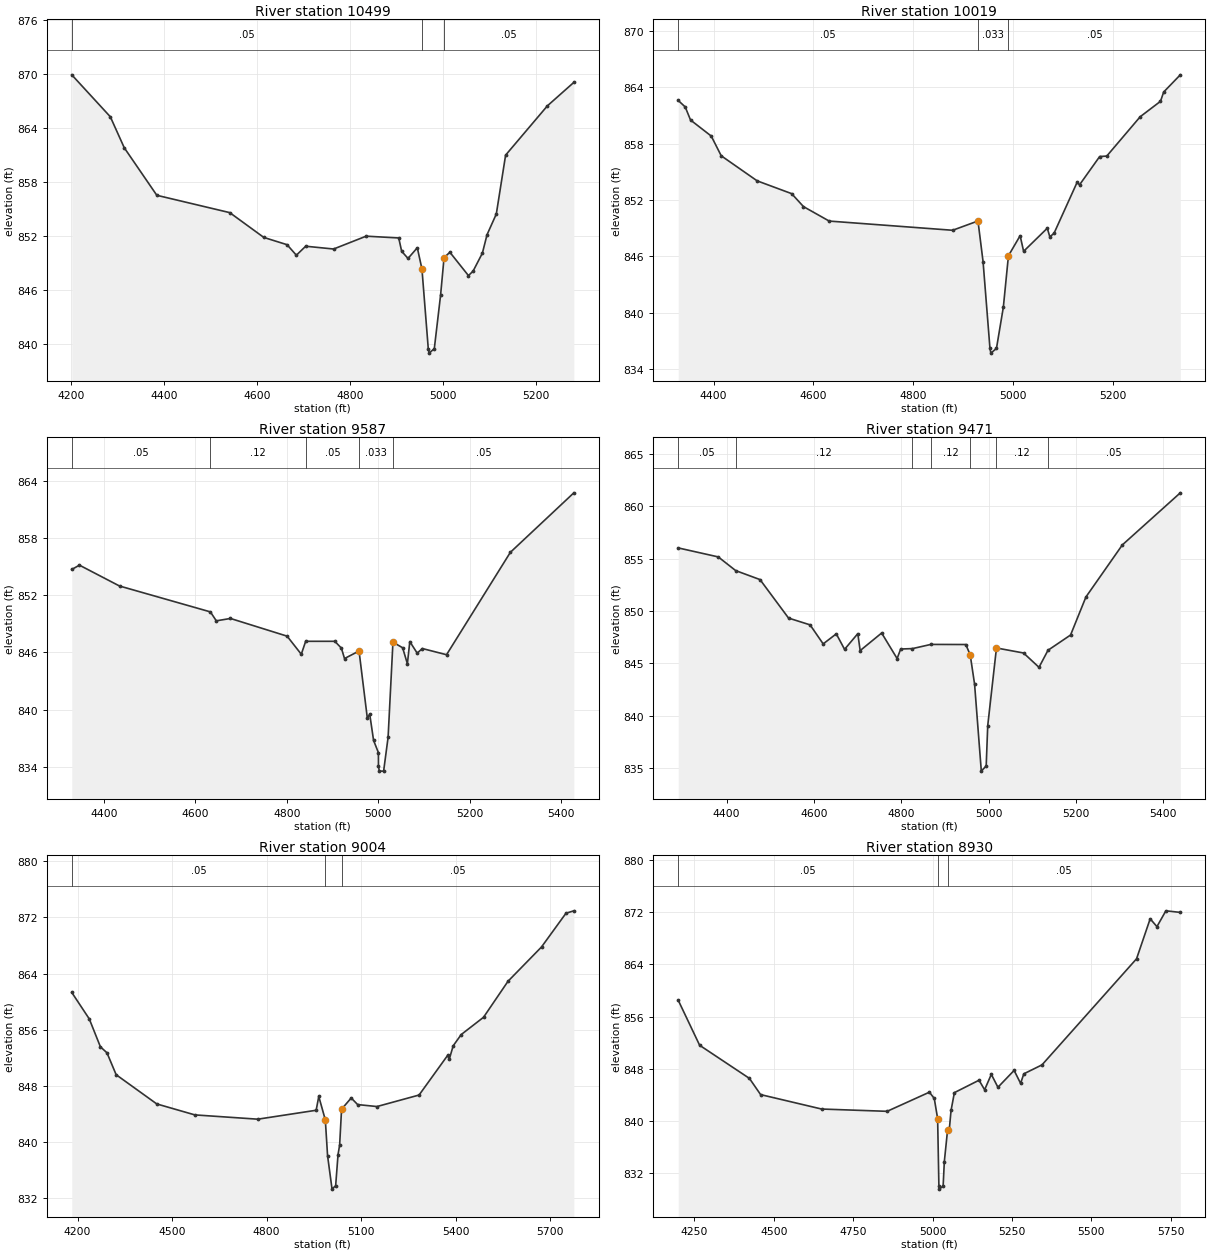
Type RM Length L Ch R = 1 ,10499   ,480,480,480
BEGIN DESCRIPTION:
UDS St 21 21.0
END DESCRIPTION:
XS GIS Cut Line= 3
      2274581.84      7193753.48        2273779.        7193710.
      2273502.12      7193708.55
#Sta/Elev= 30
  4200.7  869.95  4283.7  865.28  4313.7  861.83  4383.8  856.54  4540.8  854.61
  4614.1  851.85  4664.2  851.04  4684.2  849.87  4704.3  850.87  4764.4  850.56
  4834.5  851.99  4904.6  851.79  4910.9  850.31  4924.6  849.51  4944.6   850.7
  4954.6  848.33  4968.2  839.47    4970  838.97  4981.2  839.47  4994.7  845.42
  5002.2   849.6  5014.7   850.2  5054.7   847.6  5064.7   848.1  5084.7   850.1
  5094.7  852.15  5114.7  854.46  5134.7  861.01  5224.7   866.5  5281.6  869.11
#Mann= 3 , 0 , 0
  4200.7     .05       0  4954.6    .033       0  5002.2     .05       0
Bank Sta=4954.6,5002.2
XS Rating Curve= 0 ,0
Exp/Cntr=0.3,0.1

Type RM Length L Ch R = 1 ,10019   ,432,432,432
BEGIN DESCRIPTION:
UDS St 21 20.0
END DESCRIPTION:
XS GIS Cut Line= 3
      2274582.56      7193519.73      2274040.64      7193386.42
      2273599.88       7193309.5
#Sta/Elev= 30
  4329.3   862.6  4343.3  861.91  4353.9  860.52  4395.4  858.81  4415.4  856.71
  4487.4  854.04  4556.4  852.68  4580.1   851.3  4631.6  849.76  4878.8  848.78
  4929.6  849.77  4939.8  845.43  4953.6   836.2  4955.4   835.7  4966.6   836.2
  4980.4  840.59  4990.6  846.07    5014   848.2    5021  846.54  5068.4     849
  5073.5  848.08  5081.9  848.46    5128  853.87    5133  853.62  5173.3  856.63
  5187.5  856.68  5254.5  860.87  5295.1  862.51  5301.5   863.5  5334.8  865.33
#Mann= 3 , 0 , 0
  4329.3     .05       0  4929.6    .033       0  4990.6     .05       0
Bank Sta=4929.6,4990.6
XS Rating Curve= 0 ,0
Exp/Cntr=0.3,0.1

Type RM Length L Ch R = 1 ,9587    ,116,116,116
BEGIN DESCRIPTION:
UDS St 21 19.1
END DESCRIPTION:
XS GIS Cut Line= 3
      2274562.31      7193189.67      2273842.51      7192937.36
      2273529.77      7193060.37
#Sta/Elev= 30
  4329.3  854.72  4346.1  855.17  4433.8  852.98  4632.7  850.26  4645.6  849.32
  4676.6  849.57  4800.6  847.71  4831.6  845.81  4841.2  847.17    4905  847.17
  4919.4  846.45  4926.2  845.36    4958  846.15  4976.1  839.11  4981.4  839.51
  4989.8  836.76  5000.4  835.47  5000.5  834.03  5002.4  833.53  5011.8  833.53
  5021.6  837.09  5032.2  847.08  5053.4  846.49  5063.8  844.81  5069.1  847.14
  5085.2  845.93  5096.6  846.41  5149.5  845.76  5289.2  856.52  5428.1  862.77
#Mann= 5 ,-1 , 0
  4329.3     .05       0  4632.7     .12       0  4841.2     .05       0
    4958    .033       0  5032.2     .05       0
Bank Sta=4958,5032.2
XS Rating Curve= 0 ,0
Exp/Cntr=0.3,0.1

Type RM Length L Ch R = 1 ,9471    ,467,467,467
BEGIN DESCRIPTION:
UDS St 21 19.0
END DESCRIPTION:
XS GIS Cut Line= 4
      2274554.47      7193103.91      2273952.07      7192872.18
      2273832.32      7192863.24      2273475.88      7193006.58
#Sta/Elev= 30
  4289.1  856.03  4380.7  855.17  4420.7  853.86  4476.4     853  4541.7  849.32
    4591  848.67    4621  846.85    4651  847.81    4670  846.33  4700.3  847.83
  4705.7  846.21  4754.9  847.89  4790.3  845.45  4798.5  846.36  4825.5   846.4
  4867.7   846.8  4947.6  846.79  4957.7   845.8  4967.7     843  4983.1  834.68
  4994.3  835.18  4997.8  839.03  5017.8  846.46  5079.8  845.98  5115.2  844.61
  5135.8  846.24  5187.5   847.7  5222.7  851.34  5306.1  856.32  5438.8   861.3
#Mann= 7 ,-1 , 0
  4289.1     .05       0  4420.7     .12       0  4825.5     .05       0
  4867.7     .12       0  4957.7     .07       0  5017.8     .12       0
  5135.8     .05       0
Bank Sta=4957.7,5017.8
XS Rating Curve= 0 ,0
Exp/Cntr=0.3,0.1

Type RM Length L Ch R = 1 ,9004    ,74,74,74
BEGIN DESCRIPTION:
UDS St 21 18.0
END DESCRIPTION:
XS GIS Cut Line= 4
      2274129.57      7191863.52      2273627.63      7192525.36
      2273550.98      7192898.82      2273276.59      7193162.73
#Sta/Elev= 30
  4181.8  861.32  4237.3  857.55  4272.6  853.58  4293.5  852.72  4322.6   849.6
  4451.5  845.44  4572.2  843.88  4771.9  843.27    4957  844.54  4965.3  846.51
  4986.1  843.16  4993.2  838.07  5007.4  833.31  5018.9  833.81  5026.4  838.23
  5031.5  839.59  5037.6  844.69  5068.2  846.29  5088.6  845.35  5149.9  845.07
  5283.5  846.71    5374  852.35  5379.1  851.79  5391.7  853.72  5417.1  855.32
  5487.9  857.78  5565.6  862.91  5671.8  867.79  5749.5   872.6  5774.4  872.94
#Mann= 3 , 0 , 0
  4181.8     .05       0  4986.1    .033       0  5037.6     .05       0
Bank Sta=4986.1,5037.6
XS Rating Curve= 0 ,0
Exp/Cntr=0.3,0.1

Type RM Length L Ch R = 1 ,8930    ,265,265,265
BEGIN DESCRIPTION:
UDS St 21 17.1
END DESCRIPTION:
XS GIS Cut Line= 5
      2274064.53      7191830.41      2273599.68      7192410.37
      2273517.52      7192649.85      2273490.82      7192783.79
      2273201.66      7193126.21
#Sta/Elev= 30
  4198.8  858.51  4266.2  851.62    4423  846.55  4458.2  844.07  4650.3  841.86
  4856.7  841.51  4989.8  844.44  5005.1  843.48  5015.7  840.41  5019.7   830.1
  5021.6   829.6  5033.1   830.1  5036.8   833.8  5047.1  838.69  5052.3  838.63
    5058  841.65  5068.5  844.37  5146.1  846.27  5163.7  844.81  5184.8  847.17
  5205.6  845.19  5256.6  847.77    5277  845.79  5287.2  847.25  5344.4  848.62
  5642.2  864.86  5685.1  870.98  5706.4  869.78  5734.5   872.2    5780  871.96
#Mann= 3 , 0 , 0
  4198.8     .05       0  5015.7     .04       0  5047.1     .05       0
#XS Ineff= 2 , 0
       0                  5146.1       0  846.27
Permanent Ineff=
       F       F
Bank Sta=5015.7,5047.1
XS Rating Curve= 0 ,0
Exp/Cntr=0.3,0.1

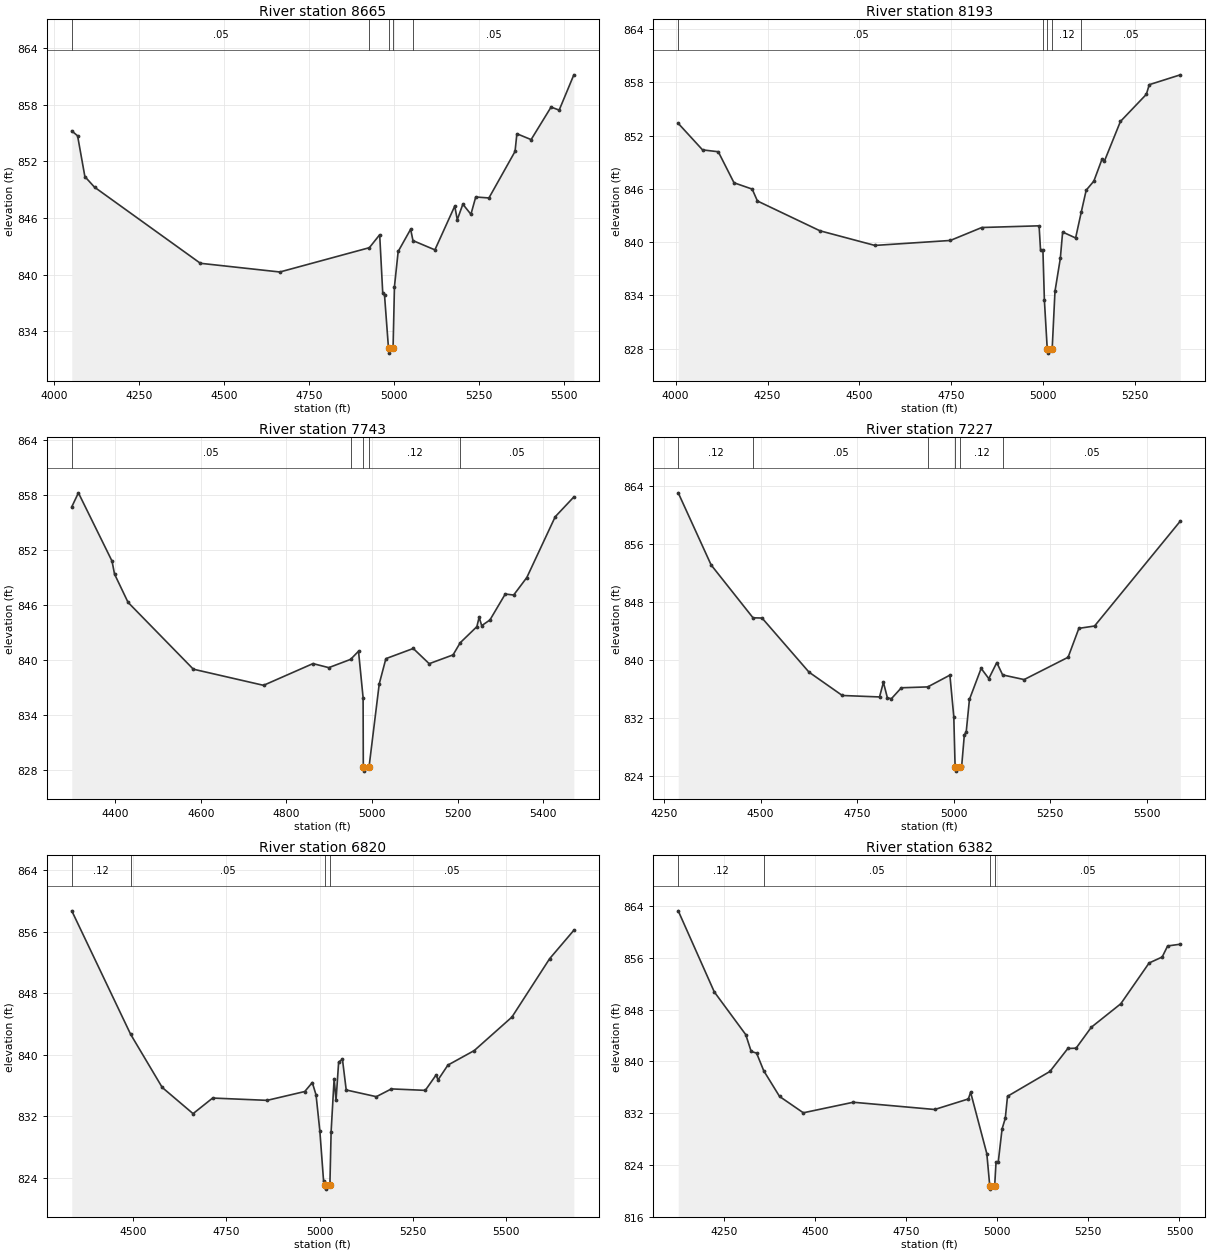
Type RM Length L Ch R = 1 ,8665    ,472,472,472
BEGIN DESCRIPTION:
UDS St 21 17.0
END DESCRIPTION:
XS GIS Cut Line= 3
      2273957.83      7191714.63      2273401.55      7192244.42
      2273127.66      7192895.67
#Sta/Elev= 30
    4053  855.21  4070.1  854.69  4091.5  850.38  4119.8  849.26  4430.8  841.21
  4664.2  840.29  4927.1  842.86  4957.4  844.23  4966.3  838.12  4971.7  837.81
  4983.3  832.21  4985.2  831.71  4996.7  832.21  5000.8  838.75  5011.7  842.46
  5048.3  844.81  5055.2  843.61  5119.6  842.63  5177.9  847.26  5185.3  845.82
  5201.7  847.46  5225.4  846.39  5239.5  848.22  5278.3  848.12    5355  853.04
  5360.4  854.91  5402.2  854.29  5460.8  857.73  5484.6  857.41  5527.7  861.14
#Mann= 5 ,-1 , 0
    4053     .05       0  4927.1     .12       0  4983.3     .07       0
  4996.7     .12       0  5055.2     .05       0
Bank Sta=4983.3,4996.7
XS Rating Curve= 0 ,0
Exp/Cntr=0.3,0.1

Type RM Length L Ch R = 1 ,8193    ,450,450,450
BEGIN DESCRIPTION:
UDS St 21 16.0
END DESCRIPTION:
XS GIS Cut Line= 3
      2273828.94      7191516.06        2273079.        7192160.
      2272783.79      7192394.21
#Sta/Elev= 30
  4007.2  853.39  4073.3   850.4  4116.1  850.19  4158.9  846.69  4208.3  845.98
  4222.5  844.64  4392.6  841.28  4541.9  839.63  4747.1  840.19  4832.7  841.65
  4988.5  841.84  4992.4   839.1  4998.9   839.1  5002.9  833.45  5010.6  827.99
  5012.5  827.49  5024.1  827.99  5031.7  834.46  5046.2  838.16  5052.5  841.14
  5087.8  840.47  5103.5  843.45  5116.6  845.86  5137.4  846.88  5159.9  849.39
  5166.3  849.15  5209.6   853.6  5280.1  856.66  5288.1  857.75  5372.5  858.86
#Mann= 5 ,-1 , 0
  4007.2     .05       0  4998.9     .12       0  5010.6     .07       0
  5024.1     .12       0  5103.5     .05       0
Bank Sta=5010.6,5024.1
XS Rating Curve= 0 ,0
Exp/Cntr=0.3,0.1

Type RM Length L Ch R = 1 ,7743    ,516,516,516
BEGIN DESCRIPTION:
UDS St 21 15.0
END DESCRIPTION:
XS GIS Cut Line= 3
      2273203.58      7191145.31      2273003.58       7191745.3
      2272817.58      7192251.88
#Sta/Elev= 30
    4299  856.71  4314.5  858.24    4393  850.79  4398.8  849.38  4430.4  846.29
  4582.8     839  4746.7  837.24  4862.1  839.61    4899  839.17  4949.9  840.07
  4968.4  840.96  4979.1   835.9  4979.6  828.38  4981.5  827.88  4993.1  828.38
  5016.8   837.4  5032.3  840.15  5096.2  841.26  5133.4   839.6  5189.1  840.56
  5205.9  841.89  5244.7  843.64    5250  844.67    5256  843.75  5275.2  844.37
    5311   847.2  5330.6  847.09  5361.3     849  5427.6  855.63  5471.1  857.79
#Mann= 5 ,-1 , 0
    4299     .05       0  4949.9     .12       0  4979.6     .07       0
  4993.1     .12       0  5205.9     .05       0
Bank Sta=4979.6,4993.1
XS Rating Curve= 0 ,0
Exp/Cntr=0.3,0.1

Type RM Length L Ch R = 1 ,7227    ,407,407,407
BEGIN DESCRIPTION:
UDS St 21 14.0
END DESCRIPTION:
XS GIS Cut Line= 3
      2272693.56      7190855.94      2272598.83      7191426.42
      2272489.67      7192139.62
#Sta/Elev= 30
  4286.7  863.01  4371.9  853.08  4480.3  845.81  4503.7  845.78  4625.3  838.33
  4711.4  835.12  4807.8  834.92  4817.9  836.93  4828.1  834.81  4838.4  834.67
  4864.3  836.18  4932.6   836.3    4990  837.92  5000.1  832.19  5003.5  825.21
  5005.4  824.71    5017  825.21  5020.4  825.35  5027.3  829.65  5032.3  830.15
  5040.6  834.58  5070.9  838.85  5090.7  837.44  5111.4  839.65  5126.5  837.95
  5182.2  837.31    5296  840.38  5323.9  844.36  5364.5  844.68  5586.5  859.12
#Mann= 6 ,-1 , 0
  4286.7     .12       0  4480.3     .05       0  4932.6     .12       0
  5003.5     .07       0    5017     .12       0  5126.5     .05       0
Bank Sta=5003.5,5017
XS Rating Curve= 0 ,0
Exp/Cntr=0.3,0.1

Type RM Length L Ch R = 1 ,6820    ,438,438,438
BEGIN DESCRIPTION:
UDS St 21 13.0
END DESCRIPTION:
XS GIS Cut Line= 3
       2272406.8      7190770.02      2272254.11      7191246.53
       2272130.7      7192084.32
#Sta/Elev= 30
  4334.9   858.7  4492.9  842.63  4577.6  835.72  4660.4  832.31  4712.9  834.34
    4859  834.04  4960.1  835.19  4980.3  836.36  4990.4  834.74  5000.5  830.09
  5010.6  823.52    5014  822.99  5015.9  822.49  5027.5  822.99  5030.8  829.98
  5038.9  836.86    5044  834.07    5051  839.02  5061.2  839.39  5071.3  835.39
  5152.1  834.52  5192.6  835.53  5283.5  835.34  5312.6  837.35  5317.6   836.7
  5344.2  838.63  5414.9  840.52    5516  844.88  5617.1  852.47  5682.1  856.17
#Mann= 4 ,-1 , 0
  4334.9     .12       0  4492.9     .05       0    5014    .033       0
  5027.5     .05       0
Bank Sta=5014,5027.5
XS Rating Curve= 0 ,0
Exp/Cntr=0.3,0.1

Type RM Length L Ch R = 1 ,6382    ,474,474,474
BEGIN DESCRIPTION:
UDS St 21 12.0
END DESCRIPTION:
XS GIS Cut Line= 3
      2272379.19       7190691.9        2271879.        7191410.
      2271594.99      7191824.74
#Sta/Elev= 30
  4124.6  863.28  4223.5  850.75  4309.9  844.14  4324.8  841.54  4339.6  841.29
  4359.2  838.56  4402.6  834.59  4467.9  832.06  4604.9  833.69  4828.3  832.57
  4920.8   834.2  4926.9  835.24  4971.4  825.75  4979.5  820.76  4981.4  820.26
    4993  820.76  4996.7  824.46  5002.8  824.46  5013.3  829.57  5022.1  831.21
  5028.2  834.61  5144.6  838.45  5193.7     842  5216.4  842.05  5258.3  845.29
    5339  848.91  5416.8  855.22  5452.6  856.14  5467.6  857.85  5502.4  858.12
#Mann= 4 ,-1 , 0
  4124.6     .12       0  4359.2     .05       0  4979.5    .033       0
    4993     .05       0
Bank Sta=4979.5,4993
XS Rating Curve= 0 ,0
Exp/Cntr=0.3,0.1

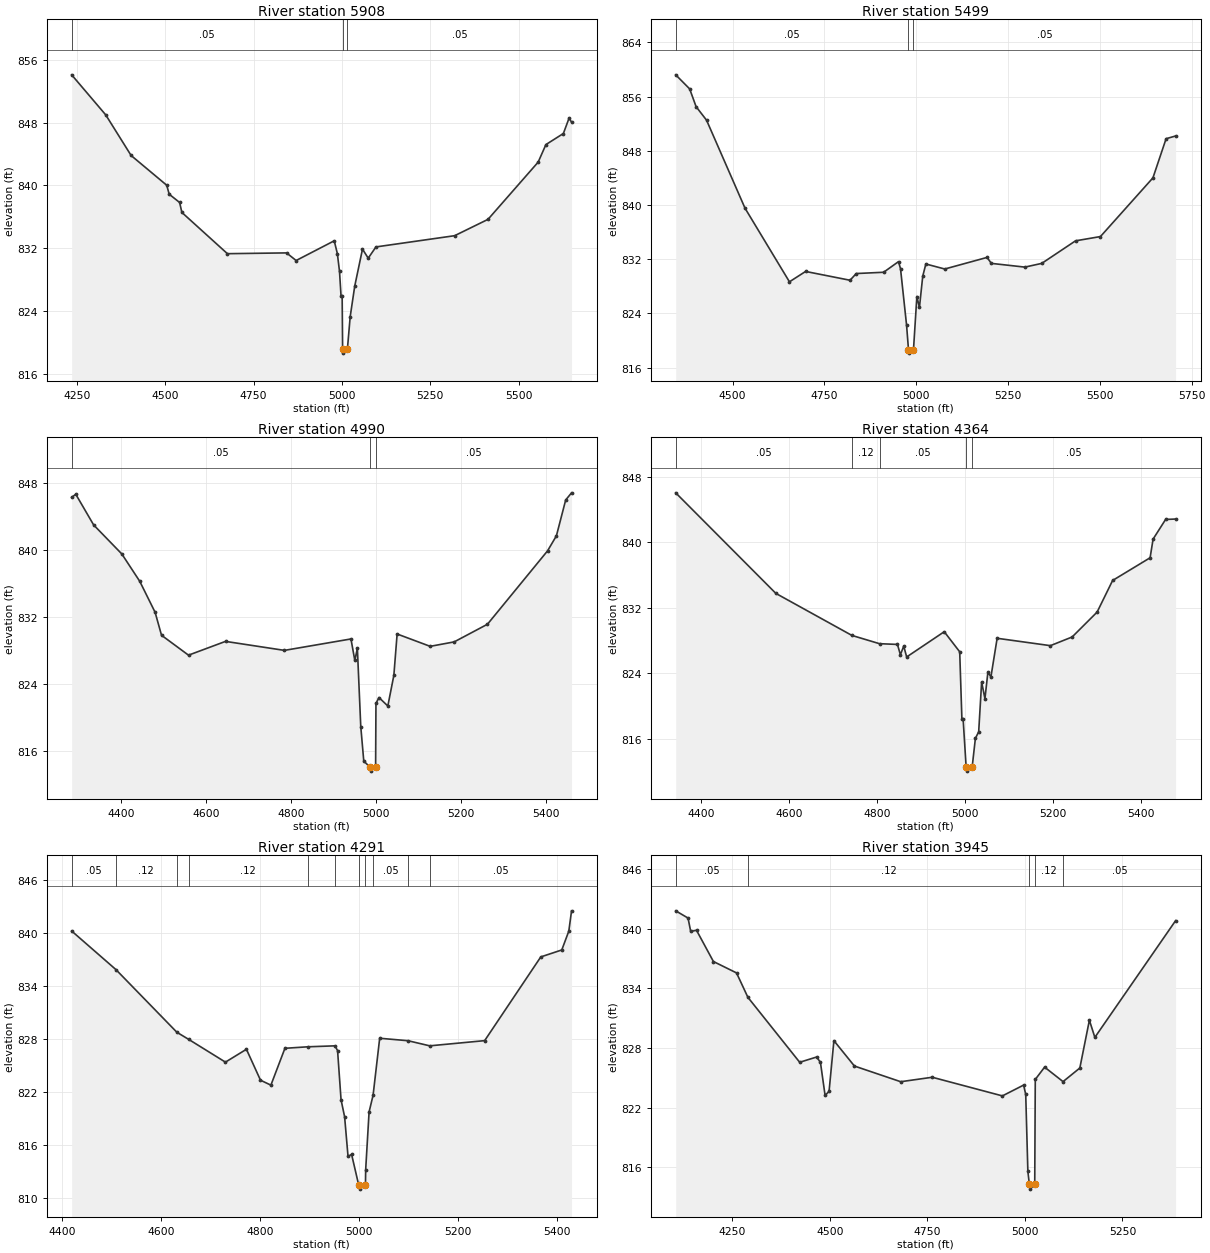
Type RM Length L Ch R = 1 ,5908    ,409,409,409
BEGIN DESCRIPTION:
UDS St 21 11.0
END DESCRIPTION:
XS GIS Cut Line= 3
      2272109.83      7190377.65        2271679.        7191010.
      2271370.73      7191581.04
#Sta/Elev= 30
  4235.3  854.07  4331.7  848.97  4403.5   843.8  4504.3  840.01  4511.2  838.87
  4540.7  837.82  4547.1  836.55  4675.9   831.3  4843.2   831.4  4870.3  830.43
  4978.1  832.94  4986.9  831.31    4993  829.05  4997.4  825.87  5000.5  825.87
  5001.8  819.14  5003.7  818.64  5015.3  819.14  5023.2  823.27  5036.1  827.18
    5058  831.88  5074.2  830.73  5096.1  832.16  5318.7  833.59  5413.1  835.67
    5555  842.96  5576.9  845.19  5626.3   846.6  5642.5  848.57  5649.4  848.04
#Mann= 3 ,-1 , 0
  4235.3     .05       0  5001.8    .033       0  5015.3     .05       0
Bank Sta=5001.8,5015.3
XS Rating Curve= 0 ,0
Exp/Cntr=0.3,0.1

Type RM Length L Ch R = 1 ,5499    ,509,509,509
BEGIN DESCRIPTION:
UDS St 21 10.0
END DESCRIPTION:
XS GIS Cut Line= 3
      2271598.88       7190258.4      2271325.29      7190855.93
      2271032.09       7191496.1
#Sta/Elev= 30
    4345  859.22    4383  857.14  4400.5  854.52    4429  852.52  4533.7  839.53
  4654.7  828.66  4698.7  830.19  4819.7  828.89  4836.7  829.88  4911.2  830.07
  4951.7  831.64  4957.2  830.59  4973.7  822.25  4978.9  818.63  4980.8  818.13
  4992.5  818.63  5001.7  826.49  5008.7  824.87  5017.7  829.49  5026.2  831.29
  5077.7  830.55  5192.8  832.26  5204.6  831.38  5295.8  830.83  5341.8  831.38
  5433.8  834.71  5501.6  835.34  5644.6  844.01  5680.4  849.79  5706.3  850.19
#Mann= 3 ,-1 , 0
    4345     .05       0  4978.9    .033       0  4992.5     .05       0
Bank Sta=4978.9,4992.5
XS Rating Curve= 0 ,0
Exp/Cntr=0.3,0.1

Type RM Length L Ch R = 1 ,4990    ,626,626,626
BEGIN DESCRIPTION:
UDS St 21 9.0
END DESCRIPTION:
XS GIS Cut Line= 3
      2271270.86      7190159.34        2270879.        7190760.
      2270578.97      7191110.03
#Sta/Elev= 30
  4282.8  846.24  4292.5  846.61  4334.6  842.96  4401.1   839.5  4443.3  836.25
  4479.5  832.56  4494.6  829.83  4558.2  827.46  4645.4   829.1  4784.3  828.03
  4941.1  829.39  4950.2  826.83  4956.2  828.28  4964.2  818.97  4971.3  814.85
  4985.6  814.16  4987.5  813.66  4999.2  814.16    5000  821.71  5007.1  822.42
    5028  821.41  5042.2  825.06  5049.9  829.98  5127.8  828.51  5184.4  829.04
  5262.8  831.14  5404.4  839.87  5425.3  841.66  5447.2  845.93    5461  846.78
#Mann= 3 ,-1 , 0
  4282.8     .05       0  4985.6    .033       0  4999.2     .05       0
#XS Ineff= 2 , 0
       0  4645.4   829.1               0
Permanent Ineff=
       F       F
Bank Sta=4985.6,4999.2
XS Rating Curve= 0 ,0
Exp/Cntr=0.3,0.1

Type RM Length L Ch R = 1 ,4364    ,73,73,73
BEGIN DESCRIPTION:
UDS St 21 8.0
END DESCRIPTION:
XS GIS Cut Line= 3
      2271121.08      7189841.54      2270633.29       7190271.6
      2270307.44      7190630.43
#Sta/Elev= 30
    4343  846.01  4570.4  833.73    4743   828.6  4805.7  827.59  4846.5   827.5
  4853.1  826.24  4860.7  827.29  4867.4  825.97  4952.7  829.05  4987.8   826.6
  4992.8  818.36  4995.6  818.36  5002.4  812.53  5004.4  812.03  5016.1  812.53
  5023.4  816.03  5030.9  816.83  5037.6  822.92  5045.1  820.87  5051.8  824.11
  5058.7  823.54  5072.8  828.25  5193.7  827.35  5243.1  828.41  5299.8  831.45
    5335  835.31  5420.1  838.08  5426.9  840.36  5455.3  842.76    5478  842.81
#Mann= 5 ,-1 , 0
    4343     .05       0    4743     .12       0  4805.7     .05       0
  5002.4    .033       0  5016.1     .05       0
#XS Ineff= 2 , 0
       0  4952.7  829.05               0
Permanent Ineff=
       F       F
Bank Sta=5002.4,5016.1
XS Rating Curve= 0 ,0
Exp/Cntr=0.3,0.1

Type RM Length L Ch R = 1 ,4291    ,346,346,346
BEGIN DESCRIPTION:
UDS St 21 7.1
END DESCRIPTION:
XS GIS Cut Line= 2
      2270987.92      7189800.06      2270290.98      7190529.83
#Sta/Elev= 30
  4420.1  840.26  4509.3  835.89  4632.5  828.77  4656.7  827.95  4730.5  825.38
  4772.9  826.84  4801.3  823.33  4822.3  822.77  4850.6  826.95  4896.6  827.12
  4951.6  827.23  4956.9  826.69  4963.9  821.11  4971.1  819.18    4978  814.68
  4985.2  814.91  4999.4  811.47  5001.4  810.97  5013.2  811.47  5013.6  813.16
  5020.5  819.73  5028.6  821.63  5041.9  828.09  5099.1  827.81  5142.9  827.23
  5253.8  827.82  5367.1  837.32  5409.5  838.11  5423.7  840.25  5429.2  842.55
#Mann= 11 ,-1 , 0
  4420.1     .05       0  4509.3     .12       0  4632.5     .05       0
  4656.7     .12       0  4896.6     .05       0  4951.6     .12       0
  4999.4     .07       0  5013.2     .12       0  5028.6     .05       0
  5099.1     .12       0  5142.9     .05       0
#XS Ineff= 2 , 0
       0  4850.6  826.95               0
Permanent Ineff=
       F       F
Bank Sta=4999.4,5013.2
XS Rating Curve= 0 ,0
Exp/Cntr=0.3,0.1

Type RM Length L Ch R = 1 ,3945    ,314,314,314
BEGIN DESCRIPTION:
UDS St 21 7.0
END DESCRIPTION:
XS GIS Cut Line= 3
      2270992.43      7189620.01       2270319.2      7189998.52
      2270134.63      7190472.94
#Sta/Elev= 30
    4105  841.83  4136.6   841.1  4143.4  839.75  4158.3  839.87  4201.6  836.72
  4260.9  835.57    4290  833.11  4422.8  826.56  4466.2  827.09    4476  826.55
  4487.9  823.22  4498.1  823.63  4510.5  828.74  4563.1  826.18  4681.7   824.6
  4762.6  825.05  4942.4  823.17  4996.8  824.26  5002.2  823.32  5007.7  815.57
  5011.5  814.27  5013.5  813.77  5025.3  814.27  5026.7  824.83  5050.6  826.07
  5097.9  824.61  5140.9  825.98  5165.4   830.8  5179.4  829.07  5386.4  840.84
#Mann= 5 ,-1 , 0
    4105     .05       0    4290     .12       0  5011.5     .07       0
  5025.3     .12       0  5097.9     .05       0
#XS Ineff= 2 , 0
       0  4510.5  828.74               0
Permanent Ineff=
       F       F
Bank Sta=5011.5,5025.3
XS Rating Curve= 0 ,0
Exp/Cntr=0.3,0.1

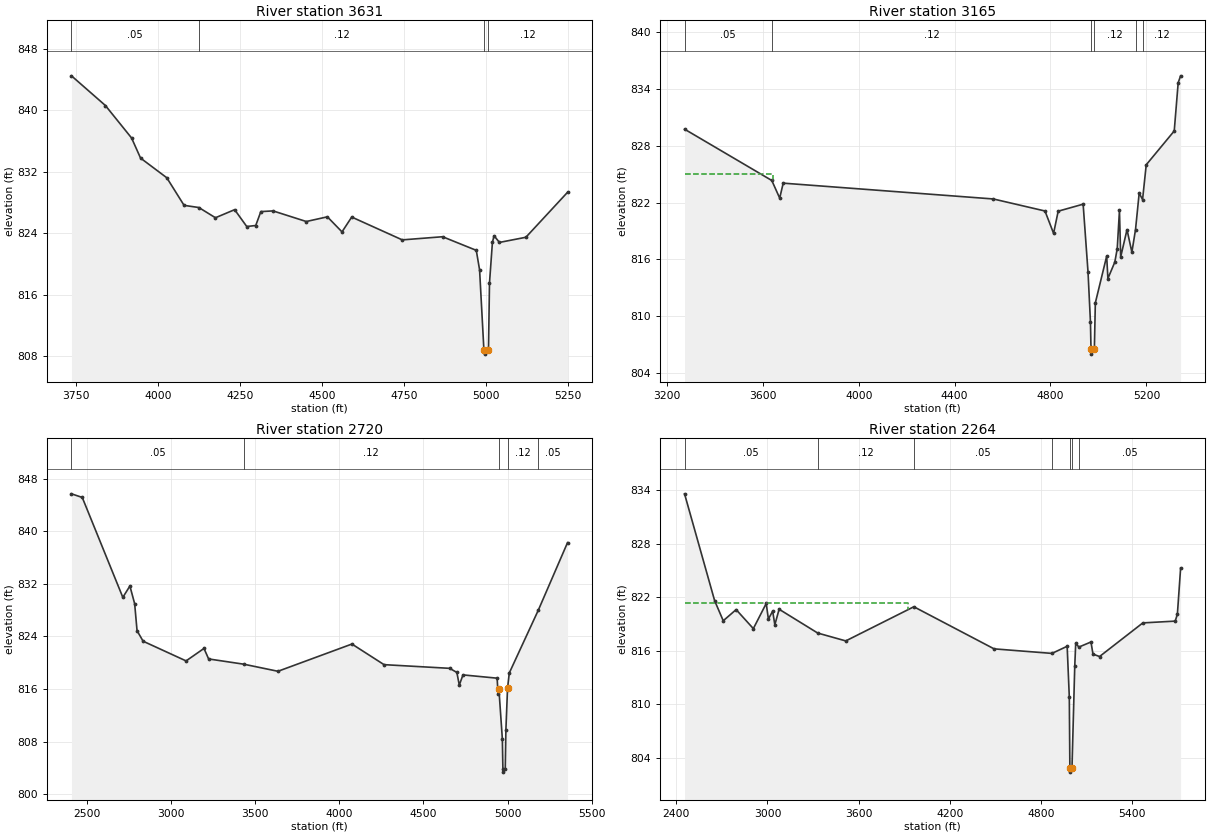
Type RM Length L Ch R = 1 ,3631    ,466,466,466
BEGIN DESCRIPTION:
UDS St 21 6.0
END DESCRIPTION:
XS GIS Cut Line= 3
      2270978.97      7189360.02      2269991.55       7189943.7
      2269945.76      7190305.99
#Sta/Elev= 30
  3735.4  844.48  3838.8  840.62  3918.7  836.39    3946  833.78    4026  831.22
  4078.7  827.63  4123.7  827.35  4174.3  826.02  4232.8  827.07  4269.7  824.88
  4297.1  825.01  4312.7  826.82  4349.8  826.91  4451.2  825.53  4515.5  826.14
  4560.1  824.18  4589.7  826.11  4743.8  823.14  4866.7  823.55  4969.4  821.78
  4979.5  819.24  4992.7  808.78  4994.7  808.28  5006.6  808.78  5009.7  817.53
  5018.6  822.82  5023.6  823.68    5040  822.81  5120.6  823.48  5247.6  829.33
#Mann= 4 ,-1 , 0
  3735.4     .05       0  4123.7     .12       0  4992.7     .07       0
  5006.6     .12       0
#XS Ineff= 2 , 0
       0  4589.7  826.11               0
Permanent Ineff=
       F       F
Bank Sta=4992.7,5006.6
XS Rating Curve= 0 ,0
Exp/Cntr=0.3,0.1

Type RM Length L Ch R = 1 ,3165    ,445,445,445
BEGIN DESCRIPTION:
UDS St 21 5.0
END DESCRIPTION:
XS GIS Cut Line= 3
      2270858.85      7188929.09      2269570.11      7189809.88
      2269479.01      7190309.97
#Sta/Elev= 30
  3273.5  829.76  3637.5  824.34  3670.4  822.48  3685.1  824.06  4561.6  822.39
    4777  821.12  4812.9  818.76  4832.1   821.1  4936.2  821.84  4956.6  814.67
  4966.7  809.39    4969  806.51    4971  806.01    4983  806.51  4987.1  811.42
  5034.4  816.35  5039.5  813.99  5068.4  815.73  5078.5  817.16  5087.7  821.18
  5092.8  816.27  5119.2  819.15  5139.5  816.77  5154.7  819.16    5170  823.01
  5184.1  822.33  5199.4     826  5316.2  829.57  5332.7  834.67  5342.8  835.39
#Mann= 6 ,-1 , 0
  3273.5     .05       0  3637.5     .12       0    4969     .07       0
    4983     .12       0  5154.7     .05       0  5184.1     .12       0
#XS Ineff= 2 , 0
       0  3640.6  824.99               0
Permanent Ineff=
       F       F
Bank Sta=4969,4983
XS Rating Curve= 0 ,0
Exp/Cntr=0.3,0.1

Type RM Length L Ch R = 1 ,2720    ,456,456,456
BEGIN DESCRIPTION:
UDS St 21 4.0
END DESCRIPTION:
XS GIS Cut Line= 3
      2270929.02      7188059.98      2269196.64      7189590.22
      2269045.84      7190205.98
#Sta/Elev= 30
  2410.5  845.73  2474.5  845.18  2715.5  829.96  2757.4  831.69  2785.7  828.99
  2799.9  824.88  2835.9  823.28    3091  820.28  3197.3  822.18  3224.9  820.58
  3433.6  819.78  3636.5   818.7  4075.7  822.85  4266.4  819.71  4656.2  819.15
  4698.9  818.52  4713.1  816.59  4735.1  818.15  4937.9  817.65  4943.2   815.3
  4948.3  816.01  4968.8  808.41  4972.1  803.84  4974.1  803.34  4986.1  803.84
  4989.9  809.77  4999.7  816.12    5010  818.44  5182.4  828.01  5355.9   838.3
#Mann= 5 ,-1 , 0
  2410.5     .05       0  3433.6     .12       0  4948.3     .07       0
  4999.7     .12       0  5182.4     .05       0
#XS Ineff= 2 , 0
       0  4075.7  822.85               0
Permanent Ineff=
       F       F
Bank Sta=4948.3,4999.7
XS Rating Curve= 0 ,0
Exp/Cntr=0.3,0.1

Type RM Length L Ch R = 1 ,2264    ,440,440,440
BEGIN DESCRIPTION:
UDS St 21 3.0
END DESCRIPTION:
XS GIS Cut Line= 3
      2270529.01      7187909.99        2268729.        7189710.
      2268279.23      7190269.81
#Sta/Elev= 30
  2454.4  833.61  2652.4  821.63    2709  819.38  2793.8  820.63    2907   818.5
  2991.8  821.32    3006  819.57  3034.2  820.46  3048.4  818.93  3076.7  820.67
  3330.8     818  3515.1  817.12    3963  820.95  4490.9  816.23  4871.7  815.72
  4971.7  816.52  4985.8  810.82  4989.5  802.91  4991.5  802.41  5003.5  802.91
  5021.6  814.26    5028  816.86  5048.8  816.43  5128.3     817  5141.6  815.64
  5184.8  815.37  5469.6  819.14  5682.4  819.34  5696.8   820.1  5718.1  825.28
#Mann= 7 ,-1 , 0
  2454.4     .05       0  3330.8     .12       0    3963     .05       0
  4871.7     .12       0  4989.5     .07       0  5003.5     .12       0
  5048.8     .05       0
#XS Ineff= 2 , 0
       0  3925.2  821.41               0
Permanent Ineff=
       F       F
Bank Sta=4989.5,5003.5
XS Rating Curve= 0 ,0
Exp/Cntr=0.3,0.1