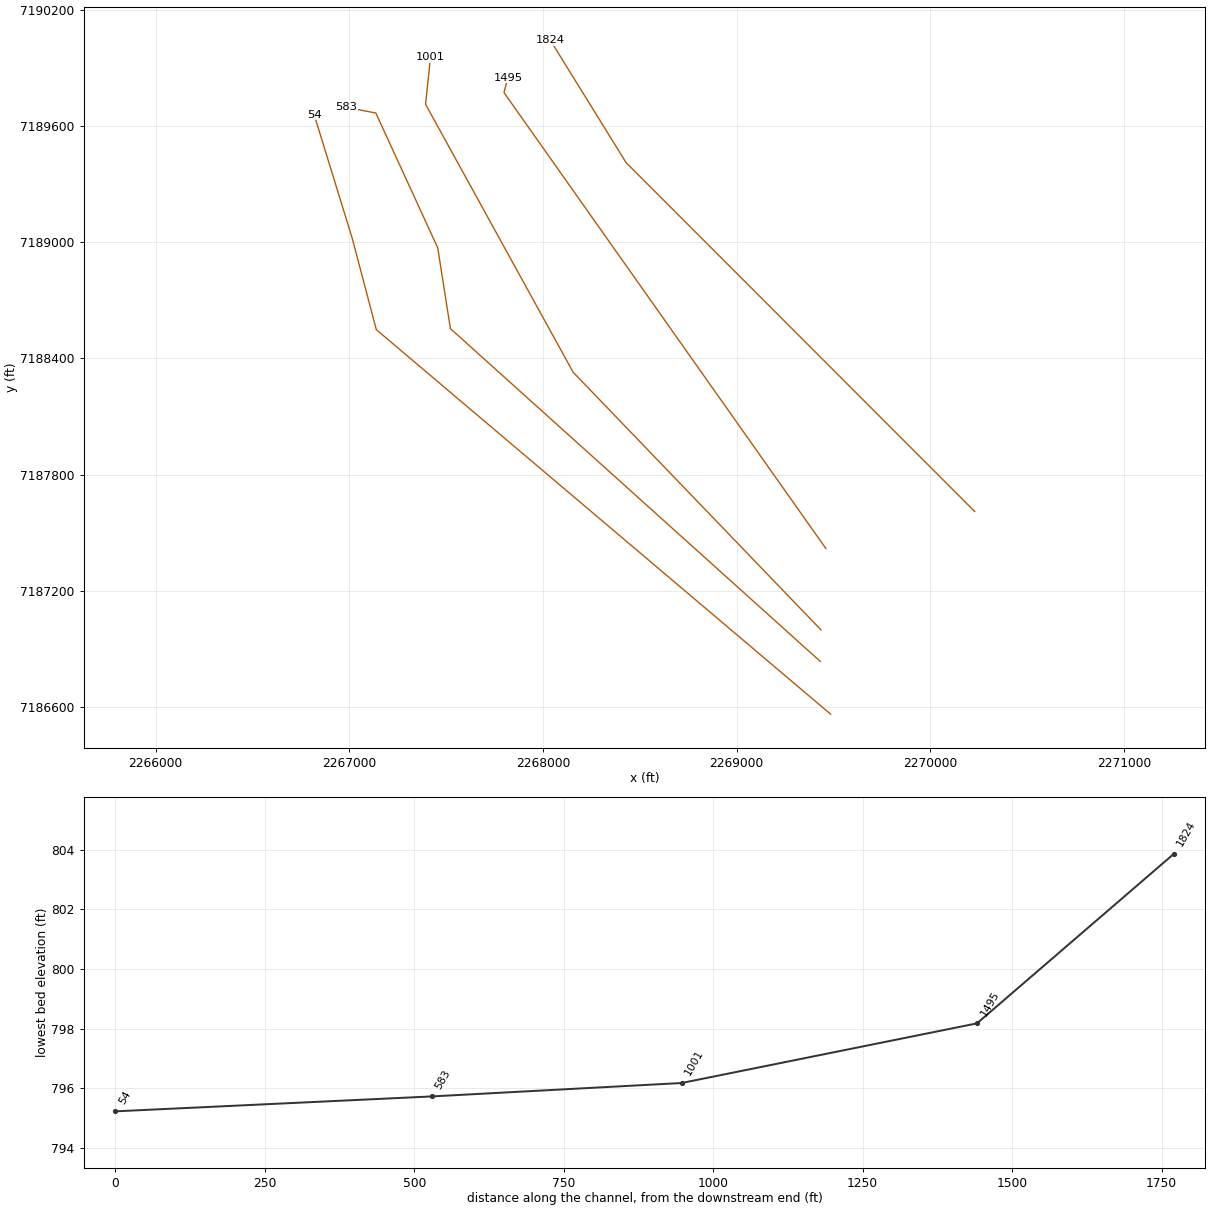
HEC-RAS study UDS St 21.prj: UDS St 21 Base Level Engineering

--- UDS St 21.g01 (geometry) --- (continued)

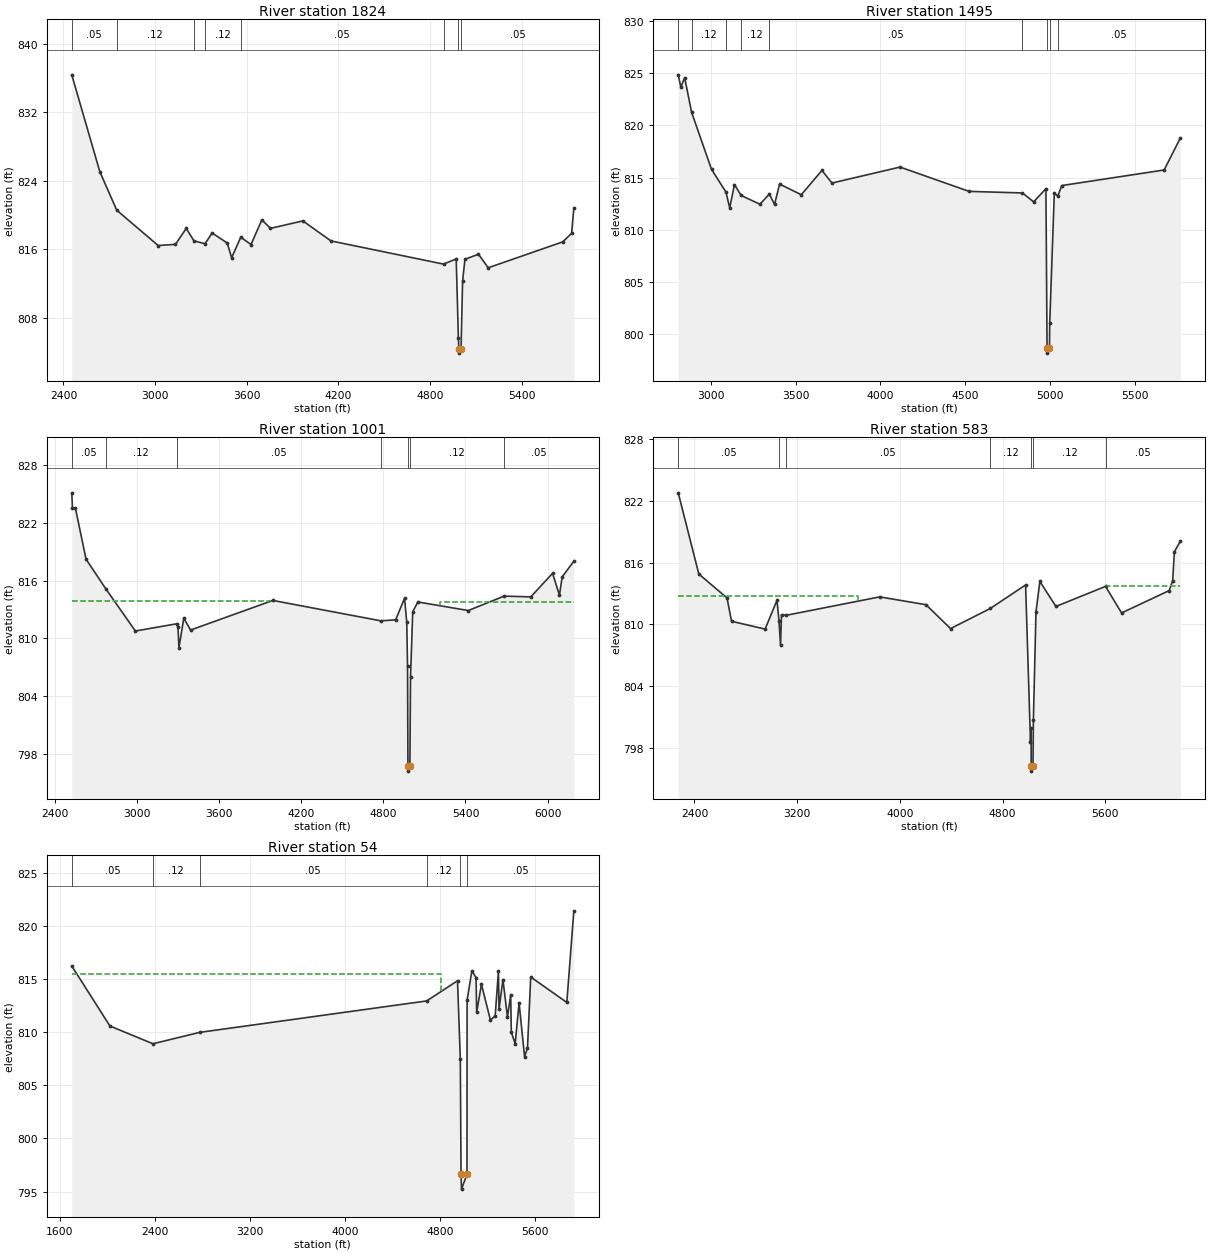
Type RM Length L Ch R = 1 ,1824    ,329,329,329
BEGIN DESCRIPTION:
UDS St 21 2.0
END DESCRIPTION:
XS GIS Cut Line= 3
      2270229.03      7187609.97        2268429.        7189410.
      2268038.31      7190040.78
#Sta/Elev= 30
  2454.4   836.4  2638.3  825.06    2749  820.57  3020.1  816.44  3133.3  816.58
    3204  818.44  3254.4  816.99  3326.8  816.65  3373.7  817.91  3472.7  816.73
    3501  815.01  3560.9  817.41  3628.2  816.56    3699  819.44  3755.5  818.45
  3967.7  819.32  4151.5  816.98  4888.5  814.27  4971.7  814.87  4985.9  805.66
  4989.5  804.36  4991.5  803.86  5003.5  804.36  5013.6  812.31    5029  814.84
  5117.6  815.42  5181.4  813.84  5669.4  816.87  5727.3  817.87    5742  820.79
#Mann= 8 ,-1 , 0
  2454.4     .05       0    2749     .12       0  3254.4     .05       0
  3326.8     .12       0  3560.9     .05       0  4888.5     .12       0
  4985.9    .033       0  5003.5     .05       0
#XS Ineff= 2 , 0
       0    3699  819.44               0
Permanent Ineff=
       F       F
Bank Sta=4989.5,5003.5
XS Rating Curve= 0 ,0
Exp/Cntr=0.3,0.1

Type RM Length L Ch R = 1 ,1495    ,494,494,494
BEGIN DESCRIPTION:
UDS St 21 1.3
END DESCRIPTION:
XS GIS Cut Line= 3
      2269460.35      7187419.07      2267798.38      7189771.67
      2267818.58      7189849.46
#Sta/Elev= 30
  2808.2  824.85  2823.5  823.67  2846.1  824.58  2887.2  821.25  3004.5  815.79
  3089.7  813.61  3111.6  812.11  3139.9  814.33  3178.9  813.29  3290.1  812.45
  3345.4  813.42  3376.2  812.43  3405.8  814.38  3533.8  813.36  3655.7  815.69
  3714.8  814.48  4116.2  816.01  4523.6  813.68  4838.1  813.53    4904  812.68
  4976.5  813.94  4983.2  798.68  4985.2  798.18  4997.3  798.68  4998.9  801.04
  5025.9  813.48  5046.5  813.24  5070.3  814.24  5673.6  815.73    5769  818.79
#Mann= 9 ,-1 , 0
  2808.2     .05       0  2887.2     .12       0  3089.7     .05       0
  3178.9     .12       0  3345.4     .05       0  4838.1     .12       0
  4983.2     .07       0  4998.9     .12       0  5046.5     .05       0
#XS Ineff= 2 , 0
       0  4116.2  816.01               0
Permanent Ineff=
       F       F
Bank Sta=4983.2,4997.3
XS Rating Curve= 0 ,0
Exp/Cntr=0.3,0.1

Type RM Length L Ch R = 1 ,1001    ,418,418,418
BEGIN DESCRIPTION:
UDS St 21 1.2
END DESCRIPTION:
XS GIS Cut Line= 4
      2269435.26      7186998.89      2268155.36      7188328.87
      2267393.58      7189711.18      2267418.91      7189954.74
#Sta/Elev= 30
    2523  825.12  2528.2  823.52  2549.5  823.54  2627.2  818.22  2773.6   815.1
  2987.9  810.75  3289.2   811.5  3299.2  811.13  3306.1  809.02  3341.6  812.09
    3391  810.85  3992.3  813.93  4781.3  811.81  4889.6  811.91  4954.9  814.15
    4971  811.66  4976.7  807.07  4979.6  796.68  4981.6  796.18  4993.8  796.68
  4998.5  805.94  5014.6  812.76  5052.4  813.77  5420.6  812.88  5682.3  814.38
  5877.3   814.3  6036.4  816.75  6086.7  814.48  6106.8  816.38    6192  818.01
#Mann= 7 ,-1 , 0
    2523     .05       0  2773.6     .12       0  3289.2     .05       0
  4781.3     .12       0  4976.7     .07       0  4993.8     .12       0
  5682.3     .05       0
#XS Ineff= 2 , 0
       0  3978.1  813.88    5215       0  813.75
Permanent Ineff=
       F       F
Bank Sta=4979.6,4993.8
XS Rating Curve= 0 ,0
Exp/Cntr=0.3,0.1

Type RM Length L Ch R = 1 ,583     ,529,529,529
BEGIN DESCRIPTION:
UDS St 21 1.1
END DESCRIPTION:
XS GIS Cut Line= 5
      2269431.61      7186836.39      2267521.75      7188553.69
      2267456.39      7188970.33       2267136.7      7189666.24
      2266983.64      7189696.05
#Sta/Elev= 30
  2273.5  822.77  2433.8  814.88  2653.6  812.56  2688.7  810.29  2950.3  809.53
    3043  812.33  3058.6  810.33  3070.6  807.94  3078.1  810.93    3111  810.86
  3842.8  812.66  4203.8   811.9  4395.1  809.58  4705.7  811.54  4979.9  813.82
  5018.1  798.59  5023.2  799.92  5023.4  796.23  5025.4  795.73  5037.6  796.23
  5040.6  800.71  5060.9   811.2  5091.2  814.16  5216.2  811.73  5602.7  813.68
  5727.7   811.1  6098.4  813.27  6125.8  814.24  6139.2  817.04  6185.4  818.07
#Mann= 7 ,-1 , 0
  2273.5     .05       0  3058.6     .12       0    3111     .05       0
  4705.7     .12       0  5023.2     .07       0  5040.6     .12       0
  5602.7     .05       0
#XS Ineff= 2 , 0
       0  3673.1  812.78  5601.8       0  813.72
Permanent Ineff=
       F       F
Bank Sta=5023.4,5037.6
XS Rating Curve= 0 ,0
Exp/Cntr=0.3,0.1

Type RM Length L Ch R = 1 ,54      ,0,0,0
BEGIN DESCRIPTION:
UDS St 21 1.0
END DESCRIPTION:
XS GIS Cut Line= 4
      2269485.03      7186564.15      2267139.13      7188548.47
      2267014.91      7189019.17      2266818.63      7189656.53
#Sta/Elev= 30
  1702.5  816.23  2023.6  810.58    2386  808.91  2778.3  809.98  4689.9  812.94
  4949.6  814.84  4973.2  807.45  4979.2  796.63  4983.2  795.23  5029.2  796.63
  5030.2  813.01  5070.5  815.78  5105.6  815.13  5110.8  811.87    5151  814.51
  5226.4  811.14  5266.5  811.52  5293.9  815.73  5299.2   812.2  5331.9  814.95
  5369.8  811.44  5397.2  813.49  5402.5  809.98  5435.1  808.93  5467.8  812.78
  5513.9   807.7  5538.4  808.49  5565.9  815.19  5869.6   812.8  5928.8  821.42
#Mann= 6 ,-1 , 0
  1702.5     .05       0    2386     .12       0  2778.3     .05       0
  4689.9     .12       0  4973.2    .033       0  5029.2     .05       0
#XS Ineff= 2 , 0
       0  4807.7  815.43  5105.6       0  815.13
Permanent Ineff=
       F       F
Bank Sta=4979.2,5029.2
XS Rating Curve= 0 ,0
Exp/Cntr=0.3,0.1

Chan Stop Cuts=-1
Use User Specified Reach Order=0
Composite Channel Slope=5