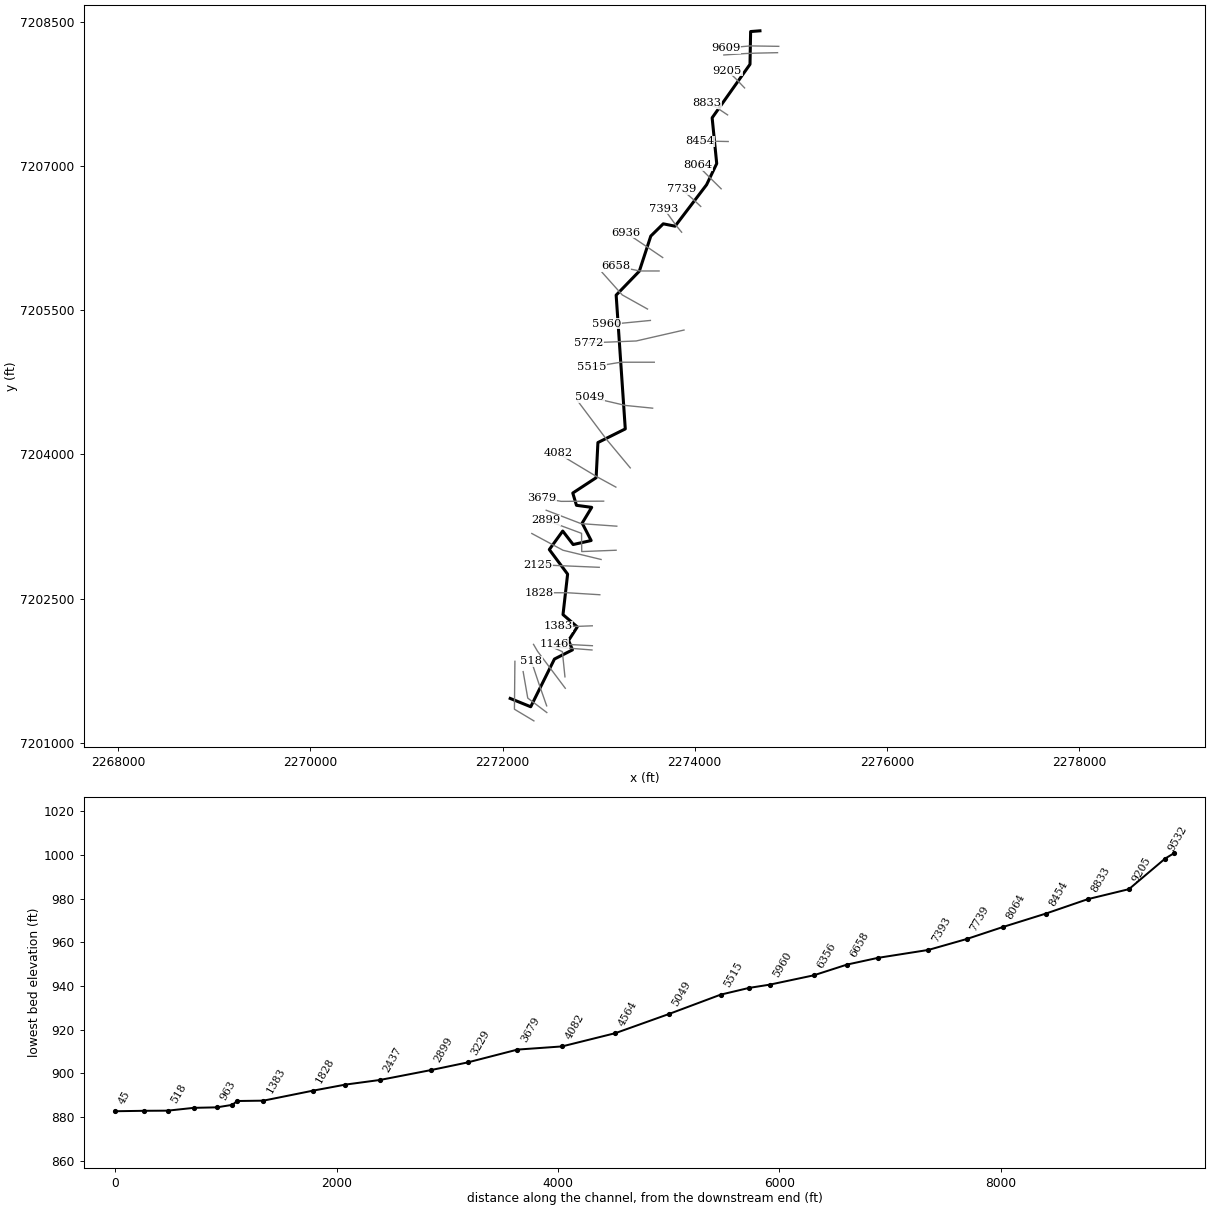
--- UDS St 22.prj (project) ---

Proj Title=UDS St 22 Base Level Engineering
Current Plan=p01
Default Exp/Contr=0.3,0.1
English Units
Geom File=g01
Flow File=f01
Plan File=p01
BEGIN DESCRIPTION:
UDS St 22
END DESCRIPTION:

--- UDS St 22.p01 (plan) ---

Plan Title=Multiple Run
Short Identifier=Multiple
Geom File=g01
Flow File=f01
Subcritical Flow
K Sum by GR= 0
Std Step Tol= 0.01
Critical Tol= 0.01
Num of Std Step Trials= 20
Max Error Tol= 0.3
Flow Tol Ratio= 0.001
Split Flow NTrial= 30
Split Flow Tol= 0.02
Split Flow Ratio= 0.02
Log Output Level= 0
Friction Slope Method= 1
Unsteady Friction Slope Method= 2
Unsteady Bridges Friction Slope Method= 1
Parabolic Critical Depth
Global Vel Dist=  1 , 1 , 1
Global Log Level= 0
CheckData=True
Encroach Param= -1, 0, 0, 0
BEGIN DESCRIPTION:
Multiple Run
END DESCRIPTION:

--- UDS St 22.f01 (steady flow) ---

Flow Title=Multiple
Number of Profiles=7
Profile Names=10-year,25-year,50-year,1pct_min,100-year,1pct_plu,500-year
River Rch & RM= UDS St 22,Reach-1,9609
     687     958    1187     730    1457    2907    2201
River Rch & RM= UDS St 22,Reach-1,5772
     884    1248    1558     965    1926    3844    2953
Boundary for River Rch & Prof#=UDS St 22,Reach-1,1
Up Type=0
Dn Type=3
Dn Slope=0.005
Boundary for River Rch & Prof#=UDS St 22,Reach-1,2
Up Type=0
Dn Type=3
Dn Slope=0.005
Boundary for River Rch & Prof#=UDS St 22,Reach-1,3
Up Type=0
Dn Type=3
Dn Slope=0.005
Boundary for River Rch & Prof#=UDS St 22,Reach-1,4
Up Type=0
Dn Type=3
Dn Slope=0.005
Boundary for River Rch & Prof#=UDS St 22,Reach-1,5
Up Type=0
Dn Type=3
Dn Slope=0.005
Boundary for River Rch & Prof#=UDS St 22,Reach-1,6
Up Type=0
Dn Type=3
Dn Slope=0.005
Boundary for River Rch & Prof#=UDS St 22,Reach-1,7
Up Type=0
Dn Type=3
Dn Slope=0.005

--- UDS St 22.g01 (geometry) ---

Geom Title=Existing Conditions

River Reach=UDS St 22,Reach-1
Reach XY= 30
      2274679.00      7208410.00      2274581.91      7208402.55
      2274575.46      7208061.46      2274181.35      7207504.48
      2274228.91      7207028.22      2274123.48      7206807.56
      2273795.67      7206376.23      2273672.27      7206400.85
      2273542.62      7206273.22      2273423.17      7205907.70
      2273182.13      7205658.37      2273277.03      7204265.65
      2272992.19      7204123.66      2272973.54      7203757.54
      2272730.50      7203598.14      2272768.82      7203470.33
      2272927.45      7203449.05      2272828.39      7203285.08
      2272921.68      7203103.62      2272734.26      7203062.08
      2272625.83      7203202.49      2272486.20      7203009.70
      2272676.74      7202754.06      2272628.79      7202332.69
      2272777.31      7202204.37      2272686.84      7202063.40
      2272727.31      7201965.43      2272539.61      7201870.06
      2272292.76      7201373.24      2272079.00      7201460.00

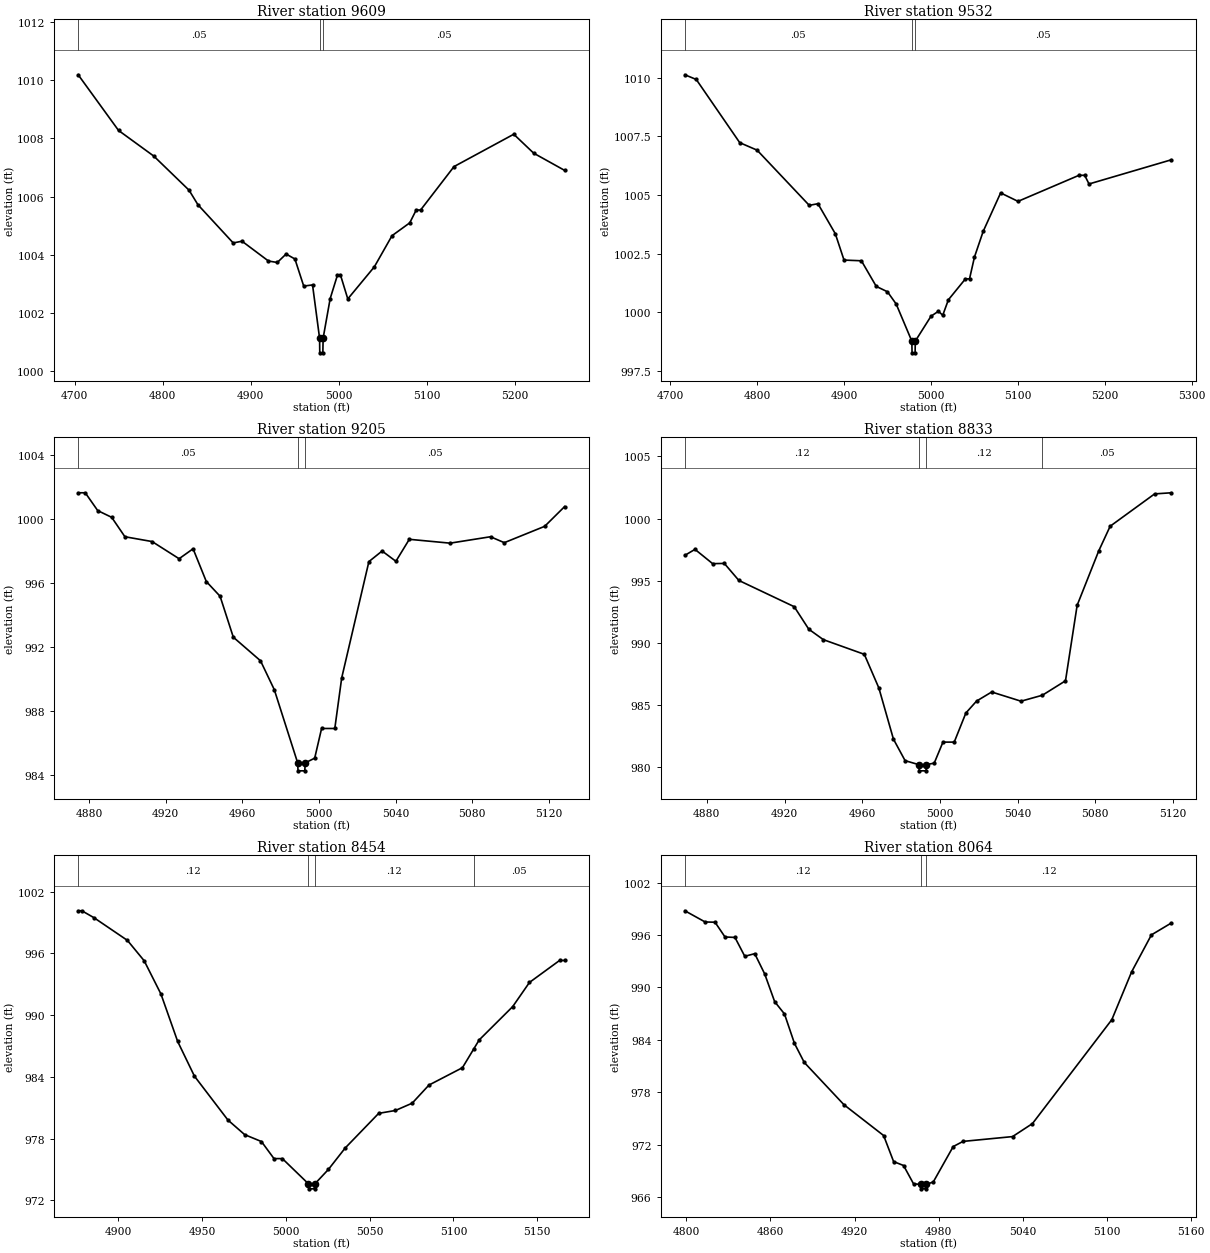
Type RM Length L Ch R = 1,9609,77,77,77
BEGIN DESCRIPTION:
UDS St 22 22.1
END DESCRIPTION:
XS GIS Cut Line= 3
      2274874.83      7208248.44      2274577.29      7208252.95
      2274324.01      7208230.02
#Sta/Elev= 30
  4704.1 1010.18  4749.9 1008.27  4789.9 1007.39  4829.9 1006.22  4840.0 1005.72
  4880.0 1004.41  4890.0 1004.47  4920.0 1003.79  4930.0 1003.74  4940.0 1004.03
  4950.0 1003.86  4960.0 1002.93  4970.0 1002.97  4978.0 1001.14  4978.2 1000.64
  4981.7 1000.64  4982.0 1001.14  4990.0 1002.50  4998.3 1003.31  5001.7 1003.31
  5010.0 1002.49  5040.1 1003.59  5060.2 1004.66  5080.3 1005.10  5087.6 1005.54
  5092.6 1005.54  5130.5 1007.03  5198.3 1008.14  5220.9 1007.49  5256.0 1006.90
#Mann=3,-1,0
  4704.1    0.05       0  4978.0   0.033       0  4982.0    0.05       0
Bank Sta=4978,4982
Exp/Cntr=0.3,0.1

Type RM Length L Ch R = 1,9532,327,327,327
BEGIN DESCRIPTION:
UDS St 22 22.0
END DESCRIPTION:
XS GIS Cut Line= 4
      2274862.06      7208182.51      2274639.74      7208177.62
      2274534.67      7208173.84      2274302.99      7208158.53
#Sta/Elev= 30
  4716.9 1010.12  4730.0 1009.92  4780.0 1007.23  4800.0 1006.91  4860.0 1004.56
  4870.0 1004.63  4890.0 1003.35  4900.0 1002.23  4920.0 1002.20  4937.1 1001.11
  4950.0 1000.88  4960.0 1000.36  4978.0  998.78  4978.3  998.28  4981.8  998.28
  4982.0  998.78  5000.1  999.84  5008.6 1000.05  5013.6  999.88  5020.1 1000.54
  5039.7 1001.43  5044.4 1001.43  5050.1 1002.36  5060.1 1003.45  5080.2 1005.09
  5100.2 1004.73  5170.4 1005.84  5176.9 1005.84  5181.9 1005.47  5276.6 1006.50
#Mann=3,-1,0
  4716.9    0.05       0  4978.0   0.033       0  4982.0    0.05       0
Bank Sta=4978,4982
Exp/Cntr=0.3,0.1

Type RM Length L Ch R = 1,9205,372,372,372
BEGIN DESCRIPTION:
UDS St 22 21.0
END DESCRIPTION:
XS GIS Cut Line= 3
      2274519.09      7207815.51      2274429.00      7207910.00
      2274339.81      7207995.34
#Sta/Elev= 30
  4874.3 1001.62  4878.0 1001.62  4884.5 1000.51  4891.8 1000.09  4898.7  998.88
  4912.9  998.58  4927.0  997.51  4934.3  998.13  4941.2  996.09  4948.4  995.17
  4955.3  992.62  4969.5  991.15  4976.7  989.35  4988.9  984.79  4989.1  984.29
  4992.6  984.29  4992.9  984.79  4997.8  985.08  5001.4  986.93  5008.3  986.93
  5011.9  990.08  5026.1  997.33  5033.0  997.99  5040.2  997.35  5047.2  998.72
  5068.5  998.48  5089.6  998.88  5096.8  998.51  5117.9  999.53  5128.3 1000.76
#Mann=3,-1,0
  4874.3    0.05       0  4988.9   0.033       0  4992.9    0.05       0
Bank Sta=4988.9,4992.9
Exp/Cntr=0.3,0.1

Type RM Length L Ch R = 1,8833,379,379,379
BEGIN DESCRIPTION:
UDS St 22 20.0
END DESCRIPTION:
XS GIS Cut Line= 3
      2274342.12      7207534.60      2274229.00      7207610.00
      2274125.01      7207658.06
#Sta/Elev= 30
  4868.7  997.04  4873.9  997.52  4883.0  996.37  4889.0  996.39  4896.5  995.02
  4925.0  992.91  4932.5  991.10  4940.0  990.26  4961.1  989.08  4968.6  986.37
  4976.1  982.26  4982.1  980.53  4989.1  980.21  4989.4  979.71  4992.9  979.71
  4993.1  980.21  4997.1  980.33  5001.6  982.02  5007.4  982.02  5013.4  984.36
  5018.9  985.32  5026.7  986.05  5041.8  985.31  5052.8  985.79  5064.7  986.95
  5070.7  993.02  5081.8  997.39  5087.7  999.38  5110.6 1001.98  5119.2 1002.07
#Mann=4,-1,0
  4868.7    0.12       0  4989.1    0.07       0  4993.1    0.12       0
  5052.8    0.05       0
Bank Sta=4989.1,4993.1
Exp/Cntr=0.3,0.1

Type RM Length L Ch R = 1,8454,390,390,390
BEGIN DESCRIPTION:
UDS St 22 19.0
END DESCRIPTION:
XS GIS Cut Line= 3
      2274348.39      7207257.61      2274229.00      7207260.00
      2274058.02      7207261.34
#Sta/Elev= 30
  4876.0 1000.15  4878.2 1000.15  4885.4  999.48  4905.4  997.27  4915.4  995.29
  4925.4  992.06  4935.4  987.44  4945.4  984.07  4965.4  979.80  4975.4  978.38
  4985.4  977.71  4992.9  976.05  4997.9  976.05  5013.4  973.61  5013.7  973.11
  5017.2  973.11  5017.4  973.61  5025.4  975.00  5035.4  977.08  5055.4  980.45
  5065.4  980.73  5075.4  981.44  5085.4  983.20  5105.4  984.89  5112.1  986.70
  5115.4  987.59  5135.4  990.83  5145.4  993.18  5163.4  995.32  5166.4  995.32
#Mann=4,-1,0
  4876.0    0.12       0  5013.4    0.07       0  5017.4    0.12       0
  5112.1    0.05       0
Bank Sta=5013.4,5017.4
Exp/Cntr=0.3,0.1

Type RM Length L Ch R = 1,8064,325,325,325
BEGIN DESCRIPTION:
UDS St 22 18.0
END DESCRIPTION:
XS GIS Cut Line= 3
      2274275.01      7206765.60      2274129.00      7206910.00
      2274028.98      7207010.02
#Sta/Elev= 30
  4799.0  998.77  4813.4  997.49  4820.5  997.46  4827.6  995.77  4834.7  995.72
  4841.7  993.56  4848.8  993.86  4855.9  991.54  4863.0  988.37  4870.0  986.96
  4877.1  983.60  4884.1  981.41  4912.4  976.57  4940.7  973.04  4947.8  970.06
  4954.9  969.61  4962.0  967.52  4967.0  967.44  4967.2  966.94  4970.7  966.94
  4971.0  967.44  4976.1  967.73  4990.3  971.78  4997.3  972.37  5032.6  972.92
  5046.8  974.41  5103.4  986.31  5117.5  991.78  5131.6  996.01  5145.8  997.37
#Mann=3,-1,0
  4799.0    0.12       0  4967.0    0.07       0  4971.0    0.12       0
Bank Sta=4967,4971
Exp/Cntr=0.3,0.1

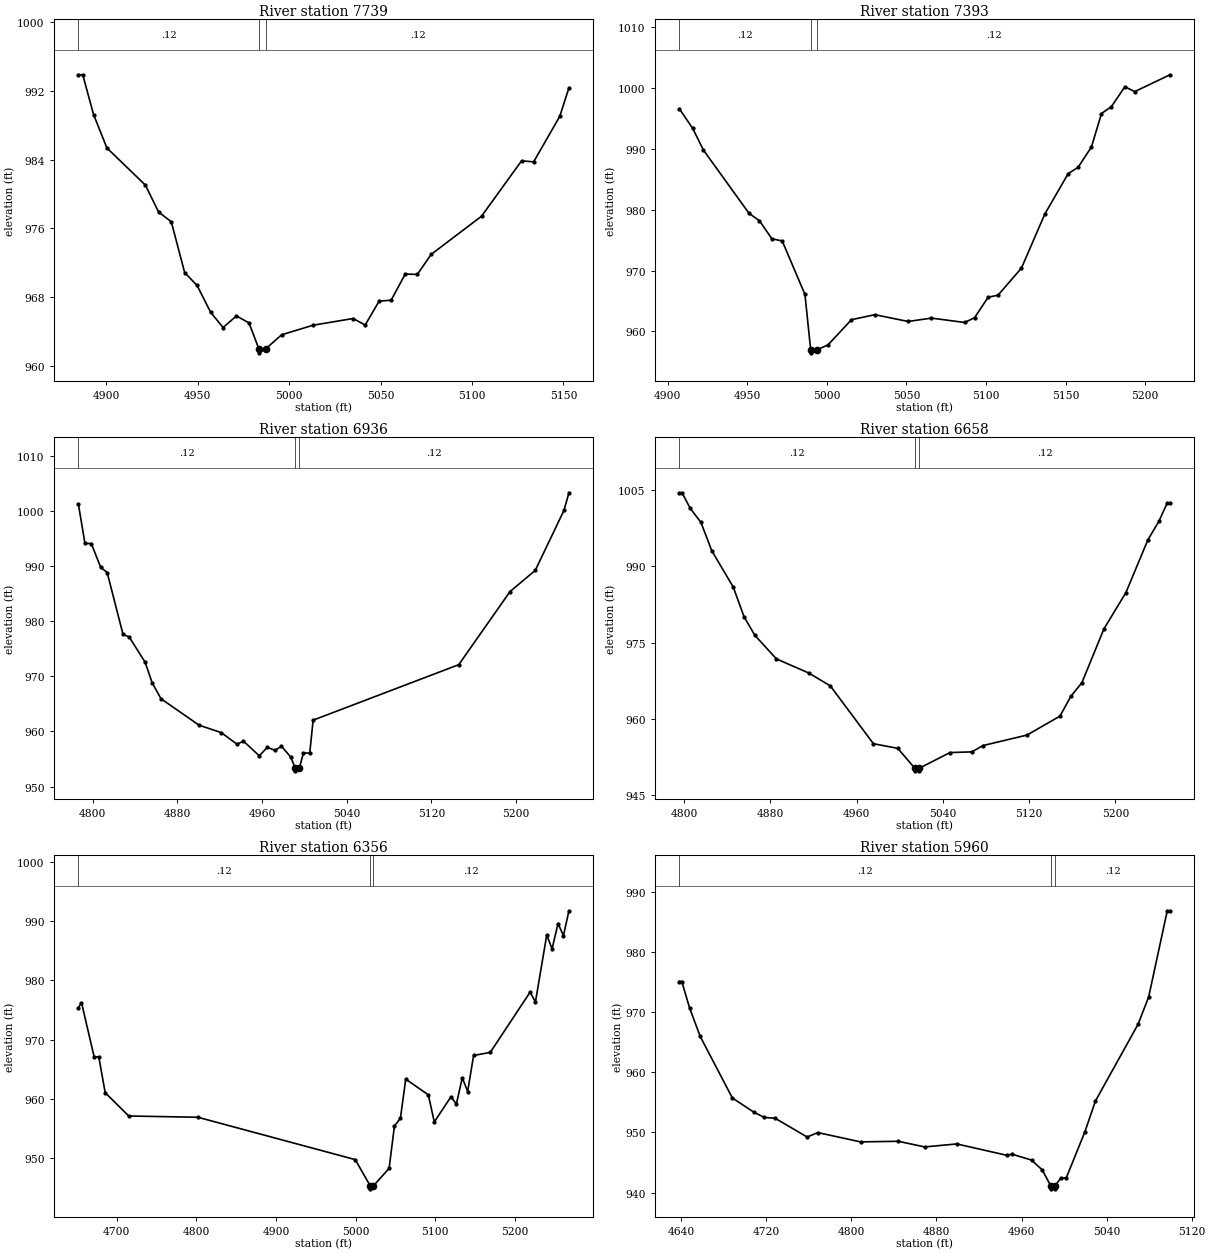
Type RM Length L Ch R = 1,7739,346,346,346
BEGIN DESCRIPTION:
UDS St 22 17.0
END DESCRIPTION:
XS GIS Cut Line= 3
      2274062.63      7206581.75      2273979.00      7206660.00
      2273862.69      7206760.44
#Sta/Elev= 30
  4884.8  993.89  4887.2  993.89  4893.1  989.25  4900.4  985.36  4921.4  981.04
  4928.7  977.88  4935.6  976.76  4942.9  970.84  4949.7  969.33  4957.1  966.21
  4963.9  964.43  4971.2  965.78  4978.1  964.97  4983.4  961.98  4983.6  961.48
  4987.4  961.98  4995.9  963.58  5013.1  964.70  5035.0  965.48  5041.6  964.72
  5049.2  967.50  5055.8  967.62  5063.5  970.66  5070.1  970.62  5077.7  972.96
  5105.2  977.40  5127.1  983.86  5133.7  983.74  5148.0  989.05  5153.0  992.37
#Mann=3,-1,0
  4884.8    0.12       0  4983.4    0.07       0  4987.4    0.12       0
Bank Sta=4983.4,4987.4
Exp/Cntr=0.3,0.1

Type RM Length L Ch R = 1,7393,457,457,457
BEGIN DESCRIPTION:
UDS St 22 16.0
END DESCRIPTION:
XS GIS Cut Line= 3
      2273863.80      7206313.56      2273806.86      7206382.32
      2273678.99      7206560.02
#Sta/Elev= 30
  4907.3  996.55  4915.7  993.32  4922.4  989.78  4951.1  979.37  4957.6  978.18
  4965.4  975.21  4971.9  974.86  4986.2  966.08  4989.8  956.99  4990.1  956.49
  4993.8  956.99  5000.7  957.79  5015.4  961.93  5030.1  962.75  5051.0  961.64
  5065.7  962.19  5086.6  961.47  5092.8  962.27  5101.3  965.62  5107.5  965.95
  5122.2  970.39  5136.9  979.27  5151.6  985.91  5157.8  986.94  5166.2  990.28
  5172.5  995.77  5178.7  996.90  5187.2 1000.16  5193.4  999.37  5215.5 1002.13
#Mann=3,-1,0
  4907.3    0.12       0  4989.8    0.07       0  4993.8    0.12       0
Bank Sta=4989.8,4993.8
Exp/Cntr=0.3,0.1

Type RM Length L Ch R = 1,6936,278,278,278
BEGIN DESCRIPTION:
UDS St 22 15.0
END DESCRIPTION:
XS GIS Cut Line= 3
      2273666.65      7206049.83      2273487.65      7206171.49
      2273282.60      7206309.32
#Sta/Elev= 30
  4786.4 1001.27  4792.6  994.14  4798.6  994.10  4807.5  989.78  4813.6  988.85
  4828.5  977.67  4834.6  977.09  4849.5  972.55  4856.1  968.83  4864.5  965.93
  4900.4  961.14  4921.4  959.79  4936.3  957.68  4942.4  958.24  4957.3  955.58
  4964.9  957.12  4972.2  956.57  4978.3  957.33  4987.2  955.31  4991.2  953.35
  4991.5  952.85  4995.2  953.35  4999.0  956.08  5005.0  956.08  5008.2  962.05
  5145.8  972.12  5194.2  985.38  5218.1  989.24  5245.2 1000.12  5249.9 1003.32
#Mann=3,-1,0
  4786.4    0.12       0  4991.2    0.07       0  4995.2    0.12       0
Bank Sta=4991.2,4995.2
Exp/Cntr=0.3,0.1

Type RM Length L Ch R = 1,6658,302,302,302
BEGIN DESCRIPTION:
UDS St 22 14.0
END DESCRIPTION:
XS GIS Cut Line= 3
      2273629.00      7205910.00      2273429.00      7205910.00
      2273178.95      7205960.01
#Sta/Elev= 30
  4795.6 1004.44  4798.1 1004.44  4805.6 1001.41  4815.6  998.62  4825.6  993.07
  4845.6  985.90  4855.6  980.07  4865.6  976.43  4885.6  971.79  4915.6  969.02
  4935.6  966.49  4975.6  955.12  4998.2  954.21  5014.0  950.29  5014.2  949.79
  5017.7  949.79  5018.0  950.29  5046.6  953.38  5067.0  953.52  5077.2  954.76
  5118.0  956.82  5148.6  960.54  5158.8  964.46  5169.0  967.13  5189.4  977.70
  5209.8  984.83  5230.2  995.21  5240.4  998.85  5248.0 1002.40  5250.6 1002.40
#Mann=3,-1,0
  4795.6    0.12       0  5014.0    0.07       0  5018.0    0.12       0
Bank Sta=5014,5018
Exp/Cntr=0.3,0.1

Type RM Length L Ch R = 1,6356,396,396,396
BEGIN DESCRIPTION:
UDS St 22 13.0
END DESCRIPTION:
XS GIS Cut Line= 3
      2273508.43      7205513.69      2273245.70      7205660.53
      2273035.47      7205895.81
#Sta/Elev= 30
  4651.7  975.40  4655.6  976.27  4671.6  967.06  4677.3  967.13  4685.4  961.07
  4715.0  957.14  4801.8  956.93  4999.6  949.79  5018.5  945.36  5018.7  944.86
  5022.5  945.36  5042.2  948.32  5048.9  955.46  5056.4  956.74  5063.1  963.36
  5091.5  960.70  5099.0  956.13  5120.0  960.40  5126.7  959.14  5134.2  963.59
  5140.9  961.26  5148.4  967.35  5169.3  967.86  5219.4  978.02  5226.1  976.36
  5240.3  987.65  5247.0  985.33  5254.5  989.59  5261.3  987.55  5268.2  991.74
#Mann=3,-1,0
  4651.7    0.12       0  5018.5    0.07       0  5022.5    0.12       0
Bank Sta=5018.5,5022.5
Exp/Cntr=0.3,0.1

Type RM Length L Ch R = 1,5960,188,188,188
BEGIN DESCRIPTION:
UDS St 22 12.0
END DESCRIPTION:
XS GIS Cut Line= 3
      2273538.55      7205394.92      2273179.00      7205360.00
      2273079.04      7205360.00
#Sta/Elev= 30
  4638.3  975.14  4640.6  975.14  4647.9  970.74  4657.9  965.99  4688.1  955.75
  4708.2  953.39  4718.2  952.50  4728.3  952.37  4758.4  949.24  4768.5  949.98
  4808.6  948.43  4844.1  948.53  4868.9  947.59  4899.1  948.09  4946.0  946.20
  4951.1  946.38  4969.4  945.40  4979.4  943.77  4987.5  941.11  4987.7  940.61
  4991.2  940.61  4991.5  941.11  4997.0  942.42  5002.0  942.42  5019.5  950.08
  5029.5  955.25  5069.5  968.00  5079.5  972.56  5097.0  986.92  5099.5  986.92
#Mann=3,-1,0
  4638.3    0.12       0  4987.5    0.07       0  4991.5    0.12       0
Bank Sta=4987.5,4991.5
Exp/Cntr=0.3,0.1

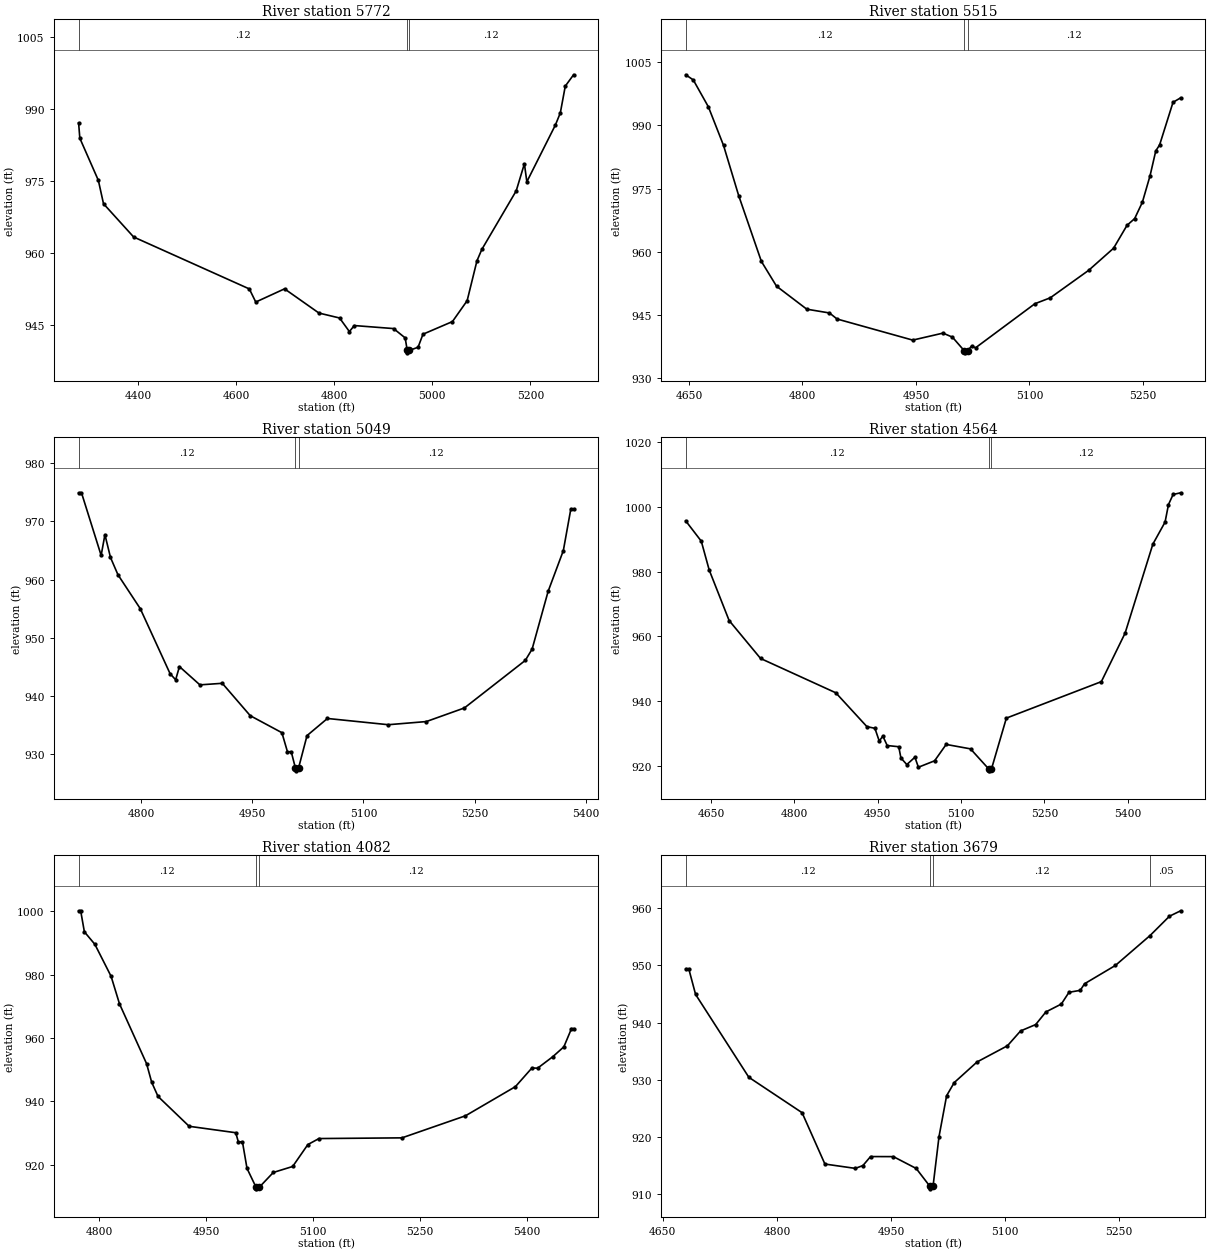
Type RM Length L Ch R = 1,5772,257,257,257
BEGIN DESCRIPTION:
UDS St 22 11.1
END DESCRIPTION:
XS GIS Cut Line= 3
      2273888.51      7205295.10      2273390.86      7205181.26
      2272892.07      7205161.00
#Sta/Elev= 30
  4278.5  987.16  4281.0  983.95  4318.8  975.14  4329.3  970.26  4390.8  963.31
  4626.8  952.46  4639.9  949.72  4698.6  952.48  4768.8  947.42  4810.9  946.39
  4830.9  943.55  4840.9  944.81  4921.0  944.18  4944.7  942.23  4948.9  939.61
  4949.2  939.11  4953.1  939.61  4971.0  940.28  4981.0  943.00  5041.1  945.64
  5071.1  950.00  5091.1  958.33  5101.1  960.72  5171.2  972.95  5187.9  978.61
  5192.9  974.85  5251.2  986.72  5261.2  989.24  5271.3  994.83  5288.2  997.20
#Mann=3,-1,0
  4278.5    0.12       0  4948.9    0.07       0  4953.1    0.12       0
Bank Sta=4948.9,4953.1
Exp/Cntr=0.3,0.1

Type RM Length L Ch R = 1,5515,466,466,466
BEGIN DESCRIPTION:
UDS St 22 11.0
END DESCRIPTION:
XS GIS Cut Line= 3
      2273579.00      7204960.00      2273229.00      7204960.00
      2272929.04      7204910.01
#Sta/Elev= 30
  4645.7 1002.01  4655.7 1000.79  4675.7  994.39  4695.7  985.24  4715.7  973.34
  4745.7  957.72  4765.7  951.84  4805.7  946.38  4835.7  945.48  4845.7  944.05
  4945.7  939.04  4985.7  940.70  4998.2  939.74  5013.8  936.52  5014.2  936.02
  5018.1  936.52  5023.6  937.64  5028.7  937.21  5107.2  947.68  5127.5  949.08
  5178.2  955.60  5211.1  960.84  5228.9  966.28  5239.0  967.88  5249.2  971.77
  5259.3  978.02  5266.9  983.94  5272.0  985.38  5289.7  995.48  5299.8  996.54
#Mann=3,-1,0
  4645.7    0.12       0  5013.8    0.07       0  5018.1    0.12       0
Bank Sta=5013.8,5018.1
Exp/Cntr=0.3,0.1

Type RM Length L Ch R = 1,5049,485,485,485
BEGIN DESCRIPTION:
UDS St 22 10.0
END DESCRIPTION:
XS GIS Cut Line= 3
      2273561.83      7204481.73      2273279.00      7204510.00
      2272905.57      7204596.70
#Sta/Elev= 30
  4715.8  974.93  4719.7  974.93  4746.2  964.18  4751.3  967.74  4758.8  963.83
  4768.9  960.85  4799.0  955.03  4839.2  943.87  4846.7  942.82  4851.8  945.09
  4879.4  941.95  4909.6  942.22  4947.3  936.66  4990.0  933.74  4997.5  930.47
  5002.6  930.47  5008.2  927.69  5008.5  927.19  5012.5  927.69  5023.9  933.24
  5051.4  936.18  5133.5  935.11  5184.8  935.65  5236.2  937.99  5318.3  946.15
  5327.5  948.09  5349.1  958.01  5369.6  965.00  5379.7  972.14  5383.4  972.14
#Mann=3,-1,0
  4715.8    0.12       0  5008.2    0.07       0  5012.5    0.12       0
Bank Sta=5008.2,5012.5
Exp/Cntr=0.3,0.1

Type RM Length L Ch R = 1,4564,482,482,482
BEGIN DESCRIPTION:
UDS St 22 9.0
END DESCRIPTION:
XS GIS Cut Line= 3
      2273328.98      7203860.03      2273079.00      7204160.00
      2272778.99      7204560.02
#Sta/Elev= 30
  4604.7  995.65  4632.7  989.38  4647.0  980.45  4682.8  964.86  4739.4  953.13
  4874.8  942.52  4930.7  932.07  4945.1  931.55  4952.9  927.61  4959.4  929.14
  4967.2  926.23  4988.0  925.86  4991.9  922.38  5002.5  920.35  5017.1  922.62
  5023.3  919.52  5052.5  921.51  5073.3  926.57  5117.1  925.20  5150.3  918.91
  5150.7  918.41  5154.7  918.91  5181.6  934.70  5352.5  945.97  5395.2  960.95
  5445.2  988.47  5467.1  995.26  5473.3 1000.70  5481.6 1003.80  5495.2 1004.33
#Mann=3,-1,0
  4604.7    0.12       0  5150.3    0.07       0  5154.7    0.12       0
Bank Sta=5150.3,5154.7
Exp/Cntr=0.3,0.1

Type RM Length L Ch R = 1,4082,403,403,403
BEGIN DESCRIPTION:
UDS St 22 8.0
END DESCRIPTION:
XS GIS Cut Line= 3
      2273179.02      7203659.99      2272980.56      7203768.41
      2272578.98      7204010.01
#Sta/Elev= 30
  4770.7 1000.15  4773.6 1000.15  4778.8  993.51  4793.5  989.57  4816.3  979.46
  4828.1  970.76  4866.1  951.88  4873.3  945.99  4882.2  941.52  4925.9  932.09
  4991.3  930.06  4994.9  927.18  5000.7  927.18  5007.1  918.79  5019.8  912.84
  5020.2  912.34  5024.3  912.84  5044.0  917.51  5071.2  919.40  5092.5  926.32
  5108.1  928.22  5224.6  928.44  5313.8  935.41  5383.9  944.62  5407.1  950.52
  5415.0  950.44  5436.3  954.06  5451.9  957.19  5462.6  962.94  5465.5  962.94
#Mann=3,-1,0
  4770.7    0.12       0  5019.8    0.07       0  5024.3    0.12       0
Bank Sta=5019.8,5024.3
Exp/Cntr=0.3,0.1

Type RM Length L Ch R = 1,3679,450,450,450
BEGIN DESCRIPTION:
UDS St 22 7.0
END DESCRIPTION:
XS GIS Cut Line= 3
      2273051.96      7203513.68      2272609.62      7203511.51
      2272404.58      7203548.52
#Sta/Elev= 30
  4680.1  949.42  4684.1  949.42  4693.1  944.92  4763.1  930.42  4833.1  924.22
  4863.1  915.23  4903.1  914.47  4913.1  914.97  4923.1  916.54  4953.1  916.53
  4983.1  914.46  5000.8  911.39  5001.3  910.89  5005.3  911.39  5013.1  920.03
  5023.1  927.19  5033.1  929.49  5063.1  933.10  5103.1  935.94  5120.3  938.53
  5140.2  939.65  5153.6  941.86  5173.9  943.24  5184.0  945.30  5198.8  945.64
  5204.4  946.79  5245.0  950.00  5290.6  955.24  5316.1  958.62  5330.8  959.57
#Mann=4,-1,0
  4680.1    0.12       0  5000.8    0.07       0  5005.3    0.12       0
  5290.6    0.05       0
Bank Sta=5000.8,5005.3
Exp/Cntr=0.3,0.1

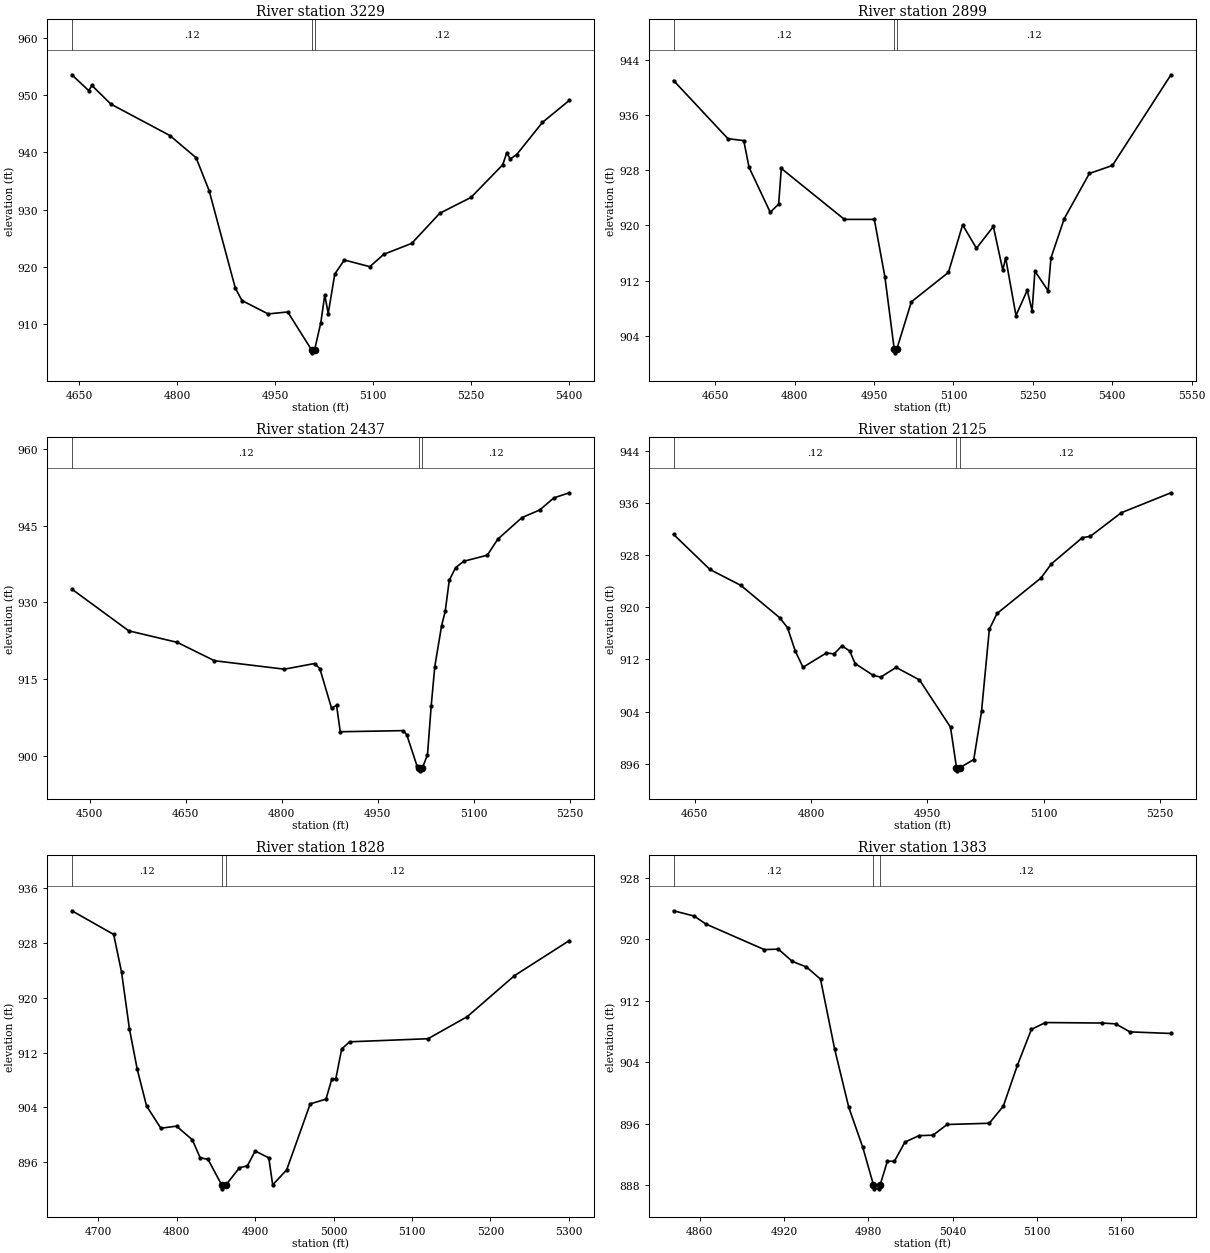
Type RM Length L Ch R = 1,3229,330,330,330
BEGIN DESCRIPTION:
UDS St 22 6.0
END DESCRIPTION:
XS GIS Cut Line= 3
      2273188.69      7203253.08      2272816.55      7203279.71
      2272453.89      7203419.05
#Sta/Elev= 30
  4639.0  953.53  4664.8  950.77  4669.8  951.66  4698.8  948.41  4789.1  942.93
  4829.2  939.06  4849.2  933.31  4889.3  916.30  4899.4  914.15  4939.5  911.81
  4969.5  912.15  5006.1  905.52  5006.6  905.02  5010.6  905.52  5020.2  910.29
  5026.2  915.12  5031.5  911.88  5041.6  918.78  5056.2  921.22  5095.2  920.05
  5116.6  922.21  5159.4  924.12  5202.3  929.37  5250.2  932.14  5298.7  937.83
  5304.9  939.94  5310.2  938.83  5320.1  939.62  5359.5  945.22  5400.6  949.06
#Mann=3,-1,0
  4639.0    0.12       0  5006.1    0.07       0  5010.6    0.12       0
Bank Sta=5006.1,5010.6
Exp/Cntr=0.3,0.1

Type RM Length L Ch R = 1,2899,462,462,462
BEGIN DESCRIPTION:
UDS St 22 5.2
END DESCRIPTION:
XS GIS Cut Line= 4
      2273181.58      7203002.70      2272823.67      7202988.87
      2272821.87      7203178.47      2272454.56      7203315.17
#Sta/Elev= 30
  4571.2  941.02  4673.9  932.59  4703.9  932.30  4713.9  928.42  4753.9  921.91
  4769.8  923.10  4774.8  928.27  4894.0  920.88  4950.5  920.88  4970.5  912.55
  4988.2  902.03  4988.7  901.53  4992.8  902.03  5020.5  908.93  5090.5  913.19
  5117.3  920.09  5143.4  916.69  5175.4  919.85  5193.2  913.52  5198.6  915.31
  5218.1  906.94  5239.4  910.61  5248.6  907.61  5253.9  913.38  5278.9  910.52
  5284.2  915.29  5309.3  920.99  5356.8  927.54  5400.3  928.70  5510.9  941.85
#Mann=3,-1,0
  4571.2    0.12       0  4988.2    0.07       0  4992.8    0.12       0
Bank Sta=4988.2,4992.8
Exp/Cntr=0.3,0.1

Type RM Length L Ch R = 1,2437,312,312,312
BEGIN DESCRIPTION:
UDS St 22 5.1
END DESCRIPTION:
XS GIS Cut Line= 3
      2273025.30      7202906.50      2272628.45      7203002.70
      2272303.93      7203176.98
#Sta/Elev= 30
  4472.3  932.61  4561.1  924.44  4637.0  922.17  4694.9  918.58  4804.2  916.92
  4851.2  918.03  4859.5  917.04  4877.8  909.27  4885.6  909.85  4891.4  904.66
  4989.5  904.88  4995.2  904.08  5011.4  897.90  5014.8  897.50  5015.3  897.00
  5019.4  897.50  5027.6  900.17  5033.4  909.75  5039.0  917.44  5049.6  925.42
  5055.3  928.28  5061.6  934.33  5071.5  936.82  5084.3  938.07  5121.0  939.26
  5137.3  942.39  5175.1  946.63  5203.0  948.13  5224.9  950.49  5249.0  951.49
#Mann=3,-1,0
  4472.3    0.12       0  5014.8    0.07       0  5019.4    0.12       0
Bank Sta=5014.8,5019.4
Exp/Cntr=0.3,0.1

Type RM Length L Ch R = 1,2125,297,297,297
BEGIN DESCRIPTION:
UDS St 22 5.0
END DESCRIPTION:
XS GIS Cut Line= 3
      2273005.89      7202824.94      2272570.03      7202843.51
      2272364.93      7202851.32
#Sta/Elev= 30
  4622.7  931.24  4669.6  925.84  4709.7  923.38  4759.7  918.41  4769.7  916.89
  4779.7  913.29  4789.7  910.80  4819.8  913.00  4829.8  912.86  4839.8  914.09
  4849.8  913.32  4856.9  911.38  4879.8  909.59  4889.8  909.28  4909.8  910.78
  4939.9  908.86  4979.9  901.59  4987.6  895.38  4988.1  894.88  4992.2  895.38
  5009.9  896.62  5019.9  904.03  5030.0  916.67  5040.0  919.08  5096.6  924.53
  5110.0  926.70  5150.0  930.74  5160.1  930.92  5200.1  934.56  5264.2  937.63
#Mann=3,-1,0
  4622.7    0.12       0  4987.6    0.07       0  4992.2    0.12       0
Bank Sta=4987.6,4992.2
Exp/Cntr=0.3,0.1

Type RM Length L Ch R = 1,1828,445,445,445
BEGIN DESCRIPTION:
UDS St 22 4.0
END DESCRIPTION:
XS GIS Cut Line= 3
      2273012.16      7202539.29      2272679.00      7202560.00
      2272379.00      7202560.00
#Sta/Elev= 30
  4666.6  932.73  4719.9  929.27  4729.9  923.77  4739.9  915.51  4749.9  909.55
  4761.8  904.18  4780.0  900.93  4800.0  901.24  4820.1  899.24  4830.1  896.61
  4840.1  896.38  4857.8  892.57  4858.3  892.07  4862.4  892.57  4880.2  895.16
  4890.2  895.43  4900.2  897.60  4917.5  896.60  4922.5  892.65  4940.3  894.84
  4970.3  904.49  4990.4  905.19  4997.9  908.15  5002.9  908.15  5010.4  912.51
  5020.4  913.57  5120.4  914.02  5170.4  917.25  5230.4  923.23  5300.4  928.37
#Mann=3,-1,0
  4666.6    0.12       0  4857.8    0.07       0  4862.4    0.12       0
Bank Sta=4857.8,4862.4
Exp/Cntr=0.3,0.1

Type RM Length L Ch R = 1,1383,237,237,237
BEGIN DESCRIPTION:
UDS St 22 3.0
END DESCRIPTION:
XS GIS Cut Line= 3
      2272933.57      7202216.03      2272779.00      7202210.00
      2272579.68      7202210.51
#Sta/Elev= 30
  4841.4  923.70  4856.0  923.02  4864.4  921.98  4906.0  918.65  4916.0  918.71
  4926.0  917.11  4936.0  916.39  4946.0  914.81  4956.1  905.68  4966.1  898.14
  4976.1  892.92  4983.7  888.03  4984.2  887.53  4987.9  887.53  4988.4  888.03
  4993.6  891.12  4998.6  891.12  5006.1  893.61  5016.1  894.45  5026.1  894.51
  5036.1  895.90  5066.1  896.06  5076.1  898.29  5086.1  903.60  5096.1  908.28
  5106.1  909.16  5146.1  909.10  5156.1  908.99  5166.1  907.95  5195.4  907.74
#Mann=3,-1,0
  4841.4    0.12       0  4983.7    0.07       0  4988.4    0.12       0
Bank Sta=4983.7,4988.4
Exp/Cntr=0.3,0.1

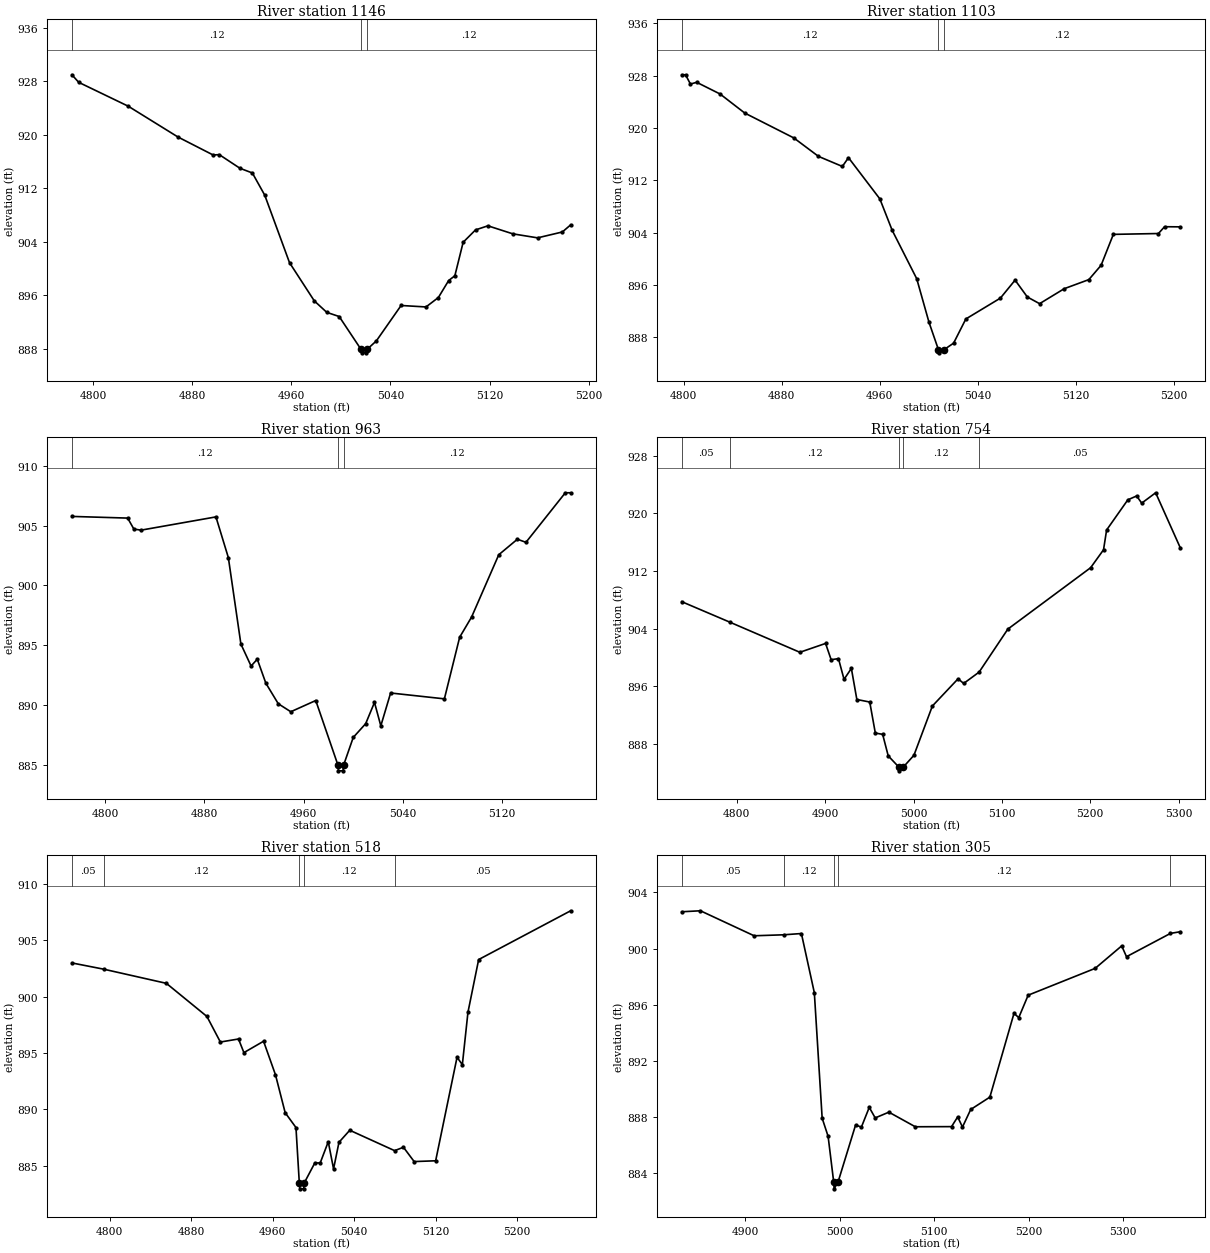
Type RM Length L Ch R = 1,1146,43,43,43
BEGIN DESCRIPTION:
UDS St 22 2.2
END DESCRIPTION:
XS GIS Cut Line= 2
      2272934.47      7202008.82      2272532.33      7202030.01
#Sta/Elev= 30
  4782.8  928.94  4788.3  927.81  4828.3  924.24  4868.4  919.64  4896.8  916.95
  4901.8  917.00  4918.5  914.96  4928.5  914.26  4938.5  910.94  4958.5  900.85
  4978.5  895.14  4988.6  893.42  4998.6  892.80  5016.3  887.87  5016.8  887.37
  5020.5  887.37  5021.0  887.87  5028.6  889.15  5048.6  894.45  5068.7  894.23
  5078.7  895.64  5087.0  898.18  5092.0  898.89  5098.7  903.90  5108.7  905.75
  5118.7  906.36  5138.8  905.16  5158.8  904.56  5178.8  905.44  5185.5  906.50
#Mann=3,-1,0
  4782.8    0.12       0  5016.3    0.07       0  5021.0    0.12       0
Bank Sta=5016.3,5021
Exp/Cntr=0.3,0.1

Type RM Length L Ch R = 1,1103,140,140,140
BEGIN DESCRIPTION:
UDS St 22 2.1
END DESCRIPTION:
XS GIS Cut Line= 2
      2272930.23      7201964.37      2272524.38      7201996.28
#Sta/Elev= 30
  4798.5  928.15  4801.6  928.15  4805.6  926.73  4810.7  927.00  4829.8  925.21
  4849.9  922.30  4890.0  918.49  4910.1  915.67  4929.6  914.13  4934.6  915.47
  4960.2  909.17  4970.3  904.35  4990.3  896.96  5000.3  890.31  5008.0  886.12
  5008.5  885.62  5012.7  886.12  5020.4  887.10  5030.4  890.80  5058.6  893.99
  5070.6  896.74  5080.6  894.16  5090.6  893.14  5110.7  895.43  5130.8  896.82
  5140.8  899.01  5150.8  903.74  5187.6  903.87  5192.6  904.91  5205.6  904.89
#Mann=3,-1,0
  4798.5    0.12       0  5008.0    0.07       0  5012.7    0.12       0
Bank Sta=5008,5012.7
Exp/Cntr=0.3,0.1

Type RM Length L Ch R = 1,963,209,209,209
BEGIN DESCRIPTION:
UDS St 22 2.0
END DESCRIPTION:
XS GIS Cut Line= 3
      2272649.00      7201684.62      2272622.18      7201946.98
      2272496.07      7202002.92
#Sta/Elev= 30
  4773.4  905.78  4818.3  905.64  4823.3  904.72  4829.1  904.63  4889.4  905.74
  4899.4  902.33  4909.5  895.09  4917.7  893.25  4922.7  893.82  4929.6  891.81
  4939.6  890.09  4949.7  889.42  4969.8  890.36  4987.6  884.97  4988.1  884.47
  4991.8  884.47  4992.3  884.97  5000.0  887.27  5010.0  888.42  5017.1  890.20
  5022.2  888.24  5030.1  890.99  5073.4  890.50  5085.7  895.66  5095.3  897.35
  5117.2  902.57  5132.2  903.87  5139.1  903.61  5170.8  907.76  5175.1  907.76
#Mann=3,-1,0
  4773.4    0.12       0  4987.6    0.07       0  4992.3    0.12       0
Bank Sta=4987.6,4992.3
Exp/Cntr=0.3,0.1

Type RM Length L Ch R = 1,754,236,236,236
BEGIN DESCRIPTION:
UDS St 22 1.1
END DESCRIPTION:
XS GIS Cut Line= 3
      2272652.49      7201565.81      2272363.92      7201950.57
      2272321.82      7202022.74
#Sta/Elev= 30
  4737.6  907.74  4792.7  904.86  4871.3  900.71  4900.4  901.94  4906.7  899.68
  4915.0  899.83  4921.3  896.95  4929.6  898.47  4935.8  894.15  4950.4  893.80
  4956.7  889.49  4965.0  889.31  4971.3  886.32  4983.5  884.74  4984.0  884.24
  4988.2  884.74  5000.4  886.40  5021.3  893.25  5050.4  897.03  5056.7  896.38
  5074.2  897.96  5106.7  903.93  5200.4  912.46  5215.0  914.95  5218.5  917.70
  5242.5  921.89  5252.5  922.43  5258.2  921.43  5274.0  922.87  5302.1  915.17
#Mann=5,-1,0
  4737.6    0.05       0  4792.7    0.12       0  4983.5    0.07       0
  4988.2    0.12       0  5074.2    0.05       0
Bank Sta=4983.5,4988.2
Exp/Cntr=0.3,0.1

Type RM Length L Ch R = 1,518,213,213,213
BEGIN DESCRIPTION:
UDS St 22 1.0
END DESCRIPTION:
XS GIS Cut Line= 3
      2272458.72      7201382.51      2272379.00      7201610.00
      2272300.28      7201845.65
#Sta/Elev= 30
  4763.1  903.00  4794.1  902.45  4855.8  901.19  4895.6  898.25  4908.8  895.98
  4926.6  896.25  4931.9  895.04  4951.2  896.05  4962.9  893.07  4972.4  889.71
  4983.0  888.39  4986.3  883.45  4986.8  882.95  4990.5  882.95  4991.0  883.45
  5001.5  885.25  5006.8  885.25  5014.7  887.13  5019.9  884.72  5025.2  887.08
  5035.8  888.15  5079.8  886.34  5088.5  886.64  5099.0  885.37  5120.1  885.44
  5141.1  894.63  5146.3  893.97  5151.8  898.62  5162.3  903.30  5252.6  907.63
#Mann=5,-1,0
  4763.1    0.05       0  4794.1    0.12       0  4986.3    0.07       0
  4991.0    0.12       0  5079.8    0.05       0
Bank Sta=4986.3,4991
Exp/Cntr=0.3,0.1

Type RM Length L Ch R = 1,305,260,260,260
BEGIN DESCRIPTION:
UDS St 22 0.7
END DESCRIPTION:
XS GIS Cut Line= 3
      2272460.11      7201313.28      2272261.71      7201463.58
      2272213.80      7201739.04
#Sta/Elev= 30
  4832.5  902.62  4852.3  902.69  4909.2  900.91  4940.6  900.98  4959.3  901.07
  4973.0  896.86  4981.3  887.92  4987.6  886.63  4993.5  883.39  4994.0  882.89
  4998.2  883.39  5016.7  887.43  5022.9  887.29  5031.2  888.69  5037.5  887.94
  5052.0  888.35  5080.0  887.31  5118.4  887.32  5124.9  888.01  5130.0  887.29
  5138.7  888.54  5159.0  889.42  5184.6  895.39  5189.6  895.08  5199.6  896.68
  5270.6  898.59  5298.7  900.19  5303.8  899.42  5350.4  901.08  5361.0  901.20
#Mann=5,-1,0
  4832.5    0.05       0  4940.6    0.12       0  4993.5    0.07       0
  4998.2    0.12       0  5350.4    0.05       0
Bank Sta=4993.5,4998.2
Exp/Cntr=0.3,0.1

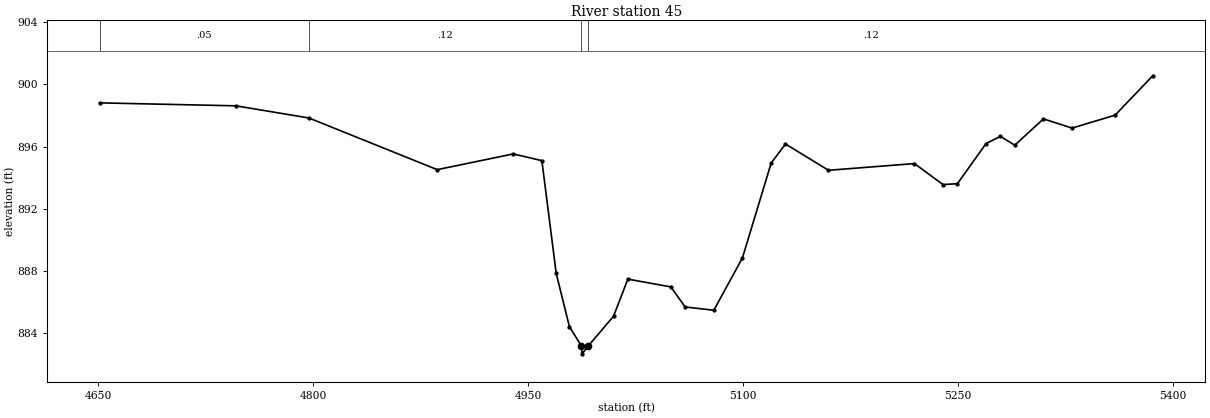
Type RM Length L Ch R = 1,45,0,0,0
BEGIN DESCRIPTION:
UDS St 22 0.8
END DESCRIPTION:
XS GIS Cut Line= 3
      2272325.62      7201226.17      2272123.03      7201347.61
      2272128.08      7201846.28
#Sta/Elev= 30
  4650.8  898.81  4745.9  898.62  4796.8  897.84  4886.4  894.52  4939.4  895.53
  4959.4  895.10  4969.4  887.86  4978.6  884.44  4987.0  883.19  4987.5  882.69
  4991.7  883.19  5009.4  885.10  5019.4  887.49  5049.4  886.99  5059.4  885.70
  5079.4  885.49  5099.4  888.86  5119.4  894.94  5129.4  896.17  5159.4  894.48
  5219.4  894.91  5239.4  893.56  5249.4  893.62  5269.4  896.20  5279.4  896.66
  5289.4  896.09  5309.4  897.78  5329.4  897.19  5359.4  898.02  5385.7  900.55
#Mann=4,-1,0
  4650.8    0.05       0  4796.8    0.12       0  4987.0    0.07       0
  4991.7    0.12       0
Bank Sta=4987,4991.7
Exp/Cntr=0.3,0.1

Chan Stop Cuts=-1