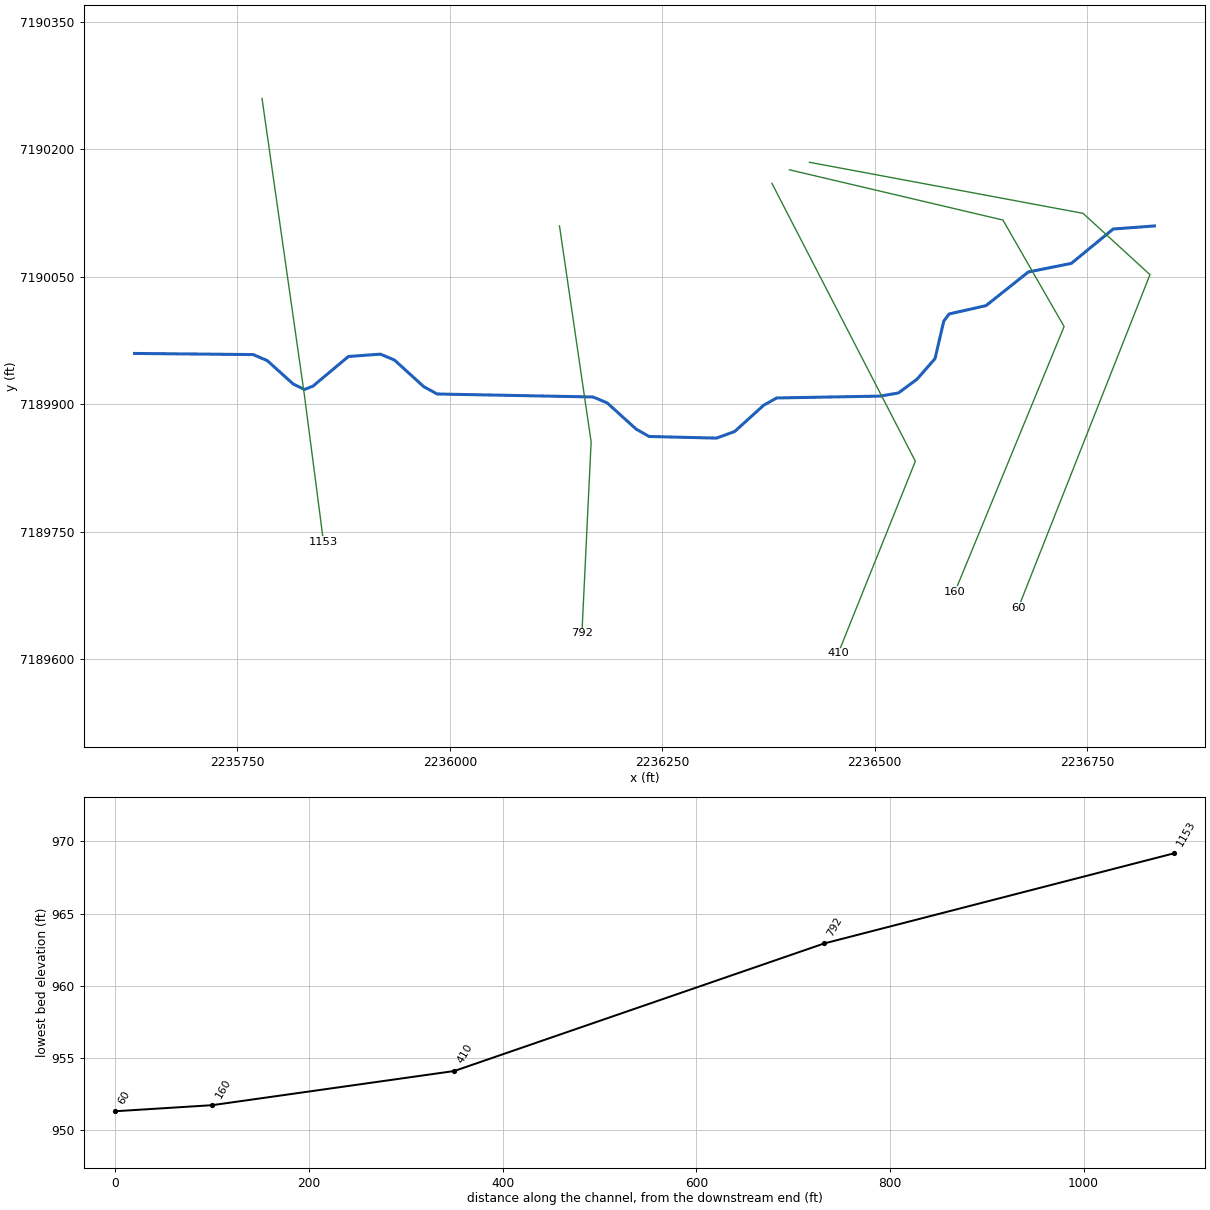
--- UDS St 24.prj (project) ---

Proj Title=UDS St 24 Base Level Engineering
Current Plan=p01
Default Exp/Contr=0.3,0.1
English Units
Geom File=g01
Flow File=f01
Plan File=p01
BEGIN DESCRIPTION:
UDS St 24
END DESCRIPTION:

--- UDS St 24.p01 (plan) ---

Plan Title=Multiple Run
Short Identifier=Multiple
Geom File=g01
Flow File=f01
Subcritical Flow
K Sum by GR= 0
Std Step Tol= 0.01
Critical Tol= 0.01
Num of Std Step Trials= 20
Max Error Tol= 0.3
Flow Tol Ratio= 0.001
Split Flow NTrial= 30
Split Flow Tol= 0.02
Split Flow Ratio= 0.02
Log Output Level= 0
Friction Slope Method= 1
Unsteady Friction Slope Method= 2
Unsteady Bridges Friction Slope Method= 1
Parabolic Critical Depth
Global Vel Dist=  1 , 1 , 1
Global Log Level= 0
CheckData=True
Encroach Param= -1, 0, 0, 0
BEGIN DESCRIPTION:
Multiple Run
END DESCRIPTION:

--- UDS St 24.f01 (steady flow) ---

Flow Title=Multiple
Number of Profiles=7
Profile Names=10-year,25-year,50-year,1pct_min,100-year,1pct_plu,500-year
River Rch & RM= UDS St 24,Reach-1,1153
     492     676     829     506    1011    2016    1502
Boundary for River Rch & Prof#=UDS St 24,Reach-1,1
Up Type=0
Dn Type=3
Dn Slope=0.005
Boundary for River Rch & Prof#=UDS St 24,Reach-1,2
Up Type=0
Dn Type=3
Dn Slope=0.005
Boundary for River Rch & Prof#=UDS St 24,Reach-1,3
Up Type=0
Dn Type=3
Dn Slope=0.005
Boundary for River Rch & Prof#=UDS St 24,Reach-1,4
Up Type=0
Dn Type=3
Dn Slope=0.005
Boundary for River Rch & Prof#=UDS St 24,Reach-1,5
Up Type=0
Dn Type=3
Dn Slope=0.005
Boundary for River Rch & Prof#=UDS St 24,Reach-1,6
Up Type=0
Dn Type=3
Dn Slope=0.005
Boundary for River Rch & Prof#=UDS St 24,Reach-1,7
Up Type=0
Dn Type=3
Dn Slope=0.005

--- UDS St 24.g01 (geometry) ---

Geom Title=Existing Conditions

River Reach=UDS St 24,Reach-1
Reach XY= 30
      2235629.00      7189960.00      2235768.59      7189958.66
      2235785.19      7189951.55      2235815.80      7189923.95
      2235829.01      7189917.59      2235838.93      7189921.53
      2235880.64      7189956.39      2235918.29      7189959.18
      2235934.91      7189952.17      2235969.33      7189920.91
      2235984.93      7189912.29      2236168.50      7189908.78
      2236185.06      7189901.85      2236219.37      7189870.81
      2236234.57      7189862.29      2236313.73      7189860.38
      2236335.03      7189868.09      2236369.35      7189899.14
      2236384.53      7189907.61      2236506.43      7189909.80
      2236527.73      7189913.48      2236549.51      7189929.54
      2236570.85      7189953.92      2236581.14      7189997.94
      2236587.49      7190006.46      2236630.85      7190016.24
      2236680.69      7190055.87      2236731.25      7190065.95
      2236780.49      7190106.40      2236829.00      7190110.00

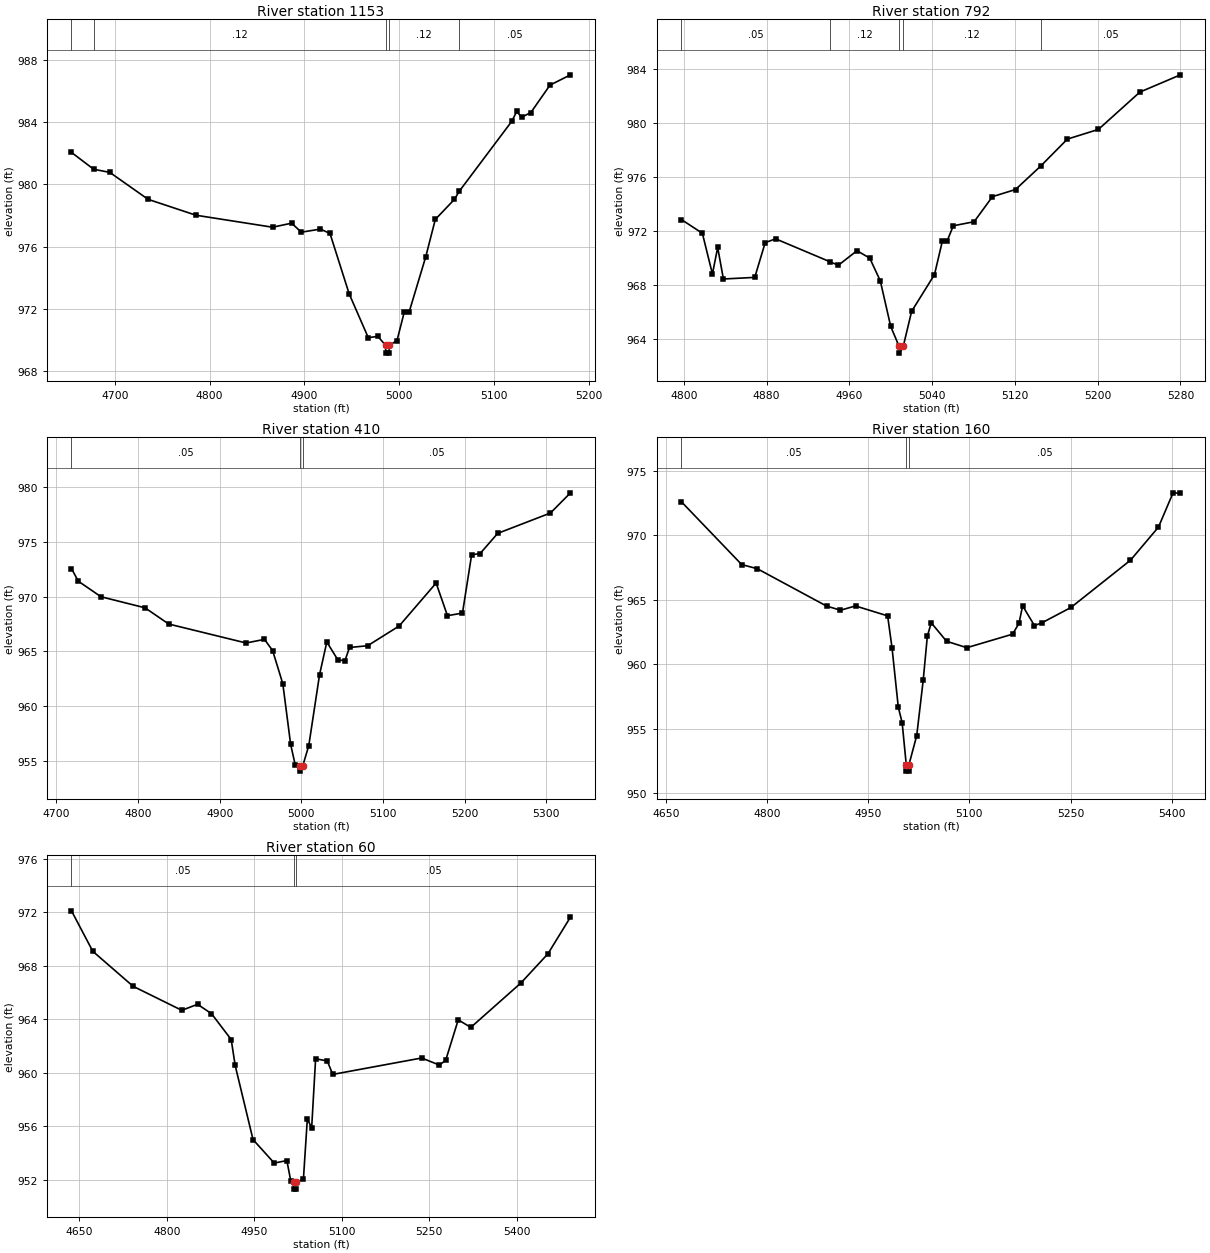
Type RM Length L Ch R = 1,1153,361,361,361
BEGIN DESCRIPTION:
UDS St 24 3.0
END DESCRIPTION:
XS GIS Cut Line= 3
      2235779.00      7190259.99      2235829.00      7189910.00
      2235851.28      7189738.58
#Sta/Elev= 30
  4654.3  982.05  4677.7  980.97  4694.7  980.77  4735.1  979.04  4785.6  978.02
  4866.4  977.25  4886.6  977.51  4896.7  976.93  4916.9  977.13  4927.0  976.85
  4947.2  972.98  4967.4  970.16  4977.5  970.25  4985.6  969.67  4985.9  969.17
  4989.4  969.17  4989.6  969.67  4997.7  969.98  5005.3  971.79  5010.4  971.79
  5028.0  975.35  5038.1  977.75  5058.3  979.04  5063.4  979.56  5118.8  984.05
  5124.0  984.68  5129.1  984.31  5138.9  984.61  5159.1  986.37  5180.7  987.03
#Mann=5,-1,0
  4654.3    0.05       0  4677.7    0.12       0  4985.6    0.07       0
  4989.6    0.12       0  5063.4    0.05       0
Bank Sta=4985.6,4989.6
Exp/Cntr=0.3,0.1

Type RM Length L Ch R = 1,792,382,382,382
BEGIN DESCRIPTION:
UDS St 24 2.0
END DESCRIPTION:
XS GIS Cut Line= 3
      2236129.00      7190110.02      2236166.23      7189855.94
      2236155.40      7189630.80
#Sta/Elev= 30
  4797.8  972.83  4818.0  971.81  4827.7  968.79  4832.8  970.76  4838.3  968.42
  4868.6  968.54  4878.7  971.12  4888.8  971.40  4941.3  969.70  4949.4  969.44
  4967.4  970.52  4979.7  969.97  4989.9  968.29  5000.0  964.90  5008.1  963.42
  5008.3  962.92  5012.1  963.42  5020.2  966.02  5042.3  968.75  5050.0  971.26
  5054.6  971.26  5060.5  972.37  5080.6  972.67  5098.3  974.53  5120.6  975.06
  5144.8  976.79  5170.7  978.80  5200.7  979.52  5240.8  982.29  5280.0  983.57
#Mann=5,-1,0
  4797.8    0.05       0  4941.3    0.12       0  5008.1    0.07       0
  5012.1    0.12       0  5144.8    0.05       0
Bank Sta=5008.1,5012.1
Exp/Cntr=0.3,0.1

Type RM Length L Ch R = 1,410,250,250,250
BEGIN DESCRIPTION:
UDS St 24 1.0
END DESCRIPTION:
XS GIS Cut Line= 3
      2236378.98      7190160.04      2236547.71      7189833.16
      2236456.98      7189607.26
#Sta/Elev= 30
  4718.5  972.55  4726.8  971.40  4754.6  969.98  4808.6  968.97  4837.6  967.49
  4932.4  965.76  4954.9  966.09  4964.9  965.07  4977.4  962.04  4987.0  956.50
  4992.7  954.60  4997.9  954.57  4998.1  954.07  5001.9  954.57  5009.2  956.40
  5022.4  962.87  5031.3  965.85  5044.9  964.21  5053.5  964.15  5059.1  965.35
  5081.3  965.51  5119.9  967.31  5165.2  971.23  5179.1  968.25  5197.5  968.49
  5208.7  973.81  5219.1  973.92  5240.6  975.76  5305.3  977.62  5329.8  979.46
#Mann=3,-1,0
  4718.5    0.05       0  4997.9   0.033       0  5001.9    0.05       0
Bank Sta=4997.9,5001.9
Exp/Cntr=0.3,0.1

Type RM Length L Ch R = 1,160,100,100,100
BEGIN DESCRIPTION:
UDS St 24 0.9
END DESCRIPTION:
XS GIS Cut Line= 4
      2236399.58      7190176.07      2236650.73      7190116.97
      2236722.73      7189991.63      2236594.38      7189679.87
#Sta/Elev= 30
  4673.2  972.60  4762.5  967.73  4785.6  967.41  4888.3  964.51  4908.9  964.19
  4931.2  964.52  4978.8  963.75  4985.4  961.24  4994.6  956.66  5000.3  955.47
  5006.4  952.20  5006.7  951.70  5010.2  951.70  5010.4  952.20  5021.9  954.45
  5031.5  958.74  5037.7  962.19  5043.5  963.21  5066.1  961.78  5096.2  961.28
  5164.0  962.33  5173.5  963.17  5178.9  964.53  5196.5  962.99  5208.2  963.23
  5250.5  964.40  5338.8  968.07  5380.3  970.64  5401.9  973.30  5412.9  973.27
#Mann=3,-1,0
  4673.2    0.05       0  5006.4   0.033       0  5010.4    0.05       0
Bank Sta=5006.4,5010.4
Exp/Cntr=0.3,0.1

Type RM Length L Ch R = 1,60,0,0,0
BEGIN DESCRIPTION:
UDS St 24 0.8
END DESCRIPTION:
XS GIS Cut Line= 4
      2236423.12      7190184.92      2236744.99      7190124.84
      2236823.76      7190052.70      2236668.99      7189661.03
#Sta/Elev= 30
  4636.7  972.12  4673.2  969.09  4742.3  966.47  4825.8  964.67  4852.8  965.12
  4876.7  964.42  4910.5  962.48  4917.3  960.54  4947.9  954.99  4984.3  953.23
  5005.9  953.42  5012.7  951.87  5018.1  951.78  5018.3  951.28  5021.8  951.28
  5022.1  951.78  5034.3  952.04  5041.0  956.54  5048.4  955.86  5055.2  961.04
  5075.1  960.88  5084.6  959.87  5237.0  961.10  5267.4  960.57  5278.2  960.93
  5299.7  963.96  5321.2  963.39  5407.2  966.72  5453.4  968.90  5492.1  971.65
#Mann=3,-1,0
  4636.7    0.05       0  5018.1   0.033       0  5022.1    0.05       0
Bank Sta=5018.1,5022.1
Exp/Cntr=0.3,0.1

Chan Stop Cuts=-1