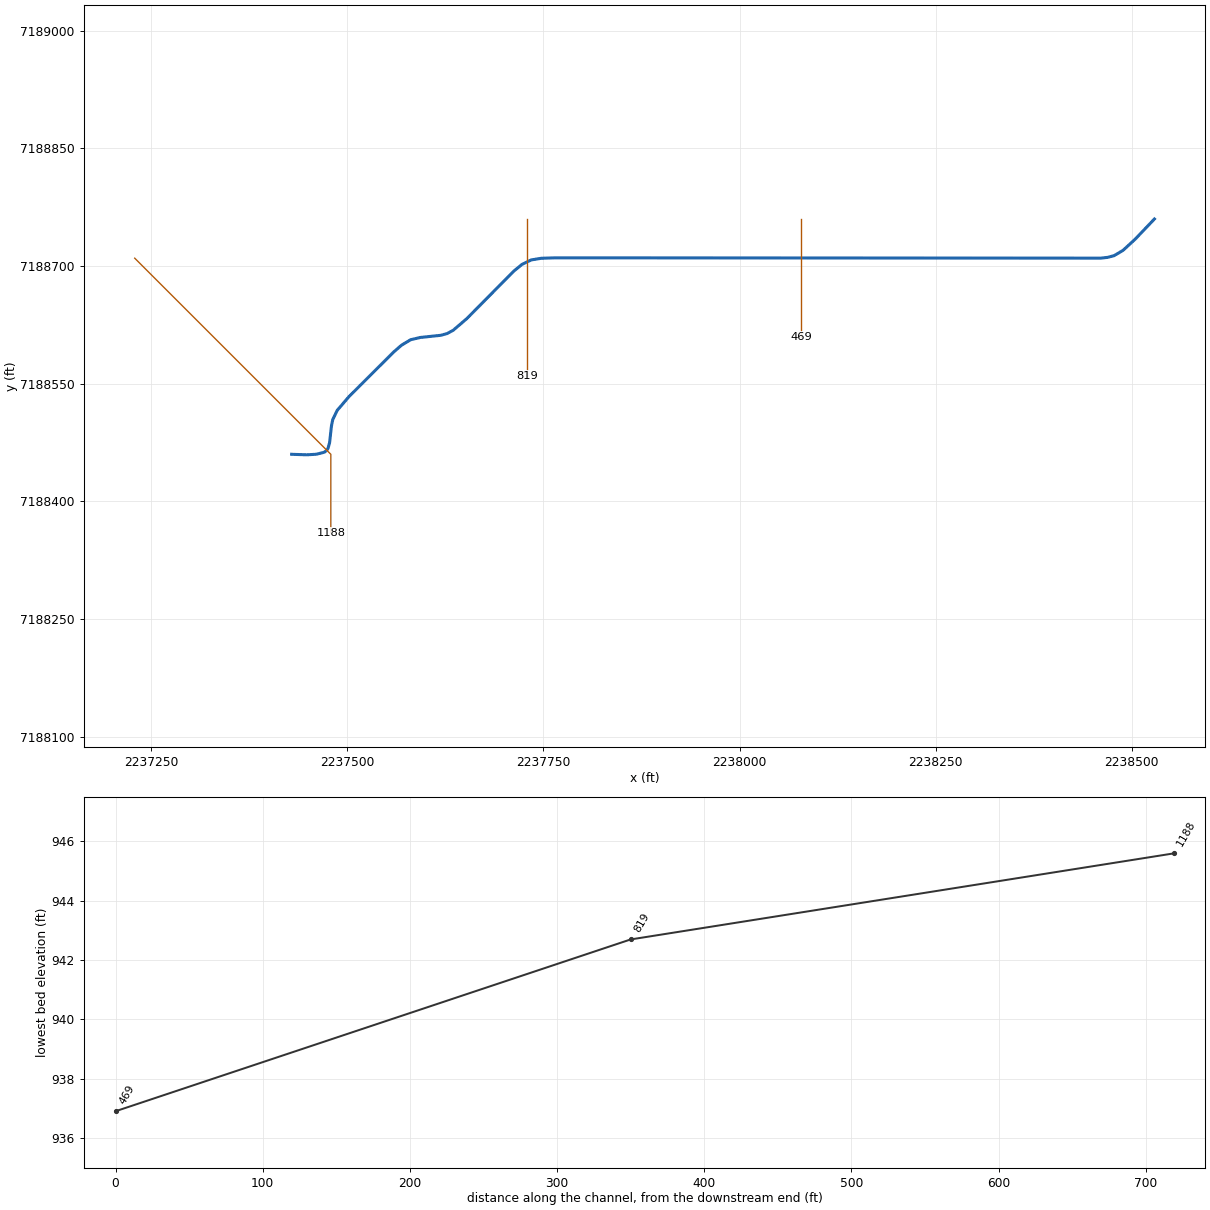
--- UDS St 25.prj (project) ---

Proj Title=UDS St 25 Base Level Engineering
Current Plan=p01
Default Exp/Contr=0.3,0.1
English Units
Geom File=g01
Flow File=f01
Plan File=p01
BEGIN DESCRIPTION:
UDS St 25
END DESCRIPTION:

--- UDS St 25.p01 (plan) ---

Plan Title=Multiple Run
Short Identifier=Multiple
Geom File=g01
Flow File=f01
Subcritical Flow
K Sum by GR= 0
Std Step Tol= 0.01
Critical Tol= 0.01
Num of Std Step Trials= 20
Max Error Tol= 0.3
Flow Tol Ratio= 0.001
Split Flow NTrial= 30
Split Flow Tol= 0.02
Split Flow Ratio= 0.02
Log Output Level= 0
Friction Slope Method= 1
Unsteady Friction Slope Method= 2
Unsteady Bridges Friction Slope Method= 1
Parabolic Critical Depth
Global Vel Dist=  1 , 1 , 1
Global Log Level= 0
CheckData=True
Encroach Param= -1, 0, 0, 0
BEGIN DESCRIPTION:
Multiple Run
END DESCRIPTION:

--- UDS St 25.f01 (steady flow) ---

Flow Title=Multiple
Number of Profiles=7
Profile Names=10-year,25-year,50-year,1pct_min,100-year,1pct_plu,500-year
River Rch & RM= UDS St 25,Reach-1,1188
     567     792     982     606    1209    2412    1836
Boundary for River Rch & Prof#=UDS St 25,Reach-1,1
Up Type=0
Dn Type=3
Dn Slope=0.005
Boundary for River Rch & Prof#=UDS St 25,Reach-1,2
Up Type=0
Dn Type=3
Dn Slope=0.005
Boundary for River Rch & Prof#=UDS St 25,Reach-1,3
Up Type=0
Dn Type=3
Dn Slope=0.005
Boundary for River Rch & Prof#=UDS St 25,Reach-1,4
Up Type=0
Dn Type=3
Dn Slope=0.005
Boundary for River Rch & Prof#=UDS St 25,Reach-1,5
Up Type=0
Dn Type=3
Dn Slope=0.005
Boundary for River Rch & Prof#=UDS St 25,Reach-1,6
Up Type=0
Dn Type=3
Dn Slope=0.005
Boundary for River Rch & Prof#=UDS St 25,Reach-1,7
Up Type=0
Dn Type=3
Dn Slope=0.005

--- UDS St 25.g01 (geometry) ---

Geom Title=Existing Conditions

River Reach=UDS St 25,Reach-1
Reach XY= 30
      2237429.00      7188460.00      2237448.25      7188459.38
      2237460.54      7188460.07      2237470.56      7188462.63
      2237473.67      7188464.92      2237475.40      7188467.70
      2237477.40      7188474.77      2237479.72      7188495.81
      2237481.41      7188504.21      2237487.05      7188515.92
      2237502.00      7188533.43      2237558.87      7188590.22
      2237569.30      7188599.23      2237580.64      7188606.03
      2237593.06      7188608.97      2237619.20      7188611.71
      2237627.35      7188613.99      2237635.04      7188618.18
      2237652.44      7188633.07      2237712.25      7188693.54
      2237722.81      7188702.17      2237734.45      7188707.82
      2237747.22      7188709.91      2237765.16      7188710.50
      2238460.78      7188710.10      2238469.45      7188711.10
      2238477.64      7188713.29      2238488.98      7188720.05
      2238504.29      7188734.11      2238529.00      7188760.00

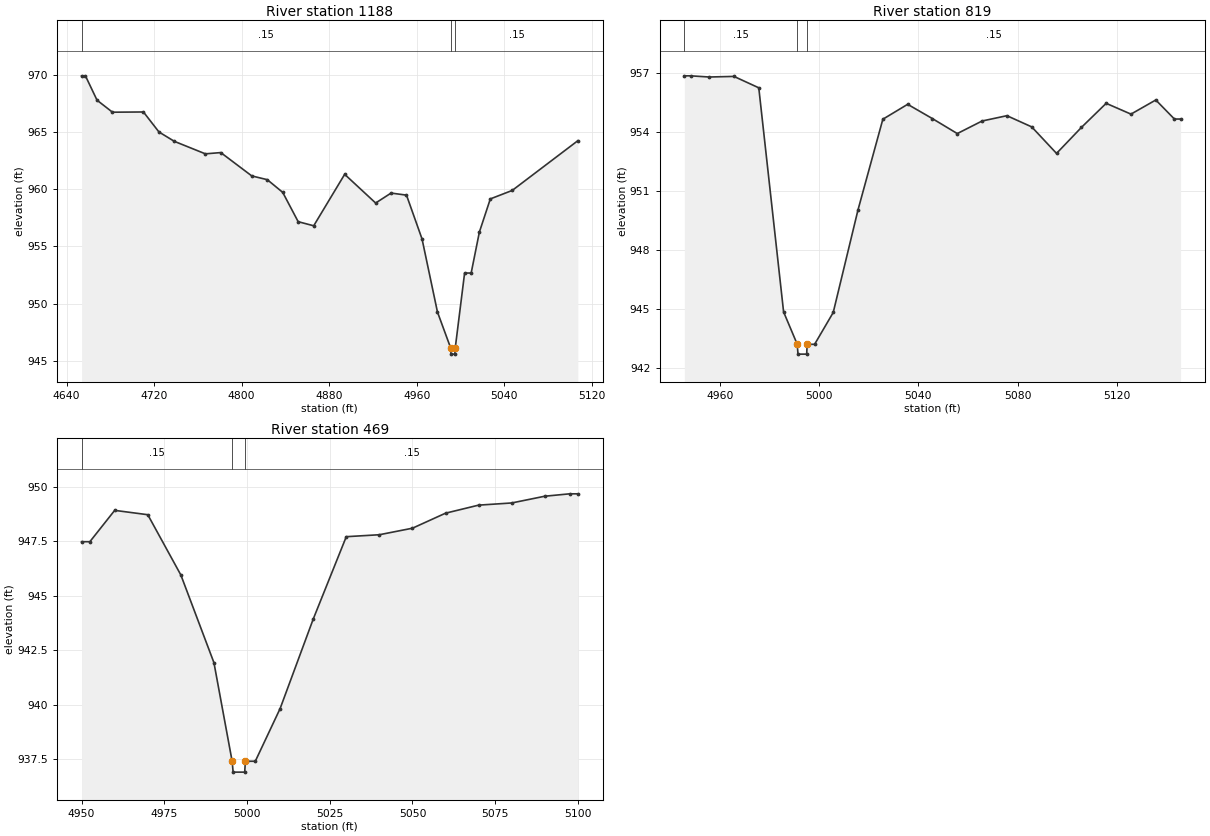
Type RM Length L Ch R = 1,1188,369,369,369
BEGIN DESCRIPTION:
UDS St 25 3.0
END DESCRIPTION:
XS GIS Cut Line= 3
      2237229.03      7188709.97      2237479.00      7188460.00
      2237479.00      7188360.01
#Sta/Elev= 30
  4653.8  969.92  4657.3  969.92  4667.9  967.79  4682.0  966.74  4710.3  966.76
  4724.5  965.01  4738.6  964.19  4766.9  963.10  4781.0  963.21  4809.3  961.17
  4823.5  960.84  4837.6  959.73  4851.7  957.17  4865.9  956.81  4894.2  961.31
  4922.5  958.80  4936.6  959.67  4950.7  959.49  4964.9  955.66  4979.0  949.27
  4991.2  946.09  4991.4  945.59  4994.9  945.59  4995.2  946.09  5003.8  952.68
  5009.8  952.68  5017.3  956.26  5027.3  959.16  5047.3  959.90  5107.3  964.25
#Mann=3,-1,0
  4653.8    0.15       0  4991.2    0.05       0  4995.2    0.15       0
Bank Sta=4991.2,4995.2
Exp/Cntr=0.3,0.1

Type RM Length L Ch R = 1,819,350,350,350
BEGIN DESCRIPTION:
UDS St 25 2.0
END DESCRIPTION:
XS GIS Cut Line= 3
      2237729.00      7188760.03      2237729.00      7188710.00
      2237729.00      7188560.03
#Sta/Elev= 27
  4945.7  956.86  4948.2  956.86  4955.7  956.80  4965.7  956.83  4975.7  956.25
  4985.7  944.84  4991.2  943.19  4991.5  942.69  4995.0  942.69  4995.2  943.19
  4998.2  943.19  5005.7  944.81  5015.7  950.04  5025.7  954.65  5035.7  955.41
  5045.7  954.68  5055.7  953.92  5065.7  954.56  5075.7  954.83  5085.7  954.26
  5095.7  952.91  5105.7  954.23  5115.7  955.46  5125.7  954.91  5135.7  955.63
  5143.2  954.66  5145.7  954.66
#Mann=3,-1,0
  4945.7    0.15       0  4991.2    0.05       0  4995.2    0.15       0
Bank Sta=4991.2,4995.2
Exp/Cntr=0.3,0.1

Type RM Length L Ch R = 1,469,0,0,0
BEGIN DESCRIPTION:
UDS St 25 1.0
END DESCRIPTION:
XS GIS Cut Line= 3
      2238079.00      7188760.01      2238079.00      7188710.00
      2238079.00      7188610.01
#Sta/Elev= 23
  4950.0  947.49  4952.5  947.49  4960.0  948.93  4970.0  948.73  4980.0  945.96
  4990.0  941.93  4995.5  937.40  4995.8  936.90  4999.3  936.90  4999.5  937.40
  5000.0  937.40  5002.5  937.40  5010.0  939.82  5020.0  943.93  5030.0  947.72
  5040.0  947.81  5050.0  948.11  5060.0  948.80  5070.0  949.17  5080.0  949.27
  5090.0  949.58  5097.5  949.69  5100.0  949.69
#Mann=3,-1,0
  4950.0    0.15       0  4995.5    0.05       0  4999.5    0.15       0
Bank Sta=4995.5,4999.5
Exp/Cntr=0.3,0.1

Chan Stop Cuts=-1