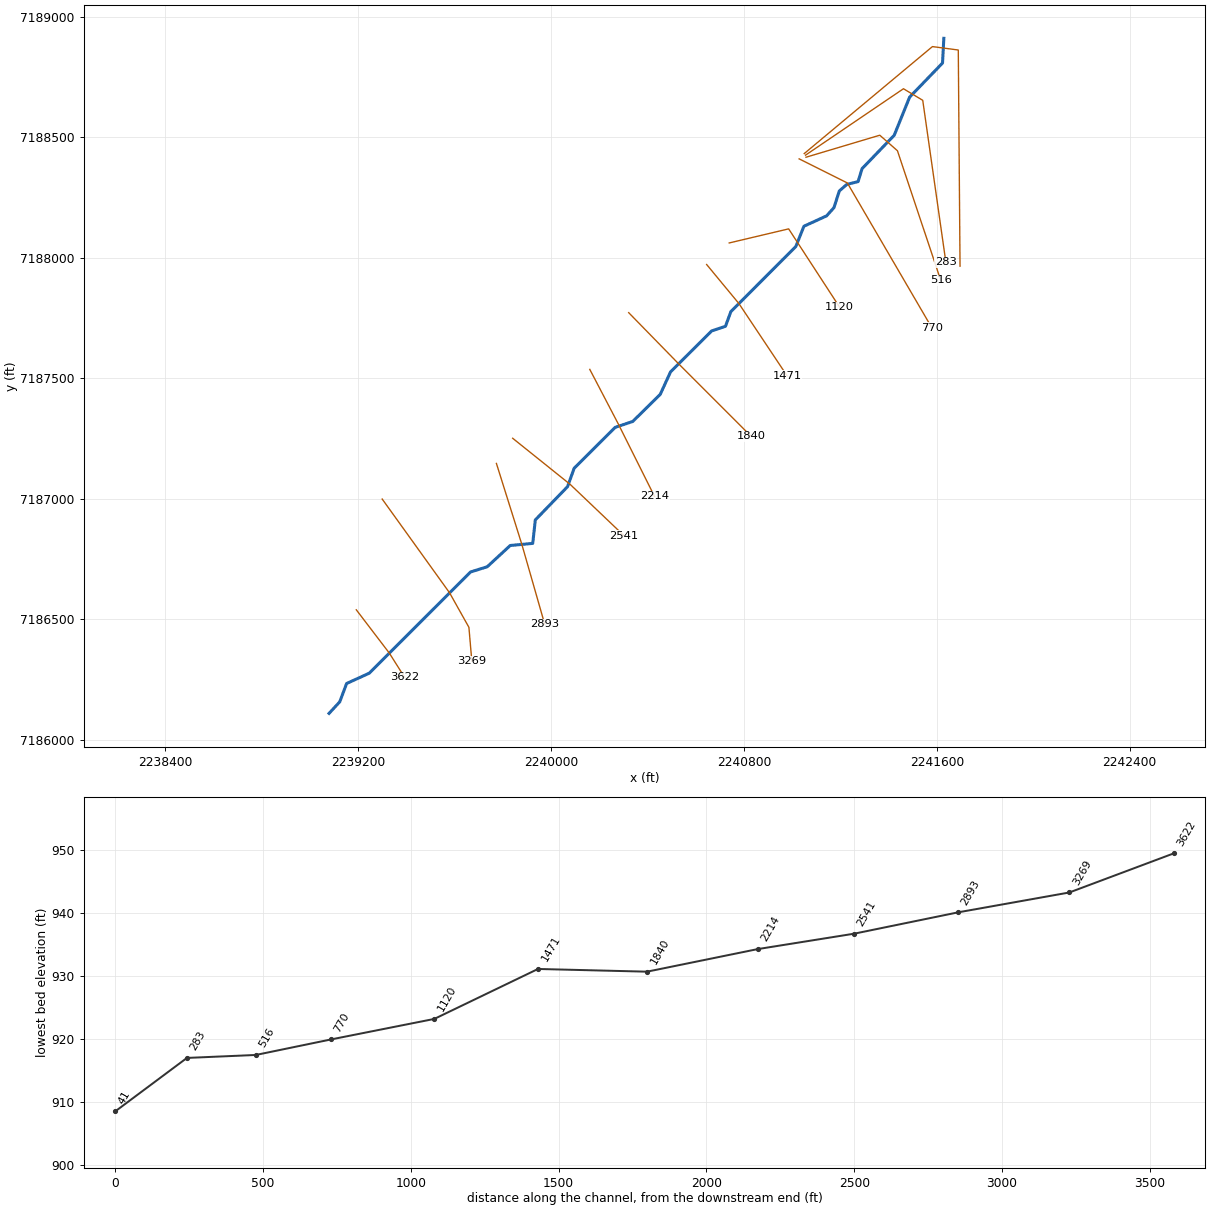
--- UDS St 26.prj (project) ---

Proj Title=UDS St 26 Base Level Engineering
Current Plan=p01
Default Exp/Contr=0.3,0.1
English Units
Geom File=g01
Flow File=f01
Plan File=p01
Y Axis Title=Elevation
X Axis Title(PF)=Main Channel Distance
X Axis Title(XS)=Station
BEGIN DESCRIPTION:
UDS St 26
END DESCRIPTION:
DSS Export Rating Curves= 0
DSS Export Rating Curve Sorted= 0
DSS Export Volume Flow Curves= 0
DXF OffsetX= 0
DXF OffsetY= 0
DXF ScaleX= 1
DXF ScaleY= 10

--- UDS St 26.p01 (plan) ---

Plan Title=Multiple Run
Short Identifier=Multiple
Geom File=g01
Flow File=f01
Subcritical Flow
K Sum by GR= 0
Std Step Tol= 0.01
Critical Tol= 0.01
Num of Std Step Trials= 20
Max Error Tol= 0.3
Flow Tol Ratio= 0.001
Split Flow NTrial= 30
Split Flow Tol= 0.02
Split Flow Ratio= 0.02
Log Output Level= 0
Friction Slope Method= 1
Unsteady Friction Slope Method= 2
Unsteady Bridges Friction Slope Method= 1
Parabolic Critical Depth
Global Vel Dist=  1 , 1 , 1
Global Log Level= 0
CheckData=True
Encroach Param= -1, 0, 0, 0
BEGIN DESCRIPTION:
Multiple Run
END DESCRIPTION:

--- UDS St 26.f01 (steady flow) ---

Flow Title=Multiple
Number of Profiles=7
Profile Names=10-year,25-year,50-year,1pct_min,100-year,1pct_plu,500-year
River Rch & RM= UDS St 26,Reach-1,3622
     686     959    1190     733    1463    2919    2218
Boundary for River Rch & Prof#=UDS St 26,Reach-1,1
Up Type=0
Dn Type=3
Dn Slope=0.005
Boundary for River Rch & Prof#=UDS St 26,Reach-1,2
Up Type=0
Dn Type=3
Dn Slope=0.005
Boundary for River Rch & Prof#=UDS St 26,Reach-1,3
Up Type=0
Dn Type=3
Dn Slope=0.005
Boundary for River Rch & Prof#=UDS St 26,Reach-1,4
Up Type=0
Dn Type=3
Dn Slope=0.005
Boundary for River Rch & Prof#=UDS St 26,Reach-1,5
Up Type=0
Dn Type=3
Dn Slope=0.005
Boundary for River Rch & Prof#=UDS St 26,Reach-1,6
Up Type=0
Dn Type=3
Dn Slope=0.005
Boundary for River Rch & Prof#=UDS St 26,Reach-1,7
Up Type=0
Dn Type=3
Dn Slope=0.005

--- UDS St 26.g01 (geometry) ---

Geom Title=Existing Conditions
Program Version=4.10

River Reach=UDS St 26       ,Reach-1
Reach XY= 30
        2239079.        7186110.      2239123.28      7186157.68
      2239151.83      7186233.86      2239245.66      7186276.66
      2239665.79      7186696.37      2239735.04      7186718.18
      2239830.58      7186806.34      2239923.89      7186815.11
      2239934.55      7186912.36      2240068.22      7187050.32
      2240095.65      7187126.67      2240265.79      7187296.37
      2240338.68      7187320.78       2240452.7      7187433.18
      2240495.65      7187526.67      2240666.02      7187696.27
      2240723.38      7187715.62      2240745.73      7187776.48
      2241015.36       7188046.8      2241048.64      7188130.47
      2241142.55      7188173.49      2241173.24      7188207.49
      2241195.58        7188277.       2241226.8      7188304.11
      2241273.35      7188315.63      2241289.89      7188369.42
      2241423.17       7188507.7      2241487.14      7188666.06
      2241623.65       7188807.5        2241629.        7188910.

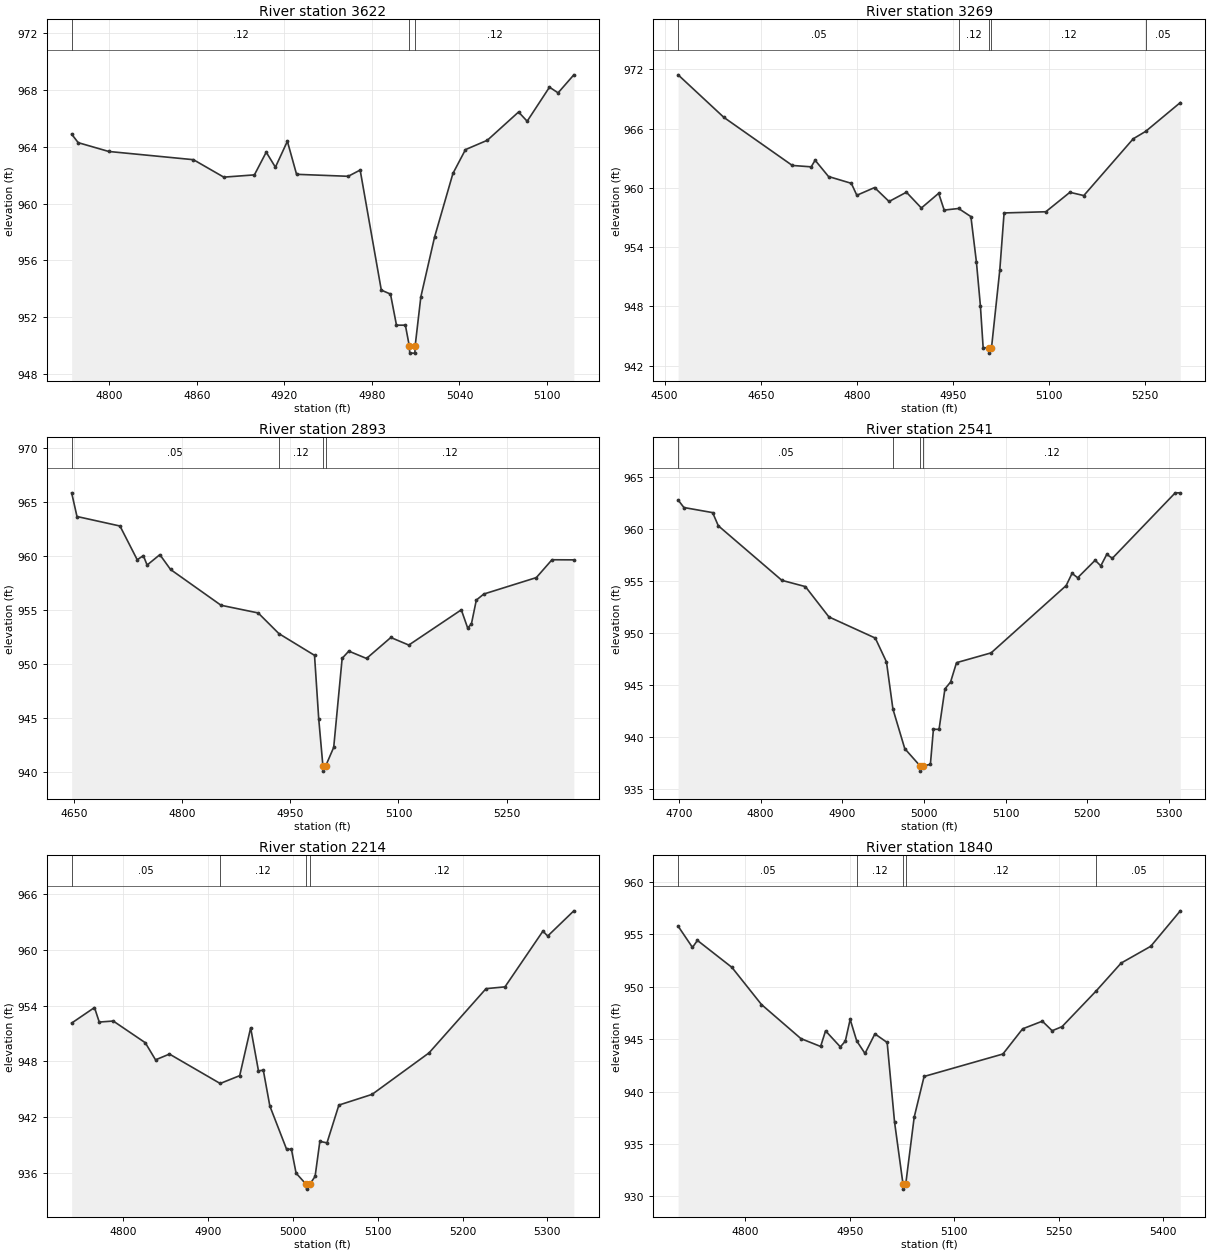
Type RM Length L Ch R = 1 ,3622    ,353,353,353
BEGIN DESCRIPTION:
UDS St 26 9.0
END DESCRIPTION:
XS GIS Cut Line= 3
      2239192.01      7186539.61        2239329.        7186360.
       2239392.3      7186259.93
#Sta/Elev= 30
  4774.1   964.9  4778.6   964.3  4799.5  963.68  4857.6   963.1  4878.4  961.87
  4899.4  962.03  4907.5  963.63  4913.8  962.57    4922   964.4  4928.3  962.07
  4963.7  961.93  4971.9  962.37  4986.4  953.91  4992.7  953.63  4996.8  951.44
  5002.9  951.44  5005.6  949.97  5005.9  949.47  5009.4  949.47  5009.6  949.97
  5013.5  953.43  5022.9  957.64  5035.5  962.13  5044.1  963.81  5059.1  964.47
  5080.5  966.46  5086.4  965.81  5101.7  968.21  5107.6  967.81  5118.4  969.08
#Mann= 3 ,-1 , 0
  4774.1     .12       0  5005.6     .07       0  5009.6     .12       0
Bank Sta=5005.6,5009.6
XS Rating Curve= 0 ,0
Exp/Cntr=0.3,0.1

Type RM Length L Ch R = 1 ,3269    ,376,376,376
BEGIN DESCRIPTION:
UDS St 26 8.0
END DESCRIPTION:
XS GIS Cut Line= 4
      2239299.45        7186999.        2239579.        7186610.
      2239659.14      7186466.99      2239671.23      7186326.78
#Sta/Elev= 30
    4521  971.46  4592.4  967.15  4699.2  962.28  4728.7  962.14  4734.8  962.81
  4755.7  961.16  4791.3  960.47  4799.9  959.26  4827.6  960.04  4850.2  958.63
  4877.3  959.57  4900.6  957.97  4927.6  959.46  4936.2  957.76  4958.7  957.92
  4977.9   957.1  4986.5  952.51  4992.7  948.09    4997  943.84    5006  943.77
  5006.3  943.27    5010  943.77    5023  951.69  5029.7  957.47  5094.8  957.59
  5132.4  959.56  5154.1  959.23  5231.2  964.98  5250.6  965.73  5304.7  968.65
#Mann= 5 ,-1 , 0
    4521     .05       0  4958.7     .12       0    5006     .07       0
    5010     .12       0  5250.6     .05       0
Bank Sta=5006,5010
XS Rating Curve= 0 ,0
Exp/Cntr=0.3,0.1

Type RM Length L Ch R = 1 ,2893    ,352,352,352
BEGIN DESCRIPTION:
UDS St 26 7.0
END DESCRIPTION:
XS GIS Cut Line= 3
      2239773.23      7187146.72        2239879.        7186810.
      2239973.54      7186480.02
#Sta/Elev= 30
  4646.9  965.86  4654.3  963.67  4713.9  962.79  4737.8  959.67  4746.3  960.05
  4751.5  959.18  4769.2  960.14    4784  958.77    4854  955.46  4905.5  954.75
  4934.2  952.84  4983.6  950.83  4989.4  944.98  4995.2  940.62  4995.5  940.12
  4999.2  940.62  5010.2  942.32  5021.9  950.55  5031.1  951.22  5055.7  950.54
  5089.4  952.48  5114.3  951.78  5187.1  955.04  5195.9  953.36  5201.1  953.73
  5207.9  955.94  5218.3   956.5  5291.1  958.02  5312.8  959.67  5343.1  959.66
#Mann= 4 ,-1 , 0
  4646.9     .05       0  4934.2     .12       0  4995.2     .07       0
  4999.2     .12       0
Bank Sta=4995.2,4999.2
XS Rating Curve= 0 ,0
Exp/Cntr=0.3,0.1

Type RM Length L Ch R = 1 ,2541    ,327,327,327
BEGIN DESCRIPTION:
UDS St 26 6.0
END DESCRIPTION:
XS GIS Cut Line= 3
      2239840.61      7187251.18        2240079.        7187060.
      2240303.07      7186846.47
#Sta/Elev= 30
    4699  962.75  4706.1  962.03  4741.3  961.54  4748.2  960.28  4826.1  955.04
  4854.9  954.44  4883.7  951.53  4940.5   949.5  4954.2  947.21  4962.1  942.69
  4976.6  938.89  4995.4  937.23  4995.6  936.73  4999.4  937.23    5008  937.38
  5011.7  940.75  5018.6  940.74  5025.8  944.62  5032.7  945.28    5040  947.14
  5082.4  948.08  5174.3  954.54  5181.5  955.71  5188.4  955.29  5209.8  956.97
  5216.7  956.43    5224  957.53  5230.9  957.16  5307.9  963.44  5314.1  963.44
#Mann= 4 ,-1 , 0
    4699     .05       0  4962.1     .12       0  4995.4     .07       0
  4999.4     .12       0
Bank Sta=4995.4,4999.4
XS Rating Curve= 0 ,0
Exp/Cntr=0.3,0.1

Type RM Length L Ch R = 1 ,2214    ,374,374,374
BEGIN DESCRIPTION:
UDS St 26 5.0
END DESCRIPTION:
XS GIS Cut Line= 3
      2240160.53       7187536.9        2240279.        7187310.
      2240429.01      7187009.98
#Sta/Elev= 30
  4739.7  952.12  4766.6  953.79  4772.2  952.23  4788.7  952.34  4826.4  950.01
  4838.5  948.17  4854.9  948.79  4914.6  945.63  4937.6  946.47  4950.5  951.61
  4959.7  946.99  4965.4  947.06  4973.1  943.21  4992.8  938.57  4998.5  938.57
    5004     936    5016  934.78  5016.3  934.28    5020  934.78  5026.4  935.65
    5032  939.41  5040.4  939.25  5054.4  943.31  5093.5  944.46  5160.6  948.92
  5227.7  955.82    5250  956.01  5294.7     962  5300.3  961.47  5331.1  964.18
#Mann= 4 ,-1 , 0
  4739.7     .05       0  4914.6     .12       0    5016     .07       0
    5020     .12       0
Bank Sta=5016,5020
XS Rating Curve= 0 ,0
Exp/Cntr=0.3,0.1

Type RM Length L Ch R = 1 ,1840    ,369,369,369
BEGIN DESCRIPTION:
UDS St 26 4.0
END DESCRIPTION:
XS GIS Cut Line= 3
      2240321.92      7187772.09        2240529.        7187560.
      2240829.01      7187259.99
#Sta/Elev= 30
  4703.8  955.77  4724.4  953.74  4731.5  954.41    4781  951.84  4823.4   948.3
    4880  945.05  4908.3   944.3  4915.4  945.79  4936.6  944.26  4943.7   944.8
  4950.7  946.88  4960.1  944.83    4972  943.63  4986.2   945.5  5003.8  944.68
  5014.4   937.1  5026.5   931.2  5026.8   930.7  5030.5   931.2  5042.6  937.56
  5056.8  941.44  5169.9  943.58  5198.2  945.98  5226.5  946.71  5240.6   945.8
  5254.8  946.19    5304  949.61  5339.6  952.25  5382.1  953.85  5424.5  957.23
#Mann= 5 ,-1 , 0
  4703.8     .05       0  4960.1     .12       0  5026.5     .07       0
  5030.5     .12       0    5304     .05       0
Bank Sta=5026.5,5030.5
XS Rating Curve= 0 ,0
Exp/Cntr=0.3,0.1

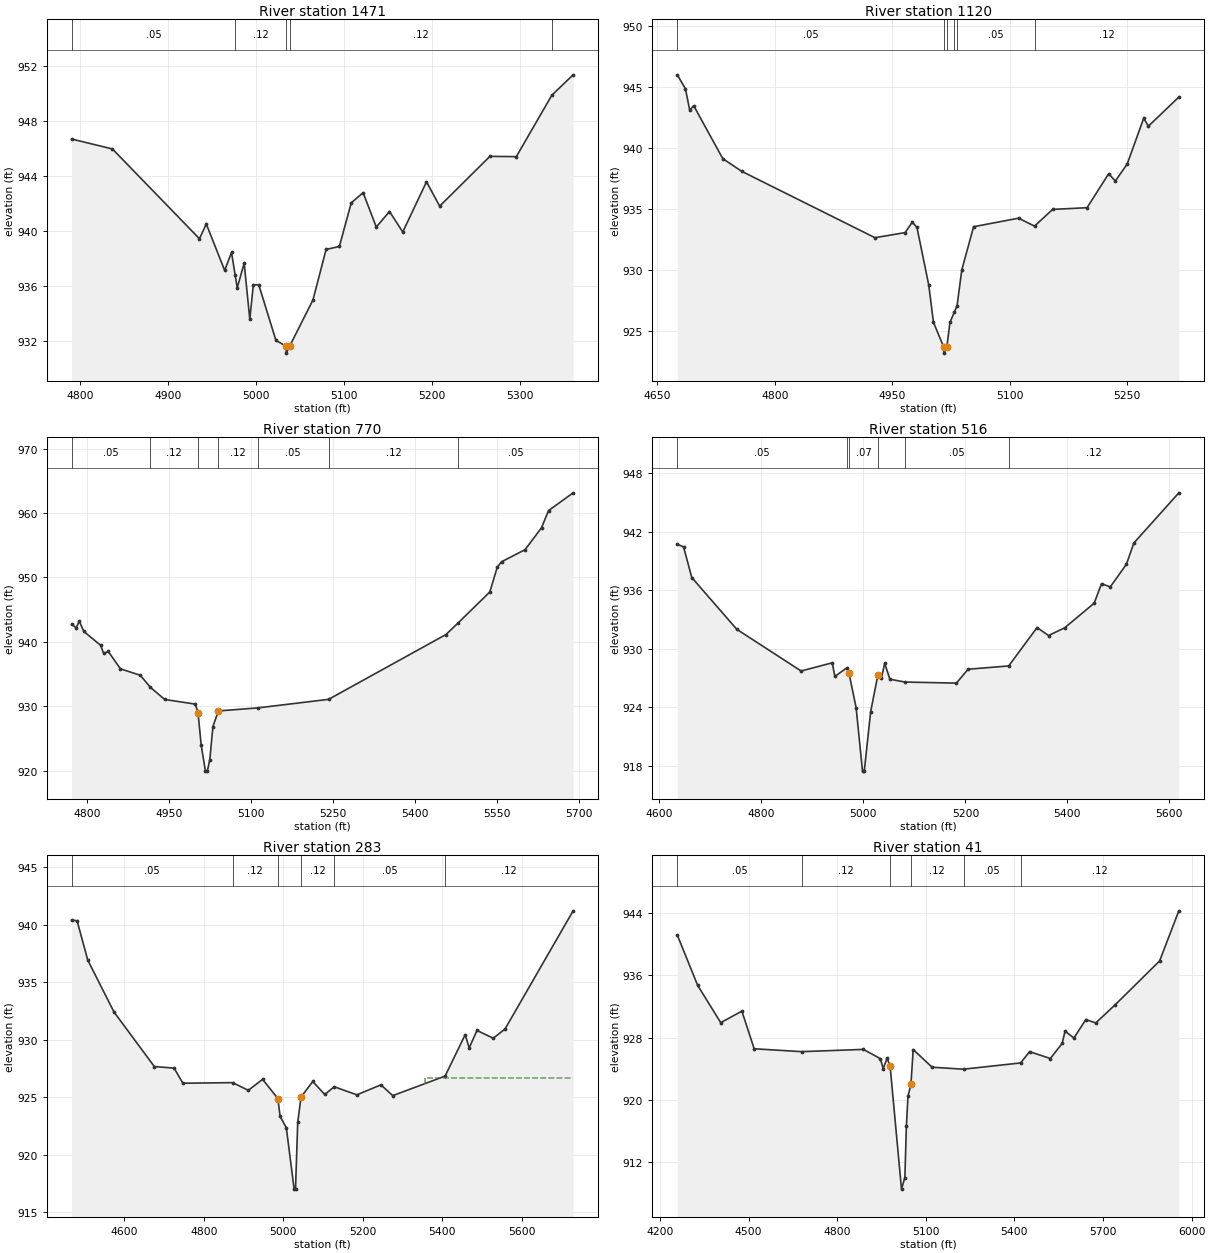
Type RM Length L Ch R = 1 ,1471    ,351,351,351
BEGIN DESCRIPTION:
UDS St 26 3.0
END DESCRIPTION:
XS GIS Cut Line= 3
      2240645.26      7187971.78        2240779.        7187810.
      2240979.02      7187509.97
#Sta/Elev= 30
  4790.3   946.7  4836.7  945.98  4935.7  939.45  4943.5  940.52  4964.4  937.15
  4972.2  938.45  4976.3  936.83  4978.7  935.88  4986.6  937.67    4993  933.59
    4997   936.1  5003.2   936.1  5022.7  932.06  5034.3  931.63  5034.5  931.13
  5038.3  931.63  5064.8  934.99  5079.8  938.67  5094.9  938.89  5108.4  942.06
  5121.9   942.8  5136.9   940.3  5151.9  941.43    5167  939.94    5194  943.59
    5209  941.82  5266.1  945.44  5296.2  945.42  5336.6  949.89  5360.8  951.37
#Mann= 5 ,-1 , 0
  4790.3     .05       0  4976.3     .12       0  5034.3     .07       0
  5038.3     .12       0  5336.6     .05       0
Bank Sta=5034.3,5038.3
XS Rating Curve= 0 ,0
Exp/Cntr=0.3,0.1

Type RM Length L Ch R = 1 ,1120    ,350,350,350
BEGIN DESCRIPTION:
UDS St 26 2.0
END DESCRIPTION:
XS GIS Cut Line= 3
      2240738.89      7188061.29      2240985.38      7188119.67
      2241196.83      7187794.84
#Sta/Elev= 30
  4675.5  946.01  4685.9  944.86  4691.3  943.11  4696.4  943.48  4733.6  939.14
  4757.8   938.1  4928.1  932.66  4966.6  933.08  4975.7  933.93  4981.7  933.51
  4996.8  928.78  5002.8  925.73  5015.9   923.7  5016.2   923.2  5019.9   923.7
  5023.9  925.72  5029.3  926.53    5033  927.09    5039  930.01  5054.1  933.56
  5111.5  934.26    5132  933.61  5155.1  934.98  5199.1  935.12  5226.7   937.9
  5235.3  937.31  5250.4   938.7  5271.5  942.45  5277.5   941.8  5316.4  944.19
#Mann= 6 ,-1 , 0
  4675.5     .05       0  5015.9    .033       0  5019.9     .05       0
  5029.3     .12       0    5033     .05       0    5132     .12       0
Bank Sta=5015.9,5019.9
XS Rating Curve= 0 ,0
Exp/Cntr=0.3,0.1

Type RM Length L Ch R = 1 ,770     ,254,254,254
BEGIN DESCRIPTION:
UDS St 26 1.0
END DESCRIPTION:
XS GIS Cut Line= 3
        2241029.        7188410.        2241229.        7188310.
      2241578.99      7187710.02
#Sta/Elev= 30
  4771.9  942.72  4780.3  942.19  4785.9  943.24  4794.3  941.61    4825  939.47
  4830.6   938.2    4839  938.51  4861.3  935.82  4897.7  934.81  4916.2  932.94
  4942.4  931.06  4998.4  930.34  5003.4  928.97  5009.1  923.98  5016.9  919.94
  5020.4  919.94  5024.9  921.72  5030.6  926.86  5040.6  929.28  5112.5  929.75
  5242.4  931.08  5457.3  941.14  5480.1  942.98  5537.6  947.75  5551.2  951.59
  5559.1  952.43  5602.1  954.31  5632.2   957.7  5645.1  960.37  5690.1  963.13
#Mann= 7 ,-1 , 0
  4771.9     .05       0  4916.2     .12       0  5003.4     .07       0
  5040.6     .12       0  5112.5     .05       0  5242.4     .12       0
  5480.1     .05       0
Bank Sta=5003.4,5040.6
XS Rating Curve= 0 ,0
Exp/Cntr=0.3,0.1

Type RM Length L Ch R = 1 ,516     ,233,233,233
BEGIN DESCRIPTION:
UDS St 26 0.9
END DESCRIPTION:
XS GIS Cut Line= 4
      2241057.28      7188416.81      2241363.39      7188508.16
      2241436.57      7188443.85      2241616.26      7187906.25
#Sta/Elev= 30
    4635   940.7  4647.2  940.44  4663.3   937.3  4751.6     932  4877.8  927.73
  4938.8  928.57    4944  927.18    4967  928.03  4971.5  927.56  4985.7  923.97
  4998.2  917.48  5001.7  917.48  5014.2  923.57  5028.4  927.33  5035.1  926.98
  5041.8  928.52  5051.9  926.89  5081.6   926.6  5182.5  926.49  5205.2  927.91
    5285  928.25  5340.6  932.18  5363.1  931.36  5394.7  932.15  5452.6  934.67
  5467.1  936.67  5484.2  936.34  5515.8  938.65  5530.4  940.83  5618.7  945.97
#Mann= 6 ,-1 , 0
    4635     .05       0    4967     .12       0  4971.5     .07       0
  5028.4     .12       0  5081.6     .05       0    5285     .12       0
#XS Ineff= 2 , 0
       0                  5205.2       0  927.91
Permanent Ineff=
       F       F
Bank Sta=4971.5,5028.4
XS Rating Curve= 0 ,0
Exp/Cntr=0.3,0.1

Type RM Length L Ch R = 1 ,283     ,242,242,242
BEGIN DESCRIPTION:
UDS St 26 0.8
END DESCRIPTION:
XS GIS Cut Line= 4
      2241055.42      7188425.46       2241461.6      7188700.91
       2241541.6       7188652.9      2241637.61       7187980.9
#Sta/Elev= 30
  4466.9   940.4  4480.6  940.35  4507.6  936.92  4573.5  932.42  4675.2  927.67
    4725  927.53  4747.1  926.22  4872.5  926.27  4911.9   925.6  4947.8  926.56
  4986.2  924.89    4992  923.33  5007.6  922.34  5027.2  917.01  5030.7  917.01
  5036.3  922.81  5044.5  925.01  5074.1  926.37  5104.4  925.24  5128.2  925.91
  5185.2  925.21  5245.8  926.08  5275.6  925.14  5407.4  926.84    5458  930.44
  5468.1  929.29  5487.7  930.81  5528.7  930.13  5558.4  930.94  5729.8  941.21
#Mann= 6 ,-1 , 0
  4466.9     .05       0  4872.5     .12       0  4986.2     .07       0
  5044.5     .12       0  5128.2     .05       0  5407.4     .12       0
#XS Ineff= 2 , 0
       0                  5356.9       0  926.71
Permanent Ineff=
       F       F
Bank Sta=4986.2,5044.5
XS Rating Curve= 0 ,0
Exp/Cntr=0.3,0.1

Type RM Length L Ch R = 1 ,41      ,0,0,0
BEGIN DESCRIPTION:
UDS St 26 0.7
END DESCRIPTION:
XS GIS Cut Line= 4
      2241049.95      7188431.93      2241581.78      7188875.81
      2241689.03      7188861.57      2241696.28      7187964.92
#Sta/Elev= 30
  4259.1  941.14  4327.9   934.7    4406  929.91  4477.6  931.39  4519.2  926.56
  4679.9  926.19  4888.9  926.48  4946.1   925.3    4956  924.01  4969.2  925.34
  4979.3  924.34  5017.9  908.55  5029.3  910.04  5034.4   916.6  5039.8  920.45
  5049.9  922.02  5057.5  926.46  5121.6  924.19    5228  923.94  5420.9  924.74
  5451.6  926.19  5521.6  925.31  5561.6  927.24  5571.6  928.82  5601.6  927.94
  5641.6   930.3  5675.7  929.88  5741.6  932.22  5891.6  937.83  5956.7  944.26
#Mann= 6 ,-1 , 0
  4259.1     .05       0  4679.9     .12       0  4979.3     .07       0
  5049.9     .12       0    5228     .05       0  5420.9     .12       0
Bank Sta=4979.3,5049.9
XS Rating Curve= 0 ,0
Exp/Cntr=0.3,0.1

Chan Stop Cuts=-1
Use User Specified Reach Order=0
Composite Channel Slope=5