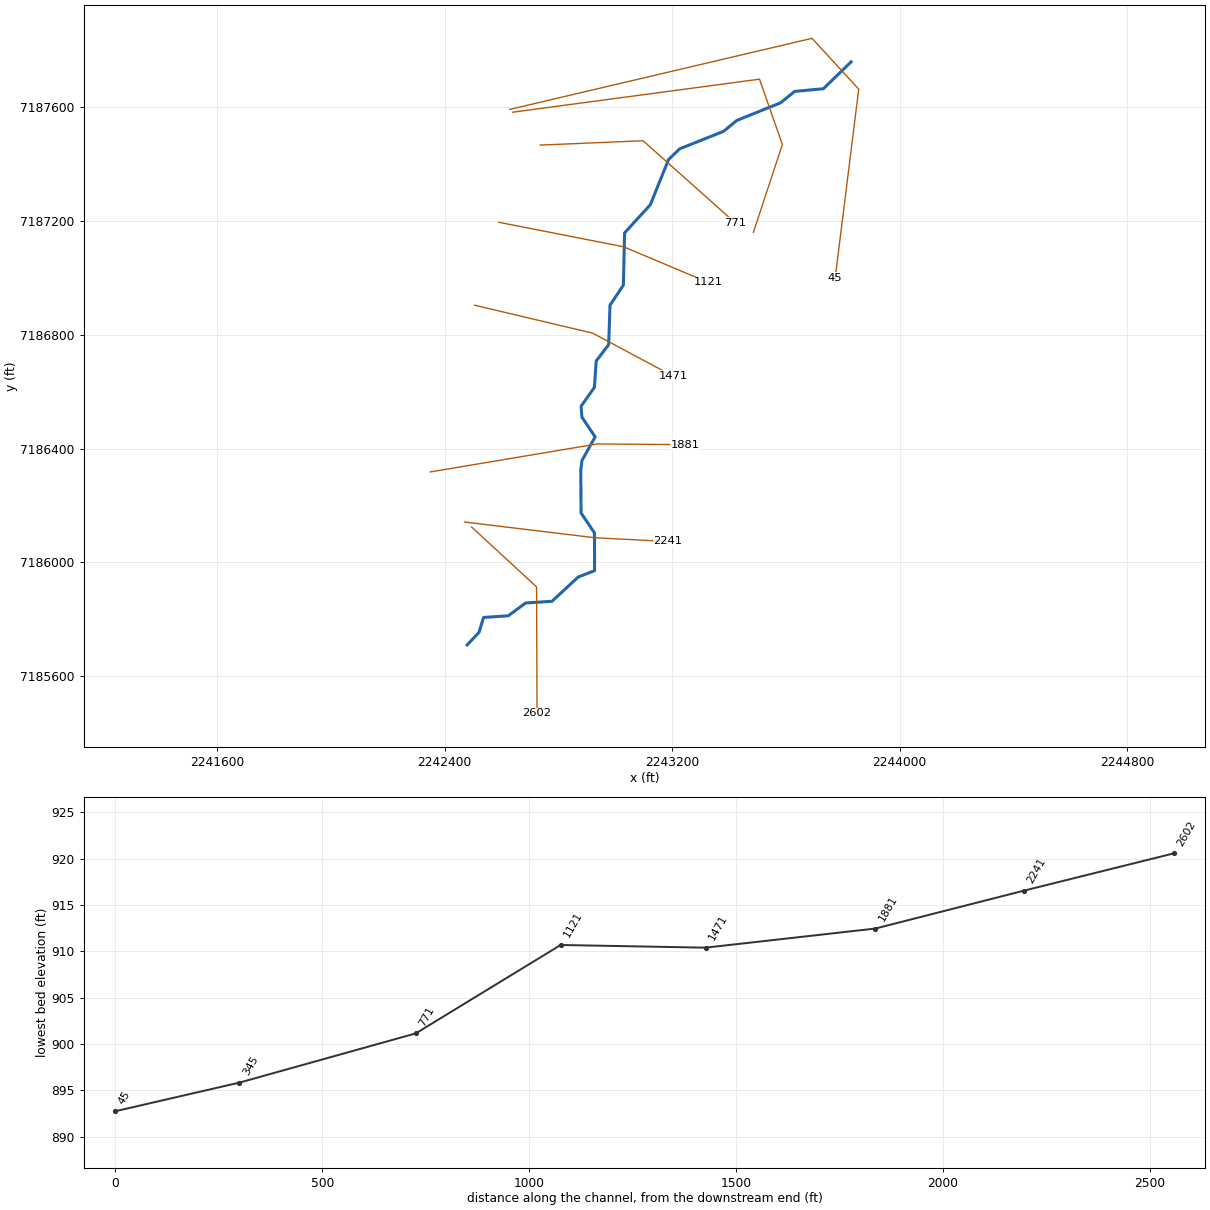
--- UDS St 27.prj (project) ---

Proj Title=UDS St 27 Base Level Engineering
Current Plan=p01
Default Exp/Contr=0.3,0.1
English Units
Geom File=g01
Flow File=f01
Plan File=p01
BEGIN DESCRIPTION:
UDS St 27
END DESCRIPTION:

--- UDS St 27.p01 (plan) ---

Plan Title=Multiple Run
Short Identifier=Multiple
Geom File=g01
Flow File=f01
Subcritical Flow
K Sum by GR= 0
Std Step Tol= 0.01
Critical Tol= 0.01
Num of Std Step Trials= 20
Max Error Tol= 0.3
Flow Tol Ratio= 0.001
Split Flow NTrial= 30
Split Flow Tol= 0.02
Split Flow Ratio= 0.02
Log Output Level= 0
Friction Slope Method= 1
Unsteady Friction Slope Method= 2
Unsteady Bridges Friction Slope Method= 1
Parabolic Critical Depth
Global Vel Dist=  1 , 1 , 1
Global Log Level= 0
CheckData=True
Encroach Param= -1, 0, 0, 0
BEGIN DESCRIPTION:
Multiple Run
END DESCRIPTION:

--- UDS St 27.f01 (steady flow) ---

Flow Title=Multiple
Number of Profiles=7
Profile Names=10-year,25-year,50-year,1pct_min,100-year,1pct_plu,500-year
River Rch & RM= UDS St 27,Reach-1,2602
     721    1019    1273     791    1578    3148    2430
Boundary for River Rch & Prof#=UDS St 27,Reach-1,1
Up Type=0
Dn Type=3
Dn Slope=0.005
Boundary for River Rch & Prof#=UDS St 27,Reach-1,2
Up Type=0
Dn Type=3
Dn Slope=0.005
Boundary for River Rch & Prof#=UDS St 27,Reach-1,3
Up Type=0
Dn Type=3
Dn Slope=0.005
Boundary for River Rch & Prof#=UDS St 27,Reach-1,4
Up Type=0
Dn Type=3
Dn Slope=0.005
Boundary for River Rch & Prof#=UDS St 27,Reach-1,5
Up Type=0
Dn Type=3
Dn Slope=0.005
Boundary for River Rch & Prof#=UDS St 27,Reach-1,6
Up Type=0
Dn Type=3
Dn Slope=0.005
Boundary for River Rch & Prof#=UDS St 27,Reach-1,7
Up Type=0
Dn Type=3
Dn Slope=0.005

--- UDS St 27.g01 (geometry) ---

Geom Title=Existing Conditions

River Reach=UDS St 27,Reach-1
Reach XY= 30
      2242479.00      7185710.00      2242520.85      7185754.36
      2242536.89      7185806.80      2242623.35      7185812.50
      2242684.97      7185857.64      2242777.50      7185863.62
      2242869.64      7185949.07      2242927.17      7185971.15
      2242926.75      7186104.05      2242879.68      7186173.92
      2242878.56      7186323.82      2242882.81      7186358.45
      2242929.16      7186441.57      2242882.40      7186511.72
      2242879.77      7186549.31      2242926.51      7186615.56
      2242932.86      7186708.40      2242976.73      7186765.94
      2242981.39      7186904.47      2243028.48      7186975.22
      2243032.55      7187158.53      2243123.15      7187257.71
      2243187.02      7187416.34      2243226.45      7187454.27
      2243381.20      7187516.08      2243426.80      7187553.92
      2243581.18      7187616.12      2243630.59      7187656.17
      2243731.45      7187665.46      2243829.00      7187760.00

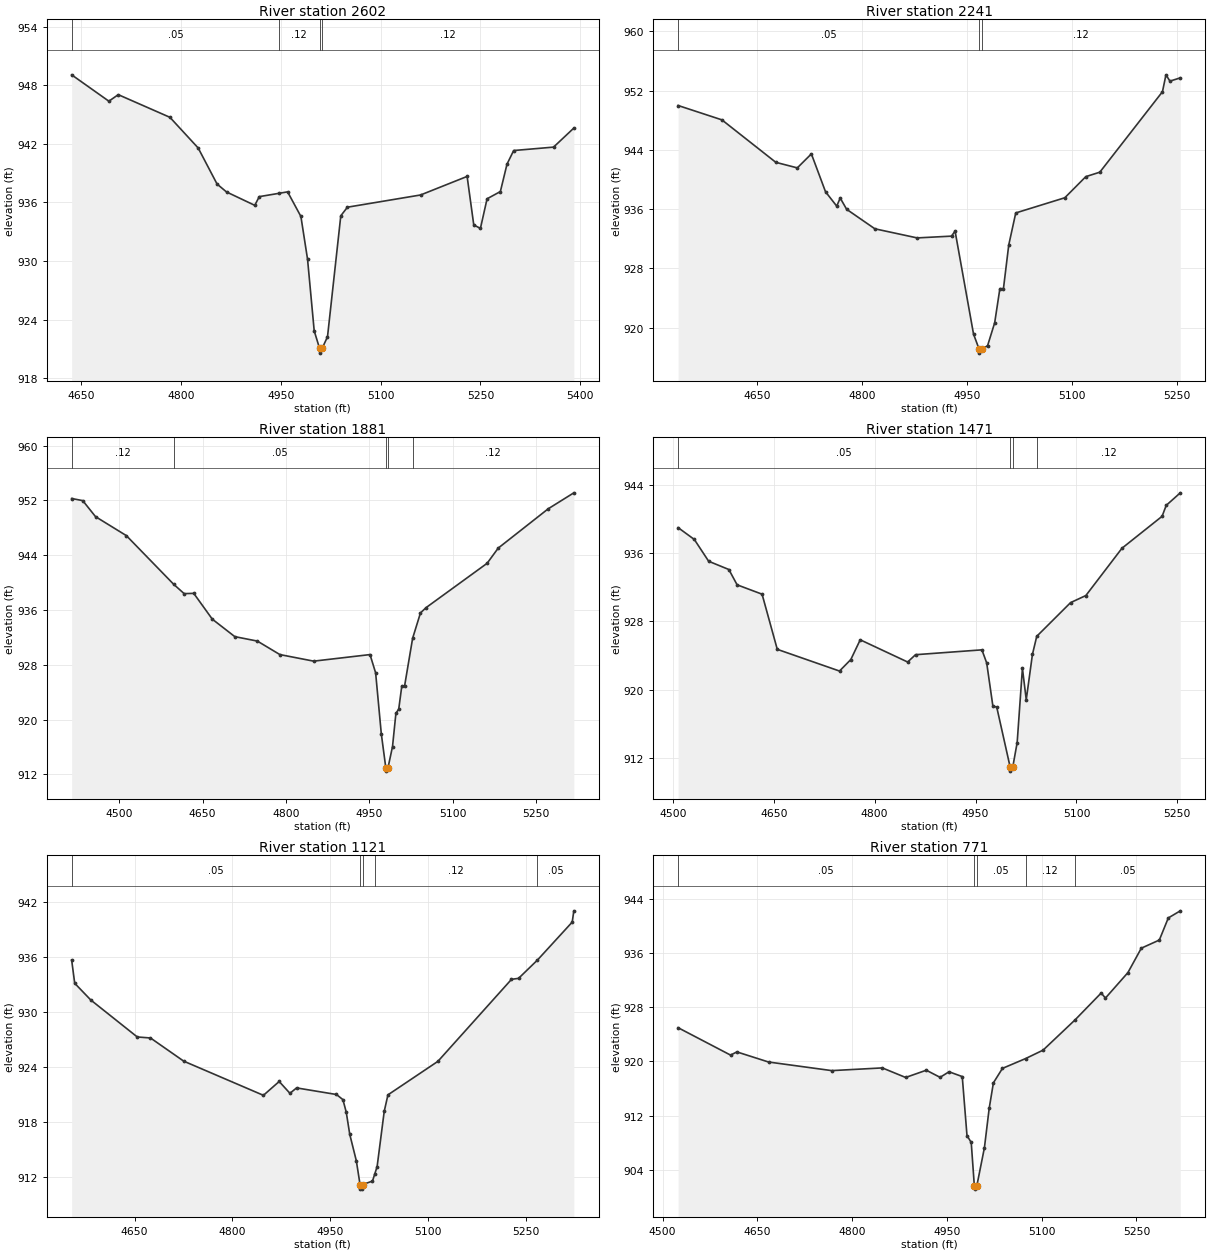
Type RM Length L Ch R = 1,2602,361,361,361
BEGIN DESCRIPTION:
UDS St 27 7.0
END DESCRIPTION:
XS GIS Cut Line= 3
      2242494.82      7186124.73      2242723.24      7185914.14
      2242724.87      7185469.53
#Sta/Elev= 30
  4635.2  949.07  4691.2  946.37  4705.3  947.04  4783.0  944.72  4825.5  941.58
  4853.9  937.89  4868.1  937.08  4910.6  935.71  4917.4  936.60  4947.1  936.94
  4960.0  937.09  4980.0  934.57  4990.0  930.19  5000.0  922.86  5008.0  921.08
  5008.3  920.58  5012.0  921.08  5020.0  922.25  5040.0  934.64  5050.0  935.52
  5160.0  936.77  5230.0  938.67  5240.0  933.70  5250.0  933.35  5260.0  936.38
  5280.0  937.12  5290.0  939.93  5300.0  941.32  5360.0  941.67  5390.5  943.62
#Mann=4,-1,0
  4635.2    0.05       0  4947.1    0.12       0  5008.0    0.07       0
  5012.0    0.12       0
Bank Sta=5008,5012
Exp/Cntr=0.3,0.1

Type RM Length L Ch R = 1,2241,360,360,360
BEGIN DESCRIPTION:
UDS St 27 6.0
END DESCRIPTION:
XS GIS Cut Line= 3
      2242469.96      7186142.27      2242928.78      7186086.89
      2243183.80      7186073.92
#Sta/Elev= 30
  4537.5  949.99  4600.1  948.05  4677.1  942.32  4707.8  941.57  4727.9  943.46
  4748.1  938.35  4764.1  936.41  4769.1  937.50  4778.3  935.98  4818.6  933.35
  4879.0  932.12  4928.1  932.36  4933.2  933.04  4959.6  919.13  4967.7  917.07
  4967.9  916.57  4971.7  917.07  4979.7  917.59  4989.8  920.67  4997.2  925.27
  5002.3  925.27  5009.9  931.17  5019.9  935.49  5090.0  937.54  5120.0  940.39
  5140.0  940.99  5229.5  951.85  5234.5  954.13  5240.2  953.28  5255.0  953.72
#Mann=3,-1,0
  4537.5    0.05       0  4967.7    0.07       0  4971.7    0.12       0
Bank Sta=4967.7,4971.7
Exp/Cntr=0.3,0.1

Type RM Length L Ch R = 1,1881,410,410,410
BEGIN DESCRIPTION:
UDS St 27 5.0
END DESCRIPTION:
XS GIS Cut Line= 3
      2242349.31      7186318.28      2242936.85      7186416.82
      2243245.10      7186414.28
#Sta/Elev= 30
  4414.4  952.28  4434.4  951.97  4457.4  949.63  4512.9  946.86  4598.1  939.75
  4616.9  938.39  4634.2  938.43  4667.6  934.66  4708.1  932.11  4748.7  931.46
  4789.2  929.49  4850.1  928.53  4951.5  929.49  4961.6  926.82  4971.8  917.93
  4979.9  912.97  4980.2  912.47  4983.9  912.97  4992.0  916.06  4998.1  920.91
  5003.2  921.53  5008.7  924.89  5013.7  924.89  5028.2  931.87  5042.3  935.57
  5052.3  936.34  5162.3  942.82  5182.3  945.04  5272.3  950.78  5318.4  953.11
#Mann=5,-1,0
  4414.4    0.12       0  4598.1    0.05       0  4979.9   0.033       0
  4983.9    0.05       0  5028.2    0.12       0
Bank Sta=4979.9,4983.9
Exp/Cntr=0.3,0.1

Type RM Length L Ch R = 1,1471,350,350,350
BEGIN DESCRIPTION:
UDS St 27 4.0
END DESCRIPTION:
XS GIS Cut Line= 3
      2242505.59      7186904.46      2242920.44      7186806.28
      2243202.87      7186655.43
#Sta/Elev= 30
  4507.9  939.02  4532.0  937.63  4553.3  935.07  4583.3  934.10  4595.6  932.30
  4632.7  931.20  4655.3  924.72  4747.8  922.17  4764.6  923.52  4778.6  925.84
  4849.1  923.23  4860.8  924.09  4959.5  924.66  4966.6  923.12  4975.8  918.05
  4981.5  917.94  5001.4  910.91  5001.7  910.41  5005.4  910.91  5011.9  913.77
  5019.7  922.49  5025.4  918.80  5034.6  924.13  5041.0  926.25  5091.3  930.21
  5114.0  931.04  5167.7  936.60  5227.3  940.35  5233.5  941.64  5254.4  943.11
#Mann=4,-1,0
  4507.9    0.05       0  5001.4   0.033       0  5005.4    0.05       0
  5041.0    0.12       0
Bank Sta=5001.4,5005.4
Exp/Cntr=0.3,0.1

Type RM Length L Ch R = 1,1121,350,350,350
BEGIN DESCRIPTION:
UDS St 27 3.0
END DESCRIPTION:
XS GIS Cut Line= 3
      2242590.23      7187196.09      2243029.00      7187110.00
      2243327.18      7186984.38
#Sta/Elev= 30
  4553.3  935.71  4558.0  933.17  4582.6  931.35  4654.0  927.31  4674.3  927.20
  4725.3  924.67  4847.6  920.94  4871.8  922.45  4888.3  921.16  4898.5  921.75
  4959.7  921.03  4969.6  920.47  4974.7  919.11  4980.1  916.68  4990.2  913.79
  4995.9  911.20  4996.1  910.70  4999.6  910.70  4999.9  911.20  5015.0  911.58
  5018.7  912.40  5022.1  913.16  5033.0  919.19  5038.7  920.99  5115.4  924.65
  5228.3  933.60  5239.2  933.71  5268.2  935.71  5321.5  939.85  5324.0  941.08
#Mann=5,-1,0
  4553.3    0.05       0  4995.9   0.033       0  4999.9    0.05       0
  5018.7    0.12       0  5268.2    0.05       0
Bank Sta=4995.9,4999.9
Exp/Cntr=0.3,0.1

Type RM Length L Ch R = 1,771,426,426,426
BEGIN DESCRIPTION:
UDS St 27 2.0
END DESCRIPTION:
XS GIS Cut Line= 3
      2242736.06      7187467.45      2243097.69      7187482.67
      2243420.92      7187194.78
#Sta/Elev= 30
  4524.6  924.97  4607.6  920.93  4617.6  921.40  4667.7  919.91  4767.8  918.64
  4847.8  919.04  4884.7  917.63  4917.4  918.70  4939.2  917.65  4953.4  918.47
  4974.3  917.76  4981.8  909.05  4988.5  908.05  4993.4  901.66  4993.7  901.16
  4997.4  901.66  5009.4  907.28  5016.9  913.06  5023.6  916.84  5037.9  918.97
  5074.6  920.42  5102.2  921.66  5152.9  926.13  5194.2  930.09  5200.9  929.34
  5236.5  933.10  5257.7  936.70  5286.2  937.90  5300.4  941.16  5319.4  942.21
#Mann=5,-1,0
  4524.6    0.05       0  4993.4   0.033       0  4997.4    0.05       0
  5074.6    0.12       0  5152.9    0.05       0
Bank Sta=4993.4,4997.4
Exp/Cntr=0.3,0.1

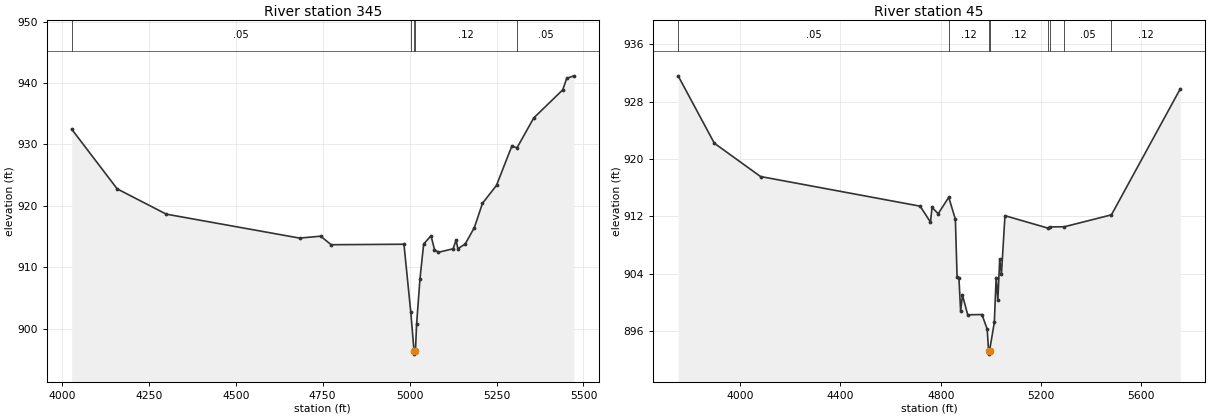
Type RM Length L Ch R = 1,345,300,300,300
BEGIN DESCRIPTION:
UDS St 27 1.0
END DESCRIPTION:
XS GIS Cut Line= 4
      2242639.28      7187583.08      2243506.93      7187699.16
      2243587.34      7187469.55      2243485.41      7187160.48
#Sta/Elev= 30
  4028.2  932.50  4159.1  922.77  4300.3  918.65  4683.7  914.75  4744.2  915.06
  4774.5  913.67  4983.8  913.75  5003.4  902.67  5012.8  896.35  5013.1  895.85
  5016.8  896.35  5020.1  900.71  5029.8  908.08  5040.4  913.78  5061.6  915.13
  5071.6  912.89  5082.8  912.44  5125.2  913.01  5133.6  914.42  5138.9  913.02
  5159.9  913.79  5186.3  916.47  5209.6  920.42  5249.9  923.34  5293.8  929.71
  5309.1  929.48  5357.0  934.32  5440.4  938.90  5451.7  940.76  5472.3  941.18
#Mann=5,-1,0
  4028.2    0.05       0  5003.4    0.12       0  5012.8   0.033       0
  5016.8    0.12       0  5309.1    0.05       0
Bank Sta=5012.8,5016.8
Exp/Cntr=0.3,0.1

Type RM Length L Ch R = 1,45,0,0,0
BEGIN DESCRIPTION:
UDS St 27 0.9
END DESCRIPTION:
XS GIS Cut Line= 4
      2242629.01      7187592.94      2243691.64      7187842.73
      2243855.87      7187664.06      2243772.96      7187000.19
#Sta/Elev= 30
  3752.5  931.62  3897.0  922.21  4081.2  917.56  4717.9  913.42  4759.2  911.19
  4765.5  913.24  4790.0  912.37  4832.0  914.66  4858.5  911.60  4865.3  903.59
  4872.7  903.41  4879.4  898.80  4886.8  901.00  4907.8  898.25  4964.5  898.29
  4985.5  896.24  4990.9  893.26  4991.1  892.76  4994.9  893.26  5013.9  897.19
  5021.2  903.45  5028.0  900.30  5035.4  906.04  5042.2  903.90  5056.4  912.09
  5226.5  910.37  5237.3  910.52  5293.8  910.55  5481.1  912.21  5755.8  929.82
#Mann=8,-1,0
  3752.5    0.05       0  4832.0    0.12       0  4990.9    0.07       0
  4994.9    0.12       0  5226.5    0.05       0  5237.3    0.12       0
  5293.8    0.05       0  5481.1    0.12       0
Bank Sta=4990.9,4994.9
Exp/Cntr=0.3,0.1

Chan Stop Cuts=-1