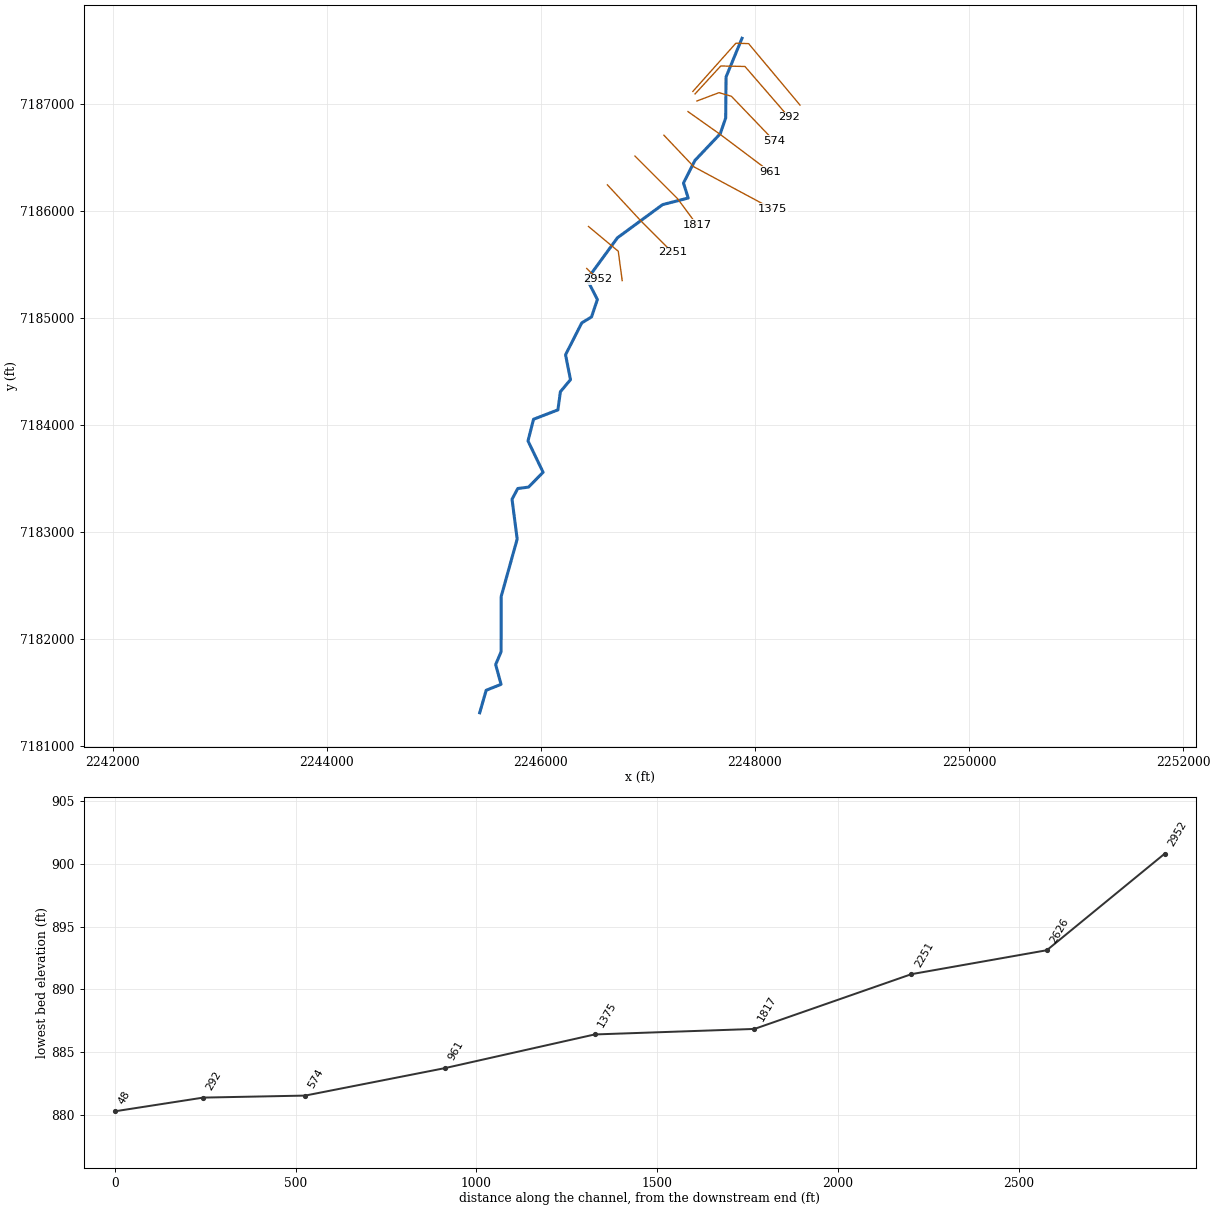
--- UDS St 28.prj (project) ---

Proj Title=UDS St 28 Base Level Engineering
Current Plan=p01
Default Exp/Contr=0.3,0.1
English Units
Geom File=g01
Flow File=f01
Plan File=p01
BEGIN DESCRIPTION:
UDS St 28
END DESCRIPTION:

--- UDS St 28.p01 (plan) ---

Plan Title=Multiple Run
Short Identifier=Multiple
Geom File=g01
Flow File=f01
Subcritical Flow
K Sum by GR= 0
Std Step Tol= 0.01
Critical Tol= 0.01
Num of Std Step Trials= 20
Max Error Tol= 0.3
Flow Tol Ratio= 0.001
Split Flow NTrial= 30
Split Flow Tol= 0.02
Split Flow Ratio= 0.02
Log Output Level= 0
Friction Slope Method= 1
Unsteady Friction Slope Method= 2
Unsteady Bridges Friction Slope Method= 1
Parabolic Critical Depth
Global Vel Dist=  1 , 1 , 1
Global Log Level= 0
CheckData=True
Encroach Param= -1, 0, 0, 0
BEGIN DESCRIPTION:
Multiple Run
END DESCRIPTION:

--- UDS St 28.f01 (steady flow) ---

Flow Title=Multiple
Number of Profiles=7
Profile Names=10-year,25-year,50-year,1pct_min,100-year,1pct_plu,500-year
River Rch & RM= UDS St 28,Reach-1,2952
     862    1221    1528     950    1895    3781    2921
River Rch & RM= UDS St 28,Reach-1,1817
     885    1258    1577     982    1959    3910    3033
Boundary for River Rch & Prof#=UDS St 28,Reach-1,1
Up Type=0
Dn Type=3
Dn Slope=0.005
Boundary for River Rch & Prof#=UDS St 28,Reach-1,2
Up Type=0
Dn Type=3
Dn Slope=0.005
Boundary for River Rch & Prof#=UDS St 28,Reach-1,3
Up Type=0
Dn Type=3
Dn Slope=0.005
Boundary for River Rch & Prof#=UDS St 28,Reach-1,4
Up Type=0
Dn Type=3
Dn Slope=0.005
Boundary for River Rch & Prof#=UDS St 28,Reach-1,5
Up Type=0
Dn Type=3
Dn Slope=0.005
Boundary for River Rch & Prof#=UDS St 28,Reach-1,6
Up Type=0
Dn Type=3
Dn Slope=0.005
Boundary for River Rch & Prof#=UDS St 28,Reach-1,7
Up Type=0
Dn Type=3
Dn Slope=0.005

--- UDS St 28.g01 (geometry) ---

Geom Title=Existing Conditions

River Reach=UDS St 28,Reach-1
Reach XY= 30
      2245429.00      7181310.00      2245489.33      7181520.17
      2245628.58      7181575.64      2245578.18      7181760.00
      2245628.93      7181880.03      2245629.68      7182396.08
      2245779.09      7182932.69      2245730.90      7183304.33
      2245784.44      7183404.75      2245885.12      7183417.88
      2246021.23      7183556.59      2245880.07      7183849.34
      2245932.07      7184051.72      2246159.59      7184139.36
      2246182.75      7184308.47      2246276.96      7184421.31
      2246230.97      7184654.11      2246382.19      7184951.65
      2246473.54      7185007.34      2246528.12      7185169.87
      2246432.10      7185358.35      2246715.44      7185746.51
      2247137.19      7186056.34      2247376.50      7186118.15
      2247332.35      7186258.27      2247439.77      7186469.68
      2247675.81      7186718.35      2247726.63      7186865.53
      2247730.20      7187249.50      2247879.00      7187610.00

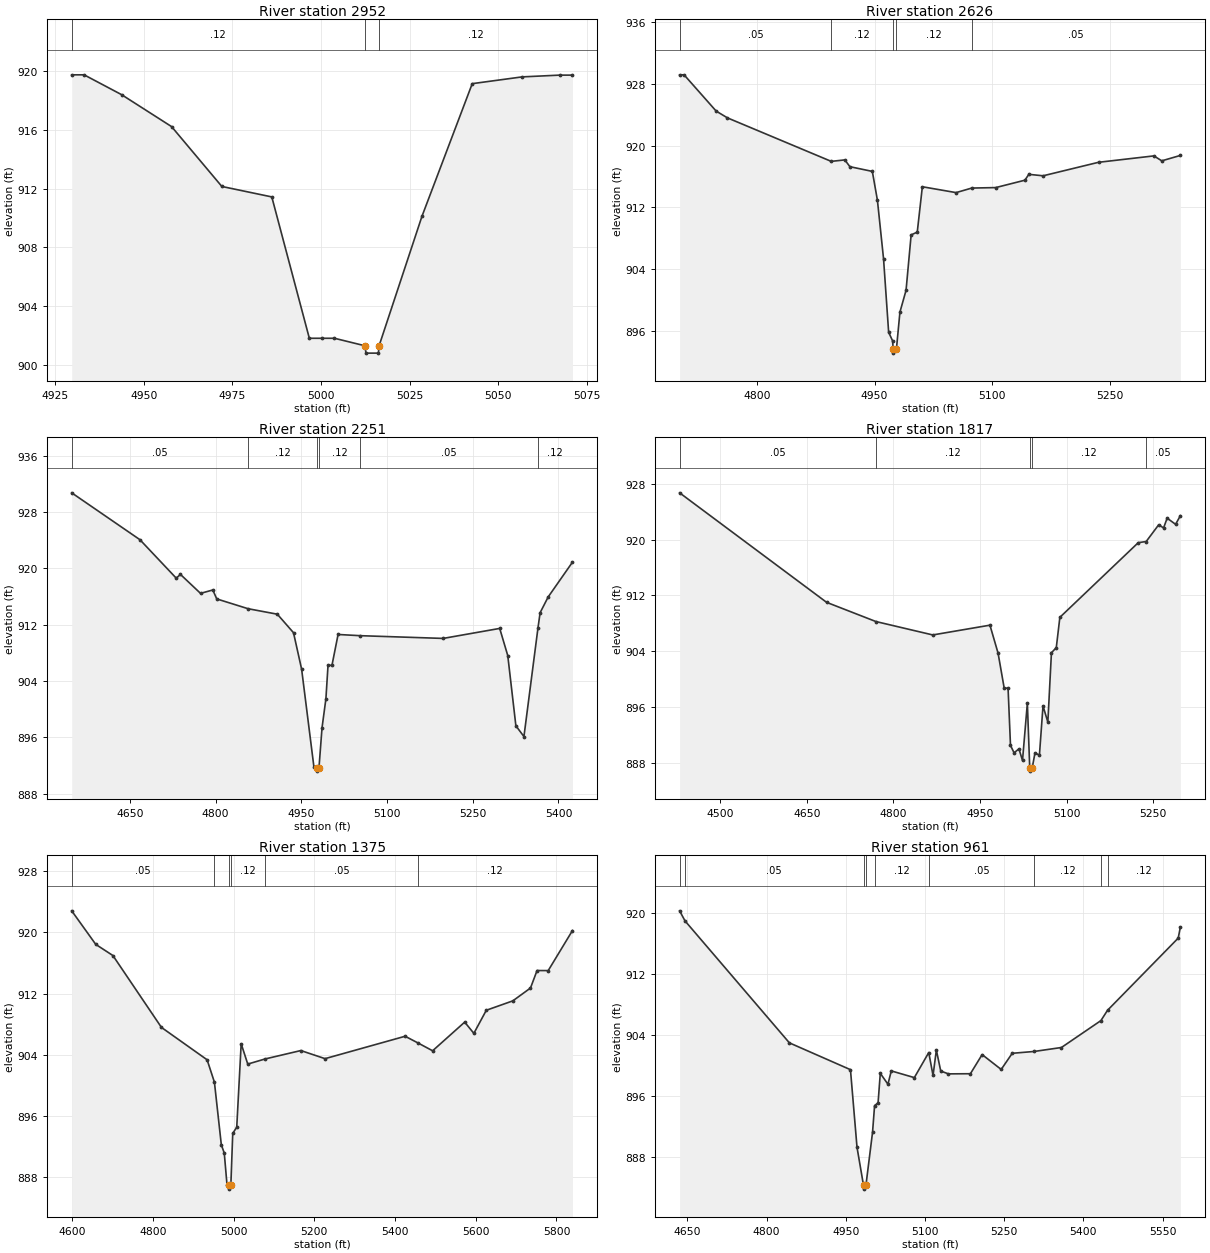
Type RM Length L Ch R = 1,2952,326,326,326
BEGIN DESCRIPTION:
UDS St 28 7.0
END DESCRIPTION:
XS GIS Cut Line= 3
      2246429.03      7185459.97      2246479.00      7185410.00
      2246529.02      7185359.98
#Sta/Elev= 18
  4929.6  919.73  4933.1  919.73  4943.7  918.38  4957.8  916.21  4972.0  912.14
  4986.1  911.43  4996.7  901.82  5000.3  901.82  5003.8  901.82  5012.4  901.31
  5012.7  900.81  5016.2  900.81  5016.4  901.31  5028.5  910.11  5042.7  919.13
  5056.8  919.59  5067.4  919.71  5071.0  919.71
#Mann=3,-1,0
  4929.6    0.12       0  5012.4    0.07       0  5016.4    0.12       0
Bank Sta=5012.4,5016.4
Exp/Cntr=0.3,0.1

Type RM Length L Ch R = 1,2626,375,375,375
BEGIN DESCRIPTION:
UDS St 28 6.0
END DESCRIPTION:
XS GIS Cut Line= 3
      2246445.23      7185852.39      2246723.26      7185621.04
      2246760.14      7185346.50
#Sta/Elev= 30
  4701.3  929.20  4707.0  929.20  4747.9  924.50  4762.3  923.62  4894.7  917.98
  4912.0  918.17  4918.5  917.29  4947.1  916.68  4953.6  912.93  4961.4  905.35
  4967.9  895.83  4972.9  894.72  4973.8  893.62  4974.0  893.12  4977.8  893.62
  4982.3  898.44  4990.1  901.26  4996.6  908.45  5004.4  908.81  5010.9  914.69
  5053.9  913.93  5073.9  914.52  5104.4  914.58  5141.7  915.54  5146.7  916.30
  5164.9  916.11  5235.6  917.86  5306.2  918.69  5316.3  918.05  5340.0  918.75
#Mann=5,-1,0
  4701.3    0.05       0  4894.7    0.12       0  4973.8    0.07       0
  4977.8    0.12       0  5073.9    0.05       0
Bank Sta=4973.8,4977.8
Exp/Cntr=0.3,0.1

Type RM Length L Ch R = 1,2251,434,434,434
BEGIN DESCRIPTION:
UDS St 28 5.0
END DESCRIPTION:
XS GIS Cut Line= 3
      2246621.67      7186241.32      2246929.00      7185910.00
      2247229.02      7185609.98
#Sta/Elev= 30
  4548.3  930.74  4667.7  924.08  4731.2  918.62  4738.6  919.15  4773.7  916.46
  4795.2  916.94  4802.1  915.67  4856.9  914.28  4908.1  913.50  4936.4  910.87
  4950.6  905.69  4972.1  891.81  4977.0  891.71  4977.2  891.21  4981.0  891.71
  4986.3  897.36  4993.1  901.49  4996.8  906.24  5003.7  906.24  5014.4  910.62
  5052.7  910.45  5198.2  910.06  5297.2  911.48  5311.3  907.62  5325.5  897.65
  5339.6  896.12  5364.1  911.51  5367.9  913.71  5382.0  915.95  5424.5  920.89
#Mann=6,-1,0
  4548.3    0.05       0  4856.9    0.12       0  4977.0    0.07       0
  4981.0    0.12       0  5052.7    0.05       0  5364.1    0.12       0
Bank Sta=4977,4981
Exp/Cntr=0.3,0.1

Type RM Length L Ch R = 1,1817,442,442,442
BEGIN DESCRIPTION:
UDS St 28 4.0
END DESCRIPTION:
XS GIS Cut Line= 3
      2246879.01      7186509.99      2247279.00      7186110.00
      2247458.40      7185867.65
#Sta/Elev= 30
  4429.9  926.70  4684.4  911.02  4769.8  908.27  4868.3  906.35  4967.3  907.75
  4981.4  903.74  4992.0  898.73  4998.7  898.73  5002.9  890.53  5009.1  889.47
  5017.5  890.04  5023.7  888.38  5032.1  896.58  5036.2  887.35  5036.6  886.85
  5040.6  887.35  5045.3  889.45  5053.0  889.14  5059.2  896.19  5067.6  893.87
  5073.8  903.80  5082.2  904.53  5088.4  908.87  5224.1  919.56  5237.9  919.73
  5259.6  922.13  5268.0  921.67  5274.2  923.07  5288.8  922.19  5297.1  923.43
#Mann=5,-1,0
  4429.9    0.05       0  4769.8    0.12       0  5036.2    0.07       0
  5040.6    0.12       0  5237.9    0.05       0
Bank Sta=5036.2,5040.6
Exp/Cntr=0.3,0.1

Type RM Length L Ch R = 1,1375,414,414,414
BEGIN DESCRIPTION:
UDS St 28 3.0
END DESCRIPTION:
XS GIS Cut Line= 3
      2247149.67      7186704.79      2247429.00      7186410.00
      2248164.25      7186015.09
#Sta/Elev= 30
  4599.0  922.82  4658.6  918.43  4701.1  916.97  4821.3  907.57  4934.5  903.33
  4952.6  900.40  4969.7  892.21  4977.0  891.13  4983.9  886.91  4988.9  886.91
  4989.3  886.41  4993.3  886.91  4998.0  893.71  5007.9  894.50  5018.9  905.43
  5035.2  902.77  5078.2  903.44  5166.7  904.54  5226.7  903.48  5425.1  906.41
  5457.1  905.53  5493.2  904.51  5572.7  908.26  5595.4  906.79  5626.2  909.81
  5691.9  911.04  5735.7  912.72  5752.0  915.01  5779.6  915.00  5839.7  920.24
#Mann=6,-1,0
  4599.0    0.05       0  4952.6    0.12       0  4988.9    0.07       0
  4993.3    0.12       0  5078.2    0.05       0  5457.1    0.12       0
Bank Sta=4988.9,4993.3
Exp/Cntr=0.3,0.1

Type RM Length L Ch R = 1,961,387,387,387
BEGIN DESCRIPTION:
UDS St 28 2.0
END DESCRIPTION:
XS GIS Cut Line= 3
      2247374.72      7186925.37      2247679.00      7186710.00
      2248139.04      7186363.87
#Sta/Elev= 30
  4635.2  920.24  4645.4  918.92  4843.1  902.92  4958.8  899.40  4971.2  889.22
  4983.5  884.23  4984.0  883.73  4988.1  884.23  5000.6  891.17  5004.5  894.69
  5011.1  895.05  5015.3  898.92  5029.8  897.49  5036.1  899.24  5079.8  898.36
  5107.1  901.65  5115.2  898.64  5121.5  901.97  5129.8  899.22  5144.4  898.85
  5186.0  898.87  5208.2  901.38  5244.3  899.43  5265.2  901.55  5306.7  901.79
  5358.4  902.31  5433.2  905.84  5445.7  907.19  5579.6  916.66  5583.7  918.11
#Mann=9,-1,0
  4635.2    0.12       0  4645.4    0.05       0  4983.5   0.033       0
  4988.1    0.05       0  5004.5    0.12       0  5107.1    0.05       0
  5306.7    0.12       0  5433.2    0.05       0  5445.7    0.12       0
Bank Sta=4983.5,4988.1
Exp/Cntr=0.3,0.1

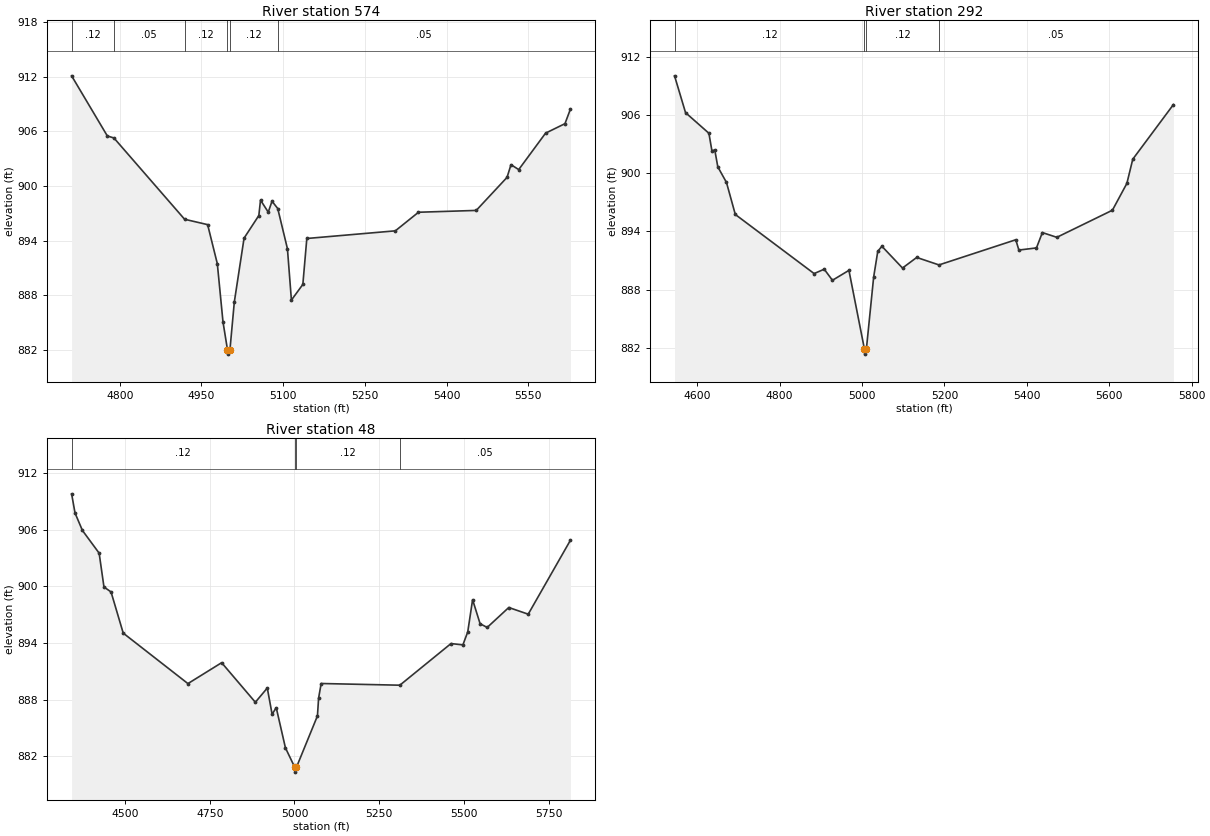
Type RM Length L Ch R = 1,574,282,282,282
BEGIN DESCRIPTION:
UDS St 28 1.0
END DESCRIPTION:
XS GIS Cut Line= 4
      2247457.57      7187024.37      2247664.66      7187102.37
      2247779.71      7187068.74      2248177.57      7186654.11
#Sta/Elev= 30
  4711.7  912.08  4777.3  905.48  4789.4  905.26  4919.1  896.34  4961.4  895.75
  4979.2  891.46  4989.6  885.08  4997.8  882.04  4998.2  881.54  5002.4  882.04
  5010.4  887.26  5028.3  894.27  5055.4  896.75  5058.5  898.44  5072.7  897.12
  5079.6  898.32  5090.1  897.52  5107.9  893.11  5115.2  887.47  5136.2  889.19
  5143.5  894.23  5306.0  895.07  5348.5  897.11  5454.5  897.31  5511.1  900.94
  5518.3  902.33  5532.5  901.79  5581.8  905.79  5617.4  906.83  5627.5  908.44
#Mann=6,-1,0
  4711.7    0.12       0  4789.4    0.05       0  4919.1    0.12       0
  4997.8    0.07       0  5002.4    0.12       0  5090.1    0.05       0
Bank Sta=4997.8,5002.4
Exp/Cntr=0.3,0.1

Type RM Length L Ch R = 1,292,244,244,244
BEGIN DESCRIPTION:
UDS St 28 0.9
END DESCRIPTION:
XS GIS Cut Line= 4
      2247440.46      7187090.41      2247680.53      7187351.52
      2247906.58      7187346.90      2248318.93      7186870.85
#Sta/Elev= 30
  4545.1  910.02  4571.8  906.23  4628.5  904.11  4635.9  902.28  4642.7  902.40
  4650.1  900.65  4671.1  899.05  4692.6  895.75  4883.8  889.67  4908.3  890.12
  4928.3  888.98  4968.3  890.00  5006.0  881.88  5006.4  881.38  5010.6  881.88
  5028.3  889.31  5038.3  891.96  5048.3  892.48  5098.3  890.24  5132.8  891.33
  5186.8  890.56  5373.2  893.15  5380.7  892.09  5423.4  892.31  5437.7  893.89
  5472.8  893.40  5607.7  896.19  5642.8  898.95  5657.1  901.44  5755.7  907.06
#Mann=4,-1,0
  4545.1    0.12       0  5006.0    0.07       0  5010.6    0.12       0
  5186.8    0.05       0
Bank Sta=5006,5010.6
Exp/Cntr=0.3,0.1

Type RM Length L Ch R = 1,48,0,0,0
BEGIN DESCRIPTION:
UDS St 28 0.8
END DESCRIPTION:
XS GIS Cut Line= 4
      2247420.28      7187114.05      2247821.88      7187564.34
      2247941.03      7187560.18      2248421.08      7186986.00
#Sta/Elev= 30
  4342.8  909.84  4352.9  907.80  4374.7  905.95  4424.0  903.54  4438.2  899.95
  4459.1  899.42  4495.0  895.05  4685.8  889.69  4785.2  891.91  4884.6  887.71
  4919.8  889.22  4934.0  886.44  4946.2  887.13  4973.3  882.87  5001.0  880.79
  5001.5  880.29  5005.6  880.79  5067.7  886.26  5071.1  888.15  5078.7  889.70
  5310.7  889.52  5461.5  893.94  5496.6  893.80  5510.9  895.18  5525.2  898.60
  5547.3  896.05  5568.2  895.65  5631.9  897.77  5689.2  897.06  5813.8  904.92
#Mann=4,-1,0
  4342.8    0.12       0  5001.0    0.07       0  5005.6    0.12       0
  5310.7    0.05       0
Bank Sta=5001,5005.6
Exp/Cntr=0.3,0.1

Chan Stop Cuts=-1