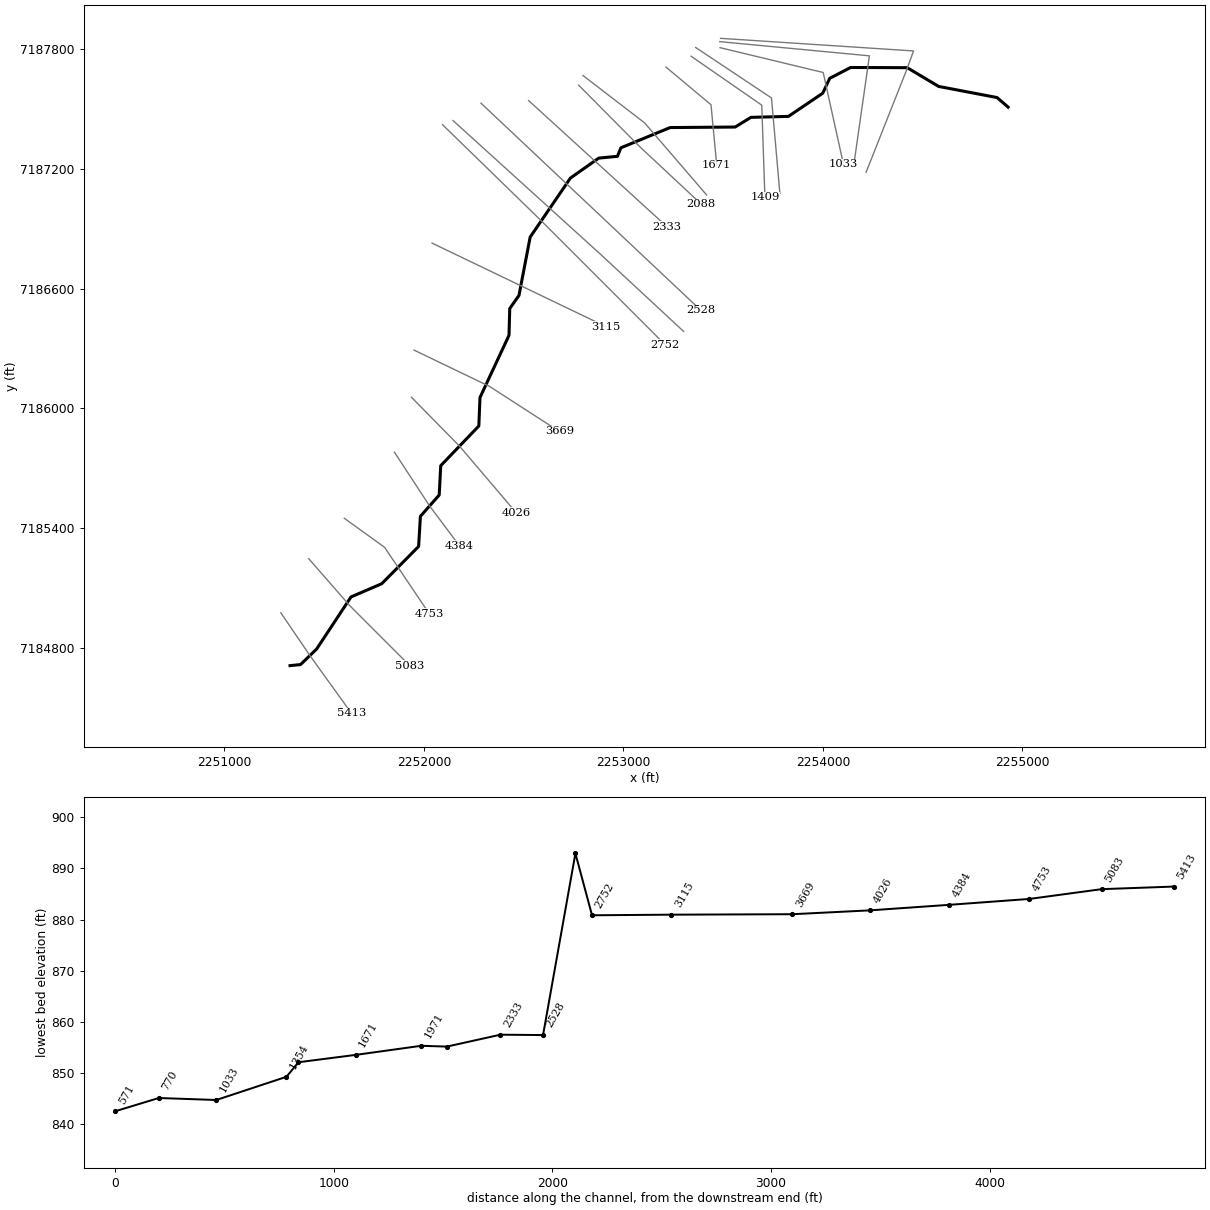
--- UDS St 29.prj (project) ---

Proj Title=UDS St 29 Base Level Engineering
Current Plan=p01
Default Exp/Contr=0.3,0.1
English Units
Geom File=g01
Flow File=f01
Plan File=p01
Y Axis Title=Elevation
X Axis Title(PF)=Main Channel Distance
X Axis Title(XS)=Station
BEGIN DESCRIPTION:
UDS St 29
END DESCRIPTION:
DSS Export Rating Curves= 0
DSS Export Rating Curve Sorted= 0
DSS Export Volume Flow Curves= 0
DXF OffsetX= 0
DXF OffsetY= 0
DXF ScaleX= 1
DXF ScaleY= 10

--- UDS St 29.p01 (plan) ---

Plan Title=Multiple Run
Short Identifier=Multiple
Geom File=g01
Flow File=f01
Subcritical Flow
K Sum by GR= 0
Std Step Tol= 0.01
Critical Tol= 0.01
Num of Std Step Trials= 20
Max Error Tol= 0.3
Flow Tol Ratio= 0.001
Split Flow NTrial= 30
Split Flow Tol= 0.02
Split Flow Ratio= 0.02
Log Output Level= 0
Friction Slope Method= 1
Unsteady Friction Slope Method= 2
Unsteady Bridges Friction Slope Method= 1
Parabolic Critical Depth
Global Vel Dist=  1 , 1 , 1
Global Log Level= 0
CheckData=True
Encroach Param= -1, 0, 0, 0
BEGIN DESCRIPTION:
Multiple Run
END DESCRIPTION:

--- UDS St 29.f01 (steady flow) ---

Flow Title=Multiple
Number of Profiles=7
Profile Names=10-year,25-year,50-year,1pct_min,100-year,1pct_plu,500-year
River Rch & RM= UDS St 29,Reach-1,5413
     644     900    1116     688    1373    2739    2082
River Rch & RM= UDS St 29,Reach-1,2528
     713    1002    1246     771    1538    3069    2348
Boundary for River Rch & Prof#=UDS St 29,Reach-1,1
Up Type=0
Dn Type=3
Dn Slope=0.005
Boundary for River Rch & Prof#=UDS St 29,Reach-1,2
Up Type=0
Dn Type=3
Dn Slope=0.005
Boundary for River Rch & Prof#=UDS St 29,Reach-1,3
Up Type=0
Dn Type=3
Dn Slope=0.005
Boundary for River Rch & Prof#=UDS St 29,Reach-1,4
Up Type=0
Dn Type=3
Dn Slope=0.005
Boundary for River Rch & Prof#=UDS St 29,Reach-1,5
Up Type=0
Dn Type=3
Dn Slope=0.005
Boundary for River Rch & Prof#=UDS St 29,Reach-1,6
Up Type=0
Dn Type=3
Dn Slope=0.005
Boundary for River Rch & Prof#=UDS St 29,Reach-1,7
Up Type=0
Dn Type=3
Dn Slope=0.005

--- UDS St 29.g01 (geometry) ---

Geom Title=Existing Conditions
Program Version=4.10

River Reach=UDS St 29       ,Reach-1
Reach XY= 30
        2251329.        7184710.      2251381.54       7184715.3
      2251462.37       7184793.3      2251634.61      7185054.41
      2251788.68      7185120.77      2251973.53      7185307.55
      2251982.56      7185458.53      2252076.81      7185565.45
      2252084.47      7185712.45      2252275.46      7185911.47
      2252281.25      7186054.07      2252426.73      7186365.94
      2252430.39      7186500.33      2252476.73      7186565.94
      2252532.82      7186858.42      2252734.62      7187154.38
      2252876.63      7187254.44      2252970.52       7187263.5
      2252987.64       7187306.1      2253234.53      7187407.62
      2253560.73      7187410.21      2253639.51      7187458.78
      2253827.53      7187463.55      2253999.43      7187579.73
      2254034.62      7187654.38      2254139.48      7187708.81
      2254423.07      7187707.76      2254580.58      7187613.83
      2254873.62      7187557.99        2254929.        7187510.

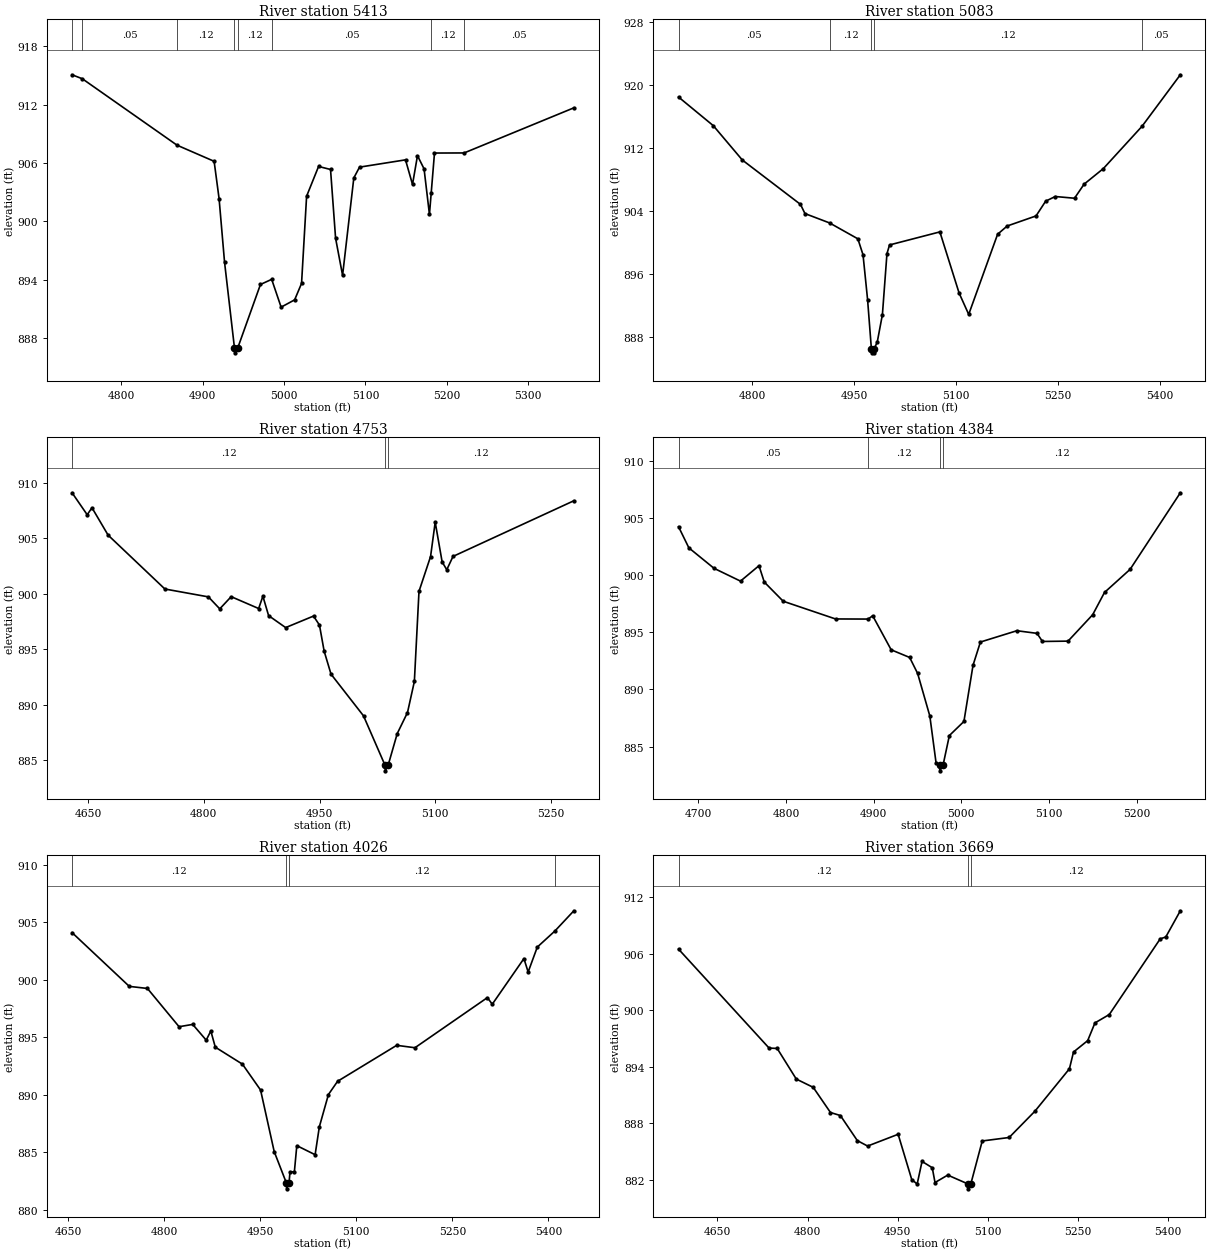
Type RM Length L Ch R = 1 ,5413    ,330,330,330
BEGIN DESCRIPTION:
UDS St 29 14.0
END DESCRIPTION:
XS GIS Cut Line= 3
      2251282.83      7184974.86        2251429.        7184760.
      2251637.37      7184470.69
#Sta/Elev= 30
  4739.7  915.06  4752.3  914.65  4868.6  907.82  4914.2  906.16  4920.3  902.32
    4927  895.79  4939.2  886.96  4939.5  886.46  4943.2  886.96  4971.1  893.49
  4984.9  894.02  4996.5  891.16  5013.1  891.91  5021.6   893.6  5027.8  902.57
  5042.5  905.63  5057.2  905.32  5063.4  898.25    5072  894.43  5085.8  904.45
  5092.8  905.56  5149.3  906.31  5157.9  903.78    5164  906.74  5172.1  905.38
  5178.7   900.7  5180.9  902.94  5184.9  907.01  5221.3  907.02  5356.1  911.66
#Mann= 8 ,-1 , 0
  4739.7     .12       0  4752.3     .05       0  4868.6     .12       0
  4939.2    .033       0  4943.2     .12       0  4984.9     .05       0
  5180.9     .12       0  5221.3     .05       0
Bank Sta=4939.2,4943.2
XS Rating Curve= 0 ,0
Exp/Cntr=0.3,0.1

Type RM Length L Ch R = 1 ,5083    ,330,330,330
BEGIN DESCRIPTION:
UDS St 29 13.0
END DESCRIPTION:
XS GIS Cut Line= 3
      2251422.78      7185246.25        2251629.        7185010.
      2251929.03      7184709.97
#Sta/Elev= 30
  4691.7  918.48  4742.8  914.84  4785.5  910.47    4871  904.83  4877.6  903.66
  4913.8  902.47  4955.4  900.45    4963  898.42  4969.7  892.72  4975.3  886.45
  4975.5  885.95    4979  885.95  4979.3  886.45  4983.9  887.31  4991.5  890.81
  4998.2  898.57    5002  899.67    5076  901.33  5104.3  893.55  5118.4  890.84
  5160.9  901.03    5175  902.08  5217.4  903.36  5231.6  905.24  5245.7  905.83
    5274  905.61  5288.1   907.4  5316.4  909.38  5373.3  914.76  5429.6  921.31
#Mann= 5 ,-1 , 0
  4691.7     .05       0  4913.8     .12       0  4975.3     .07       0
  4979.3     .12       0  5373.3     .05       0
Bank Sta=4975.3,4979.3
XS Rating Curve= 0 ,0
Exp/Cntr=0.3,0.1

Type RM Length L Ch R = 1 ,4753    ,369,369,369
BEGIN DESCRIPTION:
UDS St 29 12.0
END DESCRIPTION:
XS GIS Cut Line= 3
      2251601.12      7185448.69      2251802.92      7185303.27
      2252027.07      7184970.08
#Sta/Elev= 30
  4629.2  909.12  4648.8  907.14    4655  907.77  4675.9   905.3  4749.5  900.44
  4805.9  899.73  4820.6  898.65  4835.4  899.75    4871  898.68  4876.5  899.79
  4883.9  898.04    4906  896.96  4942.1     898  4949.8  897.19  4955.9  894.83
  4964.8  892.76  5006.9     889  5034.8  884.54  5035.1  884.04  5038.8  884.54
  5050.6   887.4  5063.9   889.3  5072.8   892.1  5078.8  900.23  5093.8  903.37
  5099.8  906.47  5108.8  902.88  5114.8  902.18  5122.9  903.38  5279.5   908.4
#Mann= 3 ,-1 , 0
  4629.2     .12       0  5034.8     .07       0  5038.8     .12       0
Bank Sta=5034.8,5038.8
XS Rating Curve= 0 ,0
Exp/Cntr=0.3,0.1

Type RM Length L Ch R = 1 ,4384    ,358,358,358
BEGIN DESCRIPTION:
UDS St 29 11.0
END DESCRIPTION:
XS GIS Cut Line= 3
      2251852.45      7185779.89        2252029.        7185510.
        2252179.      7185310.01
#Sta/Elev= 30
  4677.5  904.24  4689.3  902.39    4718   900.6  4748.2  899.48  4769.3  900.83
  4775.3   899.4  4796.9  897.72  4856.6  896.17  4893.8  896.16    4899  896.45
  4920.1  893.47  4941.2   892.8  4950.3   891.4  4964.2  887.68  4971.4  883.53
  4975.3  883.38  4975.6  882.88  4979.3  883.38  4986.5  885.97  5003.1   887.2
  5013.5  892.12  5021.9  894.15  5063.5  895.14  5086.5  894.91  5092.7   894.2
  5121.9  894.23    5150  896.54  5163.5  898.49  5192.7  900.51    5250  907.21
#Mann= 4 ,-1 , 0
  4677.5     .05       0  4893.8     .12       0  4975.3     .07       0
  4979.3     .12       0
Bank Sta=4975.3,4979.3
XS Rating Curve= 0 ,0
Exp/Cntr=0.3,0.1

Type RM Length L Ch R = 1 ,4026    ,357,357,357
BEGIN DESCRIPTION:
UDS St 29 10.0
END DESCRIPTION:
XS GIS Cut Line= 3
       2251937.9      7186055.21        2252179.        7185810.
      2252464.12      7185475.13
#Sta/Elev= 30
  4656.1  904.11  4745.5  899.43  4773.8  899.25  4823.2  895.92  4844.5  896.12
  4865.6  894.75  4872.8  895.55  4879.8  894.14  4922.2  892.66  4950.5  890.41
  4971.8  885.05  4990.9  882.31  4991.2  881.81  4994.9  882.31  4996.5  883.29
  5003.3  883.29  5007.1  885.57  5035.7  884.78  5042.3  887.21  5056.5  890.02
  5070.8  891.17  5163.1   894.3  5191.6  894.09  5304.7  898.45  5312.4  897.88
  5361.8  901.85  5368.4  900.68  5382.7  902.85  5410.2  904.25  5439.8  906.01
#Mann= 4 ,-1 , 0
  4656.1     .12       0  4990.9     .07       0  4994.9     .12       0
  5410.2     .05       0
Bank Sta=4990.9,4994.9
XS Rating Curve= 0 ,0
Exp/Cntr=0.3,0.1

Type RM Length L Ch R = 1 ,3669    ,554,554,554
BEGIN DESCRIPTION:
UDS St 29 9.0
END DESCRIPTION:
XS GIS Cut Line= 3
      2251951.04      7186291.68        2252329.        7186110.
      2252678.34      7185884.41
#Sta/Elev= 30
  4585.2  906.49  4735.9  895.99  4749.4  895.95  4781.2   892.7  4809.4  891.82
  4838.1  889.15  4854.6  888.83  4882.8  886.17  4899.9  885.59  4950.7  886.84
  4973.4  882.03  4982.4  881.56  4990.5  883.96  5007.5  883.29  5012.1  881.72
  5033.3  882.51  5067.6  881.55  5067.8  881.05  5071.6  881.55  5090.7  886.13
  5135.5   886.5  5178.4  889.29  5235.8  893.79  5242.6  895.57  5266.2  896.78
  5278.3  898.66  5302.2  899.55  5386.9  907.58  5396.2  907.78  5420.4  910.56
#Mann= 3 ,-1 , 0
  4585.2     .12       0  5067.6     .07       0  5071.6     .12       0
Bank Sta=5067.6,5071.6
XS Rating Curve= 0 ,0
Exp/Cntr=0.3,0.1

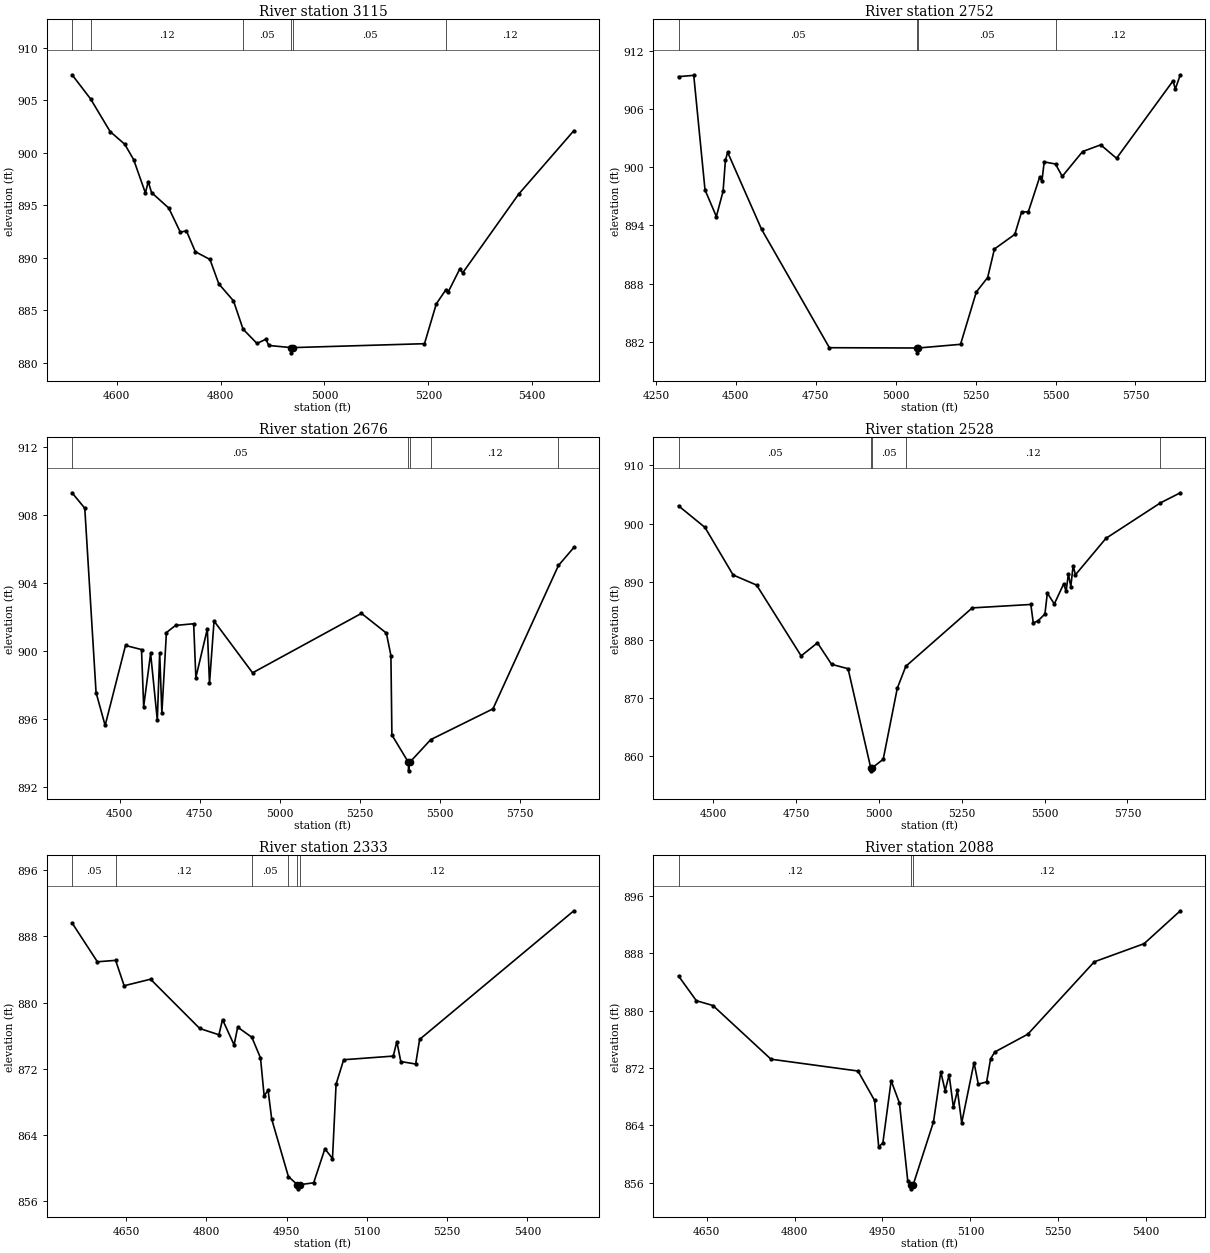
Type RM Length L Ch R = 1 ,3115    ,363,363,363
BEGIN DESCRIPTION:
UDS St 29 8.0
END DESCRIPTION:
XS GIS Cut Line= 2
      2252041.11      7186828.21      2252912.09      7186409.95
#Sta/Elev= 30
    4514  907.43  4549.7  905.13  4587.2  902.03  4615.4  900.82  4632.5  899.36
  4655.2  896.18  4660.7  897.26    4667  896.22  4700.2  894.74  4722.4  892.45
  4734.2  892.57  4751.3  890.59  4779.5  889.85  4796.6  887.52  4824.8  885.91
  4843.2  883.22  4870.1  881.85  4887.2  882.26  4892.7  881.66    4936  881.46
  4936.2  880.96    4940  881.46  5192.6  881.83  5215.3  885.62  5233.7  886.96
  5237.9  886.72  5260.5  888.94  5266.1  888.57  5373.8  896.06  5480.2  902.11
#Mann= 6 ,-1 , 0
    4514     .05       0  4549.7     .12       0  4843.2     .05       0
    4936    .033       0    4940     .05       0  5233.7     .12       0
Bank Sta=4936,4940
XS Rating Curve= 0 ,0
Exp/Cntr=0.3,0.1

Type RM Length L Ch R = 1 ,2752    ,76,76,76
BEGIN DESCRIPTION:
UDS St 29 7.0
END DESCRIPTION:
XS GIS Cut Line= 3
      2252093.62       7187421.8      2252578.63      7186949.91
      2253209.76      7186318.57
#Sta/Elev= 30
  4320.9  909.38  4368.5  909.51  4403.7  897.68  4439.2  894.92  4460.3  897.55
  4467.5  900.73  4474.5  901.56  4580.5  893.61  4792.7  881.37  5066.5  881.34
  5066.8  880.84  5070.5  881.34  5202.9  881.72  5252.3  887.13  5287.7  888.62
  5308.9  891.57  5372.6  893.08  5393.8  895.39    5415  895.42  5450.3  898.99
  5457.4  898.57  5464.5  900.57  5499.9  900.35    5521  899.07  5584.7  901.64
  5641.3  902.33  5690.8  900.94  5867.5  908.94  5874.6   908.1  5890.3  909.57
#Mann= 4 ,-1 , 0
  4320.9     .05       0  5066.5    .033       0  5070.5     .05       0
  5499.9     .12       0
Bank Sta=5066.5,5070.5
XS Rating Curve= 0 ,0
Exp/Cntr=0.3,0.1

Type RM Length L Ch R = 1 ,2676    ,148,148,148
BEGIN DESCRIPTION:
UDS St 29 6.3
END DESCRIPTION:
XS GIS Cut Line= 3
      2252145.98      7187442.95      2252887.06      7186770.86
      2253301.84      7186385.82
#Sta/Elev= 30
  4351.8  909.32  4391.5  908.41  4426.7  897.56    4455  895.62  4518.6  900.33
  4568.6  900.09  4575.3  896.73    4597  899.86  4617.9  895.94  4625.3  899.89
  4632.1  896.36  4646.3  901.09  4674.7  901.51  4731.4  901.61  4738.2  898.44
    4774   901.3  4780.8   898.1    4795  901.77  4915.3  898.72  5255.2  902.22
  5332.9  901.06  5347.1  899.74  5350.2  895.06  5401.8  893.45  5402.1  892.95
  5405.8  893.45  5471.6  894.79  5665.7   896.6  5870.1  905.04  5918.2   906.1
#Mann= 5 ,-1 , 0
  4351.8     .05       0  5401.8    .033       0  5405.8     .05       0
  5471.6     .12       0  5870.1     .05       0
Bank Sta=5401.8,5405.8
XS Rating Curve= 0 ,0
Exp/Cntr=0.3,0.1

Type RM Length L Ch R = 1 ,2528    ,195,195,195
BEGIN DESCRIPTION:
UDS St 29 6.2
END DESCRIPTION:
XS GIS Cut Line= 2
      2252286.19      7187529.95      2253388.05      7186491.78
#Sta/Elev= 30
  4395.7  903.05  4475.5  899.33  4560.4  891.14  4631.2   889.4  4765.6   877.2
  4814.9  879.45  4857.4  875.75  4907.2  874.99  4975.6   857.9  4975.8   857.4
  4979.6   857.9  5013.2  859.39  5055.7  871.63  5081.4  875.41  5281.8  885.47
  5458.6  886.06  5465.9   882.9  5480.1  883.22  5501.1  884.43  5508.4  888.01
  5529.4  886.15  5557.7  889.61    5565  888.32  5571.9  891.31  5579.2  889.13
  5586.1  892.71  5593.3  891.18  5685.2  897.45  5849.3  903.55  5909.6   905.3
#Mann= 5 ,-1 , 0
  4395.7     .05       0  4975.6    .033       0  4979.6     .05       0
  5081.4     .12       0  5849.3     .05       0
Bank Sta=4975.6,4979.6
XS Rating Curve= 0 ,0
Exp/Cntr=0.3,0.1

Type RM Length L Ch R = 1 ,2333    ,245,245,245
BEGIN DESCRIPTION:
UDS St 29 6.1
END DESCRIPTION:
XS GIS Cut Line= 2
      2252524.95      7187543.15      2253217.59       7186911.5
#Sta/Elev= 30
  4549.3  889.64  4596.6  884.94  4630.7  885.11  4646.6  882.04  4695.9  882.83
  4787.8  876.87  4823.6  876.11  4830.4  877.94    4852  874.88  4858.7  877.03
  4885.1  875.81  4901.3  873.31  4908.1  868.73  4915.5  869.39  4922.3  865.89
  4953.4  858.96  4970.2  857.97  4970.5  857.47  4974.2  857.97  5000.6   858.2
  5021.6  862.31  5035.8  861.14  5042.5  870.13  5056.7  873.09  5149.3  873.53
    5156  875.28  5163.4  872.87  5191.2  872.57  5198.6  875.55  5486.7  891.11
#Mann= 6 ,-1 , 0
  4549.3     .05       0  4630.7     .12       0  4885.1     .05       0
  4953.4     .12       0  4970.2     .07       0  4974.2     .12       0
Bank Sta=4970.2,4974.2
XS Rating Curve= 0 ,0
Exp/Cntr=0.3,0.1

Type RM Length L Ch R = 1 ,2088    ,117,117,117
BEGIN DESCRIPTION:
UDS St 29 6.0
END DESCRIPTION:
XS GIS Cut Line= 3
      2252776.04      7187620.07      2253080.94       7187312.8
       2253390.4      7187023.94
#Sta/Elev= 30
    4602  884.84  4632.4  881.39  4660.7  880.72  4759.7  873.23  4908.2  871.58
  4936.5  867.47  4943.5  861.02  4950.6  861.52  4964.8  870.23  4978.9  867.12
  4993.1  856.27  4998.1  855.64  4998.4  855.14  5002.1  855.64    5037  864.47
  5049.5  871.46  5056.9  868.83  5063.7  871.05    5071  866.51  5077.9  868.87
  5085.2  864.35  5106.2  872.75  5113.5  869.75  5127.7  870.06  5134.5  873.29
  5141.7  874.24    5198  876.72  5311.4  886.82  5396.4  889.35  5458.2  893.94
#Mann= 3 ,-1 , 0
    4602     .12       0  4998.1     .07       0  5002.1     .12       0
Bank Sta=4998.1,5002.1
XS Rating Curve= 0 ,0
Exp/Cntr=0.3,0.1

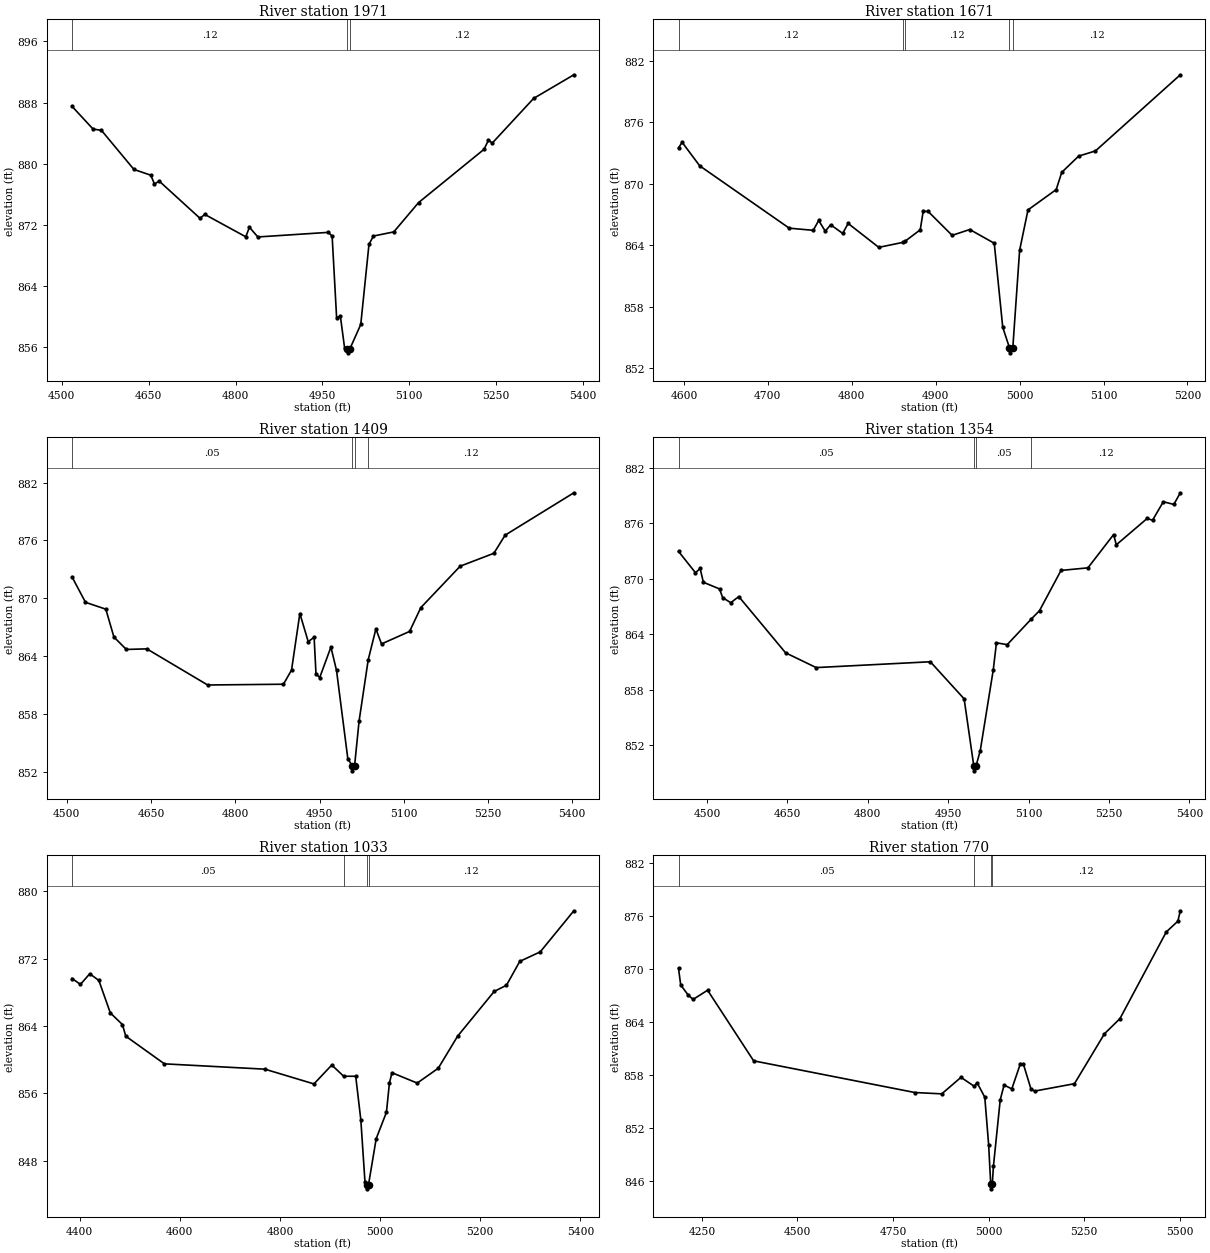
Type RM Length L Ch R = 1 ,1971    ,300,300,300
BEGIN DESCRIPTION:
UDS St 29 5.0
END DESCRIPTION:
XS GIS Cut Line= 3
      2252797.44       7187668.7      2253106.77      7187430.83
      2253417.23      7187069.89
#Sta/Elev= 30
  4517.8   887.5    4554  884.54  4568.5  884.37  4624.6  879.26  4653.7  878.51
    4660  877.36  4668.2  877.74  4738.8  872.87  4746.8  873.39  4817.7  870.46
    4824  871.71  4838.5  870.44  4960.2  871.04  4966.8  870.54  4974.5   859.9
    4981  860.09  4988.2  855.99  4993.3   855.8  4993.6   855.3  4997.3   855.8
  5016.2  859.01  5030.4  869.48  5038.1  870.56  5073.2   871.1    5116  874.93
    5229  881.89  5236.7  883.09  5243.3  882.71  5314.6  888.54  5384.1  891.63
#Mann= 3 ,-1 , 0
  4517.8     .12       0  4993.3     .07       0  4997.3     .12       0
Bank Sta=4993.3,4997.3
XS Rating Curve= 0 ,0
Exp/Cntr=0.3,0.1

Type RM Length L Ch R = 1 ,1671    ,262,262,262
BEGIN DESCRIPTION:
UDS St 29 4.0
END DESCRIPTION:
XS GIS Cut Line= 3
      2253213.96      7187710.51      2253439.34      7187522.04
      2253468.18      7187219.31
#Sta/Elev= 30
  4593.6   873.5  4597.9  874.04  4618.8  871.75  4725.5  865.67  4754.1  865.46
  4760.6  866.42  4768.4  865.38  4774.9     866  4789.2  865.16  4795.7  866.13
  4832.2   863.8  4861.2  864.29  4863.4  864.39  4881.6  865.51  4885.1  867.31
  4890.9  867.31  4919.6  864.97  4940.6  865.54  4969.8   864.2  4979.9  856.01
  4987.9  854.02  4988.2  853.52  4991.9  854.02    5000  863.51    5010  867.45
  5043.6  869.43  5050.2  871.11  5070.3  872.69  5090.4   873.2  5191.5  880.62
#Mann= 5 ,-1 , 0
  4593.6     .12       0  4861.2     .05       0  4863.4     .12       0
  4987.9     .07       0  4991.9     .12       0
#XS Ineff= 2 , 0
       0  4885.1  867.31               0
Permanent Ineff=
       F       F
Bank Sta=4987.9,4991.9
XS Rating Curve= 0 ,0
Exp/Cntr=0.3,0.1

Type RM Length L Ch R = 1 ,1409    ,55,55,55
BEGIN DESCRIPTION:
UDS St 29 3.1
END DESCRIPTION:
XS GIS Cut Line= 3
      2253339.58      7187765.27      2253693.94       7187519.9
      2253709.68      7187057.69
#Sta/Elev= 30
  4509.3   872.2  4533.2  869.57  4569.4  868.86  4583.8  865.97  4605.9  864.68
  4642.4  864.74  4750.7  860.99  4885.7  861.07  4900.1  862.54  4914.9  868.41
  4929.8  865.49  4940.3  865.94  4943.6  862.17  4950.2  861.75  4970.2  864.92
  4980.2   862.5  5000.3  853.35  5008.3  852.58  5008.5  852.08  5012.3  852.58
  5020.3  857.22  5036.6   863.6  5050.3  866.81  5060.3  865.25  5110.3  866.55
  5130.3  869.02  5200.4  873.32  5260.4  874.66  5280.4  876.54  5402.8  880.94
#Mann= 4 ,-1 , 0
  4509.3     .05       0  5008.3    .033       0  5012.3     .05       0
  5036.6     .12       0
#XS Ineff= 2 , 0
       0  4970.2  864.92               0
Permanent Ineff=
       F       F
Bank Sta=5008.3,5012.3
XS Rating Curve= 0 ,0
Exp/Cntr=0.3,0.1

Type RM Length L Ch R = 1 ,1354    ,321,321,321
BEGIN DESCRIPTION:
UDS St 29 3.0
END DESCRIPTION:
XS GIS Cut Line= 3
       2253362.7      7187808.81      2253742.65       7187555.9
      2253784.67      7187078.38
#Sta/Elev= 30
  4447.1  872.97  4478.7  870.66  4487.4  871.12  4493.4  869.63  4523.5  868.91
  4529.5  867.96  4544.5  867.42  4559.5  868.08  4646.7     862  4703.8   860.4
  4916.7  861.03  4979.7  857.02  4997.8  849.73  4998.1  849.23  5001.8  849.73
  5009.8  851.42    5034  860.14    5040  863.08    5060  862.88  5105.1  865.66
  5120.3  866.56  5160.4  870.91  5210.6  871.19  5258.5  874.79  5263.5  873.68
    5321  876.53  5331.1  876.34  5351.2  878.34  5370.8  878.05  5382.9  879.31
#Mann= 4 ,-1 , 0
  4447.1     .05       0  4997.8    .033       0  5001.8     .05       0
  5105.1     .12       0
Bank Sta=4997.8,5001.8
XS Rating Curve= 0 ,0
Exp/Cntr=0.3,0.1

Type RM Length L Ch R = 1 ,1033    ,263,263,263
BEGIN DESCRIPTION:
UDS St 29 2.0
END DESCRIPTION:
XS GIS Cut Line= 3
      2253484.69      7187808.16       2254001.9      7187683.68
      2254103.21       7187224.5
#Sta/Elev= 30
  4384.9  869.63  4401.6  868.93  4420.2  870.19  4438.4   869.4  4461.3  865.55
  4485.5  864.17  4492.2  862.79  4569.3  859.51  4769.9  858.88    4868  857.13
  4903.6  859.37  4927.3  858.04  4951.4  858.04  4961.6  852.89  4969.9  845.52
    4973  845.19  4973.3  844.69    4977  845.19  4992.3  850.64  5012.8  853.77
  5018.7  857.23  5023.8  858.46  5074.2  857.23  5116.3  858.99  5154.9  862.79
  5227.9  868.09  5252.5  868.83  5279.1  871.66    5320  872.79  5387.1  877.66
#Mann= 4 ,-1 , 0
  4384.9     .05       0  4927.3     .12       0    4973     .07       0
    4977     .12       0
Bank Sta=4973,4977
XS Rating Curve= 0 ,0
Exp/Cntr=0.3,0.1

Type RM Length L Ch R = 1 ,770     ,199,199,199
BEGIN DESCRIPTION:
UDS St 29 1.1
END DESCRIPTION:
XS GIS Cut Line= 3
      2253483.37      7187838.37      2254233.58      7187767.12
      2254154.34      7187213.55
#Sta/Elev= 30
  4188.8  870.05  4194.5  868.17  4214.5  867.01    4227  866.54  4264.8  867.58
  4385.3  859.58  4807.2  855.99  4877.5  855.84  4927.7  857.71  4962.7  856.69
  4969.8  857.11    4990  855.46  5000.1  850.08  5005.6  845.58  5005.8  845.08
  5009.6  845.58  5012.6  847.63  5030.4  855.16  5040.5  856.84  5060.7   856.4
  5083.3  859.27    5091  859.21  5111.2  856.34  5121.3  856.16  5224.6  856.99
  5303.2  862.65  5343.6  864.36  5464.8  874.18  5495.1   875.4  5501.6  876.58
#Mann= 4 ,-1 , 0
  4188.8     .05       0  4962.7     .12       0  5005.6     .07       0
  5009.6     .12       0
Bank Sta=5005.6,5009.6
XS Rating Curve= 0 ,0
Exp/Cntr=0.3,0.1

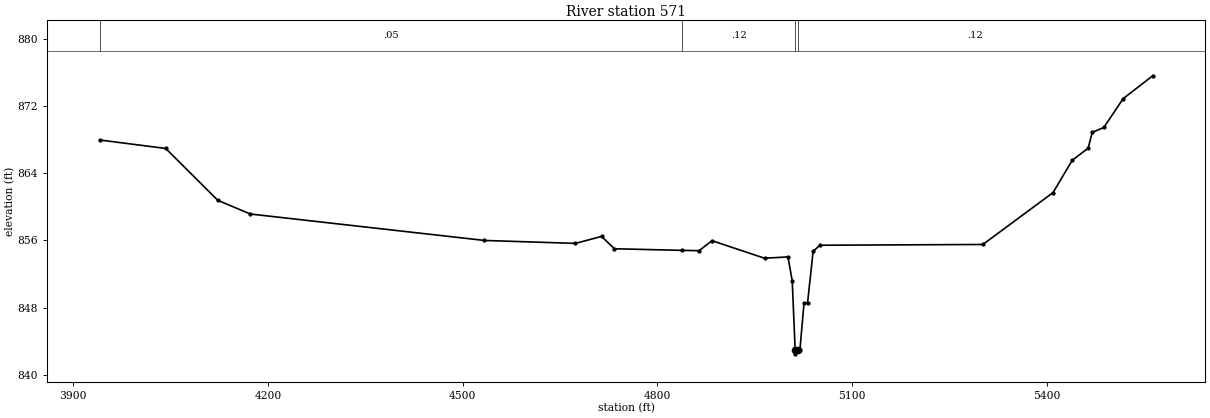
Type RM Length L Ch R = 1 ,571     ,0,0,0
BEGIN DESCRIPTION:
UDS St 29 1.0
END DESCRIPTION:
XS GIS Cut Line= 4
      2253487.28      7187854.92      2254454.89      7187791.68
      2254418.67      7187692.78      2254216.92      7187183.38
#Sta/Elev= 30
  3940.6  867.97  4042.5  866.96  4122.7  860.78  4172.8  859.15  4533.6     856
  4673.9  855.65    4714  856.48    4734  855.01    4838  854.82  4864.3  854.78
  4884.3  855.97  4965.3  853.88  5001.3  854.04  5007.9  851.19  5012.4  842.99
  5012.7  842.49  5016.4  842.99  5019.8  842.99  5026.1  848.57  5031.5  848.54
  5040.1   854.7  5050.5  855.43  5301.7  855.52  5409.8   861.7  5439.5  865.56
  5463.9  866.99  5470.3  868.87  5488.2  869.47  5517.9   872.9  5563.5  875.62
#Mann= 4 ,-1 , 0
  3940.6     .05       0    4838     .12       0  5012.4     .07       0
  5016.4     .12       0
Bank Sta=5012.4,5016.4
XS Rating Curve= 0 ,0
Exp/Cntr=0.3,0.1

Chan Stop Cuts=-1
Use User Specified Reach Order=0
Composite Channel Slope=5