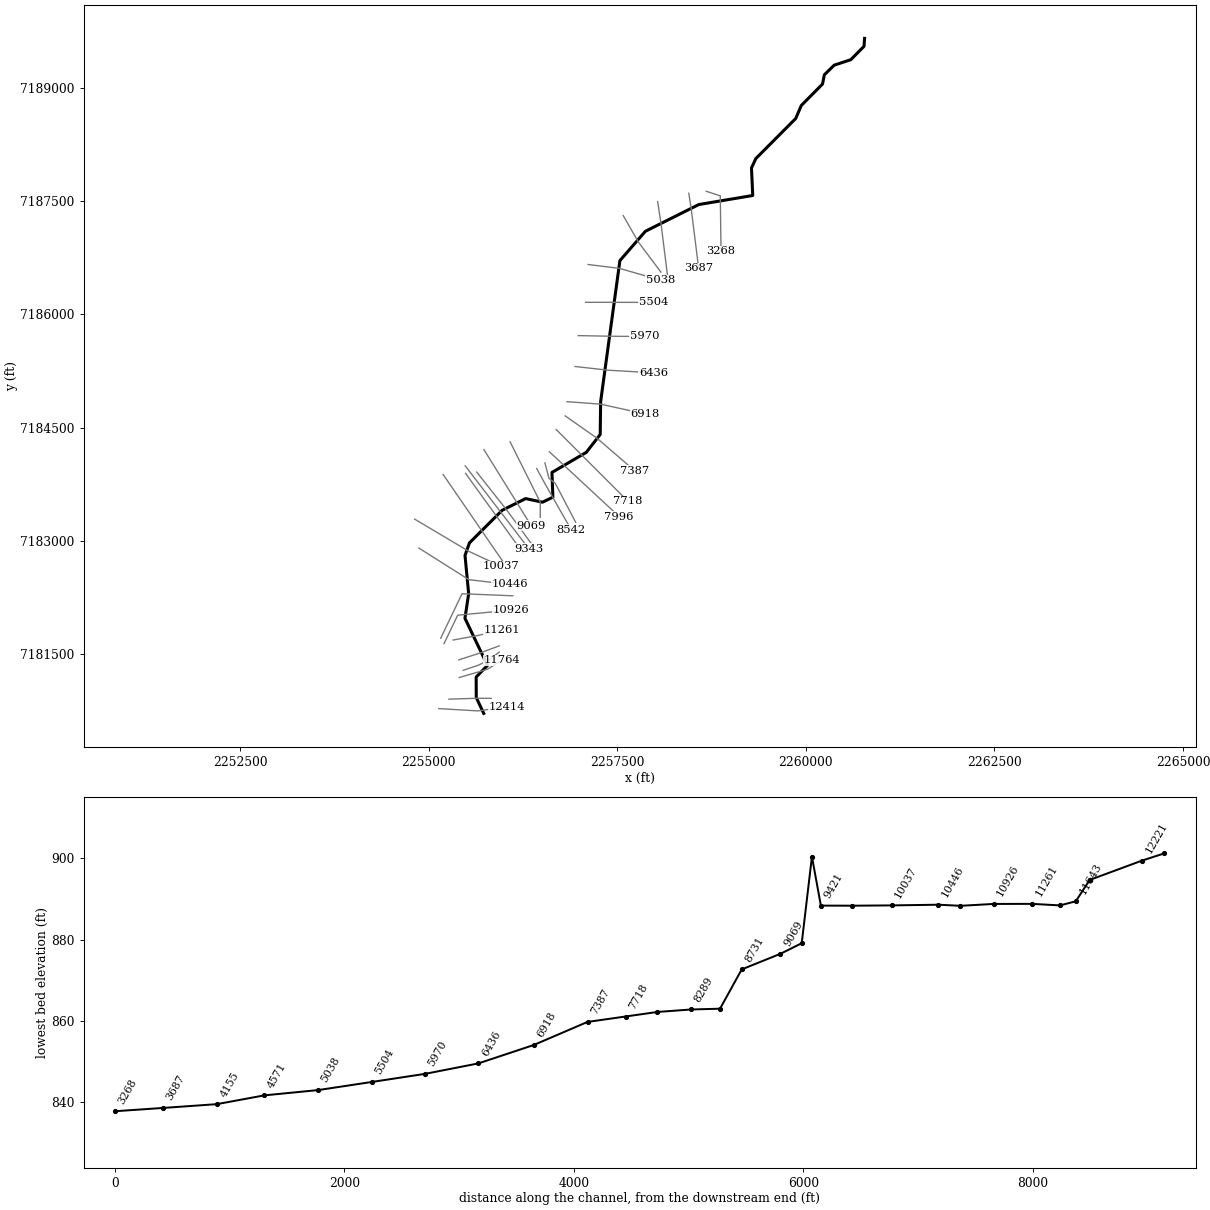
--- UDS St 30.prj (project) ---

Proj Title=UDS St 30 Base Level Engineering
Current Plan=p01
Default Exp/Contr=0.3,0.1
English Units
Geom File=g01
Flow File=f01
Plan File=p01
Y Axis Title=Elevation
X Axis Title(PF)=Main Channel Distance
X Axis Title(XS)=Station
BEGIN DESCRIPTION:
UDS St 30
END DESCRIPTION:
DSS Export Rating Curves= 0
DSS Export Rating Curve Sorted= 0
DSS Export Volume Flow Curves= 0
DXF OffsetX= 0
DXF OffsetY= 0
DXF ScaleX= 1
DXF ScaleY= 10

--- UDS St 30.p01 (plan) ---

Plan Title=Multiple Run
Short Identifier=Multiple
Geom File=g01
Flow File=f01
Subcritical Flow
K Sum by GR= 0
Std Step Tol= 0.01
Critical Tol= 0.01
Num of Std Step Trials= 20
Max Error Tol= 0.3
Flow Tol Ratio= 0.001
Split Flow NTrial= 30
Split Flow Tol= 0.02
Split Flow Ratio= 0.02
Log Output Level= 0
Friction Slope Method= 1
Unsteady Friction Slope Method= 2
Unsteady Bridges Friction Slope Method= 1
Parabolic Critical Depth
Global Vel Dist=  1 , 1 , 1
Global Log Level= 0
CheckData=True
Encroach Param= -1, 0, 0, 0
BEGIN DESCRIPTION:
Multiple Run
END DESCRIPTION:

--- UDS St 30.f01 (steady flow) ---

Flow Title=Multiple
Number of Profiles=7
Profile Names=10-year,25-year,50-year,1pct_min,100-year,1pct_plu,500-year
River Rch & RM= UDS St 30,Reach-1,12414
     655     912    1129     694    1385    2764    2091
River Rch & RM= UDS St 30,Reach-1,9696
    1065    1520    1911    1192    2378    4745    3695
River Rch & RM= UDS St 30,Reach-1,9254
    1220    1750    2206    1379    2751    5490    4293
River Rch & RM= UDS St 30,Reach-1,2769
    1546    2242    2848    1792    3575    7134    5655
Boundary for River Rch & Prof#=UDS St 30,Reach-1,1
Up Type=0
Dn Type=3
Dn Slope=0.005
Boundary for River Rch & Prof#=UDS St 30,Reach-1,2
Up Type=0
Dn Type=3
Dn Slope=0.005
Boundary for River Rch & Prof#=UDS St 30,Reach-1,3
Up Type=0
Dn Type=3
Dn Slope=0.005
Boundary for River Rch & Prof#=UDS St 30,Reach-1,4
Up Type=0
Dn Type=3
Dn Slope=0.005
Boundary for River Rch & Prof#=UDS St 30,Reach-1,5
Up Type=0
Dn Type=3
Dn Slope=0.005
Boundary for River Rch & Prof#=UDS St 30,Reach-1,6
Up Type=0
Dn Type=3
Dn Slope=0.005
Boundary for River Rch & Prof#=UDS St 30,Reach-1,7
Up Type=0
Dn Type=3
Dn Slope=0.005

--- UDS St 30.g01 (geometry) ---

Geom Title=Existing Conditions
Program Version=4.10

River Reach=UDS St 30       ,Reach-1
Reach XY= 30
        2255729.        7180710.      2255630.21      7180919.59
      2255629.04      7181191.89      2255778.85      7181345.83
       2255480.2       7181970.5      2255529.44      7182296.18
      2255481.12      7182804.12      2255539.51      7182969.79
      2255972.87      7183402.12      2256284.93      7183557.77
      2256508.83       7183509.7      2256646.15      7183576.45
      2256634.17      7183904.56      2257088.81      7184170.51
      2257273.53      7184407.55      2257279.52      7184844.78
      2257534.47      7186712.45      2257872.66      7187101.98
      2258580.58      7187456.17      2259296.14      7187576.45
      2259279.18      7187941.73      2259337.14      7188066.06
      2259865.38      7188596.79      2259939.76       7188769.7
      2260221.14      7189053.83      2260245.46      7189176.75
      2260376.57      7189304.48      2260595.68      7189376.64
      2260771.26      7189553.78        2260779.        7189660.

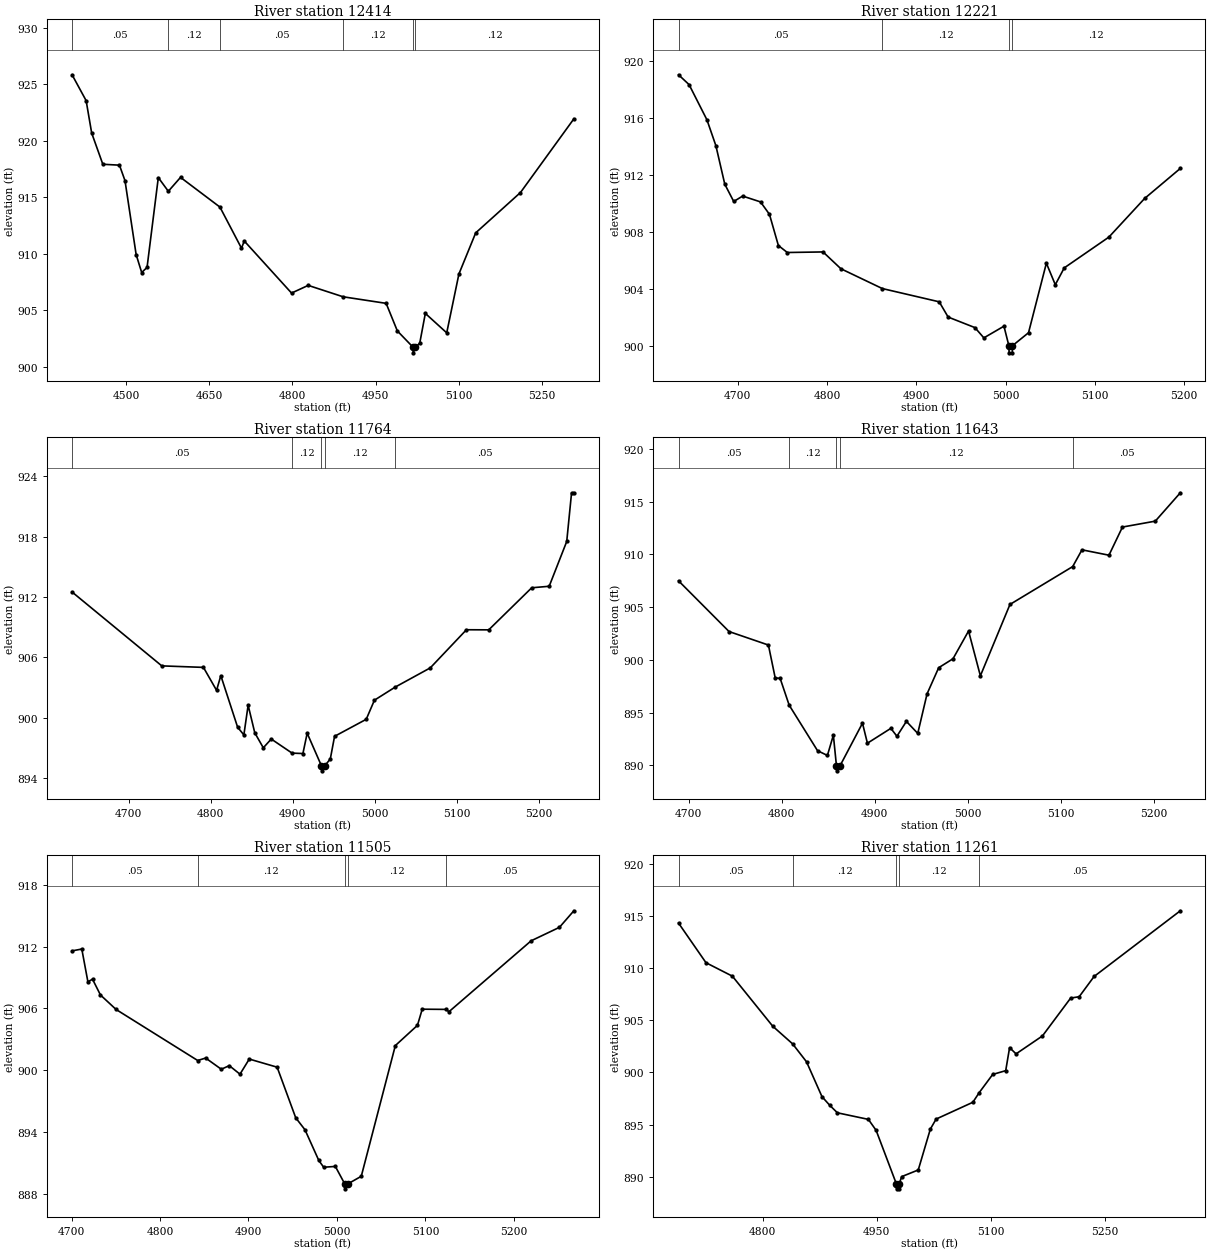
Type RM Length L Ch R = 1 ,12414   ,193,193,193
BEGIN DESCRIPTION:
UDS St 30 24.0
END DESCRIPTION:
XS GIS Cut Line= 3
      2255133.64       7180773.2      2255653.38      7180742.69
      2256034.32       7180796.8
#Sta/Elev= 30
  4402.4  925.86  4427.8  923.57  4437.8   920.7  4457.9  917.94  4487.9  917.86
  4497.9  916.49    4518  909.95    4528  908.36  4537.7  908.81    4558  916.76
  4576.1  915.55  4598.1  916.78  4669.2  914.15  4708.1  910.51  4713.1  911.15
  4798.4  906.54  4828.5  907.22  4891.5  906.21  4969.1  905.63  4989.3  903.19
  5017.6  901.75  5017.9  901.25  5021.6  901.75  5029.7   902.1  5039.8  904.74
  5078.4  903.02  5100.4  908.23  5130.7  911.87  5211.5  915.44  5307.8  921.96
#Mann= 6 ,-1 , 0
  4402.4     .05       0  4576.1     .12       0  4669.2     .05       0
  4891.5     .12       0  5017.6     .07       0  5021.6     .12       0
Bank Sta=5017.6,5021.6
XS Rating Curve= 0 ,0
Exp/Cntr=0.3,0.1

Type RM Length L Ch R = 1 ,12221   ,457,457,457
BEGIN DESCRIPTION:
UDS St 30 23.0
END DESCRIPTION:
XS GIS Cut Line= 3
      2255267.26      7180898.36        2255629.        7180910.
      2255828.97        7180910.
#Sta/Elev= 30
  4633.8     919  4645.6  918.31  4665.6  915.84  4675.6  914.03  4685.6  911.32
  4695.6  910.11  4705.6  910.49  4725.6  910.08  4735.6  909.21  4745.6  907.02
  4755.6  906.53  4795.6  906.57  4815.6  905.39    4862     904  4925.7  903.07
  4935.7     902  4965.7  901.26  4975.7  900.54  4998.2  901.36  5003.7  899.99
    5004  899.49  5007.5  899.49  5007.7  899.99  5025.7   900.9  5045.7  905.78
  5055.7  904.27  5065.7  905.45  5115.7  907.61  5155.7  910.32  5195.7  912.43
#Mann= 4 ,-1 , 0
  4633.8     .05       0    4862     .12       0  5003.7     .07       0
  5007.7     .12       0
Bank Sta=5003.7,5007.7
XS Rating Curve= 0 ,0
Exp/Cntr=0.3,0.1

Type RM Length L Ch R = 1 ,11764   ,121,121,121
BEGIN DESCRIPTION:
UDS St 30 22.0
END DESCRIPTION:
XS GIS Cut Line= 3
      2255405.26      7181185.29      2255774.84       7181293.8
      2255968.84      7181411.12
#Sta/Elev= 30
  4630.8  912.49  4740.2  905.15    4791     905    4807  902.72  4812.2  904.18
  4832.7  899.05  4840.3  898.29  4845.5  901.24  4853.6   898.5    4864  897.01
  4873.7  897.88  4899.1  896.48  4912.3  896.44  4917.5  898.46  4934.9  895.22
  4935.2  894.72  4938.9  895.22  4945.7   895.9  4950.9  898.15  4989.5  899.84
  4999.5  901.74    5025  903.05  5067.6  904.95  5111.7  908.74  5138.9  908.73
  5191.3  912.91  5212.6  913.06    5234  917.51  5239.9  922.35  5242.7  922.35
#Mann= 5 ,-1 , 0
  4630.8     .05       0  4899.1     .12       0  4934.9     .07       0
  4938.9     .12       0    5025     .05       0
Bank Sta=4934.9,4938.9
XS Rating Curve= 0 ,0
Exp/Cntr=0.3,0.1

Type RM Length L Ch R = 1 ,11643   ,138,138,138
BEGIN DESCRIPTION:
UDS St 30 21.1
END DESCRIPTION:
XS GIS Cut Line= 4
      2255457.64      7181280.65      2255668.05      7181352.79
      2255803.12      7181421.33      2255934.01      7181522.45
#Sta/Elev= 30
  4689.2  907.49  4743.5  902.68  4785.8   901.4  4793.1  898.28  4798.4  898.24
  4808.1   895.7  4838.6  891.38  4849.2  890.93  4855.6  892.85  4858.9  889.97
  4859.2  889.47  4862.9  889.97  4886.9  893.99  4892.2  892.09  4917.4   893.5
  4923.9  892.75  4934.1  894.16  4946.3  893.02  4956.3  896.77  4968.8  899.25
  4984.2   900.1  5000.9  902.73  5013.6  898.48  5045.4  905.25  5112.8  908.84
  5122.8  910.43  5151.8  909.92  5166.3  912.59  5201.6  913.15  5228.5  915.84
#Mann= 5 ,-1 , 0
  4689.2     .05       0  4808.1     .12       0  4858.9     .07       0
  4862.9     .12       0  5112.8     .05       0
Bank Sta=4858.9,4862.9
XS Rating Curve= 0 ,0
Exp/Cntr=0.3,0.1

Type RM Length L Ch R = 1 ,11505   ,244,244,244
BEGIN DESCRIPTION:
UDS St 30 21.0
END DESCRIPTION:
XS GIS Cut Line= 3
       2255398.5      7181419.01        2255679.        7181510.
      2255934.25      7181604.89
#Sta/Elev= 30
  4700.6   911.6  4711.6  911.78  4718.5  908.59  4723.7  908.85  4732.7  907.31
  4750.4   905.9  4842.6  900.94  4851.6  901.18  4869.3  900.09  4878.3  900.44
  4890.4  899.61  4900.9  901.08  4932.4  900.29  4953.4  895.37  4963.9   894.2
  4979.5  891.22    4985  890.56  4998.2  890.64  5008.7  888.96  5008.9  888.46
  5012.7  888.96  5027.5  889.68    5066  902.39    5091  904.36  5096.4  905.93
    5123  905.91  5126.7  905.69  5219.5  912.58  5251.5  913.89  5267.8   915.5
#Mann= 5 ,-1 , 0
  4700.6     .05       0  4842.6     .12       0  5008.7     .07       0
  5012.7     .12       0    5123     .05       0
Bank Sta=5008.7,5012.7
XS Rating Curve= 0 ,0
Exp/Cntr=0.3,0.1

Type RM Length L Ch R = 1 ,11261   ,335,335,335
BEGIN DESCRIPTION:
UDS St 30 20.0
END DESCRIPTION:
XS GIS Cut Line= 3
       2255323.5       7181682.4      2255633.54      7181739.28
      2255969.65      7181815.25
#Sta/Elev= 30
  4689.3  914.32  4725.4  910.52  4760.1  909.23  4813.2  904.43  4839.3  902.74
  4857.6  901.02  4877.9  897.68  4888.1  896.85  4898.2  896.13  4938.9   895.5
  4949.1  894.45  4975.6  889.34  4975.9  888.84  4979.4  888.84  4979.6  889.34
  4982.7  890.01  5004.5  890.65  5020.4  894.57    5028  895.53  5076.3  897.14
  5084.7  898.07  5102.4  899.81  5119.5  900.17  5124.6  902.38  5133.1  901.78
  5167.8   903.5  5204.9  907.13  5216.1  907.26  5235.7   909.2  5349.1   915.5
#Mann= 5 ,-1 , 0
  4689.3     .05       0  4839.3     .12       0  4975.6     .07       0
  4979.6     .12       0  5084.7     .05       0
Bank Sta=4975.6,4979.6
XS Rating Curve= 0 ,0
Exp/Cntr=0.3,0.1

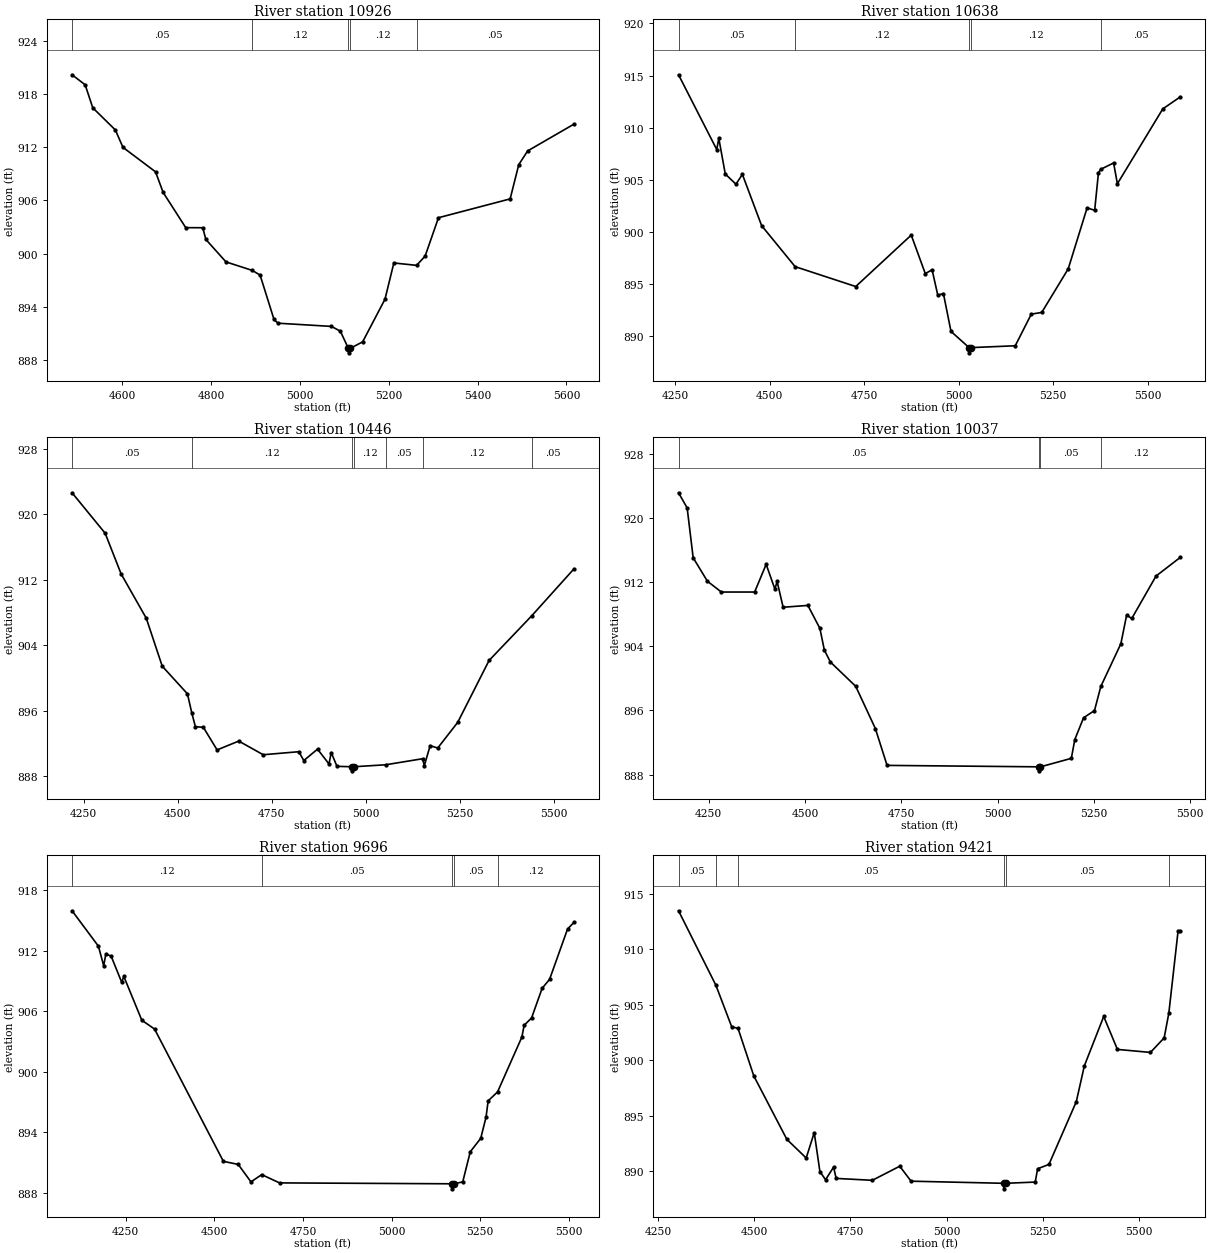
Type RM Length L Ch R = 1 ,10926   ,288,288,288
BEGIN DESCRIPTION:
UDS St 30 19.0
END DESCRIPTION:
XS GIS Cut Line= 3
      2255203.04      7181634.63      2255384.11      7182011.93
      2256092.55      7182078.91
#Sta/Elev= 30
  4486.5  920.16    4516  919.03  4533.1  916.44    4584  913.94  4601.1  911.98
  4674.5  909.22  4691.6   906.9  4742.5  902.93  4780.8  902.92  4787.8   901.6
  4833.1  899.07  4892.3  898.11    4910  897.58  4941.3  892.58  4950.1  892.16
  5070.6   891.8  5090.7  891.26  5108.8  889.32  5109.1  888.82  5112.8  889.32
  5140.9  890.06  5191.2  894.86  5211.2  898.95  5262.4  898.68  5281.6  899.72
  5311.7  904.05  5473.1  906.17  5492.5  910.03  5512.6  911.58  5616.6  914.59
#Mann= 5 ,-1 , 0
  4486.5     .05       0  4892.3     .12       0  5108.8     .07       0
  5112.8     .12       0  5262.4     .05       0
Bank Sta=5108.8,5112.8
XS Rating Curve= 0 ,0
Exp/Cntr=0.3,0.1

Type RM Length L Ch R = 1 ,10638   ,192,192,192
BEGIN DESCRIPTION:
UDS St 30 18.1
END DESCRIPTION:
XS GIS Cut Line= 3
      2255158.78       7181706.9      2255441.81      7182296.32
      2256115.49       7182268.8
#Sta/Elev= 30
  4258.5  915.07  4359.6  907.89  4365.1  908.96  4382.2  905.54  4410.4  904.56
  4427.5   905.5  4478.4  900.58  4567.1  896.64  4727.5  894.73  4874.4  899.67
  4911.6  895.97  4929.6  896.34  4944.6  893.91  4959.6  894.05  4979.6  890.42
  5027.6  888.86  5027.9  888.36  5031.6  888.86  5149.7  889.04  5192.2  892.08
  5219.8  892.24  5289.9  896.43  5339.9  902.29  5359.9  902.05  5369.9  905.66
    5376  905.99    5410   906.6    5420   904.6  5540.1  911.79  5586.6  912.95
#Mann= 5 ,-1 , 0
  4258.5     .05       0  4567.1     .12       0  5027.6     .07       0
  5031.6     .12       0    5376     .05       0
Bank Sta=5027.6,5031.6
XS Rating Curve= 0 ,0
Exp/Cntr=0.3,0.1

Type RM Length L Ch R = 1 ,10446   ,409,409,409
BEGIN DESCRIPTION:
UDS St 30 18.0
END DESCRIPTION:
XS GIS Cut Line= 3
      2254869.15      7182901.72      2255532.82      7182482.51
      2256078.66      7182419.04
#Sta/Elev= 30
  4219.3  922.64  4307.3  917.69  4349.7  912.72  4416.7  907.29  4459.1  901.43
  4526.1  898.05  4537.8  895.69  4547.3  894.03  4568.5  893.95    4605  891.19
  4662.6  892.27  4727.7   890.6  4822.3  890.97  4835.6  889.89  4872.1  891.28
  4902.6  889.47  4908.5  890.87  4923.8  889.18  4964.2  889.13  4964.4  888.63
  4968.2  889.13  5053.1  889.37  5151.4  890.11  5156.2  889.27  5171.6  891.71
  5191.7  891.42  5244.8  894.55  5328.3  902.13  5442.3  907.62  5553.8  913.32
#Mann= 7 ,-1 , 0
  4219.3     .05       0  4537.8     .12       0  4964.2     .07       0
  4968.2     .12       0  5053.1     .05       0  5151.4     .12       0
  5442.3     .05       0
Bank Sta=4964.2,4968.2
XS Rating Curve= 0 ,0
Exp/Cntr=0.3,0.1

Type RM Length L Ch R = 1 ,10037   ,341,341,341
BEGIN DESCRIPTION:
UDS St 30 17.0
END DESCRIPTION:
XS GIS Cut Line= 3
      2254813.39      7183285.64        2255529.        7182860.
      2255955.34       7182660.1
#Sta/Elev= 30
  4171.4  923.17  4193.8  921.28  4209.4  915.06  4246.4  912.13  4282.6  910.78
  4369.1  910.78    4399  914.24  4421.7  911.15  4427.5   912.1  4443.1  908.88
  4507.4  909.11  4538.6  906.24  4550.2  903.53  4565.8  902.05  4631.7  899.01
  4682.7  893.74  4713.1  889.14  5107.5  888.96  5107.7  888.46  5111.5  888.96
  5191.8  890.02  5200.8  892.37  5223.6  895.09  5251.9  895.98  5268.4     899
  5320.4  904.32  5335.4  907.89  5348.8  907.48  5411.7  912.77  5474.9  915.11
#Mann= 4 ,-1 , 0
  4171.4     .05       0  5107.5    .033       0  5111.5     .05       0
  5268.4     .12       0
Bank Sta=5107.5,5111.5
XS Rating Curve= 0 ,0
Exp/Cntr=0.3,0.1

Type RM Length L Ch R = 1 ,9696    ,275,275,275
BEGIN DESCRIPTION:
UDS St 30 16.1
END DESCRIPTION:
XS GIS Cut Line= 2
      2255191.72      7183875.97      2255993.25      7182709.15
#Sta/Elev= 30
  4098.7  915.97    4173  912.46  4187.9  910.52    4194  911.68  4208.9  911.47
  4238.7  908.88  4244.7  909.46  4295.5  905.11  4331.4  904.24  4525.5  891.12
  4567.5  890.81  4603.4  889.08  4633.7   889.8  4683.9  888.98  5170.9  888.89
  5171.7  888.39  5176.2  888.89  5200.8  889.08  5222.1  892.07  5251.6   893.4
  5266.5  895.49  5272.5  897.12    5299     898  5367.7  903.45    5374  904.61
    5395  905.34  5424.8  908.28  5445.8  909.17  5496.5  914.16  5514.3  914.81
#Mann= 5 ,-1 , 0
  4098.7     .12       0  4633.7     .05       0  5170.9    .033       0
  5176.2     .05       0    5299     .12       0
Bank Sta=5170.9,5176.2
XS Rating Curve= 0 ,0
Exp/Cntr=0.3,0.1

Type RM Length L Ch R = 1 ,9421    ,78,78,78
BEGIN DESCRIPTION:
UDS St 30 16.0
END DESCRIPTION:
XS GIS Cut Line= 3
      2255488.48      7183891.97      2255895.63      7183327.99
        2256252.      7182835.61
#Sta/Elev= 30
  4303.5  913.48  4400.5  906.77  4441.6  903.02    4458  902.88    4499  898.59
  4584.9  892.87  4635.1  891.19    4656  893.48  4670.7  889.97  4685.4  889.23
  4706.3  890.37  4712.9  889.35  4806.9  889.18  4878.1  890.45  4907.5   889.1
  5147.6  888.91  5148.4  888.41  5153.1  888.91    5230  889.02  5236.2  890.22
  5265.6  890.61  5336.7  896.27  5357.6   899.5  5407.9  903.95  5443.5  900.98
  5529.3  900.71  5564.9  902.02    5577  904.24  5601.1  911.67  5606.9  911.67
#Mann= 6 ,-1 , 0
  4303.5     .05       0  4400.5     .12       0    4458     .05       0
  5147.6    .033       0  5153.1     .05       0    5577     .12       0
Bank Sta=5147.6,5153.1
XS Rating Curve= 0 ,0
Exp/Cntr=0.3,0.1

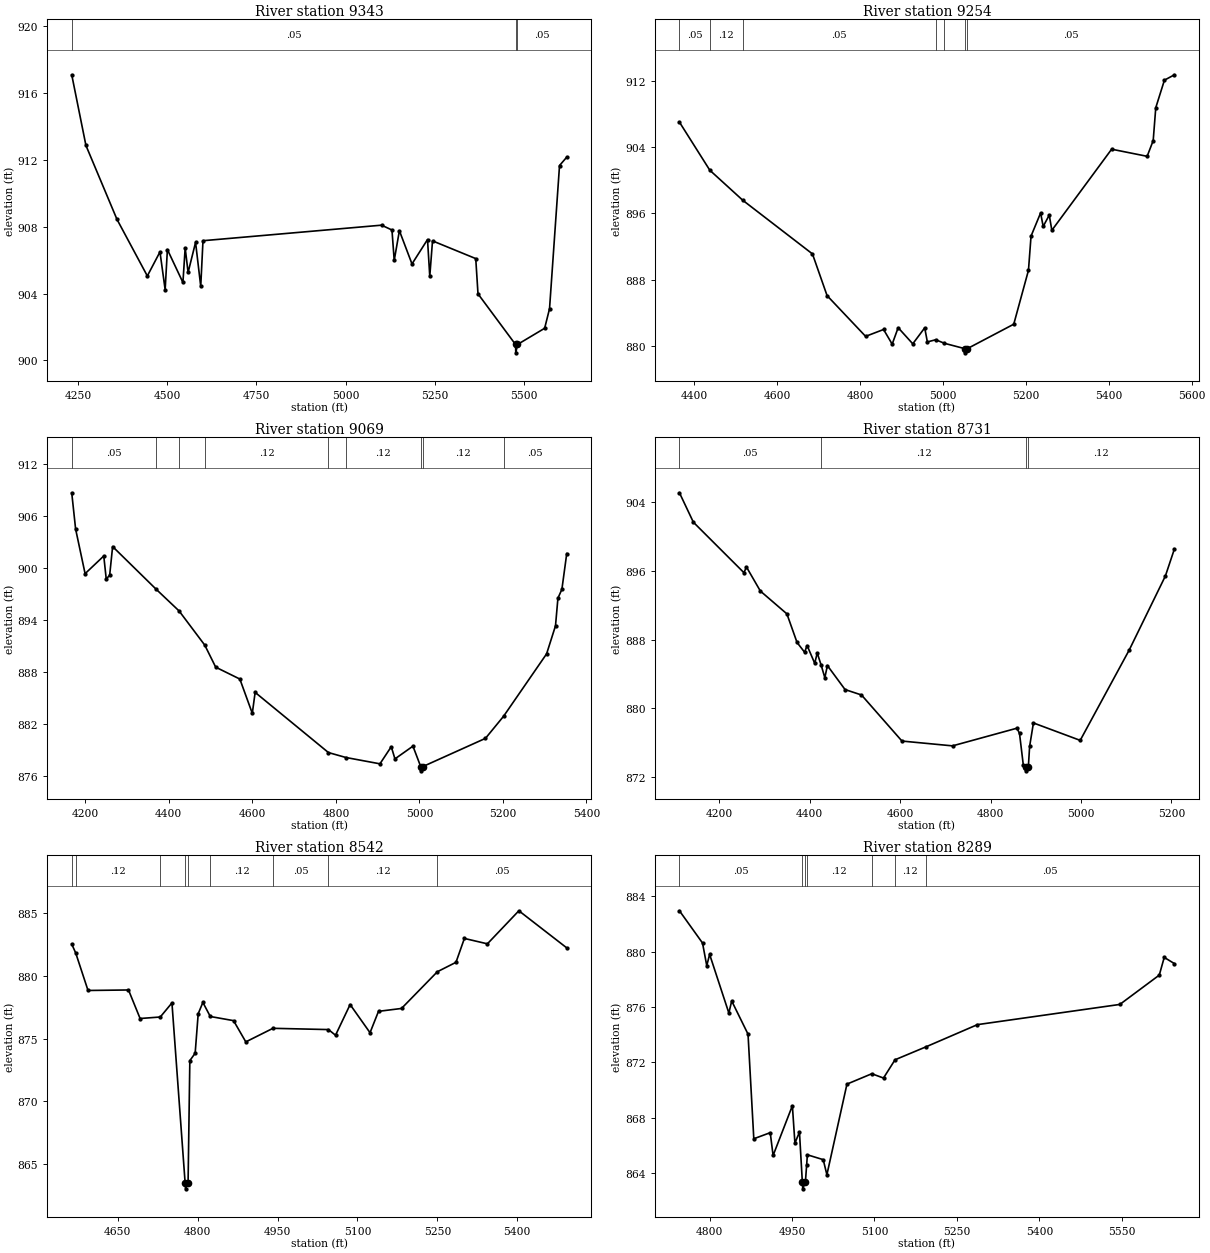
Type RM Length L Ch R = 1 ,9343    ,89,89,89
BEGIN DESCRIPTION:
UDS St 30 15.1
END DESCRIPTION:
XS GIS Cut Line= 2
      2255483.89      7183991.59      2256328.46      7182891.75
#Sta/Elev= 30
  4232.6  917.09  4272.4  912.86  4359.3  908.44  4444.4  905.05  4479.8  906.49
  4494.3  904.23  4500.6  906.63  4544.1  904.66  4550.4  906.73  4558.6  905.26
  4579.5  907.06    4594  904.43  4600.3  907.16  5100.6  908.09  5129.7   907.8
    5136  905.98  5150.5  907.76  5185.8  905.77  5229.3  907.23  5235.6  905.03
  5243.3  907.15  5364.4  906.09  5370.7  903.98  5475.8  900.95  5476.6  900.45
  5481.3  900.95  5557.4  901.92  5571.1  903.09  5599.1  911.66  5619.3  912.16
#Mann= 3 ,-1 , 0
  4232.6     .05       0  5475.8    .033       0  5481.3     .05       0
Bank Sta=5475.8,5481.3
XS Rating Curve= 0 ,0
Exp/Cntr=0.3,0.1

Type RM Length L Ch R = 1 ,9254    ,185,185,185
BEGIN DESCRIPTION:
UDS St 30 15.0
END DESCRIPTION:
XS GIS Cut Line= 3
      2255636.52      7183908.88      2256032.21      7183408.43
      2256361.31      7182959.52
#Sta/Elev= 30
  4363.9  907.03  4437.2  901.22    4517  897.58  4684.9  891.11  4720.2  886.07
  4813.2  881.15  4856.5  881.98  4877.3  880.21  4891.7   882.2    4927  880.25
  4955.8  882.18  4962.2  880.48  4982.4  880.74  5003.5  880.31  5052.9  879.66
  5053.7  879.16  5058.4  879.66  5170.7  882.62  5206.2  889.13  5212.4  893.26
  5235.5  896.06  5241.7  894.43  5256.4   895.8  5262.6  893.96  5406.9  903.76
  5492.6   902.9  5507.2   904.8  5513.4  908.77  5534.3   912.1  5558.5  912.75
#Mann= 7 ,-1 , 0
  4363.9     .05       0  4437.2     .12       0    4517     .05       0
  4982.4     .12       0  5003.5     .05       0  5052.9     .07       0
  5058.4     .05       0
Bank Sta=5052.9,5058.4
XS Rating Curve= 0 ,0
Exp/Cntr=0.3,0.1

Type RM Length L Ch R = 1 ,9069    ,338,338,338
BEGIN DESCRIPTION:
UDS St 30 14.1
END DESCRIPTION:
XS GIS Cut Line= 2
      2255731.69      7184207.16       2256357.3      7183200.64
#Sta/Elev= 30
  4167.6  908.67  4176.9  904.48  4199.6  899.33  4244.3  901.37  4250.2  898.72
  4258.4  899.14  4265.5  902.46  4369.3  897.55  4424.7  895.02  4486.2  891.07
  4512.3  888.53  4570.1  887.16  4599.9   883.2  4606.7  885.62  4782.2  878.67
  4824.1   878.1  4905.5  877.37  4932.6  879.35  4941.4  877.94  4984.5  879.41
    5003  877.06  5003.8  876.56  5008.5  877.06  5158.1  880.31  5201.3  882.85
  5304.5  890.07  5325.8  893.31  5331.6   896.5  5341.1  897.52  5352.7  901.65
#Mann= 9 ,-1 , 0
  4167.6     .05       0  4369.3     .12       0  4424.7     .05       0
  4486.2     .12       0  4782.2     .05       0  4824.1     .12       0
    5003     .07       0  5008.5     .12       0  5201.3     .05       0
Bank Sta=5003,5008.5
XS Rating Curve= 0 ,0
Exp/Cntr=0.3,0.1

Type RM Length L Ch R = 1 ,8731    ,189,189,189
BEGIN DESCRIPTION:
UDS St 30 14.0
END DESCRIPTION:
XS GIS Cut Line= 3
      2256078.99      7184310.03        2256479.        7183510.
        2256479.      7183309.96
#Sta/Elev= 30
  4112.1  905.12  4142.9  901.69  4254.7  895.81  4260.3  896.47    4291  893.67
  4349.7  891.01  4372.1  887.68  4388.8  886.54  4394.4  887.32  4411.2  885.25
  4416.8  886.45  4425.3  885.06  4433.6  883.57  4439.2  884.99  4478.3  882.19
  4514.6  881.56  4604.1  876.19  4715.9  875.63  4858.4  877.69    4864  877.08
  4872.4   873.4    4878  873.22  4878.8  872.72  4883.6  873.22  4886.4  875.58
  4894.8   878.3  4998.2  876.27  5106.6   886.8  5186.6  895.43  5206.6  898.59
#Mann= 4 ,-1 , 0
  4112.1     .05       0  4425.3     .12       0    4878     .07       0
  4883.6     .12       0
Bank Sta=4878,4883.6
XS Rating Curve= 0 ,0
Exp/Cntr=0.3,0.1

Type RM Length L Ch R = 1 ,8542    ,253,253,253
BEGIN DESCRIPTION:
UDS St 30 13.1
END DESCRIPTION:
XS GIS Cut Line= 3
       2256431.6      7183956.07      2256539.82      7183757.66
      2256888.21      7183146.37
#Sta/Elev= 30
  4563.4  882.52  4570.9  881.81    4594  878.83    4670  878.87  4691.8   876.6
  4729.7  876.72  4751.6  877.84  4776.3  863.55  4777.2  863.05  4781.9  863.55
  4785.2  873.25  4795.2  873.84  4800.9  876.98  4809.7  877.88  4823.6  876.76
  4867.3  876.43  4890.3  874.74  4941.3  875.82  5045.5  875.72  5058.8  875.27
  5086.2  877.71  5123.6  875.47  5139.5  877.17  5182.7   877.4    5250  880.32
    5285  881.07  5300.8  882.97    5344  882.54  5403.1  885.17    5493  882.22
#Mann= 9 ,-1 , 0
  4563.4     .05       0  4570.9     .12       0  4729.7     .05       0
  4776.3    .033       0  4781.9     .05       0  4823.6     .12       0
  4941.3     .05       0  5045.5     .12       0    5250     .05       0
Bank Sta=4776.3,4781.9
XS Rating Curve= 0 ,0
Exp/Cntr=0.3,0.1

Type RM Length L Ch R = 1 ,8289    ,293,293,293
BEGIN DESCRIPTION:
UDS St 30 13.0
END DESCRIPTION:
XS GIS Cut Line= 4
      2256540.66      7184030.65      2256594.79      7183825.98
      2256678.21       7183759.2      2256948.37      7183243.54
#Sta/Elev= 30
  4745.1  882.96  4787.1  880.63  4794.8  878.99    4800  879.81    4835  875.57
  4840.2  876.44  4869.9  874.04  4880.4  866.48  4910.3  866.92  4915.5  865.27
  4950.6  868.87  4955.2  866.17  4963.5  866.96  4968.7  863.36  4969.5  862.86
  4974.3  863.36  4976.6  864.61  4977.9  865.32  5006.7  864.97  5013.4  863.88
  5049.9  870.43  5095.1  871.18  5116.4  870.87  5137.4  872.19  5193.4  873.12
  5287.3  874.73  5546.4  876.19  5618.2  878.31  5627.2  879.59  5645.8  879.14
#Mann= 7 ,-1 , 0
  4745.1     .05       0  4968.7     .07       0  4974.3     .05       0
  4976.6     .12       0  5095.1     .05       0  5137.4     .12       0
  5193.4     .05       0
Bank Sta=4968.7,4974.3
XS Rating Curve= 0 ,0
Exp/Cntr=0.3,0.1

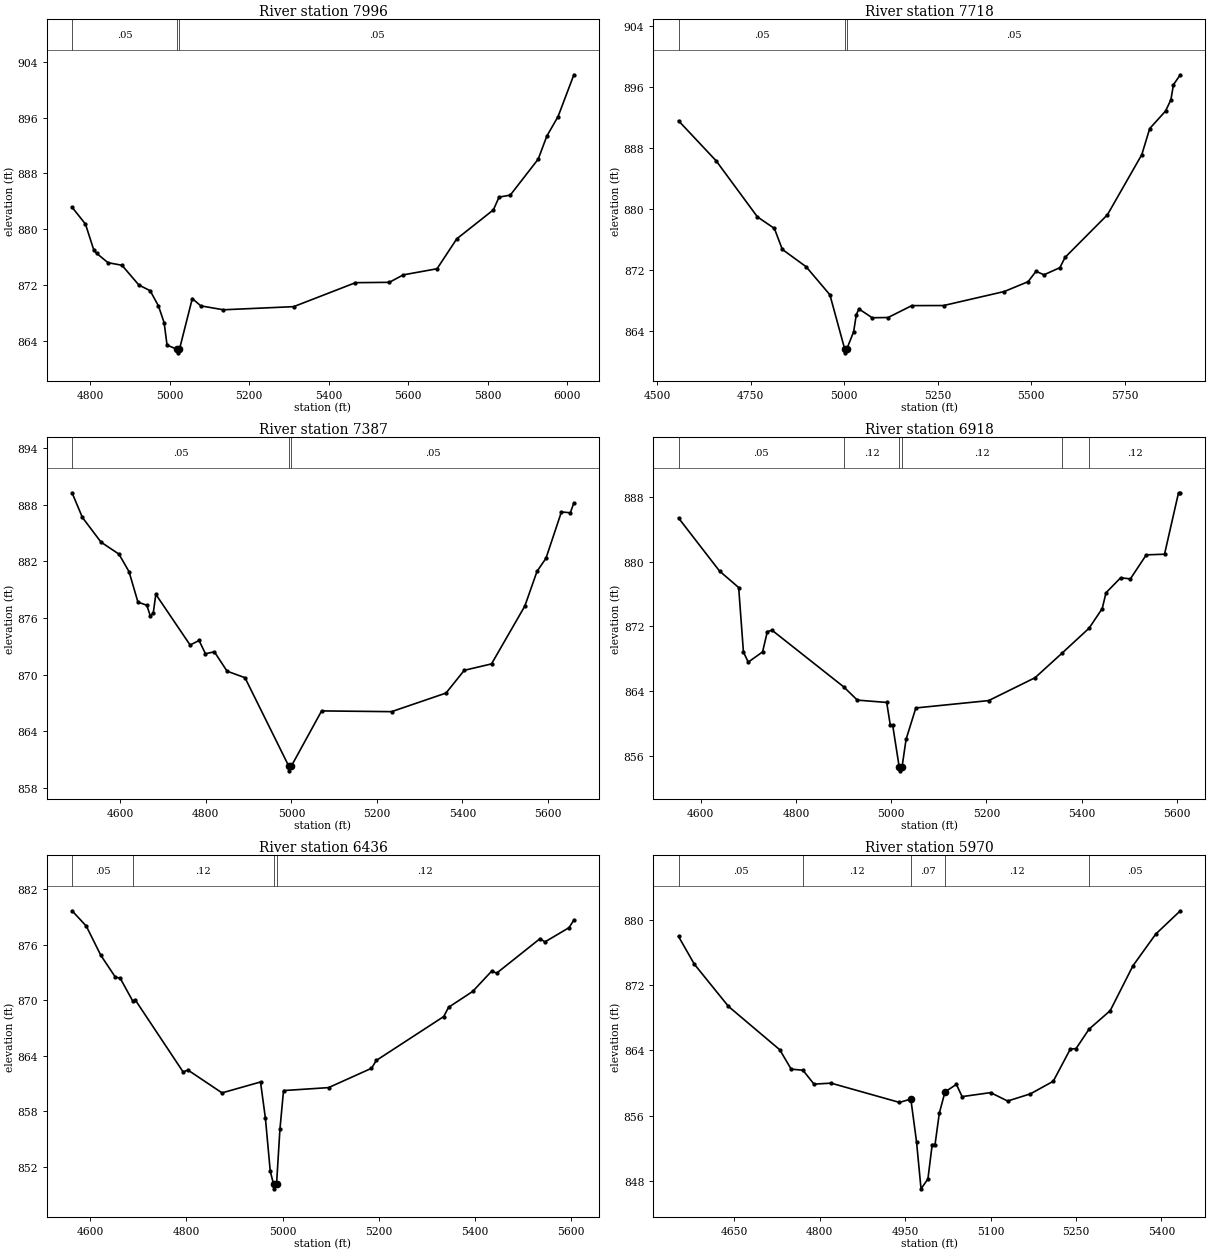
Type RM Length L Ch R = 1 ,7996    ,278,278,278
BEGIN DESCRIPTION:
UDS St 30 12.1
END DESCRIPTION:
XS GIS Cut Line= 2
      2256599.95      7184178.51      2257524.88      7183319.64
#Sta/Elev= 30
  4754.3  883.15    4788  880.73    4809     877  4816.3  876.52  4844.7  875.19
  4879.8  874.82  4922.4  871.98  4950.7  871.17  4971.7  868.97  4985.9  866.57
  4993.2  863.36  5018.8  862.75  5019.6  862.25  5024.4  862.75  5056.7  870.04
  5078.2  868.99  5134.9  868.43  5311.8  868.88  5467.2  872.32  5552.2  872.37
  5587.4  873.44  5672.4  874.32  5721.9  878.61  5814.1  882.77  5828.3   884.6
  5856.6  884.89  5926.9  890.06  5948.5  893.36  5976.8  896.17  6016.5  902.16
#Mann= 3 ,-1 , 0
  4754.3     .05       0  5018.8    .033       0  5024.4     .05       0
Bank Sta=5018.8,5024.4
XS Rating Curve= 0 ,0
Exp/Cntr=0.3,0.1

Type RM Length L Ch R = 1 ,7718    ,331,331,331
BEGIN DESCRIPTION:
UDS St 30 12.0
END DESCRIPTION:
XS GIS Cut Line= 3
       2256689.9       7184473.5      2256839.91      7184323.48
      2257639.11      7183524.27
#Sta/Elev= 30
  4556.7  891.55  4657.5  886.29  4767.8  878.95  4813.1  877.44  4834.3  874.69
    4898  872.42  4961.6  868.74  5001.2  861.63  5002.1  861.13  5006.8  861.63
  5025.2   863.9  5032.3  866.15  5039.4  866.88  5074.7  865.73  5117.2  865.76
  5180.8  867.32  5265.6  867.33  5428.3  869.17  5491.9  870.46  5513.1  871.82
  5534.3  871.36  5576.8  872.29  5590.9  873.65  5704.1  879.23    5796  887.11
  5817.2  890.53  5859.6  892.83  5873.8  894.29  5880.8  896.29  5899.1  897.58
#Mann= 3 ,-1 , 0
  4556.7     .05       0  5001.2    .033       0  5006.8     .05       0
Bank Sta=5001.2,5006.8
XS Rating Curve= 0 ,0
Exp/Cntr=0.3,0.1

Type RM Length L Ch R = 1 ,7387    ,469,469,469
BEGIN DESCRIPTION:
UDS St 30 11.0
END DESCRIPTION:
XS GIS Cut Line= 3
      2256809.23      7184654.32        2257229.        7184360.
      2257729.26      7183928.83
#Sta/Elev= 30
  4487.3  889.26  4511.4  886.65    4555  884.03  4596.9  882.76  4620.4  880.91
  4641.3  877.68  4662.2  877.34  4670.2   876.2    4677  876.49  4683.1   878.5
  4763.3  873.13  4784.2  873.61  4799.1  872.21    4820  872.41  4849.6  870.36
  4891.5  869.67  4993.9   860.3  4994.9   859.8  4999.9   860.3  5070.7  866.15
  5234.2  866.07  5361.5  868.04  5404.2  870.45  5467.9  871.13  5545.8  877.26
  5574.3  880.94  5595.2  882.32  5631.3  887.23  5652.2  887.14  5660.4  888.19
#Mann= 3 ,-1 , 0
  4487.3     .05       0  4993.9    .033       0  4999.9     .05       0
Bank Sta=4993.9,4999.9
XS Rating Curve= 0 ,0
Exp/Cntr=0.3,0.1

Type RM Length L Ch R = 1 ,6918    ,482,482,482
BEGIN DESCRIPTION:
UDS St 30 10.0
END DESCRIPTION:
XS GIS Cut Line= 3
      2256833.02      7184842.81        2257279.        7184810.
      2257871.41      7184679.01
#Sta/Elev= 30
  4553.2   885.4  4639.4  878.83  4679.5   876.8  4689.5  868.82  4699.6  867.57
  4729.7  868.83  4739.7  871.35  4749.7  871.51  4900.3   864.5  4928.7  862.87
  4990.4  862.58  4997.9  859.79  5002.9  859.79  5016.6  854.62  5017.6  854.12
  5022.7  854.62  5031.1  858.02  5051.6   861.9  5204.5  862.81    5302  865.64
  5358.5  868.67  5415.5  871.77  5443.1   874.2    5451  876.15  5481.7     878
  5502.2  877.87  5535.6  880.84  5573.9  880.92  5603.3  888.52  5607.1  888.52
#Mann= 6 ,-1 , 0
  4553.2     .05       0  4900.3     .12       0  5016.6     .07       0
  5022.7     .12       0  5358.5     .05       0  5415.5     .12       0
Bank Sta=5016.6,5022.7
XS Rating Curve= 0 ,0
Exp/Cntr=0.3,0.1

Type RM Length L Ch R = 1 ,6436    ,466,466,466
BEGIN DESCRIPTION:
UDS St 30 9.0
END DESCRIPTION:
XS GIS Cut Line= 3
      2256939.58      7185309.13        2257379.        7185260.
      2257979.05      7185225.43
#Sta/Elev= 30
  4562.2  879.68  4591.8  878.02    4622  874.86  4652.2   872.5  4662.2  872.39
  4688.8  869.87  4693.4  870.05    4793  862.25  4803.1  862.45    4874  859.98
    4954  861.16  4964.2  857.21  4974.2  851.51  4981.1   850.1  4982.1   849.6
  4987.3   850.1  4994.3  856.02  5001.8  860.23  5095.4  860.55  5184.7  862.64
  5194.7  863.49  5334.9  868.24  5344.9  869.24    5395  870.95  5434.5  873.15
  5445.1  872.94  5535.2  876.67  5545.2  876.31  5595.3  877.85  5605.4  878.67
#Mann= 4 ,-1 , 0
  4562.2     .05       0  4688.8     .12       0  4981.1     .07       0
  4987.3     .12       0
Bank Sta=4981.1,4987.3
XS Rating Curve= 0 ,0
Exp/Cntr=0.3,0.1

Type RM Length L Ch R = 1 ,5970    ,466,466,466
BEGIN DESCRIPTION:
UDS St 30 8.0
END DESCRIPTION:
XS GIS Cut Line= 3
      2256981.28      7185718.59        2257429.        7185710.
      2257862.09      7185707.04
#Sta/Elev= 30
  4552.2  877.94  4579.9  874.55  4639.9  869.37  4729.9  864.06    4750  861.68
  4770.5  861.56    4790  859.85    4820  859.97    4940  857.61    4960  858.02
    4970  852.79  4977.9  847.02    4990  848.23  4997.5  852.45  5002.5  852.45
    5010  856.29    5020   858.9    5040  859.82    5050  858.32    5100  858.81
    5130  857.78    5170  858.66    5210   860.2    5240  864.15    5250   864.2
  5272.9  866.59    5310  868.85    5350  874.36    5390  878.24  5433.1  881.09
#Mann= 5 ,-1 , 0
  4552.2     .05       0  4770.5     .12       0    4960     .07       0
    5020     .12       0  5272.9     .05       0
Bank Sta=4960,5020
XS Rating Curve= 0 ,0
Exp/Cntr=0.3,0.1

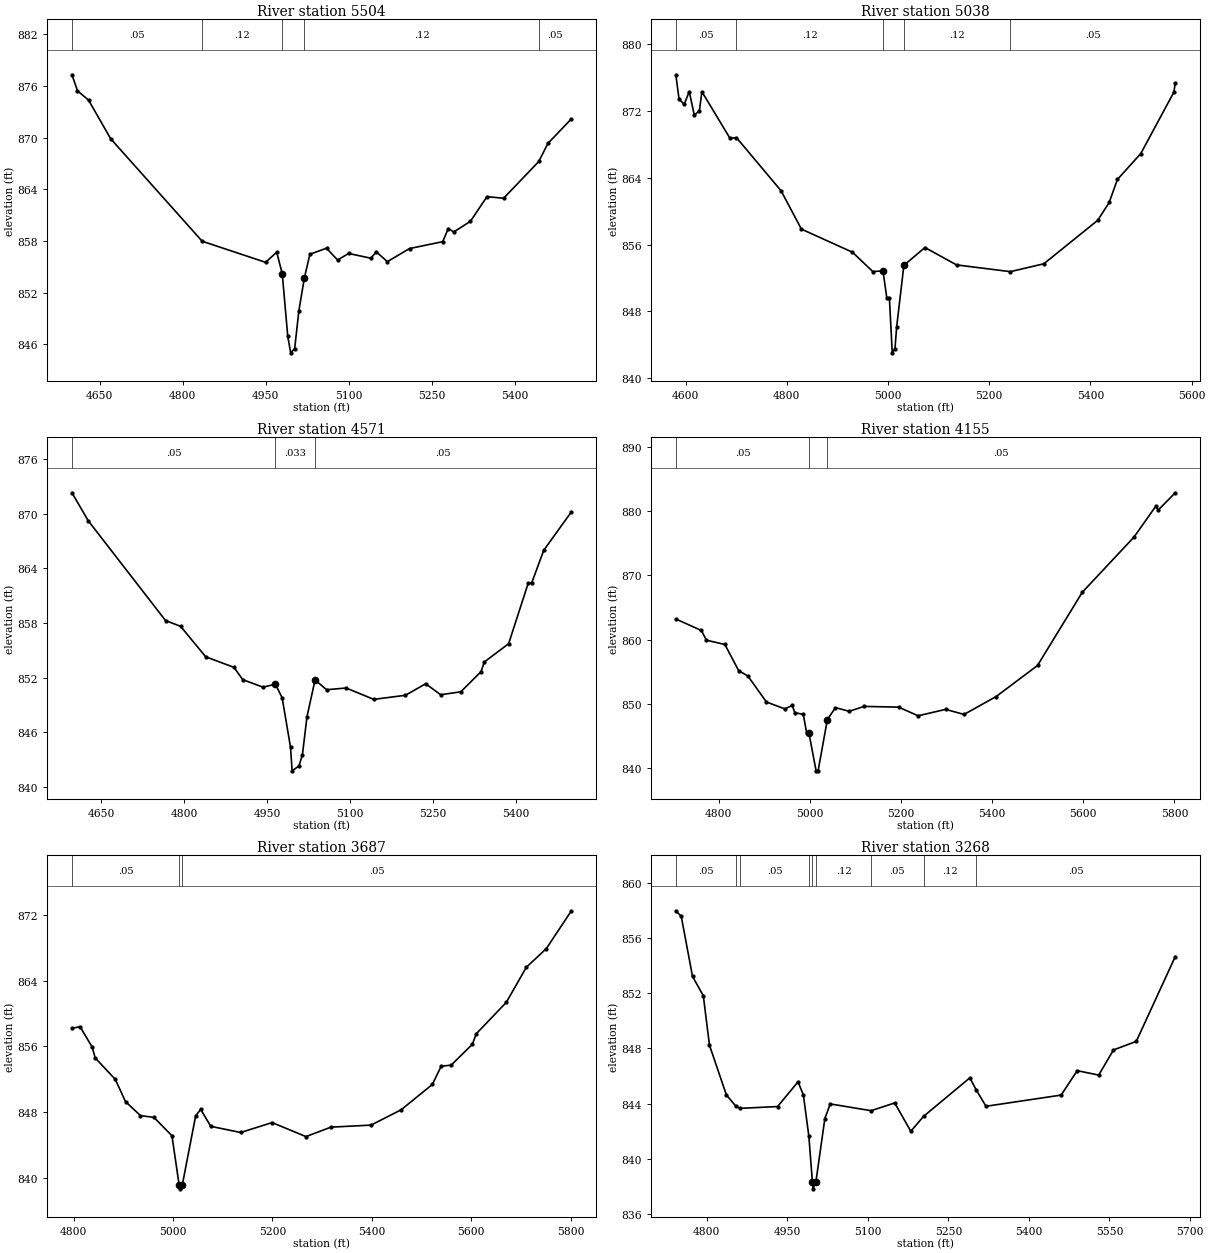
Type RM Length L Ch R = 1 ,5504    ,466,466,466
BEGIN DESCRIPTION:
UDS St 30 7.0
END DESCRIPTION:
XS GIS Cut Line= 3
      2257079.02        7186160.        2257479.        7186160.
      2257981.52      7186158.33
#Sta/Elev= 30
    4600  877.31    4610  875.45    4630  874.37    4670  869.88  4835.3  857.98
    4950  855.53    4970  856.71    4980  854.22    4990  846.92  4995.3  845.02
  5002.5  845.52    5010  849.88    5020  853.73    5030  856.47    5060  857.17
    5080   855.8    5100  856.56    5140  856.01    5150  856.74    5170  855.61
    5210  857.13    5270  857.93    5280  859.45    5290  859.06    5320  860.29
    5350  863.16    5380  862.97  5443.6  867.24    5460  869.33  5502.5  872.19
#Mann= 5 ,-1 , 0
    4600     .05       0  4835.3     .12       0    4980     .07       0
    5020     .12       0  5443.6     .05       0
Bank Sta=4980,5020
XS Rating Curve= 0 ,0
Exp/Cntr=0.3,0.1

Type RM Length L Ch R = 1 ,5038    ,467,467,467
BEGIN DESCRIPTION:
UDS St 30 6.0
END DESCRIPTION:
XS GIS Cut Line= 3
      2257112.66       7186661.3        2257529.        7186610.
      2258074.56      7186453.69
#Sta/Elev= 30
  4580.6  876.32    4587   873.4  4597.1  872.78  4607.1  874.31  4617.2  871.47
  4627.2  872.04  4632.2  874.29  4687.7  868.71  4700.4   868.8  4788.5  862.44
  4828.8  857.84  4929.6  855.08  4969.9  852.76    4990  852.84  4997.6  849.58
  5002.7  849.58  5008.3  843.03  5013.7  843.53    5017  846.12  5031.3   853.5
  5072.9  855.64  5135.3  853.56  5241.7  852.75  5307.8  853.69  5414.3  858.89
    5437  861.03  5453.3  863.79  5499.4  866.88  5564.9  874.24  5567.6  875.35
#Mann= 5 ,-1 , 0
  4580.6     .05       0  4700.4     .12       0    4990     .07       0
  5031.3     .12       0  5241.7     .05       0
Bank Sta=4990,5031.3
XS Rating Curve= 0 ,0
Exp/Cntr=0.3,0.1

Type RM Length L Ch R = 1 ,4571    ,416,416,416
BEGIN DESCRIPTION:
UDS St 30 5.0
END DESCRIPTION:
XS GIS Cut Line= 3
      2257578.99      7187310.02        2257779.        7186960.
      2258078.98      7186560.03
#Sta/Elev= 30
  4596.6  872.32  4626.1  869.24  4765.8  858.27  4793.1  857.63  4838.5  854.28
  4889.6  853.12  4905.4  851.77  4942.1  850.94  4964.5  851.27  4976.7  849.77
  4991.8  844.35  4994.7  841.74    5007  842.27  5013.3  843.49  5021.6  847.69
  5036.2  851.74    5057  850.66  5092.4  850.85  5142.4   849.6  5199.7  850.05
  5236.2  851.32  5263.3  850.11  5299.7  850.43  5336.2  852.64  5342.4  853.72
  5386.2  855.72  5421.6  862.37  5427.9   862.4  5449.7  865.99  5499.7  870.22
#Mann= 3 , 0 , 0
  4596.6     .05       0  4964.5    .033       0  5036.2     .05       0
Bank Sta=4964.5,5036.2
XS Rating Curve= 0 ,0
Exp/Cntr=0.3,0.1

Type RM Length L Ch R = 1 ,4155    ,468,468,468
BEGIN DESCRIPTION:
UDS St 30 4.0
END DESCRIPTION:
XS GIS Cut Line= 3
      2258034.82      7187496.43        2258079.        7187210.
      2258178.99      7186410.04
#Sta/Elev= 30
  4705.8  863.21  4761.9  861.42    4773  859.91  4813.5  859.24  4843.8  855.16
  4864.1  854.32  4904.6  850.29    4945  849.21  4961.5  849.76  4966.6  848.64
  4985.5  848.35  4993.1   845.4  4998.1   845.4  5013.6  839.57    5018  839.57
  5038.4  847.56  5056.1  849.41  5086.3  848.84  5119.1   849.6  5194.7  849.49
  5237.5  848.14    5298  849.14  5338.3  848.35  5408.8  851.14  5499.5  855.97
  5597.8  867.37  5711.1  875.95    5759  880.76  5764.1  880.15  5801.8  882.86
#Mann= 3 , 0 , 0
  4705.8     .05       0  4998.1    .033       0  5038.4     .05       0
Bank Sta=4998.1,5038.4
XS Rating Curve= 0 ,0
Exp/Cntr=0.3,0.1

Type RM Length L Ch R = 1 ,3687    ,419,419,419
BEGIN DESCRIPTION:
UDS St 30 3.0
END DESCRIPTION:
XS GIS Cut Line= 3
      2258447.84      7187606.19        2258479.        7187410.
        2258579.      7186609.98
#Sta/Elev= 30
  4796.6  858.22    4813   858.4  4837.1  855.94  4843.4   854.6  4883.9  851.98
  4904.4  849.27  4934.5  847.57  4961.6  847.35  4997.8  845.11  5012.2  839.14
  5013.2  838.64  5018.7  839.14  5045.6  847.56  5055.7  848.33  5075.9  846.26
  5136.3  845.51  5199.3  846.72  5267.4  845.01  5317.7  846.16  5398.4  846.41
  5458.8  848.27  5521.8  851.37  5539.5  853.59  5559.6  853.72  5602.4  856.27
    5610  857.54  5670.5  861.37  5710.8  865.65  5751.1  867.93  5801.5  872.54
#Mann= 3 ,-1 , 0
  4796.6     .05       0  5012.2     .04       0  5018.7     .05       0
Bank Sta=5012.2,5018.7
XS Rating Curve= 0 ,0
Exp/Cntr=0.3,0.1

Type RM Length L Ch R = 1 ,3268    ,499,499,499
BEGIN DESCRIPTION:
UDS St 30 2.2
END DESCRIPTION:
XS GIS Cut Line= 3
      2258679.38      7187632.15      2258865.91      7187571.49
      2258875.47       7186837.4
#Sta/Elev= 30
  4742.4  857.97  4752.5  857.57  4773.5  853.21  4793.6  851.82  4805.1  848.23
  4836.6  844.63  4854.6   843.8    4862  843.66  4931.9  843.79    4970  845.58
    4980  844.63  4990.2  841.64  4996.8  838.33  4997.8  837.83  5003.3  838.33
    5020  842.92    5030  843.98  5106.1  843.49  5150.1  844.05  5180.1     842
  5203.9  843.08  5290.1  845.87  5301.6  845.02  5320.1  843.81  5460.1  844.62
  5490.1  846.39  5530.1  846.07  5557.6  847.89  5600.1  848.51  5672.7  854.65
#Mann= 9 ,-1 , 0
  4742.4     .05       0  4854.6     .12       0    4862     .05       0
  4990.2     .12       0  4996.8     .07       0  5003.3     .12       0
  5106.1     .05       0  5203.9     .12       0  5301.6     .05       0
Bank Sta=4996.8,5003.3
XS Rating Curve= 0 ,0
Exp/Cntr=0.3,0.1