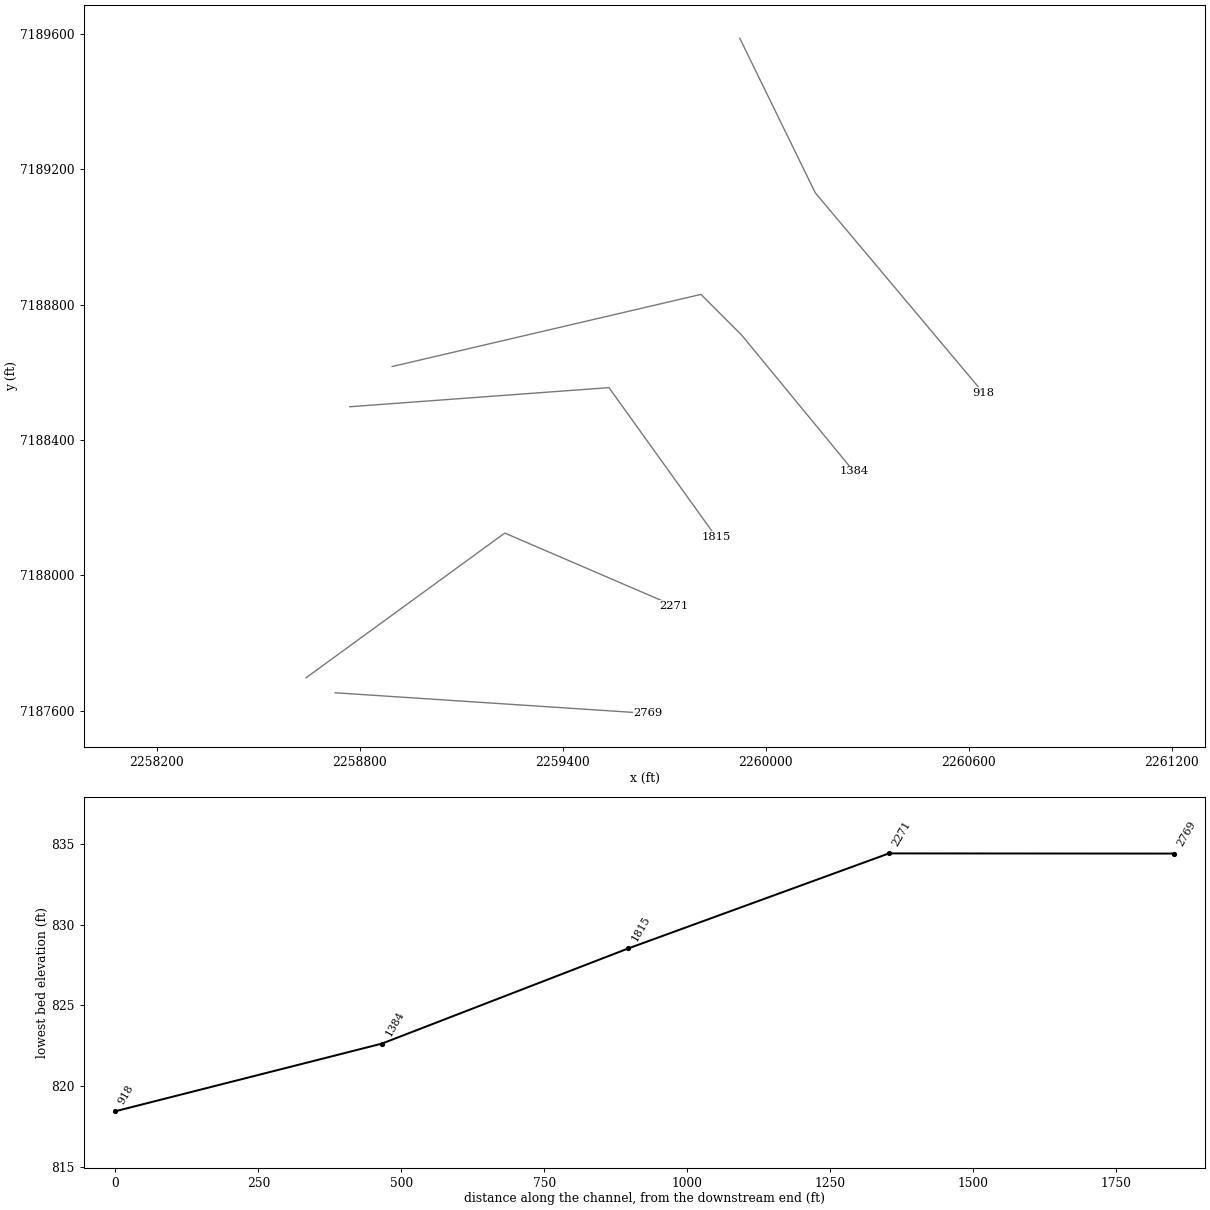
HEC-RAS study UDS St 30.prj: UDS St 30 Base Level Engineering

--- UDS St 30.g01 (geometry) --- (continued)

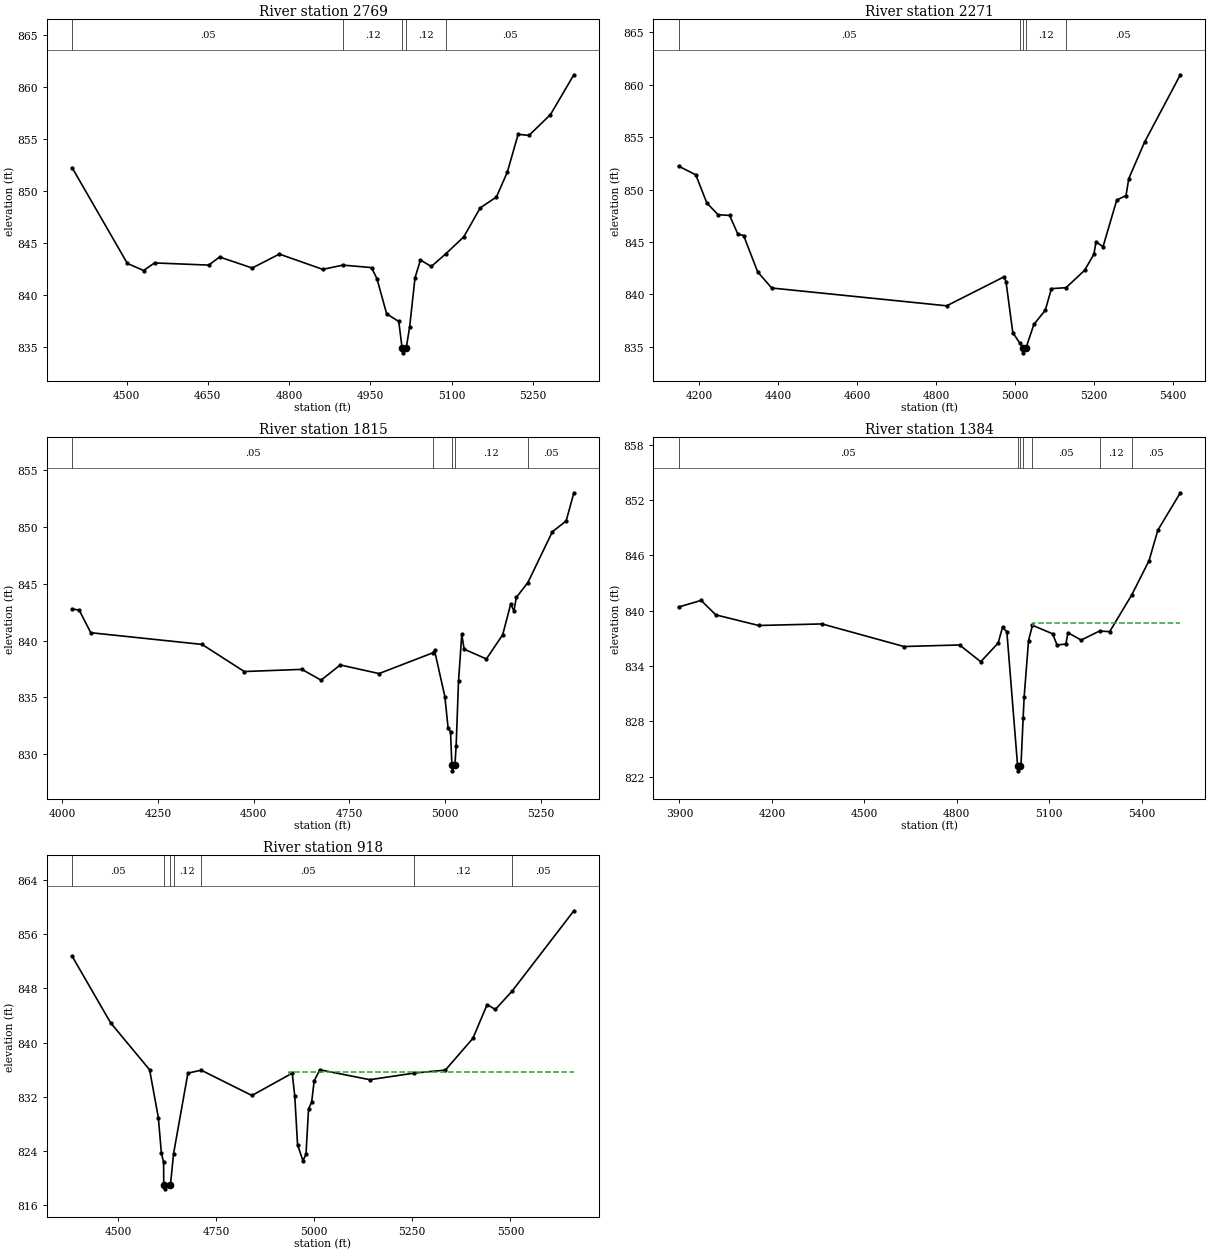
Type RM Length L Ch R = 1 ,2769    ,498,498,498
BEGIN DESCRIPTION:
UDS St 30 2.1
END DESCRIPTION:
XS GIS Cut Line= 2
      2258727.15      7187653.35      2259651.64      7187592.46
#Sta/Elev= 30
  4399.4  852.22  4501.5     843  4531.5  842.32  4551.6  843.05  4651.8  842.84
  4671.8  843.62    4732  842.56  4782.1   843.9  4862.3  842.43  4899.4  842.84
  4952.4   842.6  4962.5  841.51  4980.2  838.15  5002.6  837.42  5008.7   834.9
  5009.8   834.4  5016.5   834.9  5022.6  836.86  5032.6  841.62  5042.6  843.33
  5062.7  842.71  5089.1  843.91  5122.8  845.57  5152.9  848.34  5182.9  849.39
    5203  851.78    5223  855.42  5243.1  855.32  5282.7  857.32  5325.9  861.15
#Mann= 5 ,-1 , 0
  4399.4     .05       0  4899.4     .12       0  5008.7     .07       0
  5016.5     .12       0  5089.1     .05       0
Bank Sta=5008.7,5016.5
XS Rating Curve= 0 ,0
Exp/Cntr=0.3,0.1

Type RM Length L Ch R = 1 ,2271    ,456,456,456
BEGIN DESCRIPTION:
UDS St 30 2.0
END DESCRIPTION:
XS GIS Cut Line= 3
      2258641.05      7187697.58      2259228.41      7188125.41
      2259728.97      7187910.01
#Sta/Elev= 30
  4146.9  852.24  4190.6  851.41  4218.6  848.72    4247   847.6  4276.3  847.53
  4297.2  845.75  4311.9  845.61  4347.4  842.14    4383   840.6  4826.5   838.9
  4971.3  841.66  4976.7  841.22    4994  836.33  5012.3  835.31  5019.9  834.91
    5021  834.41  5027.7  834.91  5047.3  837.12  5076.3  838.48  5091.9  840.54
  5128.8  840.63  5175.9  842.29  5199.4  843.82  5204.9  845.01  5222.6  844.54
  5257.4     849  5280.9  849.43  5287.9  851.05    5328  854.54  5418.5  860.96
#Mann= 5 ,-1 , 0
  4146.9     .05       0  5012.3     .12       0  5019.9    .033       0
  5027.7     .12       0  5128.8     .05       0
Bank Sta=5019.9,5027.7
XS Rating Curve= 0 ,0
Exp/Cntr=0.3,0.1

Type RM Length L Ch R = 1 ,1815    ,431,431,431
BEGIN DESCRIPTION:
UDS St 30 1.1
END DESCRIPTION:
XS GIS Cut Line= 3
      2258770.37      7188498.74      2259536.38      7188555.26
      2259852.71      7188114.39
#Sta/Elev= 30
  4025.6  842.79  4044.3  842.68  4074.4  840.69  4365.1  839.66  4475.4  837.27
  4625.9  837.46    4676  836.51  4726.1  837.85  4827.4  837.09  4968.1  838.92
  4972.3  839.14  4999.3  835.07  5007.9  832.28  5014.1  831.97  5017.7  829.02
  5018.9  828.52  5025.6  829.02  5028.8  830.71    5035   836.4  5043.5  840.55
  5049.7  839.24  5107.8  838.38  5150.4  840.51  5171.3  843.21  5179.8  842.62
    5186   843.8  5216.2  845.11  5280.2  849.59  5316.1  850.53  5336.3  853.02
#Mann= 5 ,-1 , 0
  4025.6     .05       0  4968.1     .12       0  5017.7     .07       0
  5025.6     .12       0  5216.2     .05       0
#XS Ineff= 2 , 0
       0                  5043.5       0  840.55
Permanent Ineff=
       F       F
Bank Sta=5017.7,5025.6
XS Rating Curve= 0 ,0
Exp/Cntr=0.3,0.1

Type RM Length L Ch R = 1 ,1384    ,466,466,466
BEGIN DESCRIPTION:
UDS St 30 1.0
END DESCRIPTION:
XS GIS Cut Line= 4
      2258895.63      7188617.61      2259808.23      7188830.77
        2259929.        7188710.      2260259.59      7188307.91
#Sta/Elev= 30
  3897.1  840.38  3970.4   841.1  4018.1  839.53  4157.3  838.38  4362.7  838.55
  4628.8   836.1  4809.1  836.27  4877.8  834.45  4934.3  836.47  4948.5  838.19
  4962.6   837.7  4997.6  823.12  4998.8  822.62  5005.5  823.12  5008.3  823.12
  5015.5  828.33  5018.7  830.61    5033  836.75  5045.7   838.4  5111.2  837.48
  5125.6  836.26  5154.3  836.37  5160.8   837.6  5203.8   836.8  5263.5  837.78
  5296.3  837.71  5367.8  841.69  5424.1  845.41  5452.7  848.72  5525.6  852.77
#Mann= 7 ,-1 , 0
  3897.1     .05       0  4997.6    .033       0  5005.5     .05       0
  5015.5     .12       0  5045.7     .05       0  5263.5     .12       0
  5367.8     .05       0
#XS Ineff= 2 , 0
       0                  5047.4       0  838.64
Permanent Ineff=
       F       F
Bank Sta=4997.6,5005.5
XS Rating Curve= 0 ,0
Exp/Cntr=0.3,0.1

Type RM Length L Ch R = 1 ,918     ,0,0,0
BEGIN DESCRIPTION:
UDS St 30 0.9
END DESCRIPTION:
XS GIS Cut Line= 3
      2259923.05      7189587.58      2260146.05      7189131.12
      2260641.94      7188540.79
#Sta/Elev= 30
  4382.8  852.74    4481  842.91  4580.4  835.98  4602.7  828.93  4610.5  823.65
  4616.1  822.38  4616.5  818.93  4618.5  818.43  4633.4  818.93  4641.5  823.61
  4678.1  835.49  4711.9  835.92  4841.3  832.19  4943.9  835.48  4950.4  832.12
  4957.6   824.9  4971.3  822.58    4979   823.5  4985.6  830.24  4993.4  831.18
  4999.9  834.35  5014.2  835.98  5141.7  834.52  5255.6   835.5  5334.2  835.93
  5404.4  840.61  5440.8   845.6  5461.6  844.87  5504.6  847.59  5661.8  859.42
#Mann= 7 ,-1 , 0
  4382.8     .05       0  4616.5    .033       0  4633.4     .05       0
  4641.5     .12       0  4711.9     .05       0  5255.6     .12       0
  5504.6     .05       0
#XS Ineff= 2 , 0
       0                  4936.1       0  835.59
Permanent Ineff=
       F       F
Bank Sta=4616.5,4633.4
XS Rating Curve= 0 ,0
Exp/Cntr=0.3,0.1

Chan Stop Cuts=-1
Use User Specified Reach Order=0
Composite Channel Slope=5