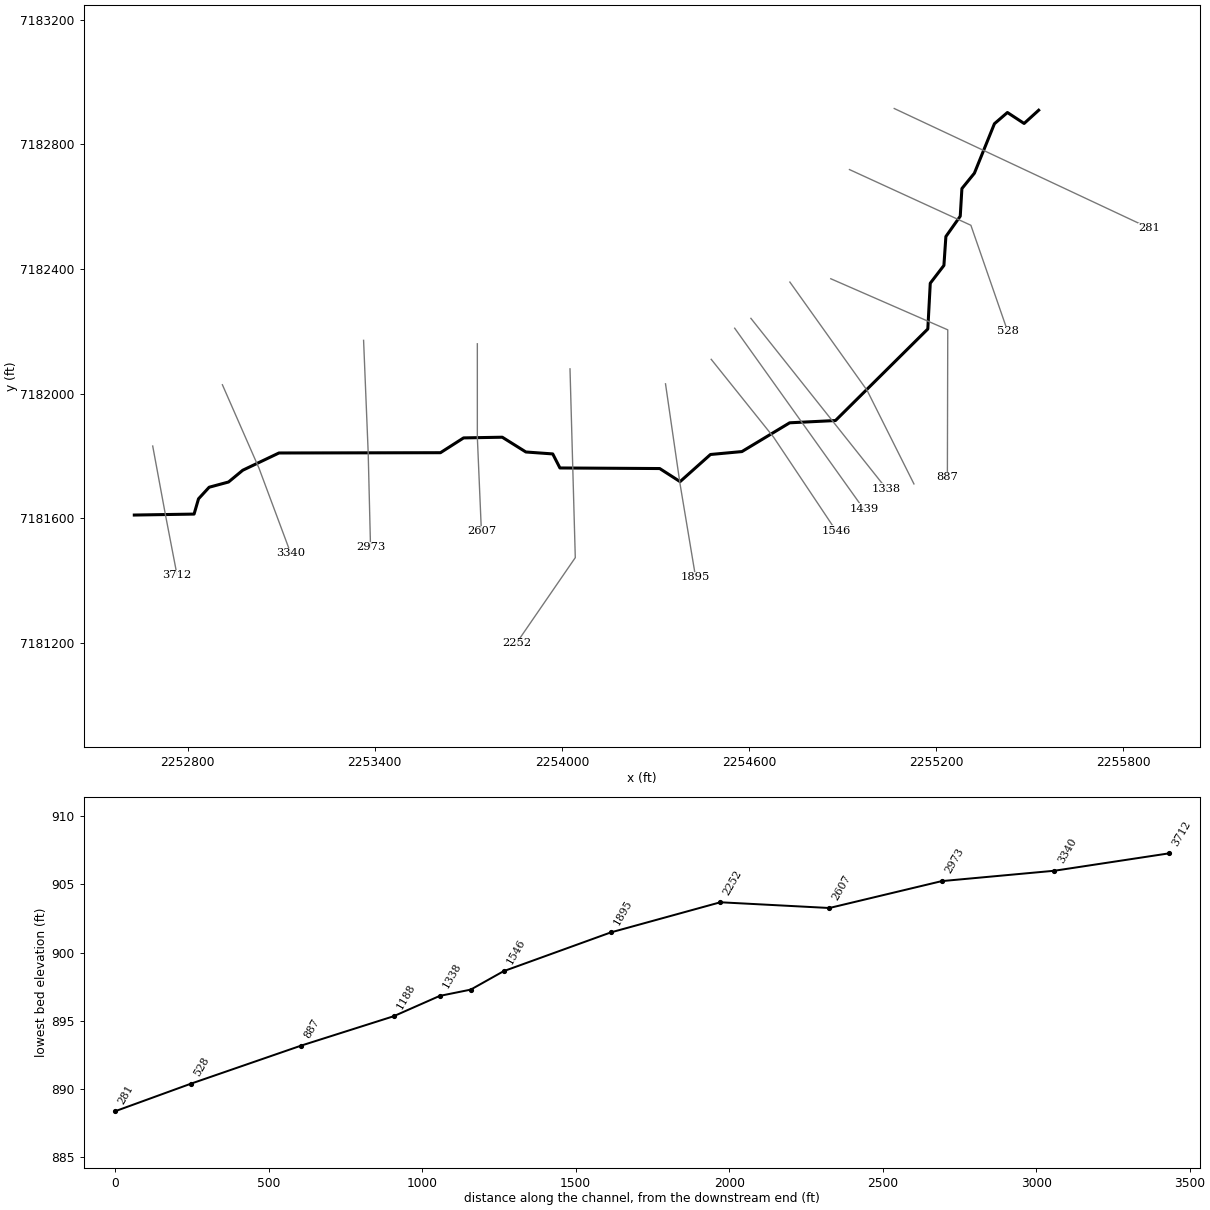
--- UDS St 31.prj (project) ---

Proj Title=UDS St 31 Base Level Engineering
Current Plan=p01
Default Exp/Contr=0.3,0.1
English Units
Geom File=g01
Flow File=f01
Plan File=p01
BEGIN DESCRIPTION:
UDS St 31
END DESCRIPTION:

--- UDS St 31.p01 (plan) ---

Plan Title=Multiple Run
Short Identifier=Multiple
Geom File=g01
Flow File=f01
Subcritical Flow
K Sum by GR= 0
Std Step Tol= 0.01
Critical Tol= 0.01
Num of Std Step Trials= 20
Max Error Tol= 0.3
Flow Tol Ratio= 0.001
Split Flow NTrial= 30
Split Flow Tol= 0.02
Split Flow Ratio= 0.02
Log Output Level= 0
Friction Slope Method= 1
Unsteady Friction Slope Method= 2
Unsteady Bridges Friction Slope Method= 1
Parabolic Critical Depth
Global Vel Dist=  1 , 1 , 1
Global Log Level= 0
CheckData=True
Encroach Param= -1, 0, 0, 0
BEGIN DESCRIPTION:
Multiple Run
END DESCRIPTION:

--- UDS St 31.f01 (steady flow) ---

Flow Title=Multiple
Number of Profiles=7
Profile Names=10-year,25-year,50-year,1pct_min,100-year,1pct_plu,500-year
River Rch & RM= UDS St 31,Reach-1,3712
     590     814    1000     611    1219    2433    1815
Boundary for River Rch & Prof#=UDS St 31,Reach-1,1
Up Type=0
Dn Type=3
Dn Slope=0.005
Boundary for River Rch & Prof#=UDS St 31,Reach-1,2
Up Type=0
Dn Type=3
Dn Slope=0.005
Boundary for River Rch & Prof#=UDS St 31,Reach-1,3
Up Type=0
Dn Type=3
Dn Slope=0.005
Boundary for River Rch & Prof#=UDS St 31,Reach-1,4
Up Type=0
Dn Type=3
Dn Slope=0.005
Boundary for River Rch & Prof#=UDS St 31,Reach-1,5
Up Type=0
Dn Type=3
Dn Slope=0.005
Boundary for River Rch & Prof#=UDS St 31,Reach-1,6
Up Type=0
Dn Type=3
Dn Slope=0.005
Boundary for River Rch & Prof#=UDS St 31,Reach-1,7
Up Type=0
Dn Type=3
Dn Slope=0.005

--- UDS St 31.g01 (geometry) ---

Geom Title=Existing Conditions

River Reach=UDS St 31,Reach-1
Reach XY= 30
      2252629.00      7181610.00      2252820.70      7181613.08
      2252834.92      7181662.14      2252869.02      7181699.31
      2252931.16      7181716.11      2252976.80      7181753.92
      2253092.91      7181809.33      2253610.73      7181810.21
      2253684.94      7181857.75      2253808.96      7181859.95
      2253884.65      7181812.50      2253970.79      7181806.28
      2253993.83      7181761.19      2254313.84      7181759.34
      2254379.10      7181717.33      2254476.57      7181804.45
      2254577.41      7181813.83      2254730.56      7181906.24
      2254877.53      7181913.54      2255173.53      7182207.55
      2255181.39      7182354.47      2255225.14      7182411.60
      2255231.47      7182504.43      2255277.51      7182569.71
      2255282.83      7182658.42      2255322.88      7182707.82
      2255387.14      7182866.68      2255428.78      7182902.71
      2255482.32      7182867.53      2255529.00      7182910.00

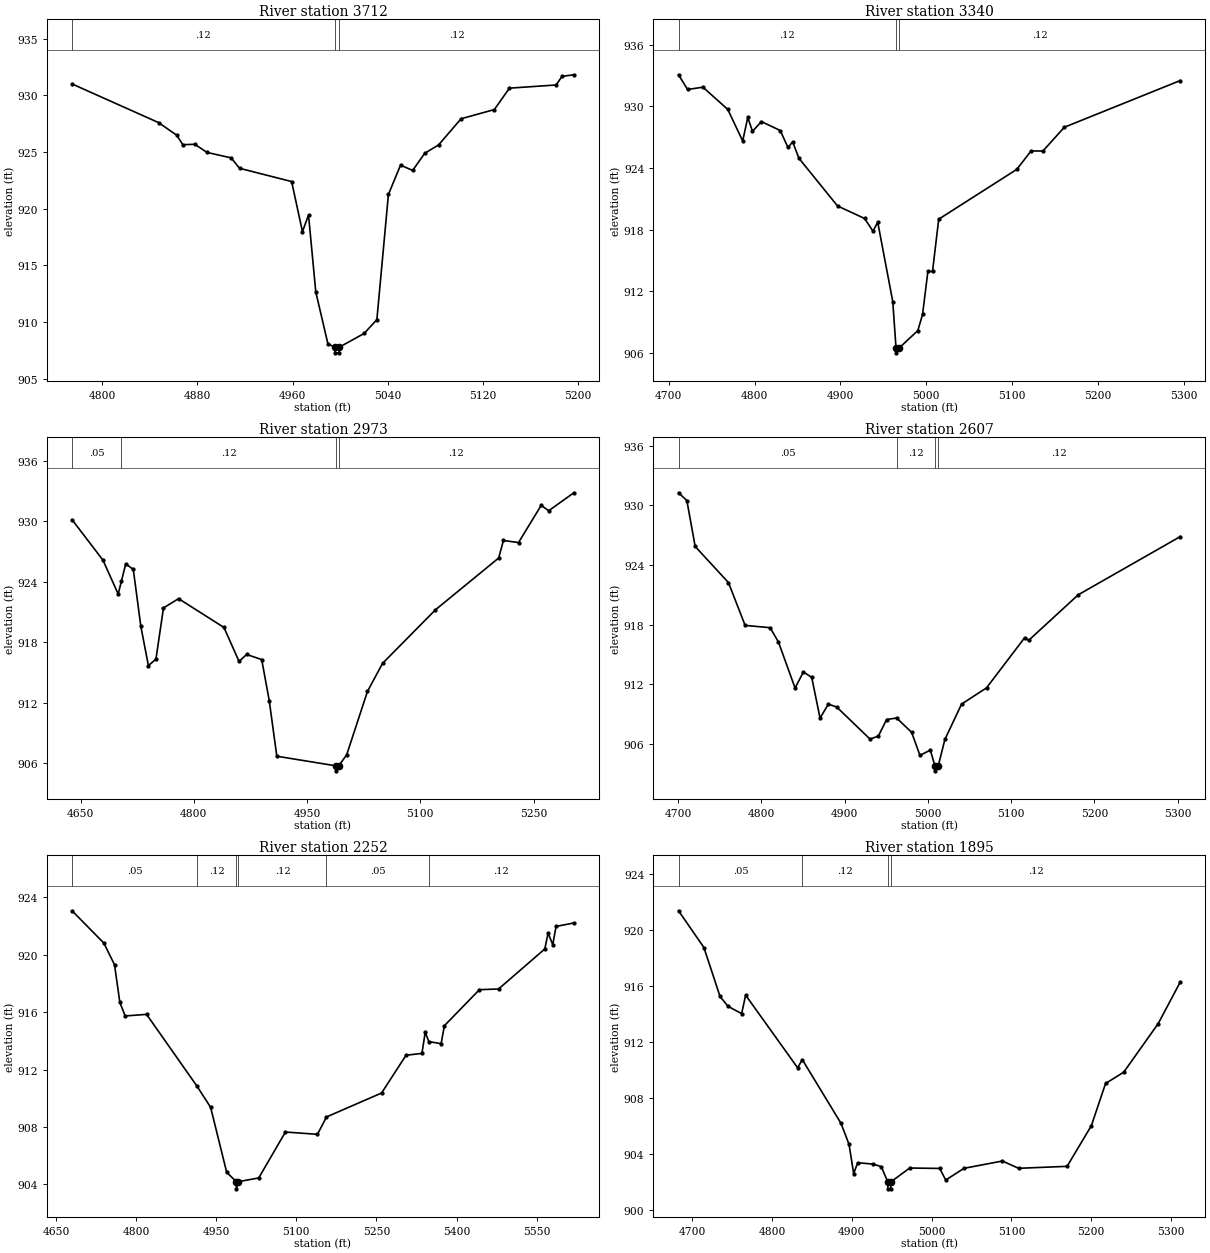
Type RM Length L Ch R = 1,3712,372,372,372
BEGIN DESCRIPTION:
UDS St 31 8.0
END DESCRIPTION:
XS GIS Cut Line= 3
      2252688.03      7181831.61      2252729.00      7181610.00
      2252766.15      7181416.80
#Sta/Elev= 30
  4774.5  930.99  4847.3  927.58  4862.5  926.47  4867.7  925.63  4877.8  925.67
  4888.0  924.95  4908.3  924.47  4915.4  923.55  4959.2  922.38  4968.3  917.96
  4973.4  919.43  4979.5  912.65  4989.7  908.07  4995.3  907.77  4995.6  907.27
  4999.1  907.27  4999.3  907.77  5020.2  908.98  5030.9  910.20  5040.6  921.24
  5050.8  923.83  5061.0  923.36  5071.1  924.87  5082.9  925.62  5101.7  927.92
  5129.7  928.73  5142.4  930.62  5181.6  930.90  5186.7  931.66  5196.6  931.80
#Mann=3,-1,0
  4774.5    0.12       0  4995.3    0.07       0  4999.3    0.12       0
Bank Sta=4995.3,4999.3
Exp/Cntr=0.3,0.1

Type RM Length L Ch R = 1,3340,367,367,367
BEGIN DESCRIPTION:
UDS St 31 7.0
END DESCRIPTION:
XS GIS Cut Line= 3
      2252911.47      7182028.44      2253029.00      7181760.00
      2253130.57      7181487.14
#Sta/Elev= 30
  4711.5  933.09  4722.0  931.66  4739.9  931.88  4768.8  929.72  4786.2  926.64
  4792.1  928.93  4797.6  927.58  4808.0  928.53  4829.9  927.66  4838.9  926.01
  4844.4  926.55  4851.7  924.95  4896.6  920.31  4928.1  919.09  4937.9  917.85
  4943.4  918.73  4960.9  911.00  4964.7  906.50  4965.0  906.00  4968.7  906.50
  4990.1  908.17  4995.6  909.74  5001.8  913.93  5007.2  913.93  5014.4  919.02
  5105.4  923.88  5121.9  925.67  5135.7  925.66  5160.7  927.98  5295.7  932.53
#Mann=3,-1,0
  4711.5    0.12       0  4964.7    0.07       0  4968.7    0.12       0
Bank Sta=4964.7,4968.7
Exp/Cntr=0.3,0.1

Type RM Length L Ch R = 1,2973,366,366,366
BEGIN DESCRIPTION:
UDS St 31 6.0
END DESCRIPTION:
XS GIS Cut Line= 3
      2253364.24      7182171.00      2253379.00      7181810.00
      2253386.49      7181506.69
#Sta/Elev= 30
  4638.7  930.15  4679.7  926.13  4699.8  922.77  4704.1  924.06  4709.8  925.77
  4719.8  925.22  4729.8  919.57  4739.8  915.68  4749.8  916.32  4759.8  921.40
  4779.8  922.32  4839.9  919.46  4859.9  916.09  4869.9  916.78  4889.9  916.28
  4899.9  912.20  4909.9  906.69  4988.0  905.74  4988.2  905.24  4992.0  905.74
  5002.5  906.84  5030.0  913.12  5050.0  915.90  5120.0  921.21  5203.8  926.35
  5210.1  928.09  5230.1  927.88  5260.1  931.57  5270.1  931.04  5303.4  932.82
#Mann=4,-1,0
  4638.7    0.05       0  4704.1    0.12       0  4988.0    0.07       0
  4992.0    0.12       0
Bank Sta=4988,4992
Exp/Cntr=0.3,0.1

Type RM Length L Ch R = 1,2607,355,355,355
BEGIN DESCRIPTION:
UDS St 31 5.0
END DESCRIPTION:
XS GIS Cut Line= 3
      2253729.00      7182159.97      2253729.00      7181860.00
      2253742.01      7181557.45
#Sta/Elev= 30
  4700.5  931.28  4710.5  930.50  4720.5  925.87  4760.5  922.23  4780.5  917.92
  4810.5  917.69  4820.5  916.25  4840.5  911.61  4850.5  913.23  4860.5  912.68
  4870.5  908.58  4880.5  909.99  4890.5  909.70  4930.5  906.47  4940.5  906.77
  4950.5  908.44  4962.5  908.59  4980.5  907.15  4990.5  904.83  5003.0  905.36
  5008.5  903.77  5008.7  903.27  5012.5  903.77  5020.5  906.44  5040.5  909.99
  5070.5  911.63  5116.2  916.67  5121.2  916.42  5180.6  921.00  5303.3  926.87
#Mann=4,-1,0
  4700.5    0.05       0  4962.5    0.12       0  5008.5    0.07       0
  5012.5    0.12       0
Bank Sta=5008.5,5012.5
Exp/Cntr=0.3,0.1

Type RM Length L Ch R = 1,2252,357,357,357
BEGIN DESCRIPTION:
UDS St 31 4.0
END DESCRIPTION:
XS GIS Cut Line= 3
      2254026.13      7182079.44      2254043.09      7181473.21
      2253854.40      7181198.43
#Sta/Elev= 30
  4680.0  923.07  4739.5  920.82  4759.5  919.31  4769.5  916.68  4779.5  915.74
  4819.5  915.85  4913.7  910.86  4939.5  909.37  4969.6  904.84  4987.6  904.19
  4987.8  903.69  4991.6  904.19  5029.6  904.45  5079.6  907.65  5139.6  907.49
  5156.5  908.70  5259.7  910.37  5305.5  913.00  5335.3  913.13  5341.4  914.61
  5348.2  913.95  5371.2  913.81  5377.3  915.06  5442.9  917.57  5478.8  917.62
  5565.4  920.41  5571.5  921.51  5580.3  920.71  5586.4  921.98  5619.8  922.22
#Mann=6,-1,0
  4680.0    0.05       0  4913.7    0.12       0  4987.6    0.07       0
  4991.6    0.12       0  5156.5    0.05       0  5348.2    0.12       0
Bank Sta=4987.6,4991.6
Exp/Cntr=0.3,0.1

Type RM Length L Ch R = 1,1895,349,349,349
BEGIN DESCRIPTION:
UDS St 31 3.0
END DESCRIPTION:
XS GIS Cut Line= 3
      2254332.39      7182031.44      2254379.00      7181710.00
      2254428.99      7181410.04
#Sta/Elev= 30
  4682.8  921.38  4714.6  918.75  4734.8  915.25  4744.9  914.54  4761.9  914.02
  4766.9  915.34  4832.1  910.14  4837.9  910.73  4886.4  906.17  4896.5  904.66
  4902.3  902.57  4907.3  903.35  4926.8  903.25  4936.9  903.07  4945.0  901.98
  4945.2  901.48  4948.7  901.48  4949.0  901.98  4972.5  902.97  5010.1  902.94
  5017.7  902.11  5040.6  902.95  5088.7  903.47  5109.0  902.95  5169.8  903.09
  5200.2  906.00  5218.0  909.02  5240.8  909.83  5283.9  913.30  5311.7  916.29
#Mann=4,-1,0
  4682.8    0.05       0  4837.9    0.12       0  4945.0    0.07       0
  4949.0    0.12       0
Bank Sta=4945,4949
Exp/Cntr=0.3,0.1

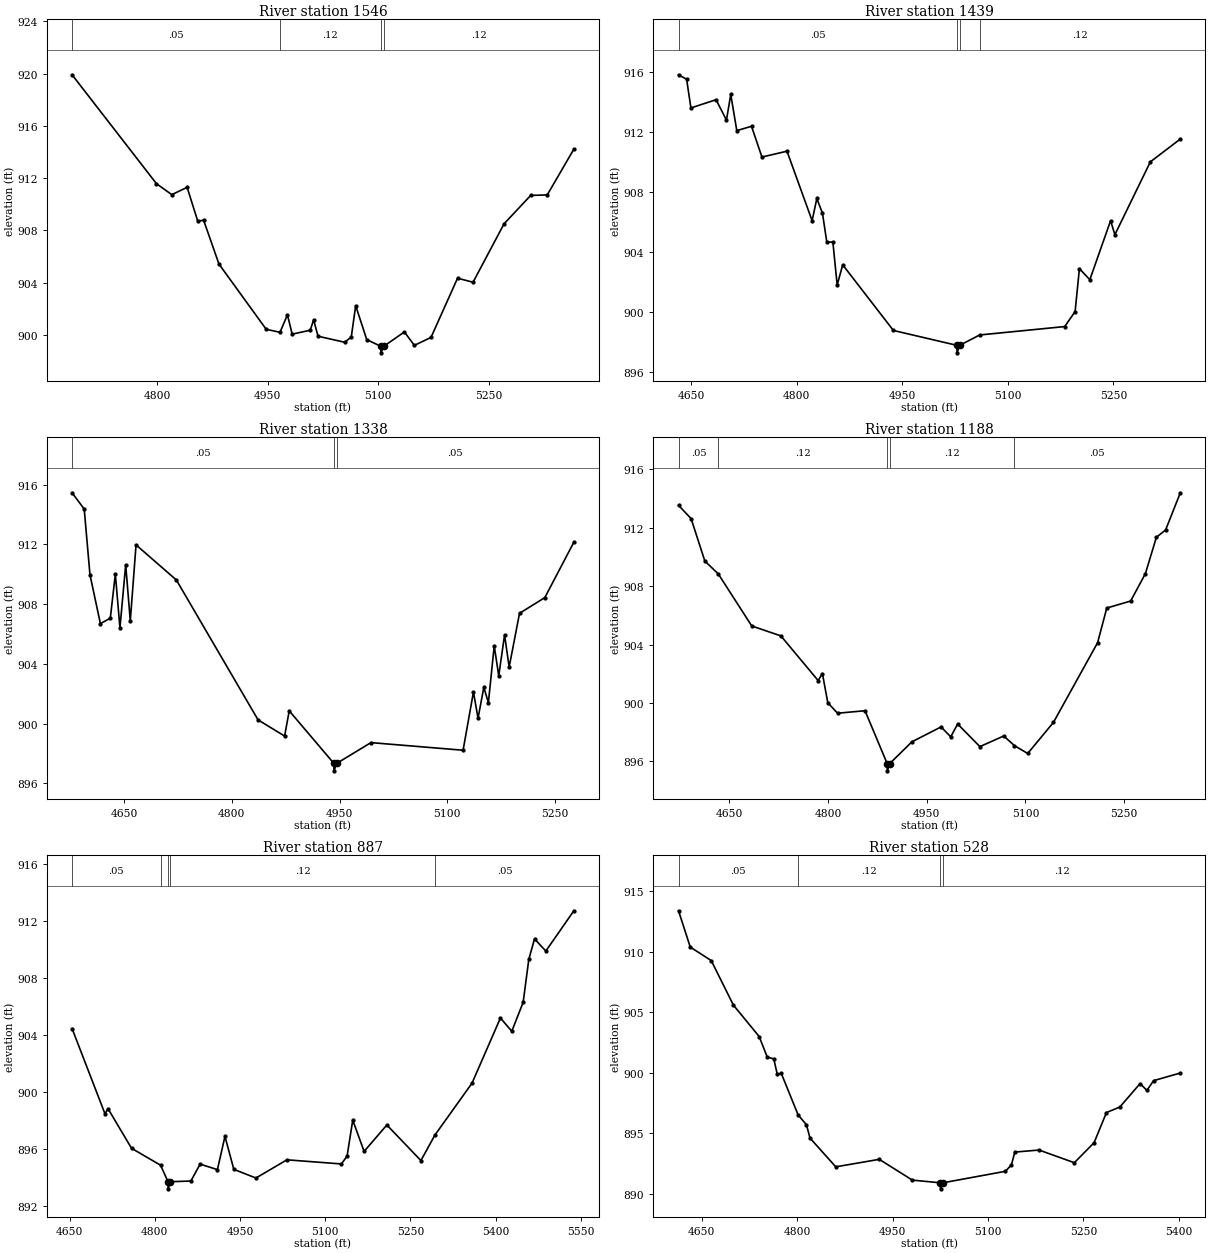
Type RM Length L Ch R = 1,1546,107,107,107
BEGIN DESCRIPTION:
UDS St 31 2.0
END DESCRIPTION:
XS GIS Cut Line= 3
      2254478.97      7182110.04      2254679.00      7181860.00
      2254879.02      7181559.97
#Sta/Elev= 30
  4684.6  919.91  4799.1  911.58  4819.9  910.74  4840.7  911.30  4855.1  908.72
  4863.1  908.78  4883.9  905.43  4948.0  900.44  4966.7  900.21  4976.8  901.55
  4983.2  900.07  5007.8  900.37  5012.3  901.17  5018.3  899.91  5054.4  899.45
  5063.4  899.85  5069.4  902.25  5084.4  899.65  5103.5  899.14  5103.7  898.64
  5107.5  899.14  5135.5  900.24  5149.0  899.21  5171.6  899.82  5207.6  904.35
  5228.6  904.04  5270.7  908.51  5306.8  910.68  5329.3  910.72  5365.4  914.22
#Mann=4,-1,0
  4684.6    0.05       0  4966.7    0.12       0  5103.5    0.07       0
  5107.5    0.12       0
Bank Sta=5103.5,5107.5
Exp/Cntr=0.3,0.1

Type RM Length L Ch R = 1,1439,101,101,101
BEGIN DESCRIPTION:
UDS St 31 1.2
END DESCRIPTION:
XS GIS Cut Line= 2
      2254554.21      7182210.00      2254967.98      7181629.35
#Sta/Elev= 30
  4632.1  915.81  4643.6  915.51  4649.7  913.60  4685.4  914.15  4700.2  912.79
  4706.3  914.50  4714.9  912.09  4735.8  912.38  4750.6  910.33  4786.2  910.72
  4821.9  906.09  4828.6  907.57  4836.6  906.59  4842.8  904.66  4851.4  904.67
  4857.5  901.81  4865.4  903.15  4937.4  898.78  5027.6  897.79  5027.9  897.29
  5031.6  897.79  5060.0  898.48  5180.8  899.04  5195.6  900.04  5201.7  902.90
  5216.5  902.16  5246.0  906.09  5252.1  905.16  5302.5  910.01  5345.1  911.53
#Mann=4,-1,0
  4632.1    0.05       0  5027.6   0.033       0  5031.6    0.05       0
  5060.0    0.12       0
Bank Sta=5027.6,5031.6
Exp/Cntr=0.3,0.1

Type RM Length L Ch R = 1,1338,150,150,150
BEGIN DESCRIPTION:
UDS St 31 1.1
END DESCRIPTION:
XS GIS Cut Line= 2
      2254606.22      7182241.65      2255040.37      7181694.97
#Sta/Elev= 30
  4577.9  915.45  4594.8  914.36  4602.8  909.96  4617.3  906.69  4631.1  907.05
  4638.1  910.00  4644.5  906.40  4652.5  910.63  4658.9  906.87  4666.9  911.96
  4723.0  909.61  4836.7  900.24  4873.6  899.16  4880.0  900.85  4942.1  897.33
  4942.3  896.83  4946.1  897.33  4993.7  898.72  5121.9  898.21  5136.3  902.11
  5142.7  900.35  5150.7  902.42  5157.1  901.40  5165.2  905.20  5171.5  903.20
  5179.6  905.93  5186.0  903.78  5200.4  907.38  5235.6  908.43  5276.0  912.14
#Mann=3,-1,0
  4577.9    0.05       0  4942.1   0.033       0  4946.1    0.05       0
Bank Sta=4942.1,4946.1
Exp/Cntr=0.3,0.1

Type RM Length L Ch R = 1,1188,301,301,301
BEGIN DESCRIPTION:
UDS St 31 1.0
END DESCRIPTION:
XS GIS Cut Line= 3
      2254731.19      7182358.17      2254979.00      7182010.00
      2255129.02      7181709.97
#Sta/Elev= 30
  4572.6  913.54  4591.7  912.63  4612.6  909.72  4633.0  908.84  4683.9  905.27
  4728.2  904.59  4784.8  901.53  4791.3  902.01  4799.5  900.01  4814.3  899.29
  4856.1  899.46  4889.7  895.84  4890.0  895.34  4893.7  895.84  4927.4  897.33
  4971.7  898.35  4986.4  897.67  4996.9  898.55  5030.7  897.00  5067.0  897.73
  5083.1  897.07  5103.4  896.53  5142.5  898.66  5209.6  904.12  5223.6  906.50
  5259.9  906.98  5282.3  908.86  5299.0  911.35  5313.0  911.85  5335.4  914.40
#Mann=5,-1,0
  4572.6    0.05       0  4633.0    0.12       0  4889.7    0.07       0
  4893.7    0.12       0  5083.1    0.05       0
Bank Sta=4889.7,4893.7
Exp/Cntr=0.3,0.1

Type RM Length L Ch R = 1,887,359,359,359
BEGIN DESCRIPTION:
UDS St 31 0.9
END DESCRIPTION:
XS GIS Cut Line= 3
      2254862.40      7182368.85      2255237.49      7182204.75
      2255236.25      7181730.66
#Sta/Elev= 30
  4654.4  904.46  4712.3  898.47  4717.8  898.82  4759.1  896.04  4810.3  894.85
  4823.3  893.69  4823.6  893.19  4827.3  893.69  4863.6  893.74  4879.9  894.93
  4910.3  894.54  4923.6  896.88  4939.2  894.56  4978.1  893.95  5032.7  895.23
  5128.6  894.94  5138.6  895.49  5148.6  898.02  5168.6  895.82  5208.6  897.68
  5268.6  895.18  5293.4  896.98  5358.6  900.62  5408.6  905.20  5428.6  904.27
  5448.6  906.30  5458.6  909.33  5468.6  910.76  5488.6  909.91  5537.9  912.74
#Mann=5,-1,0
  4654.4    0.05       0  4810.3    0.12       0  4823.3    0.07       0
  4827.3    0.12       0  5293.4    0.05       0
Bank Sta=4823.3,4827.3
Exp/Cntr=0.3,0.1

Type RM Length L Ch R = 1,528,247,247,247
BEGIN DESCRIPTION:
UDS St 31 0.8
END DESCRIPTION:
XS GIS Cut Line= 3
      2254922.31      7182719.47      2255311.64      7182540.57
      2255429.45      7182200.25
#Sta/Elev= 30
  4613.6  913.40  4632.0  910.40  4665.0  909.28  4699.8  905.60  4740.3  903.00
  4753.0  901.30  4763.3  901.15  4768.8  899.87  4775.0  899.96  4801.5  896.52
  4814.7  895.69  4820.2  894.60  4860.7  892.22  4929.1  892.84  4981.1  891.12
  5025.1  890.90  5025.3  890.40  5029.1  890.90  5127.3  891.85  5136.8  892.39
  5142.1  893.44  5180.2  893.61  5235.6  892.56  5266.7  894.22  5286.1  896.71
  5307.2  897.17  5339.0  899.11  5349.6  898.54  5360.2  899.35  5402.2  899.98
#Mann=4,-1,0
  4613.6    0.05       0  4801.5    0.12       0  5025.1    0.07       0
  5029.1    0.12       0
Bank Sta=5025.1,5029.1
Exp/Cntr=0.3,0.1

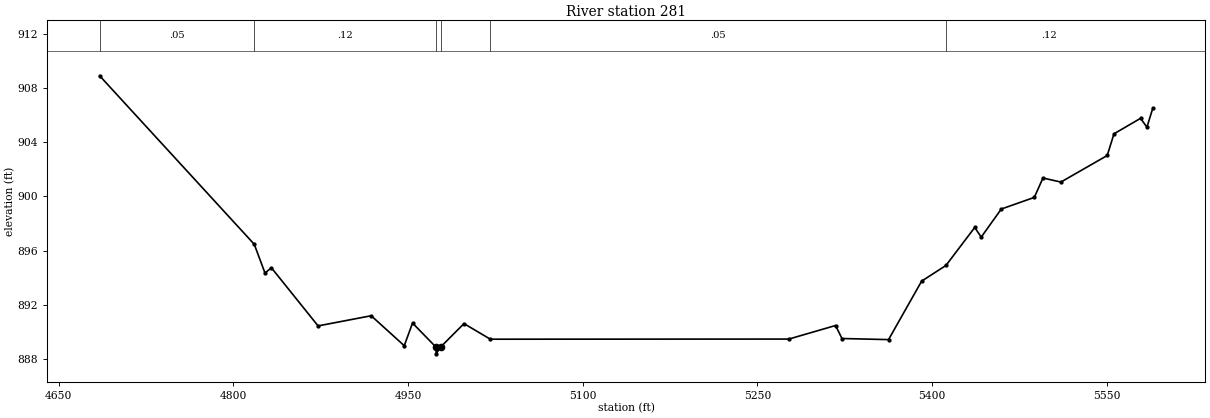
Type RM Length L Ch R = 1,281,0,0,0
BEGIN DESCRIPTION:
UDS St 31 0.7
END DESCRIPTION:
XS GIS Cut Line= 2
      2255065.84      7182915.56      2255884.38      7182530.95
#Sta/Elev= 30
  4685.1  908.89  4817.9  896.46  4827.1  894.34  4832.6  894.73  4872.7  890.44
  4918.3  891.19  4946.7  888.98  4953.8  890.65  4973.9  888.88  4974.1  888.38
  4977.9  888.88  4998.0  890.61  5020.6  889.46  5277.0  889.47  5317.1  890.47
  5322.6  889.51  5362.6  889.43  5391.0  893.74  5411.9  894.90  5436.6  897.70
  5442.2  896.99  5459.4  899.06  5487.8  899.92  5495.2  901.35  5510.6  901.05
  5550.4  903.01  5556.2  904.61  5579.0  905.75  5584.5  905.10  5589.5  906.49
#Mann=6,-1,0
  4685.1    0.05       0  4817.9    0.12       0  4973.9    0.07       0
  4977.9    0.12       0  5020.6    0.05       0  5411.9    0.12       0
Bank Sta=4973.9,4977.9
Exp/Cntr=0.3,0.1

Chan Stop Cuts=-1