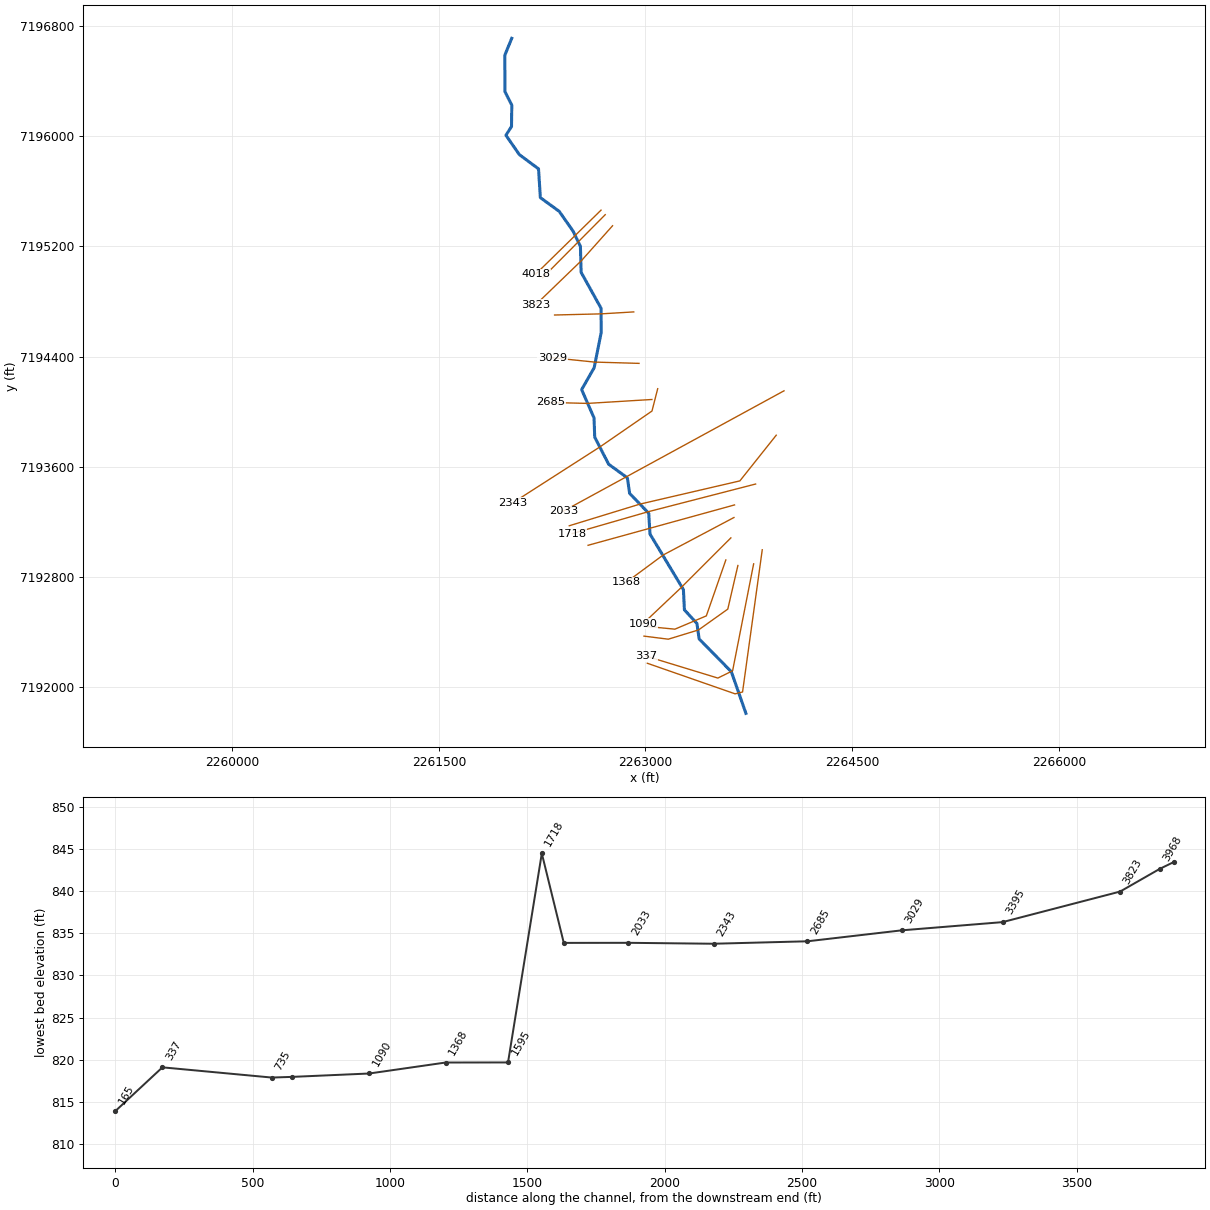
--- UDS St 32.prj (project) ---

Proj Title=UDS St 32 Base Level Engineering
Current Plan=p01
Default Exp/Contr=0.3,0.1
English Units
Geom File=g01
Flow File=f01
Plan File=p01
Y Axis Title=Elevation
X Axis Title(PF)=Main Channel Distance
X Axis Title(XS)=Station
BEGIN DESCRIPTION:
UDS St 32
END DESCRIPTION:
DSS Export Rating Curves= 0
DSS Export Rating Curve Sorted= 0
DSS Export Volume Flow Curves= 0
DXF OffsetX= 0
DXF OffsetY= 0
DXF ScaleX= 1
DXF ScaleY= 10

--- UDS St 32.p01 (plan) ---

Plan Title=Multiple Run
Short Identifier=Multiple
Geom File=g01
Flow File=f01
Subcritical Flow
K Sum by GR= 0
Std Step Tol= 0.01
Critical Tol= 0.01
Num of Std Step Trials= 20
Max Error Tol= 0.3
Flow Tol Ratio= 0.001
Split Flow NTrial= 30
Split Flow Tol= 0.02
Split Flow Ratio= 0.02
Log Output Level= 0
Friction Slope Method= 1
Unsteady Friction Slope Method= 2
Unsteady Bridges Friction Slope Method= 1
Parabolic Critical Depth
Global Vel Dist=  1 , 1 , 1
Global Log Level= 0
CheckData=True
Encroach Param= -1, 0, 0, 0
BEGIN DESCRIPTION:
Multiple Run
END DESCRIPTION:

--- UDS St 32.f01 (steady flow) ---

Flow Title=Multiple
Number of Profiles=7
Profile Names=10-year,25-year,50-year,1pct_min,100-year,1pct_plu,500-year
River Rch & RM= UDS St 32,Reach-1,4018
     907    1292    1623    1013    2022    4034    3144
River Rch & RM= UDS St 32,Reach-1,1595
     916    1305    1639    1023    2041    4073    3172
Boundary for River Rch & Prof#=UDS St 32,Reach-1,1
Up Type=0
Dn Type=3
Dn Slope=0.005
Boundary for River Rch & Prof#=UDS St 32,Reach-1,2
Up Type=0
Dn Type=3
Dn Slope=0.005
Boundary for River Rch & Prof#=UDS St 32,Reach-1,3
Up Type=0
Dn Type=3
Dn Slope=0.005
Boundary for River Rch & Prof#=UDS St 32,Reach-1,4
Up Type=0
Dn Type=3
Dn Slope=0.005
Boundary for River Rch & Prof#=UDS St 32,Reach-1,5
Up Type=0
Dn Type=3
Dn Slope=0.005
Boundary for River Rch & Prof#=UDS St 32,Reach-1,6
Up Type=0
Dn Type=3
Dn Slope=0.005
Boundary for River Rch & Prof#=UDS St 32,Reach-1,7
Up Type=0
Dn Type=3
Dn Slope=0.005

--- UDS St 32.g01 (geometry) ---

Geom Title=Existing Conditions
Program Version=4.10

River Reach=UDS St 32       ,Reach-1
Reach XY= 30
        2262029.        7196710.      2261978.87      7196587.33
      2261979.68      7196323.92      2262029.43      7196225.18
      2262027.44      7196069.59      2261986.81      7196006.59
      2262084.62      7195865.62      2262223.54      7195762.47
      2262236.81      7195553.79      2262373.38      7195454.38
      2262473.16      7195312.29      2262527.64      7195200.35
      2262532.75      7195011.55      2262677.64      7194750.35
      2262678.48      7194575.22      2262627.64      7194319.65
      2262536.53      7194160.01      2262626.61      7193954.47
      2262631.36      7193815.52      2262732.51      7193618.48
      2262868.49      7193519.81      2262884.52      7193407.57
      2263023.53      7193262.45      2263032.76      7193111.56
      2263275.24      7192708.44      2263282.56      7192561.47
      2263373.46      7192462.42      2263389.52      7192350.21
      2263623.17       7192112.3        2263729.        7191810.

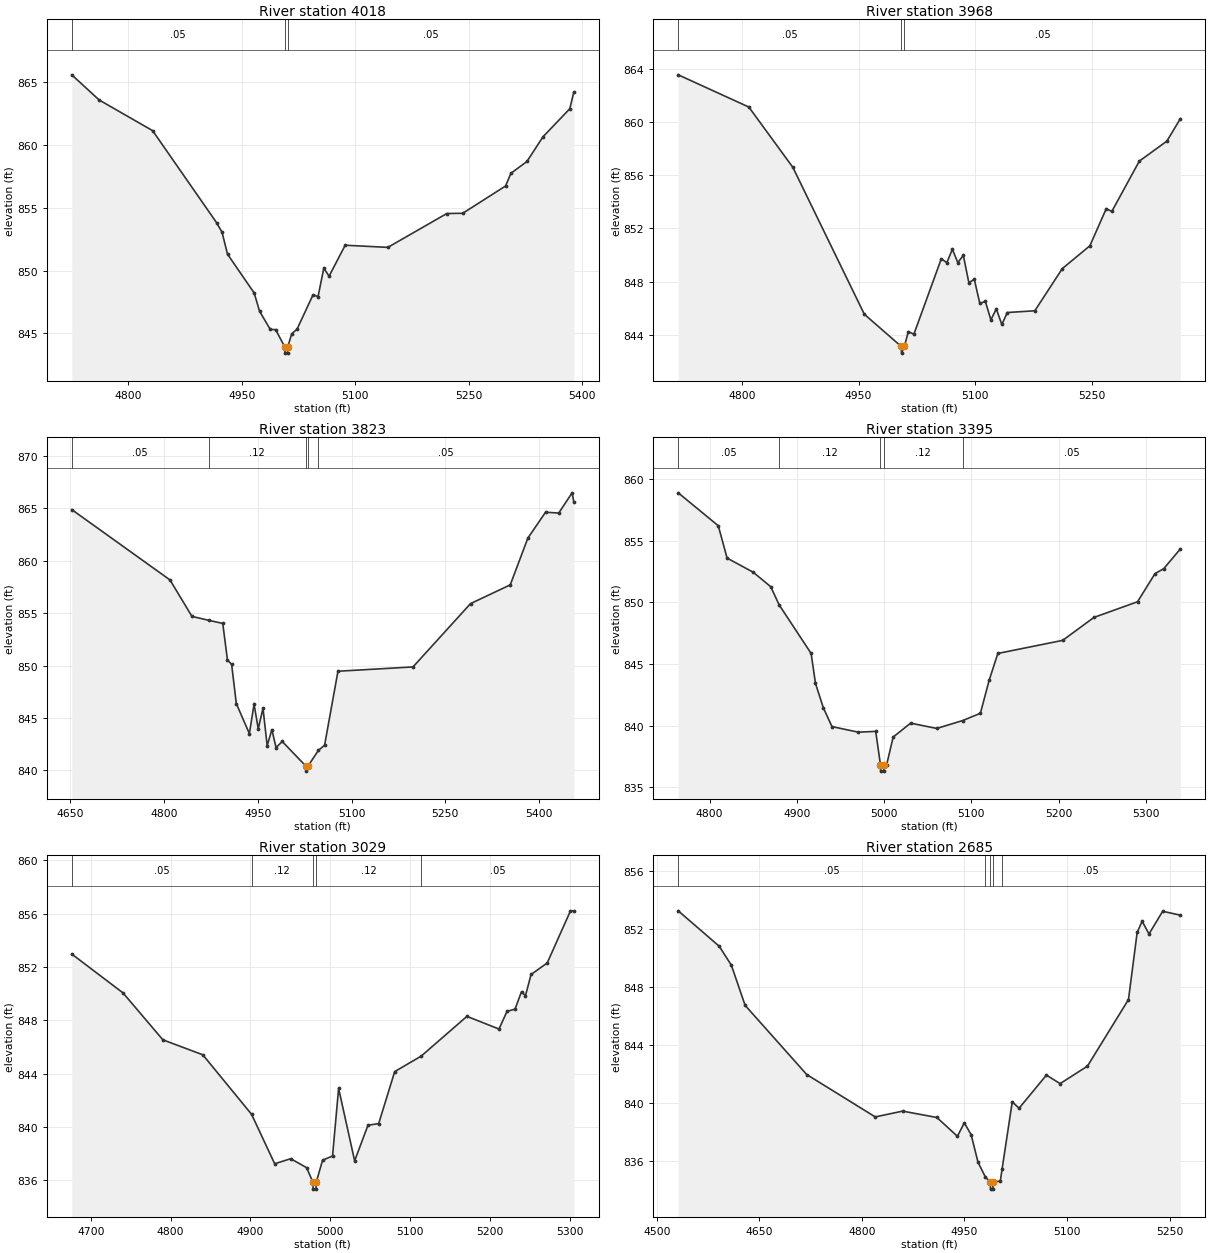
Type RM Length L Ch R = 1 ,4018    ,50,50,50
BEGIN DESCRIPTION:
UDS St 32 9.2
END DESCRIPTION:
XS GIS Cut Line= 2
      2262677.22      7195462.86      2262203.07      7194998.31
#Sta/Elev= 30
    4725  865.56  4761.2  863.56  4831.9  861.12  4916.7  853.78  4923.7  853.04
  4930.9   851.3  4966.2  848.21  4973.3  846.76  4987.5  845.31  4994.5   845.3
  5006.6  843.93  5006.9  843.43  5010.4  843.43  5010.6  843.93  5015.8  844.97
  5022.8  845.33    5044  848.07  5050.6  847.92  5058.2  850.18  5065.2  849.55
  5086.5  852.01  5142.9  851.84  5220.8  854.53  5241.9  854.55  5298.5  856.72
  5305.6  857.73  5326.8  858.67  5348.1  860.64  5383.4  862.86  5388.8  864.19
#Mann= 3 ,-1 , 0
    4725     .05       0  5006.6    .033       0  5010.6     .05       0
Bank Sta=5006.6,5010.6
XS Rating Curve= 0 ,0
Exp/Cntr=0.3,0.1

Type RM Length L Ch R = 1 ,3968    ,145,145,145
BEGIN DESCRIPTION:
UDS St 32 9.1
END DESCRIPTION:
XS GIS Cut Line= 2
      2262707.66      7195429.81      2262252.72      7194971.74
#Sta/Elev= 30
  4718.2  863.54    4809  861.12  4865.6  856.59  4957.5  845.56    5005  843.14
  5005.3  842.64    5009  843.14  5014.1  844.26  5021.2  844.06  5056.5  849.73
  5063.6  849.43  5070.7  850.44  5077.7  849.44  5084.8  849.98  5091.9  847.93
  5098.9  848.18    5106  846.37  5113.1  846.53  5120.2  845.14  5127.2  845.96
  5134.3  844.79  5141.4  845.69  5176.7  845.82  5212.1  848.99  5247.5   850.7
  5268.6  853.49  5275.7  853.28  5311.1  857.06  5346.5  858.56  5363.8  860.24
#Mann= 3 ,-1 , 0
  4718.2     .05       0    5005    .033       0    5009     .05       0
#XS Ineff= 2 , 0
       0                  5070.7       0  850.44
Permanent Ineff=
       F       F
Bank Sta=5005,5009
XS Rating Curve= 0 ,0
Exp/Cntr=0.3,0.1

Type RM Length L Ch R = 1 ,3823    ,428,428,428
BEGIN DESCRIPTION:
UDS St 32 9.0
END DESCRIPTION:
XS GIS Cut Line= 3
      2262761.02       7195349.7      2262536.76      7195098.28
       2262200.9      7194774.09
#Sta/Elev= 30
  4652.1  864.89  4809.3  858.18  4844.5   854.7  4871.1  854.33  4893.8  854.03
  4901.3  850.55    4908  850.12  4915.5  846.38  4936.4  843.52  4943.9  846.33
  4950.6  843.98  4958.2  845.94  4964.9  842.37  4972.4   843.9  4979.1  842.19
    4989  842.77  5026.5  840.44  5026.8  839.94  5030.5  840.44  5046.9  841.92
  5056.8  842.41  5078.2  849.47  5198.3  849.88  5290.4  855.92    5354  857.71
  5382.2  862.17  5410.5  864.64  5431.6  864.56    5453  866.49  5455.8  865.62
#Mann= 5 ,-1 , 0
  4652.1     .05       0  4871.1     .12       0  5026.5     .07       0
  5030.5     .12       0  5046.9     .05       0
Bank Sta=5026.5,5030.5
XS Rating Curve= 0 ,0
Exp/Cntr=0.3,0.1

Type RM Length L Ch R = 1 ,3395    ,366,366,366
BEGIN DESCRIPTION:
UDS St 32 8.0
END DESCRIPTION:
XS GIS Cut Line= 3
      2262914.85      7194724.26        2262679.        7194710.
      2262339.99      7194701.67
#Sta/Elev= 30
  4764.1  858.88    4810  856.21  4820.1  853.59  4850.1  852.44  4870.1  851.27
  4879.8  849.79  4916.4  845.86  4921.4  843.43  4930.3  841.47  4940.3  839.93
  4970.3  839.48  4990.4  839.54  4995.9  836.82  4996.1  836.32  4999.6  836.32
  4999.9  836.82  5002.9  836.82  5010.4  839.08  5030.4  840.21  5060.4  839.78
  5090.1  840.42  5110.4  841.01  5120.4  843.68  5130.4  845.86  5204.7  846.92
  5240.5  848.78  5290.5  850.05  5310.5  852.33  5320.5  852.73  5339.5  854.33
#Mann= 5 ,-1 , 0
  4764.1     .05       0  4879.8     .12       0  4995.9     .07       0
  4999.9     .12       0  5090.1     .05       0
Bank Sta=4995.9,4999.9
XS Rating Curve= 0 ,0
Exp/Cntr=0.3,0.1

Type RM Length L Ch R = 1 ,3029    ,344,344,344
BEGIN DESCRIPTION:
UDS St 32 7.0
END DESCRIPTION:
XS GIS Cut Line= 3
      2262953.17       7194350.6        2262629.        7194360.
      2262325.73      7194391.45
#Sta/Elev= 30
  4676.1  852.97  4740.3  850.06  4790.3  846.54  4840.3  845.42  4901.4  840.96
  4930.4  837.25  4950.4  837.63  4970.4  836.96  4978.4  835.85  4978.6  835.35
  4982.1  835.35  4982.4  835.85  4990.4  837.52  5002.9  837.83  5010.5   842.9
  5030.6  837.47  5047.3  840.14  5060.7  840.26  5080.8  844.16    5114  845.32
  5171.3   848.3  5211.5  847.35  5221.6  848.68  5231.6  848.84  5239.7  850.15
  5244.7  849.85  5251.7  851.44  5271.9   852.3  5301.1  856.21  5305.3  856.21
#Mann= 5 ,-1 , 0
  4676.1     .05       0  4901.4     .12       0  4978.4     .07       0
  4982.4     .12       0    5114     .05       0
Bank Sta=4978.4,4982.4
XS Rating Curve= 0 ,0
Exp/Cntr=0.3,0.1

Type RM Length L Ch R = 1 ,2685    ,342,342,342
BEGIN DESCRIPTION:
UDS St 32 6.0
END DESCRIPTION:
XS GIS Cut Line= 3
      2263046.59      7194088.48        2262579.        7194060.
      2262313.24      7194066.63
#Sta/Elev= 30
  4531.5  853.28  4591.5  850.83  4609.2  849.52  4629.3  846.75  4719.4  841.97
  4819.6  839.04  4859.7  839.44  4909.8     839  4939.8   837.7  4949.9  838.63
  4959.9  837.81  4969.9  835.91  4980.8  834.88  4987.9  834.55  4988.2  834.05
  4991.7  834.05  4991.9  834.55  5002.5   834.6  5005.2  835.45    5020  840.08
    5030  839.64    5070  841.93    5090  841.34    5130  842.55    5190  847.15
  5202.7  851.79    5210  852.56    5220  851.68    5240  853.25  5265.8  852.98
#Mann= 5 ,-1 , 0
  4531.5     .05       0  4980.8     .12       0  4987.9     .07       0
  4991.9     .12       0  5005.2     .05       0
Bank Sta=4987.9,4991.9
XS Rating Curve= 0 ,0
Exp/Cntr=0.3,0.1

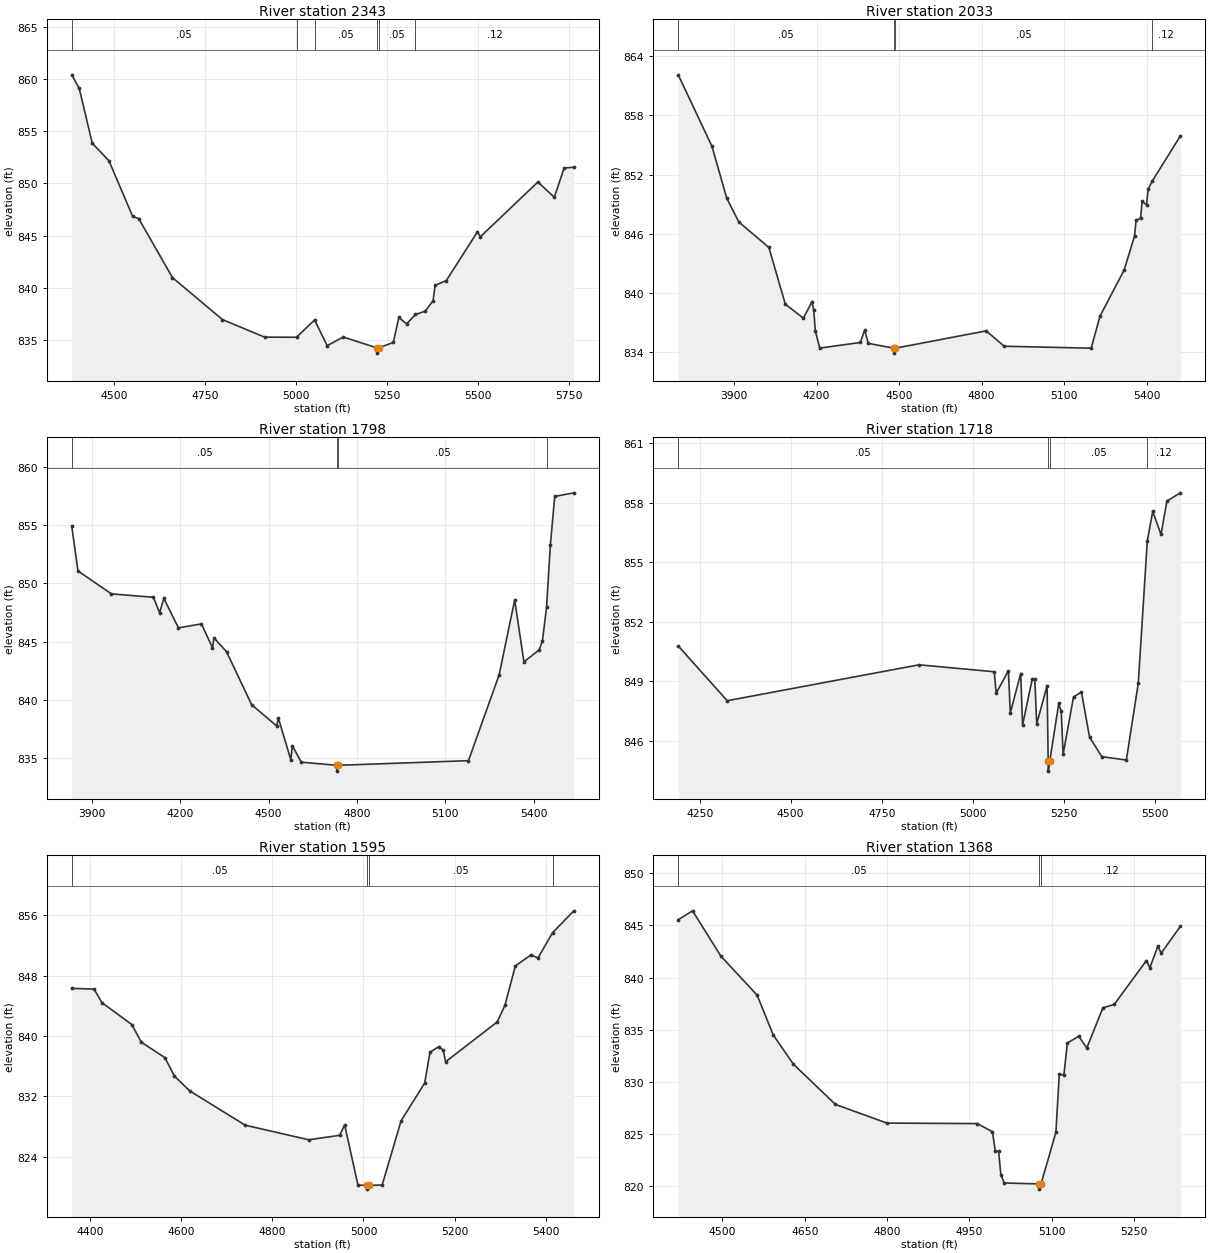
Type RM Length L Ch R = 1 ,2343    ,310,310,310
BEGIN DESCRIPTION:
UDS St 32 5.0
END DESCRIPTION:
XS GIS Cut Line= 4
      2263088.56      7194166.84       2263047.2      7194004.69
      2262671.16      7193745.42      2262035.84      7193337.87
#Sta/Elev= 30
  4383.3  860.39  4403.8  859.09  4439.5  853.85  4485.5  852.16  4550.5  846.85
  4567.2  846.63  4659.8  840.99  4797.1  836.97  4912.9  835.29  5000.5  835.28
  5050.2  836.94  5084.7  834.47  5128.8   835.3  5221.8  834.26  5222.1  833.76
  5225.8  834.26  5266.4  834.78  5281.6  837.17  5302.8  836.56  5327.3  837.46
  5354.3  837.78  5375.5  838.77  5381.4  840.25  5411.8   840.7  5497.1  845.35
  5505.6   844.9  5663.4  850.13  5708.5  848.68  5735.6  851.47  5762.2  851.55
#Mann= 6 ,-1 , 0
  4383.3     .05       0  5000.5     .12       0  5050.2     .05       0
  5221.8    .033       0  5225.8     .05       0  5327.3     .12       0
#XS Ineff= 2 , 0
       0                  5663.4       0  850.13
Permanent Ineff=
       F       F
Bank Sta=5221.8,5225.8
XS Rating Curve= 0 ,0
Exp/Cntr=0.3,0.1

Type RM Length L Ch R = 1 ,2033    ,235,235,235
BEGIN DESCRIPTION:
UDS St 32 4.1
END DESCRIPTION:
XS GIS Cut Line= 2
      2264005.51      7194151.43      2262403.59      7193277.71
#Sta/Elev= 30
  3697.2  862.13  3819.6  854.88  3873.7  849.59  3917.4  847.19  4026.6   844.6
  4086.4  838.84  4151.9  837.42    4183  839.08  4189.8  838.22  4195.5   836.1
  4211.7  834.38  4358.8  834.95  4374.9  836.21  4388.1  834.86  4482.1  834.37
  4482.4  833.87  4486.1  834.37  4816.4  836.13  4881.9  834.57    5198  834.37
  5230.2  837.64  5317.6   842.3  5355.5  845.76  5361.2  847.35  5377.4  847.58
  5383.1  849.27  5399.2  848.93  5404.9  850.52    5420  851.34  5521.9  855.92
#Mann= 4 ,-1 , 0
  3697.2     .05       0  4482.1    .033       0  4486.1     .05       0
    5420     .12       0
Bank Sta=4482.1,4486.1
XS Rating Curve= 0 ,0
Exp/Cntr=0.3,0.1

Type RM Length L Ch R = 1 ,1798    ,80,80,80
BEGIN DESCRIPTION:
UDS St 32 4.0
END DESCRIPTION:
XS GIS Cut Line= 4
      2263949.01      7193829.13       2263685.1      7193497.58
      2262959.66      7193329.03      2262446.91      7193171.93
#Sta/Elev= 30
  3831.8  854.92  3852.9  851.07  3966.6   849.1  4109.1  848.81    4130  847.47
  4144.4  848.71    4194  846.18  4272.1  846.52  4309.6  844.48  4314.7  845.32
  4357.3  844.13  4442.6  839.57  4527.8  837.74    4533  838.45  4575.6  834.84
  4580.7  836.05  4610.9  834.63  4731.9  834.36  4732.3  833.86  4736.2  834.36
  5178.8  834.76  5282.7  842.12  5335.7  848.57  5367.1  843.26  5418.9  844.28
  5429.8  845.04  5443.9  847.93  5456.9   853.3  5471.7  857.48  5536.6  857.79
#Mann= 4 ,-1 , 0
  3831.8     .05       0  4731.9    .033       0  4736.2     .05       0
  5443.9     .12       0
Bank Sta=4731.9,4736.2
XS Rating Curve= 0 ,0
Exp/Cntr=0.3,0.1

Type RM Length L Ch R = 1 ,1718    ,123,123,123
BEGIN DESCRIPTION:
UDS St 32 3.2
END DESCRIPTION:
XS GIS Cut Line= 3
      2263799.34      7193474.78      2263015.73      7193272.69
      2262468.05      7193114.92
#Sta/Elev= 30
  4191.1  850.77  4325.7  848.01  4852.4  849.82  5059.2  849.47  5064.4  848.39
  5098.1  849.52  5103.3  847.39  5131.8  849.38    5137  846.78  5163.5   849.1
  5170.6   849.1  5175.8  846.84  5204.3  848.76  5207.4  844.96  5207.7  844.46
  5211.7  844.96  5236.3  847.87  5243.2  847.47  5248.4  845.31  5276.9   848.2
  5298.7  848.45  5320.9  846.18  5354.6  845.19    5422  845.02  5454.8  848.88
  5479.6  856.06  5494.5  857.55  5517.3  856.39  5533.4  858.07  5570.3  858.49
#Mann= 4 ,-1 , 0
  4191.1     .05       0  5207.4    .033       0  5211.7     .05       0
  5479.6     .12       0
Bank Sta=5207.4,5211.7
XS Rating Curve= 0 ,0
Exp/Cntr=0.3,0.1

Type RM Length L Ch R = 1 ,1595    ,227,227,227
BEGIN DESCRIPTION:
UDS St 32 3.1
END DESCRIPTION:
XS GIS Cut Line= 2
      2263646.28      7193323.08      2262583.13        7193030.
#Sta/Elev= 30
  4359.3   846.3  4408.3   846.2  4425.6   844.4  4491.3   841.5  4512.1  839.16
  4563.9  837.12  4584.7  834.68  4618.2  832.72  4740.3  828.17  4879.6  826.24
  4947.7  826.83  4958.7  828.22  4987.9  820.23  5007.8   820.2  5008.2   819.7
  5012.1   820.2  5041.1  820.24  5082.6  828.75  5134.5  833.76  5146.1  837.84
  5165.6  838.58  5175.3  838.08  5180.5  836.57    5294  841.86  5310.8  844.07
  5333.6  849.27  5367.9  850.73  5383.4  850.33  5415.4  853.68  5462.1  856.57
#Mann= 4 ,-1 , 0
  4359.3     .05       0  5007.8    .033       0  5012.1     .05       0
  5415.4     .12       0
Bank Sta=5007.8,5012.1
XS Rating Curve= 0 ,0
Exp/Cntr=0.3,0.1

Type RM Length L Ch R = 1 ,1368    ,278,278,278
BEGIN DESCRIPTION:
UDS St 32 3.0
END DESCRIPTION:
XS GIS Cut Line= 3
       2263642.1       7193231.7        2263129.        7192960.
      2262860.28       7192761.3
#Sta/Elev= 30
  4419.4  845.55  4445.5   846.4  4497.1  842.05  4563.1  838.31  4592.6  834.48
  4629.1  831.69  4705.8  827.82  4799.5  826.03  4964.2  825.98  4991.8   825.2
  4997.2  823.32  5003.1  823.32  5007.3  821.06  5013.5  820.28  5076.1  820.19
  5076.5  819.69  5080.4  820.19  5107.5  825.13  5113.7  830.71  5122.1  830.65
  5128.4  833.72  5149.2  834.36  5163.8  833.23  5193.1  837.09  5213.9  837.42
  5272.5  841.63  5278.7  840.93  5293.3  843.01  5299.5  842.34  5334.2  844.91
#Mann= 3 ,-1 , 0
  4419.4     .05       0  5076.1    .033       0  5080.4     .12       0
Bank Sta=5076.1,5080.4
XS Rating Curve= 0 ,0
Exp/Cntr=0.3,0.1

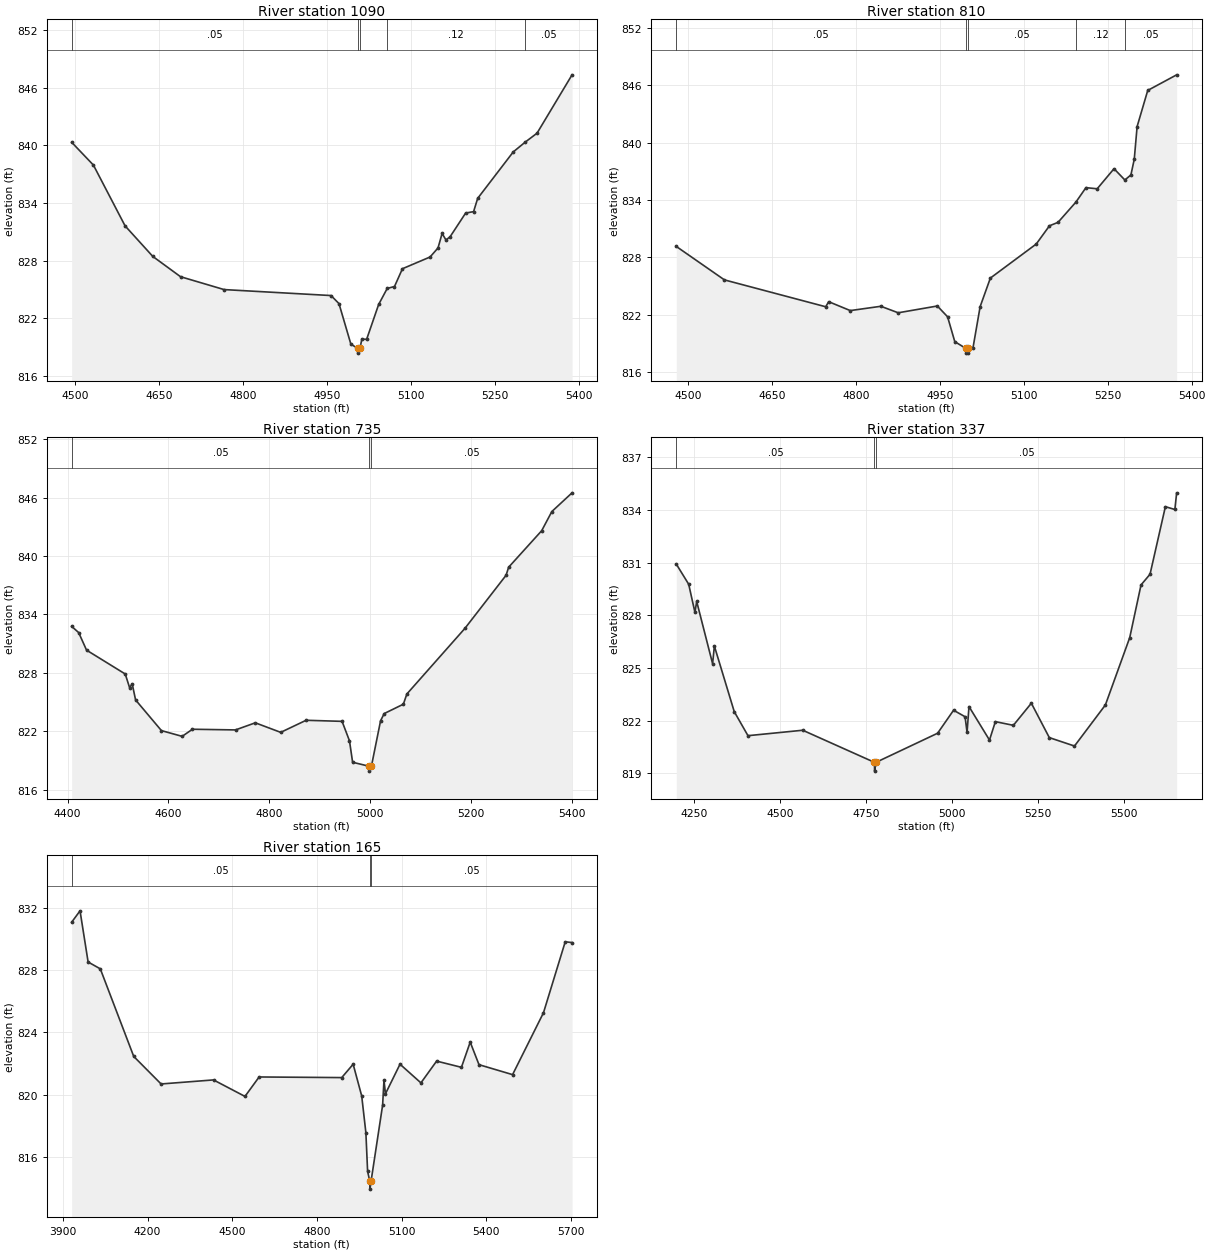
Type RM Length L Ch R = 1 ,1090    ,280,280,280
BEGIN DESCRIPTION:
UDS St 32 2.0
END DESCRIPTION:
XS GIS Cut Line= 3
      2263619.83        7193084.      2263252.86       7192717.3
      2262980.73      7192459.99
#Sta/Elev= 30
  4494.4  840.32  4533.2  837.95  4589.7  831.63  4639.2  828.45  4688.7  826.34
  4766.5     825  4957.4  824.38  4971.6  823.54  4992.8  819.33  5004.7  818.89
  5005.1  818.39  5009.1  818.89  5012.4  819.84    5021  819.83  5042.4  823.45
  5057.7  825.12  5070.7  825.32  5084.9  827.17  5134.2  828.39  5148.4  829.33
  5155.7  830.84  5162.5  830.17  5169.8  830.48  5197.7  832.96  5211.9  833.11
  5219.2  834.49  5282.7  839.32  5304.3  840.35  5325.2  841.27  5387.7  847.34
#Mann= 5 ,-1 , 0
  4494.4     .05       0  5004.7     .04       0  5009.1     .05       0
  5057.7     .12       0  5304.3     .05       0
Bank Sta=5004.7,5009.1
XS Rating Curve= 0 ,0
Exp/Cntr=0.3,0.1

Type RM Length L Ch R = 1 ,810     ,75,75,75
BEGIN DESCRIPTION:
UDS St 32 1.2
END DESCRIPTION:
XS GIS Cut Line= 4
      2263583.19      7192923.77      2263441.69      7192517.74
      2263213.36      7192421.24      2262997.54      7192442.24
#Sta/Elev= 30
  4478.5  829.15  4564.6  825.65  4745.7  822.84    4751  823.37  4789.6  822.44
  4844.3  822.89  4875.3  822.21  4945.3  822.92  4963.6  821.79  4976.5  819.19
  4996.1  818.49  4996.5  817.99  5000.1  817.99  5000.5  818.49  5009.1  818.56
  5021.8  822.85  5040.1  825.84  5122.1   829.4  5145.8  831.31  5161.1  831.67
  5193.1  833.79    5211   835.3  5231.1  835.18  5261.2  837.28  5280.6   836.1
  5291.4  836.63  5297.4  838.27  5302.5  841.69  5321.5  845.47  5373.2   847.1
#Mann= 5 ,-1 , 0
  4478.5     .05       0  4996.1    .033       0  5000.5     .05       0
  5193.1     .12       0  5280.6     .05       0
Bank Sta=4996.1,5000.5
XS Rating Curve= 0 ,0
Exp/Cntr=0.3,0.1

Type RM Length L Ch R = 1 ,735     ,398,398,398
BEGIN DESCRIPTION:
UDS St 32 1.1
END DESCRIPTION:
XS GIS Cut Line= 5
      2263670.73      7192883.52      2263597.38      7192566.79
      2263384.54      7192415.49      2263165.47      7192348.54
      2262989.18      7192370.73
#Sta/Elev= 30
    4408  832.77  4421.9  832.13  4437.5  830.33  4514.3  827.88  4522.9  826.48
  4528.1  826.87  4534.8  825.22  4586.1  822.07  4627.2  821.48  4647.7  822.21
  4733.1  822.14  4772.4  822.87  4822.8  821.89  4873.2  823.13  4944.6  823.02
  4959.3  821.02  4965.5  818.82  4998.4  818.41  4998.8  817.91  5002.8  818.41
    5021  823.08  5028.2  823.82  5066.2  824.78  5073.2  825.83  5188.3  832.56
  5270.1  838.02  5275.1  838.84  5340.7  842.59  5360.9  844.56    5401  846.48
#Mann= 3 ,-1 , 0
    4408     .05       0  4998.4    .033       0  5002.8     .05       0
Bank Sta=4998.4,5002.8
XS Rating Curve= 0 ,0
Exp/Cntr=0.3,0.1

Type RM Length L Ch R = 1 ,337     ,172,172,172
BEGIN DESCRIPTION:
UDS St 32 1.0
END DESCRIPTION:
XS GIS Cut Line= 4
      2263784.99      7192895.38      2263632.36      7192119.07
      2263525.37      7192066.28        2263005.      7192225.29
#Sta/Elev= 30
  4197.4  830.92  4233.5  829.77  4251.6  828.17  4256.7  828.79    4303  825.24
  4308.1  826.25  4365.9  822.51  4405.8  821.14    4565  821.45  4773.5  819.62
  4773.9  819.12  4777.9  819.62  4957.1  821.28  5003.5  822.59  5036.9  822.22
  5042.7  821.33  5048.3   822.8  5107.9  820.89    5125  821.94  5177.3  821.73
  5229.6  822.99  5281.8  821.03    5355  820.55  5444.8  822.89  5515.6  826.73
  5548.4  829.73  5574.6  830.34  5619.2  834.19  5646.8  834.03    5652  834.98
#Mann= 3 ,-1 , 0
  4197.4     .05       0  4773.5    .033       0  4777.9     .05       0
#XS Ineff= 2 , 0
       0                  5229.6       0  822.99
Permanent Ineff=
       F       F
Bank Sta=4773.5,4777.9
XS Rating Curve= 0 ,0
Exp/Cntr=0.3,0.1

Type RM Length L Ch R = 1 ,165     ,0,0,0
BEGIN DESCRIPTION:
UDS St 32 0.9
END DESCRIPTION:
XS GIS Cut Line= 4
      2263847.59      7192997.68      2263704.61      7191965.33
      2263650.27      7191951.84      2263013.42      7192173.75
#Sta/Elev= 30
  3931.4  831.08    3961  831.81  3989.6  828.52  4032.8  828.08  4151.2  822.45
  4248.1  820.68  4433.8  820.94  4545.3  819.88  4595.4  821.13  4888.1  821.09
  4928.5  821.95  4958.8  819.91  4973.6  817.55  4979.7  815.07  4987.5  814.42
  4987.9  813.92  4991.9  814.42  5032.9  819.32  5037.7  820.92    5043  820.05
  5094.5  821.95  5168.6  820.75  5224.2  822.15  5312.1  821.75  5343.2  823.37
  5374.3  821.92  5493.3  821.28  5602.8  825.26  5679.8  829.82    5704  829.77
#Mann= 3 ,-1 , 0
  3931.4     .05       0  4987.5    .033       0  4991.9     .05       0
#XS Ineff= 2 , 0
       0                  5343.2       0  823.37
Permanent Ineff=
       F       F
Bank Sta=4987.5,4991.9
XS Rating Curve= 0 ,0
Exp/Cntr=0.3,0.1

Chan Stop Cuts=-1
Use User Specified Reach Order=0
Composite Channel Slope=5