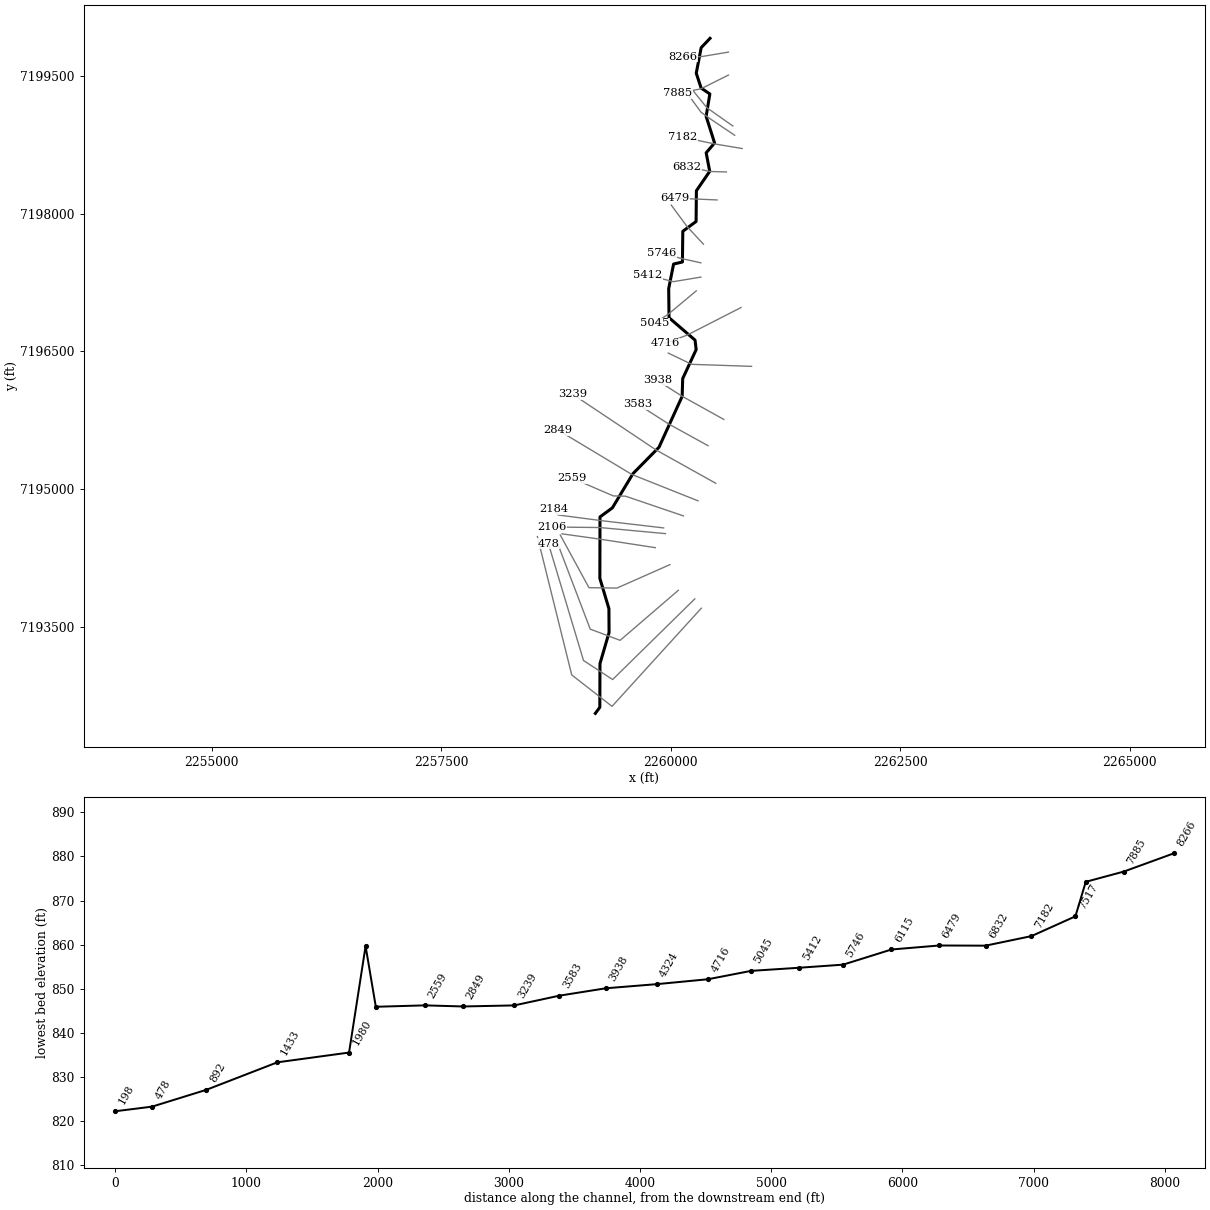
--- UDS St 33.prj (project) ---

Proj Title=UDS St 33 Base Level Engineering
Current Plan=p01
Default Exp/Contr=0.3,0.1
English Units
Geom File=g01
Flow File=f01
Plan File=p01
BEGIN DESCRIPTION:
UDS St 33
END DESCRIPTION:

--- UDS St 33.p01 (plan) ---

Plan Title=Multiple Run
Short Identifier=Multiple
Geom File=g01
Flow File=f01
Subcritical Flow
K Sum by GR= 0
Std Step Tol= 0.01
Critical Tol= 0.01
Num of Std Step Trials= 20
Max Error Tol= 0.3
Flow Tol Ratio= 0.001
Split Flow NTrial= 30
Split Flow Tol= 0.02
Split Flow Ratio= 0.02
Log Output Level= 0
Friction Slope Method= 1
Unsteady Friction Slope Method= 2
Unsteady Bridges Friction Slope Method= 1
Parabolic Critical Depth
Global Vel Dist=  1 , 1 , 1
Global Log Level= 0
CheckData=True
Encroach Param= -1, 0, 0, 0
BEGIN DESCRIPTION:
Multiple Run
END DESCRIPTION:

--- UDS St 33.f01 (steady flow) ---

Flow Title=Multiple
Number of Profiles=7
Profile Names=10-year,25-year,50-year,1pct_min,100-year,1pct_plu,500-year
River Rch & RM= UDS St 33,Reach-1,8266
     657     915    1131     695    1386    2766    2088
River Rch & RM= UDS St 33,Reach-1,1980
     675     941    1165     717    1430    2853    2159
River Rch & RM= UDS St 33,Reach-1,892
     686     957    1185     729    1455    2903    2197
Boundary for River Rch & Prof#=UDS St 33,Reach-1,1
Up Type=0
Dn Type=3
Dn Slope=0.005
Boundary for River Rch & Prof#=UDS St 33,Reach-1,2
Up Type=0
Dn Type=3
Dn Slope=0.005
Boundary for River Rch & Prof#=UDS St 33,Reach-1,3
Up Type=0
Dn Type=3
Dn Slope=0.005
Boundary for River Rch & Prof#=UDS St 33,Reach-1,4
Up Type=0
Dn Type=3
Dn Slope=0.005
Boundary for River Rch & Prof#=UDS St 33,Reach-1,5
Up Type=0
Dn Type=3
Dn Slope=0.005
Boundary for River Rch & Prof#=UDS St 33,Reach-1,6
Up Type=0
Dn Type=3
Dn Slope=0.005
Boundary for River Rch & Prof#=UDS St 33,Reach-1,7
Up Type=0
Dn Type=3
Dn Slope=0.005

--- UDS St 33.g01 (geometry) ---

Geom Title=Existing Conditions

River Reach=UDS St 33,Reach-1
Reach XY= 30
      2260429.00      7199910.00      2260332.48      7199808.56
      2260278.72      7199530.18      2260332.35      7199368.06
      2260426.99      7199304.32      2260386.56      7199060.00
      2260478.39      7198770.62      2260386.81      7198663.41
      2260425.46      7198461.47      2260280.36      7198250.35
      2260277.02      7197915.67      2260132.45      7197808.75
      2260128.18      7197474.45      2260032.00      7197452.00
      2259978.80      7197185.08      2259982.23      7196868.01
      2260265.74      7196623.63      2260277.90      7196520.56
      2260131.18      7196204.55      2260125.45      7196011.47
      2259873.24      7195457.47      2259589.78      7195169.68
      2259365.32      7194796.98      2259230.62      7194698.17
      2259229.07      7194030.03      2259327.78      7193699.50
      2259329.36      7193439.85      2259230.38      7193100.34
      2259228.64      7192625.15      2259180.04      7192558.96

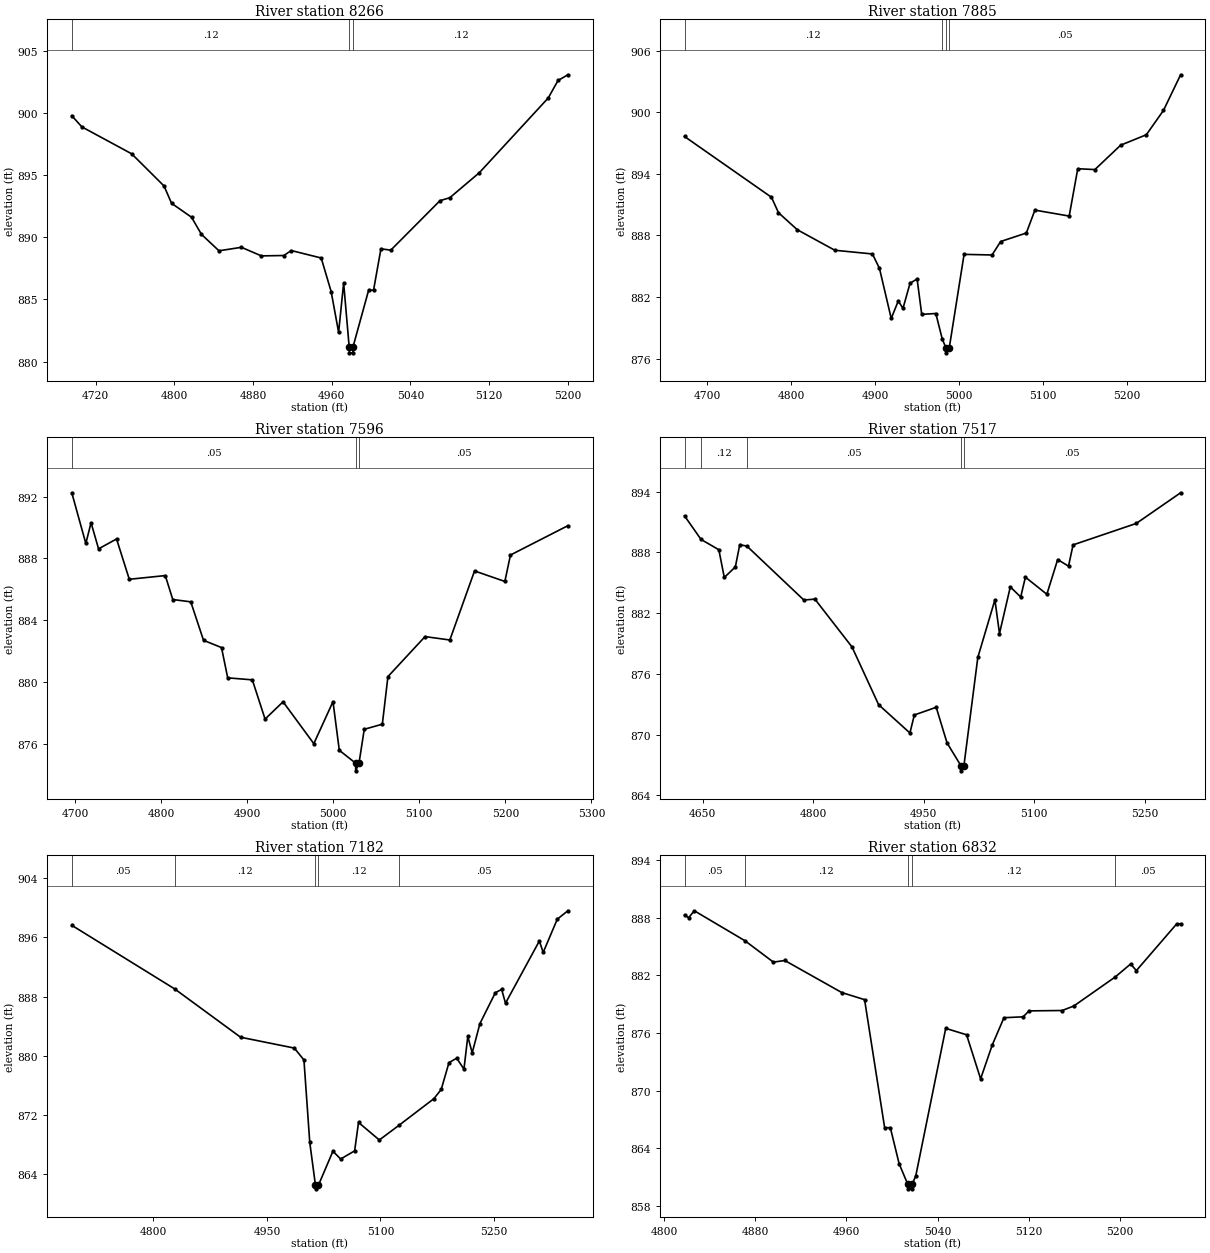
Type RM Length L Ch R = 1,8266,381,381,381
BEGIN DESCRIPTION:
UDS St 33 21.0
END DESCRIPTION:
XS GIS Cut Line= 3
      2260629.05      7199760.01      2260329.00      7199710.00
      2260128.98      7199710.00
#Sta/Elev= 30
  4695.8  899.78  4706.0  898.88  4756.7  896.71  4789.6  894.12  4797.2  892.73
  4817.5  891.61  4827.6  890.23  4845.4  888.91  4868.2  889.19  4888.5  888.50
  4911.3  888.53  4918.9  888.93  4949.3  888.33  4959.4  885.63  4967.0  882.35
  4972.1  886.32  4977.7  881.20  4978.0  880.70  4981.5  880.70  4981.7  881.20
  4997.5  885.74  5002.5  885.74  5010.0  889.07  5020.0  888.96  5070.0  892.94
  5080.0  893.18  5110.0  895.19  5180.0  901.20  5190.0  902.61  5200.0  903.07
#Mann=3,-1,0
  4695.8    0.12       0  4977.7    0.07       0  4981.7    0.12       0
Bank Sta=4977.7,4981.7
Exp/Cntr=0.3,0.1

Type RM Length L Ch R = 1,7885,289,289,289
BEGIN DESCRIPTION:
UDS St 33 20.0
END DESCRIPTION:
XS GIS Cut Line= 3
      2260629.04      7199510.02      2260329.00      7199360.00
      2260079.00      7199310.00
#Sta/Elev= 30
  4673.1  897.64  4776.6  891.72  4784.9  890.22  4807.3  888.56  4852.0  886.56
  4896.7  886.20  4905.1  884.80  4919.1  879.92  4927.5  881.62  4933.1  880.90
  4941.5  883.35  4949.9  883.76  4955.4  880.32  4972.2  880.40  4979.9  877.89
  4984.2  877.07  4984.4  876.57  4988.2  877.07  5005.8  886.16  5039.1  886.10
  5049.3  887.41  5079.9  888.24  5090.1  890.47  5130.9  889.89  5141.1  894.50
  5161.5  894.42  5192.1  896.79  5222.7  897.81  5243.1  900.18  5263.5  903.65
#Mann=4,-1,0
  4673.1    0.12       0  4979.9    0.05       0  4984.2   0.033       0
  4988.2    0.05       0
Bank Sta=4984.2,4988.2
Exp/Cntr=0.3,0.1

Type RM Length L Ch R = 1,7596,79,79,79
BEGIN DESCRIPTION:
UDS St 33 19.1
END DESCRIPTION:
XS GIS Cut Line= 3
      2260677.03      7198955.41      2260394.57      7199154.36
      2260249.53      7199333.78
#Sta/Elev= 30
  4696.4  892.25  4712.7  888.97  4718.8  890.31  4727.5  888.62  4748.4  889.26
  4763.2  886.65  4805.0  886.89  4813.7  885.34  4834.6  885.19  4849.4  882.70
  4870.3  882.23  4877.5  880.27  4906.1  880.14  4920.9  877.60  4941.8  878.72
  4977.5  876.01  4999.8  878.73  5007.1  875.58  5026.0  874.75  5026.2  874.25
  5030.0  874.75  5036.1  876.94  5057.1  877.27  5063.6  880.35  5106.7  882.94
  5135.5  882.72  5164.2  887.19  5199.4  886.51  5205.9  888.22  5272.6  890.12
#Mann=3,-1,0
  4696.4    0.05       0  5026.0   0.033       0  5030.0    0.05       0
Bank Sta=5026,5030
Exp/Cntr=0.3,0.1

Type RM Length L Ch R = 1,7517,335,335,335
BEGIN DESCRIPTION:
UDS St 33 19.0
END DESCRIPTION:
XS GIS Cut Line= 4
      2260697.68      7198854.12      2260429.42      7199034.55
      2260330.02      7199106.37      2260196.20      7199290.44
#Sta/Elev= 30
  4625.2  891.62  4647.6  889.29  4671.8  888.27  4679.2  885.53  4694.2  886.57
  4700.2  888.77  4709.9  888.63  4787.2  883.30  4802.2  883.39  4852.6  878.66
  4888.7  872.96  4931.2  870.16  4937.2  871.94  4966.9  872.70  4981.6  869.18
  5000.5  866.92  5000.8  866.42  5004.5  866.92  5023.4  877.63  5046.6  883.32
  5052.8  879.99  5067.5  884.60  5081.6  883.60  5088.0  885.56  5117.1  883.87
  5131.8  887.30  5146.5  886.65  5152.7  888.75  5238.5  890.87  5298.7  893.90
#Mann=5,-1,0
  4625.2    0.05       0  4647.6    0.12       0  4709.9    0.05       0
  5000.5   0.033       0  5004.5    0.05       0
Bank Sta=5000.5,5004.5
Exp/Cntr=0.3,0.1

Type RM Length L Ch R = 1,7182,350,350,350
BEGIN DESCRIPTION:
UDS St 33 18.0
END DESCRIPTION:
XS GIS Cut Line= 3
      2260778.99      7198710.00      2260479.00      7198760.00
      2260135.27      7198832.39
#Sta/Elev= 30
  4692.2  897.65  4828.1  889.03  4915.2  882.48  4986.2  881.01  4998.9  879.40
  5006.6  868.22  5014.1  862.43  5014.4  861.93  5018.1  862.43  5037.2  867.03
  5047.4  865.97  5065.9  867.08  5071.0  870.93  5098.5  868.55  5125.1  870.59
  5170.7  874.16  5180.3  875.41  5190.5  879.03  5200.7  879.64  5210.3  878.16
  5215.4  882.59  5221.2  880.36  5231.4  884.33  5251.8  888.52  5260.1  888.96
  5265.2  887.09  5309.9  895.52  5315.0  893.98  5333.6  898.48  5347.6  899.62
#Mann=5,-1,0
  4692.2    0.05       0  4828.1    0.12       0  5014.1    0.07       0
  5018.1    0.12       0  5125.1    0.05       0
Bank Sta=5014.1,5018.1
Exp/Cntr=0.3,0.1

Type RM Length L Ch R = 1,6832,353,353,353
BEGIN DESCRIPTION:
UDS St 33 17.0
END DESCRIPTION:
XS GIS Cut Line= 3
      2260606.98      7198454.88      2260429.00      7198460.00
      2260177.34      7198513.31
#Sta/Elev= 30
  4818.0  888.28  4821.6  888.01  4826.6  888.73  4871.0  885.61  4896.0  883.38
  4906.0  883.55  4956.0  880.21  4976.0  879.47  4993.6  866.13  4998.6  866.13
  5006.3  862.38  5013.8  860.26  5014.0  859.76  5017.5  859.76  5017.8  860.26
  5020.9  861.10  5047.2  876.48  5065.5  875.81  5077.8  871.22  5088.0  874.74
  5098.3  877.59  5115.1  877.68  5120.3  878.30  5149.4  878.34  5159.6  878.81
  5195.9  881.83  5209.4  883.18  5214.5  882.50  5249.9  887.37  5253.3  887.37
#Mann=5,-1,0
  4818.0    0.05       0  4871.0    0.12       0  5013.8    0.07       0
  5017.8    0.12       0  5195.9    0.05       0
Bank Sta=5013.8,5017.8
Exp/Cntr=0.3,0.1

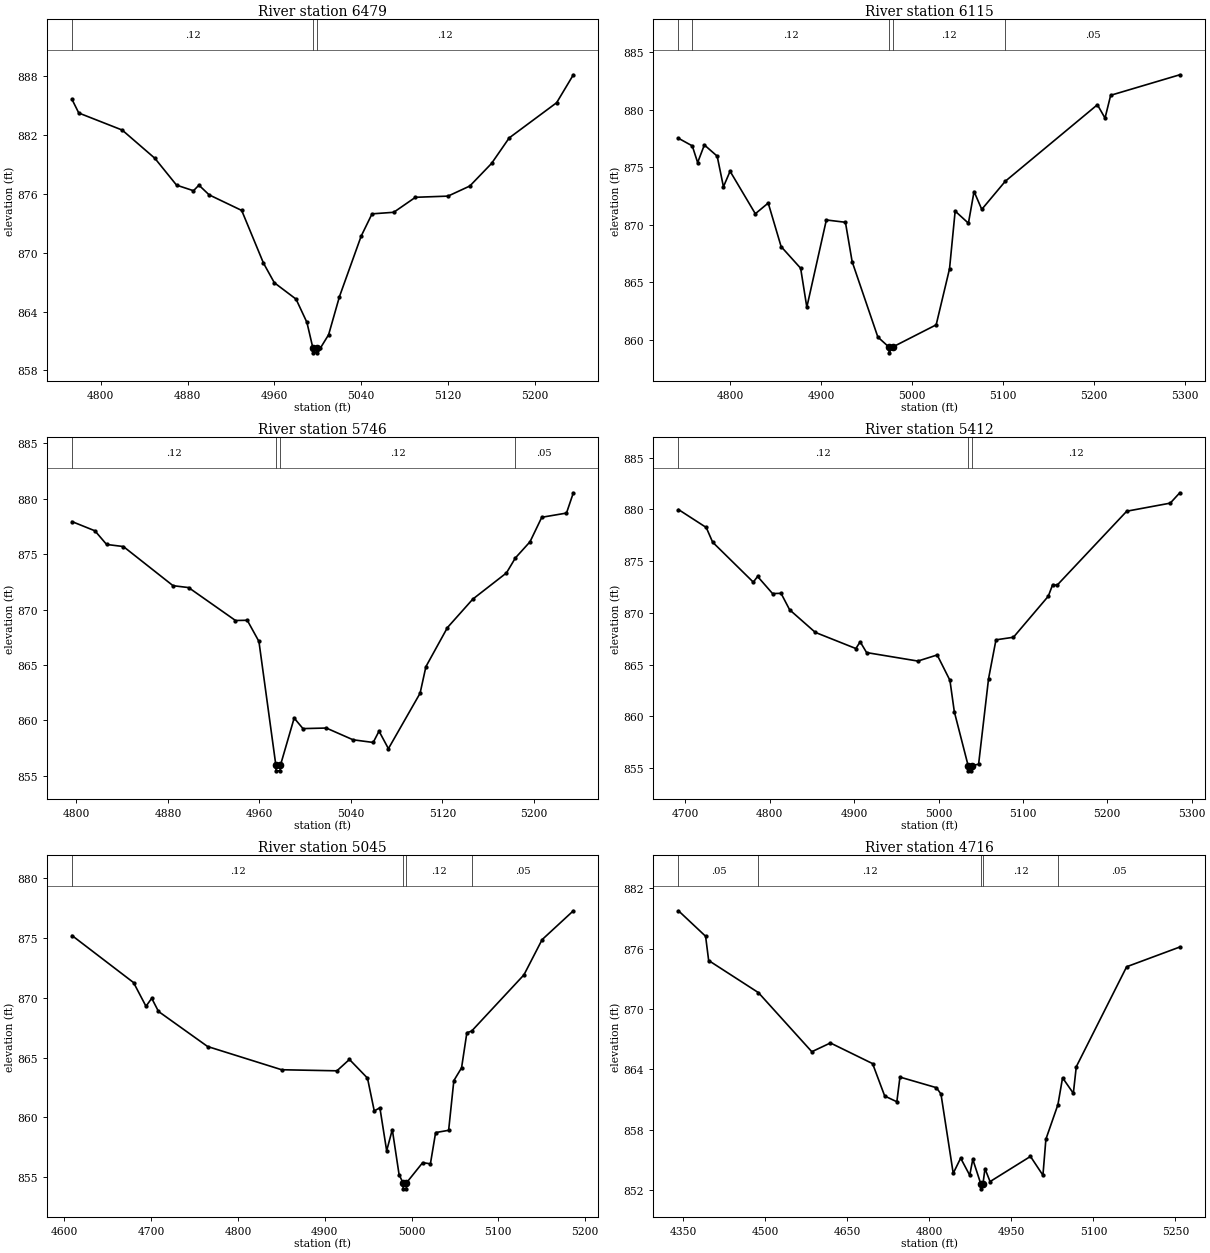
Type RM Length L Ch R = 1,6479,364,364,364
BEGIN DESCRIPTION:
UDS St 33 16.0
END DESCRIPTION:
XS GIS Cut Line= 3
      2260505.18      7198150.06      2260279.00      7198160.00
      2260043.59      7198166.63
#Sta/Elev= 30
  4773.5  885.65  4779.7  884.27  4819.7  882.53  4849.8  879.65  4869.8  876.91
  4885.4  876.34  4890.4  876.91  4899.8  875.92  4929.8  874.33  4949.9  868.95
  4959.9  866.95  4979.9  865.28  4989.9  862.91  4995.4  860.30  4995.6  859.80
  4999.1  859.80  4999.4  860.30  5002.4  860.30  5009.9  861.65  5019.9  865.54
  5039.9  871.71  5049.9  873.98  5069.9  874.14  5089.9  875.67  5119.9  875.79
  5140.0  876.82  5160.0  879.12  5176.3  881.73  5220.0  885.32  5235.4  888.17
#Mann=3,-1,0
  4773.5    0.12       0  4995.4    0.07       0  4999.4    0.12       0
Bank Sta=4995.4,4999.4
Exp/Cntr=0.3,0.1

Type RM Length L Ch R = 1,6115,369,369,369
BEGIN DESCRIPTION:
UDS St 33 15.0
END DESCRIPTION:
XS GIS Cut Line= 3
      2260357.14      7197668.19      2260179.00      7197860.00
      2260006.91      7198093.58
#Sta/Elev= 30
  4742.8  877.51  4758.0  876.85  4763.9  875.40  4771.3  876.93  4785.4  875.96
  4792.3  873.30  4799.6  874.65  4827.4  870.96  4841.6  871.89  4855.8  868.11
  4877.3  866.23  4884.1  862.85  4905.6  870.42  4926.6  870.22  4934.0  866.80
  4962.3  860.26  4974.5  859.39  4974.7  858.89  4978.5  859.39  5026.5  861.32
  5041.2  866.18  5047.4  871.19  5062.0  870.14  5068.2  872.89  5076.7  871.34
  5102.6  873.78  5204.0  880.42  5212.4  879.26  5218.6  881.24  5294.7  883.02
#Mann=5,-1,0
  4742.8    0.05       0  4758.0    0.12       0  4974.5    0.07       0
  4978.5    0.12       0  5102.6    0.05       0
Bank Sta=4974.5,4978.5
Exp/Cntr=0.3,0.1

Type RM Length L Ch R = 1,5746,334,334,334
BEGIN DESCRIPTION:
UDS St 33 14.0
END DESCRIPTION:
XS GIS Cut Line= 3
      2260328.48      7197465.34      2260129.00      7197510.00
      2259902.30      7197567.51
#Sta/Elev= 30
  4796.2  877.93  4816.2  877.10  4826.4  875.87  4841.1  875.68  4884.5  872.15
  4898.1  871.98  4939.1  869.01  4949.4  869.03  4959.6  867.12  4974.4  855.95
  4974.6  855.45  4978.1  855.45  4978.4  855.95  4990.4  860.21  4998.1  859.26
  5018.5  859.31  5041.9  858.25  5059.5  858.01  5064.6  859.03  5072.8  857.45
  5100.5  862.45  5105.6  864.85  5124.4  868.37  5146.6  870.94  5176.0  873.30
  5183.8  874.65  5196.6  876.11  5206.9  878.32  5228.5  878.70  5234.5  880.53
#Mann=4,-1,0
  4796.2    0.12       0  4974.4    0.07       0  4978.4    0.12       0
  5183.8    0.05       0
Bank Sta=4974.4,4978.4
Exp/Cntr=0.3,0.1

Type RM Length L Ch R = 1,5412,367,367,367
BEGIN DESCRIPTION:
UDS St 33 13.0
END DESCRIPTION:
XS GIS Cut Line= 3
      2260328.99      7197310.00      2260029.00      7197260.00
      2259748.10      7197332.79
#Sta/Elev= 30
  4691.7  879.98  4724.6  878.25  4732.2  876.83  4780.4  872.97  4785.5  873.52
  4803.2  871.87  4813.3  871.89  4823.5  870.30  4853.9  868.12  4902.0  866.56
  4907.1  867.21  4914.7  866.17  4975.5  865.35  4998.4  865.94  5013.5  863.49
  5018.7  860.46  5035.1  855.25  5035.4  854.75  5038.9  854.75  5039.1  855.25
  5047.5  855.39  5059.3  863.65  5068.1  867.40  5088.8  867.65  5130.1  871.61
  5135.3  872.73  5140.5  872.67  5223.1  879.82  5274.7  880.60  5286.0  881.60
#Mann=3,-1,0
  4691.7    0.12       0  5035.1    0.07       0  5039.1    0.12       0
Bank Sta=5035.1,5039.1
Exp/Cntr=0.3,0.1

Type RM Length L Ch R = 1,5045,329,329,329
BEGIN DESCRIPTION:
UDS St 33 12.0
END DESCRIPTION:
XS GIS Cut Line= 3
      2260278.99      7197159.99      2259979.00      7196910.00
      2259824.29      7196804.77
#Sta/Elev= 30
  4608.8  875.20  4679.7  871.27  4694.0  869.29  4700.6  869.96  4708.4  868.86
  4765.0  865.93  4850.3  863.99  4914.0  863.90  4928.4  864.85  4949.2  863.29
  4957.0  860.55  4963.5  860.81  4971.3  857.22  4977.8  858.99  4985.6  855.23
  4990.1  854.54  4990.4  854.04  4993.9  854.04  4994.1  854.54  5012.8  856.23
  5021.7  856.13  5027.7  858.74  5042.7  858.93  5048.7  863.08  5057.6  864.15
  5063.7  867.08  5069.2  867.22  5129.5  871.92  5150.4  874.86  5186.4  877.27
#Mann=4,-1,0
  4608.8    0.12       0  4990.1    0.07       0  4994.1    0.12       0
  5069.2    0.05       0
Bank Sta=4990.1,4994.1
Exp/Cntr=0.3,0.1

Type RM Length L Ch R = 1,4716,392,392,392
BEGIN DESCRIPTION:
UDS St 33 11.0
END DESCRIPTION:
XS GIS Cut Line= 3
      2260766.44      7196978.45      2260176.64      7196676.96
      2259937.79      7196589.07
#Sta/Elev= 30
  4341.1  879.76  4390.7  877.23  4396.3  874.82  4487.3  871.63  4585.0  865.76
  4619.0  866.63  4696.1  864.58  4718.3  861.36  4740.5  860.79  4746.2  863.24
  4812.8  862.19  4821.2  861.56  4843.6  853.68  4857.2  855.19  4873.8  853.49
  4879.4  855.07  4894.0  852.64  4894.3  852.14  4898.0  852.64  4901.7  854.14
  4911.0  852.86  4984.9  855.36  5007.7  853.49  5013.1  857.07  5035.1  860.50
  5043.6  863.17  5063.3  861.63  5068.7  864.27  5160.8  874.20  5258.0  876.16
#Mann=5,-1,0
  4341.1    0.05       0  4487.3    0.12       0  4894.0    0.07       0
  4898.0    0.12       0  5035.1    0.05       0
Bank Sta=4894,4898
Exp/Cntr=0.3,0.1

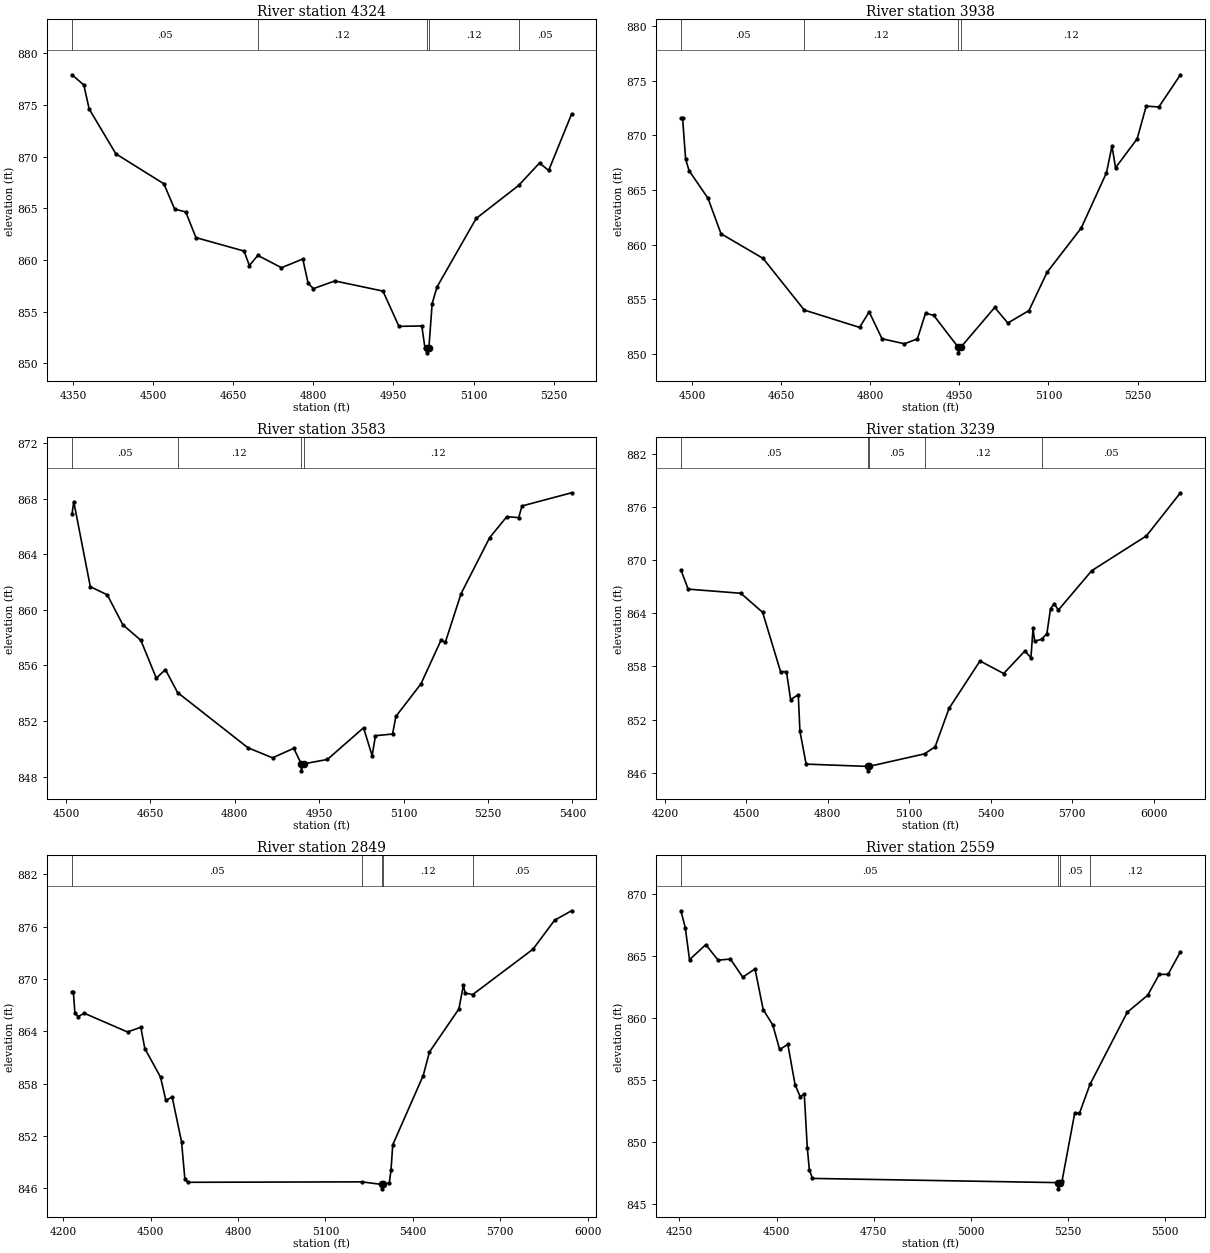
Type RM Length L Ch R = 1,4324,386,386,386
BEGIN DESCRIPTION:
UDS St 33 10.0
END DESCRIPTION:
XS GIS Cut Line= 3
      2260881.15      7196337.93      2260229.00      7196360.00
      2259973.84      7196482.81
#Sta/Elev= 30
  4347.8  877.90  4370.0  876.92  4380.0  874.60  4430.0  870.26  4520.0  867.36
  4540.1  864.92  4560.9  864.64  4580.1  862.16  4670.1  860.86  4680.1  859.46
  4696.0  860.44  4740.2  859.25  4780.2  860.09  4790.2  857.73  4800.2  857.23
  4840.2  857.97  4930.3  856.99  4960.3  853.58  5003.1  853.62  5008.9  851.53
  5012.4  851.52  5012.7  851.02  5016.4  851.52  5022.5  855.78  5031.5  857.38
  5104.9  864.01  5184.4  867.20  5223.6  869.37  5240.7  868.65  5283.5  874.08
#Mann=5,-1,0
  4347.8    0.05       0  4696.0    0.12       0  5012.4    0.07       0
  5016.4    0.12       0  5184.4    0.05       0
Bank Sta=5012.4,5016.4
Exp/Cntr=0.3,0.1

Type RM Length L Ch R = 1,3938,355,355,355
BEGIN DESCRIPTION:
UDS St 33 9.0
END DESCRIPTION:
XS GIS Cut Line= 3
      2260578.98      7195760.01      2260129.00      7196010.00
      2259853.64      7196184.77
#Sta/Elev= 30
  4481.3  871.62  4484.1  871.62  4489.3  867.83  4495.0  866.79  4527.0  864.24
  4548.8  861.00  4619.7  858.74  4689.0  854.01  4782.1  852.42  4798.2  853.84
  4819.9  851.38  4857.6  850.92  4879.4  851.37  4893.1  853.71  4906.8  853.53
  4948.3  850.59  4948.6  850.09  4952.3  850.59  5009.6  854.25  5031.6  852.82
  5067.2  853.96  5097.7  857.47  5155.3  861.53  5197.7  866.59  5207.0  869.04
  5212.9  867.04  5249.3  869.69  5264.6  872.69  5285.8  872.61  5322.2  875.56
#Mann=4,-1,0
  4481.3    0.05       0  4689.0    0.12       0  4948.3    0.07       0
  4952.3    0.12       0
Bank Sta=4948.3,4952.3
Exp/Cntr=0.3,0.1

Type RM Length L Ch R = 1,3583,344,344,344
BEGIN DESCRIPTION:
UDS St 33 8.0
END DESCRIPTION:
XS GIS Cut Line= 3
      2260407.57      7195473.91      2259979.00      7195710.00
      2259643.77      7195924.90
#Sta/Elev= 30
  4510.8  866.87  4514.0  867.79  4543.4  861.67  4573.6  861.08  4601.1  858.93
  4633.2  857.81  4660.7  855.08  4676.8  855.70  4698.4  854.05  4823.5  850.07
  4867.1  849.35  4904.9  850.03  4918.2  848.91  4918.4  848.41  4922.2  848.91
  4964.6  849.23  5028.8  851.51  5044.1  849.50  5050.0  850.94  5080.4  851.06
  5086.3  852.33  5130.8  854.67  5166.4  857.81  5174.2  857.67  5202.0  861.16
  5252.9  865.20  5283.3  866.71  5304.4  866.64  5310.4  867.48  5398.3  868.43
#Mann=4,-1,0
  4510.8    0.05       0  4698.4    0.12       0  4918.2    0.07       0
  4922.2    0.12       0
Bank Sta=4918.2,4922.2
Exp/Cntr=0.3,0.1

Type RM Length L Ch R = 1,3239,390,390,390
BEGIN DESCRIPTION:
UDS St 33 7.0
END DESCRIPTION:
XS GIS Cut Line= 3
      2260491.68      7195064.46      2259841.71      7195427.39
      2258931.16      7196035.38
#Sta/Elev= 30
  4259.1  868.92  4285.8  866.74  4479.8  866.27  4560.0  864.12  4626.2  857.41
  4647.9  857.41  4663.0  854.26  4691.3  854.80  4697.4  850.68  4720.3  846.96
  4947.4  846.70  4947.6  846.20  4951.4  846.70  5156.1  848.12  5195.2  848.92
  5246.3  853.25  5360.4  858.62  5447.6  857.20  5525.7  859.75  5547.9  858.98
  5555.7  862.29  5561.7  860.85  5587.0  861.07  5606.7  861.71  5620.0  864.53
  5633.8  865.10  5648.8  864.37  5772.0  868.83  5973.2  872.76  6098.4  877.63
#Mann=5,-1,0
  4259.1    0.05       0  4947.4   0.033       0  4951.4    0.05       0
  5156.1    0.12       0  5587.0    0.05       0
Bank Sta=4947.4,4951.4
Exp/Cntr=0.3,0.1

Type RM Length L Ch R = 1,2849,290,290,290
BEGIN DESCRIPTION:
UDS St 33 6.0
END DESCRIPTION:
XS GIS Cut Line= 3
      2260298.48      7194873.28      2259579.00      7195160.00
      2258773.09      7195644.42
#Sta/Elev= 30
  4229.8  868.55  4234.5  868.55  4240.0  866.11  4250.8  865.71  4272.3  866.08
  4420.6  863.94  4466.1  864.48  4479.9  862.04  4533.8  858.77  4552.2  856.09
  4573.7  856.49  4606.0  851.35  4617.4  847.08  4627.5  846.71  5225.2  846.76
  5294.0  846.46  5294.2  845.96  5298.0  846.46  5319.0  846.63  5324.9  848.07
  5331.0  851.01  5435.6  858.95  5457.0  861.65  5558.0  866.58  5573.5  869.30
  5579.4  868.40  5605.6  868.23  5812.5  873.43  5886.3  876.74  5944.6  877.83
#Mann=5,-1,0
  4229.8    0.05       0  5225.2    0.12       0  5294.0   0.033       0
  5298.0    0.12       0  5605.6    0.05       0
Bank Sta=5294,5298
Exp/Cntr=0.3,0.1

Type RM Length L Ch R = 1,2559,375,375,375
BEGIN DESCRIPTION:
UDS St 33 5.1
END DESCRIPTION:
XS GIS Cut Line= 4
      2260139.67      7194709.45      2259507.97      7194924.21
      2259376.08      7194927.07      2258929.05      7195119.47
#Sta/Elev= 30
  4253.7  868.62  4265.0  867.26  4275.9  864.68  4317.8  865.89  4349.5  864.64
  4381.2  864.73  4412.8  863.27  4444.5  863.93  4465.6  860.65  4490.2  859.42
  4507.9  857.44  4529.0  857.85  4547.7  854.59  4560.7  853.64  4571.3  853.84
  4579.1  849.49  4584.4  847.73  4592.4  847.05  5225.0  846.71  5225.2  846.21
  5229.0  846.71  5234.7  846.83  5267.4  852.32  5279.5  852.29  5306.7  854.63
  5402.6  860.44  5455.1  861.81  5485.1  863.50  5507.6  863.49  5539.5  865.32
#Mann=4,-1,0
  4253.7    0.05       0  5225.0   0.033       0  5229.0    0.05       0
  5306.7    0.12       0
Bank Sta=5225,5229
Exp/Cntr=0.3,0.1

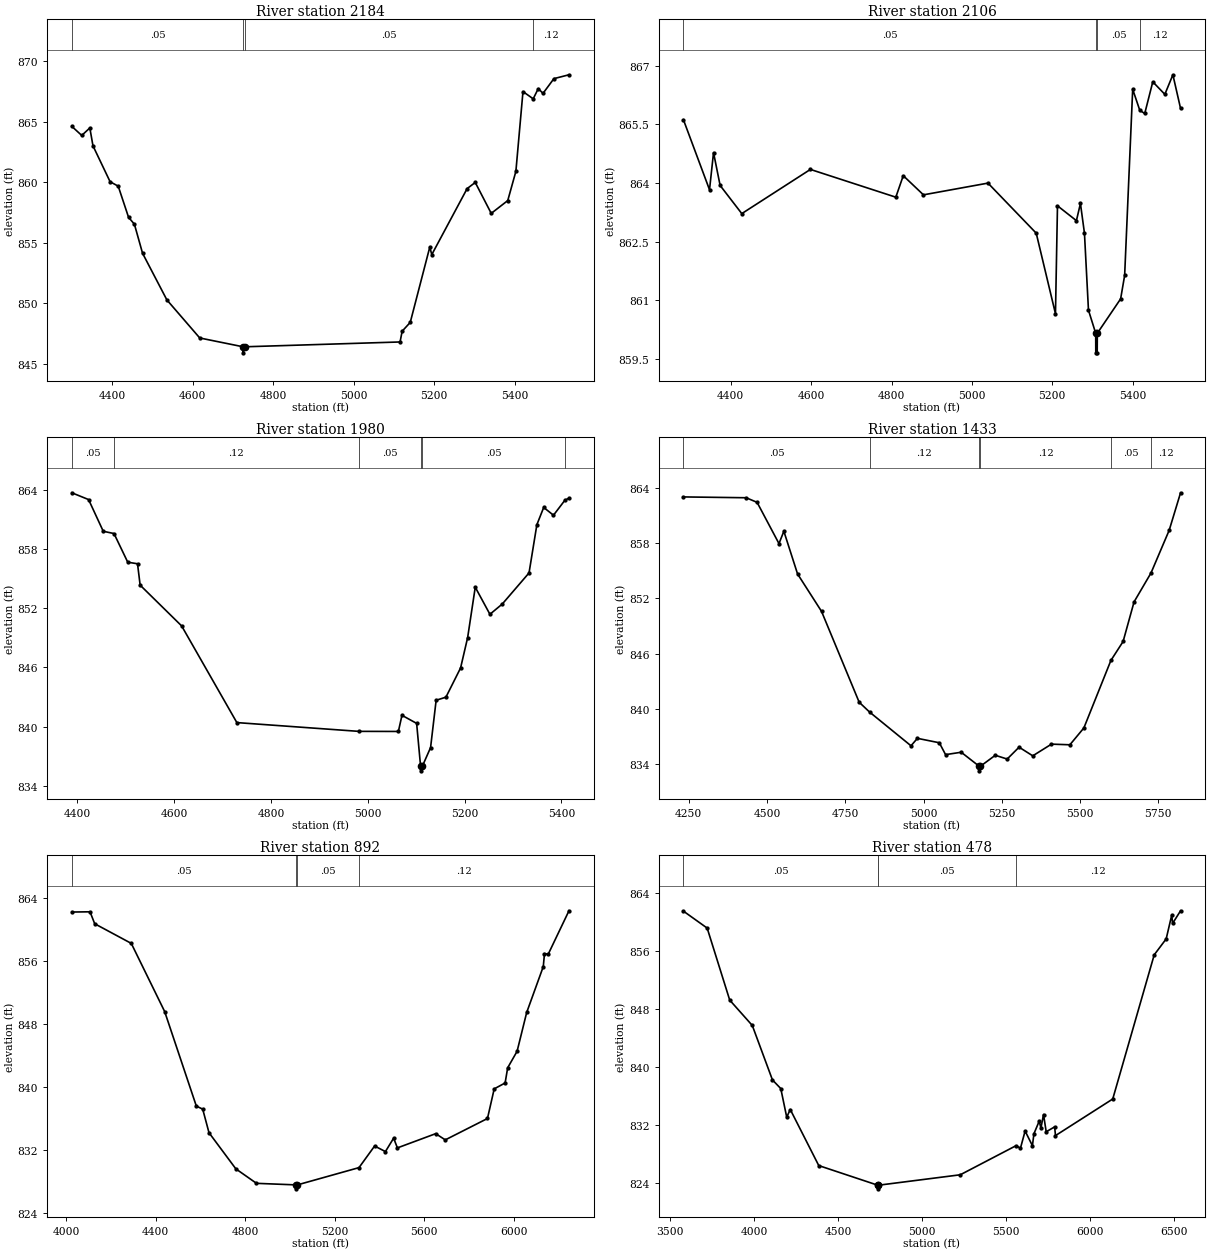
Type RM Length L Ch R = 1,2184,78,78,78
BEGIN DESCRIPTION:
UDS St 33 5.0
END DESCRIPTION:
XS GIS Cut Line= 4
      2259923.39      7194578.59      2259243.00      7194658.12
      2258773.64      7194719.63      2258729.04      7194781.17
#Sta/Elev= 30
  4300.3  864.63  4324.9  863.88  4345.0  864.50  4352.8  863.02  4395.3  860.05
  4415.5  859.68  4441.1  857.11  4455.7  856.53  4475.9  854.13  4536.3  850.27
  4617.9  847.12  4725.6  846.39  4725.8  845.89  4729.6  846.39  5115.3  846.79
  5120.5  847.68  5140.6  848.41  5189.1  854.64  5194.1  854.02  5281.8  859.48
  5302.0  859.99  5341.7  857.43  5382.7  858.49  5402.9  860.91  5420.5  867.51
  5445.9  866.91  5458.5  867.76  5470.2  867.36  5497.3  868.58  5534.7  868.90
#Mann=4,-1,0
  4300.3    0.05       0  4725.6   0.033       0  4729.6    0.05       0
  5445.9    0.12       0
Bank Sta=4725.6,4729.6
Exp/Cntr=0.3,0.1

Type RM Length L Ch R = 1,2106,126,126,126
BEGIN DESCRIPTION:
UDS St 33 4.0
END DESCRIPTION:
XS GIS Cut Line= 3
      2259943.58      7194516.43      2259230.61      7194582.69
      2258709.88      7194588.36
#Sta/Elev= 30
  4282.3  865.62  4347.2  863.83  4357.2  864.78  4373.6  863.94  4427.5  863.22
  4598.2  864.35  4810.7  863.64  4829.2  864.19  4879.4  863.70  5040.0  864.00
  5160.0  862.72  5207.9  860.66  5212.9  863.42  5260.0  863.04  5270.0  863.48
  5280.0  862.72  5290.0  860.75  5308.0  860.16  5308.2  859.66  5311.7  859.66
  5312.0  860.16  5370.0  861.04  5380.0  861.64  5400.0  866.40  5417.7  865.86
  5430.0  865.78  5450.0  866.59  5480.0  866.27  5500.0  866.77  5519.1  865.91
#Mann=4,-1,0
  4282.3    0.05       0  5308.0   0.033       0  5312.0    0.05       0
  5417.7    0.12       0
Bank Sta=5308,5312
Exp/Cntr=0.3,0.1

Type RM Length L Ch R = 1,1980,547,547,547
BEGIN DESCRIPTION:
UDS St 33 3.0
END DESCRIPTION:
XS GIS Cut Line= 3
      2259833.16      7194363.48      2259222.31      7194457.51
      2258817.28      7194514.01
#Sta/Elev= 30
  4388.7  863.74  4423.3  863.05  4453.6  859.83  4475.8  859.60  4504.2  856.69
  4524.4  856.53  4529.8  854.36  4615.5  850.22  4729.6  840.40  4981.3  839.51
  5063.3  839.50  5070.7  841.14  5101.0  840.32  5109.1  836.00  5109.3  835.50
  5113.1  836.00  5129.8  837.86  5141.3  842.67  5161.5  842.98  5191.8  845.95
  5206.4  849.04  5222.1  854.15  5252.4  851.40  5277.9  852.44  5333.2  855.60
  5349.4  860.50  5363.5  862.25  5383.7  861.46  5407.4  862.99  5415.7  863.19
#Mann=6,-1,0
  4388.7    0.05       0  4475.8    0.12       0  4981.3    0.05       0
  5109.1   0.033       0  5113.1    0.05       0  5407.4    0.12       0
Bank Sta=5109.1,5113.1
Exp/Cntr=0.3,0.1

Type RM Length L Ch R = 1,1433,541,541,541
BEGIN DESCRIPTION:
UDS St 33 2.0
END DESCRIPTION:
XS GIS Cut Line= 4
      2259992.39      7194178.78      2259415.59      7193923.63
      2259110.56      7193927.79      2258798.55      7194500.43
#Sta/Elev= 30
  4233.1  863.03  4433.6  862.94  4468.4  862.44  4538.3  857.96  4553.9  859.30
  4597.7  854.66  4674.2  850.60  4794.5  840.73  4827.5  839.67  4960.0  836.00
  4980.4  836.81  5050.4  836.33  5070.4  835.04  5120.4  835.30  5177.8  833.78
  5178.1  833.28  5181.8  833.78  5229.2  834.97  5267.2  834.56  5305.2  835.85
  5348.9  834.91  5408.7  836.18  5467.5  836.11  5512.2  837.94  5598.5  845.27
  5637.5  847.33  5672.5  851.63  5726.6  854.77  5784.7  859.41  5821.0  863.48
#Mann=6,-1,0
  4233.1    0.05       0  4827.5    0.12       0  5177.8    0.07       0
  5181.8    0.12       0  5598.5    0.05       0  5726.6    0.12       0
Bank Sta=5177.8,5181.8
Exp/Cntr=0.3,0.1

Type RM Length L Ch R = 1,892,414,414,414
BEGIN DESCRIPTION:
UDS St 33 1.2
END DESCRIPTION:
XS GIS Cut Line= 4
      2260084.09      7193899.37      2259449.64      7193354.40
      2259124.28      7193476.41      2258754.84      7194446.70
#Sta/Elev= 30
  4025.3  862.26  4106.6  862.29  4127.5  860.77  4291.0  858.27  4440.2  849.60
  4581.8  837.57  4610.3  837.18  4638.4  834.18  4758.5  829.58  4850.7  827.74
  5029.1  827.54  5029.3  827.04  5033.1  827.54  5308.9  829.74  5378.7  832.49
  5427.0  831.78  5463.7  833.49  5480.5  832.25  5651.7  834.06  5694.5  833.27
  5883.1  835.99  5913.2  839.76  5962.0  840.51  5973.4  842.44  6015.5  844.54
  6058.4  849.48  6132.6  855.32  6138.0  856.97  6154.6  856.89  6247.4  862.42
#Mann=4,-1,0
  4025.3    0.05       0  5029.1   0.035       0  5033.1    0.05       0
  5308.9    0.12       0
Bank Sta=5029.1,5033.1
Exp/Cntr=0.3,0.1

Type RM Length L Ch R = 1,478,280,280,280
BEGIN DESCRIPTION:
UDS St 33 1.1
END DESCRIPTION:
XS GIS Cut Line= 4
      2260263.03      7193805.83      2259368.30      7192927.37
      2259051.07      7193134.78      2258669.19      7194406.37
#Sta/Elev= 30
  3579.5  861.55  3720.9  859.21  3855.2  849.27  3989.6  845.77  4109.7  838.25
  4159.3  837.06  4194.6  833.12  4215.8  834.17  4385.5  826.43  4737.1  823.72
  4737.3  823.22  4741.1  823.72  5228.3  825.16  5560.7  829.18  5586.6  828.83
  5614.4  831.20  5657.9  829.17  5666.8  830.82  5698.2  832.56  5708.6  831.62
  5724.0  833.48  5739.9  831.10  5790.1  831.77  5795.3  830.57  6136.2  835.62
  6383.2  855.52  6454.5  857.72  6487.5  861.00  6492.8  859.86  6540.1  861.60
#Mann=4,-1,0
  3579.5    0.05       0  4737.1   0.035       0  4741.1    0.05       0
  5560.7    0.12       0
Bank Sta=4737.1,4741.1
Exp/Cntr=0.3,0.1

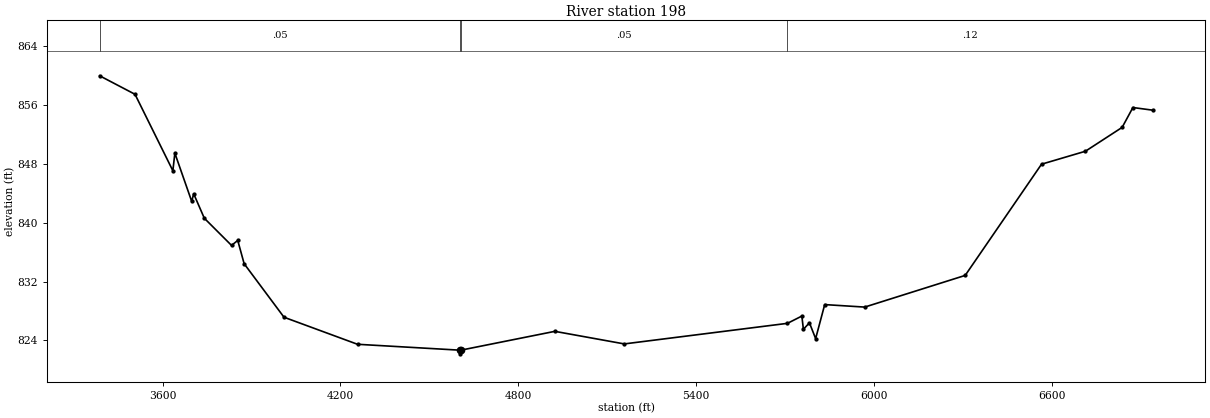
Type RM Length L Ch R = 1,198,0,0,0
BEGIN DESCRIPTION:
UDS St 33 1.0
END DESCRIPTION:
XS GIS Cut Line= 4
      2260333.69      7193704.00      2259361.56      7192635.42
      2258922.73      7192977.76      2258548.90      7194484.30
#Sta/Elev= 30
  3387.3  860.01  3506.7  857.49  3634.4  847.09  3641.1  849.48  3697.9  842.93
  3704.7  843.95  3740.5  840.63  3832.4  836.93  3853.3  837.61  3874.9  834.44
  4009.4  827.16  4257.4  823.48  4602.0  822.68  4602.3  822.18  4606.1  822.68
  4923.2  825.24  5157.5  823.53  5708.2  826.33  5756.7  827.32  5761.9  825.52
  5782.3  826.40  5803.2  824.25  5833.8  828.88  5968.7  828.54  6307.8  832.85
  6565.4  847.98  6713.3  849.74  6837.4  852.99  6873.7  855.69  6940.7  855.33
#Mann=4,-1,0
  3387.3    0.05       0  4602.0   0.033       0  4606.1    0.05       0
  5708.2    0.12       0
Bank Sta=4602,4606.1
Exp/Cntr=0.3,0.1

Chan Stop Cuts=-1