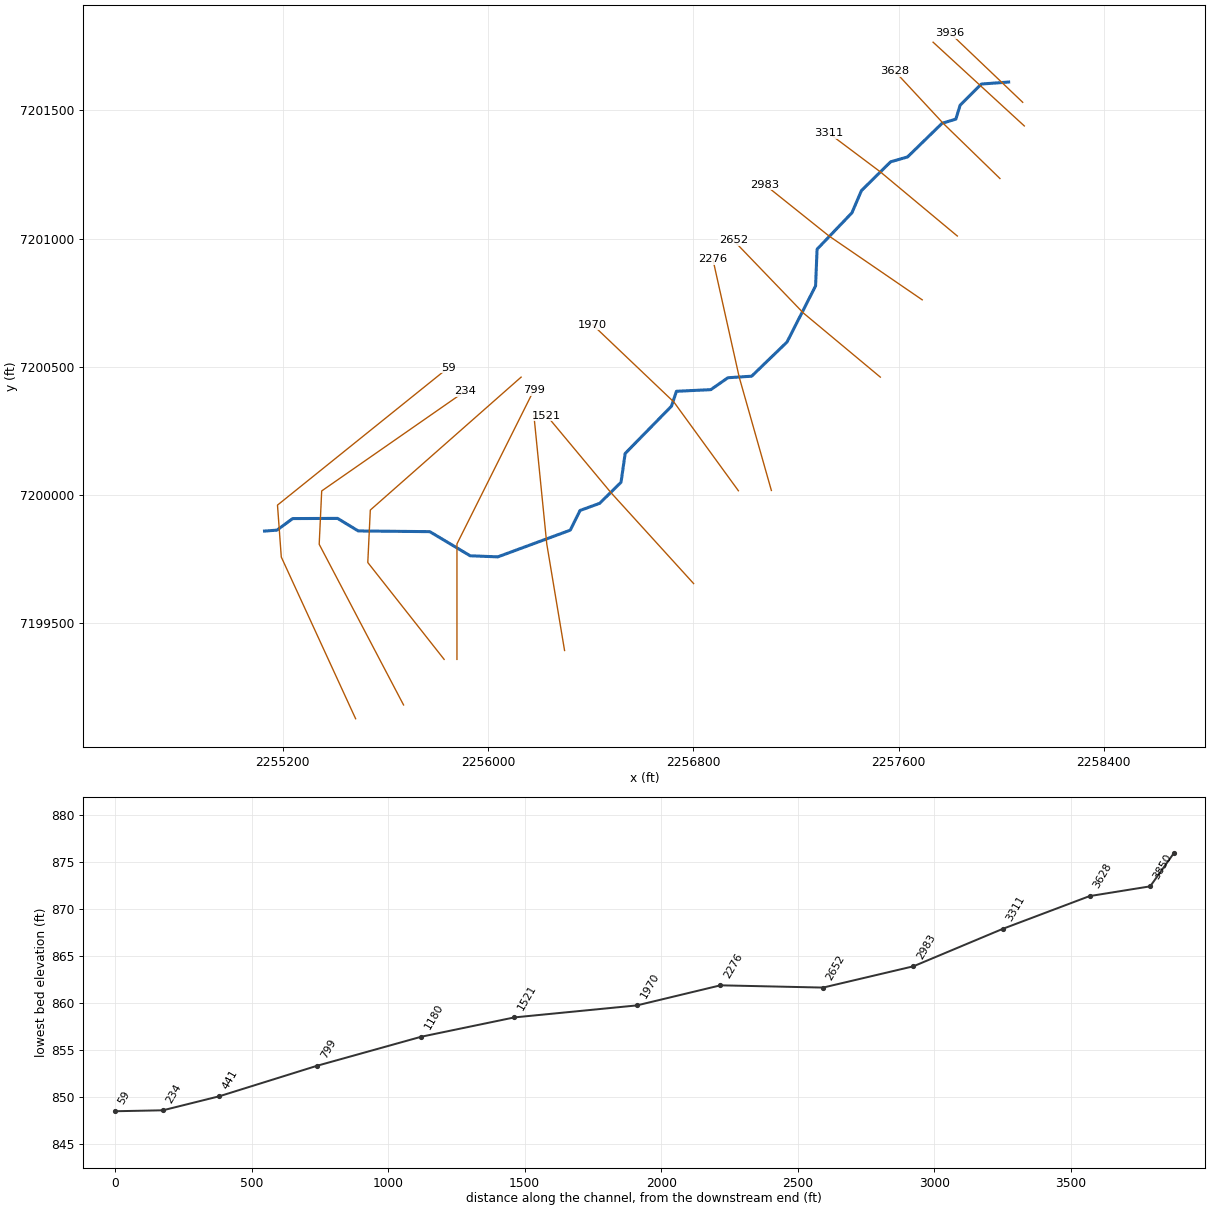
--- UDS St 37.prj (project) ---

Proj Title=UDS St 37 Base Level Engineering
Current Plan=p01
Default Exp/Contr=0.3,0.1
English Units
Geom File=g01
Flow File=f01
Plan File=p01
BEGIN DESCRIPTION:
UDS St 37
END DESCRIPTION:

--- UDS St 37.p01 (plan) ---

Plan Title=Multiple Run
Short Identifier=Multiple
Geom File=g01
Flow File=f01
Subcritical Flow
K Sum by GR= 0
Std Step Tol= 0.01
Critical Tol= 0.01
Num of Std Step Trials= 20
Max Error Tol= 0.3
Flow Tol Ratio= 0.001
Split Flow NTrial= 30
Split Flow Tol= 0.02
Split Flow Ratio= 0.02
Log Output Level= 0
Friction Slope Method= 1
Unsteady Friction Slope Method= 2
Unsteady Bridges Friction Slope Method= 1
Parabolic Critical Depth
Global Vel Dist=  1 , 1 , 1
Global Log Level= 0
CheckData=True
Encroach Param= -1, 0, 0, 0
BEGIN DESCRIPTION:
Multiple Run
END DESCRIPTION:

--- UDS St 37.f01 (steady flow) ---

Flow Title=Multiple
Number of Profiles=7
Profile Names=10-year,25-year,50-year,1pct_min,100-year,1pct_plu,500-year
River Rch & RM= UDS St 37,Reach-1,3936
     738    1042    1301     808    1612    3216    2477
Boundary for River Rch & Prof#=UDS St 37,Reach-1,1
Up Type=0
Dn Type=3
Dn Slope=0.005
Boundary for River Rch & Prof#=UDS St 37,Reach-1,2
Up Type=0
Dn Type=3
Dn Slope=0.005
Boundary for River Rch & Prof#=UDS St 37,Reach-1,3
Up Type=0
Dn Type=3
Dn Slope=0.005
Boundary for River Rch & Prof#=UDS St 37,Reach-1,4
Up Type=0
Dn Type=3
Dn Slope=0.005
Boundary for River Rch & Prof#=UDS St 37,Reach-1,5
Up Type=0
Dn Type=3
Dn Slope=0.005
Boundary for River Rch & Prof#=UDS St 37,Reach-1,6
Up Type=0
Dn Type=3
Dn Slope=0.005
Boundary for River Rch & Prof#=UDS St 37,Reach-1,7
Up Type=0
Dn Type=3
Dn Slope=0.005

--- UDS St 37.g01 (geometry) ---

Geom Title=Existing Conditions

River Reach=UDS St 37,Reach-1
Reach XY= 30
      2258029.00      7201610.00      2257922.76      7201602.27
      2257839.88      7201519.44      2257823.38      7201465.62
      2257769.58      7201449.11      2257635.05      7201318.16
      2257569.32      7201299.22      2257455.30      7201186.82
      2257418.22      7201100.32      2257282.54      7200958.53
      2257276.64      7200815.52      2257165.38      7200596.78
      2257027.50      7200463.61      2256934.98      7200457.64
      2256868.48      7200411.24      2256734.44      7200404.81
      2256715.26      7200347.05      2256534.52      7200162.43
      2256518.49      7200050.19      2256435.05      7199968.16
      2256358.57      7199940.27      2256320.51      7199863.53
      2256038.26      7199759.50      2255930.56      7199763.74
      2255773.07      7199857.76      2255494.22      7199860.52
      2255413.78      7199909.48      2255238.62      7199908.73
      2255177.49      7199863.65      2255129.00      7199860.00

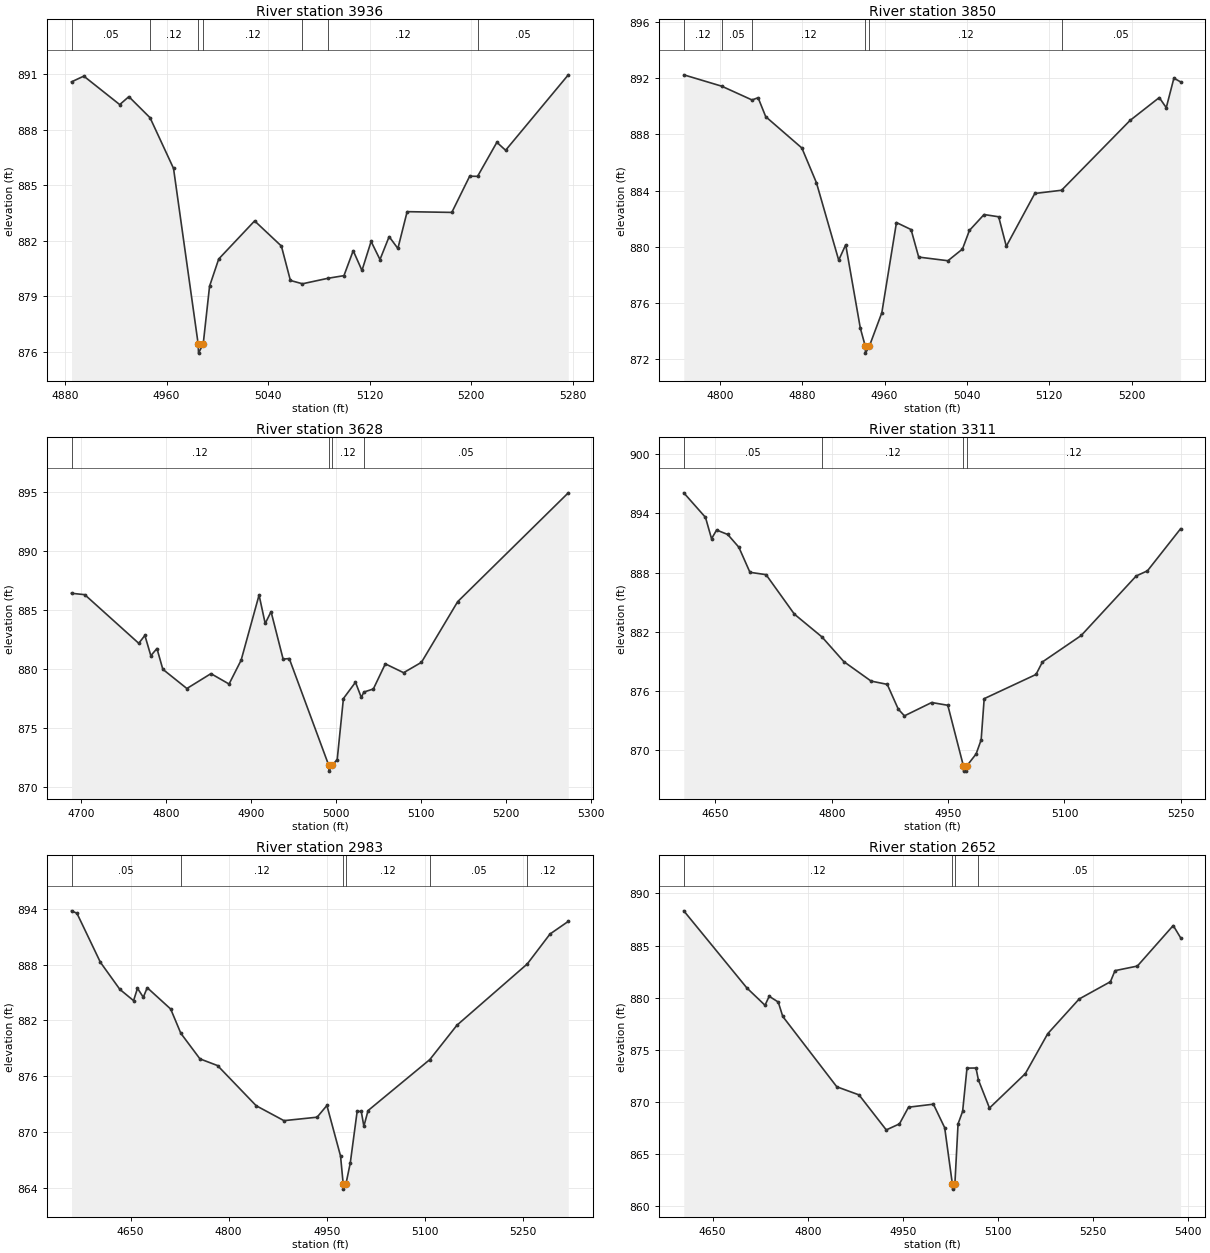
Type RM Length L Ch R = 1,3936,86,86,86
BEGIN DESCRIPTION:
UDS St 37 10.2
END DESCRIPTION:
XS GIS Cut Line= 2
      2258083.88      7201531.06      2257800.50      7201801.19
#Sta/Elev= 30
  4885.1  890.60  4894.8  890.91  4923.1  889.37  4930.3  889.80  4947.0  888.66
  4965.5  885.92  4984.9  876.43  4985.2  875.93  4988.9  876.43  4993.9  879.55
  5001.1  881.02  5029.4  883.08  5050.5  881.72  5057.6  879.86  5067.1  879.68
  5087.4  879.98  5099.8  880.12  5107.1  881.47  5114.0  880.40  5121.2  881.97
  5128.2  880.99  5135.4  882.23  5142.3  881.59  5149.6  883.58  5184.8  883.54
  5198.9  885.50  5205.1  885.49  5220.3  887.33  5227.2  886.90  5276.6  890.98
#Mann=7,-1,0
  4885.1    0.05       0  4947.0    0.12       0  4984.9    0.07       0
  4988.9    0.12       0  5067.1    0.05       0  5087.4    0.12       0
  5205.1    0.05       0
Bank Sta=4984.9,4988.9
Exp/Cntr=0.3,0.1

Type RM Length L Ch R = 1,3850,222,222,222
BEGIN DESCRIPTION:
UDS St 37 10.1
END DESCRIPTION:
XS GIS Cut Line= 2
      2258090.17      7201438.90      2257734.67      7201765.28
#Sta/Elev= 30
  4765.0  892.24  4801.9  891.43  4831.3  890.45  4837.2  890.61  4844.6  889.26
  4879.7  887.03  4893.9  884.55  4915.5  879.04  4922.3  880.14  4936.5  874.20
  4941.3  872.92  4941.5  872.42  4945.3  872.92  4957.4  875.30  4971.6  881.72
  4985.8  881.22  4993.2  879.26  5021.6  879.00  5035.7  879.83  5042.5  881.16
  5056.7  882.29  5070.9  882.13  5078.3  880.03  5106.0  883.79  5132.0  884.02
  5198.5  888.99  5226.9  890.62  5233.7  889.90  5241.1  892.00  5247.6  891.74
#Mann=6,-1,0
  4765.0    0.12       0  4801.9    0.05       0  4831.3    0.12       0
  4941.3    0.07       0  4945.3    0.12       0  5132.0    0.05       0
Bank Sta=4941.3,4945.3
Exp/Cntr=0.3,0.1

Type RM Length L Ch R = 1,3628,317,317,317
BEGIN DESCRIPTION:
UDS St 37 10.0
END DESCRIPTION:
XS GIS Cut Line= 3
      2257995.14      7201234.11      2257775.37      7201447.73
      2257586.23      7201651.22
#Sta/Elev= 30
  4689.0  886.45  4704.6  886.33  4768.1  882.21  4775.3  882.88  4782.3  881.16
  4789.5  881.77  4796.4  880.01  4824.7  878.38  4853.0  879.64  4874.3  878.76
  4888.5  880.78  4909.6  886.30  4916.8  883.89  4923.7  884.89  4937.9  880.87
  4945.1  880.92  4991.5  871.88  4991.8  871.38  4995.5  871.88  5001.5  872.36
  5008.8  877.53  5023.0  878.91  5029.8  877.63  5032.9  878.08  5044.0  878.34
  5058.1  880.47  5079.6  879.72  5100.6  880.60  5143.2  885.74  5273.3  894.96
#Mann=4,-1,0
  4689.0    0.12       0  4991.5    0.07       0  4995.5    0.12       0
  5032.9    0.05       0
Bank Sta=4991.5,4995.5
Exp/Cntr=0.3,0.1

Type RM Length L Ch R = 1,3311,328,328,328
BEGIN DESCRIPTION:
UDS St 37 9.0
END DESCRIPTION:
XS GIS Cut Line= 3
      2257829.03      7201009.98      2257529.00      7201260.00
      2257329.04      7201409.97
#Sta/Elev= 30
  4609.2  896.09  4637.2  893.60  4645.0  891.44  4651.5  892.32  4665.9  891.87
  4680.2  890.58  4694.5  888.04  4715.3  887.80  4751.8  883.80  4787.4  881.49
  4815.6  878.99  4850.7  877.02  4871.5  876.69  4885.8  874.17  4893.7  873.50
  4928.8  874.85  4949.6  874.57  4969.8  868.40  4970.0  867.90  4973.5  867.90
  4973.8  868.40  4986.1  869.64  4992.6  871.07  4996.5  875.24  5063.3  877.69
  5071.6  878.96  5121.6  881.64  5192.5  887.67  5207.0  888.19  5249.7  892.45
#Mann=4,-1,0
  4609.2    0.05       0  4787.4    0.12       0  4969.8    0.07       0
  4973.8    0.12       0
Bank Sta=4969.8,4973.8
Exp/Cntr=0.3,0.1

Type RM Length L Ch R = 1,2983,331,331,331
BEGIN DESCRIPTION:
UDS St 37 8.0
END DESCRIPTION:
XS GIS Cut Line= 3
      2257692.26      7200761.28      2257329.00      7201010.00
      2257079.01      7201209.99
#Sta/Elev= 30
  4559.5  893.77  4567.8  893.51  4603.7  888.25  4633.5  885.34  4654.5  884.13
  4660.5  885.46  4669.4  884.49  4675.4  885.52  4711.3  883.23  4726.8  880.63
  4756.1  877.88  4783.1  877.16  4842.2  872.85  4884.7  871.25  4935.4  871.62
  4950.4  872.88  4971.3  867.45  4975.4  864.40  4975.6  863.90  4979.4  864.40
  4986.2  866.71  4996.7  872.24  5003.0  872.24  5007.0  870.65  5013.4  872.33
  5108.0  877.81  5149.4  881.49  5257.1  888.07  5291.9  891.28  5319.9  892.64
#Mann=6,-1,0
  4559.5    0.05       0  4726.8    0.12       0  4975.4    0.07       0
  4979.4    0.12       0  5108.0    0.05       0  5257.1    0.12       0
Bank Sta=4975.4,4979.4
Exp/Cntr=0.3,0.1

Type RM Length L Ch R = 1,2652,376,376,376
BEGIN DESCRIPTION:
UDS St 37 7.0
END DESCRIPTION:
XS GIS Cut Line= 3
      2257529.02      7200459.98      2257229.00      7200710.00
      2256956.14      7200993.62
#Sta/Elev= 30
  4604.4  888.33  4704.0  880.93  4732.6  879.27  4739.2  880.13  4753.5  879.58
  4760.6  878.20  4845.9  871.45  4881.0  870.67  4924.0  867.31  4944.8  867.89
  4959.1  869.49  4998.4  869.78  5016.2  867.52  5028.3  862.13  5028.6  861.63
  5032.3  862.13  5037.3  867.89  5044.5  869.09  5051.4  873.24  5065.6  873.25
  5069.4  872.11  5086.9  869.41  5143.5  872.71  5178.8  876.54  5228.4  879.87
  5277.8  881.53  5285.0  882.59  5320.3  883.03  5376.9  886.92  5388.5  885.75
#Mann=4,-1,0
  4604.4    0.12       0  5028.3    0.07       0  5032.3    0.12       0
  5069.4    0.05       0
Bank Sta=5028.3,5032.3
Exp/Cntr=0.3,0.1

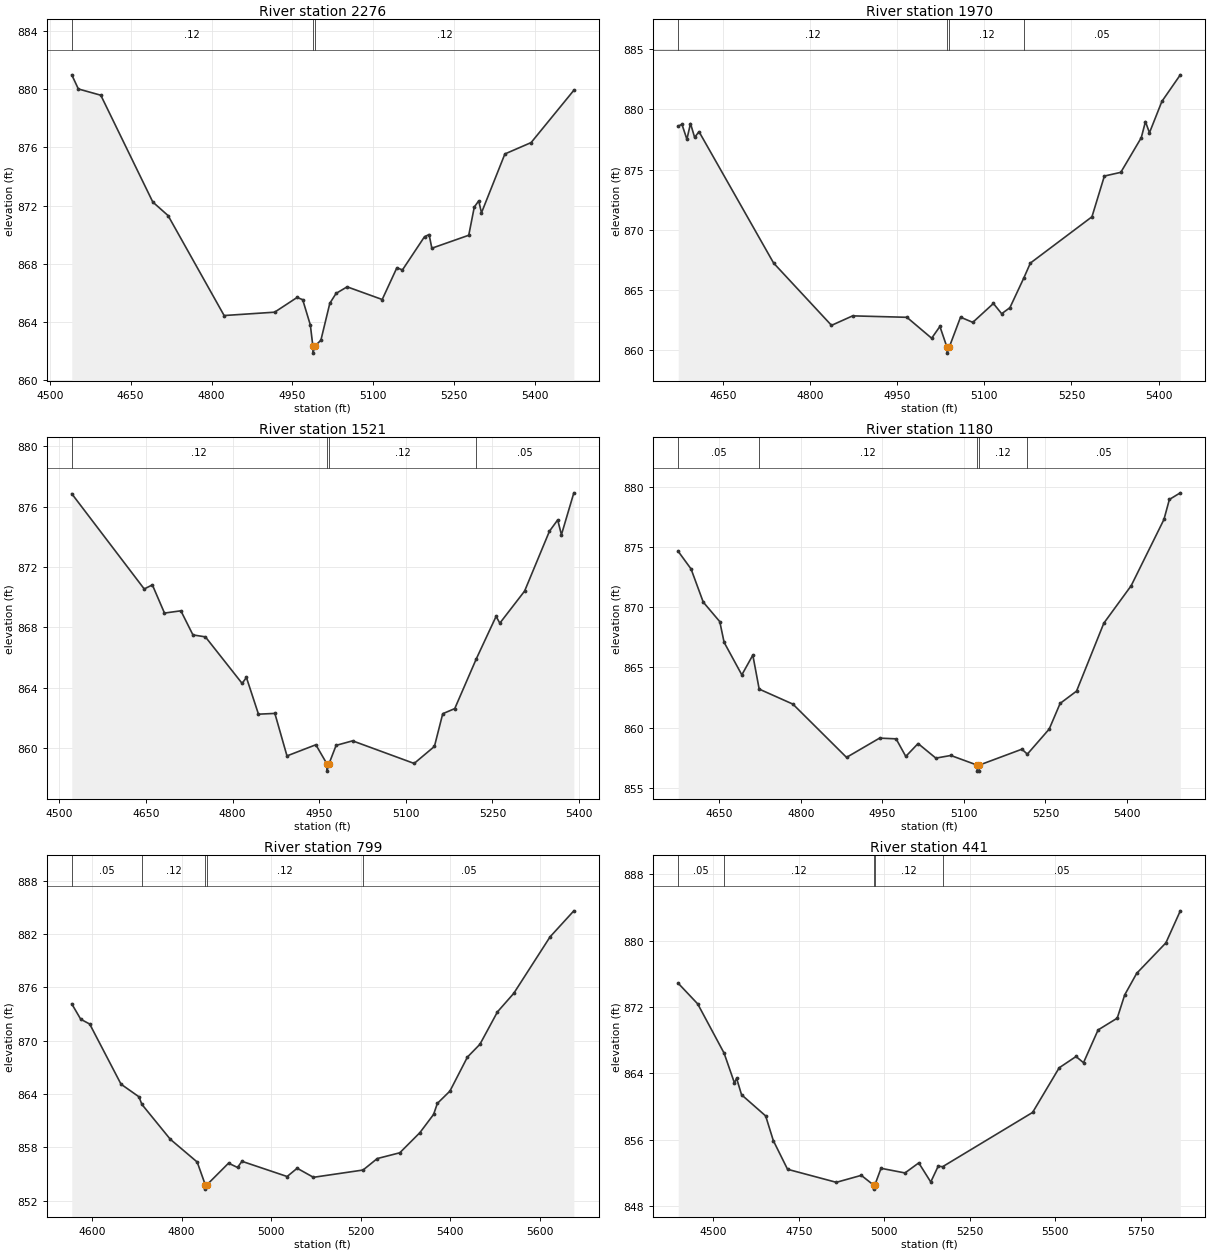
Type RM Length L Ch R = 1,2276,306,306,306
BEGIN DESCRIPTION:
UDS St 37 6.0
END DESCRIPTION:
XS GIS Cut Line= 3
      2257104.35      7200018.29      2256979.00      7200460.00
      2256876.24      7200920.11
#Sta/Elev= 30
  4540.9  880.97  4553.1  880.00  4594.7  879.57  4691.1  872.24  4719.4  871.31
  4823.3  864.45  4916.9  864.68  4958.5  865.69  4968.9  865.54  4983.1  863.80
  4987.7  862.37  4987.9  861.87  4991.7  862.37  5002.6  862.75  5019.2  865.29
  5030.8  865.97  5051.3  866.42  5116.3  865.55  5143.5  867.73  5153.8  867.58
  5194.7  869.86  5203.2  870.01  5208.3  869.07  5276.7  869.96  5287.0  871.90
  5295.2  872.32  5300.3  871.50  5343.7  875.54  5392.3  876.32  5471.5  879.91
#Mann=3,-1,0
  4540.9    0.12       0  4987.7    0.07       0  4991.7    0.12       0
Bank Sta=4987.7,4991.7
Exp/Cntr=0.3,0.1

Type RM Length L Ch R = 1,1970,449,449,449
BEGIN DESCRIPTION:
UDS St 37 5.0
END DESCRIPTION:
XS GIS Cut Line= 3
      2256975.84      7200017.16      2256724.42      7200362.95
      2256408.09      7200663.98
#Sta/Elev= 30
  4573.3  878.62  4579.7  878.76  4588.2  877.52  4594.4  878.83  4601.5  877.68
  4609.1  878.15  4737.5  867.22  4837.1  862.04  4873.5  862.83  4966.9  862.71
  5009.5  860.97  5023.7  861.95  5035.8  860.23  5036.1  859.73  5039.8  860.23
  5059.2  862.72  5080.3  862.29  5115.8  863.86  5130.0  863.01  5144.2  863.51
  5168.4  866.01  5179.4  867.22  5285.4  871.07  5306.8  874.46  5335.1  874.77
  5370.3  877.65  5377.5  878.99  5384.4  878.06  5405.8  880.67  5437.5  882.88
#Mann=4,-1,0
  4573.3    0.12       0  5035.8    0.07       0  5039.8    0.12       0
  5168.4    0.05       0
Bank Sta=5035.8,5039.8
Exp/Cntr=0.3,0.1

Type RM Length L Ch R = 1,1521,341,341,341
BEGIN DESCRIPTION:
UDS St 37 4.0
END DESCRIPTION:
XS GIS Cut Line= 3
      2256801.36      7199655.43      2256479.00      7200010.00
      2256229.01      7200309.99
#Sta/Elev= 30
  4521.3  876.86  4646.8  870.54  4660.9  870.81  4681.9  868.94  4710.3  869.09
  4731.2  867.49  4752.8  867.36  4816.4  864.27  4823.8  864.67  4844.7  862.23
  4873.1  862.28  4894.1  859.46  4944.1  860.20  4963.0  858.95  4963.3  858.45
  4967.0  858.95  4979.2  860.16  5007.7  860.46  5114.4  858.96  5149.5  860.09
  5163.9  862.26  5184.7  862.60  5221.9  865.89  5256.3  868.72  5262.8  868.27
  5305.7  870.40  5348.7  874.37  5363.0  875.12  5369.5  874.14  5391.0  876.92
#Mann=4,-1,0
  4521.3    0.12       0  4963.0    0.07       0  4967.0    0.12       0
  5221.9    0.05       0
Bank Sta=4963,4967
Exp/Cntr=0.3,0.1

Type RM Length L Ch R = 1,1180,381,381,381
BEGIN DESCRIPTION:
UDS St 37 3.0
END DESCRIPTION:
XS GIS Cut Line= 3
      2256298.38      7199394.64      2256229.00      7199810.00
      2256179.00      7200310.00
#Sta/Elev= 30
  4574.5  874.63  4598.1  873.17  4620.5  870.42  4650.9  868.80  4658.9  867.08
  4691.5  864.38  4711.7  866.02  4723.4  863.20  4785.5  861.95  4884.1  857.53
  4944.9  859.13  4975.3  859.07  4993.1  857.61  5015.7  858.68  5048.4  857.47
  5076.0  857.69  5124.3  856.89  5124.5  856.39  5128.0  856.39  5128.3  856.89
  5206.7  858.21  5216.7  857.80  5256.9  859.88  5277.0  862.01  5307.2  863.03
  5357.4  868.67  5407.7  871.78  5468.0  877.28  5478.0  878.94  5498.1  879.49
#Mann=5,-1,0
  4574.5    0.05       0  4723.4    0.12       0  5124.3    0.07       0
  5128.3    0.12       0  5216.7    0.05       0
Bank Sta=5124.3,5128.3
Exp/Cntr=0.3,0.1

Type RM Length L Ch R = 1,799,358,358,358
BEGIN DESCRIPTION:
UDS St 37 2.0
END DESCRIPTION:
XS GIS Cut Line= 3
      2255879.00      7199359.96      2255879.00      7199810.00
      2256179.02      7200410.03
#Sta/Elev= 30
  4555.0  874.15  4575.0  872.42  4595.0  871.88  4665.0  865.11  4705.0  863.69
  4711.5  862.84  4775.0  858.91  4835.0  856.35  4853.0  853.80  4853.3  853.30
  4857.0  853.80  4905.0  856.22  4925.0  855.74  4935.0  856.43  5035.8  854.72
  5058.2  855.65  5094.5  854.63  5205.3  855.45  5237.0  856.74  5287.3  857.39
  5332.1  859.65  5362.8  861.71  5371.2  862.95  5399.2  864.33  5438.3  868.16
  5466.2  869.60  5505.4  873.25  5541.7  875.33  5622.8  881.69  5675.9  884.62
#Mann=5,-1,0
  4555.0    0.05       0  4711.5    0.12       0  4853.0    0.07       0
  4857.0    0.12       0  5205.3    0.05       0
Bank Sta=4853,4857
Exp/Cntr=0.3,0.1

Type RM Length L Ch R = 1,441,207,207,207
BEGIN DESCRIPTION:
UDS St 37 1.0
END DESCRIPTION:
XS GIS Cut Line= 4
      2255828.97      7199360.03      2255531.50      7199737.52
      2255541.29      7199941.93      2256128.99      7200459.99
#Sta/Elev= 30
  4397.1  874.85  4454.0  872.37  4531.2  866.44  4561.5  862.85  4567.8  863.40
  4582.3  861.42  4652.8  858.87  4675.3  855.89  4716.9  852.44  4859.6  850.87
  4932.6  851.71  4968.3  850.55  4968.5  850.05  4972.3  850.55  4990.3  852.56
  5060.4  852.00  5100.7  853.21  5135.8  850.91  5157.6  852.82  5170.4  852.75
  5433.7  859.29  5511.5  864.67  5560.8  866.03  5582.6  865.28  5625.3  869.23
  5681.3  870.65  5703.1  873.45  5738.2  876.05  5823.6  879.72  5865.8  883.58
#Mann=5,-1,0
  4397.1    0.05       0  4531.2    0.12       0  4968.3    0.07       0
  4972.3    0.12       0  5170.4    0.05       0
Bank Sta=4968.3,4972.3
Exp/Cntr=0.3,0.1

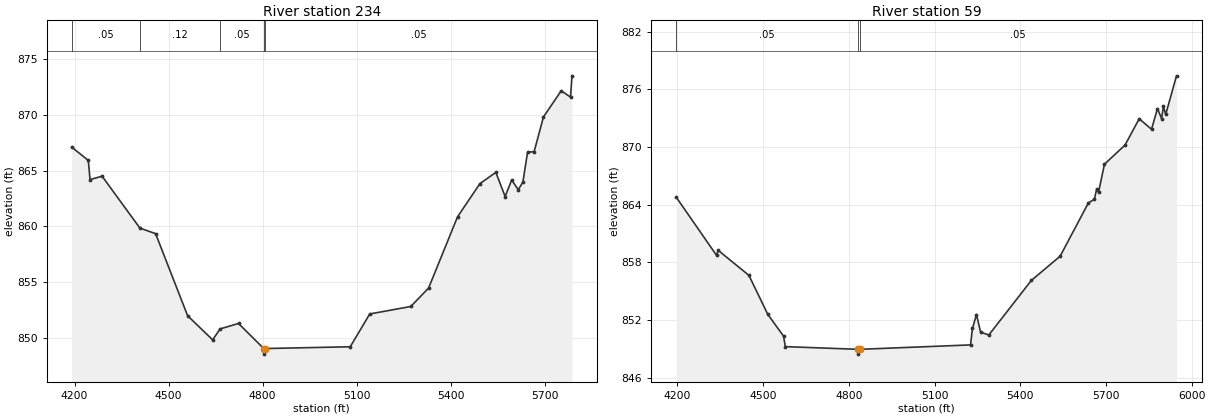
Type RM Length L Ch R = 1,234,175,175,175
BEGIN DESCRIPTION:
UDS St 37 0.9
END DESCRIPTION:
XS GIS Cut Line= 4
      2255670.86      7199182.37      2255342.09      7199808.55
      2255351.85      7200016.42      2255911.14      7200405.41
#Sta/Elev= 30
  4191.0  867.11  4244.0  865.92  4249.6  864.20  4288.1  864.50  4408.7  859.85
  4458.8  859.35  4561.0  851.99  4640.9  849.83  4664.7  850.81  4723.4  851.30
  4804.0  849.05  4804.2  848.55  4808.0  849.05  5079.9  849.21  5142.2  852.15
  5273.1  852.82  5329.9  854.47  5422.4  860.86  5493.9  863.84  5544.6  864.84
  5574.3  862.68  5595.2  864.16  5616.2  863.29  5631.0  863.98  5645.8  866.65
  5666.8  866.70  5696.5  869.81  5753.2  872.16  5782.9  871.59  5787.6  873.50
#Mann=5,-1,0
  4191.0    0.05       0  4408.7    0.12       0  4664.7    0.05       0
  4804.0   0.033       0  4808.0    0.05       0
Bank Sta=4804,4808
Exp/Cntr=0.3,0.1

Type RM Length L Ch R = 1,59,0,0,0
BEGIN DESCRIPTION:
UDS St 37 0.8
END DESCRIPTION:
XS GIS Cut Line= 4
      2255484.02      7199128.74      2255194.42      7199758.74
      2255179.54      7199961.20      2255845.59      7200497.02
#Sta/Elev= 30
  4195.8  864.79  4337.1  858.73  4342.6  859.26  4450.3  856.65  4516.4  852.59
  4571.4  850.33  4577.9  849.23  4833.5  848.95  4833.8  848.45  4837.5  848.95
  5226.1  849.41  5232.7  851.12  5246.9  852.57  5261.3  850.74  5290.0  850.44
  5438.8  856.12  5539.6  858.64  5638.8  864.20  5659.6  864.57  5667.6  865.65
  5674.0  865.29  5694.8  868.22  5766.8  870.21  5816.4  872.95  5859.6  871.86
  5880.4  874.01  5894.8  872.97  5901.2  874.23  5909.2  873.40  5947.0  877.42
#Mann=3,-1,0
  4195.8    0.05       0  4833.5   0.033       0  4837.5    0.05       0
Bank Sta=4833.5,4837.5
Exp/Cntr=0.3,0.1

Chan Stop Cuts=-1