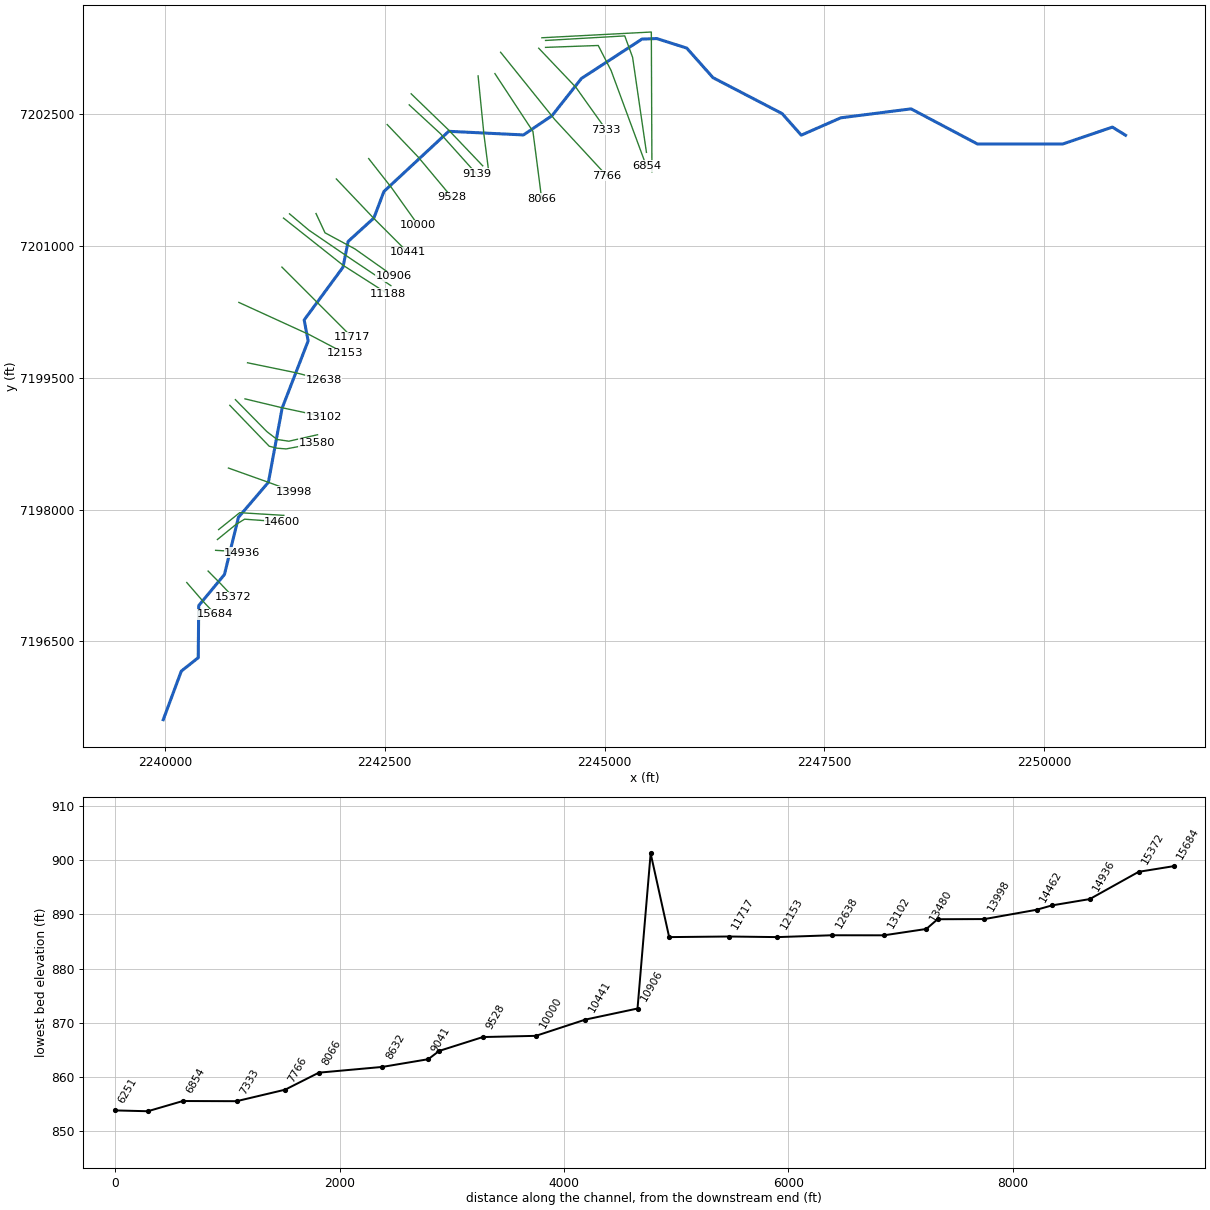
--- UDS St 39.prj (project) ---

Proj Title=UDS St 39 Base Level Engineering
Current Plan=p01
Default Exp/Contr=0.3,0.1
English Units
Geom File=g01
Flow File=f01
Plan File=p01
BEGIN DESCRIPTION:
UDS St 39
END DESCRIPTION:

--- UDS St 39.p01 (plan) ---

Plan Title=Multiple Run
Short Identifier=Multiple
Geom File=g01
Flow File=f01
Subcritical Flow
K Sum by GR= 0
Std Step Tol= 0.01
Critical Tol= 0.01
Num of Std Step Trials= 20
Max Error Tol= 0.3
Flow Tol Ratio= 0.001
Split Flow NTrial= 30
Split Flow Tol= 0.02
Split Flow Ratio= 0.02
Log Output Level= 0
Friction Slope Method= 1
Unsteady Friction Slope Method= 2
Unsteady Bridges Friction Slope Method= 1
Parabolic Critical Depth
Global Vel Dist=  1 , 1 , 1
Global Log Level= 0
CheckData=True
Encroach Param= -1, 0, 0, 0
BEGIN DESCRIPTION:
Multiple Run
END DESCRIPTION:

--- UDS St 39.f01 (steady flow) ---

Flow Title=Multiple
Number of Profiles=7
Profile Names=10-year,25-year,50-year,1pct_min,100-year,1pct_plu,500-year
River Rch & RM= UDS St 39,Reach-1,15684
     780    1102    1376     854    1704    3399    2617
River Rch & RM= UDS St 39,Reach-1,14600
     931    1321    1653    1027    2048    4087    3154
River Rch & RM= UDS St 39,Reach-1,10906
     987    1403    1757    1092    2179    4347    3361
River Rch & RM= UDS St 39,Reach-1,8066
    1312    1889    2388    1496    2984    5954    4676
Boundary for River Rch & Prof#=UDS St 39,Reach-1,1
Up Type=0
Dn Type=3
Dn Slope=0.005
Boundary for River Rch & Prof#=UDS St 39,Reach-1,2
Up Type=0
Dn Type=3
Dn Slope=0.005
Boundary for River Rch & Prof#=UDS St 39,Reach-1,3
Up Type=0
Dn Type=3
Dn Slope=0.005
Boundary for River Rch & Prof#=UDS St 39,Reach-1,4
Up Type=0
Dn Type=3
Dn Slope=0.005
Boundary for River Rch & Prof#=UDS St 39,Reach-1,5
Up Type=0
Dn Type=3
Dn Slope=0.005
Boundary for River Rch & Prof#=UDS St 39,Reach-1,6
Up Type=0
Dn Type=3
Dn Slope=0.005
Boundary for River Rch & Prof#=UDS St 39,Reach-1,7
Up Type=0
Dn Type=3
Dn Slope=0.005

--- UDS St 39.g01 (geometry) ---

Geom Title=Existing Conditions

River Reach=UDS St 39,Reach-1
Reach XY= 30
      2239979.00      7195610.00      2240184.39      7196162.69
      2240376.88      7196315.27      2240382.74      7196908.48
      2240675.25      7197261.55      2240834.47      7197912.45
      2241175.46      7198311.46      2241331.39      7199154.47
      2241627.80      7199920.51      2241582.34      7200158.28
      2242023.88      7200757.71      2242082.48      7201051.58
      2242375.33      7201318.19      2242489.63      7201620.00
      2243226.70      7202304.91      2244077.45      7202263.75
      2244402.84      7202482.86      2244737.19      7202906.33
      2245426.55      7203354.53      2245594.18      7203360.43
      2245935.19      7203252.14      2246234.47      7202915.26
      2247020.68      7202506.84      2247238.70      7202261.25
      2247688.65      7202458.64      2248488.28      7202560.45
      2249244.21      7202160.51      2250213.78      7202160.52
      2250779.09      7202352.72      2250929.00      7202260.00

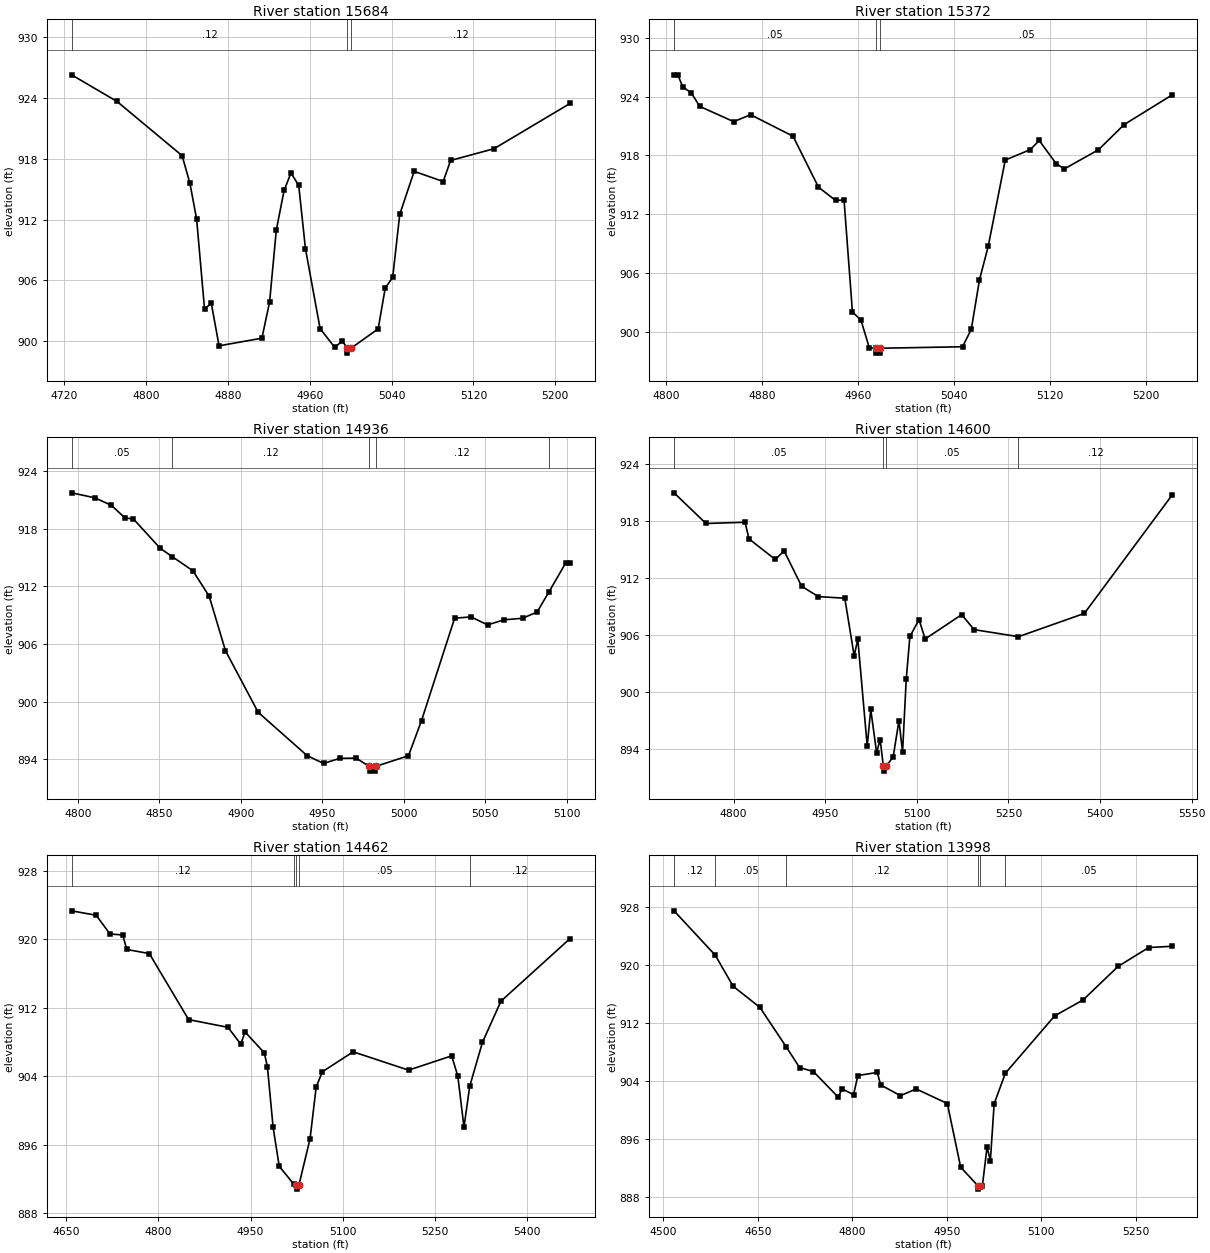
Type RM Length L Ch R = 1,15684,312,312,312
BEGIN DESCRIPTION:
UDS St 39 26.0
END DESCRIPTION:
XS GIS Cut Line= 3
      2240246.75      7197170.72      2240429.00      7196960.00
      2240572.25      7196808.09
#Sta/Elev= 30
  4727.0  926.24  4771.4  923.62  4835.1  918.28  4842.7  915.57  4849.3  912.02
  4857.0  903.19  4863.6  903.76  4871.2  899.57  4913.1  900.32  4920.6  903.87
  4927.2  910.97  4934.8  914.86  4941.5  916.58  4949.1  915.36  4955.7  909.12
  4970.0  901.27  4984.2  899.43  4991.9  900.03  4996.5  899.35  4996.7  898.85
  5000.5  899.35  5026.8  901.24  5033.7  905.26  5041.0  906.30  5047.9  912.51
  5062.0  916.74  5090.4  915.74  5097.6  917.81  5140.1  918.97  5214.4  923.42
#Mann=3,-1,0
  4727.0    0.12       0  4996.5    0.07       0  5000.5    0.12       0
Bank Sta=4996.5,5000.5
Exp/Cntr=0.3,0.1

Type RM Length L Ch R = 1,15372,436,436,436
BEGIN DESCRIPTION:
UDS St 39 25.0
END DESCRIPTION:
XS GIS Cut Line= 3
      2240489.62      7197300.92      2240629.00      7197160.00
      2240778.25      7197002.07
#Sta/Elev= 30
  4806.8  926.22  4809.9  926.22  4814.1  924.99  4821.2  924.37  4828.2  923.00
  4856.5  921.44  4870.6  922.15  4906.0  919.95  4927.2  914.75  4941.4  913.40
  4948.5  913.44  4955.5  902.01  4962.6  901.18  4969.6  898.34  4974.8  898.31
  4975.0  897.81  4978.5  897.81  4978.8  898.31  5047.3  898.46  5054.6  900.25
  5061.4  905.29  5068.7  908.72  5082.9  917.52  5103.9  918.59  5111.2  919.52
  5125.4  917.14  5132.2  916.62  5160.6  918.57  5182.0  921.14  5222.3  924.19
#Mann=3,-1,0
  4806.8    0.05       0  4974.8   0.033       0  4978.8    0.05       0
Bank Sta=4974.8,4978.8
Exp/Cntr=0.3,0.1

Type RM Length L Ch R = 1,14936,336,336,336
BEGIN DESCRIPTION:
UDS St 39 24.0
END DESCRIPTION:
XS GIS Cut Line= 3
      2240574.72      7197537.14      2240781.06      7197525.03
      2240879.01      7197510.00
#Sta/Elev= 30
  4796.2  921.72  4810.5  921.20  4820.5  920.43  4829.1  919.10  4834.1  919.01
  4850.6  915.95  4857.8  915.10  4870.6  913.62  4880.6  910.98  4890.6  905.31
  4910.7  898.90  4940.7  894.40  4950.8  893.59  4960.8  894.12  4970.8  894.14
  4978.7  893.29  4979.1  892.79  4982.6  892.79  4982.9  893.29  5002.9  894.39
  5010.9  898.05  5031.2  908.69  5041.3  908.82  5051.4  907.99  5061.5  908.52
  5072.9  908.68  5081.8  909.33  5089.0  911.40  5099.5  914.47  5102.0  914.47
#Mann=5,-1,0
  4796.2    0.05       0  4857.8    0.12       0  4978.7    0.07       0
  4982.9    0.12       0  5089.0    0.05       0
Bank Sta=4978.7,4982.9
Exp/Cntr=0.3,0.1

Type RM Length L Ch R = 1,14600,138,138,138
BEGIN DESCRIPTION:
UDS St 39 23.1
END DESCRIPTION:
XS GIS Cut Line= 4
      2240595.51      7197660.28      2240804.61      7197829.99
      2240904.28      7197891.44      2241332.97      7197860.45
#Sta/Elev= 30
  4702.4  920.94  4754.7  917.71  4818.7  917.84  4825.1  916.09  4868.2  913.92
  4882.6  914.83  4911.3  911.10  4938.7  910.01  4982.0  909.84  4997.4  903.76
  5003.3  905.55  5018.7  894.27  5024.5  898.13  5034.1  893.57  5039.9  894.96
  5045.2  892.13  5045.5  891.63  5049.4  892.13  5061.2  893.12  5070.7  896.94
  5076.6  893.64  5082.6  901.30  5088.6  905.81  5103.6  907.58  5113.6  905.55
  5173.4  908.11  5193.8  906.53  5266.4  905.79  5374.3  908.24  5518.6  920.76
#Mann=4,-1,0
  4702.4    0.05       0  5045.2   0.033       0  5049.4    0.05       0
  5266.4    0.12       0
Bank Sta=5045.2,5049.4
Exp/Cntr=0.3,0.1

Type RM Length L Ch R = 1,14462,464,464,464
BEGIN DESCRIPTION:
UDS St 39 23.0
END DESCRIPTION:
XS GIS Cut Line= 3
      2240609.07      7197772.94      2240848.47      7197965.43
      2241351.17      7197935.07
#Sta/Elev= 30
  4658.8  923.31  4698.8  922.79  4721.2  920.61  4742.0  920.49  4748.5  918.80
  4785.2  918.32  4849.2  910.61  4913.2  909.71  4934.0  907.75  4941.0  909.17
  4972.3  906.73  4977.3  905.13  4986.6  898.04  4996.6  893.48  5020.2  891.40
  5024.5  891.32  5024.8  890.82  5028.7  891.32  5046.7  896.70  5056.7  902.75
  5066.7  904.52  5116.8  906.85  5207.0  904.71  5277.1  906.38  5287.1  904.00
  5297.1  898.05  5306.4  902.82  5327.2  907.97  5357.2  912.76  5469.6  920.07
#Mann=5,-1,0
  4658.8    0.12       0  5020.2    0.05       0  5024.5    0.07       0
  5028.7    0.05       0  5306.4    0.12       0
Bank Sta=5024.5,5028.7
Exp/Cntr=0.3,0.1

Type RM Length L Ch R = 1,13998,418,418,418
BEGIN DESCRIPTION:
UDS St 39 22.0
END DESCRIPTION:
XS GIS Cut Line= 3
      2240720.72      7198473.42      2241179.00      7198310.00
      2241464.52      7198205.18
#Sta/Elev= 30
  4517.3  927.53  4582.6  921.41  4611.0  917.12  4653.5  914.20  4695.4  908.73
  4716.4  905.90  4738.4  905.34  4778.1  901.77  4783.4  902.96  4802.1  902.15
  4808.9  904.79  4839.7  905.22  4845.0  903.50  4876.4  902.01  4901.3  902.94
  4950.8  900.93  4972.0  892.13  4999.0  889.61  4999.4  889.11  5003.4  889.61
  5006.5  889.61  5013.8  894.91  5019.1  893.05  5025.1  900.90  5042.9  905.11
  5121.0  913.02  5166.2  915.23  5221.8  919.86  5270.2  922.46  5308.0  922.64
#Mann=6,-1,0
  4517.3    0.12       0  4582.6    0.05       0  4695.4    0.12       0
  4999.0    0.07       0  5003.4    0.12       0  5042.9    0.05       0
Bank Sta=4999,5003.4
Exp/Cntr=0.3,0.1

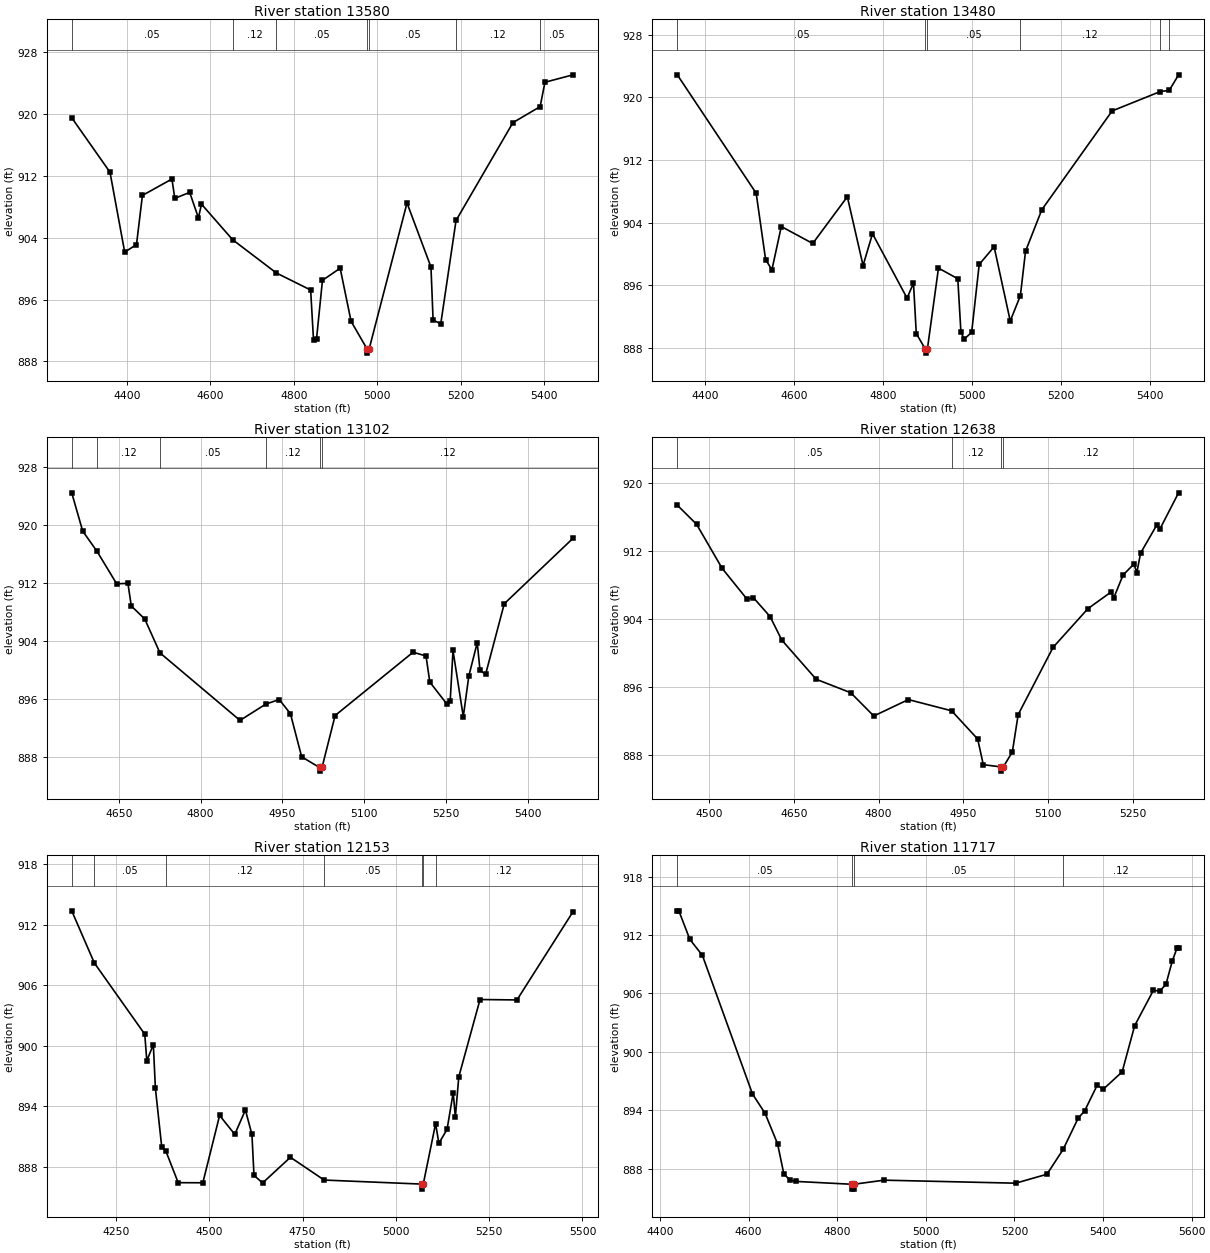
Type RM Length L Ch R = 1,13580,100,100,100
BEGIN DESCRIPTION:
UDS St 39 21.0
END DESCRIPTION:
XS GIS Cut Line= 5
      2240736.47      7199186.93      2241184.75      7198721.52
      2241270.62      7198699.74      2241376.52      7198691.01
      2241730.42      7198757.33
#Sta/Elev= 30
  4267.7  919.51  4359.4  912.47  4394.6  902.14  4422.9  903.11  4437.1  909.47
  4507.8  911.59  4514.7  909.09  4550.3  909.86  4571.3  906.57  4578.6  908.34
  4653.3  903.74  4758.1  899.44  4840.2  897.24  4847.1  890.74  4854.3  890.93
  4868.5  898.49  4910.9  900.06  4937.1  893.19  4975.8  889.58  4976.2  889.08
  4980.2  889.58  5071.1  908.49  5128.5  900.21  5133.6  893.35  5152.0  892.88
  5188.6  906.23  5324.9  918.88  5390.1  920.95  5401.6  924.10  5468.8  925.06
#Mann=7,-1,0
  4267.7    0.05       0  4653.3    0.12       0  4758.1    0.05       0
  4975.8   0.033       0  4980.2    0.05       0  5188.6    0.12       0
  5390.1    0.05       0
Bank Sta=4975.8,4980.2
Exp/Cntr=0.3,0.1

Type RM Length L Ch R = 1,13480,378,378,378
BEGIN DESCRIPTION:
UDS St 39 20.1
END DESCRIPTION:
XS GIS Cut Line= 5
      2240799.77      7199251.58      2241158.66      7198887.53
      2241274.13      7198798.47      2241407.90      7198778.83
      2241734.77      7198852.46
#Sta/Elev= 30
  4337.9  922.90  4515.3  907.75  4536.5  899.27  4550.7  897.95  4571.8  903.49
  4642.5  901.32  4720.3  907.30  4755.7  898.50  4776.9  902.57  4854.6  894.33
  4869.1  896.24  4875.4  889.79  4895.9  887.79  4896.3  887.29  4900.3  887.79
  4925.3  898.17  4968.7  896.81  4975.8  889.95  4983.2  889.09  4999.9  889.95
  5016.9  898.64  5050.4  900.90  5086.7  891.40  5109.5  894.65  5121.1  900.33
  5157.6  905.63  5315.8  918.28  5423.7  920.75  5444.3  920.92  5465.2  922.88
#Mann=6,-1,0
  4337.9    0.05       0  4895.9   0.033       0  4900.3    0.05       0
  5109.5    0.12       0  5423.7    0.05       0  5444.3    0.12       0
Bank Sta=4895.9,4900.3
Exp/Cntr=0.3,0.1

Type RM Length L Ch R = 1,13102,464,464,464
BEGIN DESCRIPTION:
UDS St 39 20.0
END DESCRIPTION:
XS GIS Cut Line= 3
      2240908.73      7199260.73      2241329.00      7199160.00
      2241805.92      7199058.41
#Sta/Elev= 30
  4563.6  924.41  4583.7  919.15  4609.9  916.37  4646.1  911.89  4666.7  911.96
  4672.9  908.84  4697.6  907.05  4725.5  902.39  4872.4  893.10  4919.7  895.34
  4944.4  895.97  4964.9  894.02  4985.5  888.09  5018.3  886.62  5018.7  886.12
  5022.9  886.62  5046.9  893.77  5190.0  902.48  5213.7  901.96  5220.7  898.37
  5251.4  895.41  5258.1  895.75  5263.2  902.72  5282.1  893.62  5292.3  899.22
  5307.7  903.79  5312.8  899.99  5323.0  899.42  5357.3  909.15  5483.4  918.15
#Mann=6,-1,0
  4563.6    0.05       0  4609.9    0.12       0  4725.5    0.05       0
  4919.7    0.12       0  5018.3    0.07       0  5022.9    0.12       0
Bank Sta=5018.3,5022.9
Exp/Cntr=0.3,0.1

Type RM Length L Ch R = 1,12638,485,485,485
BEGIN DESCRIPTION:
UDS St 39 19.0
END DESCRIPTION:
XS GIS Cut Line= 3
      2240937.95      7199671.35      2241479.00      7199560.00
      2241804.18      7199476.17
#Sta/Elev= 30
  4443.3  917.39  4477.5  915.14  4522.7  909.97  4566.9  906.34  4578.1  906.52
  4607.7  904.30  4628.4  901.54  4689.4  896.93  4750.7  895.34  4791.5  892.61
  4852.8  894.54  4929.4  893.22  4975.6  889.90  4985.5  886.89  5016.3  886.63
  5016.8  886.13  5021.0  886.63  5037.0  888.38  5047.3  892.77  5109.3  900.69
  5171.0  905.23  5211.7  907.17  5216.9  906.53  5233.2  909.18  5252.4  910.47
  5257.6  909.46  5264.2  911.75  5293.1  915.08  5298.2  914.55  5331.5  918.84
#Mann=4,-1,0
  4443.3    0.05       0  4929.4    0.12       0  5016.3    0.07       0
  5021.0    0.12       0
Bank Sta=5016.3,5021
Exp/Cntr=0.3,0.1

Type RM Length L Ch R = 1,12153,436,436,436
BEGIN DESCRIPTION:
UDS St 39 18.0
END DESCRIPTION:
XS GIS Cut Line= 3
      2240839.52      7200357.98      2241640.19      7199991.80
      2242050.06      7199776.93
#Sta/Elev= 30
  4131.4  913.40  4192.1  908.22  4327.1  901.16  4332.6  898.53  4350.1  900.12
  4355.6  895.79  4372.7  889.93  4384.0  889.53  4416.7  886.43  4482.7  886.42
  4527.7  893.10  4568.3  891.22  4596.8  893.64  4614.3  891.21  4619.8  887.16
  4642.8  886.40  4717.4  888.95  4807.8  886.69  5068.7  886.29  5069.2  885.79
  5073.4  886.29  5106.5  892.29  5115.2  890.33  5137.2  891.73  5153.7  895.37
  5159.3  892.91  5168.6  896.93  5225.5  904.60  5324.5  904.56  5474.6  913.31
#Mann=7,-1,0
  4131.4    0.12       0  4192.1    0.05       0  4384.0    0.12       0
  4807.8    0.05       0  5068.7   0.033       0  5073.4    0.05       0
  5106.5    0.12       0
Bank Sta=5068.7,5073.4
Exp/Cntr=0.3,0.1

Type RM Length L Ch R = 1,11717,529,529,529
BEGIN DESCRIPTION:
UDS St 39 17.0
END DESCRIPTION:
XS GIS Cut Line= 3
      2241329.01      7200759.99      2241729.00      7200360.00
      2242129.03      7199959.97
#Sta/Elev= 30
  4439.1  914.48  4442.6  914.48  4467.4  911.55  4495.7  909.91  4608.8  895.67
  4637.1  893.70  4665.4  890.56  4679.5  887.48  4693.6  886.81  4707.8  886.69
  4832.5  886.40  4833.2  885.90  4837.0  885.90  4837.6  886.40  4905.8  886.82
  5202.8  886.51  5273.5  887.43  5309.9  889.97  5344.2  893.21  5358.3  893.91
  5386.6  896.55  5400.8  896.17  5443.2  897.94  5471.5  902.69  5513.9  906.33
  5528.0  906.22  5542.2  906.95  5556.3  909.32  5566.9  910.63  5570.5  910.63
#Mann=4,-1,0
  4439.1    0.05       0  4832.5   0.033       0  4837.6    0.05       0
  5309.9    0.12       0
Bank Sta=4832.5,4837.6
Exp/Cntr=0.3,0.1

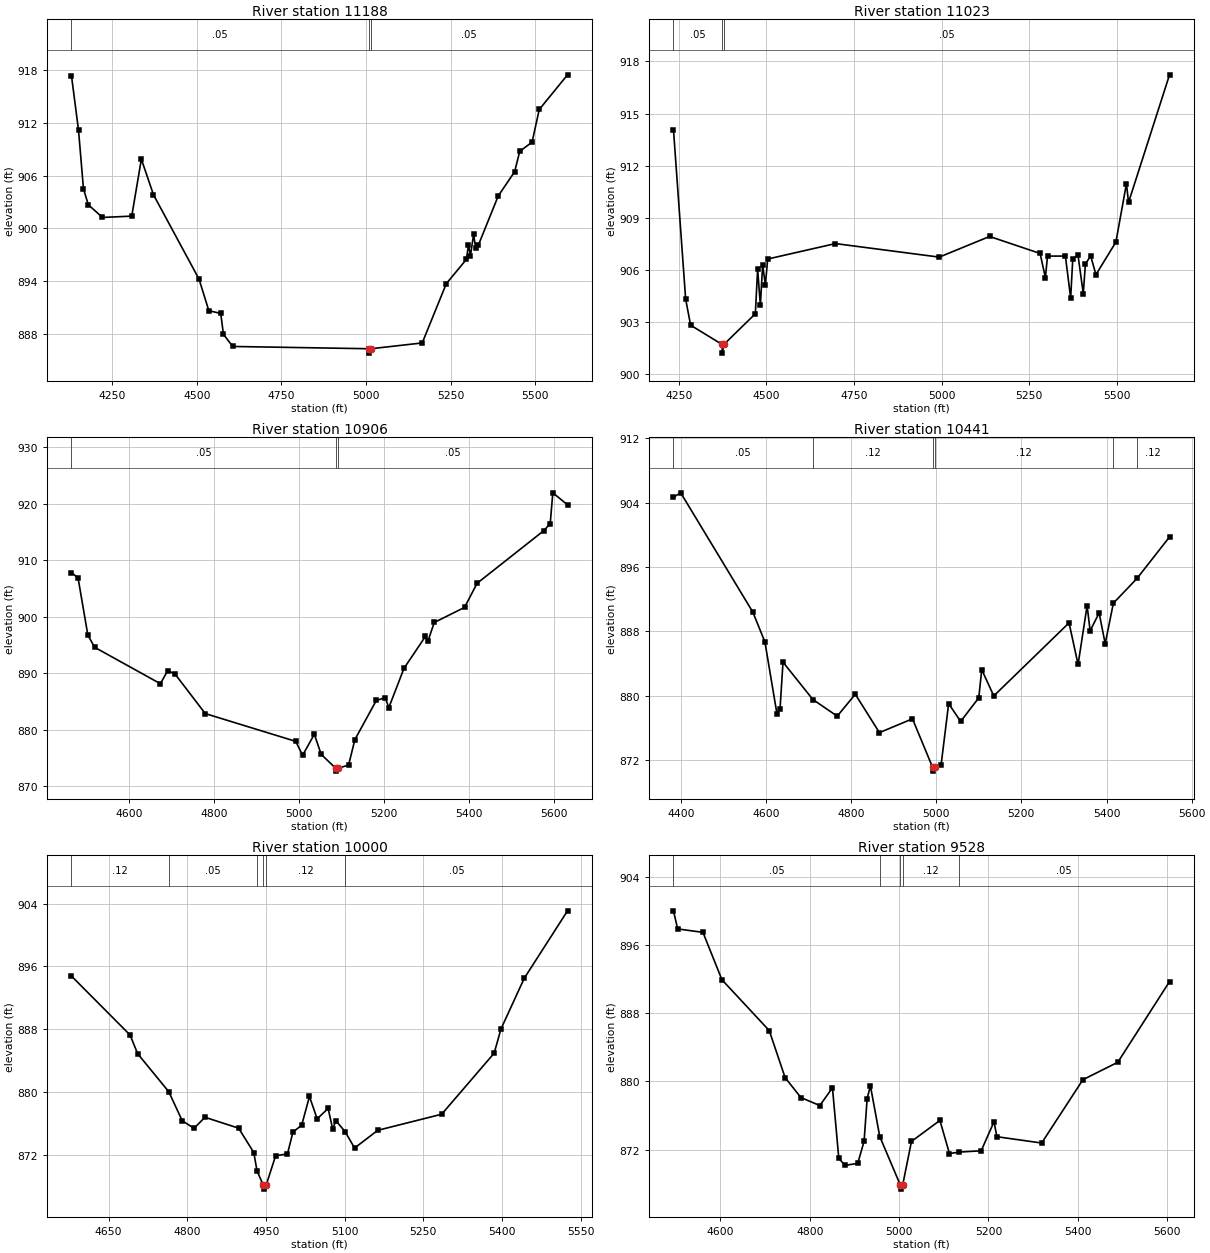
Type RM Length L Ch R = 1,11188,165,165,165
BEGIN DESCRIPTION:
UDS St 39 16.0
END DESCRIPTION:
XS GIS Cut Line= 3
      2241347.19      7201317.69      2242028.83      7200778.02
      2242530.68      7200457.66
#Sta/Elev= 30
  4130.2  917.40  4151.1  911.16  4165.6  904.51  4180.0  902.69  4221.8  901.25
  4308.2  901.40  4336.6  907.89  4372.3  903.84  4506.9  894.22  4535.8  890.63
  4571.0  890.31  4578.9  887.94  4606.3  886.55  5009.1  886.29  5009.8  885.79
  5014.3  886.29  5165.9  886.95  5237.1  893.71  5296.4  896.47  5302.5  898.09
  5308.4  896.91  5317.7  899.34  5323.6  897.81  5332.0  898.12  5390.4  903.70
  5438.8  906.46  5453.9  908.78  5490.3  909.83  5511.5  913.55  5595.0  917.50
#Mann=3,-1,0
  4130.2    0.05       0  5009.1   0.033       0  5014.3    0.05       0
Bank Sta=5009.1,5014.3
Exp/Cntr=0.3,0.1

Type RM Length L Ch R = 1,11023,117,117,117
BEGIN DESCRIPTION:
UDS St 39 15.1
END DESCRIPTION:
XS GIS Cut Line= 4
      2241415.77      7201365.87      2241636.26      7201179.86
      2242112.39      7200854.92      2242569.49      7200548.89
#Sta/Elev= 30
  4234.8  914.08  4269.5  904.32  4283.7  902.81  4373.5  901.70  4374.2  901.20
  4378.7  901.70  4468.4  903.47  4474.9  906.04  4482.7  903.95  4489.2  906.28
  4497.0  905.12  4503.5  906.62  4696.8  907.51  4992.9  906.73  5136.6  907.92
  5280.7  906.94  5295.7  905.55  5301.8  906.79  5352.8  906.79  5367.8  904.37
  5373.8  906.62  5388.8  906.83  5403.8  904.63  5409.8  906.32  5424.8  906.81
  5439.9  905.72  5496.9  907.60  5526.9  910.96  5532.9  909.88  5649.8  917.23
#Mann=3,-1,0
  4234.8    0.05       0  4373.5   0.033       0  4378.7    0.05       0
Bank Sta=4373.5,4378.7
Exp/Cntr=0.3,0.1

Type RM Length L Ch R = 1,10906,465,465,465
BEGIN DESCRIPTION:
UDS St 39 15.0
END DESCRIPTION:
XS GIS Cut Line= 4
      2241717.43      7201369.26      2241819.47      7201150.26
      2242160.81      7200966.16      2242601.89      7200654.68
#Sta/Elev= 30
  4463.6  907.81  4479.2  906.83  4502.1  896.78  4517.9  894.58  4673.2  888.12
  4690.6  890.45  4707.8  889.83  4779.0  882.83  4992.3  877.91  5008.5  875.45
  5036.1  879.16  5052.3  875.61  5086.6  873.14  5087.3  872.64  5091.8  873.14
  5116.9  873.72  5131.7  878.22  5182.2  885.15  5203.1  885.64  5211.8  883.90
  5247.5  890.84  5297.9  896.48  5304.1  895.69  5318.8  898.96  5390.2  901.63
  5419.8  905.90  5577.4  915.24  5592.2  916.47  5598.3  921.92  5633.0  919.80
#Mann=3,-1,0
  4463.6    0.05       0  5086.6   0.033       0  5091.8    0.05       0
Bank Sta=5086.6,5091.8
Exp/Cntr=0.3,0.1

Type RM Length L Ch R = 1,10441,441,441,441
BEGIN DESCRIPTION:
UDS St 39 14.0
END DESCRIPTION:
XS GIS Cut Line= 3
      2241948.20      7201763.02      2242379.00      7201310.00
      2242761.19      7200928.44
#Sta/Elev= 30
  4382.8  904.69  4399.8  905.23  4569.3  890.38  4597.6  886.68  4625.9  877.73
  4633.2  878.38  4640.1  884.16  4710.3  879.51  4767.5  877.44  4809.9  880.17
  4866.6  875.39  4944.2  877.11  4991.3  871.10  4992.0  870.60  4996.7  871.10
  5011.5  871.39  5029.2  879.00  5057.4  876.78  5099.9  879.72  5106.9  883.23
  5135.2  879.96  5312.0  889.05  5333.2  883.87  5354.4  891.19  5361.5  888.07
  5382.7  890.28  5396.9  886.45  5416.1  891.50  5471.5  894.57  5548.0  899.74
#Mann=6,-1,0
  4382.8    0.05       0  4710.3    0.12       0  4991.3    0.07       0
  4996.7    0.12       0  5416.1    0.05       0  5471.5    0.12       0
Bank Sta=4991.3,4996.7
Exp/Cntr=0.3,0.1

Type RM Length L Ch R = 1,10000,472,472,472
BEGIN DESCRIPTION:
UDS St 39 13.0
END DESCRIPTION:
XS GIS Cut Line= 3
      2242316.49      7201994.72      2242579.00      7201660.00
      2242880.52      7201235.96
#Sta/Elev= 30
  4579.2  894.77  4690.9  887.26  4705.4  884.87  4764.7  880.03  4790.4  876.32
  4812.9  875.37  4833.7  876.77  4897.9  875.38  4926.8  872.27  4932.9  869.94
  4944.9  868.11  4945.7  867.61  4950.3  868.11  4968.4  871.86  4991.0  872.10
  5001.4  874.88  5018.1  875.76  5032.9  879.42  5047.6  876.57  5068.5  877.90
  5077.2  875.27  5083.3  876.33  5101.0  874.93  5118.9  872.85  5163.2  875.11
  5285.0  877.16  5385.0  884.94  5398.1  888.04  5442.4  894.49  5524.9  903.09
#Mann=6,-1,0
  4579.2    0.12       0  4764.7    0.05       0  4932.9    0.12       0
  4944.9    0.07       0  4950.3    0.12       0  5101.0    0.05       0
Bank Sta=4944.9,4950.3
Exp/Cntr=0.3,0.1

Type RM Length L Ch R = 1,9528,389,389,389
BEGIN DESCRIPTION:
UDS St 39 12.0
END DESCRIPTION:
XS GIS Cut Line= 3
      2242527.44      7202381.77      2242882.35      7202009.67
      2243264.73      7201551.87
#Sta/Elev= 30
  4494.7  899.99  4504.1  897.87  4560.7  897.47  4603.2  891.92  4709.2  885.96
  4744.7  880.45  4780.0  878.12  4822.4  877.18  4850.7  879.26  4864.9  870.99
  4879.0  870.17  4907.3  870.41  4921.5  872.99  4928.4  878.00  4935.7  879.49
  4956.6  873.55  5002.5  867.89  5003.3  867.39  5008.0  867.89  5027.6  872.98
  5091.3  875.44  5112.7  871.55  5134.0  871.73  5183.7  871.88  5212.4  875.28
  5218.9  873.53  5319.1  872.79  5411.5  880.21  5489.6  882.25  5605.4  891.70
#Mann=5,-1,0
  4494.7    0.05       0  4956.6    0.12       0  5002.5    0.07       0
  5008.0    0.12       0  5134.0    0.05       0
Bank Sta=5002.5,5008
Exp/Cntr=0.3,0.1

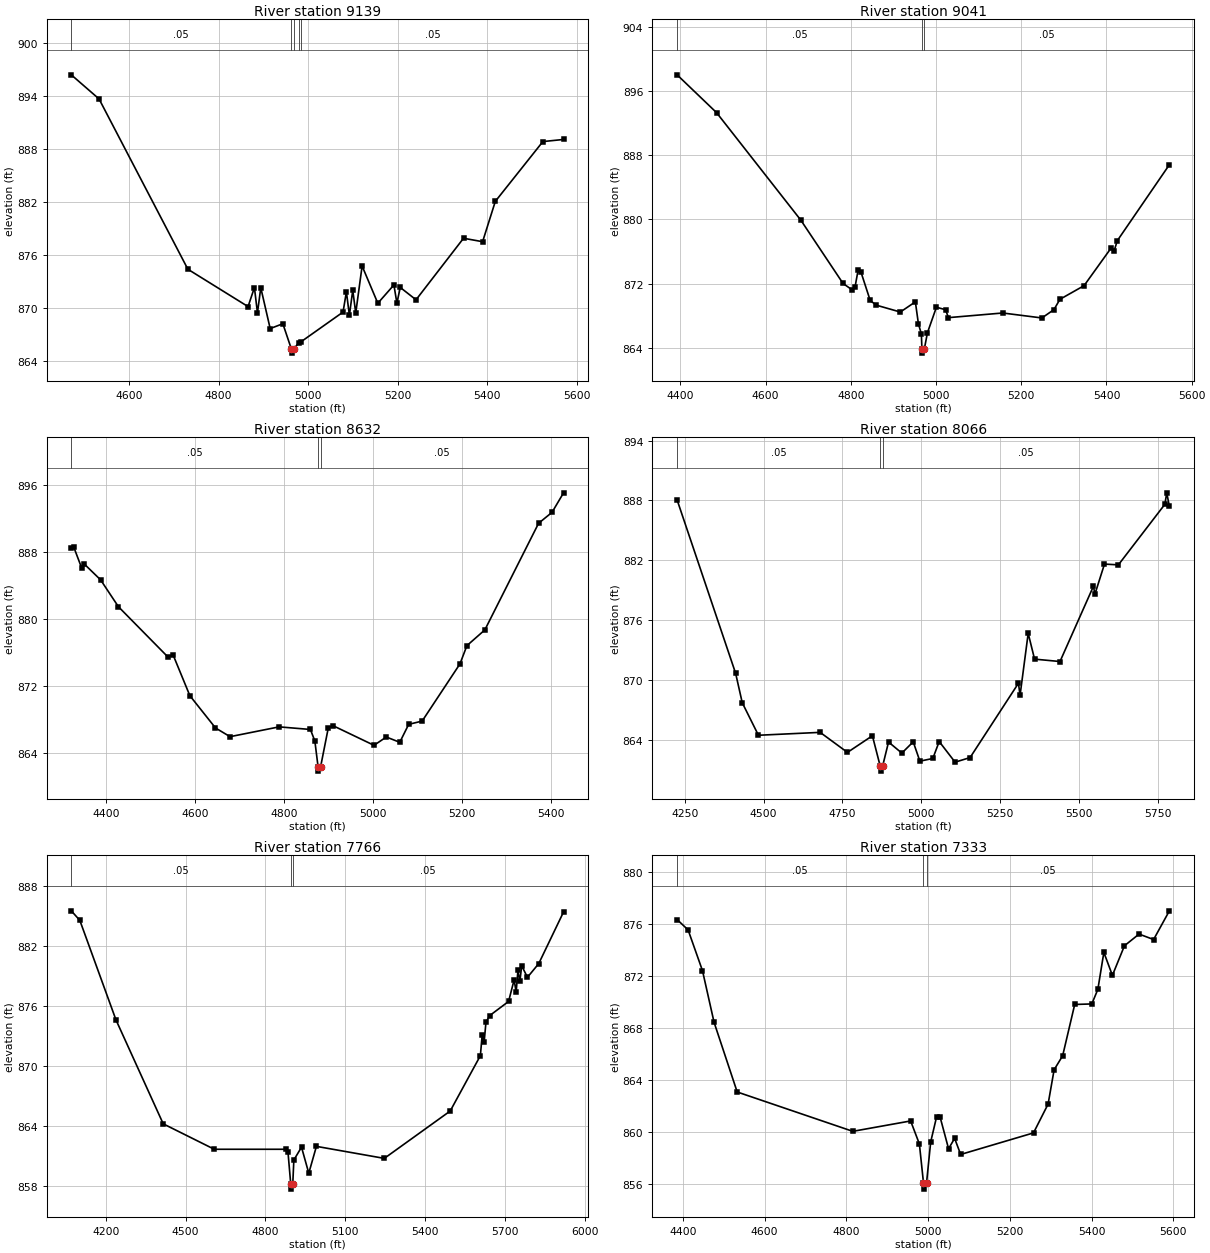
Type RM Length L Ch R = 1,9139,98,98,98
BEGIN DESCRIPTION:
UDS St 39 11.0
END DESCRIPTION:
XS GIS Cut Line= 3
      2242777.37      7202606.00      2243134.43      7202276.63
      2243544.43      7201820.09
#Sta/Elev= 30
  4471.0  896.36  4533.0  893.63  4731.4  874.34  4865.8  870.11  4880.0  872.27
  4886.8  869.39  4894.2  872.25  4915.2  867.62  4943.5  868.17  4962.3  865.34
  4963.1  864.84  4967.8  865.34  4979.7  866.02  4984.2  866.13  5077.9  869.49
  5085.4  871.78  5092.1  869.13  5099.6  871.96  5106.3  869.38  5120.5  874.71
  5155.6  870.49  5191.5  872.56  5198.2  870.51  5205.7  872.28  5240.9  870.88
  5347.0  877.85  5389.6  877.46  5418.0  882.03  5524.2  888.80  5570.4  889.04
#Mann=5,-1,0
  4471.0    0.05       0  4962.3   0.033       0  4967.8    0.05       0
  4979.7    0.12       0  4984.2    0.05       0
Bank Sta=4962.3,4967.8
Exp/Cntr=0.3,0.1

Type RM Length L Ch R = 1,9041,409,409,409
BEGIN DESCRIPTION:
UDS St 39 10.1
END DESCRIPTION:
XS GIS Cut Line= 3
      2242799.87      7202731.74      2243216.74      7202329.28
      2243614.26      7201912.22
#Sta/Elev= 30
  4392.1  898.05  4484.7  893.33  4682.8  879.89  4781.6  872.01  4802.9  871.21
  4809.9  871.60  4817.1  873.70  4824.0  873.38  4845.4  869.88  4859.5  869.30
  4916.1  868.44  4951.4  869.71  4958.6  866.96  4965.5  865.71  4966.8  863.81
  4967.7  863.31  4972.4  863.81  4979.8  865.86  5000.8  869.04  5022.2  868.73
  5029.1  867.74  5156.5  868.32  5248.4  867.70  5276.7  868.74  5290.8  870.03
  5347.4  871.73  5411.3  876.46  5418.2  876.11  5425.5  877.35  5547.7  886.83
#Mann=3,-1,0
  4392.1    0.05       0  4966.8   0.033       0  4972.4    0.05       0
Bank Sta=4966.8,4972.4
Exp/Cntr=0.3,0.1

Type RM Length L Ch R = 1,8632,566,566,566
BEGIN DESCRIPTION:
UDS St 39 10.0
END DESCRIPTION:
XS GIS Cut Line= 3
      2243561.46      7202935.72      2243629.00      7202260.00
      2243683.91      7201834.21
#Sta/Elev= 30
  4320.9  888.50  4326.6  888.60  4344.1  886.15  4349.1  886.65  4386.9  884.71
  4427.1  881.50  4537.7  875.55  4550.1  875.76  4587.9  870.89  4645.6  867.04
  4678.4  866.00  4788.9  867.17  4859.3  866.86  4869.3  865.49  4876.6  862.39
  4877.4  861.89  4882.2  862.39  4899.5  867.03  4909.5  867.33  5002.5  864.97
  5030.2  865.96  5060.5  865.33  5080.6  867.47  5110.9  867.86  5196.0  874.68
  5211.7  876.86  5252.1  878.74  5373.1  891.46  5403.3  892.76  5429.3  895.09
#Mann=3,-1,0
  4320.9    0.05       0  4876.6    0.04       0  4882.2    0.05       0
Bank Sta=4876.6,4882.2
Exp/Cntr=0.3,0.1

Type RM Length L Ch R = 1,8066,300,300,300
BEGIN DESCRIPTION:
UDS St 39 9.0
END DESCRIPTION:
XS GIS Cut Line= 3
      2243752.93      7202961.54      2244185.43      7202303.83
      2244284.97      7201535.83
#Sta/Elev= 30
  4225.4  888.05  4411.1  870.64  4432.1  867.69  4483.4  864.43  4679.2  864.72
  4765.8  862.71  4844.9  864.38  4869.7  861.33  4870.9  860.83  4877.3  861.33
  4896.1  863.75  4938.3  862.64  4974.4  863.77  4995.5  861.83  5036.6  862.10
  5056.8  863.80  5107.2  861.73  5154.8  862.19  5308.2  869.65  5313.3  868.43
  5339.1  874.66  5359.3  872.07  5440.0  871.83  5545.9  879.37  5551.0  878.61
  5581.1  881.61  5625.2  881.53  5772.7  887.61  5778.6  888.76  5787.0  887.40
#Mann=3,-1,0
  4225.4    0.05       0  4869.7    0.04       0  4877.3    0.05       0
Bank Sta=4869.7,4877.3
Exp/Cntr=0.3,0.1

Type RM Length L Ch R = 1,7766,433,433,433
BEGIN DESCRIPTION:
UDS St 39 8.0
END DESCRIPTION:
XS GIS Cut Line= 3
      2243817.59      7203204.58      2244431.42      7202441.64
      2245023.17      7201802.00
#Sta/Elev= 30
  4070.5  885.49  4102.6  884.54  4238.5  874.60  4416.1  864.22  4608.1  861.68
  4878.5  861.68  4885.0  861.44  4895.5  858.20  4896.6  857.70  4903.1  858.20
  4907.2  860.61  4936.0  861.89  4963.3  859.29  4992.0  861.97  5247.2  860.77
  5495.0  865.50  5608.4  871.03  5615.2  873.10  5622.6  872.40  5629.4  874.37
  5643.5  875.03  5714.4  876.44  5735.4  878.61  5742.8  877.35  5749.6  879.54
  5756.9  878.44  5763.7  880.01  5785.3  878.85  5827.8  880.22  5921.1  885.38
#Mann=3,-1,0
  4070.5    0.05       0  4895.5    0.04       0  4903.1    0.05       0
Bank Sta=4895.5,4903.1
Exp/Cntr=0.3,0.1

Type RM Length L Ch R = 1,7333,479,479,479
BEGIN DESCRIPTION:
UDS St 39 7.0
END DESCRIPTION:
XS GIS Cut Line= 3
      2244251.55      7203250.31      2244673.42      7202806.64
      2245016.97      7202324.43
#Sta/Elev= 30
  4386.0  876.34  4412.9  875.54  4448.1  872.40  4476.4  868.43  4533.0  863.06
  4815.8  860.03  4957.3  860.83  4978.7  859.06  4988.7  856.08  4989.8  855.58
  4996.3  856.08  5006.4  859.22  5020.6  861.12  5029.2  861.15  5050.1  858.69
  5064.9  859.49  5079.7  858.25  5257.9  859.91  5293.6  862.13  5308.3  864.77
  5329.2  865.85  5358.7  869.80  5400.5  869.84  5415.3  870.96  5430.0  873.81
  5450.9  872.04  5480.4  874.32  5516.1  875.22  5551.7  874.80  5590.3  877.01
#Mann=3,-1,0
  4386.0    0.05       0  4988.7    0.04       0  4996.3    0.05       0
Bank Sta=4988.7,4996.3
Exp/Cntr=0.3,0.1

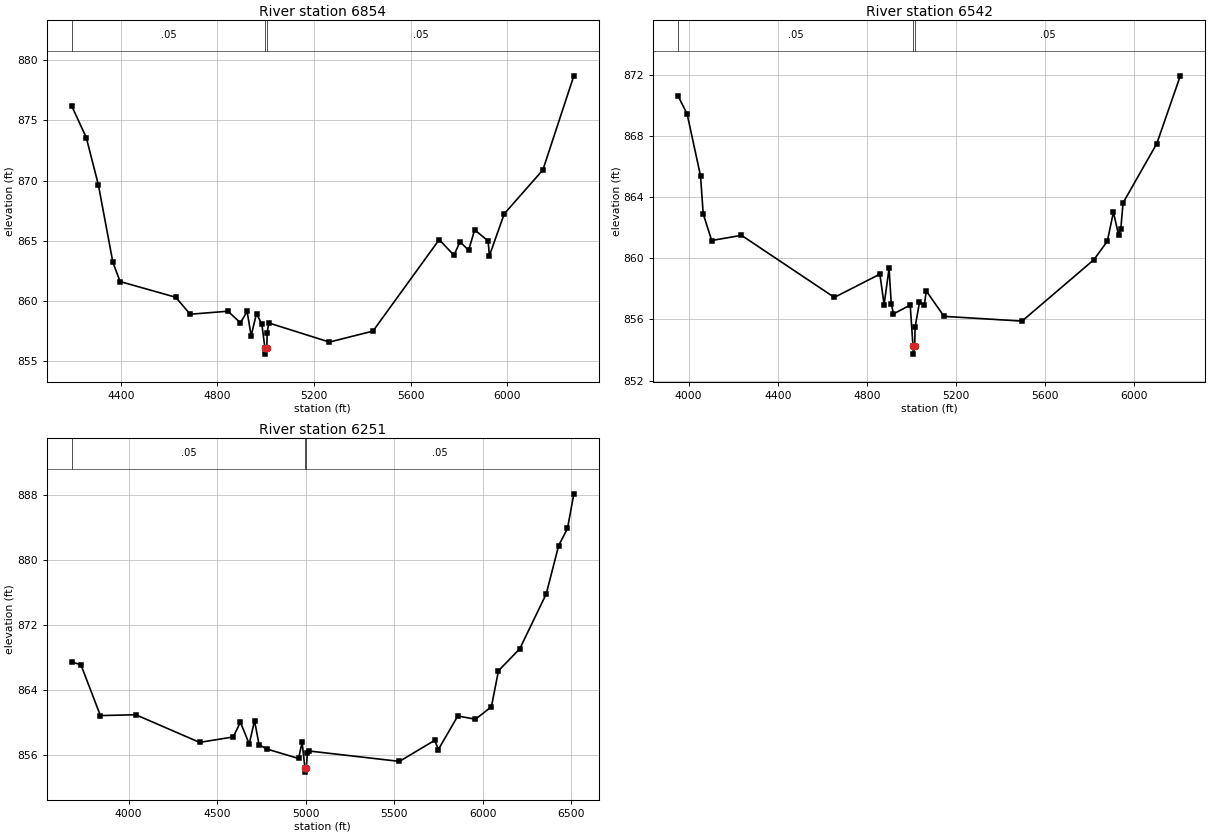
Type RM Length L Ch R = 1,6854,312,312,312
BEGIN DESCRIPTION:
UDS St 39 6.0
END DESCRIPTION:
XS GIS Cut Line= 4
      2244328.99      7203260.00      2244928.50      7203281.56
      2245074.70      7202997.11      2245476.13      7201909.66
#Sta/Elev= 30
  4196.8  876.19  4256.8  873.58  4306.9  869.66  4366.9  863.24  4396.9  861.63
  4627.1  860.33  4687.1  858.92  4843.4  859.17  4895.1  858.21  4922.9  859.15
  4939.5  857.13  4961.7  858.98  4983.9  858.09  4996.6  856.11  4997.7  855.61
  5004.3  856.11  5006.0  857.37  5012.1  858.20  5263.4  856.61  5443.9  857.52
  5718.3  865.11  5779.2  863.81  5804.3  864.93  5840.0  864.23  5865.1  865.92
  5920.6  865.00  5926.0  863.77  5987.5  867.25  6147.4  870.89  6275.7  878.70
#Mann=3,-1,0
  4196.8    0.05       0  4996.6    0.04       0  5004.3    0.05       0
Bank Sta=4996.6,5004.3
Exp/Cntr=0.3,0.1

Type RM Length L Ch R = 1,6542,291,291,291
BEGIN DESCRIPTION:
UDS St 39 5.9
END DESCRIPTION:
XS GIS Cut Line= 4
      2244329.05      7203338.73      2245230.29      7203390.66
      2245319.50      7203147.28      2245476.95      7202065.52
#Sta/Elev= 30
  3953.2  870.59  3993.2  869.43  4053.3  865.39  4065.3  862.91  4103.4  861.16
  4237.3  861.50  4654.3  857.44  4858.9  858.96  4877.9  856.97  4900.2  859.34
  4909.9  857.04  4920.0  856.36  4995.1  856.94  5007.7  854.23  5008.8  853.73
  5015.4  854.23  5016.9  855.48  5036.7  857.11  5059.0  856.96  5067.2  857.86
  5147.1  856.20  5497.5  855.89  5819.8  859.90  5880.4  861.11  5907.9  863.02
  5930.9  861.52  5941.0  861.91  5951.1  863.62  6102.7  867.50  6208.3  871.93
#Mann=3,-1,0
  3953.2    0.05       0  5007.7    0.04       0  5015.4    0.05       0
Bank Sta=5007.7,5015.4
Exp/Cntr=0.3,0.1

Type RM Length L Ch R = 1,6251,0,0,0
BEGIN DESCRIPTION:
UDS St 39 5.8
END DESCRIPTION:
XS GIS Cut Line= 3
      2244287.41      7203369.54      2245532.63      7203434.83
      2245539.63      7201844.07
#Sta/Elev= 30
  3678.4  867.44  3730.1  867.09  3840.2  860.84  4040.5  860.94  4401.0  857.54
  4591.2  858.21  4631.3  860.03  4681.4  857.34  4711.4  860.22  4737.0  857.25
  4781.5  856.72  4960.2  855.56  4980.2  857.55  4996.3  854.38  4997.5  853.88
  5004.0  854.38  5010.2  856.19  5020.2  856.48  5530.2  855.20  5730.2  857.80
  5750.2  856.66  5860.2  860.79  5960.2  860.39  6050.2  861.93  6090.2  866.36
  6210.2  869.05  6360.2  875.82  6430.2  881.76  6480.2  883.87  6516.1  888.13
#Mann=3,-1,0
  3678.4    0.05       0  4996.3   0.033       0  5004.0    0.05       0
Bank Sta=4996.3,5004
Exp/Cntr=0.3,0.1

Chan Stop Cuts=-1