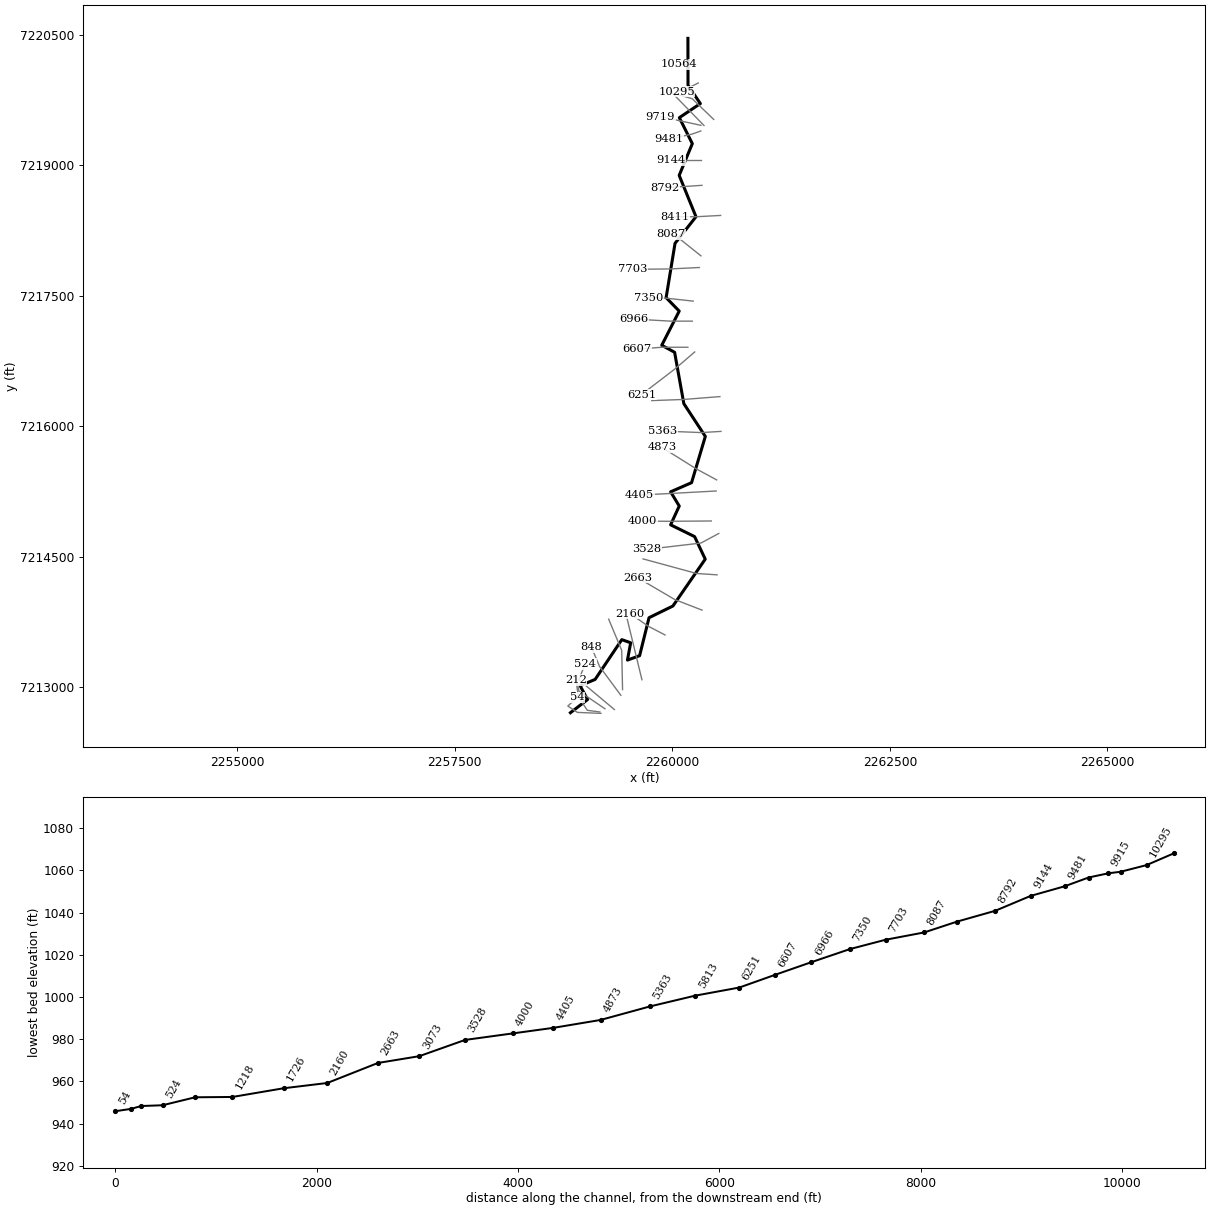
--- UDS St 42.prj (project) ---

Proj Title=UDS St 42 Base Level Engineering
Current Plan=p01
Default Exp/Contr=0.3,0.1
English Units
Geom File=g01
Flow File=f01
Plan File=p01
BEGIN DESCRIPTION:
UDS St 42
END DESCRIPTION:

--- UDS St 42.p01 (plan) ---

Plan Title=Multiple Run
Short Identifier=Multiple
Geom File=g01
Flow File=f01
Subcritical Flow
K Sum by GR= 0
Std Step Tol= 0.01
Critical Tol= 0.01
Num of Std Step Trials= 20
Max Error Tol= 0.3
Flow Tol Ratio= 0.001
Split Flow NTrial= 30
Split Flow Tol= 0.02
Split Flow Ratio= 0.02
Log Output Level= 0
Friction Slope Method= 1
Unsteady Friction Slope Method= 2
Unsteady Bridges Friction Slope Method= 1
Parabolic Critical Depth
Global Vel Dist=  1 , 1 , 1
Global Log Level= 0
CheckData=True
Encroach Param= -1, 0, 0, 0
BEGIN DESCRIPTION:
Multiple Run
END DESCRIPTION:

--- UDS St 42.f01 (steady flow) ---

Flow Title=Multiple
Number of Profiles=7
Profile Names=10-year,25-year,50-year,1pct_min,100-year,1pct_plu,500-year
River Rch & RM= UDS St 42,Reach-1,10564
     686     959    1188     732    1460    2913    2210
River Rch & RM= UDS St 42,Reach-1,5813
     792    1114    1386     856    1707    3407    2600
Boundary for River Rch & Prof#=UDS St 42,Reach-1,1
Up Type=0
Dn Type=3
Dn Slope=0.005
Boundary for River Rch & Prof#=UDS St 42,Reach-1,2
Up Type=0
Dn Type=3
Dn Slope=0.005
Boundary for River Rch & Prof#=UDS St 42,Reach-1,3
Up Type=0
Dn Type=3
Dn Slope=0.005
Boundary for River Rch & Prof#=UDS St 42,Reach-1,4
Up Type=0
Dn Type=3
Dn Slope=0.005
Boundary for River Rch & Prof#=UDS St 42,Reach-1,5
Up Type=0
Dn Type=3
Dn Slope=0.005
Boundary for River Rch & Prof#=UDS St 42,Reach-1,6
Up Type=0
Dn Type=3
Dn Slope=0.005
Boundary for River Rch & Prof#=UDS St 42,Reach-1,7
Up Type=0
Dn Type=3
Dn Slope=0.005

--- UDS St 42.g01 (geometry) ---

Geom Title=Existing Conditions

River Reach=UDS St 42,Reach-1
Reach XY= 30
      2260179.00      7220460.00      2260180.20      7219920.50
      2260321.92      7219709.99      2260080.38      7219548.41
      2260229.55      7219249.82      2260078.68      7218884.89
      2260271.70      7218409.92      2260031.06      7218104.15
      2259928.56      7217480.03      2260079.13      7217325.42
      2259878.37      7216932.77      2260026.06      7216852.03
      2260132.17      7216261.65      2260379.15      7215885.13
      2260220.99      7215353.62      2259980.34      7215248.67
      2260079.44      7215084.99      2259980.03      7214869.48
      2260255.87      7214733.82      2260378.13      7214474.71
      2260006.19      7213936.05      2259732.25      7213801.98
      2259623.83      7213365.40      2259484.17      7213314.59
      2259521.31      7213513.75      2259419.35      7213549.83
      2259112.73      7213092.79      2258939.80      7213020.37
      2259026.00      7212861.40      2258829.00      7212710.00

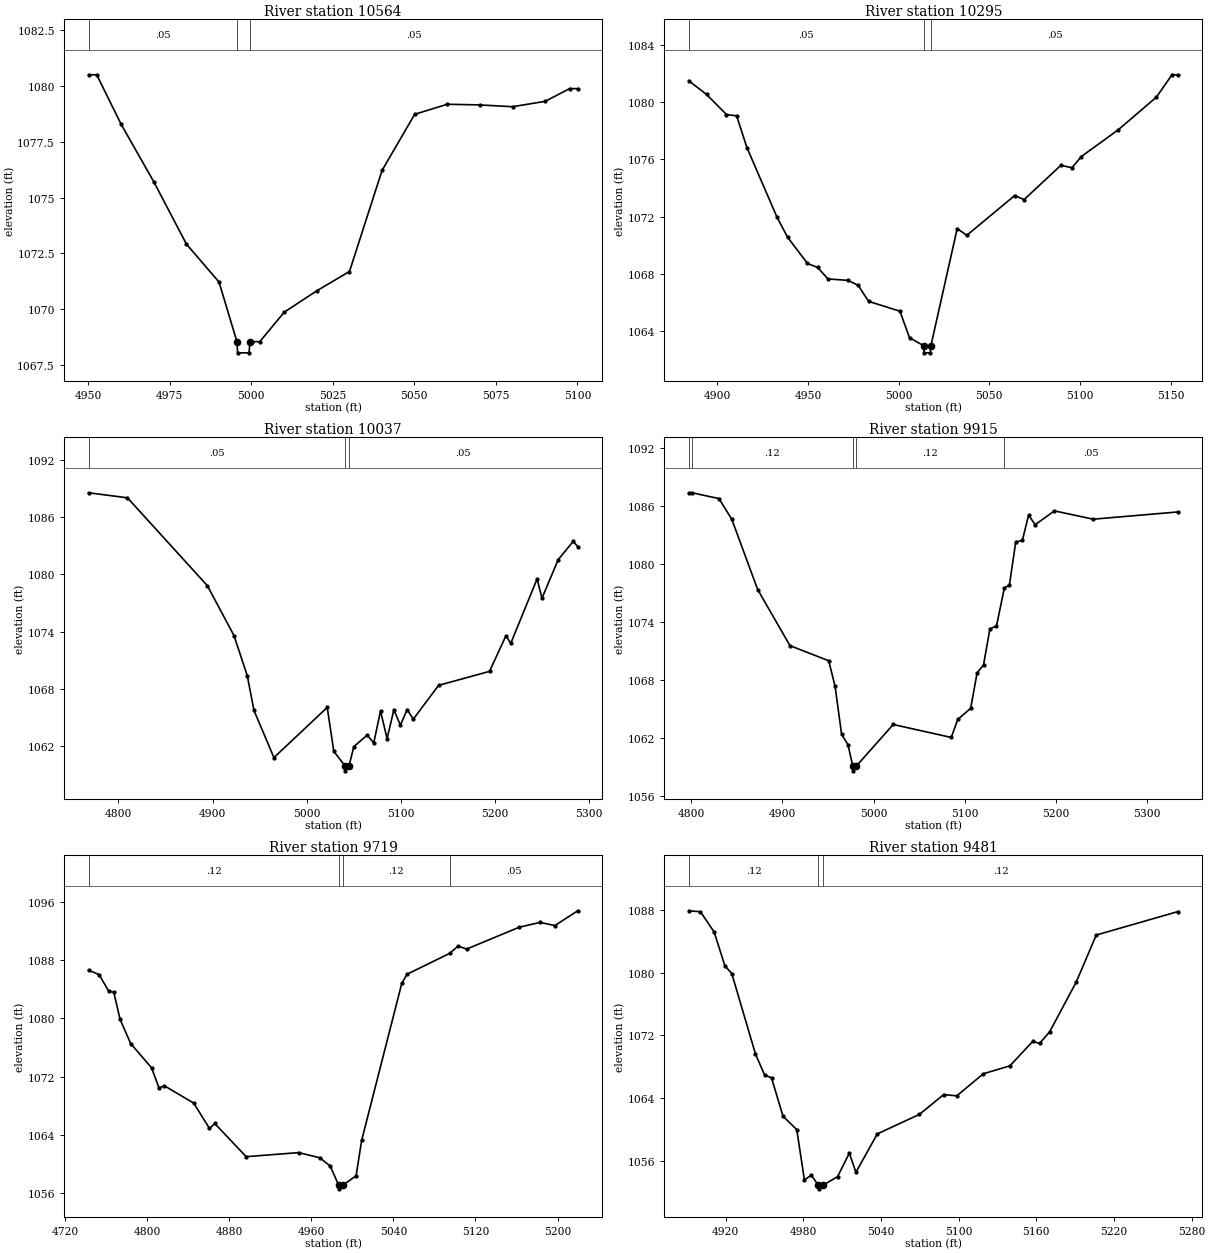
Type RM Length L Ch R = 1,10564,269,269,269
BEGIN DESCRIPTION:
UDS St 42 26.0
END DESCRIPTION:
XS GIS Cut Line= 3
      2260229.00      7220160.00      2260179.00      7220160.00
      2260079.00      7220160.00
#Sta/Elev= 23
  4950.1 1080.50  4952.6 1080.50  4960.1 1078.28  4970.1 1075.71  4980.1 1072.92
  4990.1 1071.22  4995.6 1068.55  4995.8 1068.05  4999.3 1068.05  4999.6 1068.55
  5000.1 1068.55  5002.6 1068.55  5010.1 1069.87  5020.1 1070.83  5030.1 1071.69
  5040.1 1076.22  5050.1 1078.73  5060.1 1079.18  5070.1 1079.15  5080.1 1079.07
  5090.1 1079.31  5097.6 1079.88  5100.1 1079.88
#Mann=3,-1,0
  4950.1    0.05       0  4995.6   0.033       0  4999.6    0.05       0
Bank Sta=4995.6,4999.6
Exp/Cntr=0.3,0.1

Type RM Length L Ch R = 1,10295,258,258,258
BEGIN DESCRIPTION:
UDS St 42 25.0
END DESCRIPTION:
XS GIS Cut Line= 3
      2260297.73      7219946.73      2260197.73      7219896.73
      2260047.75      7219846.73
#Sta/Elev= 30
  4884.2 1081.47  4894.0 1080.52  4905.0 1079.12  4910.6 1079.03  4916.3 1076.81
  4932.9 1071.96  4938.7 1070.57  4949.7 1068.74  4955.3 1068.46  4961.0 1067.66
  4972.1 1067.56  4977.7 1067.21  4983.4 1066.10  5000.7 1065.41  5006.0 1063.56
  5013.8 1063.01  5014.0 1062.51  5017.5 1062.51  5017.8 1063.01  5032.3 1071.17
  5037.6 1070.70  5064.0 1073.47  5069.2 1073.19  5089.5 1075.58  5095.6 1075.41
  5100.8 1076.19  5121.2 1078.06  5142.2 1080.33  5150.8 1081.89  5154.1 1081.89
#Mann=3,-1,0
  4884.2    0.05       0  5013.8   0.033       0  5017.8    0.05       0
Bank Sta=5013.8,5017.8
Exp/Cntr=0.3,0.1

Type RM Length L Ch R = 1,10037,122,122,122
BEGIN DESCRIPTION:
UDS St 42 24.2
END DESCRIPTION:
XS GIS Cut Line= 3
      2260475.39      7219527.92      2260229.17      7219765.57
      2260059.19      7219816.33
#Sta/Elev= 30
  4768.3 1088.59  4809.6 1088.06  4894.5 1078.82  4922.8 1073.57  4936.9 1069.35
  4944.0 1065.70  4965.2 1060.74  5021.8 1066.02  5028.8 1061.40  5040.9 1059.85
  5041.2 1059.35  5044.9 1059.85  5050.1 1061.90  5064.3 1063.11  5071.2 1062.28
  5078.4 1065.63  5085.4 1062.74  5092.6 1065.77  5099.5 1064.15  5106.7 1065.80
  5113.2 1064.78  5140.1 1068.34  5194.2 1069.81  5211.6 1073.55  5216.8 1072.77
  5244.7 1079.53  5249.9 1077.50  5267.2 1081.57  5283.1 1083.48  5287.9 1082.93
#Mann=3,-1,0
  4768.3    0.05       0  5040.9   0.033       0  5044.9    0.05       0
Bank Sta=5040.9,5044.9
Exp/Cntr=0.3,0.1

Type RM Length L Ch R = 1,9915,196,196,196
BEGIN DESCRIPTION:
UDS St 42 24.1
END DESCRIPTION:
XS GIS Cut Line= 2
      2260363.91      7219458.08      2259989.27      7219841.68
#Sta/Elev= 30
  4797.5 1087.37  4801.2 1087.37  4830.6 1086.77  4844.7 1084.62  4873.0 1077.37
  4908.4 1071.57  4950.9 1070.01  4957.9 1067.35  4965.0 1062.41  4972.0 1061.34
  4977.2 1059.13  4977.4 1058.63  4981.2 1059.13  5021.6 1063.42  5085.2 1062.08
  5092.3 1063.94  5106.5 1065.09  5113.5 1068.74  5120.6 1069.59  5127.6 1073.31
  5134.8 1073.60  5143.4 1077.54  5148.9 1077.80  5155.9 1082.29  5163.1 1082.44
  5170.0 1085.06  5177.2 1084.07  5198.3 1085.50  5240.8 1084.64  5333.7 1085.39
#Mann=5,-1,0
  4797.5    0.05       0  4801.2    0.12       0  4977.2    0.07       0
  4981.2    0.12       0  5143.4    0.05       0
Bank Sta=4977.2,4981.2
Exp/Cntr=0.3,0.1

Type RM Length L Ch R = 1,9719,238,238,238
BEGIN DESCRIPTION:
UDS St 42 24.0
END DESCRIPTION:
XS GIS Cut Line= 3
      2260329.04      7219459.99      2260116.36      7219506.18
      2259863.12      7219559.83
#Sta/Elev= 30
  4743.1 1086.62  4753.4 1086.00  4762.6 1083.77  4767.7 1083.57  4773.8 1079.87
  4784.1 1076.56  4804.5 1073.22  4811.7 1070.47  4816.9 1070.76  4845.5 1068.39
  4860.9 1064.91  4866.0 1065.59  4896.6 1061.04  4947.8 1061.60  4968.3 1060.89
  4978.5 1059.76  4986.7 1057.13  4987.0 1056.63  4990.7 1057.13  5003.7 1058.41
  5009.1 1063.27  5048.2 1084.81  5053.3 1086.06  5094.9 1088.92  5103.0 1089.92
  5111.4 1089.51  5162.5 1092.50  5182.9 1093.17  5197.3 1092.73  5219.6 1094.76
#Mann=4,-1,0
  4743.1    0.12       0  4986.7    0.07       0  4990.7    0.12       0
  5094.9    0.05       0
Bank Sta=4986.7,4990.7
Exp/Cntr=0.3,0.1

Type RM Length L Ch R = 1,9481,337,337,337
BEGIN DESCRIPTION:
UDS St 42 23.0
END DESCRIPTION:
XS GIS Cut Line= 3
      2260327.48      7219395.40      2260229.00      7219360.00
      2259962.19      7219301.53
#Sta/Elev= 30
  4891.6 1087.88  4900.6 1087.76  4911.2 1085.18  4919.5 1080.86  4924.8 1079.89
  4943.1 1069.64  4950.2 1066.95  4955.5 1066.60  4964.4 1061.70  4975.0 1060.01
  4980.9 1053.60  4986.2 1054.19  4991.6 1052.96  4991.8 1052.46  4995.6 1052.96
  5006.5 1054.01  5015.6 1057.01  5020.7 1054.57  5037.2 1059.46  5069.7 1061.94
  5088.4 1064.46  5098.6 1064.31  5119.1 1067.12  5139.6 1068.13  5157.3 1071.25
  5162.5 1070.98  5170.3 1072.46  5190.8 1078.79  5206.3 1084.79  5269.4 1087.78
#Mann=3,-1,0
  4891.6    0.12       0  4991.6    0.07       0  4995.6    0.12       0
Bank Sta=4991.6,4995.6
Exp/Cntr=0.3,0.1

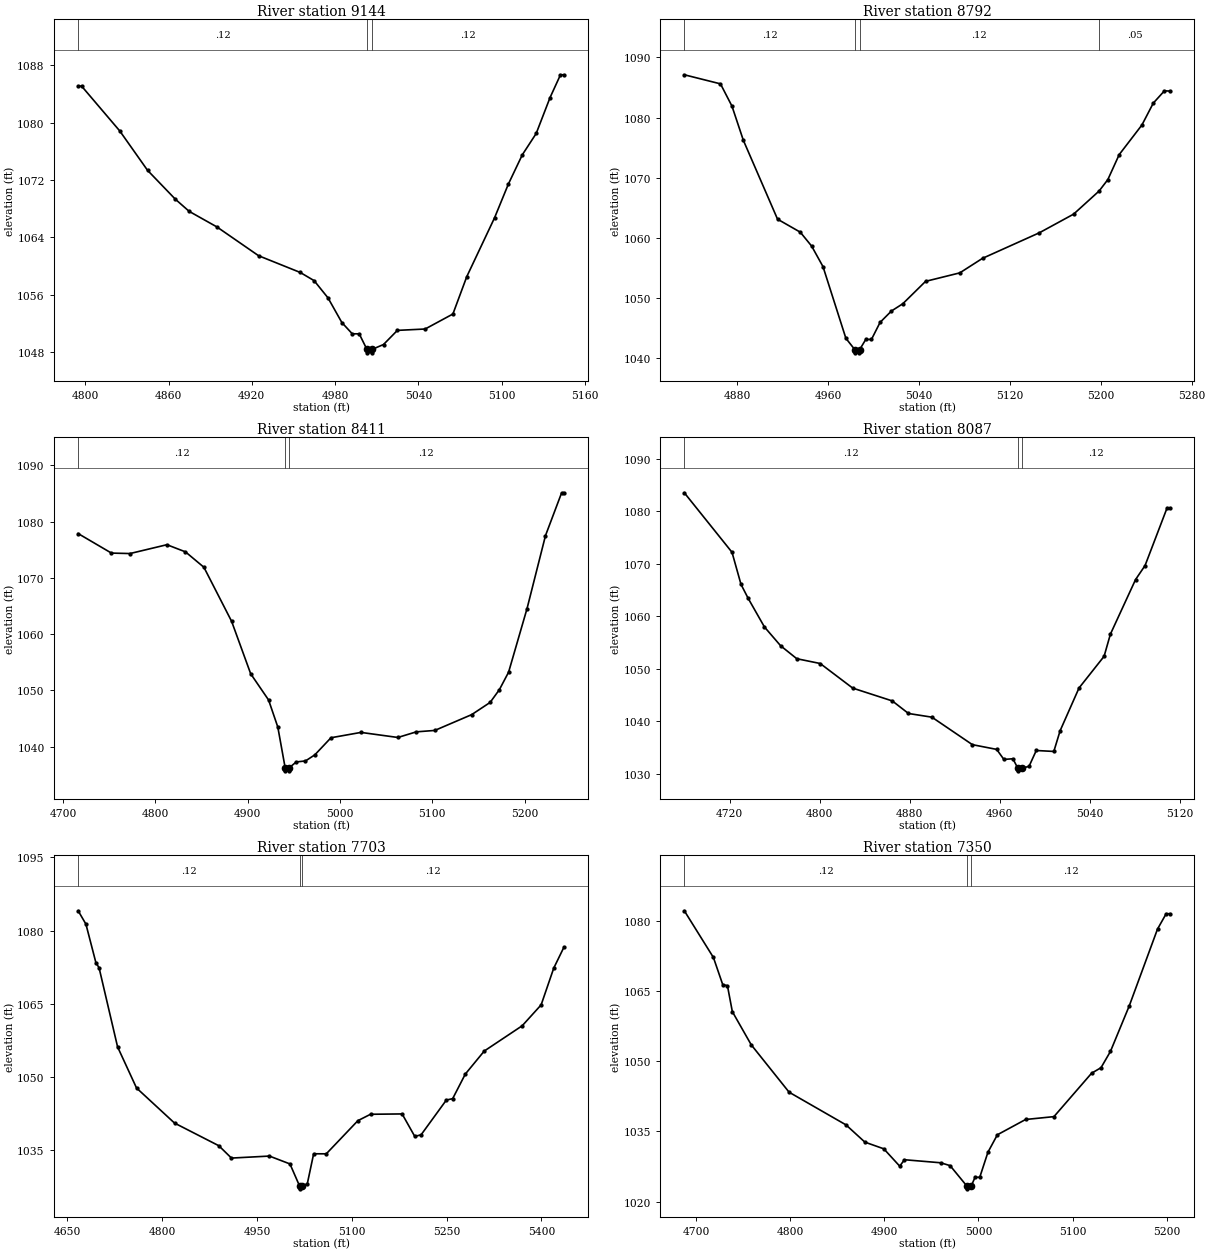
Type RM Length L Ch R = 1,9144,352,352,352
BEGIN DESCRIPTION:
UDS St 42 22.0
END DESCRIPTION:
XS GIS Cut Line= 3
      2260329.02      7219060.00      2260129.00      7219060.00
      2259979.02      7219060.00
#Sta/Elev= 30
  4794.9 1085.08  4797.4 1085.08  4824.9 1078.83  4844.9 1073.35  4864.9 1069.33
  4874.9 1067.63  4894.9 1065.46  4924.9 1061.45  4954.9 1059.12  4964.9 1057.98
  4974.9 1055.58  4984.9 1052.14  4992.4 1050.57  4997.4 1050.57  5002.9 1048.42
  5003.2 1047.92  5006.7 1047.92  5006.9 1048.42  5014.9 1049.08  5024.9 1051.05
  5044.9 1051.24  5064.9 1053.33  5074.9 1058.54  5094.9 1066.73  5104.9 1071.45
  5114.9 1075.51  5124.9 1078.48  5134.9 1083.49  5142.4 1086.66  5144.9 1086.66
#Mann=3,-1,0
  4794.9    0.12       0  5002.9    0.07       0  5006.9    0.12       0
Bank Sta=5002.9,5006.9
Exp/Cntr=0.3,0.1

Type RM Length L Ch R = 1,8792,381,381,381
BEGIN DESCRIPTION:
UDS St 42 21.0
END DESCRIPTION:
XS GIS Cut Line= 3
      2260340.77      7218770.84      2260179.00      7218760.00
      2259914.26      7218744.98
#Sta/Elev= 30
  4833.7 1087.11  4865.5 1085.60  4875.6 1081.90  4885.6 1076.22  4915.7 1063.09
  4935.7 1060.93  4945.7 1058.61  4955.7 1055.19  4975.8 1043.28  4983.8 1041.36
  4984.1 1040.86  4987.6 1040.86  4987.8 1041.36  4993.3 1043.09  4998.3 1043.09
  5005.9 1045.93  5015.9 1047.82  5025.9 1049.03  5045.9 1052.75  5076.0 1054.16
  5096.0 1056.58  5146.1 1060.84  5176.1 1063.93  5198.5 1067.77  5206.2 1069.67
  5216.2 1073.83  5236.2 1078.76  5246.2 1082.40  5256.0 1084.44  5261.0 1084.40
#Mann=4,-1,0
  4833.7    0.12       0  4983.8    0.07       0  4987.8    0.12       0
  5198.5    0.05       0
Bank Sta=4983.8,4987.8
Exp/Cntr=0.3,0.1

Type RM Length L Ch R = 1,8411,324,324,324
BEGIN DESCRIPTION:
UDS St 42 20.0
END DESCRIPTION:
XS GIS Cut Line= 3
      2260555.10      7218424.74      2260279.00      7218410.00
      2260028.99      7218410.00
#Sta/Elev= 30
  4716.2 1077.88  4752.3 1074.41  4772.4 1074.33  4812.4 1075.90  4832.5 1074.63
  4852.5 1071.89  4882.5 1062.29  4903.2 1052.96  4922.6 1048.30  4932.6 1043.49
  4940.6 1036.21  4940.9 1035.71  4944.4 1035.71  4944.6 1036.21  4952.6 1037.29
  4962.6 1037.47  4972.7 1038.55  4990.2 1041.59  5022.7 1042.54  5062.7 1041.64
  5082.7 1042.64  5102.7 1042.89  5142.7 1045.70  5162.7 1047.87  5172.7 1050.13
  5182.7 1053.24  5202.7 1064.55  5222.7 1077.52  5240.2 1085.13  5242.7 1085.13
#Mann=3,-1,0
  4716.2    0.12       0  4940.6    0.07       0  4944.6    0.12       0
Bank Sta=4940.6,4944.6
Exp/Cntr=0.3,0.1

Type RM Length L Ch R = 1,8087,384,384,384
BEGIN DESCRIPTION:
UDS St 42 19.0
END DESCRIPTION:
XS GIS Cut Line= 3
      2260328.99      7217960.01      2260079.00      7218160.00
      2259979.04      7218209.98
#Sta/Elev= 30
  4679.6 1083.51  4722.0 1072.19  4730.0 1066.08  4736.4 1063.41  4750.8 1057.99
  4765.2 1054.41  4779.6 1051.94  4800.4 1051.03  4829.3 1046.35  4864.5 1043.91
  4878.9 1041.52  4899.7 1040.82  4935.7 1035.59  4957.3 1034.69  4963.7 1032.78
  4971.7 1032.91  4976.1 1031.11  4976.4 1030.61  4980.1 1031.11  4986.1 1031.48
  4992.5 1034.48  5008.1 1034.30  5013.7 1038.24  5030.5 1046.37  5052.8 1052.40
  5058.4 1056.61  5080.8 1067.01  5089.2 1069.66  5108.7 1080.58  5111.5 1080.58
#Mann=3,-1,0
  4679.6    0.12       0  4976.1    0.07       0  4980.1    0.12       0
Bank Sta=4976.1,4980.1
Exp/Cntr=0.3,0.1

Type RM Length L Ch R = 1,7703,353,353,353
BEGIN DESCRIPTION:
UDS St 42 18.0
END DESCRIPTION:
XS GIS Cut Line= 3
      2260311.31      7217826.42      2259979.00      7217810.00
      2259542.94      7217805.15
#Sta/Elev= 30
  4666.9 1084.08  4679.2 1081.35  4695.0 1073.45  4700.0 1072.42  4729.3 1056.21
  4759.3 1047.79  4819.4 1040.61  4889.5 1035.97  4909.5 1033.44  4969.6 1033.85
  5002.1 1032.24  5017.6 1027.64  5017.9 1027.14  5021.6 1027.64  5029.6 1028.21
  5039.6 1034.32  5059.6 1034.31  5109.6 1041.10  5129.6 1042.41  5179.6 1042.48
  5199.6 1037.88  5209.6 1038.20  5249.6 1045.32  5259.6 1045.61  5279.6 1050.64
  5309.6 1055.36  5369.6 1060.53  5399.6 1064.81  5419.6 1072.35  5435.7 1076.63
#Mann=3,-1,0
  4666.9    0.12       0  5017.6    0.07       0  5021.6    0.12       0
Bank Sta=5017.6,5021.6
Exp/Cntr=0.3,0.1

Type RM Length L Ch R = 1,7350,384,384,384
BEGIN DESCRIPTION:
UDS St 42 17.0
END DESCRIPTION:
XS GIS Cut Line= 3
      2260239.68      7217440.06      2259931.37      7217473.61
      2259725.63      7217480.83
#Sta/Elev= 30
  4687.6 1082.15  4718.5 1072.17  4728.4 1066.37  4733.4 1066.14  4738.6 1060.60
  4758.7 1053.50  4798.9 1043.38  4859.3 1036.40  4879.4 1032.71  4899.5 1031.28
  4916.4 1027.57  4921.4 1028.95  4959.9 1028.30  4969.9 1027.69  4988.1 1023.23
  4988.3 1022.73  4992.1 1023.23  4996.4 1025.20  5001.4 1025.20  5010.1 1030.56
  5020.1 1034.28  5050.1 1037.55  5080.2 1038.16  5120.2 1047.44  5130.2 1048.62
  5140.2 1052.09  5160.2 1061.83  5190.2 1078.24  5199.4 1081.52  5203.6 1081.52
#Mann=3,-1,0
  4687.6    0.12       0  4988.1    0.07       0  4992.1    0.12       0
Bank Sta=4988.1,4992.1
Exp/Cntr=0.3,0.1

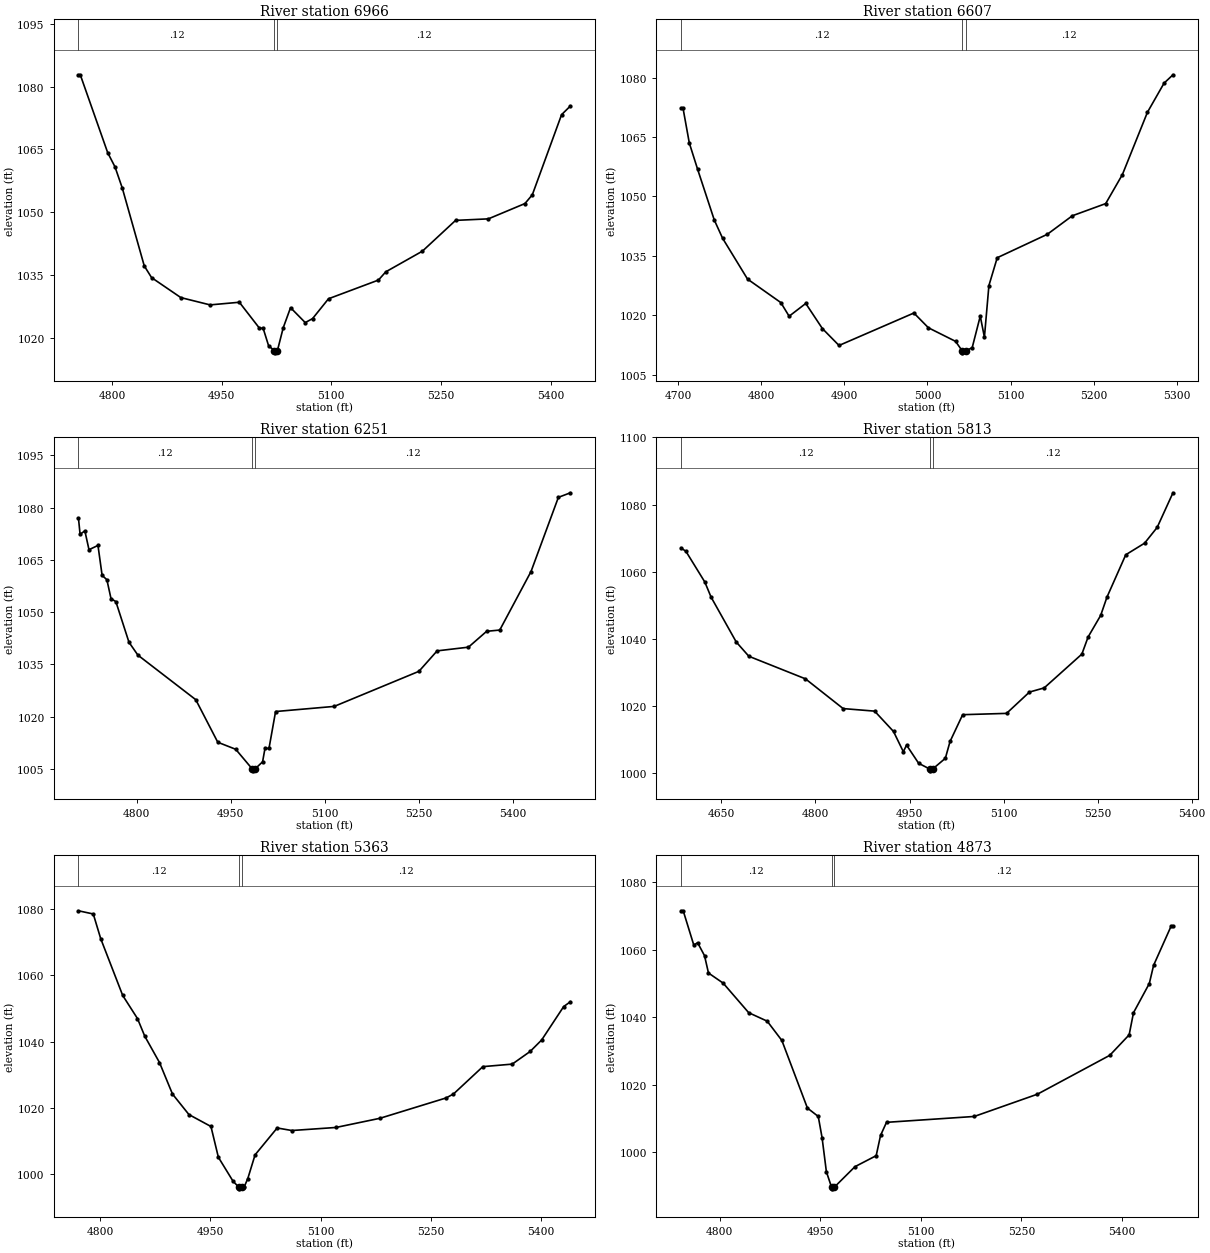
Type RM Length L Ch R = 1,6966,359,359,359
BEGIN DESCRIPTION:
UDS St 42 16.0
END DESCRIPTION:
XS GIS Cut Line= 3
      2260228.97      7217210.00      2259979.00      7217210.00
      2259556.95      7217233.84
#Sta/Elev= 30
  4754.3 1082.80  4756.8 1082.80  4794.3 1064.22  4804.3 1060.83  4814.3 1055.76
  4844.3 1037.23  4854.3 1034.44  4894.3 1029.68  4934.3 1027.94  4974.3 1028.57
  5001.8 1022.38  5006.8 1022.38  5014.3 1018.20  5022.3 1017.01  5022.6 1016.51
  5026.3 1017.01  5034.3 1022.49  5044.3 1027.28  5064.4 1023.72  5074.4 1024.67
  5096.2 1029.40  5164.5 1033.86  5174.5 1035.82  5224.6 1040.75  5270.0 1048.09
  5314.8 1048.45  5364.8 1052.10  5374.9 1054.19  5414.9 1073.29  5427.0 1075.37
#Mann=3,-1,0
  4754.3    0.12       0  5022.3    0.07       0  5026.3    0.12       0
Bank Sta=5022.3,5026.3
Exp/Cntr=0.3,0.1

Type RM Length L Ch R = 1,6607,356,356,356
BEGIN DESCRIPTION:
UDS St 42 15.0
END DESCRIPTION:
XS GIS Cut Line= 3
      2260178.99      7216910.00      2259879.00      7216910.00
      2259588.37      7216887.37
#Sta/Elev= 30
  4703.7 1072.21  4706.2 1072.21  4713.7 1063.48  4723.7 1056.85  4743.7 1044.07
  4753.7 1039.46  4783.7 1029.15  4823.7 1023.23  4833.7 1019.78  4853.7 1023.00
  4873.7 1016.66  4893.7 1012.40  4983.7 1020.59  5001.2 1016.86  5033.8 1013.44
  5041.8 1011.04  5042.1 1010.54  5045.8 1011.04  5053.8 1011.84  5063.5 1019.80
  5068.5 1014.49  5073.9 1027.52  5083.9 1034.54  5144.1 1040.45  5174.2 1045.13
  5214.3 1048.20  5234.4 1055.53  5264.5 1071.25  5284.5 1078.60  5295.2 1080.71
#Mann=3,-1,0
  4703.7    0.12       0  5041.8    0.07       0  5045.8    0.12       0
Bank Sta=5041.8,5045.8
Exp/Cntr=0.3,0.1

Type RM Length L Ch R = 1,6251,438,438,438
BEGIN DESCRIPTION:
UDS St 42 14.0
END DESCRIPTION:
XS GIS Cut Line= 3
      2260256.98      7216855.77      2260029.00      7216660.00
      2259645.40      7216365.84
#Sta/Elev= 30
  4707.2 1077.00  4709.8 1072.34  4717.4 1073.33  4724.0 1067.92  4738.3 1069.15
  4744.9 1060.57  4752.5 1059.31  4759.1 1053.87  4766.8 1053.04  4787.7 1041.38
  4801.9 1037.69  4894.1 1024.91  4929.2 1012.70  4957.8 1010.68  4984.3 1005.00
  4984.6 1004.50  4988.3 1005.00  5000.6 1007.09  5004.4 1010.93  5010.8 1010.93
  5021.3 1021.51  5114.7 1022.98  5249.7 1033.04  5278.7 1038.91  5328.6 1039.97
  5357.6 1044.52  5378.5 1044.88  5428.3 1061.66  5471.9 1082.94  5491.1 1084.25
#Mann=3,-1,0
  4707.2    0.12       0  4984.3    0.07       0  4988.3    0.12       0
Bank Sta=4984.3,4988.3
Exp/Cntr=0.3,0.1

Type RM Length L Ch R = 1,5813,450,450,450
BEGIN DESCRIPTION:
UDS St 42 13.0
END DESCRIPTION:
XS GIS Cut Line= 3
      2260546.85      7216342.85      2260129.00      7216310.00
      2259763.78      7216296.77
#Sta/Elev= 30
  4585.5 1067.09  4593.4 1066.05  4623.5 1056.92  4633.5 1052.41  4673.6 1039.05
  4693.7 1034.80  4784.0 1028.07  4844.1 1019.21  4894.3 1018.45  4924.4 1012.39
  4940.1 1006.35  4945.2 1008.33  4964.5 1002.91  4982.6 1001.16  4982.8 1000.66
  4986.6 1001.16  5007.1 1004.40  5014.6 1009.42  5034.7 1017.39  5104.7 1017.78
  5141.2 1024.13  5164.7 1025.37  5224.8 1035.44  5234.8 1040.56  5254.8 1046.97
  5264.8 1052.40  5294.8 1065.04  5324.8 1068.49  5344.9 1073.19  5370.1 1083.51
#Mann=3,-1,0
  4585.5    0.12       0  4982.6    0.07       0  4986.6    0.12       0
Bank Sta=4982.6,4986.6
Exp/Cntr=0.3,0.1

Type RM Length L Ch R = 1,5363,490,490,490
BEGIN DESCRIPTION:
UDS St 42 12.0
END DESCRIPTION:
XS GIS Cut Line= 3
      2260559.20      7215942.96      2260334.02      7215929.22
      2259889.79      7215947.25
#Sta/Elev= 30
  4770.2 1079.55  4790.4 1078.58  4800.5 1071.14  4830.5 1053.96  4850.6 1046.99
  4860.6 1041.63  4880.6 1033.70  4898.3 1024.18  4920.7 1017.98  4950.7 1014.38
  4960.8 1005.08  4980.8  997.84  4988.7  996.04  4989.0  995.54  4992.8  996.04
  4995.8  996.04  5000.8  998.58  5010.8 1005.81  5040.9 1013.93  5060.9 1013.16
  5120.9 1014.08  5181.0 1016.86  5271.0 1023.00  5281.1 1024.20  5321.1 1032.46
  5361.1 1033.22  5385.5 1037.04  5401.2 1040.51  5431.2 1050.61  5440.4 1052.07
#Mann=3,-1,0
  4770.2    0.12       0  4988.7    0.07       0  4992.8    0.12       0
Bank Sta=4988.7,4992.8
Exp/Cntr=0.3,0.1

Type RM Length L Ch R = 1,4873,468,468,468
BEGIN DESCRIPTION:
UDS St 42 11.0
END DESCRIPTION:
XS GIS Cut Line= 3
      2260509.85      7215385.39      2260279.00      7215510.00
      2259879.03      7215759.98
#Sta/Elev= 30
  4742.0 1071.51  4745.3 1071.51  4761.1 1061.34  4766.8 1062.05  4777.1 1058.21
  4783.0 1053.07  4804.9 1050.08  4843.0 1041.32  4870.6 1038.81  4892.5 1033.09
  4930.6 1013.07  4946.8 1010.58  4952.5 1004.27  4958.9  994.22  4966.6  989.64
  4966.9  989.14  4970.8  989.64  5001.5  995.70  5033.2  998.96  5039.7 1004.95
  5048.6 1008.84  5179.5 1010.58  5273.8 1017.18  5381.7 1028.69  5410.6 1034.75
  5417.1 1041.31  5440.7 1049.96  5447.1 1055.36  5473.1 1066.90  5476.0 1066.90
#Mann=3,-1,0
  4742.0    0.12       0  4966.6    0.07       0  4970.8    0.12       0
Bank Sta=4966.6,4970.8
Exp/Cntr=0.3,0.1

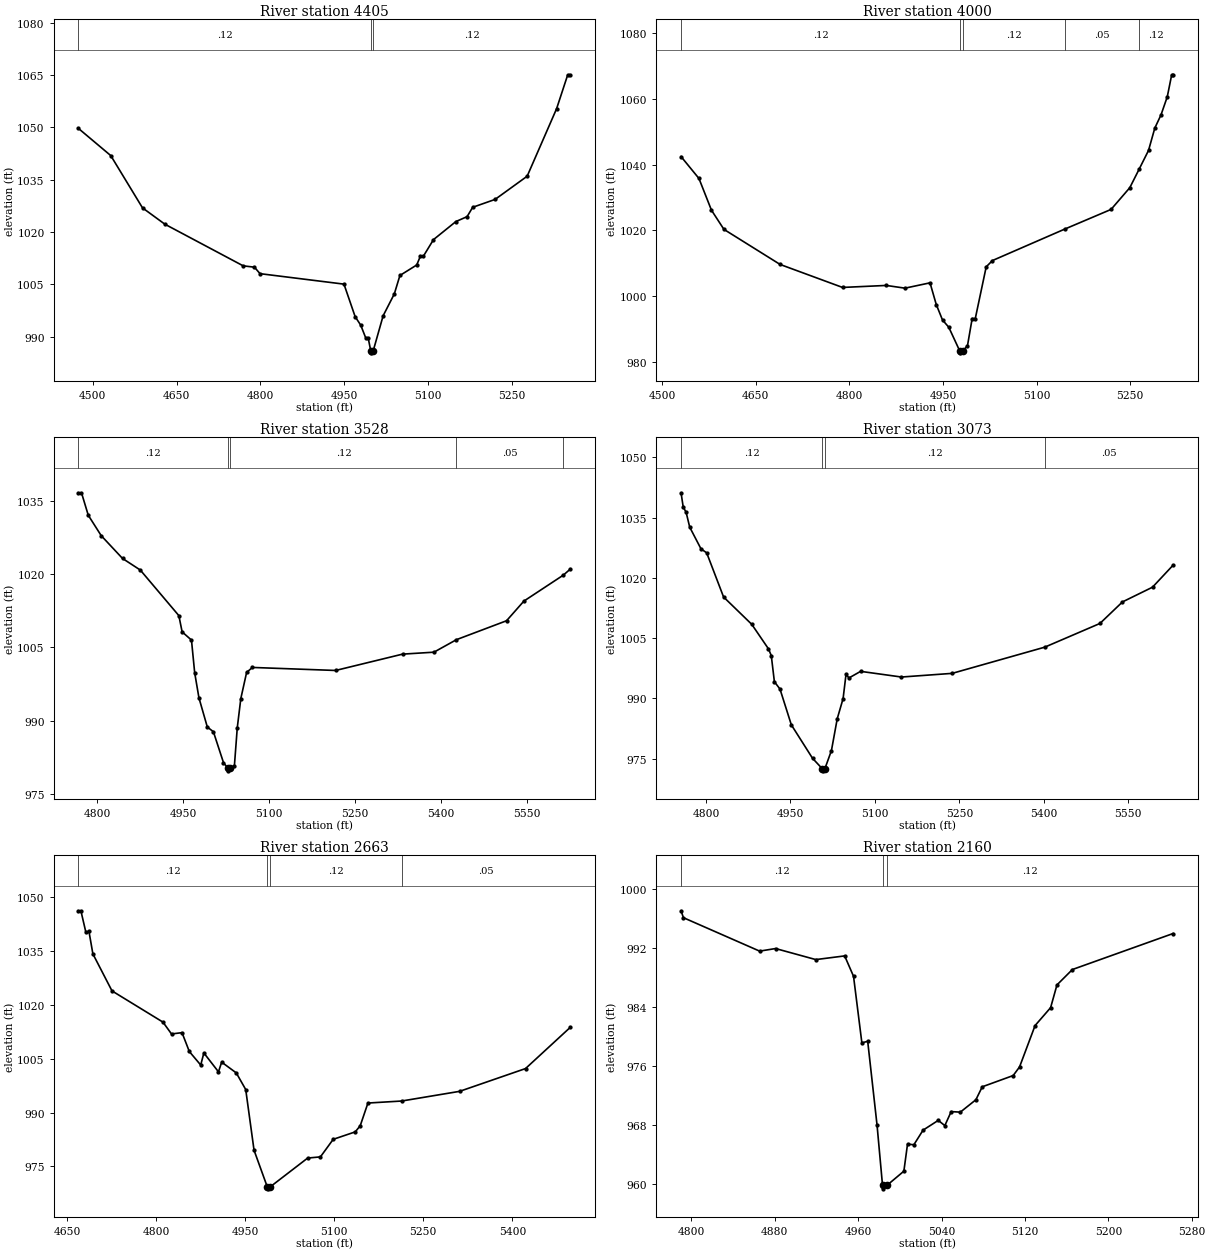
Type RM Length L Ch R = 1,4405,405,405,405
BEGIN DESCRIPTION:
UDS St 42 10.0
END DESCRIPTION:
XS GIS Cut Line= 3
      2260503.41      7215258.04      2259985.53      7215229.95
      2259624.26      7215211.08
#Sta/Elev= 30
  4474.3 1049.72  4532.1 1041.94  4588.9 1026.96  4628.9 1022.28  4769.1 1010.34
  4789.2 1009.96  4799.2 1008.10  4949.4 1005.10  4969.4  995.78  4979.4  993.34
  4988.7  989.54  4992.9  989.54  4997.4  985.91  4997.7  985.41  5001.6  985.91
  5019.5  996.04  5039.5 1002.30  5049.5 1007.58  5079.6 1010.59  5086.2 1013.15
  5091.2 1013.03  5109.6 1017.86  5149.7 1023.04  5169.7 1024.44  5179.7 1027.12
  5219.8 1029.38  5277.2 1036.03  5329.9 1055.39  5349.8 1065.10  5354.7 1065.10
#Mann=3,-1,0
  4474.3    0.12       0  4997.4    0.07       0  5001.6    0.12       0
Bank Sta=4997.4,5001.6
Exp/Cntr=0.3,0.1

Type RM Length L Ch R = 1,4000,472,472,472
BEGIN DESCRIPTION:
UDS St 42 9.0
END DESCRIPTION:
XS GIS Cut Line= 3
      2260447.74      7214913.38      2259979.00      7214910.00
      2259659.66      7214911.40
#Sta/Elev= 30
  4530.4 1042.45  4559.1 1035.79  4579.1 1026.15  4599.1 1020.31  4689.1 1009.64
  4789.1 1002.65  4859.1 1003.26  4889.1 1002.43  4929.2 1004.05  4939.2  997.45
  4949.2  992.75  4959.2  990.56  4977.0  983.26  4977.4  982.76  4981.3  983.26
  4989.2  984.93  4996.7  993.19  5001.7  993.19  5019.2 1008.92  5029.2 1010.83
  5144.8 1020.38  5219.2 1026.38  5249.2 1032.99  5264.5 1038.75  5279.2 1044.32
  5289.2 1051.09  5299.2 1055.14  5309.2 1060.62  5316.3 1067.33  5318.5 1067.33
#Mann=5,-1,0
  4530.4    0.12       0  4977.0    0.07       0  4981.3    0.12       0
  5144.8    0.05       0  5264.5    0.12       0
Bank Sta=4977,4981.3
Exp/Cntr=0.3,0.1

Type RM Length L Ch R = 1,3528,455,455,455
BEGIN DESCRIPTION:
UDS St 42 8.0
END DESCRIPTION:
XS GIS Cut Line= 3
      2260534.03      7214770.02      2260329.00      7214660.00
      2259708.34      7214587.17
#Sta/Elev= 30
  4767.6 1036.72  4772.9 1036.72  4784.7 1032.11  4807.3 1027.92  4844.4 1023.25
  4875.4 1020.87  4942.6 1011.52  4948.3 1008.19  4964.6 1006.50  4970.2  999.79
  4977.6  994.66  4992.2  988.67  5002.8  987.70  5020.4  981.36  5028.3  980.18
  5028.7  979.68  5032.6  980.18  5039.4  980.69  5044.4  988.49  5050.6  994.50
  5060.7  999.87  5070.8 1000.89  5215.8 1000.27  5332.5 1003.62  5387.2 1004.02
  5426.5 1006.59  5513.8 1010.47  5544.0 1014.50  5612.8 1019.83  5625.2 1021.10
#Mann=5,-1,0
  4767.6    0.12       0  5028.3    0.07       0  5032.6    0.12       0
  5426.5    0.05       0  5612.8    0.12       0
Bank Sta=5028.3,5032.6
Exp/Cntr=0.3,0.1

Type RM Length L Ch R = 1,3073,410,410,410
BEGIN DESCRIPTION:
UDS St 42 7.0
END DESCRIPTION:
XS GIS Cut Line= 3
      2260514.35      7214294.51      2260279.00      7214310.00
      2259663.79      7214477.62
#Sta/Elev= 30
  4755.9 1041.16  4759.8 1037.57  4764.8 1036.36  4771.3 1032.60  4791.3 1027.21
  4801.4 1026.22  4831.4 1015.23  4881.5 1008.42  4911.1 1002.33  4916.1 1000.65
  4921.6  994.16  4931.6  992.31  4951.7  983.42  4989.3  975.11  5006.8  972.48
  5007.2  971.98  5011.2  972.48  5022.9  977.03  5033.2  984.95  5043.6  989.96
  5048.8  996.01  5054.0  995.09  5074.7  996.73  5147.2  995.32  5237.2  996.23
  5401.6 1002.75  5499.6 1008.65  5539.6 1014.01  5592.9 1017.67  5629.4 1023.14
#Mann=4,-1,0
  4755.9    0.12       0  5006.8    0.07       0  5011.2    0.12       0
  5401.6    0.05       0
Bank Sta=5006.8,5011.2
Exp/Cntr=0.3,0.1

Type RM Length L Ch R = 1,2663,503,503,503
BEGIN DESCRIPTION:
UDS St 42 6.0
END DESCRIPTION:
XS GIS Cut Line= 3
      2260341.69      7213889.05      2260029.00      7214010.00
      2259603.77      7214260.11
#Sta/Elev= 30
  4669.3 1046.29  4673.4 1046.29  4681.7 1040.36  4687.0 1040.54  4693.6 1034.27
  4725.8 1023.95  4811.6 1015.25  4826.0 1011.95  4843.7 1012.31  4856.0 1007.06
  4875.2 1003.28  4880.5 1006.65  4905.1 1001.39  4910.5 1004.09  4935.1 1001.09
  4951.0  996.45  4965.0  979.54  4987.4  969.27  4987.8  968.77  4991.8  969.27
  5055.3  977.35  5076.8  977.68  5098.3  982.57  5135.4  984.65  5143.8  986.35
  5156.8  992.69  5213.5  993.25  5311.2  995.95  5422.2 1002.30  5497.9 1013.84
#Mann=4,-1,0
  4669.3    0.12       0  4987.4    0.07       0  4991.8    0.12       0
  5213.5    0.05       0
Bank Sta=4987.4,4991.8
Exp/Cntr=0.3,0.1

Type RM Length L Ch R = 1,2160,434,434,434
BEGIN DESCRIPTION:
UDS St 42 5.0
END DESCRIPTION:
XS GIS Cut Line= 3
      2259915.84      7213603.81      2259726.22      7213702.53
      2259513.52      7213849.13
#Sta/Elev= 30
  4790.0  997.05  4792.3  996.11  4865.4  991.57  4880.7  991.92  4919.3  990.42
  4947.0  990.92  4955.5  988.15  4963.5  979.11  4969.1  979.32  4978.1  967.89
  4983.3  959.78  4983.8  959.28  4987.8  959.78  5003.8  961.68  5007.3  965.35
  5013.4  965.27  5022.2  967.25  5036.8  968.58  5043.1  967.87  5049.2  969.77
  5058.0  969.70  5072.9  971.38  5079.0  973.14  5108.7  974.67  5114.8  975.84
  5129.7  981.46  5144.6  983.89  5150.7  986.98  5165.5  989.07  5262.1  993.96
#Mann=3,-1,0
  4790.0    0.12       0  4983.3    0.07       0  4987.8    0.12       0
Bank Sta=4983.3,4987.8
Exp/Cntr=0.3,0.1

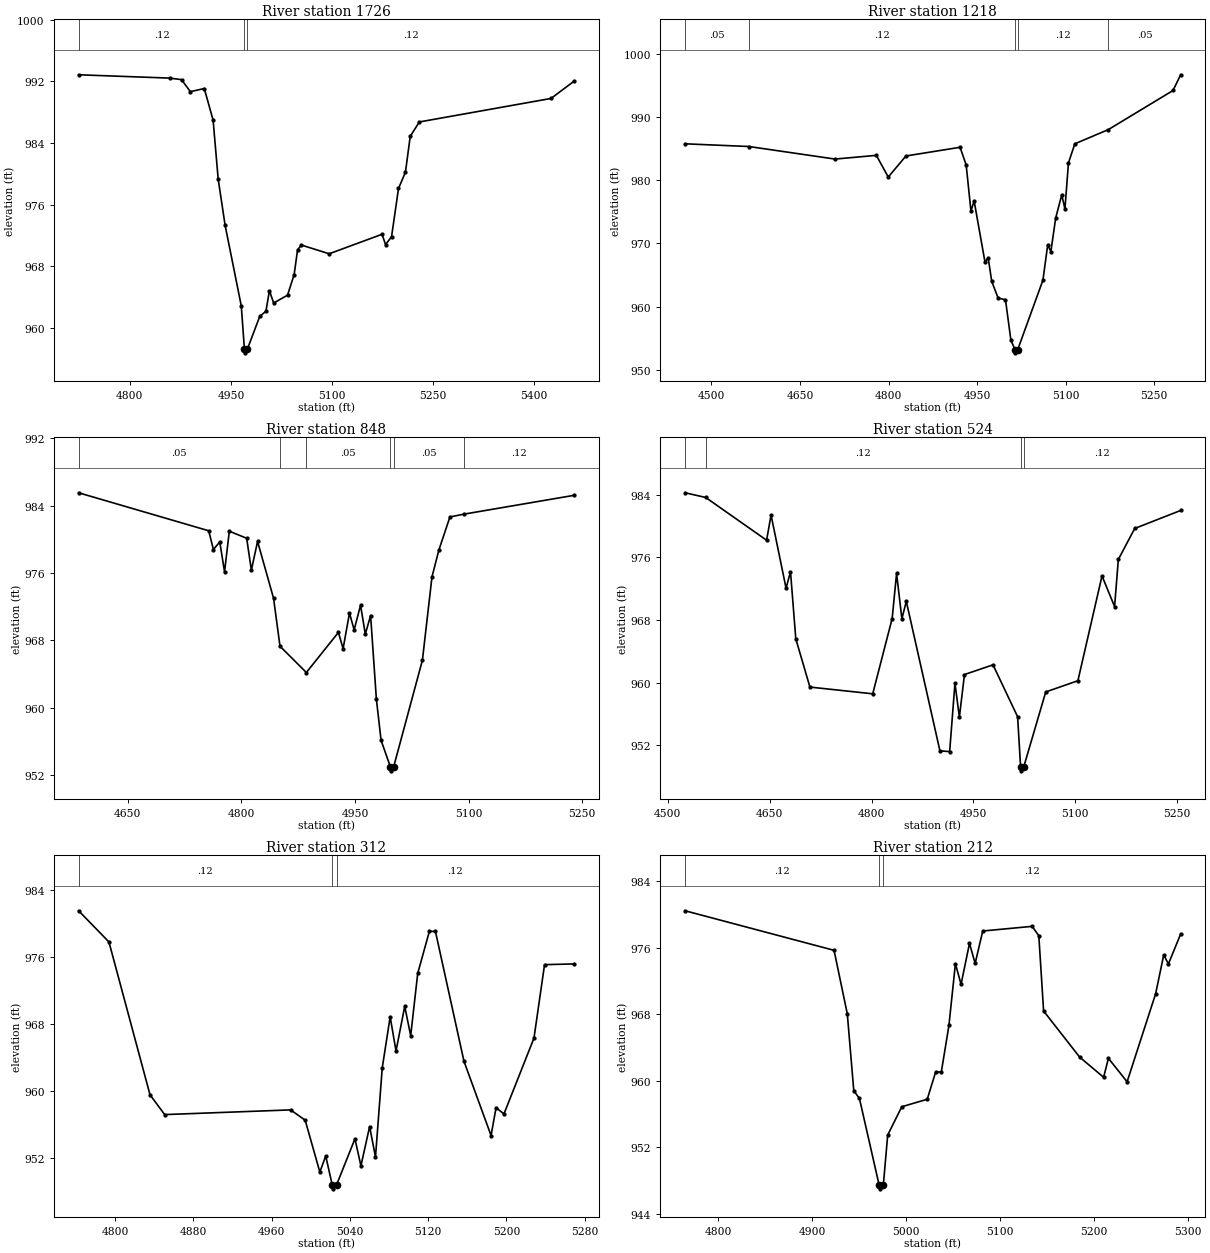
Type RM Length L Ch R = 1,1726,508,508,508
BEGIN DESCRIPTION:
UDS St 42 4.0
END DESCRIPTION:
XS GIS Cut Line= 2
      2259650.52      7213088.86      2259477.07      7213803.21
#Sta/Elev= 30
  4724.1  992.85  4859.0  992.42  4876.7  992.22  4889.9  990.66  4910.5  991.07
  4923.6  986.96  4931.1  979.33  4941.4  973.32  4965.4  962.86  4970.0  957.28
  4970.4  956.78  4974.5  957.28  4992.8  961.51  5002.0  962.18  5007.1  964.85
  5013.4  963.24  5034.0  964.26  5043.8  966.93  5048.9  970.16  5054.6  970.76
  5095.8  969.63  5174.2  972.16  5179.4  970.82  5188.3  971.84  5198.6  978.10
  5208.9  980.21  5216.0  984.86  5229.5  986.73  5424.9  989.78  5459.2  992.03
#Mann=3,-1,0
  4724.1    0.12       0  4970.0    0.07       0  4974.5    0.12       0
Bank Sta=4970,4974.5
Exp/Cntr=0.3,0.1

Type RM Length L Ch R = 1,1218,370,370,370
BEGIN DESCRIPTION:
UDS St 42 3.0
END DESCRIPTION:
XS GIS Cut Line= 3
      2259428.01      7212976.03      2259418.12      7213426.14
      2259268.38      7213785.36
#Sta/Elev= 30
  4455.4  985.79  4563.5  985.36  4709.4  983.37  4779.4  983.96  4799.5  980.52
  4829.5  983.86  4921.2  985.24  4931.5  982.44  4939.6  975.14  4945.0  976.73
  4963.4  967.04  4968.8  967.72  4974.8  963.99  4985.6  961.35  4998.1  961.07
  5007.3  954.65  5014.3  953.16  5014.7  952.66  5018.8  953.16  5061.5  964.17
  5069.6  969.75  5075.0  968.72  5083.1  974.01  5093.4  977.70  5098.8  975.47
  5104.8  982.77  5115.6  985.79  5172.3  988.04  5281.9  994.24  5294.8  996.73
#Mann=5,-1,0
  4455.4    0.05       0  4563.5    0.12       0  5014.3    0.07       0
  5018.8    0.12       0  5172.3    0.05       0
Bank Sta=5014.3,5018.8
Exp/Cntr=0.3,0.1

Type RM Length L Ch R = 1,848,324,324,324
BEGIN DESCRIPTION:
UDS St 42 2.0
END DESCRIPTION:
XS GIS Cut Line= 3
      2259408.32      7212910.00      2259164.34      7213240.29
      2259069.43      7213464.50
#Sta/Elev= 30
  4585.3  985.51  4757.0  981.00  4763.2  978.77  4771.6  979.68  4777.9  976.13
  4784.2  980.95  4807.1  980.11  4813.3  976.33  4821.5  979.73  4842.6  972.99
  4851.1  967.30  4885.9  964.18  4928.2  968.94  4934.4  967.01  4942.8  971.23
  4949.0  969.24  4957.4  972.17  4963.7  968.74  4970.7  970.94  4978.3  961.04
  4984.5  956.14  4996.7  953.01  4997.1  952.51  5001.2  953.01  5039.1  965.65
  5051.7  975.52  5060.8  978.71  5075.4  982.64  5094.3  982.98  5239.4  985.21
#Mann=6,-1,0
  4585.3    0.05       0  4851.1    0.12       0  4885.9    0.05       0
  4996.7   0.033       0  5001.2    0.05       0  5094.3    0.12       0
Bank Sta=4996.7,5001.2
Exp/Cntr=0.3,0.1

Type RM Length L Ch R = 1,524,212,212,212
BEGIN DESCRIPTION:
UDS St 42 1.0
END DESCRIPTION:
XS GIS Cut Line= 3
      2259334.28      7212746.60      2258924.76      7213089.20
      2258998.61      7213269.97
#Sta/Elev= 30
  4525.7  984.25  4556.0  983.65  4645.6  978.19  4652.2  981.40  4674.3  972.05
  4680.8  974.17  4688.6  965.59  4709.4  959.43  4801.8  958.57  4830.4  968.19
  4836.9  973.94  4844.7  968.16  4851.2  970.38  4900.7  951.28  4915.0  951.19
  4922.8  959.92  4929.3  955.59  4936.8  961.03  4978.8  962.27  5015.0  955.64
  5019.4  949.23  5019.9  948.73  5024.0  949.23  5056.4  958.81  5103.7  960.24
  5139.2  973.63  5157.7  969.71  5163.2  975.73  5187.3  979.69  5254.9  981.99
#Mann=4,-1,0
  4525.7    0.05       0  4556.0    0.12       0  5019.4    0.07       0
  5024.0    0.12       0
Bank Sta=5019.4,5024
Exp/Cntr=0.3,0.1

Type RM Length L Ch R = 1,312,100,100,100
BEGIN DESCRIPTION:
UDS St 42 0.9
END DESCRIPTION:
XS GIS Cut Line= 3
      2259226.02      7212755.09      2258927.07      7212957.83
      2258896.75      7213100.23
#Sta/Elev= 30
  4762.6  981.55  4793.6  977.83  4835.6  959.59  4850.6  957.23  4979.4  957.79
  4994.3  956.56  5009.3  950.37  5015.3  952.29  5021.9  948.87  5022.4  948.37
  5026.5  948.87  5045.2  954.34  5051.3  951.11  5060.2  955.80  5066.2  952.17
  5073.1  962.79  5081.2  968.90  5087.2  964.82  5096.1  970.15  5102.2  966.65
  5109.4  974.08  5121.3  979.09  5127.5  979.09  5156.7  963.59  5184.4  954.73
  5189.5  958.05  5197.6  957.31  5228.3  966.36  5239.1  975.12  5269.4  975.21
#Mann=3,-1,0
  4762.6    0.12       0  5021.9    0.07       0  5026.5    0.12       0
Bank Sta=5021.9,5026.5
Exp/Cntr=0.3,0.1

Type RM Length L Ch R = 1,212,158,158,158
BEGIN DESCRIPTION:
UDS St 42 0.8
END DESCRIPTION:
XS GIS Cut Line= 4
      2259167.83      7212718.29      2259023.12      7212737.75
      2258921.29      7212890.59      2258891.85      7213086.33
#Sta/Elev= 30
  4764.6  980.42  4923.2  975.67  4937.3  968.04  4944.2  958.80  4950.2  957.88
  4971.1  947.52  4971.6  947.02  4975.7  947.52  4980.3  953.48  4995.3  956.88
  5022.4  957.78  5031.4  961.07  5037.4  961.05  5045.5  966.65  5052.4  974.07
  5058.4  971.58  5067.4  976.51  5073.4  974.09  5081.5  977.99  5134.1  978.55
  5141.2  977.42  5146.3  968.38  5184.7  962.84  5210.2  960.42  5215.3  962.70
  5235.2  959.88  5265.6  970.46  5274.2  975.12  5279.2  974.04  5292.2  977.62
#Mann=3,-1,0
  4764.6    0.12       0  4971.1    0.07       0  4975.7    0.12       0
Bank Sta=4971.1,4975.7
Exp/Cntr=0.3,0.1

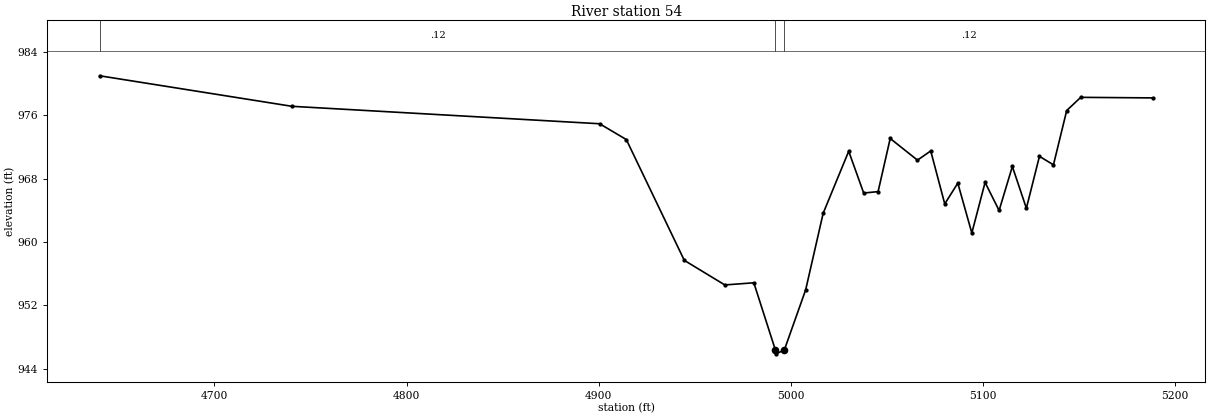
Type RM Length L Ch R = 1,54,0,0,0
BEGIN DESCRIPTION:
UDS St 42 0.7
END DESCRIPTION:
XS GIS Cut Line= 4
      2259179.03      7212702.45      2258909.52      7212713.69
      2258799.09      7212786.28      2258905.95      7212886.35
#Sta/Elev= 30
  4640.2  980.97  4740.3  977.12  4900.5  974.92  4914.4  972.93  4944.6  957.69
  4965.7  954.59  4980.8  954.86  4992.0  946.40  4992.5  945.90  4996.7  946.40
  5007.8  953.98  5016.9  963.63  5030.2  971.45  5038.0  966.18  5045.5  966.36
  5051.8  973.06  5066.0  970.33  5072.9  971.49  5080.2  964.81  5087.0  967.43
  5094.3  961.14  5101.2  967.52  5108.5  963.98  5115.4  969.53  5122.7  964.26
  5129.5  970.81  5136.8  969.74  5143.7  976.59  5151.0  978.25  5188.5  978.18
#Mann=3,-1,0
  4640.2    0.12       0  4992.0    0.07       0  4996.7    0.12       0
Bank Sta=4992,4996.7
Exp/Cntr=0.3,0.1

Chan Stop Cuts=-1