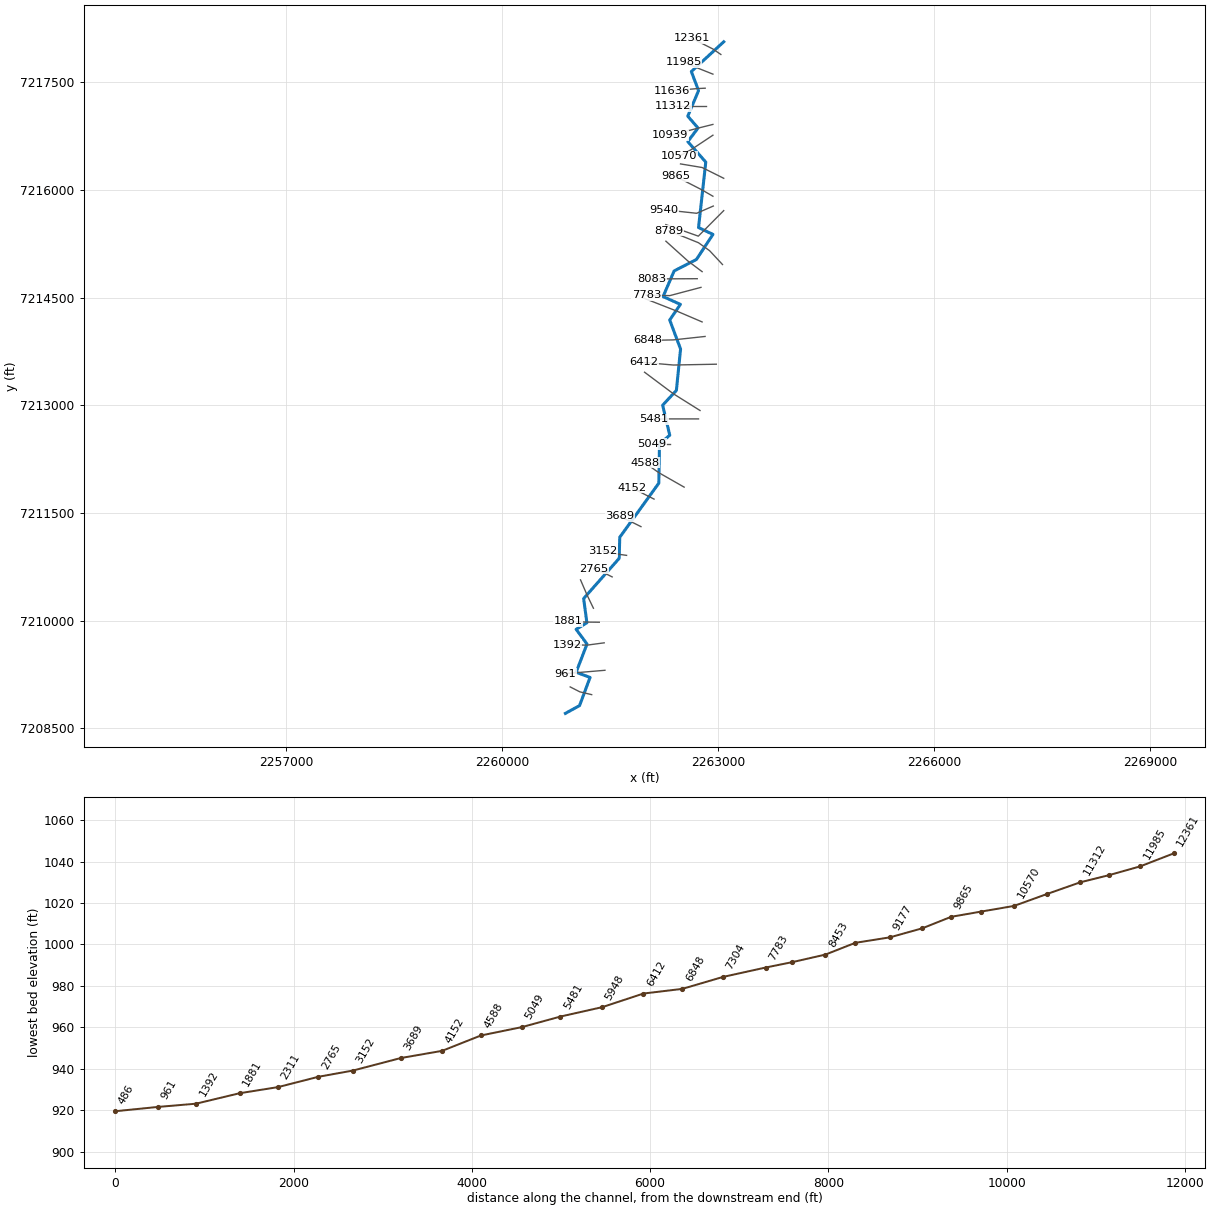
--- UDS St 43.prj (project) ---

Proj Title=UDS St 43 Base Level Engineering
Current Plan=p01
Default Exp/Contr=0.3,0.1
English Units
Geom File=g01
Flow File=f01
Plan File=p01
BEGIN DESCRIPTION:
UDS St 43
END DESCRIPTION:

--- UDS St 43.p01 (plan) ---

Plan Title=Multiple Run
Short Identifier=Multiple
Geom File=g01
Flow File=f01
Subcritical Flow
K Sum by GR= 0
Std Step Tol= 0.01
Critical Tol= 0.01
Num of Std Step Trials= 20
Max Error Tol= 0.3
Flow Tol Ratio= 0.001
Split Flow NTrial= 30
Split Flow Tol= 0.02
Split Flow Ratio= 0.02
Log Output Level= 0
Friction Slope Method= 1
Unsteady Friction Slope Method= 2
Unsteady Bridges Friction Slope Method= 1
Parabolic Critical Depth
Global Vel Dist=  1 , 1 , 1
Global Log Level= 0
CheckData=True
Encroach Param= -1, 0, 0, 0
BEGIN DESCRIPTION:
Multiple Run
END DESCRIPTION:

--- UDS St 43.f01 (steady flow) ---

Flow Title=Multiple
Number of Profiles=7
Profile Names=10-year,25-year,50-year,1pct_min,100-year,1pct_plu,500-year
River Rch & RM= UDS St 43,Reach-1,12361
     692     967    1200     739    1475    2942    2234
River Rch & RM= UDS St 43,Reach-1,7304
     850    1200    1497     927    1850    3691    2832
Boundary for River Rch & Prof#=UDS St 43,Reach-1,1
Up Type=0
Dn Type=3
Dn Slope=0.005
Boundary for River Rch & Prof#=UDS St 43,Reach-1,2
Up Type=0
Dn Type=3
Dn Slope=0.005
Boundary for River Rch & Prof#=UDS St 43,Reach-1,3
Up Type=0
Dn Type=3
Dn Slope=0.005
Boundary for River Rch & Prof#=UDS St 43,Reach-1,4
Up Type=0
Dn Type=3
Dn Slope=0.005
Boundary for River Rch & Prof#=UDS St 43,Reach-1,5
Up Type=0
Dn Type=3
Dn Slope=0.005
Boundary for River Rch & Prof#=UDS St 43,Reach-1,6
Up Type=0
Dn Type=3
Dn Slope=0.005
Boundary for River Rch & Prof#=UDS St 43,Reach-1,7
Up Type=0
Dn Type=3
Dn Slope=0.005

--- UDS St 43.g01 (geometry) ---

Geom Title=Existing Conditions

River Reach=UDS St 43,Reach-1
Reach XY= 30
      2263079.00      7218060.00      2262629.23      7217645.91
      2262729.30      7217380.34      2262579.34      7217025.04
      2262721.73      7216859.94      2262579.70      7216670.70
      2262829.53      7216385.12      2262729.03      7215473.89
      2262929.45      7215378.91      2262699.54      7215029.47
      2262389.74      7214869.70      2262236.51      7214513.10
      2262477.13      7214404.31      2262328.52      7214187.24
      2262479.46      7213782.84      2262421.18      7213206.59
      2262230.19      7213000.39      2262329.24      7212582.55
      2262186.69      7212463.67      2262177.30      7211915.46
      2261634.45      7211162.47      2261626.06      7210867.97
      2261132.42      7210308.77      2261177.50      7209971.54
      2261028.49      7209880.24      2261178.98      7209675.41
      2261028.54      7209282.53      2261221.82      7209210.33
      2261075.69      7208818.11      2260879.00      7208710.00

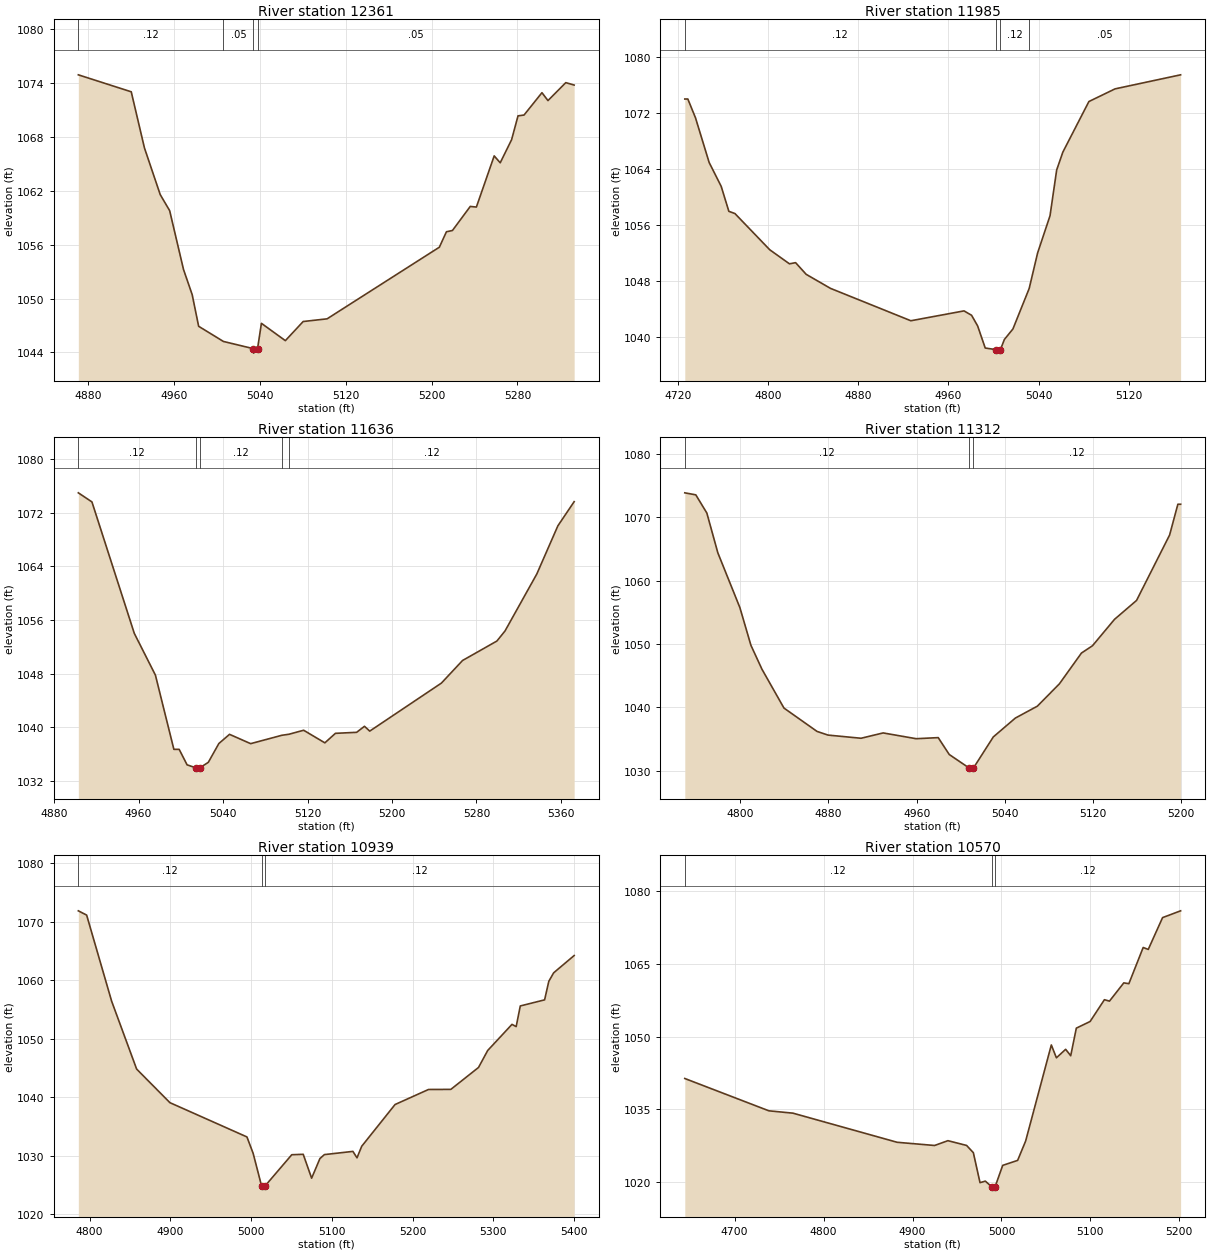
Type RM Length L Ch R = 1,12361,376,376,376
BEGIN DESCRIPTION:
UDS St 43 30.0
END DESCRIPTION:
XS GIS Cut Line= 3
      2263039.68      7217883.65      2262929.00      7217960.00
      2262637.07      7218108.52
#Sta/Elev= 30
  4870.9 1074.92  4920.2 1073.03  4932.5 1066.78  4947.2 1061.58  4956.0 1059.79
  4968.9 1053.24  4977.0 1050.43  4983.0 1046.91  5006.1 1045.22  5033.9 1044.42
  5034.2 1043.92  5037.9 1044.42  5041.5 1047.24  5063.8 1045.31  5080.4 1047.44
  5102.7 1047.74  5207.3 1055.72  5213.9 1057.44  5219.5 1057.58  5236.1 1060.26
  5241.8 1060.19  5258.4 1065.89  5264.0 1065.12  5274.6 1067.69  5280.6 1070.35
  5286.2 1070.44  5302.9 1072.93  5308.5 1072.05  5325.1 1074.05  5332.9 1073.78
#Mann=4,-1,0
  4870.9    0.12       0  5006.1    0.05       0  5033.9    0.07       0
  5037.9    0.05       0
Bank Sta=5033.9,5037.9
Exp/Cntr=0.3,0.1

Type RM Length L Ch R = 1,11985,349,349,349
BEGIN DESCRIPTION:
UDS St 43 29.0
END DESCRIPTION:
XS GIS Cut Line= 3
      2262929.03      7217609.99      2262679.00      7217710.00
      2262523.25      7217779.87
#Sta/Elev= 30
  4726.1 1074.00  4728.8 1074.00  4735.6 1071.31  4747.7 1064.93  4758.4 1061.51
  4765.2 1057.94  4770.6 1057.62  4801.5 1052.44  4819.0 1050.43  4824.4 1050.60
  4833.8 1048.93  4855.4 1046.92  4926.7 1042.29  4973.9 1043.70  4980.6 1043.07
  4986.0 1041.54  4992.7 1038.39  5002.2 1038.16  5002.5 1037.66  5006.2 1038.16
  5009.7 1039.61  5017.3 1041.12  5031.7 1046.90  5039.2 1051.99  5050.2 1057.30
  5056.1 1063.85  5061.6 1066.41  5084.7 1073.64  5107.9 1075.45  5166.1 1077.46
#Mann=4,-1,0
  4726.1    0.12       0  5002.2    0.07       0  5006.2    0.12       0
  5031.7    0.05       0
Bank Sta=5002.2,5006.2
Exp/Cntr=0.3,0.1

Type RM Length L Ch R = 1,11636,324,324,324
BEGIN DESCRIPTION:
UDS St 43 28.0
END DESCRIPTION:
XS GIS Cut Line= 3
      2262821.90      7217414.14      2262729.00      7217410.00
      2262353.69      7217378.69
#Sta/Elev= 30
  4902.9 1074.97  4915.8 1073.61  4955.9 1054.00  4975.9 1047.77  4993.4 1036.69
  4998.4 1036.69  5005.9 1034.38  5014.0 1033.94  5014.2 1033.44  5017.7 1033.44
  5018.0 1033.94  5026.0 1034.75  5036.0 1037.56  5046.1 1038.93  5066.1 1037.54
  5095.7 1038.79  5102.3 1038.94  5116.3 1039.54  5136.4 1037.66  5146.4 1039.08
  5166.5 1039.23  5173.9 1040.13  5178.9 1039.41  5246.8 1046.58  5266.8 1049.95
  5299.3 1052.85  5307.0 1054.35  5337.1 1062.85  5357.1 1070.05  5372.5 1073.65
#Mann=5,-1,0
  4902.9    0.12       0  5014.0    0.07       0  5018.0    0.12       0
  5095.7    0.05       0  5102.3    0.12       0
Bank Sta=5014,5018
Exp/Cntr=0.3,0.1

Type RM Length L Ch R = 1,11312,373,373,373
BEGIN DESCRIPTION:
UDS St 43 27.0
END DESCRIPTION:
XS GIS Cut Line= 3
      2262828.99      7217160.00      2262579.00      7217160.00
      2262378.99      7217160.00
#Sta/Elev= 30
  4749.6 1073.82  4759.6 1073.50  4769.6 1070.64  4779.6 1064.36  4799.6 1055.73
  4809.6 1049.80  4819.6 1046.03  4839.6 1039.90  4869.6 1036.22  4879.6 1035.64
  4909.6 1035.14  4929.6 1035.98  4959.6 1035.07  4979.6 1035.24  4989.6 1032.58
  5007.6 1030.46  5007.8 1029.96  5011.3 1029.96  5011.6 1030.46  5029.6 1035.35
  5049.6 1038.32  5069.6 1040.20  5089.6 1043.72  5109.6 1048.57  5119.6 1049.72
  5139.6 1053.88  5159.6 1056.86  5189.6 1067.17  5197.1 1072.02  5199.6 1072.02
#Mann=3,-1,0
  4749.6    0.12       0  5007.6    0.07       0  5011.6    0.12       0
Bank Sta=5007.6,5011.6
Exp/Cntr=0.3,0.1

Type RM Length L Ch R = 1,10939,369,369,369
BEGIN DESCRIPTION:
UDS St 43 26.0
END DESCRIPTION:
XS GIS Cut Line= 3
      2262929.04      7216910.01      2262729.00      7216860.00
      2262334.46      7216756.84
#Sta/Elev= 30
  4786.0 1071.89  4796.3 1071.16  4827.3 1056.42  4858.2 1044.84  4899.4 1039.10
  4994.8 1033.24  5002.5 1030.43  5013.0 1024.82  5013.2 1024.32  5017.0 1024.82
  5050.3 1030.20  5064.5 1030.27  5074.9 1026.19  5085.2 1029.55  5090.7 1030.22
  5126.0 1030.77  5131.1 1029.67  5136.9 1031.64  5178.2 1038.78  5219.6 1041.35
  5247.3 1041.37  5281.6 1045.12  5292.9 1048.01  5323.0 1052.48  5328.2 1052.10
  5333.3 1055.63  5363.4 1056.67  5368.6 1059.84  5374.6 1061.29  5400.0 1064.25
#Mann=3,-1,0
  4786.0    0.12       0  5013.0    0.07       0  5017.0    0.12       0
Bank Sta=5013,5017
Exp/Cntr=0.3,0.1

Type RM Length L Ch R = 1,10570,369,369,369
BEGIN DESCRIPTION:
UDS St 43 25.0
END DESCRIPTION:
XS GIS Cut Line= 3
      2262928.97      7216759.98      2262629.00      7216560.00
      2262456.15      7216465.31
#Sta/Elev= 30
  4643.9 1041.37  4738.5 1034.71  4765.5 1034.23  4882.7 1028.23  4924.8 1027.57
  4939.8 1028.56  4960.8 1027.58  4968.4 1026.09  4975.9 1019.91  4981.9 1020.23
  4988.9 1019.08  4989.1 1018.58  4992.9 1019.08  5001.4 1023.47  5018.2 1024.50
  5027.2 1028.48  5056.1 1048.28  5061.8 1045.63  5072.2 1047.38  5077.9 1046.06
  5084.2 1051.74  5099.7 1053.11  5115.8 1057.60  5121.5 1057.31  5137.6 1061.07
  5143.3 1060.90  5159.4 1068.36  5165.1 1067.96  5181.2 1074.51  5201.5 1075.91
#Mann=3,-1,0
  4643.9    0.12       0  4988.9    0.07       0  4992.9    0.12       0
Bank Sta=4988.9,4992.9
Exp/Cntr=0.3,0.1

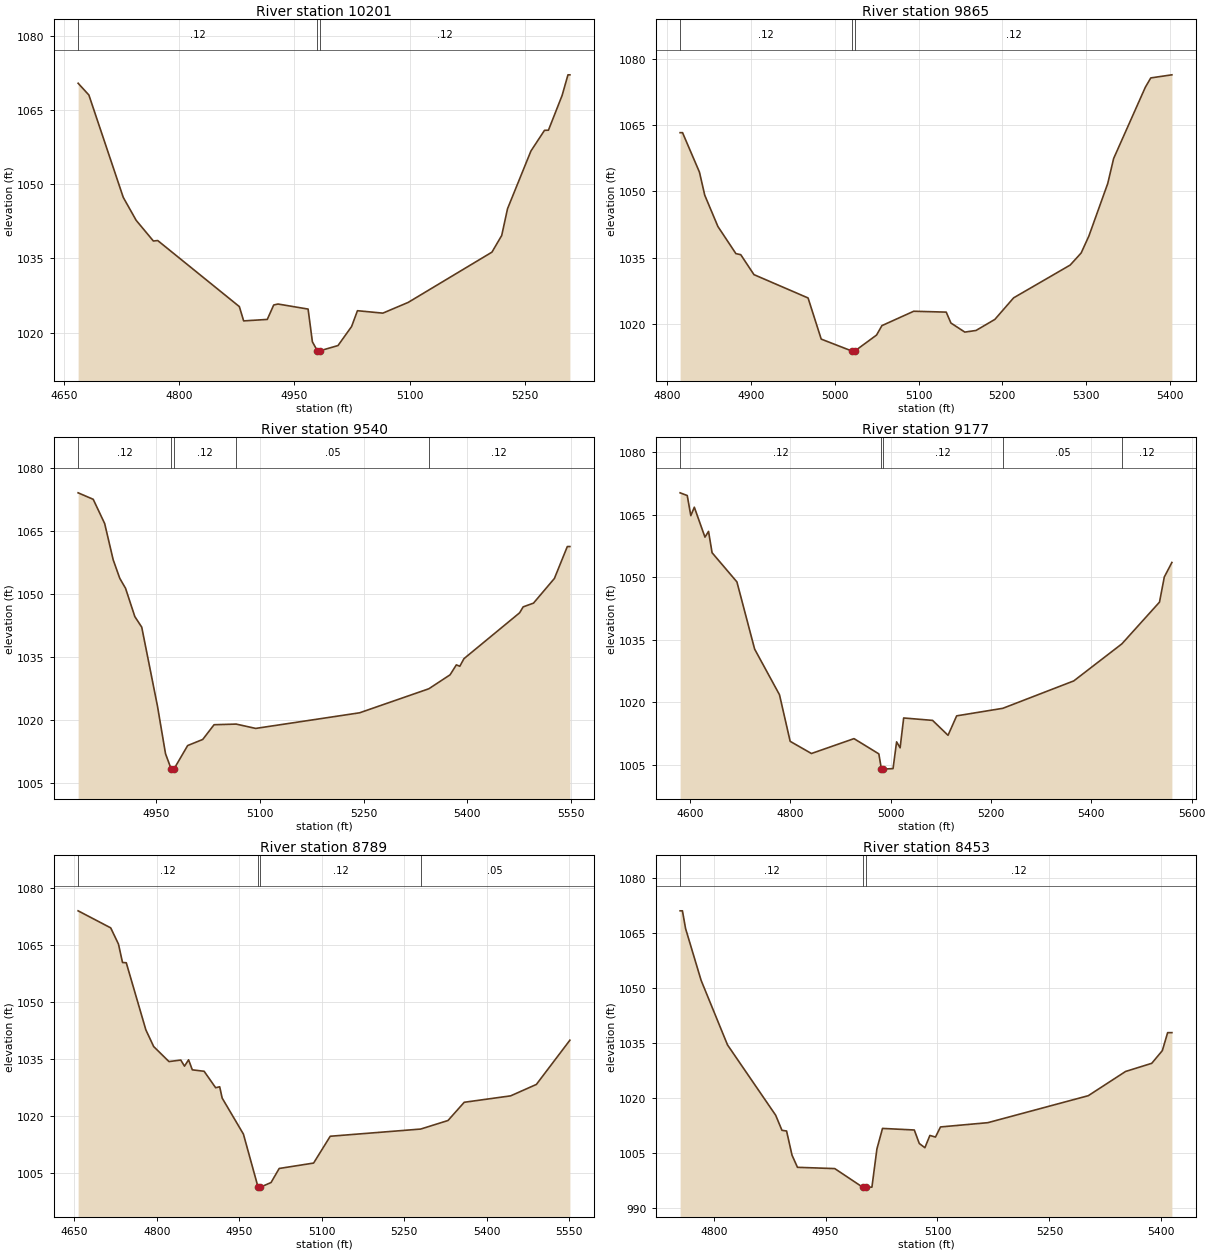
Type RM Length L Ch R = 1,10201,336,336,336
BEGIN DESCRIPTION:
UDS St 43 24.0
END DESCRIPTION:
XS GIS Cut Line= 3
      2263079.04      7216159.98      2262779.00      7216310.00
      2262478.99      7216360.00
#Sta/Elev= 30
  4668.7 1070.38  4682.7 1068.00  4727.4 1047.32  4744.2 1042.68  4766.6 1038.50
  4772.2 1038.60  4878.4 1025.25  4884.0 1022.36  4914.7 1022.66  4923.1 1025.58
  4928.7 1025.77  4967.8 1024.75  4973.4 1018.13  4979.8 1016.35  4980.0 1015.85
  4983.8 1016.35  5006.7 1017.38  5024.4 1021.23  5032.0 1024.42  5065.0 1023.93
  5097.9 1026.09  5206.9 1036.25  5219.6 1039.61  5227.2 1045.03  5257.6 1056.68
  5275.3 1060.87  5280.4 1060.89  5298.2 1067.92  5305.8 1072.08  5308.3 1072.08
#Mann=3,-1,0
  4668.7    0.12       0  4979.8    0.07       0  4983.8    0.12       0
Bank Sta=4979.8,4983.8
Exp/Cntr=0.3,0.1

Type RM Length L Ch R = 1,9865,325,325,325
BEGIN DESCRIPTION:
UDS St 43 23.0
END DESCRIPTION:
XS GIS Cut Line= 3
      2262928.97      7215910.02      2262769.57      7216002.40
      2262410.81      7216186.13
#Sta/Elev= 30
  4815.2 1063.33  4818.1 1063.33  4838.3 1054.37  4844.6 1049.16  4860.3 1042.06
  4881.8 1035.90  4887.6 1035.66  4903.4 1031.13  4968.0 1025.84  4983.7 1016.51
  5020.0 1013.83  5020.2 1013.33  5024.0 1013.83  5049.8 1017.43  5056.2 1019.57
  5094.2 1022.83  5133.0 1022.63  5138.6 1020.16  5155.2 1018.10  5168.6 1018.47
  5191.1 1020.98  5213.5 1025.87  5281.0 1033.30  5294.1 1036.03  5303.4 1039.90
  5325.9 1051.81  5332.9 1057.45  5370.8 1073.64  5377.3 1075.75  5402.5 1076.45
#Mann=3,-1,0
  4815.2    0.12       0  5020.0    0.07       0  5024.0    0.12       0
Bank Sta=5020,5024
Exp/Cntr=0.3,0.1

Type RM Length L Ch R = 1,9540,363,363,363
BEGIN DESCRIPTION:
UDS St 43 22.0
END DESCRIPTION:
XS GIS Cut Line= 3
      2262934.21      7215773.60      2262702.93      7215672.78
      2262246.70      7215722.28
#Sta/Elev= 30
  4837.2 1074.05  4859.0 1072.51  4875.6 1066.73  4887.9 1058.11  4897.4 1053.70
  4905.8 1051.31  4919.2 1044.58  4929.2 1042.06  4952.0 1023.22  4963.6 1011.91
  4971.8 1008.28  4972.0 1007.78  4975.8 1008.28  4995.6 1013.87  5017.4 1015.32
  5033.8 1018.83  5065.8 1018.98  5094.0 1017.95  5244.3 1021.67  5344.4 1027.39
  5375.1 1030.71  5384.2 1033.08  5389.2 1032.75  5395.2 1034.56  5475.7 1045.48
  5480.8 1046.89  5495.8 1047.79  5526.0 1053.66  5544.7 1061.26  5548.4 1061.26
#Mann=5,-1,0
  4837.2    0.12       0  4971.8    0.07       0  4975.8    0.12       0
  5065.8    0.05       0  5344.4    0.12       0
Bank Sta=4971.8,4975.8
Exp/Cntr=0.3,0.1

Type RM Length L Ch R = 1,9177,388,388,388
BEGIN DESCRIPTION:
UDS St 43 21.0
END DESCRIPTION:
XS GIS Cut Line= 3
      2263079.03      7215710.03      2262726.17      7215354.38
      2262274.80      7215514.73
#Sta/Elev= 30
  4580.6 1070.23  4594.8 1069.58  4601.9 1064.75  4608.9 1066.78  4630.1 1059.59
  4637.2 1060.97  4644.3 1055.85  4693.8 1048.84  4729.1 1032.71  4778.6 1021.76
  4799.9 1010.57  4842.3 1007.65  4927.1 1011.22  4976.6 1007.56  4981.7 1003.92
  4982.0 1003.42  4985.7 1003.92  5004.9 1004.02  5012.0 1010.45  5019.0 1009.01
  5026.1 1016.18  5083.7 1015.60  5114.5 1012.02  5131.7 1016.69  5223.7 1018.50
  5365.1 1025.08  5461.0 1033.98  5535.9 1043.99  5545.5 1050.03  5560.6 1053.51
#Mann=5,-1,0
  4580.6    0.12       0  4981.7    0.07       0  4985.7    0.12       0
  5223.7    0.05       0  5461.0    0.12       0
Bank Sta=4981.7,4985.7
Exp/Cntr=0.3,0.1

Type RM Length L Ch R = 1,8789,336,336,336
BEGIN DESCRIPTION:
UDS St 43 20.0
END DESCRIPTION:
XS GIS Cut Line= 4
      2263062.16      7214959.23      2262883.34      7215151.50
      2262728.47      7215262.63      2262319.11      7215428.56
#Sta/Elev= 30
  4656.7 1073.94  4716.0 1069.46  4730.1 1065.20  4737.5 1060.35  4744.3 1060.29
  4780.0 1042.63  4794.2 1038.26  4822.0 1034.31  4843.5 1034.71  4850.3 1033.10
  4857.7 1034.78  4864.5 1032.14  4886.0 1031.76  4907.0 1027.43  4914.3 1027.69
  4918.8 1024.72  4957.5 1015.24  4984.2 1001.28  4984.4 1000.78  4988.2 1001.28
  5007.8 1002.52  5022.6 1006.21  5085.2 1007.63  5115.5 1014.68  5280.1 1016.57
  5329.8 1018.82  5359.3 1023.61  5443.8 1025.30  5490.6 1028.30  5551.6 1039.93
#Mann=4,-1,0
  4656.7    0.12       0  4984.2    0.07       0  4988.2    0.12       0
  5280.1    0.05       0
Bank Sta=4984.2,4988.2
Exp/Cntr=0.3,0.1

Type RM Length L Ch R = 1,8453,370,370,370
BEGIN DESCRIPTION:
UDS St 43 19.0
END DESCRIPTION:
XS GIS Cut Line= 3
      2262779.01      7214860.00      2262579.00      7215010.00
      2262275.46      7215284.41
#Sta/Elev= 30
  4755.0 1071.15  4758.1 1071.15  4762.3 1066.31  4783.1 1052.17  4818.5 1034.52
  4883.1 1015.29  4891.5 1011.17  4897.7 1010.98  4905.0 1004.38  4912.3 1001.06
  4962.3 1000.71  4999.9  995.60  5000.1  995.10  5003.9  995.60  5012.1  995.64
  5018.8 1006.09  5026.3 1011.69  5068.9 1011.26  5075.6 1007.57  5083.1 1006.42
  5089.8 1009.77  5097.3 1009.33  5104.0 1012.09  5167.5 1013.26  5302.1 1020.63
  5352.1 1027.25  5387.2 1029.48  5401.4 1032.95  5408.5 1037.86  5414.2 1037.86
#Mann=3,-1,0
  4755.0    0.12       0  4999.9    0.07       0  5003.9    0.12       0
Bank Sta=4999.9,5003.9
Exp/Cntr=0.3,0.1

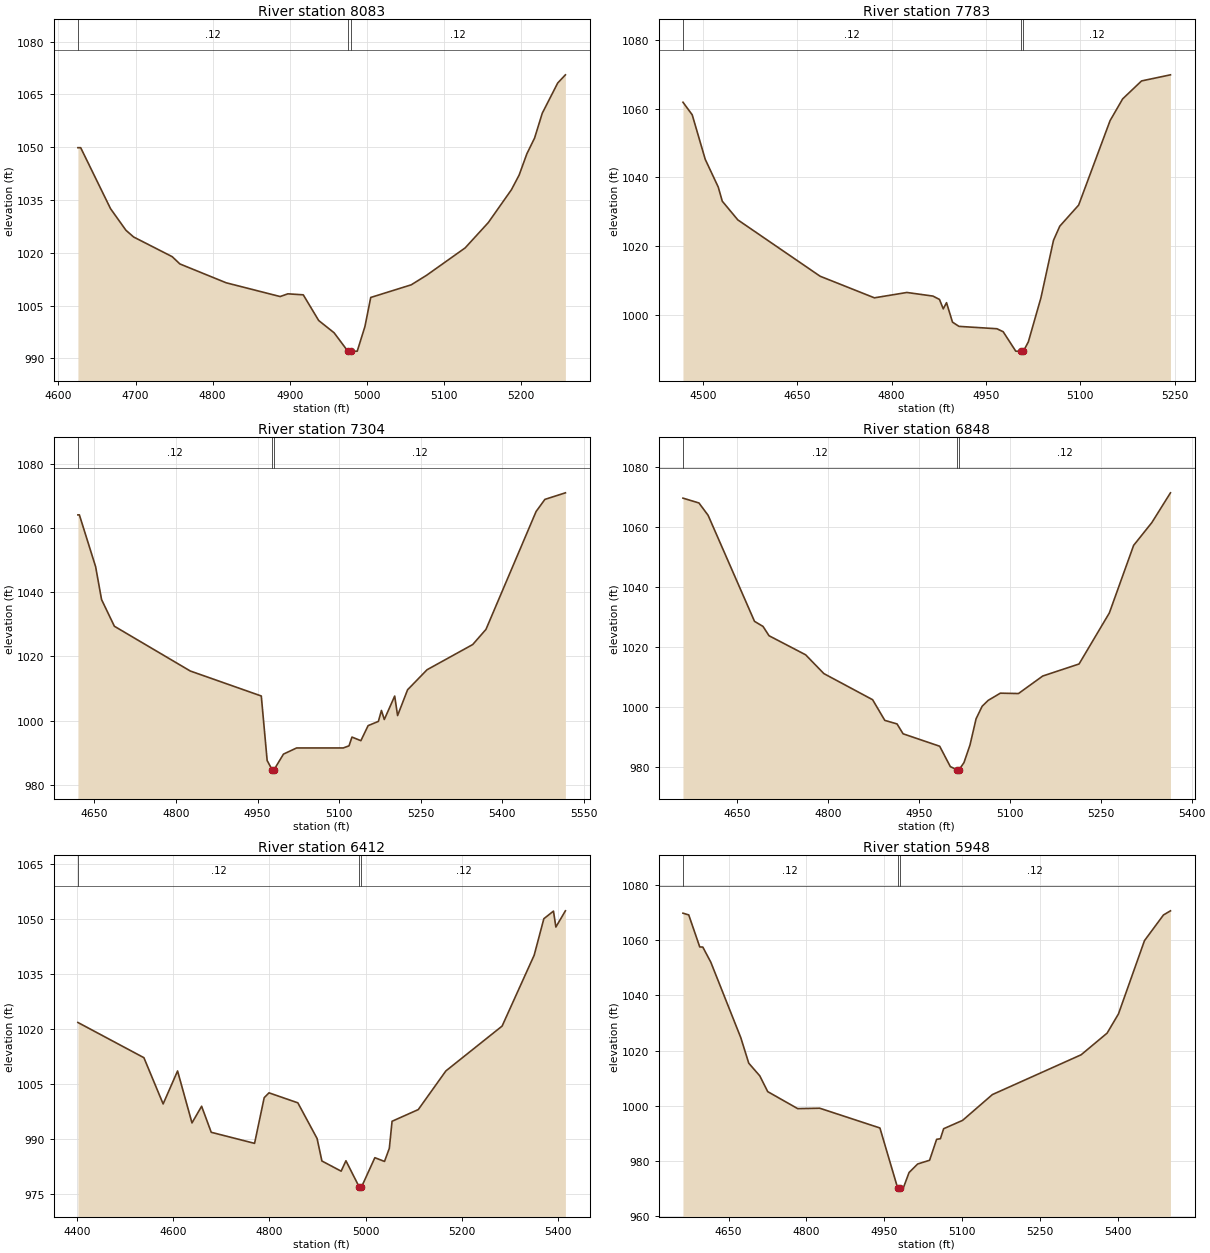
Type RM Length L Ch R = 1,8083,300,300,300
BEGIN DESCRIPTION:
UDS St 43 18.0
END DESCRIPTION:
XS GIS Cut Line= 3
      2262711.26      7214762.04      2262329.00      7214760.00
      2262078.97      7214760.00
#Sta/Elev= 30
  4625.3 1049.85  4628.9 1049.85  4667.6 1032.53  4687.6 1026.38  4697.6 1024.47
  4747.6 1018.88  4757.6 1016.81  4817.6 1011.46  4887.6 1007.55  4897.6 1008.32
  4917.6 1008.04  4937.6 1000.74  4957.6  997.25  4975.6  991.97  4975.8  991.47
  4979.6  991.97  4987.6  992.02  4997.6  999.05  5005.1 1007.29  5057.6 1010.88
  5077.6 1013.60  5127.6 1021.38  5157.6 1028.57  5187.6 1037.91  5197.6 1042.08
  5207.6 1048.11  5217.6 1052.58  5227.6 1059.65  5247.6 1068.23  5257.6 1070.56
#Mann=3,-1,0
  4625.3    0.12       0  4975.6    0.07       0  4979.6    0.12       0
Bank Sta=4975.6,4979.6
Exp/Cntr=0.3,0.1

Type RM Length L Ch R = 1,7783,479,479,479
BEGIN DESCRIPTION:
UDS St 43 17.0
END DESCRIPTION:
XS GIS Cut Line= 3
      2262763.24      7214641.31      2262330.28      7214526.51
      2262003.05      7214532.14
#Sta/Elev= 30
  4468.2 1061.91  4482.9 1058.25  4503.6 1045.29  4524.3 1037.21  4530.7 1033.10
  4555.4 1027.66  4686.3 1011.25  4772.6 1004.96  4824.3 1006.52  4865.7 1005.47
  4876.1 1004.49  4882.1 1001.75  4887.3 1003.55  4896.8  997.88  4907.1  996.65
  4967.4  995.96  4977.4  995.09  4997.4  989.43  5005.4  989.36  5005.7  988.86
  5009.4  989.36  5017.4  992.14  5037.4 1004.94  5057.4 1021.70  5067.4 1025.82
  5097.4 1031.96  5147.4 1056.56  5167.4 1062.89  5197.4 1068.11  5243.4 1069.89
#Mann=3,-1,0
  4468.2    0.12       0  5005.4    0.07       0  5009.4    0.12       0
Bank Sta=5005.4,5009.4
Exp/Cntr=0.3,0.1

Type RM Length L Ch R = 1,7304,456,456,456
BEGIN DESCRIPTION:
UDS St 43 16.0
END DESCRIPTION:
XS GIS Cut Line= 3
      2262778.99      7214160.01      2262429.00      7214310.00
      2261948.84      7214498.75
#Sta/Elev= 30
  4619.5 1064.02  4622.2 1064.02  4652.1 1047.89  4663.0 1037.68  4686.6 1029.38
  4826.2 1015.46  4956.8 1007.69  4967.6  987.62  4976.5  984.82  4976.8  984.32
  4980.5  984.82  4997.6  989.61  5021.8  991.53  5107.7  991.53  5118.2  992.19
  5123.6  994.91  5140.0  993.79  5153.3  998.47  5172.2  999.79  5177.8 1003.19
  5183.1 1000.38  5202.2 1007.67  5207.5 1001.60  5225.9 1009.62  5261.7 1015.85
  5345.7 1023.69  5370.1 1028.41  5462.3 1065.07  5478.5 1068.84  5516.2 1070.88
#Mann=3,-1,0
  4619.5    0.12       0  4976.5    0.07       0  4980.5    0.12       0
Bank Sta=4976.5,4980.5
Exp/Cntr=0.3,0.1

Type RM Length L Ch R = 1,6848,436,436,436
BEGIN DESCRIPTION:
UDS St 43 15.0
END DESCRIPTION:
XS GIS Cut Line= 3
      2262820.29      7213957.85      2262379.00      7213910.00
      2262018.17      7213902.00
#Sta/Elev= 30
  4560.2 1069.47  4586.6 1067.86  4601.7 1063.76  4678.3 1028.44  4692.3 1026.76
  4702.3 1023.65  4762.7 1017.30  4792.8 1011.04  4873.3 1002.34  4893.4  995.46
  4913.6  994.28  4923.6  990.99  4984.0  986.85  5001.6  980.06  5012.1  979.06
  5012.3  978.56  5016.1  979.06  5024.1  981.39  5034.1  987.30  5044.1  995.99
  5054.1 1000.16  5064.1 1002.12  5084.1 1004.52  5114.1 1004.40  5154.1 1010.23
  5214.1 1014.24  5264.1 1031.23  5304.2 1053.74  5334.2 1061.31  5365.0 1071.24
#Mann=3,-1,0
  4560.2    0.12       0  5012.1    0.07       0  5016.1    0.12       0
Bank Sta=5012.1,5016.1
Exp/Cntr=0.3,0.1

Type RM Length L Ch R = 1,6412,464,464,464
BEGIN DESCRIPTION:
UDS St 43 14.0
END DESCRIPTION:
XS GIS Cut Line= 3
      2262976.19      7213571.40      2262379.00      7213560.00
      2261964.33      7213596.75
#Sta/Elev= 30
  4401.8 1021.79  4539.0 1012.18  4579.0  999.56  4609.0 1008.56  4639.0  994.38
  4659.0  998.93  4679.0  991.82  4769.1  988.80  4789.1 1001.26  4799.1 1002.59
  4859.1  999.86  4899.1  990.12  4909.1  983.99  4949.1  981.21  4959.1  984.05
  4987.0  976.81  4987.4  976.31  4991.2  976.81  5019.2  984.89  5039.3  983.87
  5049.3  987.44  5055.0  994.83  5109.5  998.02  5166.9 1008.57  5283.8 1020.81
  5350.5 1040.16  5370.6 1050.11  5390.6 1052.18  5395.6 1047.84  5415.4 1052.26
#Mann=3,-1,0
  4401.8    0.12       0  4987.0    0.07       0  4991.2    0.12       0
Bank Sta=4987,4991.2
Exp/Cntr=0.3,0.1

Type RM Length L Ch R = 1,5948,467,467,467
BEGIN DESCRIPTION:
UDS St 43 13.0
END DESCRIPTION:
XS GIS Cut Line= 3
      2262749.93      7212926.89      2262379.00      7213160.00
      2261979.00      7213460.00
#Sta/Elev= 30
  4562.3 1069.86  4573.4 1069.24  4594.6 1057.62  4600.5 1057.56  4615.8 1052.11
  4673.6 1024.68  4688.9 1015.43  4710.1 1010.84  4725.4 1005.11  4783.1  998.94
  4825.5  999.09  4941.3  991.92  4975.3  970.23  4975.6  969.73  4979.5  970.23
  4986.8  970.39  4997.4  975.76  5013.9  978.85  5036.9  980.21  5050.4  987.80
  5057.7  988.02  5063.9  991.65  5100.4  994.68  5157.7 1004.04  5328.5 1018.48
  5378.5 1026.34  5400.4 1033.33  5450.4 1059.90  5486.9 1069.21  5500.4 1070.72
#Mann=3,-1,0
  4562.3    0.12       0  4975.3    0.07       0  4979.5    0.12       0
Bank Sta=4975.3,4979.5
Exp/Cntr=0.3,0.1

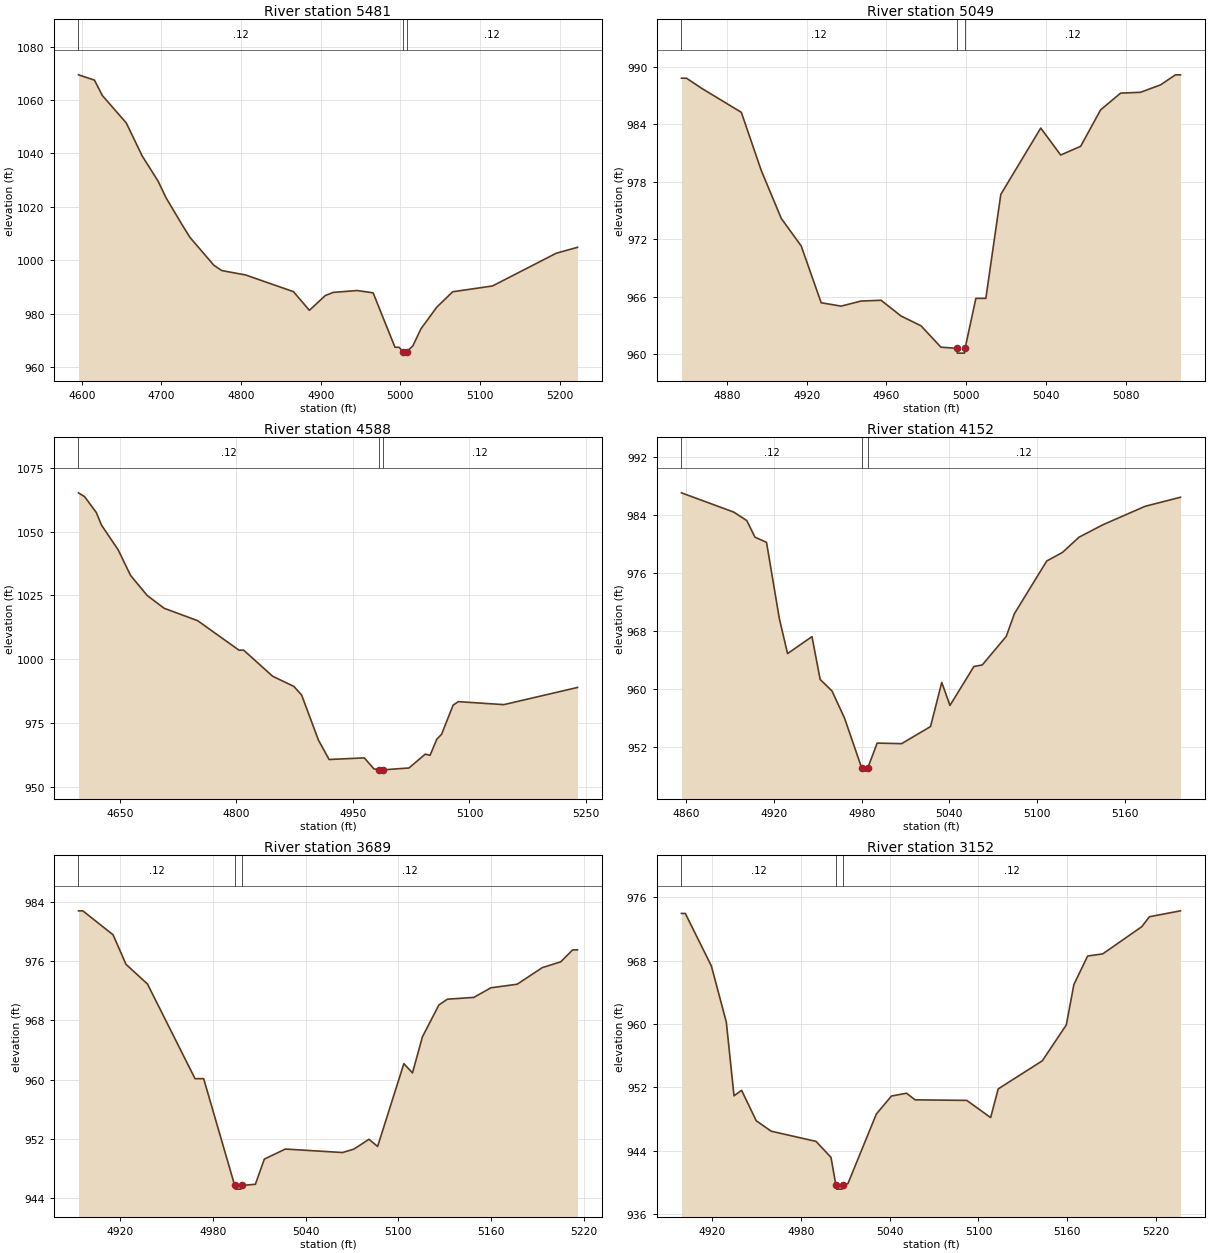
Type RM Length L Ch R = 1,5481,432,432,432
BEGIN DESCRIPTION:
UDS St 43 12.0
END DESCRIPTION:
XS GIS Cut Line= 3
      2262729.04      7212810.00      2262329.00      7212810.00
      2262102.36      7212806.68
#Sta/Elev= 30
  4595.9 1069.42  4615.9 1067.45  4625.9 1061.66  4655.9 1051.41  4675.9 1039.04
  4695.9 1029.60  4705.9 1023.37  4725.9 1013.34  4735.9 1008.55  4765.9  998.12
  4775.9  996.12  4805.9  994.47  4865.9  988.22  4885.9  981.24  4905.9  986.79
  4915.9  987.95  4945.9  988.65  4965.9  987.79  4993.4  967.41  4998.4  967.41
  5003.8  965.71  5004.1  965.21  5008.1  965.71  5015.9  967.95  5025.9  974.27
  5045.9  982.44  5065.9  988.19  5115.9  990.36  5196.0 1002.63  5222.6 1004.83
#Mann=3,-1,0
  4595.9    0.12       0  5003.8    0.07       0  5008.1    0.12       0
Bank Sta=5003.8,5008.1
Exp/Cntr=0.3,0.1

Type RM Length L Ch R = 1,5049,461,461,461
BEGIN DESCRIPTION:
UDS St 43 11.0
END DESCRIPTION:
XS GIS Cut Line= 3
      2262328.98      7212460.00      2262179.00      7212460.00
      2262078.98      7212460.00
#Sta/Elev= 30
  4857.3  988.79  4859.8  988.79  4867.3  987.75  4887.3  985.23  4897.3  979.16
  4907.3  974.17  4917.3  971.30  4927.3  965.38  4937.3  965.03  4947.3  965.56
  4957.3  965.64  4967.3  964.00  4977.3  962.98  4987.3  960.75  4995.1  960.63
  4995.5  960.13  4999.1  960.13  4999.4  960.63  5004.8  965.84  5009.8  965.84
  5017.3  976.68  5037.3  983.59  5047.3  980.78  5057.3  981.69  5067.3  985.49
  5077.3  987.23  5087.3  987.32  5097.3  988.09  5104.8  989.14  5107.3  989.14
#Mann=3,-1,0
  4857.3    0.12       0  4995.1    0.07       0  4999.4    0.12       0
Bank Sta=4995.1,4999.4
Exp/Cntr=0.3,0.1

Type RM Length L Ch R = 1,4588,436,436,436
BEGIN DESCRIPTION:
UDS St 43 10.0
END DESCRIPTION:
XS GIS Cut Line= 3
      2262529.00      7211860.00      2262179.00      7212060.00
      2261983.47      7212197.41
#Sta/Elev= 30
  4596.9 1065.18  4604.8 1063.66  4619.9 1057.43  4626.4 1052.57  4648.0 1042.81
  4663.9 1032.80  4685.4 1024.91  4707.0 1019.94  4750.2 1015.06  4803.5 1003.48
  4809.3 1003.53  4846.7  993.28  4874.0  989.30  4884.1  985.86  4905.7  968.20
  4919.4  960.63  4964.7  961.26  4977.0  956.96  4984.1  956.57  4984.5  956.07
  4988.5  956.57  5022.2  957.31  5043.1  962.73  5049.3  962.28  5058.0  968.62
  5064.1  970.50  5078.9  981.92  5085.6  983.31  5144.2  982.14  5239.0  988.87
#Mann=3,-1,0
  4596.9    0.12       0  4984.1    0.07       0  4988.5    0.12       0
Bank Sta=4984.1,4988.5
Exp/Cntr=0.3,0.1

Type RM Length L Ch R = 1,4152,463,463,463
BEGIN DESCRIPTION:
UDS St 43 9.0
END DESCRIPTION:
XS GIS Cut Line= 3
      2262110.93      7211693.34      2261979.00      7211760.00
      2261807.54      7211849.88
#Sta/Elev= 30
  4856.7  987.05  4892.5  984.39  4901.4  983.22  4907.0  980.93  4914.9  980.22
  4923.7  969.66  4929.3  964.87  4946.0  967.21  4951.6  961.30  4959.7  959.71
  4968.3  955.95  4979.9  949.15  4980.3  948.65  4983.9  948.65  4984.3  949.15
  4990.6  952.52  5007.3  952.44  5027.1  954.80  5034.8  960.89  5040.4  957.71
  5056.8  963.09  5062.5  963.30  5078.9  967.24  5084.5  970.38  5106.6  977.64
  5117.4  978.83  5128.7  980.93  5145.1  982.65  5173.9  985.19  5198.1  986.44
#Mann=3,-1,0
  4856.7    0.12       0  4979.9    0.07       0  4984.3    0.12       0
Bank Sta=4979.9,4984.3
Exp/Cntr=0.3,0.1

Type RM Length L Ch R = 1,3689,537,537,537
BEGIN DESCRIPTION:
UDS St 43 8.0
END DESCRIPTION:
XS GIS Cut Line= 3
      2261929.02      7211309.99      2261829.00      7211360.00
      2261638.48      7211451.78
#Sta/Elev= 30
  4892.8  982.83  4895.6  982.83  4915.2  979.59  4923.6  975.59  4937.5  972.93
  4968.3  960.13  4973.9  960.13  4994.0  945.69  4994.4  945.19  4998.0  945.19
  4998.5  945.69  5007.4  945.84  5013.2  949.25  5026.8  950.61  5063.9  950.14
  5071.2  950.60  5081.0  951.93  5086.6  950.96  5103.6  962.16  5109.2  960.91
  5115.6  965.77  5126.3  970.10  5131.8  970.88  5148.9  971.12  5160.0  972.42
  5177.0  972.90  5193.3  975.15  5205.2  975.93  5213.0  977.55  5216.1  977.55
#Mann=3,-1,0
  4892.8    0.12       0  4994.0    0.07       0  4998.5    0.12       0
Bank Sta=4994,4998.5
Exp/Cntr=0.3,0.1

Type RM Length L Ch R = 1,3152,387,387,387
BEGIN DESCRIPTION:
UDS St 43 7.0
END DESCRIPTION:
XS GIS Cut Line= 3
      2261729.04      7210909.99      2261621.53      7210925.22
      2261397.53      7210969.93
#Sta/Elev= 30
  4899.4  973.98  4902.0  973.98  4919.6  967.35  4929.7  960.25  4934.9  950.94
  4940.0  951.64  4949.9  947.79  4960.0  946.47  4990.3  945.18  5000.4  943.16
  5003.7  939.65  5004.2  939.15  5007.8  939.15  5008.3  939.65  5011.8  939.84
  5031.0  948.63  5041.2  950.91  5051.4  951.27  5057.2  950.43  5092.1  950.36
  5108.2  948.19  5113.3  951.81  5143.1  955.36  5159.3  959.89  5164.4  964.98
  5173.7  968.60  5183.9  968.87  5210.3  972.31  5215.4  973.56  5236.4  974.31
#Mann=3,-1,0
  4899.4    0.12       0  5003.7    0.07       0  5008.3    0.12       0
Bank Sta=5003.7,5008.3
Exp/Cntr=0.3,0.1

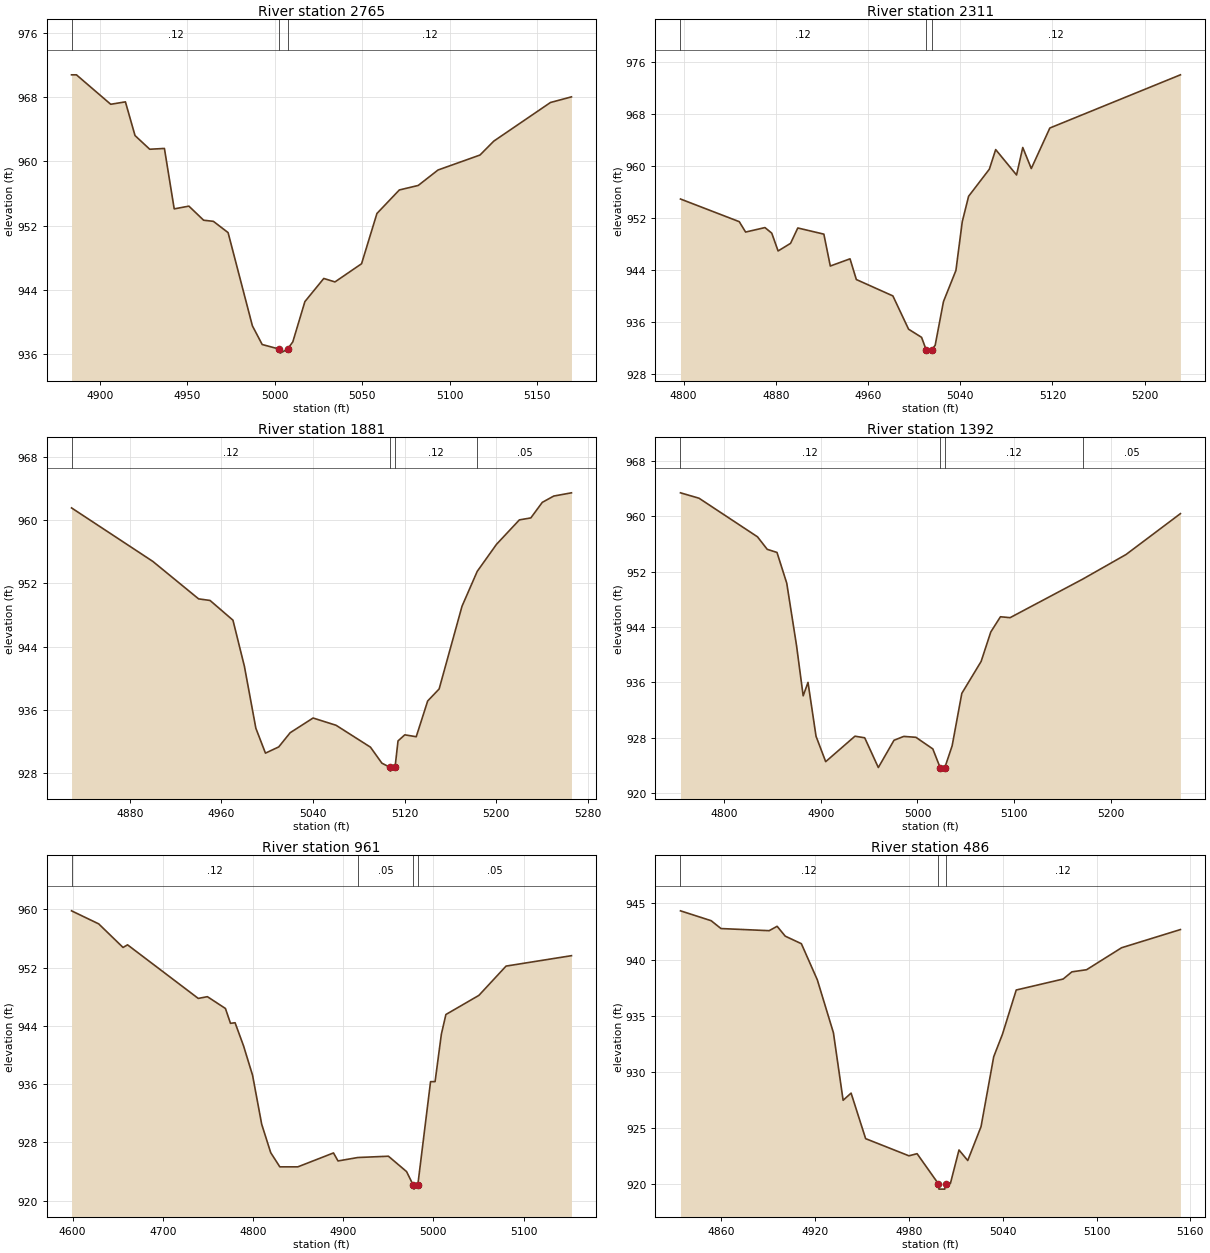
Type RM Length L Ch R = 1,2765,454,454,454
BEGIN DESCRIPTION:
UDS St 43 6.0
END DESCRIPTION:
XS GIS Cut Line= 3
      2261529.01      7210610.00      2261429.00      7210660.00
      2261267.87      7210725.64
#Sta/Elev= 30
  4883.9  970.74  4886.7  970.74  4906.3  967.08  4914.7  967.38  4920.2  963.19
  4928.6  961.49  4937.0  961.59  4942.6  954.08  4951.0  954.42  4959.4  952.67
  4965.0  952.53  4973.4  951.13  4987.3  939.54  4992.9  937.22  5002.7  936.65
  5003.2  936.15  5007.4  936.65  5010.4  937.55  5017.3  942.55  5028.1  945.43
  5034.5  945.00  5049.7  947.26  5058.5  953.51  5071.3  956.43  5082.1  956.99
  5093.4  958.91  5117.4  960.77  5125.3  962.50  5157.7  967.30  5169.7  968.00
#Mann=3,-1,0
  4883.9    0.12       0  5002.7    0.07       0  5007.4    0.12       0
Bank Sta=5002.7,5007.4
Exp/Cntr=0.3,0.1

Type RM Length L Ch R = 1,2311,430,430,430
BEGIN DESCRIPTION:
UDS St 43 5.0
END DESCRIPTION:
XS GIS Cut Line= 3
      2261268.42      7210173.91      2261179.00      7210360.00
      2261089.15      7210568.83
#Sta/Elev= 30
  4797.3  954.89  4848.3  951.40  4853.8  949.80  4870.6  950.49  4876.5  949.63
  4882.0  946.89  4892.8  948.06  4899.1  950.43  4921.7  949.48  4927.3  944.57
  4944.4  945.68  4949.9  942.49  4981.6  939.97  4995.2  934.85  5006.5  933.59
  5010.5  931.66  5011.0  931.16  5015.2  931.66  5018.3  932.37  5025.5  939.10
  5036.3  943.89  5041.8  951.40  5047.3  955.31  5065.3  959.48  5070.8  962.50
  5088.9  958.59  5094.3  962.82  5101.7  959.58  5117.8  965.82  5231.1  974.01
#Mann=3,-1,0
  4797.3    0.12       0  5010.5    0.07       0  5015.2    0.12       0
Bank Sta=5010.5,5015.2
Exp/Cntr=0.3,0.1

Type RM Length L Ch R = 1,1881,489,489,489
BEGIN DESCRIPTION:
UDS St 43 4.0
END DESCRIPTION:
XS GIS Cut Line= 3
      2261350.01      7209979.02      2261177.26      7209980.90
      2260913.50      7209990.59
#Sta/Elev= 30
  4829.1  961.58  4900.1  954.80  4940.1  950.05  4950.1  949.85  4970.1  947.35
  4980.1  941.51  4990.1  933.66  4998.5  930.50  5010.1  931.29  5020.1  933.09
  5040.1  934.95  5060.2  934.03  5090.2  931.26  5100.2  929.23  5107.0  928.72
  5107.5  928.22  5111.7  928.72  5114.3  932.05  5120.2  932.82  5130.2  932.58
  5140.2  937.11  5150.2  938.63  5170.2  949.12  5183.5  953.54  5200.3  956.96
  5220.3  960.06  5230.3  960.31  5240.3  962.28  5250.3  963.08  5265.8  963.49
#Mann=4,-1,0
  4829.1    0.12       0  5107.0    0.07       0  5111.7    0.12       0
  5183.5    0.05       0
Bank Sta=5107,5111.7
Exp/Cntr=0.3,0.1

Type RM Length L Ch R = 1,1392,431,431,431
BEGIN DESCRIPTION:
UDS St 43 3.0
END DESCRIPTION:
XS GIS Cut Line= 3
      2261417.99      7209692.20      2261179.00      7209660.00
      2260902.73      7209666.66
#Sta/Elev= 30
  4754.7  963.41  4773.9  962.63  4834.4  957.05  4844.5  955.24  4854.6  954.79
  4864.7  950.34  4874.8  941.35  4881.7  934.06  4886.7  936.00  4895.0  928.22
  4905.0  924.54  4935.3  928.22  4945.4  927.99  4959.5  923.69  4975.7  927.63
  4985.8  928.19  4998.4  928.06  5015.9  926.38  5023.5  923.67  5024.0  923.17
  5028.3  923.67  5035.9  926.83  5045.9  934.41  5065.9  939.03  5075.9  943.29
  5085.9  945.49  5095.9  945.36  5170.9  950.92  5215.9  954.49  5272.2  960.40
#Mann=4,-1,0
  4754.7    0.12       0  5023.5    0.07       0  5028.3    0.12       0
  5170.9    0.05       0
Bank Sta=5023.5,5028.3
Exp/Cntr=0.3,0.1

Type RM Length L Ch R = 1,961,475,475,475
BEGIN DESCRIPTION:
UDS St 43 2.0
END DESCRIPTION:
XS GIS Cut Line= 3
      2261429.02      7209310.00      2261030.91      7209276.11
      2260876.75      7209263.87
#Sta/Elev= 30
  4598.9  959.81  4629.0  958.02  4656.0  954.78  4661.0  955.14  4739.4  947.78
  4749.5  948.02  4769.5  946.40  4775.1  944.36  4780.2  944.44  4789.6  941.26
  4799.6  937.22  4809.7  930.50  4819.7  926.60  4829.8  924.65  4849.8  924.65
  4889.3  926.56  4894.3  925.46  4916.2  925.93  4950.2  926.11  4970.3  924.00
  4977.9  922.09  4978.5  921.59  4982.7  922.09  4996.9  936.35  5001.9  936.35
  5008.9  942.88  5013.9  945.57  5050.5  948.20  5080.6  952.22  5153.1  953.65
#Mann=4,-1,0
  4598.9    0.12       0  4916.2    0.05       0  4977.9   0.033       0
  4982.7    0.05       0
Bank Sta=4977.9,4982.7
Exp/Cntr=0.3,0.1

Type RM Length L Ch R = 1,486,0,0,0
BEGIN DESCRIPTION:
UDS St 43 1.0
END DESCRIPTION:
XS GIS Cut Line= 3
      2261244.16      7208970.70      2261079.00      7209010.00
      2260945.57      7209078.38
#Sta/Elev= 30
  4833.9  944.34  4853.5  943.46  4859.8  942.76  4890.6  942.57  4895.7  942.96
  4900.9  942.08  4911.2  941.41  4921.4  938.19  4931.7  933.47  4937.9  927.45
  4943.0  928.09  4952.3  924.03  4980.0  922.50  4985.2  922.69  4998.7  920.03
  4999.2  919.53  5002.9  919.53  5003.5  920.03  5006.5  920.03  5012.0  923.02
  5017.6  922.08  5026.1  925.10  5034.2  931.33  5039.8  933.34  5048.6  937.28
  5078.6  938.26  5084.2  938.90  5093.6  939.09  5116.0  941.05  5153.6  942.67
#Mann=3,-1,0
  4833.9    0.12       0  4998.7    0.07       0  5003.5    0.12       0
Bank Sta=4998.7,5003.5
Exp/Cntr=0.3,0.1

Chan Stop Cuts=-1