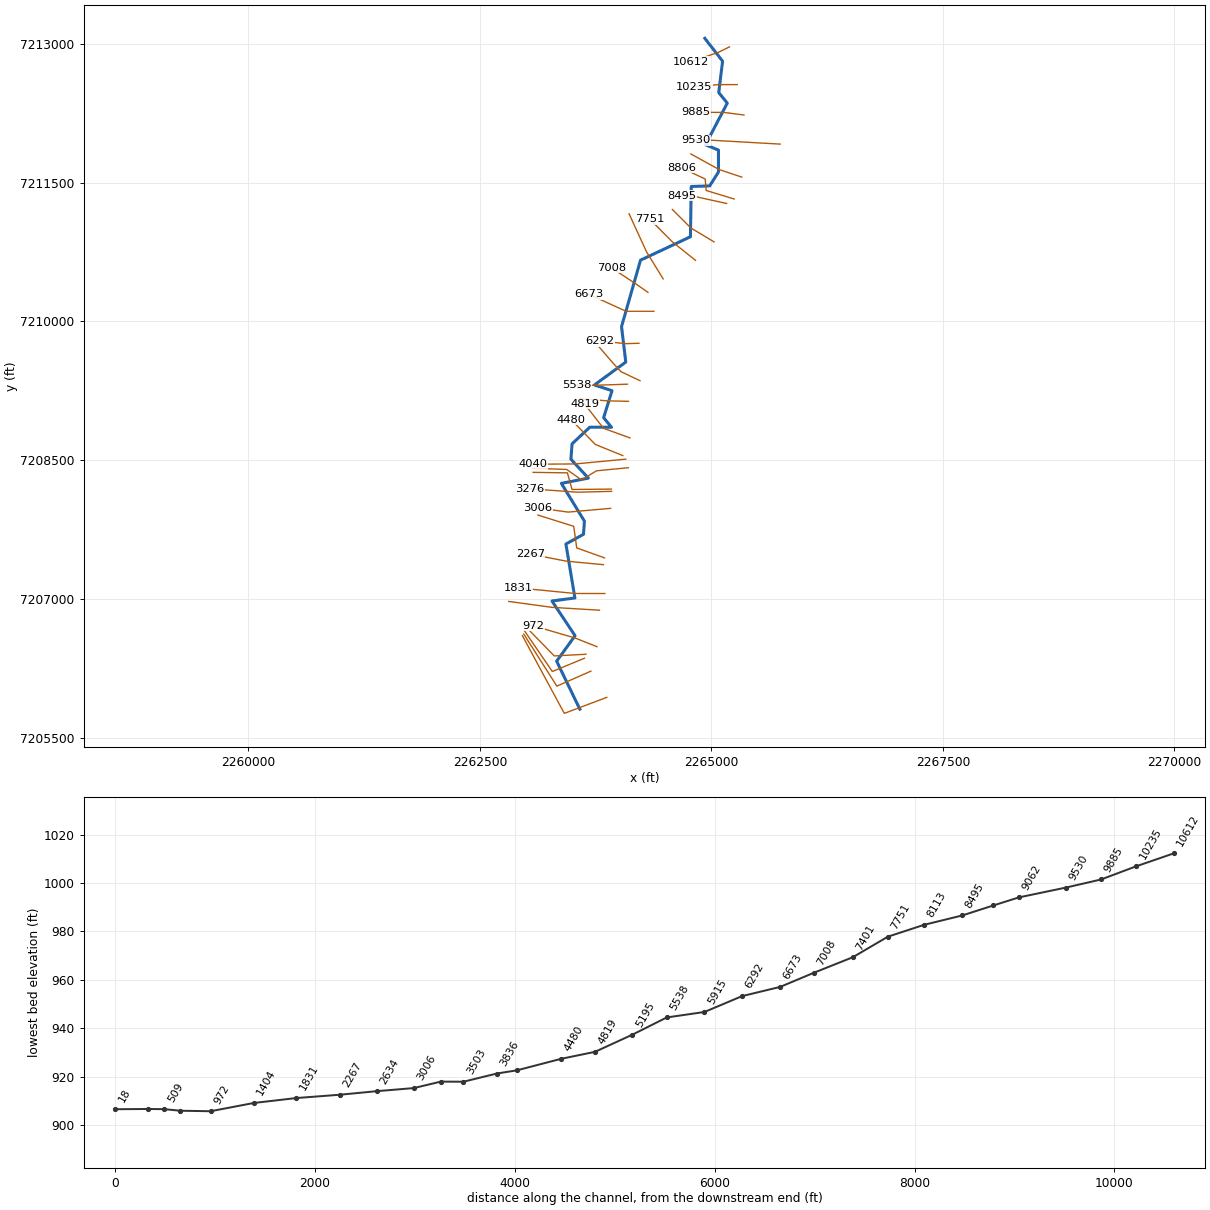
--- UDS St 44.prj (project) ---

Proj Title=UDS St 44 Base Level Engineering
Current Plan=p01
Default Exp/Contr=0.3,0.1
English Units
Geom File=g01
Flow File=f01
Plan File=p01
Y Axis Title=Elevation
X Axis Title(PF)=Main Channel Distance
X Axis Title(XS)=Station
BEGIN DESCRIPTION:
UDS St 44
END DESCRIPTION:
DSS Export Rating Curves= 0
DSS Export Rating Curve Sorted= 0
DSS Export Volume Flow Curves= 0
DXF OffsetX= 0
DXF OffsetY= 0
DXF ScaleX= 1
DXF ScaleY= 10

--- UDS St 44.p01 (plan) ---

Plan Title=Multiple Run
Short Identifier=Multiple
Geom File=g01
Flow File=f01
Subcritical Flow
K Sum by GR= 0
Std Step Tol= 0.01
Critical Tol= 0.01
Num of Std Step Trials= 20
Max Error Tol= 0.3
Flow Tol Ratio= 0.001
Split Flow NTrial= 30
Split Flow Tol= 0.02
Split Flow Ratio= 0.02
Log Output Level= 0
Friction Slope Method= 1
Unsteady Friction Slope Method= 2
Unsteady Bridges Friction Slope Method= 1
Parabolic Critical Depth
Global Vel Dist=  1 , 1 , 1
Global Log Level= 0
CheckData=True
Encroach Param= -1, 0, 0, 0
BEGIN DESCRIPTION:
Multiple Run
END DESCRIPTION:

--- UDS St 44.f01 (steady flow) ---

Flow Title=Multiple
Number of Profiles=7
Profile Names=10-year,25-year,50-year,1pct_min,100-year,1pct_plu,500-year
River Rch & RM= UDS St 44,Reach-1,10612
     683     954    1182     728    1452    2897    2197
River Rch & RM= UDS St 44,Reach-1,4040
     721    1007    1248     768    1532    3056    2315
River Rch & RM= UDS St 44,Reach-1,18
    2061    3008    3836    2419    4826    9629    7668
Boundary for River Rch & Prof#=UDS St 44,Reach-1,1
Up Type=0
Dn Type=3
Dn Slope=0.005
Boundary for River Rch & Prof#=UDS St 44,Reach-1,2
Up Type=0
Dn Type=3
Dn Slope=0.005
Boundary for River Rch & Prof#=UDS St 44,Reach-1,3
Up Type=0
Dn Type=3
Dn Slope=0.005
Boundary for River Rch & Prof#=UDS St 44,Reach-1,4
Up Type=0
Dn Type=3
Dn Slope=0.005
Boundary for River Rch & Prof#=UDS St 44,Reach-1,5
Up Type=0
Dn Type=3
Dn Slope=0.005
Boundary for River Rch & Prof#=UDS St 44,Reach-1,6
Up Type=0
Dn Type=3
Dn Slope=0.005
Boundary for River Rch & Prof#=UDS St 44,Reach-1,7
Up Type=0
Dn Type=3
Dn Slope=0.005

--- UDS St 44.g01 (geometry) ---

Geom Title=Existing Conditions
Program Version=4.10

River Reach=UDS St 44       ,Reach-1
Reach XY= 30
        2264929.        7213060.      2265120.96      7212813.32
      2265079.55      7212473.86       2265171.7      7212360.08
      2264935.99      7211909.75       2265076.3      7211852.13
      2265076.74      7211615.56      2264981.62      7211465.28
      2264782.47      7211458.82      2264773.82      7210915.38
      2264234.69      7210662.39      2264029.51      7209944.78
      2264075.47      7209560.99      2263736.38      7209313.41
      2263926.53       7209251.9      2263836.34       7208959.9
      2263921.51      7208856.38      2263687.15       7208857.5
      2263495.24      7208677.22      2263482.54      7208511.47
      2263671.47      7208306.82      2263379.58      7208250.06
      2263628.81      7207841.72      2263618.68      7207699.83
      2263428.85      7207594.49      2263525.96      7207011.36
      2263278.32      7206978.84      2263527.62      7206603.48
      2263328.81      7206328.43        2263579.        7205810.

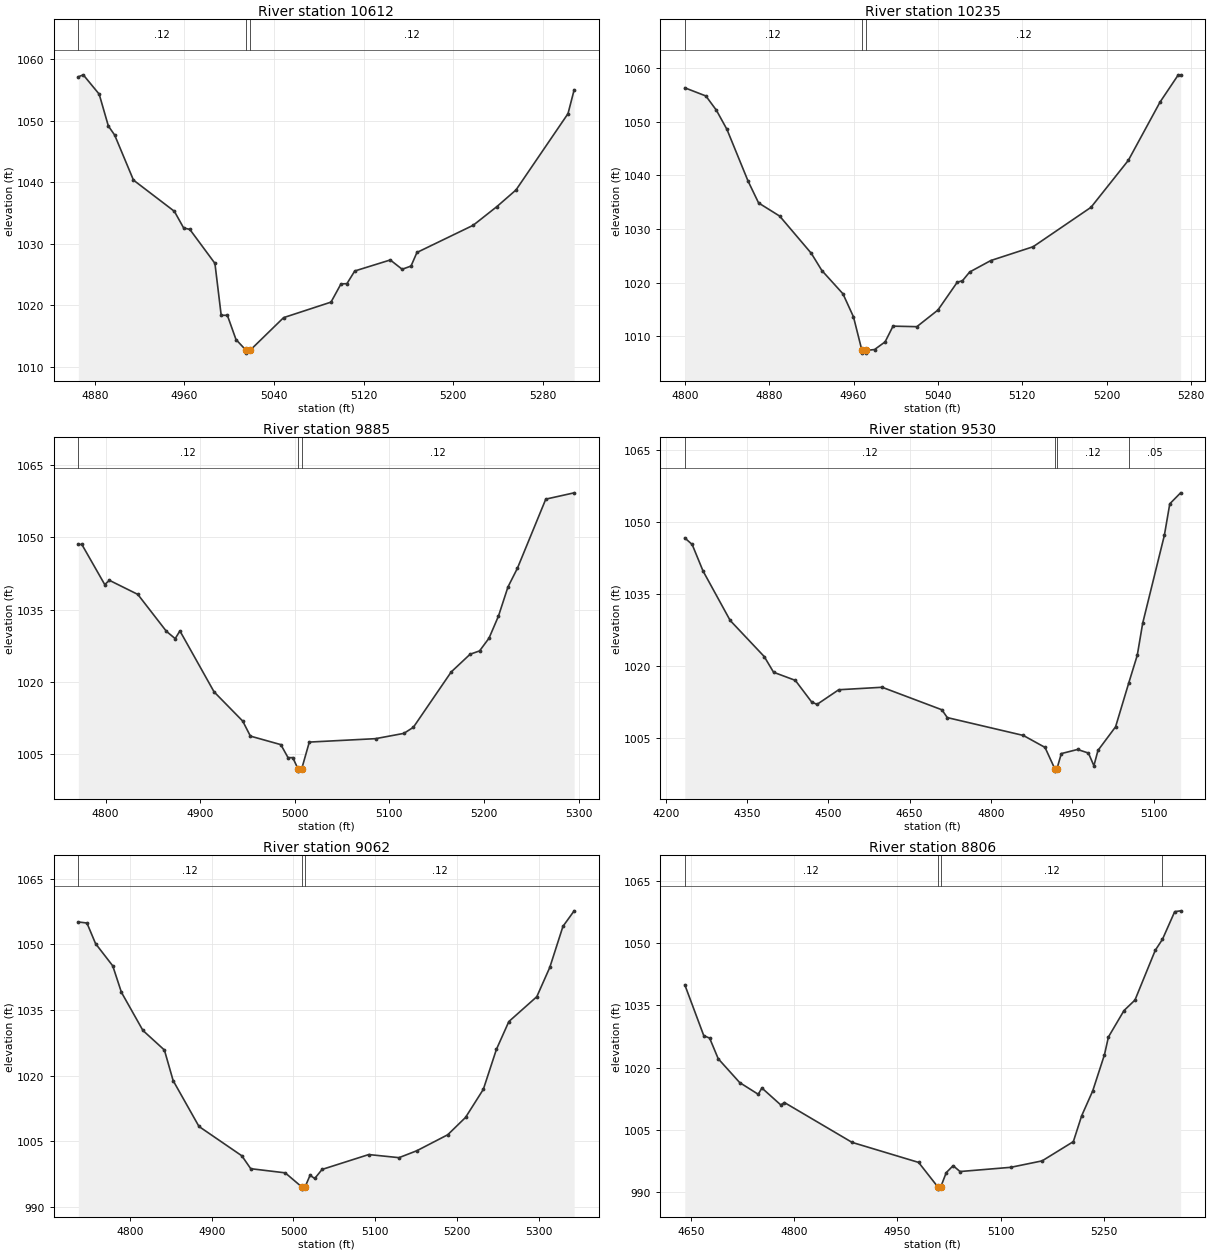
Type RM Length L Ch R = 1 ,10612   ,377,377,377
BEGIN DESCRIPTION:
UDS St 44 26.0
END DESCRIPTION:
XS GIS Cut Line= 3
      2265195.69      7212968.06        2265079.        7212910.
      2264783.79      7212808.51
#Sta/Elev= 30
  4865.4 1057.13  4869.8 1057.45    4884 1054.31  4892.2 1049.13  4897.8 1047.67
  4914.6 1040.34  4951.1 1035.27  4959.4 1032.56  4964.9 1032.33  4987.3 1026.81
  4992.9 1018.37  4998.4 1018.37  5006.1 1014.43  5014.9 1012.72  5015.1 1012.22
  5018.9 1012.72  5048.6 1017.99  5090.9 1020.51  5099.8 1023.47  5105.1 1023.51
  5112.1 1025.57  5143.8 1027.36  5154.4 1025.85  5162.3 1026.37  5167.6 1028.58
  5217.8    1033  5238.9 1036.03    5256 1038.74  5302.4 1051.14  5307.9 1055.01
#Mann= 3 ,-1 , 0
  4865.4     .12       0  5014.9     .07       0  5018.9     .12       0
Bank Sta=5014.9,5018.9
XS Rating Curve= 0 ,0
Exp/Cntr=0.3,0.1

Type RM Length L Ch R = 1 ,10235   ,350,350,350
BEGIN DESCRIPTION:
UDS St 44 25.0
END DESCRIPTION:
XS GIS Cut Line= 3
        2265279.        7212560.        2265079.        7212560.
      2264809.59      7212538.09
#Sta/Elev= 30
  4799.9 1056.32  4819.9  1054.8  4829.9 1052.13  4839.9 1048.56  4859.9 1038.94
  4869.9 1034.86  4889.9 1032.41  4919.9 1025.47  4929.9 1022.27  4949.9 1017.93
  4959.9 1013.63  4967.9 1007.37  4968.2 1006.87  4971.7 1006.87  4971.9 1007.37
  4979.9 1007.54  4989.9 1008.97  4997.4  1011.9    5020  1011.8    5040  1014.9
  5058.3 1020.08  5063.3 1020.37  5070.1 1021.99  5090.2 1024.13  5130.3  1026.7
  5185.2 1034.05  5220.6  1042.8  5250.7 1053.67    5268 1058.74  5270.2 1058.74
#Mann= 3 ,-1 , 0
  4799.9     .12       0  4967.9     .07       0  4971.9     .12       0
Bank Sta=4967.9,4971.9
XS Rating Curve= 0 ,0
Exp/Cntr=0.3,0.1

Type RM Length L Ch R = 1 ,9885    ,355,355,355
BEGIN DESCRIPTION:
UDS St 44 24.0
END DESCRIPTION:
XS GIS Cut Line= 3
      2265351.35      7212231.41        2265129.        7212260.
      2264828.98        7212260.
#Sta/Elev= 30
  4771.1 1048.52  4774.8 1048.52    4799 1040.19    4804 1041.06    4834 1038.14
  4864.2 1030.48  4873.5 1028.96  4878.5 1030.56  4914.6 1017.91  4944.9 1011.84
    4953 1008.72  4985.2 1006.95  4992.8 1004.25  4997.8 1004.25  5003.3 1001.95
  5003.5 1001.45  5007.3 1001.95  5015.3 1007.48  5085.3 1008.19  5115.3 1009.29
  5125.3 1010.55  5165.3 1022.04  5185.3 1025.72  5195.3 1026.41  5205.3 1029.06
  5215.3 1033.65  5225.3 1039.68  5235.3 1043.57  5265.3 1057.92  5295.3 1059.23
#Mann= 3 ,-1 , 0
  4771.1     .12       0  5003.3     .07       0  5007.3     .12       0
Bank Sta=5003.3,5007.3
XS Rating Curve= 0 ,0
Exp/Cntr=0.3,0.1

Type RM Length L Ch R = 1 ,9530    ,468,468,468
BEGIN DESCRIPTION:
UDS St 44 23.0
END DESCRIPTION:
XS GIS Cut Line= 3
      2265742.55      7211916.86        2264979.        7211960.
      2264828.97        7211960.
#Sta/Elev= 30
  4235.1 1046.74  4248.7 1045.37  4268.7 1039.85  4318.8 1029.52  4381.7 1021.98
  4398.9 1018.71    4439 1017.02    4469 1012.53    4479    1012  4519.1 1015.06
  4599.2 1015.58  4709.4 1010.88  4719.4 1009.25  4859.6 1005.53  4899.7 1003.03
  4917.7  998.58    4918  998.08  4921.7  998.58  4929.8 1001.74  4959.8  1002.6
  4979.8 1001.85  4989.9   999.2  4997.4  1002.4  5029.9 1007.33  5053.9 1016.37
  5069.9 1022.25  5079.9 1028.94  5119.9 1047.28  5129.9 1053.86  5149.9 1056.15
#Mann= 4 ,-1 , 0
  4235.1     .12       0  4917.7     .07       0  4921.7     .12       0
  5053.9     .05       0
Bank Sta=4917.7,4921.7
XS Rating Curve= 0 ,0
Exp/Cntr=0.3,0.1

Type RM Length L Ch R = 1 ,9062    ,256,256,256
BEGIN DESCRIPTION:
UDS St 44 22.0
END DESCRIPTION:
XS GIS Cut Line= 3
      2265329.02      7211559.99      2265082.78      7211642.35
      2264779.02      7211809.99
#Sta/Elev= 30
  4736.8 1055.09  4747.3 1054.86  4757.9 1050.14  4778.9 1045.07  4789.5 1039.03
  4815.8 1030.31  4842.1 1025.83  4852.8 1018.84  4884.4 1008.37  4936.8 1001.67
  4947.7  998.72  4989.9  997.77  5010.2  994.55  5010.4  994.05  5014.2  994.55
  5020.3  997.22    5026  996.48    5035  998.55  5092.1 1001.95  5129.1 1001.24
  5150.9 1002.82  5188.7 1006.47  5210.5 1010.43  5232.3 1016.86  5248.3 1025.99
  5263.5 1032.34  5297.7 1038.02  5313.6 1044.72  5329.7 1054.09  5343.4 1057.64
#Mann= 3 ,-1 , 0
  4736.8     .12       0  5010.2     .07       0  5014.2     .12       0
Bank Sta=5010.2,5014.2
XS Rating Curve= 0 ,0
Exp/Cntr=0.3,0.1

Type RM Length L Ch R = 1 ,8806    ,311,311,311
BEGIN DESCRIPTION:
UDS St 44 21.0
END DESCRIPTION:
XS GIS Cut Line= 4
      2265245.43       7211323.5      2264943.35      7211415.95
      2264933.14      7211539.23      2264678.99      7211660.01
#Sta/Elev= 30
  4640.8 1039.96  4668.4  1027.7  4676.9 1027.11  4689.4 1022.14  4720.7 1016.38
  4747.6 1013.57  4752.9 1015.09  4780.4    1011  4785.7 1011.58    4884 1001.98
  4980.8  997.15  5008.9  991.21  5009.2  990.71  5012.9  991.21    5021  994.69
    5031  996.36    5041  994.95  5114.9  995.97  5160.4  997.52  5205.8 1002.16
  5217.9 1008.39    5234  1014.4  5251.1 1023.13  5256.8 1027.38  5279.5 1033.76
  5295.4 1036.28  5324.9 1048.27  5335.4 1050.93  5353.2 1057.59  5361.8 1057.79
#Mann= 4 ,-1 , 0
  4640.8     .12       0  5008.9     .07       0  5012.9     .12       0
  5335.4     .05       0
Bank Sta=5008.9,5012.9
XS Rating Curve= 0 ,0
Exp/Cntr=0.3,0.1

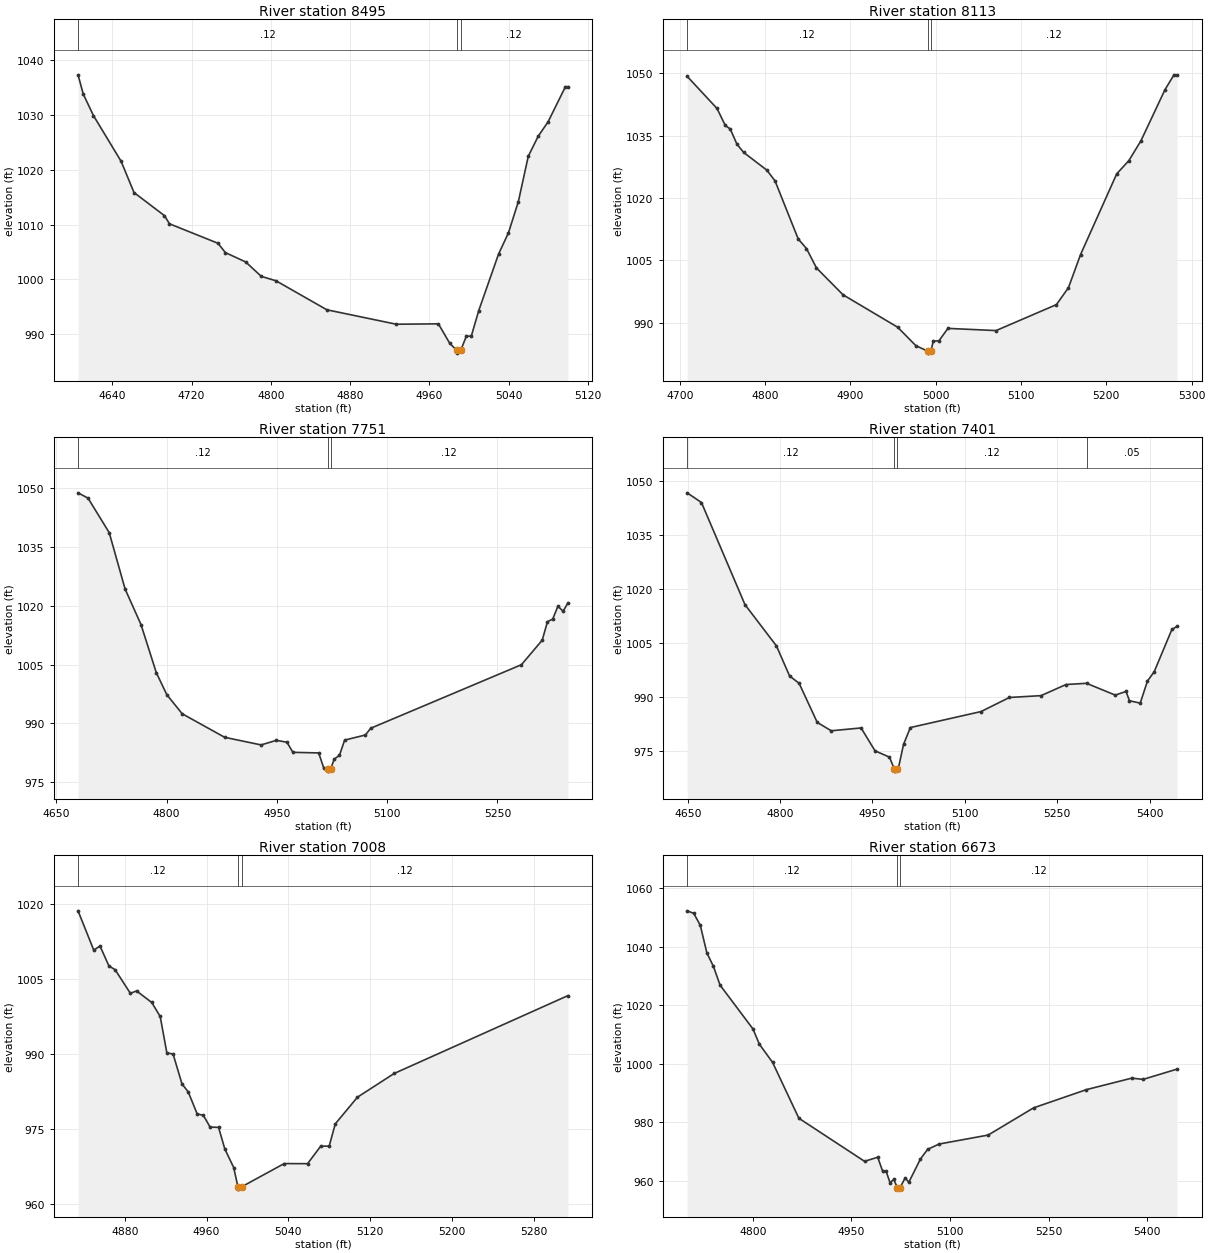
Type RM Length L Ch R = 1 ,8495    ,382,382,382
BEGIN DESCRIPTION:
UDS St 44 20.0
END DESCRIPTION:
XS GIS Cut Line= 3
      2265164.21      7211275.14        2264779.        7211360.
      2264679.04        7211360.
#Sta/Elev= 30
  4605.4 1037.25  4610.7 1033.73    4621 1029.82  4648.9  1021.5  4661.9 1015.82
  4692.6 1011.62  4697.7 1010.13  4746.6 1006.59  4754.1 1004.89  4774.6 1003.19
  4790.3 1000.57  4805.3  999.75  4856.5  994.48  4926.6  991.85  4969.1  991.92
  4980.5  988.39  4987.6  987.09  4987.9  986.59  4991.6  987.09  4997.3  989.68
  5002.3  989.68  5009.8  994.33  5029.8 1004.62  5039.8 1008.49  5049.8 1014.18
  5059.8 1022.43  5069.8 1026.07  5079.8  1028.7  5097.3 1035.09  5099.8 1035.09
#Mann= 3 ,-1 , 0
  4605.4     .12       0  4987.6     .07       0  4991.6     .12       0
Bank Sta=4987.6,4991.6
XS Rating Curve= 0 ,0
Exp/Cntr=0.3,0.1

Type RM Length L Ch R = 1 ,8113    ,362,362,362
BEGIN DESCRIPTION:
UDS St 44 19.0
END DESCRIPTION:
XS GIS Cut Line= 3
      2265028.99      7210860.01        2264779.        7211010.
      2264578.98      7211210.02
#Sta/Elev= 30
  4708.5 1049.26  4743.5 1041.54  4753.2 1037.45    4759 1036.61  4766.8 1032.98
  4774.6    1031  4801.8 1026.73  4811.5 1024.14  4838.7 1010.16  4848.4 1007.87
  4860.1  1003.2  4891.2  996.75  4955.3  988.95  4976.7   984.5  4990.3  983.22
  4990.5  982.72  4994.3  983.22  4997.1  985.65  5003.6  985.65  5014.2  988.67
  5070.7  988.14  5141.5  994.39  5155.6  998.47  5169.7 1006.39  5212.2 1025.84
  5226.3 1028.98  5240.5 1033.75  5268.7 1046.04  5279.3 1049.63  5282.9 1049.63
#Mann= 3 ,-1 , 0
  4708.5     .12       0  4990.3     .07       0  4994.3     .12       0
Bank Sta=4990.3,4994.3
XS Rating Curve= 0 ,0
Exp/Cntr=0.3,0.1

Type RM Length L Ch R = 1 ,7751    ,350,350,350
BEGIN DESCRIPTION:
UDS St 44 18.0
END DESCRIPTION:
XS GIS Cut Line= 3
      2264828.97      7210660.03        2264579.        7210860.
      2264334.79      7211105.08
#Sta/Elev= 30
  4679.7 1048.88  4693.3 1047.52  4722.1 1038.71  4743.7 1024.32  4765.3 1015.25
  4786.1 1002.98  4800.5  997.32  4821.3  992.48    4879  986.47  4928.6  984.52
  4949.4  985.69  4963.8  985.21  4971.8  982.63  5006.9  982.48  5013.9  978.58
    5019  978.33  5019.3  977.83    5023  978.33  5028.1   980.9  5035.2  981.88
  5042.2  985.75  5070.5  987.06  5077.6  988.77  5282.6    1005  5310.9 1011.27
    5318 1015.99  5325.1 1016.64  5332.2 1019.93  5339.2 1018.66  5345.8 1020.74
#Mann= 3 ,-1 , 0
  4679.7     .12       0    5019     .07       0    5023     .12       0
Bank Sta=5019,5023
XS Rating Curve= 0 ,0
Exp/Cntr=0.3,0.1

Type RM Length L Ch R = 1 ,7401    ,393,393,393
BEGIN DESCRIPTION:
UDS St 44 17.0
END DESCRIPTION:
XS GIS Cut Line= 3
        2264479.      7210459.99       2264299.9        7210752.
      2264111.01      7211163.68
#Sta/Elev= 30
  4649.1 1046.82  4672.3 1044.12    4743 1015.69  4794.1  1004.2  4815.4  995.85
  4830.9   993.8  4860.3  982.93    4883  980.59  4931.5  981.38  4954.1  975.02
  4977.6  973.25  4985.7  969.86    4986  969.36  4989.7  969.86  4991.7  969.86
  5000.4  976.78  5011.5  981.49  5126.3  985.94  5172.3  989.86  5223.8  990.37
  5264.3  993.47  5297.6   993.8  5344.3  990.52  5361.8  991.54  5367.3  988.95
  5384.8  988.29  5396.5  994.42  5407.5  997.03  5436.2 1008.79  5444.6 1009.65
#Mann= 4 ,-1 , 0
  4649.1     .12       0  4985.7     .07       0  4989.7     .12       0
  5297.6     .05       0
Bank Sta=4985.7,4989.7
XS Rating Curve= 0 ,0
Exp/Cntr=0.3,0.1

Type RM Length L Ch R = 1 ,7008    ,335,335,335
BEGIN DESCRIPTION:
UDS St 44 16.0
END DESCRIPTION:
XS GIS Cut Line= 3
      2264314.83       7210314.9        2264179.        7210410.
      2263916.78       7210581.8
#Sta/Elev= 30
  4834.2 1018.55  4849.6 1010.68  4855.7 1011.52  4864.4 1007.53  4870.5 1006.77
  4885.4 1002.05  4891.5 1002.53  4906.3 1000.22  4914.6  997.42  4921.1  990.14
  4927.2  989.91  4935.9  983.94    4942  982.34  4950.7  977.97  4956.9  977.62
  4963.4   975.3  4971.7  975.24  4977.8  970.93  4986.5  967.21  4990.6  963.39
  4990.9  962.89  4994.6  963.39  5035.9     968  5058.8  967.98  5071.7   971.5
  5079.9  971.48  5085.9  975.94  5107.6  981.28  5143.5  986.02  5313.5 1001.59
#Mann= 3 ,-1 , 0
  4834.2     .12       0  4990.6     .07       0  4994.6     .12       0
Bank Sta=4990.6,4994.6
XS Rating Curve= 0 ,0
Exp/Cntr=0.3,0.1

Type RM Length L Ch R = 1 ,6673    ,381,381,381
BEGIN DESCRIPTION:
UDS St 44 15.0
END DESCRIPTION:
XS GIS Cut Line= 3
      2264379.01        7210110.        2264079.        7210110.
      2263673.52      7210294.76
#Sta/Elev= 30
    4700 1052.32    4710 1051.46    4720 1047.35    4730 1037.89    4740 1033.31
    4750 1026.92    4800 1011.94    4810 1006.65    4830 1000.45    4870  981.34
    4970   966.6    4990     968  4997.5  963.21  5002.8  963.21  5008.8  959.24
  5014.3  960.41    5020  957.59  5020.2  957.09    5024  957.59  5031.8  960.95
  5037.3  959.42  5054.9  967.35  5065.9  970.68  5083.4  972.52  5158.1  975.59
  5227.2   984.9  5307.7  991.14  5376.5  995.06    5394  994.65  5445.6  998.16
#Mann= 3 ,-1 , 0
    4700     .12       0    5020     .07       0    5024     .12       0
Bank Sta=5020,5024
XS Rating Curve= 0 ,0
Exp/Cntr=0.3,0.1

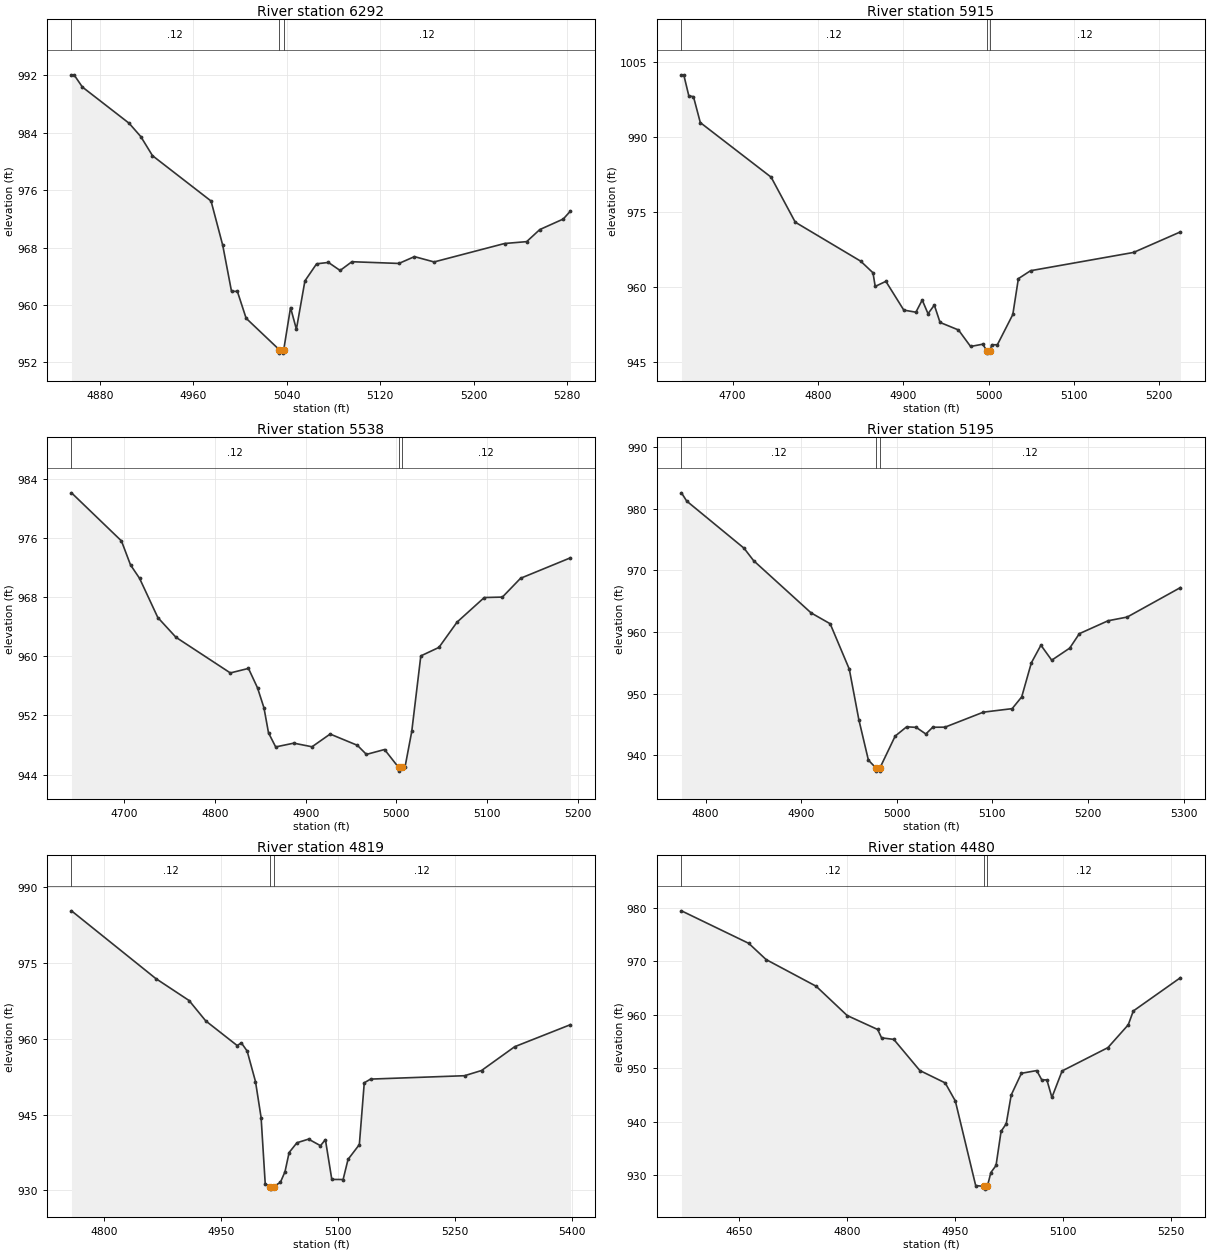
Type RM Length L Ch R = 1 ,6292    ,377,377,377
BEGIN DESCRIPTION:
UDS St 44 14.0
END DESCRIPTION:
XS GIS Cut Line= 3
       2264218.3      7209764.24        2264079.        7209760.
      2263792.86      7209788.32
#Sta/Elev= 30
  4855.8  992.08    4858  992.08  4865.1  990.38  4905.1  985.33  4915.1  983.47
  4925.1  980.81  4975.2  974.49  4985.2  968.31  4992.7   961.9  4997.7   961.9
  5005.2  958.15  5033.4  953.79  5033.6  953.29  5037.1  953.29  5037.4  953.79
  5043.2  959.64  5048.2  956.62  5055.5  963.36  5065.5  965.74  5075.6  965.93
  5085.6  964.81  5095.7  966.03  5135.9  965.79  5149.2  966.74    5166     966
  5226.3  968.57  5245.2  968.83  5256.4  970.51  5276.5  971.98  5282.7   973.1
#Mann= 3 ,-1 , 0
  4855.8     .12       0  5033.4     .07       0  5037.4     .12       0
Bank Sta=5033.4,5037.4
XS Rating Curve= 0 ,0
Exp/Cntr=0.3,0.1

Type RM Length L Ch R = 1 ,5915    ,377,377,377
BEGIN DESCRIPTION:
UDS St 44 13.0
END DESCRIPTION:
XS GIS Cut Line= 4
      2264228.97      7209360.01      2264023.33      7209457.24
        2263929.        7209560.      2263787.01      7209725.35
#Sta/Elev= 30
  4640.1 1002.48  4642.8 1002.48  4648.7  998.29  4654.2  998.09  4662.2  992.91
  4745.2  981.98  4773.5  972.96  4850.2  965.15  4864.6  962.82  4867.2  960.09
  4879.7  961.11  4900.7  955.35  4914.9  954.93  4922.3  957.37  4929.1  954.63
  4936.5  956.35  4943.2  952.88  4964.8  951.37    4979  948.06  4993.2  948.52
    4998  947.23  4998.2  946.73    5002  947.23  5003.7  948.41  5010.4  948.41
  5028.5  954.47    5035  961.65  5049.3  963.24    5170   966.9    5225  971.02
#Mann= 3 ,-1 , 0
  4640.1     .12       0    4998     .07       0    5002     .12       0
Bank Sta=4998,5002
XS Rating Curve= 0 ,0
Exp/Cntr=0.3,0.1

Type RM Length L Ch R = 1 ,5538    ,343,343,343
BEGIN DESCRIPTION:
UDS St 44 12.0
END DESCRIPTION:
XS GIS Cut Line= 3
      2264094.11       7209322.1        2263729.        7209310.
      2263543.94      7209313.56
#Sta/Elev= 30
  4641.6  982.09  4696.7  975.59  4706.7  972.35  4716.7  970.53  4736.8  965.24
  4756.8  962.57  4816.8  957.75  4836.8  958.36  4846.8  955.73  4853.9  953.03
  4858.9  949.66  4866.8  947.75  4886.8  948.26  4906.9  947.77  4926.9  949.49
  4956.9  947.97  4966.9  946.74  4986.9   947.4  5002.4  944.98  5002.7  944.48
  5006.4  944.98  5009.4  944.98  5016.9  949.84  5026.9  960.05  5046.9   961.2
  5066.9  964.62  5096.9  967.94  5116.9     968  5136.9  970.54    5192  973.31
#Mann= 3 ,-1 , 0
  4641.6     .12       0  5002.4     .07       0  5006.4     .12       0
Bank Sta=5002.4,5006.4
XS Rating Curve= 0 ,0
Exp/Cntr=0.3,0.1

Type RM Length L Ch R = 1 ,5195    ,376,376,376
BEGIN DESCRIPTION:
UDS St 44 11.0
END DESCRIPTION:
XS GIS Cut Line= 3
      2264104.52      7209136.91      2263877.98      7209141.75
      2263583.53       7209166.7
#Sta/Elev= 30
  4774.7   982.6  4780.2  981.26  4840.2   973.6  4850.2  971.58  4910.3   963.1
  4930.3  961.33  4950.3  953.96  4960.3  945.75  4970.3  939.17  4978.3  937.89
  4978.5  937.39    4982  937.39  4982.3  937.89  4998.3  943.08  5010.3  944.59
  5020.3   944.5  5030.4  943.42  5037.6  944.52  5050.4  944.53  5090.6  946.97
  5120.7  947.54  5130.7  949.45  5140.8  954.99  5150.8  957.85  5162.1  955.41
  5180.9  957.37    5191  959.72  5221.1  961.82  5241.1  962.42  5296.8  967.21
#Mann= 3 ,-1 , 0
  4774.7     .12       0  4978.3     .07       0  4982.3     .12       0
Bank Sta=4978.3,4982.3
XS Rating Curve= 0 ,0
Exp/Cntr=0.3,0.1

Type RM Length L Ch R = 1 ,4819    ,339,339,339
BEGIN DESCRIPTION:
UDS St 44 10.0
END DESCRIPTION:
XS GIS Cut Line= 3
      2264120.69      7208741.68      2263834.81      7208845.12
      2263628.98      7209110.03
#Sta/Elev= 30
  4758.6  985.31  4866.7  971.91  4909.3  967.57  4930.6  963.55  4970.9  958.67
  4976.3  959.19  4983.7  957.58  4994.4  951.55  5001.6  944.43  5006.9  931.27
  5013.6  930.77  5013.9  930.27  5017.6  930.77  5026.3  931.61  5032.2   933.7
  5037.5  937.51  5047.5  939.44  5062.4  940.16  5077.7  938.86    5084  940.06
  5092.2  932.19  5106.7  932.17    5113  936.15  5127.5  939.08  5133.8   951.3
  5141.9  952.03  5262.3   952.7  5284.1  953.73  5326.6  958.44  5398.1   962.8
#Mann= 3 ,-1 , 0
  4758.6     .12       0  5013.6     .07       0  5017.6     .12       0
Bank Sta=5013.6,5017.6
XS Rating Curve= 0 ,0
Exp/Cntr=0.3,0.1

Type RM Length L Ch R = 1 ,4480    ,440,440,440
BEGIN DESCRIPTION:
UDS St 44 9.0
END DESCRIPTION:
XS GIS Cut Line= 3
      2264042.54      7208550.51      2263745.68      7208671.14
      2263485.57      7208939.27
#Sta/Elev= 30
  4569.3  979.43  4662.9  973.35    4687  970.32  4756.6  965.33  4799.8  959.85
  4842.2  957.24  4847.6  955.68  4864.6  955.39  4900.8  949.57  4936.1  947.25
  4950.2  943.87  4978.5  928.06  4990.7  927.89  4990.9  927.39  4994.7  927.89
  4999.6  930.49  5006.8  931.81  5013.8  938.19    5021  939.62  5027.9  944.99
  5042.1  949.05  5063.4  949.56  5070.4  947.82  5077.5  947.82  5084.5  944.54
  5098.7  949.49  5162.4  953.85  5190.7  958.12  5197.7   960.7  5263.3  966.93
#Mann= 3 ,-1 , 0
  4569.3     .12       0  4990.7     .07       0  4994.7     .12       0
Bank Sta=4990.7,4994.7
XS Rating Curve= 0 ,0
Exp/Cntr=0.3,0.1

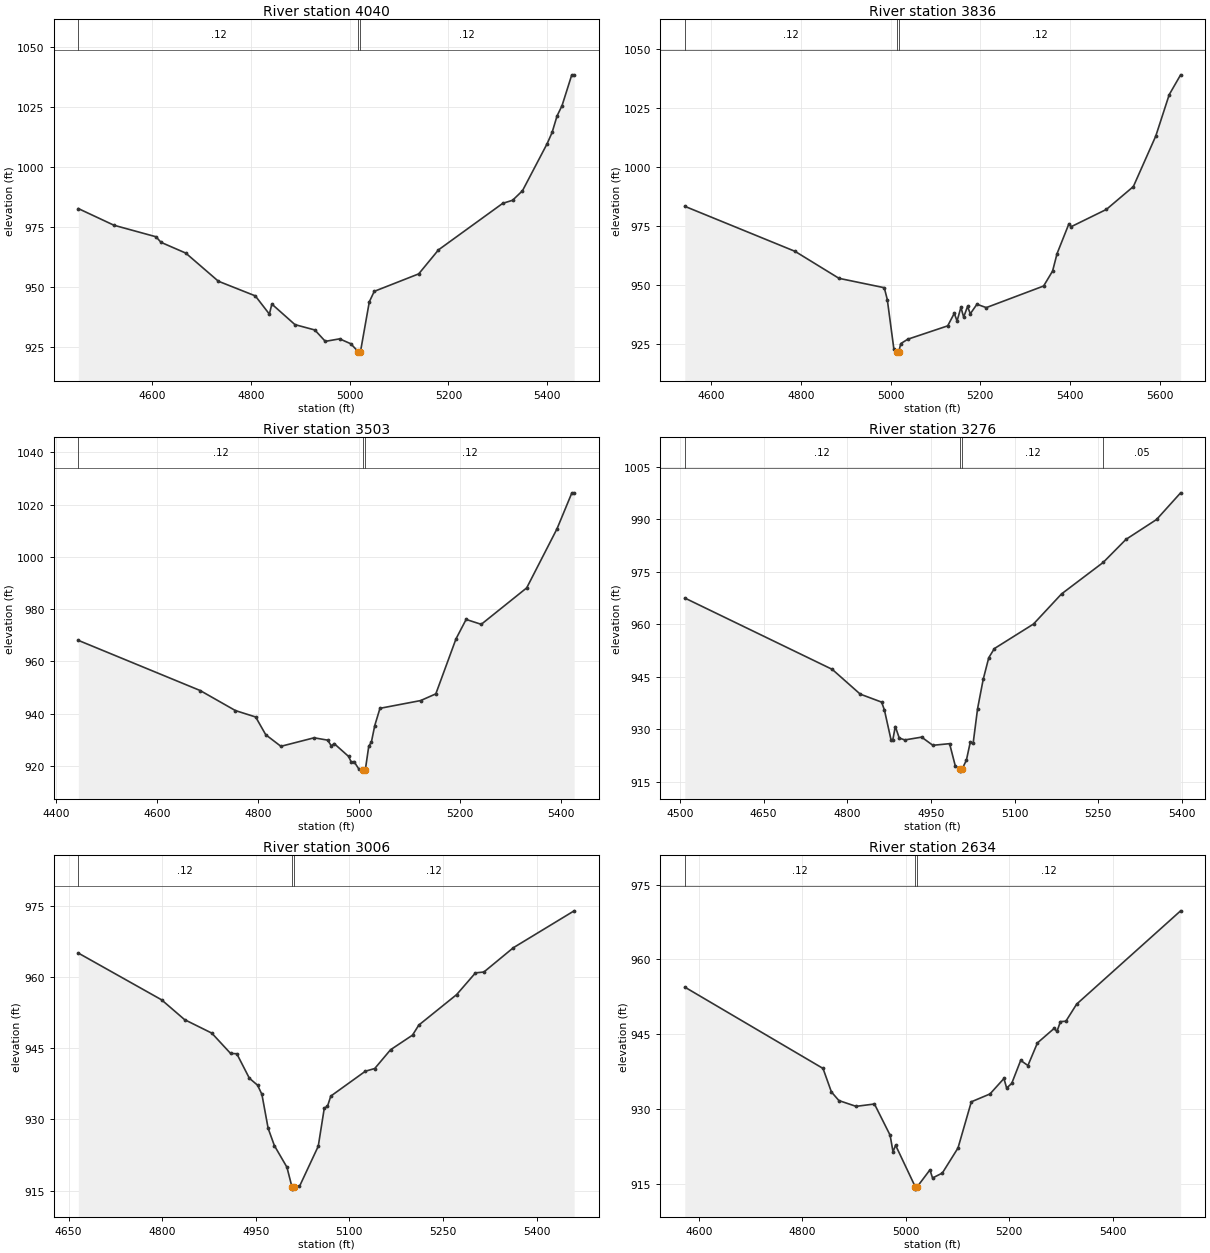
Type RM Length L Ch R = 1 ,4040    ,204,204,204
BEGIN DESCRIPTION:
UDS St 44 8.0
END DESCRIPTION:
XS GIS Cut Line= 3
      2264075.56      7208511.84        2263529.        7208460.
      2263074.43      7208457.17
#Sta/Elev= 30
  4450.9  982.72  4523.1  975.79  4608.2     971  4618.2   968.7  4668.4  964.22
  4734.4  952.53  4809.1  946.45  4837.6  938.87  4842.6  943.04  4889.4   934.5
  4929.6  932.28  4950.8  927.55  4979.8  928.59  5002.4  926.55  5017.9  923.16
  5018.2  922.66  5021.9  923.16  5039.9     944  5049.9  948.33  5139.9  955.59
  5179.9  965.57  5309.9  984.89  5329.9  986.17  5349.9  990.13  5399.9 1009.72
  5409.9 1014.38  5419.9 1021.23  5429.9 1025.45  5449.7 1038.29  5454.5 1038.29
#Mann= 3 ,-1 , 0
  4450.9     .12       0  5017.9     .07       0  5021.9     .12       0
Bank Sta=5017.9,5021.9
XS Rating Curve= 0 ,0
Exp/Cntr=0.3,0.1

Type RM Length L Ch R = 1 ,3836    ,333,333,333
BEGIN DESCRIPTION:
UDS St 44 7.3
END DESCRIPTION:
XS GIS Cut Line= 5
      2264103.53      7208419.48      2263758.65      7208385.67
      2263596.97      7208287.22      2263437.03       7208400.8
      2263063.64      7208413.25
#Sta/Elev= 30
  4541.1  983.39  4786.8  964.36  4884.9  952.94  4985.9  948.97  4992.6  943.98
  5007.2  923.19    5014  921.81  5014.3  921.31    5018  921.81  5022.7  925.33
  5038.2  927.18  5127.3  932.84    5142  938.14  5148.2   934.9  5156.8  940.68
  5162.9  936.53  5171.6  941.05  5177.7  937.95  5192.5  941.97  5213.4  940.56
  5341.2  949.69  5361.2  956.02  5371.2   963.4  5397.7  976.04  5402.7  974.78
  5481.2  982.08  5541.3  991.74  5591.3 1013.11  5621.3 1030.63  5646.7 1038.99
#Mann= 3 ,-1 , 0
  4541.1     .12       0    5014     .07       0    5018     .12       0
Bank Sta=5014,5018
XS Rating Curve= 0 ,0
Exp/Cntr=0.3,0.1

Type RM Length L Ch R = 1 ,3503    ,227,227,227
BEGIN DESCRIPTION:
UDS St 44 7.2
END DESCRIPTION:
XS GIS Cut Line= 4
      2263920.17      7208188.03      2263494.84      7208184.11
      2263445.28      7208363.74        2263075.      7208368.99
#Sta/Elev= 30
  4443.6  968.01  4684.8  948.81  4754.8  941.12  4794.8  938.67  4814.8  931.87
  4844.8  927.44  4910.5   930.7  4937.3  929.81  4944.9  927.55  4950.1  928.51
  4978.8  923.58  4984.4  921.31  4989.6  921.62  4999.5  918.64  5007.9  918.44
  5008.2  917.94    5012  918.44  5018.8  927.47    5024  929.06  5030.7   935.4
    5041  941.99  5121.6  944.96  5151.6  947.52  5191.6  968.59  5211.6  976.02
  5241.6  974.15  5331.6   988.1  5391.6 1010.71  5421.1  1024.5  5425.6  1024.5
#Mann= 3 ,-1 , 0
  4443.6     .12       0  5007.9     .07       0    5012     .12       0
Bank Sta=5007.9,5012
XS Rating Curve= 0 ,0
Exp/Cntr=0.3,0.1

Type RM Length L Ch R = 1 ,3276    ,270,270,270
BEGIN DESCRIPTION:
UDS St 44 7.1
END DESCRIPTION:
XS GIS Cut Line= 3
      2263923.26      7208163.82      2263553.05      7208154.65
      2263036.02      7208192.03
#Sta/Elev= 30
  4508.9  967.52  4773.2   947.1  4823.3  940.02  4861.7  937.73  4866.7  935.47
  4878.7  926.82  4881.6  926.82  4886.2  930.75  4893.3  927.45  4903.3  926.91
  4933.4  927.71  4953.5  925.37  4983.5  925.84  4993.6  919.55  5001.5  918.48
  5001.8  917.98  5005.6  918.48  5013.6   921.1  5020.7  926.36  5025.7  925.91
  5033.7  935.88  5043.7  944.21  5053.7  950.44  5063.8  953.06  5133.9  960.08
  5184.1  968.69  5258.8  977.71  5299.7  984.31  5354.5     990  5397.6  997.63
#Mann= 4 ,-1 , 0
  4508.9     .12       0  5001.5     .07       0  5005.6     .12       0
  5258.8     .05       0
Bank Sta=5001.5,5005.6
XS Rating Curve= 0 ,0
Exp/Cntr=0.3,0.1

Type RM Length L Ch R = 1 ,3006    ,372,372,372
BEGIN DESCRIPTION:
UDS St 44 7.0
END DESCRIPTION:
XS GIS Cut Line= 3
      2263911.92      7207980.16      2263453.54      7207939.58
      2263122.39      7207984.77
#Sta/Elev= 30
  4665.7  965.04  4799.1  955.19    4836  951.01  4879.5  948.18  4909.6   943.9
  4919.6  943.83  4939.7  938.68  4952.9   937.2  4959.8  935.28  4969.8  928.12
  4979.8  924.48  4999.9  919.93  5007.9  915.81  5008.2  915.31    5012  915.81
    5020  915.88  5050.1  924.35  5059.8   932.4  5064.8  932.73  5070.2  934.91
  5125.6  940.15  5140.6  940.72  5165.9  944.67  5201.1  947.75  5211.2  949.87
  5271.8  956.29    5302  960.87  5315.5  961.05  5362.6  966.16  5460.1  973.94
#Mann= 3 ,-1 , 0
  4665.7     .12       0  5007.9     .07       0    5012     .12       0
Bank Sta=5007.9,5012
XS Rating Curve= 0 ,0
Exp/Cntr=0.3,0.1

Type RM Length L Ch R = 1 ,2634    ,367,367,367
BEGIN DESCRIPTION:
UDS St 44 6.0
END DESCRIPTION:
XS GIS Cut Line= 4
      2263845.94      7207444.78      2263545.66      7207552.55
      2263513.03      7207786.01      2263127.16      7207907.15
#Sta/Elev= 30
  4572.5  954.47  4839.9  938.19  4856.1  933.49  4870.6  931.76  4903.8   930.6
  4939.4  931.07  4969.7  924.82  4975.3   921.5  4980.3  922.82  5018.2  914.53
  5018.5  914.03  5022.3  914.53  5046.7  917.88  5051.8  916.26  5070.7  917.25
    5101  922.26  5126.8  931.51  5162.9  933.08  5189.9  936.18  5195.1  934.27
  5204.9  935.18  5222.3   939.8  5236.3  938.77  5254.7   943.3  5287.1  946.21
  5292.4  945.59  5299.2  947.56  5309.7  947.64  5330.6  951.07  5531.7  969.74
#Mann= 3 ,-1 , 0
  4572.5     .12       0  5018.2     .07       0  5022.3     .12       0
Bank Sta=5018.2,5022.3
XS Rating Curve= 0 ,0
Exp/Cntr=0.3,0.1

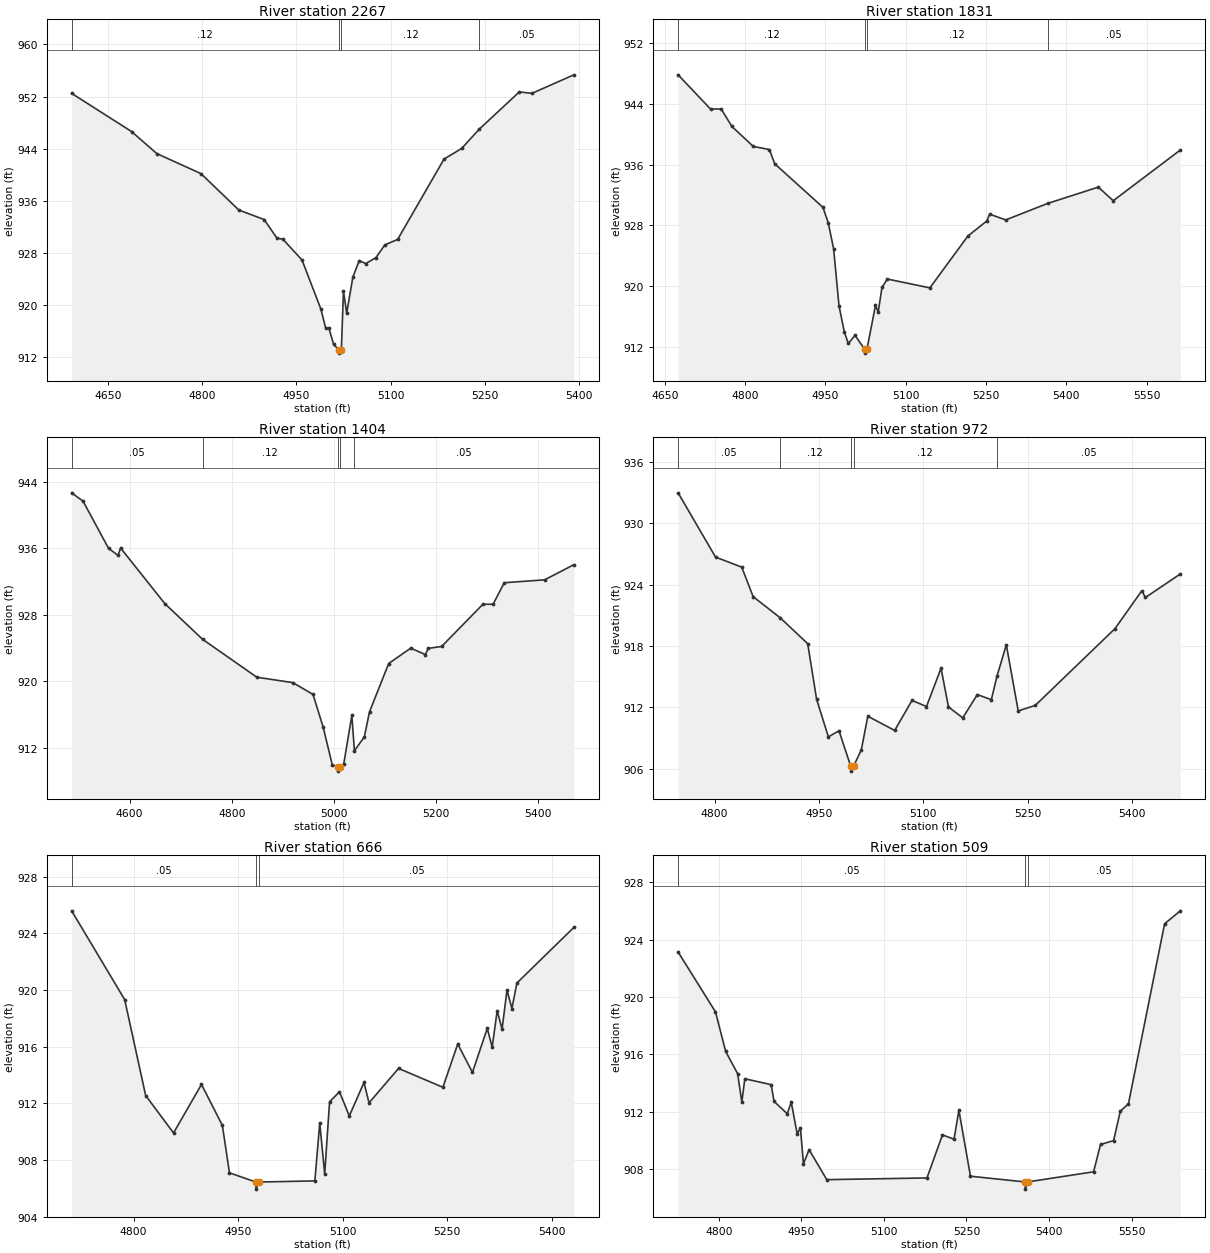
Type RM Length L Ch R = 1 ,2267    ,436,436,436
BEGIN DESCRIPTION:
UDS St 44 5.0
END DESCRIPTION:
XS GIS Cut Line= 3
      2263833.88      7207371.09        2263429.        7207410.
      2263043.77      7207484.96
#Sta/Elev= 30
  4592.4  952.48  4687.7  946.62  4727.9  943.23  4798.2  940.15  4858.5  934.55
  4898.7   933.1  4918.8  930.28  4928.8  930.05    4959  926.88  4989.1  919.32
  4996.6  916.43  5001.7  916.43  5009.3  913.92  5017.5  913.07  5017.8  912.57
  5021.6  913.07    5025  922.09  5030.1  918.71  5039.9  924.24  5050.1  926.79
  5060.3  926.32  5076.6  927.24  5090.8   929.2  5111.2  930.04    5185  942.38
  5213.1  944.02  5241.4  947.01  5304.8   952.7  5325.1  952.49  5391.6  955.33
#Mann= 4 ,-1 , 0
  4592.4     .12       0  5017.5     .07       0  5021.6     .12       0
  5241.4     .05       0
Bank Sta=5017.5,5021.6
XS Rating Curve= 0 ,0
Exp/Cntr=0.3,0.1

Type RM Length L Ch R = 1 ,1831    ,427,427,427
BEGIN DESCRIPTION:
UDS St 44 4.0
END DESCRIPTION:
XS GIS Cut Line= 3
      2263849.49      7207059.55        2263529.        7207060.
      2262914.33      7207120.21
#Sta/Elev= 30
    4675  947.83  4735.5  943.33  4755.5  943.33  4775.5  941.03  4815.5   938.4
  4845.5     938  4855.5  936.12  4945.5  930.39  4955.5  928.33  4965.5  924.93
  4975.5  917.44  4985.5  913.98    4993  912.47  5005.5  913.54  5023.5   911.7
  5023.9   911.2  5027.7   911.7  5043.7  917.48  5048.8  916.61  5055.8  919.84
  5065.8  920.95  5145.3  919.79  5216.5  926.63  5251.8   928.6  5256.9  929.49
  5286.9  928.73  5365.2   930.9  5459.9  933.05  5487.8  931.26  5613.1  937.93
#Mann= 4 ,-1 , 0
    4675     .12       0  5023.5     .07       0  5027.7     .12       0
  5365.2     .05       0
Bank Sta=5023.5,5027.7
XS Rating Curve= 0 ,0
Exp/Cntr=0.3,0.1

Type RM Length L Ch R = 1 ,1404    ,432,432,432
BEGIN DESCRIPTION:
UDS St 44 3.0
END DESCRIPTION:
XS GIS Cut Line= 3
      2263791.24      7206879.36        2263279.        7206910.
      2262812.22      7206973.98
#Sta/Elev= 30
  4486.3  942.65  4508.6  941.65  4558.7  935.96  4577.2  935.13  4582.2  936.01
  4668.9  929.32  4742.8  925.03  4849.2  920.46    4920  919.81  4959.4  918.39
  4979.4  914.42    4997  909.95  5007.5  909.66  5007.8  909.16  5011.7  909.66
  5019.6  910.02  5035.5  915.87  5040.5  911.61    5060  913.28  5070.1   916.3
  5107.7  922.11  5150.9  923.96  5179.8  923.18  5184.9  923.93  5211.4  924.16
  5292.2  929.23  5312.4  929.25  5334.2  931.83  5413.3  932.18  5470.6     934
#Mann= 5 ,-1 , 0
  4486.3     .05       0  4742.8     .12       0  5007.5     .07       0
  5011.7     .12       0  5040.5     .05       0
Bank Sta=5007.5,5011.7
XS Rating Curve= 0 ,0
Exp/Cntr=0.3,0.1

Type RM Length L Ch R = 1 ,972     ,306,306,306
BEGIN DESCRIPTION:
UDS St 44 2.0
END DESCRIPTION:
XS GIS Cut Line= 3
      2263763.98      7206485.18      2263529.05      7206578.25
      2263079.03      7206709.99
#Sta/Elev= 30
  4747.5  932.98  4801.3  926.69  4838.9  925.71  4855.3  922.82  4893.9  920.77
  4933.7  918.22  4946.5  912.78  4963.4   909.1  4978.7   909.7  4995.4  906.25
  4995.7  905.75  4999.7  906.25  5010.7  907.82  5020.1  911.12  5058.7  909.73
  5083.6  912.67  5104.4  912.07  5125.3  915.82    5136  912.03  5156.5  910.96
  5177.4  913.24  5197.6  912.74  5205.6  915.02  5219.1  918.11  5236.2  911.64
  5260.7  912.18  5375.2  919.69  5413.8   923.4    5419  922.74  5469.1  925.04
#Mann= 5 ,-1 , 0
  4747.5     .05       0  4893.9     .12       0  4995.4     .07       0
  4999.7     .12       0  5205.6     .05       0
#XS Ineff= 2 , 0
       0                  5125.3       0  915.82
Permanent Ineff=
       F       F
Bank Sta=4995.4,4999.7
XS Rating Curve= 0 ,0
Exp/Cntr=0.3,0.1

Type RM Length L Ch R = 1 ,666     ,157,157,157
BEGIN DESCRIPTION:
UDS St 44 1.1
END DESCRIPTION:
XS GIS Cut Line= 3
      2263645.03      7206403.26      2263303.07      7206384.96
      2263039.15      7206655.77
#Sta/Elev= 30
  4711.2  925.58  4787.3  919.32  4817.4  912.56  4857.4  909.92  4897.5  913.34
  4927.5  910.45  4937.6  907.11  4975.5  906.46  4975.8  905.96  4979.8  906.46
  5060.2  906.54  5067.2  910.63  5074.3  907.02  5081.3  912.12  5095.5  912.82
  5109.6  911.12  5130.7  913.48  5137.9  912.04  5180.3  914.47  5243.9  913.14
  5265.2  916.19  5286.3  914.19  5307.6  917.29  5314.6  915.96  5321.8  918.54
  5328.8  917.24  5335.9     920  5342.9  918.69  5350.1  920.49  5431.8  924.41
#Mann= 3 ,-1 , 0
  4711.2     .05       0  4975.5    .033       0  4979.8     .05       0
Bank Sta=4975.5,4979.8
XS Rating Curve= 0 ,0
Exp/Cntr=0.3,0.1

Type RM Length L Ch R = 1 ,509     ,168,168,168
BEGIN DESCRIPTION:
UDS St 44 1.0
END DESCRIPTION:
XS GIS Cut Line= 3
      2263629.01        7206360.      2263281.94      7206216.67
      2262978.97      7206660.04
#Sta/Elev= 30
    4726  923.13  4793.9  918.96  4812.4   916.2  4834.2  914.65  4841.8  912.67
  4847.2   914.3    4895  913.89  4900.4  912.72  4924.3  911.86  4931.6  912.66
  4942.4  910.45  4948.2  910.89  4953.7  908.37    4964  909.36  4996.1  907.27
  5178.2  907.39  5206.3  910.39  5227.3  910.09  5236.2   912.1  5257.2  907.51
  5356.6  907.11    5357  906.61  5360.9  907.11    5481  907.82  5493.5  909.72
  5517.3  909.99  5529.4  912.03  5544.3  912.56    5610   925.1  5638.5     926
#Mann= 3 ,-1 , 0
    4726     .05       0  5356.6    .033       0  5360.9     .05       0
Bank Sta=5356.6,5360.9
XS Rating Curve= 0 ,0
Exp/Cntr=0.3,0.1

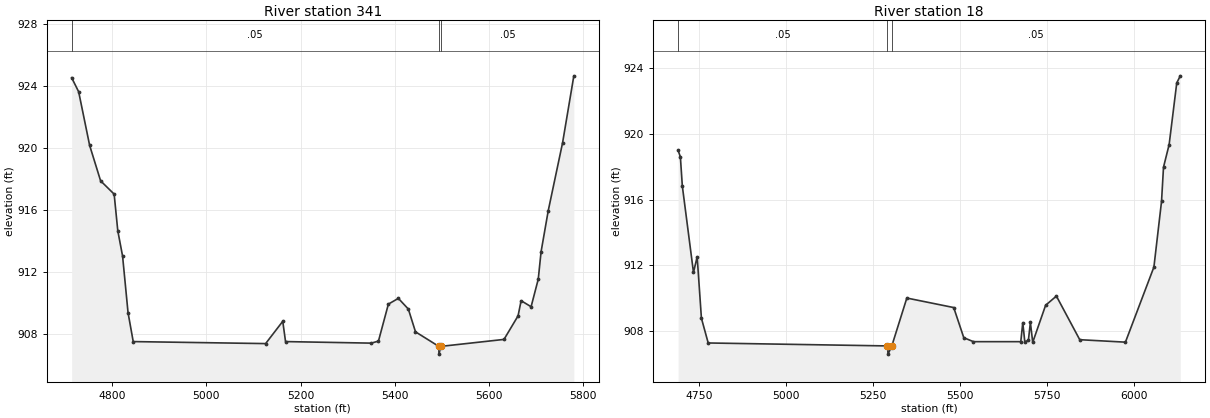
Type RM Length L Ch R = 1 ,341     ,323,323,323
BEGIN DESCRIPTION:
UDS St 44 0.9
END DESCRIPTION:
XS GIS Cut Line= 3
      2263698.66      7206220.53      2263331.13      7206058.57
      2262974.26      7206620.01
#Sta/Elev= 30
  4713.8  924.53  4728.7  923.62    4752  920.16  4775.3  917.87  4804.1  917.01
  4811.8  914.65    4822  913.01  4833.6  909.36  4844.6  907.49  5125.9  907.36
  5162.3   908.8  5168.2  907.49  5350.3  907.39  5365.6  907.52  5386.7  909.91
  5407.9  910.28  5429.1  909.59  5444.3  908.12  5493.8  907.18  5494.2  906.68
  5498.1  907.18  5632.3  907.63  5662.2  909.15  5668.7  910.13  5689.9  909.74
  5705.1  911.52  5711.1  913.29  5726.3  915.94  5756.8  920.33  5780.7  924.65
#Mann= 3 ,-1 , 0
  4713.8     .05       0  5493.8    .033       0  5498.1     .05       0
Bank Sta=5493.8,5498.1
XS Rating Curve= 0 ,0
Exp/Cntr=0.3,0.1

Type RM Length L Ch R = 1 ,18      ,0,0,0
BEGIN DESCRIPTION:
UDS St 44 0.8
END DESCRIPTION:
XS GIS Cut Line= 3
      2263870.32      7205937.24      2263411.32      7205764.18
      2262958.99      7206603.63
#Sta/Elev= 30
  4689.1     919  4695.6  918.61  4701.2  916.83  4733.3  911.56  4743.9  912.52
  4756.1  908.77  4775.6  907.26  5291.1  907.08  5292.8  906.58  5303.6  907.08
  5346.8     910  5481.6  909.42  5510.6  907.58  5538.4  907.34  5674.5  907.34
  5680.2   908.5  5686.1  907.32  5696.4  907.43  5702.1  908.51  5708.8   907.3
  5745.9  909.56  5776.9  910.12    5844  907.46  5975.4  907.31  6057.3  911.89
  6079.2  915.89  6084.9  917.98  6101.1  919.36    6123  923.12  6133.2  923.55
#Mann= 3 ,-1 , 0
  4689.1     .05       0  5291.1    .033       0  5303.6     .05       0
Bank Sta=5291.1,5303.6
XS Rating Curve= 0 ,0
Exp/Cntr=0.3,0.1

Chan Stop Cuts=-1
Use User Specified Reach Order=0
Composite Channel Slope=5