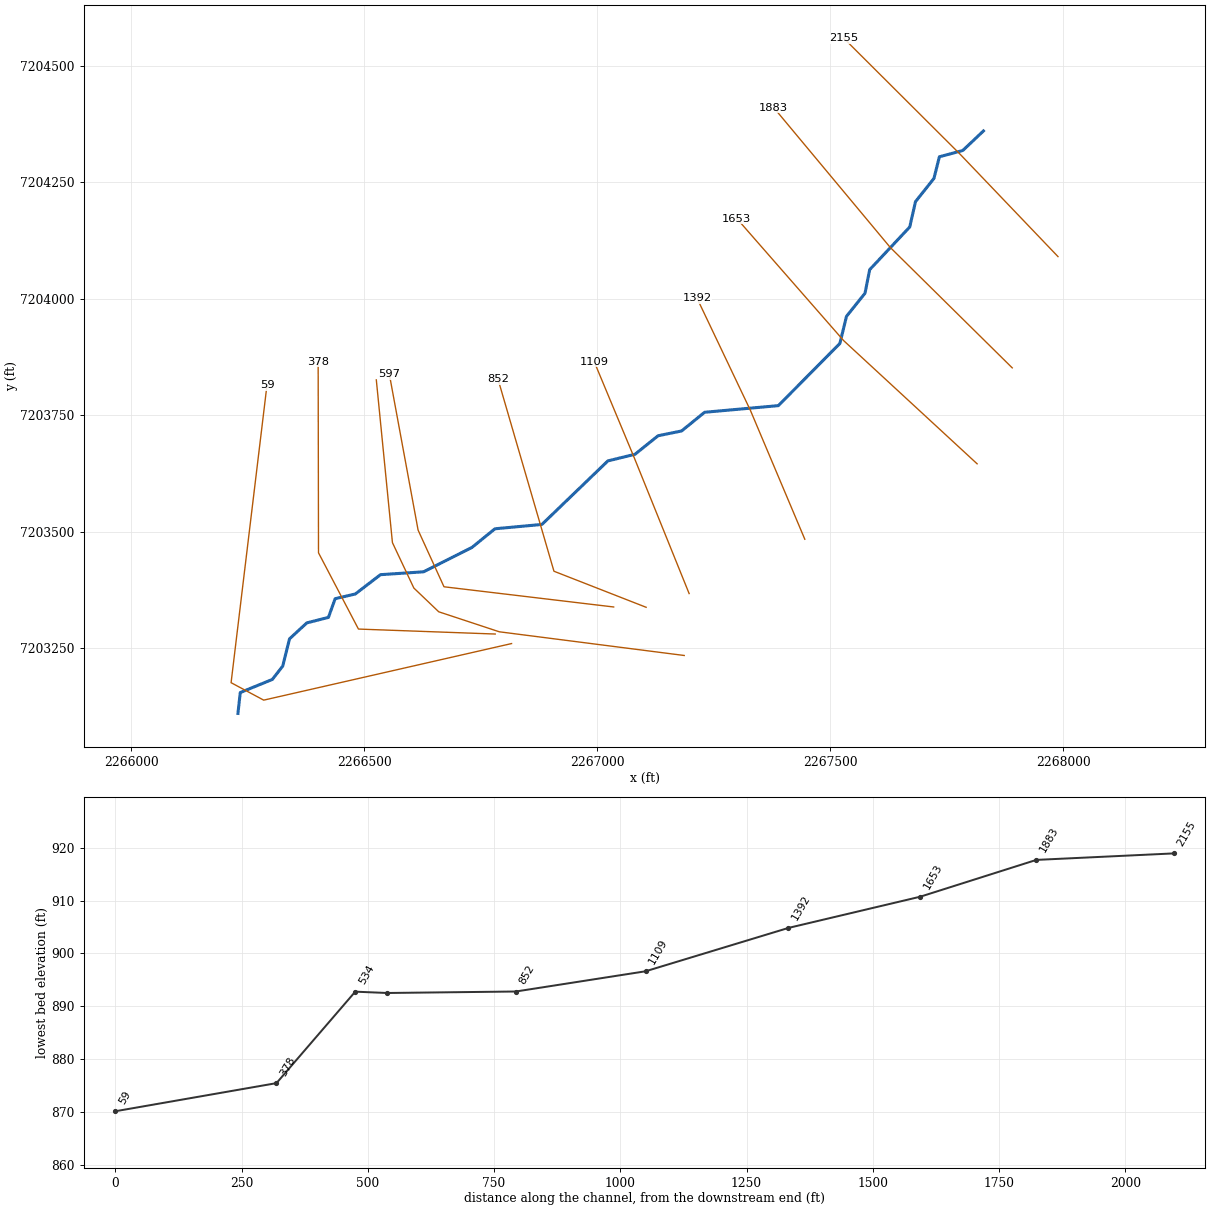
--- UDS St 46.prj (project) ---

Proj Title=UDS St 46 Base Level Engineering
Current Plan=p01
Default Exp/Contr=0.3,0.1
English Units
Geom File=g01
Flow File=f01
Plan File=p01
BEGIN DESCRIPTION:
UDS St 46
END DESCRIPTION:

--- UDS St 46.p01 (plan) ---

Plan Title=Multiple Run
Short Identifier=Multiple
Geom File=g01
Flow File=f01
Subcritical Flow
K Sum by GR= 0
Std Step Tol= 0.01
Critical Tol= 0.01
Num of Std Step Trials= 20
Max Error Tol= 0.3
Flow Tol Ratio= 0.001
Split Flow NTrial= 30
Split Flow Tol= 0.02
Split Flow Ratio= 0.02
Log Output Level= 0
Friction Slope Method= 1
Unsteady Friction Slope Method= 2
Unsteady Bridges Friction Slope Method= 1
Parabolic Critical Depth
Global Vel Dist=  1 , 1 , 1
Global Log Level= 0
CheckData=True
Encroach Param= -1, 0, 0, 0
BEGIN DESCRIPTION:
Multiple Run
END DESCRIPTION:

--- UDS St 46.f01 (steady flow) ---

Flow Title=Multiple
Number of Profiles=7
Profile Names=10-year,25-year,50-year,1pct_min,100-year,1pct_plu,500-year
River Rch & RM= UDS St 46,Reach-1,2155
     291     387     465     279     557    1111     797
Boundary for River Rch & Prof#=UDS St 46,Reach-1,1
Up Type=0
Dn Type=3
Dn Slope=0.005
Boundary for River Rch & Prof#=UDS St 46,Reach-1,2
Up Type=0
Dn Type=3
Dn Slope=0.005
Boundary for River Rch & Prof#=UDS St 46,Reach-1,3
Up Type=0
Dn Type=3
Dn Slope=0.005
Boundary for River Rch & Prof#=UDS St 46,Reach-1,4
Up Type=0
Dn Type=3
Dn Slope=0.005
Boundary for River Rch & Prof#=UDS St 46,Reach-1,5
Up Type=0
Dn Type=3
Dn Slope=0.005
Boundary for River Rch & Prof#=UDS St 46,Reach-1,6
Up Type=0
Dn Type=3
Dn Slope=0.005
Boundary for River Rch & Prof#=UDS St 46,Reach-1,7
Up Type=0
Dn Type=3
Dn Slope=0.005

--- UDS St 46.g01 (geometry) ---

Geom Title=Existing Conditions

River Reach=UDS St 46,Reach-1
Reach XY= 30
      2267829.00      7204360.00      2267784.70      7204318.12
      2267734.48      7204304.58      2267722.78      7204258.14
      2267683.18      7204208.29      2267670.84      7204153.95
      2267584.85      7204062.29      2267574.81      7204011.73
      2267535.10      7203962.19      2267520.86      7203903.94
      2267388.80      7203770.48      2267230.56      7203756.24
      2267181.18      7203716.12      2267130.72      7203705.84
      2267081.19      7203666.10      2267022.94      7203651.86
      2266881.43      7203515.52      2266780.59      7203506.17
      2266731.18      7203466.11      2266627.41      7203413.83
      2266534.94      7203407.68      2266480.86      7203366.22
      2266437.62      7203356.16      2266423.20      7203316.00
      2266376.77      7203304.17      2266339.70      7203269.97
      2266325.09      7203211.47      2266302.78      7203182.86
      2266233.96      7203154.66      2266229.00      7203110.00

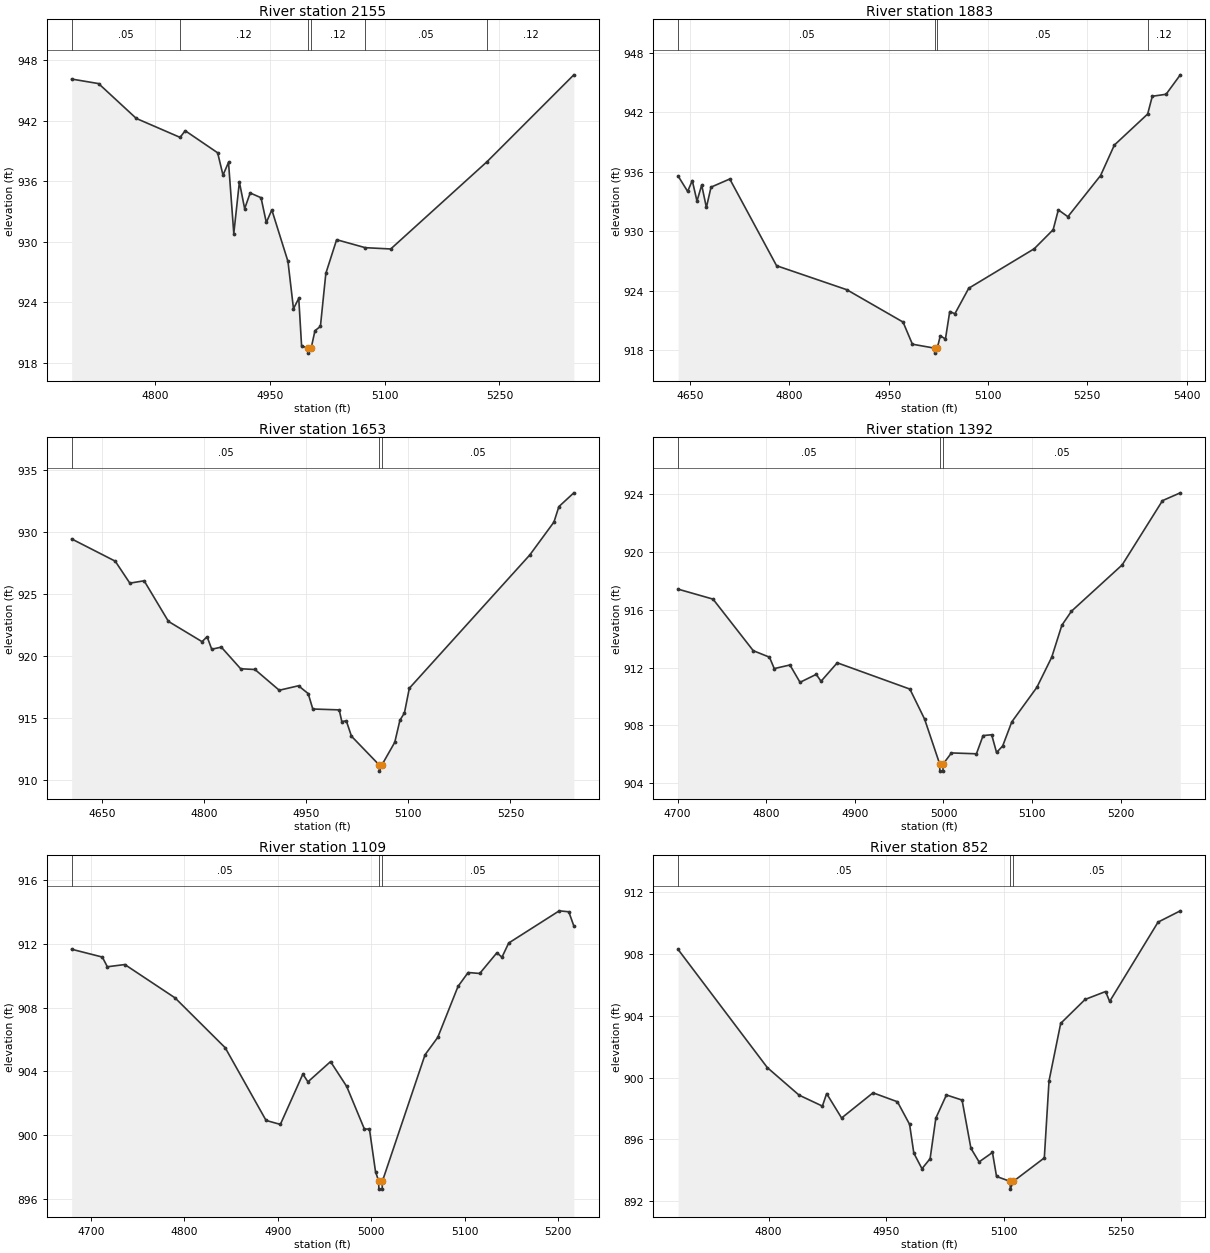
Type RM Length L Ch R = 1,2155,272,272,272
BEGIN DESCRIPTION:
UDS St 46 6.0
END DESCRIPTION:
XS GIS Cut Line= 3
      2267989.02      7204090.33      2267779.00      7204310.00
      2267529.44      7204558.80
#Sta/Elev= 30
  4690.9  946.15  4726.1  945.70  4775.4  942.24  4832.6  940.36  4839.3  941.02
  4881.7  938.83  4888.7  936.61  4895.9  937.88  4902.8  930.81  4910.1  935.93
  4917.0  933.28  4924.2  934.84  4938.4  934.37  4945.3  931.91  4952.5  933.16
  4973.6  928.04  4980.8  923.35  4987.7  924.38  4991.4  919.65  4999.9  919.44
  5000.1  918.94  5003.9  919.44  5008.9  921.17  5016.0  921.59  5023.1  926.86
  5037.2  930.20  5074.6  929.41  5107.9  929.28  5233.8  937.95  5347.2  946.57
#Mann=6,-1,0
  4690.9    0.05       0  4832.6    0.12       0  4999.9    0.07       0
  5003.9    0.12       0  5074.6    0.05       0  5233.8    0.12       0
Bank Sta=4999.9,5003.9
Exp/Cntr=0.3,0.1

Type RM Length L Ch R = 1,1883,230,230,230
BEGIN DESCRIPTION:
UDS St 46 5.0
END DESCRIPTION:
XS GIS Cut Line= 3
      2267890.82      7203851.53      2267629.00      7204110.00
      2267379.02      7204409.98
#Sta/Elev= 30
  4632.1  935.56  4646.5  934.01  4653.5  935.10  4660.6  933.03  4667.7  934.65
  4674.8  932.39  4681.8  934.44  4710.1  935.26  4780.8  926.52  4886.9  924.10
  4971.8  920.84  4985.9  918.61  5019.5  918.21  5019.7  917.71  5023.5  918.21
  5028.0  919.46  5035.8  919.13  5042.3  921.90  5050.1  921.68  5071.0  924.25
  5169.9  928.23  5198.5  930.15  5206.3  932.15  5220.7  931.46  5270.1  935.61
  5290.9  938.68  5341.2  941.81  5348.2  943.60  5369.0  943.80  5390.5  945.76
#Mann=4,-1,0
  4632.1    0.05       0  5019.5   0.033       0  5023.5    0.05       0
  5341.2    0.12       0
Bank Sta=5019.5,5023.5
Exp/Cntr=0.3,0.1

Type RM Length L Ch R = 1,1653,261,261,261
BEGIN DESCRIPTION:
UDS St 46 4.0
END DESCRIPTION:
XS GIS Cut Line= 3
      2267815.41      7203645.64      2267529.00      7203910.00
      2267299.84      7204171.94
#Sta/Elev= 30
  4605.3  929.43  4669.3  927.64  4690.8  925.87  4711.8  926.06  4747.5  922.79
  4796.9  921.16  4804.3  921.56  4811.1  920.55  4825.2  920.72  4853.6  918.98
  4874.6  918.92  4910.3  917.25  4938.6  917.61  4952.8  916.98  4959.6  915.74
  4998.4  915.67  5002.2  914.73  5008.8  914.79  5016.4  913.55  5057.1  911.24
  5057.4  910.74  5061.1  911.24  5080.0  913.06  5087.6  914.84  5094.2  915.42
  5101.4  917.41  5278.4  928.14  5313.9  930.79  5321.1  932.03  5343.1  933.14
#Mann=3,-1,0
  4605.3    0.05       0  5057.1   0.033       0  5061.1    0.05       0
Bank Sta=5057.1,5061.1
Exp/Cntr=0.3,0.1

Type RM Length L Ch R = 1,1392,283,283,283
BEGIN DESCRIPTION:
UDS St 46 3.0
END DESCRIPTION:
XS GIS Cut Line= 3
      2267445.62      7203483.71      2267329.00      7203760.00
      2267214.31      7204001.01
#Sta/Elev= 30
  4700.5  917.43  4739.9  916.74  4785.3  913.17  4803.6  912.72  4809.0  911.93
  4826.7  912.18  4838.1  910.98  4856.4  911.53  4861.8  911.05  4880.1  912.33
  4962.1  910.51  4978.7  908.43  4995.7  905.33  4995.9  904.83  4999.4  904.83
  4999.7  905.33  5009.0  906.09  5037.2  906.03  5044.7  907.29  5054.4  907.35
  5059.9  906.12  5066.8  906.57  5077.1  908.24  5105.4  910.63  5122.2  912.72
  5133.6  914.93  5144.4  915.90  5201.7  919.11  5247.2  923.56  5267.3  924.10
#Mann=3,-1,0
  4700.5    0.05       0  4995.7   0.033       0  4999.7    0.05       0
Bank Sta=4995.7,4999.7
Exp/Cntr=0.3,0.1

Type RM Length L Ch R = 1,1109,257,257,257
BEGIN DESCRIPTION:
UDS St 46 2.0
END DESCRIPTION:
XS GIS Cut Line= 3
      2267197.33      7203367.14      2267079.00      7203660.00
      2266993.77      7203864.37
#Sta/Elev= 30
  4679.6  911.67  4712.4  911.18  4717.8  910.57  4736.5  910.71  4790.2  908.62
  4843.9  905.49  4887.6  900.93  4902.9  900.68  4927.0  903.84  4932.4  903.35
  4956.6  904.62  4973.9  903.06  4992.8  900.39  4998.2  900.39  5004.7  897.72
  5008.1  897.12  5008.3  896.62  5011.8  896.62  5012.1  897.12  5057.7  905.05
  5071.3  906.14  5093.0  909.34  5103.8  910.21  5116.2  910.15  5134.6  911.45
  5140.0  911.17  5147.2  912.06  5201.3  914.08  5211.5  914.02  5216.9  913.13
#Mann=3,-1,0
  4679.6    0.05       0  5008.1   0.033       0  5012.1    0.05       0
Bank Sta=5008.1,5012.1
Exp/Cntr=0.3,0.1

Type RM Length L Ch R = 1,852,255,255,255
BEGIN DESCRIPTION:
UDS St 46 1.0
END DESCRIPTION:
XS GIS Cut Line= 3
      2267105.04      7203337.70      2266907.22      7203415.07
      2266787.32      7203826.65
#Sta/Elev= 30
  4684.5  908.29  4798.4  900.65  4838.9  898.87  4868.7  898.16  4874.1  898.97
  4893.2  897.39  4933.3  899.02  4964.5  898.44  4980.0  896.98  4985.4  895.12
  4995.8  894.11  5006.2  894.76  5013.5  897.38  5027.0  898.88  5047.0  898.55
  5058.3  895.43  5068.7  894.55  5085.8  895.16  5091.0  893.61  5108.4  893.29
  5108.6  892.79  5112.4  893.29  5152.0  894.81  5158.0  899.79  5172.9  903.51
  5204.1  905.06  5230.2  905.57  5235.4  904.93  5297.2  910.06  5325.6  910.79
#Mann=3,-1,0
  4684.5    0.05       0  5108.4   0.033       0  5112.4    0.05       0
Bank Sta=5108.4,5112.4
Exp/Cntr=0.3,0.1

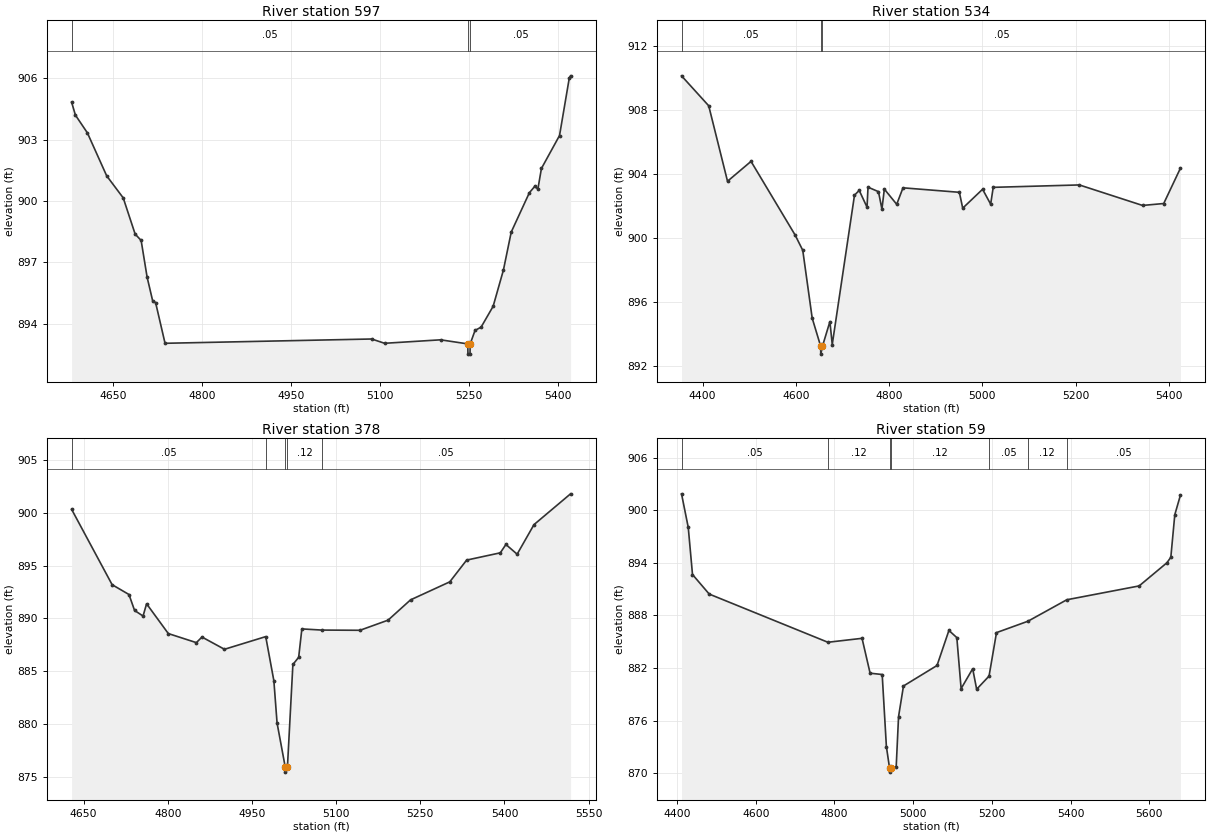
Type RM Length L Ch R = 1,597,63,63,63
BEGIN DESCRIPTION:
UDS St 46 0.9
END DESCRIPTION:
XS GIS Cut Line= 4
      2267035.38      7203338.34      2266671.22      7203381.71
      2266615.65      7203503.27      2266553.85      7203838.33
#Sta/Elev= 30
  4580.0  904.83  4586.4  904.20  4606.6  903.33  4639.1  901.23  4667.0  900.15
  4687.1  898.38  4697.2  898.07  4707.3  896.27  4716.6  895.12  4721.6  895.03
  4737.5  893.04  5085.8  893.25  5107.6  893.04  5202.0  893.21  5247.9  893.01
  5248.1  892.51  5251.6  892.51  5251.9  893.01  5260.1  893.67  5270.3  893.83
  5290.6  894.85  5307.9  896.62  5321.1  898.48  5351.6  900.40  5360.9  900.72
  5366.0  900.58  5372.0  901.59  5402.5  903.20  5419.0  906.02  5421.1  906.12
#Mann=3,-1,0
  4580.0    0.05       0  5247.9   0.033       0  5251.9    0.05       0
Bank Sta=5247.9,5251.9
Exp/Cntr=0.3,0.1

Type RM Length L Ch R = 1,534,156,156,156
BEGIN DESCRIPTION:
UDS St 46 0.8
END DESCRIPTION:
XS GIS Cut Line= 6
      2267186.81      7203234.24      2266789.93      7203285.09
      2266659.94      7203328.03      2266606.47      7203379.05
      2266560.56      7203476.46      2266525.96      7203825.73
#Sta/Elev= 30
  4355.0  910.13  4413.3  908.26  4453.6  903.55  4504.0  904.79  4598.4  900.20
  4614.9  899.24  4635.1  895.01  4653.2  893.26  4653.5  892.76  4657.2  893.26
  4673.1  894.79  4678.1  893.36  4725.8  902.68  4735.9  902.98  4752.7  901.93
  4754.8  903.18  4777.2  902.90  4784.6  901.81  4789.8  903.06  4816.3  902.11
  4829.8  903.14  4950.6  902.86  4957.8  901.87  5000.4  903.05  5017.7  902.12
  5023.2  903.17  5207.8  903.32  5343.3  902.04  5388.7  902.16  5424.6  904.37
#Mann=3,-1,0
  4355.0    0.05       0  4653.2   0.033       0  4657.2    0.05       0
Bank Sta=4653.2,4657.2
Exp/Cntr=0.3,0.1

Type RM Length L Ch R = 1,378,319,319,319
BEGIN DESCRIPTION:
UDS St 46 0.7
END DESCRIPTION:
XS GIS Cut Line= 4
      2266781.18      7203280.28      2266487.61      7203290.95
      2266401.88      7203454.65      2266401.14      7203865.20
#Sta/Elev= 30
  4628.7  900.34  4700.9  893.20  4730.9  892.27  4740.9  890.76  4756.0  890.23
  4762.3  891.39  4801.0  888.57  4851.0  887.71  4861.0  888.24  4901.1  887.08
  4974.6  888.28  4989.1  884.10  4994.8  880.10  5009.3  875.94  5009.5  875.44
  5013.3  875.94  5023.0  885.64  5033.3  886.32  5039.0  889.01  5074.7  888.90
  5142.6  888.88  5192.6  889.84  5232.6  891.76  5302.6  893.47  5332.6  895.53
  5392.6  896.22  5402.6  897.01  5422.6  896.09  5452.6  898.89  5517.8  901.81
#Mann=5,-1,0
  4628.7    0.05       0  4974.6    0.12       0  5009.3    0.07       0
  5013.3    0.12       0  5074.7    0.05       0
Bank Sta=5009.3,5013.3
Exp/Cntr=0.3,0.1

Type RM Length L Ch R = 1,59,0,0,0
BEGIN DESCRIPTION:
UDS St 46 0.6
END DESCRIPTION:
XS GIS Cut Line= 4
      2266816.25      7203259.83      2266284.30      7203138.41
      2266214.26      7203175.86      2266291.28      7203814.28
#Sta/Elev= 30
  4411.3  901.88  4428.4  898.05  4439.2  892.67  4481.7  890.44  4783.3  884.94
  4870.1  885.39  4890.6  881.41  4921.3  881.26  4932.0  873.03  4939.9  870.62
  4940.1  870.12  4943.9  870.62  4956.9  870.72  4962.9  876.46  4975.4  879.95
  5060.7  882.29  5090.9  886.29  5111.0  885.47  5121.9  879.65  5151.3  881.92
  5161.4  879.58  5192.9  881.08  5211.8  886.04  5291.7  887.34  5390.5  889.79
  5574.4  891.37  5644.9  894.01  5654.9  894.64  5665.0  899.50  5679.4  901.74
#Mann=7,-1,0
  4411.3    0.05       0  4783.3    0.12       0  4939.9    0.07       0
  4943.9    0.12       0  5192.9    0.05       0  5291.7    0.12       0
  5390.5    0.05       0
Bank Sta=4939.9,4943.9
Exp/Cntr=0.3,0.1

Chan Stop Cuts=-1