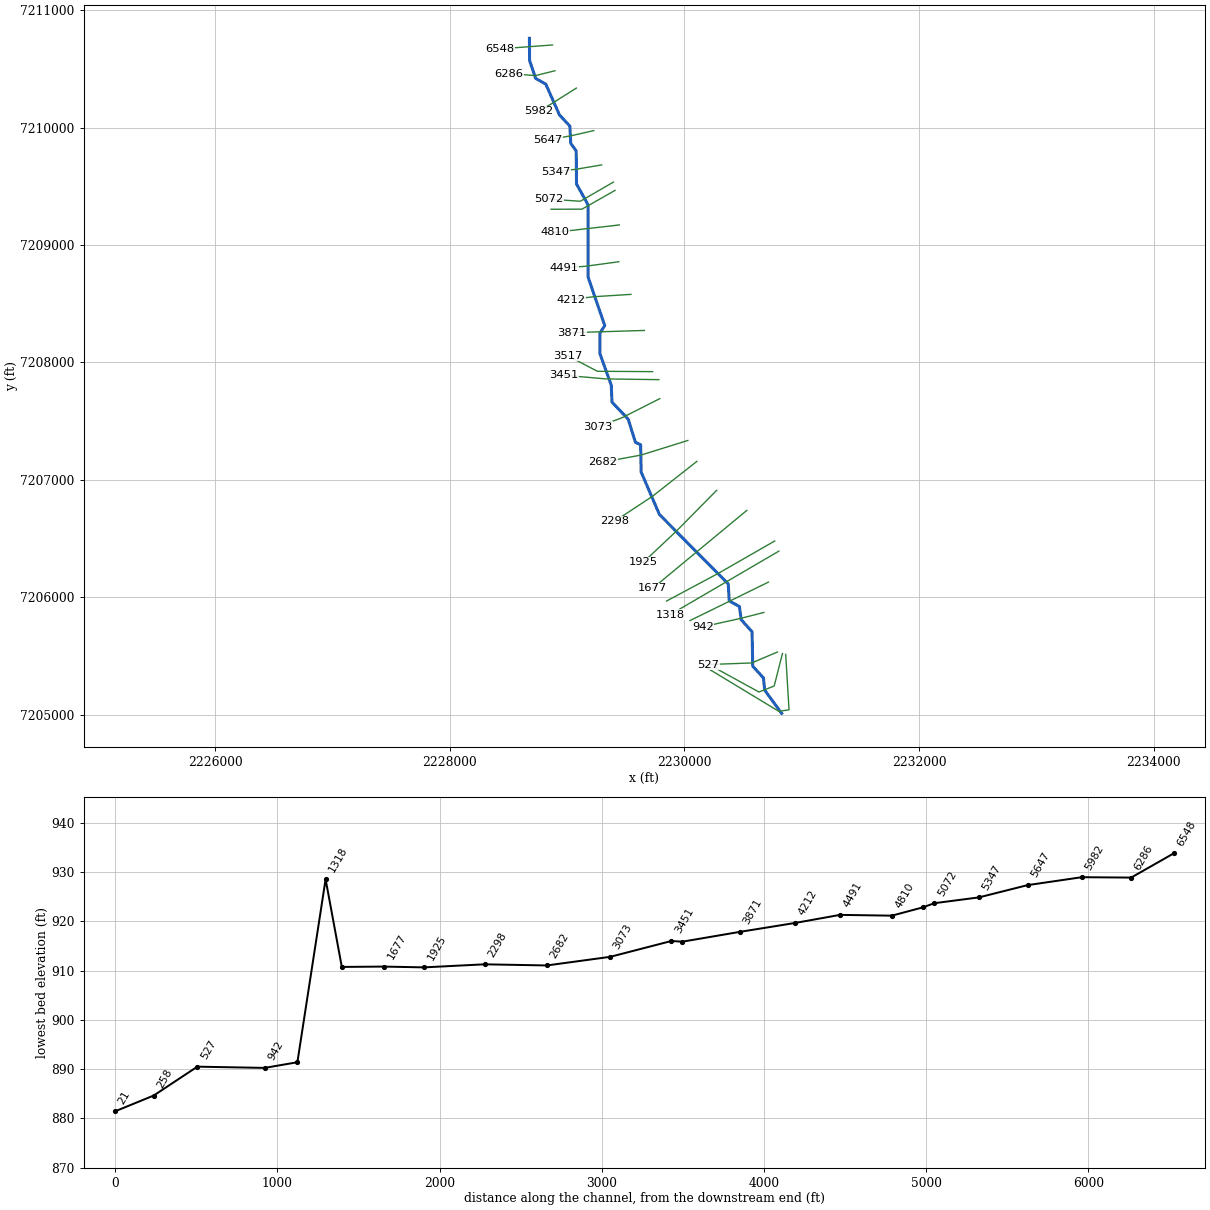
--- UDS St 49.prj (project) ---

Proj Title=UDS St 49 Base Level Engineering
Current Plan=p01
Default Exp/Contr=0.3,0.1
English Units
Geom File=g01
Flow File=f01
Plan File=p01
Y Axis Title=Elevation
X Axis Title(PF)=Main Channel Distance
X Axis Title(XS)=Station
BEGIN DESCRIPTION:
UDS St 49
END DESCRIPTION:
DSS Export Rating Curves= 0
DSS Export Rating Curve Sorted= 0
DSS Export Volume Flow Curves= 0
DXF OffsetX= 0
DXF OffsetY= 0
DXF ScaleX= 1
DXF ScaleY= 10

--- UDS St 49.p01 (plan) ---

Plan Title=Multiple Run
Short Identifier=Multiple
Geom File=g01
Flow File=f01
Subcritical Flow
K Sum by GR= 0
Std Step Tol= 0.01
Critical Tol= 0.01
Num of Std Step Trials= 20
Max Error Tol= 0.3
Flow Tol Ratio= 0.001
Split Flow NTrial= 30
Split Flow Tol= 0.02
Split Flow Ratio= 0.02
Log Output Level= 0
Friction Slope Method= 1
Unsteady Friction Slope Method= 2
Unsteady Bridges Friction Slope Method= 1
Parabolic Critical Depth
Global Vel Dist=  1 , 1 , 1
Global Log Level= 0
CheckData=True
Encroach Param= -1, 0, 0, 0
BEGIN DESCRIPTION:
Multiple Run
END DESCRIPTION:

--- UDS St 49.f01 (steady flow) ---

Flow Title=Multiple
Program Version=4.10
Number of Profiles= 7
Profile Names=10-year,25-year,50-year,1pct_min,100-year,1pct_plu,500-year
River Rch & RM=UDS St 49,Reach-1         ,6548
     648     904    1119     688    1372    2738    2071
River Rch & RM=UDS St 49,Reach-1         ,1144
     739    1036    1288     795    1586    3164    2411
River Rch & RM=UDS St 49,Reach-1         ,21
    2052    3010    3852    2438    4865    9708    7792
Boundary for River Rch & Prof#=UDS St 49,Reach-1         , 1
Up Type= 0
Dn Type= 3
Dn Slope=0.015
Boundary for River Rch & Prof#=UDS St 49,Reach-1         , 2
Up Type= 0
Dn Type= 3
Dn Slope=0.015
Boundary for River Rch & Prof#=UDS St 49,Reach-1         , 3
Up Type= 0
Dn Type= 3
Dn Slope=0.015
Boundary for River Rch & Prof#=UDS St 49,Reach-1         , 4
Up Type= 0
Dn Type= 3
Dn Slope=0.015
Boundary for River Rch & Prof#=UDS St 49,Reach-1         , 5
Up Type= 0
Dn Type= 3
Dn Slope=0.015
Boundary for River Rch & Prof#=UDS St 49,Reach-1         , 6
Up Type= 0
Dn Type= 3
Dn Slope=0.015
Boundary for River Rch & Prof#=UDS St 49,Reach-1         , 7
Up Type= 0
Dn Type= 3
Dn Slope=0.015
DSS Import GetInterval= 0
DSS Import GetPeak= 0
DSS Import FillOption= 0

--- UDS St 49.g01 (geometry) ---

Geom Title=Existing Conditions

River Reach=UDS St 49,Reach-1
Reach XY= 30
      2228679.00      7210760.00      2228680.21      7210570.50
      2228732.19      7210418.35      2228818.31      7210369.98
      2228934.85      7210107.71      2229023.52      7210012.44
      2229031.27      7209865.94      2229077.78      7209799.50
      2229080.36      7209519.65      2229178.80      7209341.74
      2229179.68      7208723.92      2229320.92      7208313.30
      2229280.38      7208249.56      2229279.52      7208075.22
      2229376.61      7207804.47      2229382.54      7207661.47
      2229520.86      7207516.06      2229582.72      7207318.21
      2229626.81      7207298.71      2229631.26      7207065.94
      2229787.14      7206703.94      2230373.53      7206112.44
      2230382.27      7205968.02      2230468.55      7205920.08
      2230484.54      7205807.58      2230576.82      7205704.55
      2230582.55      7205411.47      2230673.46      7205312.42
      2230684.52      7205207.57      2230829.00      7205010.00

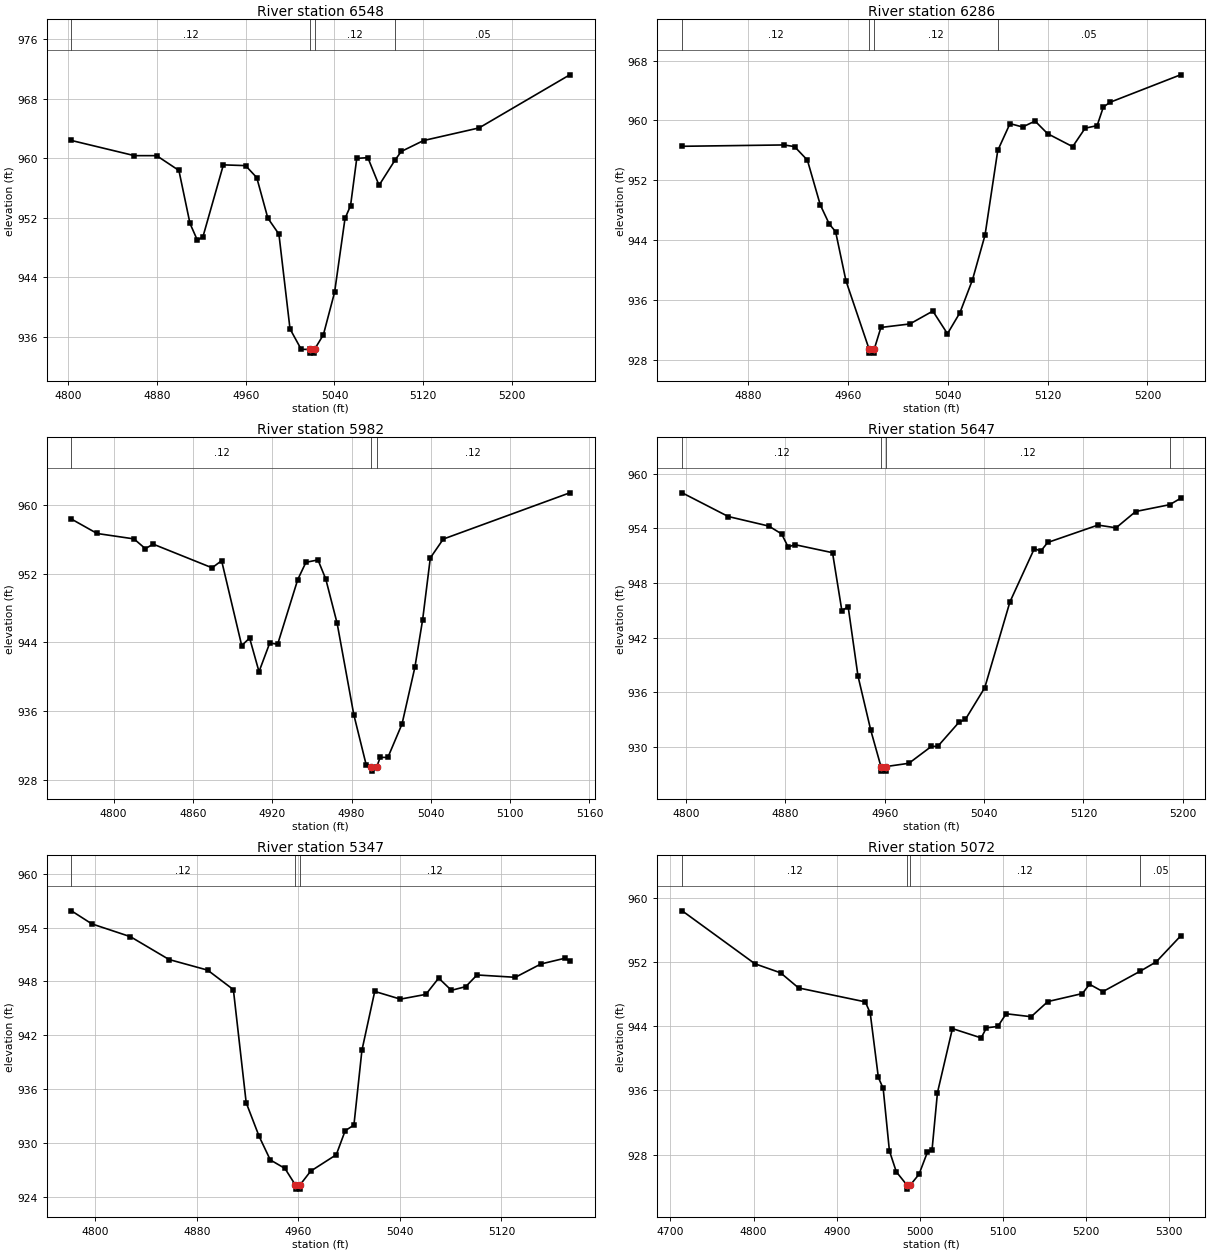
Type RM Length L Ch R = 1,6548,262,262,262
BEGIN DESCRIPTION:
UDS St 49 16.1
END DESCRIPTION:
XS GIS Cut Line= 2
      2228875.61      7210703.48      2228427.43      7210670.41
#Sta/Elev= 30
  4802.8  962.41  4859.6  960.37  4879.6  960.37  4899.7  958.38  4909.7  951.25
  4916.4  948.98  4921.4  949.47  4939.8  959.13  4959.8  959.03  4969.9  957.42
  4979.9  951.97  4989.9  949.81  4999.9  937.07  5010.0  934.32  5018.0  934.31
  5018.2  933.81  5021.7  933.81  5022.0  934.31  5030.0  936.28  5040.1  941.99
  5049.5  951.92  5054.5  953.64  5060.1  960.00  5070.1  960.10  5080.2  956.38
  5094.6  959.77  5100.2  960.93  5120.3  962.40  5170.4  964.10  5252.2  971.24
#Mann=4,-1,0
  4802.8    0.12       0  5018.0    0.07       0  5022.0    0.12       0
  5094.6    0.05       0
Bank Sta=5018,5022
Exp/Cntr=0.3,0.1

Type RM Length L Ch R = 1,6286,304,304,304
BEGIN DESCRIPTION:
UDS St 49 16.0
END DESCRIPTION:
XS GIS Cut Line= 3
      2228896.35      7210483.75      2228729.71      7210442.56
      2228502.81      7210459.67
#Sta/Elev= 30
  4827.3  956.54  4908.8  956.72  4917.3  956.50  4927.6  954.69  4937.9  948.72
  4945.1  946.16  4950.2  945.13  4958.5  938.56  4977.1  929.40  4977.3  928.90
  4980.8  928.90  4981.1  929.40  4986.5  932.33  5009.7  932.80  5028.1  934.52
  5039.8  931.49  5049.8  934.30  5059.8  938.67  5069.9  944.67  5080.1  955.98
  5089.9  959.57  5100.0  959.12  5110.0  959.91  5120.0  958.23  5140.1  956.49
  5150.1  958.96  5159.7  959.30  5164.7  961.79  5170.2  962.43  5226.5  966.09
#Mann=4,-1,0
  4827.3    0.12       0  4977.1    0.07       0  4981.1    0.12       0
  5080.1    0.05       0
Bank Sta=4977.1,4981.1
Exp/Cntr=0.3,0.1

Type RM Length L Ch R = 1,5982,335,335,335
BEGIN DESCRIPTION:
UDS St 49 15.0
END DESCRIPTION:
XS GIS Cut Line= 3
      2229078.97      7210336.32      2228879.00      7210210.00
      2228758.35      7210138.05
#Sta/Elev= 30
  4768.1  958.36  4787.5  956.68  4815.4  956.05  4824.0  954.91  4829.9  955.44
  4874.5  952.68  4881.7  953.51  4896.9  943.62  4902.9  944.49  4910.0  940.57
  4918.1  943.91  4924.1  943.77  4939.3  951.31  4945.5  953.32  4954.6  953.60
  4960.5  951.37  4969.1  946.21  4981.7  935.57  4991.1  929.70  4995.0  929.48
  4995.2  928.98  4999.0  929.48  5001.7  930.58  5007.5  930.58  5018.2  934.48
  5027.9  941.07  5033.8  946.64  5039.6  953.83  5049.4  956.03  5145.1  961.42
#Mann=3,-1,0
  4768.1    0.12       0  4995.0    0.07       0  4999.0    0.12       0
Bank Sta=4995,4999
Exp/Cntr=0.3,0.1

Type RM Length L Ch R = 1,5647,300,300,300
BEGIN DESCRIPTION:
UDS St 49 14.0
END DESCRIPTION:
XS GIS Cut Line= 3
      2229227.11      7209973.89      2229028.56      7209928.98
      2228833.44      7209896.32
#Sta/Elev= 30
  4796.8  957.91  4833.9  955.31  4866.6  954.26  4876.9  953.40  4882.2  951.95
  4887.3  952.23  4917.9  951.34  4925.4  944.99  4930.5  945.40  4938.4  937.81
  4948.7  931.86  4956.9  927.87  4957.2  927.37  4960.7  927.37  4960.9  927.87
  4979.4  928.23  4997.6  930.09  5002.7  930.09  5019.8  932.74  5024.9  933.04
  5040.5  936.52  5060.8  945.94  5080.5  951.80  5085.6  951.51  5091.2  952.46
  5131.7  954.37  5146.3  954.07  5162.1  955.86  5189.5  956.61  5198.2  957.30
#Mann=4,-1,0
  4796.8    0.12       0  4956.9    0.07       0  4960.9    0.12       0
  5189.5    0.05       0
Bank Sta=4956.9,4960.9
Exp/Cntr=0.3,0.1

Type RM Length L Ch R = 1,5347,275,275,275
BEGIN DESCRIPTION:
UDS St 49 13.0
END DESCRIPTION:
XS GIS Cut Line= 3
      2229294.81      7209681.81      2229080.23      7209645.42
      2228906.37      7209624.98
#Sta/Elev= 30
  4781.1  955.86  4797.1  954.41  4827.6  952.98  4858.0  950.44  4888.4  949.26
  4908.7  947.09  4918.8  934.50  4929.0  930.75  4937.8  928.13  4949.3  927.19
  4957.4  925.38  4957.7  924.88  4961.2  924.88  4961.4  925.38  4969.6  926.88
  4989.8  928.71  4996.8  931.38  5003.7  932.01  5010.0  940.33  5020.1  946.89
  5040.3  946.03  5060.4  946.56  5070.5  948.37  5080.5  947.01  5091.8  947.42
  5100.7  948.72  5130.9  948.46  5151.0  949.94  5169.9  950.58  5173.8  950.28
#Mann=3,-1,0
  4781.1    0.12       0  4957.4    0.07       0  4961.4    0.12       0
Bank Sta=4957.4,4961.4
Exp/Cntr=0.3,0.1

Type RM Length L Ch R = 1,5072,68,68,68
BEGIN DESCRIPTION:
UDS St 49 12.1
END DESCRIPTION:
XS GIS Cut Line= 4
      2229394.68      7209535.43      2229112.93      7209372.10
      2228957.52      7209382.96      2228839.86      7209392.39
#Sta/Elev= 30
  4714.2  958.39  4801.7  951.79  4832.6  950.66  4854.2  948.78  4934.5  947.04
  4940.4  945.65  4950.2  937.62  4956.0  936.26  4963.5  928.47  4971.8  925.86
  4984.6  924.20  4984.9  923.70  4988.6  924.20  4999.1  925.55  5009.1  928.27
  5014.8  928.61  5021.3  935.72  5039.3  943.71  5073.9  942.55  5080.2  943.80
  5093.9  943.98  5104.0  945.56  5134.0  945.19  5154.1  947.08  5195.7  948.08
  5204.2  949.24  5220.3  948.32  5265.3  950.87  5284.5  952.03  5313.7  955.24
#Mann=4,-1,0
  4714.2    0.12       0  4984.6    0.07       0  4988.6    0.12       0
  5265.3    0.05       0
Bank Sta=4984.6,4988.6
Exp/Cntr=0.3,0.1

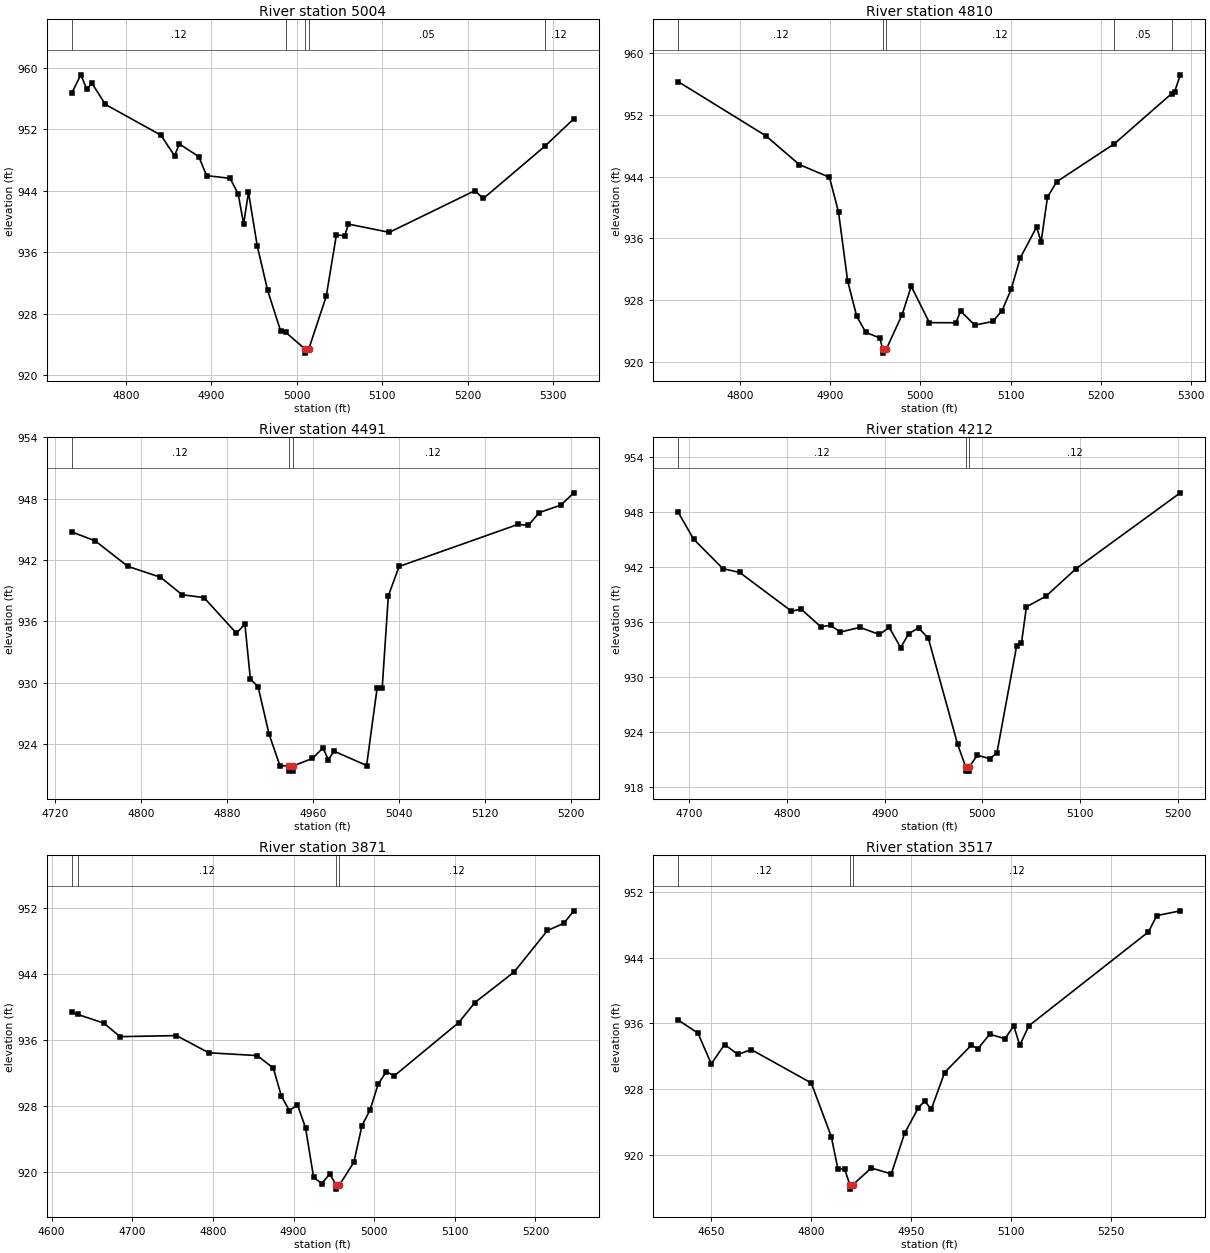
Type RM Length L Ch R = 1,5004,194,194,194
BEGIN DESCRIPTION:
UDS St 49 12.0
END DESCRIPTION:
XS GIS Cut Line= 3
      2229408.32      7209464.54      2229126.55      7209304.68
      2228863.21      7209304.26
#Sta/Elev= 30
  4736.6  956.65  4747.3  959.05  4754.5  957.15  4760.2  957.99  4776.1  955.20
  4841.0  951.21  4856.9  948.53  4862.6  950.06  4885.3  948.42  4894.4  945.95
  4921.8  945.60  4931.3  943.60  4937.7  939.66  4943.4  943.79  4953.6  936.84
  4965.8  931.03  4980.9  925.80  4986.7  925.61  5009.8  923.38  5010.0  922.88
  5013.8  923.38  5034.3  930.25  5046.2  938.24  5056.0  938.13  5060.2  939.65
  5108.1  938.58  5208.1  943.99  5218.1  942.98  5289.9  949.76  5323.9  953.34
#Mann=5,-1,0
  4736.6    0.12       0  4986.7    0.05       0  5009.8   0.033       0
  5013.8    0.05       0  5289.9    0.12       0
Bank Sta=5009.8,5013.8
Exp/Cntr=0.3,0.1

Type RM Length L Ch R = 1,4810,319,319,319
BEGIN DESCRIPTION:
UDS St 49 11.1
END DESCRIPTION:
XS GIS Cut Line= 2
      2229445.58      7209170.48      2228892.79      7209107.24
#Sta/Elev= 30
  4731.7  956.28  4828.9  949.28  4866.0  945.55  4899.4  943.91  4909.4  939.42
  4919.5  930.52  4929.6  925.93  4939.6  923.86  4955.3  923.12  4958.3  921.67
  4958.6  921.17  4962.3  921.67  4979.9  926.15  4990.0  929.81  5010.1  925.11
  5039.6  925.10  5044.6  926.62  5060.4  924.79  5080.5  925.27  5090.6  926.67
  5100.7  929.42  5110.7  933.46  5128.9  937.48  5133.9  935.55  5140.9  941.32
  5151.0  943.32  5215.1  948.25  5278.6  954.74  5281.8  954.97  5288.1  957.16
#Mann=5,-1,0
  4731.7    0.12       0  4958.3    0.07       0  4962.3    0.12       0
  5215.1    0.05       0  5278.6    0.12       0
Bank Sta=4958.3,4962.3
Exp/Cntr=0.3,0.1

Type RM Length L Ch R = 1,4491,279,279,279
BEGIN DESCRIPTION:
UDS St 49 11.0
END DESCRIPTION:
XS GIS Cut Line= 3
      2229440.84      7208857.02      2229154.66      7208818.24
      2228976.96      7208804.88
#Sta/Elev= 30
  4735.7  944.75  4757.7  943.86  4788.0  941.37  4818.3  940.31  4838.5  938.59
  4858.7  938.32  4888.9  934.83  4896.8  935.72  4901.9  930.35  4909.1  929.58
  4919.2  924.98  4929.3  921.88  4937.4  921.83  4937.6  921.33  4941.1  921.33
  4941.4  921.83  4959.6  922.57  4969.4  923.60  4974.4  922.45  4979.8  923.28
  5010.0  921.88  5019.8  929.49  5024.5  929.49  5030.2  938.49  5040.2  941.36
  5150.5  945.47  5160.5  945.40  5170.6  946.64  5190.6  947.37  5202.7  948.57
#Mann=3,-1,0
  4735.7    0.12       0  4937.4    0.07       0  4941.4    0.12       0
Bank Sta=4937.4,4941.4
Exp/Cntr=0.3,0.1

Type RM Length L Ch R = 1,4212,341,341,341
BEGIN DESCRIPTION:
UDS St 49 10.0
END DESCRIPTION:
XS GIS Cut Line= 3
      2229544.77      7208579.09      2229228.42      7208559.20
      2229032.55      7208535.25
#Sta/Elev= 30
  4688.5  947.95  4704.3  945.01  4734.4  941.78  4751.5  941.37  4804.5  937.15
  4814.5  937.36  4834.6  935.44  4844.6  935.60  4854.6  934.86  4874.6  935.37
  4894.7  934.60  4904.7  935.37  4916.4  933.16  4924.7  934.69  4934.8  935.31
  4944.8  934.17  4974.8  922.59  4982.9  920.18  4983.1  919.68  4986.6  919.68
  4986.9  920.18  4994.9  921.41  5007.7  921.04  5015.0  921.67  5035.1  933.29
  5040.1  933.63  5045.2  937.61  5065.3  938.78  5095.6  941.74  5202.8  950.06
#Mann=3,-1,0
  4688.5    0.12       0  4982.9    0.07       0  4986.9    0.12       0
Bank Sta=4982.9,4986.9
Exp/Cntr=0.3,0.1

Type RM Length L Ch R = 1,3871,354,354,354
BEGIN DESCRIPTION:
UDS St 49 9.0
END DESCRIPTION:
XS GIS Cut Line= 3
      2229658.97      7208271.80      2229252.38      7208259.39
      2229036.36      7208252.88
#Sta/Elev= 30
  4624.8  939.36  4632.1  939.12  4664.8  938.05  4684.8  936.41  4754.8  936.54
  4794.8  934.45  4854.9  934.11  4874.9  932.60  4884.9  929.18  4894.9  927.43
  4904.9  928.13  4914.9  925.32  4924.9  919.32  4934.9  918.54  4944.9  919.71
  4952.9  918.37  4953.2  917.87  4956.9  918.37  4974.9  921.15  4984.9  925.60
  4994.9  927.49  5004.9  930.61  5015.0  932.15  5025.0  931.65  5105.0  938.13
  5125.0  940.56  5173.6  944.27  5215.0  949.32  5235.1  950.18  5247.7  951.71
#Mann=4,-1,0
  4624.8    0.05       0  4632.1    0.12       0  4952.9    0.07       0
  4956.9    0.12       0
Bank Sta=4952.9,4956.9
Exp/Cntr=0.3,0.1

Type RM Length L Ch R = 1,3517,66,66,66
BEGIN DESCRIPTION:
UDS St 49 8.1
END DESCRIPTION:
XS GIS Cut Line= 3
      2229728.65      7207920.86      2229258.27      7207923.95
      2229007.73      7208055.13
#Sta/Elev= 30
  4600.2  936.41  4629.9  934.83  4649.9  931.09  4669.9  933.44  4689.9  932.23
  4709.9  932.82  4799.9  928.77  4829.9  922.26  4839.9  918.33  4849.9  918.33
  4857.9  916.38  4858.1  915.88  4861.9  916.38  4889.9  918.44  4919.9  917.73
  4939.9  922.66  4959.9  925.67  4969.9  926.59  4979.9  925.57  4999.9  930.04
  5039.9  933.35  5049.9  932.94  5067.7  934.69  5090.6  934.14  5103.6  935.73
  5112.6  933.34  5126.2  935.71  5305.6  947.11  5318.1  949.09  5353.4  949.67
#Mann=3,-1,0
  4600.2    0.12       0  4857.9    0.07       0  4861.9    0.12       0
Bank Sta=4857.9,4861.9
Exp/Cntr=0.3,0.1

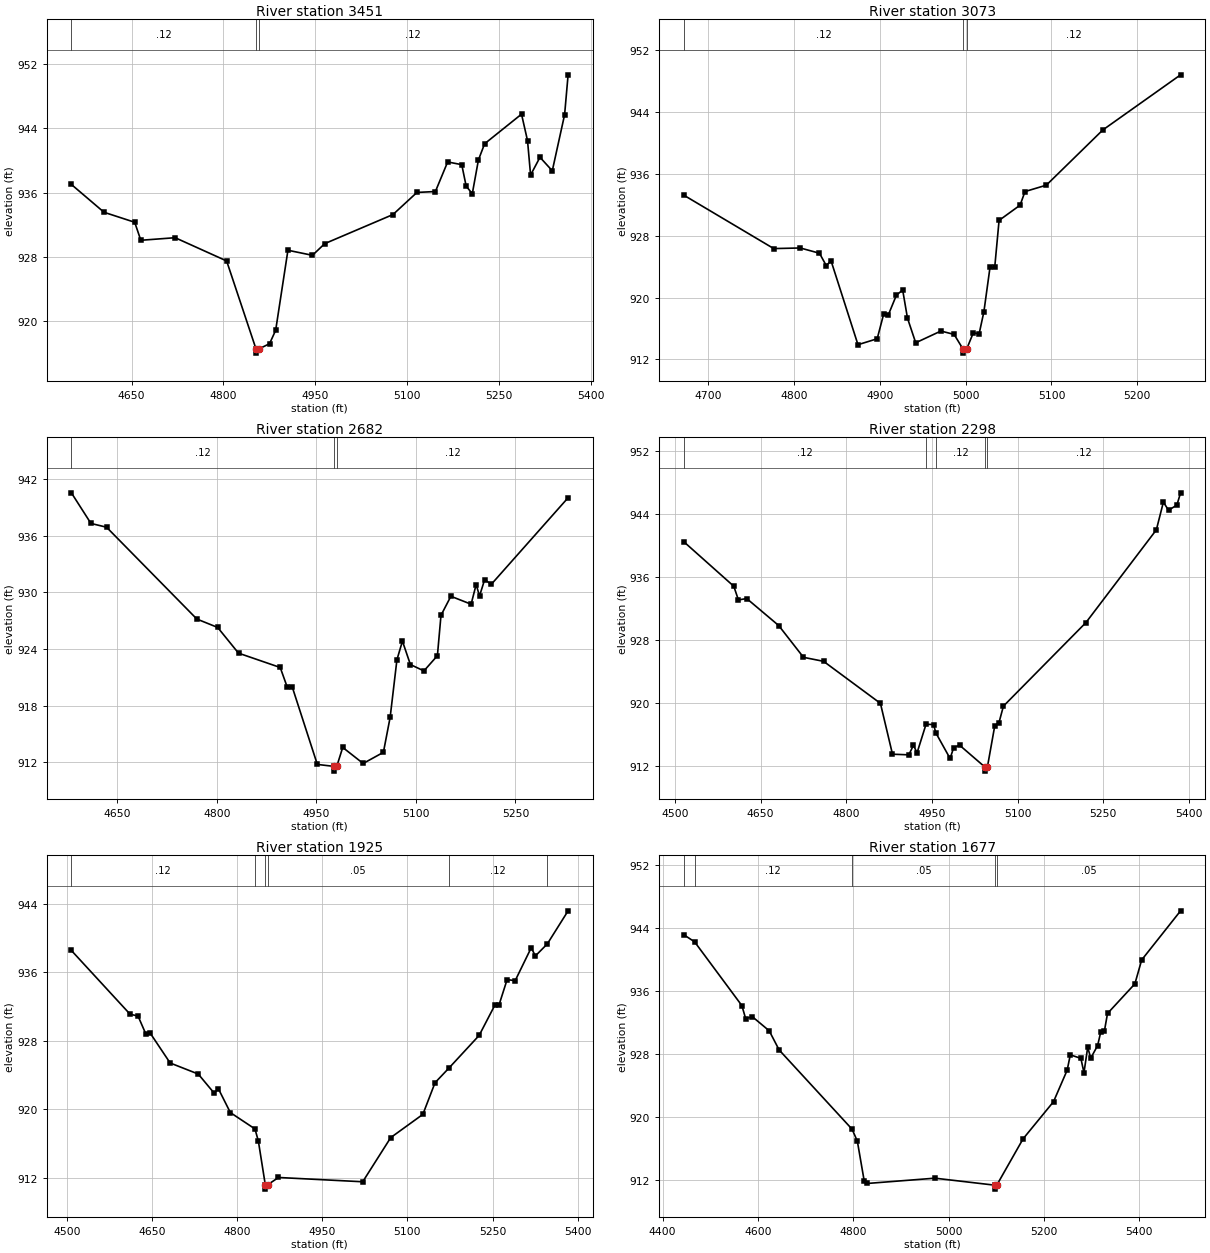
Type RM Length L Ch R = 1,3451,378,378,378
BEGIN DESCRIPTION:
UDS St 49 8.0
END DESCRIPTION:
XS GIS Cut Line= 3
      2229782.27      7207852.71      2229332.84      7207858.76
      2228973.30      7207890.39
#Sta/Elev= 30
  4551.9  937.00  4605.2  933.54  4655.2  932.30  4665.2  930.06  4721.2  930.38
  4805.2  927.49  4853.2  916.53  4853.5  916.03  4857.2  916.53  4875.2  917.20
  4885.2  918.87  4905.2  928.82  4945.2  928.19  4965.2  929.64  5076.6  933.26
  5115.7  936.01  5145.8  936.12  5165.8  939.80  5188.8  939.46  5196.0  936.79
  5206.0  935.85  5216.0  940.05  5226.1  942.06  5286.3  945.74  5296.1  942.45
  5301.1  938.17  5316.4  940.38  5336.5  938.70  5356.6  945.68  5362.3  950.63
#Mann=3,-1,0
  4551.9    0.12       0  4853.2    0.07       0  4857.2    0.12       0
Bank Sta=4853.2,4857.2
Exp/Cntr=0.3,0.1

Type RM Length L Ch R = 1,3073,391,391,391
BEGIN DESCRIPTION:
UDS St 49 7.0
END DESCRIPTION:
XS GIS Cut Line= 3
      2229790.07      7207691.07      2229469.33      7207528.56
      2229263.81      7207451.37
#Sta/Elev= 30
  4671.4  933.25  4776.2  926.34  4807.1  926.42  4829.5  925.74  4837.4  924.14
  4843.0  924.76  4874.4  913.90  4896.8  914.67  4904.3  917.85  4909.9  917.79
  4919.2  920.31  4926.5  920.98  4932.1  917.34  4941.7  914.15  4971.1  915.67
  4986.5  915.23  4997.0  913.31  4997.2  912.81  5001.0  913.31  5008.9  915.45
  5015.6  915.29  5021.2  918.17  5028.3  923.90  5033.8  923.90  5038.9  929.99
  5063.4  931.96  5069.1  933.72  5094.0  934.55  5159.8  941.69  5250.5  948.83
#Mann=3,-1,0
  4671.4    0.12       0  4997.0    0.07       0  5001.0    0.12       0
Bank Sta=4997,5001
Exp/Cntr=0.3,0.1

Type RM Length L Ch R = 1,2682,384,384,384
BEGIN DESCRIPTION:
UDS St 49 6.0
END DESCRIPTION:
XS GIS Cut Line= 3
      2230029.58      7207334.57      2229629.00      7207210.00
      2229305.26      7207150.33
#Sta/Elev= 30
  4580.6  940.52  4610.1  937.28  4633.6  936.88  4769.7  927.16  4801.1  926.27
  4832.5  923.55  4895.4  922.03  4905.9  919.96  4913.5  919.97  4951.3  911.77
  4976.6  911.56  4976.8  911.06  4980.6  911.56  4989.6  913.57  5020.4  911.87
  5050.9  913.05  5061.1  916.77  5071.3  922.85  5079.6  924.82  5091.6  922.34
  5112.0  921.67  5132.3  923.28  5137.7  927.55  5152.6  929.57  5183.1  928.73
  5190.7  930.81  5195.8  929.60  5203.5  931.33  5213.6  930.84  5329.3  940.00
#Mann=3,-1,0
  4580.6    0.12       0  4976.6    0.07       0  4980.6    0.12       0
Bank Sta=4976.6,4980.6
Exp/Cntr=0.3,0.1

Type RM Length L Ch R = 1,2298,373,373,373
BEGIN DESCRIPTION:
UDS St 49 5.0
END DESCRIPTION:
XS GIS Cut Line= 3
      2230106.09      7207156.38      2229729.00      7206860.00
      2229403.59      7206645.25
#Sta/Elev= 30
  4515.7  940.43  4603.1  934.78  4611.2  933.04  4625.7  933.22  4681.7  929.79
  4725.1  925.75  4760.3  925.24  4859.8  919.90  4880.9  913.44  4909.5  913.36
  4917.6  914.58  4923.9  913.61  4939.6  917.24  4952.8  917.21  4956.8  916.15
  4981.7  912.90  4988.1  914.28  4998.3  914.59  5043.0  911.79  5043.2  911.29
  5047.0  911.79  5060.0  917.08  5067.2  917.42  5075.1  919.55  5219.6  930.17
  5342.8  941.95  5355.1  945.47  5364.1  944.44  5378.7  945.09  5385.2  946.65
#Mann=5,-1,0
  4515.7    0.12       0  4939.6    0.05       0  4956.8    0.12       0
  5043.0    0.07       0  5047.0    0.12       0
Bank Sta=5043,5047
Exp/Cntr=0.3,0.1

Type RM Length L Ch R = 1,1925,248,248,248
BEGIN DESCRIPTION:
UDS St 49 4.0
END DESCRIPTION:
XS GIS Cut Line= 3
      2230275.05      7206910.14      2229929.00      7206560.00
      2229650.02      7206297.29
#Sta/Elev= 30
  4507.7  938.54  4611.1  931.10  4625.2  930.88  4639.3  928.73  4646.5  928.90
  4681.8  925.40  4731.3  924.11  4759.6  921.86  4766.6  922.42  4787.9  919.61
  4831.3  917.70  4837.3  916.27  4849.5  911.17  4849.7  910.67  4853.5  911.17
  4872.7  912.03  5021.2  911.53  5070.6  916.69  5127.2  919.40  5148.7  923.10
  5173.2  924.81  5226.4  928.62  5254.7  932.23  5261.5  932.19  5275.7  935.14
  5289.9  935.01  5318.2  938.86  5325.5  937.90  5346.6  939.31  5383.2  943.17
#Mann=6,-1,0
  4507.7    0.12       0  4831.3    0.05       0  4849.5   0.033       0
  4853.5    0.05       0  5173.2    0.12       0  5346.6    0.05       0
Bank Sta=4849.5,4853.5
Exp/Cntr=0.3,0.1

Type RM Length L Ch R = 1,1677,259,259,259
BEGIN DESCRIPTION:
UDS St 49 3.1
END DESCRIPTION:
XS GIS Cut Line= 2
      2230532.00      7206739.12      2229729.01      7206074.75
#Sta/Elev= 30
  4444.5  943.12  4467.1  942.22  4566.2  934.13  4574.1  932.49  4588.4  932.71
  4623.6  930.93  4644.4  928.50  4797.4  918.44  4808.5  916.92  4822.9  911.87
  4829.4  911.55  4971.3  912.22  5097.0  911.33  5097.2  910.83  5101.0  911.33
  5156.3  917.22  5220.1  921.93  5248.8  925.94  5255.3  927.88  5277.5  927.43
  5284.0  925.61  5291.8  928.83  5298.3  927.47  5312.6  929.05  5319.1  930.75
  5327.0  930.95  5333.4  933.13  5390.8  936.89  5405.1  939.93  5486.7  946.16
#Mann=5,-1,0
  4444.5    0.05       0  4467.1    0.12       0  4797.4    0.05       0
  5097.0   0.033       0  5101.0    0.05       0
Bank Sta=5097,5101
Exp/Cntr=0.3,0.1

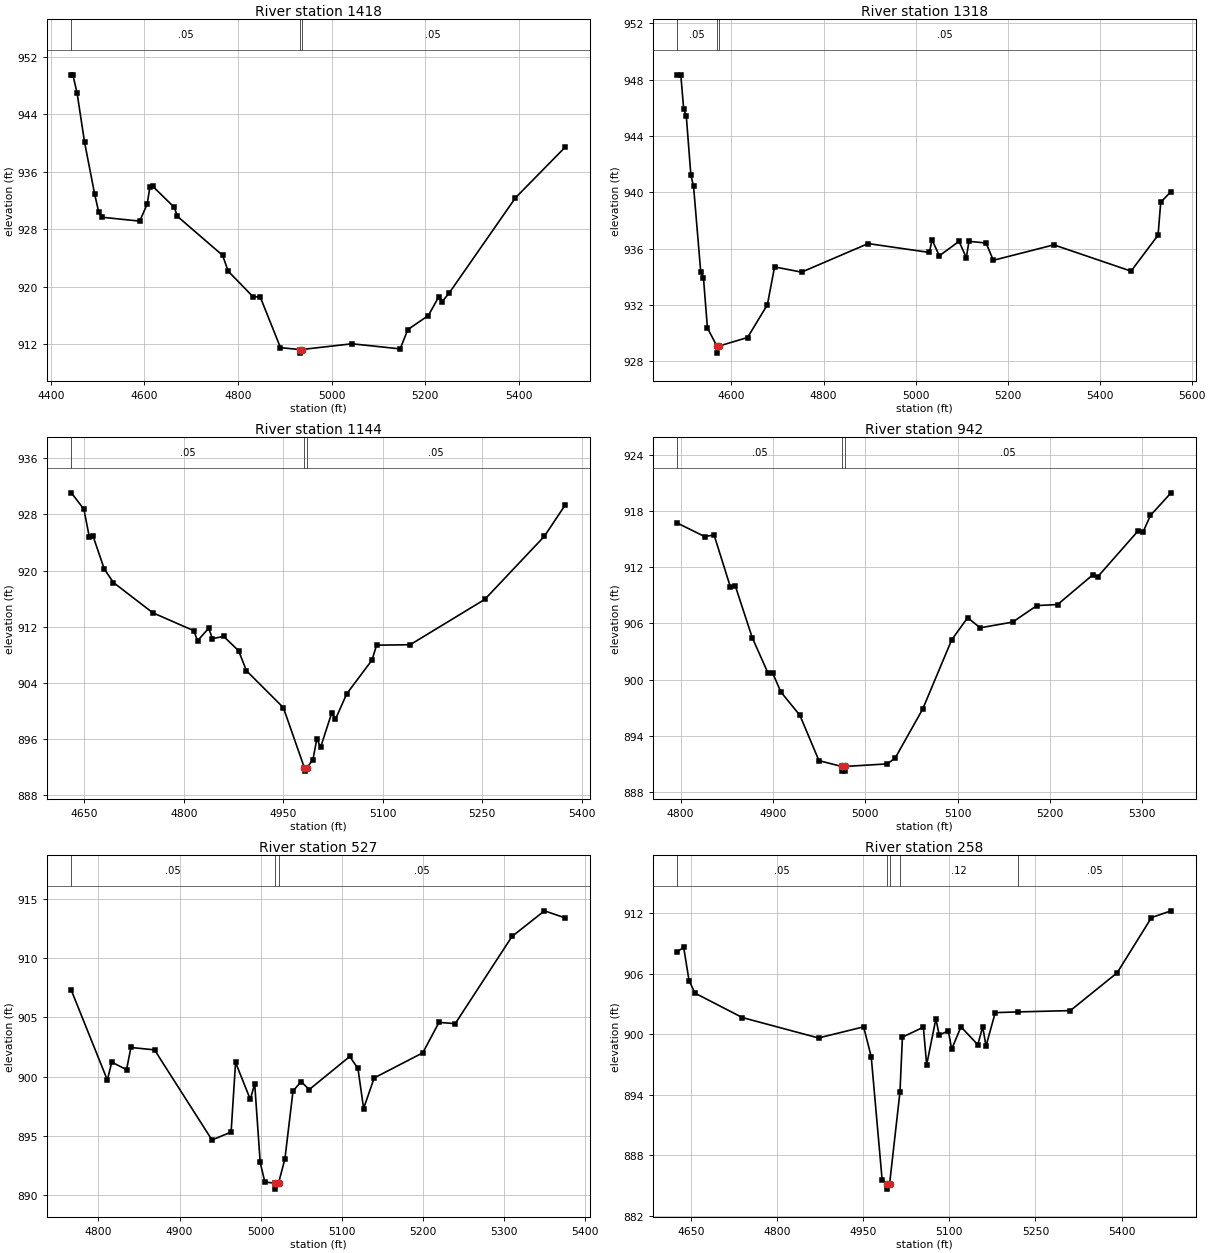
Type RM Length L Ch R = 1,1418,100,100,100
BEGIN DESCRIPTION:
UDS St 49 3.0
END DESCRIPTION:
XS GIS Cut Line= 3
      2230769.72      7206478.30      2230288.53      7206202.51
      2229847.67      7205966.88
#Sta/Elev= 30
  4443.9  949.49  4447.2  949.49  4456.3  946.90  4472.1  940.12  4493.7  932.88
  4502.4  930.38  4509.5  929.67  4590.1  929.13  4605.9  931.51  4611.6  933.84
  4617.6  933.99  4663.7  931.05  4670.6  929.79  4767.0  924.37  4779.0  922.16
  4831.7  918.63  4847.6  918.54  4890.7  911.52  4931.9  911.26  4932.1  910.76
  4935.9  911.26  5043.3  912.06  5146.4  911.35  5162.7  914.04  5206.6  915.99
  5228.5  918.56  5236.1  917.94  5250.5  919.07  5392.7  932.38  5498.4  939.39
#Mann=3,-1,0
  4443.9    0.05       0  4931.9   0.033       0  4935.9    0.05       0
Bank Sta=4931.9,4935.9
Exp/Cntr=0.3,0.1

Type RM Length L Ch R = 1,1318,174,174,174
BEGIN DESCRIPTION:
UDS St 49 2.2
END DESCRIPTION:
XS GIS Cut Line= 2
      2230805.28      7206392.01      2229879.06      7205851.10
#Sta/Elev= 30
  4482.6  948.32  4489.9  948.35  4496.1  945.95  4501.9  945.39  4511.8  941.22
  4517.6  940.43  4533.3  934.31  4539.1  933.93  4547.8  930.34  4568.4  929.06
  4568.7  928.56  4572.5  929.06  4635.0  929.67  4678.0  932.00  4693.7  934.69
  4752.4  934.32  4897.0  936.35  5030.1  935.72  5035.9  936.62  5051.6  935.48
  5094.6  936.51  5110.3  935.34  5116.1  936.51  5153.3  936.39  5169.0  935.16
  5300.5  936.26  5468.3  934.39  5527.0  936.95  5532.8  939.29  5555.2  940.05
#Mann=3,-1,0
  4482.6    0.05       0  4568.4   0.033       0  4572.5    0.05       0
Bank Sta=4568.4,4572.5
Exp/Cntr=0.3,0.1

Type RM Length L Ch R = 1,1144,202,202,202
BEGIN DESCRIPTION:
UDS St 49 2.1
END DESCRIPTION:
XS GIS Cut Line= 2
      2230716.01      7206128.10      2230047.89      7205800.54
#Sta/Elev= 30
  4630.5  931.07  4649.4  928.74  4657.6  924.77  4663.2  924.91  4680.1  920.22
  4694.0  918.28  4753.2  913.98  4815.1  911.42  4820.7  909.99  4837.6  911.77
  4843.2  910.29  4860.1  910.61  4882.6  908.57  4894.5  905.71  4950.1  900.46
  4981.7  891.91  4982.0  891.41  4985.8  891.91  4994.7  893.04  5000.6  896.05
  5006.2  894.80  5023.1  899.73  5028.7  898.82  5045.6  902.42  5083.8  907.25
  5090.6  909.36  5141.2  909.42  5253.7  915.88  5343.6  924.88  5374.6  929.28
#Mann=3,-1,0
  4630.5    0.05       0  4981.7   0.033       0  4985.8    0.05       0
Bank Sta=4981.7,4985.8
Exp/Cntr=0.3,0.1

Type RM Length L Ch R = 1,942,415,415,415
BEGIN DESCRIPTION:
UDS St 49 2.0
END DESCRIPTION:
XS GIS Cut Line= 3
      2230677.45      7205869.77      2230481.85      7205819.68
      2230157.23      7205747.76
#Sta/Elev= 30
  4796.6  916.70  4826.0  915.27  4836.3  915.43  4853.9  909.90  4859.1  910.05
  4877.6  904.49  4894.7  900.70  4899.9  900.68  4908.5  898.71  4929.2  896.21
  4949.8  891.38  4974.3  890.76  4974.6  890.26  4978.1  890.26  4978.4  890.76
  5023.6  891.03  5032.2  891.63  5062.1  896.87  5093.6  904.27  5110.8  906.62
  5124.3  905.54  5159.5  906.15  5185.8  907.91  5208.2  908.02  5246.7  911.22
  5251.8  911.00  5295.4  915.88  5300.6  915.73  5308.7  917.52  5331.0  919.93
#Mann=3,-1,0
  4796.6    0.05       0  4974.3   0.033       0  4978.4    0.05       0
Bank Sta=4974.3,4978.4
Exp/Cntr=0.3,0.1

Type RM Length L Ch R = 1,527,269,269,269
BEGIN DESCRIPTION:
UDS St 49 1.0
END DESCRIPTION:
XS GIS Cut Line= 3
      2230793.40      7205533.04      2230573.52      7205439.48
      2230203.72      7205426.08
#Sta/Elev= 30
  4766.5  907.28  4810.9  899.72  4816.4  901.22  4834.6  900.59  4840.0  902.46
  4869.1  902.26  4940.0  894.66  4963.6  895.32  4969.1  901.20  4987.3  898.08
  4992.7  899.40  4999.5  892.76  5005.2  891.11  5017.9  891.01  5018.2  890.51
  5022.1  891.01  5030.0  893.07  5040.0  898.79  5050.0  899.58  5060.0  898.91
  5110.0  901.70  5120.1  900.69  5127.1  897.31  5140.1  899.89  5200.1  902.01
  5220.1  904.58  5240.1  904.47  5310.2  911.83  5350.2  913.99  5375.5  913.40
#Mann=3,-1,0
  4766.5    0.05       0  5017.9   0.033       0  5022.1    0.05       0
Bank Sta=5017.9,5022.1
Exp/Cntr=0.3,0.1

Type RM Length L Ch R = 1,258,237,237,237
BEGIN DESCRIPTION:
UDS St 49 0.9
END DESCRIPTION:
XS GIS Cut Line= 4
      2230835.66      7205519.59      2230765.04      7205242.74
      2230635.29      7205192.28      2230253.62      7205401.11
#Sta/Elev= 30
  4626.2  908.18  4637.1  908.59  4646.4  905.31  4656.7  904.06  4739.3  901.64
  4872.0  899.62  4950.6  900.72  4963.8  897.77  4982.8  885.59  4991.6  885.15
  4991.9  884.65  4995.8  885.15  5013.9  894.26  5018.2  899.70  5054.7  900.69
  5060.4  896.95  5076.5  901.52  5082.2  899.92  5098.3  900.31  5104.0  898.51
  5120.2  900.72  5149.5  898.95  5158.1  900.74  5163.8  898.82  5179.9  902.13
  5220.3  902.20  5310.8  902.33  5392.4  906.08  5452.1  911.54  5486.2  912.21
#Mann=5,-1,0
  4626.2    0.05       0  4991.6   0.033       0  4995.8    0.05       0
  5013.9    0.12       0  5220.3    0.05       0
Bank Sta=4991.6,4995.8
Exp/Cntr=0.3,0.1

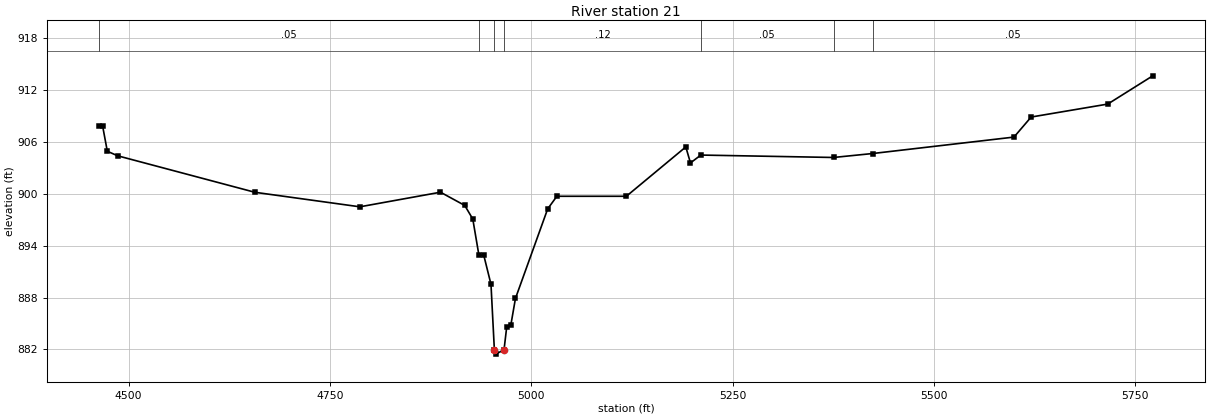
Type RM Length L Ch R = 1,21,0,0,0
BEGIN DESCRIPTION:
UDS St 49 0.8
END DESCRIPTION:
XS GIS Cut Line= 4
      2230863.28      7205512.88      2230891.83      7205040.36
      2230804.83      7205027.53      2230165.74      7205413.65
#Sta/Elev= 30
  4463.6  907.90  4467.6  907.90  4473.5  904.94  4486.5  904.41  4656.8  900.19
  4787.1  898.51  4887.2  900.20  4917.3  898.67  4927.3  897.10  4934.9  892.92
  4940.9  892.92  4949.9  889.54  4954.1  881.96  4955.7  881.46  4966.1  881.96
  4969.4  884.58  4974.5  884.80  4980.3  887.91  5020.3  898.27  5031.7  899.73
  5118.0  899.73  5191.8  905.44  5197.6  903.59  5210.5  904.50  5375.2  904.22
  5424.0  904.68  5599.3  906.58  5620.6  908.90  5715.7  910.40  5771.6  913.67
#Mann=7,-1,0
  4463.6    0.05       0  4934.9    0.12       0  4954.1    0.07       0
  4966.1    0.12       0  5210.5    0.05       0  5375.2    0.12       0
  5424.0    0.05       0
Bank Sta=4954.1,4966.1
Exp/Cntr=0.3,0.1

Chan Stop Cuts=-1