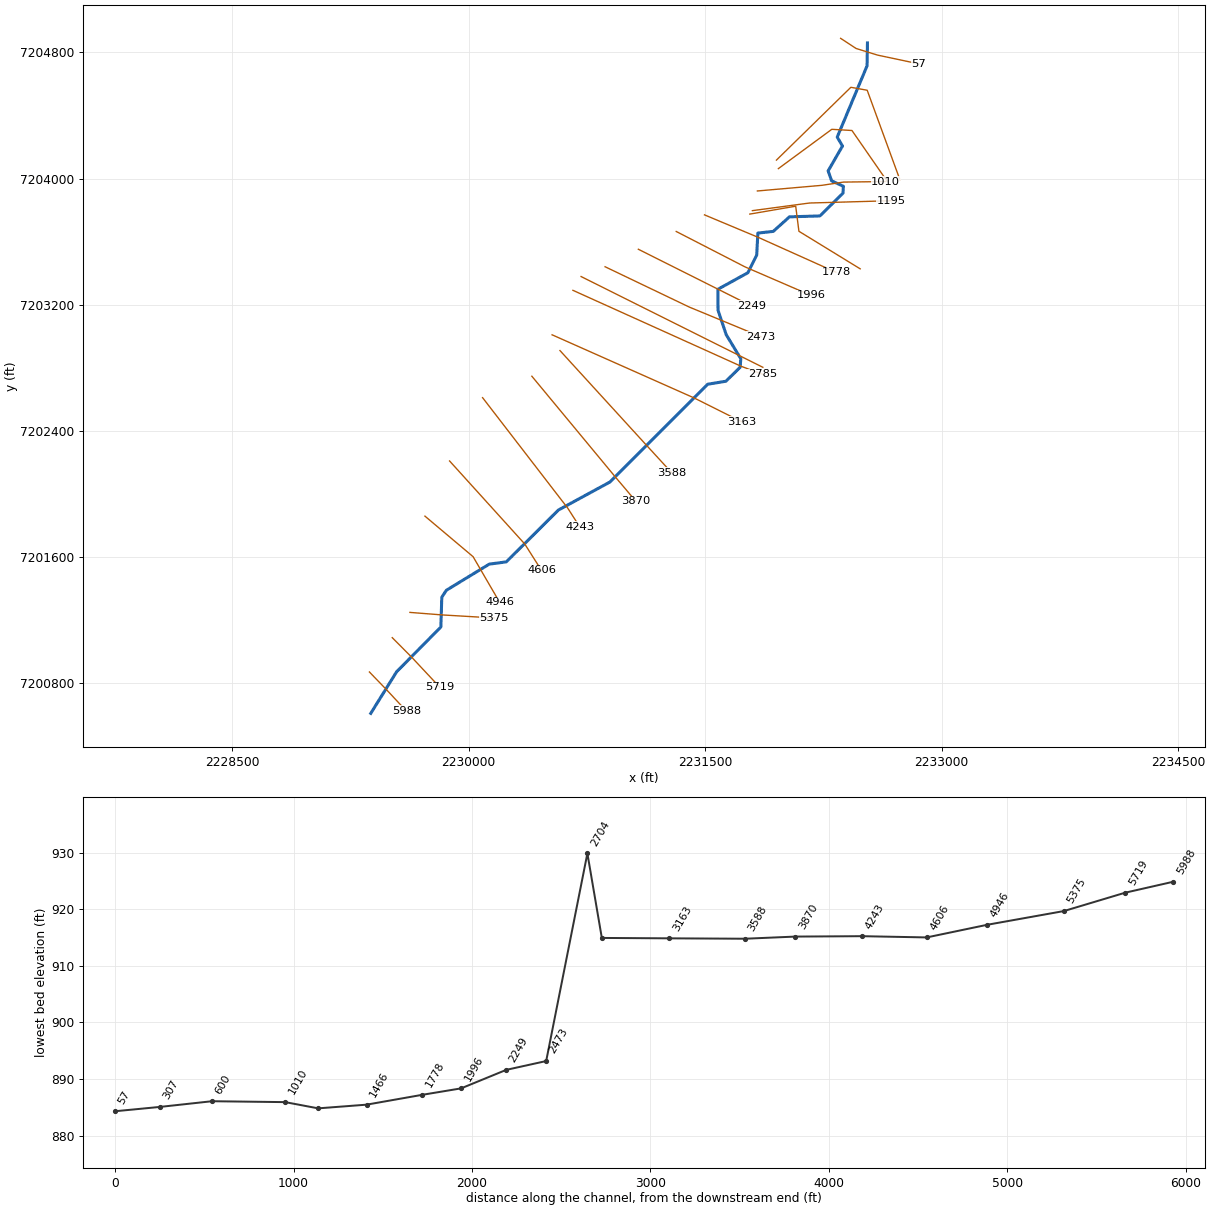
--- UDS St 50.prj (project) ---

Proj Title=UDS St 50 Base Level Engineering
Current Plan=p01
Default Exp/Contr=0.3,0.1
English Units
Geom File=g01
Flow File=f01
Plan File=p01
BEGIN DESCRIPTION:
UDS St 50
END DESCRIPTION:

--- UDS St 50.p01 (plan) ---

Plan Title=Multiple Run
Short Identifier=Multiple
Geom File=g01
Flow File=f01
Subcritical Flow
K Sum by GR= 0
Std Step Tol= 0.01
Critical Tol= 0.01
Num of Std Step Trials= 20
Max Error Tol= 0.3
Flow Tol Ratio= 0.001
Split Flow NTrial= 30
Split Flow Tol= 0.02
Split Flow Ratio= 0.02
Log Output Level= 0
Friction Slope Method= 1
Unsteady Friction Slope Method= 2
Unsteady Bridges Friction Slope Method= 1
Parabolic Critical Depth
Global Vel Dist=  1 , 1 , 1
Global Log Level= 0
CheckData=True
Encroach Param= -1, 0, 0, 0
BEGIN DESCRIPTION:
Multiple Run
END DESCRIPTION:

--- UDS St 50.f01 (steady flow) ---

Flow Title=Multiple
Number of Profiles=7
Profile Names=10-year,25-year,50-year,1pct_min,100-year,1pct_plu,500-year
River Rch & RM= UDS St 50,Reach-1,5988
     630     879    1088     670    1336    2666    2019
River Rch & RM= UDS St 50,Reach-1,1996
     658     916    1132     695    1386    2766    2085
River Rch & RM= UDS St 50,Reach-1,600
     717    1007    1250     771    1539    3071    2339
Boundary for River Rch & Prof#=UDS St 50,Reach-1,1
Up Type=0
Dn Type=3
Dn Slope=0.005
Boundary for River Rch & Prof#=UDS St 50,Reach-1,2
Up Type=0
Dn Type=3
Dn Slope=0.005
Boundary for River Rch & Prof#=UDS St 50,Reach-1,3
Up Type=0
Dn Type=3
Dn Slope=0.005
Boundary for River Rch & Prof#=UDS St 50,Reach-1,4
Up Type=0
Dn Type=3
Dn Slope=0.005
Boundary for River Rch & Prof#=UDS St 50,Reach-1,5
Up Type=0
Dn Type=3
Dn Slope=0.005
Boundary for River Rch & Prof#=UDS St 50,Reach-1,6
Up Type=0
Dn Type=3
Dn Slope=0.005
Boundary for River Rch & Prof#=UDS St 50,Reach-1,7
Up Type=0
Dn Type=3
Dn Slope=0.005

--- UDS St 50.g01 (geometry) ---

Geom Title=Existing Conditions

River Reach=UDS St 50,Reach-1
Reach XY= 30
      2229379.00      7200610.00      2229542.63      7200873.21
      2229823.54      7201157.55      2229829.48      7201346.27
      2229858.42      7201390.41      2230130.59      7201556.17
      2230238.79      7201570.52      2230569.32      7201899.22
      2230895.68      7202076.64      2231515.70      7202696.60
      2231631.44      7202715.52      2231721.53      7202803.93
      2231725.69      7202858.26      2231632.83      7203011.58
      2231581.25      7203165.95      2231580.83      7203298.87
      2231770.98      7203403.66      2231826.63      7203515.53
      2231834.04      7203654.92      2231931.36      7203665.57
      2232034.45      7203757.82      2232227.54      7203763.54
      2232374.07      7203908.04      2232376.38      7203951.49
      2232301.70      7203986.21      2232279.69      7204049.25
      2232370.76      7204206.77      2232337.28      7204263.22
      2232526.66      7204715.51      2232529.00      7204860.00

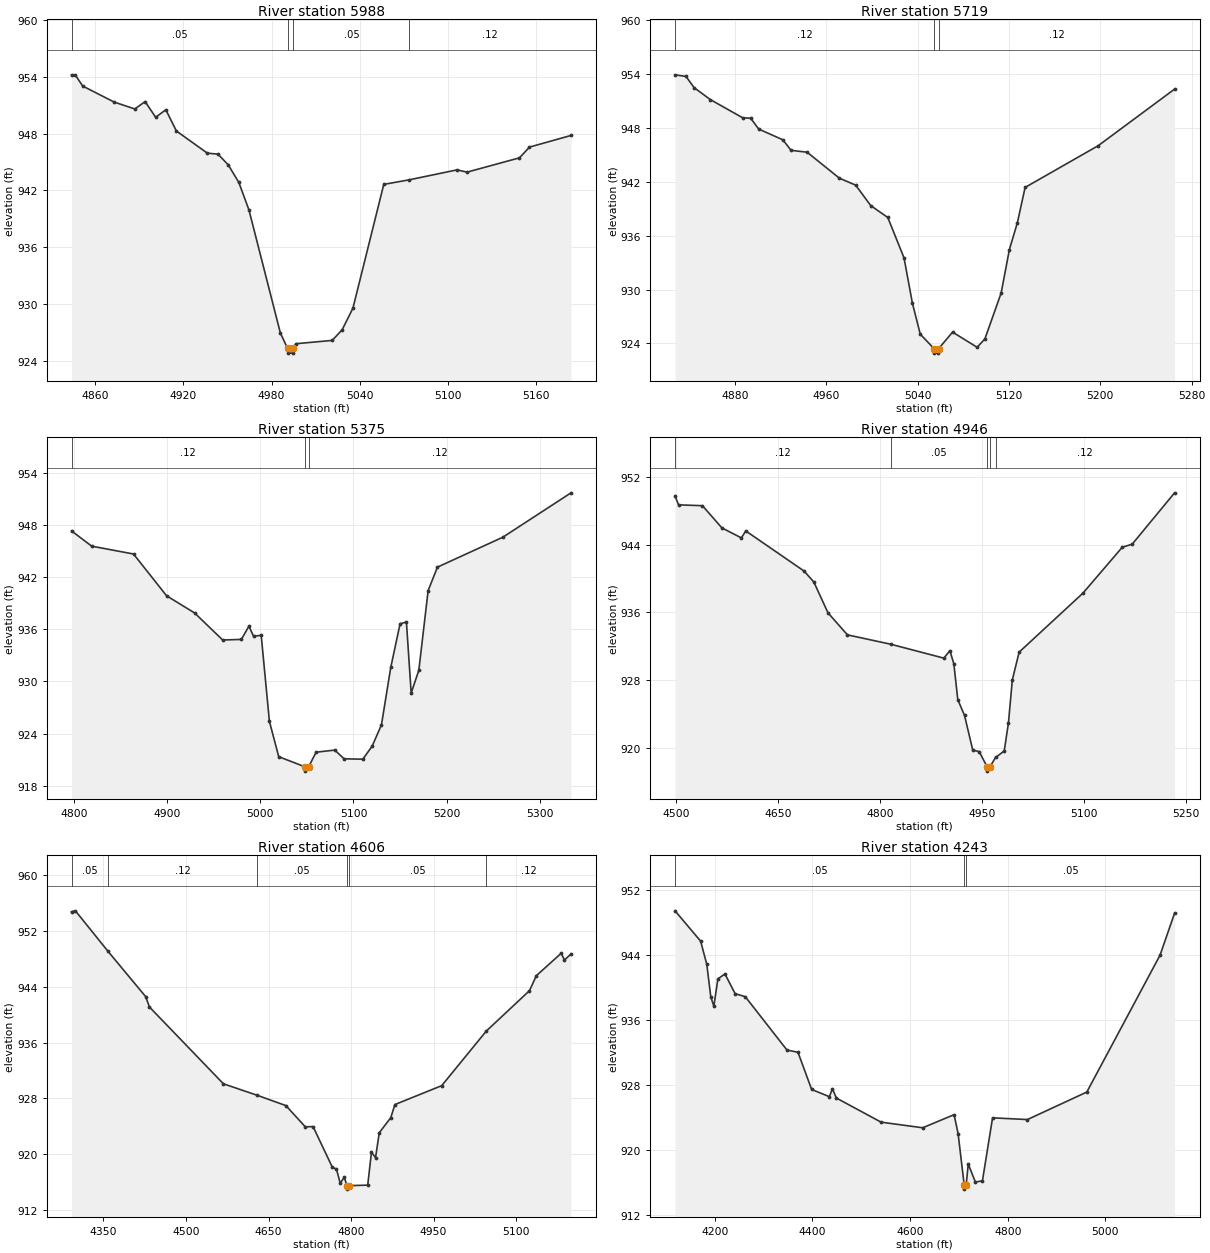
Type RM Length L Ch R = 1,5988,269,269,269
BEGIN DESCRIPTION:
UDS St 50 15.0
END DESCRIPTION:
XS GIS Cut Line= 3
      2229370.51      7200872.38      2229479.00      7200760.00
      2229604.37      7200625.46
#Sta/Elev= 30
  4843.8  954.19  4846.3  954.19  4851.4  953.01  4872.8  951.32  4886.9  950.59
  4893.9  951.37  4901.1  949.71  4908.0  950.51  4915.2  948.27  4936.3  945.93
  4943.5  945.83  4950.5  944.70  4957.7  942.85  4964.6  939.95  4986.0  926.97
  4990.9  925.35  4991.2  924.85  4994.7  924.85  4994.9  925.35  4996.5  925.84
  5021.3  926.19  5028.1  927.32  5035.4  929.59  5056.4  942.64  5073.7  943.12
  5106.3  944.17  5113.1  943.93  5148.8  945.44  5155.6  946.57  5183.9  947.80
#Mann=4,-1,0
  4843.8    0.05       0  4990.9   0.033       0  4994.9    0.05       0
  5073.7    0.12       0
Bank Sta=4990.9,4994.9
Exp/Cntr=0.3,0.1

Type RM Length L Ch R = 1,5719,344,344,344
BEGIN DESCRIPTION:
UDS St 50 14.0
END DESCRIPTION:
XS GIS Cut Line= 3
      2229515.42      7201089.97      2229638.40      7200966.30
      2229817.99      7200774.45
#Sta/Elev= 30
  4827.8  953.92  4837.4  953.74  4844.4  952.50  4858.6  951.17  4886.9  949.14
  4894.0  949.08  4901.0  947.88  4922.2  946.68  4929.3  945.51  4943.4  945.30
  4971.7  942.40  4985.9  941.63  4999.1  939.35  5014.0  938.03  5028.2  933.53
  5035.5  928.51  5042.4  925.03  5054.5  923.42  5054.8  922.92  5058.3  922.92
  5058.5  923.42  5070.7  925.26  5092.2  923.57  5099.0  924.51  5113.2  929.61
  5120.4  934.44  5127.4  937.44  5134.2  941.38  5198.2  946.03  5265.0  952.33
#Mann=3,-1,0
  4827.8    0.12       0  5054.5    0.07       0  5058.5    0.12       0
Bank Sta=5054.5,5058.5
Exp/Cntr=0.3,0.1

Type RM Length L Ch R = 1,5375,429,429,429
BEGIN DESCRIPTION:
UDS St 50 13.0
END DESCRIPTION:
XS GIS Cut Line= 3
      2229627.35      7201250.19      2229826.43      7201234.50
      2230162.05      7201214.72
#Sta/Elev= 30
  4797.5  947.32  4819.2  945.56  4864.0  944.66  4899.5  939.85  4929.6  937.87
  4959.7  934.76  4979.7  934.83  4987.8  936.35  4992.8  935.20  5001.0  935.30
  5009.8  925.40  5019.8  921.33  5047.9  920.17  5048.1  919.67  5051.9  920.17
  5059.9  921.85  5079.9  922.09  5089.9  921.09  5110.0  921.04  5120.0  922.54
  5130.0  924.99  5140.0  931.61  5150.0  936.63  5156.8  936.83  5161.9  928.65
  5170.1  931.28  5180.1  940.45  5190.1  943.15  5260.2  946.59  5333.4  951.70
#Mann=3,-1,0
  4797.5    0.12       0  5047.9    0.07       0  5051.9    0.12       0
Bank Sta=5047.9,5051.9
Exp/Cntr=0.3,0.1

Type RM Length L Ch R = 1,4946,340,340,340
BEGIN DESCRIPTION:
UDS St 50 12.0
END DESCRIPTION:
XS GIS Cut Line= 3
      2229722.61      7201860.46      2230028.15      7201603.23
      2230196.65      7201313.46
#Sta/Elev= 30
  4498.8  949.76  4503.9  948.69  4539.1  948.59  4567.7  945.97  4596.3  944.79
  4602.8  945.61  4688.6  940.87  4702.9  939.58  4723.7  935.94  4752.3  933.34
  4816.2  932.23  4894.1  930.59  4903.0  931.48  4908.8  929.91  4914.6  925.69
  4924.5  923.83  4936.6  919.73  4946.0  919.56  4957.8  917.75  4958.0  917.25
  4961.8  917.75  4970.1  918.86  4982.9  919.63  4989.1  922.95  4994.8  928.02
  5004.8  931.30  5098.6  938.26  5156.4  943.68  5171.1  944.05  5233.4  950.11
#Mann=5,-1,0
  4498.8    0.12       0  4816.2    0.05       0  4957.8    0.07       0
  4961.8    0.05       0  4970.1    0.12       0
Bank Sta=4957.8,4961.8
Exp/Cntr=0.3,0.1

Type RM Length L Ch R = 1,4606,363,363,363
BEGIN DESCRIPTION:
UDS St 50 11.0
END DESCRIPTION:
XS GIS Cut Line= 3
      2229879.00      7202210.00      2230355.65      7201683.83
      2230461.56      7201516.73
#Sta/Elev= 30
  4292.0  954.76  4299.1  954.89  4358.3  949.09  4426.8  942.59  4433.6  941.11
  4568.1  930.10  4629.7  928.45  4681.6  926.98  4716.8  923.94  4731.0  923.97
  4766.1  918.13  4773.5  917.88  4780.3  915.86  4787.7  916.71  4792.5  915.51
  4792.7  915.01  4796.5  915.51  4830.3  915.58  4837.1  920.31  4844.5  919.52
  4851.3  923.09  4872.2  925.25  4879.7  927.13  4964.8  929.84  5045.8  937.66
  5124.3  943.45  5136.7  945.59  5181.9  948.81  5187.8  947.84  5199.8  948.71
#Mann=6,-1,0
  4292.0    0.05       0  4358.3    0.12       0  4629.7    0.05       0
  4792.5   0.033       0  4796.5    0.05       0  5045.8    0.12       0
Bank Sta=4792.5,4796.5
Exp/Cntr=0.3,0.1

Type RM Length L Ch R = 1,4243,373,373,373
BEGIN DESCRIPTION:
UDS St 50 10.0
END DESCRIPTION:
XS GIS Cut Line= 3
      2230088.17      7202611.49      2230629.00      7201910.00
      2230702.93      7201794.50
#Sta/Elev= 30
  4118.8  949.43  4171.2  945.70  4183.8  942.85  4192.0  938.85  4198.3  937.71
  4206.5  941.07  4221.0  941.67  4241.8  939.25  4262.6  938.88  4348.0  932.32
  4370.5  932.05  4398.5  927.48  4434.8  926.59  4441.1  927.57  4449.0  926.43
  4540.7  923.46  4625.9  922.77  4690.2  924.38  4698.4  922.06  4710.9  915.73
  4711.1  915.23  4714.9  915.73  4719.2  918.31  4733.7  916.11  4748.2  916.24
  4769.0  923.99  4840.4  923.78  4962.0  927.16  5112.0  943.99  5141.7  949.14
#Mann=3,-1,0
  4118.8    0.05       0  4710.9   0.033       0  4714.9    0.05       0
Bank Sta=4710.9,4714.9
Exp/Cntr=0.3,0.1

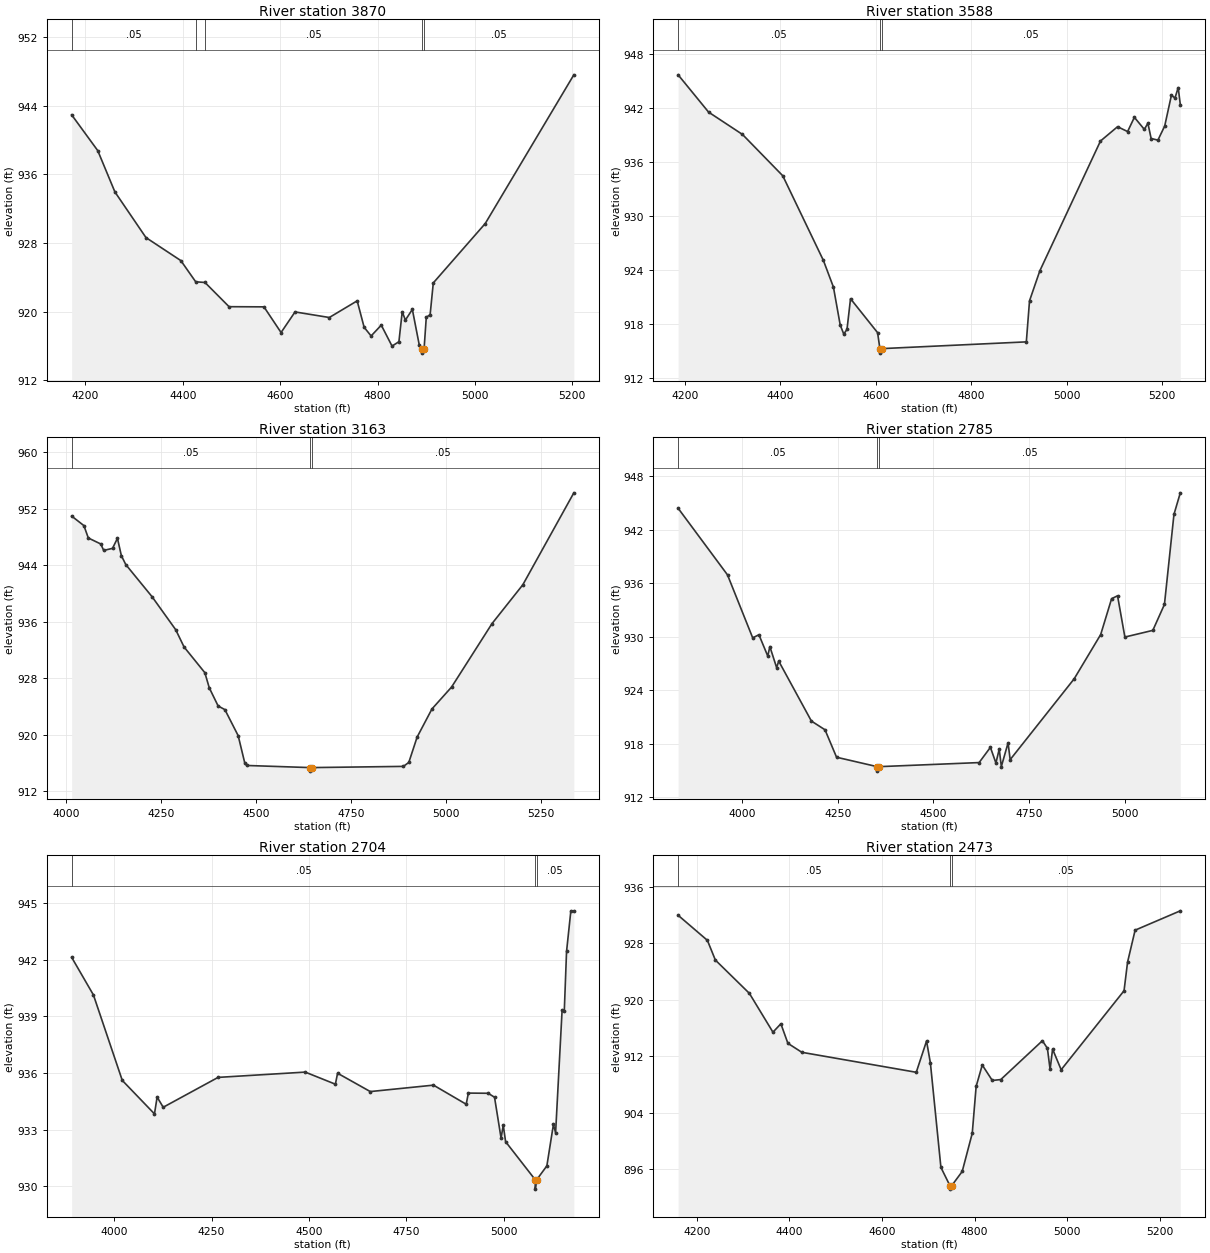
Type RM Length L Ch R = 1,3870,282,282,282
BEGIN DESCRIPTION:
UDS St 50 9.0
END DESCRIPTION:
XS GIS Cut Line= 3
      2230400.68      7202747.38      2230929.00      7202110.00
      2231060.34      7201954.78
#Sta/Elev= 30
  4171.9  942.92  4225.5  938.75  4260.7  933.94  4324.5  928.62  4396.1  925.94
  4426.6  923.47  4445.7  923.39  4495.1  920.57  4566.8  920.55  4601.9  917.56
  4630.6  919.96  4701.0  919.31  4758.2  921.25  4772.5  918.17  4786.8  917.16
  4807.7  918.42  4829.8  915.98  4843.9  916.49  4850.7  919.98  4857.2  919.01
  4871.5  920.25  4885.8  916.08  4891.6  915.66  4891.9  915.16  4895.6  915.66
  4900.1  919.33  4908.0  919.64  4914.5  923.34  5021.2  930.26  5203.1  947.58
#Mann=5,-1,0
  4171.9    0.05       0  4426.6    0.12       0  4445.7    0.05       0
  4891.6   0.033       0  4895.6    0.05       0
Bank Sta=4891.6,4895.6
Exp/Cntr=0.3,0.1

Type RM Length L Ch R = 1,3588,425,425,425
BEGIN DESCRIPTION:
UDS St 50 8.0
END DESCRIPTION:
XS GIS Cut Line= 3
      2230579.00      7202910.00      2231127.34      7202310.04
      2231289.03      7202134.03
#Sta/Elev= 30
  4186.0  945.68  4249.8  941.54  4320.8  939.06  4405.2  934.47  4490.3  925.07
  4511.3  922.11  4525.5  917.90  4532.9  916.90  4539.7  917.41  4547.1  920.82
  4603.8  917.05  4608.6  915.28  4608.8  914.78  4612.6  915.28  4915.3  916.03
  4922.0  920.59  4943.6  923.92  5070.6  938.33  5106.4  939.92  5127.4  939.38
  5141.6  940.96  5162.5  939.62  5169.9  940.31  5176.7  938.61  5190.9  938.43
  5205.1  939.99  5219.2  943.42  5226.6  943.10  5233.4  944.26  5237.8  942.38
#Mann=3,-1,0
  4186.0    0.05       0  4608.6   0.033       0  4612.6    0.05       0
Bank Sta=4608.6,4612.6
Exp/Cntr=0.3,0.1

Type RM Length L Ch R = 1,3163,378,378,378
BEGIN DESCRIPTION:
UDS St 50 7.0
END DESCRIPTION:
XS GIS Cut Line= 3
      2230528.98      7203010.01      2231429.00      7202610.00
      2231728.98      7202460.01
#Sta/Elev= 30
  4015.1  950.94  4047.3  949.59  4058.9  947.84  4091.7  946.99  4099.3  946.08
  4122.5  946.37  4135.5  947.79  4145.8  945.34  4157.4  944.08  4226.5  939.53
  4288.7  934.86  4310.6  932.42  4365.3  928.78  4376.9  926.64  4400.2  924.07
  4418.0  923.55  4452.9  919.87  4470.0  916.06  4475.4  915.65  4641.7  915.35
  4641.9  914.85  4645.7  915.35  4887.2  915.52  4901.5  916.08  4923.4  919.67
  4962.4  923.65  5014.0  926.75  5120.2  935.72  5201.3  941.22  5335.4  954.23
#Mann=3,-1,0
  4015.1    0.05       0  4641.7    0.04       0  4645.7    0.05       0
Bank Sta=4641.7,4645.7
Exp/Cntr=0.3,0.1

Type RM Length L Ch R = 1,2785,81,81,81
BEGIN DESCRIPTION:
UDS St 50 6.0
END DESCRIPTION:
XS GIS Cut Line= 3
      2230661.20      7203291.93      2231729.00      7202810.00
      2231862.29      7202760.24
#Sta/Elev= 30
  3832.0  944.43  3961.2  936.95  4027.1  929.88  4043.4  930.23  4066.5  927.84
  4072.0  928.90  4089.7  926.54  4095.2  927.27  4180.7  920.54  4216.3  919.56
  4246.5  916.48  4353.0  915.42  4353.3  914.92  4357.0  915.42  4619.5  915.88
  4649.0  917.59  4663.4  915.83  4672.1  917.39  4677.6  915.43  4695.2  918.09
  4700.7  916.21  4868.1  925.28  4937.5  930.25  4966.1  934.28  4981.6  934.60
  5000.8  929.97  5073.9  930.72  5104.3  933.63  5129.2  943.74  5145.8  946.16
#Mann=3,-1,0
  3832.0    0.05       0  4353.0   0.033       0  4357.0    0.05       0
Bank Sta=4353,4357
Exp/Cntr=0.3,0.1

Type RM Length L Ch R = 1,2704,231,231,231
BEGIN DESCRIPTION:
UDS St 50 5.1
END DESCRIPTION:
XS GIS Cut Line= 2
      2230712.80      7203379.34      2231865.70      7202803.98
#Sta/Elev= 30
  3891.0  942.12  3946.9  940.13  4020.9  935.61  4103.5  933.84  4110.3  934.73
  4125.9  934.19  4266.7  935.77  4490.3  936.05  4567.7  935.41  4573.3  935.99
  4657.2  935.02  4819.4  935.36  4903.3  934.35  4908.9  934.94  4959.7  934.93
  4976.0  934.72  4992.8  932.56  4998.4  933.24  5004.4  932.37  5080.3  930.36
  5080.6  929.86  5084.3  930.36  5110.3  931.09  5127.1  933.28  5132.7  932.84
  5149.4  939.33  5155.0  939.28  5160.8  942.43  5171.8  944.57  5179.5  944.58
#Mann=3,-1,0
  3891.0    0.05       0  5080.3   0.033       0  5084.3    0.05       0
Bank Sta=5080.3,5084.3
Exp/Cntr=0.3,0.1

Type RM Length L Ch R = 1,2473,224,224,224
BEGIN DESCRIPTION:
UDS St 50 5.0
END DESCRIPTION:
XS GIS Cut Line= 3
      2230865.11      7203441.41      2231398.57      7203186.06
      2231854.26      7202997.73
#Sta/Elev= 30
  4159.6  931.95  4222.8  928.40  4240.0  925.61  4313.5  920.89  4364.4  915.39
  4381.5  916.58  4396.7  913.81  4426.8  912.54  4673.9  909.71  4696.1  914.14
  4704.4  911.03  4727.1  896.24  4746.5  893.66  4746.7  893.16  4750.5  893.66
  4773.1  895.66  4794.8  901.07  4803.2  907.71  4816.4  910.74  4838.1  908.55
  4856.4  908.68  4946.3  914.18  4957.1  913.10  4962.9  910.11  4968.3  912.99
  4986.8  910.07  5122.6  921.26  5130.2  925.31  5146.5  929.84  5244.1  932.58
#Mann=3,-1,0
  4159.6    0.05       0  4746.5   0.033       0  4750.5    0.05       0
Bank Sta=4746.5,4750.5
Exp/Cntr=0.3,0.1

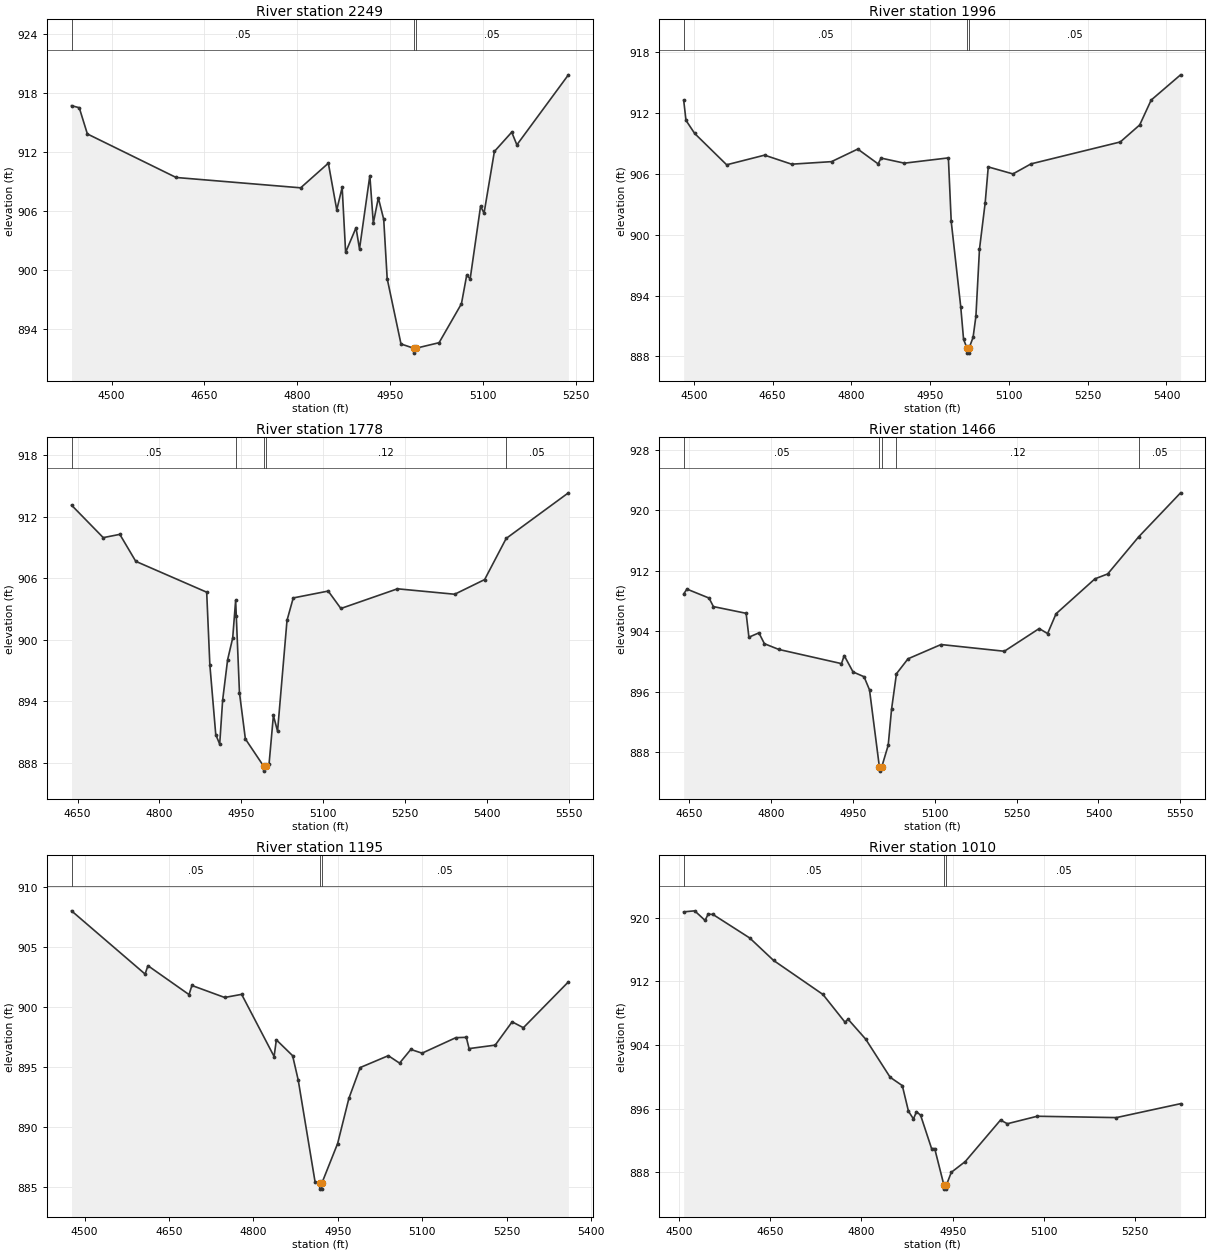
Type RM Length L Ch R = 1,2249,253,253,253
BEGIN DESCRIPTION:
UDS St 50 4.1
END DESCRIPTION:
XS GIS Cut Line= 2
      2231076.14      7203552.24      2231793.41      7203192.78
#Sta/Elev= 30
  4435.3  916.72  4447.8  916.51  4460.9  913.85  4604.2  909.43  4805.3  908.38
  4850.0  910.88  4863.6  906.14  4872.3  908.43  4877.9  901.83  4894.7  904.33
  4900.3  902.17  4917.0  909.62  4922.6  904.79  4930.7  907.36  4939.4  905.18
  4945.0  899.16  4967.3  892.53  4987.7  892.10  4987.9  891.60  4991.7  892.10
  5028.8  892.66  5064.9  896.61  5073.4  899.51  5079.0  899.14  5095.8  906.52
  5101.4  905.80  5118.1  912.07  5146.1  914.03  5154.4  912.74  5237.6  919.85
#Mann=3,-1,0
  4435.3    0.05       0  4987.7   0.033       0  4991.7    0.05       0
Bank Sta=4987.7,4991.7
Exp/Cntr=0.3,0.1

Type RM Length L Ch R = 1,1996,218,218,218
BEGIN DESCRIPTION:
UDS St 50 4.0
END DESCRIPTION:
XS GIS Cut Line= 3
      2231316.25      7203665.02      2231753.66      7203440.05
      2232170.42      7203259.92
#Sta/Elev= 30
  4480.9  913.27  4485.3  911.28  4501.8  909.99  4562.7  906.90  4634.9  907.85
  4686.4  906.96  4762.3  907.21  4812.3  908.45  4851.0  906.99  4856.7  907.56
  4901.0  907.06  4984.8  907.58  4990.2  901.31  5008.3  892.91  5013.7  889.69
  5020.2  888.83  5020.4  888.33  5023.9  888.33  5024.2  888.83  5031.8  889.88
  5037.2  891.97  5044.0  898.58  5054.9  903.18  5060.7  906.69  5107.7  906.00
  5142.1  906.99  5312.0  909.15  5349.0  910.83  5370.8  913.28  5426.8  915.77
#Mann=3,-1,0
  4480.9    0.05       0  5020.2   0.033       0  5024.2    0.05       0
Bank Sta=5020.2,5024.2
Exp/Cntr=0.3,0.1

Type RM Length L Ch R = 1,1778,312,312,312
BEGIN DESCRIPTION:
UDS St 50 3.0
END DESCRIPTION:
XS GIS Cut Line= 3
      2231495.43      7203770.39      2231838.62      7203626.77
      2232328.86      7203406.70
#Sta/Elev= 30
  4639.0  913.13  4697.1  909.96  4727.4  910.28  4756.6  907.65  4886.4  904.64
  4892.2  897.55  4903.0  890.75  4910.2  889.82  4915.6  894.11  4924.7  898.05
  4934.0  900.17  4939.4  903.85  4940.6  902.30  4946.4  894.83  4957.2  890.33
  4990.4  887.69  4990.7  887.19  4994.4  887.69  5000.6  887.91  5008.5  892.62
  5016.1  891.08  5033.4  901.89  5044.8  904.08  5108.8  904.75  5132.0  903.05
  5235.6  904.97  5340.3  904.44  5395.1  905.87  5434.5  909.88  5548.4  914.33
#Mann=5,-1,0
  4639.0    0.05       0  4940.6    0.12       0  4990.4    0.07       0
  4994.4    0.12       0  5434.5    0.05       0
Bank Sta=4990.4,4994.4
Exp/Cntr=0.3,0.1

Type RM Length L Ch R = 1,1466,271,271,271
BEGIN DESCRIPTION:
UDS St 50 2.0
END DESCRIPTION:
XS GIS Cut Line= 4
      2231783.14      7203775.26      2232073.98      7203825.27
      2232094.34      7203666.35      2232482.85      7203428.22
#Sta/Elev= 30
  4639.5  908.93  4645.4  909.58  4686.0  908.39  4694.0  907.26  4754.0  906.37
  4759.1  903.20  4777.4  903.78  4787.5  902.34  4813.9  901.58  4928.8  899.70
  4933.8  900.77  4950.0  898.60  4970.2  897.96  4980.2  896.22  4998.4  885.95
  4998.7  885.45  5002.4  885.95  5014.5  888.89  5020.6  893.64  5029.6  898.36
  5050.8  900.34  5111.3  902.23  5227.4  901.34  5291.3  904.35  5306.7  903.68
  5322.2  906.31  5393.5  910.94  5416.9  911.59  5473.6  916.50  5550.5  922.34
#Mann=5,-1,0
  4639.5    0.05       0  4998.4   0.033       0  5002.4    0.05       0
  5029.6    0.12       0  5473.6    0.05       0
Bank Sta=4998.4,5002.4
Exp/Cntr=0.3,0.1

Type RM Length L Ch R = 1,1195,185,185,185
BEGIN DESCRIPTION:
UDS St 50 1.0
END DESCRIPTION:
XS GIS Cut Line= 3
      2231799.23      7203797.03      2232161.83      7203845.47
      2232679.00      7203860.00
#Sta/Elev= 30
  4476.8  907.99  4607.6  902.72  4612.6  903.42  4685.7  901.01  4690.8  901.77
  4749.0  900.77  4779.2  901.03  4836.9  895.85  4840.9  897.24  4869.8  895.92
  4879.8  893.88  4909.8  885.38  4917.8  885.30  4918.1  884.80  4921.6  884.80
  4921.8  885.30  4949.8  888.60  4969.8  892.36  4989.9  894.93  5039.9  895.92
  5059.9  895.30  5079.9  896.44  5099.9  896.13  5159.9  897.42  5178.5  897.45
  5183.5  896.51  5229.9  896.80  5260.0  898.74  5280.0  898.25  5360.0  902.07
#Mann=3,-1,0
  4476.8    0.05       0  4917.8   0.033       0  4921.8    0.05       0
Bank Sta=4917.8,4921.8
Exp/Cntr=0.3,0.1

Type RM Length L Ch R = 1,1010,410,410,410
BEGIN DESCRIPTION:
UDS St 50 0.9
END DESCRIPTION:
XS GIS Cut Line= 4
      2231830.94      7203921.76      2232239.86      7203957.58
      2232377.62      7203978.20      2232644.62      7203981.47
#Sta/Elev= 30
  4507.7  920.75  4525.8  920.88  4542.9  919.67  4547.9  920.47  4555.9  920.42
  4616.2  917.47  4655.4  914.65  4736.6  910.37  4772.9  906.88  4777.9  907.26
  4806.9  904.75  4847.1  899.96  4867.1  898.91  4877.2  895.69  4885.4  894.72
  4890.4  895.64  4897.2  895.18  4915.2  891.00  4920.3  891.00  4935.5  886.40
  4935.8  885.90  4939.3  885.90  4939.5  886.40  4947.6  888.01  4970.6  889.37
  5028.5  894.58  5039.8  894.12  5088.9  895.06  5218.9  894.89  5324.5  896.64
#Mann=3,-1,0
  4507.7    0.05       0  4935.5   0.033       0  4939.5    0.05       0
Bank Sta=4935.5,4939.5
Exp/Cntr=0.3,0.1

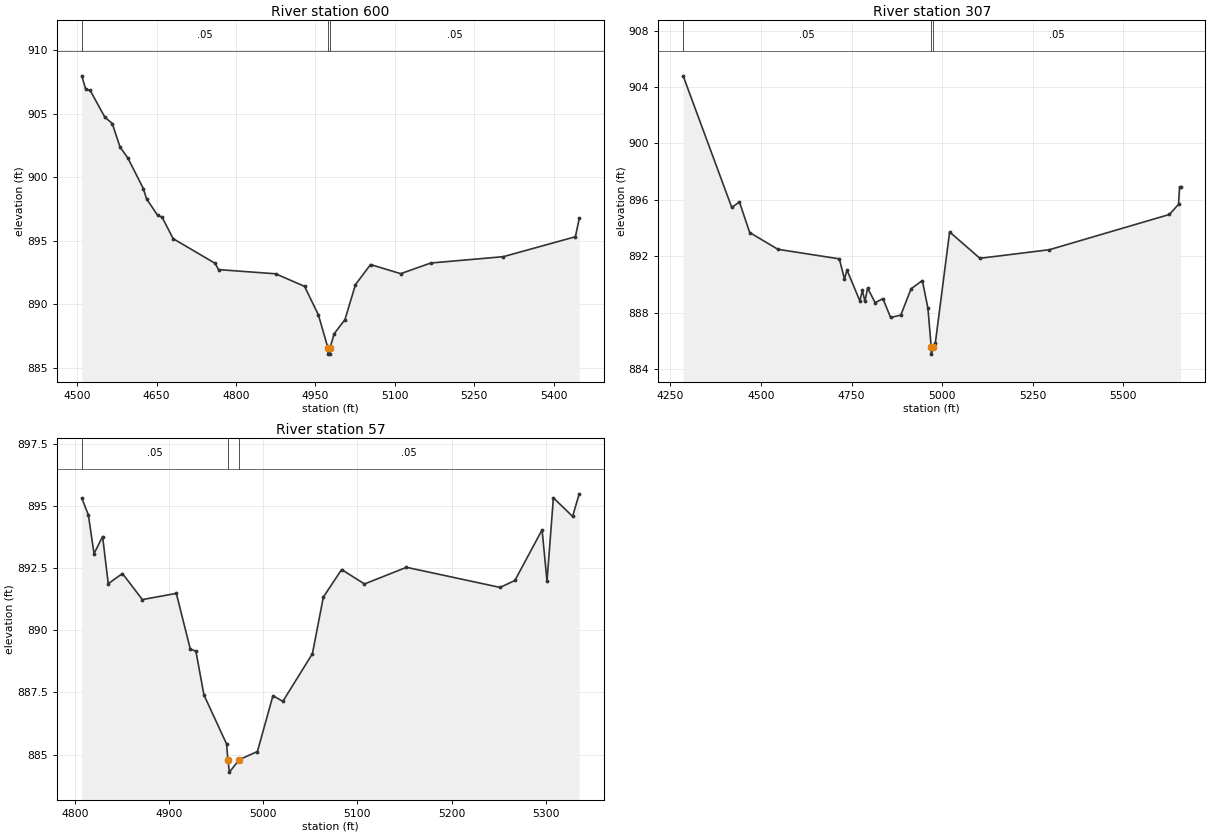
Type RM Length L Ch R = 1,600,293,293,293
BEGIN DESCRIPTION:
UDS St 50 0.8
END DESCRIPTION:
XS GIS Cut Line= 4
      2231964.02      7204063.52      2232302.92      7204312.74
      2232430.75      7204305.13      2232653.35      7203984.08
#Sta/Elev= 30
  4508.7  907.99  4516.1  906.93  4524.6  906.84  4552.1  904.74  4566.3  904.23
  4580.9  902.38  4595.6  901.52  4624.9  899.11  4631.1  898.29  4651.9  897.00
  4660.4  896.85  4681.2  895.16  4760.7  893.21  4766.9  892.72  4874.9  892.39
  4929.4  891.40  4955.5  889.16  4973.5  886.56  4973.8  886.06  4977.3  886.06
  4977.5  886.56  4985.5  887.68  5005.6  888.77  5025.6  891.54  5054.0  893.12
  5111.0  892.40  5167.8  893.24  5304.9  893.74  5440.9  895.31  5448.1  896.75
#Mann=3,-1,0
  4508.7    0.05       0  4973.5   0.033       0  4977.5    0.05       0
Bank Sta=4973.5,4977.5
Exp/Cntr=0.3,0.1

Type RM Length L Ch R = 1,307,250,250,250
BEGIN DESCRIPTION:
UDS St 50 0.7
END DESCRIPTION:
XS GIS Cut Line= 4
      2231951.76      7204117.51      2232423.77      7204579.04
      2232527.37      7204560.41      2232736.00      7203989.99
#Sta/Elev= 30
  4285.3  904.80  4419.5  895.46  4440.7  895.85  4469.0  893.68  4546.8  892.49
  4716.4  891.81  4730.6  890.38  4737.7  891.01  4773.0  888.83  4780.1  889.57
  4787.1  888.79  4794.3  889.74  4815.4  888.70  4836.7  888.99  4857.9  887.65
  4886.1  887.82  4914.4  889.69  4945.5  890.27  4960.9  888.31  4970.0  885.55
  4970.4  885.05  4974.4  885.55  4981.2  885.81  5020.8  893.72  5104.4  891.85
  5296.1  892.46  5627.3  894.96  5652.5  895.68  5655.4  896.92  5658.1  896.92
#Mann=3,-1,0
  4285.3    0.05       0  4970.0   0.033       0  4974.4    0.05       0
Bank Sta=4970,4974.4
Exp/Cntr=0.3,0.1

Type RM Length L Ch R = 1,57,0,0,0
BEGIN DESCRIPTION:
UDS St 50 0.6
END DESCRIPTION:
XS GIS Cut Line= 4
      2232359.02      7204889.46      2232456.67      7204825.31
      2232593.13      7204783.14      2232855.85      7204727.56
#Sta/Elev= 30
  4807.3  895.33  4814.3  894.65  4820.3  893.09  4829.4  893.78  4835.4  891.88
  4850.5  892.29  4871.6  891.24  4907.7  891.49  4922.5  889.25  4928.5  889.16
  4937.0  887.40  4961.1  885.42  4962.4  884.79  4964.1  884.29  4974.4  884.79
  4993.8  885.12  5010.3  887.37  5020.8  887.14  5052.2  889.06  5063.8  891.34
  5083.2  892.45  5107.5  891.87  5152.1  892.54  5251.5  891.73  5267.2  892.01
  5296.1  894.05  5301.3  891.98  5308.1  895.34  5328.5  894.59  5335.5  895.50
#Mann=3,-1,0
  4807.3    0.05       0  4962.4   0.033       0  4974.4    0.05       0
Bank Sta=4962.4,4974.4
Exp/Cntr=0.3,0.1

Chan Stop Cuts=-1