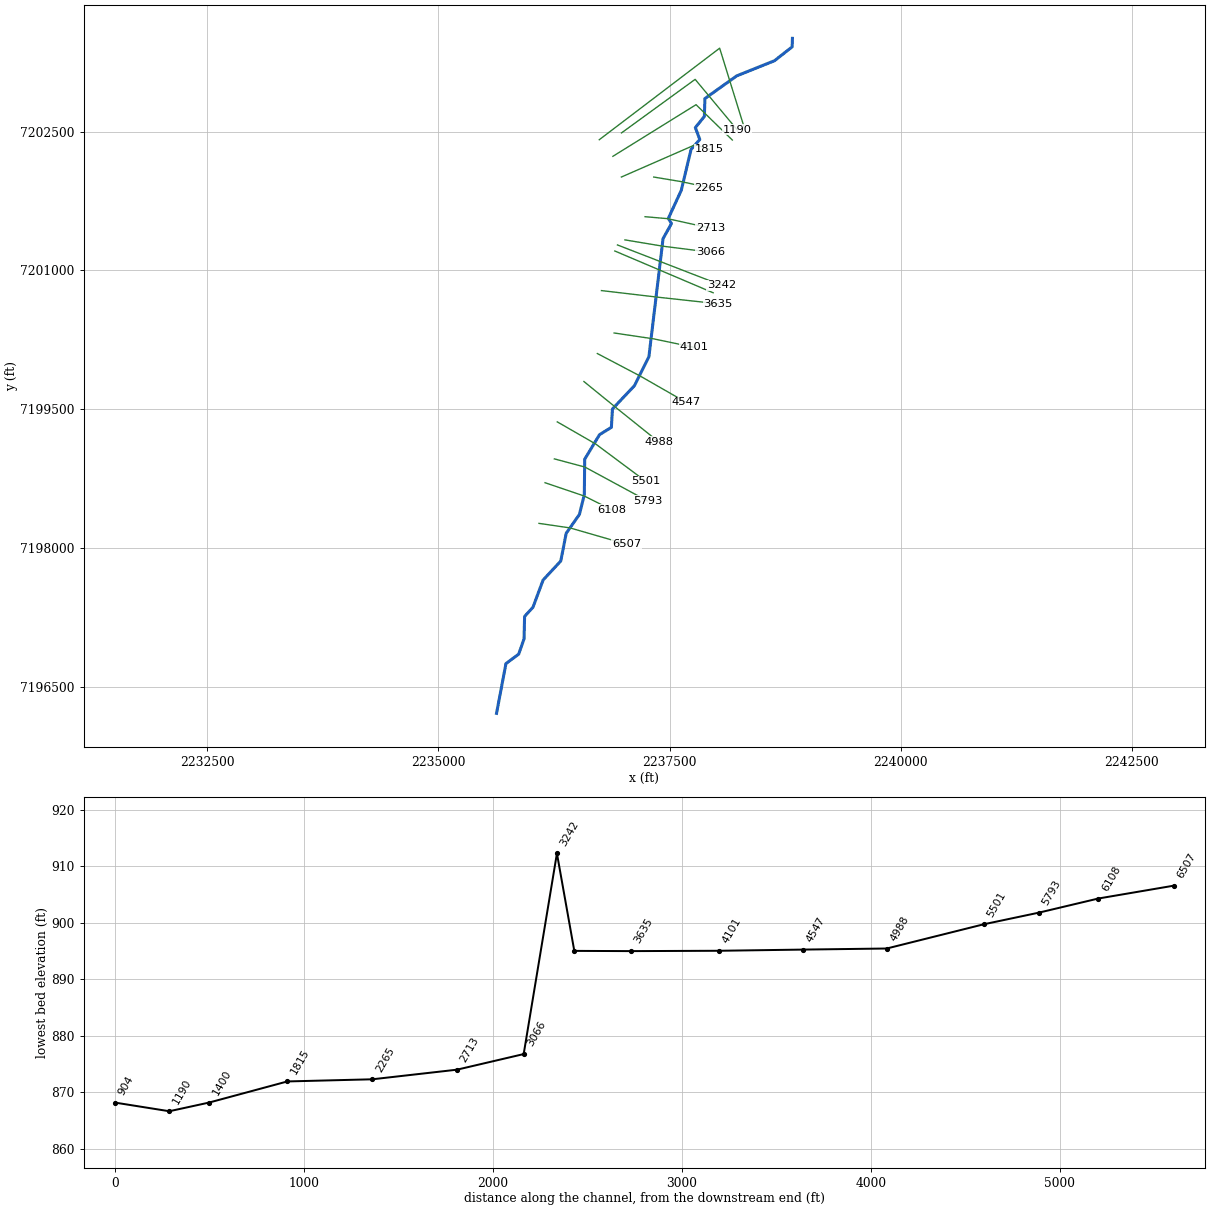
--- UDS St 53.prj (project) ---

Proj Title=UDS St 53 Base Level Engineering
Current Plan=p01
Default Exp/Contr=0.3,0.1
English Units
Geom File=g01
Flow File=f01
Plan File=p01
BEGIN DESCRIPTION:
UDS St 53
END DESCRIPTION:

--- UDS St 53.p01 (plan) ---

Plan Title=Multiple Run
Short Identifier=Multiple
Geom File=g01
Flow File=f01
Subcritical Flow
K Sum by GR= 0
Std Step Tol= 0.01
Critical Tol= 0.01
Num of Std Step Trials= 20
Max Error Tol= 0.3
Flow Tol Ratio= 0.001
Split Flow NTrial= 30
Split Flow Tol= 0.02
Split Flow Ratio= 0.02
Log Output Level= 0
Friction Slope Method= 1
Unsteady Friction Slope Method= 2
Unsteady Bridges Friction Slope Method= 1
Parabolic Critical Depth
Global Vel Dist=  1 , 1 , 1
Global Log Level= 0
CheckData=True
Encroach Param= -1, 0, 0, 0
BEGIN DESCRIPTION:
Multiple Run
END DESCRIPTION:

--- UDS St 53.f01 (steady flow) ---

Flow Title=Multiple
Number of Profiles=7
Profile Names=10-year,25-year,50-year,1pct_min,100-year,1pct_plu,500-year
River Rch & RM= UDS St 53,Reach-1,6507
     747    1051    1310     811    1618    3228    2475
River Rch & RM= UDS St 53,Reach-1,4547
     776    1093    1362     843    1682    3357    2573
River Rch & RM= UDS St 53,Reach-1,3066
     779    1095    1362     841    1679    3350    2558
Boundary for River Rch & Prof#=UDS St 53,Reach-1,1
Up Type=0
Dn Type=3
Dn Slope=0.005
Boundary for River Rch & Prof#=UDS St 53,Reach-1,2
Up Type=0
Dn Type=3
Dn Slope=0.005
Boundary for River Rch & Prof#=UDS St 53,Reach-1,3
Up Type=0
Dn Type=3
Dn Slope=0.005
Boundary for River Rch & Prof#=UDS St 53,Reach-1,4
Up Type=0
Dn Type=3
Dn Slope=0.005
Boundary for River Rch & Prof#=UDS St 53,Reach-1,5
Up Type=0
Dn Type=3
Dn Slope=0.005
Boundary for River Rch & Prof#=UDS St 53,Reach-1,6
Up Type=0
Dn Type=3
Dn Slope=0.005
Boundary for River Rch & Prof#=UDS St 53,Reach-1,7
Up Type=0
Dn Type=3
Dn Slope=0.005

--- UDS St 53.g01 (geometry) ---

Geom Title=Existing Conditions

River Reach=UDS St 53,Reach-1
Reach XY= 30
      2235629.00      7196210.00      2235730.96      7196748.81
      2235868.49      7196850.19      2235926.62      7197015.53
      2235932.55      7197258.53      2236023.15      7197357.71
      2236132.66      7197651.81      2236323.53      7197857.55
      2236382.83      7198158.42      2236525.45      7198361.47
      2236578.48      7198575.22      2236582.55      7198958.53
      2236742.48      7199223.56      2236871.30      7199303.53
      2236882.57      7199501.85      2237120.86      7199753.94
      2237276.75      7200065.93      2237429.95      7201344.04
      2237520.73      7201506.78      2237487.28      7201563.22
      2237626.75      7201865.93      2237732.62      7202308.50
      2237827.37      7202416.04      2237778.96      7202544.66
      2237876.82      7202665.45      2237882.45      7202858.75
      2238226.70      7203104.17      2238635.17      7203267.86
      2238826.01      7203417.82      2238829.00      7203510.00

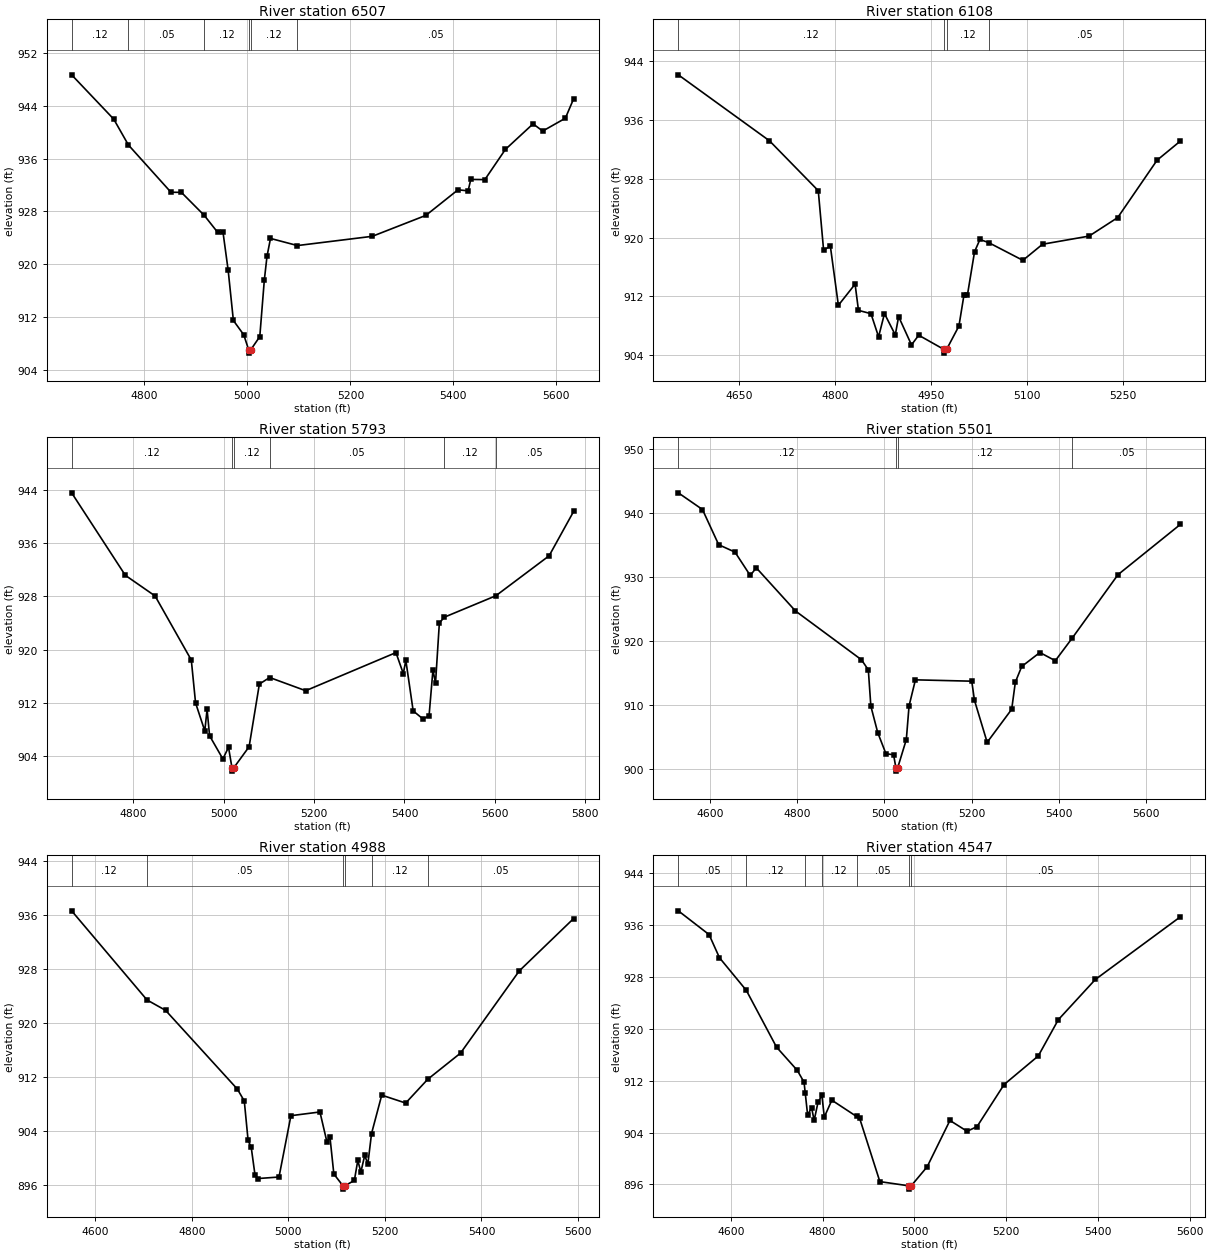
Type RM Length L Ch R = 1,6507,399,399,399
BEGIN DESCRIPTION:
UDS St 53 13.0
END DESCRIPTION:
XS GIS Cut Line= 3
      2236088.09      7198264.82      2236423.98      7198215.67
      2237034.72      7198039.16
#Sta/Elev= 30
  4658.5  948.68  4740.3  941.97  4768.8  938.06  4851.4  930.91  4871.7  930.89
  4916.2  927.40  4942.4  924.82  4952.5  924.88  4962.6  919.08  4972.7  911.50
  4992.9  909.33  5002.4  907.06  5002.6  906.56  5006.4  907.06  5024.0  909.06
  5032.8  917.61  5038.0  921.20  5044.8  923.92  5097.1  922.84  5242.6  924.24
  5346.7  927.41  5409.1  931.28  5428.7  931.12  5433.9  932.85  5461.2  932.82
  5501.1  937.39  5554.9  941.26  5573.6  940.17  5617.6  942.11  5633.7  945.06
#Mann=6,-1,0
  4658.5    0.12       0  4768.8    0.05       0  4916.2    0.12       0
  5002.4    0.07       0  5006.4    0.12       0  5097.1    0.05       0
Bank Sta=5002.4,5006.4
Exp/Cntr=0.3,0.1

Type RM Length L Ch R = 1,6108,315,315,315
BEGIN DESCRIPTION:
UDS St 53 12.0
END DESCRIPTION:
XS GIS Cut Line= 3
      2236154.12      7198704.33      2236579.00      7198560.00
      2236878.97      7198410.01
#Sta/Elev= 30
  4555.4  942.17  4697.8  933.19  4774.0  926.40  4782.3  918.33  4792.9  918.83
  4805.4  910.80  4831.5  913.68  4836.8  910.11  4856.3  909.66  4868.2  906.51
  4877.4  909.67  4894.3  906.77  4899.5  909.26  4919.6  905.41  4930.9  906.73
  4970.4  904.79  4970.7  904.29  4974.4  904.79  4993.7  907.98  5001.5  912.16
  5006.9  912.16  5018.1  918.09  5026.5  919.76  5040.2  919.33  5093.6  916.92
  5124.3  919.11  5197.0  920.22  5241.7  922.74  5303.2  930.55  5339.5  933.15
#Mann=4,-1,0
  4555.4    0.12       0  4970.4    0.07       0  4974.4    0.12       0
  5040.2    0.05       0
Bank Sta=4970.4,4974.4
Exp/Cntr=0.3,0.1

Type RM Length L Ch R = 1,5793,292,292,292
BEGIN DESCRIPTION:
UDS St 53 11.0
END DESCRIPTION:
XS GIS Cut Line= 3
      2236254.34      7198962.30      2236584.02      7198874.14
      2237260.17      7198508.37
#Sta/Elev= 30
  4664.1  943.56  4782.8  931.18  4848.6  928.08  4928.7  918.46  4938.1  912.03
  4958.5  907.83  4963.6  911.05  4969.1  907.10  4998.5  903.62  5011.0  905.37
  5018.6  902.29  5018.9  901.79  5022.6  902.29  5056.5  905.45  5079.2  914.86
  5102.0  915.84  5181.6  913.86  5381.2  919.58  5397.4  916.44  5403.1  918.40
  5419.3  910.83  5441.1  909.61  5454.4  910.08  5463.0  916.98  5468.7  915.00
  5477.2  924.04  5488.4  924.90  5602.1  928.11  5719.9  934.11  5774.1  940.77
#Mann=6,-1,0
  4664.1    0.12       0  5018.6    0.07       0  5022.6    0.12       0
  5102.0    0.05       0  5488.4    0.12       0  5602.1    0.05       0
Bank Sta=5018.6,5022.6
Exp/Cntr=0.3,0.1

Type RM Length L Ch R = 1,5501,513,513,513
BEGIN DESCRIPTION:
UDS St 53 10.0
END DESCRIPTION:
XS GIS Cut Line= 3
      2236285.88      7199362.55      2236699.55      7199124.45
      2237240.97      7198721.18
#Sta/Elev= 30
  4526.8  943.11  4582.2  940.51  4619.5  935.02  4656.9  933.87  4691.9  930.23
  4705.8  931.42  4795.8  924.69  4947.2  917.09  4963.0  915.51  4968.8  909.85
  4984.6  905.73  5003.5  902.43  5021.0  902.29  5026.3  900.23  5026.6  899.73
  5030.3  900.23  5050.2  904.65  5056.5  909.90  5071.1  913.96  5200.4  913.75
  5206.6  910.78  5235.8  904.22  5292.1  909.37  5300.5  913.60  5315.1  916.04
  5356.8  918.22  5392.2  916.94  5431.4  920.50  5536.1  930.35  5679.2  938.18
#Mann=4,-1,0
  4526.8    0.12       0  5026.3    0.07       0  5030.3    0.12       0
  5431.4    0.05       0
Bank Sta=5026.3,5030.3
Exp/Cntr=0.3,0.1

Type RM Length L Ch R = 1,4988,441,441,441
BEGIN DESCRIPTION:
UDS St 53 9.0
END DESCRIPTION:
XS GIS Cut Line= 3
      2236574.14      7199798.69      2236929.00      7199510.00
      2237383.35      7199145.74
#Sta/Elev= 30
  4551.1  936.64  4707.2  923.45  4745.7  921.91  4894.3  910.26  4908.7  908.50
  4916.6  902.66  4923.1  901.62  4931.0  897.49  4937.5  897.02  4980.6  897.24
  5005.3  906.32  5065.4  906.87  5079.8  902.46  5086.2  903.13  5094.2  897.69
  5113.0  895.95  5113.2  895.45  5117.0  895.95  5136.7  896.73  5143.8  899.69
  5150.2  897.99  5158.2  900.46  5164.6  899.14  5172.3  903.68  5193.4  909.36
  5243.0  908.19  5288.7  911.71  5356.6  915.58  5478.3  927.75  5590.9  935.50
#Mann=6,-1,0
  4551.1    0.12       0  4707.2    0.05       0  5113.0   0.033       0
  5117.0    0.05       0  5172.3    0.12       0  5288.7    0.05       0
Bank Sta=5113,5117
Exp/Cntr=0.3,0.1

Type RM Length L Ch R = 1,4547,446,446,446
BEGIN DESCRIPTION:
UDS St 53 8.0
END DESCRIPTION:
XS GIS Cut Line= 3
      2236719.65      7200101.25      2237179.00      7199860.00
      2237677.43      7199574.61
#Sta/Elev= 30
  4485.7  938.22  4552.7  934.55  4575.3  930.98  4633.8  925.94  4699.6  917.18
  4744.8  913.59  4759.5  911.77  4762.0  910.15  4767.3  906.70  4775.9  907.83
  4781.5  905.87  4789.9  908.66  4798.4  909.74  4803.6  906.38  4820.0  908.99
  4873.8  906.48  4880.3  906.25  4924.6  896.42  4988.6  895.76  4988.9  895.26
  4992.7  895.76  5027.6  898.71  5077.2  905.86  5114.6  904.19  5136.2  904.91
  5195.2  911.41  5269.6  915.82  5313.2  921.41  5393.8  927.62  5578.9  937.29
#Mann=7,-1,0
  4485.7    0.05       0  4633.8    0.12       0  4762.0    0.05       0
  4798.4    0.12       0  4873.8    0.05       0  4988.6   0.033       0
  4992.7    0.05       0
Bank Sta=4988.6,4992.7
Exp/Cntr=0.3,0.1

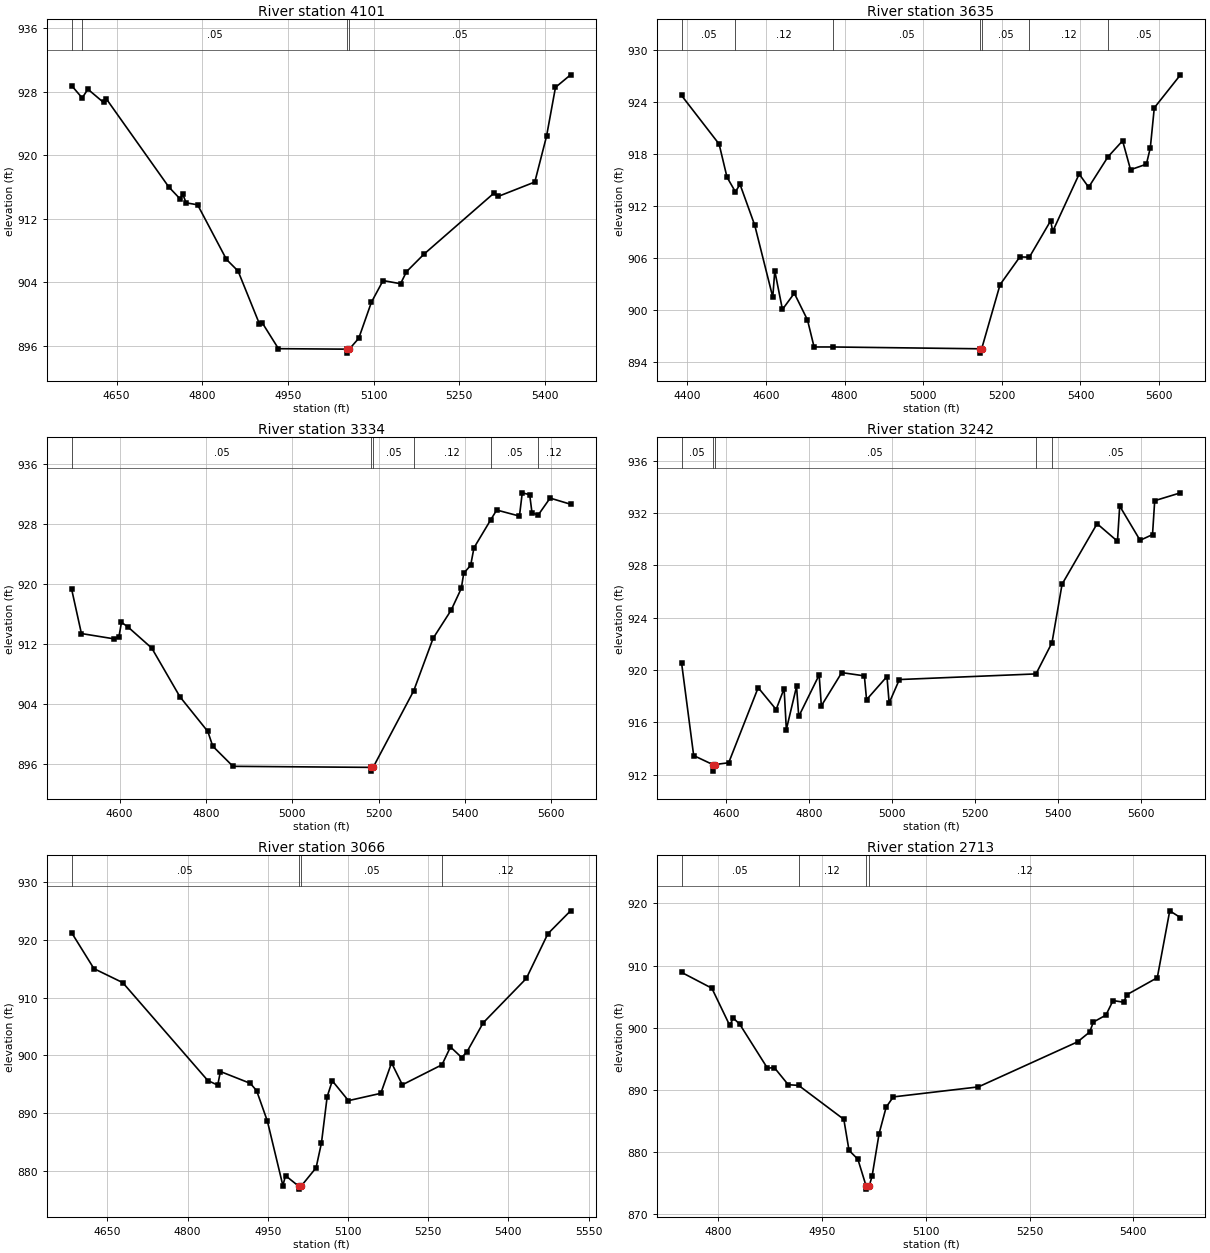
Type RM Length L Ch R = 1,4101,466,466,466
BEGIN DESCRIPTION:
UDS St 53 7.0
END DESCRIPTION:
XS GIS Cut Line= 3
      2236900.79      7200323.52      2237329.00      7200260.00
      2237760.25      7200169.69
#Sta/Elev= 30
  4571.4  928.74  4589.9  927.19  4599.9  928.29  4627.3  926.62  4632.4  927.05
  4741.5  915.98  4761.2  914.48  4766.2  915.04  4771.8  913.98  4792.0  913.73
  4842.5  906.85  4862.8  905.39  4900.1  898.75  4905.2  898.86  4933.5  895.61
  5053.3  895.55  5053.6  895.05  5057.5  895.55  5074.1  896.92  5096.3  901.47
  5116.7  904.19  5147.3  903.79  5157.6  905.30  5188.2  907.51  5310.8  915.20
  5318.7  914.80  5382.3  916.60  5402.8  922.35  5418.5  928.52  5444.9  930.10
#Mann=4,-1,0
  4571.4    0.12       0  4589.9    0.05       0  5053.3   0.033       0
  5057.5    0.05       0
Bank Sta=5053.3,5057.5
Exp/Cntr=0.3,0.1

Type RM Length L Ch R = 1,3635,301,301,301
BEGIN DESCRIPTION:
UDS St 53 6.0
END DESCRIPTION:
XS GIS Cut Line= 3
      2236764.07      7200782.11      2237379.00      7200710.00
      2238025.23      7200639.58
#Sta/Elev= 30
  4385.2  924.72  4480.8  919.11  4500.9  915.29  4522.1  913.61  4534.1  914.45
  4571.4  909.75  4617.3  901.45  4622.4  904.48  4641.9  900.03  4672.1  901.90
  4705.6  898.82  4722.4  895.70  4770.8  895.70  5144.4  895.49  5144.7  894.99
  5148.7  895.49  5195.5  902.89  5245.8  906.09  5270.0  906.06  5324.3  910.27
  5329.3  909.03  5396.7  915.65  5420.8  914.13  5470.0  917.64  5507.2  919.49
  5527.4  916.15  5567.7  916.79  5577.7  918.68  5587.8  923.29  5654.4  927.10
#Mann=7,-1,0
  4385.2    0.05       0  4522.1    0.12       0  4770.8    0.05       0
  5144.4   0.033       0  5148.7    0.05       0  5270.0    0.12       0
  5470.0    0.05       0
Bank Sta=5144.4,5148.7
Exp/Cntr=0.3,0.1

Type RM Length L Ch R = 1,3334,92,92,92
BEGIN DESCRIPTION:
UDS St 53 5.2
END DESCRIPTION:
XS GIS Cut Line= 2
      2236908.13      7201210.39      2237971.95      7200758.27
#Sta/Elev= 30
  4488.8  919.28  4511.5  913.36  4587.5  912.65  4598.4  912.93  4604.3  914.86
  4620.1  914.20  4674.5  911.42  4739.7  904.94  4804.4  900.31  4815.7  898.36
  4862.6  895.67  5183.0  895.53  5183.3  895.03  5187.3  895.53  5281.3  905.73
  5326.4  912.74  5368.1  916.48  5391.6  919.38  5397.2  921.40  5413.3  922.45
  5420.9  924.78  5459.6  928.50  5473.6  929.82  5526.3  929.01  5532.8  932.11
  5550.0  931.86  5555.4  929.44  5569.7  929.15  5597.3  931.41  5644.7  930.59
#Mann=6,-1,0
  4488.8    0.05       0  5183.0   0.033       0  5187.3    0.05       0
  5281.3    0.12       0  5459.6    0.05       0  5569.7    0.12       0
Bank Sta=5183,5187.3
Exp/Cntr=0.3,0.1

Type RM Length L Ch R = 1,3242,176,176,176
BEGIN DESCRIPTION:
UDS St 53 5.1
END DESCRIPTION:
XS GIS Cut Line= 2
      2236936.62      7201275.56      2238058.38      7200841.25
#Sta/Elev= 30
  4491.6  920.57  4520.9  913.46  4567.1  912.77  4567.4  912.27  4571.4  912.77
  4605.3  912.91  4676.4  918.65  4719.7  916.98  4738.9  918.58  4744.3  915.45
  4768.9  918.74  4774.2  916.45  4823.4  919.62  4828.7  917.26  4877.9  919.80
  4932.4  919.55  4937.7  917.73  4986.9  919.50  4992.2  917.48  5016.8  919.27
  5346.2  919.70  5384.7  922.08  5409.1  926.56  5493.5  931.18  5542.6  929.84
  5548.0  932.53  5597.2  929.91  5627.1  930.35  5632.4  932.94  5694.5  933.54
#Mann=5,-1,0
  4491.6    0.05       0  4567.1   0.033       0  4571.4    0.05       0
  5346.2    0.12       0  5384.7    0.05       0
Bank Sta=4567.1,4571.4
Exp/Cntr=0.3,0.1

Type RM Length L Ch R = 1,3066,353,353,353
BEGIN DESCRIPTION:
UDS St 53 5.0
END DESCRIPTION:
XS GIS Cut Line= 3
      2237017.83      7201330.36      2237426.81      7201262.35
      2237941.02      7201197.41
#Sta/Elev= 30
  4583.3  921.24  4625.0  915.01  4678.9  912.58  4837.9  895.61  4856.5  894.81
  4861.5  897.17  4917.4  895.12  4929.2  893.85  4949.4  888.55  4978.3  877.40
  4983.3  879.12  5008.0  877.28  5008.4  876.78  5012.3  877.28  5040.4  880.48
  5050.5  884.82  5061.1  892.80  5070.7  895.56  5100.9  892.12  5161.4  893.39
  5181.5  898.67  5201.7  894.87  5275.8  898.34  5291.7  901.43  5312.6  899.60
  5322.6  900.60  5352.9  905.62  5433.5  913.31  5473.8  921.06  5516.2  925.03
#Mann=4,-1,0
  4583.3    0.05       0  5008.0   0.033       0  5012.3    0.05       0
  5275.8    0.12       0
Bank Sta=5008,5012.3
Exp/Cntr=0.3,0.1

Type RM Length L Ch R = 1,2713,448,448,448
BEGIN DESCRIPTION:
UDS St 53 4.0
END DESCRIPTION:
XS GIS Cut Line= 3
      2237235.38      7201581.09      2237479.00      7201560.00
      2237944.15      7201457.20
#Sta/Elev= 30
  4747.2  908.90  4791.0  906.35  4816.9  900.35  4821.9  901.54  4831.1  900.59
  4871.3  893.49  4881.3  893.57  4901.4  890.82  4916.4  890.71  4981.7  885.25
  4989.2  880.26  5002.0  878.83  5013.9  874.52  5014.3  874.02  5018.3  874.52
  5022.5  876.08  5032.7  882.97  5042.9  887.22  5053.2  888.86  5176.1  890.47
  5319.5  897.72  5337.0  899.31  5342.2  900.90  5360.4  902.02  5370.7  904.36
  5385.8  904.10  5391.1  905.33  5434.6  908.04  5452.6  918.80  5468.1  917.71
#Mann=4,-1,0
  4747.2    0.05       0  4916.4    0.12       0  5013.9    0.07       0
  5018.3    0.12       0
Bank Sta=5013.9,5018.3
Exp/Cntr=0.3,0.1

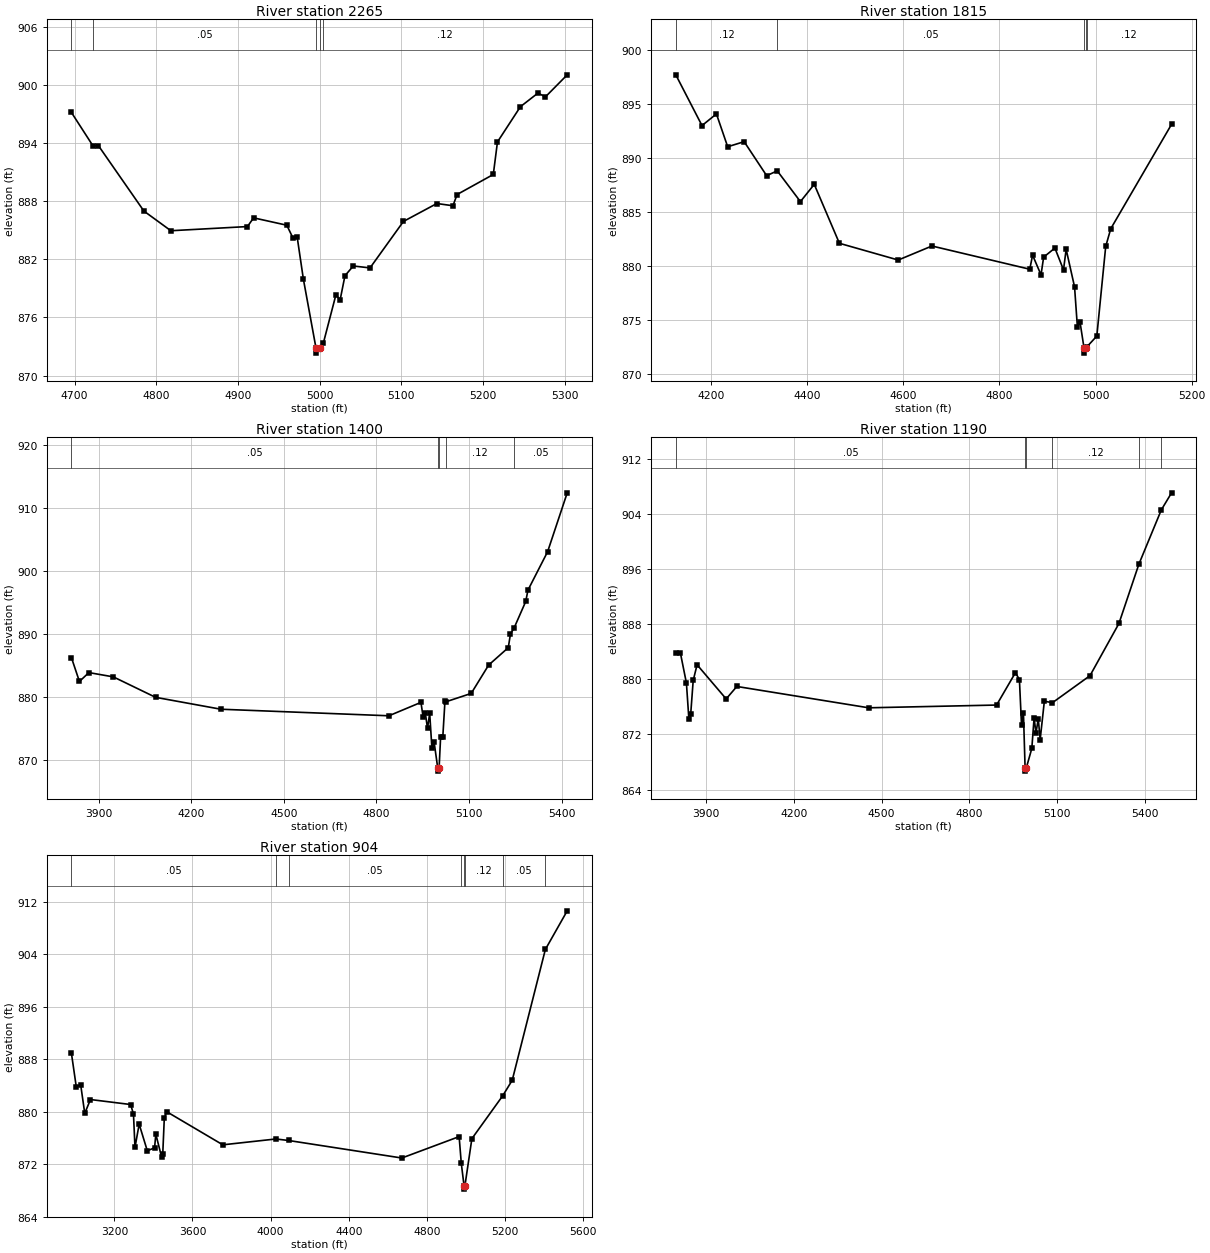
Type RM Length L Ch R = 1,2265,450,450,450
BEGIN DESCRIPTION:
UDS St 53 3.0
END DESCRIPTION:
XS GIS Cut Line= 3
      2237329.00      7202010.00      2237629.00      7201960.00
      2237925.06      7201896.62
#Sta/Elev= 30
  4696.2  897.17  4722.8  893.69  4729.1  893.76  4784.9  886.99  4817.9  884.96
  4911.6  885.39  4919.2  886.29  4959.8  885.53  4967.4  884.20  4972.5  884.32
  4980.1  879.97  4995.6  872.82  4996.0  872.32  5000.0  872.82  5004.7  873.40
  5019.9  878.33  5025.1  877.82  5031.0  880.31  5041.2  881.32  5061.7  881.12
  5102.6  885.92  5143.5  887.77  5163.2  887.54  5168.3  888.70  5212.6  890.77
  5217.7  894.13  5245.8  897.77  5267.2  899.17  5276.5  898.79  5303.1  901.06
#Mann=5,-1,0
  4696.2    0.12       0  4722.8    0.05       0  4995.6   0.033       0
  5000.0    0.05       0  5004.7    0.12       0
Bank Sta=4995.6,5000
Exp/Cntr=0.3,0.1

Type RM Length L Ch R = 1,1815,415,415,415
BEGIN DESCRIPTION:
UDS St 53 2.0
END DESCRIPTION:
XS GIS Cut Line= 3
      2236979.04      7202010.02      2237779.00      7202360.00
      2237929.02      7202309.99
#Sta/Elev= 30
  4126.8  897.71  4181.3  893.01  4211.3  894.09  4234.7  891.05  4269.0  891.52
  4315.8  888.37  4337.8  888.82  4386.0  885.97  4414.8  887.57  4467.1  882.11
  4589.5  880.56  4659.6  881.86  4863.1  879.71  4869.0  881.01  4886.5  879.19
  4892.0  880.83  4915.4  881.67  4933.3  879.65  4938.8  881.55  4956.3  878.07
  4962.2  874.35  4967.6  874.83  4975.9  872.44  4976.3  871.94  4980.3  872.44
  4982.5  872.55  5002.6  873.52  5021.1  881.82  5031.6  883.46  5158.1  893.13
#Mann=5,-1,0
  4126.8    0.12       0  4337.8    0.05       0  4975.9    0.07       0
  4980.3    0.05       0  4982.5    0.12       0
Bank Sta=4975.9,4980.3
Exp/Cntr=0.3,0.1

Type RM Length L Ch R = 1,1400,210,210,210
BEGIN DESCRIPTION:
UDS St 53 1.0
END DESCRIPTION:
XS GIS Cut Line= 3
      2236887.52      7202234.23      2237786.71      7202792.43
      2238178.99      7202410.01
#Sta/Elev= 30
  3812.1  886.22  3837.9  882.44  3868.6  883.85  3947.7  883.17  4084.7  879.92
  4296.4  878.03  4840.6  876.99  4944.4  879.12  4951.6  876.74  4958.6  877.40
  4965.7  874.98  4972.7  877.41  4979.9  871.84  4986.9  872.85  4998.8  868.70
  4999.2  868.20  5003.2  868.70  5008.2  873.69  5015.2  873.63  5022.3  879.41
  5026.9  879.24  5107.2  880.54  5163.8  885.05  5227.3  887.81  5234.5  890.01
  5245.6  890.87  5283.9  895.15  5291.1  896.95  5354.7  903.04  5418.3  912.40
#Mann=5,-1,0
  3812.1    0.05       0  4998.8   0.033       0  5003.2    0.05       0
  5026.9    0.12       0  5245.6    0.05       0
Bank Sta=4998.8,5003.2
Exp/Cntr=0.3,0.1

Type RM Length L Ch R = 1,1190,286,286,286
BEGIN DESCRIPTION:
UDS St 53 0.9
END DESCRIPTION:
XS GIS Cut Line= 3
      2236980.15      7202486.95      2237776.89      7203066.36
      2238232.16      7202520.04
#Sta/Elev= 30
  3795.7  883.86  3811.1  883.90  3832.0  879.47  3840.5  874.19  3846.7  874.98
  3855.2  879.84  3868.5  882.12  3968.0  877.16  4004.5  878.97  4455.6  875.87
  4893.3  876.27  4957.8  880.98  4971.4  879.96  4978.6  873.32  4985.1  875.18
  4990.8  867.17  4991.2  866.67  4995.2  867.17  5013.8  869.97  5021.6  874.39
  5028.1  872.22  5035.9  874.27  5042.4  871.26  5056.7  876.83  5084.4  876.61
  5212.9  880.54  5311.9  888.12  5380.0  896.72  5457.0  904.63  5492.0  907.10
#Mann=6,-1,0
  3795.7    0.05       0  4990.8   0.033       0  4995.2    0.05       0
  5084.4    0.12       0  5380.0    0.05       0  5457.0    0.12       0
Bank Sta=4990.8,4995.2
Exp/Cntr=0.3,0.1

Type RM Length L Ch R = 1,904,0,0,0
BEGIN DESCRIPTION:
UDS St 53 0.8
END DESCRIPTION:
XS GIS Cut Line= 3
      2236740.11      7202413.52      2238042.01      7203403.66
      2238309.22      7202541.04
#Sta/Elev= 30
  2980.2  888.86  3004.7  883.81  3027.5  884.08  3048.3  879.73  3077.4  881.84
  3283.3  881.08  3297.8  879.61  3305.5  874.54  3326.9  878.09  3368.6  874.03
  3405.9  874.49  3412.2  876.57  3441.3  873.13  3447.6  873.47  3455.8  879.10
  3468.8  879.97  3755.3  874.94  4027.1  875.83  4091.9  875.60  4672.0  872.93
  4965.4  876.19  4976.4  872.13  4990.6  868.69  4991.0  868.19  4995.0  868.69
  5030.7  875.88  5188.5  882.41  5237.3  884.78  5407.0  904.71  5518.9  910.59
#Mann=8,-1,0
  2980.2    0.05       0  4027.1    0.12       0  4091.9    0.05       0
  4976.4    0.12       0  4990.6    0.07       0  4995.0    0.12       0
  5188.5    0.05       0  5407.0    0.12       0
Bank Sta=4990.6,4995
Exp/Cntr=0.3,0.1

Chan Stop Cuts=-1