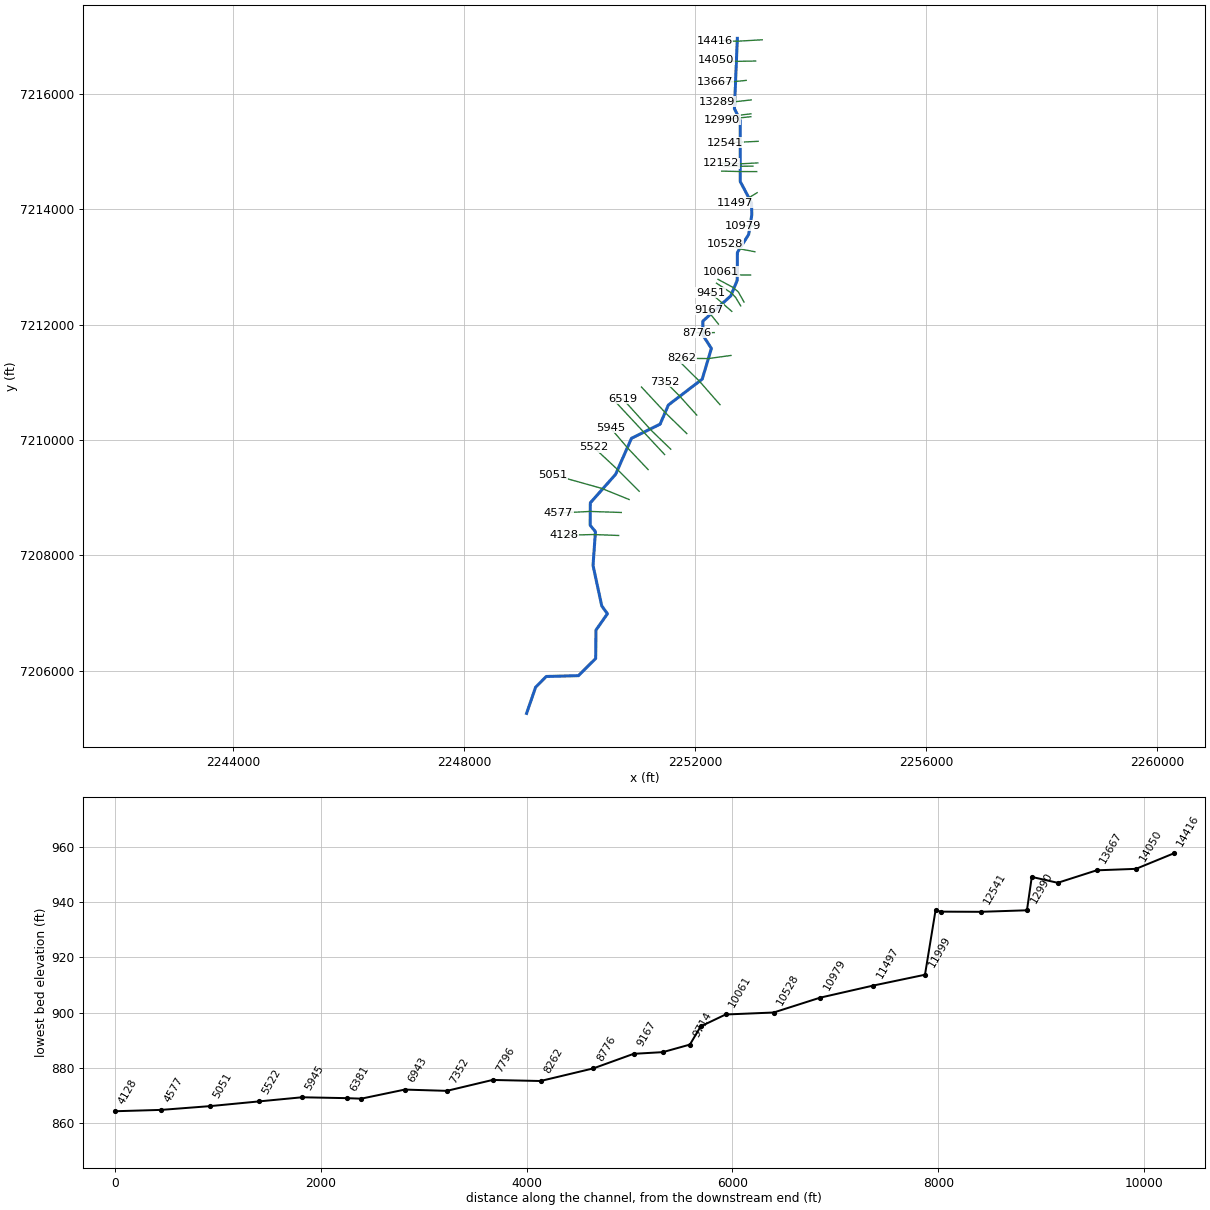
--- UDS St 54.prj (project) ---

Proj Title=UDS St 54 Base Level Engineering
Current Plan=p01
Default Exp/Contr=0.3,0.1
English Units
Geom File=g01
Flow File=f01
Plan File=p01
BEGIN DESCRIPTION:
UDS St 54
END DESCRIPTION:

--- UDS St 54.p01 (plan) ---

Plan Title=Multiple Run
Short Identifier=Multiple
Geom File=g01
Flow File=f01
Subcritical Flow
K Sum by GR= 0
Std Step Tol= 0.01
Critical Tol= 0.01
Num of Std Step Trials= 20
Max Error Tol= 0.3
Flow Tol Ratio= 0.001
Split Flow NTrial= 30
Split Flow Tol= 0.02
Split Flow Ratio= 0.02
Log Output Level= 0
Friction Slope Method= 1
Unsteady Friction Slope Method= 2
Unsteady Bridges Friction Slope Method= 1
Parabolic Critical Depth
Global Vel Dist=  1 , 1 , 1
Global Log Level= 0
CheckData=True
Encroach Param= -1, 0, 0, 0
BEGIN DESCRIPTION:
Multiple Run
END DESCRIPTION:

--- UDS St 54.f01 (steady flow) ---

Flow Title=Multiple
Number of Profiles=7
Profile Names=10-year,25-year,50-year,1pct_min,100-year,1pct_plu,500-year
River Rch & RM= UDS St 54,Reach-1,14416
     662     930    1157     715    1427    2848    2179
River Rch & RM= UDS St 54,Reach-1,10979
     847    1205    1512     942    1880    3751    2915
River Rch & RM= UDS St 54,Reach-1,7796
    1069    1539    1946    1221    2436    4860    3830
River Rch & RM= UDS St 54,Reach-1,6381
    1164    1681    2129    1338    2670    5326    4210
River Rch & RM= UDS St 54,Reach-1,4577
    1480    2159    2754    1741    3473    6930    5546
River Rch & RM= UDS St 54,Reach-1,2099
    1477    2154    2747    1735    3463    6909    5523
Boundary for River Rch & Prof#=UDS St 54,Reach-1,1
Up Type=0
Dn Type=3
Dn Slope=0.005
Boundary for River Rch & Prof#=UDS St 54,Reach-1,2
Up Type=0
Dn Type=3
Dn Slope=0.005
Boundary for River Rch & Prof#=UDS St 54,Reach-1,3
Up Type=0
Dn Type=3
Dn Slope=0.005
Boundary for River Rch & Prof#=UDS St 54,Reach-1,4
Up Type=0
Dn Type=3
Dn Slope=0.005
Boundary for River Rch & Prof#=UDS St 54,Reach-1,5
Up Type=0
Dn Type=3
Dn Slope=0.005
Boundary for River Rch & Prof#=UDS St 54,Reach-1,6
Up Type=0
Dn Type=3
Dn Slope=0.005
Boundary for River Rch & Prof#=UDS St 54,Reach-1,7
Up Type=0
Dn Type=3
Dn Slope=0.005

--- UDS St 54.g01 (geometry) ---

Geom Title=Existing Conditions

River Reach=UDS St 54,Reach-1
Reach XY= 30
      2252729.00      7216960.00      2252678.61      7215741.66
      2252778.96      7215537.23      2252779.20      7214478.26
      2252975.25      7214108.45      2252979.45      7213899.81
      2252925.45      7213561.47      2252730.36      7213250.35
      2252726.76      7212765.93      2252615.74      7212496.35
      2252132.53      7212058.55      2252131.24      7211815.93
      2252279.49      7211585.04      2252120.98      7211053.66
      2251534.26      7210604.53      2251392.24      7210273.62
      2250895.30      7210027.13      2250621.14      7209403.83
      2250182.54      7208908.54      2250180.22      7208519.59
      2250271.67      7208410.10      2250229.68      7207823.92
      2250381.16      7207121.27      2250479.48      7206987.17
      2250281.06      7206704.14      2250275.46      7206211.46
      2249977.50      7205913.61      2249419.21      7205899.57
      2249234.83      7205712.30      2249079.00      7205260.00

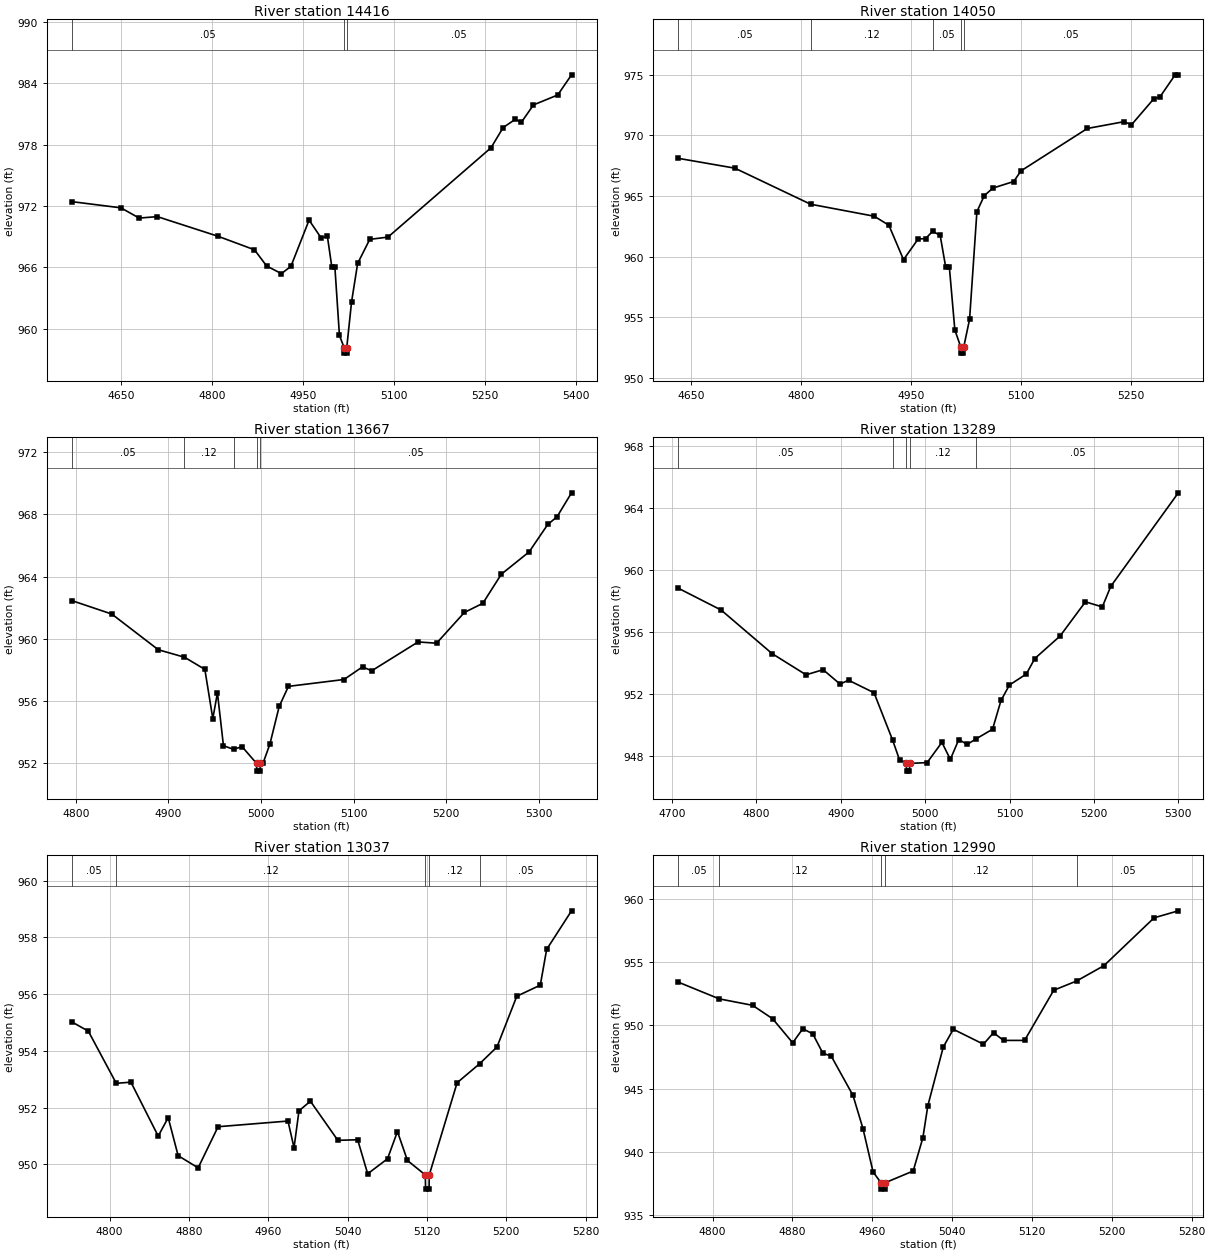
Type RM Length L Ch R = 1,14416,366,366,366
BEGIN DESCRIPTION:
UDS St 54 30.0
END DESCRIPTION:
XS GIS Cut Line= 3
      2253160.39      7216934.98      2252729.00      7216910.00
      2252336.21      7216922.47
#Sta/Elev= 30
  4568.0  972.44  4649.5  971.83  4679.6  970.83  4709.6  970.97  4809.8  969.05
  4869.9  967.73  4889.9  966.15  4914.3  965.40  4930.0  966.11  4960.0  970.63
  4980.1  968.87  4990.1  969.09  4997.6  966.02  5002.6  966.02  5010.1  959.36
  5018.1  958.13  5018.4  957.63  5021.9  957.63  5022.1  958.13  5030.1  962.64
  5040.1  966.39  5060.1  968.75  5090.2  968.97  5260.2  977.70  5280.3  979.68
  5300.3  980.48  5310.3  980.19  5330.3  981.89  5370.3  982.86  5393.1  984.83
#Mann=3,-1,0
  4568.0    0.05       0  5018.1   0.033       0  5022.1    0.05       0
Bank Sta=5018.1,5022.1
Exp/Cntr=0.3,0.1

Type RM Length L Ch R = 1,14050,383,383,383
BEGIN DESCRIPTION:
UDS St 54 29.0
END DESCRIPTION:
XS GIS Cut Line= 3
      2253046.12      7216566.87      2252679.00      7216560.00
      2252365.33      7216586.80
#Sta/Elev= 30
  4632.8  968.10  4709.9  967.29  4813.2  964.32  4900.0  963.33  4920.0  962.59
  4940.0  959.75  4960.0  961.46  4970.0  961.48  4979.7  962.09  4990.0  961.75
  4997.5  959.15  5002.5  959.15  5010.0  953.96  5018.1  952.55  5018.3  952.05
  5021.8  952.05  5022.1  952.55  5030.1  954.84  5040.1  963.71  5050.2  965.03
  5062.0  965.65  5090.3  966.19  5100.3  967.07  5190.7  970.56  5240.9  971.12
  5250.9  970.86  5281.0  972.98  5289.9  973.17  5310.5  974.98  5314.8  974.98
#Mann=5,-1,0
  4632.8    0.05       0  4813.2    0.12       0  4979.7    0.05       0
  5018.1    0.04       0  5022.1    0.05       0
Bank Sta=5018.1,5022.1
Exp/Cntr=0.3,0.1

Type RM Length L Ch R = 1,13667,378,378,378
BEGIN DESCRIPTION:
UDS St 54 28.0
END DESCRIPTION:
XS GIS Cut Line= 3
      2252882.22      7216231.22      2252679.00      7216210.00
      2252343.25      7216205.66
#Sta/Elev= 30
  4795.3  962.46  4838.8  961.59  4889.0  959.30  4917.3  958.82  4939.3  958.04
  4947.9  954.88  4952.9  956.53  4959.4  953.14  4970.3  952.91  4979.5  953.08
  4995.1  952.01  4995.4  951.51  4998.9  951.51  4999.1  952.01  5002.1  952.01
  5009.6  953.25  5019.6  955.66  5029.6  956.95  5089.6  957.39  5109.6  958.20
  5119.6  957.95  5169.6  959.80  5189.6  959.72  5219.6  961.69  5239.6  962.28
  5259.6  964.15  5289.6  965.58  5309.7  967.34  5319.7  967.83  5335.4  969.37
#Mann=5,-1,0
  4795.3    0.05       0  4917.3    0.12       0  4970.3    0.05       0
  4995.1   0.033       0  4999.1    0.05       0
Bank Sta=4995.1,4999.1
Exp/Cntr=0.3,0.1

Type RM Length L Ch R = 1,13289,252,252,252
BEGIN DESCRIPTION:
UDS St 54 27.0
END DESCRIPTION:
XS GIS Cut Line= 3
      2252969.39      7215892.59      2252679.00      7215860.00
      2252379.01      7215860.00
#Sta/Elev= 30
  4707.7  958.83  4758.4  957.42  4818.8  954.60  4859.0  953.23  4879.2  953.56
  4899.3  952.63  4909.3  952.88  4939.5  952.07  4961.5  949.01  4969.7  947.73
  4977.8  947.50  4978.0  947.00  4981.5  947.00  4981.8  947.50  5002.4  947.55
  5019.9  948.86  5029.9  947.76  5039.9  949.04  5049.9  948.73  5060.8  949.10
  5079.9  949.71  5089.9  951.57  5099.9  952.57  5119.9  953.28  5129.9  954.28
  5159.9  955.74  5189.9  957.95  5209.9  957.62  5219.9  958.95  5299.9  965.00
#Mann=5,-1,0
  4707.7    0.05       0  4961.5    0.12       0  4977.8    0.07       0
  4981.8    0.12       0  5060.8    0.05       0
Bank Sta=4977.8,4981.8
Exp/Cntr=0.3,0.1

Type RM Length L Ch R = 1,13037,47,47,47
BEGIN DESCRIPTION:
UDS St 54 26.0
END DESCRIPTION:
XS GIS Cut Line= 3
      2252965.76      7215651.88      2252729.06      7215623.44
      2252464.00      7215602.40
#Sta/Elev= 30
  4761.6  955.03  4778.5  954.70  4806.7  952.86  4821.5  952.90  4849.0  951.00
  4859.1  951.65  4869.1  950.31  4889.3  949.88  4909.4  951.33  4979.9  951.53
  4986.0  950.59  4991.0  951.89  5002.5  952.23  5030.2  950.85  5050.2  950.87
  5060.3  949.67  5080.3  950.20  5090.3  951.16  5100.4  950.14  5118.4  949.63
  5118.7  949.13  5122.2  949.13  5122.4  949.63  5150.5  952.88  5173.2  953.55
  5190.7  954.14  5210.7  955.93  5234.4  956.32  5240.8  957.58  5265.9  958.94
#Mann=5,-1,0
  4761.6    0.05       0  4806.7    0.12       0  5118.4    0.07       0
  5122.4    0.12       0  5173.2    0.05       0
Bank Sta=5118.4,5122.4
Exp/Cntr=0.3,0.1

Type RM Length L Ch R = 1,12990,449,449,449
BEGIN DESCRIPTION:
UDS St 54 25.1
END DESCRIPTION:
XS GIS Cut Line= 2
      2252962.95      7215601.80      2252464.94      7215548.04
#Sta/Elev= 30
  4765.7  953.40  4806.7  952.08  4840.1  951.57  4860.2  950.51  4880.3  948.61
  4890.4  949.72  4900.4  949.32  4910.5  947.79  4918.9  947.56  4940.7  944.46
  4950.7  941.84  4960.8  938.42  4968.8  937.56  4969.1  937.06  4972.6  937.06
  4972.8  937.56  5001.0  938.49  5010.7  941.11  5015.7  943.65  5031.2  948.29
  5041.2  949.68  5071.4  948.50  5081.5  949.41  5091.5  948.80  5112.6  948.80
  5141.8  952.76  5164.7  953.49  5192.1  954.70  5242.4  958.48  5266.6  959.03
#Mann=5,-1,0
  4765.7    0.05       0  4806.7    0.12       0  4968.8    0.07       0
  4972.8    0.12       0  5164.7    0.05       0
Bank Sta=4968.8,4972.8
Exp/Cntr=0.3,0.1

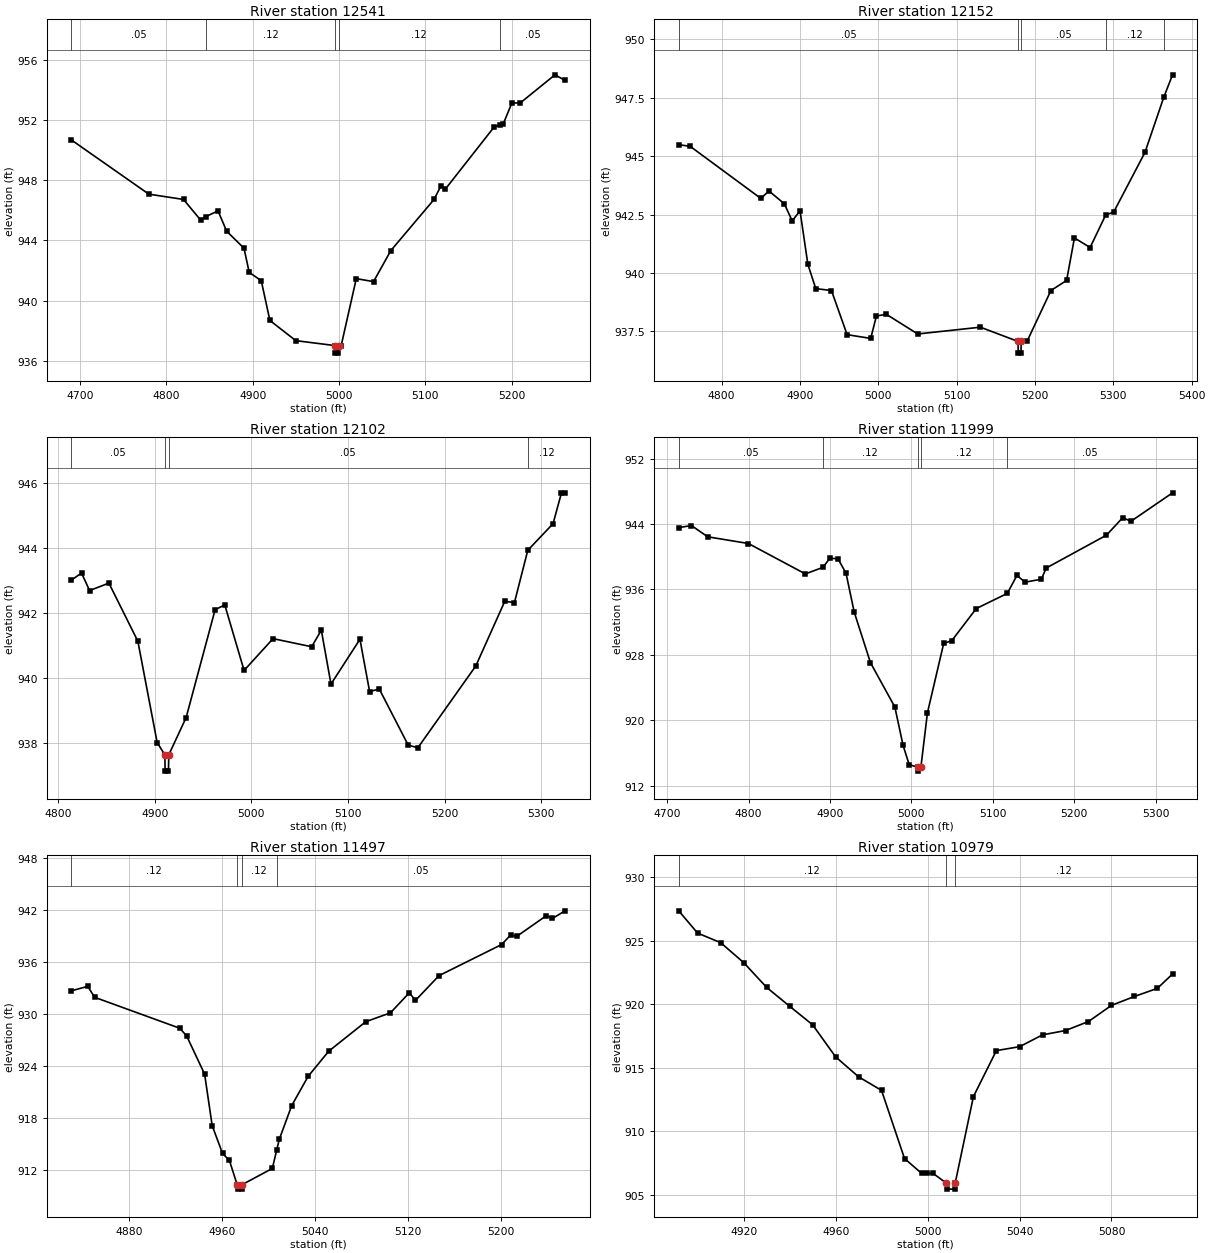
Type RM Length L Ch R = 1,12541,389,389,389
BEGIN DESCRIPTION:
UDS St 54 25.0
END DESCRIPTION:
XS GIS Cut Line= 3
      2253088.93      7215175.04      2252779.00      7215160.00
      2252517.32      7215149.19
#Sta/Elev= 30
  4689.7  950.68  4779.7  947.07  4819.8  946.72  4839.8  945.34  4845.6  945.58
  4859.8  945.96  4869.8  944.61  4889.9  943.48  4895.9  941.88  4909.9  941.32
  4919.9  938.68  4949.9  937.34  4995.5  937.01  4995.7  936.51  4999.2  936.51
  4999.5  937.01  5002.5  937.01  5020.0  941.46  5040.0  941.26  5060.0  943.32
  5110.1  946.72  5118.1  947.62  5123.1  947.40  5180.1  951.56  5186.6  951.66
  5190.2  951.72  5200.2  953.12  5210.2  953.14  5250.2  955.00  5261.9  954.63
#Mann=5,-1,0
  4689.7    0.05       0  4845.6    0.12       0  4995.5    0.07       0
  4999.5    0.12       0  5186.6    0.05       0
Bank Sta=4995.5,4999.5
Exp/Cntr=0.3,0.1

Type RM Length L Ch R = 1,12152,50,50,50
BEGIN DESCRIPTION:
UDS St 54 24.0
END DESCRIPTION:
XS GIS Cut Line= 3
      2253083.61      7214800.97      2252829.38      7214787.19
      2252453.83      7214793.65
#Sta/Elev= 30
  4745.4  945.49  4760.0  945.42  4850.2  943.19  4860.5  943.51  4880.2  942.96
  4890.2  942.23  4900.2  942.66  4910.2  940.37  4920.3  939.33  4940.3  939.25
  4960.3  937.36  4990.4  937.20  4997.7  938.16  5010.4  938.23  5050.4  937.39
  5130.4  937.68  5178.4  937.07  5178.7  936.57  5182.2  936.57  5182.4  937.07
  5190.4  937.11  5220.4  939.25  5240.4  939.68  5250.4  941.50  5270.4  941.09
  5290.4  942.49  5300.4  942.60  5340.4  945.16  5364.4  947.52  5375.6  948.48
#Mann=5,-1,0
  4745.4    0.05       0  5178.4   0.033       0  5182.4    0.05       0
  5290.4    0.12       0  5364.4    0.05       0
Bank Sta=5178.4,5182.4
Exp/Cntr=0.3,0.1

Type RM Length L Ch R = 1,12102,103,103,103
BEGIN DESCRIPTION:
UDS St 54 23.1
END DESCRIPTION:
XS GIS Cut Line= 2
      2252997.98      7214745.10      2252486.63      7214738.10
#Sta/Elev= 30
  4813.4  943.02  4824.1  943.24  4832.4  942.70  4852.4  942.93  4882.4  941.14
  4902.4  938.02  4910.4  937.64  4910.6  937.14  4914.1  937.14  4914.4  937.64
  4932.4  938.79  4962.4  942.11  4972.4  942.26  4992.4  940.24  5022.4  941.22
  5062.4  940.97  5072.4  941.48  5082.4  939.82  5112.4  941.20  5122.4  939.59
  5132.4  939.67  5162.4  937.94  5172.4  937.86  5232.4  940.38  5262.4  942.37
  5272.4  942.33  5286.2  943.94  5312.4  944.76  5321.1  945.71  5324.8  945.71
#Mann=4,-1,0
  4813.4    0.05       0  4910.4   0.033       0  4914.4    0.05       0
  5286.2    0.12       0
Bank Sta=4910.4,4914.4
Exp/Cntr=0.3,0.1

Type RM Length L Ch R = 1,11999,502,502,502
BEGIN DESCRIPTION:
UDS St 54 23.0
END DESCRIPTION:
XS GIS Cut Line= 3
      2253064.58      7214650.15      2252778.68      7214651.08
      2252457.87      7214658.62
#Sta/Elev= 30
  4714.1  943.55  4729.7  943.81  4749.7  942.43  4799.7  941.61  4869.7  937.89
  4891.3  938.69  4899.7  939.79  4909.7  939.76  4919.7  937.96  4929.7  933.23
  4949.7  927.03  4979.7  921.60  4989.7  916.94  4997.3  914.54  5007.7  914.26
  5007.9  913.76  5011.7  914.26  5019.7  920.89  5039.7  929.39  5049.7  929.73
  5079.7  933.65  5117.8  935.50  5129.7  937.70  5139.7  936.88  5159.7  937.24
  5165.7  938.61  5239.7  942.63  5259.7  944.77  5269.8  944.33  5320.9  947.81
#Mann=5,-1,0
  4714.1    0.05       0  4891.3    0.12       0  5007.7    0.07       0
  5011.7    0.12       0  5117.8    0.05       0
Bank Sta=5007.7,5011.7
Exp/Cntr=0.3,0.1

Type RM Length L Ch R = 1,11497,518,518,518
BEGIN DESCRIPTION:
UDS St 54 22.0
END DESCRIPTION:
XS GIS Cut Line= 3
      2253072.19      7214284.84      2252927.89      7214195.91
      2252687.69      7214110.02
#Sta/Elev= 30
  4830.5  932.69  4844.7  933.21  4850.6  931.95  4923.9  928.38  4929.8  927.48
  4945.2  923.09  4951.7  917.16  4960.6  913.96  4966.5  913.16  4973.2  910.35
  4973.5  909.85  4977.0  909.85  4977.2  910.35  5003.4  912.23  5007.1  914.30
  5009.4  915.59  5020.1  919.48  5034.2  922.84  5051.9  925.74  5083.8  929.14
  5105.0  930.16  5121.2  932.47  5126.5  931.59  5146.7  934.44  5200.6  938.03
  5208.3  939.12  5213.6  938.97  5239.0  941.35  5244.3  941.03  5255.1  941.91
#Mann=4,-1,0
  4830.5    0.12       0  4973.2    0.07       0  4977.2    0.12       0
  5007.1    0.05       0
Bank Sta=4973.2,4977.2
Exp/Cntr=0.3,0.1

Type RM Length L Ch R = 1,10979,451,451,451
BEGIN DESCRIPTION:
UDS St 54 21.0
END DESCRIPTION:
XS GIS Cut Line= 3
      2253037.24      7213705.82      2252929.00      7213710.00
      2252822.40      7213714.11
#Sta/Elev= 28
  4891.6  927.36  4899.8  925.61  4909.9  924.85  4919.9  923.28  4929.9  921.33
  4939.9  919.85  4949.9  918.39  4959.9  915.87  4969.9  914.30  4979.9  913.23
  4989.9  907.87  4997.4  906.69  4999.9  906.69  5002.4  906.69  5007.9  905.96
  5008.2  905.46  5011.7  905.46  5012.0  905.96  5019.9  912.74  5029.9  916.36
  5040.0  916.67  5050.0  917.60  5060.0  917.94  5070.0  918.65  5080.0  919.92
  5090.0  920.62  5100.0  921.26  5106.6  922.39
#Mann=3,-1,0
  4891.6    0.12       0  5007.9    0.07       0  5012.0    0.12       0
Bank Sta=5007.9,5012
Exp/Cntr=0.3,0.1

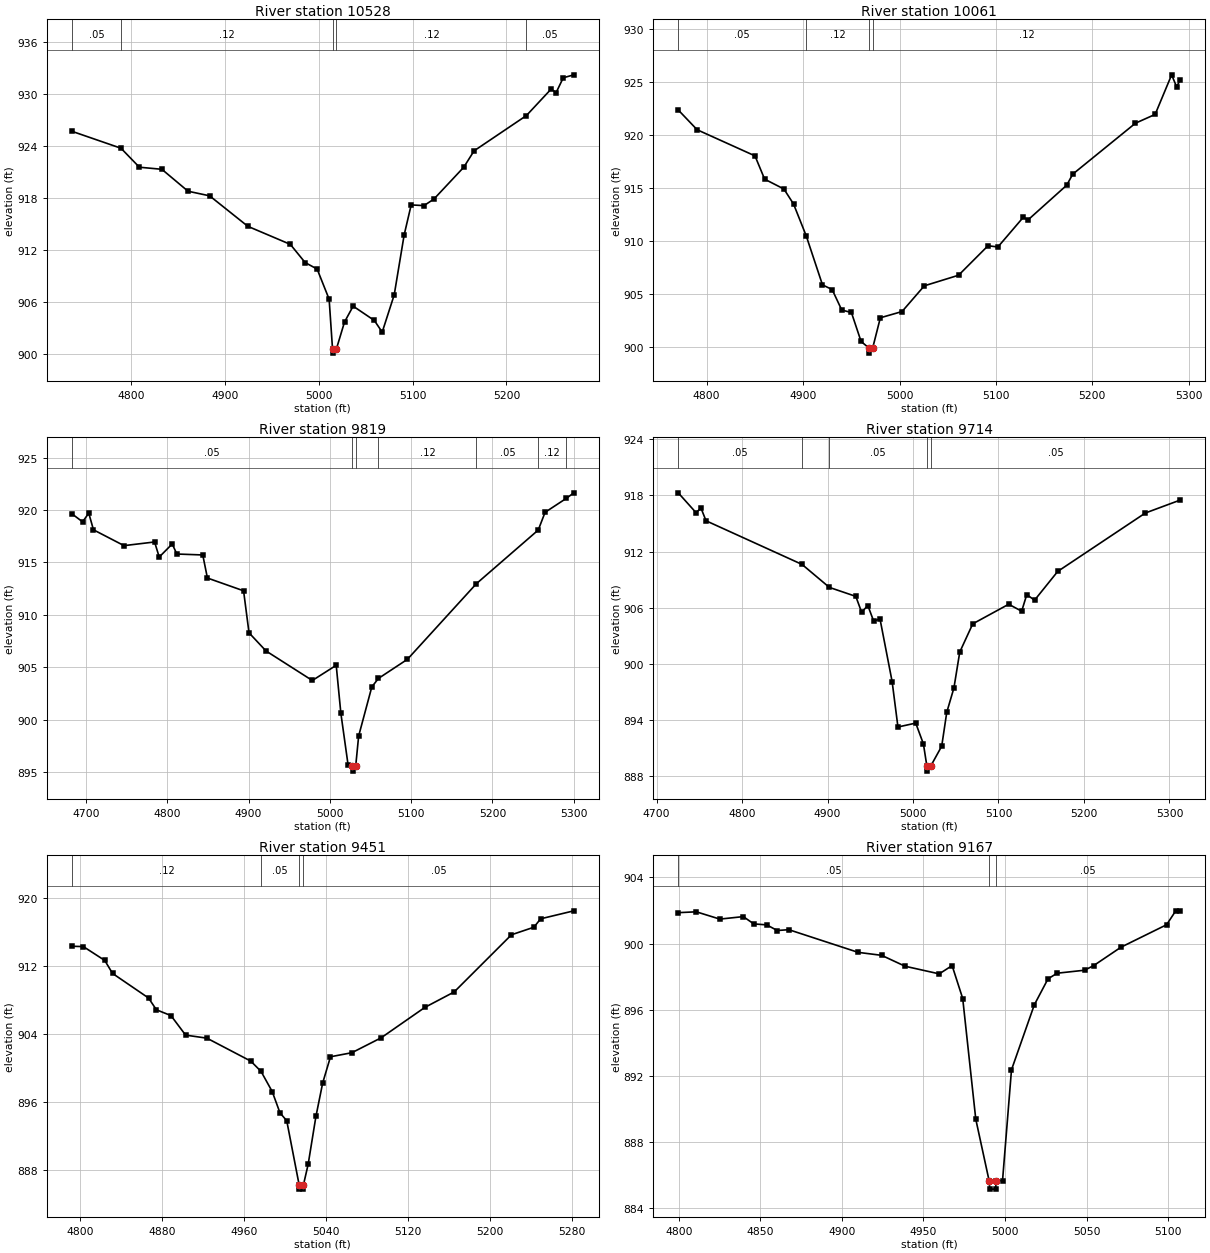
Type RM Length L Ch R = 1,10528,467,467,467
BEGIN DESCRIPTION:
UDS St 54 20.0
END DESCRIPTION:
XS GIS Cut Line= 3
      2253033.39      7213261.14      2252779.00      7213310.00
      2252518.31      7213402.03
#Sta/Elev= 30
  4736.4  925.70  4788.9  923.74  4808.5  921.55  4832.5  921.31  4860.4  918.78
  4883.4  918.25  4924.2  914.73  4969.5  912.65  4985.3  910.55  4998.1  909.80
  5010.9  906.32  5014.5  900.60  5014.9  900.10  5018.7  900.60  5027.3  903.69
  5036.5  905.52  5059.1  903.87  5067.5  902.52  5080.3  906.82  5090.9  913.73
  5098.4  917.20  5112.1  917.12  5122.7  917.88  5154.5  921.55  5165.5  923.44
  5221.3  927.51  5247.7  930.57  5253.0  930.16  5260.6  931.87  5271.9  932.21
#Mann=5,-1,0
  4736.4    0.05       0  4788.9    0.12       0  5014.5    0.07       0
  5018.7    0.12       0  5221.3    0.05       0
Bank Sta=5014.5,5018.7
Exp/Cntr=0.3,0.1

Type RM Length L Ch R = 1,10061,242,242,242
BEGIN DESCRIPTION:
UDS St 54 19.0
END DESCRIPTION:
XS GIS Cut Line= 3
      2252958.57      7212857.01      2252729.00      7212860.00
      2252443.40      7212916.39
#Sta/Elev= 30
  4770.5  922.36  4790.1  920.49  4850.1  918.02  4860.1  915.82  4880.1  914.89
  4890.1  913.47  4903.2  910.47  4920.1  905.83  4930.1  905.39  4940.1  903.45
  4950.1  903.22  4960.1  900.49  4968.0  899.88  4968.3  899.38  4972.2  899.88
  4980.1  902.72  5002.6  903.31  5025.7  905.74  5061.2  906.74  5091.8  909.53
  5102.0  909.41  5128.3  912.21  5133.4  911.98  5173.4  915.25  5179.6  916.29
  5244.7  921.11  5265.1  921.94  5282.2  925.68  5287.3  924.56  5291.2  925.19
#Mann=4,-1,0
  4770.5    0.05       0  4903.2    0.12       0  4968.0    0.07       0
  4972.2    0.12       0
Bank Sta=4968,4972.2
Exp/Cntr=0.3,0.1

Type RM Length L Ch R = 1,9819,105,105,105
BEGIN DESCRIPTION:
UDS St 54 18.1
END DESCRIPTION:
XS GIS Cut Line= 4
      2252845.22      7212388.44      2252746.38      7212564.22
      2252658.74      7212640.11      2252394.60      7212782.77
#Sta/Elev= 30
  4682.4  919.65  4695.7  918.87  4703.3  919.70  4709.1  918.11  4746.7  916.60
  4784.3  916.95  4790.0  915.51  4806.0  916.76  4811.7  915.80  4843.6  915.71
  4849.3  913.51  4893.8  912.29  4900.5  908.28  4921.4  906.55  4978.4  903.73
  5007.8  905.18  5013.5  900.61  5022.4  895.67  5027.6  895.58  5027.9  895.08
  5031.8  895.58  5035.4  898.43  5051.6  903.12  5059.8  903.93  5095.4  905.75
  5180.3  912.97  5256.4  918.09  5264.8  919.78  5291.1  921.12  5300.2  921.64
#Mann=7,-1,0
  4682.4    0.05       0  5027.6   0.033       0  5031.8    0.05       0
  5059.8    0.12       0  5180.3    0.05       0  5256.4    0.12       0
  5291.1    0.05       0
Bank Sta=5027.6,5031.8
Exp/Cntr=0.3,0.1

Type RM Length L Ch R = 1,9714,263,263,263
BEGIN DESCRIPTION:
UDS St 54 18.0
END DESCRIPTION:
XS GIS Cut Line= 5
      2252787.71      7212322.18      2252699.33      7212468.57
      2252629.23      7212544.86      2252558.91      7212590.26
      2252367.44      7212715.87
#Sta/Elev= 30
  4725.4  918.28  4746.2  916.16  4752.0  916.65  4757.9  915.29  4870.2  910.62
  4902.2  908.16  4933.1  907.20  4939.9  905.51  4947.2  906.22  4954.0  904.55
  4961.4  904.79  4975.6  898.08  4982.4  893.22  5003.2  893.64  5012.2  891.41
  5016.3  889.00  5016.6  888.50  5020.5  889.00  5033.6  891.17  5039.5  894.79
  5047.9  897.41  5054.7  901.24  5069.9  904.26  5112.0  906.36  5127.1  905.61
  5133.1  907.39  5142.2  906.79  5169.3  909.87  5271.8  916.12  5312.7  917.51
#Mann=5,-1,0
  4725.4    0.05       0  4870.2    0.12       0  4902.2    0.05       0
  5016.3   0.033       0  5020.5    0.05       0
Bank Sta=5016.3,5020.5
Exp/Cntr=0.3,0.1

Type RM Length L Ch R = 1,9451,284,284,284
BEGIN DESCRIPTION:
UDS St 54 17.1
END DESCRIPTION:
XS GIS Cut Line= 2
      2252632.94      7212227.91      2252262.88      7212549.09
#Sta/Elev= 30
  4792.0  914.36  4803.3  914.32  4824.2  912.69  4831.8  911.16  4866.9  908.27
  4874.6  906.88  4888.8  906.20  4903.1  903.90  4923.9  903.54  4966.7  900.84
  4976.7  899.63  4987.6  897.26  4995.2  894.75  5001.8  893.82  5013.9  886.27
  5014.2  885.77  5017.8  885.77  5018.1  886.27  5022.7  888.69  5030.3  894.34
  5036.9  898.28  5044.5  901.35  5065.4  901.83  5093.9  903.58  5136.7  907.17
  5165.2  908.98  5221.1  915.71  5243.0  916.60  5249.6  917.59  5282.0  918.53
#Mann=4,-1,0
  4792.0    0.12       0  4976.7    0.05       0  5013.9   0.033       0
  5018.1    0.05       0
Bank Sta=5013.9,5018.1
Exp/Cntr=0.3,0.1

Type RM Length L Ch R = 1,9167,391,391,391
BEGIN DESCRIPTION:
UDS St 54 17.0
END DESCRIPTION:
XS GIS Cut Line= 3
      2252401.51      7212007.05      2252279.00      7212160.00
      2252228.98      7212260.03
#Sta/Elev= 30
  4799.7  901.87  4810.8  901.92  4825.2  901.48  4839.6  901.63  4846.0  901.19
  4854.0  901.13  4860.4  900.79  4867.5  900.84  4910.0  899.47  4924.4  899.29
  4938.8  898.63  4959.7  898.17  4967.6  898.67  4974.1  896.68  4982.1  889.39
  4990.3  885.66  4990.7  885.16  4994.3  885.16  4994.6  885.66  4998.5  885.66
  5004.0  892.37  5018.0  896.30  5026.4  897.87  5032.0  898.21  5048.8  898.39
  5054.4  898.67  5071.1  899.78  5099.1  901.14  5104.7  901.98  5107.5  901.98
#Mann=3,-1,0
  4799.7    0.05       0  4990.3   0.033       0  4994.6    0.05       0
Bank Sta=4990.3,4994.6
Exp/Cntr=0.3,0.1

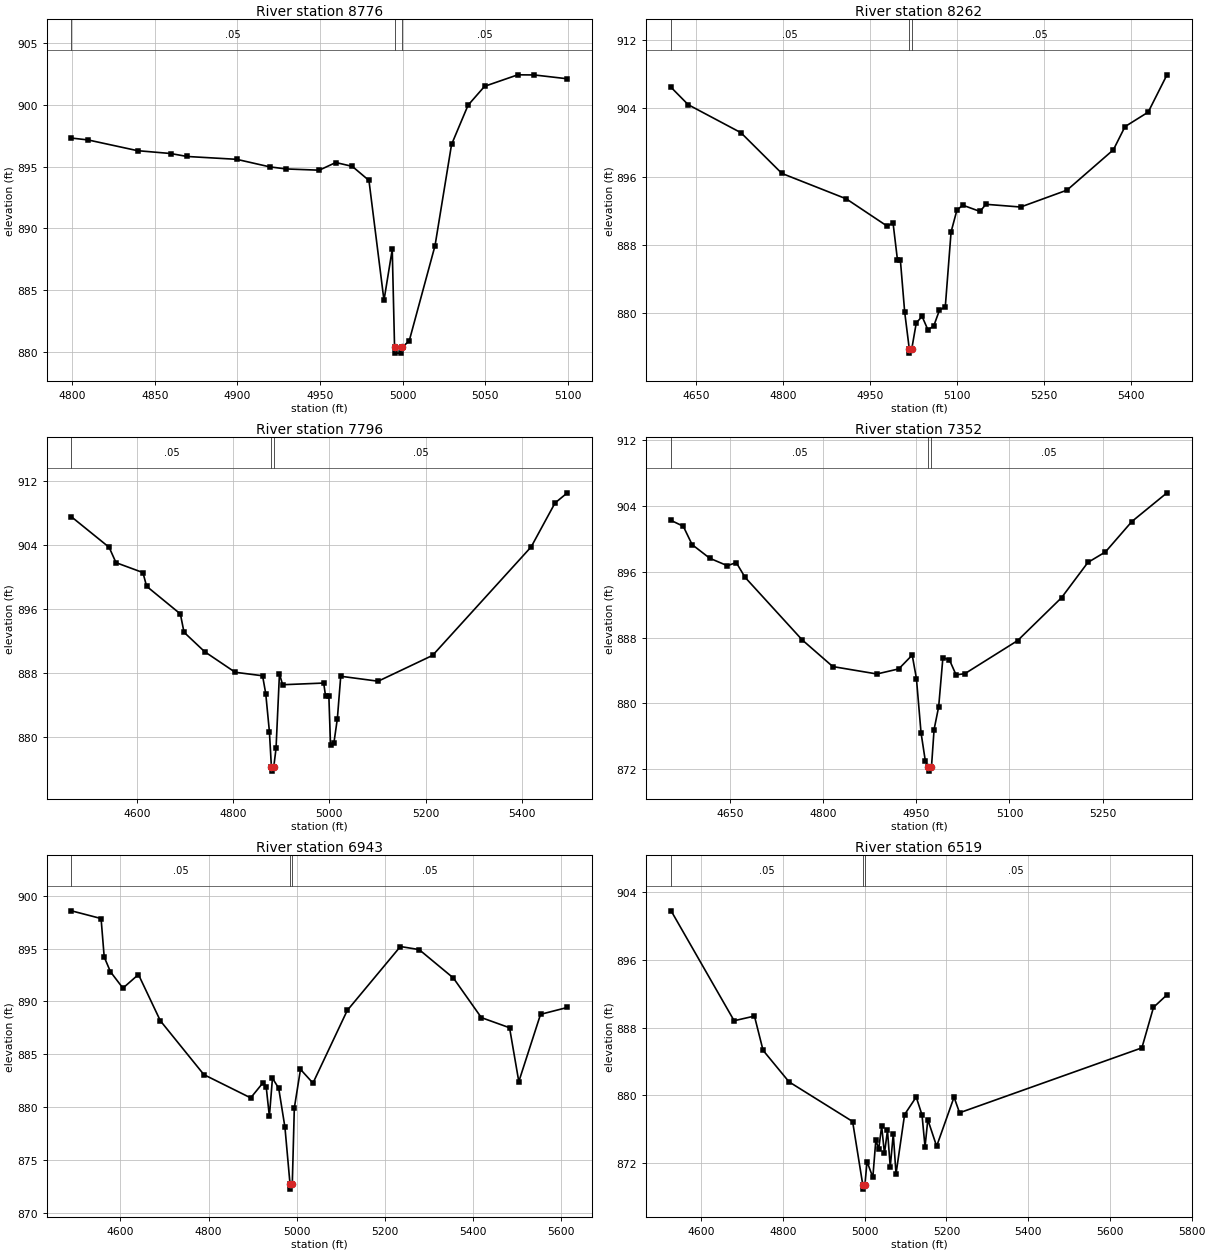
Type RM Length L Ch R = 1,8776,514,514,514
BEGIN DESCRIPTION:
UDS St 54 16.0
END DESCRIPTION:
XS GIS Cut Line= 3
      2252328.99      7211860.00      2252128.56      7211854.82
      2252028.99      7211860.00
#Sta/Elev= 27
  4799.5  897.31  4809.5  897.16  4839.5  896.29  4859.5  896.06  4869.5  895.82
  4899.5  895.59  4919.5  894.98  4929.5  894.81  4949.5  894.71  4959.5  895.33
  4969.5  895.02  4979.6  893.88  4988.7  884.17  4993.7  888.30  4995.1  880.40
  4995.5  879.90  4999.1  879.90  4999.4  880.40  5000.0  880.40  5004.0  880.90
  5019.6  888.60  5029.6  896.79  5039.6  899.97  5049.6  901.50  5069.7  902.43
  5079.7  902.42  5099.7  902.11
#Mann=3,-1,0
  4799.5    0.05       0  4995.1   0.033       0  4999.4    0.05       0
Bank Sta=4995.1,4999.4
Exp/Cntr=0.3,0.1

Type RM Length L Ch R = 1,8262,466,466,466
BEGIN DESCRIPTION:
UDS St 54 15.0
END DESCRIPTION:
XS GIS Cut Line= 3
      2252618.26      7211463.53      2252229.00      7211410.00
      2251766.63      7211412.69
#Sta/Elev= 30
  4607.0  906.47  4636.5  904.44  4727.4  901.16  4798.0  896.39  4909.1  893.41
  4979.7  890.21  4989.8  890.59  4997.4  886.27  5002.4  886.27  5009.9  880.13
  5017.8  875.83  5018.1  875.33  5022.1  875.83  5029.9  878.88  5039.9  879.63
  5049.9  878.07  5059.9  878.49  5069.9  880.37  5079.9  880.74  5089.9  889.53
  5099.9  892.07  5109.9  892.67  5139.9  891.93  5149.9  892.77  5209.9  892.45
  5289.9  894.43  5369.9  899.16  5389.9  901.87  5429.9  903.57  5462.3  907.94
#Mann=3,-1,0
  4607.0    0.05       0  5017.8   0.033       0  5022.1    0.05       0
Bank Sta=5017.8,5022.1
Exp/Cntr=0.3,0.1

Type RM Length L Ch R = 1,7796,444,444,444
BEGIN DESCRIPTION:
UDS St 54 14.0
END DESCRIPTION:
XS GIS Cut Line= 3
      2252429.03      7210609.97      2252079.00      7211010.00
      2251724.95      7211362.13
#Sta/Elev= 30
  4463.8  907.50  4542.1  903.69  4556.4  901.77  4612.4  900.53  4620.0  898.82
  4690.2  895.36  4697.8  893.07  4740.5  890.65  4804.1  888.07  4861.1  887.63
  4867.7  885.40  4875.3  880.65  4879.5  876.21  4880.1  875.71  4884.3  876.21
  4889.1  878.54  4896.2  887.87  4902.8  886.51  4988.2  886.72  4992.0  885.12
  4998.9  885.12  5002.4  878.92  5009.5  879.28  5016.6  882.27  5023.6  887.57
  5101.4  886.95  5214.6  890.18  5419.6  903.75  5469.1  909.23  5494.7  910.50
#Mann=3,-1,0
  4463.8    0.05       0  4879.5   0.033       0  4884.3    0.05       0
Bank Sta=4879.5,4884.3
Exp/Cntr=0.3,0.1

Type RM Length L Ch R = 1,7352,409,409,409
BEGIN DESCRIPTION:
UDS St 54 13.0
END DESCRIPTION:
XS GIS Cut Line= 3
      2252026.44      7210429.73      2251729.00      7210760.00
      2251479.01      7211009.99
#Sta/Elev= 30
  4555.5  902.27  4575.1  901.56  4589.3  899.33  4617.7  897.67  4646.1  896.76
  4660.3  897.15  4674.5  895.35  4766.4  887.74  4815.7  884.49  4886.7  883.59
  4921.9  884.21  4943.5  885.89  4950.3  883.03  4957.7  876.45  4964.5  873.06
  4969.3  872.27  4970.0  871.77  4974.5  872.27  4978.7  876.83  4986.1  879.61
  4992.9  885.58  5003.5  885.29  5014.1  883.48  5028.3  883.63  5113.1  887.65
  5183.8  892.87  5226.2  897.16  5254.5  898.44  5297.0  902.14  5353.5  905.63
#Mann=3,-1,0
  4555.5    0.05       0  4969.3   0.033       0  4974.5    0.05       0
Bank Sta=4969.3,4974.5
Exp/Cntr=0.3,0.1

Type RM Length L Ch R = 1,6943,424,424,424
BEGIN DESCRIPTION:
UDS St 54 12.0
END DESCRIPTION:
XS GIS Cut Line= 3
      2251853.62      7210109.59      2251487.19      7210466.04
      2251069.14      7210915.74
#Sta/Elev= 30
  4488.8  898.58  4556.0  897.85  4563.1  894.21  4577.3  892.81  4605.6  891.26
  4640.8  892.55  4690.5  888.17  4789.3  883.07  4895.5  880.87  4923.8  882.32
  4930.7  881.90  4937.9  879.12  4944.9  882.73  4959.0  881.79  4973.2  878.09
  4984.7  872.73  4985.4  872.23  4989.9  872.73  4994.5  879.91  5008.5  883.57
  5036.8  882.27  5114.6  889.15  5235.2  895.20  5277.7  894.91  5355.4  892.22
  5418.9  888.47  5482.9  887.51  5503.9  882.41  5553.2  888.78  5614.0  889.43
#Mann=3,-1,0
  4488.8    0.05       0  4984.7   0.033       0  4989.9    0.05       0
Bank Sta=4984.7,4989.9
Exp/Cntr=0.3,0.1

Type RM Length L Ch R = 1,6519,138,138,138
BEGIN DESCRIPTION:
UDS St 54 11.0
END DESCRIPTION:
XS GIS Cut Line= 3
      2251575.84      7209838.74      2251235.16      7210167.88
      2250739.09      7210716.44
#Sta/Elev= 30
  4526.3  901.78  4680.5  888.81  4730.2  889.36  4751.3  885.32  4814.8  881.60
  4970.4  876.92  4995.3  869.44  4996.0  868.94  5000.5  869.44  5005.7  872.19
  5019.9  870.33  5027.3  874.78  5034.1  873.63  5041.5  876.36  5048.3  873.15
  5055.7  875.86  5062.5  871.57  5069.9  875.46  5076.6  870.73  5097.6  877.74
  5126.0  879.81  5140.2  877.70  5147.6  873.93  5154.4  877.14  5176.0  874.00
  5218.6  879.79  5232.1  877.95  5678.2  885.61  5706.6  890.39  5739.6  891.87
#Mann=3,-1,0
  4526.3    0.05       0  4995.3   0.033       0  5000.5    0.05       0
Bank Sta=4995.3,5000.5
Exp/Cntr=0.3,0.1

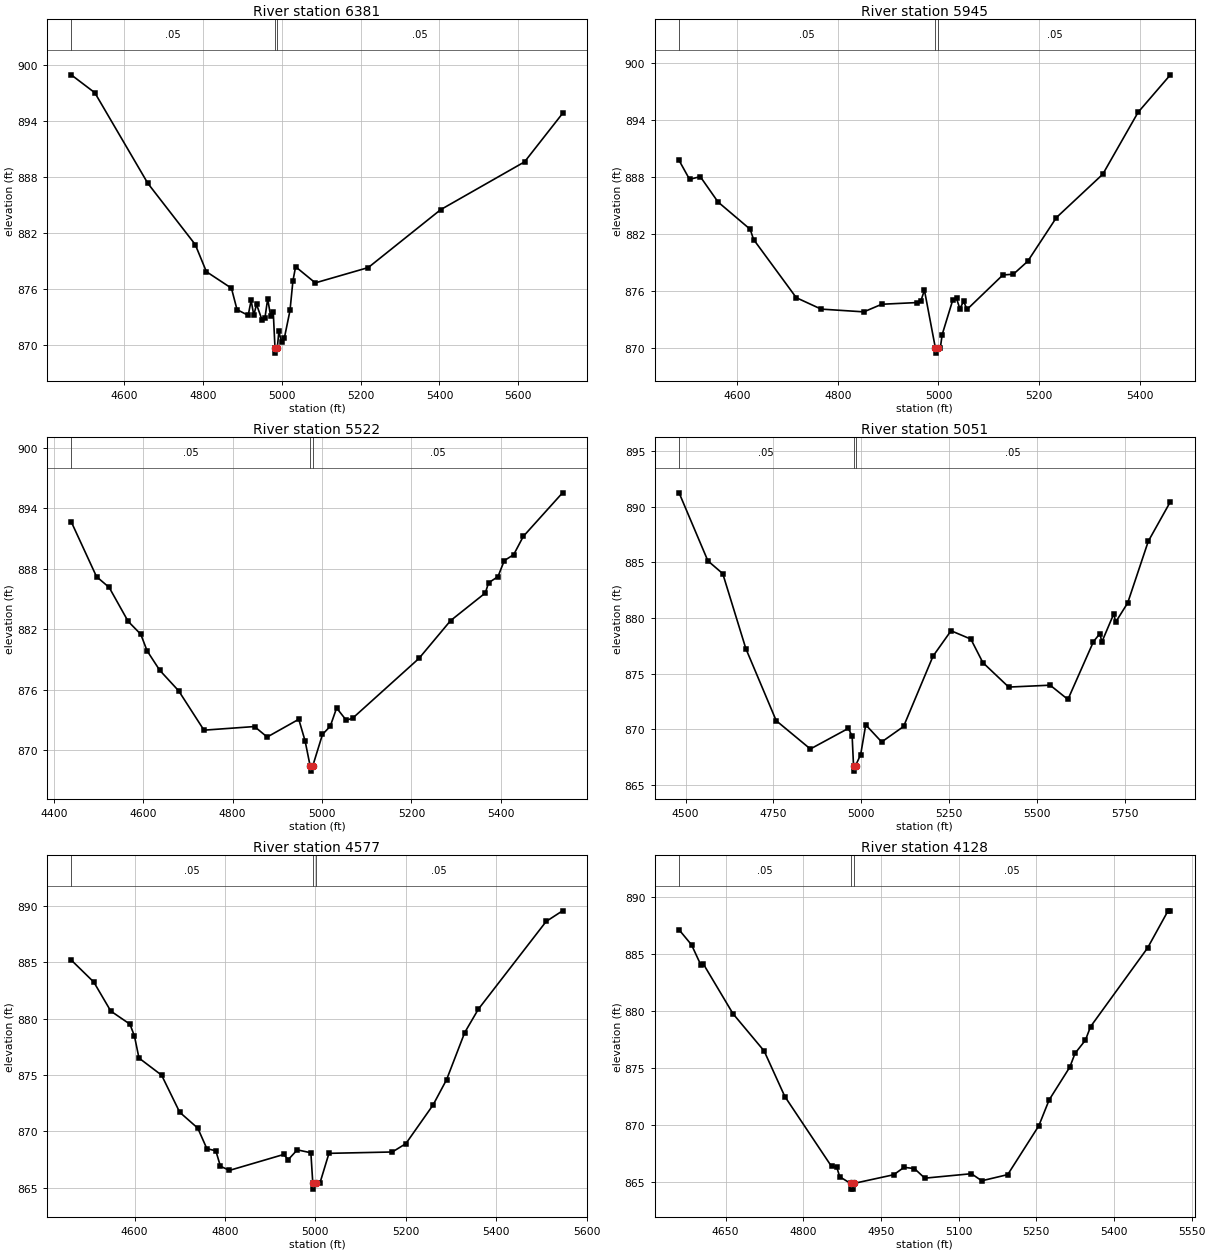
Type RM Length L Ch R = 1,6381,436,436,436
BEGIN DESCRIPTION:
UDS St 54 10.1
END DESCRIPTION:
XS GIS Cut Line= 2
      2251469.24      7209746.03      2250620.69      7210658.03
#Sta/Elev= 30
  4466.3  898.96  4526.1  897.04  4660.5  887.33  4780.7  880.77  4809.0  877.86
  4872.5  876.09  4886.7  873.79  4915.0  873.18  4922.4  874.78  4929.2  873.19
  4936.1  874.36  4950.2  872.67  4957.5  872.92  4964.4  874.95  4971.7  873.15
  4978.5  873.58  4983.0  869.63  4983.9  869.13  4988.7  869.63  4992.7  871.45
  5000.0  870.27  5006.9  870.79  5021.0  873.70  5028.4  876.87  5035.2  878.39
  5085.1  876.66  5219.4  878.30  5403.1  884.51  5615.7  889.63  5712.0  894.82
#Mann=3,-1,0
  4466.3    0.05       0  4983.0   0.033       0  4988.7    0.05       0
Bank Sta=4983,4988.7
Exp/Cntr=0.3,0.1

Type RM Length L Ch R = 1,5945,423,423,423
BEGIN DESCRIPTION:
UDS St 54 10.0
END DESCRIPTION:
XS GIS Cut Line= 3
      2251184.10      7209485.52      2250829.00      7209860.00
      2250529.03      7210209.96
#Sta/Elev= 30
  4484.2  889.72  4505.0  887.73  4526.4  888.01  4561.6  885.35  4625.5  882.48
  4632.4  881.40  4717.3  875.28  4766.7  874.08  4851.6  873.79  4887.2  874.59
  4958.0  874.77  4964.9  874.92  4972.1  876.08  4994.0  869.95  4994.9  869.45
  4999.7  869.95  5003.6  869.95  5007.4  871.40  5028.3  875.01  5035.9  875.20
  5042.5  874.13  5050.2  874.89  5056.8  874.04  5128.1  877.67  5149.0  877.75
  5177.5  879.11  5234.6  883.71  5326.8  888.27  5397.0  894.78  5461.2  898.72
#Mann=3,-1,0
  4484.2    0.05       0  4994.0   0.033       0  4999.7    0.05       0
Bank Sta=4994,4999.7
Exp/Cntr=0.3,0.1

Type RM Length L Ch R = 1,5522,471,471,471
BEGIN DESCRIPTION:
UDS St 54 9.0
END DESCRIPTION:
XS GIS Cut Line= 3
      2251029.02      7209109.98      2250629.00      7209510.00
      2250238.57      7209873.71
#Sta/Elev= 30
  4438.9  892.66  4495.5  887.22  4523.8  886.15  4566.2  882.79  4594.5  881.51
  4608.6  879.87  4636.9  877.94  4679.3  875.90  4735.9  872.00  4849.0  872.36
  4877.3  871.32  4948.0  873.08  4962.2  870.93  4973.5  868.44  4974.4  867.94
  4979.2  868.44  5001.1  871.58  5018.5  872.39  5032.7  874.20  5054.2  872.99
  5068.4  873.18  5216.9  879.11  5287.7  882.86  5365.4  885.60  5372.7  886.61
  5393.7  887.22  5407.9  888.81  5428.9  889.40  5450.4  891.21  5538.2  895.53
#Mann=3,-1,0
  4438.9    0.05       0  4973.5    0.04       0  4979.2    0.05       0
Bank Sta=4973.5,4979.2
Exp/Cntr=0.3,0.1

Type RM Length L Ch R = 1,5051,474,474,474
BEGIN DESCRIPTION:
UDS St 54 8.0
END DESCRIPTION:
XS GIS Cut Line= 3
      2250854.86      7208966.55      2250379.00      7209160.00
      2249528.51      7209398.21
#Sta/Elev= 30
  4481.7  891.25  4563.6  885.14  4605.9  883.99  4671.5  877.26  4757.9  870.78
  4855.0  868.24  4963.0  870.09  4973.8  869.39  4977.7  866.75  4978.7  866.25
  4983.5  866.75  4998.0  867.73  5012.4  870.41  5057.7  868.87  5120.0  870.26
  5203.8  876.58  5255.0  878.86  5311.3  878.11  5345.4  876.00  5418.9  873.80
  5536.8  873.97  5587.3  872.69  5660.0  877.89  5678.4  878.61  5683.6  877.84
  5717.8  880.39  5722.9  879.63  5757.1  881.35  5815.8  886.90  5878.6  890.45
#Mann=3,-1,0
  4481.7    0.05       0  4977.7    0.04       0  4983.5    0.05       0
Bank Sta=4977.7,4983.5
Exp/Cntr=0.3,0.1

Type RM Length L Ch R = 1,4577,449,449,449
BEGIN DESCRIPTION:
UDS St 54 7.0
END DESCRIPTION:
XS GIS Cut Line= 3
      2250718.86      7208742.00      2250179.00      7208760.00
      2249632.86      7208732.50
#Sta/Elev= 30
  4459.8  885.18  4509.7  883.23  4547.3  880.66  4589.7  879.50  4599.7  878.44
  4609.7  876.50  4659.8  874.98  4699.8  871.70  4739.8  870.29  4759.8  868.48
  4779.8  868.28  4789.8  866.92  4809.9  866.55  4929.9  867.96  4939.9  867.50
  4959.9  868.37  4990.0  868.11  4994.3  865.39  4995.4  864.89  5000.6  865.39
  5010.0  865.42  5030.0  868.06  5170.2  868.18  5200.2  868.92  5260.3  872.34
  5290.3  874.59  5330.4  878.76  5360.4  880.82  5510.6  888.60  5546.8  889.54
#Mann=3,-1,0
  4459.8    0.05       0  4994.3    0.04       0  5000.6    0.05       0
Bank Sta=4994.3,5000.6
Exp/Cntr=0.3,0.1

Type RM Length L Ch R = 1,4128,450,450,450
BEGIN DESCRIPTION:
UDS St 54 6.0
END DESCRIPTION:
XS GIS Cut Line= 3
      2250673.08      7208343.33      2250229.00      7208360.00
      2249725.00      7208345.38
#Sta/Elev= 30
  4560.3  887.11  4584.4  885.79  4602.1  884.05  4607.1  884.12  4664.4  879.76
  4724.5  876.50  4764.5  872.51  4854.6  866.39  4864.6  866.34  4870.5  865.48
  4891.5  864.90  4892.5  864.40  4896.8  864.40  4897.8  864.90  4974.7  865.66
  4994.7  866.31  5014.7  866.20  5034.7  865.36  5124.7  865.75  5144.7  865.13
  5194.8  865.67  5254.8  869.94  5274.8  872.21  5314.8  875.09  5324.8  876.29
  5344.8  877.44  5354.8  878.63  5464.9  885.52  5504.4  888.77  5508.9  888.77
#Mann=3,-1,0
  4560.3    0.05       0  4891.5    0.04       0  4897.8    0.05       0
Bank Sta=4891.5,4897.8
Exp/Cntr=0.3,0.1