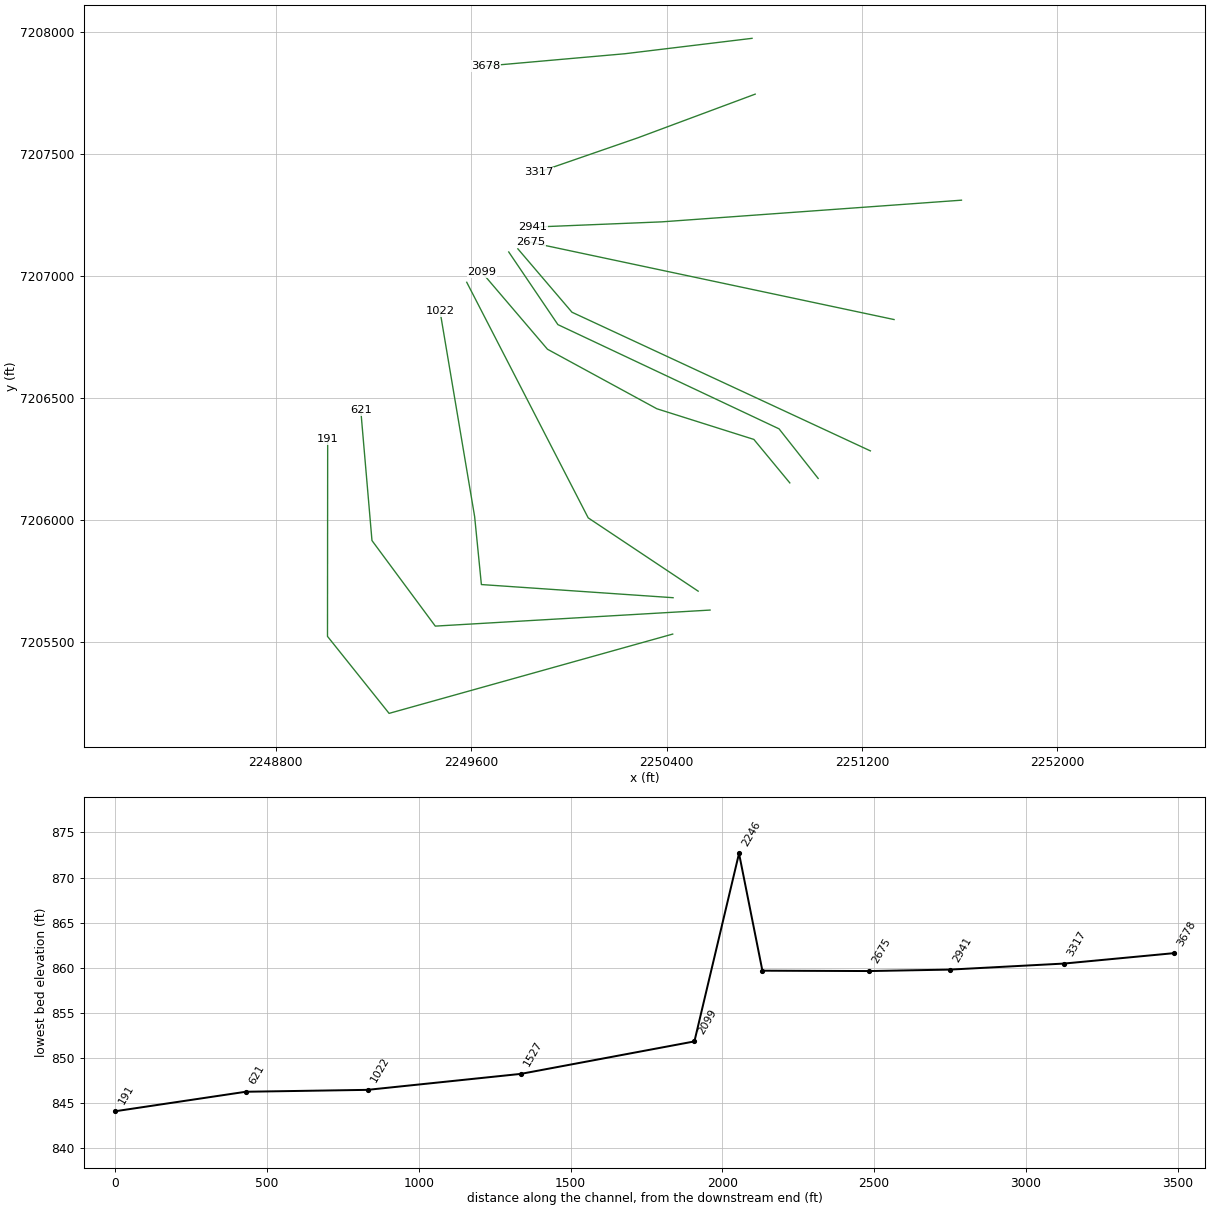
HEC-RAS study UDS St 54.prj: UDS St 54 Base Level Engineering

--- UDS St 54.g01 (geometry) --- (continued)

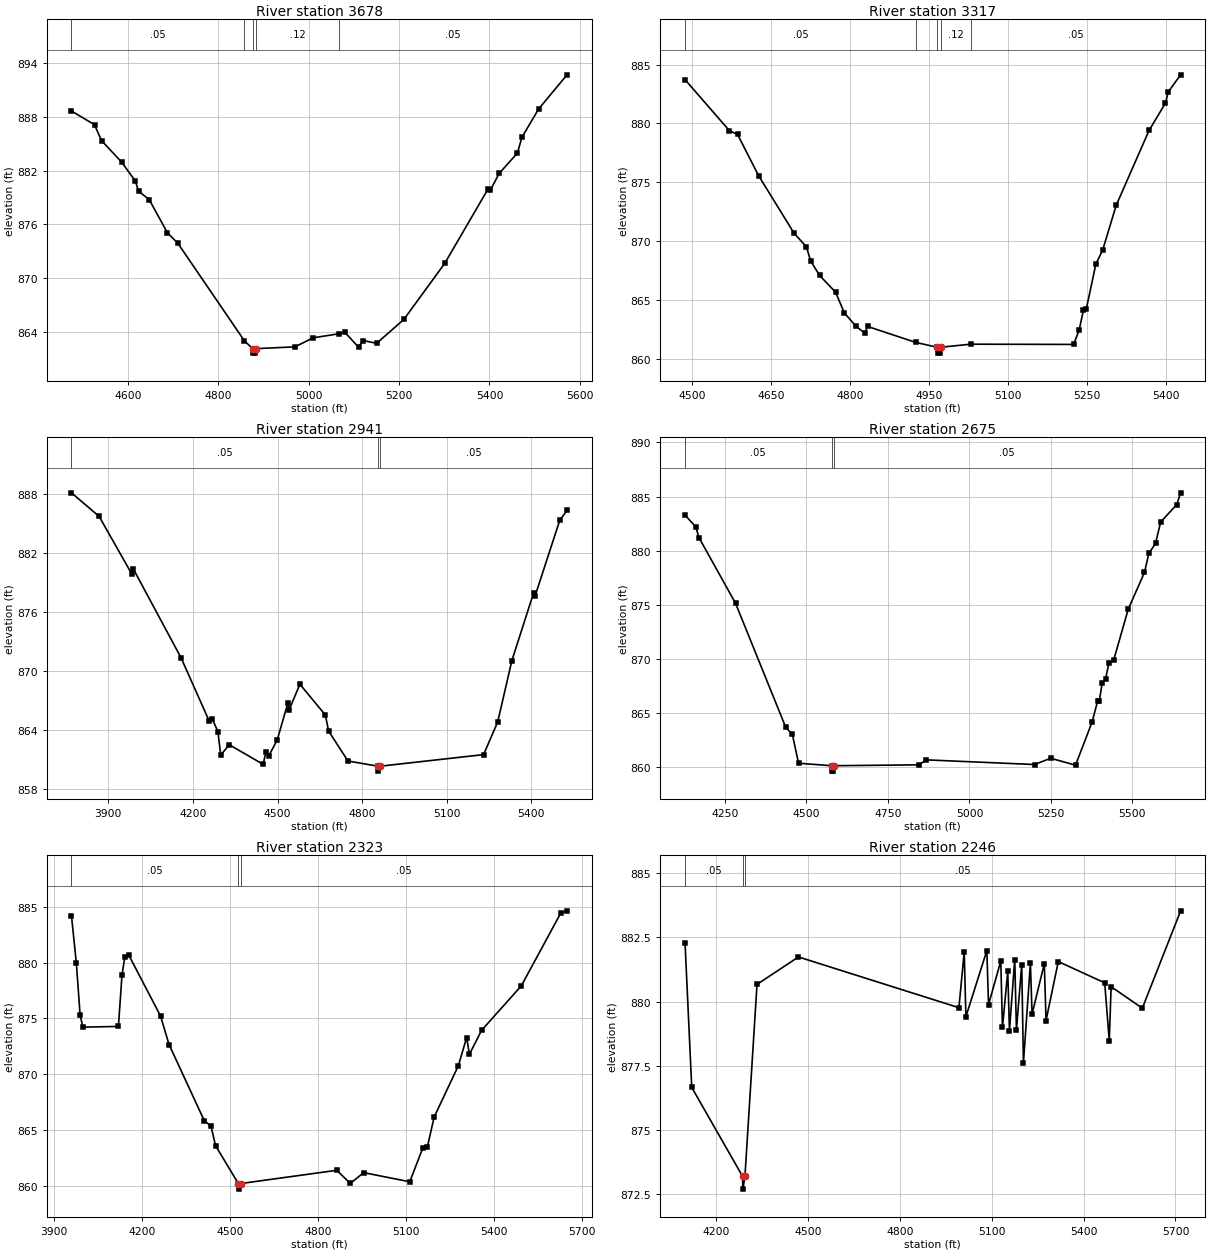
Type RM Length L Ch R = 1,3678,361,361,361
BEGIN DESCRIPTION:
UDS St 54 5.0
END DESCRIPTION:
XS GIS Cut Line= 3
      2250749.62      7207973.05      2250229.00      7207910.00
      2249659.65      7207859.58
#Sta/Elev= 30
  4475.5  888.69  4526.5  887.15  4542.0  885.38  4586.9  882.95  4617.1  880.83
  4623.9  879.72  4647.4  878.79  4687.7  875.08  4710.8  873.90  4858.2  862.98
  4876.4  862.12  4877.5  861.62  4881.8  861.62  4882.8  862.12  4969.7  862.32
  5010.0  863.33  5067.7  863.79  5080.2  863.94  5110.4  862.29  5120.4  863.03
  5150.5  862.72  5210.7  865.39  5301.1  871.66  5396.6  879.95  5401.6  879.81
  5421.6  881.72  5461.7  883.98  5471.8  885.75  5508.5  888.90  5571.5  892.73
#Mann=5,-1,0
  4475.5    0.05       0  4858.2    0.12       0  4876.4    0.07       0
  4882.8    0.12       0  5067.7    0.05       0
Bank Sta=4876.4,4882.8
Exp/Cntr=0.3,0.1

Type RM Length L Ch R = 1,3317,376,376,376
BEGIN DESCRIPTION:
UDS St 54 4.0
END DESCRIPTION:
XS GIS Cut Line= 3
      2250762.54      7207744.59      2250281.38      7207565.53
      2249876.83      7207425.51
#Sta/Elev= 30
  4486.6  883.72  4570.9  879.38  4586.4  879.06  4626.3  875.56  4693.1  870.71
  4717.3  869.49  4725.1  868.32  4742.3  867.07  4772.6  865.65  4789.1  863.90
  4810.5  862.79  4828.0  862.17  4833.3  862.74  4924.9  861.38  4965.8  860.97
  4966.9  860.47  4971.2  860.47  4972.2  860.97  5029.4  861.23  5224.7  861.21
  5235.3  862.43  5243.4  864.12  5248.7  864.19  5267.1  868.05  5279.9  869.22
  5305.7  873.04  5368.1  879.40  5399.2  881.72  5404.6  882.68  5428.1  884.13
#Mann=5,-1,0
  4486.6    0.05       0  4924.9    0.12       0  4965.8    0.07       0
  4972.2    0.12       0  5029.4    0.05       0
Bank Sta=4965.8,4972.2
Exp/Cntr=0.3,0.1

Type RM Length L Ch R = 1,2941,266,266,266
BEGIN DESCRIPTION:
UDS St 54 3.0
END DESCRIPTION:
XS GIS Cut Line= 3
      2251606.97      7207310.50      2250379.54      7207221.75
      2249853.32      7207200.22
#Sta/Elev= 30
  3769.2  888.11  3867.4  885.71  3983.4  879.84  3988.4  880.38  4158.2  871.31
  4257.4  864.91  4268.5  865.12  4288.5  863.82  4298.6  861.42  4328.6  862.49
  4448.9  860.49  4459.0  861.78  4469.0  861.35  4499.1  862.99  4536.5  866.72
  4541.5  866.06  4579.3  868.64  4669.5  865.51  4681.0  863.88  4749.7  860.83
  4856.8  860.30  4857.8  859.80  4863.3  860.30  5230.6  861.48  5280.6  864.80
  5330.7  871.02  5407.7  877.91  5412.7  877.57  5500.8  885.33  5526.5  886.32
#Mann=3,-1,0
  3769.2    0.05       0  4856.8   0.033       0  4863.3    0.05       0
Bank Sta=4856.8,4863.3
Exp/Cntr=0.3,0.1

Type RM Length L Ch R = 1,2675,352,352,352
BEGIN DESCRIPTION:
UDS St 54 2.2
END DESCRIPTION:
XS GIS Cut Line= 2
      2251331.00      7206821.88      2249843.55      7207137.67
#Sta/Elev= 30
  4127.4  883.29  4160.1  882.21  4170.3  881.20  4282.3  875.15  4436.3  863.69
  4456.6  863.04  4475.7  860.37  4576.8  860.14  4577.9  859.64  4582.3  859.64
  4583.3  860.14  4845.0  860.22  4867.7  860.68  5199.7  860.25  5249.4  860.83
  5325.5  860.19  5376.6  864.20  5393.2  866.11  5398.3  866.08  5407.3  867.78
  5417.5  868.14  5427.8  869.60  5442.8  869.92  5487.3  874.61  5537.0  877.99
  5550.4  879.75  5570.9  880.67  5586.6  882.65  5636.2  884.27  5648.0  885.35
#Mann=3,-1,0
  4127.4    0.05       0  4576.8   0.033       0  4583.3    0.05       0
Bank Sta=4576.8,4583.3
Exp/Cntr=0.3,0.1

Type RM Length L Ch R = 1,2323,77,77,77
BEGIN DESCRIPTION:
UDS St 54 2.1
END DESCRIPTION:
XS GIS Cut Line= 3
      2251234.11      7206284.24      2250012.54      7206851.82
      2249791.04      7207111.36
#Sta/Elev= 30
  3960.6  884.20  3977.3  879.96  3990.0  875.33  3999.3  874.21  4120.6  874.27
  4132.8  878.89  4142.7  880.54  4155.7  880.68  4264.0  875.21  4293.1  872.65
  4413.1  865.82  4436.0  865.33  4451.4  863.58  4529.1  860.18  4530.3  859.68
  4536.9  860.18  4864.6  861.37  4910.4  860.19  4956.1  861.16  5113.0  860.34
  5157.1  863.34  5173.2  863.48  5196.1  866.14  5278.4  870.74  5306.8  873.27
  5316.3  871.78  5358.0  873.93  5493.0  877.91  5628.1  884.47  5648.8  884.64
#Mann=3,-1,0
  3960.6    0.05       0  4529.1   0.033       0  4536.9    0.05       0
Bank Sta=4529.1,4536.9
Exp/Cntr=0.3,0.1

Type RM Length L Ch R = 1,2246,147,147,147
BEGIN DESCRIPTION:
UDS St 54 2.0
END DESCRIPTION:
XS GIS Cut Line= 4
      2251020.30      7206171.48      2250860.24      7206374.43
      2249954.92      7206801.10      2249753.72      7207098.43
#Sta/Elev= 30
  4098.6  882.29  4120.4  876.65  4286.4  873.18  4287.5  872.68  4294.2  873.18
  4333.6  880.67  4469.0  881.74  4992.9  879.76  5010.2  881.94  5015.7  879.41
  5084.1  881.99  5089.6  879.88  5129.6  881.58  5135.1  878.99  5152.4  881.18
  5157.9  878.87  5175.2  881.64  5180.7  878.89  5198.0  881.44  5203.5  877.59
  5226.3  881.49  5231.8  879.51  5271.8  881.48  5277.4  879.26  5317.4  881.56
  5468.9  880.73  5483.9  878.47  5489.9  880.58  5591.8  879.74  5716.9  883.54
#Mann=3,-1,0
  4098.6    0.05       0  4286.4    0.04       0  4294.2    0.05       0
Bank Sta=4286.4,4294.2
Exp/Cntr=0.3,0.1

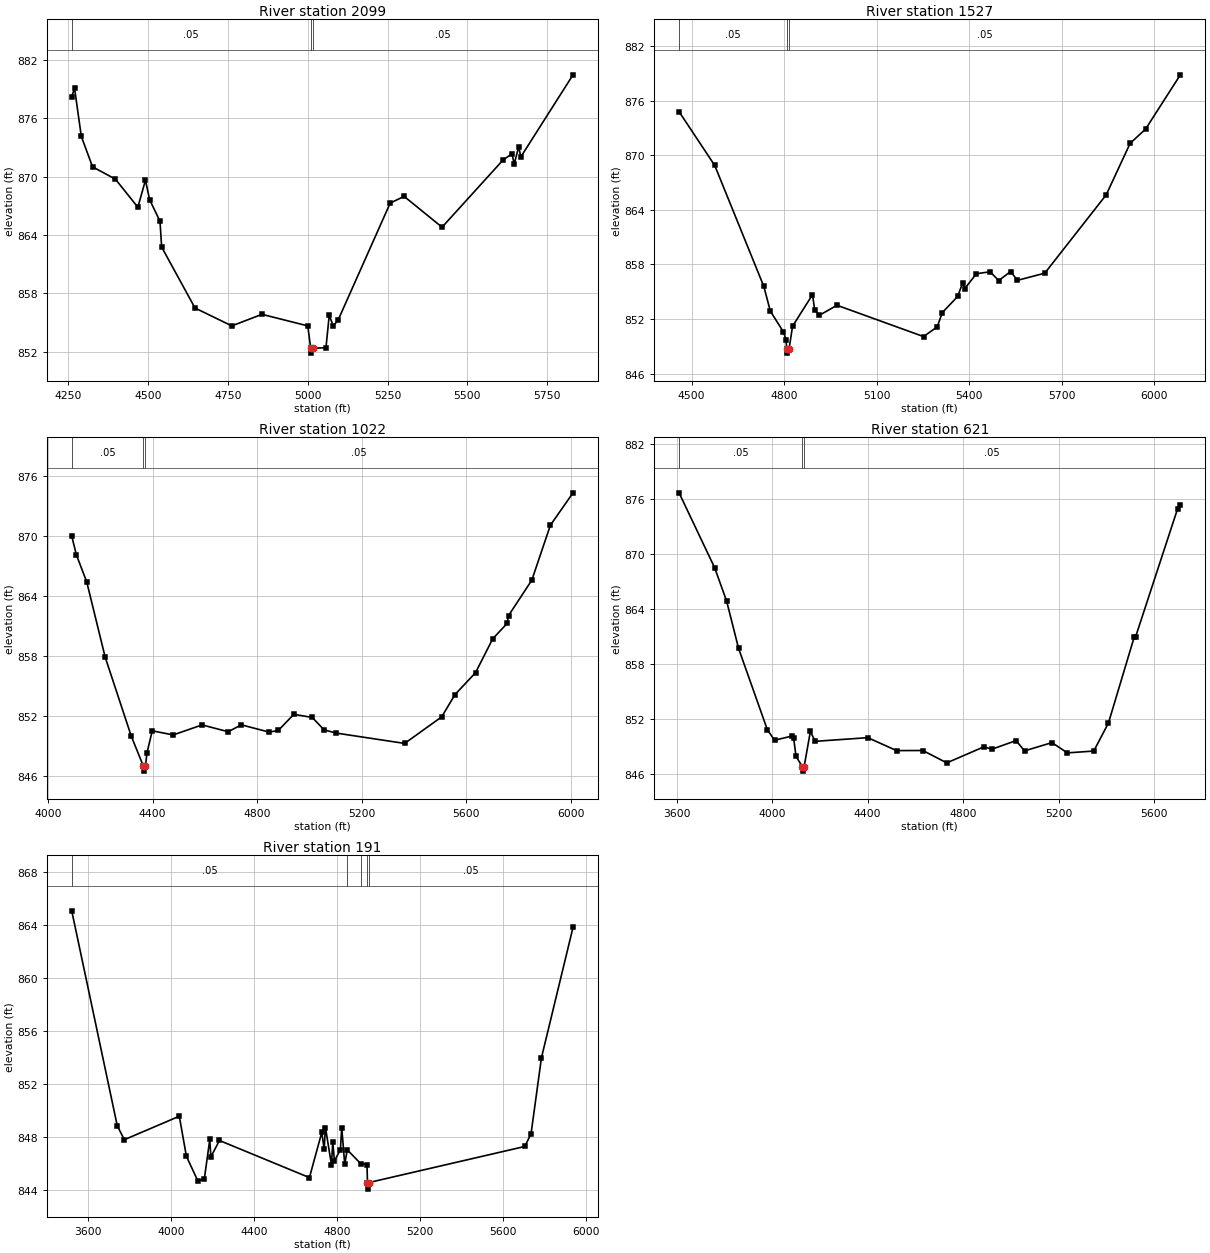
Type RM Length L Ch R = 1,2099,572,572,572
BEGIN DESCRIPTION:
UDS St 54 1.1
END DESCRIPTION:
XS GIS Cut Line= 5
      2250904.26      7206153.21      2250757.09      7206331.17
      2250360.09      7206456.61      2249912.25      7206700.29
      2249643.89      7207014.72
#Sta/Elev= 30
  4260.4  878.21  4269.2  879.09  4290.4  874.13  4325.6  871.00  4397.3  869.73
  4467.6  866.84  4491.3  869.62  4504.5  867.61  4536.9  865.41  4542.1  862.75
  4646.6  856.48  4762.0  854.64  4856.4  855.83  5000.0  854.64  5009.0  852.34
  5010.2  851.84  5016.9  852.34  5056.9  852.40  5067.1  855.72  5079.7  854.65
  5094.7  855.22  5258.1  867.27  5301.8  867.96  5420.6  864.79  5611.4  871.69
  5640.0  872.35  5646.5  871.27  5660.8  873.07  5667.4  872.02  5830.9  880.46
#Mann=3,-1,0
  4260.4    0.05       0  5009.0    0.04       0  5016.9    0.05       0
Bank Sta=5009,5016.9
Exp/Cntr=0.3,0.1

Type RM Length L Ch R = 1,1527,505,505,505
BEGIN DESCRIPTION:
UDS St 54 1.0
END DESCRIPTION:
XS GIS Cut Line= 3
      2250529.01      7205710.00      2250079.00      7206010.00
      2249581.76      7206974.42
#Sta/Elev= 30
  4459.2  874.78  4574.9  868.87  4734.1  855.57  4755.2  852.86  4797.2  850.60
  4806.2  849.73  4808.3  848.74  4809.5  848.24  4816.2  848.74  4827.3  851.20
  4891.9  854.66  4899.4  852.95  4914.4  852.40  4971.5  853.50  5252.1  850.06
  5296.4  851.12  5312.9  852.69  5362.9  854.47  5379.4  856.00  5385.1  855.31
  5423.8  856.97  5468.1  857.18  5495.9  856.22  5534.6  857.21  5556.7  856.24
  5645.4  857.03  5844.8  865.65  5922.2  871.30  5972.2  872.86  6085.1  878.83
#Mann=3,-1,0
  4459.2    0.05       0  4808.3    0.04       0  4816.2    0.05       0
Bank Sta=4808.3,4816.2
Exp/Cntr=0.3,0.1

Type RM Length L Ch R = 1,1022,401,401,401
BEGIN DESCRIPTION:
UDS St 54 0.9
END DESCRIPTION:
XS GIS Cut Line= 4
      2250426.39      7205683.18      2249641.71      7205737.04
      2249614.08      7206015.15      2249472.51      7206855.39
#Sta/Elev= 30
  4090.3  869.98  4107.7  868.13  4147.8  865.38  4218.0  857.89  4318.2  849.96
  4364.4  846.97  4365.6  846.47  4372.3  846.97  4378.4  848.32  4398.4  850.50
  4478.6  850.09  4588.9  851.09  4689.1  850.41  4739.2  851.10  4845.8  850.37
  4880.8  850.54  4940.1  852.15  5010.5  851.84  5055.8  850.60  5100.9  850.28
  5364.1  849.24  5506.0  851.90  5556.7  854.12  5635.5  856.32  5701.1  859.70
  5756.6  861.25  5761.6  862.02  5850.8  865.57  5921.8  871.06  6008.4  874.30
#Mann=3,-1,0
  4090.3    0.05       0  4364.4    0.04       0  4372.3    0.05       0
Bank Sta=4364.4,4372.3
Exp/Cntr=0.3,0.1

Type RM Length L Ch R = 1,621,430,430,430
BEGIN DESCRIPTION:
UDS St 54 0.8
END DESCRIPTION:
XS GIS Cut Line= 4
      2250577.81      7205632.56      2249452.99      7205566.88
      2249193.83      7205917.09      2249147.89      7206451.20
#Sta/Elev= 30
  3610.7  876.62  3759.8  868.44  3809.9  864.80  3859.9  859.64  3980.1  850.79
  4010.2  849.63  4084.4  850.09  4090.3  849.86  4100.3  847.87  4126.4  846.76
  4127.6  846.26  4134.3  846.76  4160.4  850.59  4180.5  849.51  4400.9  849.91
  4521.1  848.50  4631.2  848.51  4731.4  847.16  4885.7  848.90  4921.2  848.66
  5021.4  849.59  5056.9  848.47  5171.7  849.37  5236.3  848.25  5346.7  848.45
  5408.2  851.51  5516.7  860.94  5521.7  860.90  5698.0  874.91  5709.2  875.27
#Mann=3,-1,0
  3610.7    0.05       0  4126.4    0.04       0  4134.3    0.05       0
Bank Sta=4126.4,4134.3
Exp/Cntr=0.3,0.1

Type RM Length L Ch R = 1,191,0,0,0
BEGIN DESCRIPTION:
UDS St 54 0.7
END DESCRIPTION:
XS GIS Cut Line= 4
      2250424.82      7205534.24      2249263.87      7205209.66
      2249011.72      7205524.86      2249012.46      7206332.25
#Sta/Elev= 30
  3520.7  865.10  3740.2  848.88  3774.3  847.83  4039.3  849.60  4073.4  846.58
  4129.0  844.71  4160.1  844.89  4186.2  847.85  4191.4  846.53  4232.8  847.77
  4666.5  844.97  4726.1  848.38  4737.5  847.12  4743.9  848.74  4772.7  845.95
  4779.1  847.66  4787.1  846.23  4815.9  847.08  4822.3  848.75  4836.7  845.97
  4848.7  847.07  4913.9  846.02  4944.0  845.94  4946.4  844.60  4947.6  844.10
  4954.3  844.60  5705.0  847.32  5735.0  848.29  5785.0  854.01  5937.2  863.85
#Mann=5,-1,0
  3520.7    0.05       0  4848.7    0.12       0  4913.9    0.05       0
  4946.4    0.04       0  4954.3    0.05       0
Bank Sta=4946.4,4954.3
Exp/Cntr=0.3,0.1

Chan Stop Cuts=-1