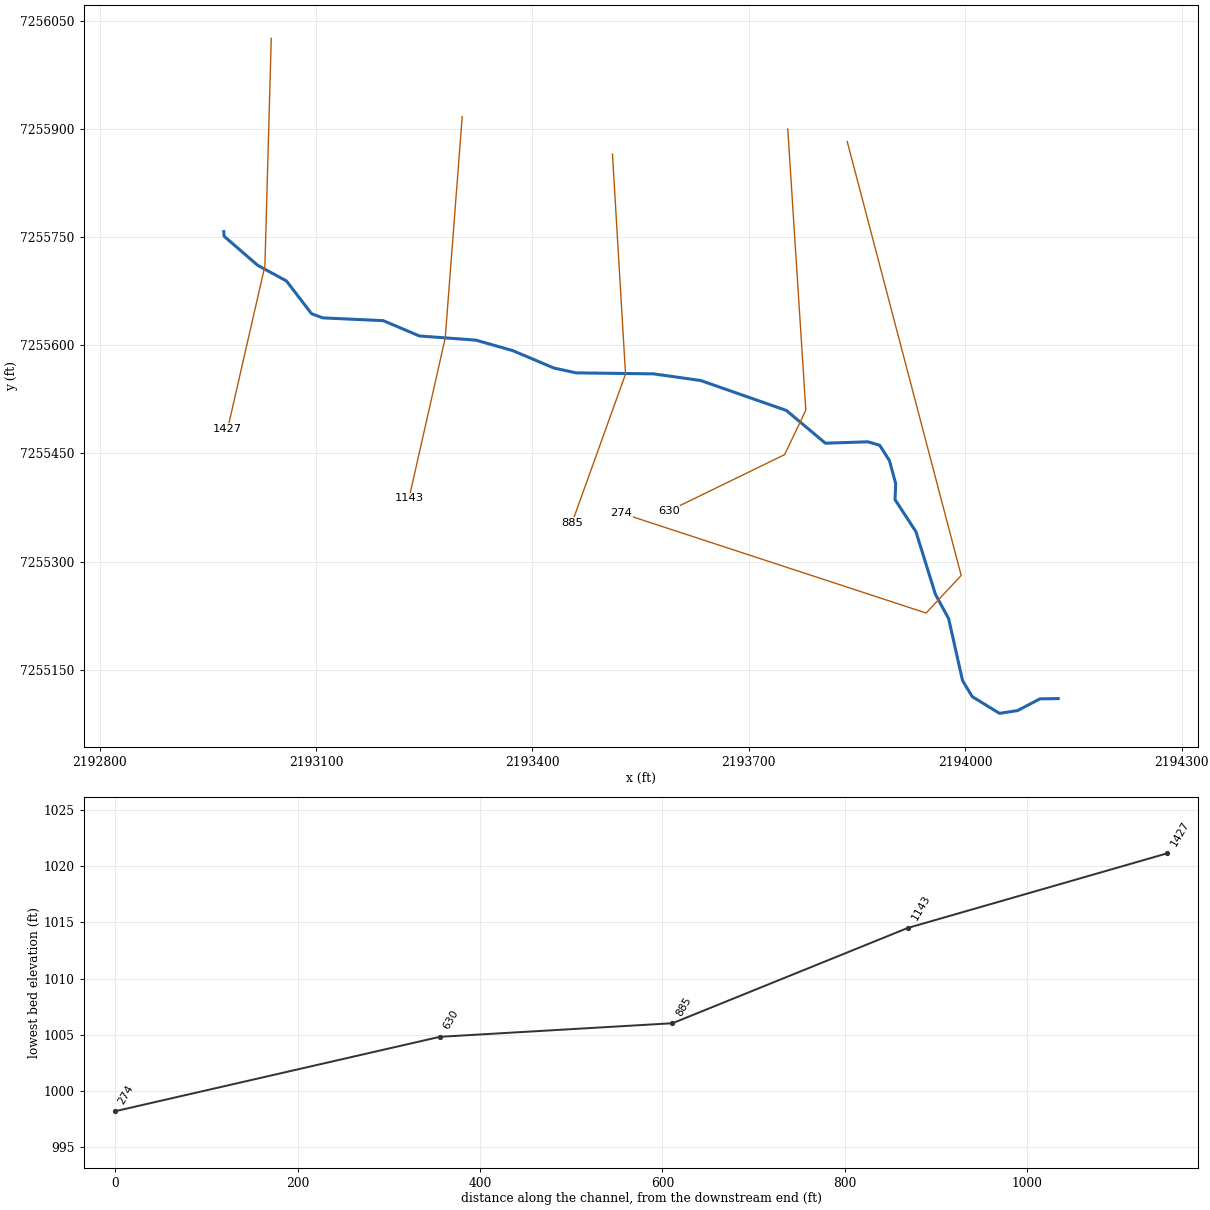
--- Upper Denton 04.prj (project) ---

Proj Title=Upper Denton 04 Base Level Engineering
Current Plan=p01
Default Exp/Contr=0.3,0.1
English Units
Geom File=g01
Flow File=f01
Plan File=p01
BEGIN DESCRIPTION:
Upper Denton 04
END DESCRIPTION:

--- Upper Denton 04.p01 (plan) ---

Plan Title=Multiple Run
Short Identifier=Multiple
Geom File=g01
Flow File=f01
Subcritical Flow
K Sum by GR= 0
Std Step Tol= 0.01
Critical Tol= 0.01
Num of Std Step Trials= 20
Max Error Tol= 0.3
Flow Tol Ratio= 0.001
Split Flow NTrial= 30
Split Flow Tol= 0.02
Split Flow Ratio= 0.02
Log Output Level= 0
Friction Slope Method= 1
Unsteady Friction Slope Method= 2
Unsteady Bridges Friction Slope Method= 1
Parabolic Critical Depth
Global Vel Dist=  1 , 1 , 1
Global Log Level= 0
CheckData=True
Encroach Param= -1, 0, 0, 0
BEGIN DESCRIPTION:
Multiple Run
END DESCRIPTION:

--- Upper Denton 04.f01 (steady flow) ---

Flow Title=Multiple
Number of Profiles=7
Profile Names=10-year,25-year,50-year,1pct_min,100-year,1pct_plu,500-year
River Rch & RM= Upper Denton 04,Reach-1,1427
     142     180     208     120     240     479     319
Boundary for River Rch & Prof#=Upper Denton 04,Reach-1,1
Up Type=0
Dn Type=3
Dn Slope=0.005
Boundary for River Rch & Prof#=Upper Denton 04,Reach-1,2
Up Type=0
Dn Type=3
Dn Slope=0.005
Boundary for River Rch & Prof#=Upper Denton 04,Reach-1,3
Up Type=0
Dn Type=3
Dn Slope=0.005
Boundary for River Rch & Prof#=Upper Denton 04,Reach-1,4
Up Type=0
Dn Type=3
Dn Slope=0.005
Boundary for River Rch & Prof#=Upper Denton 04,Reach-1,5
Up Type=0
Dn Type=3
Dn Slope=0.005
Boundary for River Rch & Prof#=Upper Denton 04,Reach-1,6
Up Type=0
Dn Type=3
Dn Slope=0.005
Boundary for River Rch & Prof#=Upper Denton 04,Reach-1,7
Up Type=0
Dn Type=3
Dn Slope=0.005

--- Upper Denton 04.g01 (geometry) ---

Geom Title=Existing Conditions

River Reach=Upper Denton 04,Reach-1
Reach XY= 30
      2192971.94      7255757.45      2192972.41      7255751.12
      2193018.86      7255710.87      2193058.84      7255689.10
      2193093.59      7255643.73      2193109.04      7255637.93
      2193193.04      7255634.07      2193243.24      7255612.83
      2193321.45      7255607.04      2193372.62      7255592.55
      2193429.59      7255568.42      2193460.48      7255561.66
      2193567.83      7255560.29      2193633.31      7255551.04
      2193752.06      7255509.52      2193806.13      7255464.14
      2193865.02      7255466.07      2193881.44      7255461.25
      2193894.95      7255440.01      2193903.64      7255408.14
      2193902.68      7255385.94      2193931.64      7255341.52
      2193958.68      7255254.63      2193977.02      7255220.84
      2193996.33      7255134.91      2194009.85      7255112.70
      2194047.50      7255089.53      2194072.61      7255093.39
      2194103.64      7255109.68      2194129.00      7255110.00

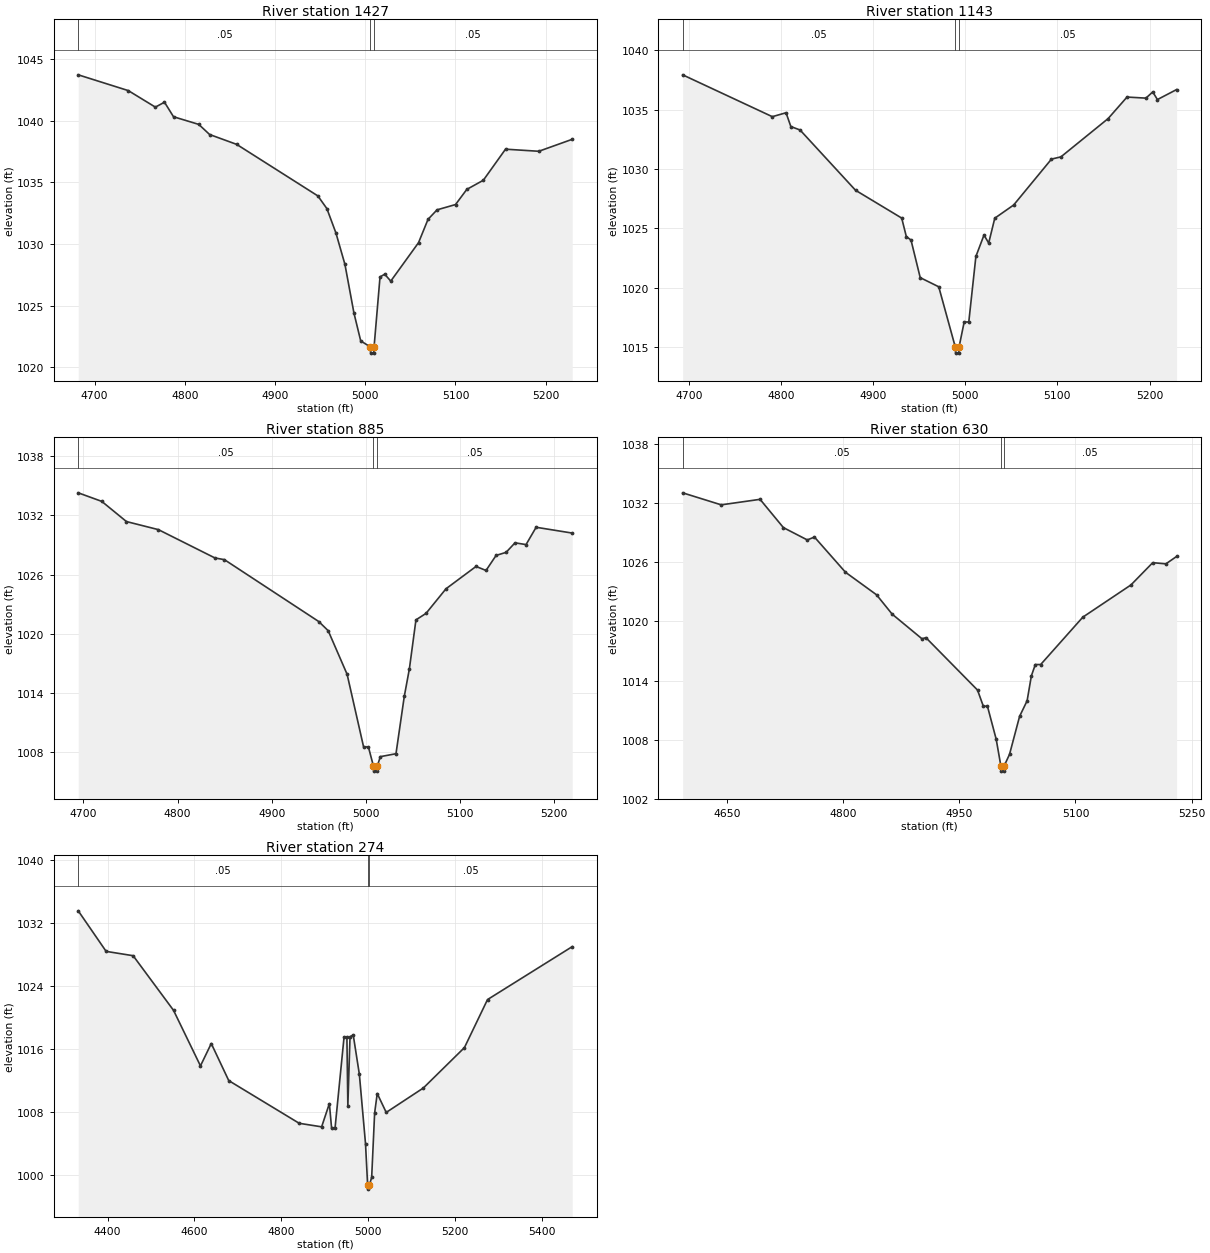
Type RM Length L Ch R = 1,1427,284,284,284
BEGIN DESCRIPTION:
Upper Denton 04 4.0
END DESCRIPTION:
XS GIS Cut Line= 3
      2193037.81      7256025.51      2193029.00      7255710.00
      2192977.27      7255483.98
#Sta/Elev= 30
  4681.9 1043.72  4737.4 1042.44  4767.4 1041.10  4777.5 1041.50  4787.5 1040.32
  4815.5 1039.70  4827.5 1038.88  4857.5 1038.08  4947.5 1033.90  4957.5 1032.87
  4967.5 1030.90  4977.5 1028.35  4987.5 1024.40  4995.0 1022.14  5005.8 1021.65
  5006.0 1021.15  5009.5 1021.15  5009.8 1021.65  5016.4 1027.33  5021.6 1027.55
  5028.3 1026.99  5059.1 1030.11  5069.6 1032.00  5079.6 1032.77  5100.1 1033.20
  5112.6 1034.43  5130.9 1035.17  5155.5 1037.69  5192.4 1037.52  5229.4 1038.49
#Mann=3,-1,0
  4681.9    0.05       0  5005.8   0.033       0  5009.8    0.05       0
Bank Sta=5005.8,5009.8
Exp/Cntr=0.3,0.1

Type RM Length L Ch R = 1,1143,258,258,258
BEGIN DESCRIPTION:
Upper Denton 04 3.0
END DESCRIPTION:
XS GIS Cut Line= 3
      2193302.57      7255917.06      2193279.00      7255610.00
      2193228.79      7255387.56
#Sta/Elev= 30
  4693.4 1037.92  4790.7 1034.40  4805.6 1034.73  4810.8 1033.57  4820.8 1033.28
  4881.0 1028.21  4931.1 1025.87  4936.1 1024.32  4941.2 1024.02  4951.2 1020.86
  4971.3 1020.09  4989.3 1015.01  4989.6 1014.51  4993.1 1014.51  4993.3 1015.01
  4998.9 1017.13  5003.9 1017.13  5011.6 1022.64  5020.4 1024.44  5025.5 1023.77
  5032.1 1025.86  5052.6 1026.97  5093.6 1030.83  5103.9 1031.02  5155.1 1034.24
  5175.6 1036.05  5196.1 1035.96  5203.5 1036.48  5208.6 1035.84  5229.4 1036.68
#Mann=3,-1,0
  4693.4    0.05       0  4989.3   0.033       0  4993.3    0.05       0
Bank Sta=4989.3,4993.3
Exp/Cntr=0.3,0.1

Type RM Length L Ch R = 1,885,255,255,255
BEGIN DESCRIPTION:
Upper Denton 04 2.0
END DESCRIPTION:
XS GIS Cut Line= 3
      2193510.90      7255864.95      2193529.00      7255560.00
      2193454.88      7255353.91
#Sta/Elev= 30
  4694.5 1034.30  4719.5 1033.43  4745.7 1031.38  4779.6 1030.56  4839.7 1027.68
  4849.7 1027.51  4949.9 1021.22  4959.9 1020.29  4980.0 1015.86  4997.5 1008.48
  5002.6 1008.48  5008.0 1006.52  5008.3 1006.02  5011.8 1006.02  5012.0 1006.52
  5015.3 1007.49  5031.9 1007.79  5040.7 1013.61  5046.1 1016.40  5053.1 1021.39
  5063.8 1022.05  5085.0 1024.55  5116.9 1026.82  5127.5 1026.41  5138.2 1027.94
  5148.8 1028.25  5158.3 1029.22  5170.0 1029.04  5180.7 1030.80  5219.0 1030.21
#Mann=3,-1,0
  4694.5    0.05       0  5008.0   0.033       0  5012.0    0.05       0
Bank Sta=5008,5012
Exp/Cntr=0.3,0.1

Type RM Length L Ch R = 1,630,356,356,356
BEGIN DESCRIPTION:
Upper Denton 04 1.0
END DESCRIPTION:
XS GIS Cut Line= 4
      2193753.96      7255899.70      2193779.00      7255510.00
      2193749.62      7255448.29      2193589.07      7255370.18
#Sta/Elev= 30
  4593.1 1033.06  4642.9 1031.84  4693.0 1032.40  4723.1 1029.53  4753.9 1028.28
  4763.2 1028.57  4803.2 1025.00  4843.3 1022.71  4863.4 1020.75  4902.0 1018.24
  4907.0 1018.36  4973.6 1013.04  4981.1 1011.40  4986.4 1011.40  4997.7 1008.05
  5003.8 1005.31  5004.0 1004.81  5007.5 1004.81  5007.8 1005.31  5014.9 1006.51
  5027.9 1010.37  5037.6 1011.95  5043.1 1014.48  5048.2 1015.63  5055.1 1015.63
  5109.5 1020.44  5171.6 1023.71  5199.7 1025.97  5216.7 1025.85  5230.5 1026.60
#Mann=3,-1,0
  4593.1    0.05       0  5003.8   0.033       0  5007.8    0.05       0
Bank Sta=5003.8,5007.8
Exp/Cntr=0.3,0.1

Type RM Length L Ch R = 1,274,0,0,0
BEGIN DESCRIPTION:
Upper Denton 04 0.5
END DESCRIPTION:
XS GIS Cut Line= 4
      2193836.41      7255882.37      2193994.41      7255280.75
      2193945.80      7255228.67      2193523.10      7255367.26
#Sta/Elev= 30
  4332.2 1033.52  4396.5 1028.37  4458.7 1027.82  4551.8 1020.88  4613.8 1013.83
  4638.7 1016.67  4679.0 1011.96  4841.3 1006.54  4893.0 1006.09  4910.8 1009.04
  4916.0 1005.89  4924.0 1005.99  4944.7 1017.51  4951.2 1017.52  4953.4 1008.75
  4958.4 1017.52  4965.8 1017.76  4979.9 1012.77  4994.1 1003.95  4999.0  998.68
  4999.2  998.18  5003.0  998.68  5008.3  999.68  5015.1 1007.84  5021.1 1010.32
  5041.8 1007.92  5127.3 1011.02  5222.0 1016.15  5275.2 1022.25  5470.3 1028.97
#Mann=3,-1,0
  4332.2    0.05       0  4999.0   0.033       0  5003.0    0.05       0
Bank Sta=4999,5003
Exp/Cntr=0.3,0.1

Chan Stop Cuts=-1