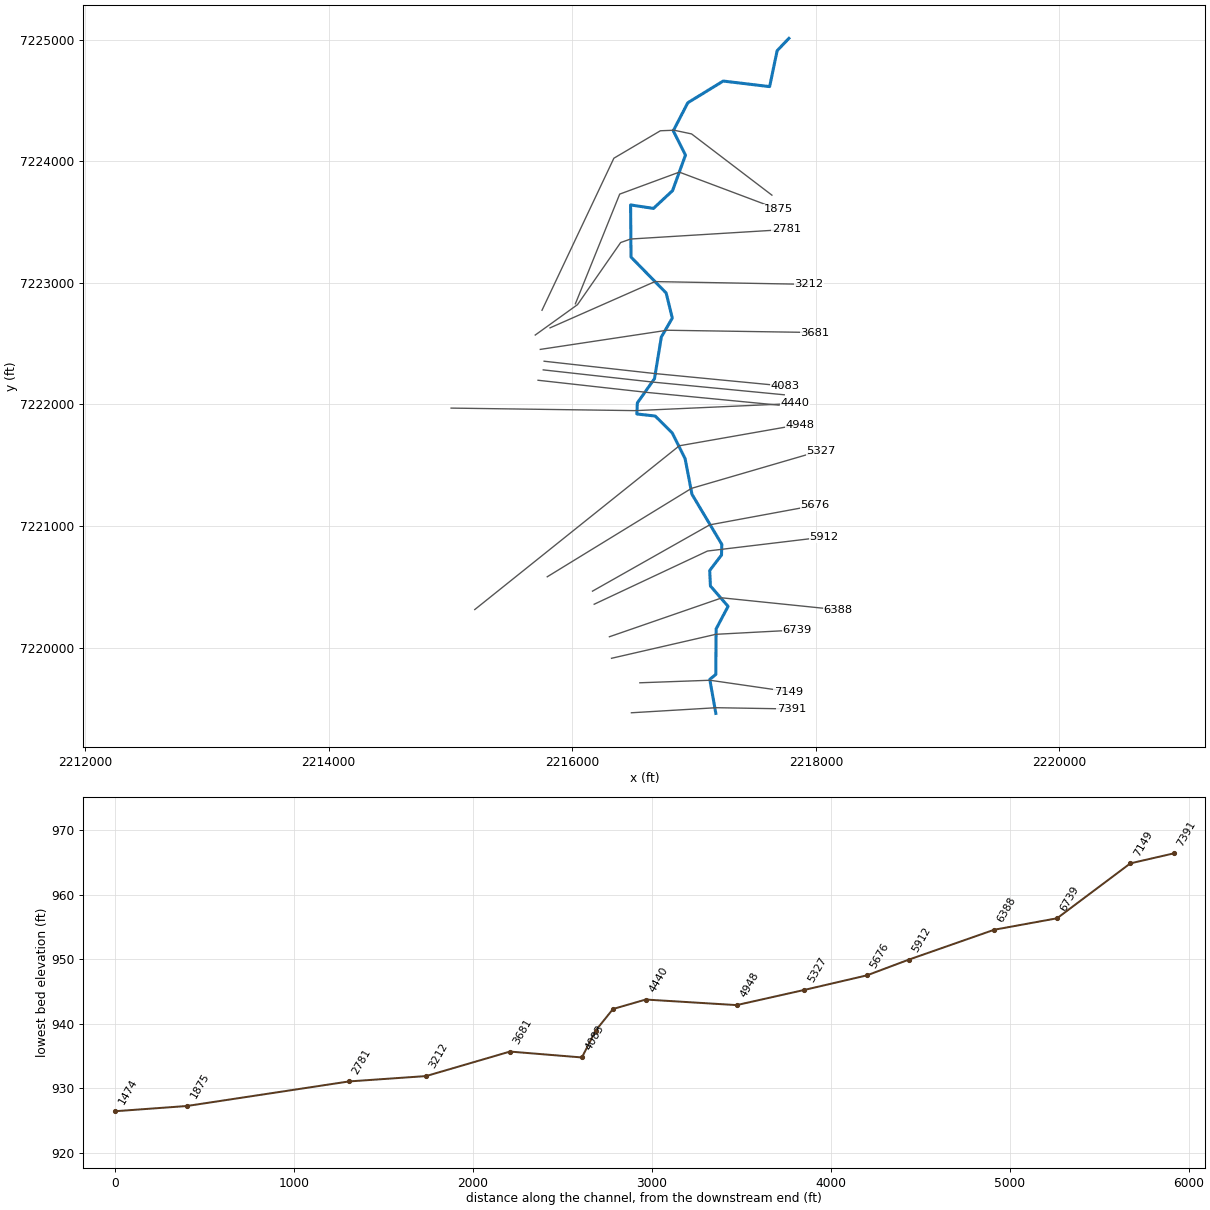
--- Upper Denton 100.prj (project) ---

Proj Title=Upper Denton 100 Base Level Engineering
Current Plan=p01
Default Exp/Contr=0.3,0.1
English Units
Geom File=g01
Flow File=f01
Plan File=p01
BEGIN DESCRIPTION:
Upper Denton 100
END DESCRIPTION:

--- Upper Denton 100.p01 (plan) ---

Plan Title=Multiple Run
Short Identifier=Multiple
Geom File=g01
Flow File=f01
Subcritical Flow
K Sum by GR= 0
Std Step Tol= 0.01
Critical Tol= 0.01
Num of Std Step Trials= 20
Max Error Tol= 0.3
Flow Tol Ratio= 0.001
Split Flow NTrial= 30
Split Flow Tol= 0.02
Split Flow Ratio= 0.02
Log Output Level= 0
Friction Slope Method= 1
Unsteady Friction Slope Method= 2
Unsteady Bridges Friction Slope Method= 1
Parabolic Critical Depth
Global Vel Dist=  1 , 1 , 1
Global Log Level= 0
CheckData=True
Encroach Param= -1, 0, 0, 0
BEGIN DESCRIPTION:
Multiple Run
END DESCRIPTION:

--- Upper Denton 100.f01 (steady flow) ---

Flow Title=Multiple
Number of Profiles=7
Profile Names=10-year,25-year,50-year,1pct_min,100-year,1pct_plu,500-year
River Rch & RM= Upper Denton 100,Reach-1,7391
     781    1107    1384     860    1717    3425    2648
River Rch & RM= Upper Denton 100,Reach-1,4257
     776    1094    1363     843    1682    3357    2570
Boundary for River Rch & Prof#=Upper Denton 100,Reach-1,1
Up Type=0
Dn Type=3
Dn Slope=0.005
Boundary for River Rch & Prof#=Upper Denton 100,Reach-1,2
Up Type=0
Dn Type=3
Dn Slope=0.005
Boundary for River Rch & Prof#=Upper Denton 100,Reach-1,3
Up Type=0
Dn Type=3
Dn Slope=0.005
Boundary for River Rch & Prof#=Upper Denton 100,Reach-1,4
Up Type=0
Dn Type=3
Dn Slope=0.005
Boundary for River Rch & Prof#=Upper Denton 100,Reach-1,5
Up Type=0
Dn Type=3
Dn Slope=0.005
Boundary for River Rch & Prof#=Upper Denton 100,Reach-1,6
Up Type=0
Dn Type=3
Dn Slope=0.005
Boundary for River Rch & Prof#=Upper Denton 100,Reach-1,7
Up Type=0
Dn Type=3
Dn Slope=0.005

--- Upper Denton 100.g01 (geometry) ---

Geom Title=Existing Conditions

River Reach=Upper Denton 100,Reach-1
Reach XY= 30
      2217179.00      7219460.00      2217129.27      7219739.70
      2217178.70      7219780.30      2217181.24      7220154.07
      2217279.41      7220339.87      2217134.45      7220507.55
      2217128.68      7220635.11      2217225.53      7220761.50
      2217228.06      7220849.51      2216982.83      7221261.58
      2216926.75      7221554.07      2216820.86      7221766.06
      2216681.44      7221904.53      2216530.36      7221921.54
      2216534.38      7222012.36      2216675.24      7222211.56
      2216731.24      7222554.07      2216821.47      7222709.99
      2216771.18      7222916.19      2216482.54      7223211.46
      2216478.98      7223640.10      2216666.90      7223611.77
      2216823.48      7223757.56      2216929.80      7224049.95
      2216829.56      7224249.36      2216948.61      7224480.20
      2217239.50      7224658.81      2217620.72      7224613.06
      2217682.48      7224908.56      2217779.00      7225010.00

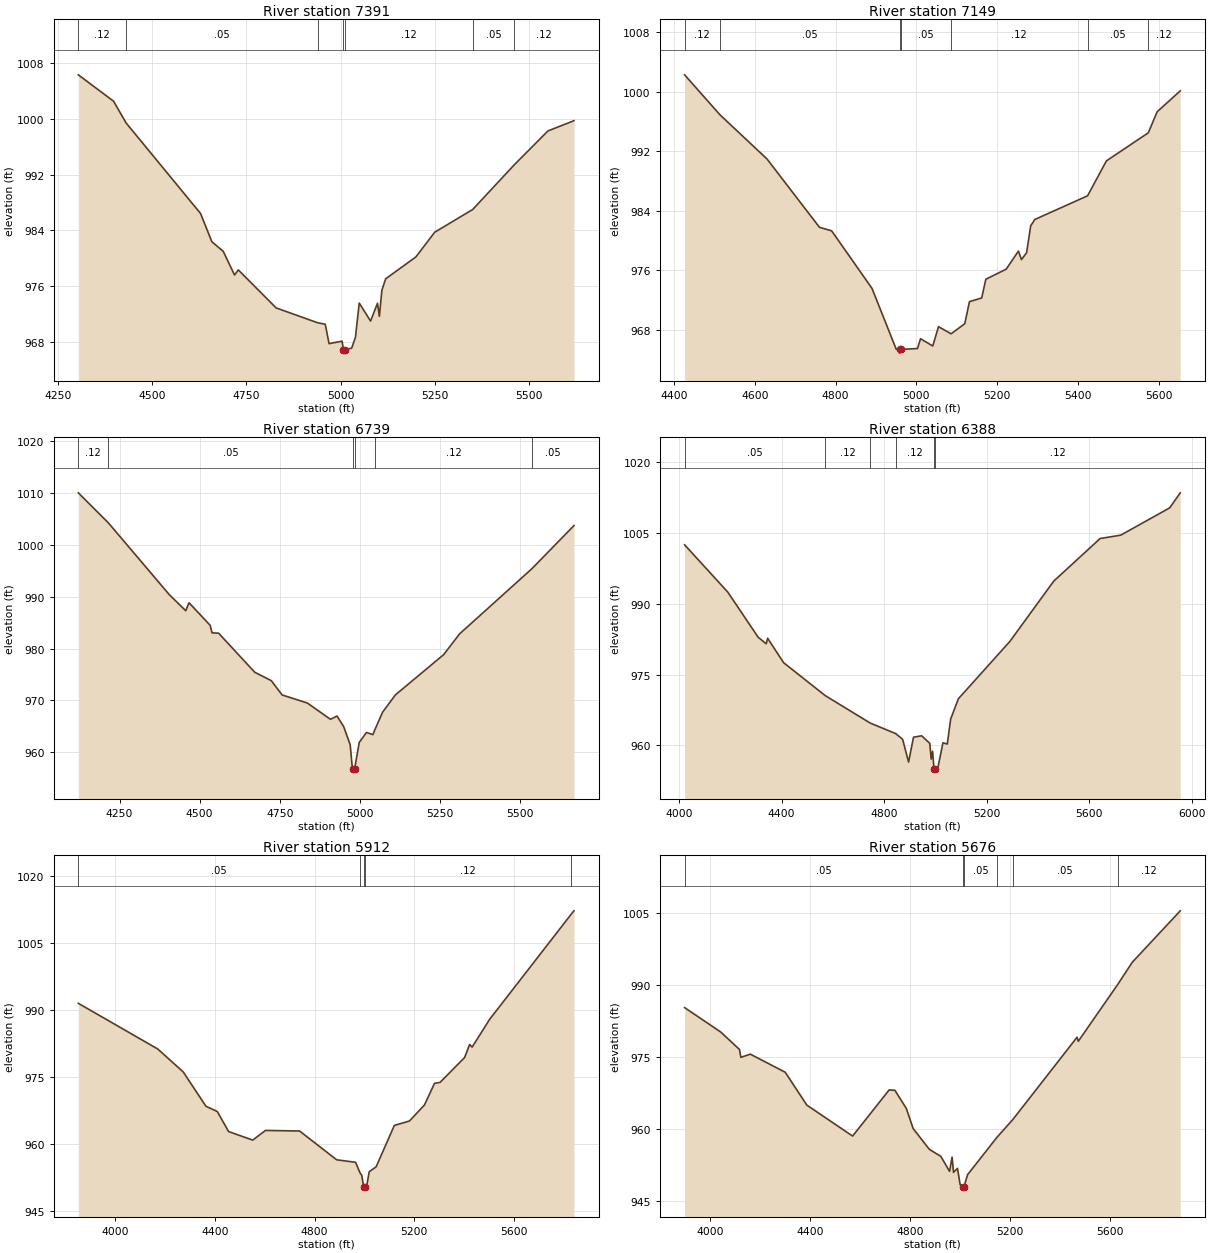
Type RM Length L Ch R = 1,7391,242,242,242
BEGIN DESCRIPTION:
Upper Denton 100 14.5
END DESCRIPTION:
XS GIS Cut Line= 3
      2216485.61      7219464.98      2217183.55      7219506.65
      2217798.08      7219496.23
#Sta/Elev= 30
  4304.8 1006.37  4398.4 1002.57  4431.2  999.47  4628.8  986.44  4658.8  982.38
  4688.9  981.00  4718.9  977.60  4728.9  978.33  4829.1  972.87  4939.4  970.73
  4959.4  970.52  4969.4  967.73  5004.0  968.09  5007.4  966.87  5007.7  966.37
  5011.4  966.87  5029.4  967.09  5039.4  968.66  5049.4  973.57  5079.4  970.98
  5097.8  973.54  5102.8  971.66  5109.4  975.40  5119.4  977.05  5199.5  980.19
  5249.5  983.75  5350.1  987.01  5459.9  993.41  5549.5  998.30  5618.6  999.78
#Mann=7,-1,0
  4304.8    0.12       0  4431.2    0.05       0  4939.4    0.12       0
  5007.4    0.07       0  5011.4    0.12       0  5350.1    0.05       0
  5459.9    0.12       0
Bank Sta=5007.4,5011.4
Exp/Cntr=0.3,0.1

Type RM Length L Ch R = 1,7149,410,410,410
BEGIN DESCRIPTION:
Upper Denton 100 14.0
END DESCRIPTION:
XS GIS Cut Line= 3
      2216555.08      7219711.51      2217131.46      7219732.34
      2217775.65      7219638.83
#Sta/Elev= 30
  4426.0 1002.28  4513.8  996.89  4630.1  990.96  4760.1  981.76  4790.2  981.29
  4890.2  973.54  4950.3  965.34  4958.3  965.33  4958.5  964.83  4962.3  965.33
  5002.8  965.45  5010.4  966.77  5040.7  965.79  5054.9  968.39  5086.2  967.43
  5120.0  968.79  5131.6  971.76  5161.9  972.25  5172.1  974.77  5222.6  976.13
  5252.9  978.56  5260.3  977.42  5273.1  978.33  5283.2  981.94  5293.3  982.81
  5424.2  986.00  5470.8  990.70  5574.6  994.48  5596.5  997.31  5653.7 1000.12
#Mann=7,-1,0
  4426.0    0.12       0  4513.8    0.05       0  4958.3   0.033       0
  4962.3    0.05       0  5086.2    0.12       0  5424.2    0.05       0
  5574.6    0.12       0
Bank Sta=4958.3,4962.3
Exp/Cntr=0.3,0.1

Type RM Length L Ch R = 1,6739,351,351,351
BEGIN DESCRIPTION:
Upper Denton 100 13.0
END DESCRIPTION:
XS GIS Cut Line= 3
      2216322.47      7219912.91      2217179.00      7220110.00
      2217845.35      7220145.46
#Sta/Elev= 30
  4121.5 1010.06  4215.0 1004.28  4405.3  990.40  4456.6  987.30  4466.8  988.84
  4532.8  984.48  4538.7  983.03  4559.2  982.96  4672.0  975.41  4723.4  973.80
  4757.2  971.04  4836.2  969.47  4908.1  966.33  4928.5  966.97  4949.1  964.95
  4969.6  961.43  4976.4  956.89  4979.6  956.83  4979.8  956.33  4983.6  956.83
  4997.8  961.87  5020.4  963.79  5040.5  963.38  5046.7  964.34  5070.5  967.69
  5110.6  971.05  5260.8  978.80  5310.9  982.83  5537.0  995.44  5667.7 1003.74
#Mann=6,-1,0
  4121.5    0.12       0  4215.0    0.05       0  4979.6   0.033       0
  4983.6    0.05       0  5046.7    0.12       0  5537.0    0.05       0
Bank Sta=4979.6,4983.6
Exp/Cntr=0.3,0.1

Type RM Length L Ch R = 1,6388,476,476,476
BEGIN DESCRIPTION:
Upper Denton 100 12.0
END DESCRIPTION:
XS GIS Cut Line= 3
      2216305.11      7220089.99      2217229.00      7220410.00
      2218180.04      7220312.21
#Sta/Elev= 30
  4021.8 1002.45  4189.9  992.47  4309.2  982.87  4340.4  981.51  4345.7  982.69
  4408.0  977.51  4570.8  970.53  4746.0  964.73  4845.3  962.51  4872.5  961.29
  4895.8  956.48  4914.9  961.74  4946.6  962.04  4978.4  960.44  4984.0  957.10
  4989.3  958.77  4994.9  955.06  4995.1  954.56  4998.9  955.06  5009.6  955.14
  5029.7  960.56  5046.6  960.29  5059.9  965.58  5090.0  969.87  5291.1  982.02
  5462.0  994.76  5642.9 1003.78  5723.3 1004.49  5914.3 1010.26  5955.6 1013.45
#Mann=6,-1,0
  4021.8    0.05       0  4570.8    0.12       0  4746.0    0.05       0
  4845.3    0.12       0  4994.9    0.07       0  4998.9    0.12       0
Bank Sta=4994.9,4998.9
Exp/Cntr=0.3,0.1

Type RM Length L Ch R = 1,5912,236,236,236
BEGIN DESCRIPTION:
Upper Denton 100 11.0
END DESCRIPTION:
XS GIS Cut Line= 3
      2216180.05      7220357.33      2217110.63      7220794.84
      2218064.79      7220909.34
#Sta/Elev= 30
  3851.6  991.48  4170.3  981.27  4272.5  976.15  4363.7  968.48  4409.3  967.30
  4454.9  962.81  4551.7  960.91  4602.8  963.07  4739.6  962.94  4888.3  956.51
  4964.5  955.94  4981.9  953.62  4989.0  953.05  4997.1  950.45  4997.4  949.95
  5001.1  950.45  5009.2  950.76  5019.3  953.86  5046.8  954.93  5120.0  964.19
  5180.4  965.17  5240.8  968.75  5281.1  973.59  5303.6  973.81  5402.0  979.37
  5422.1  982.28  5432.2  981.69  5502.7  987.92  5830.0 1011.41  5840.9 1012.15
#Mann=5,-1,0
  3851.6    0.05       0  4981.9    0.12       0  4997.1    0.07       0
  5001.1    0.12       0  5830.0    0.05       0
Bank Sta=4997.1,5001.1
Exp/Cntr=0.3,0.1

Type RM Length L Ch R = 1,5676,349,349,349
BEGIN DESCRIPTION:
Upper Denton 100 10.0
END DESCRIPTION:
XS GIS Cut Line= 3
      2216166.15      7220464.96      2217129.00      7221010.00
      2217992.53      7221169.83
#Sta/Elev= 30
  3898.2  985.30  4042.7  980.22  4117.8  976.59  4123.6  974.94  4161.1  975.61
  4301.1  971.84  4387.7  964.99  4570.9  958.55  4717.3  968.16  4740.3  968.08
  4786.0  964.30  4813.4  960.11  4878.3  955.78  4924.2  954.32  4959.1  951.20
  4969.3  954.16  4975.0  951.00  4990.9  951.82  5001.7  948.39  5012.8  948.00
  5013.0  947.50  5016.8  948.00  5031.1  950.49  5148.3  958.25  5212.3  961.98
  5469.5  979.12  5474.6  978.29  5632.8  990.14  5691.2  994.77  5882.8 1005.45
#Mann=6,-1,0
  3898.2    0.05       0  5012.8   0.033       0  5016.8    0.05       0
  5148.3    0.12       0  5212.3    0.05       0  5632.8    0.12       0
Bank Sta=5012.8,5016.8
Exp/Cntr=0.3,0.1

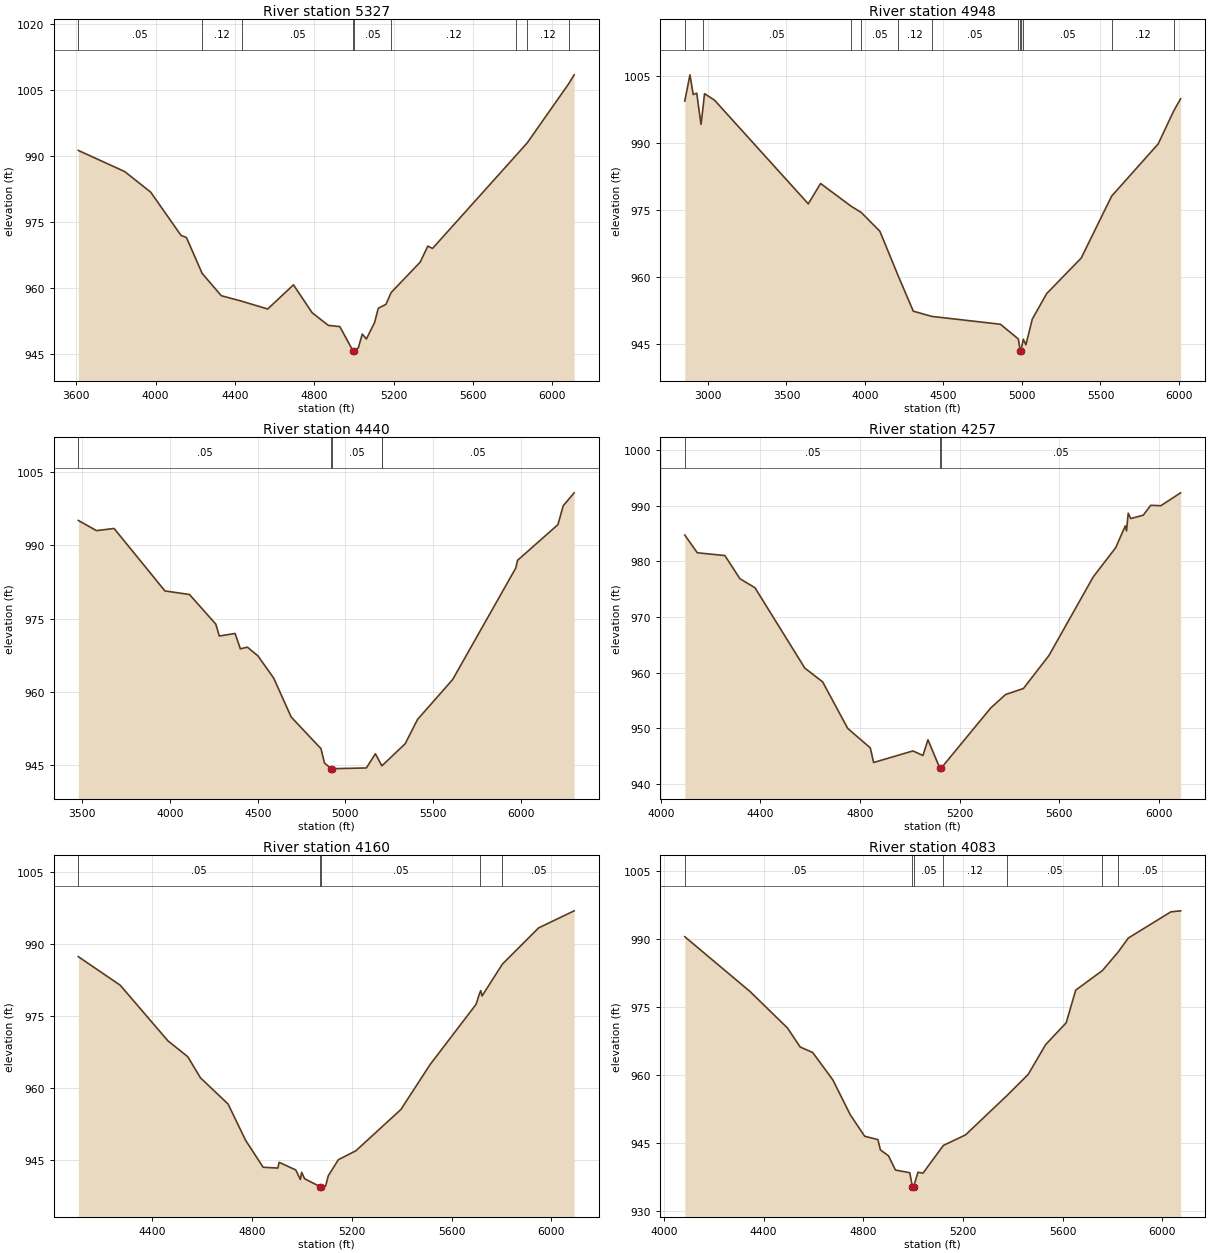
Type RM Length L Ch R = 1,5327,379,379,379
BEGIN DESCRIPTION:
Upper Denton 100 9.0
END DESCRIPTION:
XS GIS Cut Line= 3
      2215794.62      7220583.01      2216979.00      7221310.00
      2218044.29      7221621.13
#Sta/Elev= 30
  3610.3  991.23  3843.9  986.44  3975.3  981.76  4128.0  971.95  4155.2  971.49
  4234.4  963.34  4331.2  958.27  4434.7  957.02  4564.9  955.26  4694.9  960.74
  4788.8  954.42  4870.4  951.55  4928.4  951.27  4995.1  945.75  4995.3  945.25
  4999.1  945.75  5021.9  946.48  5041.7  949.57  5062.5  948.46  5104.2  952.24
  5122.3  955.43  5161.0  956.32  5187.3  959.00  5333.4  965.88  5372.2  969.53
  5395.9  969.00  5816.9  990.11  5873.4  992.96  6082.1 1006.34  6109.8 1008.38
#Mann=9,-1,0
  3610.3    0.05       0  4234.4    0.12       0  4434.7    0.05       0
  4995.1   0.033       0  4999.1    0.05       0  5187.3    0.12       0
  5816.9    0.05       0  5873.4    0.12       0  6082.1    0.05       0
Bank Sta=4995.1,4999.1
Exp/Cntr=0.3,0.1

Type RM Length L Ch R = 1,4948,508,508,508
BEGIN DESCRIPTION:
Upper Denton 100 8.0
END DESCRIPTION:
XS GIS Cut Line= 3
      2215199.44      7220313.64      2216879.00      7221660.00
      2217869.57      7221834.48
#Sta/Elev= 30
  2852.2  999.32  2885.0 1005.18  2905.8 1000.76  2928.2 1001.07  2955.4  994.11
  2965.3  996.93  2977.8 1000.96  3041.9  999.50  3638.8  976.31  3717.2  980.86
  3910.3  975.81  3976.6  974.37  4094.8  970.17  4212.5  960.12  4307.8  952.29
  4425.4  951.12  4863.1  949.36  4976.9  946.06  4989.2  943.40  4989.4  942.90
  4993.2  943.40  5008.4  946.00  5025.1  944.77  5065.7  950.51  5157.1  956.21
  5377.4  964.18  5571.3  978.04  5867.9  989.73  5966.5  997.10  6010.6  999.83
#Mann=12,-1,0
  2852.2    0.12       0  2965.3    0.05       0  3910.3    0.12       0
  3976.6    0.05       0  4212.5    0.12       0  4425.4    0.05       0
  4976.9    0.12       0  4989.2    0.07       0  4993.2    0.12       0
  5008.4    0.05       0  5571.3    0.12       0  5966.5    0.05       0
Bank Sta=4989.2,4993.2
Exp/Cntr=0.3,0.1

Type RM Length L Ch R = 1,4440,183,183,183
BEGIN DESCRIPTION:
Upper Denton 100 7.0
END DESCRIPTION:
XS GIS Cut Line= 3
      2215005.00      7221969.90      2216518.90      7221949.07
      2217831.43      7222008.10
#Sta/Elev= 30
  3476.9  995.09  3580.9  993.01  3680.9  993.45  3970.9  980.66  4111.0  979.93
  4261.0  973.86  4281.0  971.43  4371.0  971.95  4401.0  968.80  4441.0  969.15
  4501.0  967.37  4591.0  962.82  4691.0  954.84  4861.0  948.35  4881.0  945.41
  4918.9  944.26  4919.2  943.76  4923.2  944.26  5119.6  944.41  5171.2  947.31
  5208.0  944.85  5208.4  944.85  5341.0  949.37  5411.5  954.34  5611.7  962.51
  5972.0  985.36  5982.0  986.93  6212.3  994.24  6242.3  998.10  6304.8 1000.75
#Mann=5,-1,0
  3476.9    0.05       0  4918.9   0.033       0  4923.2    0.05       0
  5208.0    0.12       0  5208.4    0.05       0
Bank Sta=4918.9,4923.2
Exp/Cntr=0.3,0.1

Type RM Length L Ch R = 1,4257,97,97,97
BEGIN DESCRIPTION:
Upper Denton 100 6.5
END DESCRIPTION:
XS GIS Cut Line= 3
      2215719.12      7222198.78      2216621.87      7222098.08
      2217698.29      7221993.92
#Sta/Elev= 30
  4096.7  984.71  4146.9  981.53  4257.6  981.03  4317.9  976.87  4378.3  975.25
  4578.2  960.82  4650.0  958.33  4750.6  949.97  4841.2  946.48  4854.4  943.85
  5012.2  945.93  5052.4  945.11  5072.5  947.93  5120.6  942.80  5120.9  942.30
  5124.9  942.80  5323.7  953.61  5383.9  956.06  5455.8  957.15  5558.0  963.07
  5735.6  977.18  5826.0  982.45  5864.4  986.36  5869.4  985.46  5876.2  988.64
  5886.3  987.68  5936.5  988.28  5966.5  990.06  6006.8  989.98  6086.5  992.30
#Mann=3,-1,0
  4096.7    0.05       0  5120.6   0.033       0  5124.9    0.05       0
Bank Sta=5120.6,5124.9
Exp/Cntr=0.3,0.1

Type RM Length L Ch R = 1,4160,77,77,77
BEGIN DESCRIPTION:
Upper Denton 100 6.4
END DESCRIPTION:
XS GIS Cut Line= 3
      2215761.78      7222284.16      2216664.57      7222183.47
      2217740.96      7222079.30
#Sta/Elev= 30
  4102.4  987.34  4270.5  981.40  4461.8  969.83  4541.6  966.52  4592.6  962.12
  4703.3  956.68  4773.8  949.11  4844.2  943.51  4903.1  943.34  4908.2  944.54
  4975.0  942.95  4993.5  940.96  4998.6  942.47  5010.5  941.12  5073.4  939.46
  5073.7  938.96  5077.7  939.46  5094.6  939.59  5105.7  941.76  5145.8  945.08
  5216.2  946.94  5397.0  955.54  5513.3  964.83  5698.4  977.41  5712.8  979.73
  5717.5  980.28  5722.6  979.16  5804.5  985.81  5949.6  993.33  6092.2  996.88
#Mann=5,-1,0
  4102.4    0.05       0  5073.4   0.033       0  5077.7    0.05       0
  5712.8    0.12       0  5804.5    0.05       0
Bank Sta=5073.4,5077.7
Exp/Cntr=0.3,0.1

Type RM Length L Ch R = 1,4083,402,402,402
BEGIN DESCRIPTION:
Upper Denton 100 6.0
END DESCRIPTION:
XS GIS Cut Line= 3
      2215768.90      7222355.32      2216671.68      7222254.62
      2217748.07      7222150.46
#Sta/Elev= 30
  4083.9  990.53  4345.6  978.44  4496.5  970.35  4546.9  966.18  4597.2  964.97
  4677.7  958.95  4748.1  951.21  4805.9  946.47  4858.8  945.74  4868.8  943.47
  4901.4  942.15  4929.2  939.02  4986.7  938.42  4997.5  935.30  4997.8  934.80
  5001.8  935.30  5019.7  938.53  5039.8  938.33  5121.6  944.45  5210.6  946.78
  5375.6  955.40  5461.8  960.11  5532.1  966.72  5614.4  971.52  5652.7  978.74
  5760.0  983.07  5823.9  987.22  5863.7  990.24  6034.4  996.02  6073.7  996.25
#Mann=7,-1,0
  4083.9    0.05       0  4997.5   0.033       0  5001.8    0.05       0
  5121.6    0.12       0  5375.6    0.05       0  5760.0    0.12       0
  5823.9    0.05       0
Bank Sta=4997.5,5001.8
Exp/Cntr=0.3,0.1

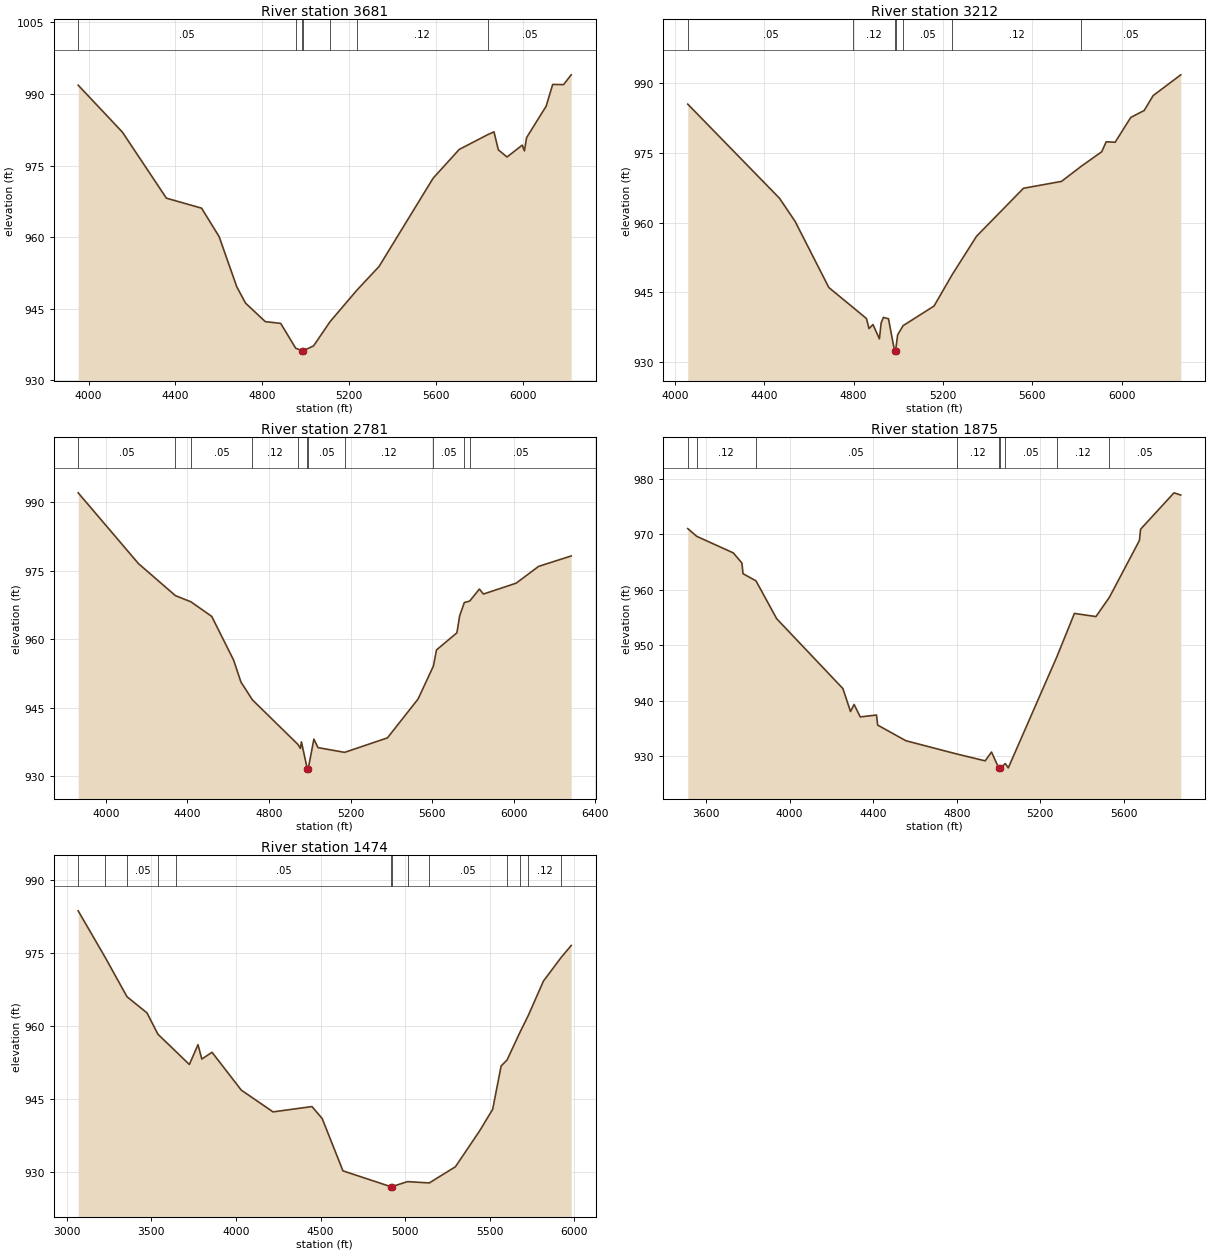
Type RM Length L Ch R = 1,3681,469,469,469
BEGIN DESCRIPTION:
Upper Denton 100 5.0
END DESCRIPTION:
XS GIS Cut Line= 3
      2215737.65      7222452.54      2216779.00      7222610.00
      2217994.27      7222591.43
#Sta/Elev= 30
  3952.3  991.84  4155.9  982.00  4358.2  968.17  4520.0  966.08  4600.9  960.11
  4681.9  949.62  4722.3  946.19  4813.3  942.31  4884.1  941.94  4953.2  936.74
  4983.1  936.21  4983.5  935.71  4987.5  936.21  5035.5  937.23  5110.9  942.28
  5234.0  948.86  5336.7  953.86  5585.6  972.36  5705.6  978.38  5836.9  981.48
  5865.6  982.06  5885.6  978.30  5925.6  976.80  5995.6  979.28  6005.6  978.07
  6015.6  980.86  6105.6  987.44  6135.6  992.00  6185.6  991.96  6220.9  994.01
#Mann=7,-1,0
  3952.3    0.05       0  4953.2    0.12       0  4983.1    0.07       0
  4987.5    0.12       0  5110.9    0.05       0  5234.0    0.12       0
  5836.9    0.05       0
Bank Sta=4983.1,4987.5
Exp/Cntr=0.3,0.1

Type RM Length L Ch R = 1,3212,431,431,431
BEGIN DESCRIPTION:
Upper Denton 100 4.0
END DESCRIPTION:
XS GIS Cut Line= 3
      2215817.51      7222629.62      2216679.00      7223010.00
      2217942.56      7222987.26
#Sta/Elev= 30
  4058.2  985.48  4468.7  965.23  4538.6  960.25  4689.4  946.03  4797.3  941.76
  4857.8  939.36  4869.0  937.20  4886.8  938.07  4915.6  934.99  4923.4  938.42
  4933.5  939.61  4956.2  939.31  4983.3  932.42  4983.7  931.92  4987.7  932.42
  4997.2  935.86  5021.6  937.83  5160.0  942.05  5241.4  948.82  5350.0  957.05
  5560.0  967.38  5730.1  968.86  5818.5  972.11  5910.1  975.23  5930.1  977.38
  5970.1  977.28  6040.1  982.62  6100.1  984.11  6140.1  987.31  6263.7  991.78
#Mann=7,-1,0
  4058.2    0.05       0  4797.3    0.12       0  4983.3    0.07       0
  4987.7    0.12       0  5021.6    0.05       0  5241.4    0.12       0
  5818.5    0.05       0
Bank Sta=4983.3,4987.7
Exp/Cntr=0.3,0.1

Type RM Length L Ch R = 1,2781,906,906,906
BEGIN DESCRIPTION:
Upper Denton 100 3.0
END DESCRIPTION:
XS GIS Cut Line= 5
      2215695.98      7222570.59      2216043.21      7222820.60
      2216397.38      7223331.01      2216479.00      7223360.00
      2217758.45      7223438.65
#Sta/Elev= 30
  3864.3  992.02  4160.2  976.51  4340.9  969.52  4417.5  968.15  4519.1  964.97
  4626.5  955.40  4662.3  950.61  4718.6  946.70  4942.2  936.92  4953.8  936.07
  4959.1  937.49  4987.7  931.59  4988.1  931.09  4992.2  931.59  5020.1  938.10
  5040.1  936.24  5170.8  935.20  5380.8  938.37  5531.0  946.88  5606.5  954.13
  5621.2  957.62  5721.4  961.37  5735.0  965.11  5757.9  968.01  5784.2  968.32
  5831.6  970.95  5851.6  969.86  6011.9  972.24  6122.2  975.92  6281.9  978.20
#Mann=11,-1,0
  3864.3    0.05       0  4340.9    0.12       0  4417.5    0.05       0
  4718.6    0.12       0  4942.2    0.05       0  4987.7   0.033       0
  4992.2    0.05       0  5170.8    0.12       0  5606.5    0.05       0
  5757.9    0.12       0  5784.2    0.05       0
Bank Sta=4987.7,4992.2
Exp/Cntr=0.3,0.1

Type RM Length L Ch R = 1,1875,401,401,401
BEGIN DESCRIPTION:
Upper Denton 100 2.0
END DESCRIPTION:
XS GIS Cut Line= 4
      2216025.84      7222827.52      2216389.56      7223729.28
      2216879.00      7223910.00      2217689.01      7223605.33
#Sta/Elev= 30
  3512.5  971.00  3555.5  969.60  3730.8  966.61  3771.7  964.79  3777.1  962.87
  3839.1  961.58  3938.2  954.75  4255.0  942.17  4291.5  938.03  4308.6  939.31
  4338.2  937.06  4416.0  937.40  4421.4  935.59  4556.3  932.77  4798.7  930.39
  4935.9  929.14  4966.3  930.73  5001.6  927.79  5002.1  927.29  5006.2  927.79
  5032.3  928.65  5046.6  927.88  5279.1  947.90  5363.1  955.71  5466.0  955.14
  5530.7  958.63  5674.2  968.86  5679.7  970.88  5839.6  977.44  5872.0  977.04
#Mann=9,-1,0
  3512.5    0.05       0  3555.5    0.12       0  3839.1    0.05       0
  4798.7    0.12       0  5001.6    0.07       0  5006.2    0.12       0
  5032.3    0.05       0  5279.1    0.12       0  5530.7    0.05       0
Bank Sta=5001.6,5006.2
Exp/Cntr=0.3,0.1

Type RM Length L Ch R = 1,1474,0,0,0
BEGIN DESCRIPTION:
Upper Denton 100 1.0
END DESCRIPTION:
XS GIS Cut Line= 6
      2215751.54      7222774.42      2216341.82      7224024.41
      2216723.77      7224250.11      2216836.61      7224254.45
      2216979.84      7224224.07      2217639.53      7223720.62
#Sta/Elev= 30
  3067.0  983.58  3226.8  974.02  3355.8  965.95  3473.8  962.64  3538.6  958.26
  3645.6  954.69  3724.3  952.05  3775.4  956.12  3798.1  953.17  3858.4  954.56
  4031.3  946.80  4219.0  942.33  4449.4  943.42  4509.7  940.97  4632.6  930.23
  4916.0  926.98  4916.5  926.48  4920.6  926.98  5014.4  928.02  5143.0  927.75
  5297.6  931.07  5440.6  938.43  5517.9  942.86  5567.8  951.74  5602.9  952.98
  5678.4  958.60  5728.4  962.11  5818.0  969.16  5922.1  973.99  5982.2  976.47
#Mann=13,-1,0
  3067.0    0.05       0  3226.8    0.12       0  3355.8    0.05       0
  3538.6    0.12       0  3645.6    0.05       0  4916.0   0.033       0
  4920.6    0.05       0  5014.4    0.12       0  5143.0    0.05       0
  5602.9    0.12       0  5678.4    0.05       0  5728.4    0.12       0
  5922.1    0.05       0
Bank Sta=4916,4920.6
Exp/Cntr=0.3,0.1

Chan Stop Cuts=-1