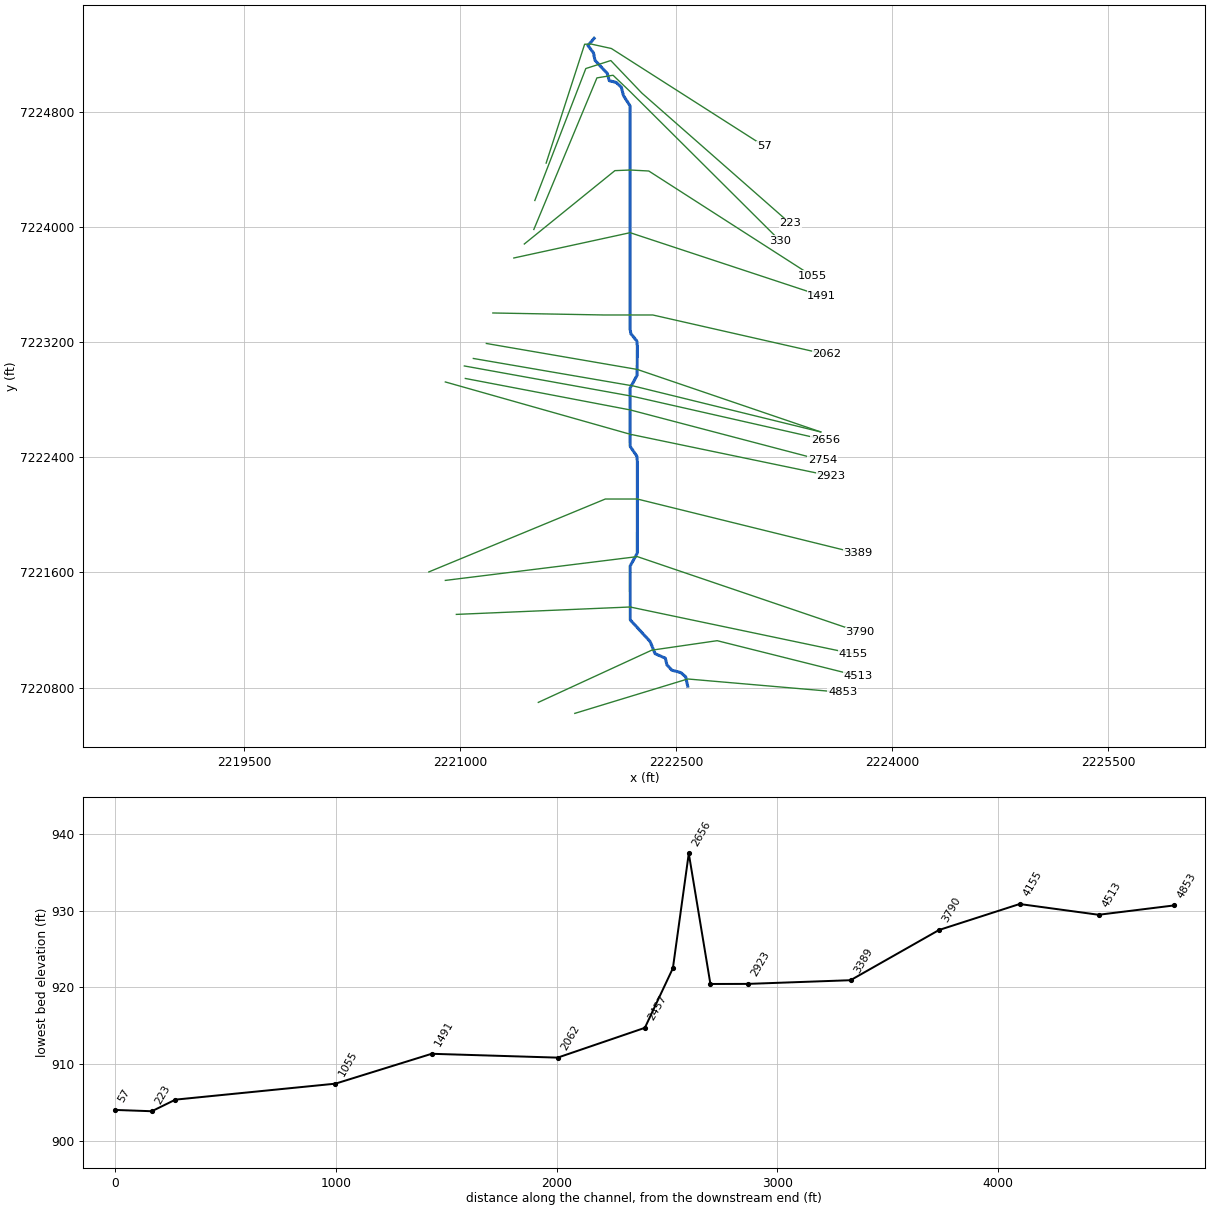
--- Upper Denton 102.prj (project) ---

Proj Title=Upper Denton 102 Base Level Engineering
Current Plan=p01
Default Exp/Contr=0.3,0.1
English Units
Geom File=g01
Flow File=f01
Plan File=p01
BEGIN DESCRIPTION:
Upper Denton 102
END DESCRIPTION:

--- Upper Denton 102.p01 (plan) ---

Plan Title=Multiple Run
Short Identifier=Multiple
Geom File=g01
Flow File=f01
Subcritical Flow
K Sum by GR= 0
Std Step Tol= 0.01
Critical Tol= 0.01
Num of Std Step Trials= 20
Max Error Tol= 0.3
Flow Tol Ratio= 0.001
Split Flow NTrial= 30
Split Flow Tol= 0.02
Split Flow Ratio= 0.02
Log Output Level= 0
Friction Slope Method= 1
Unsteady Friction Slope Method= 2
Unsteady Bridges Friction Slope Method= 1
Parabolic Critical Depth
Global Vel Dist=  1 , 1 , 1
Global Log Level= 0
CheckData=True
Encroach Param= -1, 0, 0, 0
BEGIN DESCRIPTION:
Multiple Run
END DESCRIPTION:

--- Upper Denton 102.f01 (steady flow) ---

Flow Title=Multiple
Number of Profiles=7
Profile Names=10-year,25-year,50-year,1pct_min,100-year,1pct_plu,500-year
River Rch & RM= Upper Denton 102,Reach-1,4853
     686     963    1196     739    1474    2941    2243
River Rch & RM= Upper Denton 102,Reach-1,2923
     678     948    1175     723    1443    2878    2182
Boundary for River Rch & Prof#=Upper Denton 102,Reach-1,1
Up Type=0
Dn Type=3
Dn Slope=0.005
Boundary for River Rch & Prof#=Upper Denton 102,Reach-1,2
Up Type=0
Dn Type=3
Dn Slope=0.005
Boundary for River Rch & Prof#=Upper Denton 102,Reach-1,3
Up Type=0
Dn Type=3
Dn Slope=0.005
Boundary for River Rch & Prof#=Upper Denton 102,Reach-1,4
Up Type=0
Dn Type=3
Dn Slope=0.005
Boundary for River Rch & Prof#=Upper Denton 102,Reach-1,5
Up Type=0
Dn Type=3
Dn Slope=0.005
Boundary for River Rch & Prof#=Upper Denton 102,Reach-1,6
Up Type=0
Dn Type=3
Dn Slope=0.005
Boundary for River Rch & Prof#=Upper Denton 102,Reach-1,7
Up Type=0
Dn Type=3
Dn Slope=0.005

--- Upper Denton 102.g01 (geometry) ---

Geom Title=Existing Conditions

River Reach=Upper Denton 102,Reach-1
Reach XY= 30
      2222579.00      7220810.00      2222565.73      7220873.78
      2222531.48      7220904.29      2222469.03      7220920.69
      2222434.89      7220957.79      2222423.34      7221004.34
      2222351.98      7221036.21      2222318.21      7221119.66
      2222180.05      7221270.43      2222179.52      7221644.78
      2222229.20      7221734.92      2222229.45      7222370.19
      2222225.22      7222408.43      2222179.52      7222475.22
      2222178.64      7222880.15      2222227.78      7222970.50
      2222229.45      7223170.19      2222225.22      7223208.43
      2222184.75      7223257.67      2222178.64      7223289.85
      2222178.94      7224839.98      2222133.23      7224911.78
      2222118.32      7224969.98      2222081.21      7225004.11
      2222034.65      7225015.63      2222020.70      7225065.74
      2221934.82      7225157.71      2221924.64      7225208.36
      2221885.87      7225260.12      2221929.00      7225310.00

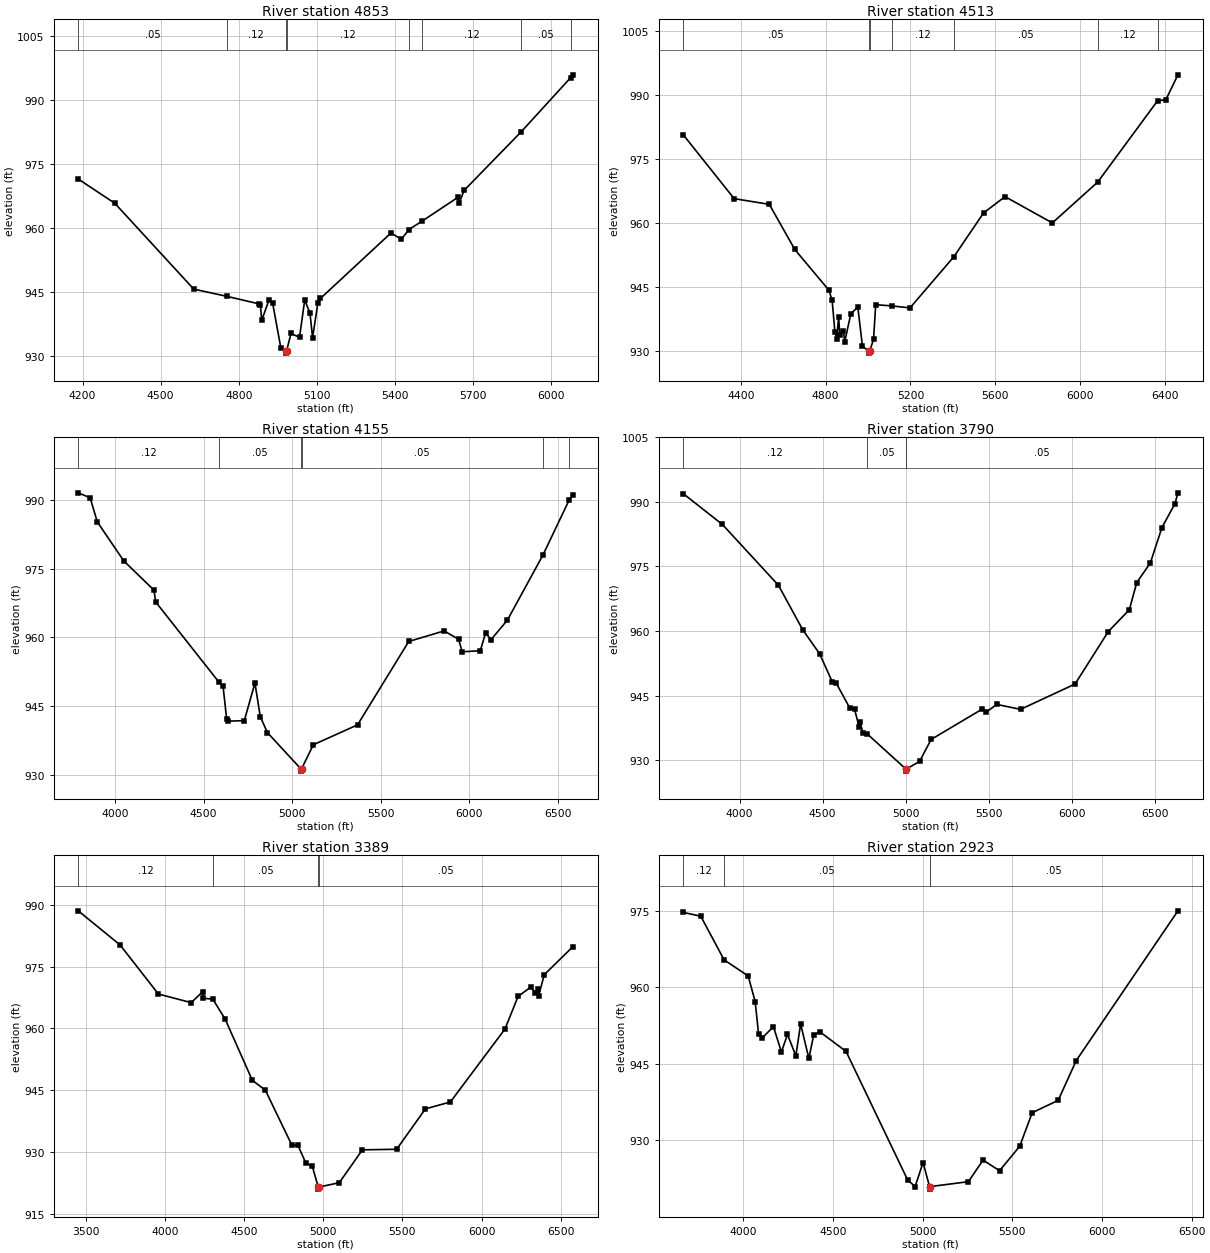
Type RM Length L Ch R = 1,4853,340,340,340
BEGIN DESCRIPTION:
Upper Denton 102 11.0
END DESCRIPTION:
XS GIS Cut Line= 3
      2221794.88      7220621.05      2222579.00      7220860.00
      2223654.97      7220766.97
#Sta/Elev= 30
  4183.6  971.47  4323.8  965.80  4627.0  945.68  4754.8  943.97  4877.9  942.22
  4883.2  941.93  4888.4  938.36  4916.0  943.13  4930.1  942.42  4961.5  931.96
  4979.7  931.17  4979.9  930.67  4983.7  931.17  5000.7  935.28  5033.4  934.36
  5053.5  943.15  5073.6  940.03  5083.6  934.30  5103.7  942.31  5113.7  943.48
  5384.7  958.83  5424.9  957.35  5453.7  959.64  5503.6  961.58  5641.3  967.16
  5646.3  965.80  5665.8  968.82  5885.9  982.61  6074.6  995.22  6083.3  995.90
#Mann=8,-1,0
  4183.6    0.05       0  4754.8    0.12       0  4979.7    0.07       0
  4983.7    0.12       0  5453.7    0.05       0  5503.6    0.12       0
  5885.9    0.05       0  6074.6    0.12       0
Bank Sta=4979.7,4983.7
Exp/Cntr=0.3,0.1

Type RM Length L Ch R = 1,4513,358,358,358
BEGIN DESCRIPTION:
Upper Denton 102 10.0
END DESCRIPTION:
XS GIS Cut Line= 4
      2221541.39      7220697.43      2222329.00      7221060.00
      2222783.75      7221125.99      2223760.13      7220881.47
#Sta/Elev= 30
  4128.6  980.61  4368.2  965.67  4534.1  964.33  4654.4  953.75  4815.2  944.21
  4830.5  941.82  4843.6  934.35  4852.5  932.78  4861.1  938.00  4866.6  933.66
  4884.0  934.71  4889.6  932.06  4918.6  938.68  4951.6  940.25  4973.6  931.04
  5003.8  929.96  5004.0  929.46  5007.8  929.96  5025.7  932.66  5036.1  940.81
  5111.7  940.53  5197.7  940.06  5404.5  952.04  5544.9  962.32  5646.1  966.14
  5869.3  959.98  6082.9  969.53  6365.6  988.60  6404.9  988.86  6461.7  994.69
#Mann=7,-1,0
  4128.6    0.05       0  5003.8   0.033       0  5007.8    0.05       0
  5111.7    0.12       0  5404.5    0.05       0  6082.9    0.12       0
  6365.6    0.05       0
Bank Sta=5003.8,5007.8
Exp/Cntr=0.3,0.1

Type RM Length L Ch R = 1,4155,365,365,365
BEGIN DESCRIPTION:
Upper Denton 102 9.0
END DESCRIPTION:
XS GIS Cut Line= 3
      2220972.01      7221308.55      2222179.00      7221360.00
      2223730.56      7221034.63
#Sta/Elev= 30
  3792.0  991.52  3859.1  990.44  3899.1  985.21  4049.2  976.67  4219.4  970.32
  4229.4  967.73  4587.1  950.23  4609.7  949.40  4629.8  942.30  4639.8  941.75
  4729.8  941.87  4789.9  950.07  4819.9  942.75  4860.0  939.27  5049.2  931.36
  5049.4  930.86  5053.2  931.36  5119.7  936.61  5369.3  940.94  5658.5  959.12
  5858.4  961.42  5940.1  959.60  5960.5  956.87  6062.7  957.10  6092.3  960.95
  6124.0  959.55  6216.0  963.79  6416.8  977.98  6565.1  989.99  6585.4  990.99
#Mann=6,-1,0
  3792.0    0.12       0  4587.1    0.05       0  5049.2   0.033       0
  5053.2    0.05       0  6416.8    0.12       0  6565.1    0.05       0
Bank Sta=5049.2,5053.2
Exp/Cntr=0.3,0.1

Type RM Length L Ch R = 1,3790,401,401,401
BEGIN DESCRIPTION:
Upper Denton 102 8.0
END DESCRIPTION:
XS GIS Cut Line= 3
      2220895.60      7221544.66      2222229.00      7221710.00
      2223775.75      7221184.15
#Sta/Elev= 30
  3661.3  991.87  3896.5  984.73  4233.5  970.63  4380.2  960.27  4481.3  954.74
  4557.2  948.27  4581.7  947.90  4662.3  942.19  4692.5  941.79  4719.1  937.79
  4724.1  938.90  4742.9  936.30  4766.7  936.17  5000.4  927.98  5000.6  927.48
  5004.4  927.98  5083.4  929.73  5152.8  934.83  5459.9  941.87  5486.0  941.24
  5548.7  942.96  5691.4  941.82  6019.4  947.70  6219.6  959.88  6346.3  964.96
  6390.6  971.23  6473.0  975.85  6542.2  984.00  6620.9  989.60  6638.6  992.08
#Mann=4,-1,0
  3661.3    0.12       0  4766.7    0.05       0  5000.4   0.033       0
  5004.4    0.05       0
Bank Sta=5000.4,5004.4
Exp/Cntr=0.3,0.1

Type RM Length L Ch R = 1,3389,466,466,466
BEGIN DESCRIPTION:
Upper Denton 102 7.0
END DESCRIPTION:
XS GIS Cut Line= 4
      2220780.97      7221603.68      2222006.69      7222110.00
      2222229.00      7222110.00      2223760.18      7221732.16
#Sta/Elev= 30
  3451.5  988.56  3715.7  980.27  3958.0  968.34  4165.5  966.25  4237.3  968.90
  4242.7  967.32  4302.0  967.09  4379.9  962.24  4551.3  947.39  4633.9  944.97
  4800.0  931.74  4840.0  931.55  4890.0  927.26  4930.0  926.58  4968.0  921.44
  4968.2  920.94  4972.0  921.44  5101.1  922.50  5247.2  930.49  5463.5  930.62
  5645.3  940.44  5803.4  942.12  6148.1  959.84  6231.1  967.77  6314.0  970.10
  6339.0  968.53  6355.5  969.58  6360.6  967.96  6397.0  973.06  6577.1  979.84
#Mann=4,-1,0
  3451.5    0.12       0  4302.0    0.05       0  4968.0   0.033       0
  4972.0    0.05       0
Bank Sta=4968,4972
Exp/Cntr=0.3,0.1

Type RM Length L Ch R = 1,2923,169,169,169
BEGIN DESCRIPTION:
Upper Denton 102 6.0
END DESCRIPTION:
XS GIS Cut Line= 3
      2220895.59      7222923.13      2222179.00      7222560.00
      2223572.63      7222270.36
#Sta/Elev= 30
  3666.3  974.70  3763.4  973.95  3893.5  965.40  4027.6  962.24  4066.7  957.23
  4085.5  950.91  4106.3  950.10  4168.6  952.31  4212.9  947.34  4246.9  950.78
  4293.4  946.59  4320.0  952.81  4366.1  946.09  4393.1  950.69  4427.0  951.30
  4573.2  947.46  4916.9  922.25  4958.5  920.96  5002.6  925.67  5038.9  920.96
  5039.2  920.46  5043.0  920.96  5255.4  921.92  5337.1  926.15  5429.1  924.07
  5541.4  928.86  5611.1  935.44  5755.9  937.86  5856.5  945.65  6423.5  975.01
#Mann=4,-1,0
  3666.3    0.12       0  3893.5    0.05       0  5038.9   0.033       0
  5043.0    0.05       0
Bank Sta=5038.9,5043
Exp/Cntr=0.3,0.1

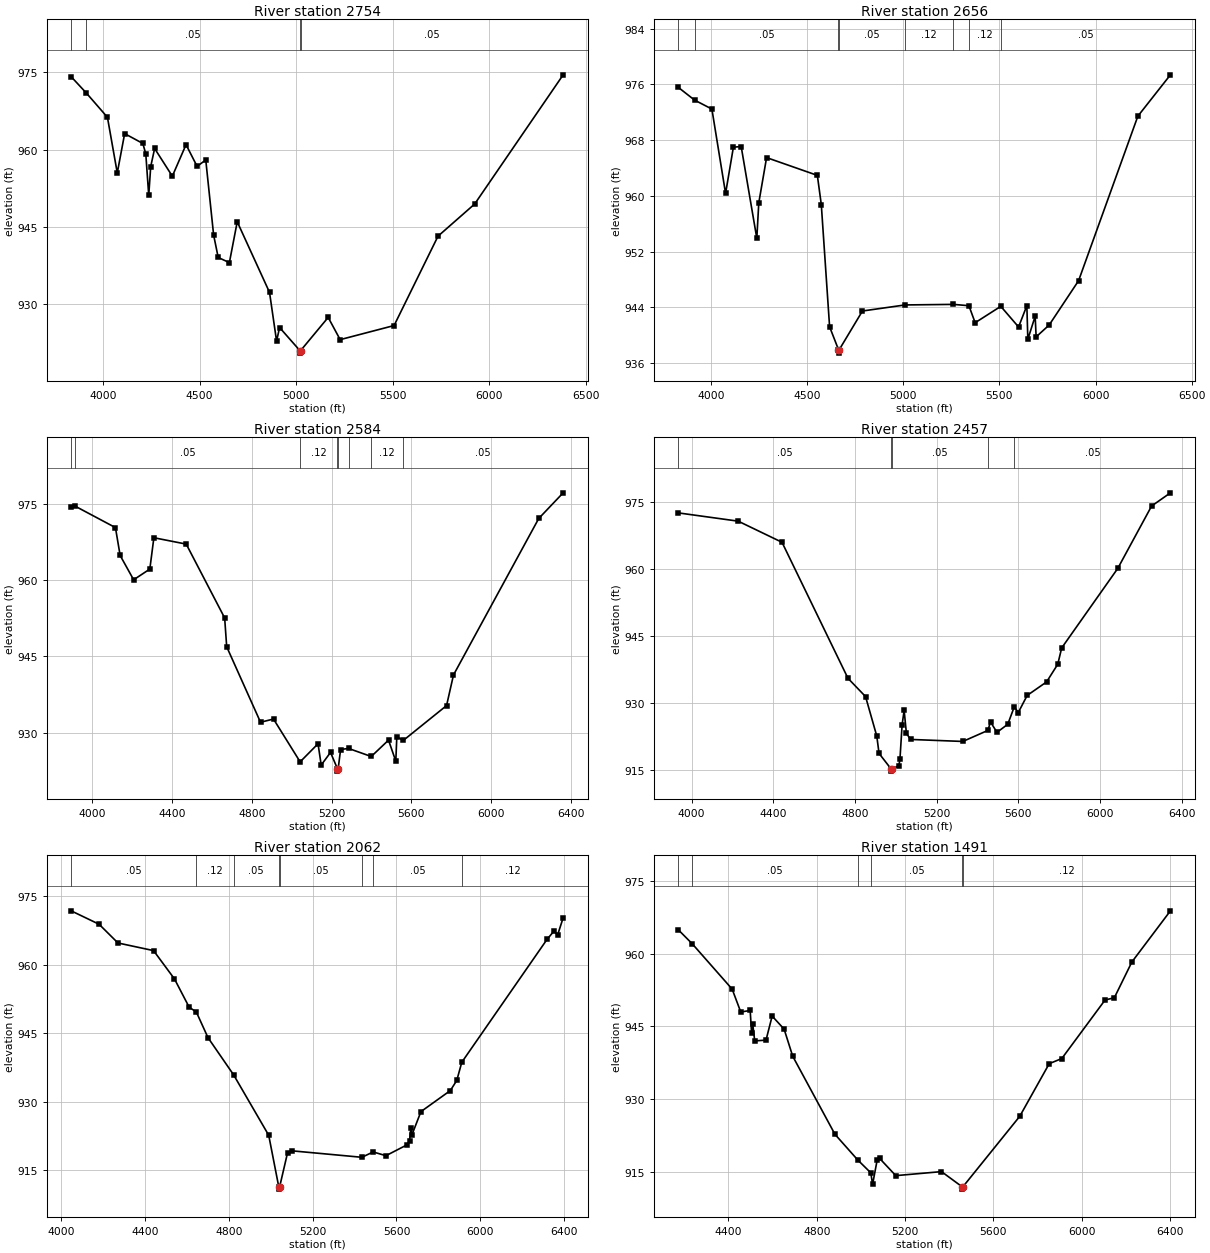
Type RM Length L Ch R = 1,2754,98,98,98
BEGIN DESCRIPTION:
Upper Denton 102 5.5
END DESCRIPTION:
XS GIS Cut Line= 3
      2221034.45      7222947.44      2222180.30      7222728.69
      2223515.57      7222378.40
#Sta/Elev= 30
  3834.8  974.15  3914.1  970.95  4022.7  966.26  4073.6  955.45  4111.8  963.09
  4205.9  961.18  4221.2  959.16  4236.5  951.08  4246.7  956.69  4267.0  960.20
  4358.6  954.82  4429.6  960.95  4486.8  956.73  4531.7  957.97  4572.4  943.39
  4596.1  939.03  4653.9  938.03  4694.6  945.97  4861.8  932.25  4898.2  922.80
  4913.9  925.42  5018.8  920.95  5019.1  920.45  5022.9  920.95  5165.4  927.39
  5227.4  923.07  5506.6  925.81  5734.0  943.17  5923.8  949.42  6381.8  974.51
#Mann=4,-1,0
  3834.8    0.12       0  3914.1    0.05       0  5018.8   0.033       0
  5022.9    0.05       0
Bank Sta=5018.8,5022.9
Exp/Cntr=0.3,0.1

Type RM Length L Ch R = 1,2656,72,72,72
BEGIN DESCRIPTION:
Upper Denton 102 5.4
END DESCRIPTION:
XS GIS Cut Line= 3
      2221027.55      7223034.24      2222201.13      7222822.44
      2223534.20      7222520.42
#Sta/Elev= 30
  3830.1  975.55  3914.0  973.74  4004.3  972.45  4075.5  960.35  4116.1  966.98
  4156.7  967.08  4238.0  953.91  4248.2  959.00  4288.8  965.49  4552.9  962.94
  4573.4  958.76  4616.6  941.23  4662.8  937.95  4663.1  937.45  4666.9  937.95
  4787.4  943.49  5009.4  944.36  5260.7  944.44  5341.3  944.25  5373.7  941.81
  5507.1  944.16  5599.6  941.20  5642.7  944.26  5647.8  939.43  5685.9  942.74
  5691.0  939.78  5758.7  941.48  5911.8  947.84  6220.1  971.43  6389.5  977.36
#Mann=8,-1,0
  3830.1    0.12       0  3914.0    0.05       0  4662.8   0.033       0
  4666.9    0.05       0  5009.4    0.12       0  5260.7    0.05       0
  5341.3    0.12       0  5507.1    0.05       0
Bank Sta=4662.8,4666.9
Exp/Cntr=0.3,0.1

Type RM Length L Ch R = 1,2584,127,127,127
BEGIN DESCRIPTION:
Upper Denton 102 5.3
END DESCRIPTION:
XS GIS Cut Line= 3
      2221090.02      7223086.33      2222201.13      7222895.36
      2223503.22      7222575.91
#Sta/Elev= 30
  3893.9  974.38  3912.7  974.51  4116.1  970.28  4139.7  964.81  4207.4  960.04
  4288.6  962.14  4308.9  968.29  4471.2  967.04  4664.0  952.55  4674.2  946.90
  4843.9  932.09  4909.0  932.72  5042.6  924.32  5132.4  927.87  5148.3  923.69
  5195.0  926.17  5229.4  923.00  5229.7  922.50  5233.5  923.00  5245.6  926.74
  5285.4  926.95  5399.3  925.37  5486.0  928.58  5522.5  924.44  5527.6  929.25
  5560.1  928.52  5777.1  935.36  5811.9  941.37  6239.6  972.07  6362.0  977.10
#Mann=8,-1,0
  3893.9    0.12       0  3912.7    0.05       0  5042.6    0.12       0
  5229.4   0.033       0  5233.5    0.12       0  5285.4    0.05       0
  5399.3    0.12       0  5560.1    0.05       0
Bank Sta=5229.4,5233.5
Exp/Cntr=0.3,0.1

Type RM Length L Ch R = 1,2457,395,395,395
BEGIN DESCRIPTION:
Upper Denton 102 5.0
END DESCRIPTION:
XS GIS Cut Line= 3
      2221180.35      7223190.49      2222229.00      7223010.00
      2223503.21      7222575.91
#Sta/Elev= 30
  3935.5  972.60  4228.4  970.75  4443.0  966.02  4766.2  935.54  4852.3  931.44
  4907.2  922.61  4918.4  918.71  4977.2  915.24  4977.5  914.74  4981.3  915.24
  5015.2  915.93  5020.7  917.36  5031.3  925.11  5041.3  928.33  5052.4  923.21
  5072.7  921.84  5328.8  921.39  5451.3  923.86  5464.4  925.75  5496.1  923.43
  5548.9  925.24  5580.8  929.15  5600.4  927.87  5644.0  931.70  5739.1  934.73
  5793.8  938.69  5813.0  942.34  6087.7  960.16  6253.5  974.14  6345.7  977.10
#Mann=5,-1,0
  3935.5    0.05       0  4977.2   0.033       0  4981.3    0.05       0
  5451.3    0.12       0  5580.8    0.05       0
Bank Sta=4977.2,4981.3
Exp/Cntr=0.3,0.1

Type RM Length L Ch R = 1,2062,571,571,571
BEGIN DESCRIPTION:
Upper Denton 102 4.0
END DESCRIPTION:
XS GIS Cut Line= 4
      2221225.48      7223402.30      2221996.27      7223388.41
      2222336.55      7223388.41      2223544.42      7223114.21
#Sta/Elev= 30
  4046.4  971.79  4179.9  968.85  4270.0  964.75  4440.0  963.08  4540.0  956.87
  4610.0  950.70  4644.4  949.63  4700.0  944.02  4822.5  935.87  4990.0  922.65
  5038.0  911.36  5038.3  910.86  5042.1  911.36  5080.0  918.83  5100.0  919.25
  5434.9  917.83  5488.7  919.00  5549.8  918.18  5652.3  920.60  5662.6  921.50
  5668.8  924.19  5673.9  922.74  5717.0  927.83  5857.4  932.44  5888.2  934.66
  5912.0  938.63  6318.9  965.52  6351.1  967.29  6370.1  966.55  6396.2  970.27
#Mann=8,-1,0
  4046.4    0.05       0  4644.4    0.12       0  4822.5    0.05       0
  5038.0   0.033       0  5042.1    0.05       0  5434.9    0.12       0
  5488.7    0.05       0  5912.0    0.12       0
Bank Sta=5038,5042.1
Exp/Cntr=0.3,0.1

Type RM Length L Ch R = 1,1491,436,436,436
BEGIN DESCRIPTION:
Upper Denton 102 3.0
END DESCRIPTION:
XS GIS Cut Line= 3
      2221371.30      7223784.25      2222179.00      7223960.00
      2223510.18      7223520.35
#Sta/Elev= 30
  4173.4  964.96  4236.2  962.08  4416.9  952.71  4455.8  947.98  4498.5  948.30
  4504.9  943.62  4510.0  945.49  4519.0  942.01  4570.2  942.16  4598.0  947.14
  4652.2  944.44  4691.1  938.84  4882.4  922.70  4985.7  917.39  5044.8  914.73
  5052.9  912.33  5073.7  917.39  5084.6  917.72  5158.0  914.15  5365.0  914.98
  5458.1  911.86  5458.5  911.36  5462.3  911.86  5719.4  926.41  5853.0  937.30
  5909.9  938.36  6105.8  950.46  6147.9  950.93  6227.3  958.32  6401.9  968.90
#Mann=6,-1,0
  4173.4    0.12       0  4236.2    0.05       0  4985.7    0.12       0
  5044.8    0.05       0  5458.1    0.07       0  5462.3    0.12       0
Bank Sta=5458.1,5462.3
Exp/Cntr=0.3,0.1

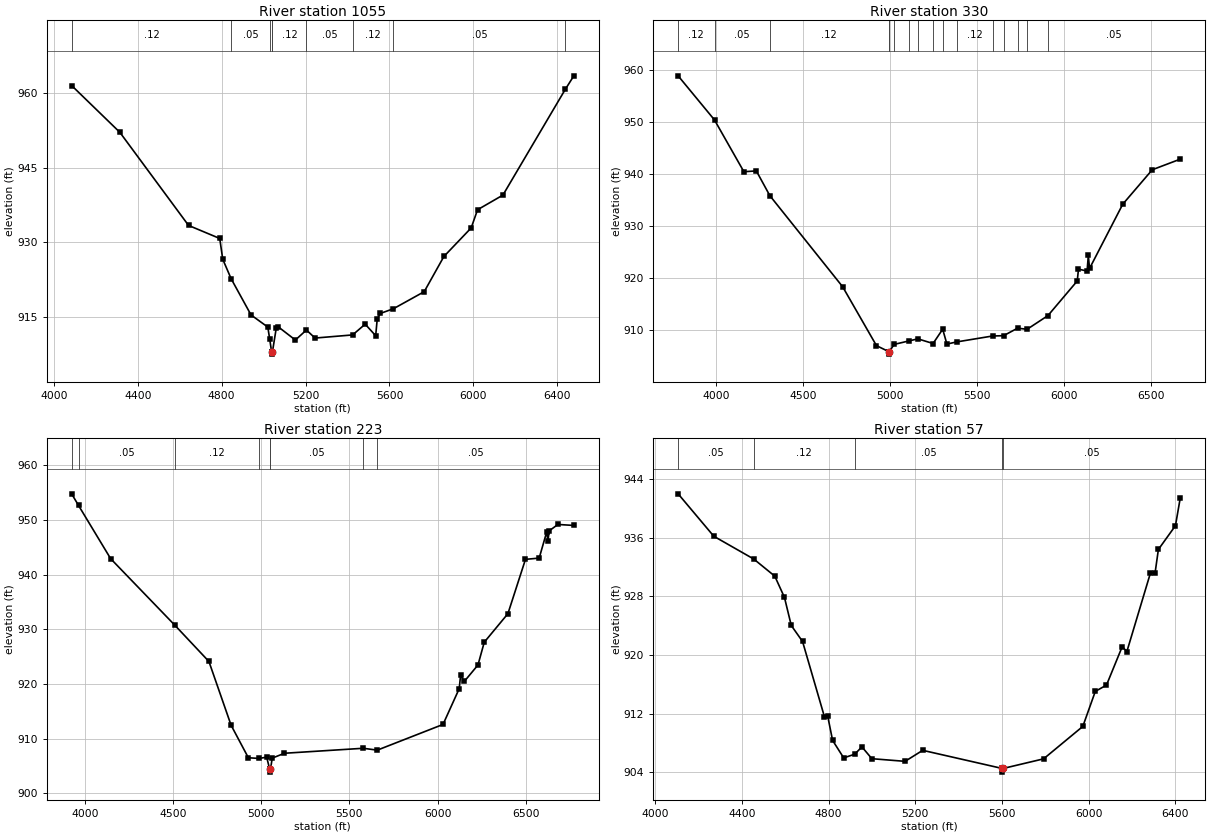
Type RM Length L Ch R = 1,1055,725,725,725
BEGIN DESCRIPTION:
Upper Denton 102 2.0
END DESCRIPTION:
XS GIS Cut Line= 5
      2221444.16      7223881.45      2222073.24      7224390.99
      2222180.30      7224395.36      2222308.77      7224388.41
      2223444.07      7223659.32
#Sta/Elev= 30
  4084.6  961.60  4314.3  952.18  4642.0  933.41  4790.7  930.78  4805.1  926.59
  4844.9  922.68  4939.9  915.37  5020.0  912.92  5029.1  910.45  5038.0  907.97
  5038.3  907.47  5042.2  907.97  5060.1  912.69  5070.1  912.96  5151.4  910.31
  5204.0  912.33  5245.2  910.71  5424.4  911.34  5484.3  913.51  5534.3  911.18
  5541.8  914.60  5557.0  915.68  5619.0  916.62  5765.8  920.06  5859.6  927.15
  5989.7  932.91  6020.1  936.57  6141.0  939.52  6438.4  960.83  6479.2  963.56
#Mann=9,-1,0
  4084.6    0.12       0  4844.9    0.05       0  5029.1    0.12       0
  5038.0   0.033       0  5042.2    0.12       0  5204.0    0.05       0
  5424.4    0.12       0  5619.0    0.05       0  6438.4    0.12       0
Bank Sta=5038,5042.2
Exp/Cntr=0.3,0.1

Type RM Length L Ch R = 1,330,107,107,107
BEGIN DESCRIPTION:
Upper Denton 102 1.5
END DESCRIPTION:
XS GIS Cut Line= 5
      2221510.18      7223982.21      2221948.53      7225035.29
      2222060.51      7225053.52      2222180.30      7224938.93
      2223220.63      7223903.62
#Sta/Elev= 30
  3779.4  958.81  3988.6  950.34  4157.6  940.40  4229.1  940.56  4307.0  935.80
  4725.5  918.32  4919.9  907.02  4989.4  905.89  4989.7  905.39  4993.6  905.89
  5022.0  907.26  5108.5  907.94  5158.0  908.32  5245.4  907.43  5300.7  910.17
  5324.9  907.32  5380.6  907.73  5587.7  908.87  5651.0  908.93  5731.3  910.37
  5786.1  910.16  5906.0  912.79  6074.4  919.43  6081.5  921.71  6131.0  921.33
  6138.1  924.33  6145.1  921.83  6336.1  934.17  6505.8  940.78  6667.0  942.82
#Mann=16,-1,0
  3779.4    0.12       0  3988.6    0.05       0  4307.0    0.12       0
  4989.4    0.07       0  4993.6    0.12       0  5022.0    0.05       0
  5108.5    0.12       0  5158.0    0.05       0  5245.4    0.12       0
  5300.7    0.05       0  5380.6    0.12       0  5587.7    0.05       0
  5651.0    0.12       0  5731.3    0.05       0  5786.1    0.12       0
  5906.0    0.05       0
Bank Sta=4989.4,4993.6
Exp/Cntr=0.3,0.1

Type RM Length L Ch R = 1,223,166,166,166
BEGIN DESCRIPTION:
Upper Denton 102 1.0
END DESCRIPTION:
XS GIS Cut Line= 5
      2221517.12      7224183.58      2221871.27      7225100.22
      2222044.88      7225155.77      2222260.16      7224930.08
      2223290.71      7224024.44
#Sta/Elev= 30
  3924.2  954.76  3963.1  952.64  4145.5  942.90  4508.9  930.76  4702.9  924.11
  4828.7  912.45  4926.6  906.51  4987.6  906.38  5030.5  906.62  5047.9  904.38
  5048.2  903.88  5052.1  904.38  5062.0  906.44  5131.5  907.33  5578.2  908.24
  5658.0  907.90  6030.9  912.60  6122.9  919.15  6130.5  921.60  6151.4  920.45
  6229.2  923.47  6264.8  927.63  6399.0  932.85  6498.6  942.78  6576.4  943.01
  6619.1  947.80  6625.8  946.12  6633.4  948.00  6682.7  949.16  6773.0  948.98
#Mann=8,-1,0
  3924.2    0.12       0  3963.1    0.05       0  4508.9    0.12       0
  4987.6    0.05       0  5047.9   0.033       0  5052.1    0.05       0
  5578.2    0.12       0  5658.0    0.05       0
Bank Sta=5047.9,5052.1
Exp/Cntr=0.3,0.1

Type RM Length L Ch R = 1,57,0,0,0
BEGIN DESCRIPTION:
Upper Denton 102 0.5
END DESCRIPTION:
XS GIS Cut Line= 5
      2221595.70      7224443.37      2221863.06      7225268.89
      2221906.46      7225270.62      2222048.82      7225239.37
      2223110.49      7224561.40
#Sta/Elev= 30
  4106.1  941.97  4270.7  936.19  4455.3  933.08  4552.1  930.75  4596.6  927.86
  4628.1  924.03  4680.1  921.85  4781.3  911.57  4796.3  911.66  4818.6  908.38
  4869.9  905.99  4920.5  906.49  4954.0  907.49  4999.8  905.88  5153.0  905.52
  5234.4  907.02  5601.2  904.55  5601.5  904.05  5605.4  904.55  5792.1  905.86
  5973.0  910.28  6030.6  915.05  6082.2  915.91  6154.9  921.16  6176.1  920.47
  6285.2  931.21  6306.4  931.21  6321.6  934.39  6400.3  937.63  6422.7  941.44
#Mann=5,-1,0
  4106.1    0.05       0  4455.3    0.12       0  4920.5    0.05       0
  5601.2   0.033       0  5605.4    0.05       0
Bank Sta=5601.2,5605.4
Exp/Cntr=0.3,0.1

Chan Stop Cuts=-1