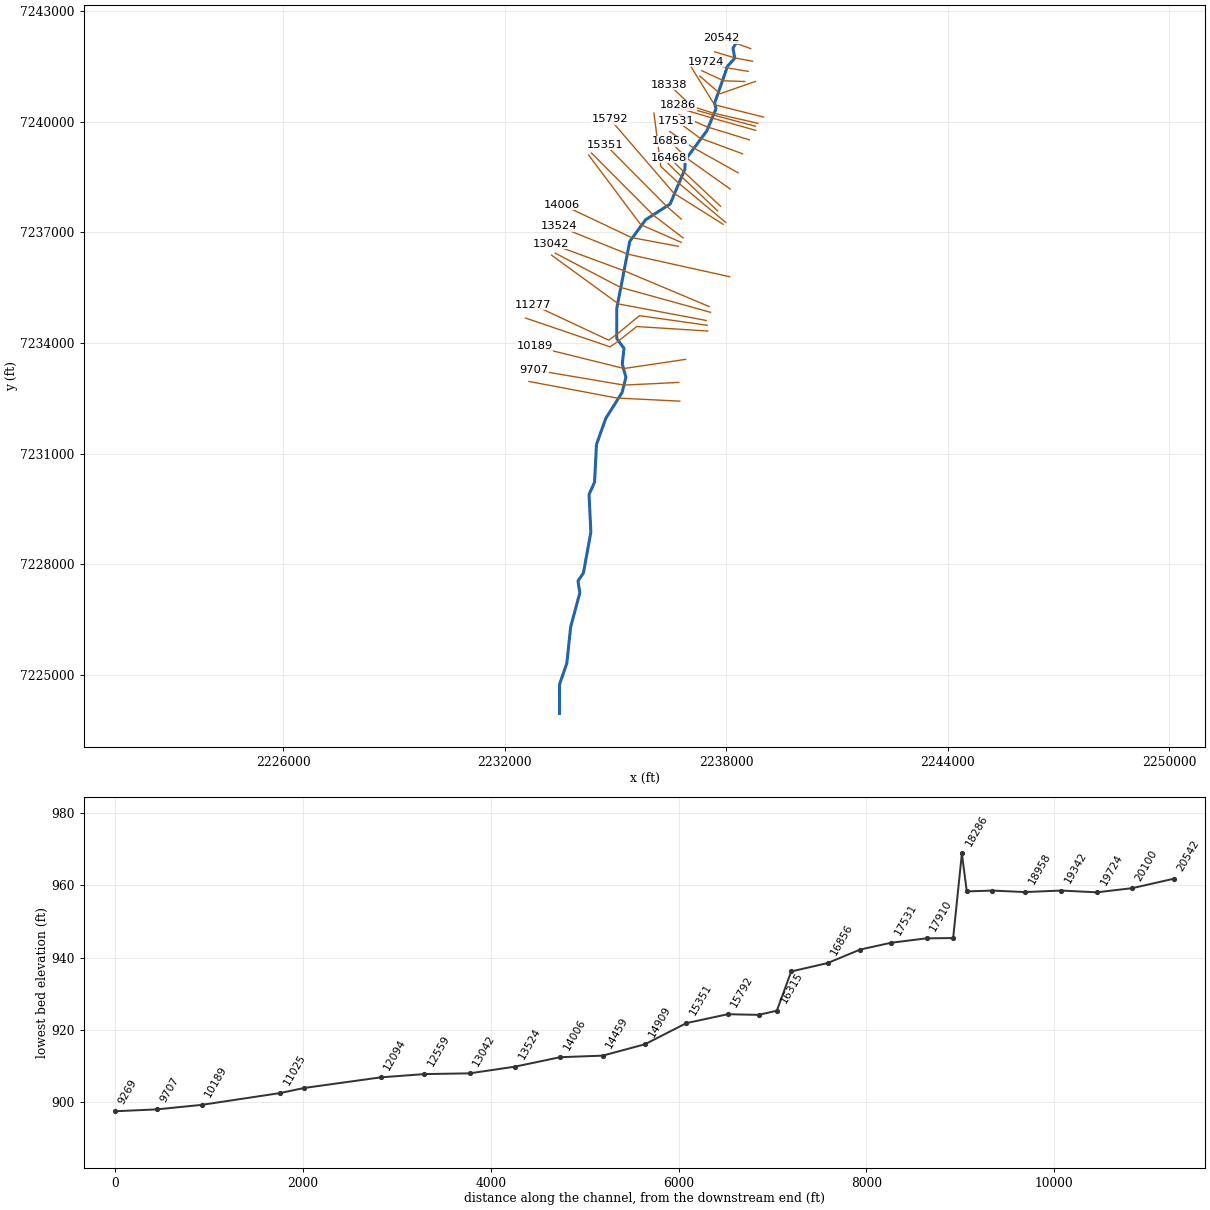
--- Upper Denton 105.prj (project) ---

Proj Title=Upper Denton 105 Base Level Engineering
Current Plan=p01
Default Exp/Contr=0.3,0.1
English Units
Geom File=g01
Flow File=f01
Plan File=p01
Y Axis Title=Elevation
X Axis Title(PF)=Main Channel Distance
X Axis Title(XS)=Station
BEGIN DESCRIPTION:
Upper Denton 105
END DESCRIPTION:
DSS Export Rating Curves= 0
DSS Export Rating Curve Sorted= 0
DSS Export Volume Flow Curves= 0
DXF OffsetX= 0
DXF OffsetY= 0
DXF ScaleX= 1
DXF ScaleY= 10

--- Upper Denton 105.p01 (plan) ---

Plan Title=Multiple Run
Short Identifier=Multiple
Geom File=g01
Flow File=f01
Subcritical Flow
K Sum by GR= 0
Std Step Tol= 0.01
Critical Tol= 0.01
Num of Std Step Trials= 20
Max Error Tol= 0.3
Flow Tol Ratio= 0.001
Split Flow NTrial= 30
Split Flow Tol= 0.02
Split Flow Ratio= 0.02
Log Output Level= 0
Friction Slope Method= 1
Unsteady Friction Slope Method= 2
Unsteady Bridges Friction Slope Method= 1
Parabolic Critical Depth
Global Vel Dist=  1 , 1 , 1
Global Log Level= 0
CheckData=True
Encroach Param= -1, 0, 0, 0
BEGIN DESCRIPTION:
Multiple Run
END DESCRIPTION:

--- Upper Denton 105.f01 (steady flow) ---

Flow Title=Multiple
Number of Profiles=7
Profile Names=10-year,25-year,50-year,1pct_min,100-year,1pct_plu,500-year
River Rch & RM= Upper Denton 105,Reach-1,20542
     767    1083    1352     838    1673    3337    2567
River Rch & RM= Upper Denton 105,Reach-1,15351
     990    1414    1777    1109    2212    4414    3437
River Rch & RM= Upper Denton 105,Reach-1,12094
    1293    1866    2363    1482    2958    5902    4653
River Rch & RM= Upper Denton 105,Reach-1,7958
    1611    2347    2990    1886    3763    7508    5984
River Rch & RM= Upper Denton 105,Reach-1,5204
    1609    2335    2967    1866    3723    7429    5887
Boundary for River Rch & Prof#=Upper Denton 105,Reach-1,1
Up Type=0
Dn Type=3
Dn Slope=0.005
Boundary for River Rch & Prof#=Upper Denton 105,Reach-1,2
Up Type=0
Dn Type=3
Dn Slope=0.005
Boundary for River Rch & Prof#=Upper Denton 105,Reach-1,3
Up Type=0
Dn Type=3
Dn Slope=0.005
Boundary for River Rch & Prof#=Upper Denton 105,Reach-1,4
Up Type=0
Dn Type=3
Dn Slope=0.005
Boundary for River Rch & Prof#=Upper Denton 105,Reach-1,5
Up Type=0
Dn Type=3
Dn Slope=0.005
Boundary for River Rch & Prof#=Upper Denton 105,Reach-1,6
Up Type=0
Dn Type=3
Dn Slope=0.005
Boundary for River Rch & Prof#=Upper Denton 105,Reach-1,7
Up Type=0
Dn Type=3
Dn Slope=0.005

--- Upper Denton 105.g01 (geometry) ---

Geom Title=Existing Conditions
Program Version=4.10

River Reach=Upper Denton 105,Reach-1
Reach XY= 30
        2238279.        7242160.      2238179.24      7241994.78
       2238227.1      7241721.95      2238032.81      7241508.44
      2237681.15      7240504.03      2237719.85      7240353.27
      2237473.48      7239757.57      2236882.75      7238958.45
      2236876.65      7238715.52       2236475.5      7237768.46
      2235812.25      7237343.54      2235381.36      7236754.48
      2235028.64      7234930.15      2235029.08      7234125.39
      2235226.84      7233854.55      2235179.07      7233430.03
      2235277.79      7233070.51      2235175.19      7232661.56
      2234732.76      7231958.44      2234480.35      7231250.36
       2234428.5      7230228.68      2234278.82      7229891.57
      2234328.32      7228873.92      2234126.76      7227765.93
       2233980.2       7227550.4      2234028.49      7227225.22
      2233780.22       7226299.5      2233677.62      7225319.66
      2233480.36      7224750.35        2233479.        7223960.

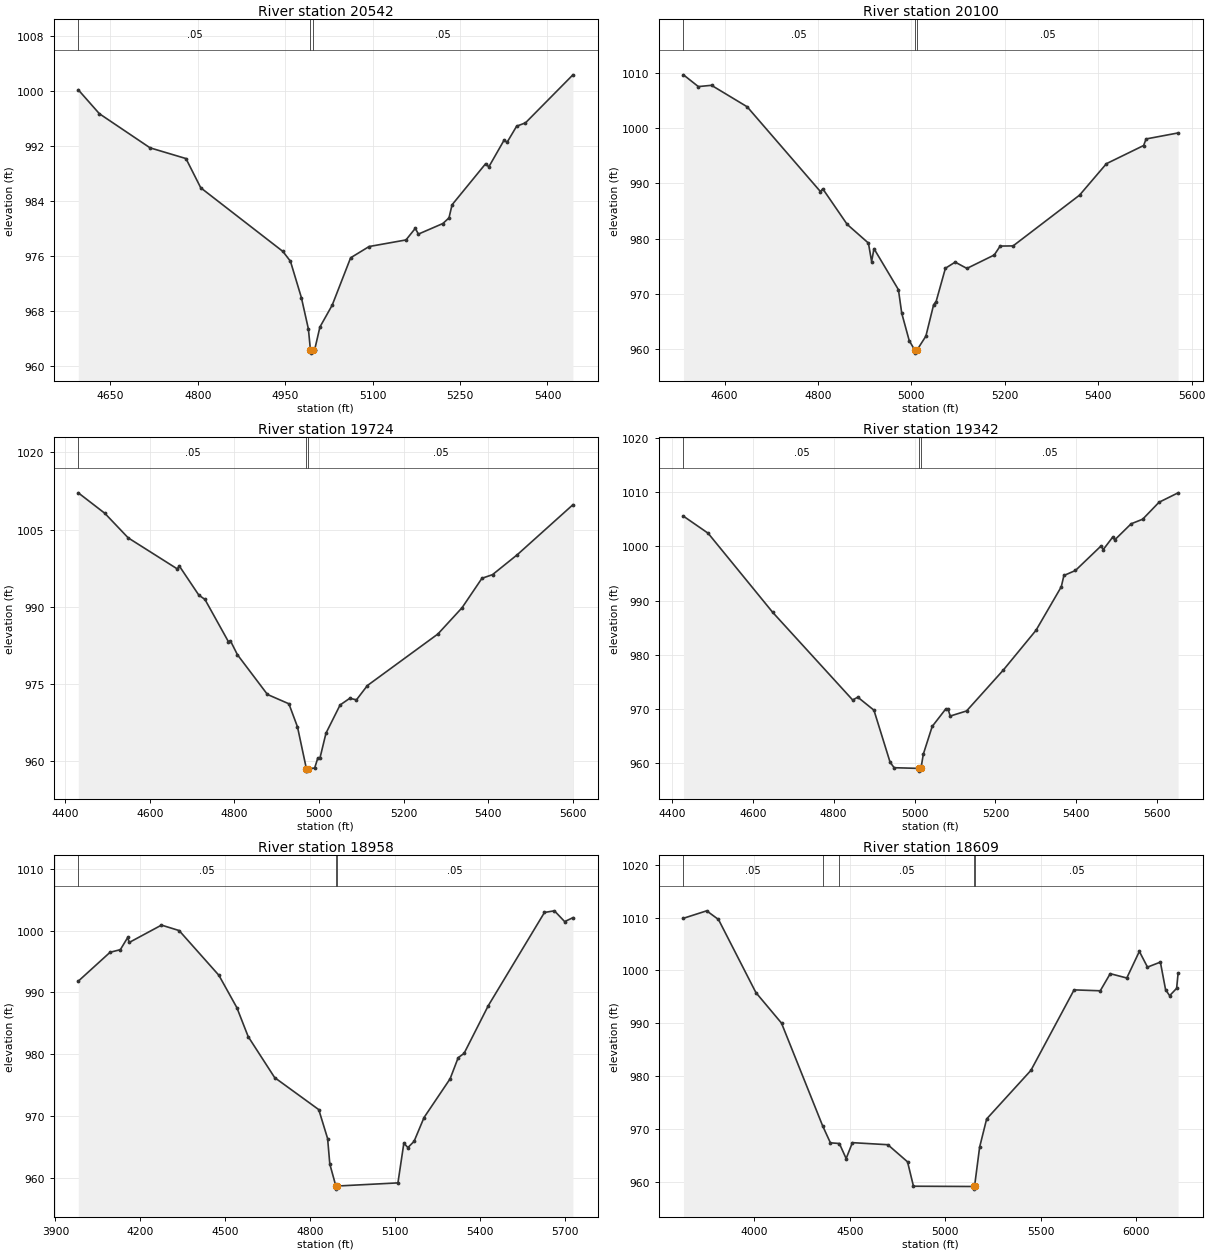
Type RM Length L Ch R = 1 ,20542   ,442,442,442
BEGIN DESCRIPTION:
Upper Denton 105 47.0
END DESCRIPTION:
XS GIS Cut Line= 3
      2238659.53      7241983.31      2238281.02      7242118.74
      2237857.41       7242261.1
#Sta/Elev= 30
  4594.8  1000.2    4631  996.72    4718  991.75  4779.6  990.19    4805  985.93
  4945.9  976.67  4958.9  975.24  4977.7  969.94  4989.7  965.39  4993.2  962.36
  4993.5  961.86  4997.2  962.36  5000.5  962.36  5009.5  965.66  5030.6  968.85
  5062.2  975.74  5093.9  977.38  5157.2  978.34  5173.2  980.03  5178.5  979.19
  5220.5  980.73    5231  981.55  5236.3  983.46    5294  989.45  5299.3  988.97
  5325.5  992.86  5330.8  992.57  5347.1   994.9  5362.3  995.39  5443.7 1002.38
#Mann= 3 ,-1 , 0
  4594.8     .05       0  4993.2    .033       0  4997.2     .05       0
Bank Sta=4993.2,4997.2
XS Rating Curve= 0 ,0
Exp/Cntr=0.3,0.1

Type RM Length L Ch R = 1 ,20100   ,376,376,376
BEGIN DESCRIPTION:
Upper Denton 105 46.0
END DESCRIPTION:
XS GIS Cut Line= 3
      2238708.07      7241639.58      2238232.41      7241729.85
      2237682.18      7241895.95
#Sta/Elev= 30
  4512.1 1009.68    4544 1007.55  4572.2 1007.78  4648.5 1003.89  4805.3  988.53
  4810.4  989.02  4862.6  982.58  4908.1  979.19  4914.9  975.85    4920  978.18
  4972.3  970.75  4979.4  966.49  4995.4  961.52  5007.6  959.75  5007.8  959.25
  5011.6  959.75  5031.1  962.33  5047.7  968.03    5053   968.6  5072.9  974.63
  5093.8  975.74  5118.9   974.6  5177.4  977.03  5190.1  978.65  5217.8  978.68
  5360.1  987.88  5417.6  993.58  5497.2  996.87  5502.5  998.06    5571  999.15
#Mann= 3 ,-1 , 0
  4512.1     .05       0  5007.6    .033       0  5011.6     .05       0
Bank Sta=5007.6,5011.6
XS Rating Curve= 0 ,0
Exp/Cntr=0.3,0.1

Type RM Length L Ch R = 1 ,19724   ,382,382,382
BEGIN DESCRIPTION:
Upper Denton 105 45.0
END DESCRIPTION:
XS GIS Cut Line= 3
      2238590.06      7241365.26        2238029.        7241460.
      2237452.59      7241628.74
#Sta/Elev= 30
    4431 1012.15  4493.7 1008.18  4549.1  1003.4    4665  997.38    4670  997.93
    4716  992.29  4730.5  991.45  4785.9  983.26  4790.9  983.39  4807.3  980.71
  4878.3  972.99    4929  971.18  4949.3   966.7  4970.3   958.6  4970.6   958.1
  4974.3   958.6  4989.9  958.69  4997.5  960.68  5002.6  960.68  5016.7  965.47
  5050.1  970.95  5072.9  972.24  5088.8  971.95  5114.6  974.72  5281.3  984.73
  5338.4  989.83  5385.5  995.55  5410.5  996.26  5468.9 1000.12  5600.6 1009.84
#Mann= 3 ,-1 , 0
    4431     .05       0  4970.3    .033       0  4974.3     .05       0
Bank Sta=4970.3,4974.3
XS Rating Curve= 0 ,0
Exp/Cntr=0.3,0.1

Type RM Length L Ch R = 1 ,19342   ,384,384,384
BEGIN DESCRIPTION:
Upper Denton 105 44.0
END DESCRIPTION:
XS GIS Cut Line= 3
      2238499.82      7241090.96        2237929.        7241110.
      2237336.56      7241382.63
#Sta/Elev= 30
  4428.5 1005.53  4489.4  1002.4  4649.4  987.81  4847.1  971.68  4859.6  972.21
  4899.6  969.81  4939.6  960.22  4949.6  959.22  5011.9  959.09  5012.1  958.59
  5015.9  959.09  5021.7  961.71  5043.7  966.82  5076.7  969.99  5082.8  970.01
  5088.3  968.73  5128.7  969.67  5219.8  977.22  5300.5  984.53  5362.9  992.53
  5369.4  994.61  5397.9  995.53  5461.3 1000.05  5466.8  999.39  5489.8 1001.65
  5495.3 1001.18  5535.7 1004.13  5564.2 1004.97  5604.6 1008.09  5651.8 1009.83
#Mann= 3 ,-1 , 0
  4428.5     .05       0  5011.9    .033       0  5015.9     .05       0
Bank Sta=5011.9,5015.9
XS Rating Curve= 0 ,0
Exp/Cntr=0.3,0.1

Type RM Length L Ch R = 1 ,18958   ,349,349,349
BEGIN DESCRIPTION:
Upper Denton 105 43.0
END DESCRIPTION:
XS GIS Cut Line= 3
      2238788.18      7241092.34        2237829.        7240760.
      2237277.55      7241240.27
#Sta/Elev= 30
  3980.5  991.81  4092.7  996.48  4129.1  996.91    4155  998.88  4160.3  998.07
  4274.3 1000.88  4336.5    1000    4477  992.76  4540.5  987.52  4580.4  982.84
  4673.9  976.21  4829.6  971.03  4860.8  966.35  4868.6  962.22  4889.9  958.67
  4890.2  958.17  4893.9  958.67  5109.1  959.18    5130  965.61  5144.2  964.89
  5166.1   965.9  5201.2  969.75  5293.3  976.02  5321.8  979.43  5342.6  980.13
  5428.1  987.85  5626.5 1002.93  5661.6 1003.19  5697.7 1001.45  5726.9 1002.08
#Mann= 3 ,-1 , 0
  3980.5     .05       0  4889.9    .033       0  4893.9     .05       0
Bank Sta=4889.9,4893.9
XS Rating Curve= 0 ,0
Exp/Cntr=0.3,0.1

Type RM Length L Ch R = 1 ,18609   ,271,271,271
BEGIN DESCRIPTION:
Upper Denton 105 42.0
END DESCRIPTION:
XS GIS Cut Line= 3
      2239006.91      7240127.08        2237679.        7240460.
      2237038.19      7241498.61
#Sta/Elev= 30
  3629.5 1009.87  3751.1 1011.28  3812.9 1009.64  4008.8   995.8  4142.8  990.02
  4358.2  970.56  4398.8  967.35  4445.7  967.22  4481.2  964.37    4514  967.38
  4699.5  966.99  4802.6  963.75  4833.6  959.13  5149.3  959.08  5149.5  958.58
  5153.3  959.08    5180  966.54  5216.7  971.87  5448.5  981.07  5674.4  996.31
  5811.5  996.14  5863.6  999.38  5950.3  998.56  6016.1  1003.6  6058.7 1000.62
  6126.2 1001.57  6153.3  996.36  6174.6  995.21  6211.2   996.6  6218.9  999.46
#Mann= 5 ,-1 , 0
  3629.5     .05       0  4358.2     .12       0  4445.7     .05       0
  5149.3    .033       0  5153.3     .05       0
Bank Sta=5149.3,5153.3
XS Rating Curve= 0 ,0
Exp/Cntr=0.3,0.1

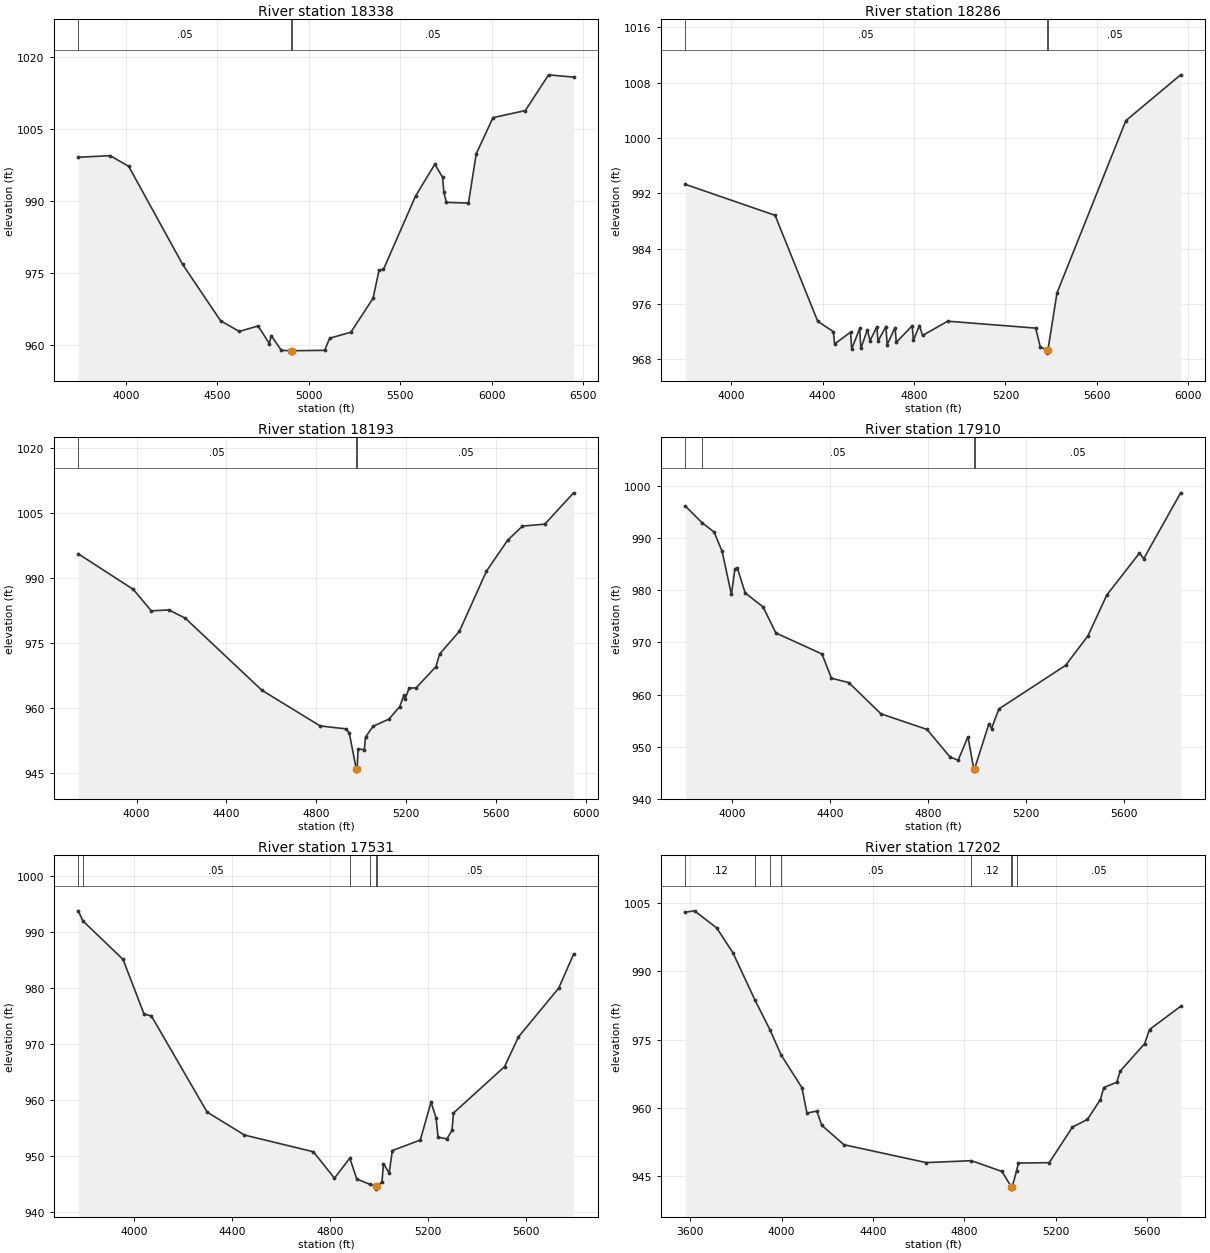
Type RM Length L Ch R = 1 ,18338   ,52,52,52
BEGIN DESCRIPTION:
Upper Denton 105 41.5
END DESCRIPTION:
XS GIS Cut Line= 4
      2238857.68      7239956.92      2237639.42      7240236.39
      2237066.12      7240415.73      2236444.48      7241008.99
#Sta/Elev= 30
  3739.3  999.13  3913.5  999.46    4015  997.24  4309.7  976.85  4517.7  965.09
  4620.2  962.87  4722.9  964.01  4784.4  960.35  4794.7     962    4850  958.92
  4905.6  958.85  4905.8  958.35  4909.6  958.85  5087.1  958.93  5114.3  961.45
  5230.6  962.71  5352.1  969.77  5384.5   975.6  5408.8  975.78  5584.5  991.05
  5689.9  997.67  5732.4  994.96  5739.3  991.84  5753.4  989.74  5873.9  989.58
  5916.4  999.85  6008.2 1007.38    6185 1008.85  6312.3 1016.29  6449.2 1015.81
#Mann= 3 ,-1 , 0
  3739.3     .05       0  4905.6    .033       0  4909.6     .05       0
Bank Sta=4905.6,4909.6
XS Rating Curve= 0 ,0
Exp/Cntr=0.3,0.1

Type RM Length L Ch R = 1 ,18286   ,93,93,93
BEGIN DESCRIPTION:
Upper Denton 105 41.0
END DESCRIPTION:
XS GIS Cut Line= 3
      2238788.17      7239877.08      2237621.53      7240189.57
      2236697.97       7240446.5
#Sta/Elev= 30
    3800  993.31  4192.5  988.83  4378.9  973.51  4447.6     972  4452.8  970.21
  4522.5  971.94  4527.6   969.5  4562.5  972.47  4567.7  969.57  4596.3   972.3
  4607.7   970.7  4637.4  972.69  4642.6  970.63  4677.4  972.75  4682.6  970.13
  4717.4   972.6  4722.6  970.46  4792.3  972.86  4797.5  970.75    4824  972.89
  4837.5  971.45  4947.3  973.52  5332.2  972.52  5352.9  969.75  5382.1   969.4
  5382.3   968.9  5386.1   969.4  5425.6  977.61  5726.6 1002.52  5966.4 1009.15
#Mann= 3 ,-1 , 0
    3800     .05       0  5382.1    .033       0  5386.1     .05       0
Bank Sta=5382.1,5386.1
XS Rating Curve= 0 ,0
Exp/Cntr=0.3,0.1

Type RM Length L Ch R = 1 ,18193   ,283,283,283
BEGIN DESCRIPTION:
Upper Denton 105 40.5
END DESCRIPTION:
XS GIS Cut Line= 3
      2238795.09      7239765.97      2237601.22      7240104.44
      2236677.11      7240380.54
#Sta/Elev= 30
  3740.6  995.51    3986  987.28  4065.5  982.36  4143.7  982.57  4216.8  980.67
  4557.7  964.06  4817.5  955.82  4931.9  955.15  4947.2  954.18  4978.1   945.9
  4978.3   945.4  4982.1   945.9  4986.3  950.52  5014.2  950.33  5019.4  953.23
  5052.5  955.72    5124  957.41  5171.7  960.26  5190.2  962.87  5195.4  961.98
  5213.5  964.53  5244.8   964.6  5333.1   969.5  5349.1  972.38  5437.6  977.66
  5557.9  991.51  5652.1  998.63  5718.3  1001.9  5817.7 1002.35    5946 1009.57
#Mann= 3 ,-1 , 0
  3740.6     .05       0  4978.1    .033       0  4982.1     .05       0
Bank Sta=4978.1,4982.1
XS Rating Curve= 0 ,0
Exp/Cntr=0.3,0.1

Type RM Length L Ch R = 1 ,17910   ,379,379,379
BEGIN DESCRIPTION:
Upper Denton 105 40.0
END DESCRIPTION:
XS GIS Cut Line= 3
      2238622.43      7239509.35        2237479.        7239860.
      2236722.86      7240194.46
#Sta/Elev= 30
  3808.2  996.13    3877  992.91  3925.7  991.16  3958.2  987.47  3996.4  979.19
  4010.5  984.11    4021  984.21  4052.4  979.49  4125.6   976.8  4177.9  971.81
  4366.2  967.78    4405  963.13  4475.8   962.3  4606.7  956.32    4795  953.32
  4889.6  948.02  4922.3  947.43  4962.4  951.92  4985.8  945.83  4986.1  945.33
  4989.8  945.83  5047.9  954.39  5058.9   953.5  5088.5  957.24  5361.1   965.6
  5452.5  971.27  5529.1  979.06  5662.5  987.11  5680.3  986.06    5831  998.67
#Mann= 4 ,-1 , 0
  3808.2     .12       0    3877     .05       0  4985.8    .033       0
  4989.8     .05       0
Bank Sta=4985.8,4989.8
XS Rating Curve= 0 ,0
Exp/Cntr=0.3,0.1

Type RM Length L Ch R = 1 ,17531   ,329,329,329
BEGIN DESCRIPTION:
Upper Denton 105 39.0
END DESCRIPTION:
XS GIS Cut Line= 3
      2238435.79      7239131.75        2237279.        7239560.
      2236643.61      7240029.93
#Sta/Elev= 30
  3770.8  993.76  3789.2  991.98  3953.5  985.09  4039.3  975.35  4069.7  974.98
  4296.9  957.85  4449.8  953.74  4731.5  950.76  4817.4  946.04  4880.1  949.63
  4908.6  945.89  4961.4  944.96  4987.1  944.59  4987.4  944.09  4991.1  944.59
  5011.6  945.39  5017.8  948.64  5040.9  946.97  5054.1  950.98  5168.2  952.85
    5212  959.62  5232.9  956.77  5240.6  953.36  5276.8  953.05  5297.6  954.56
  5303.8  957.67  5512.6  965.96    5569  971.24  5733.9  979.98  5794.6  986.03
#Mann= 6 ,-1 , 0
  3770.8     .12       0  3789.2     .05       0  4880.1     .12       0
  4961.4     .05       0  4987.1    .033       0  4991.1     .05       0
Bank Sta=4987.1,4991.1
XS Rating Curve= 0 ,0
Exp/Cntr=0.3,0.1

Type RM Length L Ch R = 1 ,17202   ,346,346,346
BEGIN DESCRIPTION:
Upper Denton 105 38.0
END DESCRIPTION:
XS GIS Cut Line= 3
      2238318.65      7238615.23        2237079.        7239310.
      2236465.38      7239735.01
#Sta/Elev= 30
  3578.7 1002.96  3618.8 1003.26  3715.8  999.52  3786.6  994.09  3882.5  983.77
  3948.9  977.17  3997.8  971.65    4089  964.45  4110.7   958.9  4154.1  959.33
  4175.8  956.21  4272.7  951.95  4632.9  948.03  4830.5  948.45  4964.4  946.08
  5005.2  942.71  5005.4  942.21  5009.2  942.71  5028.2  946.25  5036.3  947.93
  5171.4  948.02  5272.7  955.82  5338.3  957.51    5395  961.86  5409.9   964.5
  5466.6  965.65  5481.5  968.09  5588.9  974.14  5609.9  977.22  5746.2  982.32
#Mann= 8 ,-1 , 0
  3578.7     .12       0  3882.5     .05       0  3948.9     .12       0
  3997.8     .05       0  4830.5     .12       0  5005.2     .07       0
  5009.2     .12       0  5028.2     .05       0
Bank Sta=5005.2,5009.2
XS Rating Curve= 0 ,0
Exp/Cntr=0.3,0.1

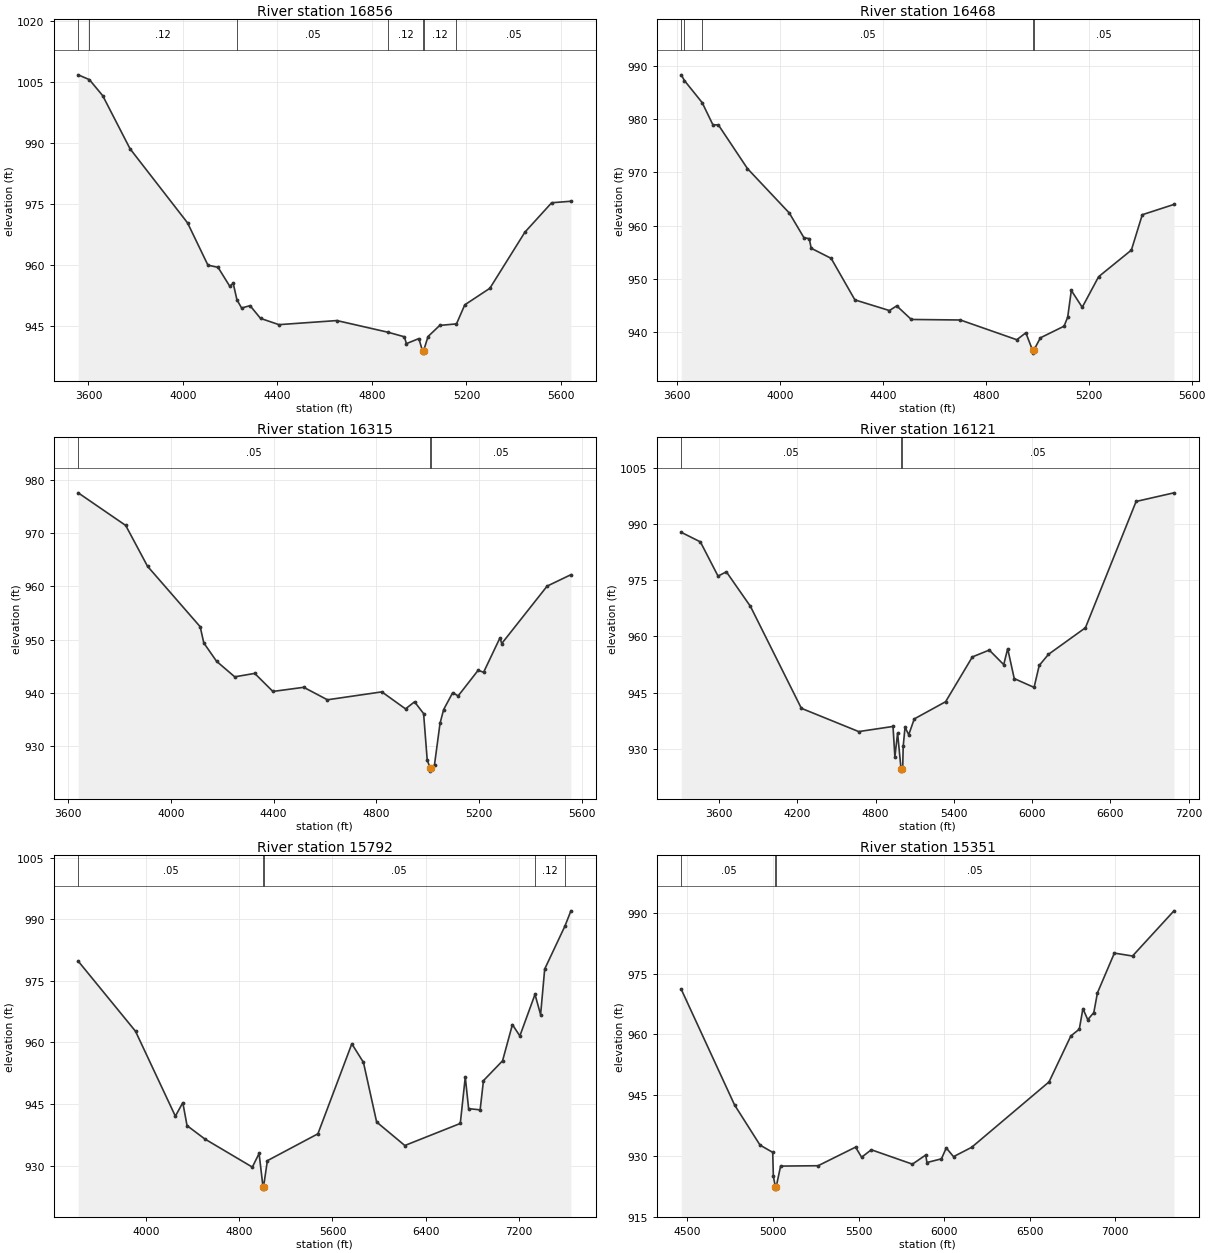
Type RM Length L Ch R = 1 ,16856   ,388,388,388
BEGIN DESCRIPTION:
Upper Denton 105 37.0
END DESCRIPTION:
XS GIS Cut Line= 3
      2238101.61      7238176.88        2236929.        7239010.
      2236474.04      7239470.25
#Sta/Elev= 30
  3556.5 1006.75  3603.9 1005.57  3660.4 1001.63    3776  988.61  4019.6  970.41
  4105.7  960.05  4148.5  959.51  4197.9  954.89  4212.7  955.59  4228.6  951.52
  4248.3  949.53    4284  950.11  4328.3  946.99  4406.1  945.45  4651.5  946.45
  4869.7  943.56  4937.1  942.47  4945.8  940.79  4998.5  942.03  5014.2  938.96
  5014.4  938.46  5018.2  938.96  5037.3  942.53  5086.9  945.26  5157.8  945.64
  5192.9  950.31    5299  954.37  5447.5  968.15  5560.6  975.36  5642.1  975.73
#Mann= 7 ,-1 , 0
  3556.5     .05       0  3603.9     .12       0  4228.6     .05       0
  4869.7     .12       0  5014.2     .07       0  5018.2     .12       0
  5157.8     .05       0
Bank Sta=5014.2,5018.2
XS Rating Curve= 0 ,0
Exp/Cntr=0.3,0.1

Type RM Length L Ch R = 1 ,16468   ,153,153,153
BEGIN DESCRIPTION:
Upper Denton 105 36.0
END DESCRIPTION:
XS GIS Cut Line= 3
      2237841.21      7237708.12        2236829.        7238660.
       2236452.3      7239027.58
#Sta/Elev= 30
  3615.5  988.29    3628  987.21  3696.9  983.08  3738.8  978.91  3759.8  978.91
  3873.1  970.71  4035.7  962.39  4092.4  957.78  4113.4  957.57  4120.7  955.79
  4198.4  953.89  4290.7  946.11    4425  944.11  4453.3  944.99    4510  942.44
  4700.9  942.34  4920.2  938.64  4955.4  939.94  4981.7  936.63    4982  936.13
  4985.7  936.63    5012     939  5103.9  941.18  5118.1  942.87  5132.2  947.88
  5174.6  944.72  5238.4  950.46  5365.7  955.44  5408.1  962.07  5531.3     964
#Mann= 5 ,-1 , 0
  3615.5     .05       0    3628     .12       0  3696.9     .05       0
  4981.7    .033       0  4985.7     .05       0
Bank Sta=4981.7,4985.7
XS Rating Curve= 0 ,0
Exp/Cntr=0.3,0.1

Type RM Length L Ch R = 1 ,16315   ,194,194,194
BEGIN DESCRIPTION:
Upper Denton 105 35.5
END DESCRIPTION:
XS GIS Cut Line= 3
      2237763.11      7237582.23      2236698.79       7238594.9
       2236378.5      7238910.41
#Sta/Elev= 30
  3639.2  977.63  3824.3  971.49  3909.2  963.81  4114.3  952.42  4128.4  949.37
  4178.1  945.92  4248.9  942.99  4326.6  943.64  4397.4  940.24  4517.5  941.02
  4609.7  938.67  4821.7  940.16  4913.9  936.96  4949.1  938.29  4984.3  936.07
  4998.4  927.31  5010.6  925.74  5010.8  925.24  5014.6  925.74  5026.8  926.47
  5048.2  934.22  5062.3  936.83  5097.5     940  5118.9   939.4  5196.6  944.22
  5217.9  943.85  5281.5  950.31  5288.6  949.26  5465.3  960.07  5557.9  962.22
#Mann= 3 ,-1 , 0
  3639.2     .05       0  5010.6    .033       0  5014.6     .05       0
Bank Sta=5010.6,5014.6
XS Rating Curve= 0 ,0
Exp/Cntr=0.3,0.1

Type RM Length L Ch R = 1 ,16121   ,329,329,329
BEGIN DESCRIPTION:
Upper Denton 105 35.0
END DESCRIPTION:
XS GIS Cut Line= 4
      2237979.66      7237273.23        2236679.        7238360.
      2236221.84      7238792.33      2236037.45      7240234.96
#Sta/Elev= 30
  3309.5   987.8  3456.4  985.24  3591.8  976.11  3655.5  977.26  3840.3  968.03
  4230.7  940.84  4670.6  934.63  4933.5     936  4947.8  927.87  4968.6  934.23
  4995.3  924.58  4995.5  924.08  4999.3  924.58  5007.9  924.97  5011.5  930.68
  5025.7  935.79    5054  933.79  5096.5  938.01  5336.8   942.6  5541.9  954.55
  5671.6  956.38  5782.5  952.49  5812.8  956.75  5863.2  948.77  6015.2  946.42
  6054.7  952.28  6125.3  955.23    6409  962.33  6797.7  996.03    7088  998.33
#Mann= 3 ,-1 , 0
  3309.5     .05       0  4995.3    .033       0  4999.3     .05       0
Bank Sta=4995.3,4999.3
XS Rating Curve= 0 ,0
Exp/Cntr=0.3,0.1

Type RM Length L Ch R = 1 ,15792   ,441,441,441
BEGIN DESCRIPTION:
Upper Denton 105 34.0
END DESCRIPTION:
XS GIS Cut Line= 3
      2237914.56      7237218.97        2236579.        7238060.
      2234854.67      7240061.84
#Sta/Elev= 30
  3421.7  979.78  3912.8   962.7  4254.2  942.02  4317.8  945.32  4354.3  939.72
  4506.1  936.48  4913.5  929.62  4971.2  932.94  5005.1  924.76  5005.4  924.26
  5009.1  924.76  5042.3  931.19  5475.1  937.73  5765.5  959.64  5865.1  955.12
  5978.1   940.6  6219.5  934.88  6694.6  940.25  6737.3  951.55  6765.9  943.86
  6864.6  943.56  6893.1  950.68  7056.6   955.5  7141.1  964.32  7204.8  961.56
  7334.6  971.68  7382.5  966.74  7417.6  977.85  7591.8  988.36  7642.1  992.02
#Mann= 5 ,-1 , 0
  3421.7     .05       0  5005.1    .033       0  5009.1     .05       0
  7334.6     .12       0  7591.8     .05       0
Bank Sta=5005.1,5009.1
XS Rating Curve= 0 ,0
Exp/Cntr=0.3,0.1

Type RM Length L Ch R = 1 ,15351   ,442,442,442
BEGIN DESCRIPTION:
Upper Denton 105 33.0
END DESCRIPTION:
XS GIS Cut Line= 3
      2236778.99      7237360.01        2236379.        7237710.
      2234724.45      7239378.27
#Sta/Elev= 30
  4463.5  971.15  4775.3  942.58  4924.3  932.66  4998.5  930.87  5002.1  924.96
  5014.2  922.29  5014.5  921.79  5018.3  922.29  5044.5  927.48  5263.7  927.57
  5482.9  932.16  5518.2  929.66  5574.8  931.51  5815.2  927.96    5893  930.21
  5900.1  928.36  5984.9  929.27  6013.2  931.97  6055.6  929.81  6161.7  932.12
  6614.3  948.28  6741.5  959.61  6791.1   961.3  6812.2  966.36  6840.5  963.64
  6875.9  965.39  6897.1  970.26  6996.1  980.08  7102.2  979.36  7344.6  990.52
#Mann= 3 ,-1 , 0
  4463.5     .05       0  5014.2    .033       0  5018.3     .05       0
Bank Sta=5014.2,5018.3
XS Rating Curve= 0 ,0
Exp/Cntr=0.3,0.1

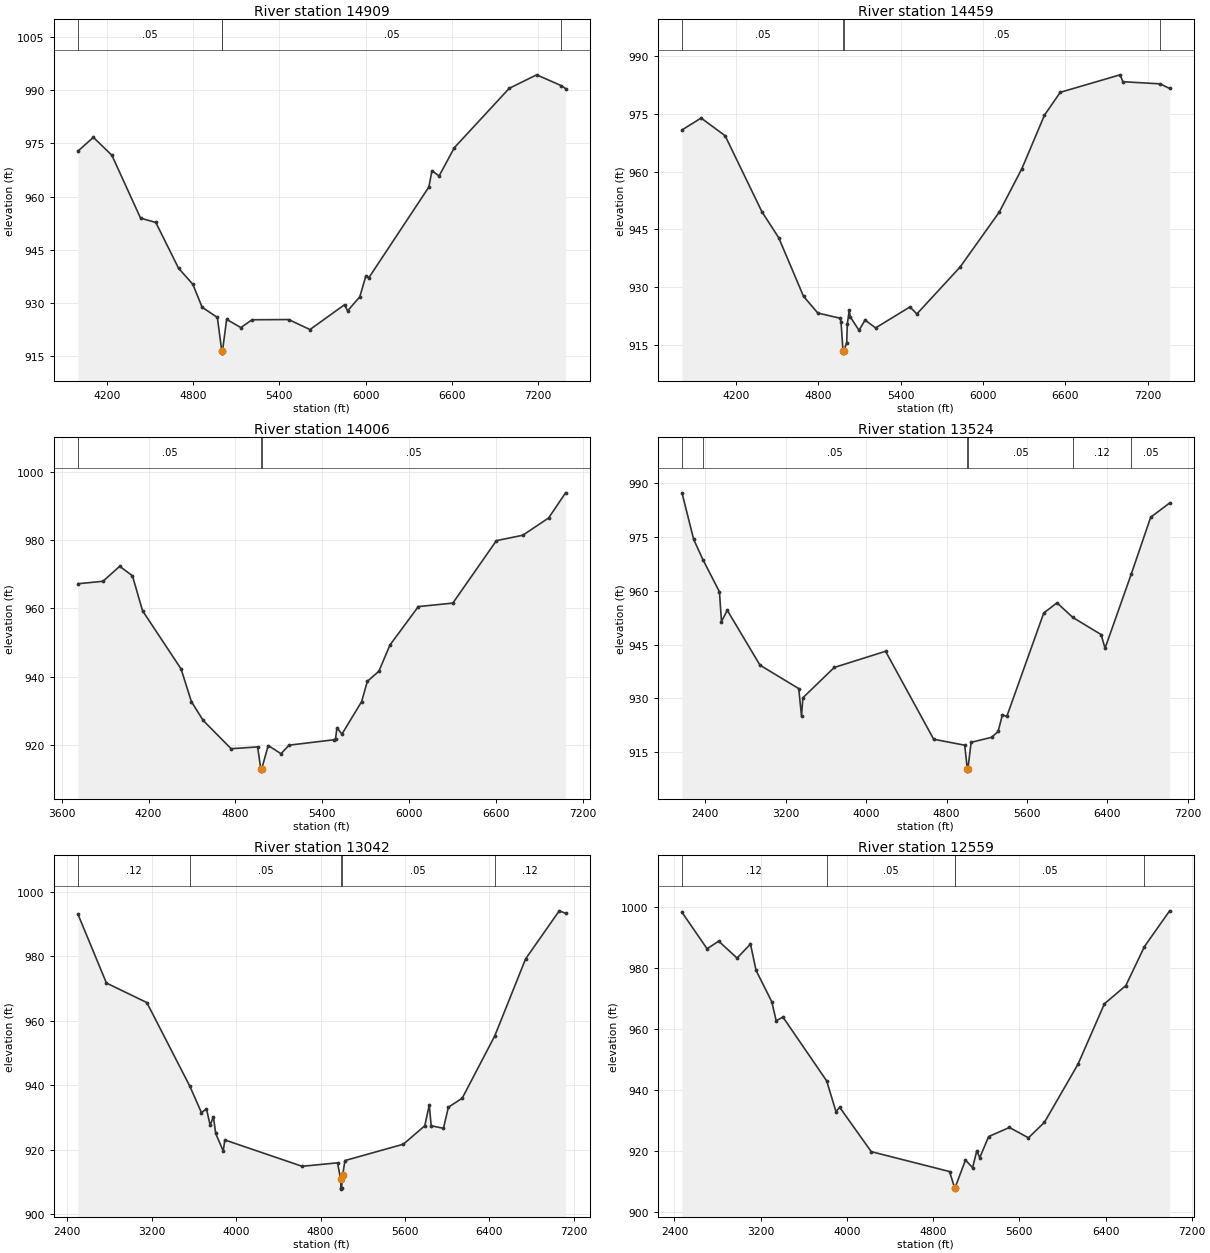
Type RM Length L Ch R = 1 ,14909   ,450,450,450
BEGIN DESCRIPTION:
Upper Denton 105 32.0
END DESCRIPTION:
XS GIS Cut Line= 3
      2236829.52      7236850.03        2236029.        7237460.
      2234344.69      7239150.39
#Sta/Elev= 30
  3998.8  972.82  4106.2   976.7    4235  971.65  4434.6  953.94  4540.7  952.72
  4698.6  939.85  4798.4  935.29  4862.8  928.84  4968.9  925.97    5000  916.41
  5000.3  915.91  5004.2  916.41  5033.5  925.42  5132.5  923.11  5210.3  925.31
  5464.8  925.37  5613.3  922.55  5853.7  929.55    5875  927.81  5959.8  931.78
  6002.3  937.65  6023.5  937.19  6440.7  962.72  6461.9  967.33  6511.4   965.8
  6617.4  973.77  6999.3   990.5  7190.2  994.31  7361.4  991.27  7391.5  990.44
#Mann= 4 ,-1 , 0
  3998.8     .05       0    5000    .033       0  5004.2     .05       0
  7361.4     .12       0
Bank Sta=5000,5004.2
XS Rating Curve= 0 ,0
Exp/Cntr=0.3,0.1

Type RM Length L Ch R = 1 ,14459   ,453,453,453
BEGIN DESCRIPTION:
Upper Denton 105 31.0
END DESCRIPTION:
XS GIS Cut Line= 3
      2236775.21       7236730.7        2235679.        7237210.
      2234269.14      7239095.58
#Sta/Elev= 30
  3808.1  970.86  3947.5  973.96  4122.1  969.36  4390.4  949.56  4512.8  942.78
    4693  927.55  4797.5  923.19  4960.9  921.84  4966.7  920.74  4980.6  913.26
  4980.9  912.76  4984.8  913.26  5007.6  915.48  5011.8  920.23  5026.4  924.05
  5032.6  922.24  5097.3   918.7    5141  921.37  5218.1  919.33  5468.2  924.79
  5518.3  922.96    5833  935.16  6118.5  949.48  6283.2  960.79  6447.8  974.73
  6562.5  980.66  6998.1  985.21  7018.9  983.42  7289.8  982.86  7358.9  981.66
#Mann= 4 ,-1 , 0
  3808.1     .05       0  4980.6    .033       0  4984.8     .05       0
  7289.8     .12       0
Bank Sta=4980.6,4984.8
XS Rating Curve= 0 ,0
Exp/Cntr=0.3,0.1

Type RM Length L Ch R = 1 ,14006   ,482,482,482
BEGIN DESCRIPTION:
Upper Denton 105 30.0
END DESCRIPTION:
XS GIS Cut Line= 3
      2236699.26      7236622.19        2235429.        7236860.
       2233553.3      7237750.32
#Sta/Elev= 30
  3712.1  967.18  3885.3  967.91  4000.7   972.3  4088.8   969.5  4158.5  959.28
  4424.5  942.26  4495.7   932.7  4577.1  927.18  4770.4  918.89  4953.6  919.42
  4975.7  912.83  4976.3  912.33  4980.6  912.83  5026.6  919.83  5115.1  917.43
  5170.5  919.93  5478.7   921.5  5491.5  921.77  5501.4  925.01  5535.8  923.17
  5671.6  932.66  5711.5  938.63  5790.8  941.55  5867.8  949.26  6063.5   960.5
  6301.9  961.52  6602.9   979.8  6784.8  981.38  6963.7  986.44  7080.7   993.8
#Mann= 3 ,-1 , 0
  3712.1     .05       0  4975.7    .033       0  4980.6     .05       0
Bank Sta=4975.7,4980.6
XS Rating Curve= 0 ,0
Exp/Cntr=0.3,0.1

Type RM Length L Ch R = 1 ,13524   ,482,482,482
BEGIN DESCRIPTION:
Upper Denton 105 29.0
END DESCRIPTION:
XS GIS Cut Line= 3
      2238092.58      7235797.34        2235329.        7236410.
      2233457.13      7237164.54
#Sta/Elev= 30
  2169.4  987.39  2285.7  974.39  2379.7  968.62  2541.8  959.78  2562.3  951.46
  2619.6  954.61  2945.2  939.28  3330.5  932.74    3358  925.02  3371.5  930.18
  3683.6  938.64  4193.8  943.16  4672.3   918.6  4980.8  916.94    5007   910.2
  5007.6   909.7    5012   910.2  5044.4  917.74  5248.1  919.14  5312.9  920.77
  5355.8  925.45    5399  924.95  5766.7  953.84  5898.2  956.68    6056   952.6
    6337  947.82  6376.2     944  6637.3  964.74    6830  980.58  7018.3  984.55
#Mann= 6 ,-1 , 0
  2169.4     .12       0  2379.7     .05       0    5007    .033       0
    5012     .05       0    6056     .12       0  6637.3     .05       0
Bank Sta=5007,5012
XS Rating Curve= 0 ,0
Exp/Cntr=0.3,0.1

Type RM Length L Ch R = 1 ,13042   ,483,483,483
BEGIN DESCRIPTION:
Upper Denton 105 28.0
END DESCRIPTION:
XS GIS Cut Line= 3
      2237532.61      7234990.07        2235229.        7235960.
      2233236.88      7236695.38
#Sta/Elev= 30
  2500.1  993.01  2770.2  971.68  3153.3  965.63  3562.1  939.65  3671.4  931.53
  3718.9  932.72  3753.5  927.63  3784.4  930.26  3806.4  925.08  3877.6  919.67
  3892.9  923.08  4625.6  914.92  4961.3     916  4990.4  910.97  4994.4  908.35
    4995  907.85  4999.4  908.35  5009.5  912.13  5031.6   916.7  5585.9  921.77
  5788.4  927.48    5831  933.89  5849.2  927.47  5965.6  926.69  6012.2  933.23
  6142.8  935.99  6451.6  955.28  6744.5  979.17  7063.2  994.04  7123.1  993.29
#Mann= 5 ,-1 , 0
  2500.1     .12       0  3562.1     .05       0  4994.4    .033       0
  4999.4     .05       0  6451.6     .12       0
Bank Sta=4990.4,5009.5
XS Rating Curve= 0 ,0
Exp/Cntr=0.3,0.1

Type RM Length L Ch R = 1 ,12559   ,465,465,465
BEGIN DESCRIPTION:
Upper Denton 105 27.0
END DESCRIPTION:
XS GIS Cut Line= 3
       2237571.7      7234833.81        2235129.        7235510.
      2233366.32       7236435.2
#Sta/Elev= 30
  2469.6  998.21  2702.4  986.27  2810.5  988.76  2980.8  983.22  3105.3  987.81
  3157.2  979.19  3303.2  968.92    3344   962.7  3406.1  963.95  3812.6  943.03
  3898.8  932.98  3933.1  934.41    4226   919.9  4952.7  913.39    4999  908.14
  4999.7  907.64  5004.2  908.14  5100.6  917.16  5166.7  914.65  5205.2  920.17
  5232.9  917.94  5315.4  924.84  5508.3  927.81  5684.7  924.43  5833.4   929.5
  6144.8  948.52  6389.8  968.26  6588.3  974.22  6761.6  987.01  6994.9  998.68
#Mann= 5 ,-1 , 0
  2469.6     .12       0  3812.6     .05       0    4999    .033       0
  5004.2     .05       0  6761.6     .12       0
Bank Sta=4999,5004.2
XS Rating Curve= 0 ,0
Exp/Cntr=0.3,0.1

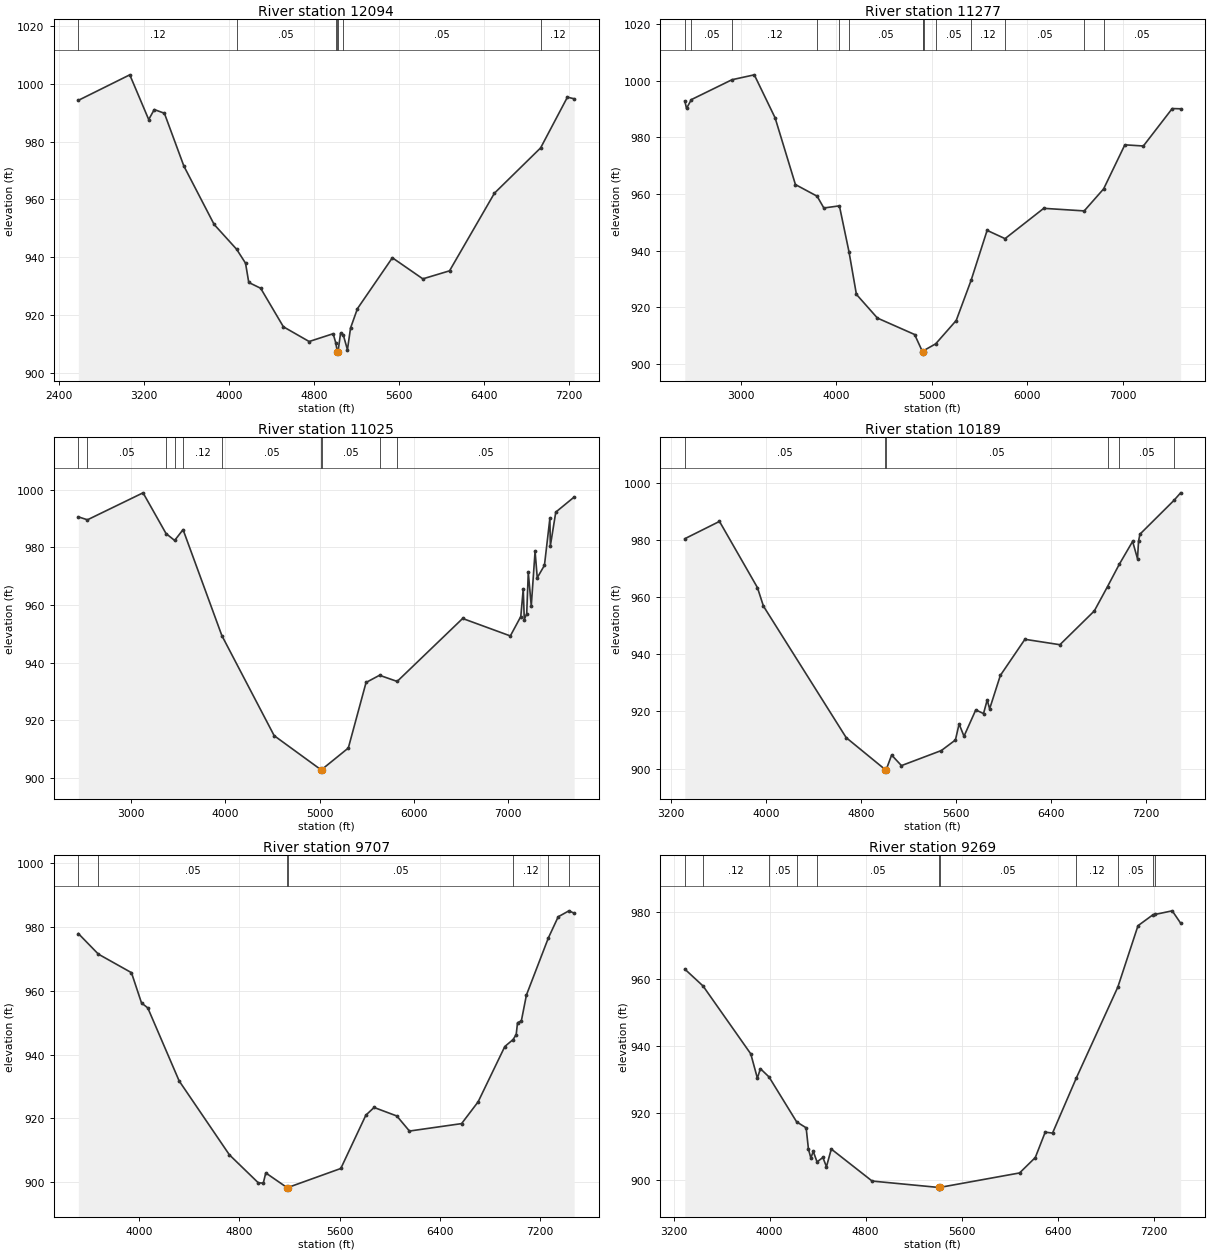
Type RM Length L Ch R = 1 ,12094   ,817,817,817
BEGIN DESCRIPTION:
Upper Denton 105 26.0
END DESCRIPTION:
XS GIS Cut Line= 3
      2237454.52      7234612.45        2235079.        7235060.
      2233262.91      7236382.49
#Sta/Elev= 30
  2583.1  994.26    3067  1003.1    3245  987.62  3297.5  991.08  3392.6  989.79
  3575.8  971.51  3860.7  951.28  4072.2  942.69  4155.8  937.88  4186.3   931.2
  4298.3  929.19    4512  915.85  4754.2  910.75  4980.1  913.45  5004.7  910.27
  5019.2  907.23  5020.3  906.73  5025.6  907.23  5049.9  913.64  5074.9  913.08
  5114.4  907.92  5143.7  915.43  5208.6  922.14    5537  939.75  5823.7  932.45
  6074.8  935.23  6497.2  962.12  6931.4  977.79  7183.6  995.37    7247   994.8
#Mann= 7 ,-1 , 0
  2583.1     .12       0  4072.2     .05       0  5004.7     .12       0
  5019.2    .033       0  5025.6     .12       0  5074.9     .05       0
  6931.4     .12       0
Bank Sta=5019.2,5025.6
XS Rating Curve= 0 ,0
Exp/Cntr=0.3,0.1

Type RM Length L Ch R = 1 ,11277   ,252,252,252
BEGIN DESCRIPTION:
Upper Denton 105 24.0
END DESCRIPTION:
XS GIS Cut Line= 5
      2237480.54      7234482.25      2235644.64      7234742.66
      2235045.68      7234247.87      2234811.31      7234078.59
      2232754.04      7235042.12
#Sta/Elev= 30
  2412.6  992.86  2430.8  990.28  2481.1  993.37  2906.7  1000.4  3140.3 1002.13
  3358.2  986.93  3571.1  963.35    3798  959.24  3868.6  955.07  4031.5  955.83
    4132  939.59  4209.6  924.55  4429.6  916.17  4819.1  910.36  4901.7  904.28
  4902.8  903.78  4908.5  904.28  4913.1  904.66  5039.6  907.06  5254.6  915.31
    5410  929.45  5578.3  947.16  5766.1  944.24  6171.2  954.95    6595  954.04
  6798.4  961.83  7020.7  977.39  7214.4  976.98  7516.7  990.21  7604.6  990.13
#Mann= 14 ,-1 , 0
  2412.6     .12       0  2481.1     .05       0  2906.7     .12       0
    3798     .05       0  4031.5     .12       0    4132     .05       0
  4901.7     .07       0  4908.5     .05       0  4913.1     .12       0
  5039.6     .05       0    5410     .12       0  5766.1     .05       0
    6595     .12       0  6798.4     .05       0
Bank Sta=4901.7,4908.5
XS Rating Curve= 0 ,0
Exp/Cntr=0.3,0.1

Type RM Length L Ch R = 1 ,11025   ,836,836,836
BEGIN DESCRIPTION:
Upper Denton 105 23.0
END DESCRIPTION:
XS GIS Cut Line= 5
      2237493.64      7234325.99      2235570.47      7234447.79
      2235071.72      7234052.55      2234850.37       7233896.3
      2232558.71      7234677.55
#Sta/Elev= 30
  2441.6  990.63  2538.5  989.61  3127.6  998.97  3371.2  984.84  3462.4  982.44
  3551.7   986.2  3962.9  949.42  4517.6  914.68  5012.8  902.88  5013.9  902.38
  5019.7  902.88  5303.3   910.4  5491.4  933.15  5634.4  935.65    5821  933.51
  6515.2  955.36  7020.6   949.3  7131.5  956.04  7157.5  965.65  7168.5  954.99
  7194.1  956.99  7210.8  971.34  7242.5   959.7  7282.9  978.67  7305.9   969.5
  7382.2   973.8  7439.6  990.06  7444.9   980.6  7502.3  992.27  7697.1  997.51
#Mann= 10 ,-1 , 0
  2441.6     .12       0  2538.5     .05       0  3371.2     .12       0
  3462.4     .05       0  3551.7     .12       0  3962.9     .05       0
  5012.8    .033       0  5019.7     .05       0  5634.4     .12       0
    5821     .05       0
Bank Sta=5012.8,5019.7
XS Rating Curve= 0 ,0
Exp/Cntr=0.3,0.1

Type RM Length L Ch R = 1 ,10189   ,482,482,482
BEGIN DESCRIPTION:
Upper Denton 105 22.0
END DESCRIPTION:
XS GIS Cut Line= 3
      2236894.68      7233557.77        2235229.        7233310.
      2232806.13      7233909.32
#Sta/Elev= 30
    3316  980.43  3608.3  986.49  3928.3  963.33  3978.9  956.85  4676.5  910.82
  5006.8   899.6  5007.9   899.1  5013.8   899.6  5059.6  904.73  5142.4  901.03
    5479  906.31  5597.5     910  5628.4  915.62  5669.6   911.3    5769  920.52
  5834.4  919.24  5865.3     924  5885.9   920.9  5976.1  932.59  6183.2  945.23
  6478.3  943.34  6768.3  955.16  6879.9   963.7  6977.9  971.42  7091.2  979.49
  7132.4  973.43  7141.2   979.6    7153  982.02  7439.1  993.82  7495.9  996.49
#Mann= 6 ,-1 , 0
    3316     .05       0  5006.8    .033       0  5013.8     .05       0
  6879.9     .12       0  6977.9     .05       0  7439.1     .12       0
Bank Sta=5006.8,5013.8
XS Rating Curve= 0 ,0
Exp/Cntr=0.3,0.1

Type RM Length L Ch R = 1 ,9707    ,438,438,438
BEGIN DESCRIPTION:
Upper Denton 105 21.0
END DESCRIPTION:
XS GIS Cut Line= 3
      2236712.32      7232932.76        2235229.        7232860.
      2232793.57      7233271.22
#Sta/Elev= 30
  3515.3  977.93  3675.2  971.48  3939.1  965.67  4019.2  956.19  4069.3  954.63
  4319.6  931.74  4720.1   908.6  4950.3  899.84  4990.4   899.7  5010.5  902.92
  5179.4  898.34  5180.5  897.84  5186.5  898.34  5608.9  904.31    5809  921.03
  5874.5  923.43  6055.8  920.76  6156.5  916.04  6572.3  918.37  6704.2  925.19
  6917.2  942.53  6983.1  944.71  7007.9  946.27  7018.6  949.99    7049  950.54
  7089.6  958.67  7264.7  976.57  7343.1  983.19  7428.7  985.05  7470.3  984.31
#Mann= 7 ,-1 , 0
  3515.3     .12       0  3675.2     .05       0  5179.4    .033       0
  5186.5     .05       0  6983.1     .12       0  7264.7     .05       0
  7428.7     .12       0
Bank Sta=5179.4,5186.5
XS Rating Curve= 0 ,0
Exp/Cntr=0.3,0.1

Type RM Length L Ch R = 1 ,9269    ,419,419,419
BEGIN DESCRIPTION:
Upper Denton 105 20.0
END DESCRIPTION:
XS GIS Cut Line= 3
      2236738.38      7232424.95        2235029.        7232510.
      2232649.86       7232958.8
#Sta/Elev= 30
    3293  963.02  3445.1  957.98  3843.1   937.7  3897.9  930.46  3923.2  933.29
  3994.9  930.83  4225.2  917.41  4304.4  915.64  4323.7  909.24  4343.7  906.64
  4363.7  908.59  4395.3  905.46  4443.8  906.78  4473.8  904.02  4513.9   909.3
  4854.3  899.74  5409.3  897.83  5410.4  897.33  5416.5  897.83  6083.2  902.16
  6214.3  906.76  6296.9  914.34    6358  914.06  6556.1   930.5  6902.2  957.65
  7070.3  975.98  7195.3  979.25  7211.3  979.33  7355.7  980.42  7425.6  976.74
#Mann= 11 ,-1 , 0
    3293     .05       0  3445.1     .12       0  3994.9     .05       0
  4225.2     .12       0  4395.3     .05       0  5409.3     .04       0
  5416.5     .05       0  6556.1     .12       0  6902.2     .05       0
  7195.3     .12       0  7211.3     .05       0
Bank Sta=5409.3,5416.5
XS Rating Curve= 0 ,0
Exp/Cntr=0.3,0.1