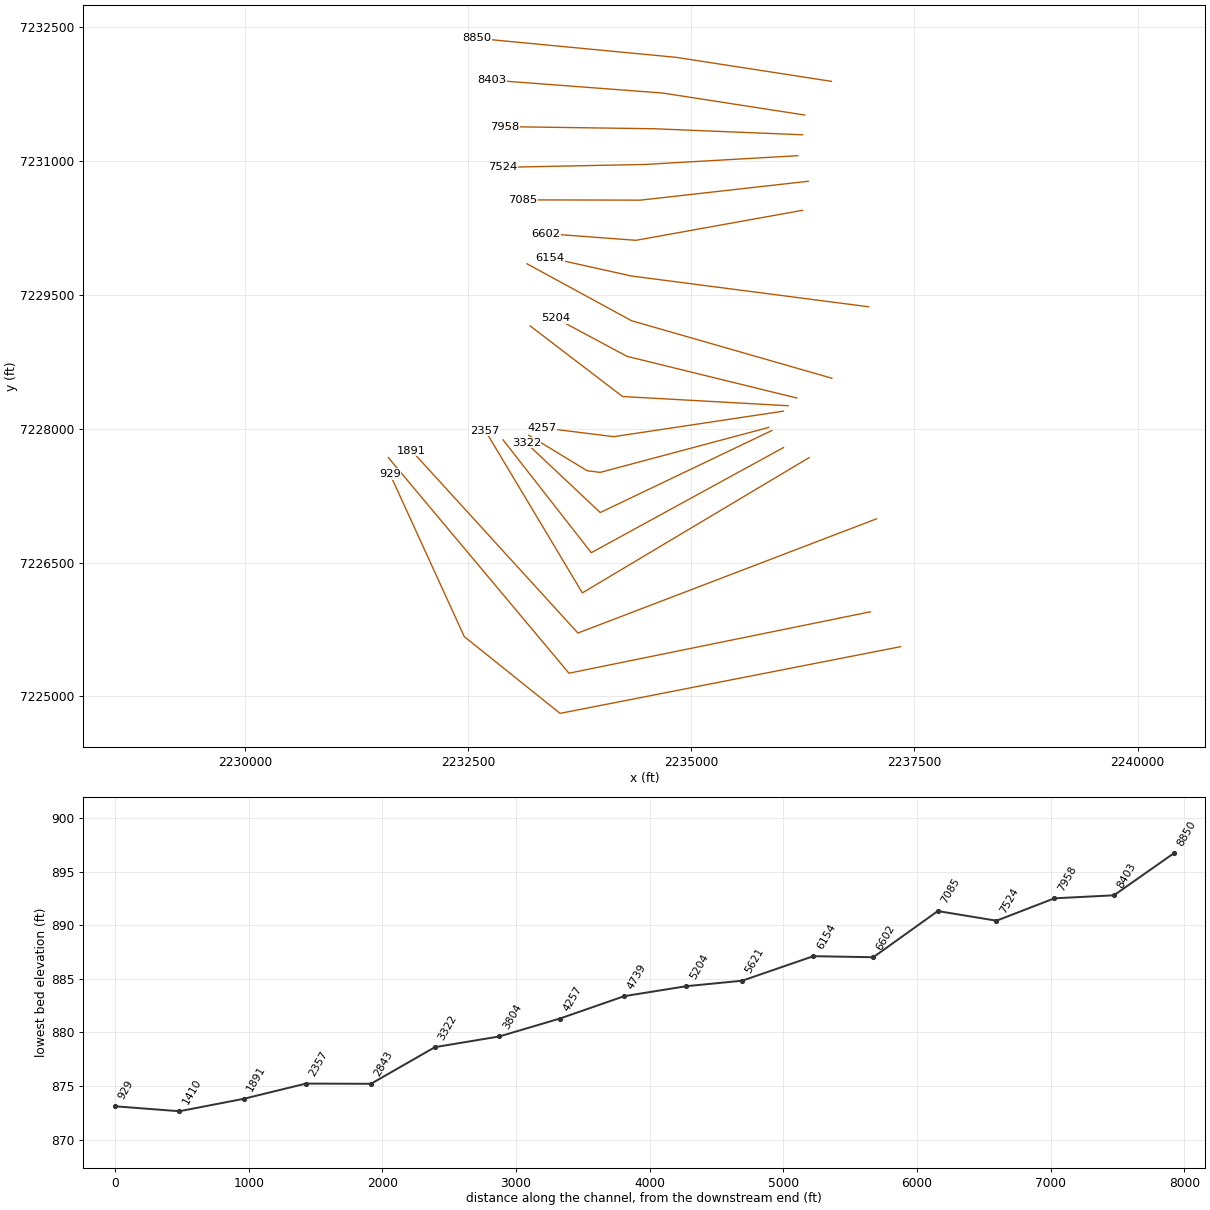
HEC-RAS study Upper Denton 105.prj: Upper Denton 105 Base Level Engineering

--- Upper Denton 105.g01 (geometry) --- (continued)

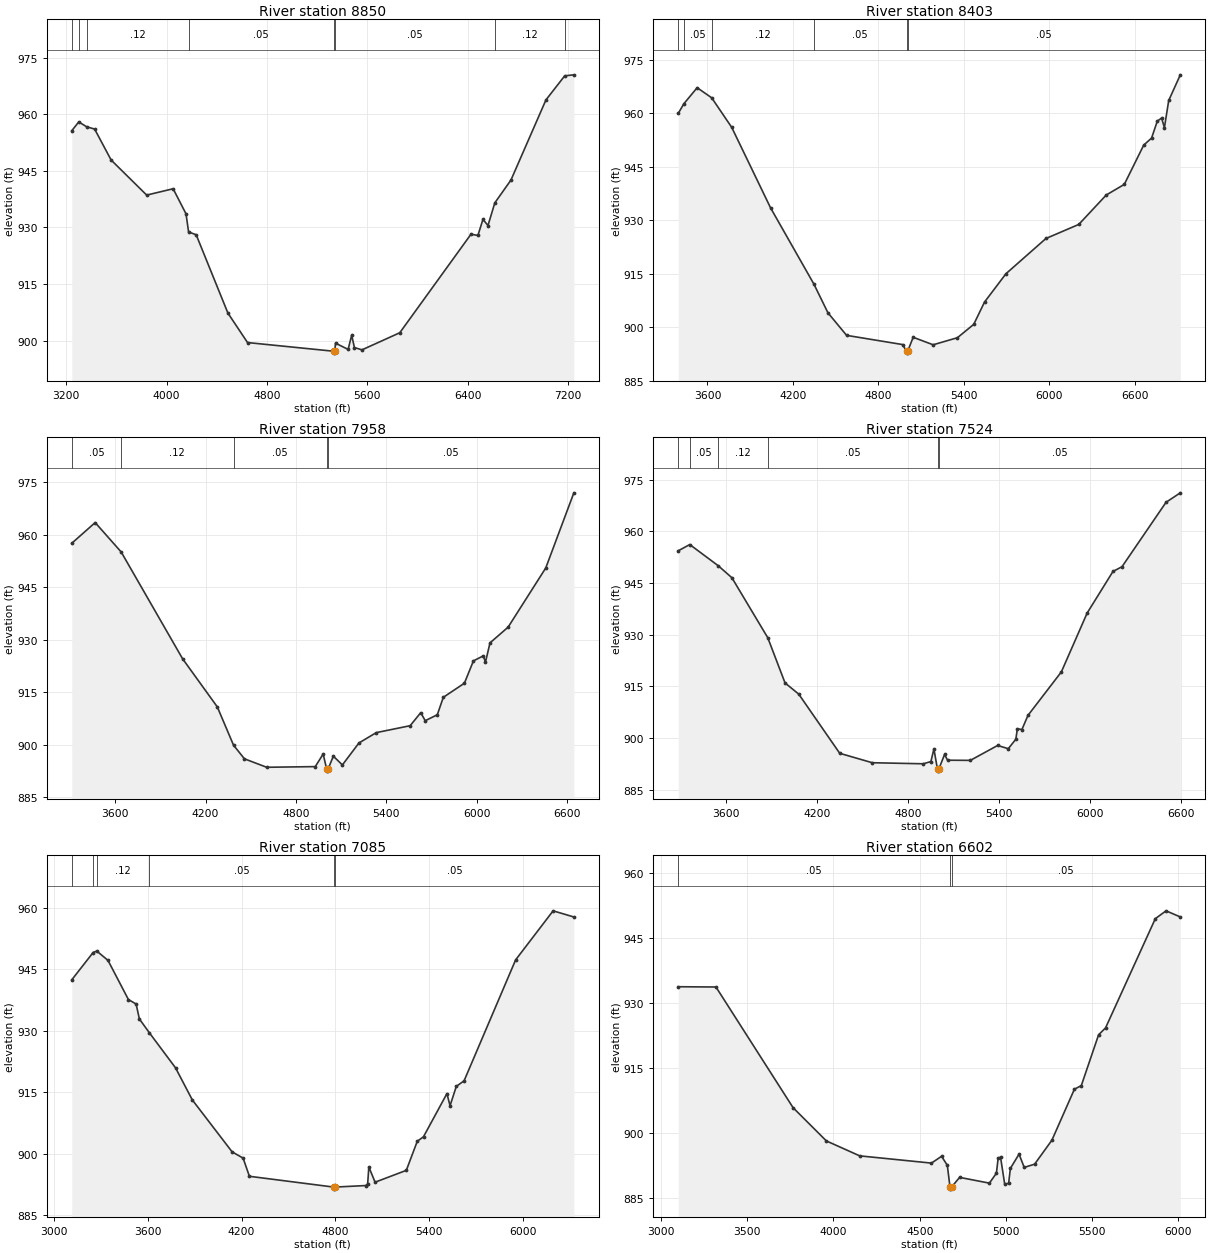
Type RM Length L Ch R = 1 ,8850    ,447,447,447
BEGIN DESCRIPTION:
Upper Denton 105 19.0
END DESCRIPTION:
XS GIS Cut Line= 3
      2236569.15      7231891.09        2234829.        7232160.
      2232597.74      7232372.87
#Sta/Elev= 30
  3243.9  955.64  3299.7  957.97  3361.4   956.7  3426.2  956.07  3557.7  947.87
  3841.1  938.58  4051.9  940.26  4154.7  933.61    4175  928.82  4235.7  928.06
  4488.7   907.3    4645   899.5  5332.6   897.2  5333.7   896.7  5339.8   897.2
  5346.3  899.34  5446.7  897.69  5475.2  901.44  5496.9  898.18  5557.2  897.57
  5858.6   902.1  6426.2  928.21  6481.4  927.89  6521.6  932.14  6561.7  930.52
  6616.1  936.52  6744.8  942.57  7023.8  963.81  7173.3  970.18  7246.1  970.45
#Mann= 8 ,-1 , 0
  3243.9     .12       0  3299.7     .05       0  3361.4     .12       0
    4175     .05       0  5332.6     .04       0  5339.8     .05       0
  6616.1     .12       0  7173.3     .05       0
Bank Sta=5332.6,5339.8
XS Rating Curve= 0 ,0
Exp/Cntr=0.3,0.1

Type RM Length L Ch R = 1 ,8403    ,445,445,445
BEGIN DESCRIPTION:
Upper Denton 105 18.0
END DESCRIPTION:
XS GIS Cut Line= 3
      2236270.29      7231513.71        2234679.        7231760.
      2232767.68      7231904.33
#Sta/Elev= 30
  3394.5  959.96  3434.1  962.67  3527.4  967.16  3629.6  964.33  3770.2  956.05
  4043.4  933.47  4347.9  912.11  4446.1  904.09  4577.2  897.77  4970.7  895.19
  4998.6  893.29  4999.7  892.79  5005.9  893.29  5044.9  897.23  5185.3  895.13
  5355.7  897.11  5470.3  900.85  5546.3  907.11  5696.7  915.04  5977.5  924.91
  6208.2  928.85  6401.4   937.1    6528  940.07  6664.6  951.09  6719.6  953.04
  6759.7  957.78  6789.8  958.66  6809.9  955.99    6840  963.58  6921.5  970.77
#Mann= 6 ,-1 , 0
  3394.5     .12       0  3434.1     .05       0  3629.6     .12       0
  4347.9     .05       0  4998.6     .04       0  5005.9     .05       0
Bank Sta=4998.6,5005.9
XS Rating Curve= 0 ,0
Exp/Cntr=0.3,0.1

Type RM Length L Ch R = 1 ,7958    ,434,434,434
BEGIN DESCRIPTION:
Upper Denton 105 17.0
END DESCRIPTION:
XS GIS Cut Line= 3
      2236244.26      7231292.35        2234579.        7231360.
       2232912.5      7231383.48
#Sta/Elev= 30
  3311.6  957.61    3467  963.52  3639.5  955.13  4047.5   924.6  4277.7  910.87
  4385.6  899.92  4457.8  896.03  4605.8  893.61  4928.2   893.8  4980.7   897.4
  5004.3  893.01  5005.5  892.51  5012.2  893.01  5048.2  896.78  5108.2  894.28
  5218.3  900.56  5333.2  903.51  5558.3  905.49  5628.3  909.21  5658.3  906.92
  5738.3  908.61  5778.3   913.6  5918.3  917.63  5978.3  924.01  6043.2  925.43
  6058.3  923.68  6088.3  929.15  6208.4  933.64  6458.4  950.55  6644.9  972.02
#Mann= 5 ,-1 , 0
  3311.6     .05       0  3639.5     .12       0  4385.6     .05       0
  5004.3     .04       0  5012.2     .05       0
Bank Sta=5004.3,5012.2
XS Rating Curve= 0 ,0
Exp/Cntr=0.3,0.1

Type RM Length L Ch R = 1 ,7524    ,439,439,439
BEGIN DESCRIPTION:
Upper Denton 105 16.0
END DESCRIPTION:
XS GIS Cut Line= 3
       2236192.2      7231057.98        2234479.        7230960.
      2232884.82      7230927.77
#Sta/Elev= 30
    3284  954.36  3360.1  956.17  3548.4     950  3637.8  946.54  3874.5  929.12
  3988.3  916.01  4078.5  912.77  4348.9  895.59  4563.2  892.86  4899.8  892.55
  4949.9   893.2  4969.9  896.85  4993.5  890.92  4994.7  890.42  5001.4  890.92
    5040  895.25    5060  893.59    5210  893.54  5390.1  897.87  5460.1  896.93
  5510.1  899.68  5520.1  902.73  5550.1  902.49  5590.1   906.6  5810.2  919.22
  5980.2  936.29  6150.2  948.35  6210.2  949.75  6500.3  968.43  6594.5  971.18
#Mann= 6 ,-1 , 0
    3284     .12       0  3360.1     .05       0  3548.4     .12       0
  3874.5     .05       0  4993.5     .04       0  5001.4     .05       0
Bank Sta=4993.5,5001.4
XS Rating Curve= 0 ,0
Exp/Cntr=0.3,0.1

Type RM Length L Ch R = 1 ,7085    ,483,483,483
BEGIN DESCRIPTION:
Upper Denton 105 15.0
END DESCRIPTION:
XS GIS Cut Line= 3
      2236309.31      7230771.52        2234429.        7230560.
      2233106.28      7230563.19
#Sta/Elev= 30
  3112.9  942.37  3249.5  949.03    3273  949.39  3344.7  947.12  3475.5  937.57
  3524.9  936.46  3545.9  932.82  3609.3  929.48  3777.4   920.9  3884.9  913.07
  4139.6  900.41  4210.1  898.88  4250.3  894.45  4789.7  891.82  4790.9  891.32
  4797.8  891.82    4995  892.19  5007.6  892.61  5015.1  896.73  5055.1  893.01
  5255.1   895.9  5325.1  902.98  5365.1   904.1  5515.1  914.62  5535.1  911.66
  5575.1  916.37  5625.1  917.75  5955.1  947.24  6195.1   959.2  6327.8   957.7
#Mann= 6 ,-1 , 0
  3112.9     .12       0  3249.5     .05       0    3273     .12       0
  3609.3     .05       0  4789.7     .04       0  4797.8     .05       0
Bank Sta=4789.7,4797.8
XS Rating Curve= 0 ,0
Exp/Cntr=0.3,0.1

Type RM Length L Ch R = 1 ,6602    ,448,448,448
BEGIN DESCRIPTION:
Upper Denton 105 14.0
END DESCRIPTION:
XS GIS Cut Line= 3
      2236244.23        7230446.        2234379.        7230110.
      2233366.67      7230185.58
#Sta/Elev= 30
  3100.2  933.67  3318.9  933.61    3766  905.78    3959  898.12  4152.1  894.68
    4568  893.01  4626.7  894.58  4660.1  892.49  4675.4  887.51  4676.8  887.01
  4685.1  887.51  4731.3  889.72    4904  888.39  4944.6  890.69  4954.8   894.2
  4968.6  894.35  4992.9   888.1  5015.5  888.39  5025.5  891.79  5075.7  895.07
  5105.8  892.02  5165.9  892.76  5266.2  898.29  5396.6  910.04  5436.7  910.88
    5537   922.6  5577.1  924.17  5865.7  949.36    5928  951.17  6010.6  949.76
#Mann= 3 ,-1 , 0
  3100.2     .05       0  4675.4    .033       0  4685.1     .05       0
Bank Sta=4675.4,4685.1
XS Rating Curve= 0 ,0
Exp/Cntr=0.3,0.1

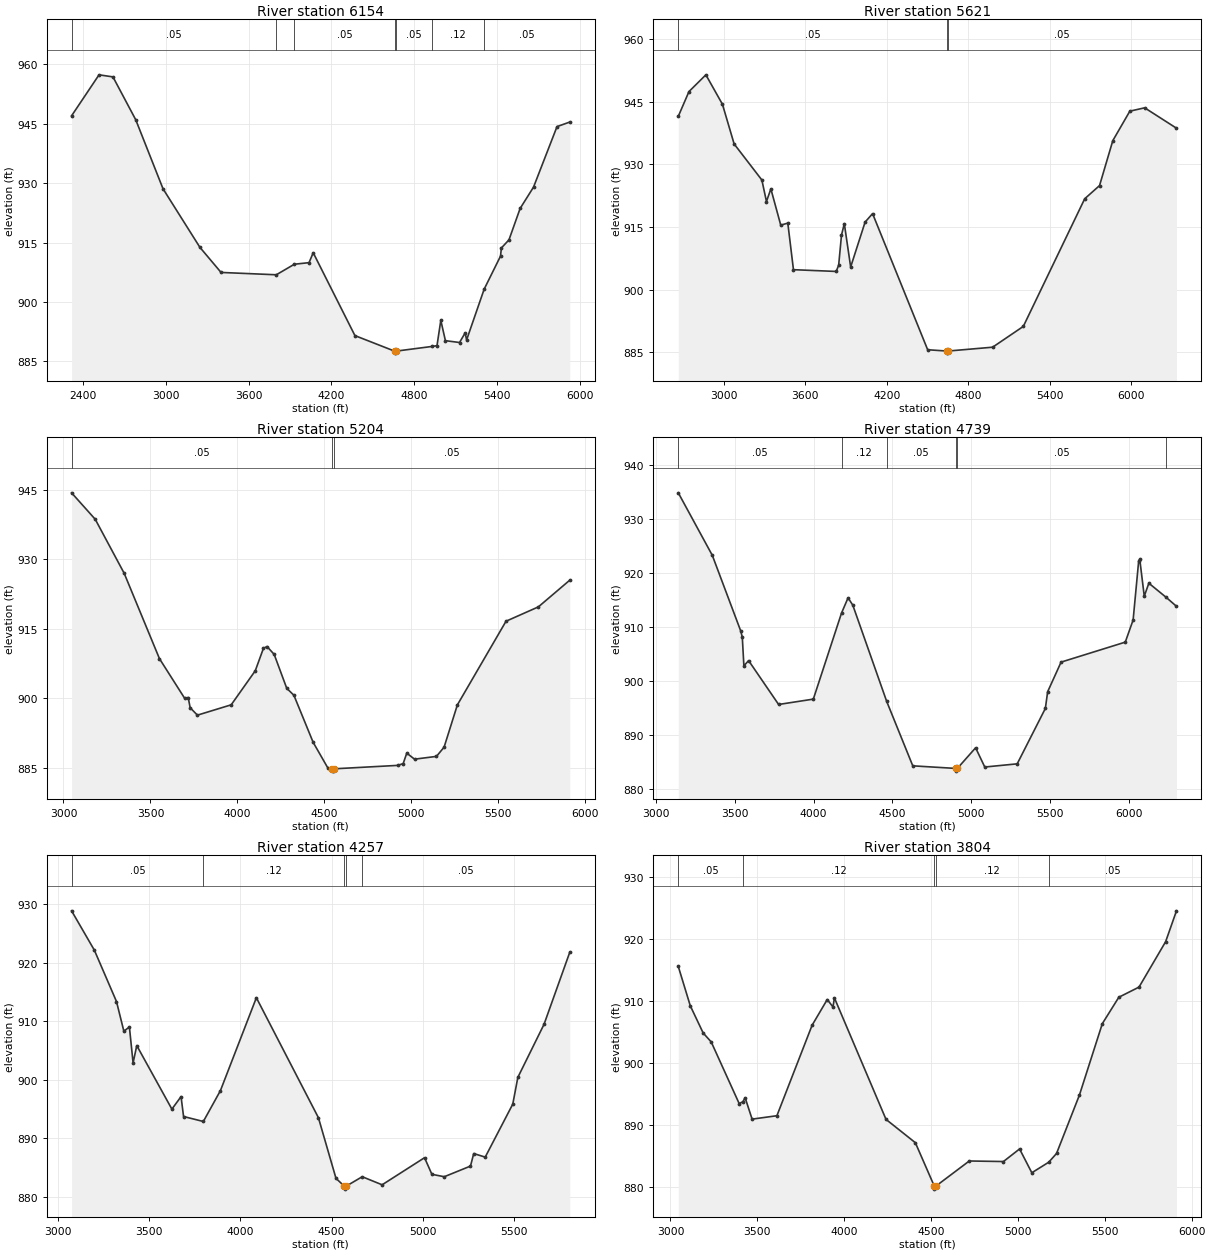
Type RM Length L Ch R = 1 ,6154    ,533,533,533
BEGIN DESCRIPTION:
Upper Denton 105 13.0
END DESCRIPTION:
XS GIS Cut Line= 3
      2236986.48      7229365.26        2234329.        7229710.
      2233418.72      7229912.15
#Sta/Elev= 30
  2316.1  946.96  2515.2   957.3  2616.1  956.78  2781.4  945.96  2979.1  928.56
  3246.6  913.79  3399.9  907.46  3800.6  906.87  3931.4  909.53  4037.9  909.93
  4068.1  912.43  4370.6  891.53  4658.2  887.61  4659.6  887.11  4667.9  887.61
  4930.8   888.8  4965.6  888.99  4993.3  895.38  5026.6  890.25    5129  889.79
    5170  892.22  5180.2  890.43  5307.7  903.25  5426.1  911.57  5432.6  913.64
  5487.5  915.68  5568.4   923.6  5665.7  928.99  5835.8  944.24  5928.3  945.39
#Mann= 7 ,-1 , 0
  2316.1     .05       0  3800.6     .12       0  3931.4     .05       0
  4658.2     .07       0  4667.9     .05       0  4930.8     .12       0
  5307.7     .05       0
Bank Sta=4658.2,4667.9
XS Rating Curve= 0 ,0
Exp/Cntr=0.3,0.1

Type RM Length L Ch R = 1 ,5621    ,417,417,417
BEGIN DESCRIPTION:
Upper Denton 105 12.0
END DESCRIPTION:
XS GIS Cut Line= 3
       2236574.3      7228564.69      2234330.19      7229209.02
       2233158.3      7229847.05
#Sta/Elev= 30
  2663.9  941.52  2742.5  947.45  2867.1  951.46  2988.9  944.42  3075.2  934.91
  3279.5  926.27  3313.3  921.12  3345.7  924.15  3418.5  915.47  3470.5  915.95
  3512.1   904.8    3827  904.38  3845.1  905.88  3865.9  913.08  3886.7  915.82
  3933.4  905.45  4039.8   916.2  4094.8  918.23  4500.5  885.63  4641.3  885.32
  4642.7  884.82  4651.1  885.32    4979  886.24    5205  891.22  5657.1  921.78
  5766.3  924.94  5864.2  935.71  5989.5  942.76  6098.7  943.56    6333  938.68
#Mann= 3 ,-1 , 0
  2663.9     .05       0  4641.3    .033       0  4651.1     .05       0
Bank Sta=4641.3,4651.1
XS Rating Curve= 0 ,0
Exp/Cntr=0.3,0.1

Type RM Length L Ch R = 1 ,5204    ,465,465,465
BEGIN DESCRIPTION:
Upper Denton 105 11.0
END DESCRIPTION:
XS GIS Cut Line= 3
        2236180.      7228343.57        2234279.        7228810.
      2233480.38      7229237.65
#Sta/Elev= 30
  3046.8  944.37  3182.8  938.66  3349.1  927.01  3551.8  908.59  3696.5  900.04
  3717.1  900.19  3728.4  897.99    3770  896.39  3964.2  898.62  4102.6  905.97
  4149.6  910.82  4170.2   911.2  4211.3   909.5  4283.4  902.19  4324.6  900.68
  4435.2  890.53  4518.3  885.08  4546.2  884.81  4547.6  884.31    4556  884.81
  4921.8  885.55  4952.7  885.94  4973.3  888.19    5018  886.89  5143.9  887.49
  5187.8  889.48  5264.2  898.61  5543.7  916.66  5729.8  919.76  5910.1  925.52
#Mann= 3 ,-1 , 0
  3046.8     .05       0  4546.2    .033       0    4556     .05       0
Bank Sta=4546.2,4556
XS Rating Curve= 0 ,0
Exp/Cntr=0.3,0.1

Type RM Length L Ch R = 1 ,4739    ,482,482,482
BEGIN DESCRIPTION:
Upper Denton 105 10.0
END DESCRIPTION:
XS GIS Cut Line= 3
      2236084.51      7228256.76        2234229.        7228360.
      2233193.92      7229150.84
#Sta/Elev= 30
    3142   934.9  3357.8  923.33  3538.1  909.33  3548.1   908.2  3558.2  902.87
  3588.2  903.84  3778.5  895.72  3998.8  896.71  4177.6  912.63  4219.2  915.46
  4249.2  914.11    4464  896.31  4629.8  884.36  4902.9  883.88  4904.3  883.38
  4912.7  883.88  5028.5   887.7  5086.6  884.14  5292.4  884.73  5471.1  894.99
  5485.6  898.08  5570.8  903.56  5978.1  907.26  6027.9  911.36  6063.3  922.34
  6070.1  922.57  6098.6  915.76  6127.7  918.17  6237.9  915.54    6303  913.89
#Mann= 6 ,-1 , 0
    3142     .05       0  4177.6     .12       0    4464     .05       0
  4902.9    .033       0  4912.7     .05       0  6237.9     .12       0
Bank Sta=4902.9,4912.7
XS Rating Curve= 0 ,0
Exp/Cntr=0.3,0.1

Type RM Length L Ch R = 1 ,4257    ,453,453,453
BEGIN DESCRIPTION:
Upper Denton 105 9.0
END DESCRIPTION:
XS GIS Cut Line= 3
      2236032.46        7228196.        2234129.        7227910.
      2233329.05      7228009.99
#Sta/Elev= 30
  3075.1  928.85  3199.9  922.13  3321.3  913.35  3361.7  908.28  3392.1     909
  3412.3  902.85  3432.5  905.82    3625  894.96  3675.2   897.1    3689   893.7
  3797.4  892.85    3891  898.12  4088.1     914  4428.2   893.5  4524.6  883.13
  4570.3  881.79  4571.7  881.29  4580.1  881.79  4668.4  883.41  4777.5  882.03
    5010  886.66  5050.3  883.82  5118.3  883.41  5261.9  885.23  5279.6  887.37
  5342.6  886.76  5493.7  895.82  5521.5  900.39  5665.1  909.46  5806.1  921.77
#Mann= 5 ,-1 , 0
  3075.1     .05       0  3797.4     .12       0  4570.3    .033       0
  4580.1     .12       0  4668.4     .05       0
Bank Sta=4570.3,4580.1
XS Rating Curve= 0 ,0
Exp/Cntr=0.3,0.1

Type RM Length L Ch R = 1 ,3804    ,482,482,482
BEGIN DESCRIPTION:
Upper Denton 105 8.0
END DESCRIPTION:
XS GIS Cut Line= 4
      2235867.48       7228013.7        2233979.        7227510.
      2233833.09      7227528.24      2233178.13      7227925.94
#Sta/Elev= 30
    3045  915.54  3114.1  909.19  3188.3   904.8  3234.4  903.37  3395.3  893.43
  3416.7  893.71  3429.8  894.36  3469.9  890.91  3612.7  891.46  3815.2  906.05
  3902.4   910.2  3935.5  909.01  3943.8  910.46  4240.8  890.87  4409.6  887.11
  4518.4  880.12  4519.8  879.62  4528.5  880.12  4720.1  884.16  4916.7  884.07
  5009.6   886.1  5080.1  882.26  5177.4  883.96  5222.4  885.37  5354.2   894.8
  5485.9  906.31  5580.9  910.57  5697.2  912.21  5850.3  919.53  5912.8  924.51
#Mann= 5 ,-1 , 0
    3045     .05       0  3416.7     .12       0  4518.4     .07       0
  4528.5     .12       0  5177.4     .05       0
Bank Sta=4518.4,4528.5
XS Rating Curve= 0 ,0
Exp/Cntr=0.3,0.1

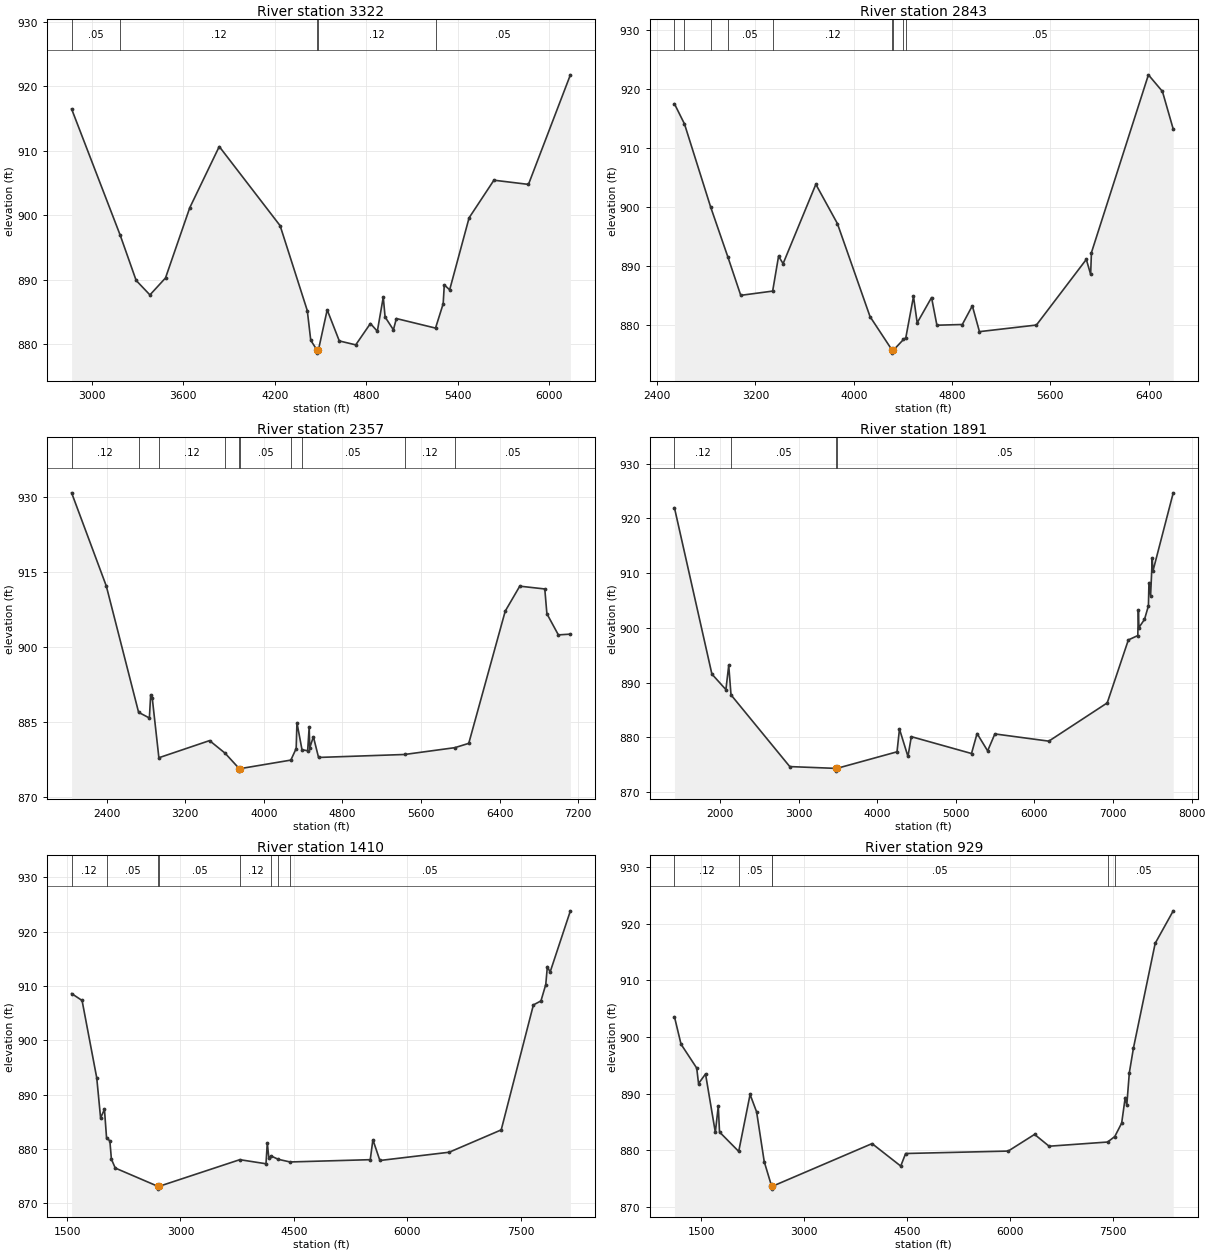
Type RM Length L Ch R = 1 ,3322    ,479,479,479
BEGIN DESCRIPTION:
Upper Denton 105 7.0
END DESCRIPTION:
XS GIS Cut Line= 3
      2235902.26        7227979.        2233979.        7227060.
       2233150.5      7227840.09
#Sta/Elev= 30
  2868.8  916.46  3187.9  896.86  3291.8  889.89  3382.2  887.64  3484.3  890.27
  3643.1  901.14  3836.6  910.64  4235.6  898.37  4413.7  885.21  4436.4  880.61
  4476.7  879.12  4478.1  878.62  4486.8  879.12  4544.2  885.32  4623.5  880.51
  4731.2   879.9  4827.5  883.21  4872.8  882.01  4911.7  887.29  4923.7  884.22
  4978.2  882.23  4997.6  883.98  5254.3   882.5  5304.4  886.27  5311.7  889.19
  5346.9  888.43  5474.3  899.59    5637  905.42  5863.5  904.77  6138.3  921.75
#Mann= 5 ,-1 , 0
  2868.8     .05       0  3187.9     .12       0  4476.7     .07       0
  4486.8     .12       0  5254.3     .05       0
Bank Sta=4476.7,4486.8
XS Rating Curve= 0 ,0
Exp/Cntr=0.3,0.1

Type RM Length L Ch R = 1 ,2843    ,486,486,486
BEGIN DESCRIPTION:
Upper Denton 105 6.0
END DESCRIPTION:
XS GIS Cut Line= 3
      2236032.49      7227788.04        2233879.        7226610.
      2232890.06      7227874.84
#Sta/Elev= 30
  2540.5  917.44  2622.1  914.03  2834.4     900  2975.7  891.47  3080.2  884.99
  3339.9  885.71    3388  891.62  3424.9  890.36  3691.4   903.8  3866.7  897.16
  4132.5  881.39  4312.4   875.7  4313.8   875.2  4322.5   875.7  4404.8  877.51
  4423.8  877.81  4486.3   884.8  4516.4  880.33  4633.3  884.62  4676.9  879.93
  4883.7  880.05  4965.3  883.22  5023.2  878.84  5487.1  879.96  5893.1  891.08
  5928.4  888.54  5934.7  892.22  6398.6  922.35  6512.6  919.54  6600.7  913.15
#Mann= 9 ,-1 , 0
  2540.5     .12       0  2622.1     .05       0  2834.4     .12       0
  2975.7     .05       0  3339.9     .12       0  4312.4    .033       0
  4322.5     .12       0  4404.8     .12       0  4423.8     .05       0
Bank Sta=4312.4,4322.5
XS Rating Curve= 0 ,0
Exp/Cntr=0.3,0.1

Type RM Length L Ch R = 1 ,2357    ,466,466,466
BEGIN DESCRIPTION:
Upper Denton 105 5.0
END DESCRIPTION:
XS GIS Cut Line= 3
      2236318.88      7227675.16        2233779.        7226160.
      2232690.44      7227978.97
#Sta/Elev= 30
  2042.6  930.74  2395.9  912.14  2724.6  886.95  2834.3  885.82  2847.5  890.47
    2863   889.9    2931  877.89  3446.9  881.31  3604.3  878.81  3749.1  875.72
  3750.5  875.22  3759.2  875.72  4274.3  877.42  4328.6  879.73  4336.4  884.88
  4387.9  879.48  4445.4  879.29    4461  884.02  4466.8  879.87  4503.8  882.08
  4556.3  877.95    5432  878.54  5943.6   879.9  6085.3  880.76  6456.8  907.15
  6604.6  912.12  6859.3  911.56  6880.7  906.62  6997.4   902.4  7119.9  902.55
#Mann= 10 ,-1 , 0
  2042.6     .12       0  2724.6     .05       0    2931     .12       0
  3604.3     .05       0  3749.1    .033       0  3759.2     .05       0
  4274.3     .12       0  4387.9     .05       0    5432     .12       0
  5943.6     .05       0
Bank Sta=3749.1,3759.2
XS Rating Curve= 0 ,0
Exp/Cntr=0.3,0.1

Type RM Length L Ch R = 1 ,1891    ,481,481,481
BEGIN DESCRIPTION:
Upper Denton 105 4.0
END DESCRIPTION:
XS GIS Cut Line= 3
       2237074.1       7226989.4        2233729.        7225710.
      2231865.76      7227753.31
#Sta/Elev= 30
    1419  921.94  1895.5  891.54  2073.7   888.7  2109.7  893.13  2138.6  887.74
  2886.4  874.63    3475   874.3  3476.5   873.8  3485.2   874.3    4251  877.33
  4282.2  881.49  4390.1  876.48    4433   880.1  5198.7  877.02  5269.6  880.67
  5404.1   877.5    5496   880.6  6182.4  879.28  6925.6  886.27  7194.5  897.78
  7314.8  898.58  7322.2   903.3    7329  900.04  7399.9  901.53  7449.9  904.01
  7456.7  908.25  7477.6  905.88  7499.2  912.73    7506  910.29  7765.7  924.67
#Mann= 4 ,-1 , 0
    1419     .12       0  2138.6     .05       0    3475    .033       0
  3485.2     .05       0
Bank Sta=3475,3485.2
XS Rating Curve= 0 ,0
Exp/Cntr=0.3,0.1

Type RM Length L Ch R = 1 ,1410    ,481,481,481
BEGIN DESCRIPTION:
Upper Denton 105 3.0
END DESCRIPTION:
XS GIS Cut Line= 3
      2237004.66      7225947.73        2233629.        7225260.
      2231605.43      7227675.09
#Sta/Elev= 30
  1560.2  908.63  1698.6  907.36  1892.6  893.12  1943.6  885.74  1994.6  887.32
  2022.6  882.02    2066  881.54  2086.5  878.15  2137.5  876.52  2703.7  873.14
  2705.2  872.64  2714.2  873.14  3784.4  878.06  4130.6  877.31    4148  881.12
  4168.4  878.39  4197.2  878.75  4292.1  878.13  4448.5  877.64  5509.4  878.06
  5544.5  881.73  5636.9  877.91  6552.8  879.43  7241.1  883.54  7666.7  906.54
  7766.7  907.28  7830.5   910.3  7851.3   913.6  7887.7  912.58    8156  923.86
#Mann= 8 ,-1 , 0
  1560.2     .12       0  2022.6     .05       0  2703.7    .033       0
  2714.2     .05       0  3784.4     .12       0  4197.2     .05       0
  4292.1     .12       0  4448.5     .05       0
Bank Sta=2703.7,2714.2
XS Rating Curve= 0 ,0
Exp/Cntr=0.3,0.1

Type RM Length L Ch R = 1 ,929     ,0,0,0
BEGIN DESCRIPTION:
Upper Denton 105 2.0
END DESCRIPTION:
XS GIS Cut Line= 4
      2237343.21      7225557.11        2233529.        7224810.
      2232456.05      7225669.96      2231623.34      7227491.51
#Sta/Elev= 30
  1108.5  903.58  1204.5  898.73  1432.7  894.51  1459.3  891.77  1561.2  893.47
  1703.8  883.15  1746.7  887.76    1765   883.2  2044.3  879.77  2210.1  889.84
    2305  886.76    2416  877.96    2524   873.6  2525.4   873.1  2534.5   873.6
  3986.4  881.15  4404.2  877.18  4475.5   879.4  5969.2  879.83  6353.6  882.78
  6565.1  880.69  7416.9  881.43  7521.5   882.4  7622.1  884.78  7673.6   889.3
  7696.6  887.96  7733.7   893.7  7794.2  898.09    8110  916.57  8373.1  922.32
#Mann= 6 ,-1 , 0
  1108.5     .12       0  2044.3     .05       0    2524    .033       0
  2534.5     .05       0  7416.9     .12       0  7521.5     .05       0
Bank Sta=2524,2534.5
XS Rating Curve= 0 ,0
Exp/Cntr=0.3,0.1

Chan Stop Cuts=-1
Use User Specified Reach Order=0
Composite Channel Slope=5