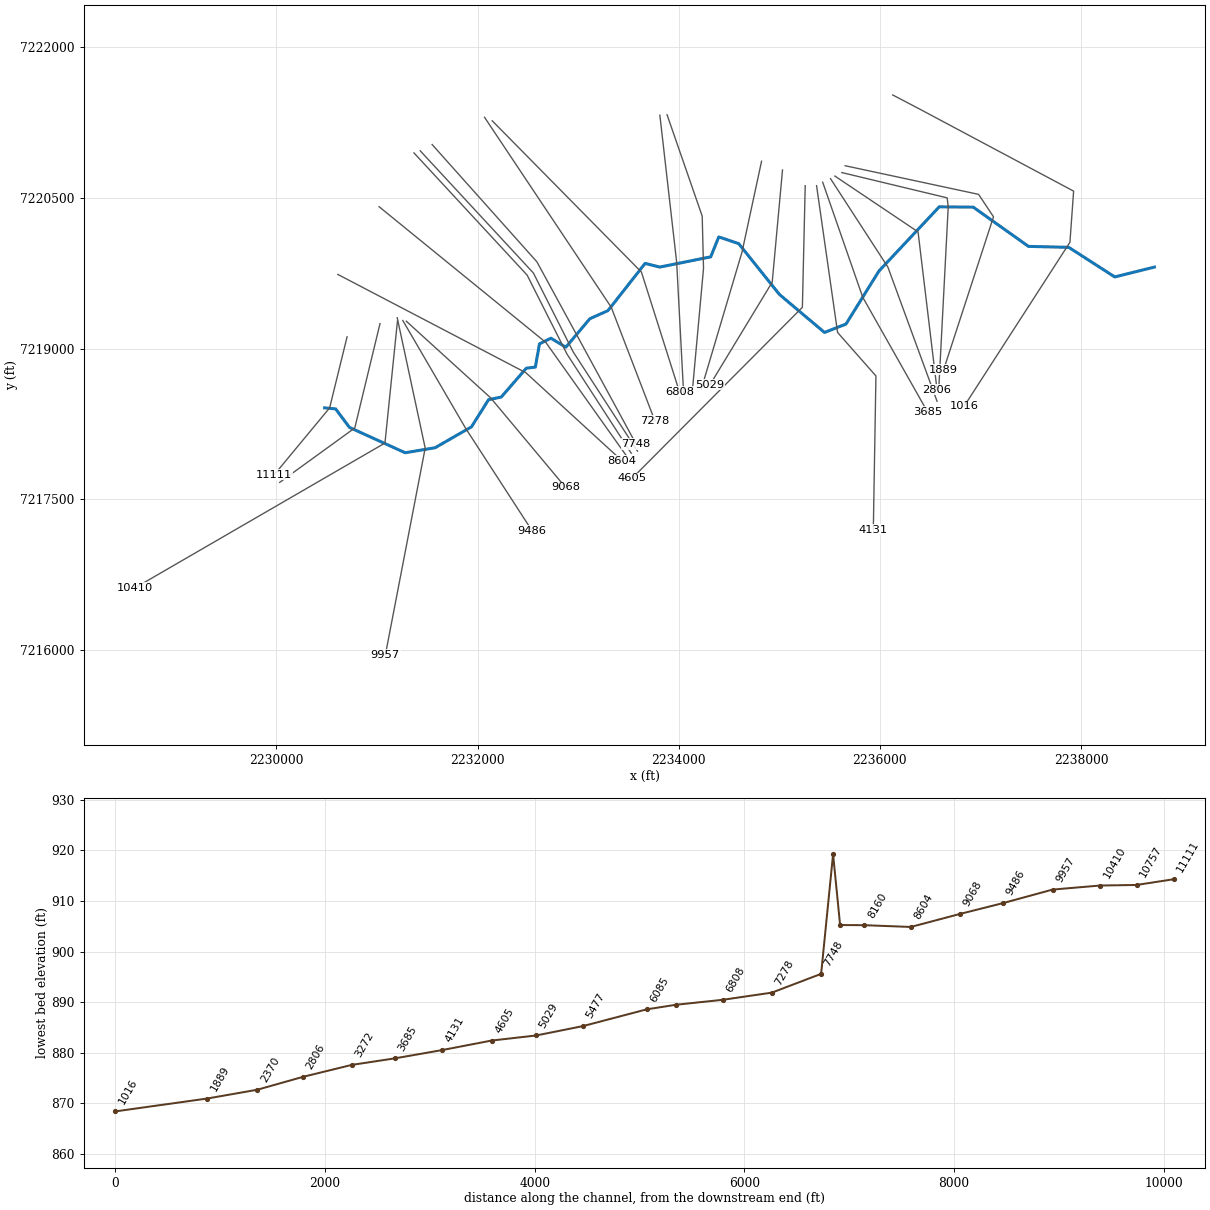
--- Upper Denton 108.prj (project) ---

Proj Title=Upper Denton 108 Base Level Engineering
Current Plan=p01
Default Exp/Contr=0.3,0.1
English Units
Geom File=g01
Flow File=f01
Plan File=p01
BEGIN DESCRIPTION:
Upper Denton 108
END DESCRIPTION:

--- Upper Denton 108.p01 (plan) ---

Plan Title=Multiple Run
Short Identifier=Multiple
Geom File=g01
Flow File=f01
Subcritical Flow
K Sum by GR= 0
Std Step Tol= 0.01
Critical Tol= 0.01
Num of Std Step Trials= 20
Max Error Tol= 0.3
Flow Tol Ratio= 0.001
Split Flow NTrial= 30
Split Flow Tol= 0.02
Split Flow Ratio= 0.02
Log Output Level= 0
Friction Slope Method= 1
Unsteady Friction Slope Method= 2
Unsteady Bridges Friction Slope Method= 1
Parabolic Critical Depth
Global Vel Dist=  1 , 1 , 1
Global Log Level= 0
CheckData=True
Encroach Param= -1, 0, 0, 0
BEGIN DESCRIPTION:
Multiple Run
END DESCRIPTION:

--- Upper Denton 108.f01 (steady flow) ---

Flow Title=Multiple
Number of Profiles=7
Profile Names=10-year,25-year,50-year,1pct_min,100-year,1pct_plu,500-year
River Rch & RM= Upper Denton 108,Reach-1,11111
     763    1081    1354     842    1680    3352    2595
River Rch & RM= Upper Denton 108,Reach-1,9486
     962    1369    1717    1068    2132    4254    3297
River Rch & RM= Upper Denton 108,Reach-1,4131
    1169    1675    2110    1318    2629    5247    4097
Boundary for River Rch & Prof#=Upper Denton 108,Reach-1,1
Up Type=0
Dn Type=3
Dn Slope=0.005
Boundary for River Rch & Prof#=Upper Denton 108,Reach-1,2
Up Type=0
Dn Type=3
Dn Slope=0.005
Boundary for River Rch & Prof#=Upper Denton 108,Reach-1,3
Up Type=0
Dn Type=3
Dn Slope=0.005
Boundary for River Rch & Prof#=Upper Denton 108,Reach-1,4
Up Type=0
Dn Type=3
Dn Slope=0.005
Boundary for River Rch & Prof#=Upper Denton 108,Reach-1,5
Up Type=0
Dn Type=3
Dn Slope=0.005
Boundary for River Rch & Prof#=Upper Denton 108,Reach-1,6
Up Type=0
Dn Type=3
Dn Slope=0.005
Boundary for River Rch & Prof#=Upper Denton 108,Reach-1,7
Up Type=0
Dn Type=3
Dn Slope=0.005

--- Upper Denton 108.g01 (geometry) ---

Geom Title=Existing Conditions

River Reach=Upper Denton 108,Reach-1
Reach XY= 30
      2230479.00      7218410.00      2230588.84      7218399.58
      2230726.33      7218215.42      2231280.50      7217963.47
      2231577.53      7218013.55      2231938.70      7218220.76
      2232108.46      7218490.53      2232235.43      7218517.79
      2232484.55      7218804.71      2232573.90      7218815.11
      2232615.37      7219046.57      2232729.08      7219102.70
      2232877.35      7219013.10      2233115.76      7219296.39
      2233295.71      7219376.63      2233665.27      7219846.62
      2233810.66      7219810.06      2234317.42      7219911.62
      2234397.63      7220109.93      2234596.05      7220043.51
      2235002.04      7219536.62      2235448.99      7219159.94
      2235662.37      7219243.29      2235989.70      7219769.97
      2236589.29      7220409.00      2236927.45      7220406.25
      2237476.72      7220015.82      2237877.45      7220006.25
      2238334.71      7219711.94      2238729.00      7219810.00

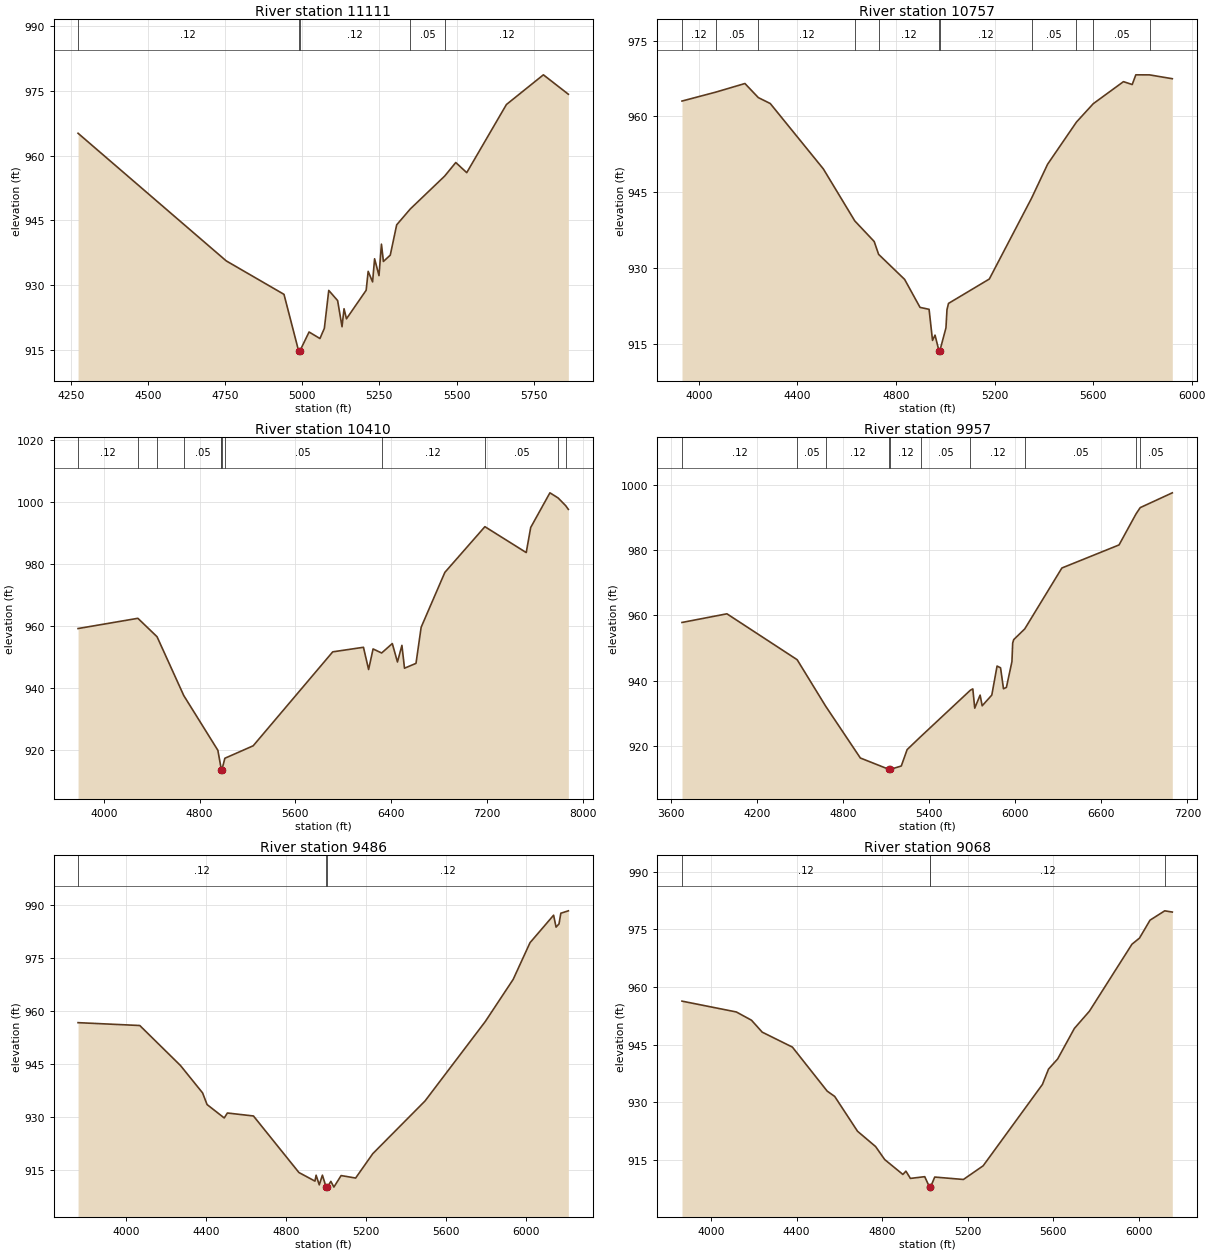
Type RM Length L Ch R = 1,11111,354,354,354
BEGIN DESCRIPTION:
Upper Denton 108 22.0
END DESCRIPTION:
XS GIS Cut Line= 3
      2230702.29      7219116.17      2230529.00      7218410.00
      2229979.37      7217746.37
#Sta/Elev= 30
  4273.6  965.17  4753.6  935.65  4940.9  927.90  4988.4  914.80  4988.7  914.30
  4992.4  914.80  5022.2  919.19  5057.4  917.68  5071.7  920.03  5086.0  928.81
  5114.7  926.46  5129.0  920.41  5135.5  924.57  5143.4  922.24  5207.2  928.85
  5213.7  933.22  5228.0  930.78  5234.5  936.13  5248.8  932.23  5256.7  939.51
  5263.1  935.51  5285.3  936.97  5306.1  943.98  5350.0  947.64  5461.7  955.27
  5497.6  958.40  5533.1  956.06  5661.7  971.82  5781.5  978.69  5862.4  974.20
#Mann=5,-1,0
  4273.6    0.12       0  4988.4    0.07       0  4992.4    0.12       0
  5350.0    0.05       0  5461.7    0.12       0
Bank Sta=4988.4,4992.4
Exp/Cntr=0.3,0.1

Type RM Length L Ch R = 1,10757,347,347,347
BEGIN DESCRIPTION:
Upper Denton 108 21.0
END DESCRIPTION:
XS GIS Cut Line= 3
      2231029.72      7219248.15      2230779.00      7218210.00
      2230032.75      7217669.19
#Sta/Elev= 30
  3931.9  963.05  4069.2  964.82  4187.2  966.52  4241.7  963.73  4290.1  962.56
  4505.5  949.62  4633.1  939.33  4711.8  935.26  4729.7  932.72  4835.3  927.76
  4897.8  922.22  4934.5  921.84  4948.5  915.69  4958.7  916.73  4974.4  913.67
  4974.6  913.17  4978.4  913.67  5003.0  918.17  5007.2  921.78  5013.4  923.01
  5178.9  927.83  5350.3  943.82  5415.5  950.55  5532.7  958.90  5600.8  962.53
  5723.3  966.89  5758.8  966.32  5773.5  968.24  5829.0  968.23  5921.5  967.47
#Mann=11,-1,0
  3931.9    0.12       0  4069.2    0.05       0  4241.7    0.12       0
  4633.1    0.05       0  4729.7    0.12       0  4974.4    0.07       0
  4978.4    0.12       0  5350.3    0.05       0  5532.7    0.12       0
  5600.8    0.05       0  5829.0    0.12       0
Bank Sta=4974.4,4978.4
Exp/Cntr=0.3,0.1

Type RM Length L Ch R = 1,10410,453,453,453
BEGIN DESCRIPTION:
Upper Denton 108 20.0
END DESCRIPTION:
XS GIS Cut Line= 3
      2231203.33      7219274.17      2231079.00      7218060.00
      2228590.47      7216617.90
#Sta/Elev= 30
  3783.9  959.06  4283.9  962.36  4443.9  956.42  4667.2  937.44  4952.2  919.77
  4980.3  913.69  4982.3  913.56  4982.6  913.06  4986.3  913.56  5010.5  917.21
  5247.1  921.23  5911.8  951.54  6168.6  953.01  6211.6  945.84  6248.9  952.48
  6320.6  951.17  6409.6  954.22  6452.7  948.27  6489.9  953.63  6511.5  946.26
  6607.6  947.83  6650.6  959.47  6848.6  977.17  7183.3  991.92  7528.6  983.57
  7565.9  991.66  7726.5 1002.84  7795.0 1001.19  7858.2  998.70  7880.6  997.50
#Mann=12,-1,0
  3783.9    0.12       0  4283.9    0.05       0  4443.9    0.12       0
  4667.2    0.05       0  4980.3    0.12       0  4982.3    0.07       0
  4986.3    0.12       0  5010.5    0.05       0  6320.6    0.12       0
  7183.3    0.05       0  7795.0    0.12       0  7858.2    0.05       0
Bank Sta=4982.3,4986.3
Exp/Cntr=0.3,0.1

Type RM Length L Ch R = 1,9957,471,471,471
BEGIN DESCRIPTION:
Upper Denton 108 19.0
END DESCRIPTION:
XS GIS Cut Line= 3
      2231200.89      7219306.44      2231479.00      7218010.00
      2231083.10      7215953.60
#Sta/Elev= 30
  3674.4  957.80  3987.8  960.45  4477.7  946.39  4676.0  932.19  4918.5  916.28
  5120.5  912.76  5120.8  912.26  5124.6  912.76  5204.0  913.83  5244.7  918.85
  5341.4  922.91  5686.0  937.05  5703.0  937.45  5716.4  931.55  5753.9  935.55
  5768.3  932.27  5835.4  935.56  5872.1  944.44  5896.5  943.91  5916.9  937.50
  5937.2  937.90  5975.9  945.82  5981.0  951.47  5988.1  952.54  6065.2  955.82
  6324.2  974.48  6723.0  981.55  6841.4  991.05  6870.8  992.98  7094.5  997.51
#Mann=10,-1,0
  3674.4    0.12       0  4477.7    0.05       0  4676.0    0.12       0
  5120.5    0.07       0  5124.6    0.12       0  5341.4    0.05       0
  5686.0    0.12       0  6065.2    0.05       0  6841.4    0.12       0
  6870.8    0.05       0
Bank Sta=5120.5,5124.6
Exp/Cntr=0.3,0.1

Type RM Length L Ch R = 1,9486,418,418,418
BEGIN DESCRIPTION:
Upper Denton 108 18.0
END DESCRIPTION:
XS GIS Cut Line= 3
      2231256.46      7219278.62      2231879.00      7218210.00
      2232541.18      7217188.36
#Sta/Elev= 30
  3758.6  956.73  4067.6  955.92  4271.1  944.61  4382.0  936.84  4404.3  933.55
  4490.3  929.75  4506.0  931.15  4636.6  930.31  4864.2  914.30  4944.5  911.87
  4950.2  913.54  4966.0  910.81  4981.7  913.55  5000.8  910.10  5001.2  909.60
  5005.0  910.10  5024.0  911.79  5039.2  910.19  5075.4  913.44  5148.0  912.74
  5233.7  919.63  5495.4  934.56  5797.4  957.08  5936.5  968.97  6020.9  979.37
  6138.9  987.15  6151.3  983.78  6166.0  984.68  6175.1  987.71  6212.8  988.39
#Mann=3,-1,0
  3758.6    0.12       0  5000.8    0.07       0  5005.0    0.12       0
Bank Sta=5000.8,5005
Exp/Cntr=0.3,0.1

Type RM Length L Ch R = 1,9068,464,464,464
BEGIN DESCRIPTION:
Upper Denton 108 17.0
END DESCRIPTION:
XS GIS Cut Line= 3
      2231291.14      7219271.73      2232129.00      7218510.00
      2232874.27      7217619.20
#Sta/Elev= 30
  3863.6  956.34  4117.8  953.52  4188.8  951.37  4238.8  948.27  4380.0  944.38
  4542.9  932.92  4578.0  931.54  4684.8  922.48  4769.3  918.50  4811.8  915.12
  4897.0  911.24  4911.2  912.10  4932.1  910.21  4999.2  910.66  5021.8  907.92
  5022.1  907.42  5026.0  907.92  5046.0  910.56  5180.1  909.93  5272.5  913.49
  5549.6  934.65  5578.3  938.65  5621.2  941.31  5699.3  949.24  5769.6  953.72
  5968.6  971.15  6003.8  972.74  6053.2  977.41  6122.0  979.84  6157.4  979.52
#Mann=4,-1,0
  3863.6    0.12       0  5021.8    0.07       0  5026.0    0.12       0
  6122.0    0.05       0
Bank Sta=5021.8,5026
Exp/Cntr=0.3,0.1

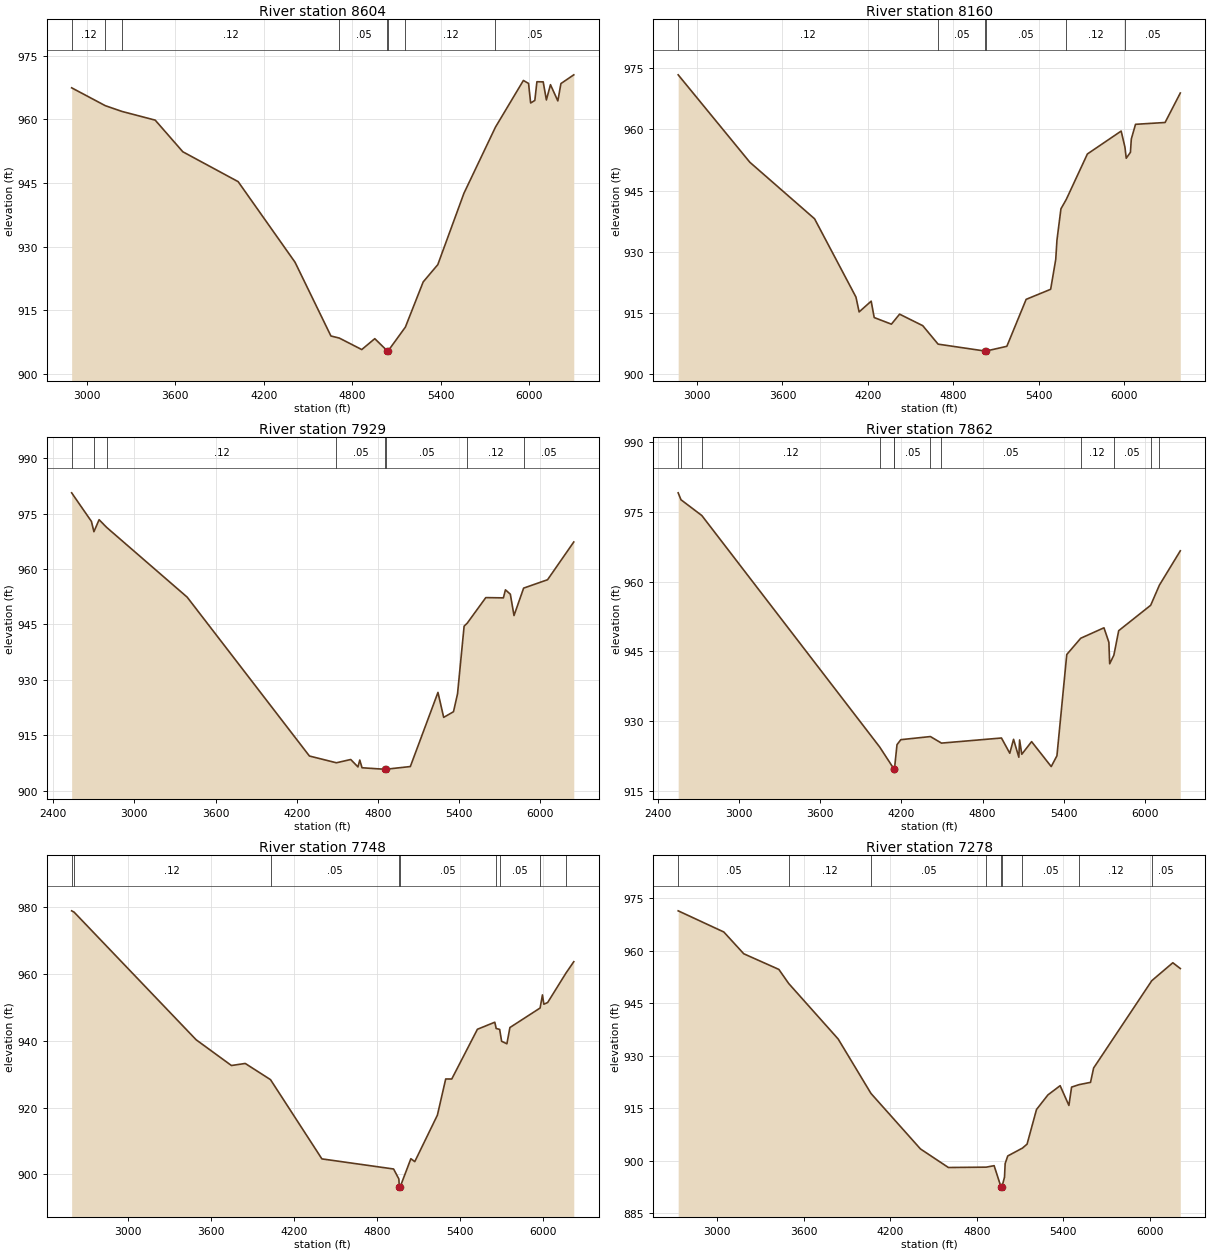
Type RM Length L Ch R = 1,8604,444,444,444
BEGIN DESCRIPTION:
Upper Denton 108 16.0
END DESCRIPTION:
XS GIS Cut Line= 3
      2230610.66      7219736.95      2232479.00      7218760.00
      2233435.84      7217883.88
#Sta/Elev= 30
  2896.3  967.41  3124.3  963.20  3237.6  961.84  3463.0  959.79  3650.4  952.33
  4025.6  945.29  4411.7  926.28  4654.8  908.91  4711.6  908.42  4864.0  905.71
  4952.3  908.28  5038.0  905.37  5038.3  904.87  5042.3  905.37  5159.8  911.00
  5280.6  921.65  5379.9  925.74  5556.9  942.54  5770.5  958.12  5960.2  969.14
  5995.3  968.44  6009.5  963.83  6037.8  964.43  6052.0  968.84  6094.6  968.81
  6116.2  964.55  6143.9  968.15  6193.9  964.32  6214.8  968.41  6302.0  970.47
#Mann=8,-1,0
  2896.3    0.12       0  3124.3    0.05       0  3237.6    0.12       0
  4711.6    0.05       0  5038.0   0.033       0  5042.3    0.05       0
  5159.8    0.12       0  5770.5    0.05       0
Bank Sta=5038,5042.3
Exp/Cntr=0.3,0.1

Type RM Length L Ch R = 1,8160,231,231,231
BEGIN DESCRIPTION:
Upper Denton 108 15.0
END DESCRIPTION:
XS GIS Cut Line= 3
      2231020.38      7220410.56      2232679.00      7219060.00
      2233484.64      7217925.85
#Sta/Elev= 30
  2866.7  973.36  3370.4  951.96  3825.7  938.11  4116.5  918.95  4138.8  915.31
  4223.6  917.94  4244.8  913.93  4365.8  912.31  4423.2  914.76  4586.2  911.94
  4694.0  907.42  5025.6  905.72  5026.0  905.22  5029.9  905.72  5177.4  906.89
  5313.1  918.39  5485.3  920.85  5521.0  928.15  5529.6  932.87  5557.6  940.55
  5595.1  942.85  5743.6  953.98  5981.0  959.59  6007.5  955.67  6016.7  952.94
  6046.2  954.39  6052.4  957.65  6081.9  961.24  6289.8  961.69  6396.8  968.91
#Mann=6,-1,0
  2866.7    0.12       0  4694.0    0.05       0  5025.6   0.033       0
  5029.9    0.05       0  5595.1    0.12       0  6007.5    0.05       0
Bank Sta=5025.6,5029.9
Exp/Cntr=0.3,0.1

Type RM Length L Ch R = 1,7929,67,67,67
BEGIN DESCRIPTION:
Upper Denton 108 14.5
END DESCRIPTION:
XS GIS Cut Line= 4
      2231367.57      7220945.30      2232492.56      7219730.03
      2232888.40      7218945.31      2233527.26      7217959.23
#Sta/Elev= 30
  2536.9  980.63  2683.0  972.89  2701.5  970.10  2739.7  973.35  2796.0  971.25
  3390.6  952.37  4293.8  909.34  4493.1  907.51  4598.8  908.40  4652.2  906.39
  4665.7  908.25  4682.4  906.16  4851.6  905.75  4852.0  905.25  4856.0  905.75
  5039.2  906.49  5243.4  926.57  5285.6  919.81  5358.1  921.34  5388.0  926.20
  5436.6  944.52  5459.6  945.33  5596.8  952.25  5726.7  952.18  5741.9  954.36
  5778.1  953.17  5805.2  947.39  5876.3  954.82  6053.1  957.09  6246.8  967.32
#Mann=8,-1,0
  2536.9    0.12       0  2701.5    0.05       0  2796.0    0.12       0
  4493.1    0.05       0  4851.6   0.033       0  4856.0    0.05       0
  5459.6    0.12       0  5876.3    0.05       0
Bank Sta=4851.6,4856
Exp/Cntr=0.3,0.1

Type RM Length L Ch R = 1,7862,114,114,114
BEGIN DESCRIPTION:
Upper Denton 108 14.4
END DESCRIPTION:
XS GIS Cut Line= 4
      2231429.87      7220966.07      2232554.86      7219750.80
      2232950.70      7218966.07      2233589.56      7217980.00
#Sta/Elev= 30
  2550.6  979.15  2571.3  977.66  2725.5  974.26  4039.2  924.45  4144.3  919.75
  4144.7  919.25  4148.7  919.75  4167.4  924.95  4195.8  926.02  4414.3  926.69
  4495.9  925.28  4939.3  926.38  5000.6  923.10  5028.5  926.10  5067.5  922.24
  5073.1  925.96  5089.2  922.88  5161.8  925.60  5306.8  920.23  5349.0  922.55
  5421.6  944.35  5524.7  947.85  5696.5  950.10  5732.8  946.98  5738.7  942.36
  5769.7  944.21  5805.3  949.48  6041.7  954.95  6105.8  959.27  6260.5  966.67
#Mann=12,-1,0
  2550.6    0.12       0  2571.3    0.05       0  2725.5    0.12       0
  4039.2    0.05       0  4144.3   0.033       0  4148.7    0.05       0
  4414.3    0.12       0  4495.9    0.05       0  5524.7    0.12       0
  5769.7    0.05       0  6041.7    0.12       0  6105.8    0.05       0
Bank Sta=4144.3,4148.7
Exp/Cntr=0.3,0.1

Type RM Length L Ch R = 1,7748,470,470,470
BEGIN DESCRIPTION:
Upper Denton 108 14.0
END DESCRIPTION:
XS GIS Cut Line= 4
      2231548.13      7221028.63      2232589.79      7219861.97
      2233013.40      7219084.20      2233574.94      7218051.23
#Sta/Elev= 30
  2594.4  978.82  2611.8  978.44  3493.3  940.26  3748.2  932.56  3847.7  933.18
  4030.2  928.34  4401.3  904.64  4918.9  901.62  4956.9  898.64  4960.4  896.10
  4960.8  895.60  4964.8  896.10  5043.6  904.70  5071.8  903.82  5235.2  917.73
  5295.1  928.54  5338.8  928.53  5524.0  943.40  5649.5  945.51  5659.6  943.64
  5684.7  943.36  5698.8  939.81  5736.9  939.06  5758.7  943.92  5976.7  949.76
  5993.6  953.68  6003.8  950.89  6031.4  951.41  6164.1  960.25  6219.8  963.61
#Mann=9,-1,0
  2594.4    0.05       0  2611.8    0.12       0  4030.2    0.05       0
  4960.4   0.033       0  4964.8    0.05       0  5659.6    0.12       0
  5684.7    0.05       0  5976.7    0.12       0  6164.1    0.05       0
Bank Sta=4960.4,4964.8
Exp/Cntr=0.3,0.1

Type RM Length L Ch R = 1,7278,470,470,470
BEGIN DESCRIPTION:
Upper Denton 108 13.0
END DESCRIPTION:
XS GIS Cut Line= 3
      2232068.95      7221299.48      2233329.00      7219410.00
      2233763.40      7218278.63
#Sta/Elev= 30
  2728.4  971.42  3045.1  965.37  3183.3  959.15  3426.7  954.68  3494.7  950.67
  3838.3  934.79  4065.8  919.23  4409.1  903.37  4602.8  898.07  4865.3  898.17
  4919.9  898.59  4968.6  892.39  4969.1  891.89  4973.3  892.39  4992.0  895.32
  4996.5  899.20  5014.5  901.37  5116.6  903.62  5148.5  904.75  5213.9  914.64
  5293.2  918.82  5377.9  921.45  5438.7  915.81  5457.3  921.05  5509.3  921.75
  5588.6  922.40  5610.1  926.50  6013.8  951.47  6159.5  956.58  6211.4  954.93
#Mann=9,-1,0
  2728.4    0.05       0  3494.7    0.12       0  4065.8    0.05       0
  4865.3    0.12       0  4968.6    0.07       0  4973.3    0.12       0
  5116.6    0.05       0  5509.3    0.12       0  6013.8    0.05       0
Bank Sta=4968.6,4973.3
Exp/Cntr=0.3,0.1

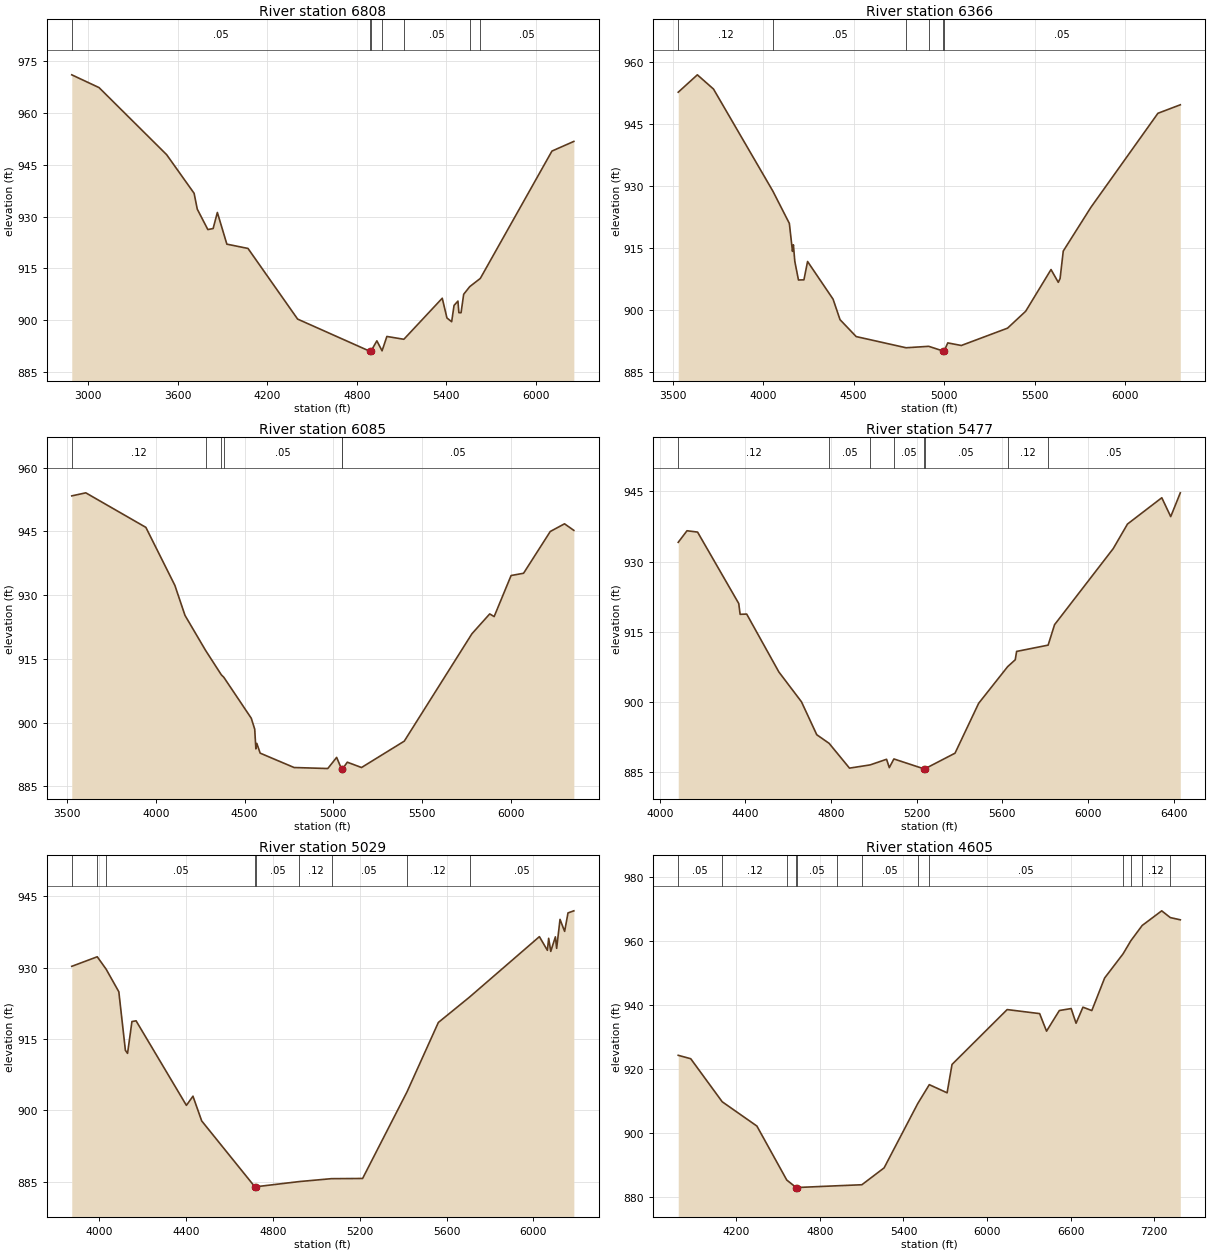
Type RM Length L Ch R = 1,6808,442,442,442
BEGIN DESCRIPTION:
Upper Denton 108 12.0
END DESCRIPTION:
XS GIS Cut Line= 3
      2232145.36      7221264.73      2233629.00      7219760.00
      2234006.46      7218570.29
#Sta/Elev= 30
  2891.7  971.10  3074.4  967.40  3527.0  947.96  3710.8  936.77  3732.0  932.18
  3802.7  926.27  3838.1  926.57  3866.4  931.22  3930.0  922.04  4071.5  920.80
  4403.8  900.33  4889.4  890.97  4889.9  890.47  4894.2  890.97  4934.2  894.03
  4969.1  891.14  5001.3  895.30  5115.0  894.48  5372.0  906.38  5403.5  900.65
  5435.0  899.57  5451.0  904.29  5477.0  905.55  5483.3  902.19  5497.9  902.17
  5515.5  907.52  5556.2  909.74  5626.9  912.12  6106.4  949.01  6253.0  951.81
#Mann=7,-1,0
  2891.7    0.05       0  4889.4    0.07       0  4894.2    0.05       0
  4969.1    0.12       0  5115.0    0.05       0  5556.2    0.12       0
  5626.9    0.05       0
Bank Sta=4889.4,4894.2
Exp/Cntr=0.3,0.1

Type RM Length L Ch R = 1,6366,281,281,281
BEGIN DESCRIPTION:
Upper Denton 108 11.0
END DESCRIPTION:
XS GIS Cut Line= 3
      2233812.01      7221320.26      2233979.00      7219860.00
      2234048.12      7218556.41
#Sta/Elev= 30
  3530.3  952.72  3636.0  956.93  3725.3  953.48  4053.2  928.77  4144.5  920.93
  4161.8  914.16  4166.8  915.74  4174.7  911.72  4194.9  907.22  4225.1  907.26
  4245.2  911.70  4386.1  902.58  4424.6  897.61  4513.9  893.51  4789.7  890.80
  4915.0  891.15  4995.1  890.00  4995.7  889.50  5000.0  890.00  5020.1  891.98
  5094.9  891.35  5350.6  895.55  5450.7  899.64  5590.9  909.75  5631.0  906.66
  5641.0  907.58  5658.5  914.23  5811.2  924.82  6181.7  947.61  6305.5  949.67
#Mann=6,-1,0
  3530.3    0.12       0  4053.2    0.05       0  4789.7    0.12       0
  4915.0    0.05       0  4995.1   0.033       0  5000.0    0.05       0
Bank Sta=4995.1,5000
Exp/Cntr=0.3,0.1

Type RM Length L Ch R = 1,6085,608,608,608
BEGIN DESCRIPTION:
Upper Denton 108 10.0
END DESCRIPTION:
XS GIS Cut Line= 4
      2233883.62      7221324.66      2234233.02      7220316.71
      2234246.04      7219795.88      2234133.19      7218557.70
#Sta/Elev= 30
  3525.5  953.33  3604.5  954.05  3943.2  945.93  4107.0  932.27  4164.0  925.22
  4280.0  916.99  4369.3  911.22  4382.6  910.68  4537.7  901.03  4557.1  898.46
  4563.6  893.83  4568.9  895.11  4587.9  892.82  4779.1  889.44  4969.1  889.20
  5019.1  891.82  5046.7  889.09  5047.3  888.59  5051.6  889.09  5079.2  890.69
  5159.4  889.44  5400.4  895.64  5781.9  920.90  5882.3  925.57  5907.2  924.94
  6002.8  934.60  6073.1  935.13  6223.7  944.96  6304.1  946.76  6356.6  945.22
#Mann=6,-1,0
  3525.5    0.12       0  4280.0    0.05       0  4369.3    0.12       0
  4382.6    0.05       0  5046.7   0.033       0  5051.6    0.05       0
Bank Sta=5046.7,5051.6
Exp/Cntr=0.3,0.1

Type RM Length L Ch R = 1,5477,448,448,448
BEGIN DESCRIPTION:
Upper Denton 108 9.0
END DESCRIPTION:
XS GIS Cut Line= 3
      2234823.11      7220862.65      2234629.00      7219960.00
      2234224.15      7218597.04
#Sta/Elev= 30
  4085.9  934.13  4126.8  936.60  4176.2  936.32  4368.5  921.07  4375.0  918.76
  4405.7  918.81  4555.7  906.47  4661.4  900.09  4733.0  893.05  4790.7  891.21
  4885.8  885.92  4982.4  886.61  5059.0  887.81  5071.8  886.03  5093.2  887.88
  5232.9  885.78  5233.6  885.28  5238.0  885.78  5378.7  889.11  5489.1  899.76
  5624.6  907.59  5660.0  909.06  5666.4  910.84  5813.6  912.18  5843.7  916.55
  6117.8  932.80  6184.2  938.03  6344.5  943.65  6386.2  939.62  6431.0  944.70
#Mann=8,-1,0
  4085.9    0.12       0  4790.7    0.05       0  4982.4    0.12       0
  5093.2    0.05       0  5232.9    0.07       0  5238.0    0.05       0
  5624.6    0.12       0  5813.6    0.05       0
Bank Sta=5232.9,5238
Exp/Cntr=0.3,0.1

Type RM Length L Ch R = 1,5029,424,424,424
BEGIN DESCRIPTION:
Upper Denton 108 8.0
END DESCRIPTION:
XS GIS Cut Line= 3
      2235031.46      7220775.93      2234929.00      7219660.00
      2234310.99      7218640.51
#Sta/Elev= 30
  3873.5  930.26  3990.9  932.27  4032.0  929.65  4090.3  924.91  4120.5  912.61
  4130.5  911.96  4150.6  918.65  4169.7  918.81  4401.6  901.03  4431.8  902.96
  4471.9  897.77  4716.7  883.92  4717.4  883.42  4721.9  883.92  4921.8  885.01
  5070.0  885.62  5213.2  885.66  5417.9  903.88  5562.2  918.46  5705.7  923.79
  6027.6  936.50  6064.4  933.63  6070.3  936.16  6079.9  933.40  6101.3  936.46
  6107.1  934.04  6122.6  940.13  6143.9  937.61  6159.4  941.49  6186.3  941.93
#Mann=9,-1,0
  3873.5    0.05       0  3990.9    0.12       0  4032.0    0.05       0
  4716.7    0.07       0  4721.9    0.05       0  4921.8    0.12       0
  5070.0    0.05       0  5417.9    0.12       0  5705.7    0.05       0
Bank Sta=4716.7,4721.9
Exp/Cntr=0.3,0.1

Type RM Length L Ch R = 1,4605,474,474,474
BEGIN DESCRIPTION:
Upper Denton 108 7.0
END DESCRIPTION:
XS GIS Cut Line= 3
      2235257.15      7220619.65      2235229.00      7219410.00
      2233538.42      7217711.67
#Sta/Elev= 30
  3782.1  924.25  3871.8  923.19  4097.9  909.73  4347.1  902.14  4561.8  885.25
  4629.4  882.92  4630.1  882.42  4634.6  882.92  4919.2  883.46  5101.1  883.79
  5260.8  889.06  5502.1  909.14  5585.4  915.08  5713.3  912.53  5748.7  921.40
  6144.7  938.55  6378.0  937.29  6427.5  931.80  6519.4  938.25  6604.3  938.87
  6639.6  934.28  6689.1  939.30  6752.8  938.24  6844.7  948.41  6977.5  955.99
  7033.4  960.09  7114.5  964.84  7254.8  969.42  7316.4  967.31  7388.4  966.61
#Mann=13,-1,0
  3782.1    0.05       0  4097.9    0.12       0  4561.8    0.05       0
  4629.4    0.07       0  4634.6    0.05       0  4919.2    0.12       0
  5101.1    0.05       0  5502.1    0.12       0  5585.4    0.05       0
  6977.5    0.12       0  7033.4    0.05       0  7114.5    0.12       0
  7316.4    0.05       0
Bank Sta=4629.4,4634.6
Exp/Cntr=0.3,0.1

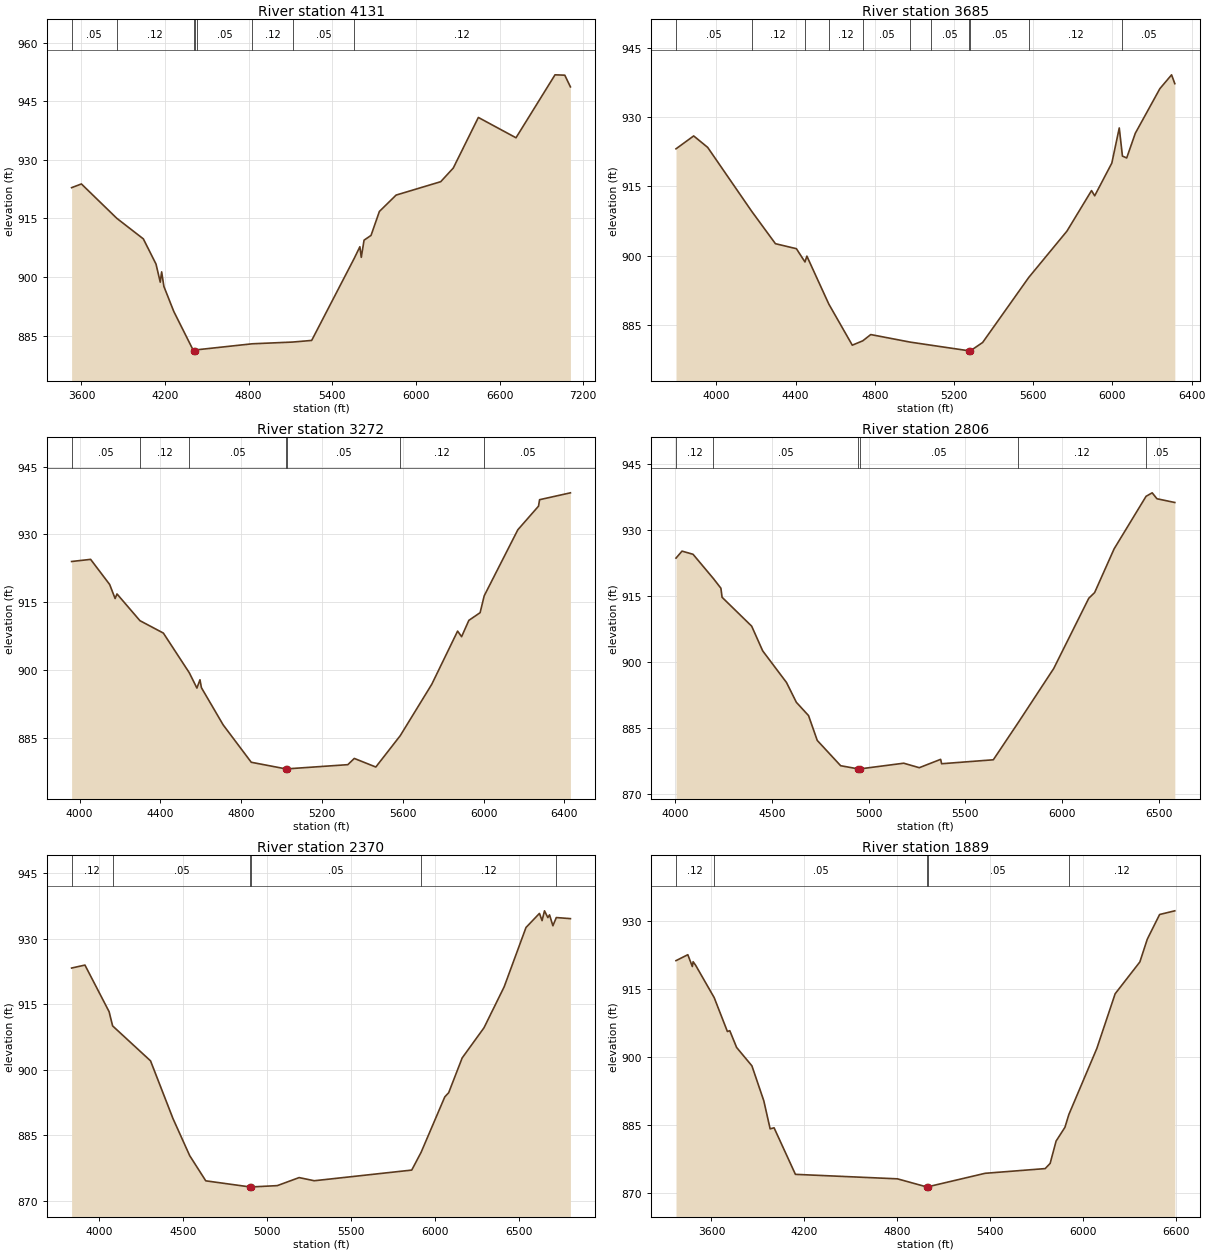
Type RM Length L Ch R = 1,4131,446,446,446
BEGIN DESCRIPTION:
Upper Denton 108 6.0
END DESCRIPTION:
XS GIS Cut Line= 4
      2235370.00      7220619.61      2235579.00      7219160.00
      2235960.27      7218727.28      2235934.23      7217199.53
#Sta/Elev= 30
  3529.5  922.88  3599.8  923.83  3854.0  915.03  4044.3  909.77  4135.2  903.32
  4165.5  898.69  4175.6  901.33  4191.7  897.60  4262.4  891.22  4405.5  881.03
  4406.6  880.53  4411.8  881.03  4427.1  881.38  4825.9  882.92  5114.5  883.36
  5252.1  883.78  5557.4  904.78  5598.0  907.76  5608.0  905.05  5628.0  909.44
  5678.0  910.66  5738.0  916.79  5858.0  920.98  6178.1  924.41  6268.1  927.90
  6448.1  940.85  6718.2  935.65  6998.2  951.76  7068.2  951.67  7108.7  948.68
#Mann=8,-1,0
  3529.5    0.05       0  3854.0    0.12       0  4405.5    0.07       0
  4411.8    0.12       0  4427.1    0.05       0  4825.9    0.12       0
  5114.5    0.05       0  5557.4    0.12       0
Bank Sta=4405.5,4411.8
Exp/Cntr=0.3,0.1

Type RM Length L Ch R = 1,3685,413,413,413
BEGIN DESCRIPTION:
Upper Denton 108 5.0
END DESCRIPTION:
XS GIS Cut Line= 3
      2235430.77      7220654.32      2235829.00      7219510.00
      2236472.44      7218371.35
#Sta/Elev= 30
  3795.6  923.14  3884.9  925.93  3955.6  923.45  4177.5  909.64  4297.8  902.60
  4403.7  901.52  4447.0  898.65  4456.6  899.91  4567.3  889.54  4686.0  880.63
  4738.8  881.57  4779.3  882.93  4977.6  881.30  5081.3  880.64  5276.2  879.41
  5277.2  878.91  5282.5  879.41  5344.3  881.21  5577.0  895.28  5770.3  905.33
  5894.4  914.10  5910.3  912.97  5996.9  920.05  6034.5  927.66  6050.5  921.57
  6072.0  921.16  6115.3  926.49  6239.5  936.16  6298.7  939.16  6315.1  937.25
#Mann=11,-1,0
  3795.6    0.05       0  4177.5    0.12       0  4447.0    0.05       0
  4567.3    0.12       0  4738.8    0.05       0  4977.6    0.12       0
  5081.3    0.05       0  5276.2    0.07       0  5282.5    0.05       0
  5577.0    0.12       0  6050.5    0.05       0
Bank Sta=5276.2,5282.5
Exp/Cntr=0.3,0.1

Type RM Length L Ch R = 1,3272,466,466,466
BEGIN DESCRIPTION:
Upper Denton 108 4.0
END DESCRIPTION:
XS GIS Cut Line= 3
      2235508.91      7220689.05      2236079.00      7219810.00
      2236567.90      7218475.57
#Sta/Elev= 30
  3960.7  924.01  4054.9  924.48  4149.1  918.92  4176.1  915.81  4185.3  916.83
  4299.0  910.91  4414.8  908.17  4543.4  899.37  4580.9  895.99  4596.1  897.83
  4603.2  896.08  4710.8  887.85  4849.9  879.57  5020.5  878.11  5021.5  877.61
  5026.9  878.11  5327.9  879.04  5359.9  880.42  5466.4  878.52  5587.2  885.45
  5743.3  896.83  5871.2  908.60  5891.0  907.37  5926.9  910.98  5982.6  912.68
  6002.9  916.42  6169.3  931.03  6271.7  936.26  6277.0  937.69  6429.6  939.21
#Mann=7,-1,0
  3960.7    0.05       0  4299.0    0.12       0  4543.4    0.05       0
  5020.5   0.033       0  5026.9    0.05       0  5587.2    0.12       0
  6002.9    0.05       0
Bank Sta=5020.5,5026.9
Exp/Cntr=0.3,0.1

Type RM Length L Ch R = 1,2806,436,436,436
BEGIN DESCRIPTION:
Upper Denton 108 3.0
END DESCRIPTION:
XS GIS Cut Line= 3
      2235552.31      7220715.11      2236379.00      7220160.00
      2236567.91      7218588.38
#Sta/Elev= 30
  4004.2  923.70  4035.3  925.29  4092.3  924.57  4197.7  919.04  4236.3  916.85
  4242.4  914.79  4395.4  908.22  4452.4  902.60  4575.4  895.41  4626.4  890.90
  4689.4  887.88  4734.4  882.23  4855.4  876.48  4947.2  875.75  4948.2  875.25
  4953.6  875.75  5181.3  877.05  5261.8  876.03  5372.3  877.93  5377.3  876.93
  5644.6  877.83  5774.3  886.35  5956.8  898.59  6138.1  914.57  6168.3  915.86
  6269.0  925.80  6434.3  937.76  6465.9  938.55  6490.6  937.20  6582.9  936.35
#Mann=6,-1,0
  4004.2    0.12       0  4197.7    0.05       0  4947.2   0.033       0
  4953.6    0.05       0  5774.3    0.12       0  6434.3    0.05       0
Bank Sta=4947.2,4953.6
Exp/Cntr=0.3,0.1

Type RM Length L Ch R = 1,2370,481,481,481
BEGIN DESCRIPTION:
Upper Denton 108 2.0
END DESCRIPTION:
XS GIS Cut Line= 4
      2235621.74      7220749.84      2236668.26      7220498.46
      2236679.00      7220410.00      2236585.27      7218605.72
#Sta/Elev= 30
  3834.7  923.32  3914.2  924.00  4058.1  913.33  4079.1  910.07  4305.0  902.07
  4438.7  888.86  4538.4  880.36  4634.1  874.60  4898.2  873.20  4899.3  872.70
  4904.7  873.20  5060.2  873.50  5190.3  875.34  5280.5  874.62  5861.3  877.06
  5917.0  881.12  6058.4  893.83  6081.5  894.78  6161.7  902.73  6291.8  909.64
  6412.0  919.02  6542.2  932.61  6622.3  935.83  6637.9  934.18  6652.3  936.42
  6672.3  934.87  6682.4  935.49  6702.4  933.00  6722.7  934.88  6806.8  934.63
#Mann=6,-1,0
  3834.7    0.12       0  4079.1    0.05       0  4898.2   0.033       0
  4904.7    0.05       0  5917.0    0.12       0  6722.7    0.05       0
Bank Sta=4898.2,4904.7
Exp/Cntr=0.3,0.1

Type RM Length L Ch R = 1,1889,873,873,873
BEGIN DESCRIPTION:
Upper Denton 108 1.0
END DESCRIPTION:
XS GIS Cut Line= 4
      2235654.40      7220817.90      2236980.76      7220533.18
      2237129.00      7220310.00      2236633.78      7218790.88
#Sta/Elev= 30
  3371.2  921.35  3447.5  922.66  3476.7  920.05  3481.8  921.11  3498.6  920.30
  3617.9  913.19  3703.2  905.72  3718.5  905.90  3762.8  902.20  3861.6  898.14
  3938.4  890.43  3979.3  884.25  4004.7  884.48  4142.6  874.21  4801.8  873.22
  4989.4  871.45  4990.5  870.95  4995.9  871.45  5367.9  874.44  5756.1  875.48
  5788.0  876.62  5826.6  881.55  5883.7  884.59  5908.7  887.39  6089.6  901.97
  6208.1  914.05  6367.6  921.06  6415.6  926.08  6495.3  931.53  6593.5  932.34
#Mann=5,-1,0
  3371.2    0.12       0  3617.9    0.05       0  4989.4   0.033       0
  4995.9    0.05       0  5908.7    0.12       0
Bank Sta=4989.4,4995.9
Exp/Cntr=0.3,0.1

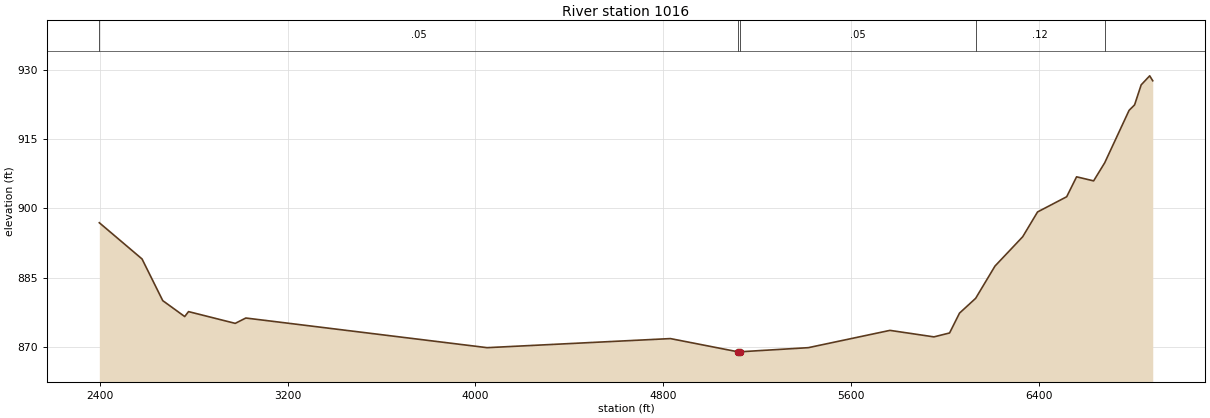
Type RM Length L Ch R = 1,1016,0,0,0
BEGIN DESCRIPTION:
Upper Denton 108 0.5
END DESCRIPTION:
XS GIS Cut Line= 5
      2236127.07      7221521.65      2236393.04      7221382.34
      2237925.59      7220565.40      2237888.94      7220056.69
      2236836.40      7218424.98
#Sta/Elev= 30
  2397.4  896.91  2579.3  889.06  2667.6  880.02  2761.2  876.57  2777.5  877.64
  2976.4  875.09  3021.7  876.25  4049.9  869.82  4830.8  871.79  5118.8  868.92
  5119.9  868.42  5125.5  868.92  5418.5  869.82  5766.3  873.57  5953.8  872.16
  6020.4  873.01  6062.7  877.31  6131.5  880.52  6213.8  887.51  6331.9  893.87
  6395.3  899.25  6519.4  902.55  6561.6  906.87  6634.2  905.99  6681.4  909.91
  6785.4  921.29  6808.7  922.47  6836.8  926.81  6873.1  928.77  6886.1  927.70
#Mann=5,-1,0
  2397.4    0.05       0  5118.8   0.033       0  5125.5    0.05       0
  6131.5    0.12       0  6681.4    0.05       0
Bank Sta=5118.8,5125.5
Exp/Cntr=0.3,0.1

Chan Stop Cuts=-1