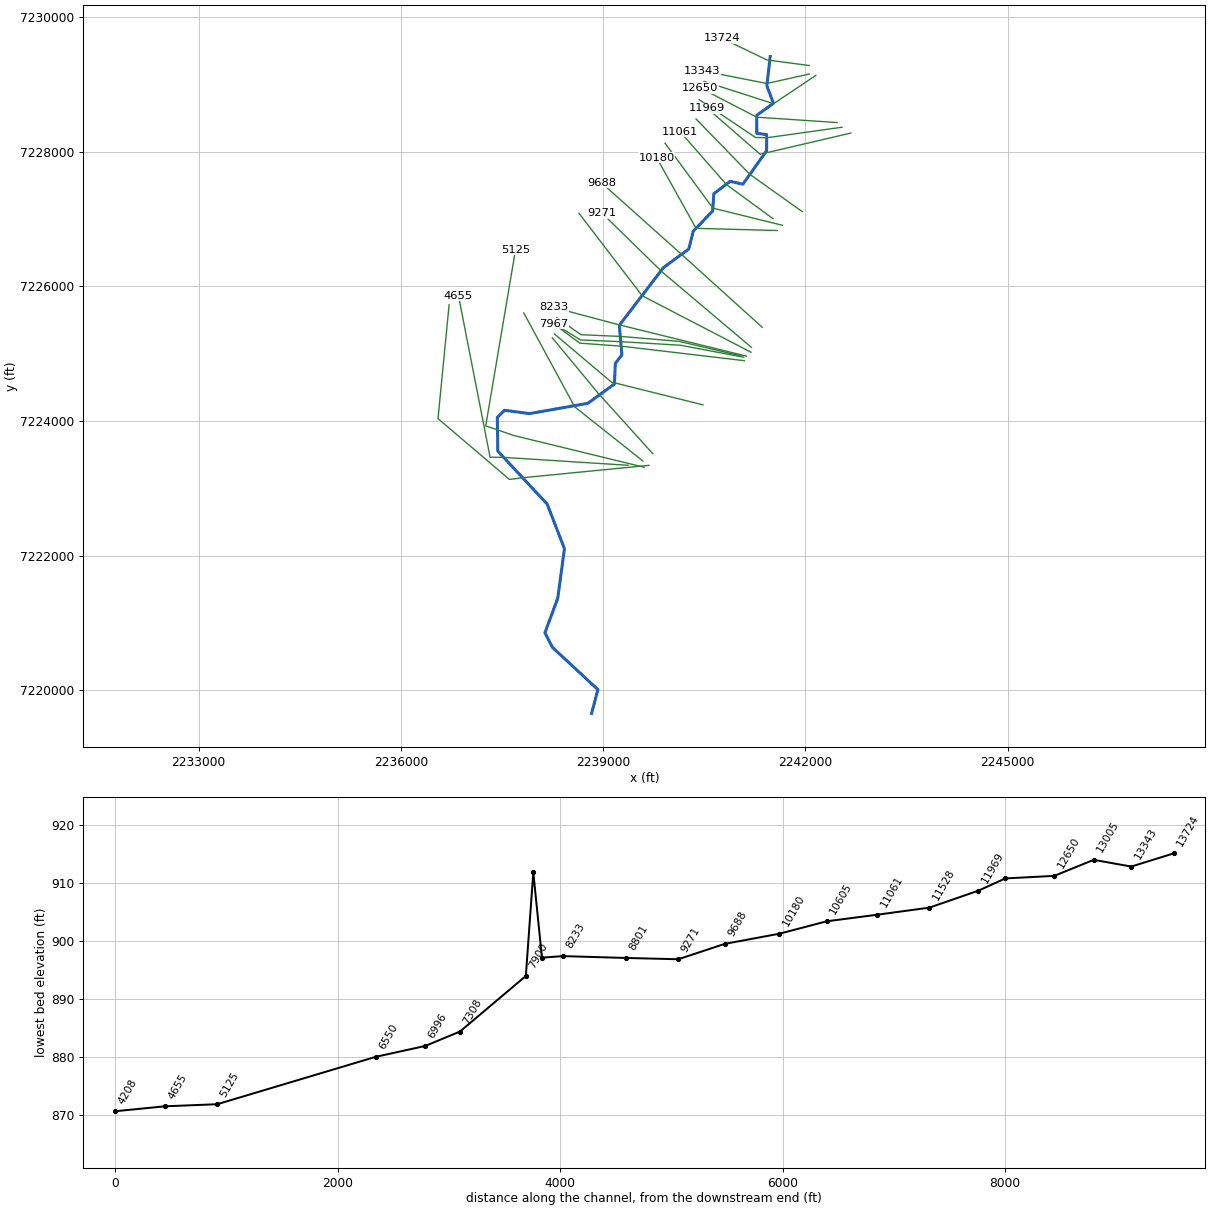
--- Upper Denton 110.prj (project) ---

Proj Title=Upper Denton 110 Base Level Engineering
Current Plan=p01
Default Exp/Contr=0.3,0.1
English Units
Geom File=g01
Flow File=f01
Plan File=p01
Y Axis Title=Elevation
X Axis Title(PF)=Main Channel Distance
X Axis Title(XS)=Station
BEGIN DESCRIPTION:
Upper Denton 110
END DESCRIPTION:
DSS Export Rating Curves= 0
DSS Export Rating Curve Sorted= 0
DSS Export Volume Flow Curves= 0
DXF OffsetX= 0
DXF OffsetY= 0
DXF ScaleX= 1
DXF ScaleY= 10

--- Upper Denton 110.p01 (plan) ---

Plan Title=Multiple Run
Short Identifier=Multiple
Geom File=g01
Flow File=f01
Subcritical Flow
K Sum by GR= 0
Std Step Tol= 0.01
Critical Tol= 0.01
Num of Std Step Trials= 20
Max Error Tol= 0.3
Flow Tol Ratio= 0.001
Split Flow NTrial= 30
Split Flow Tol= 0.02
Split Flow Ratio= 0.02
Log Output Level= 0
Friction Slope Method= 1
Unsteady Friction Slope Method= 2
Unsteady Bridges Friction Slope Method= 1
Parabolic Critical Depth
Global Vel Dist=  1 , 1 , 1
Global Log Level= 0
CheckData=True
Encroach Param= -1, 0, 0, 0
BEGIN DESCRIPTION:
Multiple Run
END DESCRIPTION:

--- Upper Denton 110.f01 (steady flow) ---

Flow Title=Multiple
Number of Profiles=7
Profile Names=10-year,25-year,50-year,1pct_min,100-year,1pct_plu,500-year
River Rch & RM= Upper Denton 110,Reach-1,13724
     637     884    1090     667    1331    2656    1993
River Rch & RM= Upper Denton 110,Reach-1,11061
     812    1137    1410     868    1731    3454    2618
River Rch & RM= Upper Denton 110,Reach-1,4208
    1174    1677    2109    1314    2621    5230    4064
Boundary for River Rch & Prof#=Upper Denton 110,Reach-1,1
Up Type=0
Dn Type=3
Dn Slope=0.005
Boundary for River Rch & Prof#=Upper Denton 110,Reach-1,2
Up Type=0
Dn Type=3
Dn Slope=0.005
Boundary for River Rch & Prof#=Upper Denton 110,Reach-1,3
Up Type=0
Dn Type=3
Dn Slope=0.005
Boundary for River Rch & Prof#=Upper Denton 110,Reach-1,4
Up Type=0
Dn Type=3
Dn Slope=0.005
Boundary for River Rch & Prof#=Upper Denton 110,Reach-1,5
Up Type=0
Dn Type=3
Dn Slope=0.005
Boundary for River Rch & Prof#=Upper Denton 110,Reach-1,6
Up Type=0
Dn Type=3
Dn Slope=0.005
Boundary for River Rch & Prof#=Upper Denton 110,Reach-1,7
Up Type=0
Dn Type=3
Dn Slope=0.005

--- Upper Denton 110.g01 (geometry) ---

Geom Title=Existing Conditions

River Reach=Upper Denton 110,Reach-1
Reach XY= 30
      2241479.00      7229410.00      2241428.70      7228978.38
      2241527.04      7228715.65      2241278.80      7228537.36
      2241280.71      7228270.80      2241426.08      7228252.08
      2241425.55      7228011.25      2241073.53      7227515.11
      2240884.63      7227558.27      2240642.23      7227373.67
      2240625.77      7227118.01      2240336.75      7226816.45
      2240271.15      7226553.81      2239895.49      7226277.05
      2239240.10      7225420.06      2239278.98      7224982.76
      2239181.23      7224854.10      2239168.68      7224549.83
      2238773.07      7224262.25      2237908.97      7224110.07
      2237539.43      7224158.97      2237431.16      7224054.57
      2237438.31      7223553.34      2238171.12      7222766.17
      2238426.65      7222104.48      2238327.62      7221369.66
      2238137.02      7220856.69      2238248.78      7220639.91
      2238923.55      7220012.46      2238829.00      7219660.00

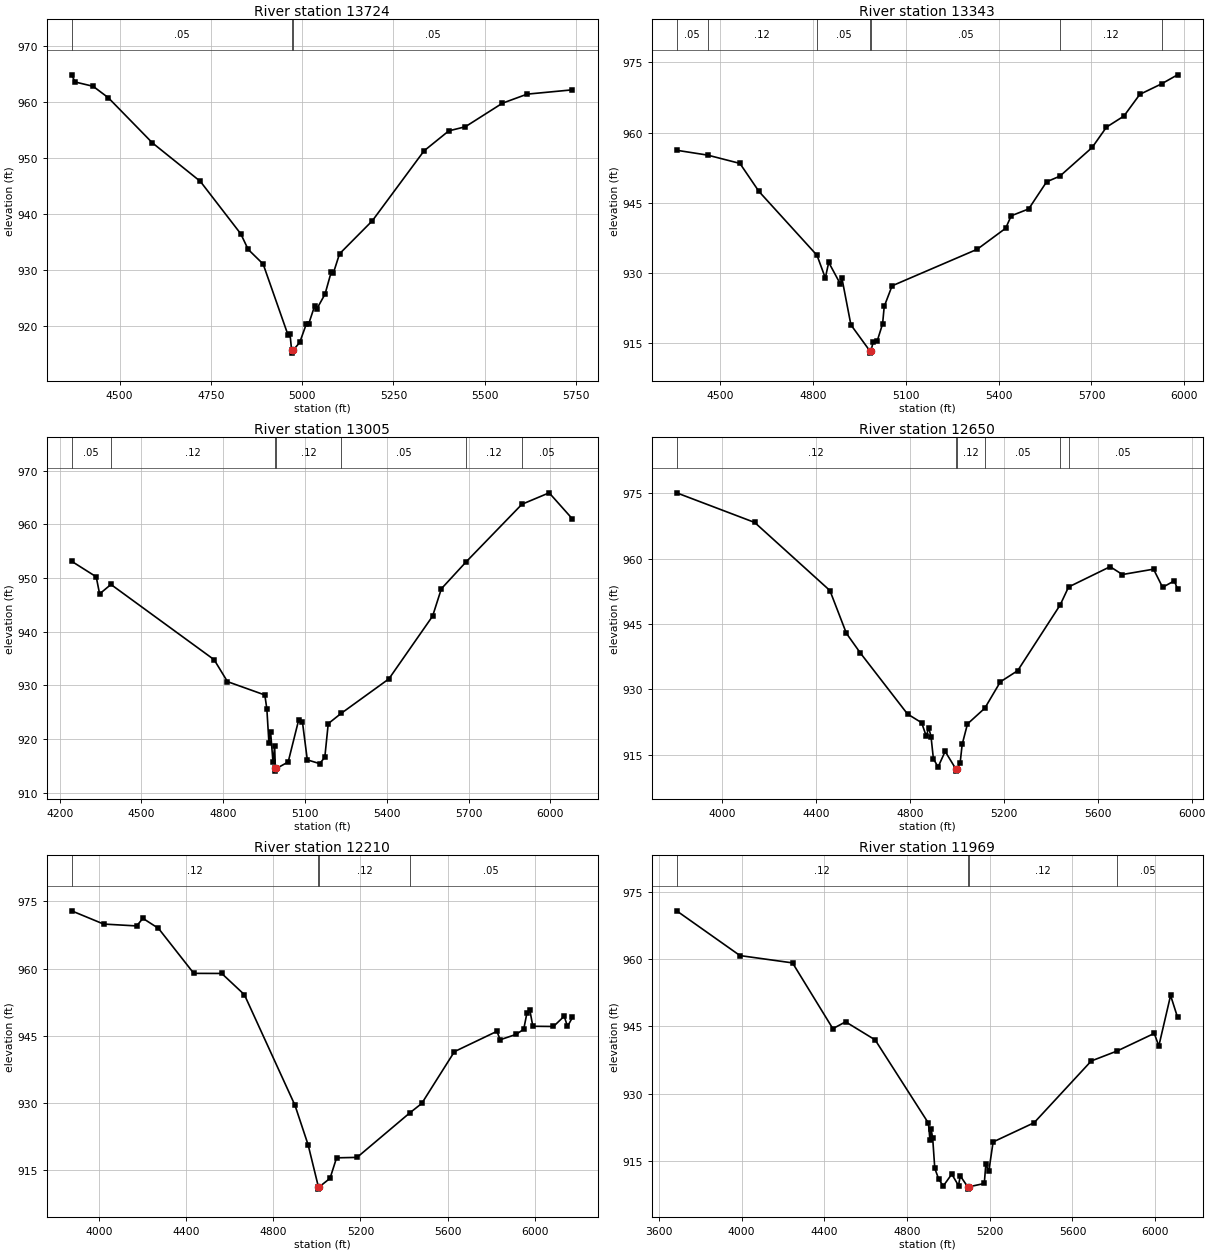
Type RM Length L Ch R = 1,13724,381,381,381
BEGIN DESCRIPTION:
Upper Denton 110 28.0
END DESCRIPTION:
XS GIS Cut Line= 3
      2242058.51      7229276.72      2241429.00      7229360.00
      2240765.06      7229680.39
#Sta/Elev= 30
  4368.3  964.85  4377.9  963.57  4427.3  962.80  4468.7  960.77  4589.7  952.69
  4720.9  945.82  4831.8  936.44  4852.0  933.66  4893.1  931.04  4961.5  918.31
  4966.6  918.63  4971.0  915.63  4971.3  915.13  4975.0  915.63  4993.2  917.03
  5011.8  920.42  5017.4  920.27  5034.4  923.61  5040.0  923.02  5062.6  925.67
  5079.6  929.64  5085.2  929.38  5102.3  932.87  5192.1  938.77  5333.9  951.27
  5401.7  954.84  5446.9  955.57  5548.5  959.78  5616.3  961.40  5740.5  962.17
#Mann=3,-1,0
  4368.3    0.05       0  4971.0   0.033       0  4975.0    0.05       0
Bank Sta=4971,4975
Exp/Cntr=0.3,0.1

Type RM Length L Ch R = 1,13343,338,338,338
BEGIN DESCRIPTION:
Upper Denton 110 27.0
END DESCRIPTION:
XS GIS Cut Line= 3
      2242058.44      7229150.85      2241429.00      7229010.00
      2240474.26      7229198.61
#Sta/Elev= 30
  4359.9  956.21  4460.3  955.17  4564.3  953.40  4625.8  947.41  4813.4  933.76
  4840.2  928.92  4851.2  932.25  4888.7  927.64  4893.9  928.86  4922.9  918.90
  4983.8  913.36  4984.0  912.86  4987.8  913.36  4994.7  915.21  5007.5  915.38
  5025.3  919.13  5030.5  922.83  5055.9  927.24  5331.1  935.06  5422.8  939.54
  5440.8  942.21  5497.2  943.67  5555.3  949.48  5597.9  950.67  5702.3  956.81
  5748.5  961.15  5804.9  963.52  5856.2  968.15  5927.0  970.42  5978.1  972.33
#Mann=7,-1,0
  4359.9    0.05       0  4460.3    0.12       0  4813.4    0.05       0
  4983.8   0.033       0  4987.8    0.05       0  5597.9    0.12       0
  5927.0    0.05       0
Bank Sta=4983.8,4987.8
Exp/Cntr=0.3,0.1

Type RM Length L Ch R = 1,13005,355,355,355
BEGIN DESCRIPTION:
Upper Denton 110 26.0
END DESCRIPTION:
XS GIS Cut Line= 3
      2242153.99      7229129.17      2241529.00      7228710.00
      2240495.99      7229042.35
#Sta/Elev= 30
  4243.8  953.14  4334.1  950.24  4346.6  947.05  4388.2  948.81  4766.7  934.79
  4815.7  930.70  4952.8  928.21  4960.2  925.60  4967.8  919.31  4973.9  921.29
  4982.8  915.67  4988.8  918.66  4991.3  914.52  4991.6  914.02  4995.3  914.52
  5038.4  915.72  5076.6  923.49  5090.9  923.12  5108.6  916.12  5153.9  915.42
  5172.8  916.59  5185.4  922.87  5232.7  924.78  5407.9  931.21  5568.3  942.91
  5600.4  948.01  5691.4  953.03  5896.0  963.76  5995.9  965.89  6081.5  961.01
#Mann=7,-1,0
  4243.8    0.05       0  4388.2    0.12       0  4991.3    0.07       0
  4995.3    0.12       0  5232.7    0.05       0  5691.4    0.12       0
  5896.0    0.05       0
Bank Sta=4991.3,4995.3
Exp/Cntr=0.3,0.1

Type RM Length L Ch R = 1,12650,440,440,440
BEGIN DESCRIPTION:
Upper Denton 110 25.0
END DESCRIPTION:
XS GIS Cut Line= 3
      2242470.85      7228430.37      2241279.00      7228510.00
      2240443.97      7228942.49
#Sta/Elev= 30
  3805.0  975.12  4137.6  968.32  4458.3  952.69  4528.5  942.88  4588.6  938.32
  4789.0  924.36  4849.2  922.36  4869.2  919.23  4879.2  921.26  4889.3  919.14
  4899.3  914.10  4919.3  912.19  4949.4  915.78  4995.0  911.75  4995.3  911.25
  4999.0  911.75  5013.4  913.18  5022.0  917.39  5044.6  922.08  5118.4  925.69
  5184.8  931.75  5258.5  934.30  5439.6  949.38  5475.5  953.51  5652.7  958.17
  5704.8  956.37  5837.6  957.60  5876.2  953.44  5926.1  954.91  5939.9  953.03
#Mann=6,-1,0
  3805.0    0.12       0  4995.0    0.07       0  4999.0    0.12       0
  5118.4    0.05       0  5439.6    0.12       0  5475.5    0.05       0
Bank Sta=4995,4999
Exp/Cntr=0.3,0.1

Type RM Length L Ch R = 1,12210,241,241,241
BEGIN DESCRIPTION:
Upper Denton 110 24.0
END DESCRIPTION:
XS GIS Cut Line= 4
      2242544.57      7228360.93      2241429.14      7228204.68
      2241259.87      7228209.02      2240426.53      7228768.92
#Sta/Elev= 30
  3874.1  972.89  4021.1  969.94  4172.6  969.52  4201.5  971.21  4272.9  968.98
  4435.1  958.94  4563.4  958.92  4667.3  954.19  4899.6  929.52  4960.2  920.66
  5007.2  911.31  5007.5  910.81  5011.2  911.31  5060.6  913.22  5090.6  917.79
  5184.7  917.89  5427.1  927.83  5481.6  929.92  5631.7  941.48  5826.7  946.01
  5841.7  944.13  5913.7  945.31  5949.7  946.45  5964.7  950.13  5978.0  950.70
  5991.7  947.14  6086.4  947.09  6135.7  949.39  6150.7  947.09  6173.7  949.12
#Mann=4,-1,0
  3874.1    0.12       0  5007.2    0.07       0  5011.2    0.12       0
  5427.1    0.05       0
Bank Sta=5007.2,5011.2
Exp/Cntr=0.3,0.1

Type RM Length L Ch R = 1,11969,441,441,441
BEGIN DESCRIPTION:
Upper Denton 110 23.0
END DESCRIPTION:
XS GIS Cut Line= 3
      2242674.84      7228274.13      2241329.00      7227960.00
      2240543.87      7228642.92
#Sta/Elev= 30
  3685.6  970.81  3992.1  960.82  4246.1  959.19  4441.2  944.51  4502.8  946.04
  4645.6  942.01  4903.3  923.43  4911.0  919.56  4916.2  922.08  4923.9  920.14
  4934.1  913.34  4953.6  910.88  4975.2  909.40  5016.3  912.05  5048.9  909.48
  5057.3  911.66  5093.6  909.20  5093.9  908.70  5097.6  909.20  5173.6  909.96
  5181.1  914.35  5195.3  912.67  5216.2  919.23  5414.6  923.52  5690.9  937.30
  5816.1  939.53  5995.7  943.46  6017.6  940.63  6074.6  951.93  6108.2  947.05
#Mann=4,-1,0
  3685.6    0.12       0  5093.6    0.07       0  5097.6    0.12       0
  5816.1    0.05       0
Bank Sta=5093.6,5097.6
Exp/Cntr=0.3,0.1

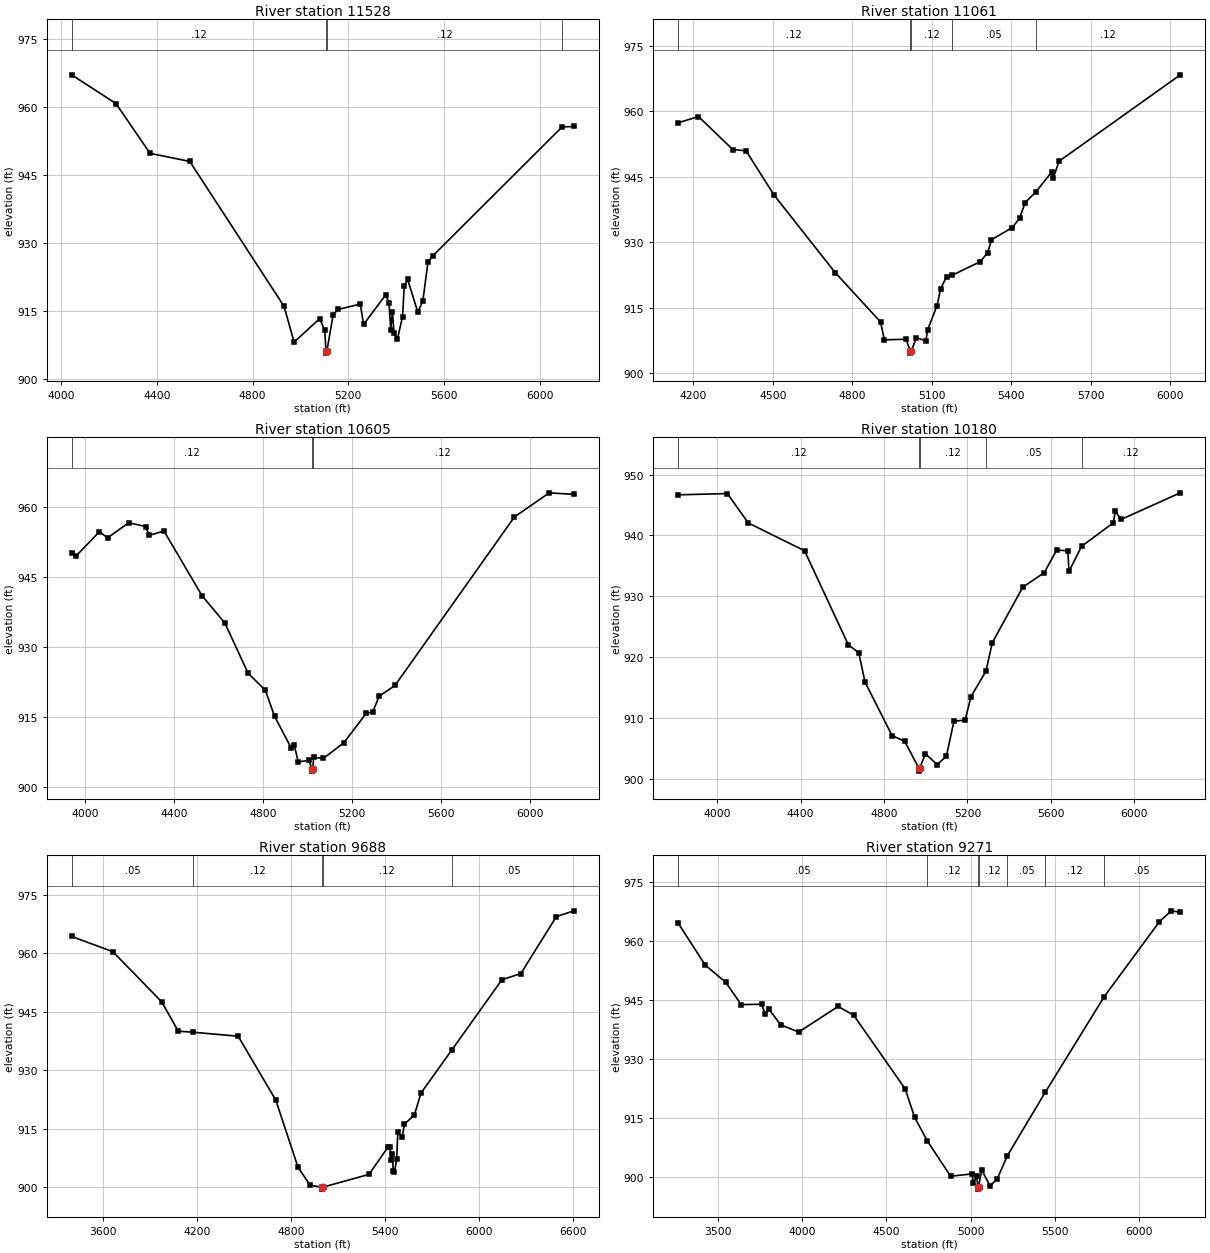
Type RM Length L Ch R = 1,11528,467,467,467
BEGIN DESCRIPTION:
Upper Denton 110 22.0
END DESCRIPTION:
XS GIS Cut Line= 3
      2241954.68      7227107.31      2241179.00      7227660.00
      2240379.17      7228483.17
#Sta/Elev= 30
  4043.1  967.17  4228.4  960.83  4371.0  949.85  4537.0  948.07  4931.6  916.07
  4973.4  908.20  5080.3  913.38  5101.6  910.77  5106.6  906.27  5106.9  905.77
  5110.6  906.27  5136.9  914.29  5158.2  915.42  5250.1  916.59  5264.2  912.11
  5356.3  918.61  5370.4  916.88  5377.4  910.96  5384.6  914.84  5391.5  910.14
  5405.7  908.92  5427.0  913.85  5434.0  920.47  5448.1  922.05  5490.6  914.86
  5511.7  917.20  5533.0  925.83  5554.1  927.27  6094.1  955.67  6143.3  955.77
#Mann=4,-1,0
  4043.1    0.12       0  5106.6    0.07       0  5110.6    0.12       0
  6094.1    0.05       0
Bank Sta=5106.6,5110.6
Exp/Cntr=0.3,0.1

Type RM Length L Ch R = 1,11061,456,456,456
BEGIN DESCRIPTION:
Upper Denton 110 21.0
END DESCRIPTION:
XS GIS Cut Line= 3
      2241520.69      7227003.12      2240829.00      7227510.00
      2240144.76      7228292.23
#Sta/Elev= 30
  4142.2  957.31  4219.0  958.76  4348.6  951.20  4398.8  950.89  4505.3  940.70
  4735.3  923.01  4906.7  911.71  4921.4  907.59  5003.1  907.73  5019.1  905.05
  5019.3  904.55  5023.1  905.05  5042.0  908.07  5078.0  907.37  5084.7  909.92
  5119.8  915.38  5134.0  919.34  5155.9  922.07  5177.3  922.39  5283.1  925.49
  5311.5  927.59  5325.8  930.52  5403.6  933.30  5432.1  935.44  5452.9  939.04
  5493.4  941.47  5552.6  945.99  5559.3  944.70  5581.1  948.52  6039.0  968.31
#Mann=5,-1,0
  4142.2    0.12       0  5019.1    0.07       0  5023.1    0.12       0
  5177.3    0.05       0  5493.4    0.12       0
Bank Sta=5019.1,5023.1
Exp/Cntr=0.3,0.1

Type RM Length L Ch R = 1,10605,425,425,425
BEGIN DESCRIPTION:
Upper Denton 110 20.0
END DESCRIPTION:
XS GIS Cut Line= 3
      2241658.16      7226905.78      2240629.00      7227160.00
      2239918.59      7228124.52
#Sta/Elev= 30
  3940.5  950.16  3960.2  949.46  4065.4  954.65  4101.7  953.34  4197.2  956.57
  4272.6  955.77  4289.9  953.88  4355.5  954.82  4526.8  940.96  4629.8  935.08
  4733.7  924.38  4811.5  920.71  4852.9  915.15  4928.5  908.28  4941.0  909.02
  4959.4  905.39  5007.9  905.72  5020.5  903.91  5020.8  903.41  5024.6  903.91
  5028.8  906.34  5072.7  906.14  5164.5  909.49  5264.8  915.78  5294.1  916.08
  5323.4  919.45  5394.3  921.74  5931.2  957.81  6087.8  962.98  6198.5  962.65
#Mann=3,-1,0
  3940.5    0.12       0  5020.5    0.07       0  5024.6    0.12       0
Bank Sta=5020.5,5024.6
Exp/Cntr=0.3,0.1

Type RM Length L Ch R = 1,10180,492,492,492
BEGIN DESCRIPTION:
Upper Denton 110 19.0
END DESCRIPTION:
XS GIS Cut Line= 3
      2241585.26      7226827.65      2240379.00      7226860.00
      2239793.79      7227910.61
#Sta/Elev= 30
  3812.0  946.68  4048.3  946.89  4148.4  942.06  4418.5  937.49  4628.6  922.04
  4678.6  920.73  4708.6  915.91  4838.6  907.10  4898.7  906.19  4966.6  901.77
  4966.9  901.27  4970.7  901.77  4998.7  904.13  5054.1  902.35  5098.8  903.69
  5135.3  909.47  5189.0  909.65  5216.5  913.48  5288.9  917.71  5319.4  922.39
  5465.7  931.51  5568.6  933.88  5628.0  937.61  5681.7  937.47  5687.4  934.10
  5747.6  938.22  5900.1  942.08  5909.2  944.01  5936.7  942.63  6221.3  947.01
#Mann=5,-1,0
  3812.0    0.12       0  4966.6    0.07       0  4970.7    0.12       0
  5288.9    0.05       0  5747.6    0.12       0
Bank Sta=4966.6,4970.7
Exp/Cntr=0.3,0.1

Type RM Length L Ch R = 1,9688,417,417,417
BEGIN DESCRIPTION:
Upper Denton 110 18.0
END DESCRIPTION:
XS GIS Cut Line= 3
      2241361.28      7225390.17      2240179.00      7226460.00
      2238976.43      7227535.49
#Sta/Elev= 30
  3400.6  964.31  3663.9  960.40  3975.5  947.56  4081.6  940.01  4176.0  939.75
  4464.2  938.72  4704.8  922.32  4846.7  905.10  4924.4  900.51  4999.9  900.01
  5000.4  899.51  5004.5  900.01  5299.8  903.29  5420.1  910.21  5434.3  910.30
  5441.0  906.96  5448.5  908.64  5455.3  904.26  5462.8  903.91  5477.0  907.23
  5483.7  914.06  5512.1  912.83  5526.3  916.19  5589.8  918.53  5632.5  924.18
  5829.8  935.24  6149.1  953.21  6269.6  954.79  6496.8  969.40  6608.4  970.88
#Mann=5,-1,0
  3400.6    0.05       0  4176.0    0.12       0  4999.9    0.07       0
  5004.5    0.12       0  5829.8    0.05       0
Bank Sta=4999.9,5004.5
Exp/Cntr=0.3,0.1

Type RM Length L Ch R = 1,9271,470,470,470
BEGIN DESCRIPTION:
Upper Denton 110 17.0
END DESCRIPTION:
XS GIS Cut Line= 3
      2241199.84      7225093.27      2239879.00      7226210.00
      2238986.27      7227082.88
#Sta/Elev= 30
  3265.3  964.55  3426.5  953.84  3547.4  949.49  3639.7  943.79  3760.5  943.90
  3781.4  941.37  3803.3  942.65  3873.7  938.66  3980.3  936.82  4214.3  943.34
  4306.6  941.10  4612.1  922.34  4668.0  915.11  4743.5  909.10  4881.2  900.14
  5009.0  900.74  5016.2  898.49  5037.3  900.08  5042.2  897.36  5042.6  896.86
  5046.8  897.36  5065.6  901.78  5115.2  897.68  5157.6  899.45  5218.3  905.39
  5442.6  921.50  5792.1  945.81  6119.3  964.88  6190.0  967.66  6243.5  967.29
#Mann=7,-1,0
  3265.3    0.05       0  4743.5    0.12       0  5042.2    0.07       0
  5046.8    0.12       0  5218.3    0.05       0  5442.6    0.12       0
  5792.1    0.05       0
Bank Sta=5042.2,5046.8
Exp/Cntr=0.3,0.1

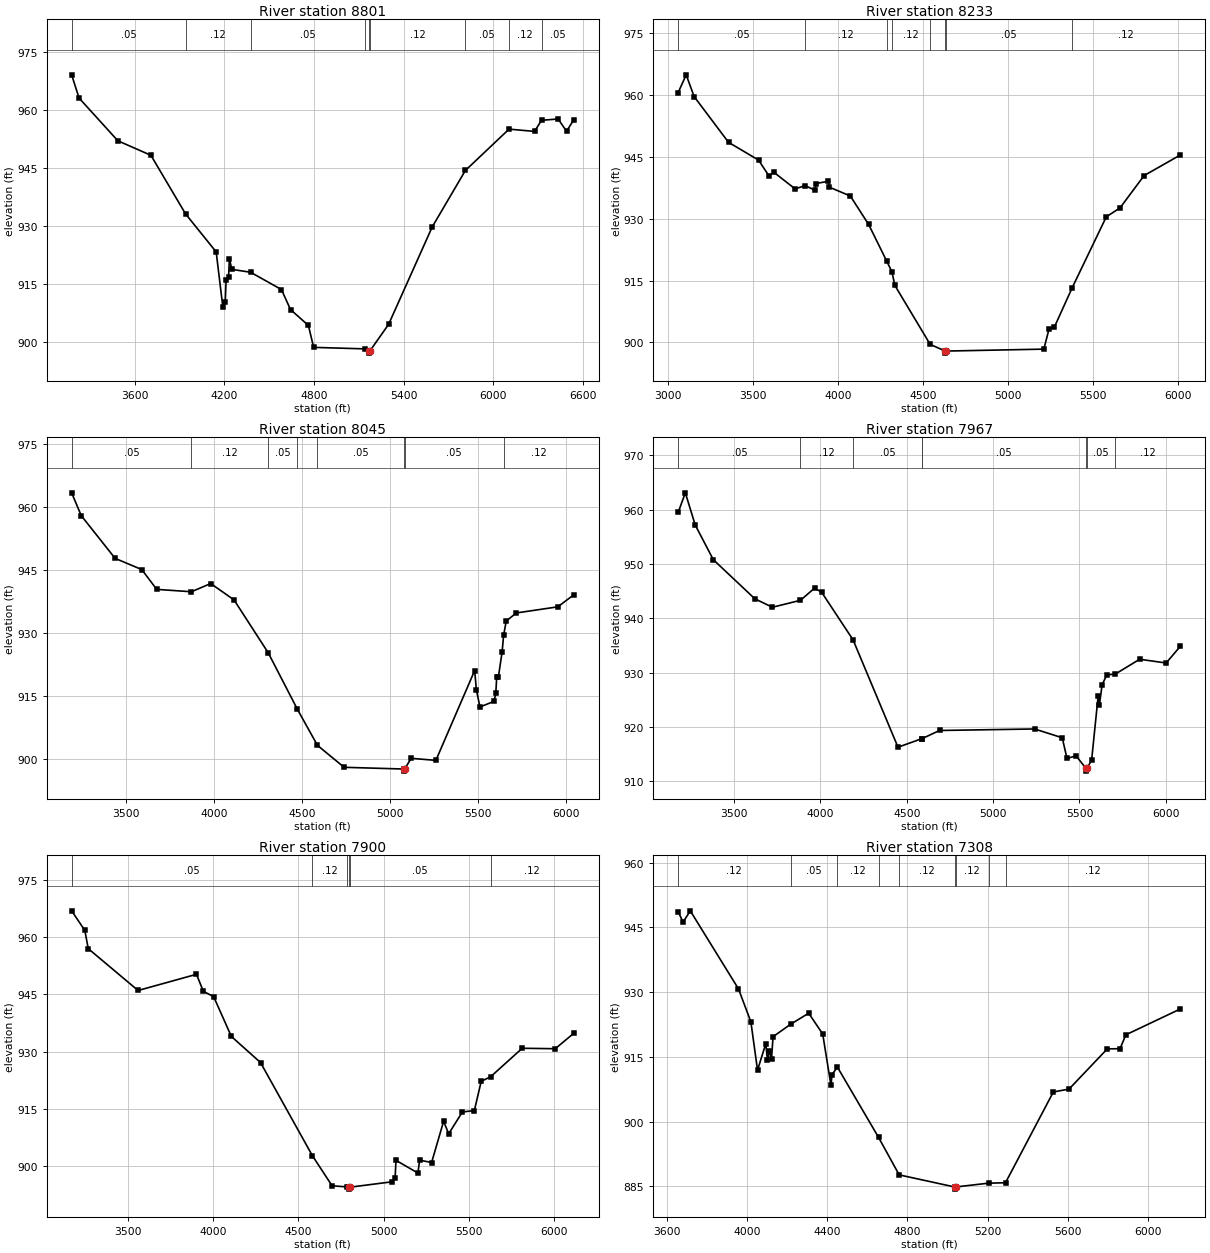
Type RM Length L Ch R = 1,8801,568,568,568
BEGIN DESCRIPTION:
Upper Denton 110 16.0
END DESCRIPTION:
XS GIS Cut Line= 3
      2241194.62      7225020.36      2239579.00      7225860.00
      2238643.28      7227081.90
#Sta/Elev= 30
  3179.2  969.18  3228.8  963.16  3488.5  952.09  3709.6  948.33  3941.2  933.16
  4146.3  923.30  4190.5  909.13  4207.0  910.43  4212.6  915.90  4229.1  916.80
  4234.7  921.50  4251.2  918.78  4376.6  918.03  4583.0  913.55  4643.6  908.37
  4763.3  904.25  4798.4  898.57  5143.9  898.18  5169.0  897.58  5169.5  897.08
  5173.7  897.58  5300.1  904.54  5592.0  929.79  5813.7  944.40  6105.9  955.11
  6276.5  954.52  6323.1  957.40  6434.3  957.74  6490.5  954.57  6539.0  957.54
#Mann=9,-1,0
  3179.2    0.05       0  3941.2    0.12       0  4376.6    0.05       0
  5143.9    0.12       0  5169.0   0.033       0  5173.7    0.12       0
  5813.7    0.05       0  6105.9    0.12       0  6323.1    0.05       0
Bank Sta=5169,5173.7
Exp/Cntr=0.3,0.1

Type RM Length L Ch R = 1,8233,188,188,188
BEGIN DESCRIPTION:
Upper Denton 110 15.0
END DESCRIPTION:
XS GIS Cut Line= 3
      2241126.93      7224963.07      2239241.50      7225426.61
      2238263.18      7225686.80
#Sta/Elev= 30
  3061.6  960.62  3108.7  964.91  3155.4  959.64  3357.9  948.53  3534.4  944.23
  3595.0  940.43  3625.8  941.23  3749.4  937.24  3808.6  938.03  3866.7  936.91
  3873.0  938.54  3944.6  939.09  3949.8  937.68  4074.4  935.51  4181.9  928.62
  4288.0  919.75  4319.1  917.11  4336.4  913.82  4544.0  899.52  4632.6  897.90
  4633.2  897.40  4637.5  897.90  5212.7  898.37  5243.8  903.35  5274.8  903.73
  5378.8  913.20  5580.3  930.48  5660.6  932.61  5802.5  940.47  6015.5  945.46
#Mann=8,-1,0
  3061.6    0.05       0  3808.6    0.12       0  4288.0    0.05       0
  4319.1    0.12       0  4544.0    0.05       0  4632.6   0.033       0
  4637.5    0.05       0  5378.8    0.12       0
Bank Sta=4632.6,4637.5
Exp/Cntr=0.3,0.1

Type RM Length L Ch R = 1,8045,78,78,78
BEGIN DESCRIPTION:
Upper Denton 110 14.5
END DESCRIPTION:
XS GIS Cut Line= 5
      2241059.26      7224963.06      2240126.98      7225182.55
      2239272.75      7225254.74      2238673.79      7225280.78
      2238314.45      7225530.75
#Sta/Elev= 30
  3191.3  963.38  3245.7  957.96  3438.1  947.78  3589.8  945.11  3674.4  940.40
  3871.6  939.83  3981.3  941.79  4113.6  937.89  4307.9  925.30  4473.7  911.84
  4587.7  903.26  4739.1  898.04  5077.7  897.63  5078.3  897.13  5082.6  897.63
  5120.2  900.18  5260.3  899.69  5480.5  921.07  5490.5  916.45  5510.6  912.40
  5590.6  913.74  5600.7  915.64  5605.8  919.60  5615.5  919.59  5636.5  925.50
  5645.3  929.57  5660.1  932.86  5716.8  934.78  5952.8  936.24  6043.6  939.10
#Mann=8,-1,0
  3191.3    0.05       0  3871.6    0.12       0  4307.9    0.05       0
  4473.7    0.12       0  4587.7    0.05       0  5077.7   0.033       0
  5082.6    0.05       0  5645.3    0.12       0
Bank Sta=5077.7,5082.6
Exp/Cntr=0.3,0.1

Type RM Length L Ch R = 1,7967,67,67,67
BEGIN DESCRIPTION:
Upper Denton 110 14.4
END DESCRIPTION:
XS GIS Cut Line= 5
      2241085.27      7224947.44      2240147.75      7225124.53
      2239283.17      7225176.61      2238668.58      7225202.65
      2238263.18      7225446.93
#Sta/Elev= 30
  3175.6  959.46  3217.0  963.07  3274.4  957.14  3379.2  950.76  3619.6  943.57
  3721.4  942.01  3884.1  943.29  3965.6  945.53  4006.3  944.79  4188.8  936.00
  4449.0  916.25  4585.8  917.81  4586.6  917.80  4689.5  919.33  5240.2  919.61
  5400.4  917.99  5427.8  914.19  5480.5  914.66  5538.1  912.35  5538.7  911.85
  5543.0  912.35  5570.5  913.86  5608.3  925.62  5615.9  924.08  5631.5  927.77
  5658.7  929.57  5707.0  929.70  5848.9  932.44  6002.3  931.75  6084.3  934.82
#Mann=8,-1,0
  3175.6    0.05       0  3884.1    0.12       0  4188.8    0.05       0
  4585.8    0.12       0  4586.6    0.05       0  5538.1   0.033       0
  5543.0    0.05       0  5707.0    0.12       0
Bank Sta=5538.1,5543
Exp/Cntr=0.3,0.1

Type RM Length L Ch R = 1,7900,592,592,592
BEGIN DESCRIPTION:
Upper Denton 110 14.0
END DESCRIPTION:
XS GIS Cut Line= 4
      2241095.67      7224895.36      2239279.00      7225110.00
      2238652.96      7225155.78      2238263.15      7225446.83
#Sta/Elev= 30
  3170.7  966.91  3247.9  961.78  3268.0  957.00  3560.1  946.03  3902.4  950.27
  3942.7  945.81  4003.1  944.42  4107.0  933.98  4277.8  927.15  4582.2  902.71
  4697.3  894.85  4782.4  894.56  4796.2  894.47  4796.8  893.97  4801.1  894.47
  5050.1  895.90  5066.9  896.94  5071.9  901.52  5200.5  898.18  5210.6  901.57
  5280.8  900.94  5350.9  911.72  5381.0  908.49  5461.2  914.19  5531.4  914.56
  5571.5  922.23  5626.7  923.42  5812.0  930.89  6005.8  930.77  6114.2  934.82
#Mann=6,-1,0
  3170.7    0.05       0  4582.2    0.12       0  4782.4    0.05       0
  4796.2   0.033       0  4801.1    0.05       0  5626.7    0.12       0
Bank Sta=4796.2,4801.1
Exp/Cntr=0.3,0.1

Type RM Length L Ch R = 1,7308,312,312,312
BEGIN DESCRIPTION:
Upper Denton 110 13.0
END DESCRIPTION:
XS GIS Cut Line= 3
      2240481.12      7224240.01      2239121.71      7224578.57
      2238277.92      7225292.14
#Sta/Elev= 30
  3655.8  948.65  3680.1  946.20  3716.2  948.83  3956.8  930.75  4018.7  923.10
  4051.8  911.93  4093.1  918.09  4101.1  914.31  4111.4  916.33  4121.7  914.60
  4129.3  919.68  4216.5  922.55  4307.2  925.12  4377.1  920.31  4418.4  908.38
  4423.5  910.89  4450.4  912.64  4656.0  896.35  4758.8  887.68  5035.4  884.88
  5036.0  884.38  5040.3  884.88  5204.7  885.76  5289.4  885.86  5528.3  906.89
  5606.3  907.54  5797.4  916.86  5861.1  916.90  5889.7  920.11  6161.8  926.10
#Mann=9,-1,0
  3655.8    0.12       0  4216.5    0.05       0  4450.4    0.12       0
  4656.0    0.05       0  4758.8    0.12       0  5035.4    0.07       0
  5040.3    0.12       0  5204.7    0.05       0  5289.4    0.12       0
Bank Sta=5035.4,5040.3
Exp/Cntr=0.3,0.1

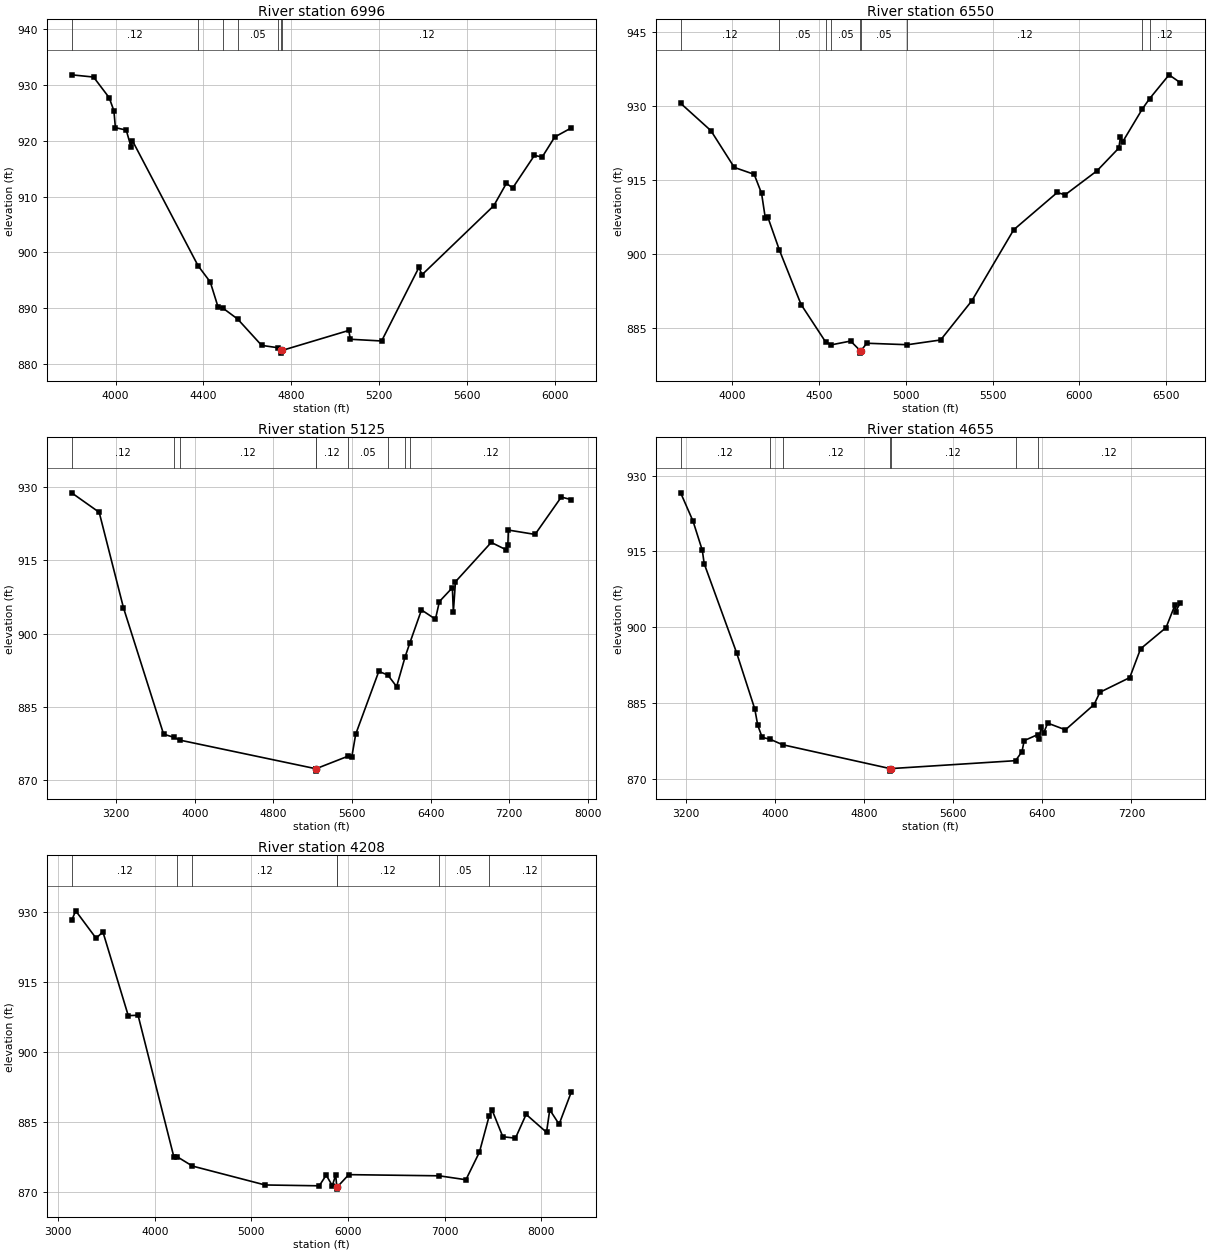
Type RM Length L Ch R = 1,6996,446,446,446
BEGIN DESCRIPTION:
Upper Denton 110 12.0
END DESCRIPTION:
XS GIS Cut Line= 3
      2239736.32      7223516.04      2238929.00      7224410.00
      2238246.70      7225234.82
#Sta/Elev= 30
  3800.4  931.86  3900.1  931.46  3971.1  927.76  3992.7  925.41  3999.5  922.37
  4048.8  921.94  4070.5  918.94  4077.2  920.02  4376.0  897.57  4431.4  894.66
  4466.5  890.21  4490.6  889.92  4556.0  888.01  4665.3  883.28  4741.3  882.85
  4754.8  882.39  4755.4  881.89  4759.7  882.39  5061.6  885.96  5069.4  884.38
  5211.4  884.07  5381.3  897.29  5395.1  895.96  5722.0  908.36  5779.3  912.38
  5808.0  911.54  5907.0  917.40  5942.1  917.09  5999.5  920.70  6075.4  922.34
#Mann=7,-1,0
  3800.4    0.12       0  4376.0    0.05       0  4490.6    0.12       0
  4556.0    0.05       0  4741.3    0.12       0  4754.8    0.07       0
  4759.7    0.12       0
Bank Sta=4754.8,4759.7
Exp/Cntr=0.3,0.1

Type RM Length L Ch R = 1,6550,1425,1425,1425
BEGIN DESCRIPTION:
Upper Denton 110 11.0
END DESCRIPTION:
XS GIS Cut Line= 3
      2239590.46      7223406.69      2238579.00      7224210.00
      2237823.55      7225603.78
#Sta/Elev= 30
  3704.2  930.52  3878.4  924.99  4013.0  917.56  4127.5  916.16  4170.0  912.32
  4191.3  907.37  4205.2  907.59  4273.2  900.79  4397.5  889.84  4540.4  882.18
  4572.0  881.69  4682.6  882.45  4737.8  880.51  4738.5  880.01  4742.8  880.51
  4775.6  882.01  5010.0  881.71  5200.7  882.67  5380.5  890.60  5621.4  904.95
  5872.1  912.49  5917.2  912.01  6101.2  916.88  6226.7  921.48  6235.7  923.65
  6248.6  922.73  6362.8  929.43  6403.5  931.45  6515.8  936.28  6581.2  934.67
#Mann=9,-1,0
  3704.2    0.12       0  4273.2    0.05       0  4540.4    0.12       0
  4572.0    0.05       0  4737.8   0.033       0  4742.8    0.05       0
  5010.0    0.12       0  6362.8    0.05       0  6403.5    0.12       0
Bank Sta=4737.8,4742.8
Exp/Cntr=0.3,0.1

Type RM Length L Ch R = 1,5125,470,470,470
BEGIN DESCRIPTION:
Upper Denton 110 10.0
END DESCRIPTION:
XS GIS Cut Line= 4
      2239611.30      7223312.94      2237675.53      7223784.58
      2237258.86      7223927.81      2237701.58      7226545.04
#Sta/Elev= 30
  2746.9  928.85  3027.2  924.86  3274.2  905.31  3682.9  879.40  3789.1  878.75
  3846.9  878.19  5230.3  872.33  5230.9  871.83  5235.4  872.33  5561.2  874.90
  5597.9  874.67  5638.5  879.41  5873.5  892.27  5965.5  891.52  6054.8  889.15
  6141.6  895.27  6188.3  898.03  6307.9  904.86  6449.9  902.96  6490.4  906.58
  6622.3  909.41  6632.4  904.42  6653.7  910.63  7017.8  918.69  7170.0  917.18
  7187.2  918.23  7192.3  921.22  7464.1  920.33  7730.9  927.98  7834.3  927.45
#Mann=9,-1,0
  2746.9    0.12       0  3789.1    0.05       0  3846.9    0.12       0
  5230.3    0.07       0  5235.4    0.12       0  5561.2    0.05       0
  5965.5    0.12       0  6141.6    0.05       0  6188.3    0.12       0
Bank Sta=5230.3,5235.4
Exp/Cntr=0.3,0.1

Type RM Length L Ch R = 1,4655,447,447,447
BEGIN DESCRIPTION:
Upper Denton 110 9.0
END DESCRIPTION:
XS GIS Cut Line= 4
      2239369.95      7223342.75      2237529.00      7223460.00
      2237323.72      7223462.64      2236855.30      7225856.77
#Sta/Elev= 30
  3150.5  926.58  3261.7  920.97  3345.1  915.19  3361.9  912.56  3652.5  894.95
  3816.5  883.77  3842.9  880.57  3882.9  878.15  3953.9  877.79  4066.1  876.70
  5032.6  871.97  5033.3  871.47  5037.7  871.97  6158.5  873.54  6216.7  875.32
  6236.3  877.51  6356.8  878.69  6369.6  877.81  6390.0  880.19  6410.3  878.97
  6447.5  880.98  6607.1  879.65  6864.7  884.66  6916.2  887.08  7184.8  889.99
  7281.9  895.69  7510.8  899.89  7591.0  904.36  7596.1  903.08  7640.0  904.80
#Mann=7,-1,0
  3150.5    0.12       0  3953.9    0.05       0  4066.1    0.12       0
  5032.6    0.07       0  5037.7    0.12       0  6158.5    0.05       0
  6356.8    0.12       0
Bank Sta=5032.6,5037.7
Exp/Cntr=0.3,0.1

Type RM Length L Ch R = 1,4208,0,0,0
BEGIN DESCRIPTION:
Upper Denton 110 8.0
END DESCRIPTION:
XS GIS Cut Line= 5
      2239680.73      7223341.88      2237829.00      7223160.00
      2237610.18      7223132.78      2236551.15      7224035.56
      2236715.92      7225726.60
#Sta/Elev= 30
  3139.7  928.13  3181.6  930.18  3392.6  924.31  3463.0  925.68  3725.4  907.75
  3826.8  907.83  4196.5  877.58  4233.2  877.53  4389.0  875.56  5141.4  871.51
  5702.1  871.33  5773.5  873.62  5837.1  871.36  5872.3  873.66  5882.9  871.12
  5884.0  870.62  5890.1  871.12  6007.3  873.72  6943.0  873.47  7219.7  872.63
  7359.5  878.54  7459.8  886.25  7491.0  887.51  7601.5  881.83  7732.2  881.53
  7842.7  886.62  8053.7  882.78  8087.2  887.60  8183.9  884.51  8311.5  891.48
#Mann=7,-1,0
  3139.7    0.12       0  4233.2    0.05       0  4389.0    0.12       0
  5882.9    0.07       0  5890.1    0.12       0  6943.0    0.05       0
  7459.8    0.12       0
Bank Sta=5882.9,5890.1
Exp/Cntr=0.3,0.1

Chan Stop Cuts=-1