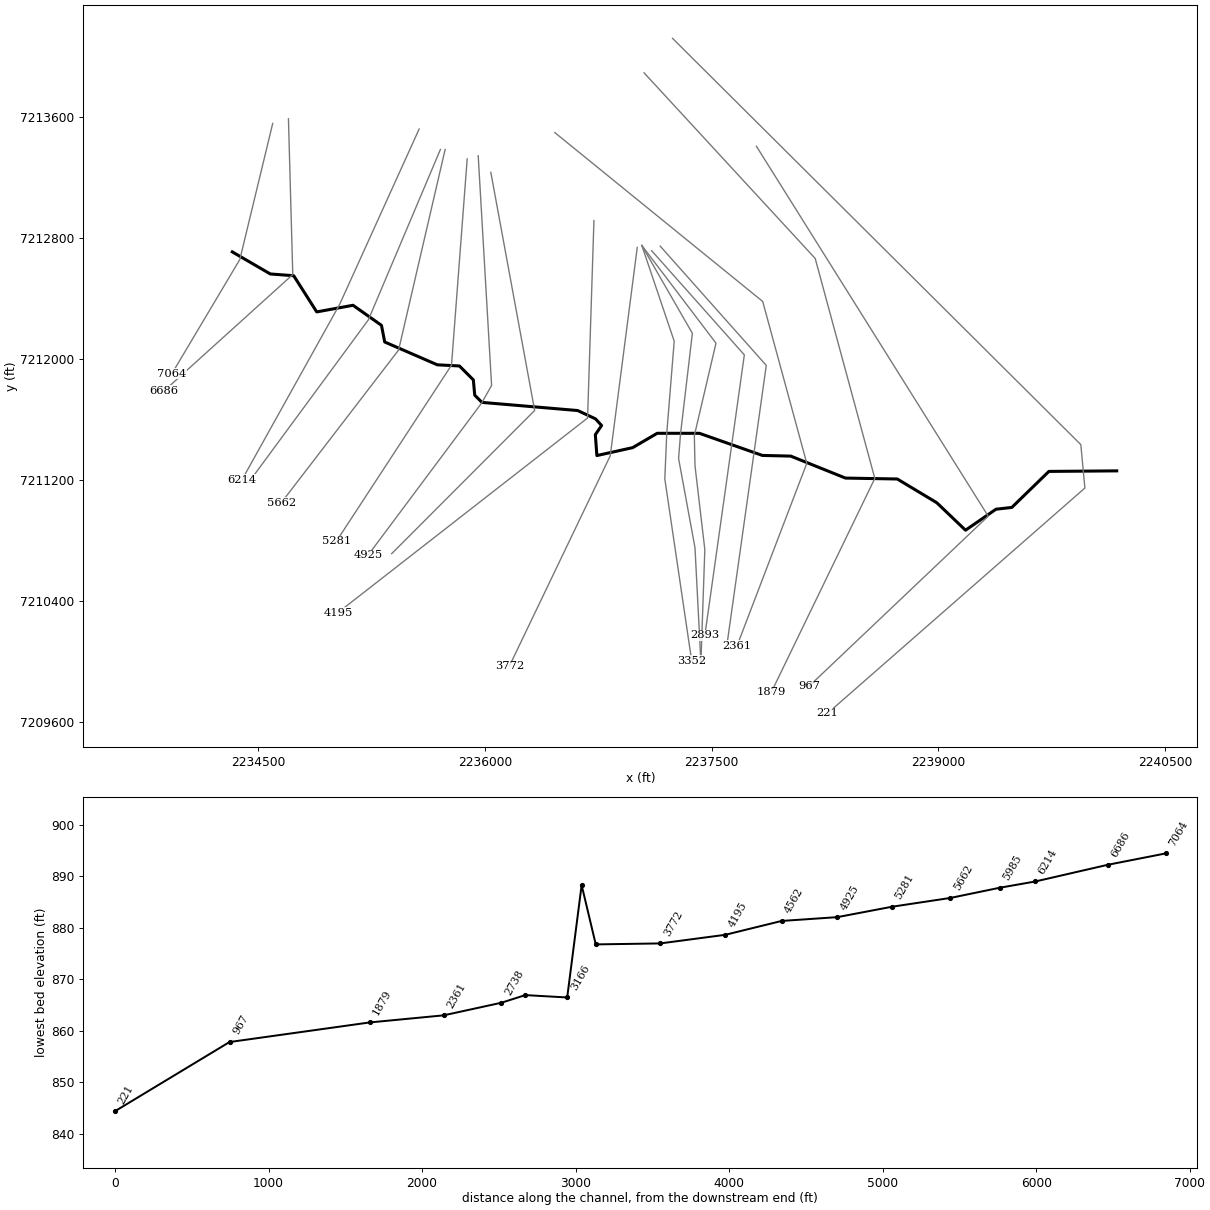
--- Upper Denton 114.prj (project) ---

Proj Title=Upper Denton 114 Base Level Engineering
Current Plan=p01
Default Exp/Contr=0.3,0.1
English Units
Geom File=g01
Flow File=f01
Plan File=p01
Y Axis Title=Elevation
X Axis Title(PF)=Main Channel Distance
X Axis Title(XS)=Station
BEGIN DESCRIPTION:
Upper Denton 114
END DESCRIPTION:
DSS Export Rating Curves= 0
DSS Export Rating Curve Sorted= 0
DSS Export Volume Flow Curves= 0
DXF OffsetX= 0
DXF OffsetY= 0
DXF ScaleX= 1
DXF ScaleY= 10

--- Upper Denton 114.p01 (plan) ---

Plan Title=Multiple Run
Short Identifier=Multiple
Geom File=g01
Flow File=f01
Subcritical Flow
K Sum by GR= 0
Std Step Tol= 0.01
Critical Tol= 0.01
Num of Std Step Trials= 20
Max Error Tol= 0.3
Flow Tol Ratio= 0.001
Split Flow NTrial= 30
Split Flow Tol= 0.02
Split Flow Ratio= 0.02
Log Output Level= 0
Friction Slope Method= 1
Unsteady Friction Slope Method= 2
Unsteady Bridges Friction Slope Method= 1
Parabolic Critical Depth
Global Vel Dist=  1 , 1 , 1
Global Log Level= 0
CheckData=True
Encroach Param= -1, 0, 0, 0
BEGIN DESCRIPTION:
Multiple Run
END DESCRIPTION:

--- Upper Denton 114.f01 (steady flow) ---

Flow Title=Multiple
Program Version=4.10
Number of Profiles= 7
Profile Names=10-year,25-year,50-year,1pct_min,100-year,1pct_plu,500-year
River Rch & RM=Upper Denton 114,Reach-1         ,7064
     749    1056    1318     817    1630    3253    2501
River Rch & RM=Upper Denton 114,Reach-1         ,3772
     982    1401    1761    1099    2192    4374    3405
Boundary for River Rch & Prof#=Upper Denton 114,Reach-1         , 1
Up Type= 0
Dn Type= 3
Dn Slope=0.01
Boundary for River Rch & Prof#=Upper Denton 114,Reach-1         , 2
Up Type= 0
Dn Type= 3
Dn Slope=0.01
Boundary for River Rch & Prof#=Upper Denton 114,Reach-1         , 3
Up Type= 0
Dn Type= 3
Dn Slope=0.01
Boundary for River Rch & Prof#=Upper Denton 114,Reach-1         , 4
Up Type= 0
Dn Type= 3
Dn Slope=0.01
Boundary for River Rch & Prof#=Upper Denton 114,Reach-1         , 5
Up Type= 0
Dn Type= 3
Dn Slope=0.01
Boundary for River Rch & Prof#=Upper Denton 114,Reach-1         , 6
Up Type= 0
Dn Type= 3
Dn Slope=0.01
Boundary for River Rch & Prof#=Upper Denton 114,Reach-1         , 7
Up Type= 0
Dn Type= 3
Dn Slope=0.01
DSS Import GetInterval= 0
DSS Import GetPeak= 0
DSS Import FillOption= 0

--- Upper Denton 114.g01 (geometry) ---

Geom Title=Existing Conditions

River Reach=Upper Denton 114,Reach-1
Reach XY= 30
      2234329.00      7212710.00      2234580.56      7212563.76
      2234735.21      7212552.19      2234887.46      7212312.62
      2235127.53      7212356.46      2235315.73      7212223.62
      2235337.16      7212113.38      2235684.94      7211962.27
      2235831.46      7211954.54      2235923.48      7211862.44
      2235932.51      7211761.25      2235980.22      7211713.44
      2236613.79      7211659.49      2236731.86      7211604.18
      2236771.77      7211560.32      2236730.37      7211499.55
      2236740.52      7211361.37      2236977.42      7211413.83
      2237139.50      7211508.80      2237418.50      7211508.78
      2237834.94      7211362.26      2238023.06      7211357.74
      2238384.94      7211212.26      2238727.45      7211206.25
      2238988.68      7211049.22      2239179.00      7210867.08
      2239380.59      7211006.17      2239485.17      7211017.86
      2239730.46      7211256.46      2240179.00      7211260.00

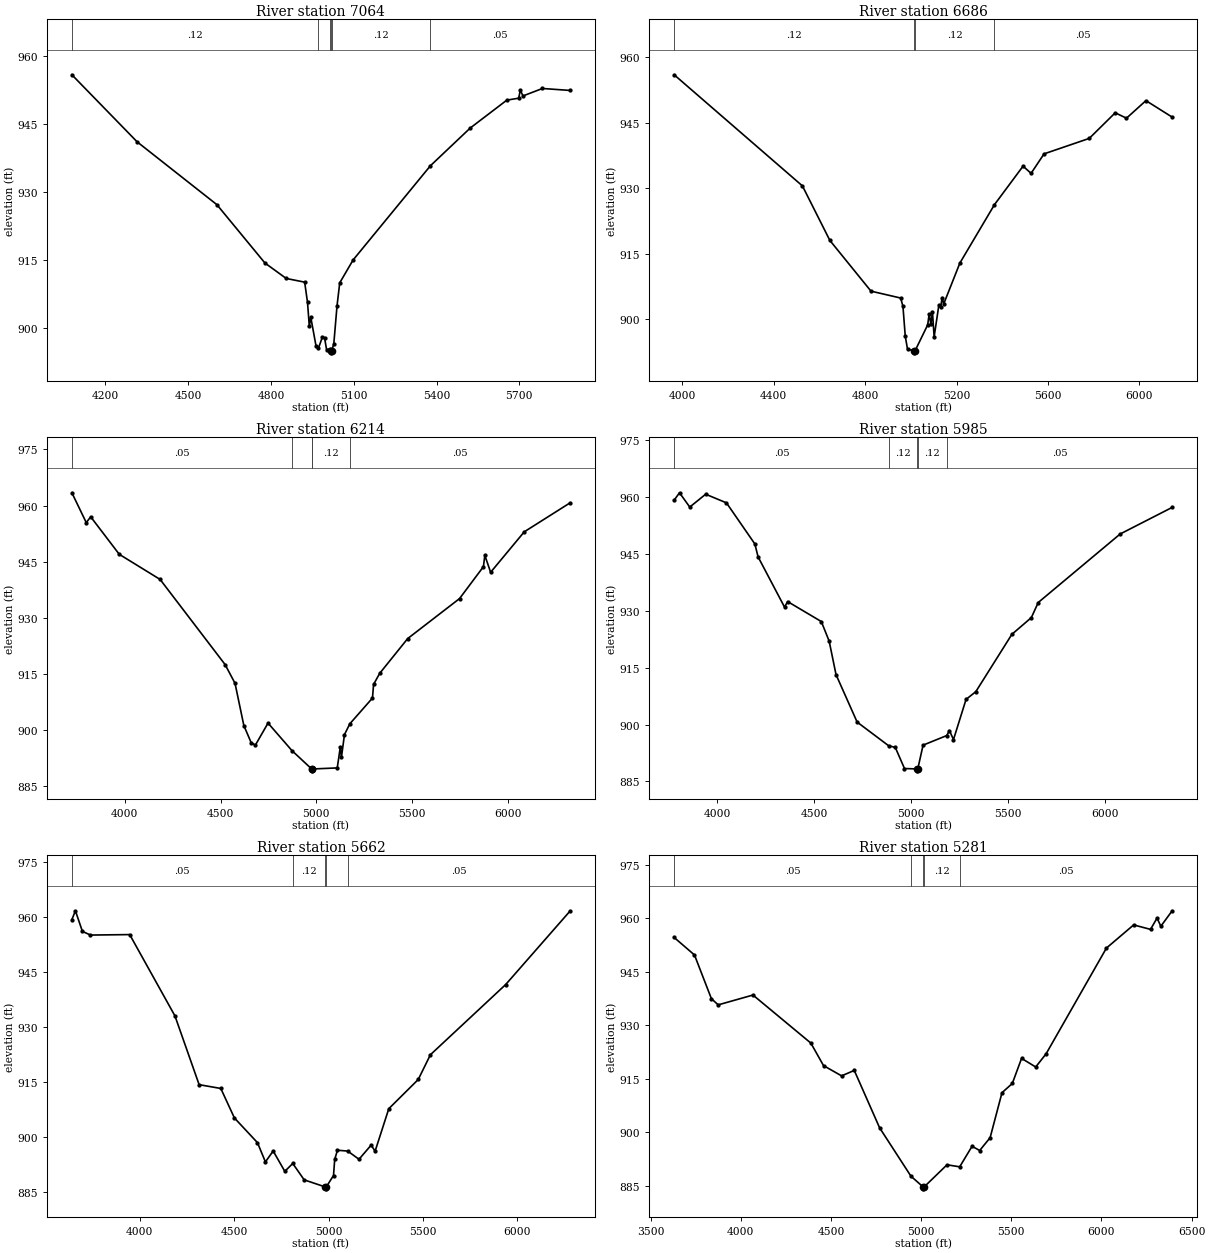
Type RM Length L Ch R = 1,7064,378,378,378
BEGIN DESCRIPTION:
Upper Denton 114 15.0
END DESCRIPTION:
XS GIS Cut Line= 3
      2234596.22      7213560.12      2234379.00      7212660.00
      2233929.91      7211904.46
#Sta/Elev= 30
  4078.3  955.94  4315.0  941.10  4603.8  927.22  4777.9  914.32  4855.1  910.90
  4922.0  910.08  4932.3  905.61  4938.9  900.29  4944.0  902.37  4963.1  895.99
  4971.8  895.45  4985.9  897.88  4994.0  897.81  5001.7  895.06  5012.1  895.34
  5015.9  894.95  5016.1  894.45  5019.9  894.95  5027.5  896.37  5039.3  904.86
  5049.1  909.93  5097.7  915.00  5377.9  935.83  5522.4  944.18  5654.9  950.34
  5697.7  950.76  5703.6  952.54  5713.3  951.26  5783.7  952.91  5883.2  952.48
#Mann=6,-1,0
  4078.3    0.12       0  4971.8    0.05       0  5012.1    0.12       0
  5015.9   0.033       0  5019.9    0.12       0  5377.9    0.05       0
Bank Sta=5015.9,5019.9
Exp/Cntr=0.3,0.1

Type RM Length L Ch R = 1,6686,472,472,472
BEGIN DESCRIPTION:
Upper Denton 114 14.0
END DESCRIPTION:
XS GIS Cut Line= 3
      2234700.38      7213591.33      2234729.00      7212560.00
      2233877.44      7211789.24
#Sta/Elev= 30
  3963.9  956.02  4525.4  930.53  4645.5  918.03  4825.6  906.39  4955.6  904.81
  4965.6  902.88  4975.6  896.08  4985.6  893.05  5014.9  892.74  5015.2  892.24
  5018.9  892.74  5073.7  898.64  5080.4  901.15  5087.9  898.75  5094.6  901.69
  5102.1  895.91  5123.0  903.27  5130.5  902.65  5137.2  904.91  5144.0  903.46
  5214.9  912.85  5366.2  926.23  5491.4  935.06  5526.5  933.41  5583.3  937.88
  5781.3  941.43  5894.9  947.30  5944.2  946.06  6029.4  950.09  6144.2  946.31
#Mann=4,-1,0
  3963.9    0.12       0  5014.9    0.07       0  5018.9    0.12       0
  5366.2    0.05       0
Bank Sta=5014.9,5018.9
Exp/Cntr=0.3,0.1

Type RM Length L Ch R = 1,6214,229,229,229
BEGIN DESCRIPTION:
Upper Denton 114 13.0
END DESCRIPTION:
XS GIS Cut Line= 3
      2235564.95      7213523.61      2235038.92      7212362.17
      2234393.54      7211201.54
#Sta/Elev= 30
  3723.0  963.41  3798.2  955.42  3821.3  956.98  3970.8  946.94  4184.2  940.22
  4524.0  917.43  4575.7  912.43  4621.9  901.12  4660.1  896.54  4682.0  895.87
  4748.3  901.78  4873.9  894.38  4976.4  889.50  4976.7  889.00  4980.4  889.50
  5110.1  889.78  5126.1  895.38  5131.8  892.57  5147.8  898.69  5175.9  901.59
  5294.2  908.48  5300.0  912.13  5332.0  915.09  5478.4  924.40  5749.4  935.10
  5874.1  943.63  5881.5  946.66  5911.8  942.13  6087.5  952.96  6326.0  960.68
#Mann=5,-1,0
  3723.0    0.05       0  4873.9    0.12       0  4976.4    0.07       0
  4980.4    0.12       0  5175.9    0.05       0
Bank Sta=4976.4,4980.4
Exp/Cntr=0.3,0.1

Type RM Length L Ch R = 1,5985,323,323,323
BEGIN DESCRIPTION:
Upper Denton 114 12.0
END DESCRIPTION:
XS GIS Cut Line= 3
      2235705.58      7213388.21      2235229.00      7212260.00
      2234434.78      7211179.92
#Sta/Elev= 30
  3779.6  959.25  3807.1  961.19  3859.9  957.42  3941.9  960.81  4049.0  958.53
  4195.2  947.69  4211.9  944.27  4348.3  931.00  4363.9  932.48  4537.5  927.21
  4577.9  922.06  4613.5  913.18  4722.1  900.67  4884.5  894.42  4918.7  893.98
  4966.1  888.41  5030.5  888.30  5030.8  887.80  5034.5  888.30  5061.8  894.58
  5183.7  897.11  5197.6  898.43  5218.5  896.05  5283.2  906.66  5333.4  908.69
  5519.3  923.83  5619.6  928.24  5655.1  932.23  6077.1  950.31  6345.0  957.33
#Mann=5,-1,0
  3779.6    0.05       0  4884.5    0.12       0  5030.5    0.07       0
  5034.5    0.12       0  5183.7    0.05       0
Bank Sta=5030.5,5034.5
Exp/Cntr=0.3,0.1

Type RM Length L Ch R = 1,5662,381,381,381
BEGIN DESCRIPTION:
Upper Denton 114 11.0
END DESCRIPTION:
XS GIS Cut Line= 3
      2235736.83      7213388.18      2235429.00      7212060.00
      2234653.76      7211050.01
#Sta/Elev= 30
  3641.2  959.31  3659.9  961.72  3696.9  956.10  3739.6  955.09  3947.3  955.22
  4186.9  933.02  4314.9  914.25  4429.7  913.21  4501.6  905.17  4623.9  898.41
  4665.8  893.16  4706.9  896.14  4768.5  890.59  4810.7  892.73  4871.1  888.26
  4983.8  886.31  4984.1  885.81  4987.8  886.31  5026.4  889.45  5032.7  893.84
  5047.2  896.35  5101.6  896.12  5161.4  893.88  5225.7  897.75  5246.6  896.08
  5319.1  907.69  5475.0  915.66  5539.3  922.41  5938.1  941.59  6277.8  961.59
#Mann=5,-1,0
  3641.2    0.05       0  4810.7    0.12       0  4983.8    0.07       0
  4987.8    0.12       0  5101.6    0.05       0
Bank Sta=4983.8,4987.8
Exp/Cntr=0.3,0.1

Type RM Length L Ch R = 1,5281,356,356,356
BEGIN DESCRIPTION:
Upper Denton 114 10.0
END DESCRIPTION:
XS GIS Cut Line= 3
      2235882.67      7213325.69      2235779.00      7211960.00
      2235018.27      7210794.76
#Sta/Elev= 30
  3630.7  954.65  3743.4  949.74  3837.0  937.49  3874.7  935.74  4067.6  938.50
  4388.6  925.01  4458.8  918.69  4559.1  915.81  4629.3  917.34  4769.7  901.24
  4943.7  887.64  5011.9  884.60  5012.1  884.10  5015.9  884.60  5143.6  890.85
  5213.8  890.28  5282.4  896.05  5324.6  894.86  5382.5  898.45  5448.3  911.08
  5505.6  913.68  5556.9  920.72  5635.3  918.30  5693.0  922.01  6027.4  951.68
  6178.4  958.18  6271.9  956.93  6308.1  960.10  6329.2  957.81  6391.9  962.15
#Mann=5,-1,0
  3630.7    0.05       0  4943.7    0.12       0  5011.9    0.07       0
  5015.9    0.12       0  5213.8    0.05       0
Bank Sta=5011.9,5015.9
Exp/Cntr=0.3,0.1

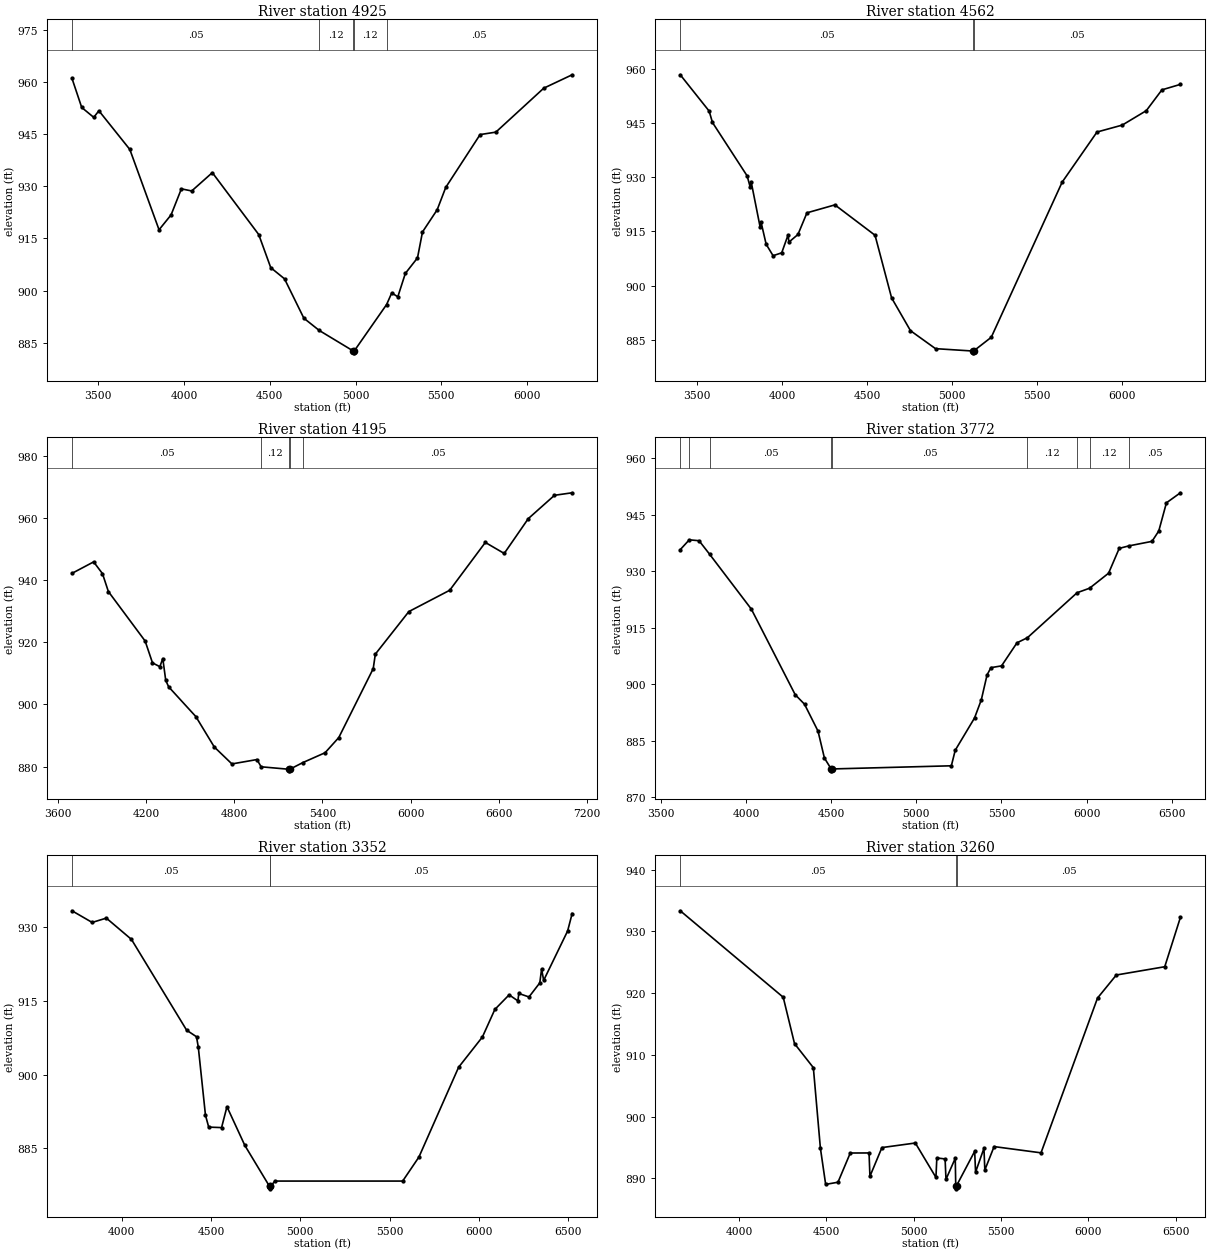
Type RM Length L Ch R = 1,4925,363,363,363
BEGIN DESCRIPTION:
Upper Denton 114 9.0
END DESCRIPTION:
XS GIS Cut Line= 4
      2235955.58      7213346.57      2236044.13      7211825.72
      2235979.00      7211710.00      2235226.41      7210700.71
#Sta/Elev= 30
  3347.5  961.02  3404.2  952.66  3474.3  949.81  3504.3  951.71  3684.6  940.58
  3854.9  917.48  3925.0  921.75  3985.1  929.25  4045.3  928.64  4165.5  933.91
  4435.9  916.11  4506.0  906.58  4586.2  903.37  4699.0  892.04  4788.9  888.51
  4988.0  882.58  4988.3  882.08  4992.0  882.58  5181.2  895.97  5211.2  899.31
  5246.6  898.20  5290.4  904.92  5361.3  909.39  5390.4  916.85  5476.0  923.23
  5526.0  929.67  5726.2  944.86  5817.9  945.56  6097.3  958.21  6262.7  962.06
#Mann=5,-1,0
  3347.5    0.05       0  4788.9    0.12       0  4988.0    0.07       0
  4992.0    0.12       0  5181.2    0.05       0
Bank Sta=4988,4992
Exp/Cntr=0.3,0.1

Type RM Length L Ch R = 1,4562,367,367,367
BEGIN DESCRIPTION:
Upper Denton 114 8.0
END DESCRIPTION:
XS GIS Cut Line= 3
      2236038.92      7213237.17      2236329.00      7211660.00
      2235383.33      7210711.79
#Sta/Elev= 30
  3401.5  958.43  3571.5  948.37  3591.1  945.20  3795.2  930.39  3813.5  927.21
  3818.6  928.80  3871.6  916.19  3876.7  917.63  3907.0  911.44  3947.7  908.27
  3998.5  909.07  4035.9  914.02  4041.0  912.04  4094.0  914.15  4147.1  920.16
  4311.4  922.36  4547.6  913.94  4645.0  896.58  4756.2  887.48  4903.4  882.50
  5123.3  881.84  5123.6  881.34  5127.3  881.84  5231.4  885.65  5648.6  928.67
  5853.6  942.56  6002.1  944.48  6143.6  948.48  6235.5  954.25  6344.3  955.77
#Mann=3,-1,0
  3401.5    0.05       0  5123.3   0.033       0  5127.3    0.05       0
Bank Sta=5123.3,5127.3
Exp/Cntr=0.3,0.1

Type RM Length L Ch R = 1,4195,423,423,423
BEGIN DESCRIPTION:
Upper Denton 114 7.0
END DESCRIPTION:
XS GIS Cut Line= 3
      2236721.12      7212917.25      2236679.00      7211610.00
      2235028.41      7210321.81
#Sta/Elev= 30
  3697.1  942.15  3844.4  945.84  3904.5  942.06  3944.5  936.31  4194.6  920.39
  4244.6  913.37  4294.7  912.14  4314.7  914.76  4334.7  907.74  4354.7  905.65
  4539.5  896.10  4664.9  886.32  4784.9  880.87  4955.0  882.28  4983.5  879.95
  5174.0  879.15  5174.2  878.65  5178.0  879.15  5267.0  881.30  5418.4  884.47
  5511.6  889.35  5745.8  911.51  5760.3  916.18  5988.2  929.86  6265.9  936.71
  6508.3  952.09  6636.8  948.55  6800.5  959.75  6978.7  967.25  7098.8  968.06
#Mann=5,-1,0
  3697.1    0.05       0  4983.5    0.12       0  5174.0    0.07       0
  5178.0    0.12       0  5267.0    0.05       0
Bank Sta=5174,5178
Exp/Cntr=0.3,0.1

Type RM Length L Ch R = 1,3772,420,420,420
BEGIN DESCRIPTION:
Upper Denton 114 6.0
END DESCRIPTION:
XS GIS Cut Line= 3
      2237007.58      7212739.36      2236829.00      7211360.00
      2236161.24      7209965.95
#Sta/Elev= 30
  3614.0  935.76  3667.1  938.37  3724.5  938.13  3786.2  934.55  4031.6  919.94
  4288.9  897.22  4343.6  894.69  4422.9  887.54  4460.4  880.39  4500.2  877.48
  4500.4  876.98  4504.2  877.48  5205.8  878.32  5228.5  882.45  5341.8  891.02
  5381.6  895.84  5415.3  902.45  5438.0  904.40  5500.4  904.87  5591.1  911.00
  5652.5  912.36  5944.0  924.31  6017.3  925.51  6128.9  929.50  6191.3  936.09
  6247.3  936.75  6383.8  937.96  6423.5  940.71  6468.5  948.20  6550.6  950.87
#Mann=9,-1,0
  3614.0    0.05       0  3667.1    0.12       0  3786.2    0.05       0
  4500.2   0.033       0  4504.2    0.05       0  5652.5    0.12       0
  5944.0    0.05       0  6017.3    0.12       0  6247.3    0.05       0
Bank Sta=4500.2,4504.2
Exp/Cntr=0.3,0.1

Type RM Length L Ch R = 1,3352,92,92,92
BEGIN DESCRIPTION:
Upper Denton 114 5.0
END DESCRIPTION:
XS GIS Cut Line= 5
      2237037.96      7212752.36      2237252.07      7212118.57
      2237202.89      7211511.05      2237189.87      7211207.23
      2237367.81      7210000.67
#Sta/Elev= 30
  3720.7  933.32  3833.7  930.95  3913.2  931.83  4053.9  927.50  4363.1  909.04
  4418.3  907.71  4428.4  905.59  4468.5  891.77  4486.6  889.34  4558.8  889.24
  4588.9  893.49  4689.2  885.61  4827.5  877.29  4827.9  876.79  4831.9  877.29
  4858.1  878.37  5573.4  878.37  5664.4  883.25  5886.8  901.51  6020.1  907.66
  6089.8  913.26  6169.8  916.23  6218.9  915.00  6224.0  916.51  6281.0  915.80
  6341.6  918.66  6351.7  921.47  6363.3  919.17  6497.5  929.21  6522.9  932.76
#Mann=3,-1,0
  3720.7    0.05       0  4827.5   0.033       0  4831.9    0.05       0
Bank Sta=4827.5,4831.9
Exp/Cntr=0.3,0.1

Type RM Length L Ch R = 1,3260,94,94,94
BEGIN DESCRIPTION:
Upper Denton 114 4.5
END DESCRIPTION:
XS GIS Cut Line= 6
      2237037.94      7212752.39      2237372.16      7212170.77
      2237294.03      7211506.71      2237281.01      7211341.77
      2237389.52      7210751.50      2237428.51      7209993.47
#Sta/Elev= 30
  3663.9  933.32  4253.6  919.32  4318.3  911.81  4426.1  907.92  4466.4  894.90
  4496.6  889.02  4567.1  889.37  4637.6  894.10  4745.1  894.11  4750.1  890.33
  4818.8  894.98  5010.1  895.72  5128.1  890.15  5133.2  893.30  5180.5  893.14
  5185.6  889.84  5238.7  893.24  5241.5  888.80  5241.9  888.30  5245.9  888.80
  5349.9  894.37  5355.0  891.01  5403.0  894.86  5408.1  891.35  5461.1  895.14
  5729.8  894.13  6053.4  919.19  6161.0  922.92  6438.3  924.26  6528.0  932.25
#Mann=3,-1,0
  3663.9    0.05       0  5241.5   0.033       0  5245.9    0.05       0
Bank Sta=5241.5,5245.9
Exp/Cntr=0.3,0.1

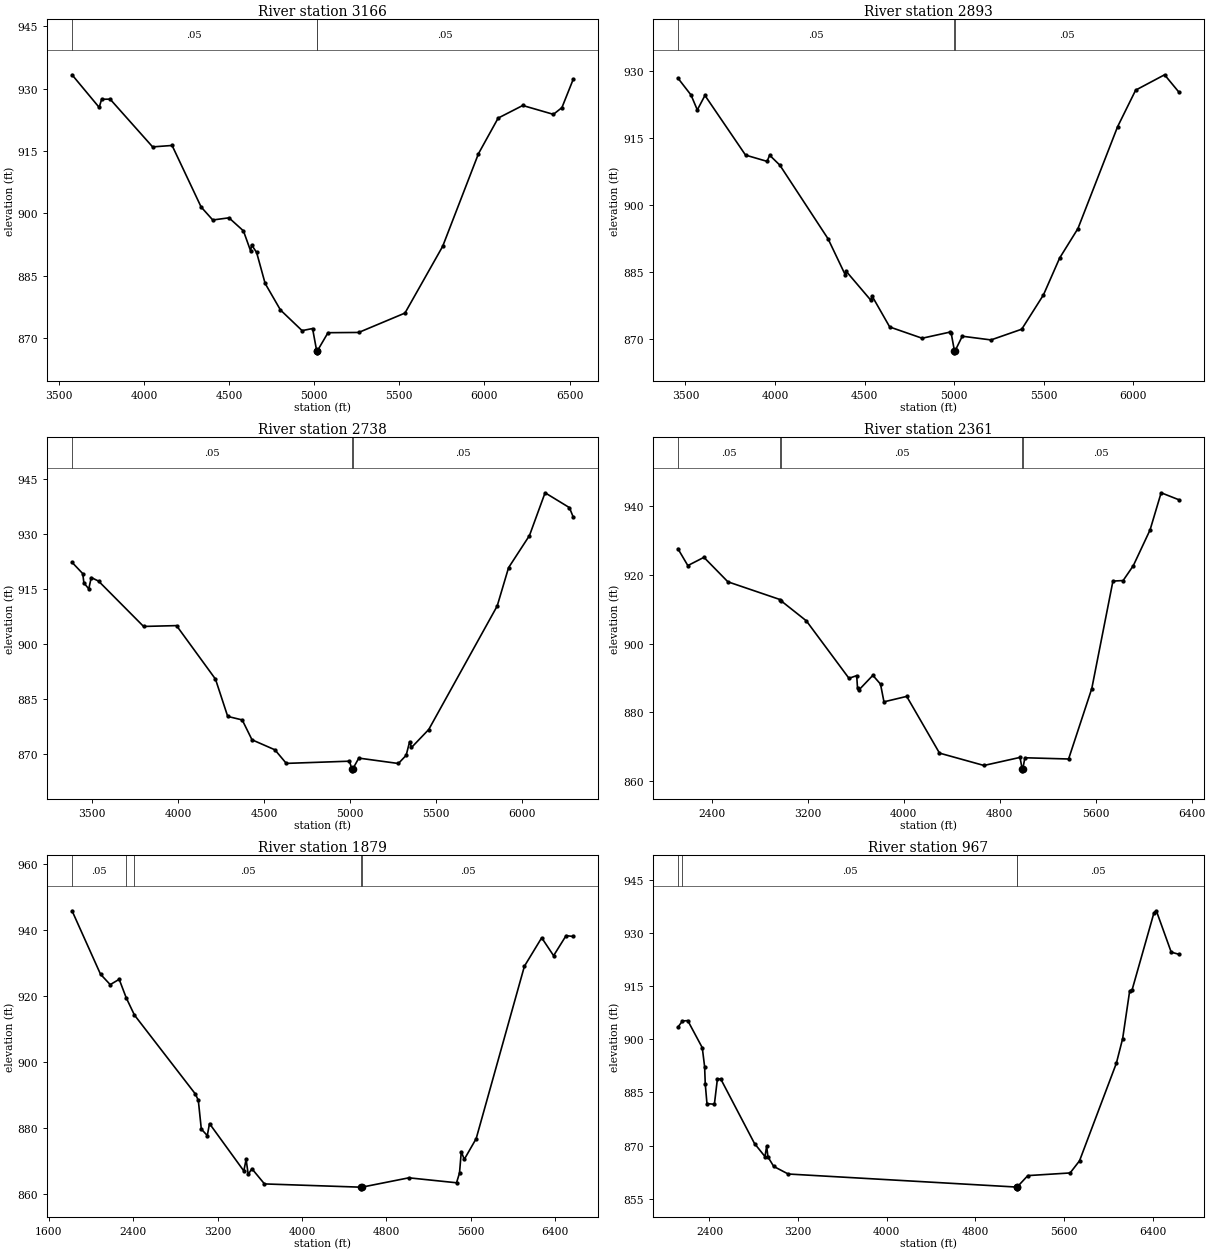
Type RM Length L Ch R = 1,3166,273,273,273
BEGIN DESCRIPTION:
Upper Denton 114 4.4
END DESCRIPTION:
XS GIS Cut Line= 6
      2237037.98      7212752.33      2237528.41      7212105.66
      2237385.18      7211493.68      2237389.52      7211294.03
      2237454.63      7210738.48      2237428.64      7209993.51
#Sta/Elev= 30
  3577.1  933.32  3736.5  925.48  3751.0  927.44  3800.9  927.46  4050.5  915.99
  4164.9  916.33  4335.5  901.54  4403.9  898.42  4499.1  898.94  4584.1  895.80
  4626.5  890.95  4631.7  892.44  4661.5  890.62  4711.5  883.17  4801.6  876.79
  4928.6  871.83  4990.2  872.33  5014.3  866.99  5014.7  866.49  5018.7  866.99
  5080.9  871.33  5261.3  871.39  5533.1  876.05  5754.6  892.09  5964.9  914.36
  6080.5  922.91  6225.0  925.94  6405.1  923.81  6455.2  925.43  6521.7  932.25
#Mann=3,-1,0
  3577.1    0.05       0  5014.3    0.04       0  5018.7    0.05       0
Bank Sta=5014.3,5018.7
Exp/Cntr=0.3,0.1

Type RM Length L Ch R = 1,2893,155,155,155
BEGIN DESCRIPTION:
Upper Denton 114 4.0
END DESCRIPTION:
XS GIS Cut Line= 4
      2237103.09      7212717.61      2237715.88      7212028.03
      2237628.24      7211402.54      2237454.63      7210169.92
#Sta/Elev= 30
  3457.6  928.48  3531.1  924.68  3566.2  921.34  3608.9  924.58  3835.5  911.23
  3955.9  909.82  3970.1  911.20  4027.0  908.98  4296.3  892.49  4393.5  884.32
  4398.5  885.17  4536.2  878.68  4541.3  879.73  4640.7  872.74  4821.7  870.22
  4974.6  871.57  4984.0  871.34  5001.9  867.45  5002.4  866.95  5006.4  867.45
  5045.9  870.67  5206.2  869.84  5377.8  872.24  5499.0  879.91  5589.9  888.20
  5691.7  894.77  5913.1  917.57  6014.1  925.77  6175.6  929.21  6256.5  925.28
#Mann=3,-1,0
  3457.6    0.05       0  5001.9    0.04       0  5006.4    0.05       0
Bank Sta=5001.9,5006.4
Exp/Cntr=0.3,0.1

Type RM Length L Ch R = 1,2738,377,377,377
BEGIN DESCRIPTION:
Upper Denton 114 3.5
END DESCRIPTION:
XS GIS Cut Line= 4
      2237159.47      7212748.05      2237860.98      7211958.32
      2237775.81      7211350.46      2237602.20      7210117.84
#Sta/Elev= 30
  3383.0  922.28  3445.3  919.20  3452.0  916.65  3480.4  915.05  3494.7  918.14
  3537.3  917.16  3799.1  904.81  3990.6  905.04  4217.2  890.46  4288.3  880.30
  4372.7  879.34  4429.6  873.93  4562.8  871.20  4629.1  867.50  4996.1  868.10
  5010.9  865.97  5011.4  865.47  5015.4  865.97  5050.8  868.94  5281.0  867.47
  5326.2  869.70  5346.4  873.43  5357.2  871.83  5457.5  876.73  5855.6  910.38
  5921.7  920.82  6043.3  929.58  6134.1  941.23  6275.5  937.19  6297.9  934.61
#Mann=3,-1,0
  3383.0    0.05       0  5010.9   0.033       0  5015.4    0.05       0
Bank Sta=5010.9,5015.4
Exp/Cntr=0.3,0.1

Type RM Length L Ch R = 1,2361,482,482,482
BEGIN DESCRIPTION:
Upper Denton 114 3.0
END DESCRIPTION:
XS GIS Cut Line= 4
      2236462.40      7213499.79      2237837.44      7212381.71
      2238129.00      7211310.00      2237667.29      7210100.43
#Sta/Elev= 30
  2117.1  927.58  2200.2  922.66  2334.5  925.05  2534.2  917.94  2967.7  912.80
  2977.4  912.42  3187.8  906.61  3543.4  889.90  3607.8  890.69  3614.5  887.09
  3628.8  886.61  3742.3  890.77  3806.2  888.22  3835.0  883.07  4024.6  884.65
  4297.9  868.17  4668.4  864.58  4968.9  866.92  4987.4  863.52  4987.8  863.02
  4991.9  863.52  5009.7  866.82  5373.9  866.46  5567.3  886.94  5743.5  918.15
  5828.4  918.31  5913.3  922.63  6052.9  933.01  6145.3  943.81  6294.7  941.76
#Mann=5,-1,0
  2117.1    0.05       0  2967.7    0.12       0  2977.4    0.05       0
  4987.4    0.04       0  4991.9    0.05       0
Bank Sta=4987.4,4991.9
Exp/Cntr=0.3,0.1

Type RM Length L Ch R = 1,1879,912,912,912
BEGIN DESCRIPTION:
Upper Denton 114 2.0
END DESCRIPTION:
XS GIS Cut Line= 4
      2237052.73      7213895.58      2238184.66      7212666.43
      2238579.00      7211210.00      2237894.37      7209794.27
#Sta/Elev= 30
  1820.2  945.91  2090.3  926.68  2182.2  923.53  2267.3  925.14  2334.1  919.52
  2411.9  914.31  2989.2  890.40  3017.5  888.48  3045.9  879.76  3102.6  877.78
  3123.6  881.41  3449.1  867.06  3470.7  870.58  3490.7  866.00  3525.3  867.75
  3644.9  863.13  4562.8  862.14  4563.2  861.64  4567.3  862.14  5014.1  864.98
  5465.9  863.48  5494.1  866.42  5511.0  872.91  5539.3  870.57  5652.2  876.86
  6109.7  929.12  6273.4  937.73  6386.3  932.30  6504.8  938.38  6572.6  938.12
#Mann=5,-1,0
  1820.2    0.05       0  2334.1    0.12       0  2411.9    0.05       0
  4562.8   0.033       0  4567.3    0.05       0
Bank Sta=4562.8,4567.3
Exp/Cntr=0.3,0.1

Type RM Length L Ch R = 1,967,746,746,746
BEGIN DESCRIPTION:
Upper Denton 114 1.0
END DESCRIPTION:
XS GIS Cut Line= 3
      2237795.76      7213409.49      2239329.00      7210960.00
      2238144.51      7209834.53
#Sta/Elev= 30
  2114.9  903.40  2156.6  905.15  2204.3  905.26  2335.2  897.63  2356.4  892.28
  2362.3  887.35  2377.6  881.86  2444.6  881.68  2471.9  888.83  2502.5  888.78
  2806.7  870.62  2901.0  866.94  2916.3  869.83  2928.3  866.82  2980.0  864.16
  3110.8  862.02  5172.0  858.34  5172.5  857.84  5176.8  858.34  5273.5  861.57
  5655.3  862.32  5740.2  865.74  6072.7  893.25  6129.4  900.18  6192.9  913.65
  6214.3  913.88  6412.1  935.66  6433.5  936.22  6567.8  924.56  6638.6  923.94
#Mann=4,-1,0
  2114.9    0.12       0  2156.6    0.05       0  5172.0   0.033       0
  5176.8    0.05       0
Bank Sta=5172,5176.8
Exp/Cntr=0.3,0.1

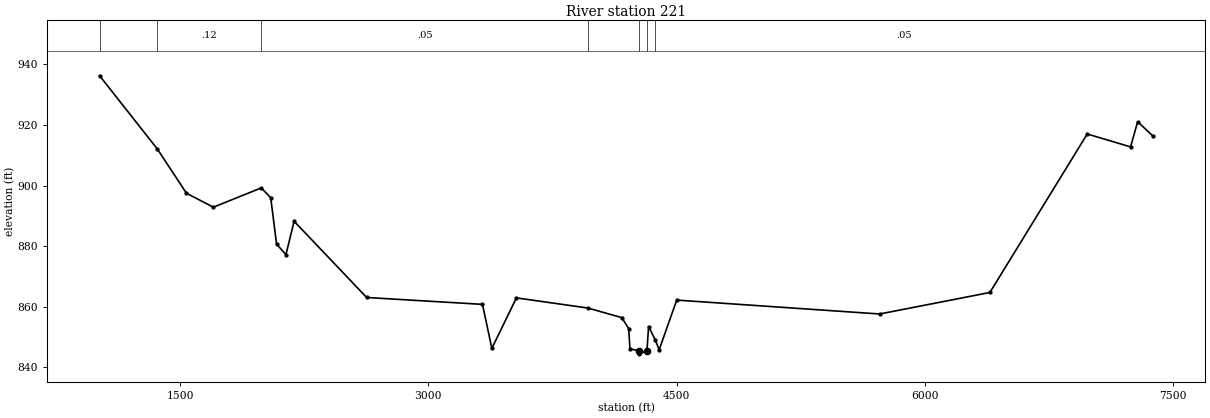
Type RM Length L Ch R = 1,221,0,0,0
BEGIN DESCRIPTION:
Upper Denton 114 0.5
END DESCRIPTION:
XS GIS Cut Line= 4
      2237240.79      7214124.03      2239941.61      7211433.79
      2239968.56      7211146.39      2238265.88      7209654.25
#Sta/Elev= 30
  1013.4  936.24  1362.6  912.03  1538.2  897.44  1700.9  892.84  1990.4  899.21
  2047.4  895.96  2082.7  880.67  2139.3  877.17  2188.8  888.19  2627.2  863.02
  3327.2  860.75  3383.8  846.22  3532.3  862.89  3965.0  859.53  4168.7  856.37
  4211.1  852.73  4218.2  846.10  4271.0  845.41  4275.0  844.41  4321.0  845.41
  4331.3  853.42  4370.3  849.13  4395.0  845.75  4501.0  862.16  5727.5  857.57
  6393.7  864.67  6982.1  917.02  7244.0  912.75  7286.7  921.07  7378.1  916.40
#Mann=7,-1,0
  1013.4    0.05       0  1362.6    0.12       0  1990.4    0.05       0
  3965.0    0.12       0  4271.0   0.033       0  4321.0    0.12       0
  4370.3    0.05       0
Bank Sta=4271,4321
Exp/Cntr=0.3,0.1

Chan Stop Cuts=-1