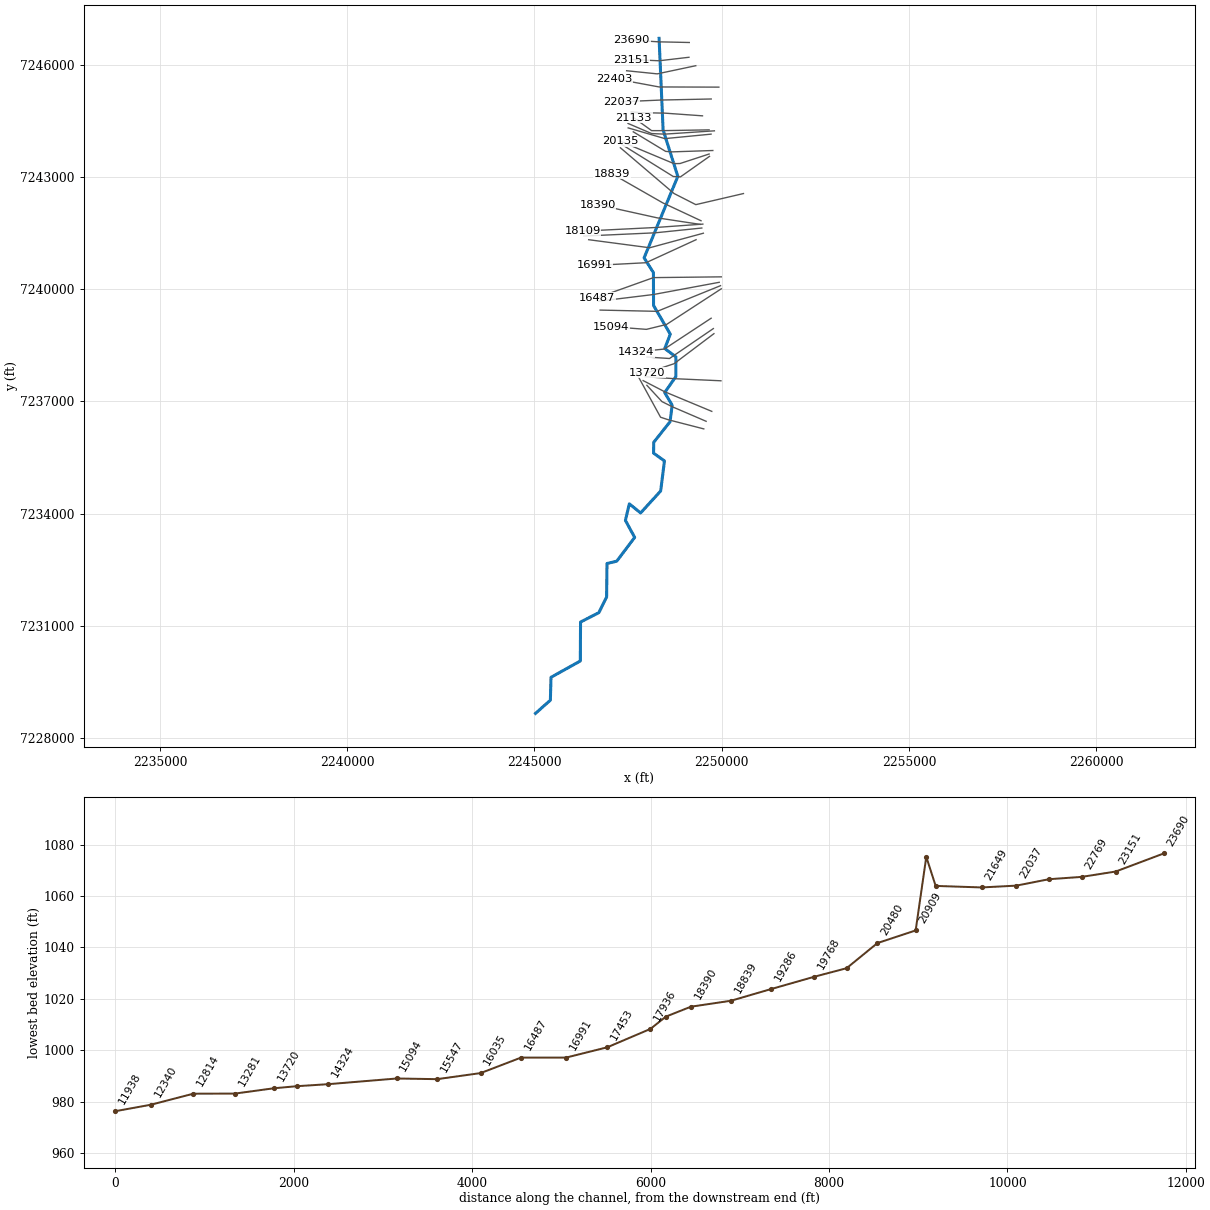
--- Upper Denton 115.prj (project) ---

Proj Title=Upper Denton 115 Base Level Engineering
Current Plan=p01
Default Exp/Contr=0.3,0.1
English Units
Geom File=g01
Flow File=f01
Plan File=p01
Y Axis Title=Elevation
X Axis Title(PF)=Main Channel Distance
X Axis Title(XS)=Station
BEGIN DESCRIPTION:
Upper Denton 115
END DESCRIPTION:
DSS Export Rating Curves= 0
DSS Export Rating Curve Sorted= 0
DSS Export Volume Flow Curves= 0
DXF OffsetX= 0
DXF OffsetY= 0
DXF ScaleX= 1
DXF ScaleY= 10

--- Upper Denton 115.p01 (plan) ---

Plan Title=Multiple Run
Short Identifier=Multiple
Geom File=g01
Flow File=f01
Subcritical Flow
K Sum by GR= 0
Std Step Tol= 0.01
Critical Tol= 0.01
Num of Std Step Trials= 20
Max Error Tol= 0.3
Flow Tol Ratio= 0.001
Split Flow NTrial= 30
Split Flow Tol= 0.02
Split Flow Ratio= 0.02
Log Output Level= 0
Friction Slope Method= 1
Unsteady Friction Slope Method= 2
Unsteady Bridges Friction Slope Method= 1
Parabolic Critical Depth
Global Vel Dist=  1 , 1 , 1
Global Log Level= 0
CheckData=True
Encroach Param= -1, 0, 0, 0
BEGIN DESCRIPTION:
Multiple Run
END DESCRIPTION:

--- Upper Denton 115.f01 (steady flow) ---

Flow Title=Multiple
Program Version=4.10
Number of Profiles= 8
Profile Names=5-year,10-year,25-year,50-year,1pct_min,100-year,1pct_plu,500-year
River Rch & RM=Upper Denton 115,Reach-1         ,23690
     523     712    1002    1248     773    1541    3076    2358
River Rch & RM=Upper Denton 115,Reach-1         ,20480
     662     910    1299    1634    1020    2036    4062    3170
River Rch & RM=Upper Denton 115,Reach-1         ,19286
     912    1269    1837    2332    1468    2928    5843    4633
River Rch & RM=Upper Denton 115,Reach-1         ,13720
    1157    1624    2377    3038    1924    3839    7659    6152
River Rch & RM=Upper Denton 115,Reach-1         ,10968
    1319    1859    2735    3507    2227    4444    8866    7160
River Rch & RM=Upper Denton 115,Reach-1         ,6847
    1425    2009    2957    3793    2407    4803    9582    7732
Boundary for River Rch & Prof#=Upper Denton 115,Reach-1         , 1
Up Type= 0
Dn Type= 3
Dn Slope=0.01
Boundary for River Rch & Prof#=Upper Denton 115,Reach-1         , 2
Up Type= 0
Dn Type= 3
Dn Slope=0.01
Boundary for River Rch & Prof#=Upper Denton 115,Reach-1         , 3
Up Type= 0
Dn Type= 3
Dn Slope=0.01
Boundary for River Rch & Prof#=Upper Denton 115,Reach-1         , 4
Up Type= 0
Dn Type= 3
Dn Slope=0.01
Boundary for River Rch & Prof#=Upper Denton 115,Reach-1         , 5
Up Type= 0
Dn Type= 3
Dn Slope=0.01
Boundary for River Rch & Prof#=Upper Denton 115,Reach-1         , 6
Up Type= 0
Dn Type= 3
Dn Slope=0.01
Boundary for River Rch & Prof#=Upper Denton 115,Reach-1         , 7
Up Type= 0
Dn Type= 3
Dn Slope=0.01
Boundary for River Rch & Prof#=Upper Denton 115,Reach-1         , 8
Up Type= 0
Dn Type= 3
Dn Slope=0.01
DSS Import GetInterval= 0
DSS Import GetPeak= 0
DSS Import FillOption= 0

--- Upper Denton 115.g01 (geometry) ---

Geom Title=Existing Conditions
Program Version=4.10

River Reach=Upper Denton 115,Reach-1
Reach XY= 30
        2248329.        7246710.      2248436.56        7244260.
       2248829.5      7243019.26      2247928.69      7240839.82
       2248178.1      7240445.29      2248181.35      7239565.52
       2248627.8      7238799.48      2248480.96      7238415.66
      2248778.93      7238191.77      2248776.66      7237665.52
      2248478.69      7237239.66      2248677.81      7236900.39
      2248621.46      7236456.84      2248186.52      7235910.04
      2248181.98      7235618.34       2248472.1        7235410.
       2248371.4      7234606.66      2247835.66      7234018.95
      2247534.34      7234262.74      2247429.69      7233819.62
      2247676.83      7233365.44      2247199.48      7232729.61
      2246937.84      7232667.05       2246927.8       7231770.5
      2246721.19      7231353.79      2246231.81      7231102.04
      2246225.57      7230061.23      2245442.44      7229623.64
      2245425.97      7229011.98        2245029.        7228660.

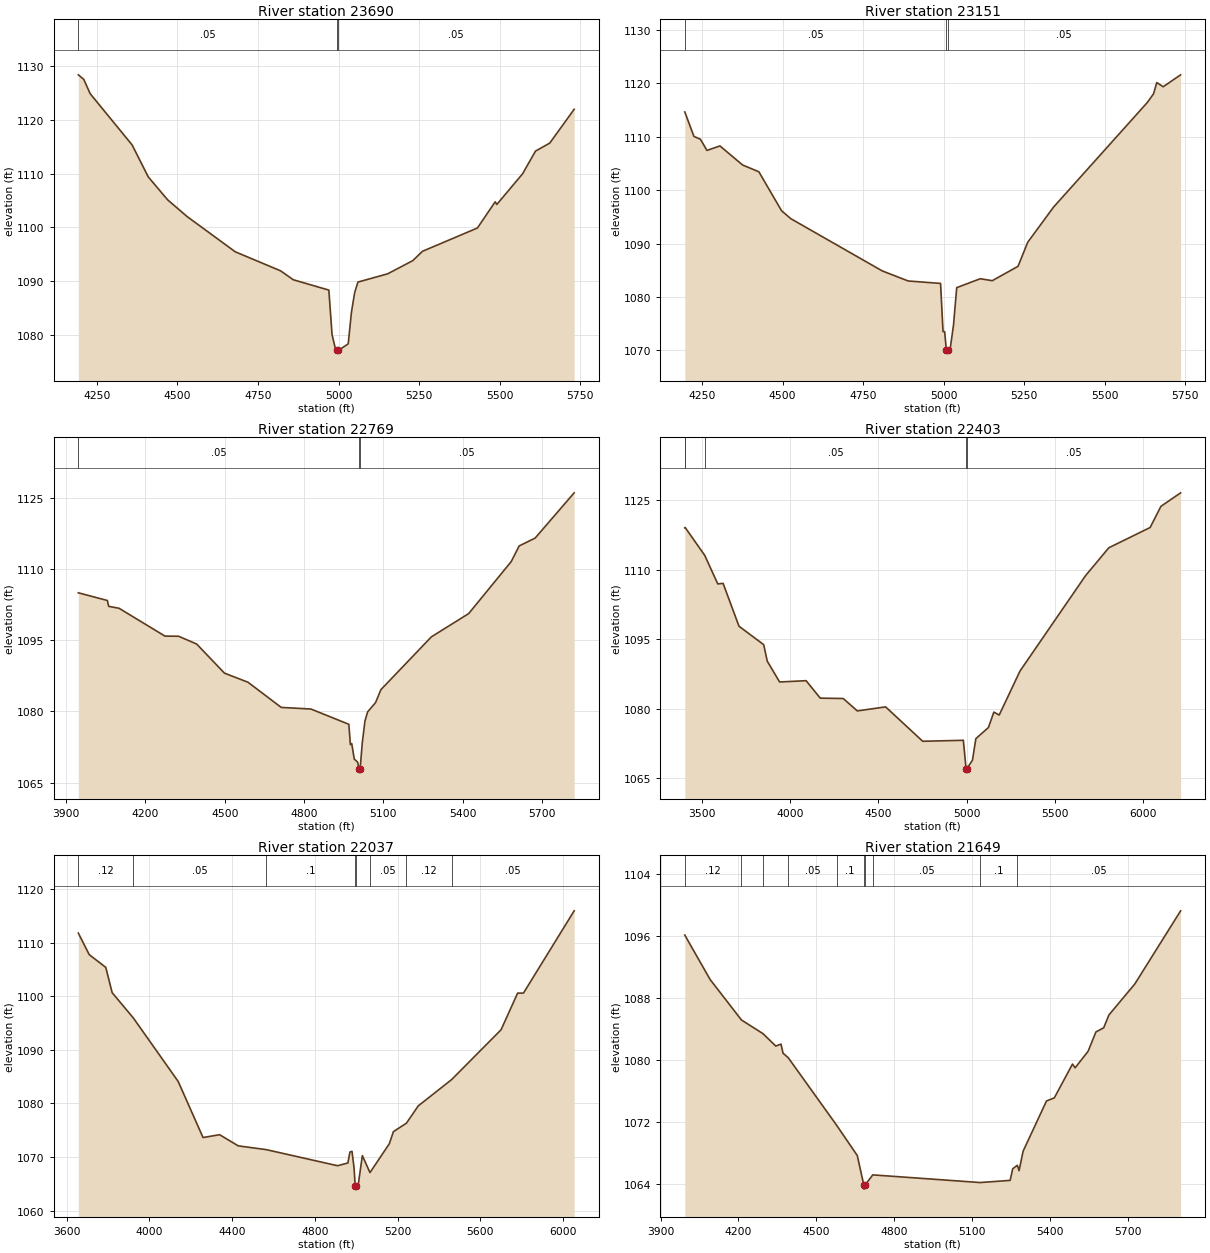
Type RM Length L Ch R = 1 ,23690   ,539,539,539
BEGIN DESCRIPTION:
Upper Denton 115 50.0
END DESCRIPTION:
XS GIS Cut Line= 3
      2249135.83      7246598.78      2248328.58      7246616.14
       2247599.4      7246659.54
#Sta/Elev= 30
    4193 1128.42  4209.8 1127.58  4229.8  1124.9  4359.9 1115.35  4409.9  1109.4
  4469.9 1105.13  4529.9 1102.03  4679.9 1095.43    4820  1091.9    4860 1090.22
    4970  1088.3    4980    1080    4990 1077.46  4995.7 1077.05    4996 1076.55
  4999.7 1077.05  5030.1 1078.28  5040.1 1084.17  5050.1 1087.83  5060.1 1089.79
  5152.4 1091.33  5230.4 1093.79  5260.5 1095.53  5430.8 1099.87    5486 1104.75
    5491 1104.26    5571 1109.98  5611.1 1114.21  5655.3  1115.7  5730.9    1122
#Mann= 3 ,-1 , 0
    4193     .05       0  4995.7    .033       0  4999.7     .05       0
Bank Sta=4995.7,4999.7
XS Rating Curve= 0 ,0
Exp/Cntr=0.3,0.1

Type RM Length L Ch R = 1 ,23151   ,382,382,382
BEGIN DESCRIPTION:
Upper Denton 115 49.0
END DESCRIPTION:
XS GIS Cut Line= 3
      2249127.21      7246203.81        2248329.        7246110.
      2247595.05      7246143.05
#Sta/Elev= 30
  4196.8 1114.65  4225.2 1110.07  4245.3 1109.54  4265.5 1107.45  4305.8 1108.29
  4376.2 1104.72  4426.6 1103.45  4497.1 1096.15  4525.8 1094.67  4809.2  1084.9
  4889.7 1083.01  4990.4 1082.55    4998 1073.53    5003 1073.53  5008.5    1070
  5008.8  1069.5  5012.5    1070  5020.5 1070.42  5030.5 1074.75  5040.5 1081.76
  5113.6 1083.43  5150.7 1083.06  5230.7 1085.75  5260.8 1090.25  5340.8 1096.83
  5631.1 1116.37  5651.2 1118.04  5661.2 1120.15  5681.2 1119.37  5735.2  1121.6
#Mann= 3 ,-1 , 0
  4196.8     .05       0  5008.5    .033       0  5012.5     .05       0
Bank Sta=5008.5,5012.5
XS Rating Curve= 0 ,0
Exp/Cntr=0.3,0.1

Type RM Length L Ch R = 1 ,22769   ,366,366,366
BEGIN DESCRIPTION:
Upper Denton 115 48.0
END DESCRIPTION:
XS GIS Cut Line= 3
      2249309.45      7245978.11        2248279.        7245760.
      2247462.23      7245843.39
#Sta/Elev= 30
  3946.7 1105.03  4056.4 1103.41  4061.5 1102.17  4100.5 1101.77  4274.3 1095.89
  4325.4 1095.87  4394.1 1094.22  4499.1 1088.08  4587.8 1086.17  4713.8 1080.85
    4826 1080.51  4969.3 1077.29  4975.1 1073.01  4980.2 1073.23  4989.8 1069.95
  5002.5 1069.31    5008 1067.91  5008.3 1067.41    5012 1067.91  5020.1 1073.39
  5030.1 1077.96  5040.2  1079.9  5070.3 1081.87  5090.5  1084.6  5281.4 1095.74
  5422.2 1100.64    5583 1111.61  5613.2 1114.92  5673.5 1116.57    5821 1126.12
#Mann= 3 ,-1 , 0
  3946.7     .05       0    5008    .033       0    5012     .05       0
Bank Sta=5008,5012
XS Rating Curve= 0 ,0
Exp/Cntr=0.3,0.1

Type RM Length L Ch R = 1 ,22403   ,366,366,366
BEGIN DESCRIPTION:
Upper Denton 115 47.0
END DESCRIPTION:
XS GIS Cut Line= 3
      2249925.82       7245405.2        2248329.        7245410.
      2247139.36      7245630.89
#Sta/Elev= 30
  3403.5 1119.09  3405.8 1119.14  3516.3 1113.13  3590.3 1106.96  3620.3 1107.08
  3710.3 1097.82  3850.3 1093.83  3870.3 1090.27  3940.3 1085.77  4090.3 1086.05
  4170.3 1082.28  4300.3  1082.2  4380.3 1079.52  4540.3 1080.39  4750.3 1072.96
  4980.3 1073.17  4995.8 1067.01  4996.1 1066.51  4999.8 1067.01  5031.8 1068.86
  5051.2 1073.53  5122.4 1075.93  5152.9 1079.26  5183.4 1078.63    5301 1088.13
  5671.6 1108.72  5803.8 1114.77  6037.8 1119.15  6098.8 1123.72  6210.3 1126.64
#Mann= 5 ,-1 , 0
  3403.5     .05       0  3405.8     .12       0  3516.3     .05       0
  4995.8    .033       0  4999.8     .05       0
Bank Sta=4995.8,4999.8
XS Rating Curve= 0 ,0
Exp/Cntr=0.3,0.1

Type RM Length L Ch R = 1 ,22037   ,388,388,388
BEGIN DESCRIPTION:
Upper Denton 115 46.0
END DESCRIPTION:
XS GIS Cut Line= 3
      2249721.81      7245088.36        2248379.        7245060.
      2247325.99      7245014.58
#Sta/Elev= 30
  3656.9  1111.8  3709.7 1107.78  3789.7  1105.4  3820.4 1100.69  3923.4 1095.93
  4139.8  1084.1  4259.8 1073.64  4339.9 1074.17  4429.9 1072.09  4565.7 1071.38
    4910 1068.38    4960 1068.89    4970 1070.94    4980 1071.06    4990 1067.95
  4995.5 1064.51  4995.8 1064.01  4999.5 1064.51    5010 1064.79    5030 1070.27
  5066.9  1067.1  5160.2 1072.47  5180.2 1074.74  5243.3 1076.33  5300.3 1079.55
  5461.4 1084.45  5700.7 1093.76  5780.7  1100.6  5808.9  1100.6    6054 1115.96
#Mann= 8 ,-1 , 0
  3656.9     .12       0  3923.4     .05       0  4565.7      .1       0
  4995.5     .07       0  4999.5      .1       0  5066.9     .05       0
  5243.3     .12       0  5461.4     .05       0
Bank Sta=4995.5,4999.5
XS Rating Curve= 0 ,0
Exp/Cntr=0.3,0.1

Type RM Length L Ch R = 1 ,21649   ,516,516,516
BEGIN DESCRIPTION:
Upper Denton 115 45.0
END DESCRIPTION:
XS GIS Cut Line= 3
       2249488.3      7244637.84        2248479.        7244710.
      2247583.02      7244726.36
#Sta/Elev= 30
  3993.4 1096.11  4090.9 1090.37  4211.4 1085.15  4294.4 1083.38  4343.6 1081.78
  4363.6 1082.03  4371.5 1080.86  4391.6 1080.27  4577.2 1071.58  4657.1 1067.65
  4682.5 1063.81  4682.7 1063.31  4686.5 1063.81  4716.8 1065.15  5130.2 1064.16
  5245.3 1064.44  5255.3 1065.94  5273.2 1066.39  5279.7 1065.69  5295.3 1068.21
  5385.3 1074.69  5415.3 1075.09  5485.4 1079.46  5495.4 1078.97  5545.4 1081.11
  5575.4  1083.6  5605.4 1084.14  5625.4 1085.79  5725.4 1089.81  5901.4 1099.24
#Mann= 10 ,-1 , 0
  3993.4     .12       0  4211.4     .05       0  4294.4     .12       0
  4391.6     .05       0  4577.2      .1       0  4682.5    .033       0
  4686.5      .1       0  4716.8     .05       0  5130.2      .1       0
  5273.2     .05       0
Bank Sta=4682.5,4686.5
XS Rating Curve= 0 ,0
Exp/Cntr=0.3,0.1

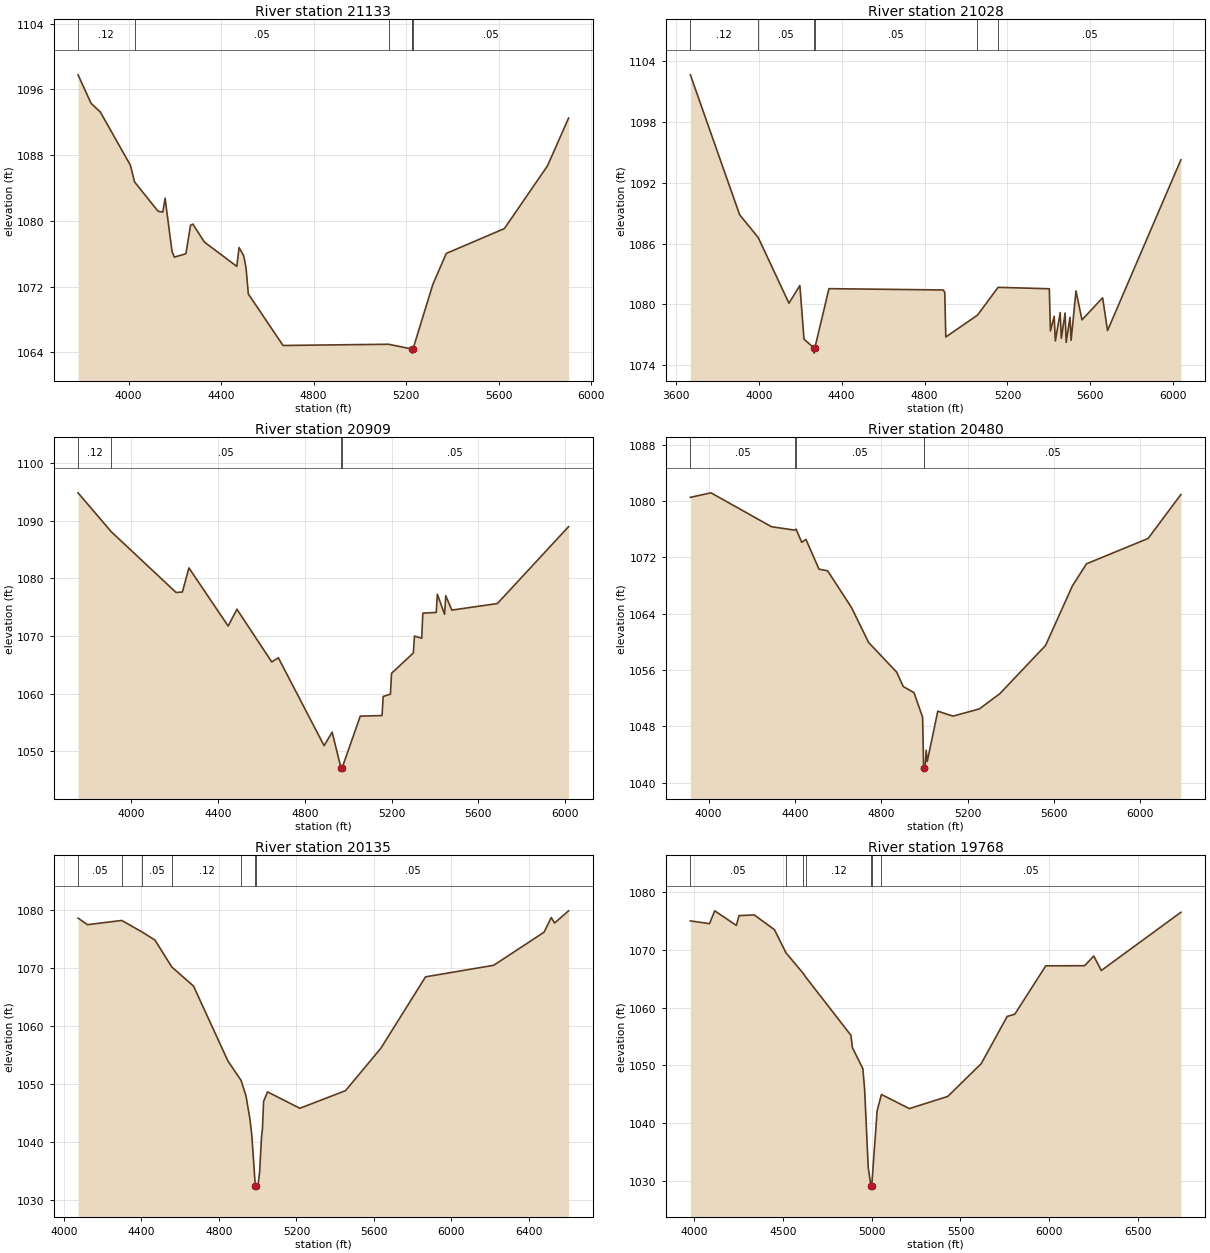
Type RM Length L Ch R = 1 ,21133   ,105,105,105
BEGIN DESCRIPTION:
Upper Denton 115 44.0
END DESCRIPTION:
XS GIS Cut Line= 4
      2249665.34      7244262.84      2248441.42      7244242.01
      2248128.92      7244242.01      2247655.52      7244585.35
#Sta/Elev= 30
  3781.5 1097.76  3837.8 1094.29  3877.9 1093.23  4007.9 1086.76  4025.9 1084.73
  4127.9 1081.15  4147.9 1081.07  4157.9 1082.74  4187.9 1076.27  4197.9 1075.58
  4247.9 1075.99  4267.9 1079.46  4277.9  1079.6  4327.9 1077.41  4467.9 1074.46
  4477.9 1076.75  4497.9 1075.75  4507.9  1074.3  4517.9  1071.1    4668 1064.83
  5124.2 1064.98  5223.8 1064.41    5226  1064.4  5226.3  1063.9    5230  1064.4
  5315.6 1072.24  5373.9 1076.03  5625.2 1079.05  5811.5 1086.68  5902.9  1092.5
#Mann= 6 ,-1 , 0
  3781.5     .12       0  4025.9     .05       0  5124.2      .1       0
  5223.8     .05       0    5226    .033       0    5230     .05       0
Bank Sta=5226,5230
XS Rating Curve= 0 ,0
Exp/Cntr=0.3,0.1

Type RM Length L Ch R = 1 ,21028   ,119,119,119
BEGIN DESCRIPTION:
Upper Denton 115 43.5
END DESCRIPTION:
XS GIS Cut Line= 4
      2249806.03       7244236.8      2248477.88      7244148.26
      2248128.92      7244163.88      2247498.75       7244434.7
#Sta/Elev= 30
  3670.3 1102.62  3907.9 1088.84  3997.8 1086.59  4145.9 1080.13  4198.5 1081.87
  4218.5 1076.59  4266.7 1075.71  4266.9 1075.21  4270.7 1075.71  4338.8 1081.56
    4890 1081.43  4897.5  1081.2  4902.5  1076.8  5055.4 1078.95  5154.8 1081.69
  5401.9 1081.55  5407.3  1077.4  5425.4 1078.84  5430.9 1076.41  5454.4 1079.21
  5459.9 1076.67    5478 1079.16  5483.4 1076.27  5501.5 1078.74    5507 1076.47
  5530.5 1081.34  5559.5 1078.49  5659.1 1080.66  5682.7 1077.43  6036.6 1094.25
#Mann= 6 ,-1 , 0
  3670.3     .12       0  3997.8     .05       0  4266.7    .033       0
  4270.7     .05       0  5055.4      .1       0  5154.8     .05       0
Bank Sta=4266.7,4270.7
XS Rating Curve= 0 ,0
Exp/Cntr=0.3,0.1

Type RM Length L Ch R = 1 ,20909   ,429,429,429
BEGIN DESCRIPTION:
Upper Denton 115 43.0
END DESCRIPTION:
XS GIS Cut Line= 3
      2249717.45      7244148.26      2248483.09      7244028.47
      2247503.99      7244314.91
#Sta/Elev= 30
  3755.3 1094.81  3908.2 1088.07    4207 1077.54    4236 1077.62  4266.1  1081.8
    4447 1071.72  4487.2 1074.64  4647.9  1065.5  4678.1 1066.23    4889 1050.99
    4926 1053.33  4967.4 1047.08  4967.7 1046.58  4971.4 1047.08  5055.7 1056.11
    5156 1056.21  5161.2 1059.51  5194.6 1059.92  5199.8 1063.53  5300.2 1067.06
  5305.4 1069.98  5338.8 1069.61    5344 1073.96  5405.7 1074.08  5410.9 1077.24
  5444.3 1073.76  5449.5 1076.98  5477.8 1074.49  5687.4 1075.62  6015.6 1088.95
#Mann= 4 ,-1 , 0
  3755.3     .12       0  3908.2     .05       0  4967.4    .033       0
  4971.4     .05       0
Bank Sta=4967.4,4971.4
XS Rating Curve= 0 ,0
Exp/Cntr=0.3,0.1

Type RM Length L Ch R = 1 ,20480   ,345,345,345
BEGIN DESCRIPTION:
Upper Denton 115 42.0
END DESCRIPTION:
XS GIS Cut Line= 4
      2249764.34      7243710.76      2248681.01       7243674.3
      2248503.73      7243687.29      2247639.37      7244210.74
#Sta/Elev= 30
  3915.2 1080.54  4010.6 1081.18  4290.7 1076.37  4398.3 1075.88  4404.9 1076.03
  4430.8 1074.15  4450.8 1074.56  4510.9 1070.34  4550.9 1070.11    4661 1064.92
    4741 1059.92  4871.1  1055.7  4901.1 1053.67  4951.1  1052.8  4991.1  1049.3
  4995.6 1042.15  4995.9 1041.65  4999.6 1042.15  5002.7 1042.15  5007.5 1044.62
  5012.5 1043.03  5061.3 1050.17  5131.5 1049.46  5254.1 1050.49  5349.1 1052.66
  5560.5  1059.5  5685.1 1067.98  5750.5  1071.1  6035.6  1074.7  6187.4 1080.94
#Mann= 5 ,-1 , 0
  3915.2     .05       0  4398.3     .12       0  4404.9     .05       0
  4995.6    .033       0  4999.6     .05       0
Bank Sta=4995.6,4999.6
XS Rating Curve= 0 ,0
Exp/Cntr=0.3,0.1

Type RM Length L Ch R = 1 ,20135   ,367,367,367
BEGIN DESCRIPTION:
Upper Denton 115 41.0
END DESCRIPTION:
XS GIS Cut Line= 5
       2249665.4      7243617.01      2248889.19      7243362.75
        2248779.        7243360.      2248670.59      7243382.63
      2247292.19        7243960.
#Sta/Elev= 30
    4073 1078.64  4121.8 1077.51  4298.7 1078.24  4403.8 1076.24  4469.6 1074.87
  4557.2  1070.2    4669 1066.92  4846.5    1054  4914.2 1050.66    4940 1047.96
    4960 1044.03    4970 1041.15    4988 1032.38  4988.3 1031.88    4992 1032.38
  5002.6  1032.7  5010.2 1034.82  5019.9 1040.82    5025 1042.33  5030.7 1047.01
  5051.1 1048.66    5218 1045.83  5453.7 1048.87  5636.4  1056.2  5866.8 1068.51
  6218.4  1070.5  6478.6 1076.21  6515.6 1078.74  6532.8  1077.8  6605.2  1079.9
#Mann= 7 ,-1 , 0
    4073     .05       0  4298.7     .12       0  4403.8     .05       0
  4557.2     .12       0  4914.2     .05       0    4988    .033       0
    4992     .05       0
Bank Sta=4988,4992
XS Rating Curve= 0 ,0
Exp/Cntr=0.3,0.1

Type RM Length L Ch R = 1 ,19768   ,482,482,482
BEGIN DESCRIPTION:
Upper Denton 115 40.0
END DESCRIPTION:
XS GIS Cut Line= 5
      2249675.76      7243554.48       2248899.2        7243005.
        2248829.        7243010.      2248707.18      7243015.68
      2247333.07      7243871.58
#Sta/Elev= 30
  3978.8 1075.04  4086.5 1074.57  4116.1 1076.79  4237.9 1074.26  4252.7 1075.96
  4338.8 1076.08  4452.6 1073.51  4516.8 1069.53  4614.6 1065.93  4629.2 1065.27
  4882.8 1055.21  4891.5 1053.05  4950.3  1049.4  4960.4 1045.71  4980.4 1032.28
    4996 1029.01  4996.2 1028.51    5000 1029.01  5030.5  1042.1  5054.8 1044.93
  5212.2 1042.48  5428.1 1044.59  5616.9 1050.28  5763.3 1058.48  5805.8 1058.85
  5980.3 1067.25  6198.8 1067.27  6250.7 1068.95  6293.2 1066.44  6741.3 1076.54
#Mann= 7 ,-1 , 0
  3978.8     .05       0  4516.8     .12       0  4614.6     .05       0
  4629.2     .12       0    4996     .07       0    5000     .12       0
  5054.8     .05       0
Bank Sta=4996,5000
XS Rating Curve= 0 ,0
Exp/Cntr=0.3,0.1

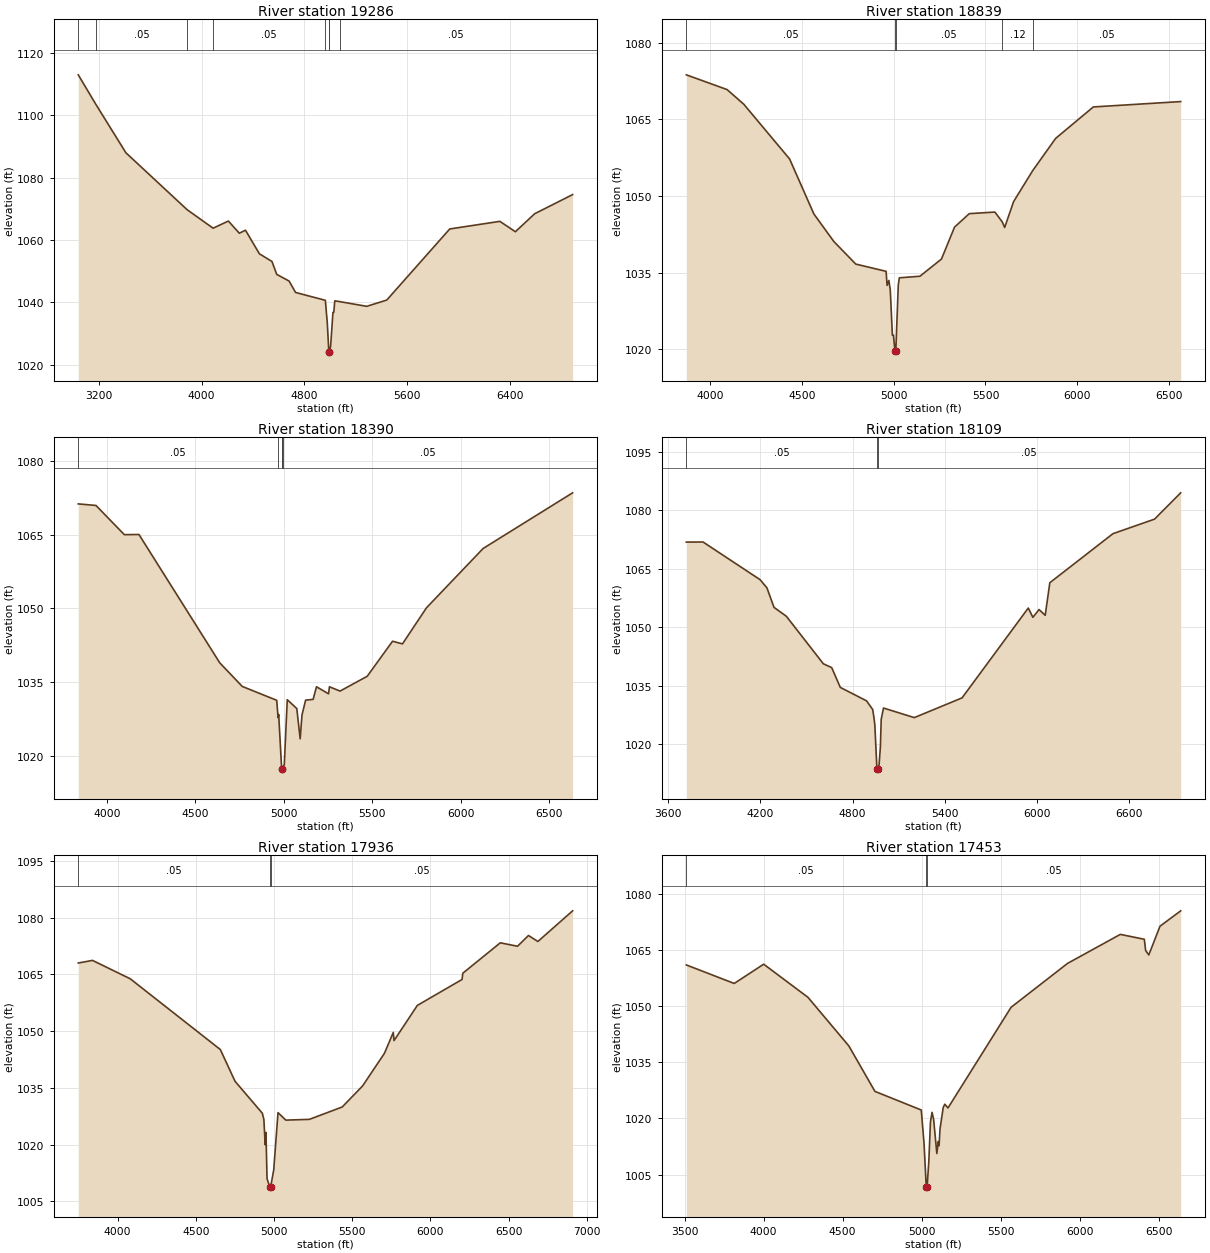
Type RM Length L Ch R = 1 ,19286   ,447,447,447
BEGIN DESCRIPTION:
Upper Denton 115 39.0
END DESCRIPTION:
XS GIS Cut Line= 4
      2250582.02      7242559.71      2249310.09       7242263.1
        2248729.        7242560.      2247295.58      7243783.68
#Sta/Elev= 30
  3041.9 1113.01  3177.9  1103.6  3412.2 1088.01  3887.7 1069.77  4090.1 1063.81
    4209 1066.11  4294.1  1062.2  4341.8 1063.17  4450.2  1055.6  4547.8 1053.14
    4585    1049  4681.1 1046.85  4731.2  1043.2  4962.9 1040.68    4978 1033.41
  4989.9 1024.24  4990.4 1023.74  4994.5 1024.24  5003.8 1025.98  5021.9 1036.78
  5028.5 1036.84  5036.2 1040.51  5073.4 1040.27  5284.3 1038.75  5440.2 1040.76
  5929.9 1063.57  6319.6 1066.01  6440.4 1062.68  6589.7 1068.44  6885.2 1074.59
#Mann= 8 ,-1 , 0
  3041.9     .12       0  3177.9     .05       0  3887.7     .12       0
  4090.1     .05       0  4962.9     .12       0  4989.9     .07       0
  4994.5     .12       0  5073.4     .05       0
Bank Sta=4989.9,4994.5
XS Rating Curve= 0 ,0
Exp/Cntr=0.3,0.1

Type RM Length L Ch R = 1 ,18839   ,449,449,449
BEGIN DESCRIPTION:
Upper Denton 115 38.0
END DESCRIPTION:
XS GIS Cut Line= 3
      2249449.01      7241832.53        2248429.        7242310.
      2247067.02      7243089.49
#Sta/Elev= 30
  3869.1 1073.73  4091.3 1070.84  4182.7 1067.96  4432.2 1057.25  4564.7 1046.47
  4673.3 1041.09    4793 1036.66  4958.3 1035.24  4963.8 1032.49  4973.3 1033.45
  4981.2 1031.58  4992.6 1022.74  4998.2 1022.74  5006.7 1019.72  5007.2 1019.22
  5011.3 1019.72  5024.8 1032.55  5030.6 1033.97  5142.8 1034.28  5260.3 1037.65
  5331.4  1043.9    5412 1046.54  5551.6 1046.85  5592.3 1044.89  5604.8 1043.83
  5653.7 1048.91  5757.6 1054.96  5882.5 1061.27  6088.3 1067.44  6564.6 1068.49
#Mann= 5 ,-1 , 0
  3869.1     .05       0  5006.7    .033       0  5011.3     .05       0
  5592.3     .12       0  5757.6     .05       0
Bank Sta=5006.7,5011.3
XS Rating Curve= 0 ,0
Exp/Cntr=0.3,0.1

Type RM Length L Ch R = 1 ,18390   ,281,281,281
BEGIN DESCRIPTION:
Upper Denton 115 37.0
END DESCRIPTION:
XS GIS Cut Line= 3
      2249428.19      7241735.32        2248279.        7241910.
      2246685.13      7242263.09
#Sta/Elev= 30
  3837.2 1071.23  3937.5 1070.91  4097.8 1064.97  4180.3 1065.01  4637.1 1038.92
  4764.3 1034.12  4959.1  1031.3    4967 1027.76  4970.3 1028.41  4987.1  1017.4
  4987.6  1016.9  4991.8  1017.4  4993.1 1017.61  5002.1 1018.24  5018.8 1031.42
  5072.7 1029.62  5091.8 1023.47    5102  1028.3  5122.5 1031.33    5165 1031.49
    5184 1034.05  5252.2 1032.62  5257.3 1034.05  5317.1 1033.17  5470.7 1036.18
  5614.1 1043.31  5670.2 1042.77  5806.2 1050.12  6126.3 1062.17  6632.1 1073.48
#Mann= 5 ,-1 , 0
  3837.2     .05       0    4967     .12       0  4987.1    .033       0
  4991.8     .12       0  4993.1     .05       0
Bank Sta=4987.1,4991.8
XS Rating Curve= 0 ,0
Exp/Cntr=0.3,0.1

Type RM Length L Ch R = 1 ,18109   ,173,173,173
BEGIN DESCRIPTION:
Upper Denton 115 36.5
END DESCRIPTION:
XS GIS Cut Line= 3
      2249497.54      7241742.26       2248233.7      7241651.99
      2246289.29      7241554.77
#Sta/Elev= 30
  3719.2  1071.8    3828 1071.82    4199 1062.15  4243.1 1060.07  4289.2 1055.05
  4369.4 1052.77    4610 1040.57  4664.2 1039.59  4720.3 1034.51  4890.7 1031.07
  4930.8 1028.84  4939.9 1026.52  4944.9 1024.72  4958.4 1013.53    4959 1013.03
  4963.4 1013.53  4970.9 1013.95  4980.9  1019.3  4986.1 1026.32    5001 1029.22
  5201.2 1026.76  5511.6 1031.82  5942.2 1054.88  5972.2 1052.49  6012.2 1054.49
  6052.3 1053.01  6082.3 1061.37  6492.8 1073.96  6763.2 1077.69  6933.1 1084.44
#Mann= 3 ,-1 , 0
  3719.2     .05       0  4958.4    .033       0  4963.4     .05       0
Bank Sta=4958.4,4963.4
XS Rating Curve= 0 ,0
Exp/Cntr=0.3,0.1

Type RM Length L Ch R = 1 ,17936   ,483,483,483
BEGIN DESCRIPTION:
Upper Denton 115 36.0
END DESCRIPTION:
XS GIS Cut Line= 3
      2249469.81       7241638.1        2248229.        7241510.
      2246316.99      7241422.82
#Sta/Elev= 30
  3748.1 1067.99  3839.4 1068.68  4080.7 1063.82  4656.7 1045.13  4750.6 1036.75
  4925.1 1028.31  4935.2 1026.63  4943.5 1019.99  4948.5 1023.23  4955.3 1011.06
  4972.8 1008.75  4973.5 1008.25  4977.9 1008.75    4998 1013.32  5025.5 1028.46
  5075.6 1026.48  5225.7 1026.68    5436 1029.95  5566.1  1035.5  5706.2 1044.14
  5762.6 1049.65  5767.6  1047.5  5916.5 1056.79  6202.4 1063.64  6207.4  1065.3
    6447 1073.33  6557.1 1072.42  6627.2 1075.26  6687.3 1073.68  6909.5 1081.78
#Mann= 3 ,-1 , 0
  3748.1     .05       0  4972.8    .033       0  4977.9     .05       0
Bank Sta=4972.8,4977.9
XS Rating Curve= 0 ,0
Exp/Cntr=0.3,0.1

Type RM Length L Ch R = 1 ,17453   ,462,462,462
BEGIN DESCRIPTION:
Upper Denton 115 35.0
END DESCRIPTION:
XS GIS Cut Line= 3
      2249511.47      7241499.21        2248079.        7241110.
        2246449.       7241325.6
#Sta/Elev= 30
  3510.8 1061.05  3813.9  1056.1  4000.4 1061.25  4280.2 1052.41  4539.3  1039.4
  4704.5 1027.24  4997.7 1022.26  5015.4 1013.16  5029.3 1001.61    5030 1001.11
  5034.5 1001.61  5045.6 1008.64  5055.7 1019.07  5065.8 1021.64  5075.9 1019.76
  5096.1 1010.63  5105.4 1013.85  5110.4 1012.71  5116.2 1017.15  5136.4 1022.92
  5146.5 1023.82  5166.7 1022.81  5566.1 1049.73  5923.2 1061.46  6257.3 1069.22
  6409.3 1067.91  6417.5  1064.9  6437.7 1063.73  6508.3  1071.4  6639.4 1075.52
#Mann= 3 ,-1 , 0
  3510.8     .05       0  5029.3    .033       0  5034.5     .05       0
Bank Sta=5029.3,5034.5
XS Rating Curve= 0 ,0
Exp/Cntr=0.3,0.1

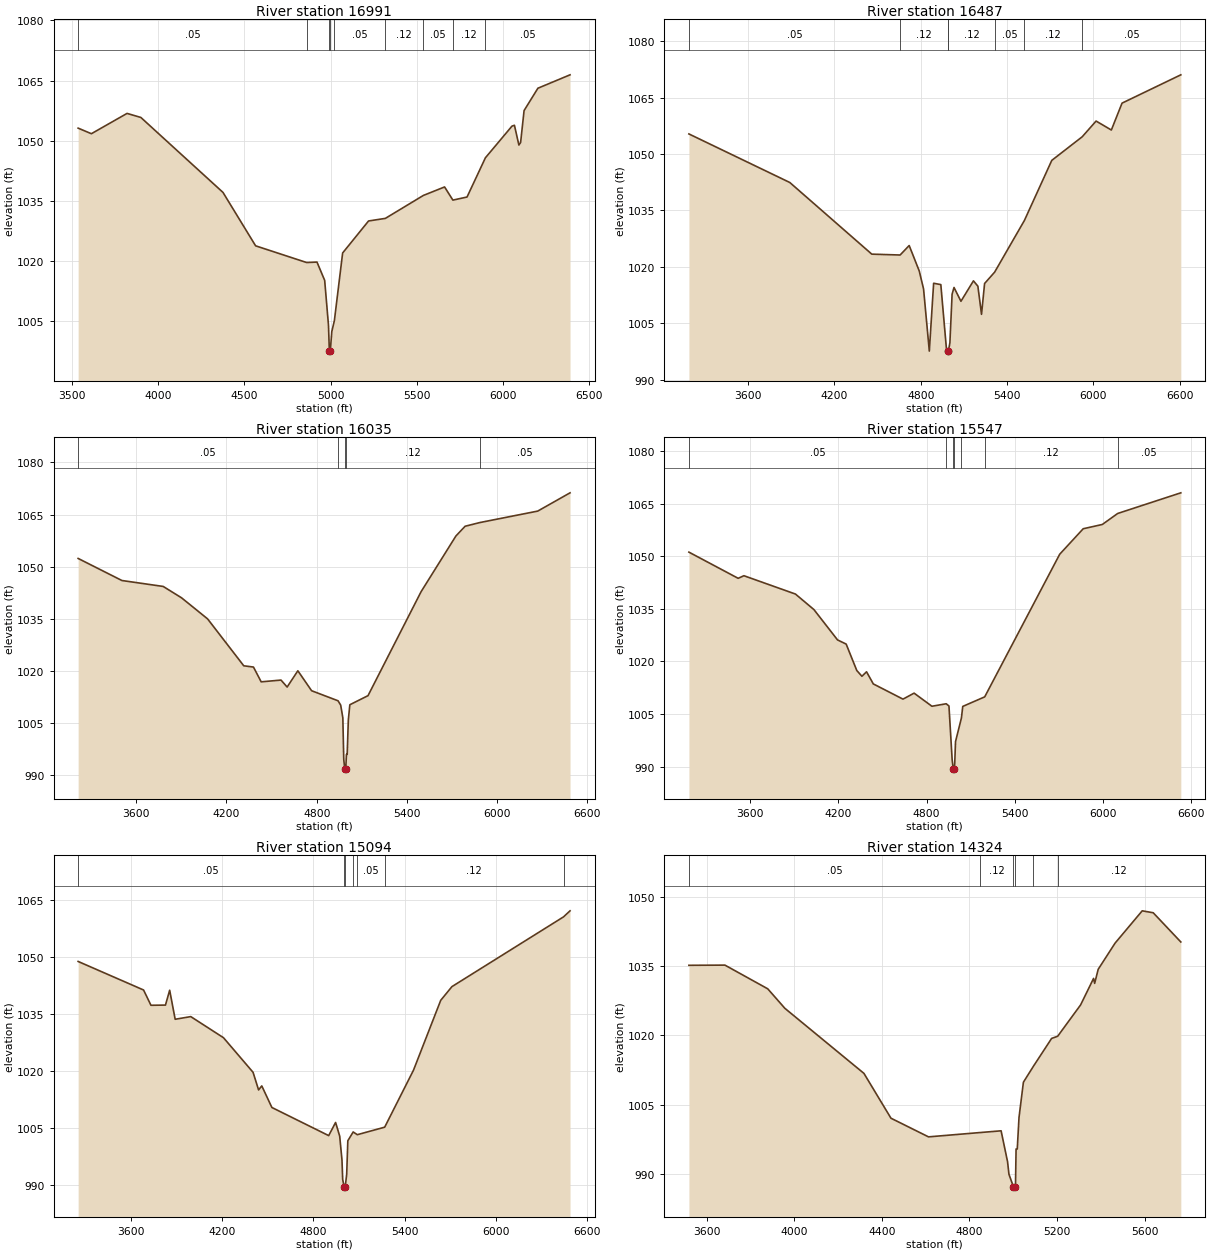
Type RM Length L Ch R = 1 ,16991   ,504,504,504
BEGIN DESCRIPTION:
Upper Denton 115 34.0
END DESCRIPTION:
XS GIS Cut Line= 3
      2249317.03       7241325.6        2247979.        7240710.
      2246602.92      7240638.16
#Sta/Elev= 30
  3536.5 1053.15  3613.3 1051.76    3820 1056.82    3900 1055.81  4375.9 1037.14
  4565.1 1023.83  4860.8 1019.67  4920.7 1019.78  4965.3 1015.23  4987.3 1004.08
  4992.5   997.6  4993.2   997.1  4997.7   997.6  5006.6 1002.47  5021.6 1005.21
  5069.4 1022.05  5219.6 1030.02  5317.2 1030.67  5537.1 1036.38  5660.2  1038.5
  5708.3 1035.22  5790.4 1035.99  5896.8 1045.76  6050.8 1053.65  6065.1 1053.86
  6090.8 1048.94  6100.8 1049.56  6120.9 1057.52    6201 1063.09  6387.3 1066.43
#Mann= 9 ,-1 , 0
  3536.5     .05       0  4860.8     .12       0  4992.5     .07       0
  4997.7     .12       0  5021.6     .05       0  5317.2     .12       0
  5537.1     .05       0  5708.3     .12       0  5896.8     .05       0
Bank Sta=4992.5,4997.7
XS Rating Curve= 0 ,0
Exp/Cntr=0.3,0.1

Type RM Length L Ch R = 1 ,16487   ,452,452,452
BEGIN DESCRIPTION:
Upper Denton 115 33.0
END DESCRIPTION:
XS GIS Cut Line= 3
      2249990.61      7240332.54      2248178.14      7240311.71
      2246664.22      7239770.03
#Sta/Elev= 30
  3188.3 1055.33    3890 1042.43    4460  1023.4  4656.9 1023.17    4720 1025.69
    4790 1018.92    4820 1014.15    4860  997.65    4890 1015.67    4940 1015.31
    4980  997.82  4987.4  997.61  4988.1  997.11  4992.6  997.61  5003.1  999.87
  5018.4 1012.77  5031.8 1014.55  5079.9 1010.88  5166.9 1016.31  5197.7 1014.88
    5223 1007.41  5244.3  1015.6    5314 1018.61    5521 1032.33  5711.6 1048.31
    5923 1054.57  6019.6 1058.75  6125.8 1056.37  6200.1 1063.51  6608.8 1071.03
#Mann= 7 ,-1 , 0
  3188.3     .05       0  4656.9     .12       0  4987.4     .07       0
  4992.6     .12       0    5314     .05       0    5521     .12       0
    5923     .05       0
Bank Sta=4987.4,4992.6
XS Rating Curve= 0 ,0
Exp/Cntr=0.3,0.1

Type RM Length L Ch R = 1 ,16035   ,488,488,488
BEGIN DESCRIPTION:
Upper Denton 115 32.0
END DESCRIPTION:
XS GIS Cut Line= 3
      2249935.06      7240186.71        2248179.        7239860.
      2246705.88      7239679.76
#Sta/Elev= 30
  3213.8 1052.35  3504.8 1045.99  3779.4 1044.28  3901.5    1041  4074.4 1034.94
    4315 1021.42  4379.5 1021.06  4430.7  1016.8  4562.6 1017.31  4603.3  1015.3
  4674.5 1019.99    4766 1014.24  4941.9 1011.34  4959.3  1010.1  4973.6 1006.45
  4979.7  994.44  4986.8  991.58  4987.8  991.08  4992.9  991.58  4997.5   995.9
  5002.5   995.9  5010.1  1005.8  5020.1  1010.2    5141 1012.82  5493.7 1042.76
  5725.4 1058.82  5786.5 1061.62  5883.7 1062.68  6269.4 1065.99  6484.1 1071.25
#Mann= 5 ,-1 , 0
  3213.8     .05       0  4941.9     .12       0  4986.8     .07       0
  4992.9     .12       0  5883.7     .05       0
Bank Sta=4986.8,4992.9
XS Rating Curve= 0 ,0
Exp/Cntr=0.3,0.1

Type RM Length L Ch R = 1 ,15547   ,453,453,453
BEGIN DESCRIPTION:
Upper Denton 115 31.0
END DESCRIPTION:
XS GIS Cut Line= 3
      2249969.79      7240096.42        2248279.        7239410.
      2246754.48      7239443.66
#Sta/Elev= 30
  3182.1 1051.19  3517.5 1043.72  3556.7 1044.46  3907.6 1039.23  4033.4  1034.8
  4194.1 1026.15    4253 1024.95  4325.3 1017.42  4360.2 1015.77  4391.7 1017.05
  4437.8 1013.59    4640 1009.25  4715.5 1010.96  4836.9 1007.22  4934.2 1007.93
  4952.9  1007.3  4974.5  992.09  4982.2  989.21  4983.3  988.71  4988.4  989.21
  4992.2  990.82  4997.6  997.13    5038 1003.91  5046.9 1007.17  5196.4  1009.9
  5707.1 1050.59  5867.1 1057.86  5997.2 1059.08  6101.9 1062.22  6531.8 1068.11
#Mann= 7 ,-1 , 0
  3182.1     .05       0  4934.2     .12       0  4982.2     .07       0
  4988.4     .12       0    5038     .05       0  5196.4     .12       0
  6101.9     .05       0
Bank Sta=4982.2,4988.4
XS Rating Curve= 0 ,0
Exp/Cntr=0.3,0.1

Type RM Length L Ch R = 1 ,15094   ,770,770,770
BEGIN DESCRIPTION:
Upper Denton 115 30.0
END DESCRIPTION:
XS GIS Cut Line= 4
      2249990.61      7240013.08        2248529.        7239060.
      2247991.03       7238928.2       2247053.6      7238999.18
#Sta/Elev= 30
  3250.5 1048.87  3681.3 1041.36    3730 1037.34  3825.5 1037.39  3853.2  1041.3
  3889.4 1033.66  3992.1 1034.36  4207.5 1028.81  4402.4  1019.7  4438.6 1015.07
  4459.7 1016.13  4526.2 1010.45  4900.3 1003.05  4945.7 1006.51  4972.7 1002.92
  4987.8  996.61  4992.4  991.52  5002.5  989.47  5003.6  988.97  5008.8  989.47
  5018.8  992.91  5026.3  1001.7  5061.5 1004.01  5088.6 1003.29    5269 1005.27
  5458.7 1020.27    5638 1038.65  5711.8 1042.25  6446.5  1060.6  6489.4 1062.19
#Mann= 7 ,-1 , 0
  3250.5     .05       0  5002.5    .033       0  5008.8     .05       0
  5061.5     .12       0  5088.6     .05       0    5269     .12       0
  6446.5     .05       0
Bank Sta=5002.5,5008.8
XS Rating Curve= 0 ,0
Exp/Cntr=0.3,0.1

Type RM Length L Ch R = 1 ,14324   ,351,351,351
BEGIN DESCRIPTION:
Upper Denton 115 29.0
END DESCRIPTION:
XS GIS Cut Line= 3
      2249719.81      7239226.64      2248469.81      7238401.99
       2247723.6       7238323.9
#Sta/Elev= 30
    3518 1035.19  3682.6 1035.23  3878.3  1030.1  3956.5 1025.88  4317.8  1011.8
  4441.3  1002.1  4612.8  998.06  4849.8     999  4944.6  999.37  4974.1  992.68
  4980.5  989.96    5001  987.25  5002.1  986.75  5007.5  987.25  5010.3  987.42
    5013  995.43  5018.4  995.43  5026.4 1002.25  5046.5 1009.89  5092.5 1013.36
  5175.5 1019.37    5203 1019.83  5307.9 1026.62  5367.1 1032.35  5372.1 1031.28
  5388.3 1034.33  5465.4 1039.99  5589.4 1046.98  5639.7 1046.56  5765.8 1040.24
#Mann= 6 ,-1 , 0
    3518     .05       0  4849.8     .12       0    5001     .07       0
  5007.5     .12       0  5092.5     .05       0    5203     .12       0
Bank Sta=5001,5007.5
XS Rating Curve= 0 ,0
Exp/Cntr=0.3,0.1

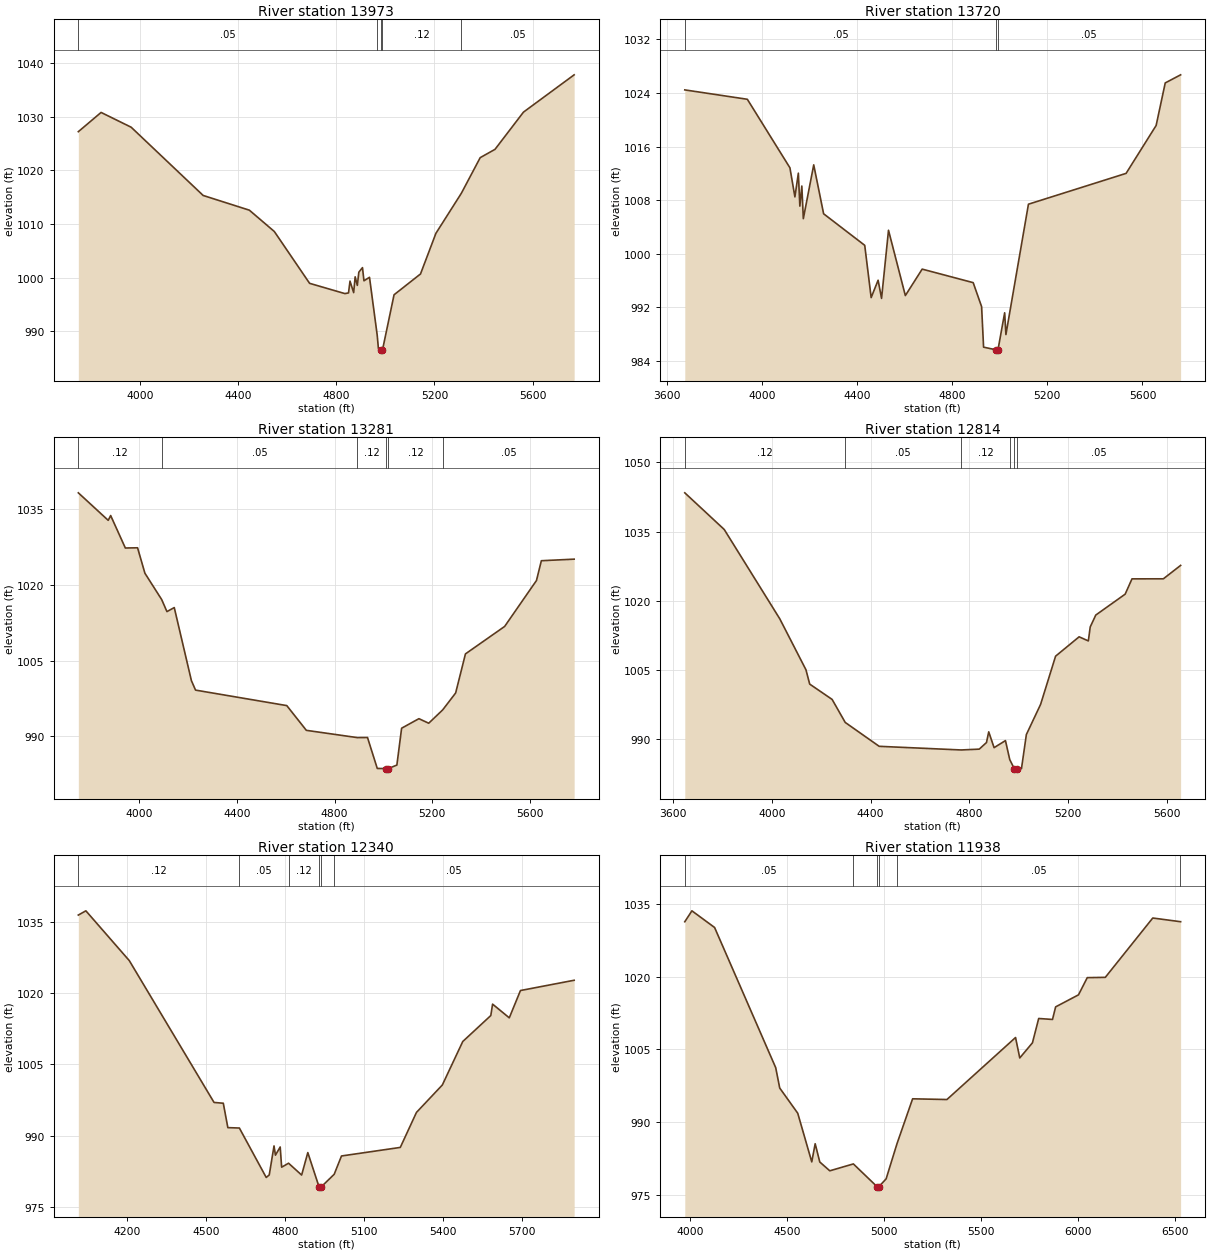
Type RM Length L Ch R = 1 ,13973   ,253,253,253
BEGIN DESCRIPTION:
Upper Denton 115 28.5
END DESCRIPTION:
XS GIS Cut Line= 3
      2249778.05      7238948.96      2248607.47      7238148.89
      2248007.26      7238188.56
#Sta/Elev= 30
  3749.9 1027.18  3842.6 1030.76  3965.1 1028.01  4258.3 1015.31  4446.6 1012.57
  4548.2  1008.6  4691.8  998.96  4835.4  997.05  4850.3  997.17  4856.4  999.37
  4871.3  997.23  4877.3 1000.17  4886.2  998.58  4892.3 1001.03  4907.2 1001.88
  4913.2  999.43  4935.8 1000.08  4967.2  989.29  4972.1   986.8  4981.8  986.47
  4982.8  985.97  4988.3  986.47  5035.8  996.83  5143.5  1000.7  5206.3 1008.27
  5309.9 1015.72  5386.7 1022.35  5446.9 1023.89  5562.9 1030.82  5769.3 1037.76
#Mann= 5 ,-1 , 0
  3749.9     .05       0  4967.2     .12       0  4981.8     .07       0
  4988.3     .12       0  5309.9     .05       0
Bank Sta=4981.8,4988.3
XS Rating Curve= 0 ,0
Exp/Cntr=0.3,0.1

Type RM Length L Ch R = 1 ,13720   ,439,439,439
BEGIN DESCRIPTION:
Upper Denton 115 28.0
END DESCRIPTION:
XS GIS Cut Line= 3
      2249793.69      7238813.55        2248729.        7238010.
      2248017.68       7237771.9
#Sta/Elev= 30
  3676.5 1024.47  3939.4 1023.07  4118.4 1012.84  4139.3  1008.5  4153.8 1012.04
  4160.1 1007.12  4168.4 1010.12  4174.7 1005.25  4218.4 1013.28    4260 1005.98
  4432.8 1001.27  4459.8  993.47    4489  996.06  4503.5  993.35  4532.7 1003.52
  4603.5  993.77  4674.2  997.72  4888.6   995.7    4924  992.12  4932.3  986.07
  4984.2  985.68  4985.4  985.18  4992.9  985.68  5020.9   991.2  5026.2  987.95
  5120.9 1007.41  5531.3 1012.01  5657.6 1019.16  5695.8 1025.51  5760.5 1026.72
#Mann= 3 ,-1 , 0
  3676.5     .05       0  4984.2    .033       0  4992.9     .05       0
Bank Sta=4984.2,4992.9
XS Rating Curve= 0 ,0
Exp/Cntr=0.3,0.1

Type RM Length L Ch R = 1 ,13281   ,467,467,467
BEGIN DESCRIPTION:
Upper Denton 115 27.0
END DESCRIPTION:
XS GIS Cut Line= 3
      2249981.18      7237553.15        2248729.        7237610.
      2247955.15      7237662.52
#Sta/Elev= 30
  3751.5 1038.23  3873.8 1032.78  3883.8 1033.73  3943.9  1027.3  3993.9 1027.34
    4024  1022.3  4092.8 1017.07  4114.1  1014.7  4144.1  1015.5  4214.2 1001.03
  4231.2  999.15  4604.6  996.08  4684.6  991.18  4893.2  989.74  4934.9  989.76
  4974.9  983.63  5010.6   983.6  5011.9   983.1  5019.4   983.6  5055.1   984.3
  5074.5   991.6  5145.3  993.49  5185.4  992.59  5242.6  995.23  5295.6  998.58
  5335.7 1006.32  5496.1 1011.76  5626.4 1020.86  5646.4 1024.78  5780.6 1025.09
#Mann= 6 ,-1 , 0
  3751.5     .12       0  4092.8     .05       0  4893.2     .12       0
  5010.6     .07       0  5019.4     .12       0  5242.6     .05       0
Bank Sta=5010.6,5019.4
XS Rating Curve= 0 ,0
Exp/Cntr=0.3,0.1

Type RM Length L Ch R = 1 ,12814   ,474,474,474
BEGIN DESCRIPTION:
Upper Denton 115 26.0
END DESCRIPTION:
XS GIS Cut Line= 3
       2249736.4      7236735.45        2248479.        7237260.
      2247903.56      7237558.11
#Sta/Elev= 30
  3646.4 1043.41  3806.3 1035.46  4031.5 1016.09  4137.7 1005.03  4152.8 1001.93
  4243.8   998.6  4296.9  993.61  4434.6  988.43  4767.2  987.64  4840.4  987.82
  4869.7  989.25  4878.8  991.57  4900.5  988.14  4946.6  989.67  4964.1  985.54
  4982.7  983.55    4984  983.05  4991.6  983.55  5011.6  983.59  5031.4  990.98
  5089.1  997.52  5149.9 1007.98  5245.3 1012.18  5282.7 1011.29  5290.4 1014.33
  5312.9  1016.9    5432 1021.43  5459.7 1024.75  5586.9 1024.76  5656.9 1027.67
#Mann= 6 ,-1 , 0
  3646.4     .12       0  4296.9     .05       0  4767.2     .12       0
  4964.1     .05       0  4982.7    .033       0  4991.6     .05       0
Bank Sta=4982.7,4991.6
XS Rating Curve= 0 ,0
Exp/Cntr=0.3,0.1

Type RM Length L Ch R = 1 ,12340   ,402,402,402
BEGIN DESCRIPTION:
Upper Denton 115 25.0
END DESCRIPTION:
XS GIS Cut Line= 4
      2249585.37      7236469.82        2248679.        7236860.
      2248406.01       7236996.5        2248003.      7237432.32
#Sta/Elev= 30
  4013.8  1036.4  4042.5 1037.29  4207.6 1026.82  4529.9     997  4565.1  996.83
  4582.4   991.7  4626.2  991.62  4728.4  981.22  4739.9  981.76    4758  987.85
  4763.4  985.91  4781.5  987.63    4787  983.38  4813.3  984.22    4863  981.73
  4886.5  986.45  4929.1  979.27  4930.4  978.77    4938  979.27  4986.8  981.89
  5014.6  985.74  5238.2  987.54  5299.7   994.9  5398.1 1000.67  5475.8 1009.81
  5582.4 1015.27  5589.2 1017.67  5652.7 1014.79  5695.2 1020.53  5899.4 1022.69
#Mann= 6 ,-1 , 0
  4013.8     .12       0  4626.2     .05       0  4813.3     .12       0
  4929.1    .033       0    4938     .12       0  4986.8     .05       0
Bank Sta=4929.1,4938
XS Rating Curve= 0 ,0
Exp/Cntr=0.3,0.1

Type RM Length L Ch R = 1 ,11938   ,514,514,514
BEGIN DESCRIPTION:
Upper Denton 115 24.0
END DESCRIPTION:
XS GIS Cut Line= 4
      2249522.87      7236266.69        2248579.        7236510.
      2248368.33      7236578.88      2247715.58      7237771.91
#Sta/Elev= 30
  3973.2 1031.29  4009.9 1033.54  4126.8 1030.11  4441.9 1001.24  4462.6  997.05
  4555.5  991.86  4627.8  981.84  4645.4  985.58  4669.1  981.82  4720.7     980
  4842.3  981.42  4964.6  976.73  4965.9  976.23  4973.6  976.73  5011.1  978.34
  5067.6  985.63  5147.8  994.83  5324.6  994.68  5678.4 1007.45  5700.2 1003.24
  5765.6 1006.36  5797.8 1011.37    5869 1011.17  5885.1 1013.76    6003 1016.24
  6048.2 1019.78  6141.2 1019.84  6385.9 1032.06  6528.7  1031.3  6529.5  1031.3
#Mann= 6 ,-1 , 0
  3973.2     .05       0  4842.3     .12       0  4964.6     .07       0
  4973.6     .12       0  5067.6     .05       0  6528.7     .12       0
Bank Sta=4964.6,4973.6
XS Rating Curve= 0 ,0
Exp/Cntr=0.3,0.1