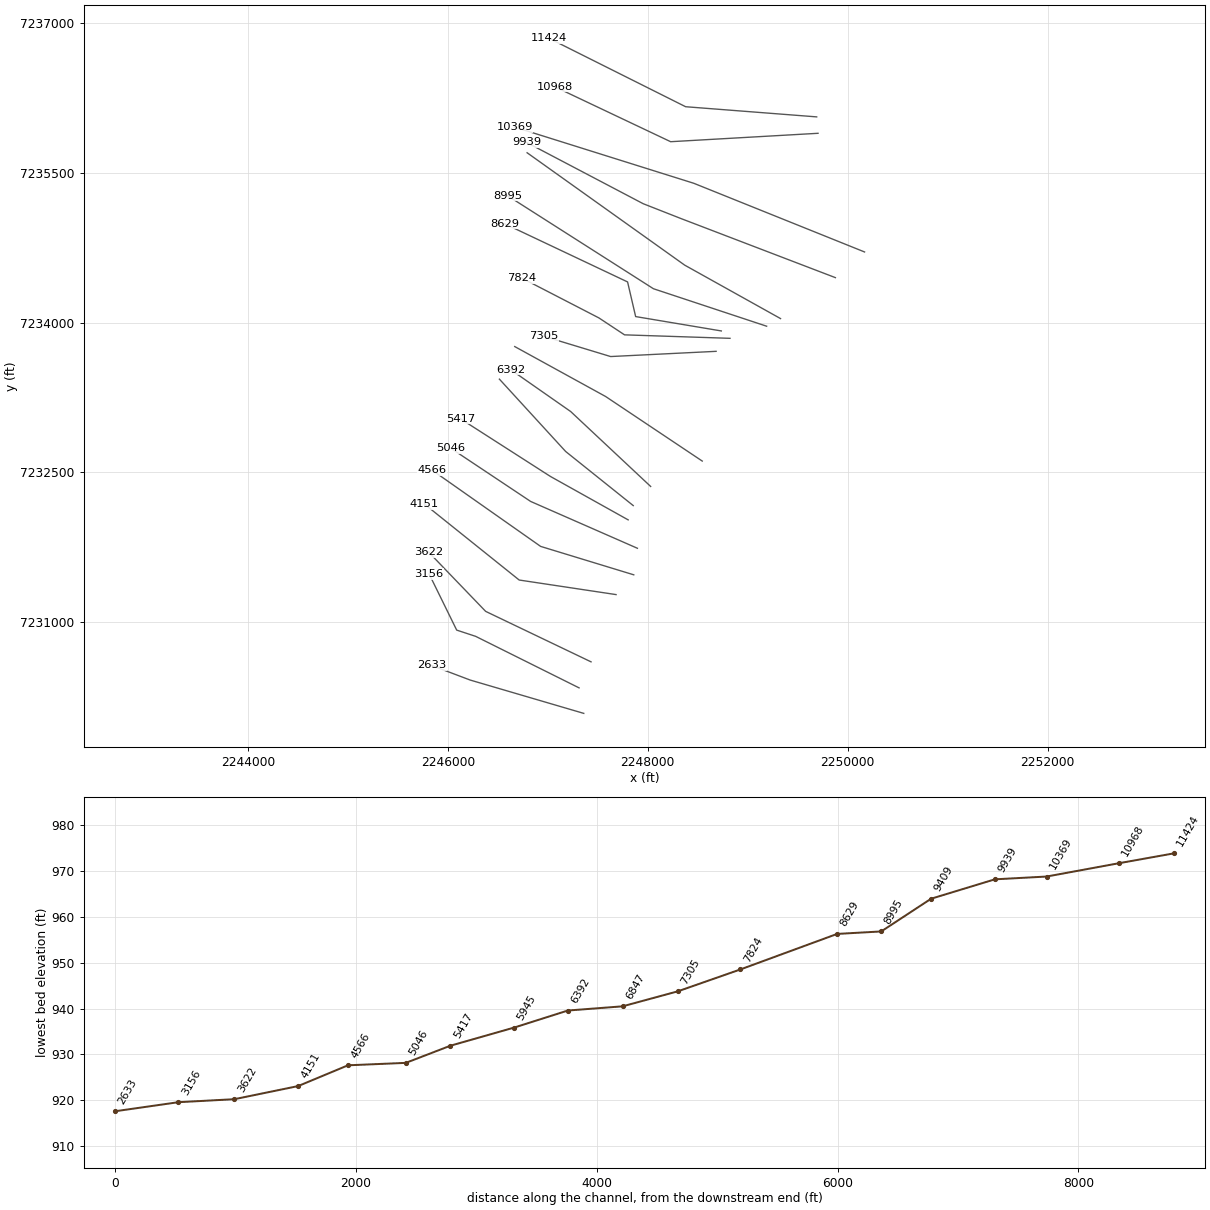
HEC-RAS study Upper Denton 115.prj: Upper Denton 115 Base Level Engineering

--- Upper Denton 115.g01 (geometry) --- (continued)

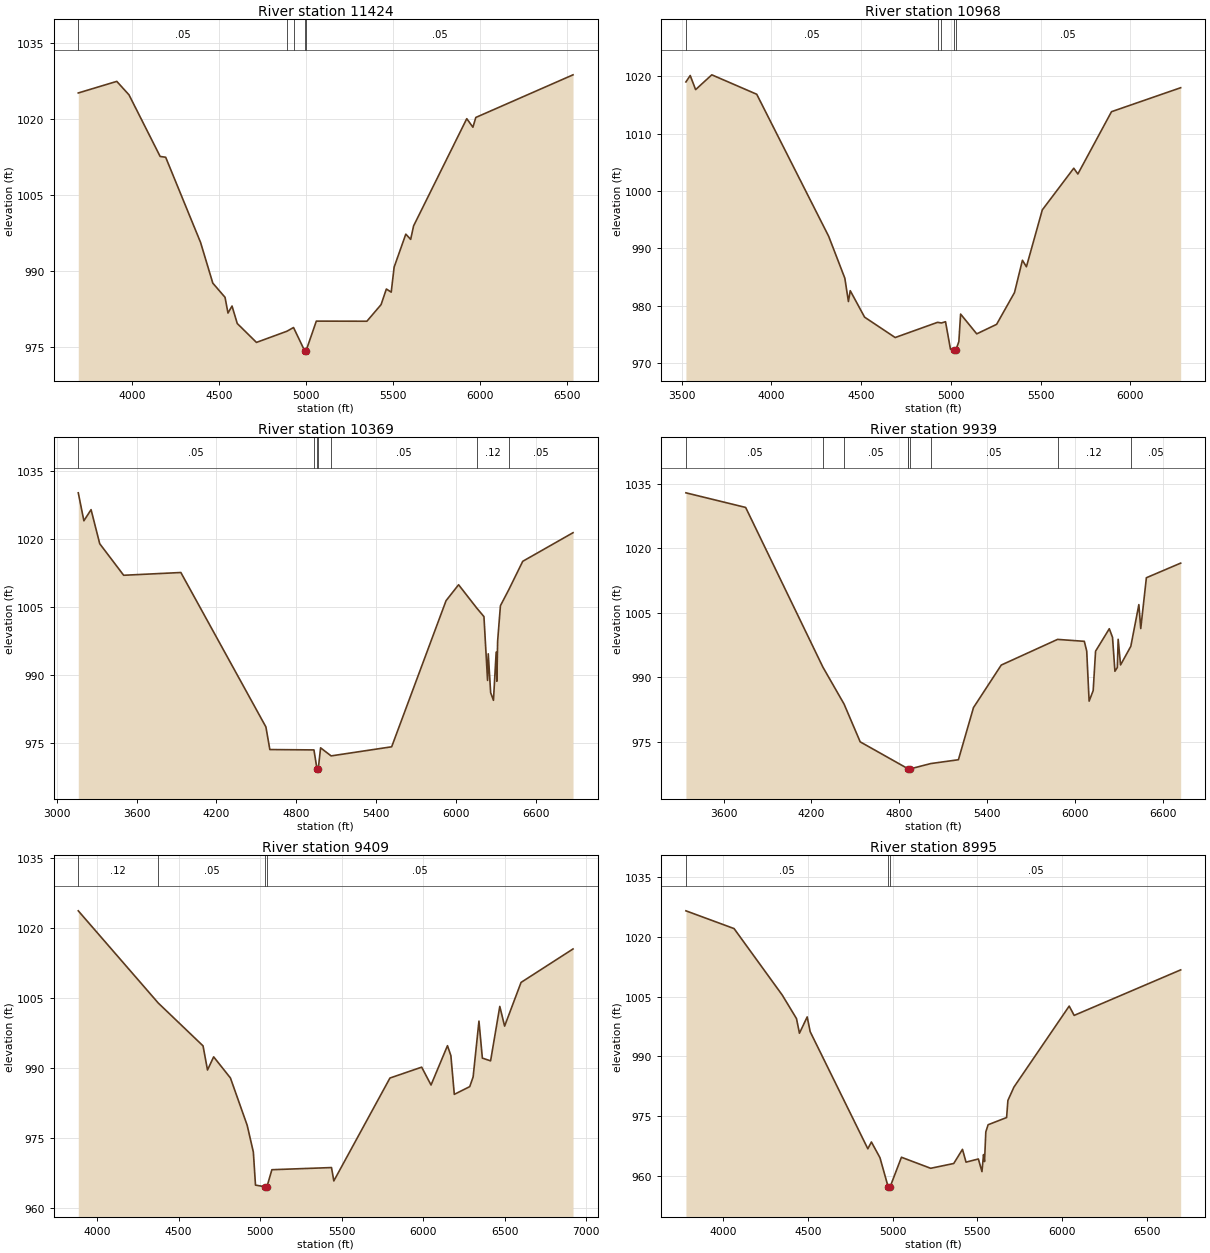
Type RM Length L Ch R = 1 ,11424   ,456,456,456
BEGIN DESCRIPTION:
Upper Denton 115 23.0
END DESCRIPTION:
XS GIS Cut Line= 3
      2249689.53      7236058.36        2248379.        7236160.
      2247013.26      7236844.41
#Sta/Elev= 30
  3690.4 1025.08  3911.6 1027.36  3981.8 1024.71  4160.8 1012.58  4192.4 1012.43
    4393  995.65  4463.2  987.65  4533.5  984.85  4550.4  981.76  4573.6  983.14
  4603.7   979.7    4714  975.98  4889.1  978.18  4926.9  978.91  4990.3  974.37
  4991.6  973.87  4999.3  974.37  5057.9  980.17  5348.4  980.15  5429.9  983.42
  5460.2  986.49  5488.1  985.87  5504.8  990.79  5571.9  997.29  5599.8  996.26
  5616.6  998.91  5922.1 1020.02  5957.4 1018.34  5974.1 1020.26  6532.5 1028.65
#Mann= 5 ,-1 , 0
  3690.4     .05       0  4889.1     .12       0  4926.9     .05       0
  4990.3    .033       0  4999.3     .05       0
Bank Sta=4990.3,4999.3
XS Rating Curve= 0 ,0
Exp/Cntr=0.3,0.1

Type RM Length L Ch R = 1 ,10968   ,599,599,599
BEGIN DESCRIPTION:
Upper Denton 115 22.0
END DESCRIPTION:
XS GIS Cut Line= 3
      2249702.87      7235894.12        2248229.        7235810.
      2247072.52      7236358.66
#Sta/Elev= 30
  3524.5 1019.02  3548.4 1020.14  3578.5 1017.68  3668.6 1020.26    3919 1016.87
  4319.7   992.1  4409.8  984.79  4429.8  980.72  4439.9  982.61    4520  977.99
  4690.3  974.44  4926.2  977.09  4948.1  976.98  4970.7   977.2  4998.3  972.42
  5018.2  972.22  5019.6  971.72  5027.6  972.22    5045  973.72  5054.8  978.53
  5144.7  975.08  5255.3  976.74    5355  982.28  5399.2  987.92  5421.4  986.78
  5509.9   996.7  5685.2 1003.97    5708 1002.96  5895.4 1013.83  6280.8 1018.01
#Mann= 5 ,-1 , 0
  3524.5     .05       0  4926.2     .12       0  4948.1     .05       0
  5018.2    .033       0  5027.6     .05       0
Bank Sta=5018.2,5027.6
XS Rating Curve= 0 ,0
Exp/Cntr=0.3,0.1

Type RM Length L Ch R = 1 ,10369   ,430,430,430
BEGIN DESCRIPTION:
Upper Denton 115 21.0
END DESCRIPTION:
XS GIS Cut Line= 3
      2250168.16      7234706.63      2248459.86      7235394.12
      2246668.23      7235956.61
#Sta/Elev= 30
  3161.8 1030.22    3204 1024.05  3257.9 1026.51  3323.1 1018.99    3503 1012.03
  3932.9 1012.64  4572.3  978.57  4601.9  973.58  4933.4   973.5  4956.3  969.32
  4957.7  968.82  4965.8  969.32  4983.4  973.96  5062.6  972.18  5517.7  974.19
  5926.5 1006.42  6020.8 1009.94    6157 1004.81  6211.4 1002.91  6238.6  988.83
  6243.8   994.7  6261.9  986.13  6282.9  984.44  6303.4  995.08  6308.6  988.66
  6314.3  997.49  6335.3 1005.31  6399.2 1008.91    6503 1015.11  6881.1 1021.42
#Mann= 7 ,-1 , 0
  3161.8     .05       0  4933.4     .12       0  4956.3     .07       0
  4965.8     .12       0  5062.6     .05       0    6157     .12       0
  6399.2     .05       0
Bank Sta=4956.3,4965.8
XS Rating Curve= 0 ,0
Exp/Cntr=0.3,0.1

Type RM Length L Ch R = 1 ,9939    ,530,530,530
BEGIN DESCRIPTION:
Upper Denton 115 20.0
END DESCRIPTION:
XS GIS Cut Line= 4
      2249876.54      7234449.67      2248334.86      7235039.95
      2247954.37      7235189.49      2246786.22      7235803.86
#Sta/Elev= 30
  3342.9 1032.94  3750.9 1029.54  4278.4  992.41  4423.3   983.8  4533.3  975.02
  4861.5  968.73  4861.9  968.71  4863.3  968.21  4872.3  968.71  5015.4  969.97
  5204.2  970.86  5307.2  982.99  5496.8  992.88  5881.5  998.85  6064.2   998.4
  6080.6  996.14    6097  984.49  6124.7  986.94  6141.1  996.11  6234.9 1001.33
  6256.9  999.32  6273.3  991.44  6289.7  992.31  6295.4  998.87  6311.8  992.91
  6381.8  997.24  6436.8 1006.94  6449.7 1001.37  6488.1 1013.19  6722.4 1016.59
#Mann= 9 ,-1 , 0
  3342.9     .05       0  4278.4     .12       0  4423.3     .05       0
  4861.5     .12       0  4861.9     .07       0  4872.3     .12       0
  5015.4     .05       0  5881.5     .12       0  6381.8     .05       0
Bank Sta=4861.9,4872.3
XS Rating Curve= 0 ,0
Exp/Cntr=0.3,0.1

Type RM Length L Ch R = 1 ,9409    ,414,414,414
BEGIN DESCRIPTION:
Upper Denton 115 19.0
END DESCRIPTION:
XS GIS Cut Line= 3
       2249327.9      7234039.96      2248369.58      7234574.67
      2246793.56      7235699.41
#Sta/Elev= 30
  3884.7 1023.59  4375.3 1003.83  4649.7  994.66  4677.1  989.49  4714.8  992.31
  4817.7  987.78  4920.5  977.63  4958.2  971.91  4971.3  964.83    5031  964.47
  5032.4  963.97  5041.4  964.47  5071.8  968.13  5437.4  968.59  5451.6  965.73
  5795.8  987.77  5990.2   990.1  6047.7  986.28  6148.5   994.7  6169.4  992.56
  6190.3  984.27    6285  985.93  6305.8  988.02  6341.5  999.96  6362.4  992.04
  6412.8  991.45  6469.3 1003.11  6498.8  998.89  6599.6 1008.25  6918.3 1015.42
#Mann= 4 ,-1 , 0
  3884.7     .12       0  4375.3     .05       0    5031    .033       0
  5041.4     .05       0
Bank Sta=5031,5041.4
XS Rating Curve= 0 ,0
Exp/Cntr=0.3,0.1

Type RM Length L Ch R = 1 ,8995    ,366,366,366
BEGIN DESCRIPTION:
Upper Denton 115 18.0
END DESCRIPTION:
XS GIS Cut Line= 3
        2249189.      7233963.57      2248057.08      7234338.56
      2246598.71      7235269.14
#Sta/Elev= 30
  3779.4 1026.43  4063.8 1021.99  4348.3 1005.37  4432.5  999.48    4450  995.82
  4495.7   999.9  4513.4   996.2  4853.9  966.92    4875  968.62  4925.5   964.7
  4974.4  957.33  4975.8  956.83  4984.9  957.33  5052.4   964.8    5225  962.04
  5361.3  963.24  5412.9  966.78    5434  963.58  5506.8  964.37    5528  961.21
  5537.3  965.47  5543.2  963.73  5550.8  971.14  5564.3  972.93  5673.5  974.73
  5681.3  979.01  5716.9  982.35  6043.3 1002.61  6072.7 1000.28  6701.8 1011.66
#Mann= 3 ,-1 , 0
  3779.4     .05       0  4974.4    .033       0  4984.9     .05       0
Bank Sta=4974.4,4984.9
XS Rating Curve= 0 ,0
Exp/Cntr=0.3,0.1

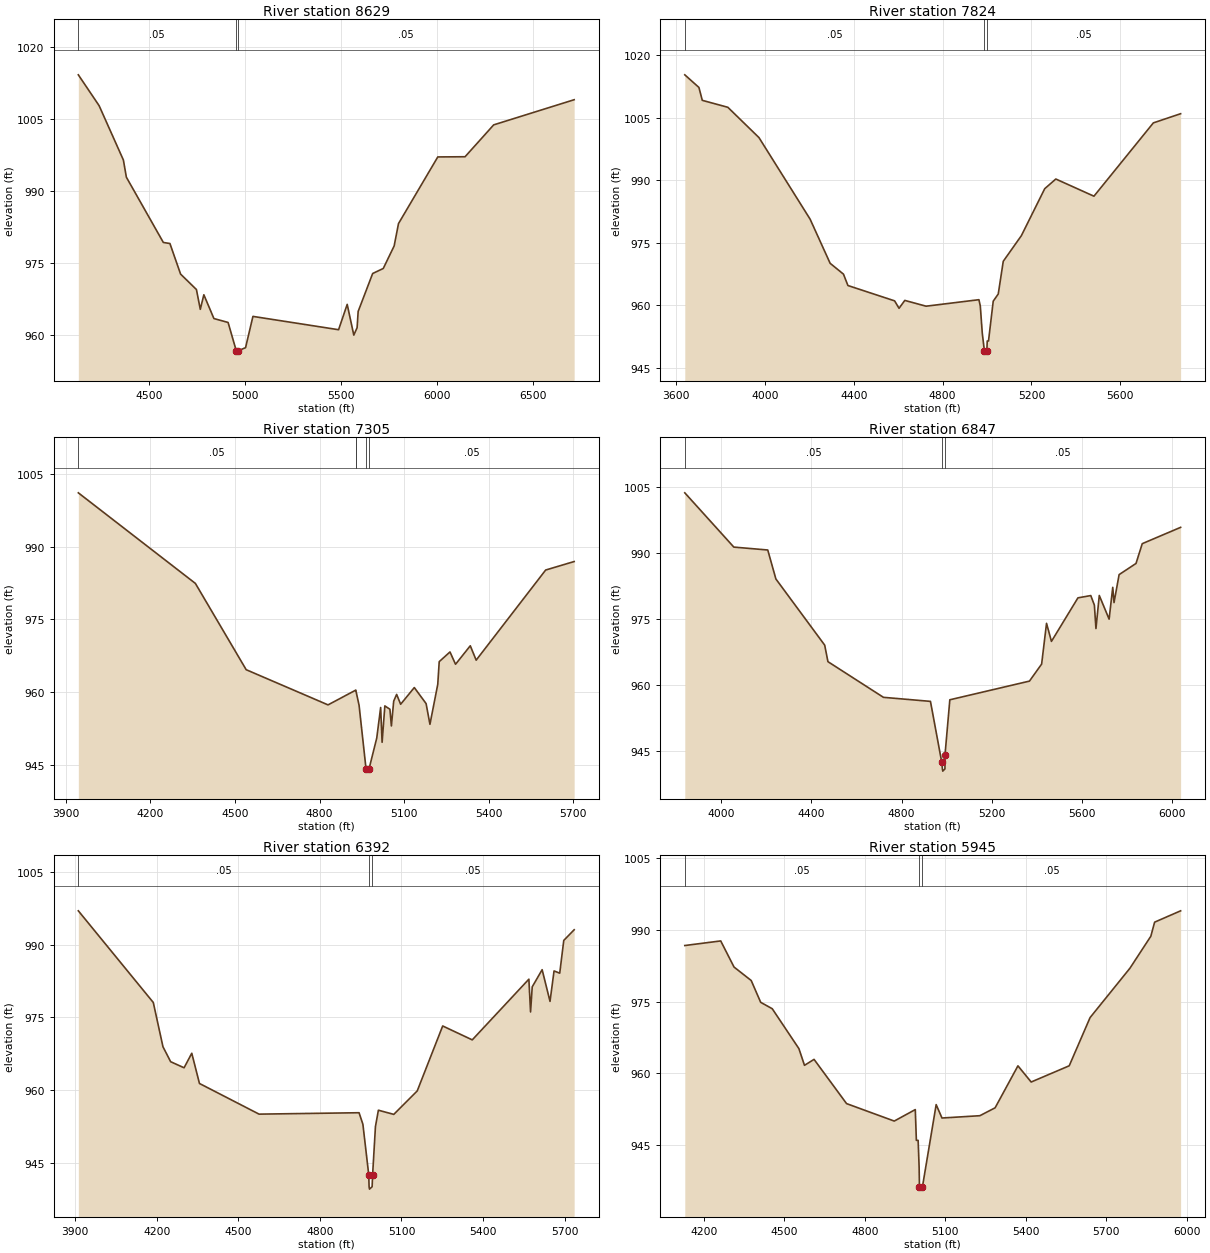
Type RM Length L Ch R = 1 ,8629    ,805,805,805
BEGIN DESCRIPTION:
Upper Denton 115 17.0
END DESCRIPTION:
XS GIS Cut Line= 4
      2248735.87      7233916.19        2247879.        7234060.
      2247798.34      7234406.64      2246570.03      7234988.24
#Sta/Elev= 30
  4131.6 1014.18    4240 1007.76  4366.4  996.46  4381.9  992.89  4574.6  979.31
  4608.9  979.09  4664.5  972.73    4747  969.52  4767.2   965.4  4785.7  968.43
  4838.2  963.48    4912  962.67  4954.6  956.79  4956.1  956.29  4965.1  956.79
    5003  957.42  5041.5  963.93  5487.8  961.16  5532.7  966.43  5567.1  960.04
  5584.3  961.58  5589.8  964.96  5665.4  972.85  5720.7   973.9  5777.4  978.59
  5800.1  983.24  6004.8   997.1  6146.9  997.14  6296.1 1003.77  6715.4    1009
#Mann= 3 ,-1 , 0
  4131.6     .05       0  4954.6    .033       0  4965.1     .05       0
Bank Sta=4954.6,4965.1
XS Rating Curve= 0 ,0
Exp/Cntr=0.3,0.1

Type RM Length L Ch R = 1 ,7824    ,519,519,519
BEGIN DESCRIPTION:
Upper Denton 115 16.0
END DESCRIPTION:
XS GIS Cut Line= 4
      2248822.61      7233842.41      2247767.96      7233877.13
      2247511.88       7234046.4      2246739.98      7234445.36
#Sta/Elev= 30
    3640 1015.29  3703.6 1012.26  3718.7 1009.17  3833.7  1007.5  3973.8 1000.23
  4203.9  980.66    4294  970.07    4354  967.47    4374  964.74  4584.1  961.06
  4604.1  959.27  4629.9  961.17  4725.8  959.78  4963.5  961.34  4969.7  959.83
  4978.6  953.31  4988.2  949.02  4989.7  948.52  4999.1  949.02  5000.9  951.43
  5006.6  951.43  5027.9  960.99  5050.5  962.71    5073  970.55  5154.5   976.7
  5259.6  987.97  5309.5  990.29  5481.1  986.17  5748.4 1003.76  5871.1 1005.96
#Mann= 3 ,-1 , 0
    3640     .05       0  4988.2    .033       0  4999.1     .05       0
Bank Sta=4988.2,4999.1
XS Rating Curve= 0 ,0
Exp/Cntr=0.3,0.1

Type RM Length L Ch R = 1 ,7305    ,458,458,458
BEGIN DESCRIPTION:
Upper Denton 115 15.0
END DESCRIPTION:
XS GIS Cut Line= 3
      2248683.77       7233712.2        2247629.        7233660.
      2246956.35       7233864.1
#Sta/Elev= 30
  3944.3  1001.1  4359.6  982.43  4539.8  964.65  4830.2   957.4  4928.1  960.43
  4928.5  960.46  4940.3  957.31  4964.9  944.25  4966.3  943.75  4975.8  944.25
    5003  950.57  5016.8  956.86    5022  949.69  5031.7  957.19  5049.7   956.5
  5054.9  953.06  5063.1  958.17  5073.5  959.56  5087.8  957.53  5136.2  960.97
    5178  957.67  5191.7   953.4  5219.4  961.63  5224.6  966.31  5262.8  968.31
  5282.5  965.77  5334.8  969.58  5355.7  966.62  5602.2  985.19  5703.3  986.94
#Mann= 5 ,-1 , 0
  3944.3     .05       0  4928.1     .12       0  4928.5     .05       0
  4964.9    .033       0  4975.8     .05       0
Bank Sta=4964.9,4975.8
XS Rating Curve= 0 ,0
Exp/Cntr=0.3,0.1

Type RM Length L Ch R = 1 ,6847    ,455,455,455
BEGIN DESCRIPTION:
Upper Denton 115 14.0
END DESCRIPTION:
XS GIS Cut Line= 3
      2248544.88       7232614.1        2247579.        7233260.
      2246669.84      7233759.95
#Sta/Elev= 30
  3838.1 1003.76  4055.6  991.42  4206.1  990.76  4242.2  984.17  4458.7  969.13
  4473.1  965.37  4719.3  957.26  4927.9  956.34  4977.5  942.62  4980.9  940.98
  4982.5  940.48  4992.1  940.98  4992.5  944.22  5013.8   956.7  5367.1  960.95
    5421  964.82  5442.8  974.08  5464.6  969.98  5582.1  979.88  5639.1   980.4
    5655  978.23    5662   972.9  5676.8  980.42  5720.4  975.04  5736.5  982.27
  5742.2   978.8  5764.7  985.16  5839.7   987.7  5867.4   992.2  6037.6  995.91
#Mann= 3 ,-1 , 0
  3838.1     .05       0  4980.9    .033       0  4992.1     .05       0
Bank Sta=4977.5,4992.5
XS Rating Curve= 0 ,0
Exp/Cntr=0.3,0.1

Type RM Length L Ch R = 1 ,6392    ,447,447,447
BEGIN DESCRIPTION:
Upper Denton 115 13.0
END DESCRIPTION:
XS GIS Cut Line= 3
      2248029.01      7232359.99        2247229.        7233110.
      2246632.47      7233526.78
#Sta/Elev= 30
    3911  997.01  4186.8  978.09  4222.4  968.95  4250.7  965.86  4300.1  964.61
  4328.4  967.61  4356.7  961.37    4576  955.04  4943.9  955.33    4958  952.95
  4979.5  942.53  4980.8  940.06  4982.3  939.56    4992  940.06  4993.7  942.48
  5004.2  952.48    5015  955.85  5071.7  954.99    5158  959.84  5251.6  973.24
  5360.4  970.37  5568.7   982.9  5574.9  976.13    5581  981.31  5617.5  984.86
  5646.5  978.31  5661.3   984.6  5682.2  984.14  5697.1   990.9  5735.3   993.1
#Mann= 3 ,-1 , 0
    3911     .05       0  4980.8    .033       0    4992     .05       0
Bank Sta=4979.5,4993.7
XS Rating Curve= 0 ,0
Exp/Cntr=0.3,0.1

Type RM Length L Ch R = 1 ,5945    ,528,528,528
BEGIN DESCRIPTION:
Upper Denton 115 12.0
END DESCRIPTION:
XS GIS Cut Line= 3
      2247854.94      7232168.44        2247179.        7232710.
      2246516.41      7233434.06
#Sta/Elev= 30
  4129.4  986.73  4263.3  987.69  4312.9  982.23  4376.9  979.42  4412.1  974.87
  4455.3  973.52  4554.6  965.19  4575.4   961.7  4611.1  962.94  4732.2   953.7
  4909.9  950.05  4988.3  952.45  4992.3  946.02  4998.9  946.02  5002.6  940.39
  5003.8  936.33  5005.3  935.83    5015  936.33  5066.1  953.49  5087.7  950.69
  5228.9  951.17  5285.7  952.82  5370.8  961.59  5420.1  958.21  5561.9   961.6
  5639.6  971.67  5788.3     982    5866  988.67  5880.1  991.61    5977  993.98
#Mann= 3 ,-1 , 0
  4129.4     .05       0  5003.8    .033       0    5015     .05       0
Bank Sta=5003.8,5015
XS Rating Curve= 0 ,0
Exp/Cntr=0.3,0.1

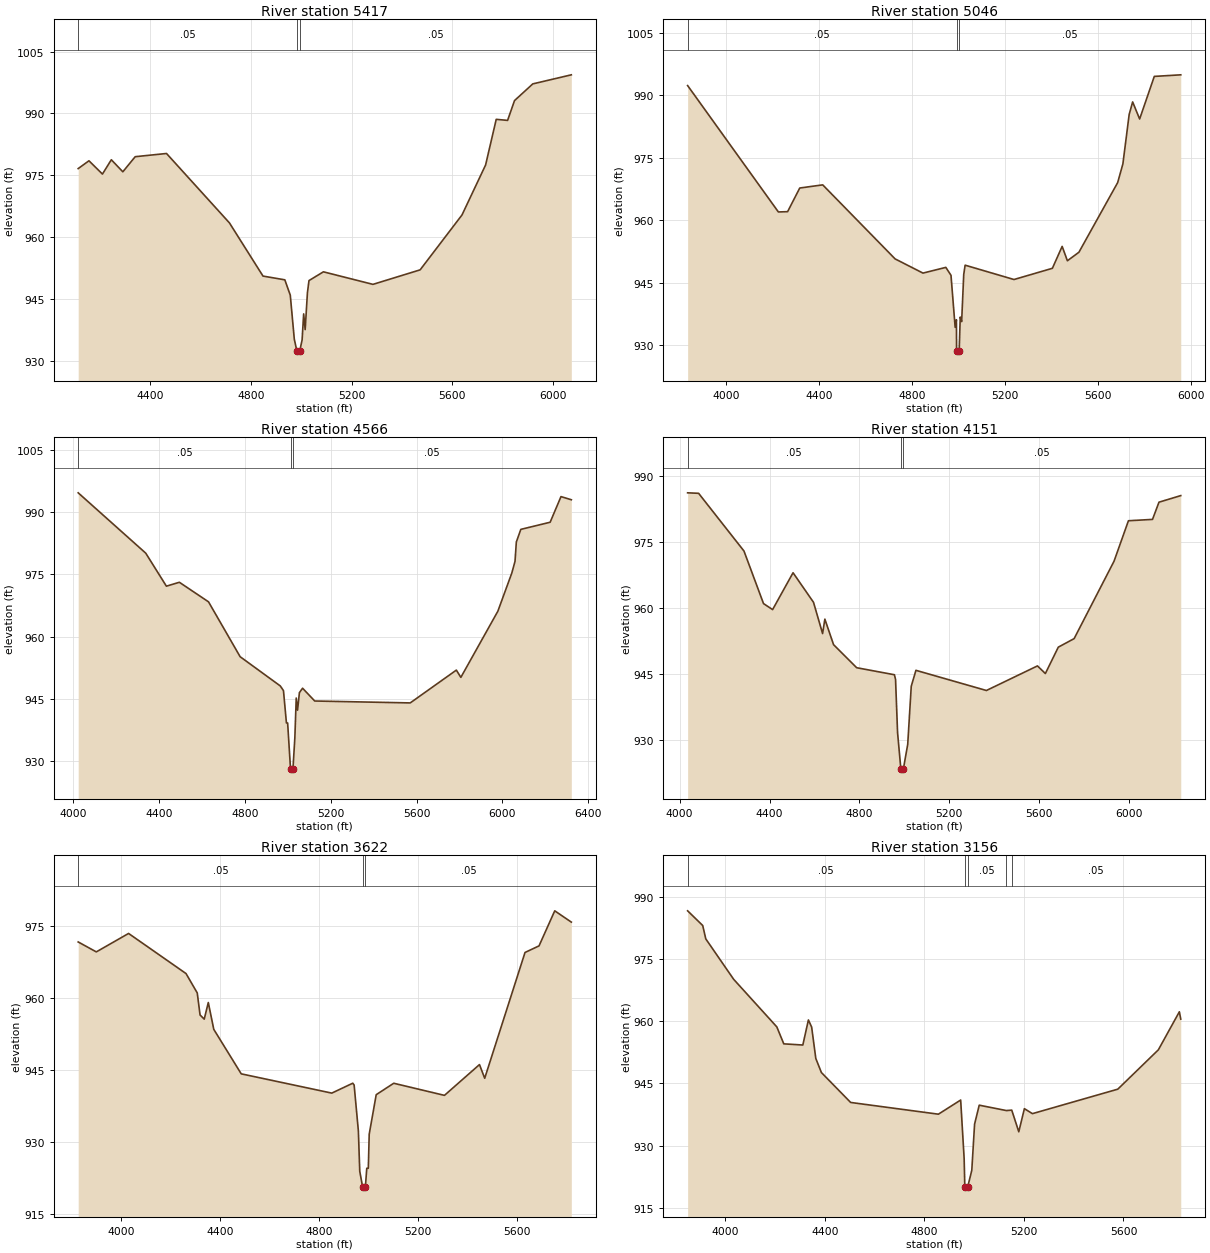
Type RM Length L Ch R = 1 ,5417    ,371,371,371
BEGIN DESCRIPTION:
Upper Denton 115 11.0
END DESCRIPTION:
XS GIS Cut Line= 3
      2247804.02      7232025.61      2247026.81      7232460.11
      2246125.76      7233038.25
#Sta/Elev= 30
  4112.7  976.62  4155.5  978.51  4209.1  975.29  4244.5  978.76  4290.2  975.84
  4339.4   979.5  4463.9  980.28  4714.2  963.45  4847.6  950.56  4934.4  949.65
  4956.1  945.93  4972.1  935.26  4982.4  932.38  4983.9  931.88  4993.6  932.38
  5003.1  935.07  5009.3  941.39  5015.3  937.58  5024.3  946.52  5030.5  949.47
  5087.9  951.59  5284.8  948.55  5472.5  952.07    5639  965.38  5732.8  977.49
  5775.1  988.56  5820.3   988.3  5847.8   993.1  5920.4  997.15  6073.7  999.35
#Mann= 3 ,-1 , 0
  4112.7     .05       0  4982.4    .033       0  4993.6     .05       0
Bank Sta=4982.4,4993.6
XS Rating Curve= 0 ,0
Exp/Cntr=0.3,0.1

Type RM Length L Ch R = 1 ,5046    ,480,480,480
BEGIN DESCRIPTION:
Upper Denton 115 10.0
END DESCRIPTION:
XS GIS Cut Line= 3
      2247896.65      7231741.34        2246829.        7232210.
      2246032.98      7232740.72
#Sta/Elev= 30
  3833.4  992.32    4224     962  4263.8  962.07    4316  967.74  4414.9   968.5
  4726.4  950.74  4846.5  947.33  4944.8   948.7  4967.1   946.8    4985  934.33
  4990.4  936.14  4991.1  928.63  4992.6  928.13  5002.3  928.63  5006.9  936.78
  5012.9  935.69  5021.9  946.99  5027.9  949.23  5238.2  945.79  5403.5  948.48
  5445.6  953.74  5468.1  950.29  5517.7  952.33  5684.5  969.04    5707  973.53
    5734  985.37    5749   988.4  5779.1   984.3  5842.2  994.52  5956.1   994.9
#Mann= 3 ,-1 , 0
  3833.4     .05       0  4991.1    .033       0  5002.3     .05       0
Bank Sta=4991.1,5002.3
XS Rating Curve= 0 ,0
Exp/Cntr=0.3,0.1

Type RM Length L Ch R = 1 ,4566    ,415,415,415
BEGIN DESCRIPTION:
Upper Denton 115 9.0
END DESCRIPTION:
XS GIS Cut Line= 3
      2247860.16      7231475.73        2246929.        7231760.
      2245844.49      7232522.64
#Sta/Elev= 30
  4022.2  994.68  4337.1  980.14  4433.5  972.18  4493.9  973.12  4629.8  968.41
  4777.3  955.18  4964.4  948.14  4979.4     947  4993.2  939.21  4998.8  939.21
  5012.3   928.1  5013.9   927.6  5023.6   928.1  5032.5  935.71  5038.9  945.22
    5045  942.29  5053.7  946.51  5068.5  947.58  5125.2   944.5  5570.4  944.04
  5785.5  951.95  5806.5   950.2    5979  966.14  6044.3  975.37  6059.1  978.18
  6065.2  982.82  6086.1  985.87  6222.9  987.59  6273.4  993.77  6321.6  993.01
#Mann= 3 ,-1 , 0
  4022.2     .05       0  5012.3    .033       0  5023.6     .05       0
Bank Sta=5012.3,5023.6
XS Rating Curve= 0 ,0
Exp/Cntr=0.3,0.1

Type RM Length L Ch R = 1 ,4151    ,529,529,529
BEGIN DESCRIPTION:
Upper Denton 115 8.0
END DESCRIPTION:
XS GIS Cut Line= 3
      2247683.02      7231277.83      2246714.31      7231423.65
      2245766.43      7232184.04
#Sta/Elev= 30
  4035.4  986.12  4084.3  986.01  4286.2  972.93  4373.2  961.02  4413.6  959.66
  4504.6  968.01  4595.7  961.31  4636.1  954.23  4646.2   957.5  4684.9  951.72
  4787.8  946.49  4955.8   944.9  4960.8  943.83  4969.8  931.79  4984.4  923.56
    4986  923.06  4995.7  923.56    5015  929.14  5030.7  942.29  5051.5   945.9
  5365.2  941.33  5592.4   946.9  5627.6  945.17  5685.2  951.15  5755.6  953.08
  5933.3  970.63  5997.3  979.79  6104.5   980.1  6133.3     984  6230.2  985.49
#Mann= 3 ,-1 , 0
  4035.4     .05       0  4984.4    .033       0  4995.7     .05       0
Bank Sta=4984.4,4995.7
XS Rating Curve= 0 ,0
Exp/Cntr=0.3,0.1

Type RM Length L Ch R = 1 ,3622    ,466,466,466
BEGIN DESCRIPTION:
Upper Denton 115 7.0
END DESCRIPTION:
XS GIS Cut Line= 3
      2247433.05      7230604.79        2246379.        7231110.
      2245808.05      7231703.76
#Sta/Elev= 30
  3826.9  971.66  3900.1  969.59  4030.5  973.43  4262.6  965.08    4308  961.04
  4319.3  956.46  4336.2  955.59  4352.6  959.05  4374.8  953.46  4485.7   944.2
  4851.6  940.19  4936.4  942.25  4941.9  941.87    4959  932.33  4964.6  923.92
    4976   920.7  4977.6   920.2  4987.4   920.7    4993  924.54  4999.2  924.54
  5002.8  931.63  5031.1  939.86  5101.9  942.24  5306.9  939.72  5448.4  946.13
  5469.5  943.28  5632.4  969.47    5689  970.84  5752.5  978.14  5819.5  975.79
#Mann= 3 ,-1 , 0
  3826.9     .05       0    4976    .033       0  4987.4     .05       0
Bank Sta=4976,4987.4
XS Rating Curve= 0 ,0
Exp/Cntr=0.3,0.1

Type RM Length L Ch R = 1 ,3156    ,523,523,523
BEGIN DESCRIPTION:
Upper Denton 115 6.0
END DESCRIPTION:
XS GIS Cut Line= 4
      2247313.23      7230344.39        2246279.        7230860.
      2246089.31       7230922.5      2245813.64      7231484.25
#Sta/Elev= 30
    3849  986.61  3909.6  983.07    3922  979.84  4033.9  970.11  4207.3  958.64
  4235.3  954.55  4311.8  954.27  4334.2  960.31  4347.2   958.6    4364  951.02
  4386.4  947.64  4503.9  940.43  4856.4   937.6  4945.9  941.01  4959.9  926.89
  4962.6  920.04  4964.1  919.54    4974  920.04  4990.6  924.07  5001.8   935.2
  5020.5  939.77    5130  938.47  5151.1  938.58  5179.4  933.36  5201.9  938.93
  5234.3  937.73  5577.2  943.63  5740.1  953.11  5824.5  962.28  5830.1  960.52
#Mann= 5 ,-1 , 0
    3849     .05       0  4962.6    .033       0    4974     .05       0
    5130     .12       0  5151.1     .05       0
Bank Sta=4962.6,4974
XS Rating Curve= 0 ,0
Exp/Cntr=0.3,0.1

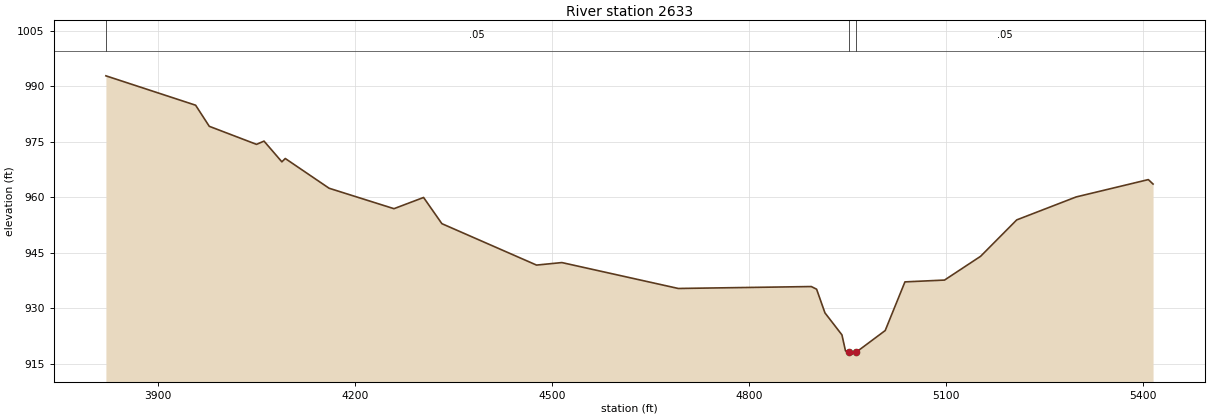
Type RM Length L Ch R = 1 ,2633    ,333,333,333
BEGIN DESCRIPTION:
Upper Denton 115 5.0
END DESCRIPTION:
XS GIS Cut Line= 3
      2247360.14      7230089.17      2246224.73       7230422.5
      2245839.32      7230568.33
#Sta/Elev= 30
  3820.6  992.77  3957.3  984.83  3978.1  979.13  4050.1  974.25  4061.5  975.13
  4088.7  969.53  4093.9  970.43  4160.7  962.39  4259.5  956.87  4304.6   959.9
  4332.5  952.82  4476.7  941.63  4515.3  942.31  4692.7  935.31  4895.3  935.83
  4903.4  935.11  4916.1  928.72    4942  922.77  4947.4  918.45  4952.1  918.07
  4953.6  917.57  4963.5  918.07  5007.9  923.94    5038  937.09  5098.3  937.58
  5153.3  944.01  5208.3  953.84  5298.8  960.04  5408.8  964.73    5416  963.53
#Mann= 3 ,-1 , 0
  3820.6     .05       0  4952.1    .033       0  4963.5     .05       0
Bank Sta=4952.1,4963.5
XS Rating Curve= 0 ,0
Exp/Cntr=0.3,0.1