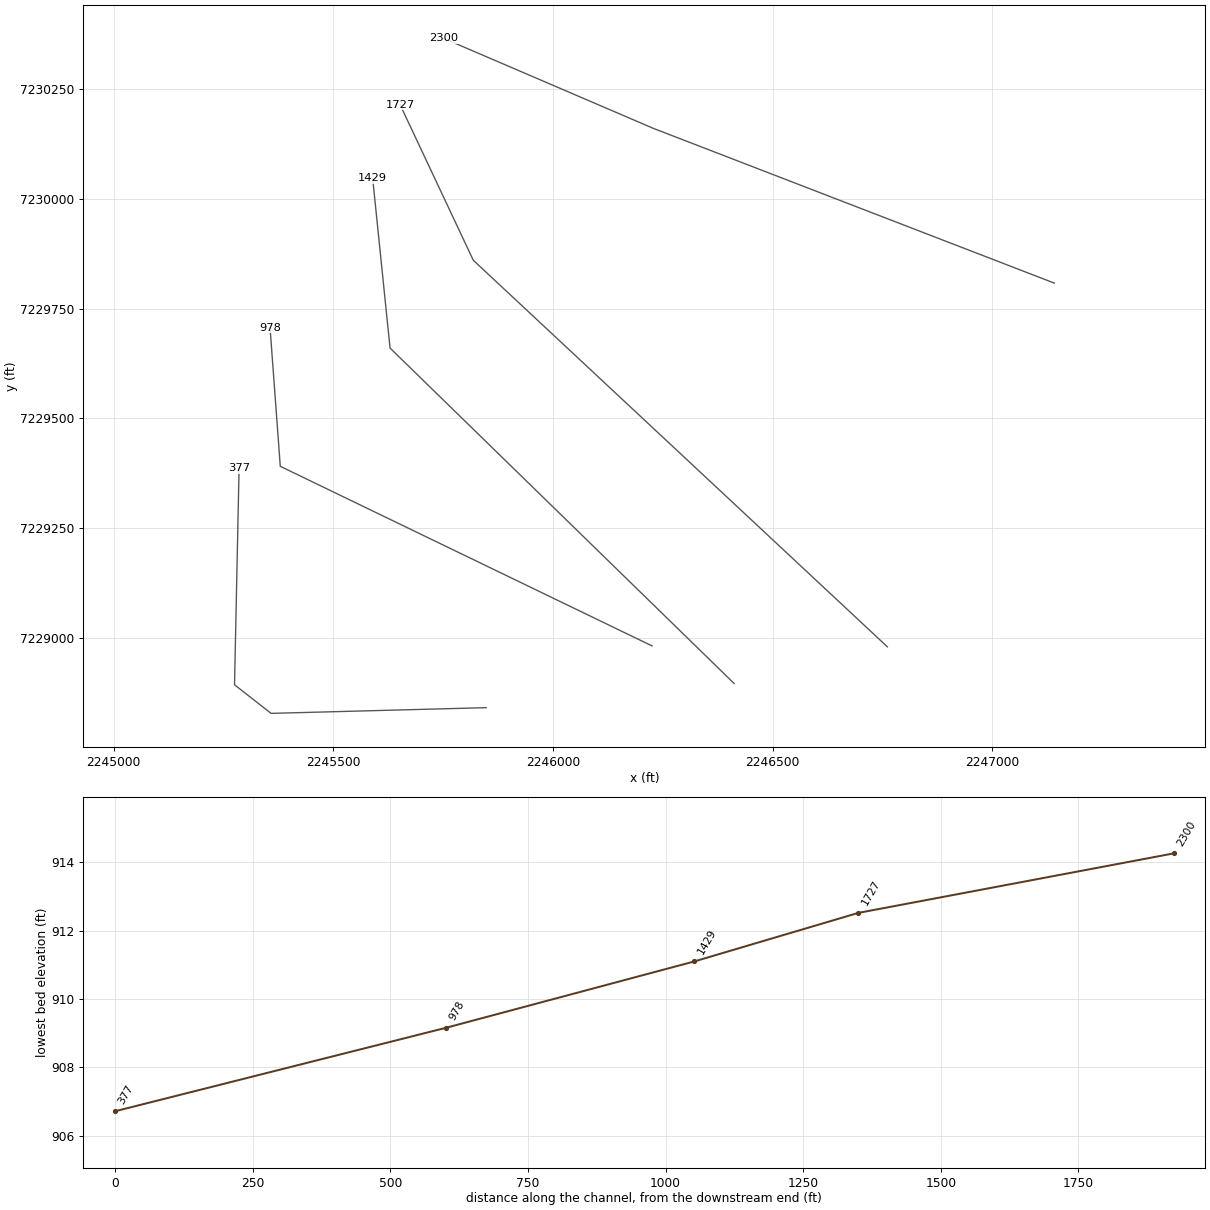
HEC-RAS study Upper Denton 115.prj: Upper Denton 115 Base Level Engineering

--- Upper Denton 115.g01 (geometry) --- (continued)

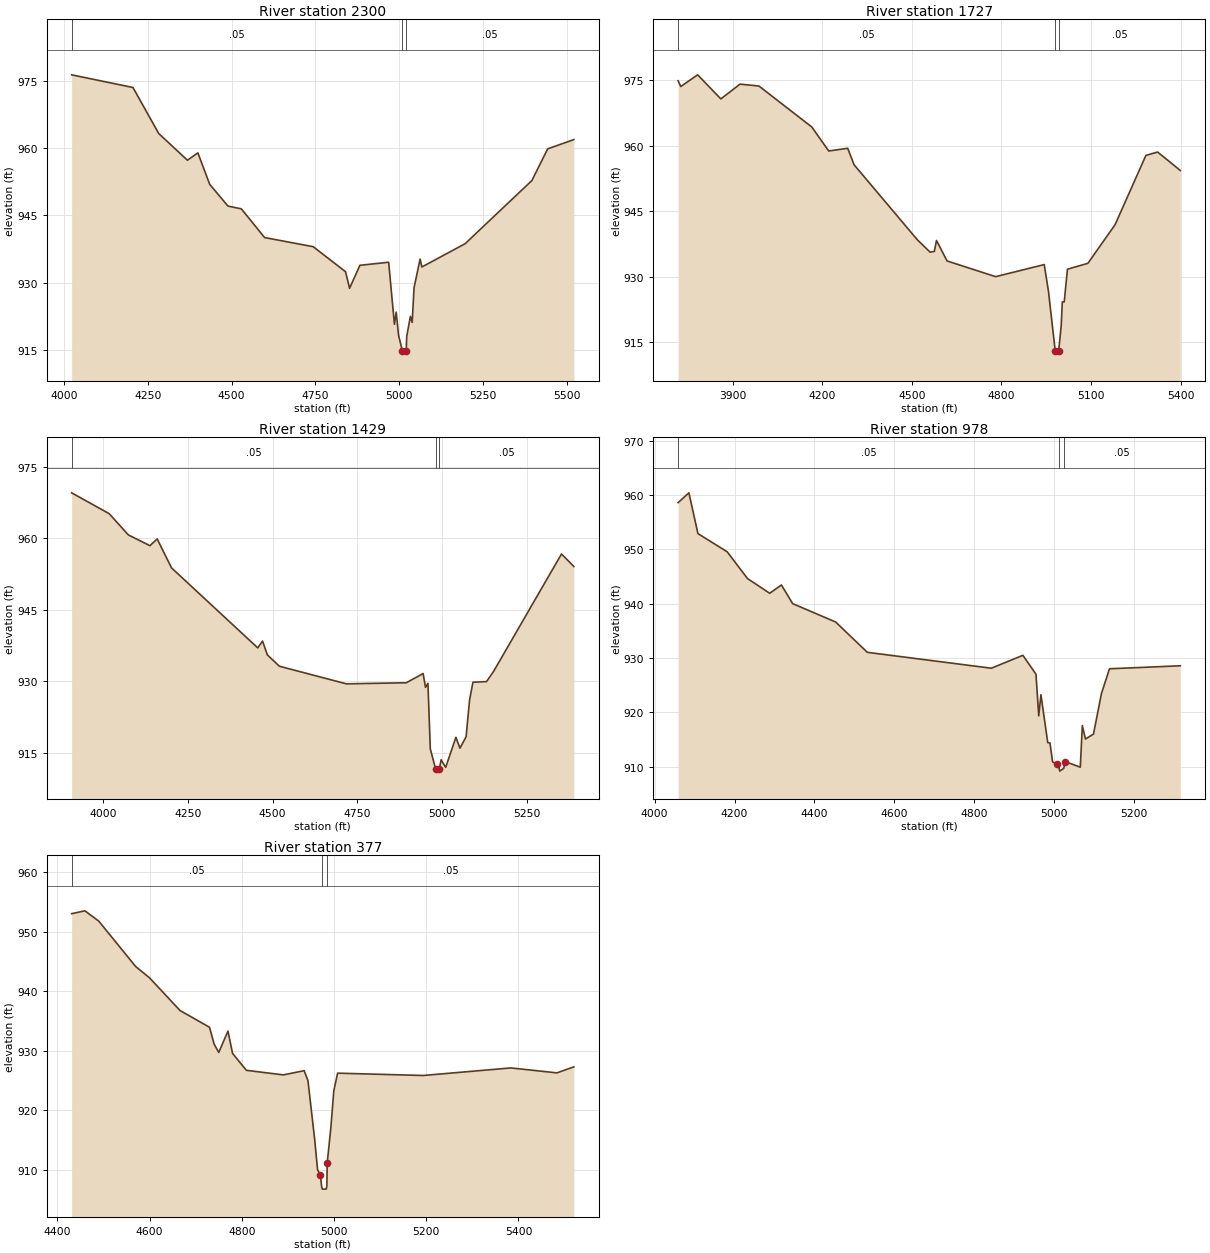
Type RM Length L Ch R = 1 ,2300    ,573,573,573
BEGIN DESCRIPTION:
Upper Denton 115 4.0
END DESCRIPTION:
XS GIS Cut Line= 3
      2247141.38      7229807.92        2246229.        7230160.
      2245750.82      7230365.19
#Sta/Elev= 30
  4022.6  976.41  4205.5  973.58  4282.4   963.3  4368.1  957.34  4399.2  958.98
  4434.5  951.96    4489   947.1  4528.9  946.48  4598.2  940.07  4743.3  938.03
  4839.8  932.44  4851.8  928.74  4882.6  933.87  4968.4  934.56  4985.6   920.7
  4990.9  923.42  4997.9  918.27  5009.4  914.76  5010.9  914.26  5020.8  914.76
  5022.3  917.99  5033.2  922.46  5038.6  921.12  5044.1  928.83  5062.2  935.27
  5067.6   933.5  5196.4  938.69  5395.7   952.8  5442.8  959.87  5520.9  961.95
#Mann= 3 ,-1 , 0
  4022.6     .05       0  5009.4    .033       0  5020.8     .05       0
Bank Sta=5009.4,5020.8
XS Rating Curve= 0 ,0
Exp/Cntr=0.3,0.1

Type RM Length L Ch R = 1 ,1727    ,298,298,298
BEGIN DESCRIPTION:
Upper Denton 115 3.0
END DESCRIPTION:
XS GIS Cut Line= 3
      2246761.28       7228979.8      2245818.48        7229860.
      2245651.83      7230214.13
#Sta/Elev= 30
  3717.4  974.81  3726.2   973.5  3782.9  976.17  3860.5  970.66  3924.5  974.04
    3988  973.61  4164.9  964.24  4221.6  958.75  4285.1  959.37  4306.6  955.59
  4518.6  938.42  4561.1  935.61  4575.2  935.79  4582.4  938.28  4617.8   933.6
  4780.4  930.01  4943.1  932.77  4957.3  926.62  4979.9  913.02  4981.4  912.52
  4991.4  913.02  4999.8  918.74  5003.6  924.24    5010  924.24  5020.8  931.71
  5089.2  933.06  5180.3   941.9  5283.5  957.75  5322.6  958.51  5398.6   954.3
#Mann= 3 ,-1 , 0
  3717.4     .05       0  4979.9    .033       0  4991.4     .05       0
Bank Sta=4979.9,4991.4
XS Rating Curve= 0 ,0
Exp/Cntr=0.3,0.1

Type RM Length L Ch R = 1 ,1429    ,451,451,451
BEGIN DESCRIPTION:
Upper Denton 115 2.0
END DESCRIPTION:
XS GIS Cut Line= 3
      2246412.24      7228896.44        2245629.        7229660.
      2245589.44      7230046.24
#Sta/Elev= 30
  3906.8  969.49  4017.7  965.11  4074.3  960.65  4137.8   958.4  4159.2  959.82
  4201.6  953.74    4456  936.96  4470.2  938.39  4484.3   935.5  4519.8  933.11
  4717.8  929.41  4894.5  929.64  4944.1  931.58  4951.1  928.67  4958.3  929.52
  4965.3  915.77  4980.8   911.6  4982.4   911.1  4992.3   911.6  4997.1  913.48
  5010.7  911.89  5040.8  918.19  5052.8  915.91    5071  918.33  5081.1  925.98
  5091.1  929.75  5131.3  929.89  5152.2  932.04  5352.5  956.66  5388.9  954.04
#Mann= 3 ,-1 , 0
  3906.8     .05       0  4980.8    .033       0  4992.3     .05       0
Bank Sta=4980.8,4992.3
XS Rating Curve= 0 ,0
Exp/Cntr=0.3,0.1

Type RM Length L Ch R = 1 ,978     ,601,601,601
BEGIN DESCRIPTION:
Upper Denton 115 1.0
END DESCRIPTION:
XS GIS Cut Line= 3
      2246225.45      7228981.88      2245379.06      7229390.75
      2245355.75      7229706.72
#Sta/Elev= 30
  4058.8  958.63  4085.8  960.44  4108.4  952.93  4181.7  949.57  4232.5  944.64
  4288.1  941.93  4317.3  943.46  4345.5  940.02    4453  936.64  4532.4  931.05
  4842.7  928.12  4921.6   930.5  4954.4  927.02  4961.3  919.35  4966.8  923.24
  4983.9   914.4  4989.4  914.36    4996  910.85  5008.1  910.41  5012.3  909.66
  5013.9  909.16  5023.8  909.66  5028.1   910.9  5065.3  909.89  5070.4  917.55
  5078.2  915.08  5098.3  915.98  5118.3  923.47  5138.4  928.02  5315.6  928.57
#Mann= 3 ,-1 , 0
  4058.8     .05       0  5012.3    .033       0  5023.8     .05       0
Bank Sta=5008.1,5028.1
XS Rating Curve= 0 ,0
Exp/Cntr=0.3,0.1

Type RM Length L Ch R = 1 ,377     ,0,0,0
BEGIN DESCRIPTION:
Upper Denton 115 0.5
END DESCRIPTION:
XS GIS Cut Line= 4
      2245847.78      7228841.27      2245358.22      7228828.25
      2245274.89      7228893.36      2245285.27      7229386.57
#Sta/Elev= 30
  4431.2  953.04    4460  953.52    4490  951.79    4570  944.15    4600  942.26
  4666.1  936.76  4730.1  933.94  4740.1  931.12  4750.1   929.7  4770.1  933.29
  4780.1  929.54  4810.1   926.7  4890.1  925.93  4935.4  926.64  4943.6  924.93
    4958  915.17  4964.4  909.97  4970.7  909.09    4973  907.22  4974.6  906.72
    4983  906.72  4984.6  907.22  4985.2  911.03  4993.3  917.14  4999.6  923.26
  5007.8  926.22  5193.4  925.83  5383.4   927.1  5483.4  926.27    5520  927.28
#Mann= 3 ,-1 , 0
  4431.2     .05       0    4973    .033       0  4984.6     .05       0
Bank Sta=4970.7,4985.2
XS Rating Curve= 0 ,0
Exp/Cntr=0.3,0.1

Chan Stop Cuts=-1
Use User Specified Reach Order=0
Composite Channel Slope=5