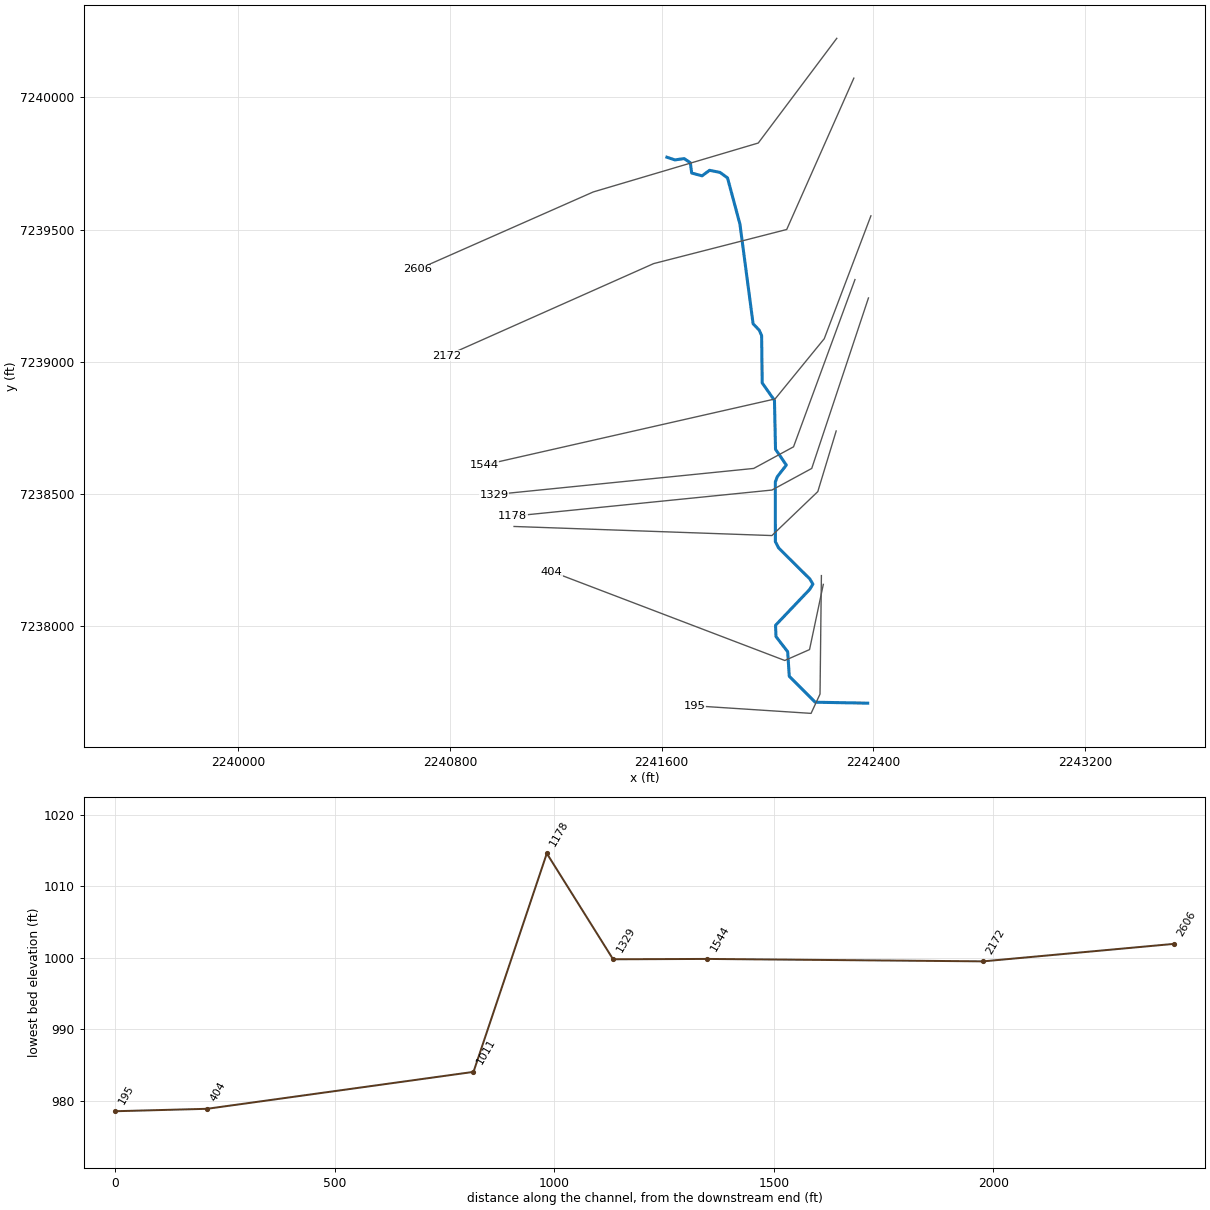
--- Upper Denton 118.prj (project) ---

Proj Title=Upper Denton 118 Base Level Engineering
Current Plan=p01
Default Exp/Contr=0.3,0.1
English Units
Geom File=g01
Flow File=f01
Plan File=p01
Y Axis Title=Elevation
X Axis Title(PF)=Main Channel Distance
X Axis Title(XS)=Station
BEGIN DESCRIPTION:
Upper Denton 118
END DESCRIPTION:
DSS Export Rating Curves= 0
DSS Export Rating Curve Sorted= 0
DSS Export Volume Flow Curves= 0
DXF OffsetX= 0
DXF OffsetY= 0
DXF ScaleX= 1
DXF ScaleY= 10

--- Upper Denton 118.p01 (plan) ---

Plan Title=Multiple Run
Short Identifier=Multiple
Geom File=g01
Flow File=f01
Subcritical Flow
K Sum by GR= 0
Std Step Tol= 0.01
Critical Tol= 0.01
Num of Std Step Trials= 20
Max Error Tol= 0.3
Flow Tol Ratio= 0.001
Split Flow NTrial= 30
Split Flow Tol= 0.02
Split Flow Ratio= 0.02
Log Output Level= 0
Friction Slope Method= 1
Unsteady Friction Slope Method= 2
Unsteady Bridges Friction Slope Method= 1
Parabolic Critical Depth
Global Vel Dist=  1 , 1 , 1
Global Log Level= 0
CheckData=True
Encroach Param= -1, 0, 0, 0
BEGIN DESCRIPTION:
Multiple Run
END DESCRIPTION:

--- Upper Denton 118.f01 (steady flow) ---

Flow Title=Multiple
Program Version=4.10
Number of Profiles= 7
Profile Names=10-year,25-year,50-year,1pct_min,100-year,1pct_plu,500-year
River Rch & RM=Upper Denton 118,Reach-1         ,2606
     606     835    1026     626    1248    2491    1854
Boundary for River Rch & Prof#=Upper Denton 118,Reach-1         , 1
Up Type= 0
Dn Type= 3
Dn Slope=0.005
Boundary for River Rch & Prof#=Upper Denton 118,Reach-1         , 2
Up Type= 0
Dn Type= 3
Dn Slope=0.005
Boundary for River Rch & Prof#=Upper Denton 118,Reach-1         , 3
Up Type= 0
Dn Type= 3
Dn Slope=0.005
Boundary for River Rch & Prof#=Upper Denton 118,Reach-1         , 4
Up Type= 0
Dn Type= 3
Dn Slope=0.005
Boundary for River Rch & Prof#=Upper Denton 118,Reach-1         , 5
Up Type= 0
Dn Type= 3
Dn Slope=0.005
Boundary for River Rch & Prof#=Upper Denton 118,Reach-1         , 6
Up Type= 0
Dn Type= 3
Dn Slope=0.005
Boundary for River Rch & Prof#=Upper Denton 118,Reach-1         , 7
Up Type= 0
Dn Type= 3
Dn Slope=0.005
DSS Import GetInterval= 0
DSS Import GetPeak= 0
DSS Import FillOption= 0

--- Upper Denton 118.g01 (geometry) ---

Geom Title=Existing Conditions
Program Version=4.10

River Reach=Upper Denton 118,Reach-1
Reach XY= 30
      2241619.98      7239773.69       2241650.5      7239763.54
      2241685.09      7239768.48      2241708.52      7239752.85
      2241713.73      7239713.79      2241752.79      7239703.37
      2241781.44      7239724.21       2241820.5       7239716.4
      2241849.15      7239695.56      2241896.02      7239521.08
      2241945.85      7239144.03      2241968.95      7239119.98
      2241978.04       7239099.6      2241980.22      7238920.51
      2242026.62      7238854.47      2242030.55      7238669.59
      2242071.44        7238610.      2242037.45      7238566.19
      2242029.83      7238546.14      2242030.05      7238320.43
      2242042.37      7238296.68      2242159.79        7238180.
      2242171.93        7238160.      2242159.79        7238140.
      2242030.73      7238004.38      2242032.34      7237961.75
       2242076.5      7237904.44      2242082.61      7237811.48
      2242180.45      7237713.52        2242379.        7237710.

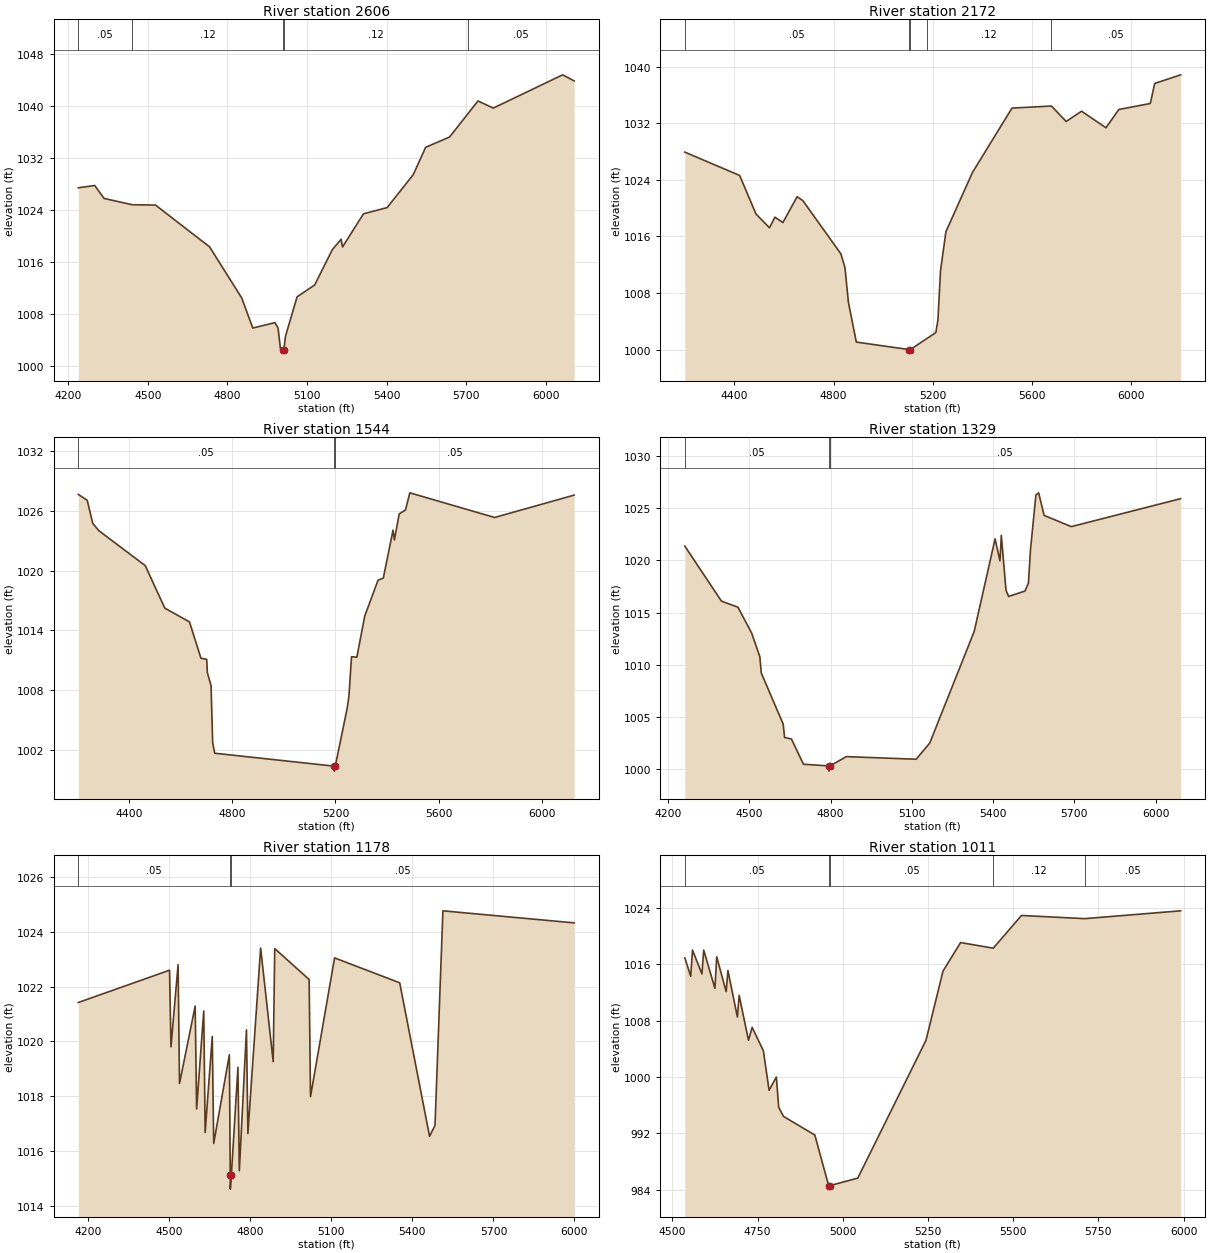
Type RM Length L Ch R = 1 ,2606    ,434,434,434
BEGIN DESCRIPTION:
Upper Denton 118 6.0
END DESCRIPTION:
XS GIS Cut Line= 4
      2242262.14      7240223.07      2241965.36      7239827.36
      2241341.71      7239642.42      2240679.33      7239349.94
#Sta/Elev= 30
  4237.7 1027.39  4299.5 1027.74  4334.9 1025.75  4441.1 1024.78  4528.7 1024.73
  4732.3 1018.31  4853.7 1010.44  4895.4 1005.81  4978.9 1006.64  4990.7 1005.81
  4999.7  1002.6  5008.2 1002.45  5008.4 1001.95  5012.2 1002.45  5018.7 1004.55
  5062.4 1010.62  5128.8 1012.44  5195.3 1017.88  5228.5 1019.47  5233.7 1018.28
  5312.6 1023.38  5401.7 1024.34  5500.4 1029.41    5547 1033.62  5637.2  1035.2
  5707.4 1038.84  5744.4 1040.75    5802 1039.65  6063.5 1044.77  6106.9 1043.84
#Mann= 5 ,-1 , 0
  4237.7     .05       0  4441.1     .12       0  5008.2     .07       0
  5012.2     .12       0  5707.4     .05       0
Bank Sta=5008.2,5012.2
XS Rating Curve= 0 ,0
Exp/Cntr=0.3,0.1

Type RM Length L Ch R = 1 ,2172    ,628,628,628
BEGIN DESCRIPTION:
Upper Denton 118 5.0
END DESCRIPTION:
XS GIS Cut Line= 4
      2242326.66      7240072.57      2242072.88      7239500.49
      2241569.66      7239371.46      2240786.92      7239023.09
#Sta/Elev= 30
  4199.5 1027.91  4421.1 1024.61  4486.7 1019.18  4541.4 1017.22  4563.3 1018.72
  4595.7 1017.96  4653.1 1021.62  4676.4 1021.05  4829.9 1013.53  4846.1 1011.61
  4860.3 1006.66  4892.1 1001.07  5106.1 1000.01  5106.3  999.51  5110.1 1000.01
  5177.3 1001.58  5213.1 1002.41  5221.6 1004.17    5232 1011.12  5253.9 1016.67
  5361.3 1025.05  5520.7 1034.13  5679.8 1034.42  5739.6 1032.24  5801.6 1033.69
  5900.1 1031.35    5952 1033.93  6079.2 1034.78  6096.9 1037.61  6201.6 1038.83
#Mann= 5 ,-1 , 0
  4199.5     .05       0  5106.1    .033       0  5110.1     .05       0
  5177.3     .12       0  5679.8     .05       0
Bank Sta=5106.1,5110.1
XS Rating Curve= 0 ,0
Exp/Cntr=0.3,0.1

Type RM Length L Ch R = 1 ,1544    ,215,215,215
BEGIN DESCRIPTION:
Upper Denton 118 4.0
END DESCRIPTION:
XS GIS Cut Line= 4
      2242391.17      7239552.13      2242214.81      7239087.59
        2242029.        7238860.       2240928.8      7238610.18
#Sta/Elev= 30
  4205.1 1027.68  4239.5 1027.09  4260.9 1024.77  4284.6 1024.03  4464.1 1020.52
  4539.8 1016.24  4635.2 1014.86  4679.7  1011.2    4702 1011.09  4704.3 1009.78
  4718.7 1008.45  4725.1 1002.69    4733 1001.65  5195.4 1000.35  5195.6  999.85
  5199.4 1000.35  5245.6 1006.17  5252.2 1007.35  5262.4 1011.36  5282.9 1011.31
  5313.7 1015.46    5365 1019.05  5385.5 1019.27  5423.1 1024.09  5428.2  1023.1
    5447 1025.72  5471.3 1026.12    5488 1027.84  5816.2 1025.36    6124 1027.61
#Mann= 3 ,-1 , 0
  4205.1     .05       0  5195.4    .033       0  5199.4     .05       0
Bank Sta=5195.4,5199.4
XS Rating Curve= 0 ,0
Exp/Cntr=0.3,0.1

Type RM Length L Ch R = 1 ,1329    ,151,151,151
BEGIN DESCRIPTION:
Upper Denton 118 3.0
END DESCRIPTION:
XS GIS Cut Line= 4
      2242330.93       7239311.2      2242098.69        7238679.
      2241948.15      7238597.28      2240967.53      7238498.35
#Sta/Elev= 30
  4261.9 1021.37  4397.2 1016.09  4458.1 1015.51  4508.2 1013.06  4538.9 1010.77
  4544.2 1009.21    4625 1004.31  4630.4 1003.02  4655.5 1002.88    4700 1000.46
  4793.9  1000.3  4794.1   999.8  4797.9  1000.3  4858.2 1001.19  5115.9 1000.94
  5166.2 1002.49  5330.3 1013.19  5407.4 1022.06  5425.4 1019.95  5430.4  1022.4
  5447.6 1017.13  5457.6 1016.54  5517.9 1017.06  5530.5 1017.83    5538 1021.01
  5558.1 1026.26  5568.2 1026.47  5588.3 1024.31  5688.8 1023.23  6092.3 1025.91
#Mann= 3 ,-1 , 0
  4261.9     .05       0  4793.9    .033       0  4797.9     .05       0
Bank Sta=4793.9,4797.9
XS Rating Curve= 0 ,0
Exp/Cntr=0.3,0.1

Type RM Length L Ch R = 1 ,1178    ,167,167,167
BEGIN DESCRIPTION:
Upper Denton 118 2.0
END DESCRIPTION:
XS GIS Cut Line= 4
      2242381.89      7239241.72       2242167.5      7238597.28
      2242016.97      7238515.56       2241036.3      7238416.63
#Sta/Elev= 30
  4162.8 1021.42  4500.6  1022.6  4505.9  1019.8  4532.2  1022.8  4537.5 1018.46
  4595.5 1021.29  4600.8 1017.53  4627.2 1021.11  4632.4 1016.67  4658.8 1020.18
  4664.1 1016.27  4722.1 1019.51  4725.4  1015.1  4725.6  1014.6  4729.4  1015.1
  4753.8 1019.05    4759 1015.27  4785.4 1020.42  4790.7 1016.63  4837.9 1023.41
  4884.4 1019.26  4890.1 1023.39  5017.5 1022.26  5022.6 1017.98  5111.7 1023.05
  5352.9 1022.14  5463.5 1016.53  5483.6 1016.93  5512.9 1024.77  5998.9 1024.33
#Mann= 3 ,-1 , 0
  4162.8     .05       0  4725.4    .033       0  4729.4     .05       0
Bank Sta=4725.4,4729.4
XS Rating Curve= 0 ,0
Exp/Cntr=0.3,0.1

Type RM Length L Ch R = 1 ,1011    ,607,607,607
BEGIN DESCRIPTION:
Upper Denton 118 1.0
END DESCRIPTION:
XS GIS Cut Line= 4
      2242259.88      7238738.89      2242190.43       7238509.7
      2242016.97      7238343.52      2241042.27      7238377.87
#Sta/Elev= 30
  4536.3 1016.93  4553.7 1014.32  4558.9 1018.04  4586.6 1014.65  4591.8 1018.04
  4624.7  1012.6    4630 1017.08  4657.7 1012.13  4662.9 1015.14  4690.6 1008.52
  4695.8  1011.6  4723.2 1005.22  4733.9 1007.06  4766.9 1003.73  4783.6  998.11
    4805  999.99  4811.9  995.68  4826.1  994.39  4917.9  991.75  4958.4  984.56
  4958.6  984.06  4962.4  984.56    5044  985.63  5244.1 1005.22  5294.1 1015.06
  5345.6 1019.11  5441.5 1018.31  5524.3 1022.96  5709.9 1022.51  5991.3 1023.62
#Mann= 5 ,-1 , 0
  4536.3     .05       0  4958.4    .033       0  4962.4     .05       0
  5441.5     .12       0  5709.9     .05       0
Bank Sta=4958.4,4962.4
XS Rating Curve= 0 ,0
Exp/Cntr=0.3,0.1

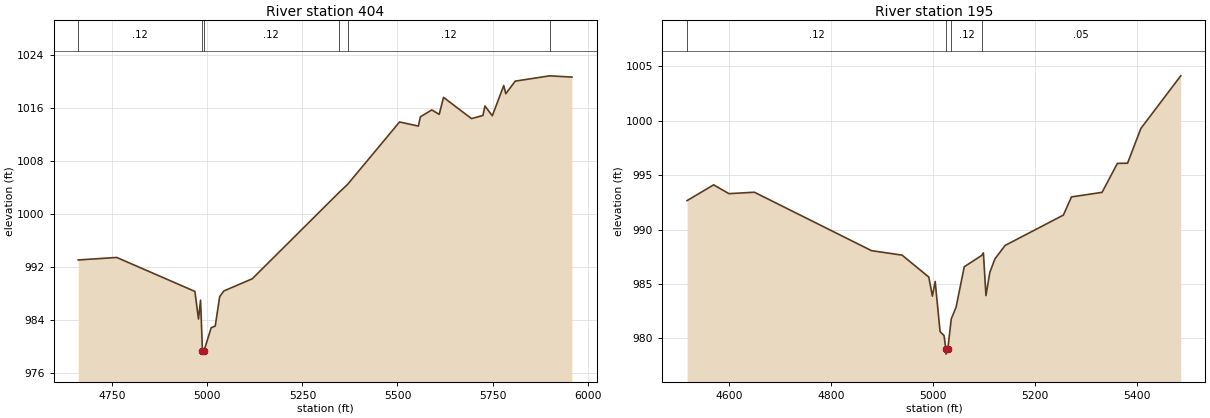
Type RM Length L Ch R = 1 ,404     ,209,209,209
BEGIN DESCRIPTION:
Upper Denton 118 0.5
END DESCRIPTION:
XS GIS Cut Line= 4
      2242211.27      7238159.04      2242159.18      7237912.48
      2242065.58       7237871.3      2241183.61      7238207.67
#Sta/Elev= 30
  4660.5   993.1  4761.7  993.48  4967.3  988.36  4976.8  984.19  4982.2  987.04
  4987.2   979.4  4987.4   978.9  4991.2   979.4  5010.2  982.89  5020.8  983.13
  5032.5  987.56  5043.2  988.42  5118.1  990.26  5345.2 1003.21  5368.9  1004.5
  5505.5 1013.91    5555 1013.29  5560.3 1014.69  5590.4 1015.73  5609.8 1015.06
  5621.2 1017.62  5694.7 1014.42  5724.8 1014.89  5730.1 1016.32  5749.5 1014.85
  5779.6 1019.41  5784.9 1018.17  5809.7 1020.07  5900.5 1020.87  5958.7 1020.68
#Mann= 6 ,-1 , 0
  4660.5     .12       0  4987.2     .03       0  4991.2     .12       0
  5345.2     .05       0  5368.9     .12       0  5900.5     .05       0
Bank Sta=4987.2,4991.2
XS Rating Curve= 0 ,0
Exp/Cntr=0.3,0.1

Type RM Length L Ch R = 1 ,195     ,0,0,0
BEGIN DESCRIPTION:
Upper Denton 118 0.4
END DESCRIPTION:
XS GIS Cut Line= 4
      2242204.03       7238192.2      2242198.82      7237744.28
      2242164.97      7237671.37      2241724.84      7237700.01
#Sta/Elev= 30
  4516.8  992.67    4569  994.12    4599  993.31    4649  993.44    4879  988.07
    4939  987.66  4991.5  985.64  4998.5  983.89    5004  985.24  5013.6  980.63
  5021.4  980.26  5024.9  979.06  5025.2  978.56  5028.9  979.06  5035.6   981.8
  5045.1  982.88  5061.1  986.59  5095.3  987.63  5098.7  987.87  5103.7  983.94
  5111.3  986.07  5121.3  987.31  5141.3  988.55  5255.8  991.34  5271.6  993.01
  5331.7  993.43  5361.8  996.09  5381.8  996.11  5407.9   999.3  5486.2 1004.14
#Mann= 4 ,-1 , 0
  4516.8     .12       0  5024.9     .03       0  5035.6     .12       0
  5095.3     .05       0
Bank Sta=5024.9,5028.9
XS Rating Curve= 0 ,0
Exp/Cntr=0.3,0.1

Chan Stop Cuts=-1
Use User Specified Reach Order=0
Composite Channel Slope=5