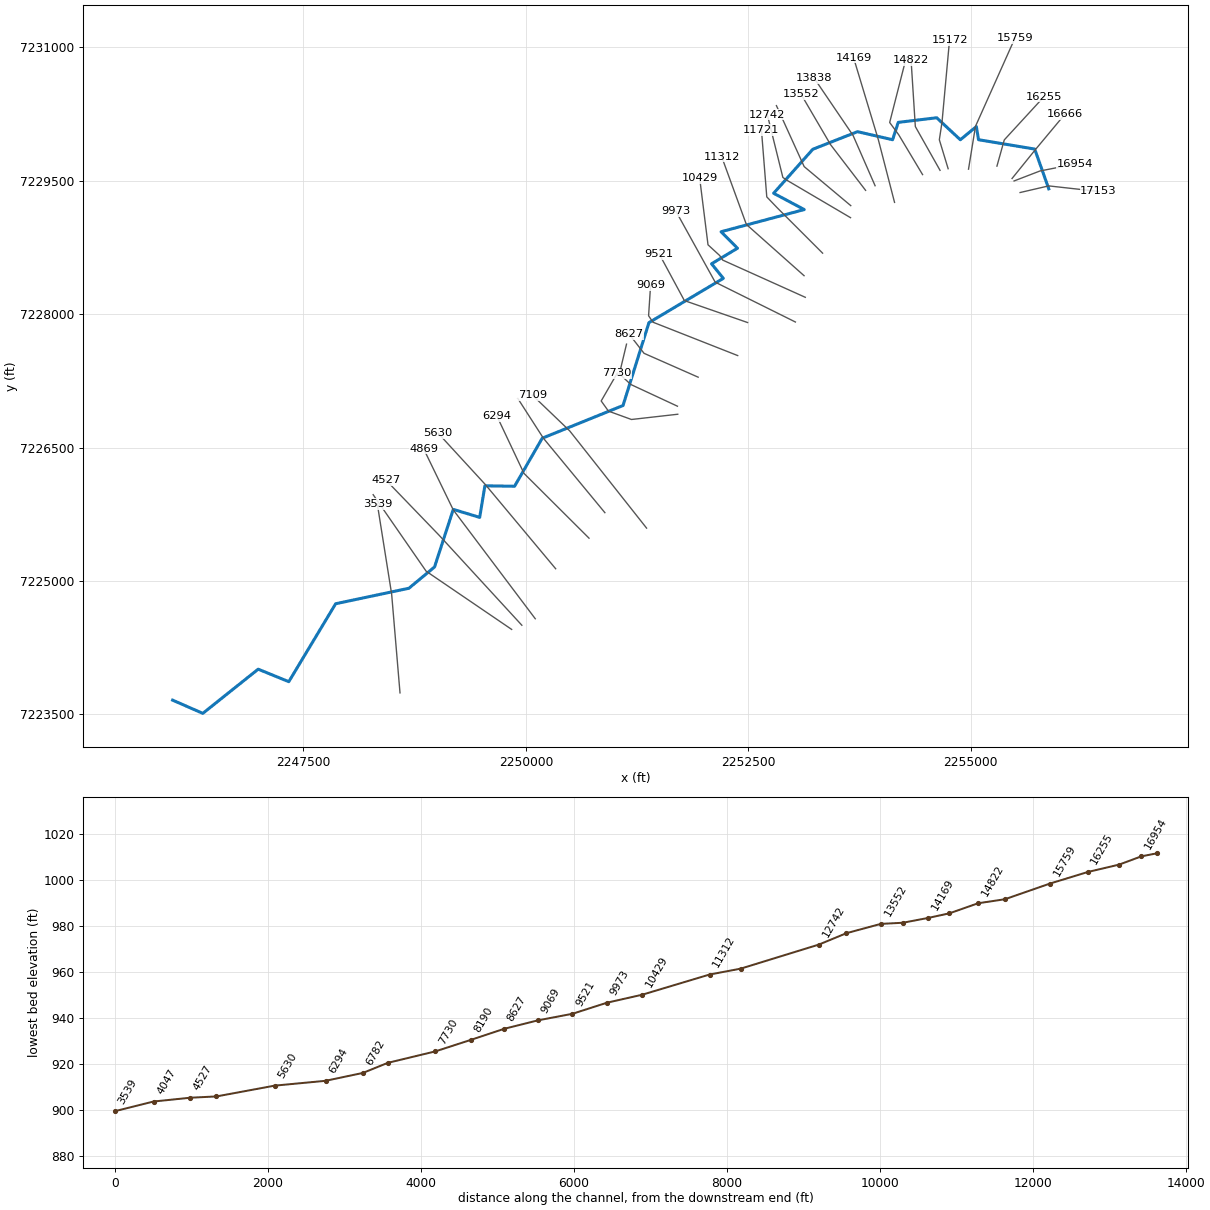
--- Upper Denton 119.prj (project) ---

Proj Title=Upper Denton 119 Base Level Engineering
Current Plan=p01
Default Exp/Contr=0.3,0.1
English Units
Geom File=g01
Flow File=f01
Plan File=p01
BEGIN DESCRIPTION:
Upper Denton 119
END DESCRIPTION:

--- Upper Denton 119.p01 (plan) ---

Plan Title=Multiple Run
Short Identifier=Multiple
Geom File=g01
Flow File=f01
Subcritical Flow
K Sum by GR= 0
Std Step Tol= 0.01
Critical Tol= 0.01
Num of Std Step Trials= 20
Max Error Tol= 0.3
Flow Tol Ratio= 0.001
Split Flow NTrial= 30
Split Flow Tol= 0.02
Split Flow Ratio= 0.02
Log Output Level= 0
Friction Slope Method= 1
Unsteady Friction Slope Method= 2
Unsteady Bridges Friction Slope Method= 1
Parabolic Critical Depth
Global Vel Dist=  1 , 1 , 1
Global Log Level= 0
CheckData=True
Encroach Param= -1, 0, 0, 0
BEGIN DESCRIPTION:
Multiple Run
END DESCRIPTION:

--- Upper Denton 119.f01 (steady flow) ---

Flow Title=Multiple
Number of Profiles=7
Profile Names=10-year,25-year,50-year,1pct_min,100-year,1pct_plu,500-year
River Rch & RM= Upper Denton 119,Reach-1,17153
     733    1032    1285     795    1587    3165    2425
River Rch & RM= Upper Denton 119,Reach-1,11721
     781    1101    1372     850    1695    3382    2594
River Rch & RM= Upper Denton 119,Reach-1,8190
    1117    1607    2030    1272    2539    5065    3984
River Rch & RM= Upper Denton 119,Reach-1,7109
    1806    2651    3395    2152    4295    8569    6899
Boundary for River Rch & Prof#=Upper Denton 119,Reach-1,1
Up Type=0
Dn Type=3
Dn Slope=0.005
Boundary for River Rch & Prof#=Upper Denton 119,Reach-1,2
Up Type=0
Dn Type=3
Dn Slope=0.005
Boundary for River Rch & Prof#=Upper Denton 119,Reach-1,3
Up Type=0
Dn Type=3
Dn Slope=0.005
Boundary for River Rch & Prof#=Upper Denton 119,Reach-1,4
Up Type=0
Dn Type=3
Dn Slope=0.005
Boundary for River Rch & Prof#=Upper Denton 119,Reach-1,5
Up Type=0
Dn Type=3
Dn Slope=0.005
Boundary for River Rch & Prof#=Upper Denton 119,Reach-1,6
Up Type=0
Dn Type=3
Dn Slope=0.005
Boundary for River Rch & Prof#=Upper Denton 119,Reach-1,7
Up Type=0
Dn Type=3
Dn Slope=0.005

--- Upper Denton 119.g01 (geometry) ---

Geom Title=Existing Conditions

River Reach=Upper Denton 119,Reach-1
Reach XY= 30
      2255879.00      7229410.00      2255720.99      7229856.77
      2255089.48      7229961.85      2255065.17      7230109.99
      2254884.88      7229961.48      2254619.36      7230208.90
      2254186.60      7230157.02      2254123.38      7229961.77
      2253729.01      7230052.47      2253226.27      7229854.65
      2252785.99      7229359.79      2253130.14      7229176.51
      2252195.01      7228927.13      2252379.45      7228741.64
      2252087.95      7228566.69      2252220.18      7228403.00
      2251383.93      7227904.96      2251092.70      7226973.24
      2250184.00      7226605.00      2249873.53      7226065.26
      2249539.47      7226069.85      2249481.31      7225715.08
      2249184.44      7225804.91      2248973.60      7225157.29
      2248685.34      7224918.02      2247861.84      7224743.91
      2247335.07      7223867.45      2246990.95      7224008.10
      2246368.45      7223511.10      2246029.00      7223660.00

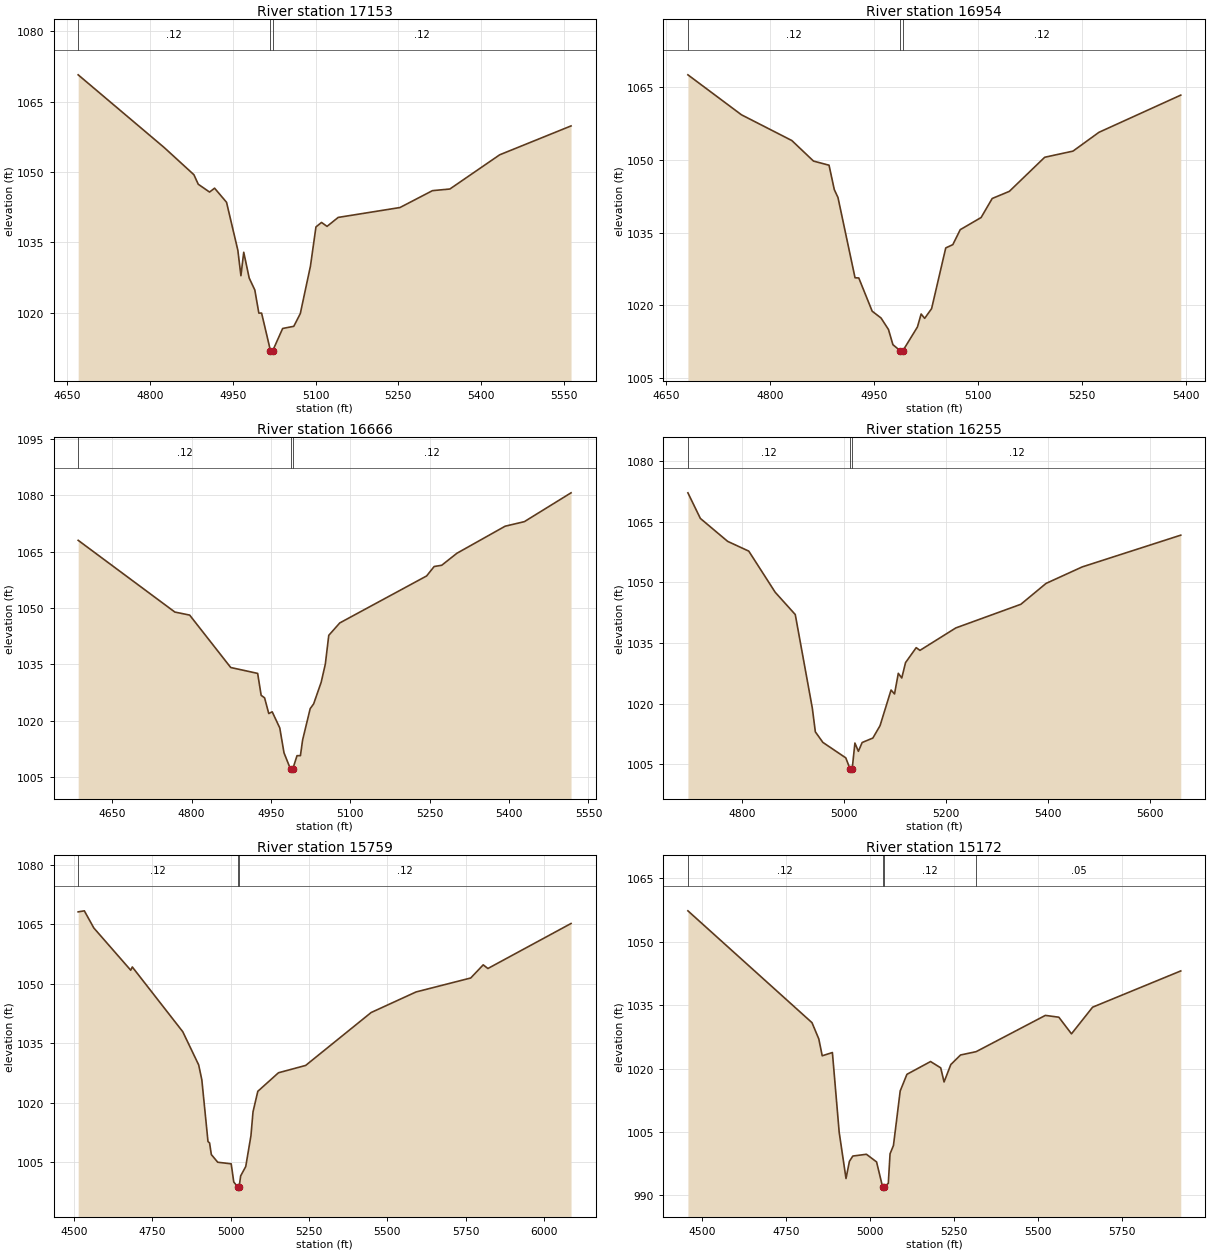
Type RM Length L Ch R = 1,17153,199,199,199
BEGIN DESCRIPTION:
Upper Denton 119 35.5
END DESCRIPTION:
XS GIS Cut Line= 3
      2255556.87      7229368.09      2255878.04      7229442.74
      2256438.84      7229380.24
#Sta/Elev= 30
  4669.5 1070.75  4825.7 1055.22  4879.4 1049.44  4887.3 1047.41  4907.8 1045.74
  4916.9 1046.57  4938.6 1043.56  4959.1 1033.34  4964.7 1027.90  4969.8 1032.90
  4979.7 1027.40  4989.9 1024.85  4997.2 1019.92  5002.2 1019.92  5018.3 1011.88
  5018.6 1011.38  5022.3 1011.88  5040.4 1016.64  5060.6 1017.10  5072.4 1019.81
  5090.8 1029.94  5100.8 1038.30  5110.9 1039.26  5120.9 1038.42  5141.1 1040.33
  5253.2 1042.44  5312.1 1046.04  5343.7 1046.39  5434.1 1053.69  5563.5 1059.85
#Mann=3,-1,0
  4669.5    0.12       0  5018.3    0.07       0  5022.3    0.12       0
Bank Sta=5018.3,5022.3
Exp/Cntr=0.3,0.1

Type RM Length L Ch R = 1,16954,288,288,288
BEGIN DESCRIPTION:
Upper Denton 119 35.0
END DESCRIPTION:
XS GIS Cut Line= 3
      2255489.14      7229498.29      2255779.00      7229610.00
      2256171.47      7229687.54
#Sta/Elev= 30
  4681.4 1067.56  4758.6 1059.31  4831.3 1053.99  4862.5 1049.75  4884.9 1048.90
  4892.5 1043.86  4897.8 1042.23  4922.4 1025.66  4927.8 1025.62  4947.1 1018.76
  4959.9 1017.35  4970.6 1014.98  4977.0 1011.85  4987.4 1010.60  4987.6 1010.10
  4991.4 1010.60  5012.4 1015.51  5017.7 1018.18  5022.8 1017.28  5032.8 1019.29
  5053.2 1031.82  5063.4 1032.50  5074.1 1035.59  5104.2 1038.10  5120.2 1042.03
  5144.9 1043.50  5195.9 1050.54  5236.7 1051.81  5274.1 1055.69  5392.1 1063.37
#Mann=3,-1,0
  4681.4    0.12       0  4987.4    0.07       0  4991.4    0.12       0
Bank Sta=4987.4,4991.4
Exp/Cntr=0.3,0.1

Type RM Length L Ch R = 1,16666,411,411,411
BEGIN DESCRIPTION:
Upper Denton 119 34.0
END DESCRIPTION:
XS GIS Cut Line= 3
      2255466.59      7229526.09      2255728.74      7229850.73
      2256057.94      7230245.77
#Sta/Elev= 30
  4585.6 1068.05  4768.3 1048.93  4796.3 1048.12  4873.9 1034.15  4924.8 1032.58
  4931.4 1026.74  4937.9 1026.06  4945.8 1021.88  4952.3 1022.34  4966.6 1018.05
  4974.6 1011.41  4987.0 1007.03  4987.2 1006.53  4991.0 1007.03  4999.2 1010.65
  5005.6 1010.65  5009.8 1014.85  5024.1 1023.19  5030.6 1024.45  5044.9 1030.24
  5052.7 1035.05  5059.2 1042.72  5080.0 1046.03  5244.1 1058.55  5258.4 1061.07
  5272.7 1061.40  5301.3 1064.59  5392.5 1071.81  5428.9 1073.03  5517.1 1080.71
#Mann=3,-1,0
  4585.6    0.12       0  4987.0    0.07       0  4991.0    0.12       0
Bank Sta=4987,4991
Exp/Cntr=0.3,0.1

Type RM Length L Ch R = 1,16255,496,496,496
BEGIN DESCRIPTION:
Upper Denton 119 33.0
END DESCRIPTION:
XS GIS Cut Line= 3
      2255296.45      7229664.99      2255379.00      7229960.00
      2255825.97      7230446.23
#Sta/Elev= 30
  4693.5 1072.16  4717.9 1065.83  4771.4 1060.16  4812.9 1057.74  4864.8 1047.55
  4904.1 1042.05  4937.5 1018.94  4943.5 1013.03  4958.3 1010.42  5003.2 1006.60
  5011.7 1003.82  5012.0 1003.32  5015.7 1003.82  5021.1 1010.27  5027.9 1008.22
  5035.3 1010.40  5056.3 1011.50  5070.4 1014.57  5092.0 1023.38  5098.8 1022.41
  5106.2 1027.51  5113.0 1026.36  5120.4 1030.16  5141.3 1033.86  5148.7 1033.19
  5219.0 1038.74  5346.6 1044.59  5396.0 1049.75  5466.9 1053.83  5660.3 1061.69
#Mann=3,-1,0
  4693.5    0.12       0  5011.7    0.07       0  5015.7    0.12       0
Bank Sta=5011.7,5015.7
Exp/Cntr=0.3,0.1

Type RM Length L Ch R = 1,15759,587,587,587
BEGIN DESCRIPTION:
Upper Denton 119 32.0
END DESCRIPTION:
XS GIS Cut Line= 3
      2254977.00      7229630.67      2255055.13      7230112.45
      2255497.85      7231102.06
#Sta/Elev= 30
  4513.8 1068.13  4533.4 1068.39  4563.8 1064.06  4681.4 1053.43  4686.4 1054.25
  4847.4 1037.94  4898.1 1029.59  4908.2 1025.84  4927.9 1010.26  4932.9 1009.92
  4938.6 1006.98  4958.9 1005.06  5001.9 1004.65  5010.1 1000.08  5023.1  998.78
  5023.3  998.28  5027.1  998.78  5032.1 1001.61  5048.3 1003.97  5064.9 1011.74
  5071.5 1017.75  5086.8 1022.92  5152.6 1027.59  5239.4 1029.44  5448.3 1042.77
  5591.5 1047.95  5766.0 1051.47  5805.8 1054.78  5820.8 1053.86  6086.0 1065.20
#Mann=3,-1,0
  4513.8    0.12       0  5023.1    0.07       0  5027.1    0.12       0
Bank Sta=5023.1,5027.1
Exp/Cntr=0.3,0.1

Type RM Length L Ch R = 1,15172,350,350,350
BEGIN DESCRIPTION:
Upper Denton 119 31.0
END DESCRIPTION:
XS GIS Cut Line= 4
      2254747.83      7229635.91      2254648.87      7229961.41
      2254679.00      7230160.00      2254763.46      7231081.16
#Sta/Elev= 30
  4458.9 1057.29  4828.0 1030.85  4848.3 1027.00  4858.4 1023.02  4888.7 1023.79
  4908.9 1004.93  4929.2  994.01  4939.3  998.06  4949.4  999.32  4989.9  999.74
  5020.1  997.93  5038.1  992.00  5038.4  991.50  5042.1  992.00  5055.0  992.87
  5060.2  999.85  5070.3 1001.81  5090.4 1014.71  5110.4 1018.64  5180.7 1021.66
  5210.9 1020.17  5220.9 1016.84  5241.0 1020.96  5269.9 1023.21  5316.4 1024.00
  5522.2 1032.57  5562.3 1032.14  5599.9 1028.21  5662.7 1034.51  5925.0 1043.08
#Mann=4,-1,0
  4458.9    0.12       0  5038.1    0.07       0  5042.1    0.12       0
  5316.4    0.05       0
Bank Sta=5038.1,5042.1
Exp/Cntr=0.3,0.1

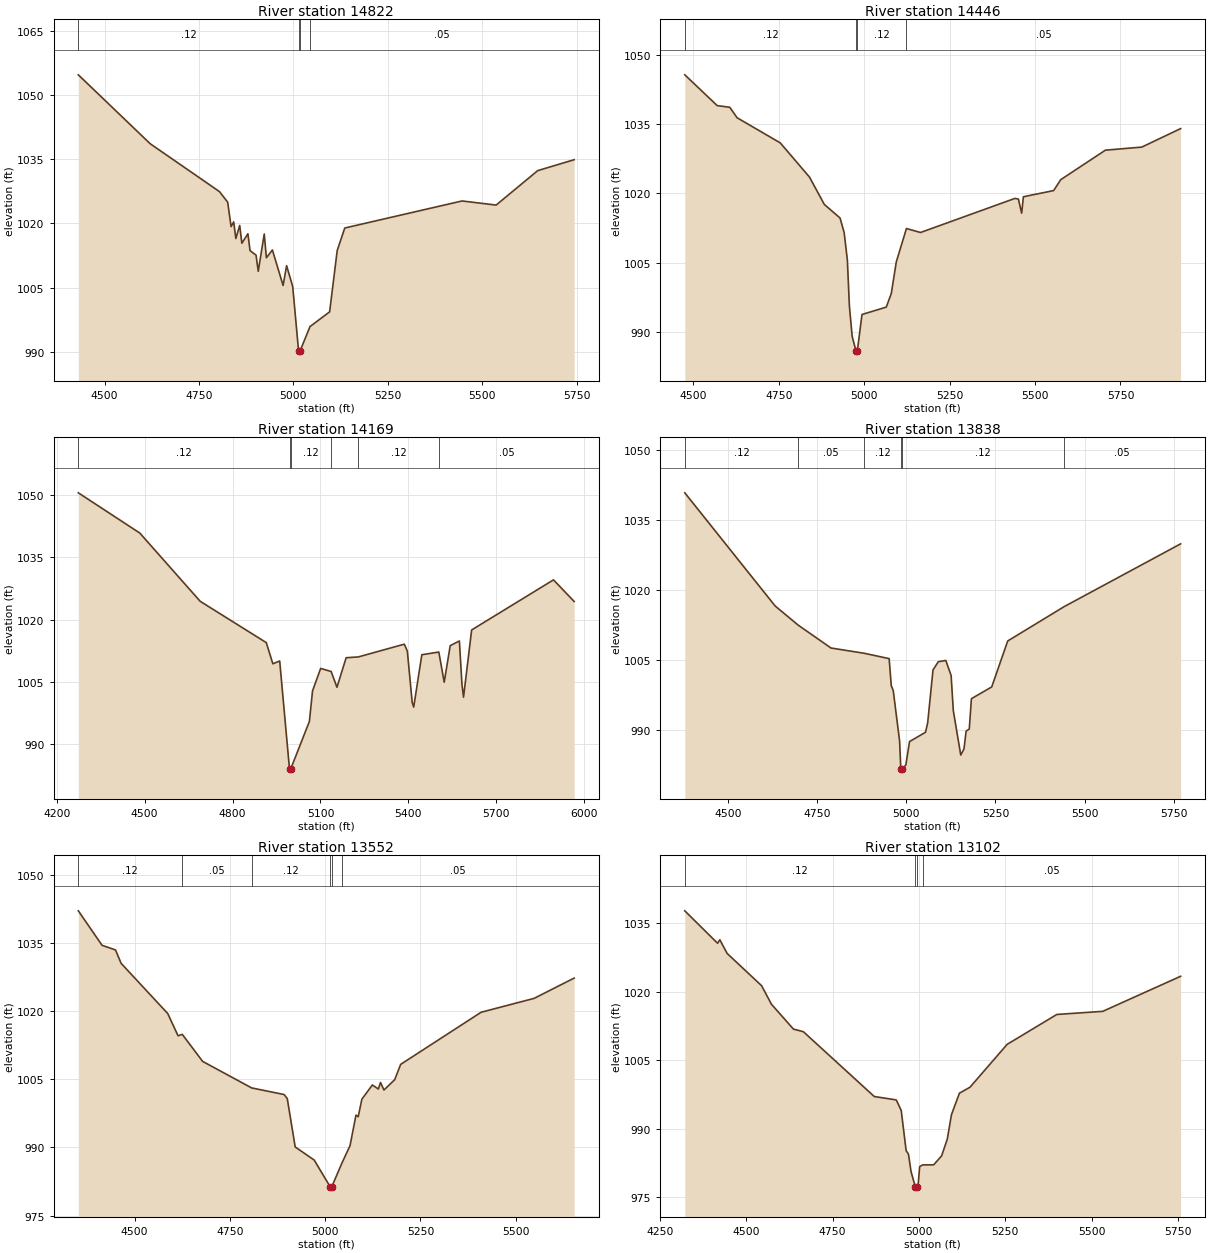
Type RM Length L Ch R = 1,14822,376,376,376
BEGIN DESCRIPTION:
Upper Denton 119 30.0
END DESCRIPTION:
XS GIS Cut Line= 3
      2254656.66      7229617.70      2254379.00      7230110.00
      2254331.24      7230856.17
#Sta/Elev= 30
  4430.7 1054.67  4621.1 1038.59  4804.5 1027.43  4826.2 1024.96  4835.2 1019.27
  4842.1 1020.37  4847.8 1016.49  4858.0 1019.54  4863.7 1015.39  4879.7 1017.60
  4885.4 1013.67  4901.3 1012.61  4907.1 1008.85  4923.0 1017.55  4928.7 1012.01
  4944.6 1013.82  4972.9 1005.55  4982.2 1010.16  4998.4 1005.28  5013.9  990.26
  5014.2  989.76  5017.9  990.26  5044.1  995.95  5096.1  999.39  5116.2 1013.69
  5136.2 1018.94  5446.8 1025.25  5537.0 1024.29  5647.2 1032.33  5743.6 1034.87
#Mann=4,-1,0
  4430.7    0.12       0  5013.9    0.07       0  5017.9    0.12       0
  5044.1    0.05       0
Bank Sta=5013.9,5017.9
Exp/Cntr=0.3,0.1

Type RM Length L Ch R = 1,14446,277,277,277
BEGIN DESCRIPTION:
Upper Denton 119 29.0
END DESCRIPTION:
XS GIS Cut Line= 4
      2254460.34      7229569.74      2254192.11      7230017.66
      2254090.54      7230155.68      2254278.05      7230890.07
#Sta/Elev= 30
  4474.7 1045.73  4569.5 1039.06  4606.4 1038.69  4627.8 1036.42  4754.2 1030.97
  4839.8 1023.55  4883.0 1017.64  4929.2 1014.68  4941.2 1011.51  4950.6 1005.55
  4956.5  995.60  4964.6  989.02  4975.8  985.88  4976.1  985.38  4979.8  985.88
  4993.4  993.76  5064.5  995.36  5079.2  998.32  5093.8 1005.16  5123.5 1012.40
  5164.8 1011.54  5441.0 1018.93  5451.3 1018.78  5460.8 1015.73  5465.9 1019.29
  5554.5 1020.63  5575.1 1022.99  5705.9 1029.39  5812.5 1030.06  5926.1 1034.07
#Mann=4,-1,0
  4474.7    0.12       0  4975.8    0.07       0  4979.8    0.12       0
  5123.5    0.05       0
Bank Sta=4975.8,4979.8
Exp/Cntr=0.3,0.1

Type RM Length L Ch R = 1,14169,331,331,331
BEGIN DESCRIPTION:
Upper Denton 119 28.0
END DESCRIPTION:
XS GIS Cut Line= 3
      2254145.22      7229257.28      2253962.94      7229962.97
      2253684.30      7230884.82
#Sta/Elev= 30
  4273.7 1050.59  4483.4 1040.88  4689.6 1024.40  4915.0 1014.43  4937.5 1009.31
  4960.8 1010.00  4994.3  983.90  4994.6  983.40  4998.3  983.90  5062.1  995.39
  5072.9 1002.78  5100.6 1008.20  5136.4 1007.45  5156.2 1003.64  5187.5 1010.78
  5229.0 1010.97  5386.0 1014.05  5396.4 1012.37  5412.9  999.99  5418.1  998.86
  5445.8 1011.50  5503.8 1012.15  5522.2 1004.87  5542.7 1013.70  5574.0 1014.82
  5582.8 1004.33  5588.1 1001.25  5615.8 1017.48  5895.1 1029.58  5965.6 1024.36
#Mann=6,-1,0
  4273.7    0.12       0  4994.3    0.07       0  4998.3    0.12       0
  5136.4    0.05       0  5229.0    0.12       0  5503.8    0.05       0
Bank Sta=4994.3,4998.3
Exp/Cntr=0.3,0.1

Type RM Length L Ch R = 1,13838,286,286,286
BEGIN DESCRIPTION:
Upper Denton 119 27.0
END DESCRIPTION:
XS GIS Cut Line= 3
      2253926.50      7229444.71      2253679.00      7230010.00
      2253244.20      7230650.45
#Sta/Elev= 30
  4378.4 1040.82  4631.9 1016.62  4696.5 1012.53  4788.6 1007.63  4881.6 1006.51
  4951.8 1005.36  4957.7  999.59  4963.2  998.56  4981.1  987.74  4984.5  981.80
  4984.8  981.30  4988.5  981.80  4998.5  982.60  5009.0  987.62  5053.8  989.61
  5059.9  991.64  5074.8 1002.94  5089.8 1004.70  5110.8 1004.97  5125.7 1001.74
  5131.8  994.24  5152.7  984.74  5161.7  986.04  5167.7  989.84  5176.6  990.30
  5182.6  996.79  5239.6  999.31  5284.4 1009.13  5442.1 1016.45  5769.6 1029.91
#Mann=6,-1,0
  4378.4    0.12       0  4696.5    0.05       0  4881.6    0.12       0
  4984.5    0.07       0  4988.5    0.12       0  5442.1    0.05       0
Bank Sta=4984.5,4988.5
Exp/Cntr=0.3,0.1

Type RM Length L Ch R = 1,13552,450,450,450
BEGIN DESCRIPTION:
Upper Denton 119 26.0
END DESCRIPTION:
XS GIS Cut Line= 3
      2253819.70      7229392.67      2253426.48      7229905.68
      2253095.77      7230470.74
#Sta/Elev= 30
  4352.4 1042.14  4414.7 1034.54  4450.0 1033.52  4464.6 1030.58  4587.0 1019.51
  4614.1 1014.61  4625.2 1014.92  4678.5 1008.97  4807.2 1003.12  4892.5 1001.66
  4900.7 1000.76  4921.5  990.11  4971.3  987.23  5013.4  981.32  5013.6  980.82
  5017.4  981.32  5043.9  986.52  5065.3  990.38  5081.0  997.13  5086.8  996.77
  5096.5 1000.65  5124.0 1003.77  5139.7 1002.88  5145.4 1004.32  5154.4 1002.66
  5182.6 1004.94  5198.3 1008.31  5409.3 1019.79  5548.4 1022.85  5653.5 1027.32
#Mann=6,-1,0
  4352.4    0.12       0  4625.2    0.05       0  4807.2    0.12       0
  5013.4    0.07       0  5017.4    0.12       0  5043.9    0.05       0
Bank Sta=5013.4,5017.4
Exp/Cntr=0.3,0.1

Type RM Length L Ch R = 1,13102,360,360,360
BEGIN DESCRIPTION:
Upper Denton 119 25.0
END DESCRIPTION:
XS GIS Cut Line= 3
      2253653.01      7229220.81      2253129.00      7229660.00
      2252817.27      7230345.42
#Sta/Elev= 30
  4321.5 1037.72  4416.5 1030.62  4423.0 1031.38  4444.2 1028.39  4544.0 1021.33
  4572.6 1017.27  4636.4 1011.82  4665.0 1011.26  4870.6  997.06  4934.3  996.32
  4948.6  994.02  4962.9  985.21  4969.5  984.47  4977.2  980.58  4989.5  977.29
  4989.8  976.79  4993.5  977.29  4998.1  978.05  5002.0  981.72  5010.9  982.09
  5042.6  982.11  5065.6  984.07  5082.1  987.74  5094.2  993.09  5117.3  997.79
  5148.0  999.11  5255.6 1008.49  5399.5 1015.03  5532.5 1015.71  5758.2 1023.39
#Mann=4,-1,0
  4321.5    0.12       0  4989.5    0.07       0  4993.5    0.12       0
  5010.9    0.05       0
Bank Sta=4989.5,4993.5
Exp/Cntr=0.3,0.1

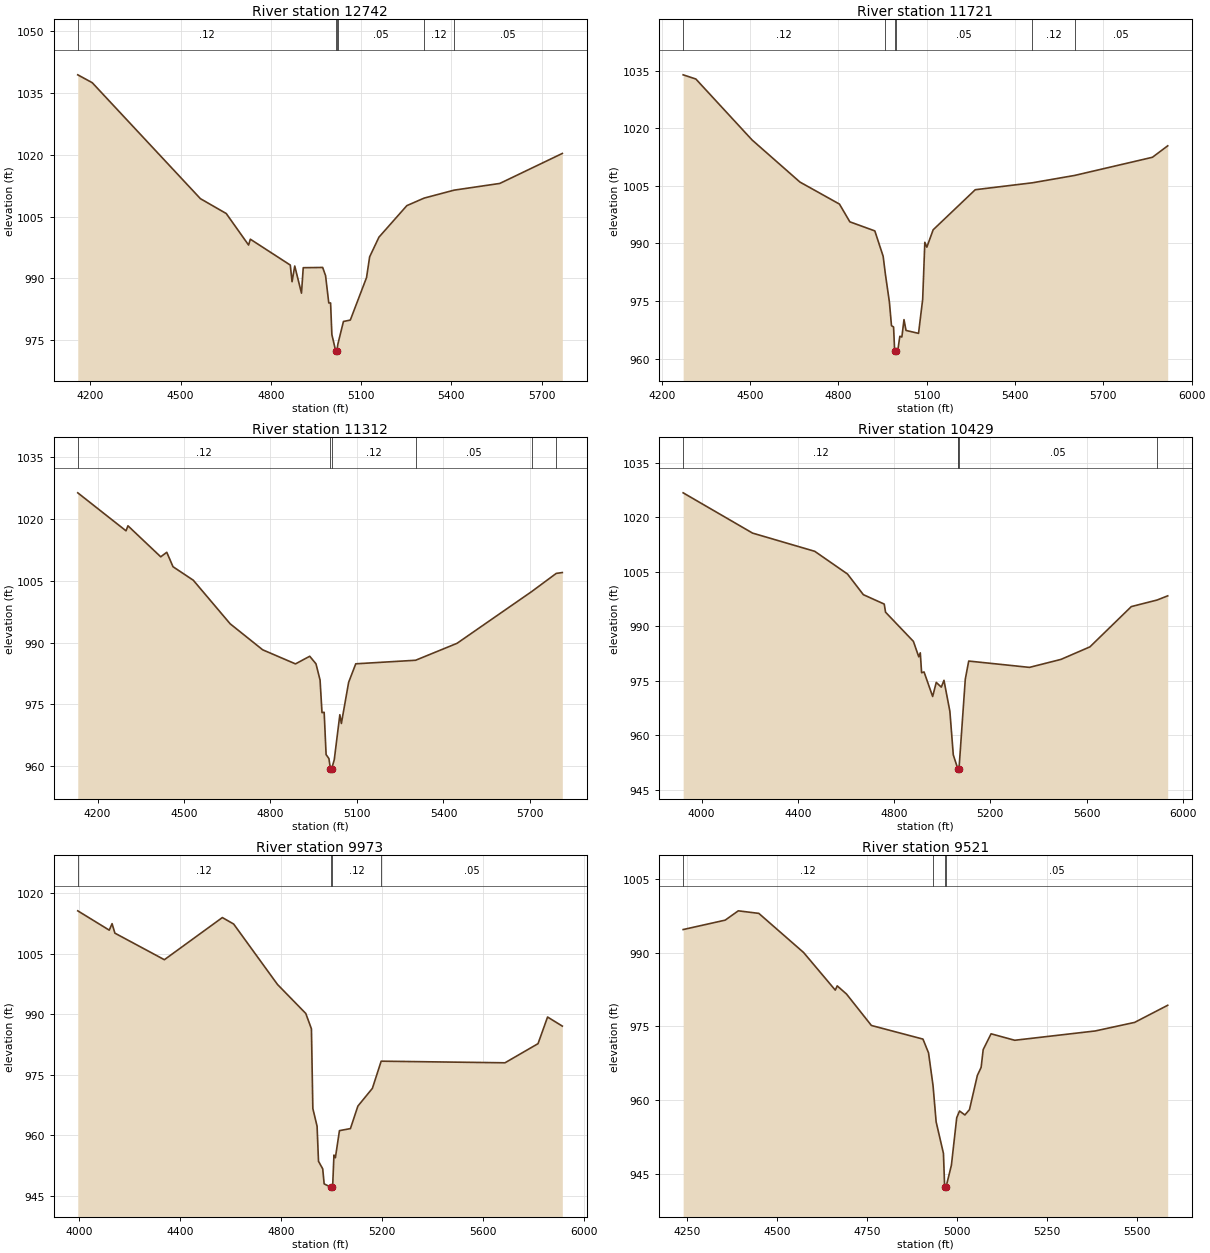
Type RM Length L Ch R = 1,12742,1021,1021,1021
BEGIN DESCRIPTION:
Upper Denton 119 24.0
END DESCRIPTION:
XS GIS Cut Line= 4
      2253650.44      7229085.36      2252929.00      7229510.00
      2252889.56      7229538.06      2252715.54      7230241.62
#Sta/Elev= 30
  4158.4 1039.42  4206.5 1037.51  4566.0 1009.35  4651.9 1005.74  4726.1  998.09
  4731.9  999.51  4864.7  993.23  4870.5  989.19  4879.5  993.00  4901.9  986.41
  4907.7  992.59  4972.3  992.65  4981.9  990.67  4992.6  984.03  4998.6  984.03
  5002.9  976.35  5015.7  972.35  5015.9  971.85  5019.7  972.35  5022.7  974.00
  5041.3  979.53  5064.2  979.88  5118.1  990.20  5128.4  995.23  5159.3 1000.00
  5252.0 1007.66  5309.5 1009.49  5409.1 1011.42  5561.0 1013.05  5768.7 1020.33
#Mann=6,-1,0
  4158.4    0.12       0  5015.7    0.07       0  5019.7    0.12       0
  5022.7    0.05       0  5309.5    0.12       0  5409.1    0.05       0
Bank Sta=5015.7,5019.7
Exp/Cntr=0.3,0.1

Type RM Length L Ch R = 1,11721,409,409,409
BEGIN DESCRIPTION:
Upper Denton 119 23.0
END DESCRIPTION:
XS GIS Cut Line= 4
      2253336.39      7228686.39      2252825.96      7229196.82
      2252708.81      7229319.07      2252648.88      7230071.81
#Sta/Elev= 30
  4272.3 1033.93  4315.4 1032.84  4506.4 1016.96  4669.0 1005.99  4803.3 1000.25
  4838.7  995.62  4923.5  993.26  4951.8  986.65  4959.7  981.82  4973.0  974.74
  4980.1  968.56  4987.2  968.23  4990.9  961.91  4991.1  961.41  4994.9  961.91
  5001.2  961.96  5008.5  965.80  5015.4  965.61  5022.6  970.14  5029.5  967.32
  5072.0  966.56  5086.1  975.42  5093.4  990.29  5100.3  989.03  5121.7  993.55
  5264.7 1003.99  5459.1 1005.80  5602.8 1007.72  5866.6 1012.44  5918.6 1015.43
#Mann=6,-1,0
  4272.3    0.12       0  4959.7    0.05       0  4990.9   0.033       0
  4994.9    0.05       0  5459.1    0.12       0  5602.8    0.05       0
Bank Sta=4990.9,4994.9
Exp/Cntr=0.3,0.1

Type RM Length L Ch R = 1,11312,883,883,883
BEGIN DESCRIPTION:
Upper Denton 119 22.0
END DESCRIPTION:
XS GIS Cut Line= 3
      2253128.08      7228432.90      2252479.00      7229010.00
      2252200.96      7229773.20
#Sta/Elev= 30
  4131.5 1026.29  4298.9 1017.08  4305.6 1018.30  4419.3 1010.78  4440.2 1011.88
  4461.9 1008.38  4532.2 1005.11  4660.1  994.55  4773.0  988.24  4886.7  984.83
  4936.1  986.68  4957.8  984.85  4972.0  980.91  4978.7  973.02  4986.2  973.10
  4992.9  962.85  5002.7  961.89  5008.0  959.34  5008.2  958.84  5012.0  959.34
  5021.3  961.63  5040.6  972.51  5045.9  970.39  5071.1  980.36  5095.8  984.85
  5303.4  985.71  5447.0  989.81  5706.3 1002.37  5791.2 1006.76  5812.3 1006.97
#Mann=6,-1,0
  4131.5    0.12       0  5008.0    0.07       0  5012.0    0.12       0
  5303.4    0.05       0  5706.3    0.12       0  5791.2    0.05       0
Bank Sta=5008,5012
Exp/Cntr=0.3,0.1

Type RM Length L Ch R = 1,10429,456,456,456
BEGIN DESCRIPTION:
Upper Denton 119 21.0
END DESCRIPTION:
XS GIS Cut Line= 5
      2253141.92      7228189.89      2252213.63      7228608.05
      2252179.00      7228660.00      2252048.18      7228780.16
      2251954.43      7229530.14
#Sta/Elev= 30
  3923.4 1026.70  4211.8 1015.61  4470.5 1010.59  4606.6 1004.33  4672.4  998.65
  4759.2  996.06  4764.6  993.83  4880.4  985.79  4902.7  981.54  4909.0  982.64
  4914.5  977.16  4924.7  977.37  4960.4  970.62  4975.4  974.49  4996.4  973.19
  5007.4  975.07  5032.0  966.54  5046.2  954.53  5065.5  950.60  5065.7  950.56
  5066.0  950.06  5069.8  950.56  5096.1  975.41  5110.3  980.37  5362.8  978.63
  5493.8  980.83  5614.1  984.28  5786.1  995.37  5893.3  997.18  5937.4  998.33
#Mann=5,-1,0
  3923.4    0.12       0  5065.5    0.05       0  5065.7    0.07       0
  5069.8    0.05       0  5893.3    0.12       0
Bank Sta=5065.7,5069.8
Exp/Cntr=0.3,0.1

Type RM Length L Ch R = 1,9973,452,452,452
BEGIN DESCRIPTION:
Upper Denton 119 20.0
END DESCRIPTION:
XS GIS Cut Line= 3
      2253030.79      7227912.12      2252129.00      7228360.00
      2251687.09      7229158.60
#Sta/Elev= 30
  3994.0 1015.59  4118.8 1010.80  4129.9 1012.41  4141.1 1010.06  4337.1 1003.48
  4566.8 1013.92  4611.6 1012.32  4785.2  997.35  4897.3  990.16  4919.7  986.35
  4925.3  966.61  4942.1  962.21  4947.7  953.54  4964.5  951.65  4970.1  947.94
  4996.0  947.14  4996.3  946.64  5000.1  947.14  5003.7  947.14  5008.9  955.09
  5014.6  954.42  5030.7  961.13  5074.2  961.64  5103.7  967.21  5161.2  971.61
  5196.0  978.34  5686.6  977.94  5817.4  982.68  5855.2  989.28  5913.6  987.03
#Mann=4,-1,0
  3994.0    0.12       0  4996.0    0.07       0  5000.1    0.12       0
  5196.0    0.05       0
Bank Sta=4996,5000.1
Exp/Cntr=0.3,0.1

Type RM Length L Ch R = 1,9521,452,452,452
BEGIN DESCRIPTION:
Upper Denton 119 19.0
END DESCRIPTION:
XS GIS Cut Line= 3
      2252493.00      7227906.19      2251782.47      7228153.06
      2251500.49      7228675.98
#Sta/Elev= 30
  4239.9  994.78  4356.7  996.70  4393.1  998.60  4450.1  998.08  4574.5  990.10
  4662.6  982.42  4667.9  983.29  4693.7  981.63  4762.9  975.21  4906.2  972.43
  4921.7  969.61  4934.2  962.94  4942.8  955.54  4963.1  949.11  4966.4  942.32
  4966.7  941.82  4970.5  942.32  4985.2  946.70  5000.0  956.39  5007.8  957.76
  5022.7  956.95  5035.4  958.04  5057.3  965.01  5067.8  966.66  5073.5  970.28
  5095.4  973.51  5161.1  972.19  5384.9  974.09  5494.4  975.84  5586.2  979.33
#Mann=4,-1,0
  4239.9    0.12       0  4934.2    0.05       0  4966.4   0.033       0
  4970.5    0.05       0
Bank Sta=4966.4,4970.5
Exp/Cntr=0.3,0.1

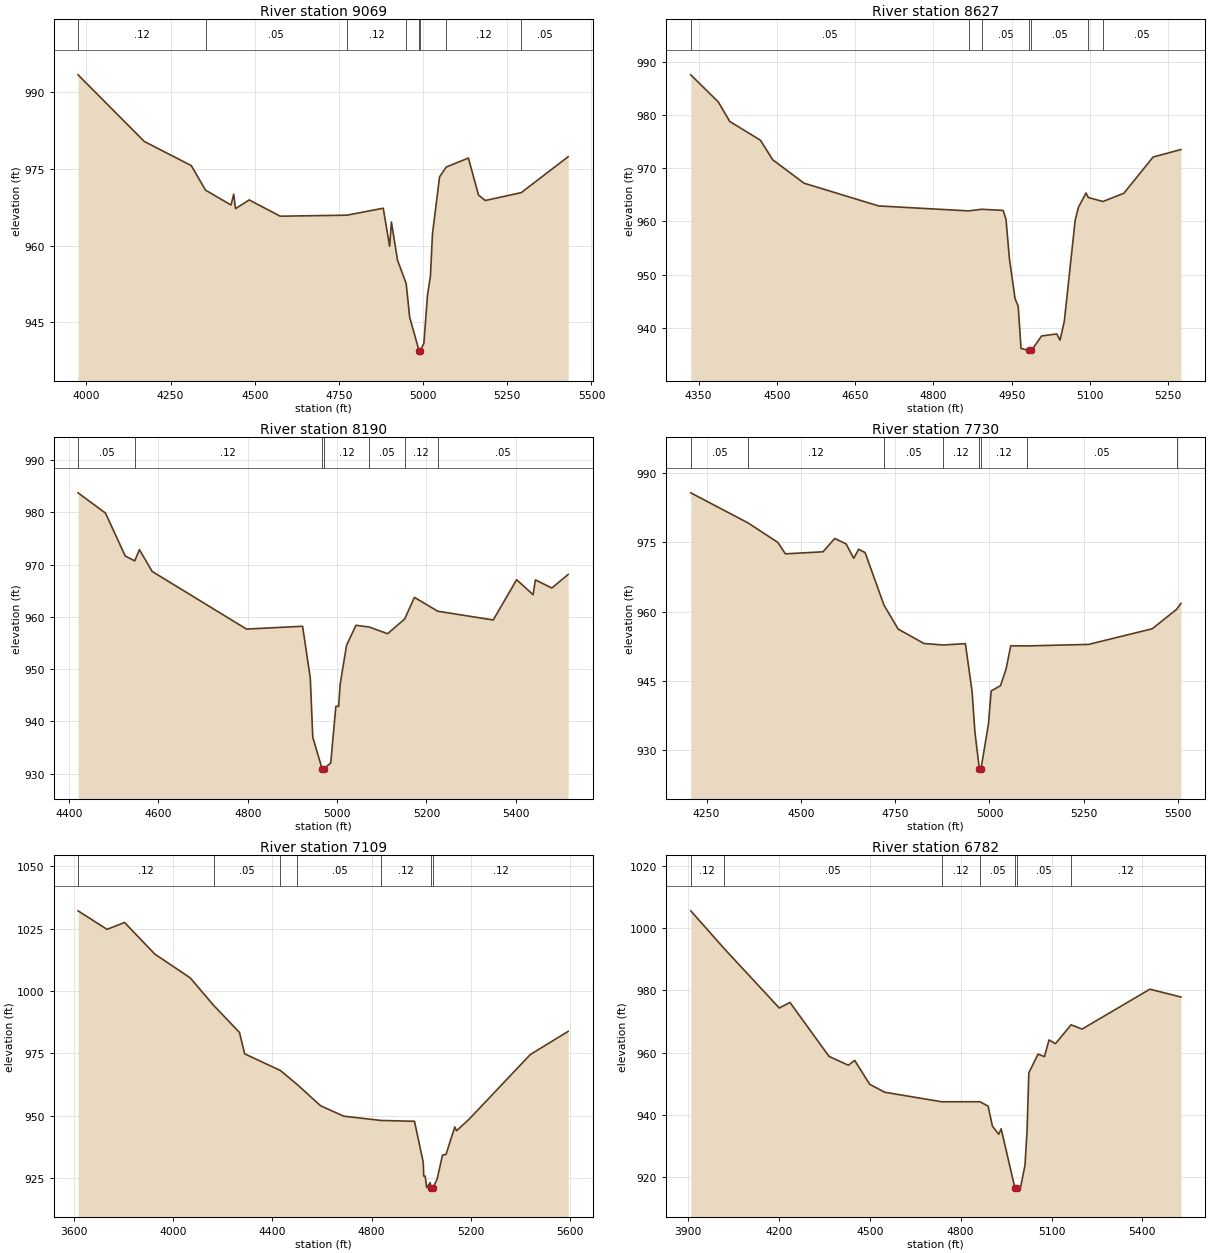
Type RM Length L Ch R = 1,9069,442,442,442
BEGIN DESCRIPTION:
Upper Denton 119 18.0
END DESCRIPTION:
XS GIS Cut Line= 4
      2252381.82      7227534.69      2251429.00      7227910.00
      2251380.04      7227982.57      2251402.65      7228325.71
#Sta/Elev= 30
  3975.3  993.40  4172.2  980.36  4311.5  975.65  4354.0  970.84  4429.7  967.94
  4437.6  970.06  4442.9  967.23  4483.5  968.93  4575.6  965.75  4773.9  965.95
  4881.6  967.31  4900.6  959.86  4905.9  964.61  4924.1  957.13  4949.8  952.58
  4960.1  946.01  4987.8  939.47  4988.1  938.97  4992.0  939.47  5002.4  940.92
  5012.9  950.21  5021.8  954.04  5027.9  962.36  5048.9  973.44  5068.7  975.36
  5134.5  977.13  5164.5  969.90  5184.6  968.82  5291.5  970.36  5430.8  977.39
#Mann=8,-1,0
  3975.3    0.12       0  4354.0    0.05       0  4773.9    0.12       0
  4949.8    0.05       0  4987.8   0.033       0  4992.0    0.05       0
  5068.7    0.12       0  5291.5    0.05       0
Bank Sta=4987.8,4992
Exp/Cntr=0.3,0.1

Type RM Length L Ch R = 1,8627,437,437,437
BEGIN DESCRIPTION:
Upper Denton 119 17.0
END DESCRIPTION:
XS GIS Cut Line= 3
      2251937.44      7227291.61      2251329.00      7227560.00
      2251160.71      7227776.35
#Sta/Elev= 30
  4335.0  987.51  4387.7  982.42  4409.8  978.75  4468.6  975.23  4491.9  971.58
  4551.9  967.18  4694.9  962.91  4867.2  961.98  4892.4  962.28  4933.5  962.07
  4939.0  960.39  4945.4  953.12  4956.3  945.52  4962.3  944.09  4967.8  936.16
  4983.5  935.79  4983.8  935.29  4987.8  935.79  5007.2  938.51  5036.2  938.89
  5042.5  937.72  5050.7  941.26  5071.5  960.22  5077.8  962.67  5092.3  965.33
  5096.7  964.49  5124.7  963.74  5164.7  965.28  5220.8  972.08  5274.1  973.49
#Mann=7,-1,0
  4335.0    0.05       0  4867.2    0.12       0  4892.4    0.05       0
  4983.5   0.033       0  4987.8    0.05       0  5096.7    0.12       0
  5124.7    0.05       0
Bank Sta=4983.5,4987.8
Exp/Cntr=0.3,0.1

Type RM Length L Ch R = 1,8190,460,460,460
BEGIN DESCRIPTION:
Upper Denton 119 16.0
END DESCRIPTION:
XS GIS Cut Line= 4
      2251704.74      7226965.24      2251179.00      7227210.00
      2251052.00      7227329.81      2251131.87      7227663.16
#Sta/Elev= 30
  4420.1  983.74  4481.6  979.86  4525.7  971.65  4547.0  970.71  4557.5  972.87
  4585.9  968.70  4797.3  957.66  4922.8  958.20  4940.1  948.26  4945.6  936.96
  4966.3  930.97  4966.7  930.47  4970.6  930.97  4985.8  932.02  4997.3  942.87
  5003.5  942.87  5007.1  947.20  5021.3  954.57  5042.3  958.38  5071.7  958.06
  5113.1  956.77  5151.4  959.60  5173.2  963.73  5225.4  961.08  5349.6  959.40
  5402.0  967.11  5438.9  964.25  5444.0  967.07  5480.9  965.52  5517.4  968.12
#Mann=7,-1,0
  4420.1    0.05       0  4547.0    0.12       0  4966.3    0.07       0
  4970.6    0.12       0  5071.7    0.05       0  5151.4    0.12       0
  5225.4    0.05       0
Bank Sta=4966.3,4970.6
Exp/Cntr=0.3,0.1

Type RM Length L Ch R = 1,7730,621,621,621
BEGIN DESCRIPTION:
Upper Denton 119 15.0
END DESCRIPTION:
XS GIS Cut Line= 5
      2251708.27      7226874.95      2251187.42      7226815.92
      2250929.00      7226910.00      2250847.14      7227024.25
      2251027.17      7227335.84
#Sta/Elev= 30
  4208.1  985.65  4359.9  979.15  4438.8  974.95  4459.0  972.47  4558.7  972.91
  4589.8  975.79  4620.0  974.61  4640.1  971.51  4653.4  973.46  4670.3  972.74
  4720.4  961.39  4758.0  956.21  4826.4  953.10  4876.9  952.77  4936.2  953.07
  4954.1  942.68  4961.4  934.05  4973.2  926.02  4973.6  925.52  4977.6  926.02
  4997.3  935.63  5004.6  942.85  5029.4  943.99  5044.1  947.57  5056.5  952.61
  5098.9  952.57  5262.9  952.90  5431.7  956.28  5496.1  960.46  5507.7  961.77
#Mann=8,-1,0
  4208.1    0.05       0  4359.9    0.12       0  4720.4    0.05       0
  4876.9    0.12       0  4973.2    0.07       0  4977.6    0.12       0
  5098.9    0.05       0  5496.1    0.12       0
Bank Sta=4973.2,4977.6
Exp/Cntr=0.3,0.1

Type RM Length L Ch R = 1,7109,327,327,327
BEGIN DESCRIPTION:
Upper Denton 119 14.0
END DESCRIPTION:
XS GIS Cut Line= 3
      2251357.49      7225594.44      2250492.90      7226688.19
      2250073.36      7227090.40
#Sta/Elev= 30
  3616.7 1032.20  3733.7 1024.76  3804.2 1027.53  3926.0 1014.85  4068.7 1005.32
  4162.8  994.32  4267.4  983.40  4288.2  974.83  4432.5  968.13  4500.9  962.44
  4594.4  953.99  4687.4  949.82  4838.9  948.09  4972.7  947.77  5008.0  931.30
  5010.0  925.77  5015.8  925.77  5022.0  921.16  5036.1  923.16  5039.1  921.05
  5040.4  920.55  5047.6  921.05  5064.4  924.76  5085.6  934.20  5099.7  934.48
  5135.2  945.49  5142.1  943.97  5191.8  948.50  5439.3  974.52  5592.1  983.85
#Mann=7,-1,0
  3616.7    0.12       0  4162.8    0.05       0  4432.5    0.12       0
  4500.9    0.05       0  4838.9    0.12       0  5039.1    0.07       0
  5047.6    0.12       0
Bank Sta=5039.1,5047.6
Exp/Cntr=0.3,0.1

Type RM Length L Ch R = 1,6782,488,488,488
BEGIN DESCRIPTION:
Upper Denton 119 13.0
END DESCRIPTION:
XS GIS Cut Line= 3
      2250888.72      7225768.07      2250197.76      7226604.86
      2249909.57      7227052.77
#Sta/Elev= 30
  3909.3 1005.50  4017.9  993.56  4201.5  974.30  4236.7  976.11  4365.7  958.77
  4429.5  955.94  4450.3  957.49  4499.8  949.83  4549.3  947.27  4737.7  944.21
  4863.7  944.22  4890.7  942.80  4905.0  936.39  4925.9  933.77  4933.7  935.54
  4978.9  916.67  4980.2  916.17  4987.4  916.67  4998.1  916.87  5012.5  923.87
  5019.2  934.88  5025.1  953.47  5055.5  959.50  5076.6  958.71  5091.8  964.05
  5112.9  962.85  5164.6  968.92  5200.8  967.54  5424.6  980.34  5527.1  977.84
#Mann=7,-1,0
  3909.3    0.12       0  4017.9    0.05       0  4737.7    0.12       0
  4863.7    0.05       0  4978.9   0.033       0  4987.4    0.05       0
  5164.6    0.12       0
Bank Sta=4978.9,4987.4
Exp/Cntr=0.3,0.1

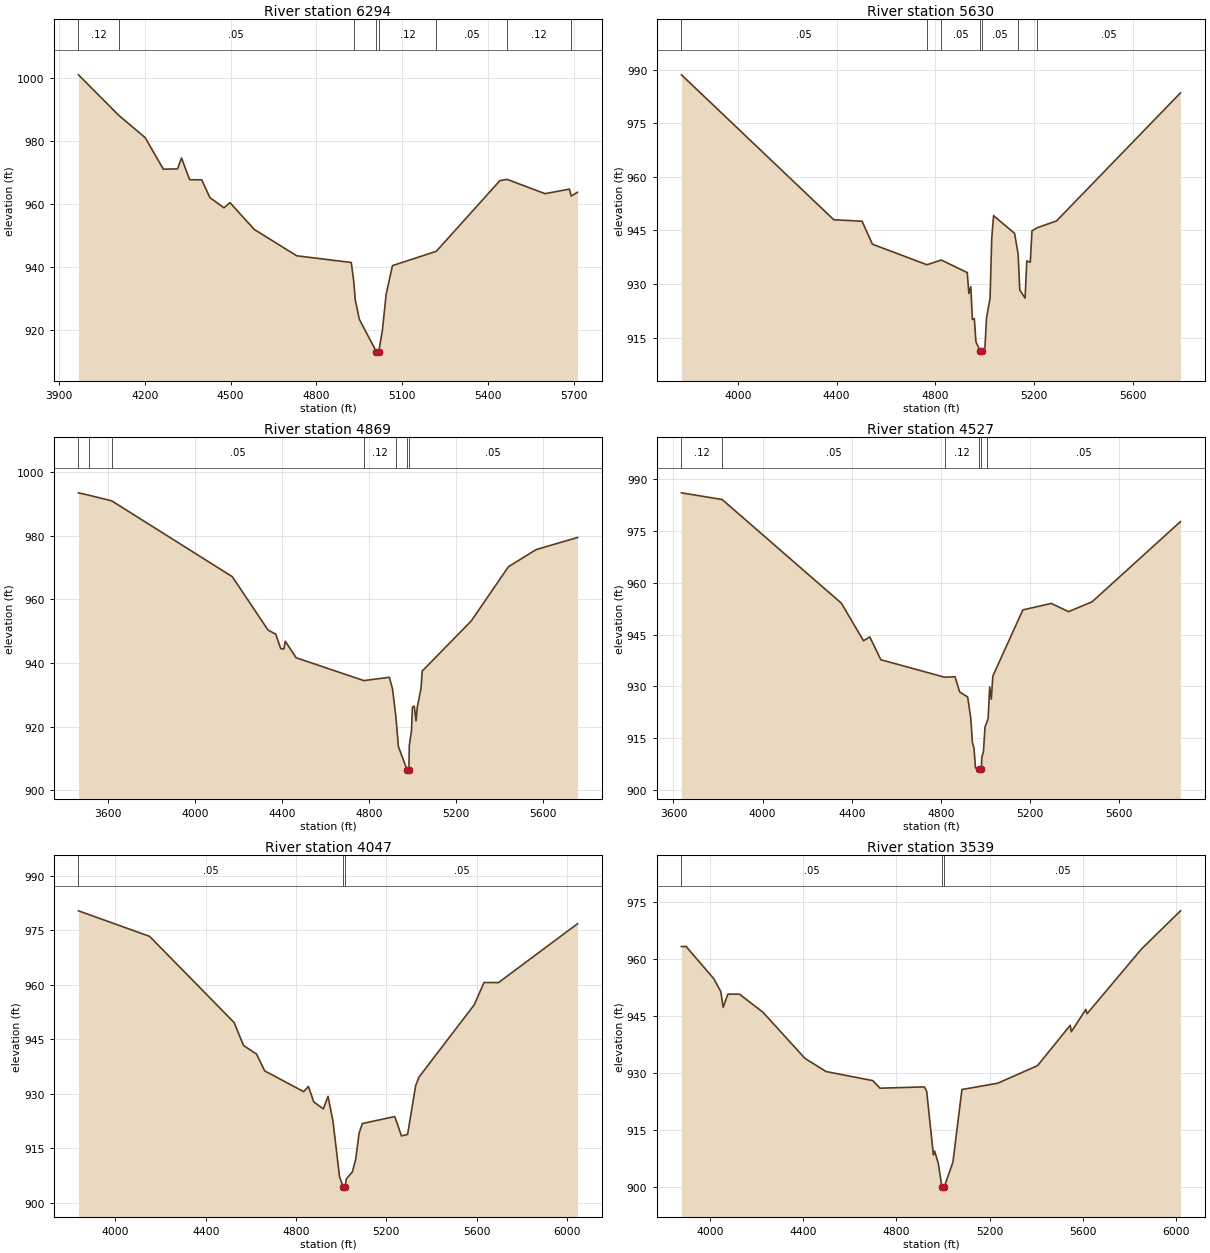
Type RM Length L Ch R = 1,6294,664,664,664
BEGIN DESCRIPTION:
Upper Denton 119 12.0
END DESCRIPTION:
XS GIS Cut Line= 3
      2250710.33      7225481.33      2249979.00      7226210.00
      2249674.27      7226855.51
#Sta/Elev= 30
  3967.6 1001.03  4108.1  988.22  4200.9  981.11  4264.6  971.10  4314.1  971.19
  4328.2  974.65  4356.5  967.77  4398.9  967.72  4427.2  962.12  4476.7  958.84
  4497.9  960.48  4582.8  951.98  4731.3  943.63  4922.2  941.50  4930.7  935.63
  4936.3  929.56  4950.5  923.47  5009.8  913.25  5011.1  912.75  5018.4  913.25
  5031.4  920.19  5044.2  931.44  5066.3  940.51  5219.8  945.05  5442.3  967.48
  5467.6  967.87  5600.0  963.34  5685.5  964.78  5691.7  962.56  5713.8  963.79
#Mann=8,-1,0
  3967.6    0.12       0  4108.1    0.05       0  4930.7    0.12       0
  5009.8    0.07       0  5018.4    0.12       0  5219.8    0.05       0
  5467.6    0.12       0  5691.7    0.05       0
Bank Sta=5009.8,5018.4
Exp/Cntr=0.3,0.1

Type RM Length L Ch R = 1,5630,761,761,761
BEGIN DESCRIPTION:
Upper Denton 119 11.0
END DESCRIPTION:
XS GIS Cut Line= 3
      2250335.34      7225137.56      2249543.68      7226085.47
      2249013.22      7226662.74
#Sta/Elev= 30
  3772.2  988.54  4388.5  947.99  4503.0  947.57  4544.7  941.15  4765.5  935.39
  4823.5  936.71  4928.6  933.20  4935.1  927.35  4942.9  929.27  4949.4  920.05
  4957.2  920.35  4963.7  913.81  4981.5  911.16  4982.7  910.66  4990.2  911.16
  5000.1  912.25  5006.7  920.63  5020.8  926.02  5027.6  942.75  5035.0  949.13
  5120.1  944.17  5134.3  938.41  5141.1  928.32  5162.6  926.05  5169.4  936.46
  5183.6  936.09  5190.4  944.87  5212.4  945.78  5289.7  947.65  5791.2  983.49
#Mann=7,-1,0
  3772.2    0.05       0  4765.5    0.12       0  4823.5    0.05       0
  4981.5   0.033       0  4990.2    0.05       0  5134.3    0.12       0
  5212.4    0.05       0
Bank Sta=4981.5,4990.2
Exp/Cntr=0.3,0.1

Type RM Length L Ch R = 1,4869,342,342,342
BEGIN DESCRIPTION:
Upper Denton 119 10.0
END DESCRIPTION:
XS GIS Cut Line= 3
      2250106.15      7224575.09      2249184.31      7225799.01
      2248851.32      7226485.80
#Sta/Elev= 30
  3464.0  993.50  3511.2  992.77  3616.9  990.98  4171.6  967.13  4336.1  950.33
  4371.5  949.05  4394.3  944.51  4408.9  944.38  4415.2  946.84  4465.1  941.64
  4776.7  934.45  4894.1  935.49  4908.6  931.81  4924.2  922.98  4935.7  913.70
  4974.9  906.48  4976.2  905.98  4984.0  906.48  4985.7  913.99  4996.2  918.93
  4999.9  926.06  5008.5  926.44  5016.9  921.76  5022.5  926.13  5039.5  931.92
  5045.1  937.44  5270.8  953.21  5441.9  970.27  5569.8  975.66  5759.5  979.46
#Mann=7,-1,0
  3464.0    0.05       0  3511.2    0.12       0  3616.9    0.05       0
  4776.7    0.12       0  4924.2    0.05       0  4974.9   0.033       0
  4984.0    0.05       0
Bank Sta=4974.9,4984
Exp/Cntr=0.3,0.1

Type RM Length L Ch R = 1,4527,480,480,480
BEGIN DESCRIPTION:
Upper Denton 119 9.0
END DESCRIPTION:
XS GIS Cut Line= 3
      2249955.17      7224502.11      2249029.00      7225510.00
      2248425.19      7226136.21
#Sta/Elev= 30
  3635.8  986.07  3818.4  984.13  4353.2  954.09  4452.5  943.20  4480.8  944.31
  4530.2  937.71  4816.2  932.64  4863.1  932.77  4884.1  928.36  4919.8  926.90
  4934.0  920.68  4940.8  913.81  4948.2  912.04  4955.0  906.33  4971.9  905.92
  4973.2  905.42  4981.1  905.92  4983.3  909.41  4990.7  911.07  4997.5  918.20
  5008.7  920.10  5011.7  920.81  5018.6  929.84  5025.8  926.26  5032.8  932.96
  5167.3  952.14  5294.7  954.02  5372.4  951.63  5478.3  954.50  5874.5  977.73
#Mann=6,-1,0
  3635.8    0.12       0  3818.4    0.05       0  4816.2    0.12       0
  4971.9    0.07       0  4981.1    0.12       0  5008.7    0.05       0
Bank Sta=4971.9,4981.1
Exp/Cntr=0.3,0.1

Type RM Length L Ch R = 1,4047,508,508,508
BEGIN DESCRIPTION:
Upper Denton 119 8.0
END DESCRIPTION:
XS GIS Cut Line= 3
      2249840.55      7224455.27      2248879.00      7225110.00
      2248283.61      7225970.39
#Sta/Elev= 30
  3836.7  980.40  4151.6  973.37  4525.6  949.66  4567.6  943.32  4625.0  940.97
  4661.3  936.32  4833.9  930.61  4854.9  932.05  4878.7  927.77  4920.7  925.88
  4941.7  929.32  4963.7  922.43  4992.5  907.23  5008.9  904.27  5010.2  903.77
  5018.2  904.27  5022.3  906.56  5049.3  908.50  5064.2  911.98  5079.1  919.16
  5093.9  921.84  5237.2  923.75  5266.9  918.42  5293.9  918.84  5329.8  932.30
  5344.6  934.63  5589.3  954.55  5632.4  960.66  5696.7  960.65  6046.3  976.84
#Mann=3,-1,0
  3836.7    0.05       0  5008.9   0.033       0  5018.2    0.05       0
Bank Sta=5008.9,5018.2
Exp/Cntr=0.3,0.1

Type RM Length L Ch R = 1,3539,134,134,134
BEGIN DESCRIPTION:
Upper Denton 119 7.0
END DESCRIPTION:
XS GIS Cut Line= 3
      2248585.35      7223741.74      2248491.60      7224851.10
      2248330.28      7225865.84
#Sta/Elev= 30
  3877.8  963.26  3897.5  963.30  4017.1  954.78  4046.7  951.42  4056.7  947.31
  4076.8  950.77  4126.6  950.77  4227.3  946.02  4407.9  933.88  4498.3  930.44
  4699.0  928.05  4729.6  926.07  4919.8  926.41  4929.8  925.28  4958.7  908.54
  4963.8  909.55  4980.0  906.25  4995.2  900.06  4996.6  899.56  5005.0  900.06
  5042.6  906.70  5081.1  925.72  5234.3  927.37  5405.2  931.98  5545.5  942.58
  5550.5  940.90  5612.7  946.77  5617.8  945.62  5850.7  962.58  6018.6  972.65
#Mann=3,-1,0
  3877.8    0.05       0  4995.2   0.033       0  5005.0    0.05       0
Bank Sta=4995.2,5005
Exp/Cntr=0.3,0.1