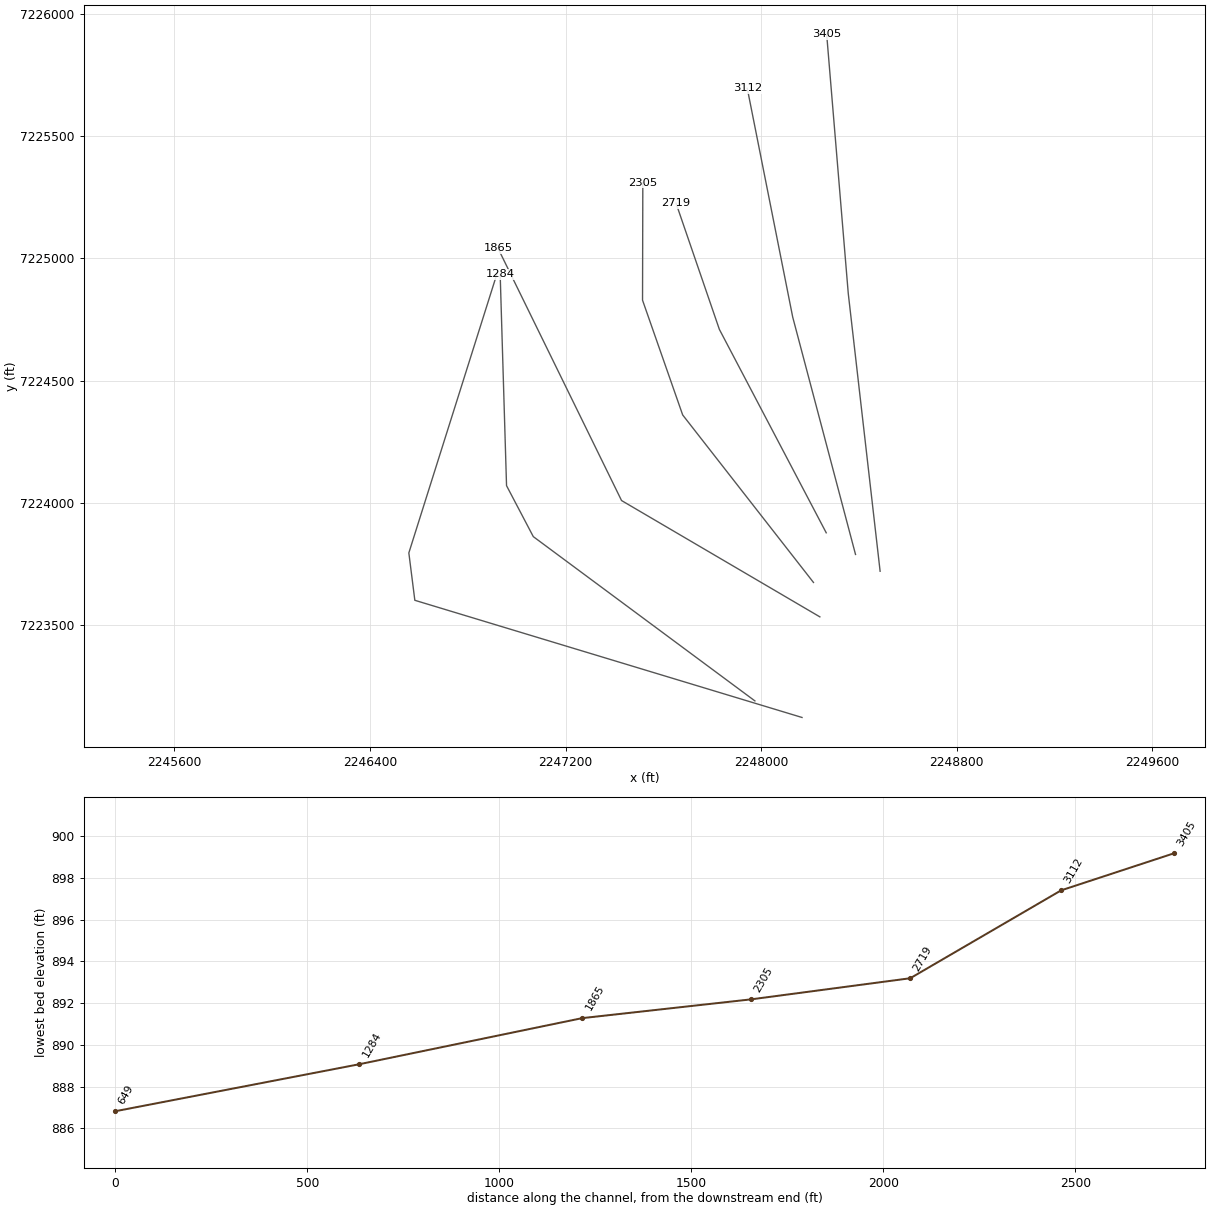
HEC-RAS study Upper Denton 119.prj: Upper Denton 119 Base Level Engineering

--- Upper Denton 119.g01 (geometry) --- (continued)

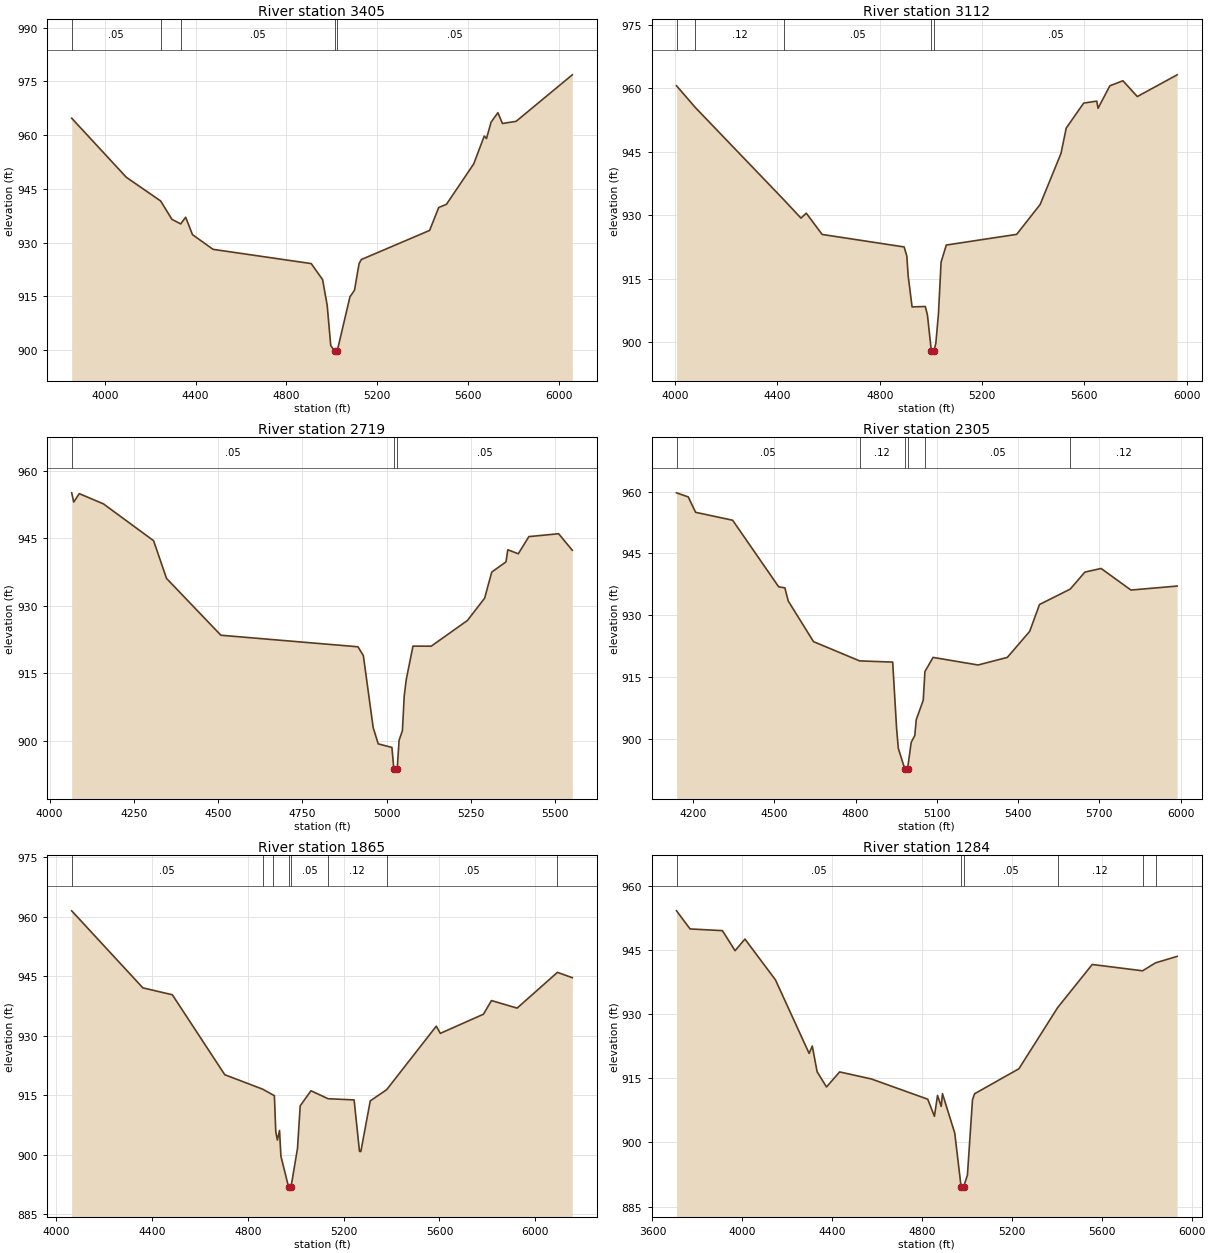
Type RM Length L Ch R = 1,3405,293,293,293
BEGIN DESCRIPTION:
Upper Denton 119 6.5
END DESCRIPTION:
XS GIS Cut Line= 3
      2248486.39      7223720.88      2248356.18      7224856.30
      2248267.80      7225916.86
#Sta/Elev= 30
  3853.4  964.70  4094.1  948.23  4245.7  941.61  4295.4  936.49  4333.9  935.21
  4355.8  937.07  4386.0  932.22  4476.6  928.12  4909.4  924.15  4959.7  919.67
  4979.9  912.47  4995.6  901.27  5013.9  899.67  5015.3  899.17  5023.7  899.67
  5080.3  914.89  5100.3  916.73  5120.4  924.12  5130.4  925.28  5431.5  933.40
  5471.6  939.79  5505.5  940.67  5625.9  951.95  5672.3  959.72  5682.3  959.03
  5702.4  963.59  5732.5  966.25  5752.6  963.22  5812.8  963.83  6060.5  976.80
#Mann=5,-1,0
  3853.4    0.05       0  4245.7    0.12       0  4333.9    0.05       0
  5013.9   0.033       0  5023.7    0.05       0
Bank Sta=5013.9,5023.7
Exp/Cntr=0.3,0.1

Type RM Length L Ch R = 1,3112,393,393,393
BEGIN DESCRIPTION:
Upper Denton 119 6.0
END DESCRIPTION:
XS GIS Cut Line= 3
      2248385.81      7223789.55      2248129.00      7224760.00
      2247943.19      7225695.37
#Sta/Elev= 30
  4005.3  960.63  4079.1  955.47  4424.1  933.72  4491.9  929.33  4512.6  930.50
  4574.7  925.47  4895.4  922.51  4905.7  920.39  4911.2  915.60  4926.4  908.33
  4978.1  908.43  4986.4  906.44  5001.7  897.90  5003.0  897.40  5011.5  897.90
  5019.3  899.73  5029.5  906.71  5039.8  918.92  5060.1  922.96  5335.4  925.49
  5427.2  932.56  5508.7  944.64  5529.1  950.62  5597.4  956.54  5648.5  957.00
  5653.6  955.31  5699.7  960.62  5750.8  961.82  5807.1  958.08  5962.8  963.22
#Mann=5,-1,0
  4005.3    0.05       0  4079.1    0.12       0  4424.1    0.05       0
  5001.7   0.033       0  5011.5    0.05       0
Bank Sta=5001.7,5011.5
Exp/Cntr=0.3,0.1

Type RM Length L Ch R = 1,2719,414,414,414
BEGIN DESCRIPTION:
Upper Denton 119 5.0
END DESCRIPTION:
XS GIS Cut Line= 3
      2248266.03      7223878.08      2247829.00      7224710.00
      2247651.80      7225226.00
#Sta/Elev= 30
  4065.5  955.10  4071.6  953.05  4088.0  954.92  4159.8  952.64  4308.5  944.45
  4346.9  936.06  4508.2  923.42  4914.9  920.85  4930.9  918.88  4960.0  902.88
  4975.0  899.26  5015.6  898.46  5021.4  893.69  5022.8  893.19  5031.3  893.69
  5036.9  900.04  5046.8  902.20  5052.1  909.88  5058.1  913.54  5078.1  921.00
  5132.1  920.98  5239.6  926.70  5290.7  931.66  5311.8  937.47  5354.1  939.74
  5359.4  942.44  5390.6  941.54  5421.9  945.36  5510.3  946.00  5550.8  942.32
#Mann=3,-1,0
  4065.5    0.05       0  5021.4   0.033       0  5031.3    0.05       0
Bank Sta=5021.4,5031.3
Exp/Cntr=0.3,0.1

Type RM Length L Ch R = 1,2305,440,440,440
BEGIN DESCRIPTION:
Upper Denton 119 4.0
END DESCRIPTION:
XS GIS Cut Line= 4
      2248213.93      7223674.99      2247679.00      7224360.00
      2247514.84      7224829.27      2247516.01      7225310.39
#Sta/Elev= 30
  4139.4  959.70  4182.7  958.70  4209.9  954.97  4346.5  953.05  4516.5  936.89
  4539.1  936.65  4551.8  933.44  4644.9  923.60  4814.7  918.93  4937.1  918.63
  4951.5  902.57  4957.9  897.71  4981.9  892.68  4983.3  892.18  4991.8  892.68
  5005.4  899.17  5018.7  900.82  5024.0  904.66  5049.8  909.37  5056.1  916.33
  5086.1  919.77  5252.2  917.93  5360.1  919.77  5442.6  926.08  5479.0  932.61
  5592.5  936.35  5646.4  940.47  5706.4  941.35  5816.4  936.11  5986.8  937.08
#Mann=6,-1,0
  4139.4    0.05       0  4814.7    0.12       0  4981.9    0.07       0
  4991.8    0.12       0  5056.1    0.05       0  5592.5    0.12       0
Bank Sta=4981.9,4991.8
Exp/Cntr=0.3,0.1

Type RM Length L Ch R = 1,1865,581,581,581
BEGIN DESCRIPTION:
Upper Denton 119 3.0
END DESCRIPTION:
XS GIS Cut Line= 3
      2248240.00      7223534.35      2247429.00      7224010.00
      2246923.14      7225043.00
#Sta/Elev= 30
  4064.2  961.50  4361.5  942.06  4484.5  940.32  4703.4  920.15  4861.7  916.50
  4906.0  915.01  4910.6  914.87  4916.4  905.74  4923.2  903.66  4932.1  906.09
  4937.9  899.58  4970.1  891.78  4971.5  891.28  4980.0  891.78  5007.2  901.59
  5018.4  912.30  5063.4  916.10  5134.8  914.09  5243.5  913.79  5266.0  900.80
  5271.6  900.77  5311.0  913.55  5379.4  916.37  5586.6  932.40  5603.5  930.58
  5783.5  935.41  5817.2  938.86  5924.1  936.95  6092.5  945.97  6154.6  944.63
#Mann=8,-1,0
  4064.2    0.05       0  4861.7    0.12       0  4906.0    0.05       0
  4970.1   0.033       0  4980.0    0.05       0  5134.8    0.12       0
  5379.4    0.05       0  6092.5    0.12       0
Bank Sta=4970.1,4980
Exp/Cntr=0.3,0.1

Type RM Length L Ch R = 1,1284,635,635,635
BEGIN DESCRIPTION:
Upper Denton 119 2.0
END DESCRIPTION:
XS GIS Cut Line= 4
      2247974.37      7223190.60      2247068.10      7223862.49
      2246958.72      7224070.82      2246932.69      7224935.16
#Sta/Elev= 30
  3707.2  954.22  3767.4  949.98  3911.5  949.58  3967.8  944.89  4011.6  947.61
  4147.3  938.08  4297.5  920.83  4311.4  922.57  4333.0  916.55  4374.7  912.98
  4433.1  916.51  4575.0  914.85  4825.4  910.12  4855.1  906.11  4868.9  911.01
  4885.3  908.44  4890.9  911.42  4945.5  902.21  4974.0  889.57  4975.5  889.07
  4984.7  889.57  5002.0  892.35  5024.6  910.01  5034.0  911.40  5231.2  917.25
  5403.6  931.57  5557.4  941.66  5781.6  940.18  5839.2  942.04  5935.4  943.56
#Mann=6,-1,0
  3707.2    0.05       0  4974.0   0.033       0  4984.7    0.05       0
  5403.6    0.12       0  5781.6    0.05       0  5839.2    0.12       0
Bank Sta=4974,4984.7
Exp/Cntr=0.3,0.1

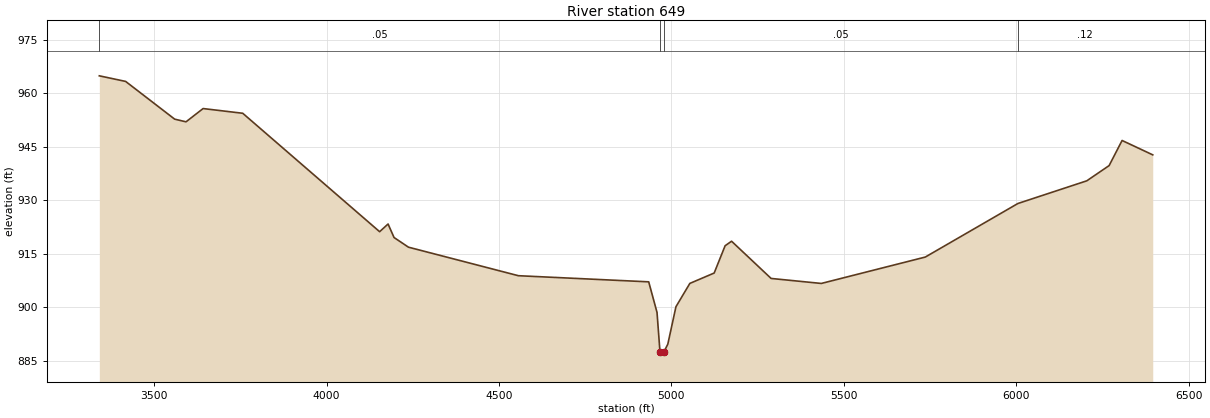
Type RM Length L Ch R = 1,649,0,0,0
BEGIN DESCRIPTION:
Upper Denton 119 1.0
END DESCRIPTION:
XS GIS Cut Line= 4
      2248167.04      7223122.91      2246583.72      7223602.07
      2246559.19      7223795.84      2246922.15      7224945.46
#Sta/Elev= 30
  3340.8  964.86  3417.1  963.29  3559.3  952.71  3592.2  951.96  3641.7  955.68
  3756.7  954.36  4153.7  921.15  4178.2  923.31  4195.5  919.52  4237.3  916.81
  4556.1  908.81  4934.1  907.09  4958.2  898.52  4966.9  887.32  4968.3  886.82
  4977.6  887.32  4989.5  889.61  5013.1  900.11  5053.4  906.65  5124.0  909.56
  5155.7  917.21  5174.4  918.48  5289.1  908.04  5434.7  906.64  5736.3  914.04
  6004.9  929.06  6204.7  935.42  6269.4  939.69  6307.0  946.73  6395.9  942.70
#Mann=4,-1,0
  3340.8    0.05       0  4966.9   0.033       0  4977.6    0.05       0
  6004.9    0.12       0
Bank Sta=4966.9,4977.6
Exp/Cntr=0.3,0.1

Chan Stop Cuts=-1