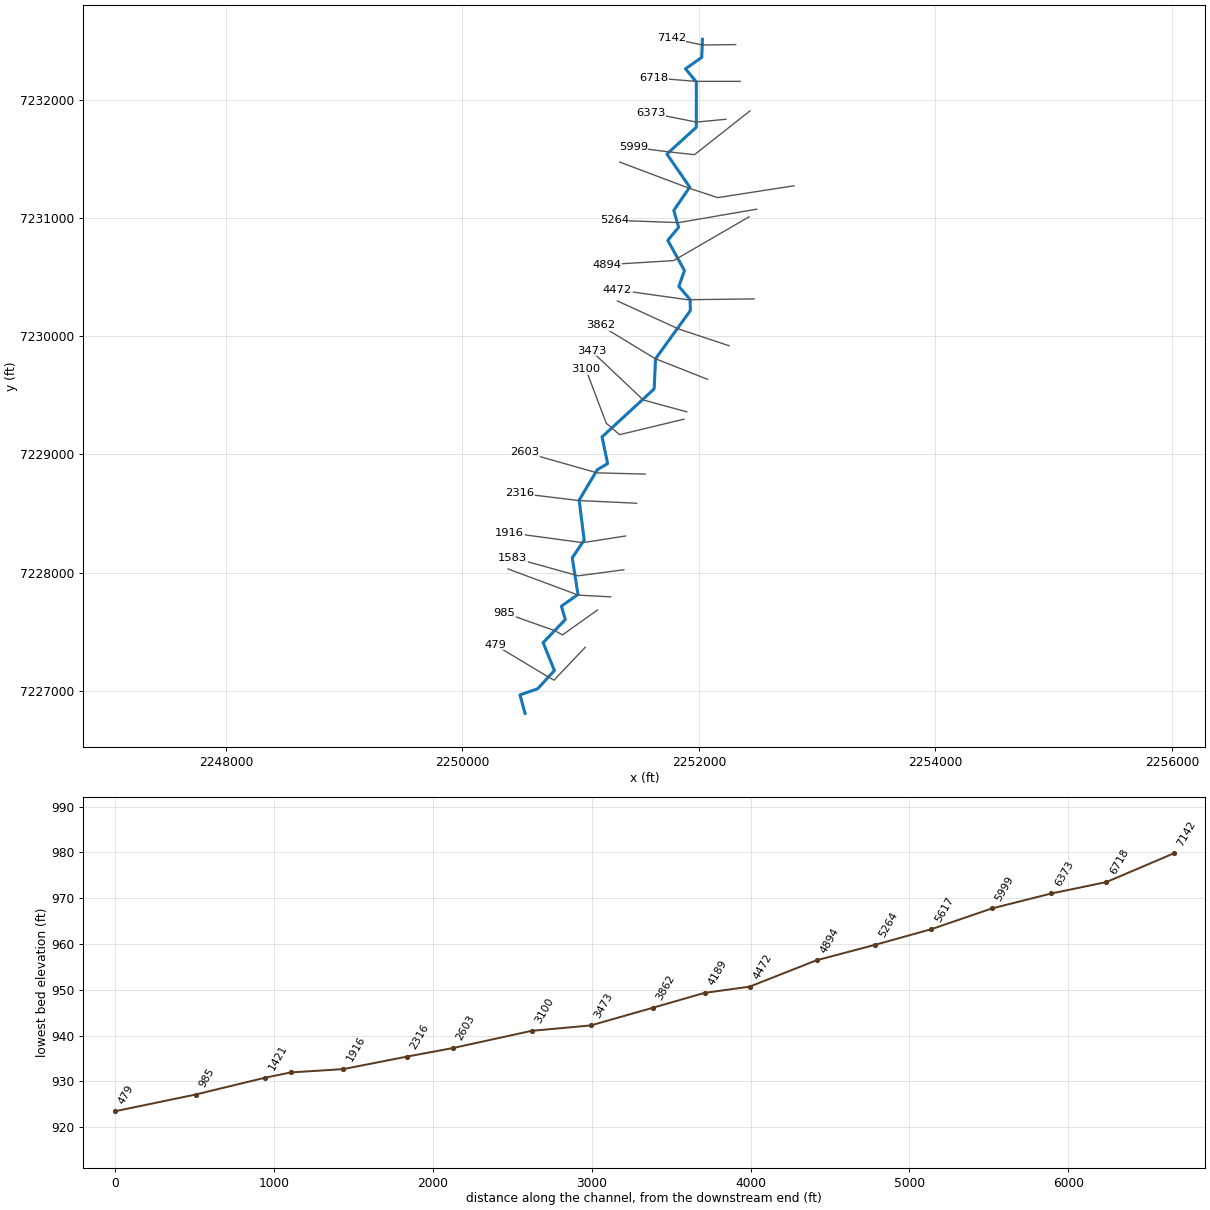
--- Upper Denton 121.prj (project) ---

Proj Title=Upper Denton 121 Base Level Engineering
Current Plan=p01
Default Exp/Contr=0.3,0.1
English Units
Geom File=g01
Flow File=f01
Plan File=p01
BEGIN DESCRIPTION:
Upper Denton 121
END DESCRIPTION:

--- Upper Denton 121.p01 (plan) ---

Plan Title=Multiple Run
Short Identifier=Multiple
Geom File=g01
Flow File=f01
Subcritical Flow
K Sum by GR= 0
Std Step Tol= 0.01
Critical Tol= 0.01
Num of Std Step Trials= 20
Max Error Tol= 0.3
Flow Tol Ratio= 0.001
Split Flow NTrial= 30
Split Flow Tol= 0.02
Split Flow Ratio= 0.02
Log Output Level= 0
Friction Slope Method= 1
Unsteady Friction Slope Method= 2
Unsteady Bridges Friction Slope Method= 1
Parabolic Critical Depth
Global Vel Dist=  1 , 1 , 1
Global Log Level= 0
CheckData=True
Encroach Param= -1, 0, 0, 0
BEGIN DESCRIPTION:
Multiple Run
END DESCRIPTION:

--- Upper Denton 121.f01 (steady flow) ---

Flow Title=Multiple
Number of Profiles=7
Profile Names=10-year,25-year,50-year,1pct_min,100-year,1pct_plu,500-year
River Rch & RM= Upper Denton 121,Reach-1,7142
     818    1162    1456     907    1809    3610    2801
River Rch & RM= Upper Denton 121,Reach-1,2316
     815    1155    1445     898    1791    3574    2761
Boundary for River Rch & Prof#=Upper Denton 121,Reach-1,1
Up Type=0
Dn Type=3
Dn Slope=0.005
Boundary for River Rch & Prof#=Upper Denton 121,Reach-1,2
Up Type=0
Dn Type=3
Dn Slope=0.005
Boundary for River Rch & Prof#=Upper Denton 121,Reach-1,3
Up Type=0
Dn Type=3
Dn Slope=0.005
Boundary for River Rch & Prof#=Upper Denton 121,Reach-1,4
Up Type=0
Dn Type=3
Dn Slope=0.005
Boundary for River Rch & Prof#=Upper Denton 121,Reach-1,5
Up Type=0
Dn Type=3
Dn Slope=0.005
Boundary for River Rch & Prof#=Upper Denton 121,Reach-1,6
Up Type=0
Dn Type=3
Dn Slope=0.005
Boundary for River Rch & Prof#=Upper Denton 121,Reach-1,7
Up Type=0
Dn Type=3
Dn Slope=0.005

--- Upper Denton 121.g01 (geometry) ---

Geom Title=Existing Conditions

River Reach=Upper Denton 121,Reach-1
Reach XY= 30
      2252029.00      7232510.00      2252023.67      7232357.28
      2251886.00      7232260.22      2251977.94      7232149.57
      2251977.02      7231765.67      2251728.59      7231539.87
      2251921.92      7231260.00      2251787.04      7231063.32
      2251828.05      7230920.48      2251736.33      7230810.10
      2251877.37      7230553.96      2251829.61      7230420.63
      2251925.53      7230308.50      2251926.86      7230215.97
      2251632.55      7229808.53      2251621.20      7229553.79
      2251180.51      7229148.13      2251227.47      7228921.88
      2251139.69      7228869.98      2250986.81      7228613.41
      2251028.98      7228275.36      2250928.23      7228125.09
      2250977.02      7227815.67      2250836.39      7227716.33
      2250869.85      7227603.27      2250682.10      7227408.35
      2250777.48      7227171.88      2250635.45      7227017.75
      2250486.34      7226966.39      2250529.00      7226810.00

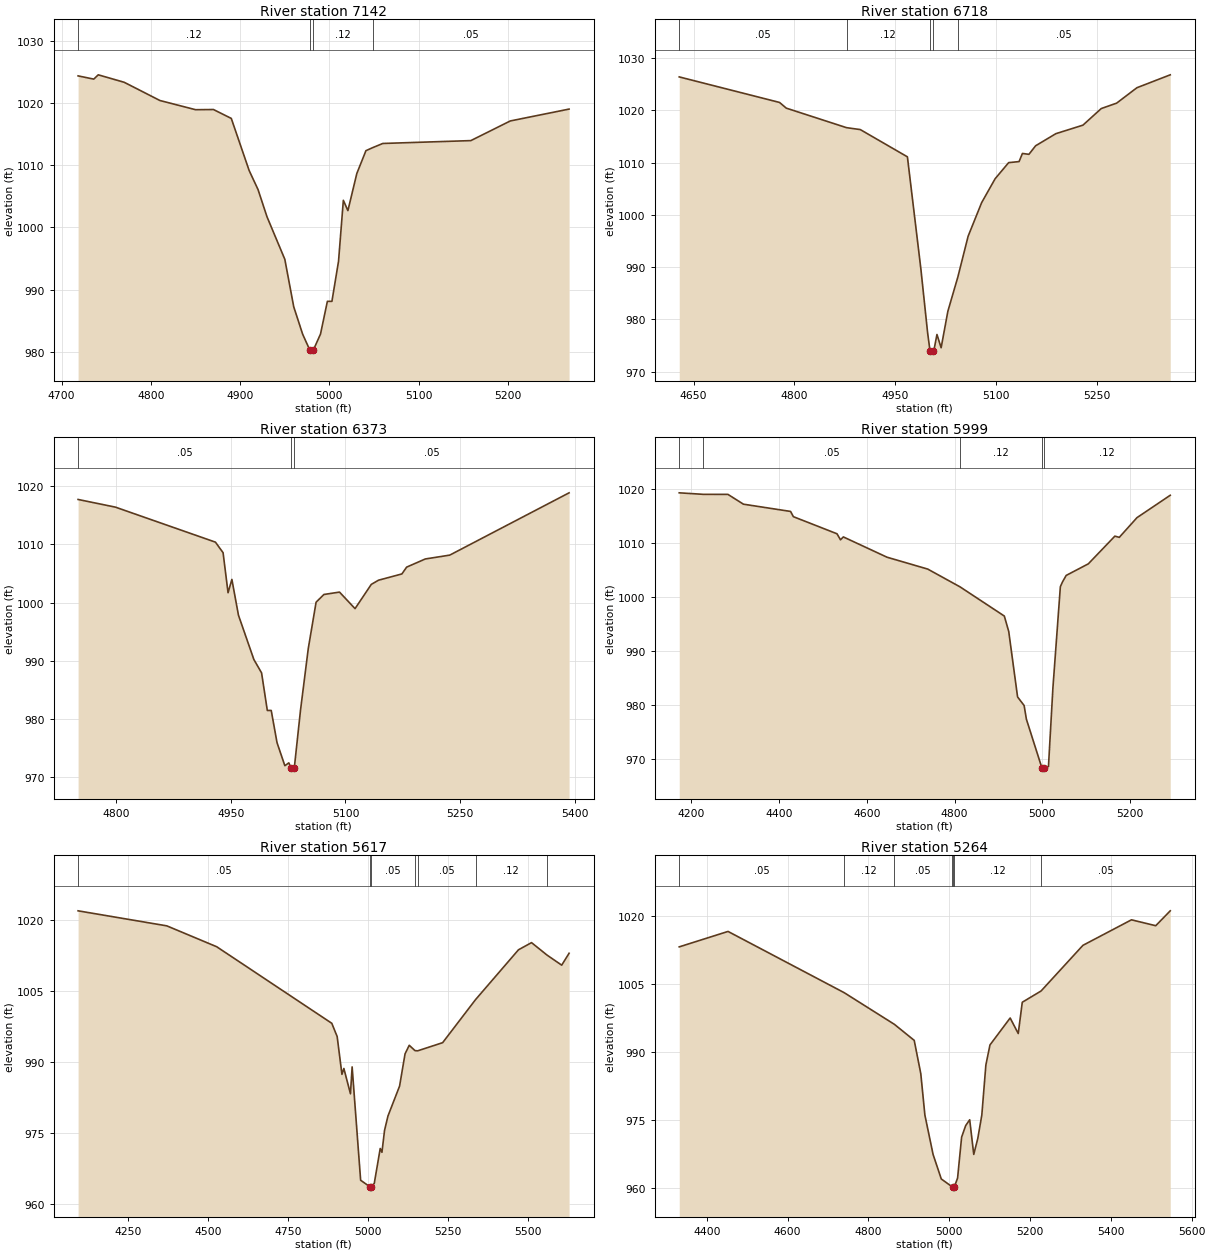
Type RM Length L Ch R = 1,7142,424,424,424
BEGIN DESCRIPTION:
Upper Denton 121 18.0
END DESCRIPTION:
XS GIS Cut Line= 3
      2252310.71      7232465.23      2252028.56      7232461.75
      2251766.43      7232518.17
#Sta/Elev= 30
  4718.4 1024.38  4736.0 1023.86  4741.0 1024.55  4770.1 1023.35  4810.1 1020.42
  4850.1 1018.94  4870.1 1018.97  4890.1 1017.54  4910.1 1009.17  4920.1 1006.09
  4930.1 1001.73  4950.1  994.88  4960.1  987.24  4970.1  982.83  4978.1  980.29
  4978.4  979.79  4982.1  980.29  4990.1  982.86  4997.8  988.12  5002.9  988.12
  5010.3  994.57  5015.7 1004.37  5020.8 1002.71  5030.8 1008.68  5041.0 1012.35
  5048.6 1012.84  5059.9 1013.51  5158.6 1013.97  5202.8 1017.13  5268.7 1019.04
#Mann=4,-1,0
  4718.4    0.12       0  4978.1    0.07       0  4982.1    0.12       0
  5048.6    0.05       0
Bank Sta=4978.1,4982.1
Exp/Cntr=0.3,0.1

Type RM Length L Ch R = 1,6718,345,345,345
BEGIN DESCRIPTION:
Upper Denton 121 17.0
END DESCRIPTION:
XS GIS Cut Line= 3
      2252348.02      7232154.46      2251973.01      7232154.46
      2251619.68      7232183.11
#Sta/Elev= 30
  4628.8 1026.43  4777.8 1021.54  4787.8 1020.45  4877.3 1016.71  4897.8 1016.34
  4967.8 1011.12  4987.8  989.65  4997.8  977.44  5001.3  974.02  5001.6  973.52
  5005.3  974.02  5007.1  974.02  5011.7  977.09  5017.9  974.55  5027.9  981.54
  5042.8  988.13  5058.0  995.91  5078.1 1002.35  5098.1 1006.92  5118.2 1010.01
  5133.7 1010.21  5138.7 1011.77  5148.3 1011.60  5158.3 1013.24  5188.4 1015.56
  5228.6 1017.19  5255.8 1020.37  5278.7 1021.41  5308.8 1024.36  5358.3 1026.83
#Mann=5,-1,0
  4628.8    0.05       0  4877.3    0.12       0  5001.3    0.07       0
  5005.3    0.12       0  5042.8    0.05       0
Bank Sta=5001.3,5005.3
Exp/Cntr=0.3,0.1

Type RM Length L Ch R = 1,6373,374,374,374
BEGIN DESCRIPTION:
Upper Denton 121 16.0
END DESCRIPTION:
XS GIS Cut Line= 3
      2252227.57      7231833.86      2251979.00      7231810.00
      2251594.75      7231885.95
#Sta/Elev= 30
  4750.7 1017.70  4799.5 1016.38  4930.1 1010.37  4940.1 1008.56  4946.6 1001.68
  4951.6 1003.97  4960.2  997.82  4980.3  990.22  4990.4  987.91  4997.9  981.46
  5003.0  981.46  5010.6  975.92  5020.8  971.97  5026.0  972.46  5029.1  971.54
  5029.4  971.04  5033.1  971.54  5041.2  981.45  5051.4  992.10  5061.6 1000.05
  5071.8 1001.38  5092.2 1001.79  5112.5  998.95  5133.7 1003.11  5143.1 1003.83
  5173.7 1004.91  5179.9 1006.08  5204.3 1007.48  5236.2 1008.14  5392.1 1018.84
#Mann=3,-1,0
  4750.7    0.05       0  5029.1   0.033       0  5033.1    0.05       0
Bank Sta=5029.1,5033.1
Exp/Cntr=0.3,0.1

Type RM Length L Ch R = 1,5999,382,382,382
BEGIN DESCRIPTION:
Upper Denton 121 15.0
END DESCRIPTION:
XS GIS Cut Line= 4
      2252430.66      7231904.15      2251961.94      7231534.38
      2251729.00      7231560.00      2251443.83      7231596.87
#Sta/Elev= 30
  4172.4 1019.23  4227.3 1018.95  4283.4 1018.94  4318.7 1017.13  4426.1 1015.79
  4432.5 1014.82  4531.9 1011.66  4539.9 1010.54  4546.3 1011.08  4645.8 1007.33
  4738.7 1005.13  4812.4 1001.84  4913.2  996.45  4923.3  993.58  4943.4  981.50
  4958.3  979.91  4963.5  977.38  4999.2  968.28  4999.5  967.78  5003.2  968.28
  5013.8  968.65  5023.9  983.13  5040.9 1001.88  5045.9 1002.78  5054.2 1003.96
  5104.6 1006.10  5165.1 1011.22  5175.2 1011.00  5215.5 1014.64  5291.3 1018.78
#Mann=5,-1,0
  4172.4    0.12       0  4227.3    0.05       0  4812.4    0.12       0
  4999.2    0.07       0  5003.2    0.12       0
Bank Sta=4999.2,5003.2
Exp/Cntr=0.3,0.1

Type RM Length L Ch R = 1,5617,353,353,353
BEGIN DESCRIPTION:
Upper Denton 121 14.0
END DESCRIPTION:
XS GIS Cut Line= 4
      2252803.07      7231271.36      2252158.65      7231171.35
      2251917.67      7231250.53      2251329.11      7231471.89
#Sta/Elev= 30
  4094.8 1021.94  4372.1 1018.77  4528.2 1014.36  4887.7  998.22  4904.5  995.43
  4919.5  987.45  4925.5  988.69  4946.1  983.35  4951.3  989.02  4977.9  965.11
  5006.9  963.74  5007.2  963.24  5010.9  963.74  5020.5  964.45  5039.1  971.81
  5044.5  971.01  5052.6  975.63  5063.3  978.66  5099.6  984.97  5116.7  991.77
  5129.8  993.58  5147.9  992.45  5156.1  992.41  5234.2  994.13  5336.9 1003.20
  5471.2 1013.72  5512.0 1015.23  5560.6 1012.60  5606.3 1010.48  5629.4 1012.99
#Mann=7,-1,0
  4094.8    0.05       0  5006.9   0.033       0  5010.9    0.05       0
  5147.9    0.12       0  5156.1    0.05       0  5336.9    0.12       0
  5560.6    0.05       0
Bank Sta=5006.9,5010.9
Exp/Cntr=0.3,0.1

Type RM Length L Ch R = 1,5264,370,370,370
BEGIN DESCRIPTION:
Upper Denton 121 13.0
END DESCRIPTION:
XS GIS Cut Line= 3
      2252488.00      7231073.45      2251829.00      7230960.00
      2251283.15      7230979.66
#Sta/Elev= 30
  4332.1 1013.20  4452.8 1016.60  4740.2 1003.11  4864.5  996.13  4913.5  992.60
  4929.8  985.26  4939.9  976.15  4960.2  967.47  4980.5  962.07  5006.6  960.39
  5008.8  960.33  5009.0  959.83  5012.8  960.33  5020.8  962.26  5030.8  971.29
  5040.8  973.82  5050.8  975.11  5060.8  967.48  5070.8  970.99  5080.8  976.16
  5090.8  987.17  5100.9  991.59  5150.9  997.53  5170.9  994.11  5180.9 1001.00
  5227.4 1003.48  5331.0 1013.54  5451.1 1019.16  5511.1 1017.86  5547.0 1021.14
#Mann=7,-1,0
  4332.1    0.05       0  4740.2    0.12       0  4864.5    0.05       0
  5006.6    0.12       0  5008.8   0.033       0  5012.8    0.12       0
  5227.4    0.05       0
Bank Sta=5008.8,5012.8
Exp/Cntr=0.3,0.1

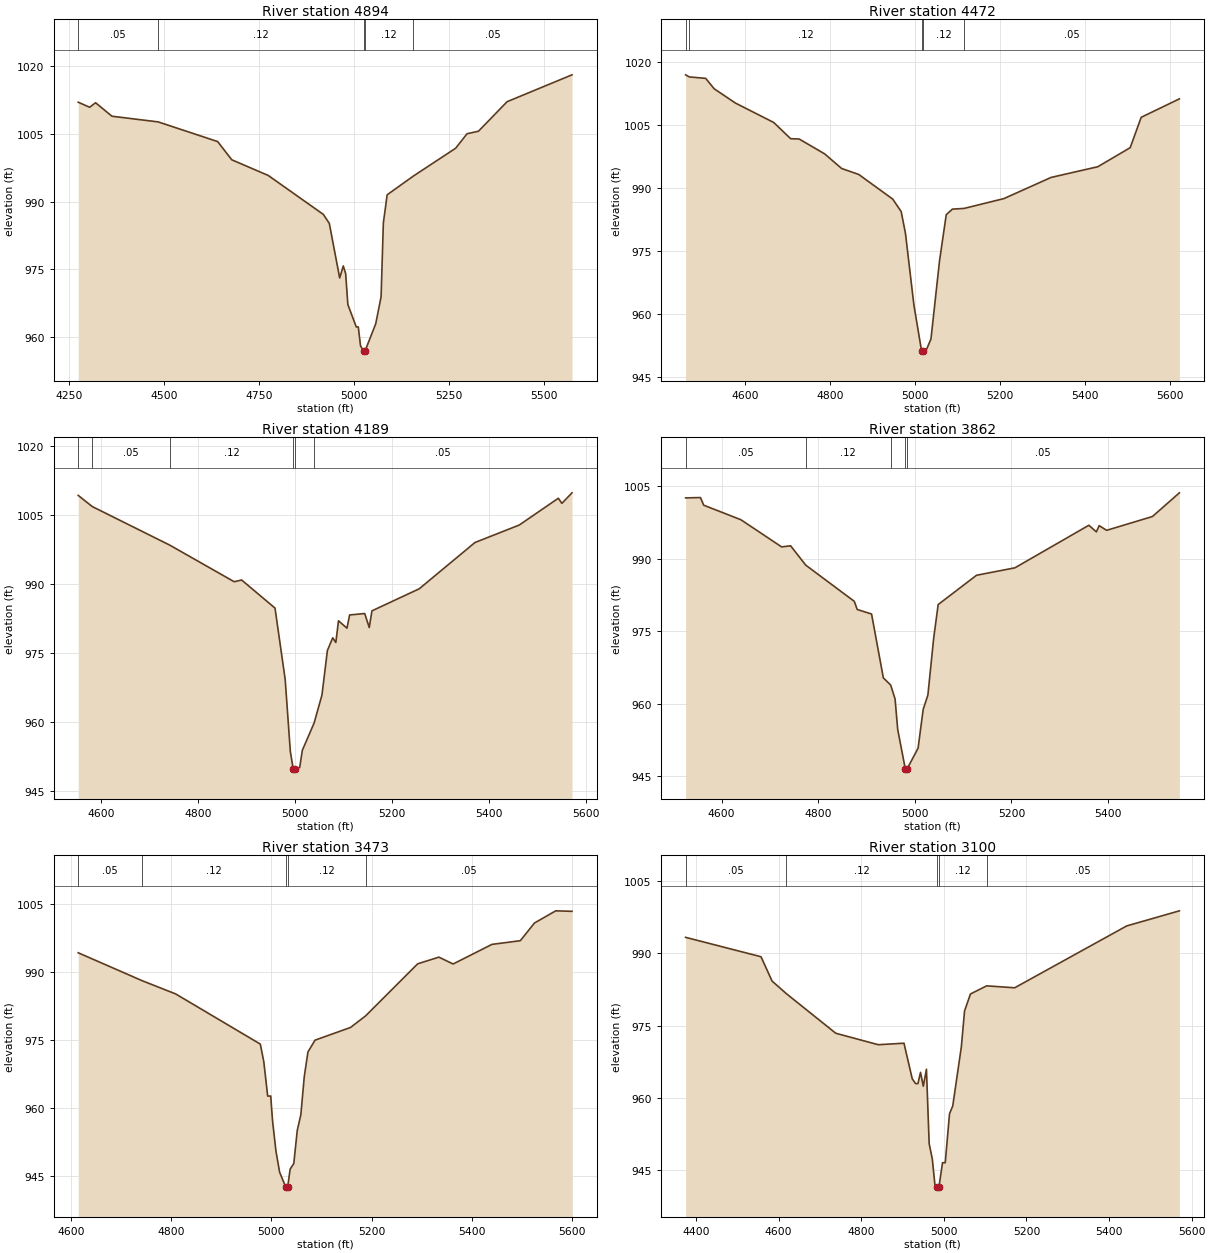
Type RM Length L Ch R = 1,4894,422,422,422
BEGIN DESCRIPTION:
Upper Denton 121 12.0
END DESCRIPTION:
XS GIS Cut Line= 3
      2252422.85      7231008.33      2251784.86      7230638.55
      2251223.18      7230604.74
#Sta/Elev= 30
  4273.9 1012.08  4303.9 1010.96  4319.6 1011.96  4362.7 1008.97  4484.5 1007.71
  4641.0 1003.35  4678.2  999.31  4774.3  995.83  4919.3  987.20  4935.0  985.21
  4962.3  973.11  4971.8  975.77  4978.1  974.03  4983.8  967.23  5006.0  962.25
  5011.3  962.25  5017.2  958.04  5025.2  956.94  5025.4  956.44  5029.2  956.94
  5057.2  962.94  5071.3  968.92  5077.3  985.32  5087.3  991.55  5156.6  995.72
  5267.6 1001.87  5297.7 1005.09  5327.7 1005.64  5403.1 1012.19  5574.0 1018.15
#Mann=5,-1,0
  4273.9    0.05       0  4484.5    0.12       0  5025.2    0.07       0
  5029.2    0.12       0  5156.6    0.05       0
Bank Sta=5025.2,5029.2
Exp/Cntr=0.3,0.1

Type RM Length L Ch R = 1,4472,283,283,283
BEGIN DESCRIPTION:
Upper Denton 121 11.0
END DESCRIPTION:
XS GIS Cut Line= 3
      2252466.32      7230314.78      2251903.78      7230307.84
      2251309.98      7230391.18
#Sta/Elev= 30
  4459.3 1016.89  4468.0 1016.39  4506.6 1016.05  4526.6 1013.57  4576.6 1010.17
  4666.6 1005.56  4706.6 1001.69  4726.6 1001.62  4786.6  998.08  4826.6  994.60
  4866.7  993.19  4946.7  987.33  4966.7  984.36  4976.7  979.21  4996.7  962.09
  5014.7  951.17  5014.9  950.67  5018.7  951.17  5026.8  951.65  5036.8  954.03
  5057.0  972.68  5072.8  983.62  5087.3  984.93  5115.1  985.11  5208.5  987.44
  5319.6  992.48  5429.4  995.02  5505.7  999.55  5531.6 1006.78  5621.5 1011.17
#Mann=5,-1,0
  4459.3    0.05       0  4468.0    0.12       0  5014.7    0.07       0
  5018.7    0.12       0  5115.1    0.05       0
Bank Sta=5014.7,5018.7
Exp/Cntr=0.3,0.1

Type RM Length L Ch R = 1,4189,327,327,327
BEGIN DESCRIPTION:
Upper Denton 121 10.0
END DESCRIPTION:
XS GIS Cut Line= 3
      2252254.49      7229918.95      2251829.00      7230060.00
      2251309.99      7230297.44
#Sta/Elev= 30
  4552.0 1009.24  4580.9 1006.82  4741.0  998.43  4873.8  990.48  4889.3  990.85
  4958.1  984.75  4979.1  969.24  4989.7  953.61  4995.6  949.82  4995.9  949.32
  4999.6  949.82  5009.0  950.10  5014.5  953.85  5038.8  959.78  5055.0  965.87
  5066.2  975.54  5077.2  978.29  5083.6  977.27  5089.1  981.99  5106.6  980.39
  5112.1  983.26  5143.2  983.57  5152.6  980.53  5158.1  984.15  5255.7  988.94
  5370.7  999.00  5462.1 1002.80  5542.8 1008.62  5550.1 1007.51  5571.0 1009.80
#Mann=6,-1,0
  4552.0    0.12       0  4580.9    0.05       0  4741.0    0.12       0
  4995.6    0.07       0  4999.6    0.12       0  5038.8    0.05       0
Bank Sta=4995.6,4999.6
Exp/Cntr=0.3,0.1

Type RM Length L Ch R = 1,3862,389,389,389
BEGIN DESCRIPTION:
Upper Denton 121 9.0
END DESCRIPTION:
XS GIS Cut Line= 3
      2252073.88      7229634.24      2251629.00      7229810.00
      2251164.19      7230092.56
#Sta/Elev= 30
  4525.5 1002.59  4556.2 1002.66  4563.0 1001.08  4640.0  998.07  4724.3  992.45
  4742.9  992.68  4774.2  988.68  4874.8  981.18  4880.8  979.50  4910.5  978.56
  4934.9  965.35  4950.1  963.86  4959.2  960.97  4964.6  954.68  4980.3  946.55
  4980.6  946.05  4984.3  946.55  5006.8  950.80  5017.4  958.83  5027.1  961.79
  5039.0  973.45  5048.4  980.52  5127.8  986.58  5207.3  988.12  5360.4  996.93
  5375.9  995.56  5381.7  996.85  5397.2  995.88  5492.1  998.74  5547.8 1003.64
#Mann=5,-1,0
  4525.5    0.05       0  4774.2    0.12       0  4950.1    0.05       0
  4980.3   0.033       0  4984.3    0.05       0
Bank Sta=4980.3,4984.3
Exp/Cntr=0.3,0.1

Type RM Length L Ch R = 1,3473,373,373,373
BEGIN DESCRIPTION:
Upper Denton 121 8.0
END DESCRIPTION:
XS GIS Cut Line= 3
      2251896.85      7229359.92      2251529.00      7229460.00
      2251089.04      7229876.12
#Sta/Elev= 30
  4613.9  994.26  4742.1  988.09  4808.6  985.20  4977.8  974.15  4984.8  970.25
  4992.5  962.71  4998.6  962.71  5002.2  957.28  5009.1  950.55  5016.4  945.93
  5028.5  942.71  5028.8  942.21  5032.5  942.71  5037.4  946.60  5044.7  947.85
  5051.6  955.12  5058.8  958.61  5065.7  967.05  5073.0  972.42  5087.2  975.02
  5158.0  977.81  5188.3  980.37  5292.3  991.83  5334.7  993.30  5363.1  991.79
  5440.7  996.11  5497.4  996.92  5525.7 1000.82  5568.2 1003.50  5600.7 1003.39
#Mann=5,-1,0
  4613.9    0.05       0  4742.1    0.12       0  5028.5    0.07       0
  5032.5    0.12       0  5188.3    0.05       0
Bank Sta=5028.5,5032.5
Exp/Cntr=0.3,0.1

Type RM Length L Ch R = 1,3100,497,497,497
BEGIN DESCRIPTION:
Upper Denton 121 7.0
END DESCRIPTION:
XS GIS Cut Line= 5
      2251872.56      7229297.43      2251328.47      7229166.71
      2251279.00      7229210.00      2251216.28      7229262.70
      2251043.32      7229719.31
#Sta/Elev= 30
  4374.9  993.34  4557.5  989.31  4584.2  984.26  4618.4  981.67  4738.5  973.41
  4841.4  971.03  4903.6  971.34  4923.6  963.96  4931.6  962.95  4937.4  962.95
  4943.7  965.29  4950.4  962.40  4958.0  965.93  4964.6  950.48  4972.2  947.28
  4978.8  941.68  4984.4  941.52  4984.7  941.02  4988.4  941.52  4996.9  946.51
  5003.5  946.51  5013.9  956.69  5021.7  958.31  5042.5  970.58  5050.3  978.06
  5064.6  981.57  5103.8  983.26  5171.7  982.86  5442.8  995.71  5570.4  998.85
#Mann=5,-1,0
  4374.9    0.05       0  4618.4    0.12       0  4984.4    0.07       0
  4988.4    0.12       0  5103.8    0.05       0
Bank Sta=4984.4,4988.4
Exp/Cntr=0.3,0.1

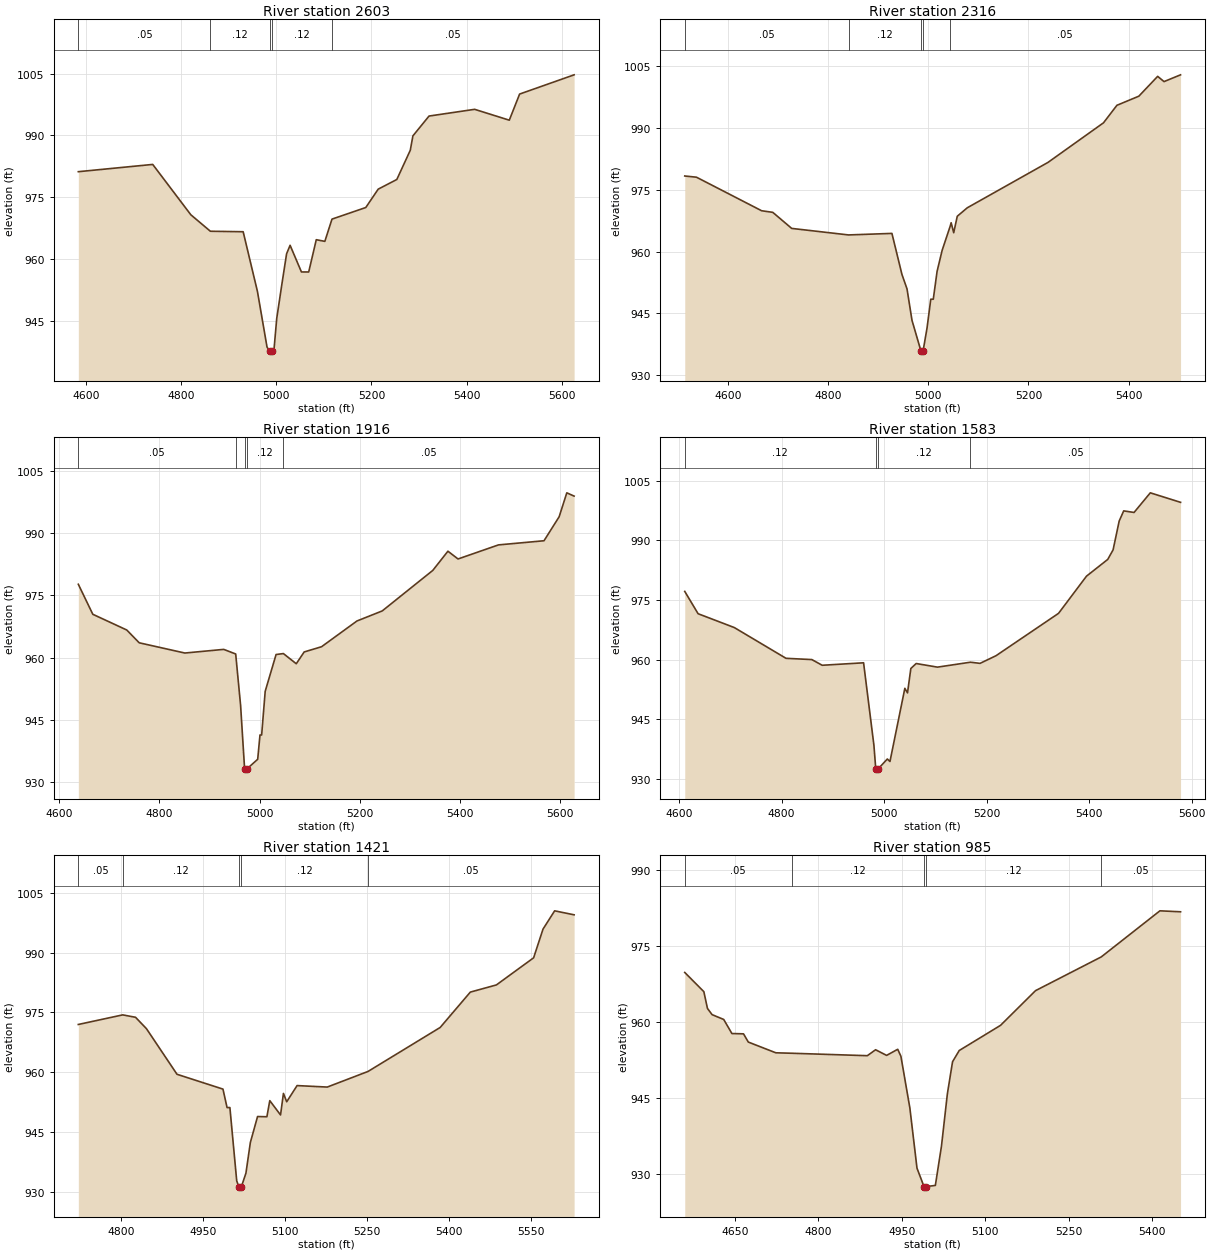
Type RM Length L Ch R = 1,2603,287,287,287
BEGIN DESCRIPTION:
Upper Denton 121 6.0
END DESCRIPTION:
XS GIS Cut Line= 3
      2251545.23      7228833.45      2251139.02      7228843.86
      2250527.94      7229017.47
#Sta/Elev= 30
  4584.3  981.21  4740.6  982.97  4820.6  970.78  4861.7  966.78  4930.6  966.66
  4960.6  952.20  4980.7  938.74  4986.0  937.75  4986.4  937.25  4990.2  937.75
  4995.3  937.99  5001.1  945.63  5011.5  953.62  5021.8  961.31  5029.2  963.38
  5053.0  956.92  5068.3  956.91  5084.2  964.73  5102.2  964.33  5117.2  969.72
  5188.2  972.53  5214.3  976.98  5253.4  979.32  5281.7  986.40  5287.2  989.89
  5321.1  994.69  5416.9  996.32  5489.7  993.69  5511.4 1000.02  5625.9 1004.68
#Mann=5,-1,0
  4584.3    0.05       0  4861.7    0.12       0  4986.0    0.07       0
  4990.2    0.12       0  5117.2    0.05       0
Bank Sta=4986,4990.2
Exp/Cntr=0.3,0.1

Type RM Length L Ch R = 1,2316,400,400,400
BEGIN DESCRIPTION:
Upper Denton 121 5.0
END DESCRIPTION:
XS GIS Cut Line= 3
      2251472.37      7228586.92      2250979.00      7228610.00
      2250486.28      7228670.25
#Sta/Elev= 30
  4513.5  978.29  4536.9  978.00  4667.0  969.88  4689.3  969.49  4727.1  965.60
  4840.6  964.02  4927.3  964.39  4947.3  954.46  4957.4  950.97  4967.4  943.34
  4985.3  935.90  4985.6  935.40  4989.5  935.90  4997.4  941.46  5004.9  948.45
  5009.9  948.45  5017.5  955.20  5027.6  960.29  5043.4  966.03  5045.6  966.97
  5050.7  964.55  5057.8  968.54  5077.9  970.60  5239.1  981.59  5349.9  991.17
  5376.7  995.41  5420.5  997.62  5458.1 1002.42  5470.8 1001.15  5503.8 1002.79
#Mann=5,-1,0
  4513.5    0.05       0  4840.6    0.12       0  4985.3    0.07       0
  4989.5    0.12       0  5043.4    0.05       0
Bank Sta=4985.3,4989.5
Exp/Cntr=0.3,0.1

Type RM Length L Ch R = 1,1916,333,333,333
BEGIN DESCRIPTION:
Upper Denton 121 4.0
END DESCRIPTION:
XS GIS Cut Line= 3
      2251379.03      7228310.00      2251017.50      7228253.58
      2250399.40      7228336.92
#Sta/Elev= 30
  4638.3  977.70  4667.2  970.47  4735.0  966.68  4759.8  963.60  4850.9  961.13
  4928.5  962.01  4952.4  960.90  4962.2  948.50  4970.2  933.17  4970.5  932.67
  4974.4  933.17  4996.3  935.52  5000.9  941.38  5004.2  941.38  5011.3  951.91
  5033.0  960.77  5047.6  961.00  5073.3  958.55  5089.1  961.39  5123.8  962.65
  5194.4  968.85  5244.9  971.28  5345.8  981.04  5376.0  985.67  5396.2  983.80
  5476.9  987.19  5567.8  988.19  5598.0  993.97  5613.3  999.74  5627.9  998.95
#Mann=5,-1,0
  4638.3    0.05       0  4952.4    0.12       0  4970.2    0.07       0
  4974.4    0.12       0  5047.6    0.05       0
Bank Sta=4970.2,4974.4
Exp/Cntr=0.3,0.1

Type RM Length L Ch R = 1,1583,162,162,162
BEGIN DESCRIPTION:
Upper Denton 121 3.5
END DESCRIPTION:
XS GIS Cut Line= 3
      2251364.75      7228024.42      2250979.00      7227973.19
      2250422.17      7228128.06
#Sta/Elev= 30
  4611.3  977.14  4637.3  971.53  4707.9  968.05  4808.8  960.31  4859.2  959.99
  4879.4  958.56  4960.1  959.18  4980.3  938.42  4983.9  932.43  4984.2  931.93
  4988.1  932.43  5006.4  934.98  5011.6  934.36  5040.6  952.76  5045.8  951.62
  5052.3  957.75  5062.7  959.00  5104.2  958.09  5168.6  959.33  5187.3  959.04
  5218.4  960.96  5340.4  971.62  5394.9  980.97  5436.4  985.19  5446.8  987.59
  5458.7  994.84  5467.5  997.40  5487.7  997.00  5519.4 1001.94  5578.4  999.55
#Mann=4,-1,0
  4611.3    0.12       0  4983.9    0.07       0  4988.1    0.12       0
  5168.6    0.05       0
Bank Sta=4983.9,4988.1
Exp/Cntr=0.3,0.1

Type RM Length L Ch R = 1,1421,436,436,436
BEGIN DESCRIPTION:
Upper Denton 121 3.0
END DESCRIPTION:
XS GIS Cut Line= 3
      2251253.64      7227795.25      2250979.00      7227810.00
      2250385.57      7228031.35
#Sta/Elev= 30
  4721.3  971.99  4802.6  974.39  4826.1  973.79  4846.1  970.94  4902.1  959.52
  4986.3  955.81  4993.8  951.19  4999.0  951.19  5011.5  932.84  5015.6  931.27
  5015.9  930.77  5019.8  931.27  5028.4  934.77  5036.5  942.45  5049.7  948.94
  5066.8  948.89  5072.1  952.92  5091.8  949.34  5097.1  954.73  5103.1  952.64
  5122.1  956.69  5177.4  956.32  5252.1  960.23  5384.3  971.24  5439.5  980.09
  5487.3  981.89  5555.5  988.68  5572.7  995.86  5594.0 1000.44  5629.7  999.44
#Mann=5,-1,0
  4721.3    0.05       0  4802.6    0.12       0  5015.6    0.07       0
  5019.8    0.12       0  5252.1    0.05       0
Bank Sta=5015.6,5019.8
Exp/Cntr=0.3,0.1

Type RM Length L Ch R = 1,985,506,506,506
BEGIN DESCRIPTION:
Upper Denton 121 2.0
END DESCRIPTION:
XS GIS Cut Line= 4
      2251142.21      7227684.72      2250845.80      7227473.48
      2250779.00      7227510.00      2250354.05      7227660.40
#Sta/Elev= 30
  4559.9  969.75  4594.2  965.97  4600.7  962.67  4609.0  961.45  4629.9  960.50
  4644.6  957.73  4665.5  957.67  4674.1  956.05  4723.5  953.94  4752.2  953.85
  4888.0  953.37  4902.8  954.54  4922.6  953.43  4942.6  954.63  4948.3  953.26
  4964.4  943.08  4977.2  931.24  4989.8  927.61  4990.2  927.11  4994.1  927.61
  5010.2  927.84  5021.2  935.58  5031.8  945.87  5041.1  952.18  5053.1  954.39
  5127.3  959.34  5190.2  966.17  5308.3  972.81  5413.7  981.88  5450.8  981.69
#Mann=5,-1,0
  4559.9    0.05       0  4752.2    0.12       0  4989.8    0.07       0
  4994.1    0.12       0  5308.3    0.05       0
Bank Sta=4989.8,4994.1
Exp/Cntr=0.3,0.1

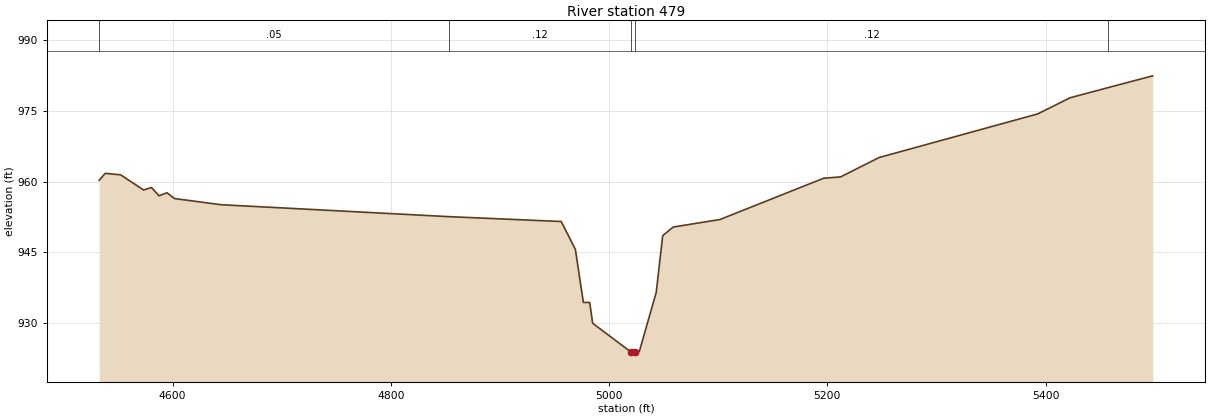
Type RM Length L Ch R = 1,479,0,0,0
BEGIN DESCRIPTION:
Upper Denton 121 1.0
END DESCRIPTION:
XS GIS Cut Line= 4
      2251038.01      7227368.72      2250774.15      7227090.97
      2250718.60      7227122.22      2250274.16      7227389.58
#Sta/Elev= 30
  4532.7  960.27  4538.2  961.72  4552.3  961.42  4573.4  958.20  4580.6  958.73
  4587.5  956.97  4594.8  957.62  4601.7  956.39  4644.2  955.09  4853.2  952.56
  4956.1  951.53  4969.1  945.62  4976.4  934.40  4982.2  934.40  4984.9  930.00
  5019.7  923.96  5020.0  923.46  5024.0  923.96  5027.7  924.03  5043.2  936.55
  5049.1  948.54  5058.7  950.36  5101.5  951.95  5196.6  960.69  5212.2  960.98
  5247.5  965.08  5392.8  974.31  5422.5  977.73  5456.8  979.84  5498.2  982.37
#Mann=5,-1,0
  4532.7    0.05       0  4853.2    0.12       0  5019.7    0.07       0
  5024.0    0.12       0  5456.8    0.05       0
Bank Sta=5019.7,5024
Exp/Cntr=0.3,0.1

Chan Stop Cuts=-1