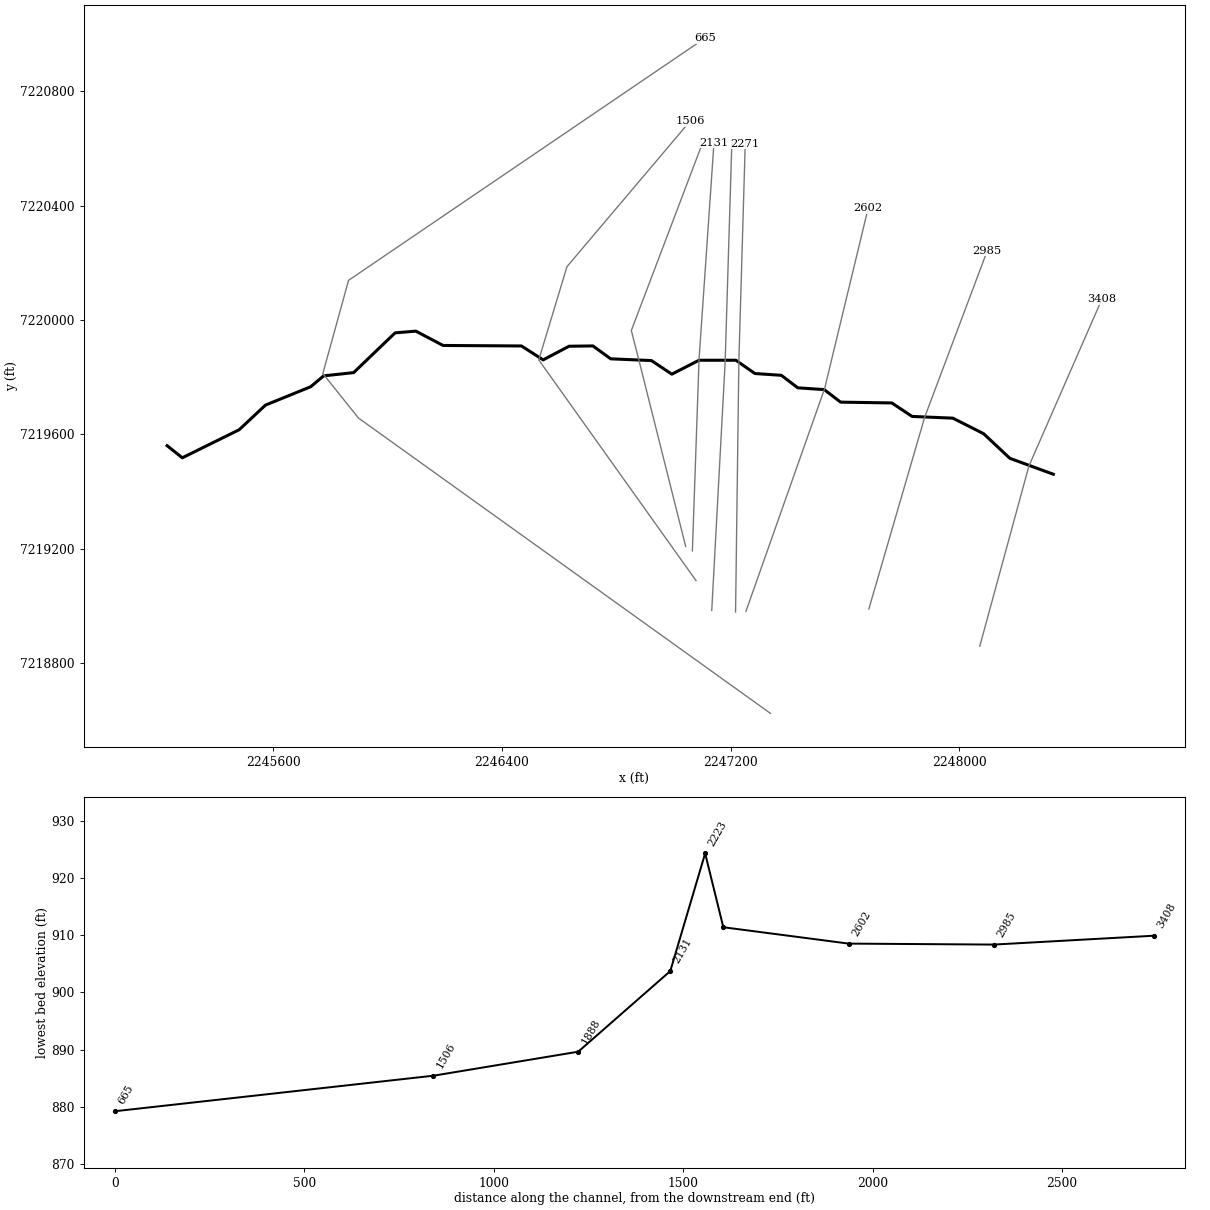
--- Upper Denton 122.prj (project) ---

Proj Title=Upper Denton 122 Base Level Engineering
Current Plan=p01
Default Exp/Contr=0.3,0.1
English Units
Geom File=g01
Flow File=f01
Plan File=p01
Y Axis Title=Elevation
X Axis Title(PF)=Main Channel Distance
X Axis Title(XS)=Station
BEGIN DESCRIPTION:
Upper Denton 122
END DESCRIPTION:
DSS Export Rating Curves= 0
DSS Export Rating Curve Sorted= 0
DSS Export Volume Flow Curves= 0
DXF OffsetX= 0
DXF OffsetY= 0
DXF ScaleX= 1
DXF ScaleY= 10

--- Upper Denton 122.p01 (plan) ---

Plan Title=Multiple Run
Short Identifier=Multiple
Geom File=g01
Flow File=f01
Subcritical Flow
K Sum by GR= 0
Std Step Tol= 0.01
Critical Tol= 0.01
Num of Std Step Trials= 20
Max Error Tol= 0.3
Flow Tol Ratio= 0.001
Split Flow NTrial= 30
Split Flow Tol= 0.02
Split Flow Ratio= 0.02
Log Output Level= 0
Friction Slope Method= 1
Unsteady Friction Slope Method= 2
Unsteady Bridges Friction Slope Method= 1
Parabolic Critical Depth
Global Vel Dist=  1 , 1 , 1
Global Log Level= 0
CheckData=True
Encroach Param= -1, 0, 0, 0
BEGIN DESCRIPTION:
Multiple Run
END DESCRIPTION:

--- Upper Denton 122.f01 (steady flow) ---

Flow Title=Multiple
Program Version=4.10
Number of Profiles= 7
Profile Names=10-year,25-year,50-year,1pct_min,100-year,1pct_plu,500-year
River Rch & RM=Upper Denton 122,Reach-1         ,3408
     874    1254    1583     993    1982    3954    3115
Boundary for River Rch & Prof#=Upper Denton 122,Reach-1         , 1
Up Type= 0
Dn Type= 3
Dn Slope=0.02
Boundary for River Rch & Prof#=Upper Denton 122,Reach-1         , 2
Up Type= 0
Dn Type= 3
Dn Slope=0.02
Boundary for River Rch & Prof#=Upper Denton 122,Reach-1         , 3
Up Type= 0
Dn Type= 3
Dn Slope=0.02
Boundary for River Rch & Prof#=Upper Denton 122,Reach-1         , 4
Up Type= 0
Dn Type= 3
Dn Slope=0.02
Boundary for River Rch & Prof#=Upper Denton 122,Reach-1         , 5
Up Type= 0
Dn Type= 3
Dn Slope=0.02
Boundary for River Rch & Prof#=Upper Denton 122,Reach-1         , 6
Up Type= 0
Dn Type= 3
Dn Slope=0.02
Boundary for River Rch & Prof#=Upper Denton 122,Reach-1         , 7
Up Type= 0
Dn Type= 3
Dn Slope=0.02
DSS Import GetInterval= 0
DSS Import GetPeak= 0
DSS Import FillOption= 0

--- Upper Denton 122.g01 (geometry) ---

Geom Title=Existing Conditions
Program Version=4.10

River Reach=Upper Denton 122,Reach-1
Reach XY= 30
        2248329.        7219460.       2248176.7      7219515.83
      2248085.05      7219601.84      2247977.44      7219656.24
      2247834.94      7219662.27      2247763.78      7219709.48
      2247584.94      7219712.26       2247527.4      7219756.14
      2247434.97      7219762.35       2247377.4      7219806.15
      2247284.98      7219812.36      2247218.49       7219858.8
       2247089.5      7219858.77      2246994.39      7219810.09
      2246923.07       7219857.7      2246780.57      7219863.79
      2246718.45       7219908.9      2246634.97      7219907.81
      2246544.39      7219860.09       2246468.5      7219908.76
      2246194.22      7219910.52      2246099.04      7219960.61
      2246026.57       7219954.6      2245881.43      7219815.52
      2245776.68      7219804.23      2245731.18      7219766.12
      2245572.95      7219701.84      2245481.29      7219615.85
       2245282.2      7219517.58        2245229.        7219560.

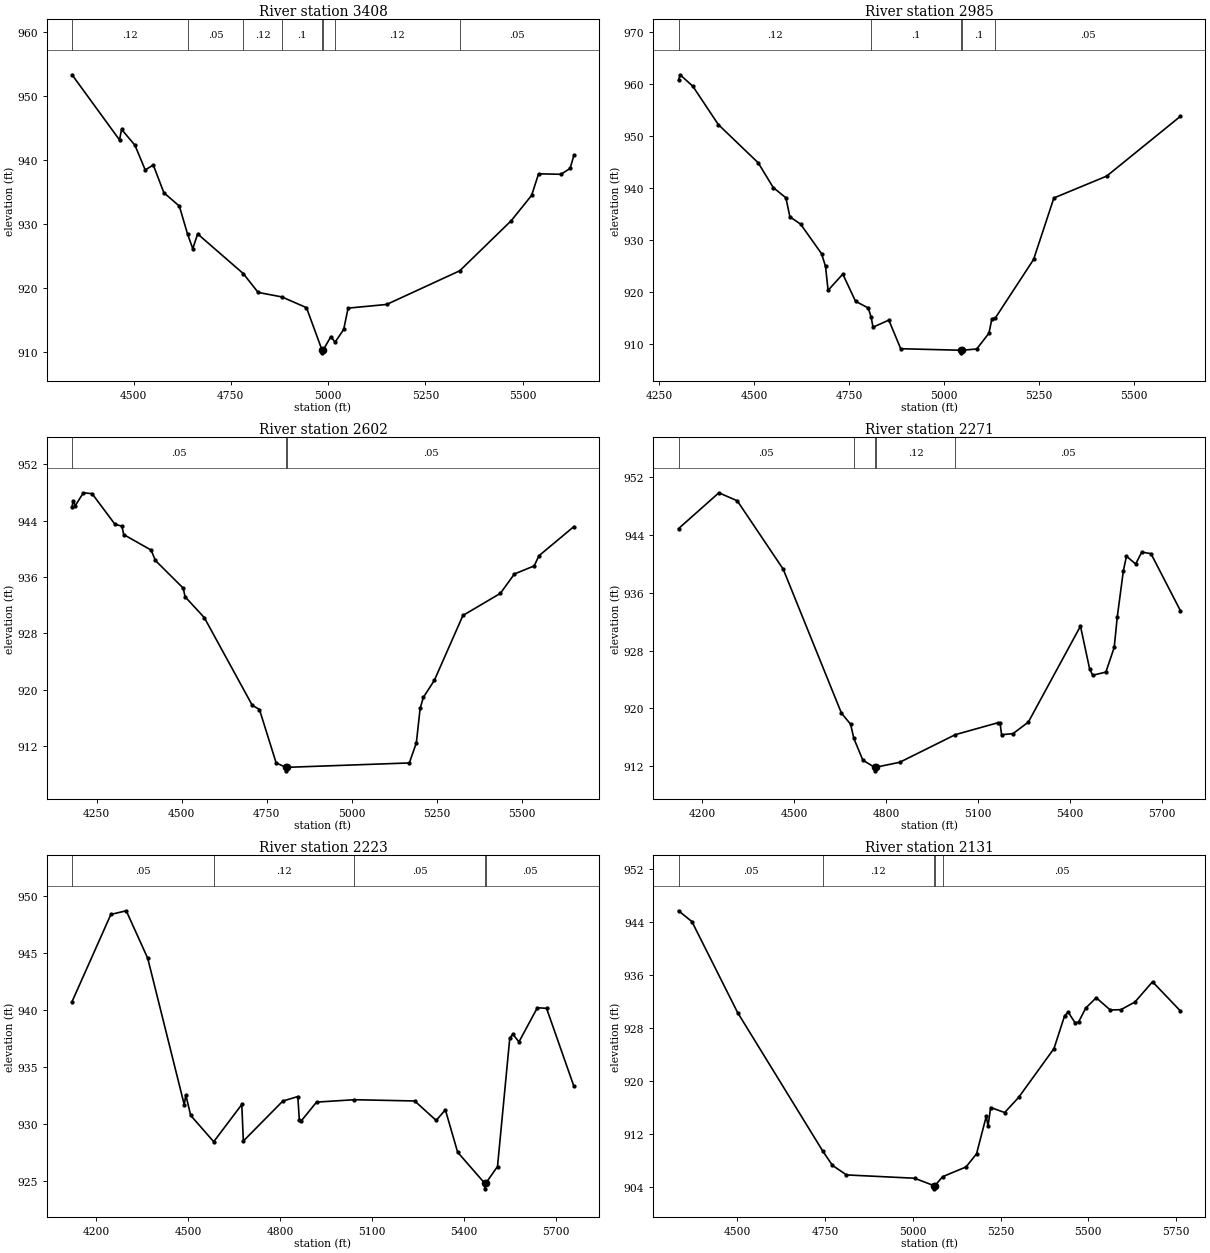
Type RM Length L Ch R = 1 ,3408    ,423,423,423
BEGIN DESCRIPTION:
Upper Denton 122 6.0
END DESCRIPTION:
XS GIS Cut Line= 3
      2248071.54       7218858.6      2248243.41      7219488.79
      2248498.61       7220072.1
#Sta/Elev= 30
  4341.8  953.29  4463.8  943.12    4469  944.77  4503.5  942.29  4529.8  938.44
  4550.6   939.2  4577.8  934.88  4617.6  932.79  4638.7  928.41  4652.1  926.15
  4664.6  928.45  4781.9  922.26  4820.1  919.32    4881  918.62  4944.4  916.94
  4983.9  910.39  4984.1  909.89  4987.9  910.39  5007.2  912.44  5017.8  911.54
    5040  913.54  5051.4  916.87  5150.4  917.44  5338.4   922.7  5470.8  930.52
  5523.1  934.47    5541  937.83  5598.7  937.76  5622.1  938.68  5631.7  940.71
#Mann= 8 ,-1 , 0
  4341.8     .12       0  4638.7     .05       0  4781.9     .12       0
    4881      .1       0  4983.9     .07       0  4987.9      .1       0
  5017.8     .12       0  5338.4     .05       0
Bank Sta=4983.9,4987.9
XS Rating Curve= 0 ,0
Exp/Cntr=0.3,0.1

Type RM Length L Ch R = 1 ,2985    ,383,383,383
BEGIN DESCRIPTION:
Upper Denton 122 5.0
END DESCRIPTION:
XS GIS Cut Line= 3
       2247683.5      7218988.74        2247879.        7219660.
      2248097.59      7220241.42
#Sta/Elev= 30
  4301.2  960.75  4305.4  961.79  4338.9  959.58  4405.9  952.22  4510.8  944.87
  4550.3  940.12  4583.7  938.14  4594.2  934.49  4622.5  933.07  4677.5   927.4
  4687.9  924.97  4694.7  920.35  4733.4  923.48  4766.9  918.25  4800.4  916.96
  4808.1  915.16  4812.9  913.27  4854.5  914.63  4885.8  909.13  5043.7  908.84
  5043.9  908.34  5047.7  908.84  5085.8  909.08  5117.9  912.11  5125.7  914.87
  5134.9  915.06  5235.4  926.29  5288.8  938.11  5427.7  942.31  5621.5  953.79
#Mann= 5 ,-1 , 0
  4301.2     .12       0  4808.1      .1       0  5043.7     .07       0
  5047.7      .1       0  5134.9     .05       0
Bank Sta=5043.7,5047.7
XS Rating Curve= 0 ,0
Exp/Cntr=0.3,0.1

Type RM Length L Ch R = 1 ,2602    ,331,331,331
BEGIN DESCRIPTION:
Upper Denton 122 4.0
END DESCRIPTION:
XS GIS Cut Line= 3
      2247253.82      7218980.98        2247529.        7219760.
      2247680.91      7220389.84
#Sta/Elev= 30
    4178  945.87  4180.4  946.74  4187.6  946.14  4211.3  947.95  4236.9  947.82
  4304.2  943.47  4324.4  943.22  4329.7  942.02  4410.3  939.82  4422.5  938.36
  4504.6  934.42  4509.9  933.21  4566.5  930.24  4707.2  917.82  4728.5  917.21
  4777.6  909.62  4806.5  909.01  4806.8  908.51  4810.5  909.01  5168.8  909.63
  5189.4  912.48  5200.5  917.37  5209.9  918.92  5242.4  921.36  5326.2  930.55
  5436.2  933.68  5477.4  936.43  5535.6  937.58  5549.4  939.01  5652.1  943.15
#Mann= 3 ,-1 , 0
    4178     .05       0  4806.5    .033       0  4810.5     .05       0
Bank Sta=4806.5,4810.5
XS Rating Curve= 0 ,0
Exp/Cntr=0.3,0.1

Type RM Length L Ch R = 1 ,2271    ,48,48,48
BEGIN DESCRIPTION:
Upper Denton 122 3.0
END DESCRIPTION:
XS GIS Cut Line= 3
      2247217.37      7218978.35        2247229.        7219860.
       2247251.2      7220615.74
#Sta/Elev= 30
  4122.8   944.9  4254.5  949.86  4314.5  948.75  4464.5  939.28  4654.5  919.36
  4684.5  917.82  4694.8  915.88  4724.5  912.84  4762.5  911.87  4762.8  911.37
  4766.5  911.87  4844.5  912.55  5026.3  916.38  5164.6  918.02  5172.2  917.99
  5177.2  916.37  5214.6  916.52  5264.6  918.12  5434.7   931.4  5464.7  925.45
  5474.7   924.6  5517.6  925.04  5544.8  928.45  5554.8  932.68  5574.8   939.1
  5584.8  941.08  5614.8     940  5634.8  941.65  5664.8  941.43  5760.6  933.56
#Mann= 5 ,-1 , 0
  4122.8     .05       0  4694.8     .12       0  4762.5     .07       0
  4766.5     .12       0  5026.3     .05       0
Bank Sta=4762.5,4766.5
XS Rating Curve= 0 ,0
Exp/Cntr=0.3,0.1

Type RM Length L Ch R = 1 ,2223    ,92,92,92
BEGIN DESCRIPTION:
Upper Denton 122 2.5
END DESCRIPTION:
XS GIS Cut Line= 3
      2247134.03      7218983.55      2247180.91      7219850.77
      2247204.35      7220619.03
#Sta/Elev= 30
  4121.8  940.72  4248.4  948.38  4298.5   948.7  4368.6  944.53  4487.8  931.66
  4492.8  932.52  4508.8  930.72    4584  928.41  4675.5  931.68  4680.6  928.47
  4809.3  931.98  4858.3  932.38  4863.3  930.33  4869.3  930.23  4919.4  931.89
  5042.9   932.1  5239.6  931.99  5309.7  930.28  5339.7  931.21  5379.7  927.49
  5467.7  924.77    5468  924.27  5471.7  924.77  5509.8  926.23  5549.8  937.51
  5559.8  937.86  5579.8  937.18  5639.8  940.18  5669.8  940.13  5758.9  933.29
#Mann= 5 ,-1 , 0
  4121.8     .05       0    4584     .12       0  5042.9     .05       0
  5467.7     .07       0  5471.7     .05       0
Bank Sta=5467.7,5471.7
XS Rating Curve= 0 ,0
Exp/Cntr=0.3,0.1

Type RM Length L Ch R = 1 ,2131    ,243,243,243
BEGIN DESCRIPTION:
Upper Denton 122 2.4
END DESCRIPTION:
XS GIS Cut Line= 3
      2247066.32      7219191.89      2247089.76      7219863.79
      2247141.84      7220618.99
#Sta/Elev= 30
  4332.7  945.66  4370.8  944.03  4500.9  930.31  4743.6   909.4  4771.1  907.25
  4811.1  905.81    5005  905.31  5059.3  904.21  5059.6  903.71  5063.3  904.21
  5084.8  905.54  5151.6  907.01  5181.6     909  5209.3  914.66  5214.3  913.16
  5221.7  915.98  5261.8  915.22  5301.9  917.54  5402.2  924.88  5432.2  929.79
  5442.3   930.4  5462.3  928.75  5472.3  928.89  5492.4  930.97  5522.4  932.54
  5562.5  930.69  5592.6  930.74  5632.7  931.89  5682.8  934.95    5762  930.56
#Mann= 5 ,-1 , 0
  4332.7     .05       0  4743.6     .12       0  5059.3     .07       0
  5063.3     .12       0  5084.8     .05       0
Bank Sta=5059.3,5063.3
XS Rating Curve= 0 ,0
Exp/Cntr=0.3,0.1

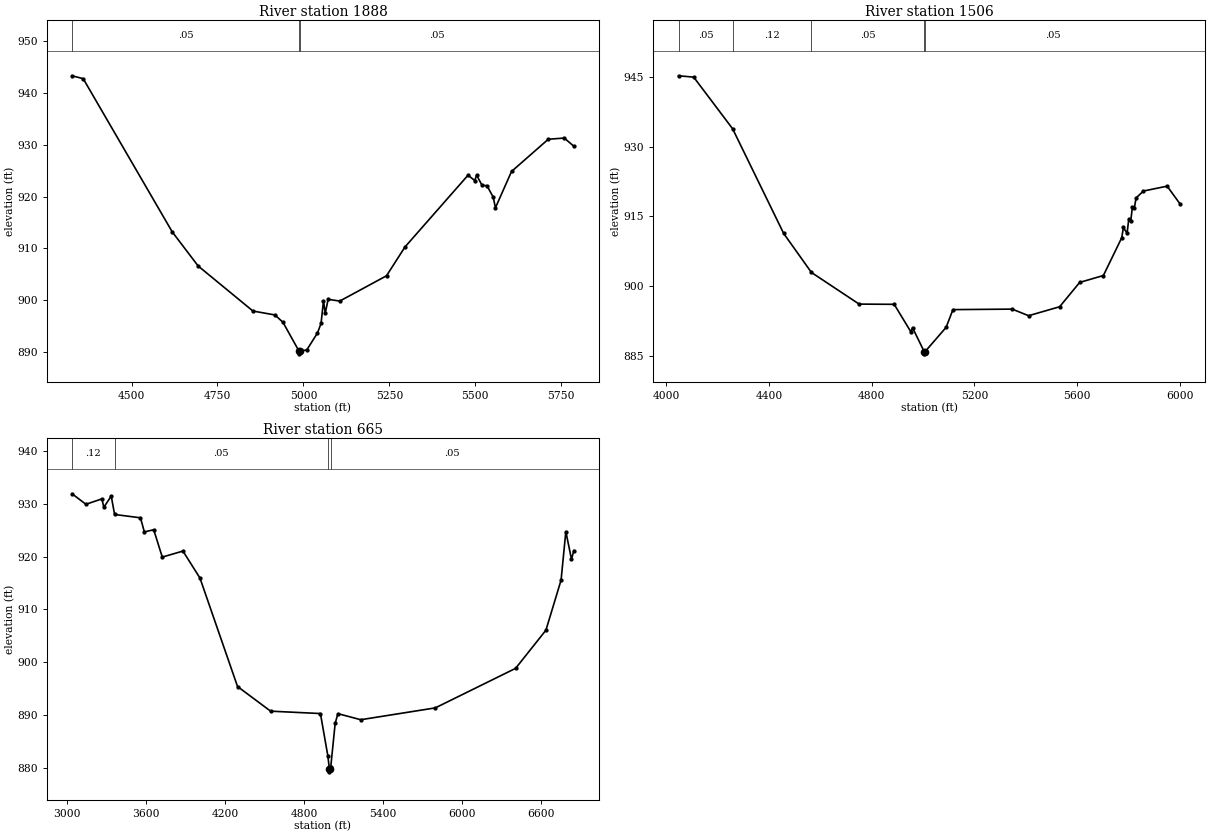
Type RM Length L Ch R = 1 ,1888    ,382,382,382
BEGIN DESCRIPTION:
Upper Denton 122 2.0
END DESCRIPTION:
XS GIS Cut Line= 4
       2247042.9      7219207.51        2246879.        7219860.
      2246852.78      7219962.75      2247094.49      7220599.51
#Sta/Elev= 30
  4326.9  943.33  4359.3  942.77  4618.2  913.19  4693.7  906.59  4853.1  897.89
  4917.2  897.13  4940.5  895.71  4987.4  890.12  4987.6  889.62  4991.4  890.12
    5010   890.4  5040.9  893.65  5051.3   895.5  5058.4  899.87  5063.5  897.47
  5071.9  900.15  5105.7  899.81  5241.8   904.7  5295.3  910.25    5479  924.13
  5498.4  923.09  5503.8  924.13  5519.9  922.15  5533.9  922.11    5552  919.91
  5558.7  917.84  5605.5  924.85  5712.4  931.07  5758.9   931.3  5786.8  929.72
#Mann= 3 ,-1 , 0
  4326.9     .05       0  4987.4    .033       0  4991.4     .05       0
Bank Sta=4987.4,4991.4
XS Rating Curve= 0 ,0
Exp/Cntr=0.3,0.1

Type RM Length L Ch R = 1 ,1506    ,841,841,841
BEGIN DESCRIPTION:
Upper Denton 122 1.0
END DESCRIPTION:
XS GIS Cut Line= 4
      2247079.03      7219088.07        2246529.        7219860.
      2246627.67      7220186.13      2247057.37      7220693.95
#Sta/Elev= 30
  4048.3  945.24  4107.3  944.95  4258.9  933.84  4457.7  911.32  4565.8  902.93
  4751.5  896.13    4888  896.08  4953.1  890.15  4959.3  891.07  5004.6  885.93
  5004.8  885.43  5008.6  885.93  5090.2  891.13  5116.7  894.94  5347.6  895.05
  5411.3  893.63  5532.2  895.56  5610.2  900.79  5702.5  902.28  5773.9  910.39
  5780.5  912.61  5794.8  911.34  5801.3   914.4    5809     914  5815.6  917.04
  5823.3  916.87  5829.9  918.97  5858.5  920.45  5950.8   921.5  6002.1  917.59
#Mann= 5 ,-1 , 0
  4048.3     .05       0  4258.9     .12       0  4565.8     .05       0
  5004.6    .033       0  5008.6     .05       0
Bank Sta=5004.6,5008.6
XS Rating Curve= 0 ,0
Exp/Cntr=0.3,0.1

Type RM Length L Ch R = 1 ,665     ,0,0,0
BEGIN DESCRIPTION:
Upper Denton 122 0.5
END DESCRIPTION:
XS GIS Cut Line= 5
      2247339.43      7218623.66       2245898.5      7219656.62
      2245773.79      7219812.26      2245863.78      7220138.39
      2247109.46      7220984.76
#Sta/Elev= 30
  3036.3  931.88  3141.5  929.89  3263.1  930.91  3277.8  929.33  3334.3  931.44
  3359.7  927.96  3556.6  927.33  3586.1  924.66  3657.3  925.07  3722.4  919.89
  3879.6  921.03  4008.9  915.93  4294.8  895.38  4546.5  890.71  4925.4  890.26
  4981.5  882.28  4993.9  879.72  4994.1  879.22  4997.9  879.72  5003.9  880.15
  5037.5   888.4  5058.2  890.24  5232.2  889.09  5799.1  891.33  6409.9  898.82
  6640.4  906.04  6755.7  915.52    6792  924.72    6835  919.48    6853  921.12
#Mann= 4 ,-1 , 0
  3036.3     .12       0  3359.7     .05       0  4981.5    .033       0
  5003.9     .05       0
Bank Sta=4993.9,4997.9
XS Rating Curve= 0 ,0
Exp/Cntr=0.3,0.1

Chan Stop Cuts=-1
Use User Specified Reach Order=0
Composite Channel Slope=5