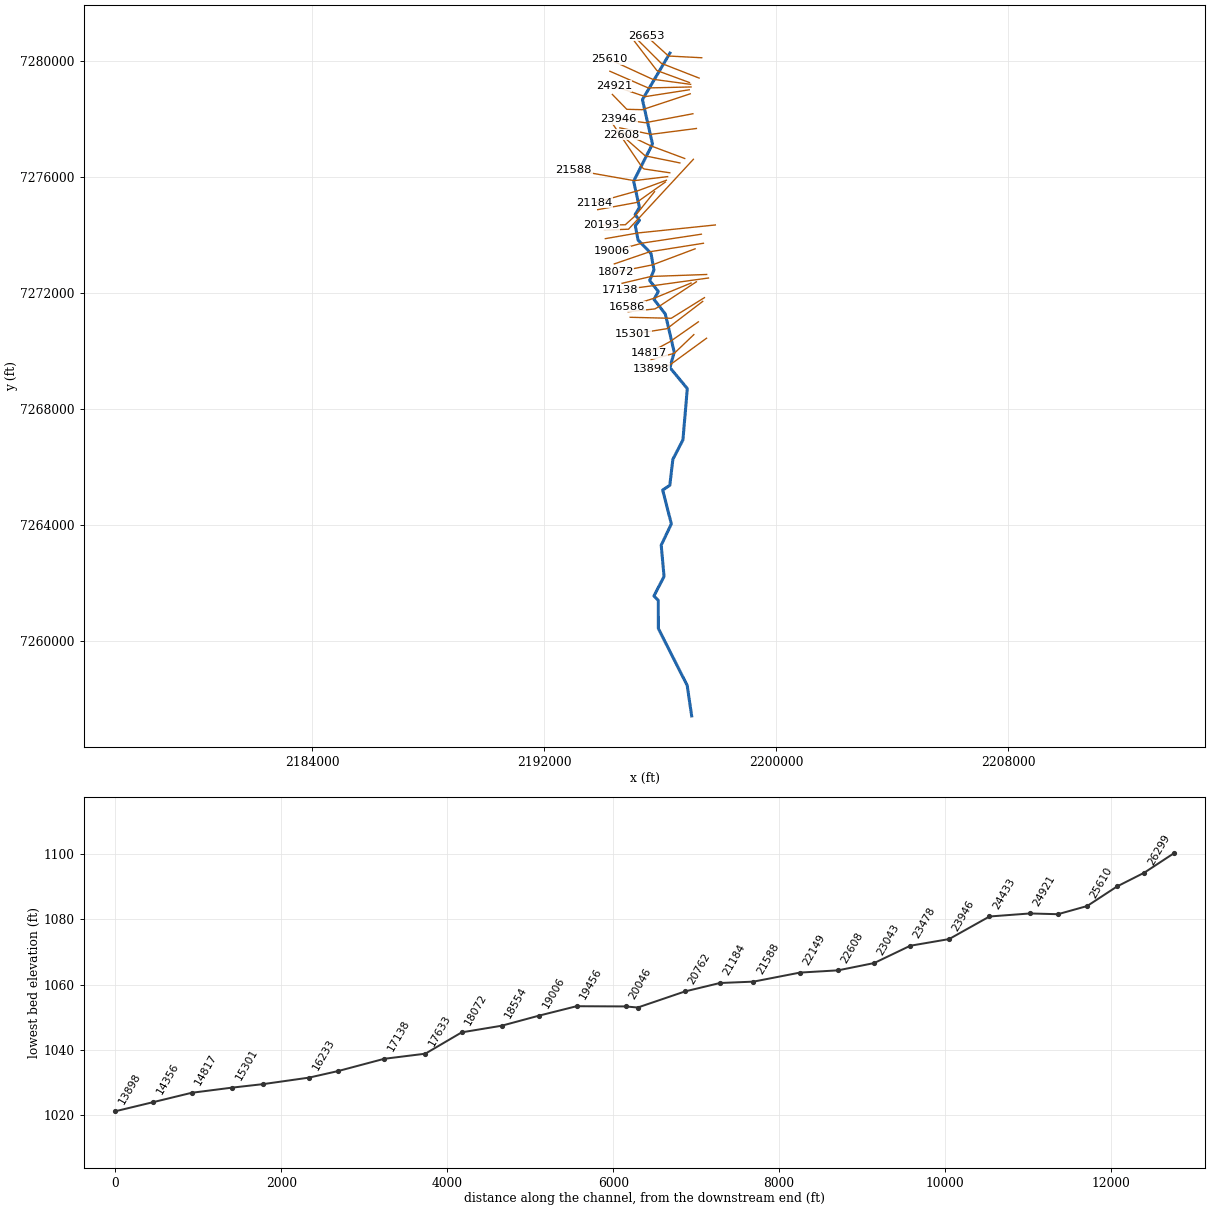
--- Upper Denton 47.prj (project) ---

Proj Title=Upper Denton 47 Base Level Engineering
Current Plan=p01
Default Exp/Contr=0.3,0.1
English Units
Geom File=g01
Flow File=f01
Plan File=p01
Y Axis Title=Elevation
X Axis Title(PF)=Main Channel Distance
X Axis Title(XS)=Station
BEGIN DESCRIPTION:
Upper Denton 47
END DESCRIPTION:
DSS Export Rating Curves= 0
DSS Export Rating Curve Sorted= 0
DSS Export Volume Flow Curves= 0
DXF OffsetX= 0
DXF OffsetY= 0
DXF ScaleX= 1
DXF ScaleY= 10

--- Upper Denton 47.p01 (plan) ---

Plan Title=Multiple Run
Short Identifier=Multiple
Geom File=g01
Flow File=f01
Subcritical Flow
K Sum by GR= 0
Std Step Tol= 0.01
Critical Tol= 0.01
Num of Std Step Trials= 20
Max Error Tol= 0.3
Flow Tol Ratio= 0.001
Split Flow NTrial= 30
Split Flow Tol= 0.02
Split Flow Ratio= 0.02
Log Output Level= 0
Friction Slope Method= 1
Unsteady Friction Slope Method= 2
Unsteady Bridges Friction Slope Method= 1
Parabolic Critical Depth
Global Vel Dist=  1 , 1 , 1
Global Log Level= 0
CheckData=True
Encroach Param= -1, 0, 0, 0
BEGIN DESCRIPTION:
Multiple Run
END DESCRIPTION:

--- Upper Denton 47.f01 (steady flow) ---

Flow Title=Multiple
Program Version=4.10
Number of Profiles= 7
Profile Names=10-year,25-year,50-year,1pct_min,100-year,1pct_plu,500-year
River Rch & RM=Upper Denton 47,Reach-1         ,26653
     561     768     937     568    1134    2263    1665
River Rch & RM=Upper Denton 47,Reach-1         ,24433
     874    1225    1519     934    1863    3718    2814
River Rch & RM=Upper Denton 47,Reach-1         ,19456
    1180    1677    2101    1303    2600    5188    3998
River Rch & RM=Upper Denton 47,Reach-1         ,14817
    1200    1707    2138    1326    2646    5280    4069
River Rch & RM=Upper Denton 47,Reach-1         ,12865
    1674    2420    3064    1920    3831    7643    6010
River Rch & RM=Upper Denton 47,Reach-1         ,10813
    1984    2890    3679    2316    4622    9222    7323
River Rch & RM=Upper Denton 47,Reach-1         ,10164
    1984    2890    3679    2316    4622    9222    7323
River Rch & RM=Upper Denton 47,Reach-1         ,9217
    2825    4163    5343    3386    6756   13481   10848
River Rch & RM=Upper Denton 47,Reach-1         ,2127
    3100    4594    5918    3764    7509   14983   12144
Boundary for River Rch & Prof#=Upper Denton 47,Reach-1         , 1
Up Type= 0
Dn Type= 3
Dn Slope=0.004
Boundary for River Rch & Prof#=Upper Denton 47,Reach-1         , 2
Up Type= 0
Dn Type= 3
Dn Slope=0.004
Boundary for River Rch & Prof#=Upper Denton 47,Reach-1         , 3
Up Type= 0
Dn Type= 3
Dn Slope=0.004
Boundary for River Rch & Prof#=Upper Denton 47,Reach-1         , 4
Up Type= 0
Dn Type= 3
Dn Slope=0.004
Boundary for River Rch & Prof#=Upper Denton 47,Reach-1         , 5
Up Type= 0
Dn Type= 3
Dn Slope=0.004
Boundary for River Rch & Prof#=Upper Denton 47,Reach-1         , 6
Up Type= 0
Dn Type= 3
Dn Slope=0.004
Boundary for River Rch & Prof#=Upper Denton 47,Reach-1         , 7
Up Type= 0
Dn Type= 3
Dn Slope=0.004
DSS Import GetInterval= 0
DSS Import GetPeak= 0
DSS Import FillOption= 0

--- Upper Denton 47.g01 (geometry) ---

Geom Title=Existing Conditions
Program Version=4.10

River Reach=Upper Denton 47 ,Reach-1
Reach XY= 30
        2196329.        7280260.      2195381.18      7278654.55
      2195728.79      7277128.27      2195078.34      7275841.77
      2195279.07      7274941.71      2195128.62      7274689.81
      2195279.11      7274494.64      2195136.32       7274310.1
      2195231.23       7273815.9      2195676.62      7273354.47
      2195779.28      7272782.76      2195629.59      7272420.62
      2195929.27      7272041.48      2195780.36      7271769.67
      2196171.01      7271263.35      2196477.62      7269950.34
      2196331.17      7269415.45      2196928.64      7268694.85
      2196778.04      7266925.96      2196431.12      7266254.12
      2196325.56      7265361.22      2196079.91      7265194.06
      2196378.93      7264030.03      2196029.37      7263294.83
      2196127.04      7262215.89      2195778.21      7261544.92
      2195928.96      7261389.81      2195930.92      7260421.95
      2196925.46      7258458.53        2197079.        7257410.

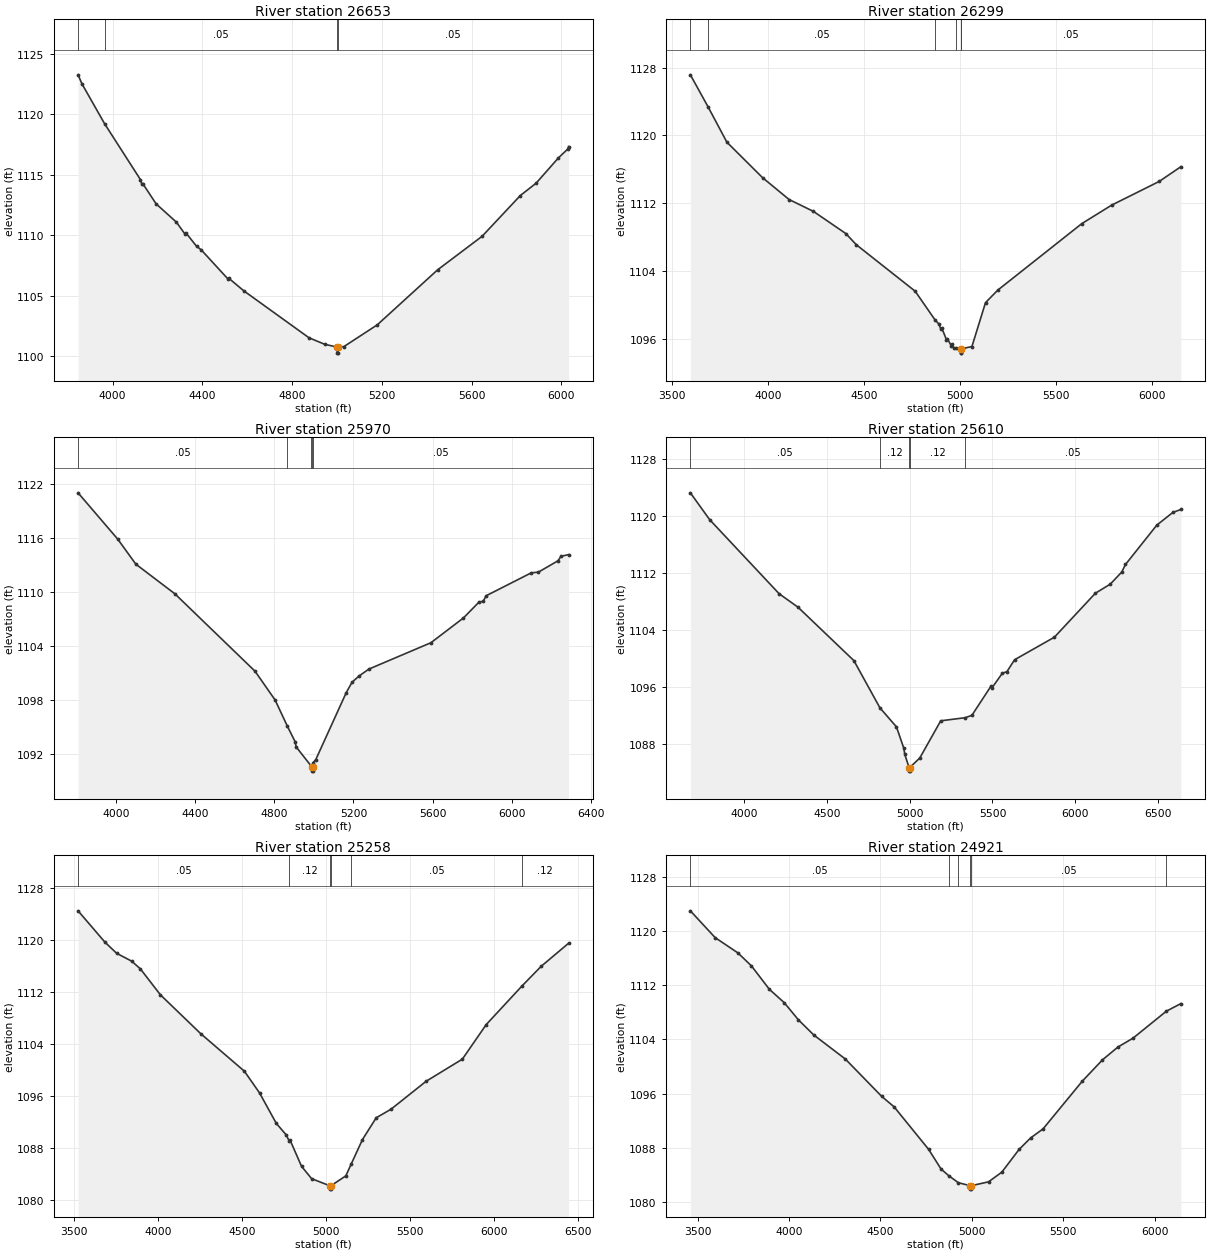
Type RM Length L Ch R = 1 ,26653   ,354,354,354
BEGIN DESCRIPTION:
Upper Denton 47 58.0
END DESCRIPTION:
XS GIS Cut Line= 3
      2197426.46      7280100.22        2196279.        7280160.
      2195511.01      7280856.05
#Sta/Elev= 30
  3846.5 1123.25    3864  1122.5  3964.6 1119.21  4124.3 1114.59    4130 1114.24
    4135 1114.25  4194.4 1112.58  4284.6 1111.07  4321.2 1110.13  4326.2  1110.2
  4374.7 1109.07  4394.7 1108.79  4512.4 1106.41  4517.5 1106.44    4585 1105.39
  4875.4 1101.51  4945.5 1100.97  5000.6 1100.74  5000.9 1100.24  5004.4 1100.24
  5004.6 1100.74    5031 1100.78  5179.7 1102.58  5448.7 1107.13  5646.7  1109.9
    5817 1113.27  5887.3 1114.29  5986.6 1116.38  6029.2 1117.13    6032 1117.32
#Mann= 4 ,-1 , 0
  3846.5     .12       0  3964.6     .05       0  5000.6    .033       0
  5004.6     .05       0
Bank Sta=5000.6,5004.6
XS Rating Curve= 0 ,0
Exp/Cntr=0.3,0.1

Type RM Length L Ch R = 1 ,26299   ,329,329,329
BEGIN DESCRIPTION:
Upper Denton 47 57.0
END DESCRIPTION:
XS GIS Cut Line= 3
      2197336.16      7279398.83        2196029.        7279910.
      2195212.73      7280723.67
#Sta/Elev= 30
  3596.2 1127.15    3688 1123.39  3786.4 1119.21  3972.2 1115.03  4110.6 1112.45
  4237.4 1111.05  4406.6 1108.43  4460.9 1107.12  4767.6 1101.64    4871 1098.26
  4892.4 1097.74  4900.7 1097.18  4906.1 1097.31  4930.5 1095.93  4935.9 1096.05
    4955 1095.22  4960.4 1095.39  4967.5 1094.97  4978.5 1094.91  5004.8 1094.84
  5005.1 1094.34  5008.6 1094.34  5008.8 1094.84  5063.4 1095.12  5134.1 1100.29
  5197.7 1101.76  5636.1 1109.61  5791.7 1111.79  6039.2 1114.58  6152.3 1116.32
#Mann= 6 ,-1 , 0
  3596.2     .12       0    3688     .05       0    4871     .12       0
  4978.5     .05       0  5004.8    .033       0  5008.8     .05       0
Bank Sta=5004.8,5008.8
XS Rating Curve= 0 ,0
Exp/Cntr=0.3,0.1

Type RM Length L Ch R = 1 ,25970   ,360,360,360
BEGIN DESCRIPTION:
Upper Denton 47 56.0
END DESCRIPTION:
XS GIS Cut Line= 3
      2197002.81      7279246.06        2195879.        7279660.
      2195100.69      7280675.78
#Sta/Elev= 30
  3809.2 1121.01  4009.5 1115.87    4101 1113.09  4298.1  1109.8  4703.1  1101.2
  4804.3 1098.01  4866.5 1095.09  4905.6 1093.37  4910.9 1092.79  4987.9 1090.64
  4989.6 1090.61  4989.8 1090.11  4993.3 1090.11  4993.6 1090.61  4996.9 1091.06
    5010  1091.4  5163.7 1098.83  5192.7 1099.97    5228 1100.67  5277.9 1101.44
  5591.6 1104.37  5755.7 1107.12  5834.6 1108.89  5855.4 1108.96  5869.9 1109.58
  6098.4 1112.13  6133.7  1112.2  6233.4 1113.47    6248 1113.96  6286.5 1114.15
#Mann= 5 ,-1 , 0
  3809.2     .05       0  4866.5     .12       0  4987.9     .05       0
  4989.6    .033       0  4993.6     .05       0
Bank Sta=4989.6,4993.6
XS Rating Curve= 0 ,0
Exp/Cntr=0.3,0.1

Type RM Length L Ch R = 1 ,25610   ,352,352,352
BEGIN DESCRIPTION:
Upper Denton 47 55.0
END DESCRIPTION:
XS GIS Cut Line= 3
      2197044.52      7279183.55        2195729.        7279360.
      2194238.97      7280044.65
#Sta/Elev= 30
  3672.7 1123.23  3789.3 1119.46  4209.1 1109.06    4324 1107.15  4661.8 1099.65
  4819.4 1093.01  4919.3 1090.34  4963.5 1087.35  4969.7 1086.47  4995.5 1084.62
  4995.7 1084.12  4999.2 1084.12  4999.5 1084.62  5060.2 1085.96  5187.1 1091.19
  5335.6 1091.63  5375.5 1091.96  5490.4 1096.04  5495.9 1095.79  5559.3 1097.86
  5587.8 1098.11  5633.7 1099.77  5874.6 1102.94  6122.5 1109.12  6212.8  1110.4
  6281.7 1112.09  6304.7 1113.16  6494.1 1118.69  6591.5 1120.48  6639.8 1120.89
#Mann= 5 ,-1 , 0
  3672.7     .05       0  4819.4     .12       0  4995.5     .07       0
  4999.5     .12       0  5335.6     .05       0
Bank Sta=4995.5,4999.5
XS Rating Curve= 0 ,0
Exp/Cntr=0.3,0.1

Type RM Length L Ch R = 1 ,25258   ,337,337,337
BEGIN DESCRIPTION:
Upper Denton 47 54.0
END DESCRIPTION:
XS GIS Cut Line= 3
      2197058.43      7279093.27        2195579.        7279060.
      2194259.75      7279634.95
#Sta/Elev= 30
  3524.9 1124.43  3684.4 1119.62  3754.4  1117.9  3844.4 1116.68  3896.1 1115.49
  4014.5 1111.52  4254.5 1105.54  4514.6 1099.76  4604.6 1096.43  4704.6 1091.73
  4764.6 1089.93  4780.1 1089.06    4786 1089.19  4854.7 1085.13  4914.7 1083.23
  5024.5 1082.12  5024.8 1081.62  5028.3 1081.62  5028.5 1082.12  5118.3 1083.66
  5150.1 1085.47  5217.4 1089.25  5299.2  1092.6  5386.5  1093.9  5596.1 1098.21
  5811.9 1101.62  5953.7 1106.93  6165.8 1112.85    6281  1115.9  6443.8 1119.44
#Mann= 6 ,-1 , 0
  3524.9     .05       0  4780.1     .12       0  5024.5     .07       0
  5028.5     .12       0  5150.1     .05       0  6165.8     .12       0
Bank Sta=5024.5,5028.5
XS Rating Curve= 0 ,0
Exp/Cntr=0.3,0.1

Type RM Length L Ch R = 1 ,24921   ,488,488,488
BEGIN DESCRIPTION:
Upper Denton 47 53.0
END DESCRIPTION:
XS GIS Cut Line= 3
      2196995.89      7278996.05        2195479.        7278760.
      2194392.87      7279127.61
#Sta/Elev= 30
  3460.9 1123.04  3596.1 1119.08  3720.9 1116.81  3794.8 1114.89  3892.9 1111.42
  3973.9 1109.45  4051.4 1106.91  4135.8 1104.66  4307.9 1101.11  4506.8 1095.58
  4574.7 1094.03  4763.3 1087.74  4831.3 1084.83  4873.8 1083.83  4926.1  1082.8
  4991.5 1082.35  4991.8 1081.85  4995.3 1081.85  4995.5 1082.35  5091.1 1082.93
  5163.6 1084.36  5257.9 1087.72  5320.8 1089.42  5388.9 1090.76  5603.7 1097.83
  5713.9 1100.98  5798.4 1102.88  5881.3  1104.2  6063.4 1108.19  6142.7 1109.31
#Mann= 6 ,-1 , 0
  3460.9     .05       0  4873.8     .12       0  4926.1     .05       0
  4991.5    .033       0  4995.5     .05       0  6063.4     .12       0
Bank Sta=4991.5,4995.5
XS Rating Curve= 0 ,0
Exp/Cntr=0.3,0.1

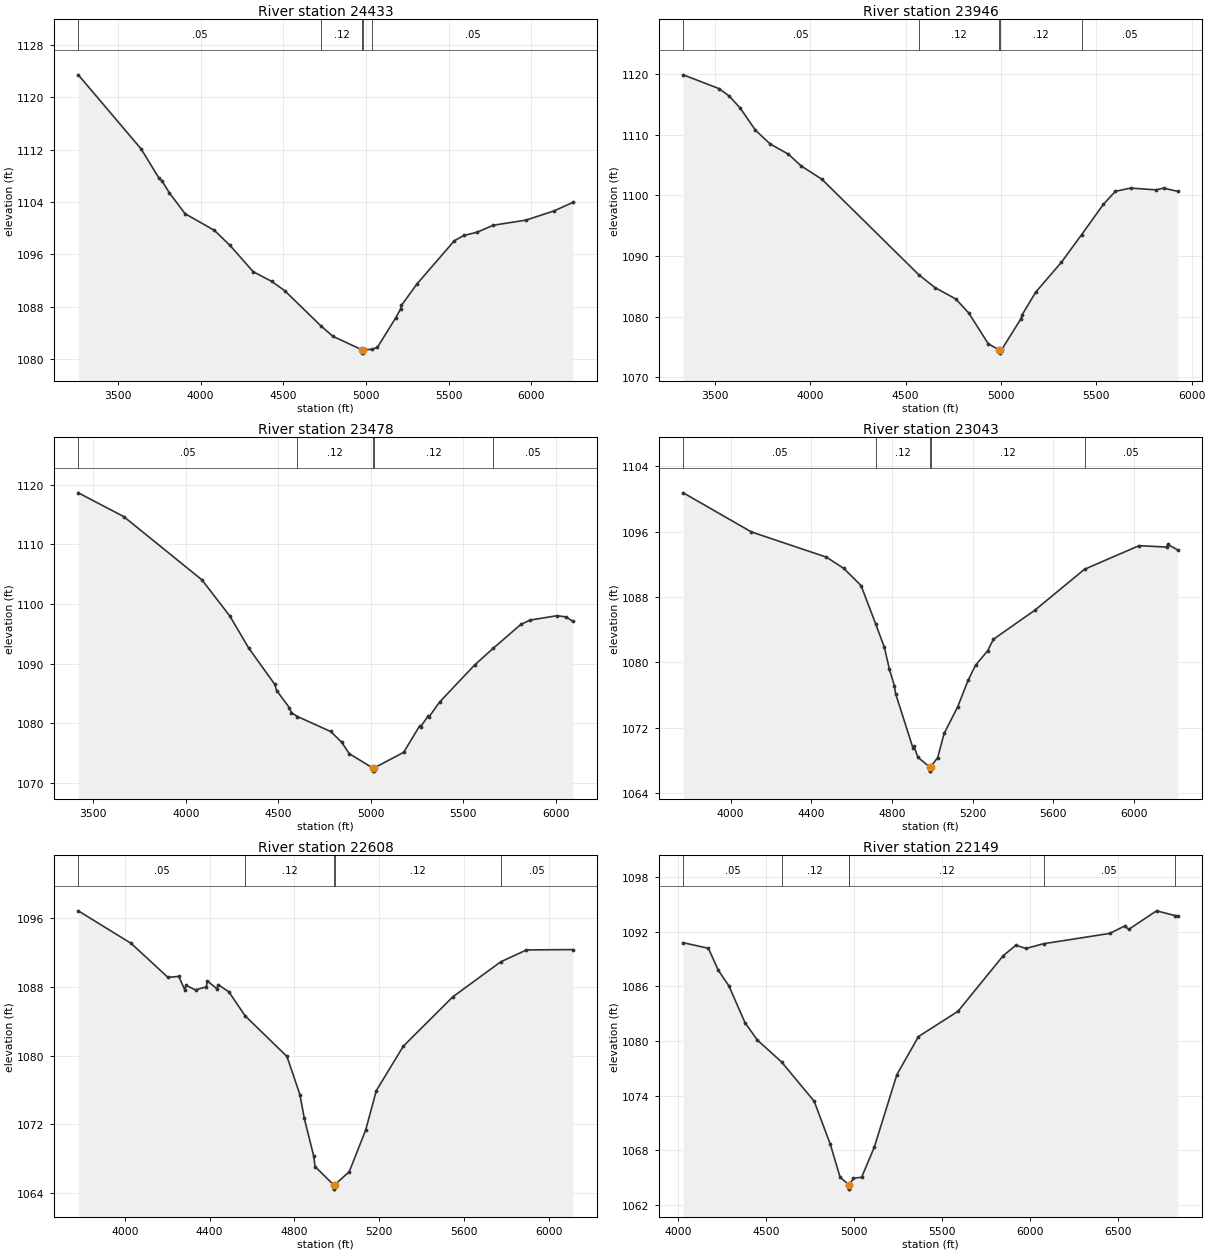
Type RM Length L Ch R = 1 ,24433   ,487,487,487
BEGIN DESCRIPTION:
Upper Denton 47 52.0
END DESCRIPTION:
XS GIS Cut Line= 4
      2197030.62      7278857.16        2195379.        7278310.
      2194843.12      7278322.44      2194344.17      7278835.24
#Sta/Elev= 30
  3259.7 1123.44  3640.6  1112.1  3747.4 1107.68  3767.1 1107.21  3810.8 1105.41
  3905.9 1102.22  4083.1 1099.68  4177.9 1097.37    4318 1093.36  4430.7 1091.87
  4508.2 1090.47  4729.5 1085.04  4799.4  1083.5  4976.5 1081.42  4976.7 1080.92
  4980.2 1080.92  4980.5 1081.42  5037.2 1081.51  5069.6 1081.81  5179.6 1086.29
  5209.6 1087.67  5214.9 1088.22  5309.7 1091.52  5535.2  1098.1  5593.4 1098.91
  5671.3 1099.38  5770.1 1100.46  5968.1 1101.24  6137.9 1102.65  6251.1 1103.94
#Mann= 5 ,-1 , 0
  3259.7     .05       0  4729.5     .12       0  4976.5     .07       0
  4980.5     .12       0  5037.2     .05       0
Bank Sta=4976.5,4980.5
XS Rating Curve= 0 ,0
Exp/Cntr=0.3,0.1

Type RM Length L Ch R = 1 ,23946   ,468,468,468
BEGIN DESCRIPTION:
Upper Denton 47 51.0
END DESCRIPTION:
XS GIS Cut Line= 3
       2197120.9      7278169.66        2195479.        7277860.
      2194565.32      7277989.11
#Sta/Elev= 30
  3333.4 1119.83    3522 1117.55  3574.4 1116.34  3631.9 1114.37  3711.9 1110.72
  3789.2 1108.45  3884.9 1106.76  3951.5 1104.84  4061.5 1102.61  4569.1  1086.9
  4653.3  1084.8  4763.3 1082.91  4831.2  1080.6    4933 1075.55    4992  1074.5
  4992.3    1074  4995.8    1074  4996.1  1074.5  5006.8 1074.74  5105.2  1079.7
  5110.9 1080.32    5182 1084.04  5317.3 1088.98  5422.4 1093.49  5537.4 1098.52
  5600.1 1100.65  5679.5 1101.18  5812.2 1100.89  5852.6 1101.17    5927 1100.64
#Mann= 5 ,-1 , 0
  3333.4     .05       0  4569.1     .12       0    4992     .07       0
  4996.1     .12       0  5422.4     .05       0
Bank Sta=4992,4996.1
XS Rating Curve= 0 ,0
Exp/Cntr=0.3,0.1

Type RM Length L Ch R = 1 ,23478   ,435,435,435
BEGIN DESCRIPTION:
Upper Denton 47 50.0
END DESCRIPTION:
XS GIS Cut Line= 3
      2197242.38      7277661.84        2195679.        7277460.
      2194603.76      7277682.64
#Sta/Elev= 30
  3418.7 1118.62  3664.1 1114.65  4087.6 1104.03  4238.8 1097.95  4339.7 1092.64
  4480.8 1086.53  4491.7 1085.47    4561 1082.58  4571.6 1081.76  4604.4 1081.11
  4783.3 1078.61  4843.8  1076.8  4884.1 1074.89  5012.9 1072.46  5013.3 1071.96
  5016.8 1071.96  5017.1 1072.46  5178.9 1075.12    5266  1079.6  5271.1 1079.42
  5311.1 1081.22  5316.2 1081.07  5372.9 1083.54    5562 1089.74  5663.9 1092.58
    5813 1096.57  5863.2 1097.29  6008.6 1098.02  6058.8  1097.8  6093.1 1097.07
#Mann= 5 ,-1 , 0
  3418.7     .05       0  4604.4     .12       0  5012.9     .07       0
  5017.1     .12       0  5663.9     .05       0
Bank Sta=5012.9,5017.1
XS Rating Curve= 0 ,0
Exp/Cntr=0.3,0.1

Type RM Length L Ch R = 1 ,23043   ,435,435,435
BEGIN DESCRIPTION:
Upper Denton 47 49.0
END DESCRIPTION:
XS GIS Cut Line= 3
      2196839.65      7276627.12        2195679.        7277060.
      2194583.32      7277578.22
#Sta/Elev= 30
  3765.5 1100.74  4102.6 1095.96  4475.4 1092.86    4561 1091.49  4646.6 1089.39
  4719.4 1084.68  4762.6  1081.8  4787.5 1079.12  4812.1 1077.11  4817.9 1076.16
  4903.5 1069.53  4908.8 1069.73  4928.5 1068.36  4986.9 1067.16  4987.3 1066.66
  4990.9 1066.66  4991.2 1067.16  5026.4 1068.31  5058.4 1071.27  5125.9 1074.54
  5177.7 1077.81  5214.4 1079.63  5274.2  1081.4  5302.9 1082.81  5507.3 1086.35
  5754.4 1091.38  6024.6 1094.27  6161.1  1094.1  6166.6 1094.43  6216.3 1093.74
#Mann= 5 ,-1 , 0
  3765.5     .05       0  4719.4     .12       0  4986.9     .07       0
  4991.2     .12       0  5754.4     .05       0
Bank Sta=4986.9,4991.2
XS Rating Curve= 0 ,0
Exp/Cntr=0.3,0.1

Type RM Length L Ch R = 1 ,22608   ,459,459,459
BEGIN DESCRIPTION:
Upper Denton 47 48.0
END DESCRIPTION:
XS GIS Cut Line= 3
      2196672.97      7276474.35        2195479.      7276716.94
      2194645.21      7277453.51
#Sta/Elev= 30
    3781 1096.88    4030 1093.09  4203.4 1089.13  4254.5 1089.23  4283.2 1087.66
  4288.3 1088.19  4333.8 1087.66  4384.5 1088.02  4389.6 1088.71  4435.1 1087.77
  4440.2 1088.28  4490.8 1087.44  4567.8 1084.63  4764.7  1079.9  4825.9 1075.45
  4846.3  1072.7  4890.7  1068.3  4897.3 1067.06  4984.7 1064.93    4985 1064.43
  4988.6 1064.43    4989 1064.93  5058.1 1066.44  5135.9 1071.33  5186.1 1075.92
  5313.3  1081.1  5546.6 1086.85  5771.5 1090.92  5893.8 1092.32  6111.9 1092.36
#Mann= 5 ,-1 , 0
    3781     .05       0  4567.8     .12       0  4984.7     .07       0
    4989     .12       0  5771.5     .05       0
Bank Sta=4984.7,4989
XS Rating Curve= 0 ,0
Exp/Cntr=0.3,0.1

Type RM Length L Ch R = 1 ,22149   ,561,561,561
BEGIN DESCRIPTION:
Upper Denton 47 47.0
END DESCRIPTION:
XS GIS Cut Line= 4
      2196325.79      7276134.07      2195438.26      7276265.56
        2195379.        7276310.      2194346.74      7277835.23
#Sta/Elev= 30
  4028.7 1090.77  4171.8 1090.16  4227.6 1087.77  4288.3 1086.04  4380.3 1081.99
    4450  1080.1  4588.5 1077.68  4773.5 1073.38  4864.5 1068.71  4921.1 1065.04
  4969.7 1064.24  4970.1 1063.74  4973.7 1063.74    4974 1064.24  4996.9 1064.94
  5043.4 1065.04  5115.3 1068.33  5244.2 1076.31    5367 1080.48  5591.7 1083.25
  5849.4 1089.36  5921.3  1090.5  5978.2 1090.14  6078.2 1090.66  6454.6 1091.79
  6541.4 1092.62  6562.4 1092.23  6721.2 1094.27  6825.9 1093.75  6841.7 1093.73
#Mann= 6 ,-1 , 0
  4028.7     .05       0  4588.5     .12       0  4969.7     .07       0
    4974     .12       0  6078.2     .05       0  6825.9     .12       0
Bank Sta=4969.7,4974
XS Rating Curve= 0 ,0
Exp/Cntr=0.3,0.1

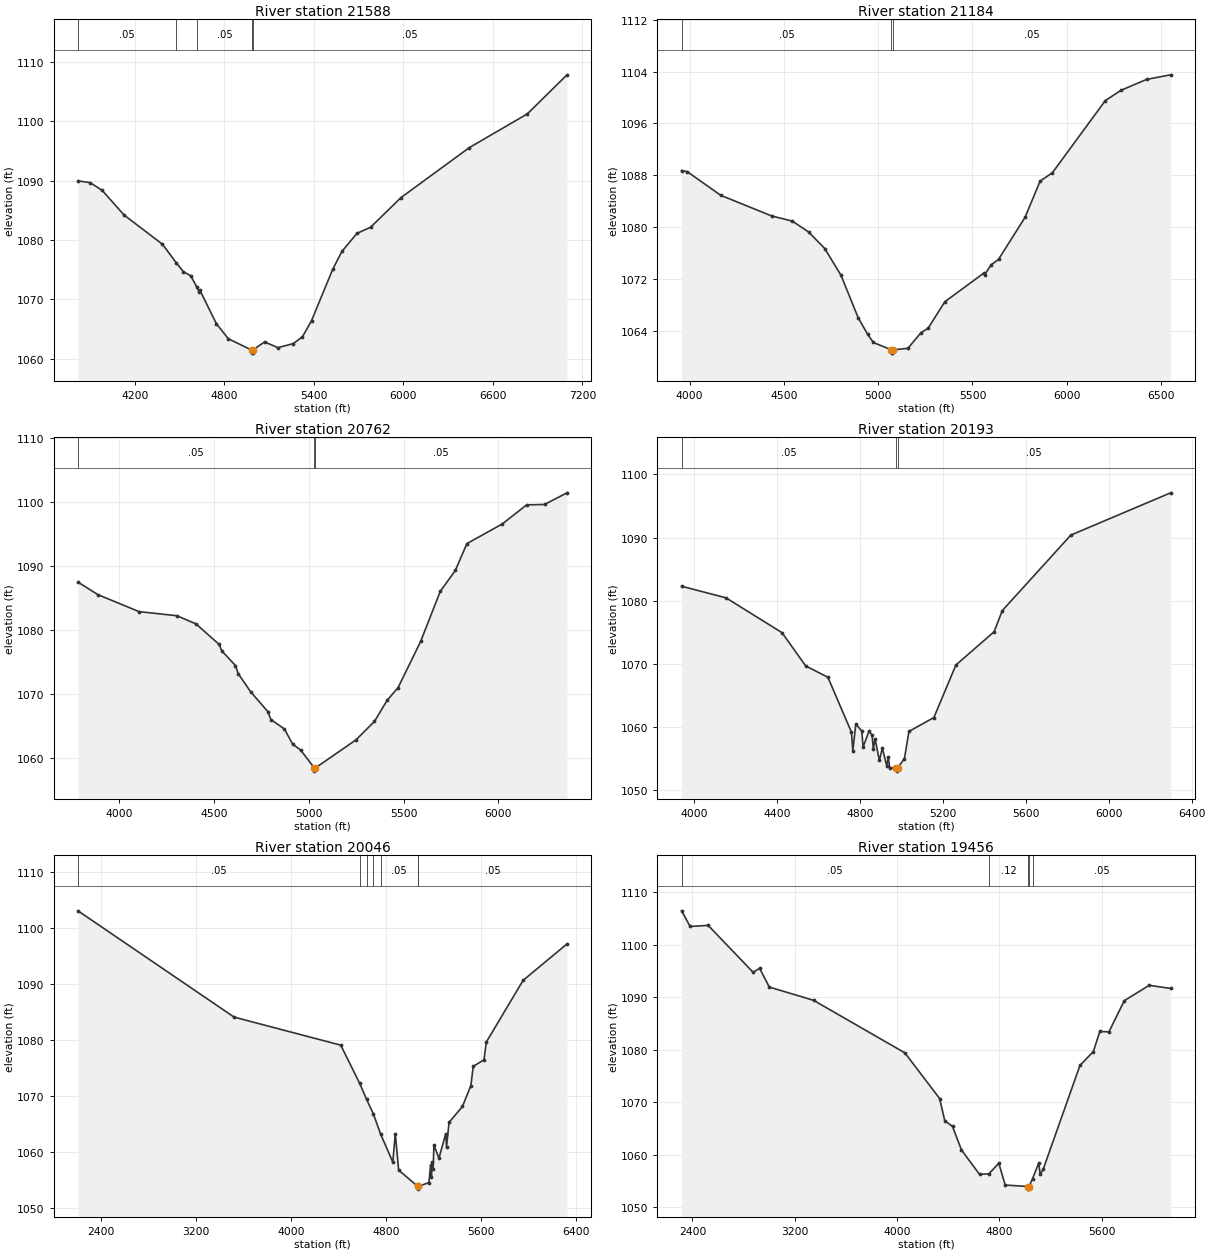
Type RM Length L Ch R = 1 ,21588   ,404,404,404
BEGIN DESCRIPTION:
Upper Denton 47 46.0
END DESCRIPTION:
XS GIS Cut Line= 3
      2196249.38      7276002.13      2195096.59      7275863.24
      2193013.67      7276231.22
#Sta/Elev= 30
  3820.2 1089.94  3901.2 1089.65  3981.7 1088.36  4129.2 1084.19  4385.5  1079.3
  4478.5 1076.17  4525.6 1074.68    4576 1073.97  4617.4 1072.02  4631.8 1071.23
  4636.8 1071.56  4747.2 1065.93  4827.8 1063.38  4985.5 1061.47  4985.9 1060.97
  4989.5 1060.97    4990 1061.47  5070.3 1062.85  5160.2 1061.89  5263.2 1062.58
  5324.1 1063.72  5385.1 1066.44  5527.2 1075.08  5588.2 1078.07  5689.7 1081.12
  5781.1 1082.15  5984.2 1087.13  6441.2 1095.52  6831.5 1101.22  7096.5 1107.78
#Mann= 5 ,-1 , 0
  3820.2     .05       0  4478.5     .12       0  4617.4     .05       0
  4985.5    .033       0    4990     .05       0
Bank Sta=4985.5,4990
XS Rating Curve= 0 ,0
Exp/Cntr=0.3,0.1

Type RM Length L Ch R = 1 ,21184   ,422,422,422
BEGIN DESCRIPTION:
Upper Denton 47 45.0
END DESCRIPTION:
XS GIS Cut Line= 3
      2196207.68      7275877.12      2195228.53      7275516.02
       2193735.5      7275099.35
#Sta/Elev= 30
  3957.4 1088.72  3987.5 1088.54  4164.8  1084.9  4435.6 1081.71  4544.5 1080.92
  4630.5 1079.25  4716.5 1076.69  4802.5 1072.57  4893.9 1066.01    4944 1063.45
  4974.5 1062.19  5070.4 1061.05  5071.3 1060.55  5075.2 1060.55    5076 1061.05
  5157.5 1061.29  5225.9 1063.67  5265.2 1064.41  5353.5 1068.48  5559.4 1072.88
  5564.6 1072.64  5598.8 1074.17  5638.1 1075.01  5779.2 1081.52  5858.8 1087.09
  5924.5  1088.4  6204.9 1099.52  6287.9  1101.1  6423.3 1102.78  6551.1 1103.49
#Mann= 3 ,-1 , 0
  3957.4     .05       0  5070.4     .04       0    5076     .05       0
Bank Sta=5070.4,5076
XS Rating Curve= 0 ,0
Exp/Cntr=0.3,0.1

Type RM Length L Ch R = 1 ,20762   ,569,569,569
BEGIN DESCRIPTION:
Upper Denton 47 44.0
END DESCRIPTION:
XS GIS Cut Line= 3
      2196172.94       7275814.6        2195179.        7275110.
       2193839.6      7274863.23
#Sta/Elev= 30
  3781.2  1087.5  3887.2 1085.53  4103.8 1082.89  4303.1 1082.25    4404 1080.97
  4525.8 1077.77  4540.6 1076.74    4612 1074.46  4626.7  1073.2    4692 1070.37
  4783.4 1067.25    4799 1066.02  4870.4 1064.55  4913.8 1062.18  4956.5 1061.24
  5028.3 1058.46  5029.2 1057.96  5033.9 1058.46  5248.3 1062.85  5345.3 1065.72
  5412.4 1069.02  5470.5 1071.02  5589.3 1078.23  5692.8 1086.06  5772.3 1089.32
  5833.4 1093.52    6021 1096.61  6148.6 1099.58  6243.3 1099.64  6361.5 1101.46
#Mann= 3 ,-1 , 0
  3781.2     .05       0  5028.3    .033       0  5033.9     .05       0
Bank Sta=5028.3,5033.9
XS Rating Curve= 0 ,0
Exp/Cntr=0.3,0.1

Type RM Length L Ch R = 1 ,20193   ,147,147,147
BEGIN DESCRIPTION:
Upper Denton 47 43.0
END DESCRIPTION:
XS GIS Cut Line= 4
      2195797.96      7275481.27      2195138.26       7274654.9
      2194791.03       7274342.4      2193957.68      7274328.52
#Sta/Elev= 30
  3940.6 1082.29  4154.3 1080.46  4424.9 1074.94  4538.6 1069.69  4645.9 1067.89
  4759.6 1059.19    4766 1056.22  4780.4 1060.46  4809.2 1059.41  4815.6 1056.86
  4844.4 1059.38  4858.8 1058.74  4865.2 1056.52  4873.3 1058.17  4894.1 1054.73
  4908.5 1056.67  4929.3 1053.92  4937.3 1055.21  4943.7 1053.59  4976.1 1053.54
    4977 1053.04  4981.8 1053.54    5015 1055.02  5036.7 1059.32    5157 1061.52
  5263.1 1069.83    5447 1075.08  5487.2 1078.45  5817.2 1090.38  6298.6 1097.07
#Mann= 3 ,-1 , 0
  3940.6     .05       0  4976.1    .033       0  4981.8     .05       0
Bank Sta=4976.1,4981.8
XS Rating Curve= 0 ,0
Exp/Cntr=0.3,0.1

Type RM Length L Ch R = 1 ,20046   ,590,590,590
BEGIN DESCRIPTION:
Upper Denton 47 42.0
END DESCRIPTION:
XS GIS Cut Line= 4
      2197138.29      7276599.38      2195235.48      7274543.79
      2194902.14      7274189.63      2194069.92      7274154.95
#Sta/Elev= 30
  2206.2    1103  3521.5 1084.05  4420.2 1079.05  4580.2 1072.22  4638.3 1069.37
  4694.7 1066.82  4755.9 1063.22    4859 1058.19    4880 1063.26  4908.3 1056.77
  5068.2 1053.88  5069.1 1053.38  5073.9 1053.88  5163.3 1054.54  5177.3 1057.67
  5184.3 1055.49  5191.2 1058.19  5198.5 1056.89  5205.4 1061.22  5247.9 1058.88
  5304.5 1063.25  5311.8 1060.91  5332.8 1065.27  5446.1 1068.13  5516.8 1071.85
  5536.8 1075.27  5626.9 1076.43  5646.9  1079.6  5957.2 1090.61  6326.6  1097.1
#Mann= 7 ,-1 , 0
  2206.2     .05       0  4580.2     .12       0  4638.3     .05       0
  4694.7     .12       0  4755.9     .05       0  5068.2    .033       0
  5073.9     .05       0
Bank Sta=5068.2,5073.9
XS Rating Curve= 0 ,0
Exp/Cntr=0.3,0.1

Type RM Length L Ch R = 1 ,19456   ,450,450,450
BEGIN DESCRIPTION:
Upper Denton 47 41.0
END DESCRIPTION:
XS GIS Cut Line= 3
      2197895.24      7274335.46        2195229.        7274060.
       2194103.8      7273863.28
#Sta/Elev= 30
  2315.3 1106.45  2381.9 1103.47  2522.6 1103.68  2874.5 1094.73  2924.8 1095.51
  3000.6 1091.93    3347  1089.4  4060.8 1079.39  4332.2 1070.69  4372.4 1066.47
  4432.8 1065.37  4503.1 1060.89  4643.9 1056.26  4717.9 1056.37  4794.7 1058.38
  4844.8 1054.22  5024.5 1053.94  5025.6 1053.44  5031.6 1053.94  5058.6 1055.43
  5107.4 1058.43  5117.6 1056.25  5141.9 1057.23  5429.2    1077  5533.8 1079.65
  5584.5 1083.47  5655.6 1083.39    5776 1089.34  5970.3 1092.26    6138 1091.67
#Mann= 5 ,-1 , 0
  2315.3     .05       0  4717.9     .12       0  5024.5     .07       0
  5031.6     .12       0  5058.6     .05       0
Bank Sta=5024.5,5031.6
XS Rating Curve= 0 ,0
Exp/Cntr=0.3,0.1

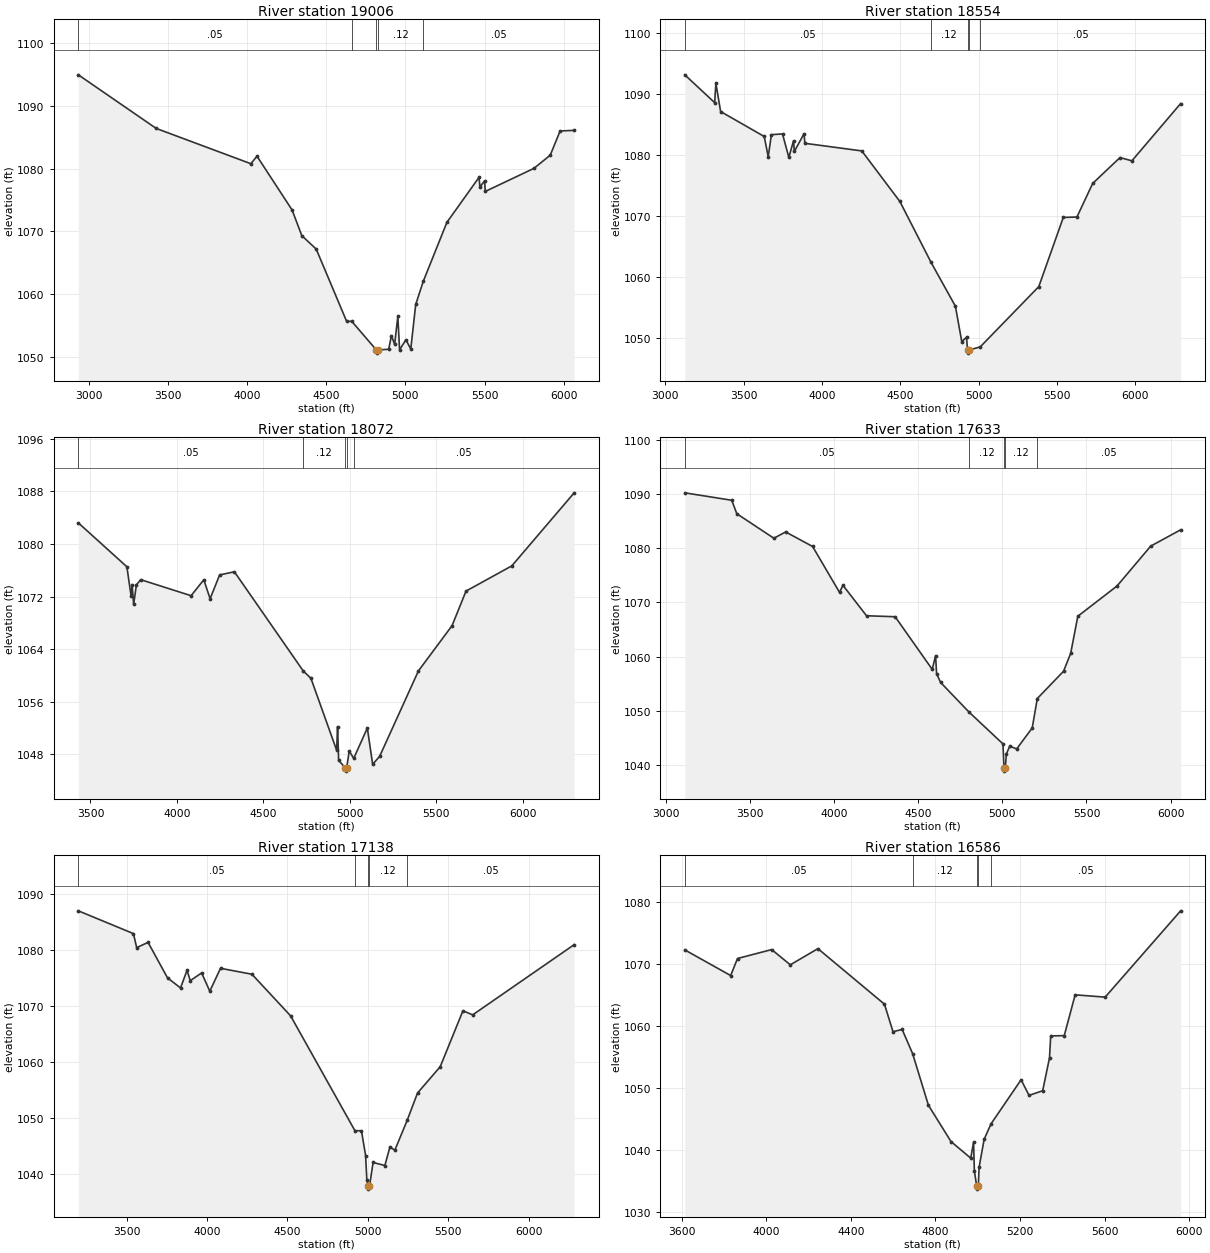
Type RM Length L Ch R = 1 ,19006   ,452,452,452
BEGIN DESCRIPTION:
Upper Denton 47 40.0
END DESCRIPTION:
XS GIS Cut Line= 3
      2197415.42      7274016.94        2195379.        7273710.
      2194343.23      7273426.85
#Sta/Elev= 30
  2933.2 1094.97  3425.1 1086.42  4023.3 1080.79  4062.2 1081.99  4283.9 1073.41
  4345.4 1069.31  4436.4 1067.17  4628.6 1055.64  4661.1 1055.64  4816.7 1051.07
  4817.8 1050.57  4823.9 1051.07  4894.3 1051.19  4911.7 1053.35  4931.9 1051.98
  4952.2 1056.43  4963.2 1051.11    5003 1052.69  5034.1 1051.24  5065.2 1058.34
  5113.6 1062.07  5262.2 1071.43  5465.5 1078.62  5470.7 1077.08    5500 1078.04
  5505.2 1076.37  5812.4 1080.05  5915.3 1082.15  5977.5 1086.01  6066.4 1086.11
#Mann= 5 ,-1 , 0
  2933.2     .05       0  4661.1     .12       0  4816.7     .07       0
  4823.9     .12       0  5113.6     .05       0
Bank Sta=4816.7,4823.9
XS Rating Curve= 0 ,0
Exp/Cntr=0.3,0.1

Type RM Length L Ch R = 1 ,18554   ,482,482,482
BEGIN DESCRIPTION:
Upper Denton 47 39.0
END DESCRIPTION:
XS GIS Cut Line= 3
      2197484.86      7273704.44        2195629.        7273410.
      2194412.99      7272992.98
#Sta/Elev= 30
  3125.3 1093.19  3315.9 1088.62  3323.6 1091.82    3354 1087.16  3632.3 1083.06
  3657.7 1079.74    3678 1083.36  3748.9 1083.48  3789.4 1079.62  3819.2 1082.36
  3824.3  1080.6  3886.5 1083.53  3891.6 1081.94  4255.1 1080.69  4498.1 1072.38
  4696.9 1062.39  4852.5 1055.17    4893 1049.36  4923.4 1050.08  4929.8 1047.97
  4930.9 1047.47  4937.1 1047.97  5010.7 1048.49  5384.7  1058.4    5541 1069.76
  5628.1 1069.83  5728.7 1075.35    5903  1079.6  5978.8 1079.06  6289.9 1088.47
#Mann= 5 ,-1 , 0
  3125.3     .05       0  4696.9     .12       0  4929.8     .07       0
  4937.1     .12       0  5010.7     .05       0
Bank Sta=4929.8,4937.1
XS Rating Curve= 0 ,0
Exp/Cntr=0.3,0.1

Type RM Length L Ch R = 1 ,18072   ,439,439,439
BEGIN DESCRIPTION:
Upper Denton 47 38.0
END DESCRIPTION:
XS GIS Cut Line= 3
      2197198.42      7273513.46        2195729.        7272960.
      2194455.34      7272706.17
#Sta/Elev= 30
  3429.8 1083.21  3710.7 1076.53  3735.6 1072.01    3741 1073.82  3749.8  1070.8
  3765.8 1073.78  3790.7 1074.57  4082.2 1072.13  4155.8 1074.55  4192.3 1071.67
  4247.4 1075.29  4332.7 1075.77  4731.2 1060.68  4775.6 1059.56  4924.5 1048.61
  4929.8 1052.21  4935.9 1047.07  4974.9 1045.94  4976.1 1045.44  4982.3 1045.94
  4997.3  1048.5  5023.2 1047.38    5102 1051.99  5132.8 1046.48  5173.3 1047.69
  5397.7 1060.69  5592.4 1067.58    5673 1072.83  5938.1 1076.67  6298.7 1087.78
#Mann= 5 ,-1 , 0
  3429.8     .05       0  4731.2     .12       0  4974.9     .07       0
  4982.3     .12       0  5023.2     .05       0
Bank Sta=4974.9,4982.3
XS Rating Curve= 0 ,0
Exp/Cntr=0.3,0.1

Type RM Length L Ch R = 1 ,17633   ,495,495,495
BEGIN DESCRIPTION:
Upper Denton 47 37.0
END DESCRIPTION:
XS GIS Cut Line= 3
      2197597.74      7272628.05        2195679.        7272560.
      2194681.12      7272324.24
#Sta/Elev= 30
  3114.1  1090.2    3393 1088.83    3423 1086.35  3643.2 1081.83  3713.2 1082.99
  3873.3 1080.31  4033.4 1071.84  4053.4 1073.16  4193.5 1067.54  4363.6 1067.36
  4583.8 1057.66  4603.8 1060.19  4609.8 1056.85  4633.8 1055.24  4802.3 1049.79
    5004 1043.92  5010.2  1039.4  5011.4  1038.9  5017.9  1039.4    5024 1042.04
  5044.3 1043.51  5085.4 1042.99  5177.9 1046.86    5208 1052.28  5364.1 1057.32
  5406.4 1060.62  5448.7 1067.45  5681.4 1073.02  5881.9 1080.38  6059.4 1083.38
#Mann= 5 ,-1 , 0
  3114.1     .05       0  4802.3     .12       0  5010.2     .07       0
  5017.9     .12       0    5208     .05       0
Bank Sta=5010.2,5017.9
XS Rating Curve= 0 ,0
Exp/Cntr=0.3,0.1

Type RM Length L Ch R = 1 ,17138   ,552,552,552
BEGIN DESCRIPTION:
Upper Denton 47 36.0
END DESCRIPTION:
XS GIS Cut Line= 3
      2197658.48      7272506.52        2195879.        7272260.
      2194603.47      7272089.93
#Sta/Elev= 30
  3199.7 1086.93  3542.4 1082.87  3562.6 1080.37  3633.3 1081.31  3754.4 1074.98
  3835.2 1073.19  3875.6 1076.32  3895.8 1074.49  3966.4 1075.86  4017.2 1072.61
  4083.9 1076.69  4279.4 1075.63  4519.6 1068.22  4919.6 1047.76  4960.3 1047.74
  4986.1 1043.33  4993.7 1039.04  5002.4 1037.84  5003.6 1037.34  5010.1 1037.84
  5032.7 1042.09  5105.9 1041.55  5137.4 1044.87  5167.7 1044.27  5244.7  1049.6
  5308.9 1054.46  5450.2 1059.16  5591.4 1069.12  5651.9 1068.39    6283  1080.9
#Mann= 5 ,-1 , 0
  3199.7     .05       0  4919.6     .12       0  5002.4     .07       0
  5010.1     .12       0  5244.7     .05       0
Bank Sta=5002.4,5010.1
XS Rating Curve= 0 ,0
Exp/Cntr=0.3,0.1

Type RM Length L Ch R = 1 ,16586   ,353,353,353
BEGIN DESCRIPTION:
Upper Denton 47 35.0
END DESCRIPTION:
XS GIS Cut Line= 3
      2197059.59      7272332.93      2195792.19      7271812.08
      2194863.68      7271517.04
#Sta/Elev= 30
  3615.4  1072.2  3832.3 1068.06  3864.7 1070.81  4026.2 1072.25  4114.3 1069.79
  4244.9  1072.4  4559.5 1063.44  4599.9    1059  4643.1 1059.37  4692.8 1055.45
  4767.5 1047.13  4874.2 1041.28  4967.5 1038.61  4980.8 1041.17  4984.7 1036.52
  4995.6 1034.11  4996.8 1033.61  5003.4 1034.11  5006.9 1037.13    5031 1041.66
  5063.6 1044.15  5205.6 1051.25  5243.1 1048.73  5307.6 1049.48  5339.9 1054.78
  5345.7 1058.32  5409.6 1058.37  5461.2 1064.95  5603.1 1064.58  5959.9  1078.5
#Mann= 5 ,-1 , 0
  3615.4     .05       0  4692.8     .12       0  4995.6     .07       0
  5003.4     .12       0  5063.6     .05       0
Bank Sta=4995.6,5003.4
XS Rating Curve= 0 ,0
Exp/Cntr=0.3,0.1

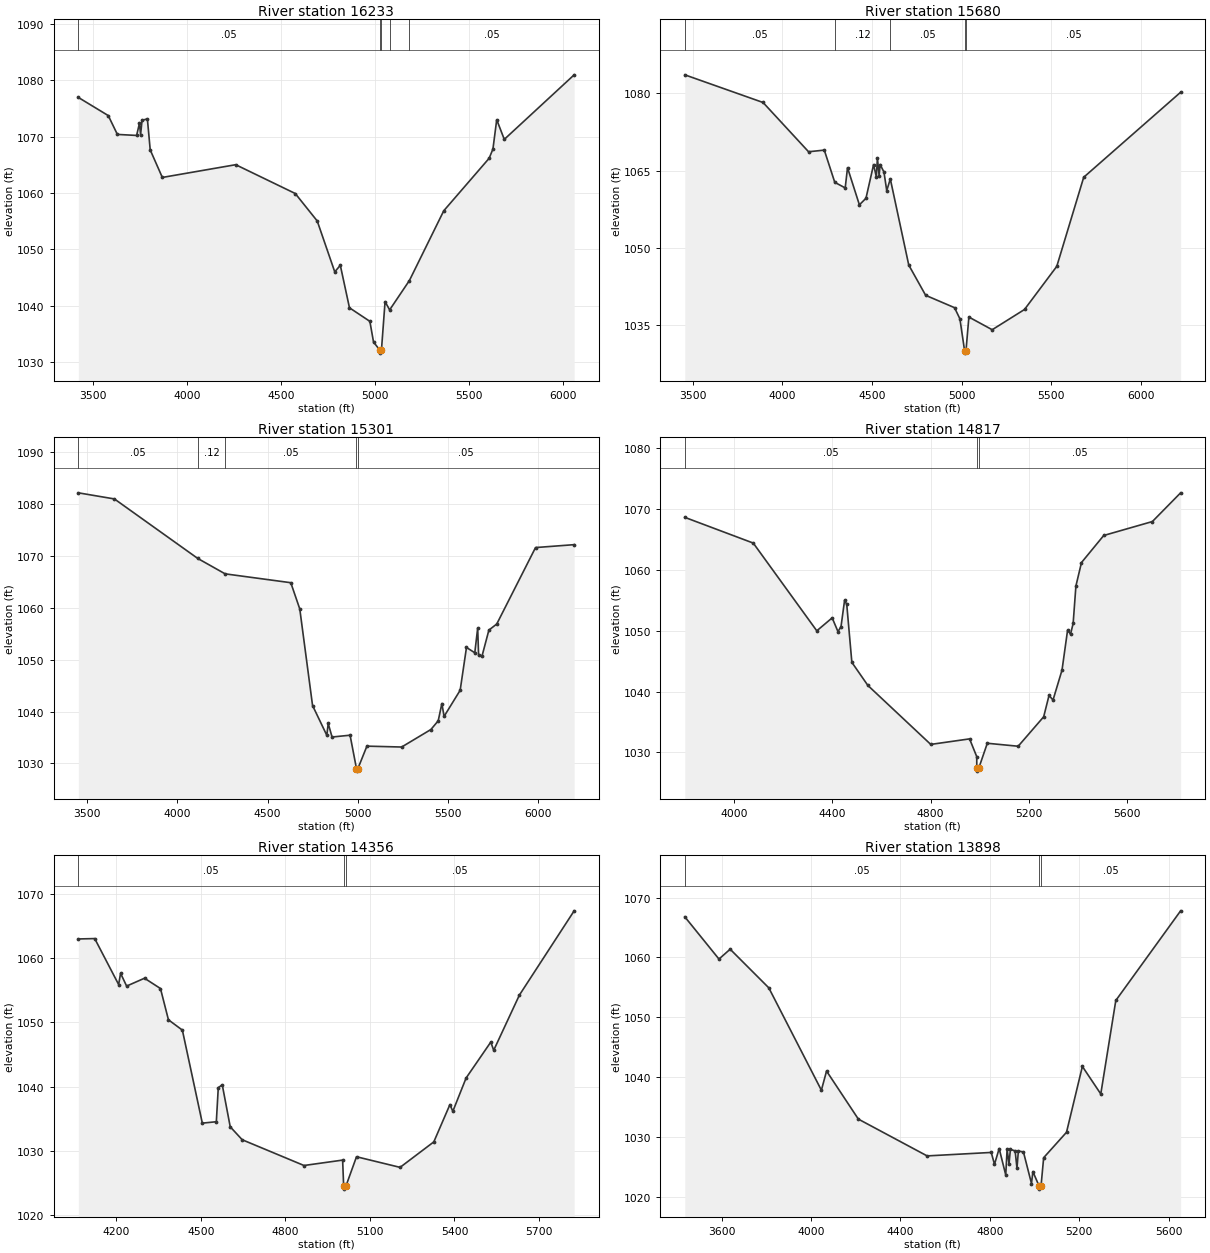
Type RM Length L Ch R = 1 ,16233   ,553,553,553
BEGIN DESCRIPTION:
Upper Denton 47 34.0
END DESCRIPTION:
XS GIS Cut Line= 4
      2197241.86      7272376.33        2195929.        7271510.
       2195813.6      7271440.76      2194889.44      7271343.33
#Sta/Elev= 30
    3423 1076.93  3582.2 1073.71  3630.6 1070.37    3733 1070.19  3748.1 1072.35
  3754.1 1070.33  3761.9 1072.87  3790.2 1073.13  3805.3 1067.62  3869.7 1062.74
  4259.9    1065  4576.6 1059.89  4693.4 1055.02  4786.7 1045.99  4816.2 1047.16
  4864.9 1039.62  4973.3 1037.22  4992.9 1033.55    5027 1032.08  5028.2 1031.58
  5034.9 1032.08  5054.2 1040.71  5078.6 1039.25  5183.7 1044.46  5366.4 1056.83
  5607.7 1066.14  5627.9 1067.78    5648 1072.98  5688.2 1069.49  6059.8 1080.94
#Mann= 5 ,-1 , 0
    3423     .05       0    5027    .033       0  5034.9     .05       0
  5078.6     .12       0  5183.7     .05       0
Bank Sta=5027,5034.9
XS Rating Curve= 0 ,0
Exp/Cntr=0.3,0.1

Type RM Length L Ch R = 1 ,15680   ,379,379,379
BEGIN DESCRIPTION:
Upper Denton 47 33.0
END DESCRIPTION:
XS GIS Cut Line= 3
      2197519.62      7271829.44      2196373.79      7271117.64
      2194958.84      7271152.36
#Sta/Elev= 30
  3456.6  1083.6  3892.9 1078.23  4146.6 1068.67  4234.3 1068.99  4292.7 1062.74
  4350.9 1061.65  4363.8 1065.58    4430 1058.37  4466.6 1059.64  4509.1 1066.18
  4524.5 1063.79  4530.4 1067.44  4539.9 1064.06  4545.7 1066.19    4567 1064.73
  4582.4 1061.13  4602.4 1063.39  4705.2 1046.68  4799.4 1040.81  4960.4 1038.41
  4990.4 1036.24  5016.3 1030.09  5017.5 1029.59  5024.4 1030.09  5040.4 1036.59
  5170.4 1034.13  5350.5 1038.06  5530.5 1046.43  5680.6 1063.72  6220.9 1080.22
#Mann= 5 ,-1 , 0
  3456.6     .05       0  4292.7     .12       0  4602.4     .05       0
  5016.3    .033       0  5024.4     .05       0
Bank Sta=5016.3,5024.4
XS Rating Curve= 0 ,0
Exp/Cntr=0.3,0.1

Type RM Length L Ch R = 1 ,15301   ,484,484,484
BEGIN DESCRIPTION:
Upper Denton 47 32.0
END DESCRIPTION:
XS GIS Cut Line= 3
      2197458.87      7271699.24        2196229.        7270760.
      2195045.64      7270570.76
#Sta/Elev= 30
  3452.1 1082.19  3651.9 1081.01  4113.5 1069.53  4265.1 1066.56  4628.7 1064.85
  4678.5 1059.78  4749.2 1041.16  4828.2 1035.41    4836 1037.69  4857.2 1035.08
    4957 1035.43  4992.4    1029  4993.6  1028.5  5000.5    1029  5050.2 1033.32
  5242.7 1033.15  5404.7 1036.53  5445.2 1038.21  5465.4 1041.54  5477.6 1039.06
  5566.7  1044.1  5601.7 1052.36  5647.7 1051.33  5663.7 1056.09  5668.8 1050.82
  5688.2 1050.76  5725.8 1055.71  5769.3 1056.88  5984.1 1071.63    6198 1072.19
#Mann= 5 ,-1 , 0
  3452.1     .05       0  4113.5     .12       0  4265.1     .05       0
  4992.4    .033       0  5000.5     .05       0
Bank Sta=4992.4,5000.5
XS Rating Curve= 0 ,0
Exp/Cntr=0.3,0.1

Type RM Length L Ch R = 1 ,14817   ,461,461,461
BEGIN DESCRIPTION:
Upper Denton 47 31.0
END DESCRIPTION:
XS GIS Cut Line= 3
      2197311.29      7270996.11        2196329.        7270310.
      2195602.63      7269920.48
#Sta/Elev= 30
  3797.6 1068.64  4076.9 1064.41    4336 1049.99  4398.7 1052.12  4422.3 1049.87
  4434.7 1050.66  4449.3 1054.99  4458.1 1054.36    4479 1044.81  4544.4 1041.01
  4800.8 1031.32  4959.2 1032.23  4988.4 1029.31  4988.6 1027.43  4989.8 1026.93
  4996.8 1027.43  5031.5 1031.51  5157.4 1031.02  5261.4 1035.86  5283.3 1039.38
  5299.5 1038.61  5336.2 1043.53  5358.9 1050.09    5371 1049.44  5381.6  1051.2
  5392.9 1057.36  5415.6 1061.21  5506.4 1065.66  5704.8 1067.95    5820 1072.67
#Mann= 3 ,-1 , 0
  3797.6     .05       0  4988.6    .033       0  4996.8     .05       0
Bank Sta=4988.6,4996.8
XS Rating Curve= 0 ,0
Exp/Cntr=0.3,0.1

Type RM Length L Ch R = 1 ,14356   ,458,458,458
BEGIN DESCRIPTION:
Upper Denton 47 30.0
END DESCRIPTION:
XS GIS Cut Line= 3
      2197154.97      7270556.08        2196479.        7269910.
      2195683.46      7269695.16
#Sta/Elev= 30
  4065.5 1062.94  4123.6    1063  4208.5 1055.86  4215.4 1057.61  4236.8 1055.62
  4300.3 1056.84  4356.9 1055.24  4385.2 1050.38  4434.6 1048.78  4505.4 1034.33
  4555.1 1034.55    4562 1039.84  4576.1 1040.29  4604.4 1033.76  4646.9 1031.75
  4866.1 1027.75  5003.2 1028.59  5006.8 1024.58    5008 1024.08  5015.1 1024.58
  5052.4 1029.11    5207 1027.46  5326.7 1031.42  5383.8 1037.21  5394.2 1036.17
  5441.2 1041.34  5528.8 1046.92  5539.2 1045.65  5630.3 1054.22  5824.6 1067.31
#Mann= 3 ,-1 , 0
  4065.5     .05       0  5006.8    .033       0  5015.1     .05       0
Bank Sta=5006.8,5015.1
XS Rating Curve= 0 ,0
Exp/Cntr=0.3,0.1

Type RM Length L Ch R = 1 ,13898   ,472,472,472
BEGIN DESCRIPTION:
Upper Denton 47 29.0
END DESCRIPTION:
XS GIS Cut Line= 3
      2197592.49      7270431.09        2196329.        7269510.
      2195689.68      7269375.52
#Sta/Elev= 30
  3435.9 1066.78  3588.7 1059.72  3638.7 1061.37  3811.5 1054.91  4046.6 1037.81
  4069.7 1041.01  4211.9 1032.98  4519.4 1026.83    4806 1027.41  4820.6 1025.43
  4841.5 1028.06  4870.9 1023.64    4877 1027.97  4885.5 1025.49  4891.7 1027.92
  4912.9 1027.67  4921.1 1024.77  4927.3 1027.65    4950 1027.49    4986 1022.22
  4992.2 1024.21  5020.2 1021.78  5021.5 1021.28  5028.6 1021.78  5040.4 1026.53
  5142.6 1030.78  5213.5 1041.78  5295.8 1037.18    5363  1052.8  5652.8 1067.78
#Mann= 3 ,-1 , 0
  3435.9     .05       0  5020.2    .033       0  5028.6     .05       0
Bank Sta=5020.2,5028.6
XS Rating Curve= 0 ,0
Exp/Cntr=0.3,0.1