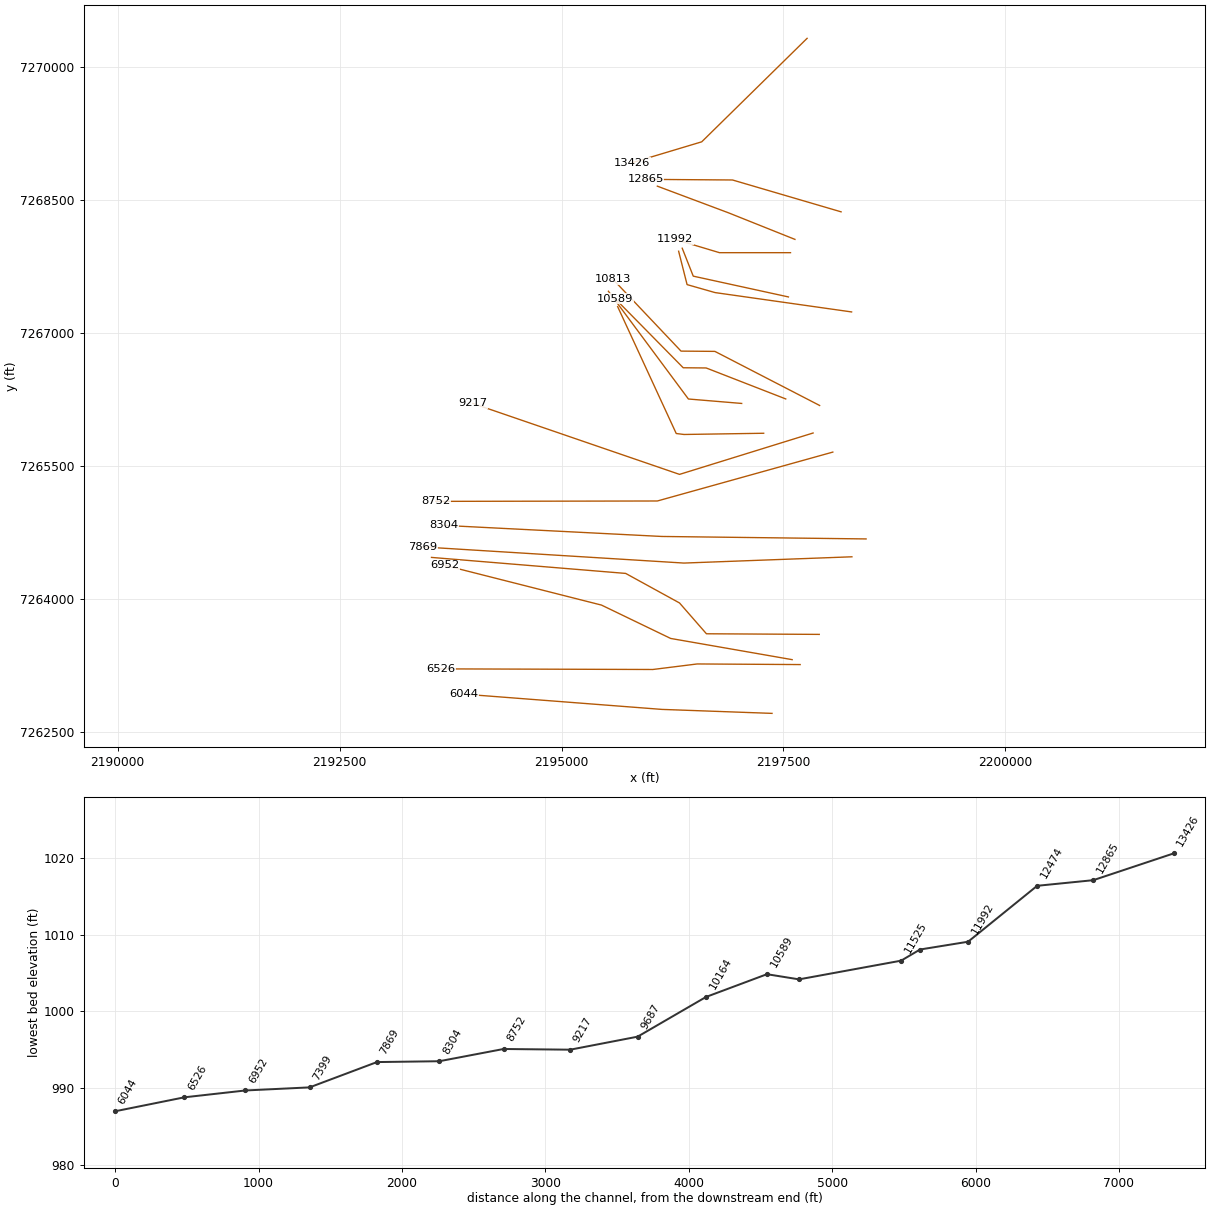
HEC-RAS study Upper Denton 47.prj: Upper Denton 47 Base Level Engineering

--- Upper Denton 47.g01 (geometry) --- (continued)

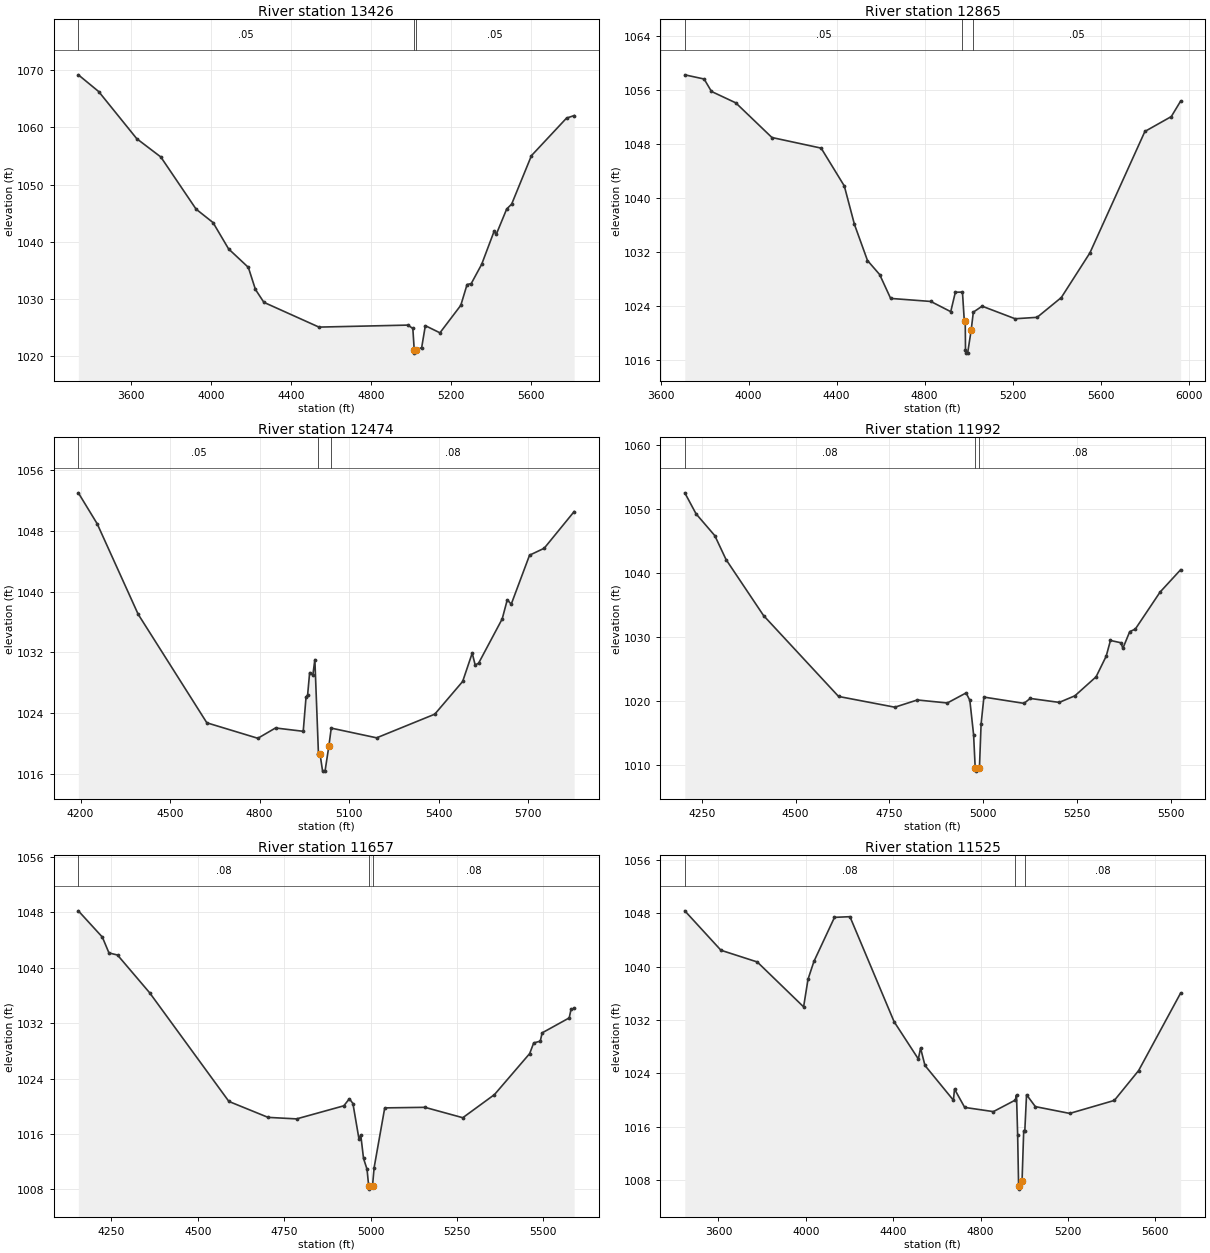
Type RM Length L Ch R = 1 ,13426   ,561,561,561
BEGIN DESCRIPTION:
Upper Denton 47 28.0
END DESCRIPTION:
XS GIS Cut Line= 3
      2197766.06      7270326.89        2196579.        7269160.
      2195795.35      7268924.58
#Sta/Elev= 30
  3335.7 1069.19  3437.5 1066.27  3628.4 1058.02  3748.7 1054.83  3925.4 1045.71
  4010.3 1043.36  4088.1 1038.76    4187 1035.53  4222.4 1031.68  4264.8 1029.42
  4540.6 1025.09  4986.2 1025.44  5010.7 1024.85  5017.8 1021.04    5019 1020.54
  5026.2 1021.04    5055 1021.52  5073.3 1025.34  5146.4 1024.09  5250.9  1028.9
  5282.2 1032.53  5303.1  1032.7  5355.3 1036.06  5417.9 1041.86  5428.4  1041.3
  5480.6 1045.73  5505.5 1046.59  5604.6 1055.06  5780.2 1061.62  5818.5 1062.07
#Mann= 3 ,-1 , 0
  3335.7     .05       0  5017.8    .033       0  5026.2     .05       0
Bank Sta=5017.8,5026.2
XS Rating Curve= 0 ,0
Exp/Cntr=0.3,0.1

Type RM Length L Ch R = 1 ,12865   ,391,391,391
BEGIN DESCRIPTION:
Upper Denton 47 27.0
END DESCRIPTION:
XS GIS Cut Line= 3
      2198149.06      7268370.48       2196925.8      7268729.69
      2195946.63      7268736.63
#Sta/Elev= 30
  3709.6 1058.26  3797.4 1057.64  3830.8  1055.8  3941.4 1054.11  4105.7 1048.98
  4329.4 1047.41  4434.7 1041.81  4480.9 1036.11  4540.1 1030.77  4595.5 1028.69
  4645.4 1025.16    4828 1024.71  4918.6  1023.2  4939.5 1026.07  4971.9  1026.1
  4980.2 1021.86  4984.5 1021.86  4985.7 1017.56  4987.2 1017.06  4995.4 1017.06
  5011.3 1020.41  5021.3 1023.13  5061.3 1024.01  5211.3 1022.15  5311.3 1022.36
  5421.3 1025.29  5551.3  1031.9  5801.3 1049.88  5921.3 1052.08  5963.7 1054.37
#Mann= 3 ,-1 , 0
  3709.6     .05       0  4971.9    .033       0  5021.3     .05       0
Bank Sta=4984.5,5011.3
XS Rating Curve= 0 ,0
Exp/Cntr=0.3,0.1

Type RM Length L Ch R = 1 ,12474   ,482,482,482
BEGIN DESCRIPTION:
Upper Denton 47 26.0
END DESCRIPTION:
XS GIS Cut Line= 3
      2197628.97      7268060.01        2196879.        7268360.
      2196079.04      7268659.99
#Sta/Elev= 30
  4192.6 1053.02  4255.8 1048.94  4393.2 1037.01  4623.4  1022.7  4794.4 1020.66
  4853.6 1022.02  4946.5 1021.58  4955.9 1026.09  4961.3  1026.4    4968 1029.32
  4978.8    1029  4985.5 1031.04  4997.6 1018.54    5003 1018.54  5011.4 1016.33
  5019.6 1016.33  5032.4 1019.62  5040.4    1022  5192.6 1020.72  5387.5 1023.84
  5480.9 1028.15    5513 1031.89  5522.8 1030.33  5534.3 1030.55  5613.5  1036.4
  5630.5 1038.92  5643.8 1038.34  5705.2  1044.8  5754.2 1045.71  5854.7 1050.55
#Mann= 3 ,-1 , 0
  4192.6     .05       0  4997.6    .033       0  5040.4     .08       0
Bank Sta=5003,5032.4
XS Rating Curve= 0 ,0
Exp/Cntr=0.3,0.1

Type RM Length L Ch R = 1 ,11992   ,335,335,335
BEGIN DESCRIPTION:
Upper Denton 47 25.0
END DESCRIPTION:
XS GIS Cut Line= 3
      2197578.97        7267910.        2196779.        7267910.
      2196278.99        7268060.
#Sta/Elev= 30
  4204.6 1052.55  4234.6 1049.27  4284.6 1045.86  4314.6 1042.12  4414.6 1033.37
  4614.6 1020.73  4764.6 1019.05  4824.6 1020.18  4904.6 1019.71  4954.6 1021.28
  4964.6 1020.12  4974.6 1014.77  4978.9 1009.56  4980.5 1009.06  4990.2 1009.56
  4994.6 1016.42  5002.1 1020.63    5109 1019.65  5125.5 1020.42  5202.9  1019.8
  5244.7 1020.83  5301.2  1023.8  5328.2 1027.03  5339.5 1029.48  5367.4 1029.12
  5372.6 1028.25  5390.9 1030.86  5405.7 1031.25  5471.8 1037.04  5526.6 1040.53
#Mann= 3 ,-1 , 0
  4204.6     .08       0  4978.9    .033       0  4990.2     .08       0
Bank Sta=4978.9,4990.2
XS Rating Curve= 0 ,0
Exp/Cntr=0.3,0.1

Type RM Length L Ch R = 1 ,11657   ,132,132,132
BEGIN DESCRIPTION:
Upper Denton 47 24.5
END DESCRIPTION:
XS GIS Cut Line= 3
      2197555.61      7267410.97      2196483.53      7267645.36
      2196359.38      7267959.83
#Sta/Elev= 30
  4154.1 1048.23  4223.6 1044.44  4242.8 1042.15  4267.5 1041.85  4360.4 1036.41
    4590 1020.71  4703.4 1018.41    4786 1018.19  4922.8 1020.08  4938.8  1021.1
  4949.1 1020.41  4966.7 1015.26  4971.8 1015.86  4979.8 1012.48    4990 1010.91
  4994.6 1008.55  4996.1 1008.05  5005.9 1008.55  5010.5 1011.16  5041.2 1019.78
  5157.5 1019.86  5267.2 1018.36  5358.9  1021.7  5460.8 1027.62  5472.5 1029.16
  5491.5 1029.41  5496.9 1030.61  5575.3 1032.77  5580.7 1034.04  5589.6 1034.14
#Mann= 3 , 0 , 0
  4154.1     .08       0  4994.6    .033       0  5005.9     .08       0
Bank Sta=4994.6,5005.9
XS Rating Curve= 0 ,0
Exp/Cntr=0.3,0.1

Type RM Length L Ch R = 1 ,11525   ,712,712,712
BEGIN DESCRIPTION:
Upper Denton 47 24.0
END DESCRIPTION:
XS GIS Cut Line= 4
      2198267.37      7267241.71        2196729.        7267460.
      2196414.08      7267549.87       2196318.9      7267926.26
#Sta/Elev= 30
  3445.8 1048.39  3611.2 1042.47  3777.5 1040.71  3989.6 1033.97  4009.8 1038.11
  4036.8 1040.79    4131 1047.41  4201.7 1047.51  4403.7 1031.75  4514.8 1026.14
  4524.9 1027.78  4545.1 1025.17  4675.3 1019.95  4680.3 1021.63  4726.9 1018.87
  4858.2 1018.24  4959.1 1019.98  4964.1 1020.74  4969.3 1014.74  4973.7  1007.1
  4975.3  1006.6  4989.5 1007.83  4997.1  1015.4  5002.2  1015.4    5010 1020.78
  5050.3 1018.99  5207.6 1017.97  5411.9 1019.92  5523.2 1024.41  5715.3 1036.04
#Mann= 3 ,-1 , 0
  3445.8     .08       0  4959.1    .033       0  5002.2     .08       0
Bank Sta=4973.7,4989.5
XS Rating Curve= 0 ,0
Exp/Cntr=0.3,0.1

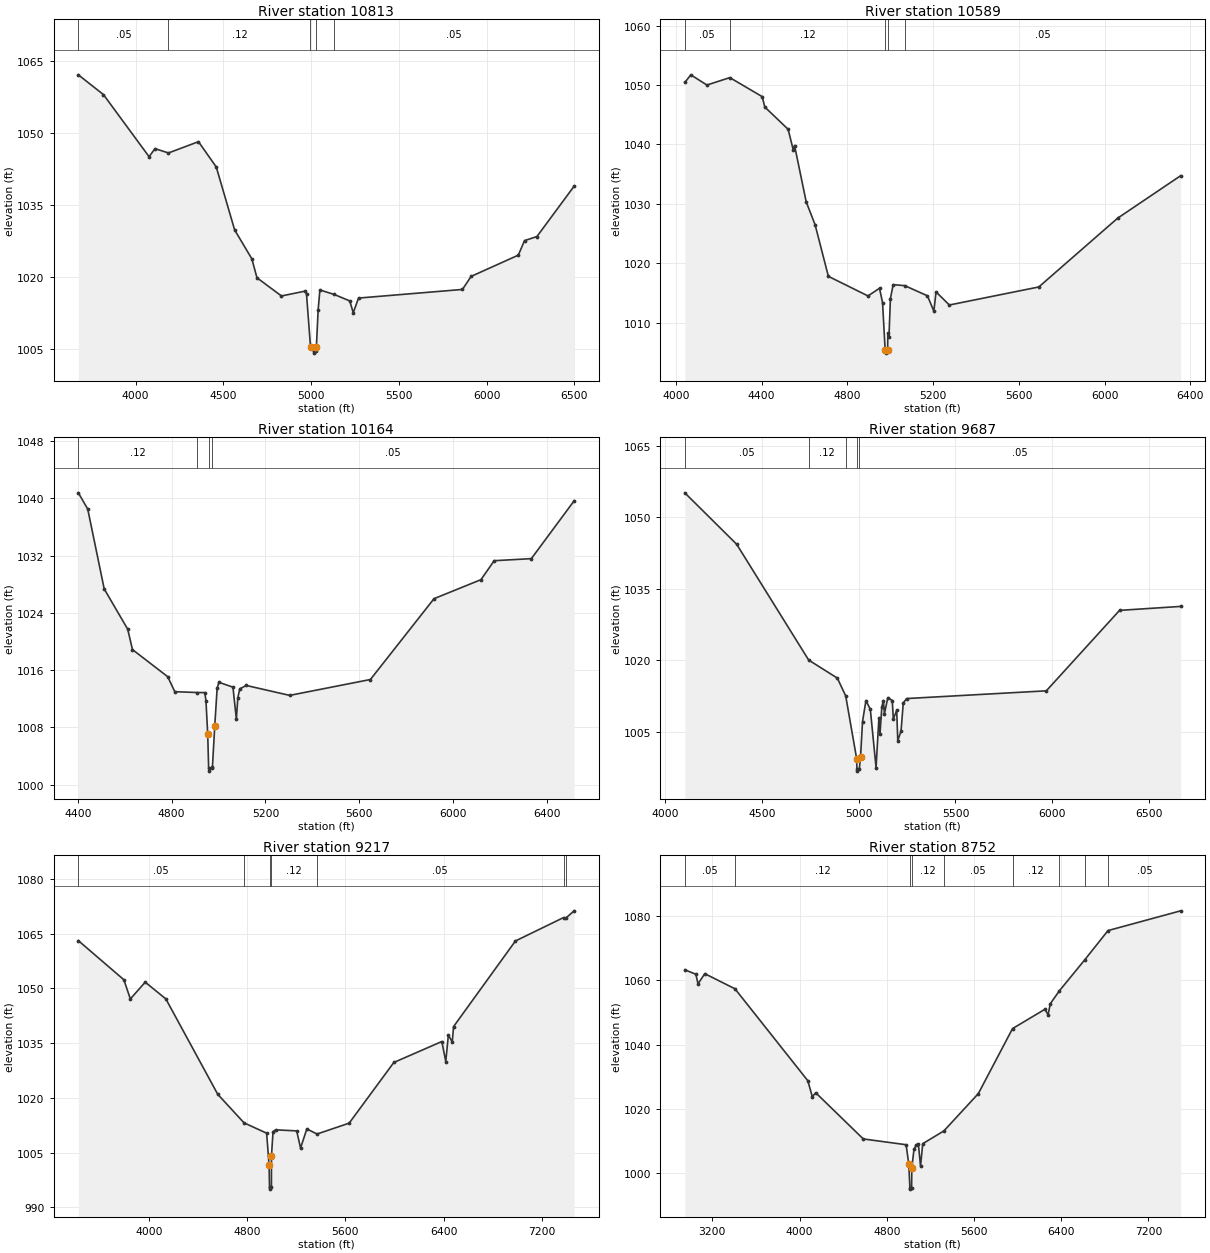
Type RM Length L Ch R = 1 ,10813   ,224,224,224
BEGIN DESCRIPTION:
Upper Denton 47 23.0
END DESCRIPTION:
XS GIS Cut Line= 4
       2197907.1      7266187.04       2196727.3      7266796.92
      2196345.76        7266800.      2195579.02      7267609.98
#Sta/Elev= 30
  3673.9  1062.2  3817.2 1058.07    4077 1045.13  4110.8 1046.81  4187.5 1045.91
  4358.4 1048.26  4459.8 1042.98  4564.5 1029.86  4662.4 1023.84  4691.7 1019.88
  4831.2 1016.09  4966.3  1017.1    4974 1016.47  4996.2 1005.79    5002 1005.52
  5016.2 1004.17  5026.1 1004.67  5030.3 1005.52  5040.3 1013.23  5050.3 1017.34
  5131.5 1016.41  5220.3 1015.06  5240.3  1012.6  5270.3 1015.65  5862.4 1017.45
  5911.8 1020.17  6180.8  1024.6    6216 1027.63  6286.7 1028.48  6498.9 1038.99
#Mann= 5 ,-1 , 0
  3673.9     .05       0  4187.5     .12       0  4996.2     .03       0
  5026.1     .12       0  5131.5     .05       0
Bank Sta=5002,5030.3
XS Rating Curve= 0 ,0
Exp/Cntr=0.3,0.1

Type RM Length L Ch R = 1 ,10589   ,425,425,425
BEGIN DESCRIPTION:
Upper Denton 47 22.0
END DESCRIPTION:
XS GIS Cut Line= 4
       2197525.2       7266260.8        2196629.        7266610.
      2196370.38      7266612.31      2195604.23      7267390.76
#Sta/Elev= 30
  4042.1 1050.45  4070.2 1051.74  4145.3 1050.02  4252.1 1051.27  4402.9 1048.07
  4415.4 1046.31  4524.1 1042.56  4548.6 1038.99    4554 1039.83  4608.4 1030.33
  4649.8 1026.49  4711.8 1017.78  4896.6 1014.48  4950.3 1015.77  4964.5 1013.36
  4976.7 1005.34  4978.3 1004.84  4988.2 1005.34    4989 1008.26  4994.4 1007.59
  5001.2 1014.03  5013.9 1016.38  5068.3 1016.21  5173.9  1014.5  5203.9 1011.91
  5213.9 1015.16    5276 1012.95  5693.3 1015.99  6060.9 1027.58  6354.8 1034.74
#Mann= 5 ,-1 , 0
  4042.1     .05       0  4252.1     .12       0  4976.7     .07       0
  4988.2     .12       0  5068.3     .05       0
Bank Sta=4976.7,4988.2
XS Rating Curve= 0 ,0
Exp/Cntr=0.3,0.1

Type RM Length L Ch R = 1 ,10164   ,477,477,477
BEGIN DESCRIPTION:
Upper Denton 47 21.0
END DESCRIPTION:
XS GIS Cut Line= 3
        2197029.        7266210.        2196429.        7266260.
      2195527.85      7267475.13
#Sta/Elev= 30
  4402.1 1040.79  4442.2 1038.52  4512.5 1027.35  4612.8 1021.72  4632.9 1018.88
  4783.4 1015.08  4813.5 1012.99  4909.8 1012.87  4941.5 1012.86  4946.5 1011.72
    4954 1007.03  4957.9 1002.38  4959.6 1001.88  4970.2 1002.38  4974.1 1002.49
  4984.1 1008.25  4994.1 1013.44  5001.7  1014.3  5061.6 1013.62  5076.2 1009.14
  5082.4 1012.16  5090.8 1013.38  5117.9 1013.86  5303.6 1012.47  5647.9 1014.69
  5919.2 1025.99  6119.5 1028.65  6175.8  1031.3  6334.4 1031.59    6517 1039.68
#Mann= 4 ,-1 , 0
  4402.1     .12       0  4909.8     .05       0  4957.9    .035       0
  4970.2     .05       0
Bank Sta=4954,4984.1
XS Rating Curve= 0 ,0
Exp/Cntr=0.3,0.1

Type RM Length L Ch R = 1 ,9687    ,470,470,470
BEGIN DESCRIPTION:
Upper Denton 47 20.0
END DESCRIPTION:
XS GIS Cut Line= 4
      2197276.88      7265873.71        2196379.        7265860.
      2196291.82       7265870.9      2195631.89       7267301.7
#Sta/Elev= 30
  4101.7 1055.08  4369.6  1044.3  4741.7 1020.01  4889.7 1016.23    4933 1012.49
  4989.7   999.3    4991  997.22  4992.7  996.72  5003.3  997.22  5009.8  999.74
  5019.8 1007.12  5037.5  1011.5  5060.1  1009.7  5089.8  997.47  5104.6 1007.92
  5110.1 1004.51  5119.6 1010.19  5127.6 1011.51  5133.1 1008.77  5150.5 1012.13
  5173.5 1011.53    5179 1007.66  5196.4 1009.46    5202 1003.11  5218.7  1005.1
  5230.4 1011.02  5247.9 1011.94  5969.4 1013.56  6347.6 1030.43  6663.2 1031.26
#Mann= 5 ,-1 , 0
  4101.7     .05       0  4741.7     .12       0    4933     .05       0
    4991    .033       0  5003.3     .05       0
Bank Sta=4989.7,5009.8
XS Rating Curve= 0 ,0
Exp/Cntr=0.3,0.1

Type RM Length L Ch R = 1 ,9217    ,465,465,465
BEGIN DESCRIPTION:
Upper Denton 47 19.0
END DESCRIPTION:
XS GIS Cut Line= 3
      2197833.48      7265876.58        2196329.        7265410.
      2194000.12      7266209.91
#Sta/Elev= 30
  3425.3 1063.07  3796.4 1052.35  3848.8  1047.1    3970  1051.7  4138.1 1047.11
  4560.7 1020.99  4774.6 1013.18  4958.6 1010.35  4978.9 1001.53  4982.1  995.53
  4984.1  995.03  4997.8  995.53  4997.9 1004.06  5010.8 1010.77  5032.2 1011.26
  5203.6 1010.98  5234.9 1006.28    5286 1011.51    5369 1010.12  5630.6 1013.09
  5994.4 1029.71  6385.6 1035.45  6417.3 1029.96  6438.5 1037.19  6470.2 1035.33
  6480.8 1039.53  6984.5 1062.97  7376.3 1069.38  7393.5  1069.2  7462.9 1071.23
#Mann= 7 ,-1 , 0
  3425.3     .05       0  4774.6     .12       0  4982.1     .07       0
  4997.8     .12       0    5369     .05       0  7376.3     .12       0
  7393.5     .05       0
Bank Sta=4978.9,4997.9
XS Rating Curve= 0 ,0
Exp/Cntr=0.3,0.1

Type RM Length L Ch R = 1 ,8752    ,448,448,448
BEGIN DESCRIPTION:
Upper Denton 47 18.0
END DESCRIPTION:
XS GIS Cut Line= 3
      2198055.67      7265661.29        2196079.        7265110.
      2193583.71      7265105.74
#Sta/Elev= 30
  2947.7 1063.25  3049.4 1061.86  3068.8 1058.89  3131.1 1062.04  3407.7 1057.35
  4075.8  1028.8  4117.4 1023.81  4148.5 1025.06  4584.5 1010.71  4977.5 1008.91
  5002.3 1002.79  5011.9  995.62  5013.9  995.12  5027.8  995.62  5029.8 1001.77
  5049.8 1007.48  5069.8 1008.82  5089.8 1009.22  5109.8 1002.24  5129.8 1009.23
  5324.5 1013.22  5639.8 1024.79  5953.4 1044.98  6249.8 1050.97  6279.8  1049.3
  6299.8  1052.7  6382.4 1056.69  6614.8  1066.3  6829.2 1075.43  7495.1 1081.56
#Mann= 9 ,-1 , 0
  2947.7     .05       0  3407.7     .12       0  5011.9     .07       0
  5027.8     .12       0  5324.5     .05       0  5953.4     .12       0
  6382.4     .05       0  6614.8     .12       0  6829.2     .05       0
Bank Sta=5002.3,5029.8
XS Rating Curve= 0 ,0
Exp/Cntr=0.3,0.1

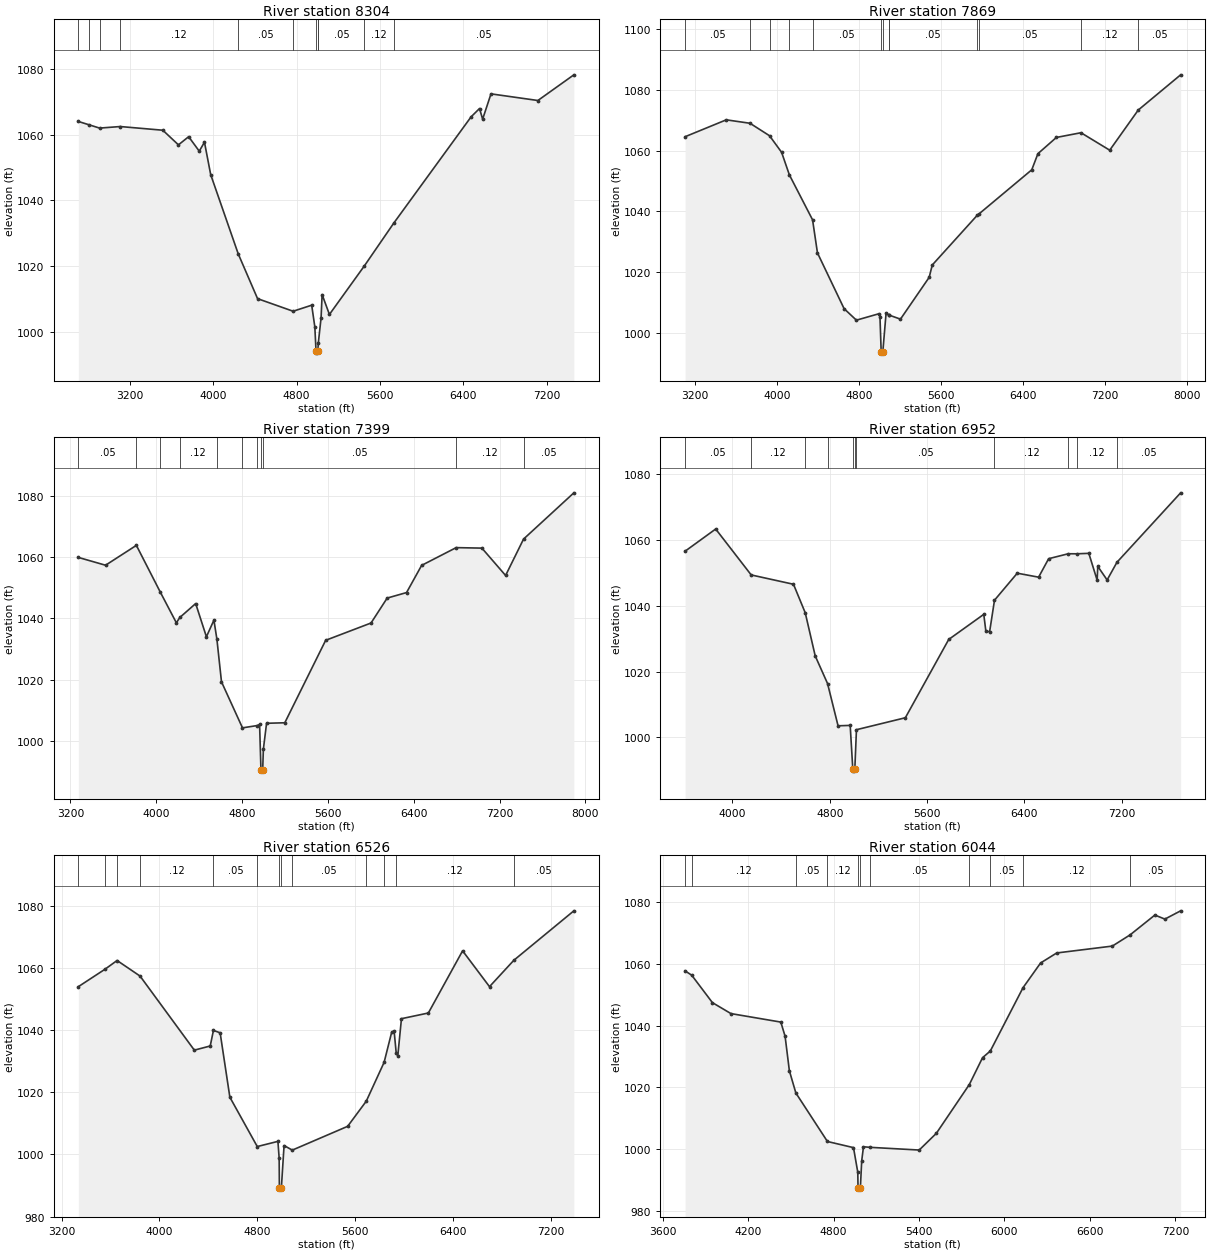
Type RM Length L Ch R = 1 ,8304    ,435,435,435
BEGIN DESCRIPTION:
Upper Denton 47 17.0
END DESCRIPTION:
XS GIS Cut Line= 3
      2198430.65      7264682.13        2196129.        7264710.
      2193673.89       7264834.9
#Sta/Elev= 30
  2702.7    1064  2807.8 1062.96    2907 1061.98  3105.4 1062.45  3514.4 1061.33
  3664.4 1056.88  3762.6 1059.36  3864.4 1054.96  3914.4 1057.69  3974.4 1047.81
  4238.8 1023.72  4424.5  1010.1    4766 1006.27  4944.5 1008.11  4974.5 1001.53
  4986.5  994.03  4988.5  993.53  5002.6  994.03  5008.4  996.68  5034.6 1004.25
  5044.6 1011.34  5114.7 1005.29  5451.6 1020.12  5732.4 1033.06  6476.1 1065.42
  6556.5 1067.93  6586.6  1064.7  6666.7 1072.39  7117.2 1070.37  7462.8 1078.18
#Mann= 11 ,-1 , 0
  2702.7     .05       0  2807.8     .12       0    2907     .05       0
  3105.4     .12       0  4238.8     .05       0    4766     .12       0
  4986.5     .07       0  5002.6     .12       0  5008.4     .05       0
  5451.6     .12       0  5732.4     .05       0
Bank Sta=4986.5,5002.6
XS Rating Curve= 0 ,0
Exp/Cntr=0.3,0.1

Type RM Length L Ch R = 1 ,7869    ,470,470,470
BEGIN DESCRIPTION:
Upper Denton 47 16.0
END DESCRIPTION:
XS GIS Cut Line= 3
      2198270.99      7264480.74        2196379.        7264410.
      2193437.63      7264591.85
#Sta/Elev= 30
  3102.3 1064.54  3504.6 1070.09  3736.4 1068.96  3927.1 1064.86  4044.9 1059.42
  4120.9    1052  4347.4 1037.23  4395.2 1026.36  4655.4 1008.03  4775.5 1004.25
  4998.1 1006.39  5005.6  1005.4  5017.6  993.92  5019.6  993.42  5033.8  993.92
  5065.7 1006.66  5094.9 1005.92  5095.5 1005.91    5206 1004.59  5486.5 1018.33
  5516.6 1022.38  5954.2 1038.66    5973 1039.17  6488.5 1053.67  6548.6 1058.97
  6728.9  1064.3  6969.2 1065.85  7249.9 1060.11  7528.4  1073.3  7942.6 1084.88
#Mann= 13 ,-1 , 0
  3102.3     .05       0  3736.4     .12       0  3927.1     .05       0
  4120.9     .12       0  4347.4     .05       0  5017.6    .033       0
  5033.8     .05       0  5094.9     .12       0  5095.5     .05       0
  5954.2     .12       0    5973     .05       0  6969.2     .12       0
  7528.4     .05       0
Bank Sta=5017.6,5033.8
XS Rating Curve= 0 ,0
Exp/Cntr=0.3,0.1

Type RM Length L Ch R = 1 ,7399    ,447,447,447
BEGIN DESCRIPTION:
Upper Denton 47 15.0
END DESCRIPTION:
XS GIS Cut Line= 5
       2197902.9      7263605.74      2196632.08      7263612.68
        2196329.        7263960.      2195722.36      7264293.24
      2193534.84      7264473.79
#Sta/Elev= 30
  3272.9 1059.82  3526.8 1057.27    3814 1063.75  4035.9 1048.58  4186.8  1038.5
  4218.8 1040.23  4366.8 1044.77  4466.8 1033.94  4536.8 1039.37  4564.6 1033.15
  4607.4 1019.25  4803.1 1004.24  4941.8    1005  4962.5 1005.35  4975.2  990.63
  4977.2  990.13  4991.5  990.63  4997.6  997.24  5027.5 1005.73  5197.5  1005.9
  5578.4 1032.79  6001.2 1038.43  6151.7 1046.56  6332.4 1048.36  6472.8 1057.22
  6794.8 1063.01  7034.7 1062.85  7255.5 1053.93  7422.9  1065.8  7891.8 1080.88
#Mann= 11 ,-1 , 0
  3272.9     .05       0    3814     .12       0  4035.9     .05       0
  4218.8     .12       0  4564.6     .05       0  4803.1     .12       0
  4941.8     .05       0  4975.2    .033       0  4991.5     .05       0
  6794.8     .12       0  7422.9     .05       0
Bank Sta=4975.2,4991.5
XS Rating Curve= 0 ,0
Exp/Cntr=0.3,0.1

Type RM Length L Ch R = 1 ,6952    ,426,426,426
BEGIN DESCRIPTION:
Upper Denton 47 14.0
END DESCRIPTION:
XS GIS Cut Line= 4
       2197597.4      7263321.01        2196229.        7263560.
      2195450.09      7263936.11      2193687.67      7264383.51
#Sta/Elev= 30
  3611.1 1056.64  3862.5 1063.39  4154.3 1049.42  4501.9 1046.58  4598.5  1037.9
  4680.5 1024.78  4781.9 1016.37  4868.2 1003.52  4967.9 1003.64  4989.5  990.23
  4991.5  989.73  5005.8  990.23  5019.3 1002.33  5421.2 1005.97  5777.6 1029.79
  6065.7 1037.43    6083 1032.26  6113.9 1032.18  6153.8 1041.73  6340.9 1049.95
  6516.3 1048.74  6598.8 1054.36  6759.9 1055.86  6827.8 1055.85    6929 1055.99
  6997.3 1047.83  7002.5 1052.03  7079.3 1047.89  7160.1 1053.27  7683.5  1074.4
#Mann= 11 ,-1 , 0
  3611.1     .05       0  4154.3     .12       0  4598.5     .05       0
  4781.9     .12       0  4989.5     .07       0  5005.8     .12       0
  5019.3     .05       0  6153.8     .12       0  6759.9     .05       0
  6827.8     .12       0  7160.1     .05       0
Bank Sta=4989.5,5005.8
XS Rating Curve= 0 ,0
Exp/Cntr=0.3,0.1

Type RM Length L Ch R = 1 ,6526    ,482,482,482
BEGIN DESCRIPTION:
Upper Denton 47 13.0
END DESCRIPTION:
XS GIS Cut Line= 4
      2197687.64      7263265.46      2196527.91       7263272.4
        2196029.        7263210.      2193639.06      7263216.85
#Sta/Elev= 30
    3337 1054.08  3554.9  1059.7    3654 1062.52  3841.9  1057.5  4285.7 1033.63
  4415.7 1034.97    4442 1039.99  4496.8 1039.22  4576.3 1018.46  4800.4 1002.56
  4969.3 1004.23  4979.4  998.82  4981.3  989.34  4983.3  988.84  4997.6  989.34
  5019.6 1002.89  5086.8 1001.41  5539.6 1009.08  5691.9 1017.19  5837.7  1029.7
  5899.6 1039.41  5919.6 1039.78  5936.8 1032.66  5949.6 1031.82  5979.6 1043.77
  6199.6  1045.6  6479.6 1065.64  6699.6 1054.09  6898.8  1062.6  7389.5 1078.53
#Mann= 13 ,-1 , 0
    3337     .05       0  3554.9      .1       0    3654     .05       0
  3841.9     .12       0    4442     .05       0  4800.4     .12       0
  4981.3     .07       0  4997.6     .12       0  5086.8     .05       0
  5691.9     .12       0  5837.7     .05       0  5936.8     .12       0
  6898.8     .05       0
Bank Sta=4981.3,4997.6
XS Rating Curve= 0 ,0
Exp/Cntr=0.3,0.1

Type RM Length L Ch R = 1 ,6044    ,481,481,481
BEGIN DESCRIPTION:
Upper Denton 47 12.0
END DESCRIPTION:
XS GIS Cut Line= 3
      2197370.77      7262715.11        2196129.        7262760.
      2193898.61      7262932.12
#Sta/Elev= 30
  3757.5 1057.72    3804 1056.33  3949.4 1047.44  4079.5 1043.89  4429.7 1041.14
  4459.7 1036.54  4489.7 1025.38  4535.3 1018.17    4757 1002.46    4940 1000.47
  4970.1   992.5  4971.8  987.53  4973.8  987.03  4988.4  987.53  4997.6   996.2
  5010.1 1000.75  5056.8 1000.57  5401.3  999.69  5521.6  1005.1  5753.4 1020.92
  5846.2 1029.61  5900.7 1031.77  6130.4 1052.28  6253.8 1060.29  6366.9 1063.53
  6757.5 1065.76    6882 1069.38  7056.2 1075.81  7126.4  1074.5  7237.1 1077.18
#Mann= 11 ,-1 , 0
  3757.5     .05       0    3804     .12       0  4535.3     .05       0
    4757     .12       0  4971.8     .07       0  4988.4     .12       0
  5056.8     .05       0  5753.4     .12       0  5900.7     .05       0
  6130.4     .12       0    6882     .05       0
Bank Sta=4971.8,4988.4
XS Rating Curve= 0 ,0
Exp/Cntr=0.3,0.1