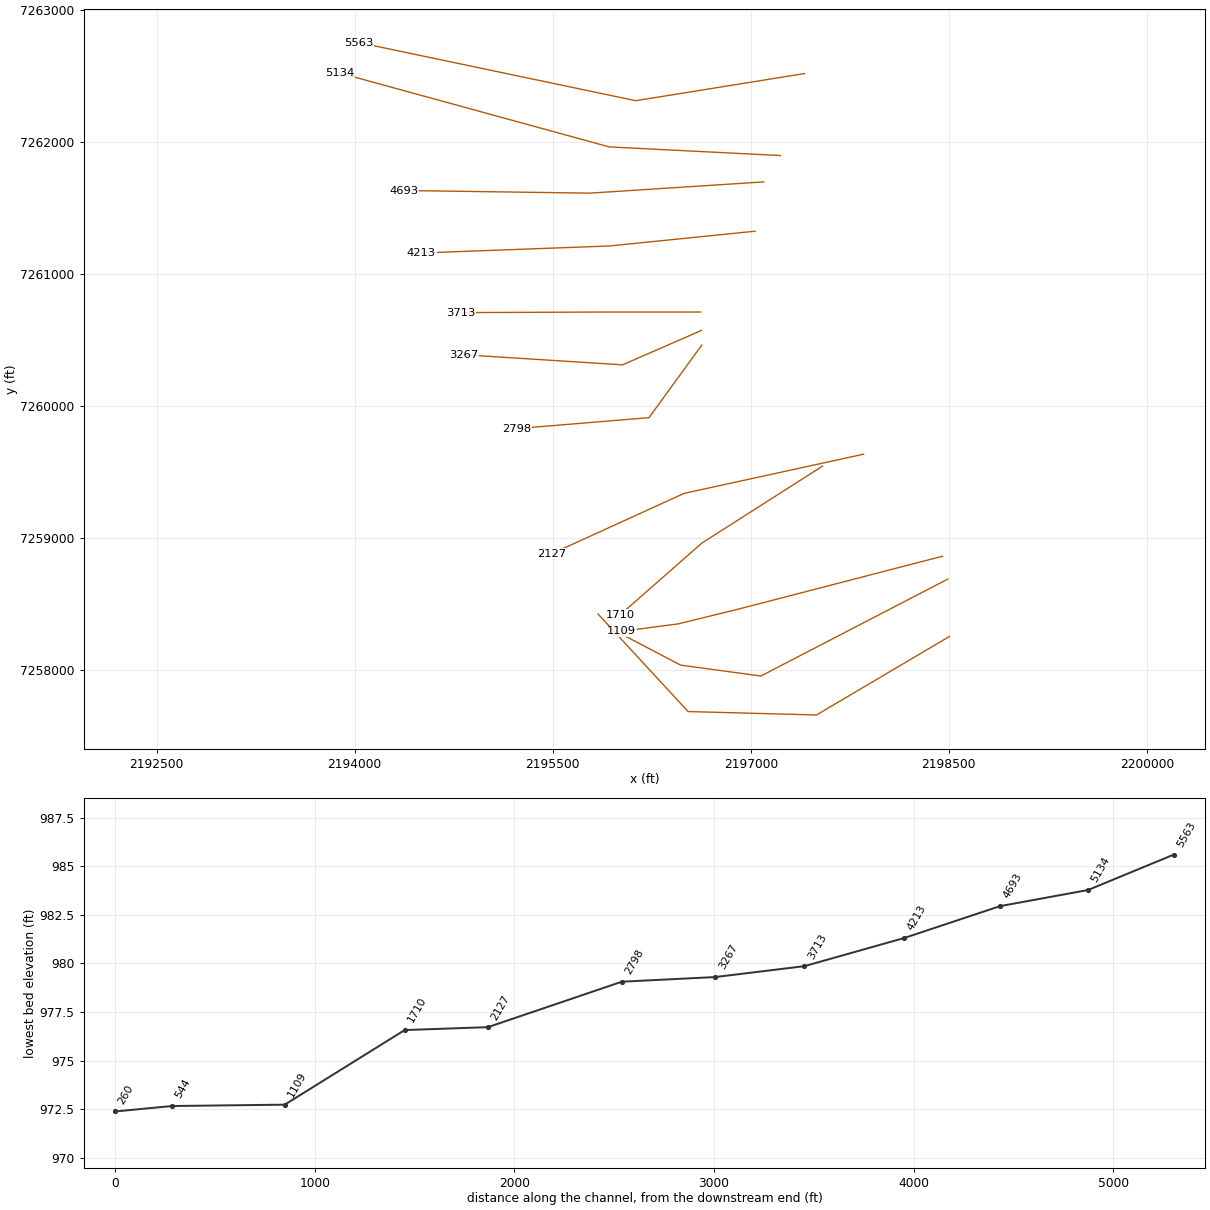
HEC-RAS study Upper Denton 47.prj: Upper Denton 47 Base Level Engineering

--- Upper Denton 47.g01 (geometry) --- (continued)

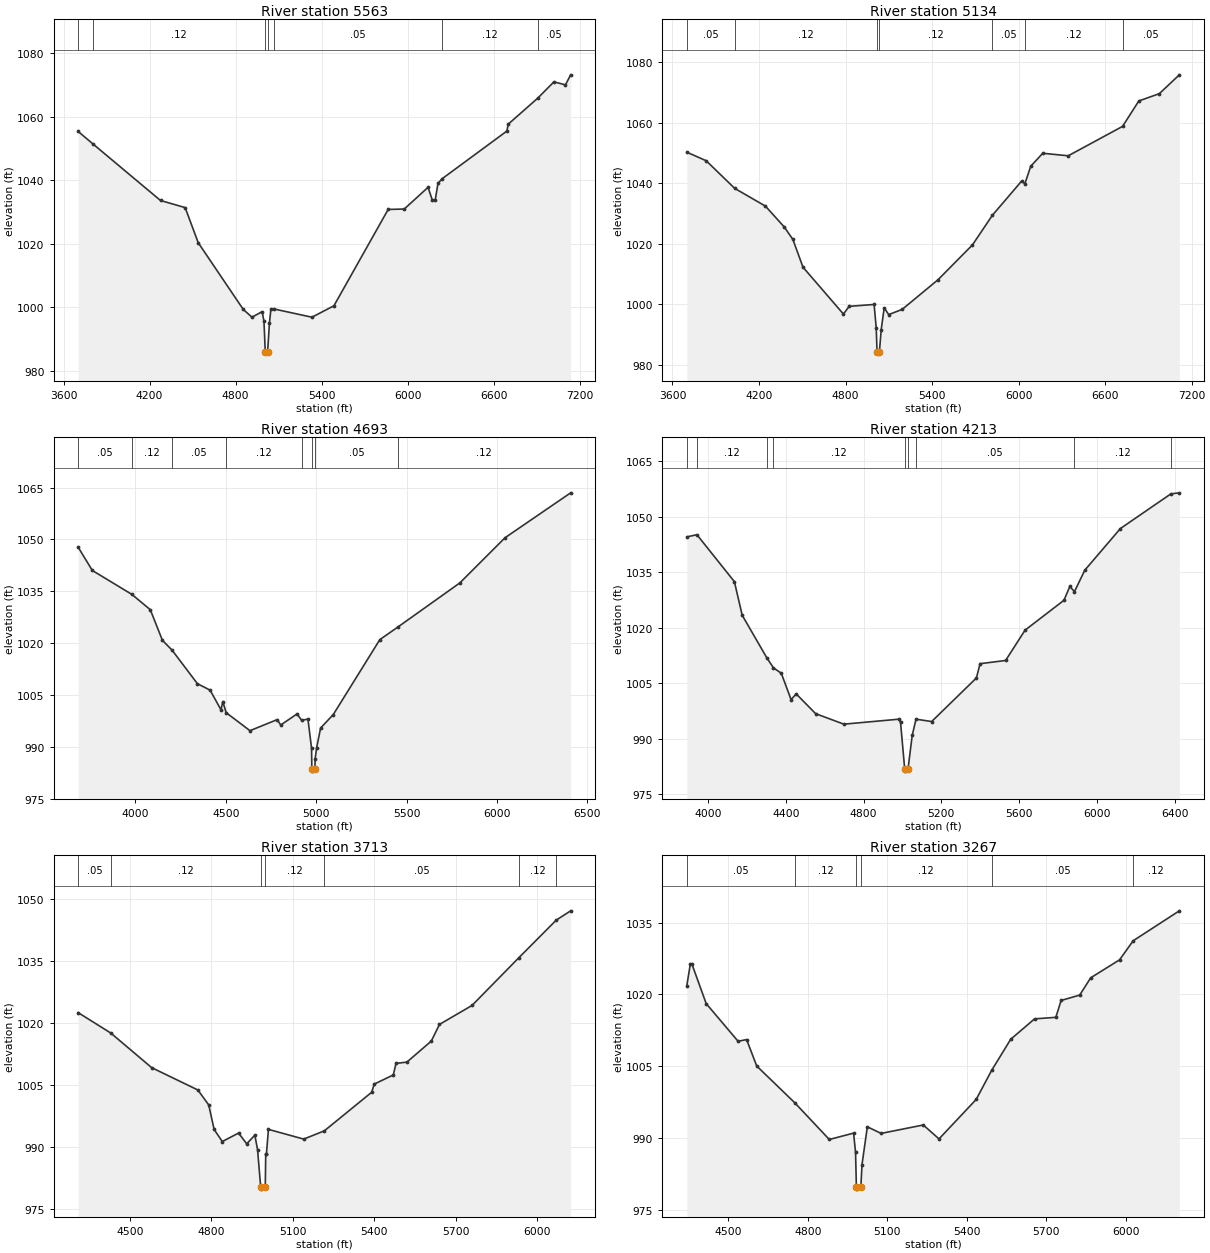
Type RM Length L Ch R = 1 ,5563    ,429,429,429
BEGIN DESCRIPTION:
Upper Denton 47 11.0
END DESCRIPTION:
XS GIS Cut Line= 3
      2197405.51      7262515.46        2196129.        7262310.
      2194033.58      7262749.74
#Sta/Elev= 30
  3701.9 1055.35  3805.8 1051.39    4276 1033.63  4447.9 1031.39    4539 1020.34
    4853  999.36  4913.8   996.9  4984.7  998.66  4997.4  995.63  5006.4   986.1
  5008.4   985.6    5023   986.1  5035.7  995.13  5045.9  999.46  5067.5  999.49
    5332   996.9  5485.3  1000.5  5863.4 1030.81  5975.7 1030.94  6141.7 1037.78
  6169.9 1033.92  6191.6 1033.77  6210.8 1039.02  6240.2 1040.49    6691 1055.47
  6701.2 1057.67  6905.7  1065.8  7019.3 1070.96  7099.7 1070.01  7135.9 1073.17
#Mann= 7 ,-1 , 0
  3701.9     .05       0  3805.8     .12       0  5006.4     .07       0
    5023     .12       0  5067.5     .05       0  6240.2     .12       0
  6905.7     .05       0
Bank Sta=5006.4,5023
XS Rating Curve= 0 ,0
Exp/Cntr=0.3,0.1

Type RM Length L Ch R = 1 ,5134    ,441,441,441
BEGIN DESCRIPTION:
Upper Denton 47 10.0
END DESCRIPTION:
XS GIS Cut Line= 3
      2197223.18       7261894.8        2195929.        7261960.
      2193885.51      7262519.81
#Sta/Elev= 30
  3699.8 1050.27  3834.1 1047.43  4031.4  1038.3  4244.7 1032.42  4374.8 1025.54
  4434.9  1021.4    4505 1012.22  4785.4  996.71  4825.4  999.26  4998.2  999.88
  5012.9  992.08  5018.4  984.28  5020.4  983.78  5035.1  984.28  5047.3  991.54
  5068.2  998.77  5099.3  996.53  5192.6  998.24  5441.5 1008.07  5679.9 1019.58
  5818.3 1029.39  6022.1 1040.77  6043.2 1039.79  6084.3 1045.61  6167.3 1049.91
    6344 1049.07  6720.7  1058.8  6833.6 1067.21    6976 1069.64  7114.4 1075.86
#Mann= 7 ,-1 , 0
  3699.8     .05       0  4031.4     .12       0  5018.4     .07       0
  5035.1     .12       0  5818.3     .05       0  6043.2     .12       0
  6720.7     .05       0
Bank Sta=5018.4,5035.1
XS Rating Curve= 0 ,0
Exp/Cntr=0.3,0.1

Type RM Length L Ch R = 1 ,4693    ,480,480,480
BEGIN DESCRIPTION:
Upper Denton 47 9.0
END DESCRIPTION:
XS GIS Cut Line= 3
      2197097.32      7261695.15        2195779.        7261610.
        2194376.      7261630.04
#Sta/Elev= 30
  3683.3 1047.75  3761.8 1041.02  3979.9 1034.12  4082.4 1029.67  4149.3 1020.81
    4203 1017.95    4343 1008.25  4413.1 1006.39  4473.3  1000.7  4483.3 1003.09
  4501.8  999.88  4633.6  994.66  4783.9  997.85  4803.9   996.3  4894.1  999.51
  4919.5  997.65  4954.3  998.02  4974.3  989.59  4975.9  983.45  4977.9  982.95
  4992.7  983.45  4994.3  986.49  5001.9  989.61  5024.4  995.43  5094.4  999.32
  5351.9 1021.01  5452.2 1024.67  5794.4 1037.42  6044.5  1050.5  6407.5  1063.5
#Mann= 8 ,-1 , 0
  3683.3     .05       0  3979.9     .12       0    4203     .05       0
  4501.8     .12       0  4919.5     .05       0  4975.9    .033       0
  4992.7     .05       0  5452.2     .12       0
Bank Sta=4975.9,4992.7
XS Rating Curve= 0 ,0
Exp/Cntr=0.3,0.1

Type RM Length L Ch R = 1 ,4213    ,500,500,500
BEGIN DESCRIPTION:
Upper Denton 47 8.0
END DESCRIPTION:
XS GIS Cut Line= 3
      2197032.27      7261321.89        2195929.        7261210.
      2194506.21      7261156.95
#Sta/Elev= 30
  3891.1 1044.56  3942.9 1045.15  4135.6 1032.48  4175.8  1023.4    4303 1011.85
  4336.5 1009.21  4376.8 1007.74  4427.1 1000.63  4453.6 1002.16  4553.4  996.83
  4698.5  993.99  4979.9  995.33    4990  994.51  5011.6  981.81  5013.6  981.31
  5028.4  981.81  5050.1  990.96  5069.6  995.34  5150.1   994.7  5380.3 1006.47
    5399 1010.32  5530.4 1011.19  5630.5 1019.38  5830.6 1027.45  5860.6 1031.18
  5884.5 1029.78  5937.5 1035.56  6120.8 1046.82  6380.1 1056.17  6423.8 1056.46
#Mann= 9 ,-1 , 0
  3891.1     .05       0  3942.9     .12       0    4303     .05       0
  4336.5     .12       0  5011.6     .07       0  5028.4     .12       0
  5069.6     .05       0  5884.5     .12       0  6380.1     .05       0
Bank Sta=5011.6,5028.4
XS Rating Curve= 0 ,0
Exp/Cntr=0.3,0.1

Type RM Length L Ch R = 1 ,3713    ,446,446,446
BEGIN DESCRIPTION:
Upper Denton 47 7.0
END DESCRIPTION:
XS GIS Cut Line= 3
       2196619.9       7260709.9        2195929.        7260710.
       2194805.7      7260705.56
#Sta/Elev= 30
  4309.1 1022.51    4429 1017.59    4580 1009.21    4750 1003.82    4790 1000.21
    4810  994.27    4840  991.36    4900  993.41    4930  990.81    4960  992.91
    4970  989.36  4981.5  980.36  4983.5  979.86  4998.4  980.36    5000  988.27
  5002.5  988.27    5010   994.3    5140  991.95  5215.8  993.94    5390 1003.25
    5400 1005.25    5470 1007.45    5480 1010.25    5520 1010.55    5610 1015.64
    5640 1019.66    5760 1024.25    5932 1035.75    6070 1044.85  6123.3 1047.11
#Mann= 7 ,-1 , 0
  4309.1     .05       0    4429     .12       0  4981.5     .07       0
  4998.4     .12       0  5215.8     .05       0    5932     .12       0
    6070     .05       0
Bank Sta=4981.5,4998.4
XS Rating Curve= 0 ,0
Exp/Cntr=0.3,0.1

Type RM Length L Ch R = 1 ,3267    ,469,469,469
BEGIN DESCRIPTION:
Upper Denton 47 6.0
END DESCRIPTION:
XS GIS Cut Line= 3
      2196625.77      7260570.43        2196029.        7260310.
      2194823.84       7260386.4
#Sta/Elev= 30
  4343.7 1021.84  4356.9 1026.33  4362.4 1026.39  4416.6 1018.07  4537.2 1010.18
  4569.3 1010.55  4607.4 1005.02  4751.1  997.34  4881.3  989.67    4973     991
  4980.4     987  4983.6   979.8  4985.6   979.3  5000.5   979.8  5004.8  984.44
  5024.9  992.32  5076.9  990.94  5236.1   992.7  5295.4  989.79  5435.7  998.04
  5494.1 1004.11    5566 1010.61  5656.1 1014.87  5736.3 1015.19  5756.3 1018.72
  5826.5 1019.84  5867.9 1023.45  5976.8  1027.2  6028.3 1031.19  6202.4 1037.44
#Mann= 6 ,-1 , 0
  4343.7     .05       0  4751.1     .12       0  4983.6     .07       0
  5000.5     .12       0  5494.1     .05       0  6028.3     .12       0
Bank Sta=4983.6,5000.5
XS Rating Curve= 0 ,0
Exp/Cntr=0.3,0.1

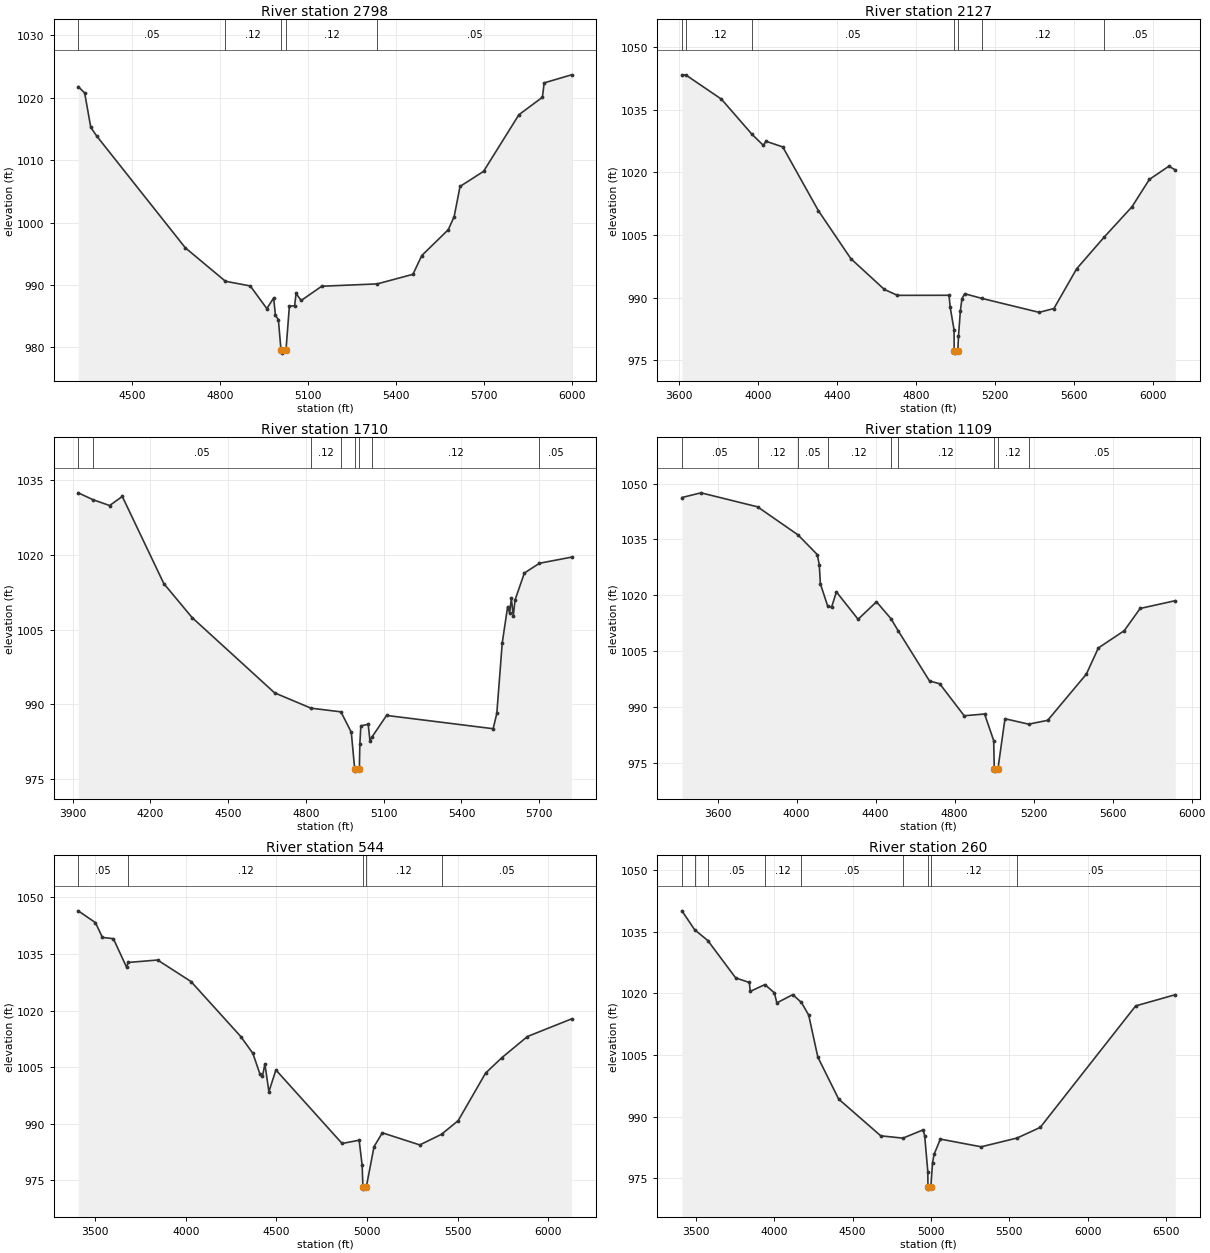
Type RM Length L Ch R = 1 ,2798    ,671,671,671
BEGIN DESCRIPTION:
Upper Denton 47 5.0
END DESCRIPTION:
XS GIS Cut Line= 3
      2196628.99      7260459.98        2196229.        7259910.
      2195229.96      7259827.38
#Sta/Elev= 30
  4315.5  1021.8  4337.5 1020.79  4358.4 1015.26  4379.2 1013.84  4680.6  995.96
  4817.5  990.59  4902.4  989.83  4958.8   986.2    4982   987.9  4988.2   985.1
  4998.1  984.44  5007.1  979.56  5009.1  979.06  5024.1  979.56  5035.7   986.6
  5053.5  986.64  5058.5  988.63  5075.8   987.5  5146.1  989.79    5335  990.16
  5457.1   991.7  5487.2  994.71  5577.5  998.85  5597.6 1000.95  5617.7 1005.79
  5697.9 1008.21  5818.4 1017.29  5898.6 1020.09  5904.6  1022.4    5998 1023.69
#Mann= 5 ,-1 , 0
  4315.5     .05       0  4817.5     .12       0  5007.1     .07       0
  5024.1     .12       0    5335     .05       0
Bank Sta=5007.1,5024.1
XS Rating Curve= 0 ,0
Exp/Cntr=0.3,0.1

Type RM Length L Ch R = 1 ,2127    ,417,417,417
BEGIN DESCRIPTION:
Upper Denton 47 4.0
END DESCRIPTION:
XS GIS Cut Line= 3
      2197854.13      7259633.44      2196494.72      7259336.55
      2195489.53      7258878.23
#Sta/Elev= 30
  3615.4 1043.34  3635.6 1043.29  3815.1 1037.52  3970.4 1029.07  4027.4 1026.45
  4040.3 1027.44  4125.5 1026.08  4306.2 1010.78  4470.2  999.32  4639.1  991.98
  4705.6  990.55    4967  990.57  4972.1  987.85  4992.2  982.29    4993  977.22
    4995  976.72  5011.2  977.22  5014.6  980.75  5024.1  986.85  5032.2  989.77
  5046.1  990.94  5132.2  989.83  5422.8  986.48  5497.4   987.4  5612.7  996.92
  5752.6 1004.54  5892.4 1011.75  5980.3  1018.3  6079.2 1021.47  6111.6 1020.57
#Mann= 7 ,-1 , 0
  3615.4     .05       0  3635.6     .12       0  3970.4     .05       0
    4993    .033       0  5011.2     .05       0  5132.2     .12       0
  5752.6     .05       0
Bank Sta=4993,5011.2
XS Rating Curve= 0 ,0
Exp/Cntr=0.3,0.1

Type RM Length L Ch R = 1 ,1710    ,601,601,601
BEGIN DESCRIPTION:
Upper Denton 47 3.0
END DESCRIPTION:
XS GIS Cut Line= 3
      2197542.45      7259542.66        2196629.        7258960.
      2196012.58      7258418.87
#Sta/Elev= 30
  3921.2 1032.48  3978.7 1031.09  4042.5 1029.93  4091.3 1031.75  4251.5 1014.25
  4360.7 1007.42  4678.9   992.3  4819.3  989.22    4935  988.48    4975  984.37
  4987.9  977.07  4989.9  976.57  5006.1  977.07    5008     982  5011.8  985.66
  5040.2  985.99  5046.9   982.7    5056  983.52  5111.1  987.76  5522.3  985.09
  5536.5  988.17  5557.4 1002.33  5578.3 1009.61  5585.9 1008.34  5592.5 1011.27
  5600.1 1007.73  5606.7 1010.94  5642.8 1016.36    5701 1018.33  5824.9 1019.56
#Mann= 8 ,-1 , 0
  3921.2     .12       0  3978.7     .05       0  4819.3     .12       0
    4935     .05       0  4987.9    .033       0  5006.1     .05       0
    5056     .12       0    5701     .05       0
Bank Sta=4987.9,5006.1
XS Rating Curve= 0 ,0
Exp/Cntr=0.3,0.1

Type RM Length L Ch R = 1 ,1109    ,565,565,565
BEGIN DESCRIPTION:
Upper Denton 47 2.0
END DESCRIPTION:
XS GIS Cut Line= 4
      2198452.18      7258860.86      2196911.39      7258461.55
      2196451.32      7258348.71       2196022.8      7258292.44
#Sta/Elev= 30
  3419.6 1046.25  3515.9 1047.51  3802.3 1043.75  4007.2 1036.21  4104.7 1030.92
    4115 1028.15  4120.4 1023.06  4157.3 1017.11    4177 1016.78  4201.6 1020.89
  4311.3 1013.54  4404.5 1018.23  4477.2 1013.73  4514.4 1010.44  4672.9  996.96
  4724.5  996.21  4848.5  987.61  4951.8  988.08  4997.9  980.92  5000.8  973.23
  5002.8  972.73    5019  973.23  5054.9  986.81  5174.7  985.35  5271.2  986.38
  5466.8  998.79  5527.7 1005.83  5658.8 1010.47  5739.2 1016.44  5917.2 1018.53
#Mann= 9 ,-1 , 0
  3419.6     .05       0  3802.3     .12       0  4007.2     .05       0
  4157.3     .12       0  4477.2     .05       0  4514.4     .12       0
  5000.8     .07       0    5019     .12       0  5174.7     .05       0
Bank Sta=5000.8,5019
XS Rating Curve= 0 ,0
Exp/Cntr=0.3,0.1

Type RM Length L Ch R = 1 ,544     ,284,284,284
BEGIN DESCRIPTION:
Upper Denton 47 1.0
END DESCRIPTION:
XS GIS Cut Line= 4
      2198491.21      7258687.23      2197076.32      7257953.74
      2196468.68      7258036.21      2196013.47      7258274.65
#Sta/Elev= 30
    3407 1046.44    3502 1043.31  3540.6 1039.39    3601 1039.06  3673.4 1031.52
  3682.6 1032.75  3844.8  1033.4    4029  1027.7  4303.8  1013.1  4370.2 1008.66
  4408.8 1003.23  4423.2  1002.6  4436.6 1005.84  4458.7  998.49  4497.3 1004.26
  4862.3  984.76  4956.4  985.63  4972.9  979.01  4977.3  973.16  4979.3  972.66
  4995.6  973.16  5038.4  983.91  5084.1  987.59  5290.7  984.38  5410.7   987.2
  5502.6  990.82  5653.7 1003.42    5742 1007.45  5884.5 1013.12  6127.8 1017.79
#Mann= 5 ,-1 , 0
    3407     .05       0  3682.6     .12       0  4977.3     .07       0
  4995.6     .12       0  5410.7     .05       0
Bank Sta=4977.3,4995.6
XS Rating Curve= 0 ,0
Exp/Cntr=0.3,0.1

Type RM Length L Ch R = 1 ,260     ,0,0,0
BEGIN DESCRIPTION:
Upper Denton 47 0.5
END DESCRIPTION:
XS GIS Cut Line= 4
       2198504.3      7258253.24      2197497.33       7257658.6
       2196525.1      7257684.64      2195843.87      7258422.29
#Sta/Elev= 30
  3412.1 1040.05  3493.3 1035.44  3576.8 1032.83    3755 1023.73  3841.7 1022.63
  3847.9 1020.47  3941.2 1022.12  4001.7  1020.1  4017.3 1017.67  4118.7 1019.67
  4173.7 1017.78  4220.2 1014.72  4278.7 1004.48  4411.4  994.28  4679.9  985.34
  4821.4  984.78    4950  986.79    4960  985.39    4980  976.65  4980.9  972.88
  4982.9  972.38  4999.2  972.88    5010  978.77    5020  980.84    5060  984.55
  5320.1  982.67  5549.5  984.81  5696.9  987.39  6305.3 1016.93  6558.2 1019.66
#Mann= 9 ,-1 , 0
  3412.1     .05       0  3493.3     .12       0  3576.8     .05       0
  3941.2     .12       0  4173.7     .05       0  4821.4     .12       0
  4980.9     .07       0  4999.2     .12       0  5549.5     .05       0
Bank Sta=4980.9,4999.2
XS Rating Curve= 0 ,0
Exp/Cntr=0.3,0.1

Chan Stop Cuts=-1
Use User Specified Reach Order=0
Composite Channel Slope=5