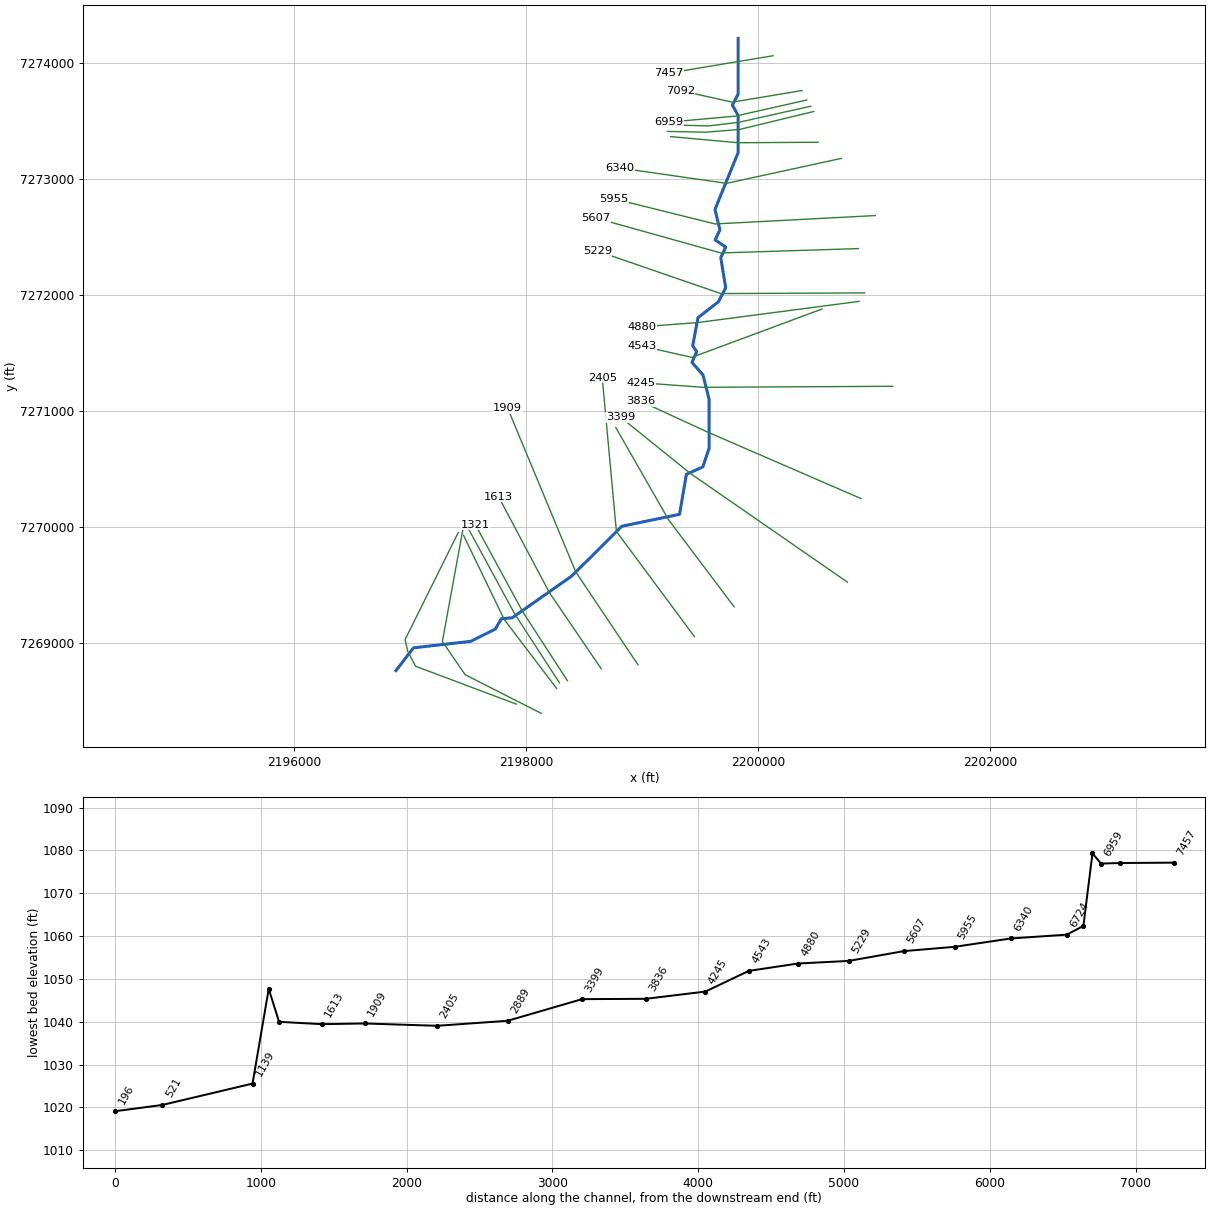
--- Upper Denton 50.prj (project) ---

Proj Title=Upper Denton 50 Base Level Engineering
Current Plan=p01
Default Exp/Contr=0.3,0.1
English Units
Geom File=g01
Flow File=f01
Plan File=p01
BEGIN DESCRIPTION:
Upper Denton 50
END DESCRIPTION:

--- Upper Denton 50.p01 (plan) ---

Plan Title=Multiple Run
Short Identifier=Multiple
Geom File=g01
Flow File=f01
Subcritical Flow
K Sum by GR= 0
Std Step Tol= 0.01
Critical Tol= 0.01
Num of Std Step Trials= 20
Max Error Tol= 0.3
Flow Tol Ratio= 0.001
Split Flow NTrial= 30
Split Flow Tol= 0.02
Split Flow Ratio= 0.02
Log Output Level= 0
Friction Slope Method= 1
Unsteady Friction Slope Method= 2
Unsteady Bridges Friction Slope Method= 1
Parabolic Critical Depth
Global Vel Dist=  1 , 1 , 1
Global Log Level= 0
CheckData=True
Encroach Param= -1, 0, 0, 0
BEGIN DESCRIPTION:
Multiple Run
END DESCRIPTION:

--- Upper Denton 50.f01 (steady flow) ---

Flow Title=Multiple
Number of Profiles=7
Profile Names=10-year,25-year,50-year,1pct_min,100-year,1pct_plu,500-year
River Rch & RM= Upper Denton 50,Reach-1,7457
     628     869    1070     654    1305    2604    1948
River Rch & RM= Upper Denton 50,Reach-1,3399
     782    1096    1359     837    1670    3333    2529
Boundary for River Rch & Prof#=Upper Denton 50,Reach-1,1
Up Type=0
Dn Type=3
Dn Slope=0.005
Boundary for River Rch & Prof#=Upper Denton 50,Reach-1,2
Up Type=0
Dn Type=3
Dn Slope=0.005
Boundary for River Rch & Prof#=Upper Denton 50,Reach-1,3
Up Type=0
Dn Type=3
Dn Slope=0.005
Boundary for River Rch & Prof#=Upper Denton 50,Reach-1,4
Up Type=0
Dn Type=3
Dn Slope=0.005
Boundary for River Rch & Prof#=Upper Denton 50,Reach-1,5
Up Type=0
Dn Type=3
Dn Slope=0.005
Boundary for River Rch & Prof#=Upper Denton 50,Reach-1,6
Up Type=0
Dn Type=3
Dn Slope=0.005
Boundary for River Rch & Prof#=Upper Denton 50,Reach-1,7
Up Type=0
Dn Type=3
Dn Slope=0.005

--- Upper Denton 50.g01 (geometry) ---

Geom Title=Existing Conditions

River Reach=Upper Denton 50,Reach-1
Reach XY= 30
      2199829.00      7274210.00      2199828.91      7273730.03
      2199778.60      7273635.00      2199828.46      7273544.79
      2199828.48      7273225.22      2199628.77      7272735.07
      2199671.39      7272559.96      2199630.26      7272472.03
      2199721.74      7272410.30      2199678.60      7272320.21
      2199721.47      7272059.99      2199659.23      7271939.91
      2199482.07      7271801.70      2199436.79      7271559.90
      2199471.17      7271510.08      2199430.66      7271416.05
      2199525.44      7271308.53      2199577.78      7271099.50
      2199578.48      7270675.21      2199523.75      7270515.44
      2199382.07      7270451.72      2199323.65      7270107.26
      2198826.57      7270004.48      2198392.21      7269573.63
      2197881.36      7269215.56      2197787.35      7269206.81
      2197735.32      7269118.07      2197523.07      7269012.24
      2197030.48      7268956.39      2196879.00      7268760.00

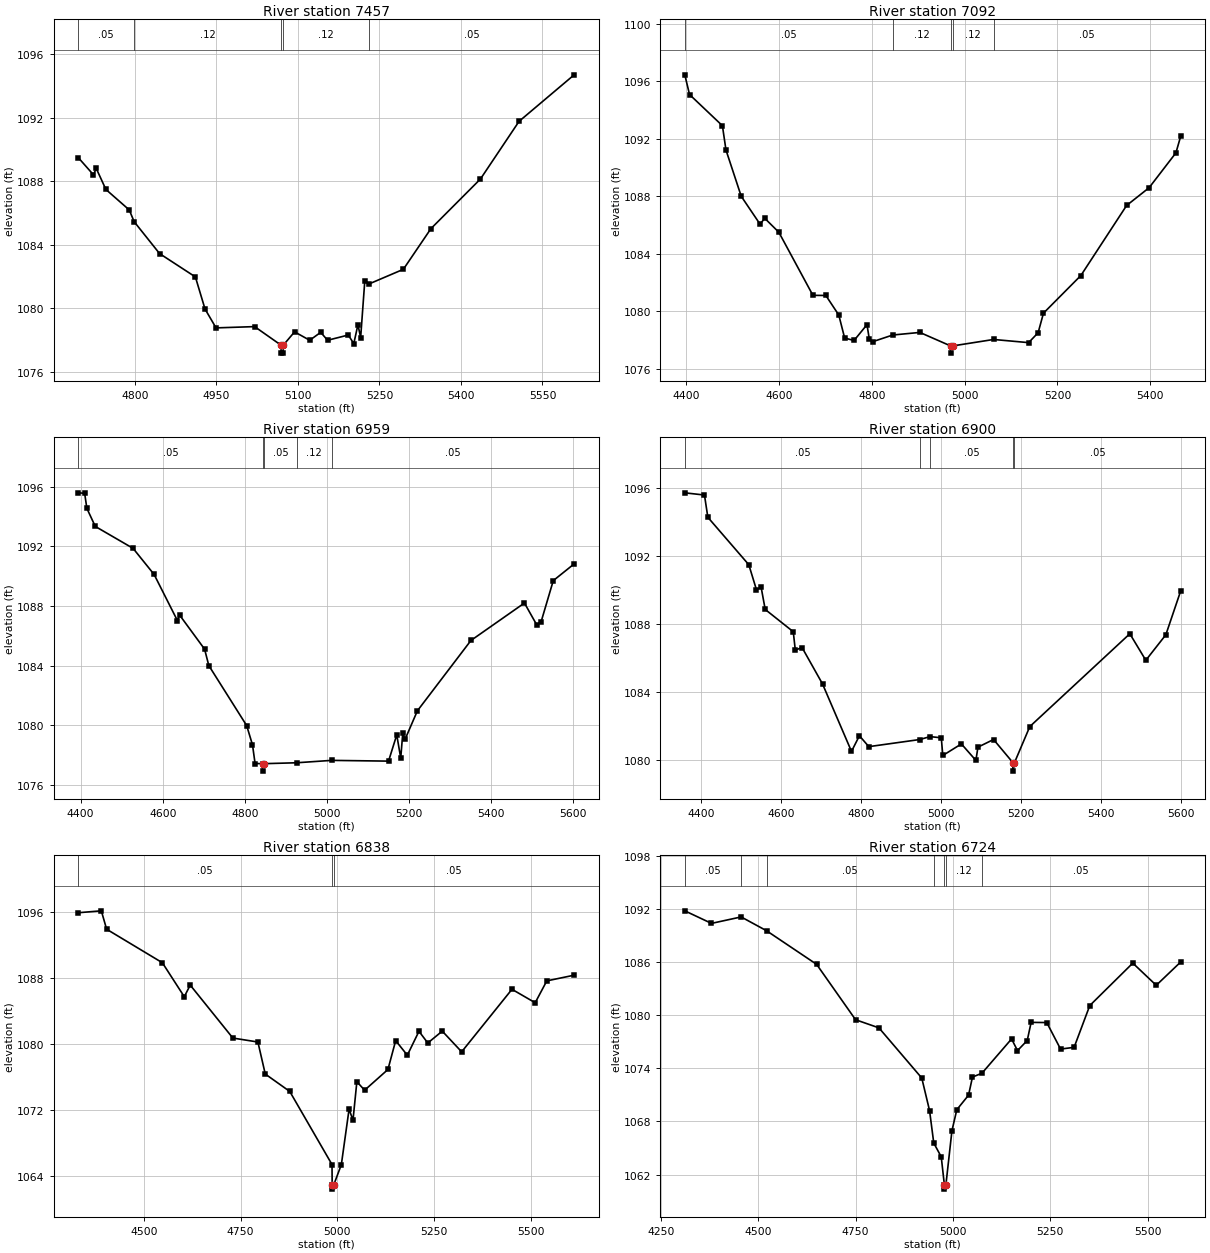
Type RM Length L Ch R = 1,7457,365,365,365
BEGIN DESCRIPTION:
Upper Denton 50 18.0
END DESCRIPTION:
XS GIS Cut Line= 3
      2200128.97      7274060.00      2199829.00      7274010.00
      2199228.99      7273910.00
#Sta/Elev= 30
  4695.9 1089.47  4723.8 1088.39  4728.8 1088.80  4746.6 1087.47  4789.6 1086.18
  4798.6 1085.44  4845.4 1083.43  4911.3 1081.96  4929.0 1079.94  4949.3 1078.75
  5020.3 1078.83  5069.0 1077.66  5069.2 1077.16  5072.7 1077.16  5073.0 1077.66
  5093.8 1078.50  5121.7 1077.97  5141.9 1078.47  5154.6 1077.97  5192.6 1078.30
  5202.8 1077.76  5210.4 1078.95  5215.4 1078.14  5223.0 1081.70  5230.3 1081.51
  5294.0 1082.44  5344.7 1085.00  5435.9 1088.13  5506.9 1091.76  5608.3 1094.69
#Mann=5,-1,0
  4695.9    0.05       0  4798.6    0.12       0  5069.0    0.07       0
  5073.0    0.12       0  5230.3    0.05       0
Bank Sta=5069,5073
Exp/Cntr=0.3,0.1

Type RM Length L Ch R = 1,7092,133,133,133
BEGIN DESCRIPTION:
Upper Denton 50 17.0
END DESCRIPTION:
XS GIS Cut Line= 3
      2200379.05      7273760.01      2199779.00      7273660.00
      2199329.00      7273760.00
#Sta/Elev= 30
  4396.4 1096.44  4406.6 1095.07  4477.5 1092.90  4485.2 1091.21  4518.1 1087.99
  4558.7 1086.05  4568.8 1086.46  4599.2 1085.49  4672.7 1081.10  4700.6 1081.09
  4728.5 1079.73  4741.1 1078.13  4761.4 1077.96  4789.3 1079.06  4794.4 1078.04
  4802.0 1077.88  4844.8 1078.34  4903.3 1078.52  4969.8 1077.58  4970.0 1077.08
  4973.8 1077.58  5062.4 1078.03  5137.9 1077.81  5158.4 1078.50  5169.9 1079.86
  5250.6 1082.48  5349.2 1087.35  5397.8 1088.59  5455.5 1091.01  5465.7 1092.15
#Mann=5,-1,0
  4396.4    0.05       0  4844.8    0.12       0  4969.8    0.07       0
  4973.8    0.12       0  5062.4    0.05       0
Bank Sta=4969.8,4973.8
Exp/Cntr=0.3,0.1

Type RM Length L Ch R = 1,6959,59,59,59
BEGIN DESCRIPTION:
Upper Denton 50 16.8
END DESCRIPTION:
XS GIS Cut Line= 3
      2200419.26      7273678.34      2199804.71      7273539.46
      2199228.30      7273487.37
#Sta/Elev= 30
  4394.3 1095.58  4409.7 1095.55  4415.1 1094.54  4435.6 1093.33  4527.8 1091.86
  4579.1 1090.11  4635.9 1087.02  4641.0 1087.40  4702.1 1085.11  4712.4 1084.01
  4804.7 1079.99  4818.9 1078.70  4825.2 1077.45  4843.7 1077.44  4843.9 1076.94
  4847.7 1077.44  4926.6 1077.50  5011.7 1077.66  5150.6 1077.61  5170.6 1079.37
  5180.3 1077.81  5185.3 1079.50  5190.7 1079.06  5220.9 1080.98  5351.4 1085.69
  5481.9 1088.20  5512.0 1086.73  5522.7 1086.96  5552.2 1089.70  5603.1 1090.82
#Mann=5,-1,0
  4394.3    0.05       0  4843.7    0.07       0  4847.7    0.05       0
  4926.6    0.12       0  5011.7    0.05       0
Bank Sta=4843.7,4847.7
Exp/Cntr=0.3,0.1

Type RM Length L Ch R = 1,6900,62,62,62
BEGIN DESCRIPTION:
Upper Denton 50 16.5
END DESCRIPTION:
XS GIS Cut Line= 4
      2200455.34      7273624.96      2199831.62      7273485.64
      2199570.85      7273454.76      2199231.98      7273464.75
#Sta/Elev= 30
  4358.5 1095.69  4407.7 1095.56  4416.2 1094.25  4518.7 1091.46  4537.9 1089.98
  4549.4 1090.15  4559.7 1088.83  4629.9 1087.52  4635.0 1086.44  4651.9 1086.59
  4703.1 1084.45  4775.6 1080.48  4795.4 1081.40  4819.0 1080.76  4946.8 1081.18
  4972.1 1081.35  5000.3 1081.28  5004.1 1080.24  5050.6 1080.92  5086.9 1079.95
  5092.0 1080.73  5131.1 1081.18  5179.5 1079.82  5179.7 1079.32  5183.5 1079.82
  5221.8 1081.94  5472.1 1087.40  5512.1 1085.84  5562.2 1087.34  5599.2 1089.91
#Mann=5,-1,0
  4358.5    0.05       0  4946.8    0.12       0  4972.1    0.05       0
  5179.5   0.033       0  5183.5    0.05       0
Bank Sta=5179.5,5183.5
Exp/Cntr=0.3,0.1

Type RM Length L Ch R = 1,6838,114,114,114
BEGIN DESCRIPTION:
Upper Denton 50 16.4
END DESCRIPTION:
XS GIS Cut Line= 4
      2200480.04      7273579.38      2199839.43      7273424.44
      2199549.07      7273401.00      2199218.32      7273407.51
#Sta/Elev= 30
  4330.5 1095.89  4389.9 1096.12  4403.6 1093.89  4547.6 1089.83  4604.3 1085.71
  4619.6 1087.12  4729.8 1080.70  4794.5 1080.22  4813.5 1076.34  4876.8 1074.23
  4986.0 1065.37  4986.4 1062.89  4986.6 1062.39  4990.4 1062.89  5010.1 1065.36
  5030.1 1072.08  5040.2 1070.74  5050.2 1075.41  5070.3 1074.38  5130.5 1076.89
  5150.5 1080.39  5180.6 1078.62  5210.7 1081.52  5233.5 1080.10  5270.9 1081.54
  5321.0 1079.03  5451.0 1086.61  5511.0 1084.98  5541.0 1087.63  5611.7 1088.32
#Mann=3,-1,0
  4330.5    0.05       0  4986.4   0.033       0  4990.4    0.05       0
Bank Sta=4986.4,4990.4
Exp/Cntr=0.3,0.1

Type RM Length L Ch R = 1,6724,384,384,384
BEGIN DESCRIPTION:
Upper Denton 50 16.0
END DESCRIPTION:
XS GIS Cut Line= 3
      2200517.46      7273314.21      2199829.00      7273310.00
      2199246.67      7273362.82
#Sta/Elev= 30
  4311.6 1091.81  4380.1 1090.39  4456.3 1091.12  4521.5 1089.56  4650.1 1085.76
  4750.1 1079.50  4810.1 1078.58  4920.1 1072.91  4940.1 1069.23  4950.9 1065.56
  4970.1 1064.00  4978.1 1060.85  4978.3 1060.35  4982.1 1060.85  4997.6 1066.96
  5010.1 1069.33  5040.2 1070.97  5050.3 1073.02  5074.6 1073.45  5150.7 1077.33
  5165.9 1076.01  5190.9 1077.15  5200.9 1079.20  5241.1 1079.18  5276.5 1076.18
  5311.3 1076.38  5351.5 1081.10  5462.0 1085.90  5522.2 1083.39  5584.8 1086.02
#Mann=7,-1,0
  4311.6    0.05       0  4456.3    0.12       0  4521.5    0.05       0
  4950.9    0.12       0  4978.1    0.07       0  4982.1    0.12       0
  5074.6    0.05       0
Bank Sta=4978.1,4982.1
Exp/Cntr=0.3,0.1

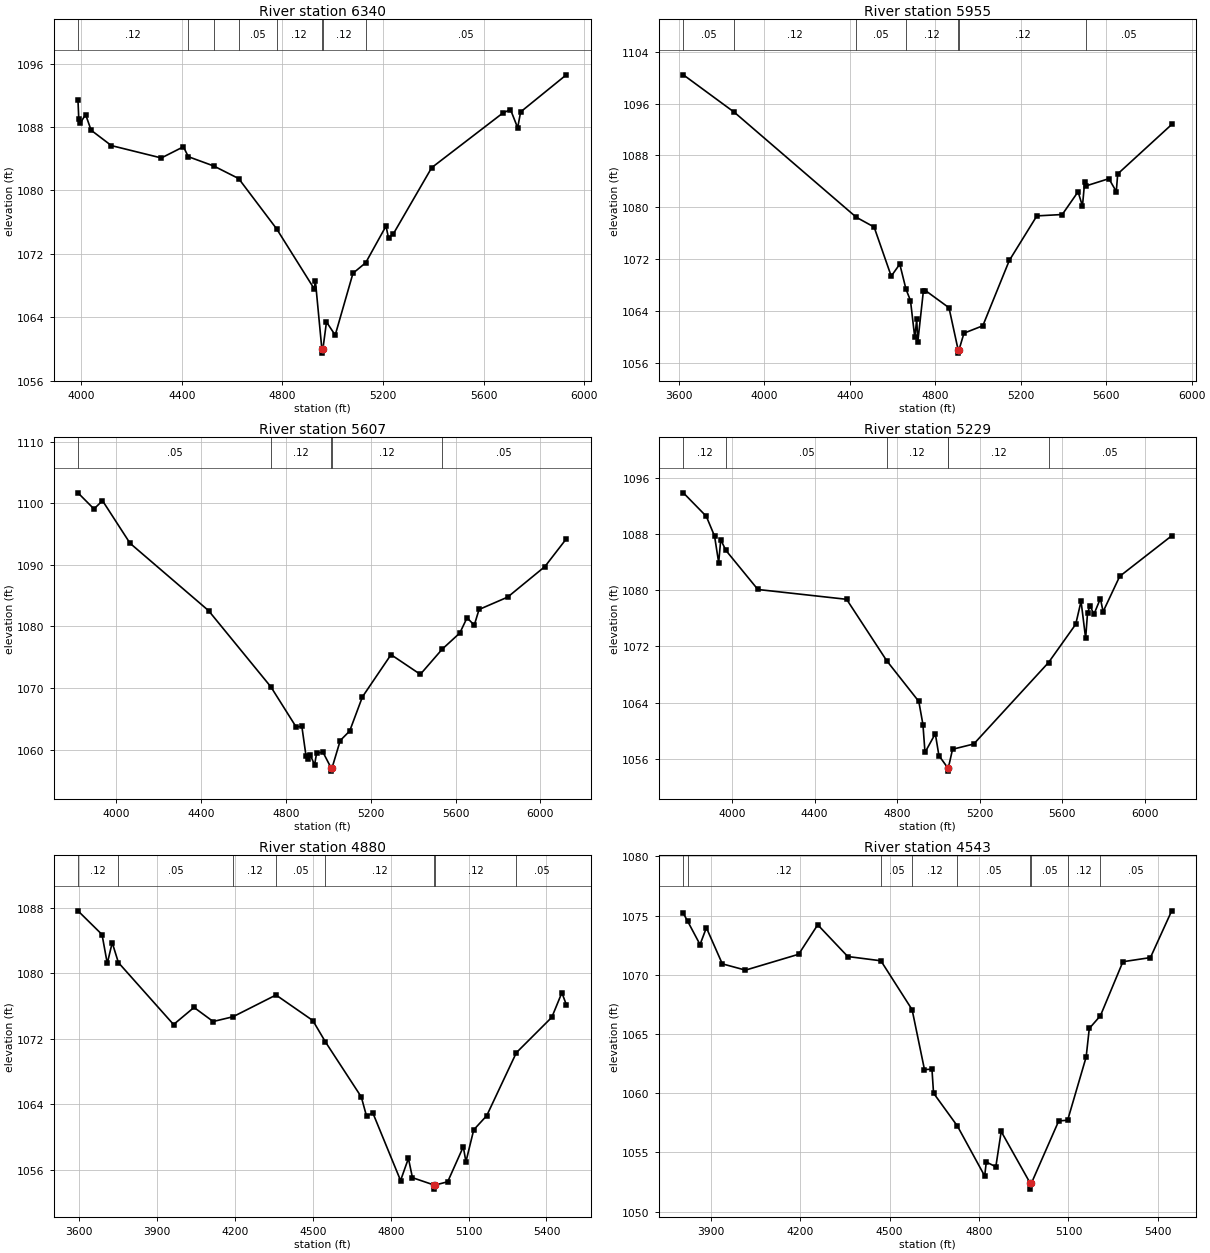
Type RM Length L Ch R = 1,6340,385,385,385
BEGIN DESCRIPTION:
Upper Denton 50 15.0
END DESCRIPTION:
XS GIS Cut Line= 3
      2200718.84      7273175.33      2199729.00      7272960.00
      2198809.11      7273091.99
#Sta/Elev= 30
  3987.0 1091.41  3990.2 1089.06  3997.1 1088.55  4017.5 1089.56  4039.3 1087.59
  4119.9 1085.65  4318.6 1084.09  4406.4 1085.50  4425.9 1084.25  4526.8 1083.08
  4626.1 1081.49  4777.2 1075.14  4926.3 1067.59  4931.4 1068.54  4957.1 1059.96
  4957.3 1059.46  4961.1 1059.96  4975.4 1063.39  5010.1 1061.73  5080.8 1069.54
  5131.5 1070.87  5212.1 1075.49  5222.2 1073.99  5241.9 1074.54  5394.0 1082.87
  5676.9 1089.76  5707.2 1090.20  5735.8 1087.90  5747.6 1089.90  5929.3 1094.58
#Mann=8,-1,0
  3987.0    0.12       0  4425.9    0.05       0  4526.8    0.12       0
  4626.1    0.05       0  4777.2    0.12       0  4957.1    0.07       0
  4961.1    0.12       0  5131.5    0.05       0
Bank Sta=4957.1,4961.1
Exp/Cntr=0.3,0.1

Type RM Length L Ch R = 1,5955,348,348,348
BEGIN DESCRIPTION:
Upper Denton 50 14.0
END DESCRIPTION:
XS GIS Cut Line= 3
      2201010.55      7272682.27      2199629.00      7272610.00
      2198753.79      7272828.05
#Sta/Elev= 30
  3621.2 1100.44  3860.0 1094.66  4430.6 1078.47  4514.0 1076.96  4594.1 1069.38
  4634.1 1071.24  4663.1 1067.38  4684.2 1065.61  4704.2 1059.94  4713.4 1062.72
  4718.4 1059.23  4744.3 1067.02  4754.3 1067.16  4864.4 1064.51  4907.2 1058.01
  4907.5 1057.51  4911.2 1058.01  4934.5 1060.59  5022.7 1061.73  5146.6 1071.80
  5275.6 1078.68  5394.4 1078.89  5468.4 1082.40  5489.0 1080.20  5499.3 1083.90
  5506.9 1083.32  5612.7 1084.42  5647.3 1082.43  5653.9 1085.15  5906.6 1092.78
#Mann=7,-1,0
  3621.2    0.05       0  3860.0    0.12       0  4430.6    0.05       0
  4663.1    0.12       0  4907.2    0.07       0  4911.2    0.12       0
  5506.9    0.05       0
Bank Sta=4907.2,4911.2
Exp/Cntr=0.3,0.1

Type RM Length L Ch R = 1,5607,378,378,378
BEGIN DESCRIPTION:
Upper Denton 50 13.0
END DESCRIPTION:
XS GIS Cut Line= 3
      2200864.66      7272397.55      2199679.00      7272360.00
      2198602.44      7272660.98
#Sta/Elev= 30
  3818.6 1101.69  3894.2 1099.07  3934.3 1100.42  4064.4 1093.50  4434.6 1082.57
  4728.8 1070.19  4848.3 1063.66  4874.8 1063.80  4894.8 1058.93  4904.8 1058.40
  4914.8 1059.16  4934.8 1057.50  4944.8 1059.47  4974.8 1059.57  5013.2 1057.01
  5013.5 1056.51  5017.2 1057.01  5056.1 1061.48  5100.6 1063.02  5160.6 1068.56
  5295.6 1075.42  5433.9 1072.22  5537.4 1076.32  5620.2 1078.93  5654.3 1081.40
  5688.5 1080.21  5710.9 1082.75  5845.9 1084.76  6021.7 1089.72  6122.7 1094.22
#Mann=5,-1,0
  3818.6    0.05       0  4728.8    0.12       0  5013.2    0.07       0
  5017.2    0.12       0  5537.4    0.05       0
Bank Sta=5013.2,5017.2
Exp/Cntr=0.3,0.1

Type RM Length L Ch R = 1,5229,349,349,349
BEGIN DESCRIPTION:
Upper Denton 50 12.0
END DESCRIPTION:
XS GIS Cut Line= 3
      2200920.28      7272015.60      2199679.00      7272010.00
      2198614.69      7272376.71
#Sta/Elev= 30
  3764.0 1093.92  3875.3 1090.57  3915.3 1087.75  3935.3 1083.96  3945.3 1087.23
  3970.2 1085.71  4125.3 1080.13  4555.3 1078.73  4750.2 1069.95  4905.3 1064.16
  4925.3 1060.87  4935.3 1056.89  4985.3 1059.56  5002.8 1056.43  5044.8 1054.72
  5045.1 1054.22  5048.8 1054.72  5068.8 1057.34  5171.7 1058.09  5534.0 1069.71
  5665.8 1075.17  5691.7 1078.46  5713.9 1073.15  5723.0 1076.77  5735.1 1077.80
  5754.2 1076.60  5785.4 1078.84  5798.6 1076.97  5879.0 1082.01  6131.0 1087.79
#Mann=6,-1,0
  3764.0    0.12       0  3970.2    0.05       0  4750.2    0.12       0
  5044.8    0.07       0  5048.8    0.12       0  5534.0    0.05       0
Bank Sta=5044.8,5048.8
Exp/Cntr=0.3,0.1

Type RM Length L Ch R = 1,4880,337,337,337
BEGIN DESCRIPTION:
Upper Denton 50 11.0
END DESCRIPTION:
XS GIS Cut Line= 3
      2200870.89      7271942.68      2199479.00      7271760.00
      2199003.39      7271723.98
#Sta/Elev= 30
  3595.6 1087.63  3688.3 1084.73  3708.5 1081.20  3727.5 1083.74  3751.4 1081.30
  3963.8 1073.73  4042.6 1075.82  4116.3 1074.10  4192.6 1074.68  4358.3 1077.34
  4500.1 1074.22  4548.6 1071.61  4686.8 1064.88  4706.9 1062.54  4731.3 1062.92
  4838.1 1054.66  4868.3 1057.37  4883.8 1055.01  4967.2 1054.11  4967.4 1053.61
  4971.2 1054.11  5019.5 1054.51  5079.7 1058.79  5089.7 1056.95  5119.8 1060.86
  5169.9 1062.59  5284.0 1070.29  5420.6 1074.62  5459.3 1077.62  5476.4 1076.16
#Mann=8,-1,0
  3595.6    0.12       0  3751.4    0.05       0  4192.6    0.12       0
  4358.3    0.05       0  4548.6    0.12       0  4967.2    0.07       0
  4971.2    0.12       0  5284.0    0.05       0
Bank Sta=4967.2,4971.2
Exp/Cntr=0.3,0.1

Type RM Length L Ch R = 1,4543,298,298,298
BEGIN DESCRIPTION:
Upper Denton 50 10.0
END DESCRIPTION:
XS GIS Cut Line= 3
      2200551.48      7271876.72      2199429.00      7271460.00
      2198999.41      7271557.27
#Sta/Elev= 30
  3808.5 1075.19  3823.4 1074.50  3864.5 1072.55  3885.8 1073.97  3939.2 1070.92
  4016.9 1070.39  4195.2 1071.73  4259.2 1074.22  4359.9 1071.54  4471.0 1071.18
  4575.7 1067.05  4617.2 1061.99  4642.3 1062.02  4647.6 1060.00  4727.6 1057.22
  4819.1 1053.00  4824.5 1054.18  4856.5 1053.78  4874.5 1056.76  4971.8 1052.39
  4972.1 1051.89  4975.8 1052.39  5067.4 1057.65  5097.3 1057.71  5159.4 1063.05
  5169.9 1065.46  5207.3 1066.54  5282.7 1071.10  5375.0 1071.45  5446.3 1075.40
#Mann=9,-1,0
  3808.5    0.05       0  3823.4    0.12       0  4471.0    0.05       0
  4575.7    0.12       0  4727.6    0.05       0  4971.8   0.033       0
  4975.8    0.05       0  5097.3    0.12       0  5207.3    0.05       0
Bank Sta=4971.8,4975.8
Exp/Cntr=0.3,0.1

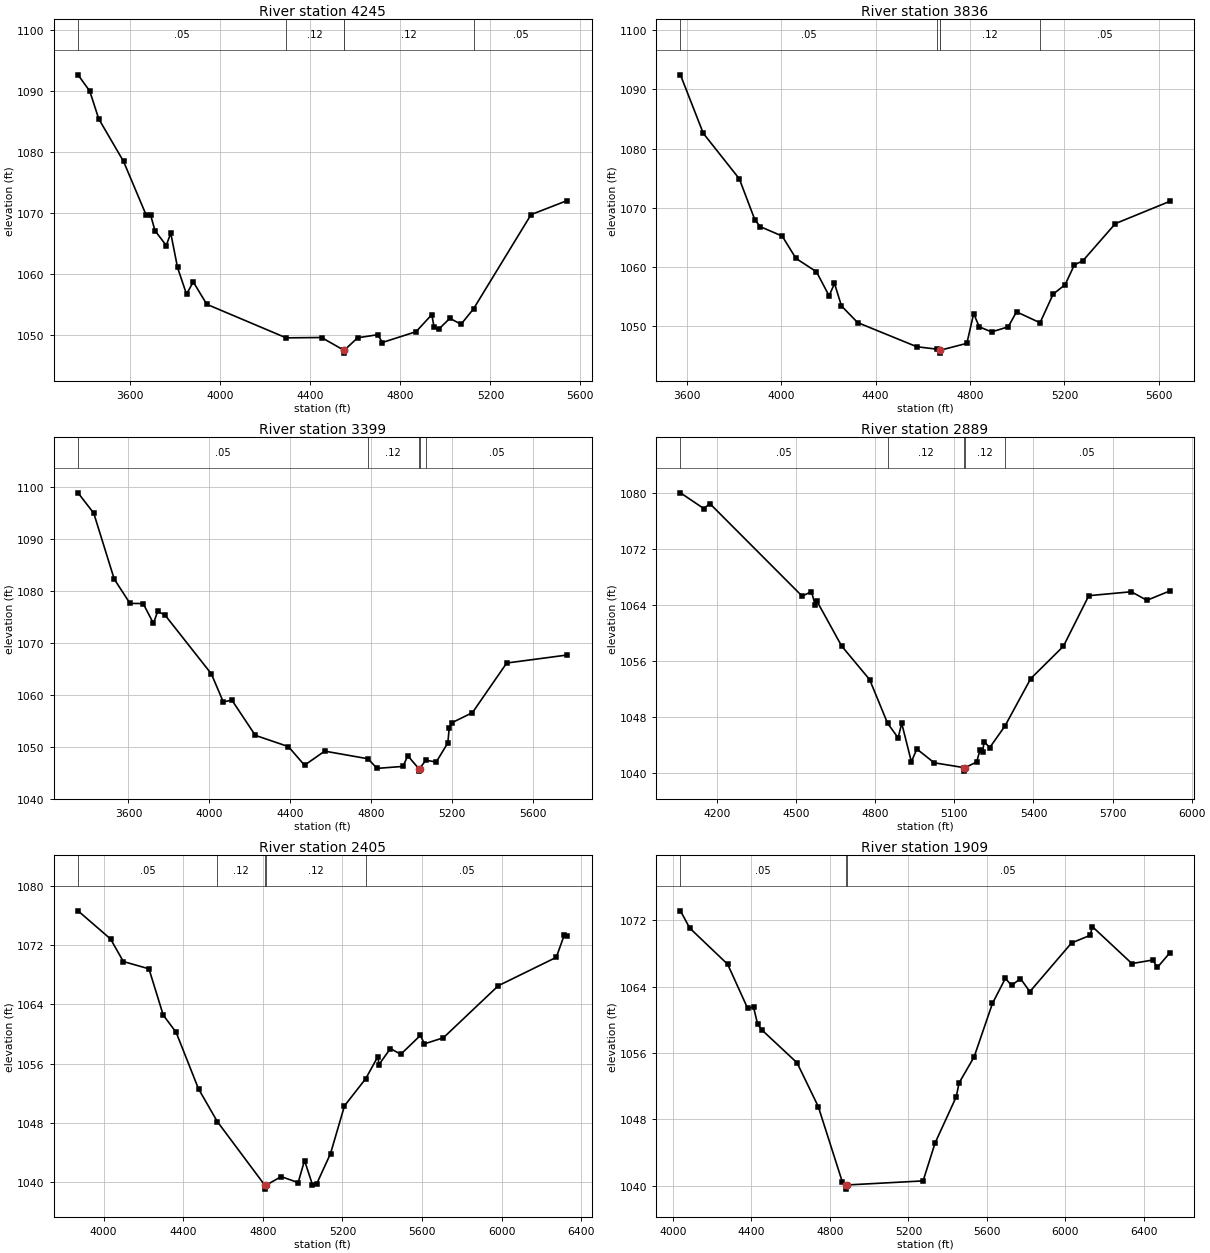
Type RM Length L Ch R = 1,4245,409,409,409
BEGIN DESCRIPTION:
Upper Denton 50 9.0
END DESCRIPTION:
XS GIS Cut Line= 3
      2201161.19      7271210.70      2199524.93      7271202.02
      2198988.95      7271241.30
#Sta/Elev= 30
  3367.4 1092.65  3419.6 1089.99  3459.6 1085.43  3569.6 1078.48  3669.6 1069.74
  3689.6 1069.73  3709.6 1067.12  3759.6 1064.69  3779.6 1066.72  3809.6 1061.10
  3849.6 1056.72  3879.6 1058.73  3939.6 1055.06  4292.6 1049.56  4449.6 1049.62
  4547.6 1047.56  4547.9 1047.06  4551.6 1047.56  4609.6 1049.57  4699.6 1050.08
  4719.6 1048.80  4869.6 1050.57  4939.6 1053.37  4949.6 1051.33  4969.6 1050.95
  5019.7 1052.75  5069.8 1051.80  5125.1 1054.32  5380.6 1069.75  5541.1 1072.05
#Mann=5,-1,0
  3367.4    0.05       0  4292.6    0.12       0  4547.6    0.07       0
  4551.6    0.12       0  5125.1    0.05       0
Bank Sta=4547.6,4551.6
Exp/Cntr=0.3,0.1

Type RM Length L Ch R = 1,3836,437,437,437
BEGIN DESCRIPTION:
Upper Denton 50 8.0
END DESCRIPTION:
XS GIS Cut Line= 3
      2200887.82      7270242.80      2199579.00      7270810.00
      2198992.53      7271079.82
#Sta/Elev= 30
  3573.6 1092.48  3670.4 1082.58  3823.0 1074.88  3888.4 1067.99  3910.8 1066.80
  4004.7 1065.18  4062.8 1061.41  4149.9 1059.14  4203.4 1055.06  4226.2 1057.17
  4255.8 1053.35  4324.3 1050.54  4575.0 1046.45  4662.2 1046.03  4671.1 1045.87
  4671.3 1045.37  4675.1 1045.87  4786.9 1047.03  4815.8 1052.07  4839.3 1049.82
  4891.7 1048.96  4962.1 1049.82  4997.3 1052.36  5096.9 1050.51  5152.1 1055.34
  5203.5 1056.98  5242.2 1060.31  5278.0 1060.99  5415.8 1067.29  5645.6 1071.05
#Mann=5,-1,0
  3573.6    0.05       0  4662.2    0.12       0  4671.1    0.07       0
  4675.1    0.12       0  5096.9    0.05       0
Bank Sta=4671.1,4675.1
Exp/Cntr=0.3,0.1

Type RM Length L Ch R = 1,3399,510,510,510
BEGIN DESCRIPTION:
Upper Denton 50 7.0
END DESCRIPTION:
XS GIS Cut Line= 3
      2200770.58      7269522.34      2199416.42      7270459.83
      2198814.12      7270945.14
#Sta/Elev= 30
  3350.5 1098.86  3428.5 1094.93  3529.8 1082.25  3607.8 1077.58  3673.1 1077.54
  3723.7 1073.73  3744.7 1076.03  3780.5 1075.36  4010.2 1064.02  4069.7 1058.59
  4111.6 1058.98  4227.8 1052.18  4392.0 1050.00  4471.4 1046.42  4571.1 1049.14
  4785.1 1047.67  4830.5 1045.82  4958.9 1046.20  4982.2 1048.25  5036.4 1045.79
  5036.6 1045.29  5040.4 1045.79  5071.9 1047.38  5123.2 1047.05  5180.7 1050.73
  5187.2 1053.57  5201.5 1054.62  5302.3 1056.55  5471.9 1066.10  5771.0 1067.64
#Mann=5,-1,0
  3350.5    0.05       0  4785.1    0.12       0  5036.4    0.07       0
  5040.4    0.12       0  5071.9    0.05       0
Bank Sta=5036.4,5040.4
Exp/Cntr=0.3,0.1

Type RM Length L Ch R = 1,2889,484,484,484
BEGIN DESCRIPTION:
Upper Denton 50 6.0
END DESCRIPTION:
XS GIS Cut Line= 3
      2199794.04      7269309.64      2199229.00      7270060.00
      2198774.07      7270854.79
#Sta/Elev= 30
  4061.2 1079.99  4150.0 1077.74  4172.8 1078.45  4522.7 1065.24  4558.1 1065.87
  4572.6 1063.94  4578.9 1064.51  4672.6 1058.11  4778.8 1053.31  4846.9 1047.07
  4887.0 1044.99  4900.4 1047.08  4937.0 1041.58  4957.8 1043.40  5023.6 1041.43
  5136.7 1040.74  5137.0 1040.24  5140.9 1040.74  5184.9 1041.55  5197.0 1043.24
  5207.0 1042.91  5212.8 1044.43  5234.4 1043.61  5292.2 1046.70  5389.8 1053.46
  5513.5 1058.07  5610.0 1065.30  5771.1 1065.86  5830.1 1064.64  5916.3 1065.96
#Mann=5,-1,0
  4061.2    0.05       0  4846.9    0.12       0  5136.7    0.07       0
  5140.9    0.12       0  5292.2    0.05       0
Bank Sta=5136.7,5140.9
Exp/Cntr=0.3,0.1

Type RM Length L Ch R = 1,2405,496,496,496
BEGIN DESCRIPTION:
Upper Denton 50 5.0
END DESCRIPTION:
XS GIS Cut Line= 3
      2199451.17      7269053.55      2198779.00      7269960.00
      2198656.87      7271284.50
#Sta/Elev= 30
  3871.2 1076.60  4034.6 1072.81  4099.3 1069.76  4227.8 1068.78  4299.6 1062.54
  4364.3 1060.22  4476.9 1052.59  4571.4 1048.18  4810.8 1039.57  4811.2 1039.07
  4815.0 1039.57  4892.2 1040.76  4977.7 1039.95  5009.7 1042.93  5049.5 1039.67
  5070.0 1039.73  5140.3 1043.86  5210.6 1050.30  5317.4 1053.97  5378.6 1056.95
  5383.6 1055.86  5441.5 1058.03  5493.3 1057.25  5592.2 1059.80  5612.3 1058.66
  5707.6 1059.48  5983.8 1066.50  6275.1 1070.33  6315.2 1073.33  6329.8 1073.14
#Mann=5,-1,0
  3871.2    0.05       0  4571.4    0.12       0  4810.8    0.07       0
  4815.0    0.12       0  5317.4    0.05       0
Bank Sta=4810.8,4815
Exp/Cntr=0.3,0.1

Type RM Length L Ch R = 1,1909,296,296,296
BEGIN DESCRIPTION:
Upper Denton 50 4.0
END DESCRIPTION:
XS GIS Cut Line= 3
      2198965.02      7268810.54      2198429.00      7269610.00
      2197840.91      7271024.06
#Sta/Elev= 30
  4037.7 1073.11  4085.2 1071.03  4278.4 1066.68  4380.4 1061.38  4410.3 1061.53
  4431.5 1059.45  4452.5 1058.78  4632.6 1054.81  4740.6 1049.54  4863.7 1040.44
  4882.6 1040.11  4882.9 1039.61  4886.8 1040.11  5275.0 1040.60  5336.0 1045.16
  5444.3 1050.74  5458.2 1052.39  5535.2 1055.53  5628.4 1061.96  5694.5 1064.98
  5725.9 1064.13  5771.5 1064.95  5819.2 1063.38  6031.7 1069.24  6126.6 1070.16
  6137.9 1071.21  6339.6 1066.76  6445.8 1067.19  6469.6 1066.30  6531.7 1068.02
#Mann=3,-1,0
  4037.7    0.05       0  4882.6   0.033       0  4886.8    0.05       0
Bank Sta=4882.6,4886.8
Exp/Cntr=0.3,0.1

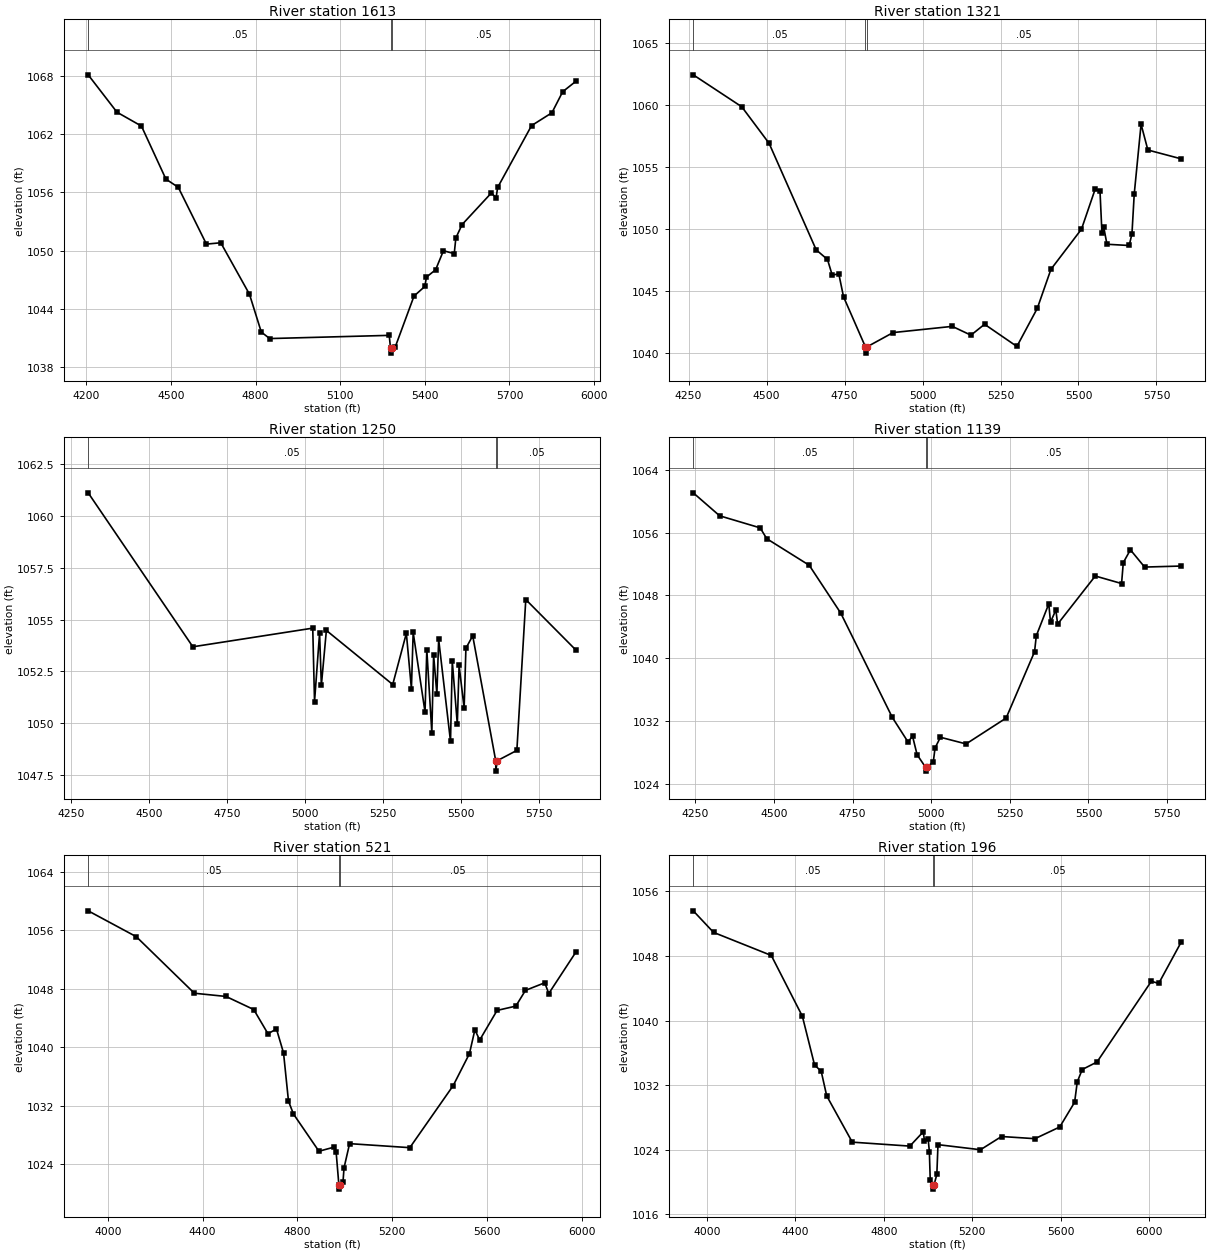
Type RM Length L Ch R = 1,1613,292,292,292
BEGIN DESCRIPTION:
Upper Denton 50 3.0
END DESCRIPTION:
XS GIS Cut Line= 3
      2198648.18      7268775.83      2198201.15      7269432.98
      2197763.37      7270259.06
#Sta/Elev= 30
  4206.1 1068.12  4308.2 1064.27  4395.0 1062.84  4481.7 1057.38  4525.6 1056.53
  4625.4 1050.68  4676.3 1050.82  4778.0 1045.52  4820.0 1041.62  4849.8 1040.95
  5273.6 1041.28  5278.3 1039.95  5278.6 1039.45  5282.6 1039.95  5295.6 1040.13
  5361.6 1045.33  5399.9 1046.32  5405.6 1047.28  5438.2 1048.04  5465.9 1050.00
  5504.2 1049.70  5509.9 1051.31  5531.9 1052.69  5636.2 1055.96  5652.5 1055.44
  5658.2 1056.52  5778.4 1062.89  5850.5 1064.21  5888.8 1066.38  5935.8 1067.46
#Mann=3,-1,0
  4206.1    0.05       0  5278.3   0.033       0  5282.6    0.05       0
Bank Sta=5278.3,5282.6
Exp/Cntr=0.3,0.1

Type RM Length L Ch R = 1,1321,71,71,71
BEGIN DESCRIPTION:
Upper Denton 50 2.5
END DESCRIPTION:
XS GIS Cut Line= 3
      2198357.38      7268672.59      2197971.98      7269266.31
      2197563.12      7270018.20
#Sta/Elev= 30
  4265.0 1062.47  4420.5 1059.89  4508.1 1056.94  4659.1 1048.34  4695.3 1047.56
  4710.5 1046.30  4731.6 1046.40  4746.7 1044.55  4817.0 1040.50  4817.4 1040.00
  4821.5 1040.50  4905.7 1041.66  5095.4 1042.16  5155.2 1041.45  5198.9 1042.33
  5302.5 1040.54  5368.0 1043.62  5411.7 1046.77  5509.6 1050.01  5553.3 1053.23
  5568.9 1053.10  5575.2 1049.69  5580.8 1050.18  5591.3 1048.79  5662.5 1048.69
  5671.4 1049.64  5678.7 1052.85  5700.6 1058.48  5722.4 1056.40  5828.7 1055.69
#Mann=3,-1,0
  4265.0    0.05       0  4817.0   0.033       0  4821.5    0.05       0
Bank Sta=4817,4821.5
Exp/Cntr=0.3,0.1

Type RM Length L Ch R = 1,1250,111,111,111
BEGIN DESCRIPTION:
Upper Denton 50 2.4
END DESCRIPTION:
XS GIS Cut Line= 3
      2198287.94      7268655.22      2197902.54      7269248.95
      2197493.39      7270001.35
#Sta/Elev= 30
  4303.7 1061.12  4639.4 1053.69  5023.9 1054.59  5029.6 1051.04  5045.8 1054.35
  5051.5 1051.83  5067.6 1054.48  5280.4 1051.87  5324.1 1054.34  5340.3 1051.67
  5346.0 1054.38  5384.0 1050.54  5389.7 1053.55  5405.8 1049.54  5411.5 1053.29
  5422.0 1051.41  5427.7 1054.05  5465.7 1049.13  5471.4 1052.99  5487.5 1049.96
  5493.2 1052.79  5509.4 1050.73  5515.1 1053.62  5536.9 1054.22  5610.7 1048.19
  5611.1 1047.69  5615.2 1048.19  5678.5 1048.69  5707.1 1055.97  5868.0 1053.53
#Mann=3,-1,0
  4303.7    0.05       0  5610.7   0.033       0  5615.2    0.05       0
Bank Sta=5610.7,5615.2
Exp/Cntr=0.3,0.1

Type RM Length L Ch R = 1,1139,618,618,618
BEGIN DESCRIPTION:
Upper Denton 50 2.0
END DESCRIPTION:
XS GIS Cut Line= 3
      2198263.62      7268606.62      2197812.26      7269200.34
      2197461.82      7269925.50
#Sta/Elev= 30
  4243.2 1061.08  4327.1 1058.15  4456.0 1056.61  4476.9 1055.23  4612.0 1051.84
  4712.2 1045.74  4876.1 1032.44  4926.0 1029.31  4940.6 1030.03  4955.1 1027.67
  4981.9 1026.08  4982.4 1025.58  4986.5 1026.08  5006.6 1026.78  5012.2 1028.54
  5029.2 1029.90  5110.8 1029.05  5238.2 1032.35  5328.6 1040.81  5334.1 1042.84
  5373.8 1046.92  5379.3 1044.59  5396.4 1046.14  5401.9 1044.33  5521.7 1050.47
  5605.3 1049.51  5610.8 1052.18  5633.4 1053.81  5678.6 1051.61  5794.4 1051.74
#Mann=3,-1,0
  4243.2    0.05       0  4981.9   0.033       0  4986.5    0.05       0
Bank Sta=4981.9,4986.5
Exp/Cntr=0.3,0.1

Type RM Length L Ch R = 1,521,325,325,325
BEGIN DESCRIPTION:
Upper Denton 50 1.0
END DESCRIPTION:
XS GIS Cut Line= 4
      2198131.73      7268391.30      2197475.45      7268724.65
      2197279.00      7269010.00      2197454.31      7269969.49
#Sta/Elev= 30
  3917.4 1058.65  4120.5 1055.11  4365.3 1047.38  4498.9 1046.94  4615.9 1045.15
  4675.9 1041.84  4711.8 1042.49  4741.6 1039.22  4762.5 1032.62  4783.5 1030.86
  4891.0 1025.77  4956.6 1026.35  4963.5 1025.66  4975.3 1021.09  4975.7 1020.59
  4979.9 1021.09  4992.5 1021.60  4996.9 1023.51  5020.3 1026.81  5274.4 1026.26
  5457.4 1034.75  5526.0 1039.12  5548.9 1042.38  5569.2 1040.98  5642.6 1045.03
  5721.7 1045.62  5762.3 1047.77  5843.7 1048.81  5860.6 1047.34  5975.3 1053.02
#Mann=3,-1,0
  3917.4    0.05       0  4975.3   0.033       0  4979.9    0.05       0
Bank Sta=4975.3,4979.9
Exp/Cntr=0.3,0.1

Type RM Length L Ch R = 1,196,0,0,0
BEGIN DESCRIPTION:
Upper Denton 50 0.5
END DESCRIPTION:
XS GIS Cut Line= 5
      2197916.01      7268471.30      2197047.91      7268797.71
      2196980.39      7268926.67      2196957.64      7269026.87
      2197415.95      7269950.45
#Sta/Elev= 30
  3937.8 1053.60  4029.5 1050.93  4290.9 1048.07  4431.4 1040.54  4486.5 1034.51
  4516.7 1033.71  4541.6 1030.67  4657.2 1024.94  4917.7 1024.45  4978.3 1026.22
  4983.9 1025.12  5000.3 1025.39  5006.0 1023.78  5009.9 1020.30  5022.2 1019.62
  5022.6 1019.12  5026.8 1019.62  5039.8 1020.94  5045.0 1024.63  5237.3 1024.00
  5332.5 1025.64  5483.8 1025.37  5595.9 1026.82  5663.1 1029.88  5675.2 1032.41
  5697.6 1033.94  5764.5 1034.87  6010.5 1044.88  6043.6 1044.60  6144.6 1049.69
#Mann=3,-1,0
  3937.8    0.05       0  5022.2   0.033       0  5026.8    0.05       0
Bank Sta=5022.2,5026.8
Exp/Cntr=0.3,0.1

Chan Stop Cuts=-1