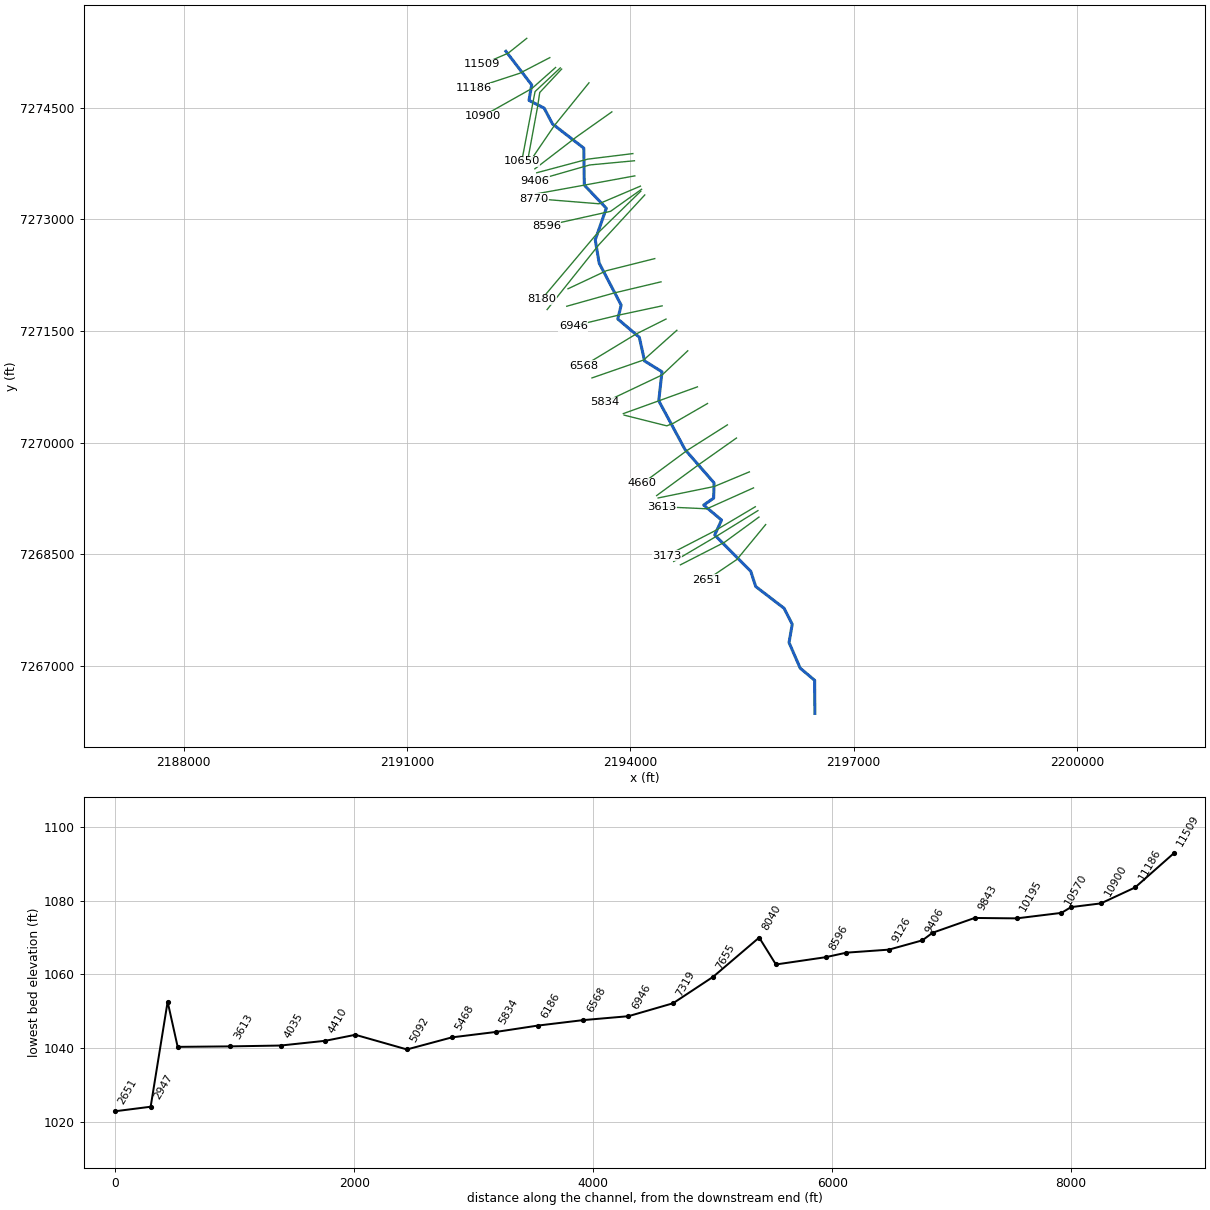
--- Upper Denton 51.prj (project) ---

Proj Title=Upper Denton 51 Base Level Engineering
Current Plan=p01
Default Exp/Contr=0.3,0.1
English Units
Geom File=g01
Flow File=f01
Plan File=p01
Y Axis Title=Elevation
X Axis Title(PF)=Main Channel Distance
X Axis Title(XS)=Station
BEGIN DESCRIPTION:
Upper Denton 51
END DESCRIPTION:
DSS Export Rating Curves= 0
DSS Export Rating Curve Sorted= 0
DSS Export Volume Flow Curves= 0
DXF OffsetX= 0
DXF OffsetY= 0
DXF ScaleX= 1
DXF ScaleY= 10

--- Upper Denton 51.p01 (plan) ---

Plan Title=Multiple Run
Short Identifier=Multiple
Geom File=g01
Flow File=f01
Subcritical Flow
K Sum by GR= 0
Std Step Tol= 0.01
Critical Tol= 0.01
Num of Std Step Trials= 20
Max Error Tol= 0.3
Flow Tol Ratio= 0.001
Split Flow NTrial= 30
Split Flow Tol= 0.02
Split Flow Ratio= 0.02
Log Output Level= 0
Friction Slope Method= 1
Unsteady Friction Slope Method= 2
Unsteady Bridges Friction Slope Method= 1
Parabolic Critical Depth
Global Vel Dist=  1 , 1 , 1
Global Log Level= 0
CheckData=True
Encroach Param= -1, 0, 0, 0
BEGIN DESCRIPTION:
Multiple Run
END DESCRIPTION:

--- Upper Denton 51.f01 (steady flow) ---

Flow Title=Multiple
Program Version=4.10
Number of Profiles= 7
Profile Names=10-year,25-year,50-year,1pct_min,100-year,1pct_plu,500-year
River Rch & RM=Upper Denton 51,Reach-1         ,11509
     567     776     948     576    1148    2291    1688
River Rch & RM=Upper Denton 51,Reach-1         ,3613
     616     847    1038     632    1261    2515    1863
Boundary for River Rch & Prof#=Upper Denton 51,Reach-1         , 1
Up Type= 0
Dn Type= 3
Dn Slope=0.0009
Boundary for River Rch & Prof#=Upper Denton 51,Reach-1         , 2
Up Type= 0
Dn Type= 3
Dn Slope=0.0009
Boundary for River Rch & Prof#=Upper Denton 51,Reach-1         , 3
Up Type= 0
Dn Type= 3
Dn Slope=0.0009
Boundary for River Rch & Prof#=Upper Denton 51,Reach-1         , 4
Up Type= 0
Dn Type= 3
Dn Slope=0.0009
Boundary for River Rch & Prof#=Upper Denton 51,Reach-1         , 5
Up Type= 0
Dn Type= 3
Dn Slope=0.0009
Boundary for River Rch & Prof#=Upper Denton 51,Reach-1         , 6
Up Type= 0
Dn Type= 3
Dn Slope=0.0009
Boundary for River Rch & Prof#=Upper Denton 51,Reach-1         , 7
Up Type= 0
Dn Type= 3
Dn Slope=0.0009
DSS Import GetInterval= 0
DSS Import GetPeak= 0
DSS Import FillOption= 0

--- Upper Denton 51.g01 (geometry) ---

Geom Title=Existing Conditions
Program Version=4.10

River Reach=Upper Denton 51 ,Reach-1
Reach XY= 30
        2192329.        7275260.      2192675.54      7274808.51
      2192639.18      7274600.29      2192842.66      7274496.74
      2192955.29      7274283.18      2193375.18      7273958.42
      2193382.44      7273461.25      2193678.03       7273149.7
      2193529.38      7272725.27      2193582.55      7272411.47
      2193877.47      7271848.12      2193832.04      7271661.42
      2194121.14      7271416.17      2194192.37      7271096.68
      2194426.07      7270952.03      2194382.54      7270561.47
      2194737.14      7269903.94      2195125.32      7269458.41
      2195119.82      7269253.05      2194985.98      7269160.21
      2195225.99      7268958.57      2195134.06       7268757.7
      2195618.48      7268269.79      2195684.58      7268065.58
      2196065.38      7267773.21      2196175.33      7267558.42
      2196132.67      7267311.58      2196282.38      7266968.15
      2196476.86      7266804.04        2196479.        7266360.

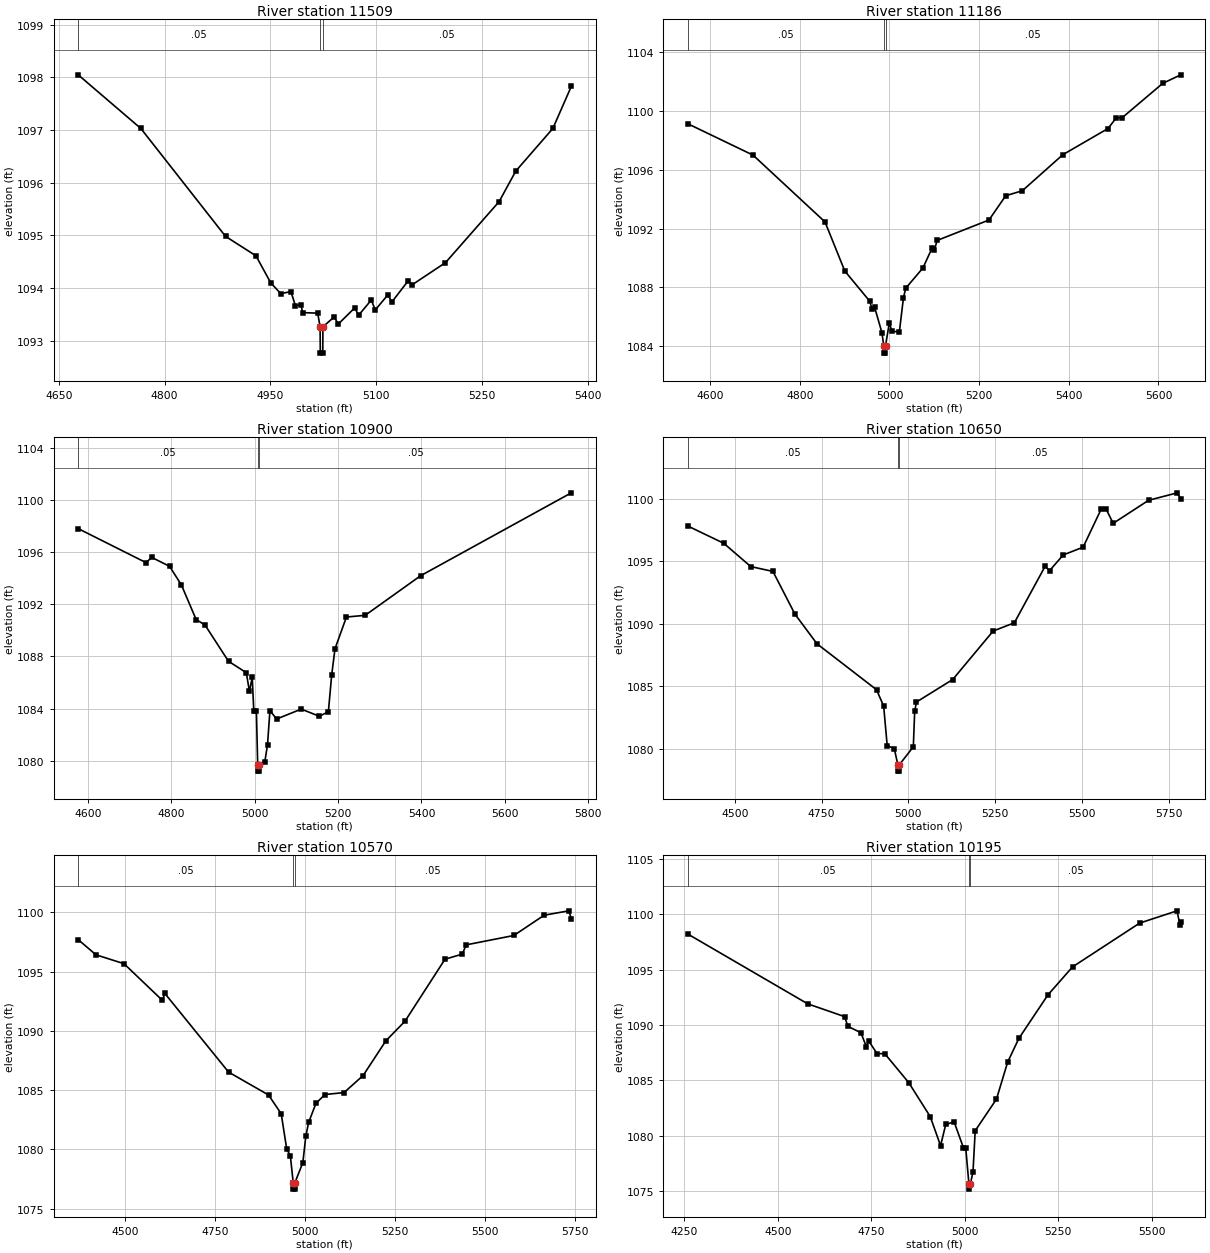
Type RM Length L Ch R = 1 ,11509   ,323,323,323
BEGIN DESCRIPTION:
Upper Denton 51 27.5
END DESCRIPTION:
XS GIS Cut Line= 3
      2192609.18      7275433.93      2192359.21      7275233.96
      2192010.41      7275084.47
#Sta/Elev= 30
  4677.3 1098.05  4766.2 1097.03  4886.3 1094.98  4929.5 1094.61  4950.3  1094.1
  4964.7 1093.89  4979.1 1093.93  4985.5 1093.66  4993.5 1093.68  4995.7 1093.53
  5017.1 1093.52  5020.5 1093.26  5020.8 1092.76  5024.3 1092.76  5024.5 1093.26
  5040.6 1093.45  5046.1 1093.31  5069.6 1093.62  5075.1 1093.48  5093.2 1093.77
  5098.7 1093.58  5116.8 1093.87  5122.2 1093.73  5145.8 1094.14  5151.2 1094.06
  5198.4 1094.48  5274.5 1095.64  5298.1 1096.22  5350.7 1097.03  5376.9 1097.83
#Mann= 3 ,-1 , 0
  4677.3     .05       0  5020.5    .033       0  5024.5     .05       0
Bank Sta=5020.5,5024.5
XS Rating Curve= 0 ,0
Exp/Cntr=0.3,0.1

Type RM Length L Ch R = 1 ,11186   ,286,286,286
BEGIN DESCRIPTION:
Upper Denton 51 27.0
END DESCRIPTION:
XS GIS Cut Line= 3
      2192919.06      7275174.54      2192512.82      7274963.61
      2191902.39      7274763.59
#Sta/Elev= 30
  4549.7 1099.13  4695.6 1096.99  4856.1 1092.45  4900.3 1089.11  4955.4 1087.08
    4961 1086.56  4966.7 1086.66  4983.1 1084.92  4987.2 1084.03  4987.5 1083.53
    4991 1083.53  4991.2 1084.03  4999.6  1085.6  5005.3 1085.02    5022 1084.97
  5031.2 1087.31  5036.4 1087.95  5074.6 1089.32  5094.8 1090.66  5100.1 1090.53
  5106.2 1091.19  5221.9 1092.58  5259.3 1094.23  5296.4 1094.57  5386.7 1097.02
  5487.5  1098.8    5506 1099.53  5519.3 1099.54  5609.6 1101.87  5649.8 1102.45
#Mann= 3 ,-1 , 0
  4549.7     .05       0  4987.2    .033       0  4991.2     .05       0
Bank Sta=4987.2,4991.2
XS Rating Curve= 0 ,0
Exp/Cntr=0.3,0.1

Type RM Length L Ch R = 1 ,10900   ,250,250,250
BEGIN DESCRIPTION:
Upper Denton 51 26.0
END DESCRIPTION:
XS GIS Cut Line= 3
      2192996.48      7275041.95        2192679.        7274760.
      2192018.06       7274388.1
#Sta/Elev= 30
  4576.5 1097.79  4738.9 1095.19  4753.2 1095.58  4795.8  1094.9  4824.2 1093.47
  4859.4 1090.83  4880.7 1090.41  4937.1 1087.63  4979.8 1086.76  4987.3 1085.33
    4994  1086.4  4997.8 1083.82    5004 1083.82  5007.1 1079.72  5007.3 1079.22
  5010.8 1079.22  5011.1 1079.72  5024.1 1079.91  5030.7 1081.25  5036.5 1083.86
  5052.4 1083.21  5111.7 1083.97    5155 1083.42  5176.7 1083.77  5184.7  1086.6
  5192.6 1088.59    5220 1091.02    5265 1091.15  5397.9 1094.18  5759.5 1100.53
#Mann= 3 ,-1 , 0
  4576.5     .05       0  5007.1    .033       0  5011.1     .05       0
Bank Sta=5007.1,5011.1
XS Rating Curve= 0 ,0
Exp/Cntr=0.3,0.1

Type RM Length L Ch R = 1 ,10650   ,80,80,80
BEGIN DESCRIPTION:
Upper Denton 51 25.5
END DESCRIPTION:
XS GIS Cut Line= 4
       2193059.7      7275036.53      2192721.16      7274718.82
      2192685.25      7274536.04      2192541.47      7273778.71
#Sta/Elev= 30
  4363.9 1097.83  4468.1 1096.44  4545.7 1094.58  4609.7 1094.19  4673.2 1090.77
  4736.7  1088.4  4908.5 1084.72  4928.9 1083.41  4939.1 1080.25  4959.5 1080.01
  4969.9 1078.71  4970.1 1078.21  4973.6 1078.21  4973.9 1078.71  5014.4 1080.16
  5018.3 1082.99  5023.4 1083.74  5127.9 1085.54  5244.5 1089.42  5305.6 1090.08
  5394.3  1094.6  5407.4 1094.26  5446.5 1095.51  5503.9 1096.13  5556.1 1099.19
  5570.2 1099.17  5590.6 1098.04  5692.4 1099.88  5775.3 1100.48  5785.3 1100.01
#Mann= 3 ,-1 , 0
  4363.9     .05       0  4969.9    .033       0  4973.9     .05       0
Bank Sta=4969.9,4973.9
XS Rating Curve= 0 ,0
Exp/Cntr=0.3,0.1

Type RM Length L Ch R = 1 ,10570   ,375,375,375
BEGIN DESCRIPTION:
Upper Denton 51 25.0
END DESCRIPTION:
XS GIS Cut Line= 4
      2193077.95      7275020.92      2192783.66      7274705.79
      2192755.01      7274515.69      2192619.94      7273783.17
#Sta/Elev= 30
  4370.7 1097.69  4420.1 1096.41  4497.8 1095.66  4604.3 1092.57  4611.2 1093.15
    4788 1086.52  4898.8 1084.59    4934 1083.01  4949.3 1080.04  4959.4 1079.46
  4967.5 1077.15  4967.8 1076.65  4971.3 1076.65  4971.5 1077.15  4994.1 1078.89
  5002.3 1081.12  5010.1 1082.27  5030.4 1083.88  5055.3 1084.63  5108.3 1084.79
  5161.3 1086.23  5224.5 1089.16  5277.5 1090.81  5388.6 1096.04  5436.5 1096.47
  5447.3 1097.25  5579.5 1098.04  5663.7 1099.75  5732.1 1100.12    5739 1099.44
#Mann= 3 ,-1 , 0
  4370.7     .05       0  4967.5    .033       0  4971.5     .05       0
Bank Sta=4967.5,4971.5
XS Rating Curve= 0 ,0
Exp/Cntr=0.3,0.1

Type RM Length L Ch R = 1 ,10195   ,352,352,352
BEGIN DESCRIPTION:
Upper Denton 51 24.0
END DESCRIPTION:
XS GIS Cut Line= 3
      2193445.12        7274836.        2192979.        7274260.
      2192653.71      7273781.71
#Sta/Elev= 30
  4258.8 1098.23  4580.1 1091.91  4679.2 1090.75  4687.2 1089.88  4722.4  1089.3
  4736.8 1088.04  4743.2 1088.56  4765.5 1087.41  4786.3  1087.4  4850.3 1084.79
  4907.8 1081.72  4935.5 1079.09  4949.4 1081.01  4971.8 1081.24  4996.6 1078.91
  5002.8 1078.91  5011.3 1075.66  5011.5 1075.16  5015.3 1075.66  5022.2 1076.68
  5028.2 1080.44  5085.1  1083.3    5115 1086.64  5144.9 1088.78  5222.8 1092.72
  5288.6 1095.25  5468.2 1099.21  5568.2 1100.32    5576 1099.05  5578.2 1099.29
#Mann= 3 ,-1 , 0
  4258.8     .05       0  5011.3     .04       0  5015.3     .05       0
Bank Sta=5011.3,5015.3
XS Rating Curve= 0 ,0
Exp/Cntr=0.3,0.1

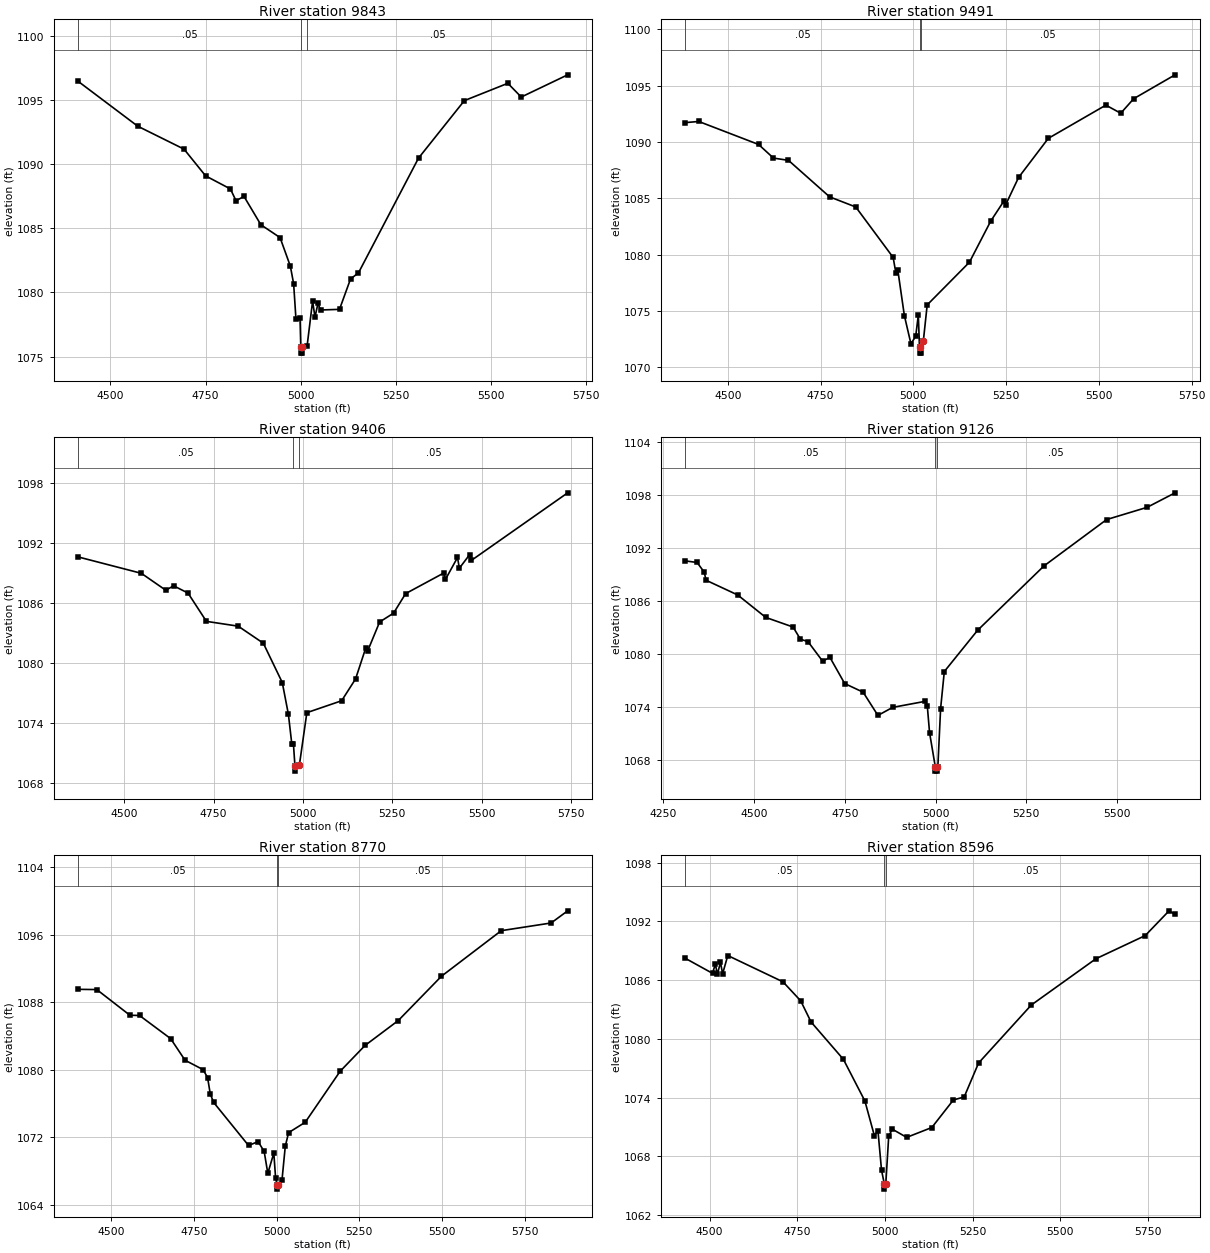
Type RM Length L Ch R = 1 ,9843    ,352,352,352
BEGIN DESCRIPTION:
Upper Denton 51 23.0
END DESCRIPTION:
XS GIS Cut Line= 3
      2193752.37      7274445.35        2193279.        7274110.
      2192718.53      7273679.73
#Sta/Elev= 30
  4414.9 1096.45  4571.7 1092.95  4693.5 1091.16  4750.1 1089.08  4815.3 1088.06
  4830.1 1087.14    4851 1087.48  4895.4 1085.27  4945.8 1084.27  4972.9 1082.04
  4981.5 1080.67  4987.6 1077.91  4998.2 1078.03  5000.3 1075.77  5000.5 1075.27
    5004 1075.27  5004.3 1075.77  5016.8 1075.81  5031.3 1079.32  5037.6 1078.07
  5045.4 1079.15  5052.1 1078.63    5102 1078.68    5131 1081.05  5151.8 1081.52
  5309.6 1090.46  5430.1 1094.94  5544.3 1096.29  5579.6 1095.22  5701.6 1096.95
#Mann= 3 ,-1 , 0
  4414.9     .05       0  5000.3    .033       0  5016.8     .05       0
Bank Sta=5000.3,5004.3
XS Rating Curve= 0 ,0
Exp/Cntr=0.3,0.1

Type RM Length L Ch R = 1 ,9491    ,85,85,85
BEGIN DESCRIPTION:
Upper Denton 51 22.0
END DESCRIPTION:
XS GIS Cut Line= 3
      2194034.76      7273884.62        2193429.        7273810.
      2192743.57      7273626.93
#Sta/Elev= 30
  4385.5 1091.72  4421.5 1091.82  4582.7 1089.78  4622.9 1088.57  4663.3 1088.37
  4774.2 1085.13  4844.7 1084.23  4945.5 1079.75  4952.7 1078.38  4957.8 1078.68
  4975.7 1074.59  4993.3  1072.1  5006.2 1072.74  5013.3 1074.65  5016.5 1071.76
  5016.7 1071.26  5020.2 1071.26  5020.5 1071.76  5026.9 1072.36  5037.2 1075.54
  5151.1 1079.33  5208.5 1082.98  5243.4 1084.73  5248.6 1084.42  5283.5 1086.85
  5363.6 1090.32  5518.8 1093.27  5558.9 1092.55  5593.8 1093.84  5705.3 1095.96
#Mann= 3 ,-1 , 0
  4385.5     .05       0  5016.5    .033       0  5020.5     .05       0
Bank Sta=5016.5,5026.9
XS Rating Curve= 0 ,0
Exp/Cntr=0.3,0.1

Type RM Length L Ch R = 1 ,9406    ,280,280,280
BEGIN DESCRIPTION:
Upper Denton 51 21.5
END DESCRIPTION:
XS GIS Cut Line= 3
      2194055.56      7273788.26      2193455.04      7273731.88
        2192717.      7273520.02
#Sta/Elev= 30
  4370.2 1090.61  4547.5 1088.97  4615.9 1087.28  4637.9 1087.72  4678.1    1087
  4729.7 1084.17  4818.7 1083.69    4889 1081.99  4942.1 1078.06  4959.3 1074.87
  4968.9 1071.88  4973.4 1071.88  4977.6 1069.71  4977.9 1069.21    4990 1069.82
  5010.9 1075.05  5108.3 1076.24  5147.3 1078.42  5175.8 1081.51    5181  1081.2
  5214.7 1084.11  5253.7 1084.99  5287.4 1086.94  5393.8 1088.99    5399 1088.36
  5432.7 1090.55  5437.9 1089.48  5466.4 1090.82  5471.6 1090.26  5741.2 1097.01
#Mann= 3 ,-1 , 0
  4370.2     .05       0  4973.4    .033       0    4990     .05       0
Bank Sta=4977.6,4990
XS Rating Curve= 0 ,0
Exp/Cntr=0.3,0.1

Type RM Length L Ch R = 1 ,9126    ,356,356,356
BEGIN DESCRIPTION:
Upper Denton 51 21.0
END DESCRIPTION:
XS GIS Cut Line= 3
      2194060.79      7273585.14        2193379.        7273460.
      2192733.28      7273343.06
#Sta/Elev= 30
  4310.6  1090.5  4342.9 1090.32  4362.5 1089.22  4367.5 1088.31  4454.8 1086.64
    4532  1084.1  4607.3 1083.01  4627.6 1081.63  4648.4 1081.36  4688.6 1079.15
  4708.9 1079.57  4749.5 1076.61  4800.4 1075.63  4841.1    1073  4881.8 1073.91
  4972.1  1074.6  4977.2 1074.08  4983.4 1071.06  4999.2 1067.19  4999.5 1066.69
    5003 1066.69  5003.2 1067.19  5006.3 1067.19  5013.9 1073.78  5024.1 1077.97
  5115.6 1082.63  5298.5 1089.92  5471.3 1095.18  5583.1 1096.57    5660 1098.21
#Mann= 3 ,-1 , 0
  4310.6     .05       0  4999.2     .04       0  5003.2     .05       0
Bank Sta=4999.2,5003.2
XS Rating Curve= 0 ,0
Exp/Cntr=0.3,0.1

Type RM Length L Ch R = 1 ,8770    ,174,174,174
BEGIN DESCRIPTION:
Upper Denton 51 20.0
END DESCRIPTION:
XS GIS Cut Line= 3
       2194136.3      7273447.11        2193579.        7273210.
      2192709.19      7273280.45
#Sta/Elev= 30
  4400.7 1089.54  4457.4 1089.51  4557.3 1086.47  4586.4 1086.44  4680.3  1083.7
  4723.8 1081.14  4778.1 1080.03  4791.8 1079.09  4799.9 1077.16    4810 1076.15
  4915.5 1071.04  4944.5  1071.5  4962.7 1070.33  4973.7 1067.74  4991.8 1070.14
  4997.2 1067.19  5001.6 1066.37  5001.9 1065.87  5005.6 1066.37  5016.4  1066.9
  5026.4 1070.94  5036.4 1072.56  5086.6 1073.79    5192 1079.83  5267.2 1082.89
  5367.5 1085.84  5497.9 1091.09  5678.5 1096.49    5829  1097.4    5879 1098.84
#Mann= 3 ,-1 , 0
  4400.7     .05       0  5001.6     .04       0  5005.6     .05       0
Bank Sta=5001.6,5005.6
XS Rating Curve= 0 ,0
Exp/Cntr=0.3,0.1

Type RM Length L Ch R = 1 ,8596    ,416,416,416
BEGIN DESCRIPTION:
Upper Denton 51 19.0
END DESCRIPTION:
XS GIS Cut Line= 3
      2194151.92      7273405.44      2193735.26      7273108.57
      2192872.34      7272916.24
#Sta/Elev= 30
  4431.3 1088.23  4508.6  1086.7  4516.5 1087.64  4522.6 1086.62  4531.2 1087.82
  4537.4 1086.66  4552.1 1088.52  4709.5 1085.83  4759.9 1083.89  4789.4 1081.73
  4881.6 1077.91  4942.9 1073.65  4969.8 1070.12  4980.1 1070.62  4990.3 1066.59
  4998.4 1065.14  4998.6 1064.64  5002.4 1065.14  5010.8 1070.05    5021 1070.77
    5062 1069.93  5133.7 1070.94  5195.2 1073.76  5225.9 1074.06  5266.9 1077.53
  5417.2 1083.46  5601.4 1088.19    5742 1090.56  5809.9 1093.09    5827 1092.72
#Mann= 3 ,-1 , 0
  4431.3     .05       0  4998.4    .033       0  5002.4     .05       0
Bank Sta=4998.4,5002.4
XS Rating Curve= 0 ,0
Exp/Cntr=0.3,0.1

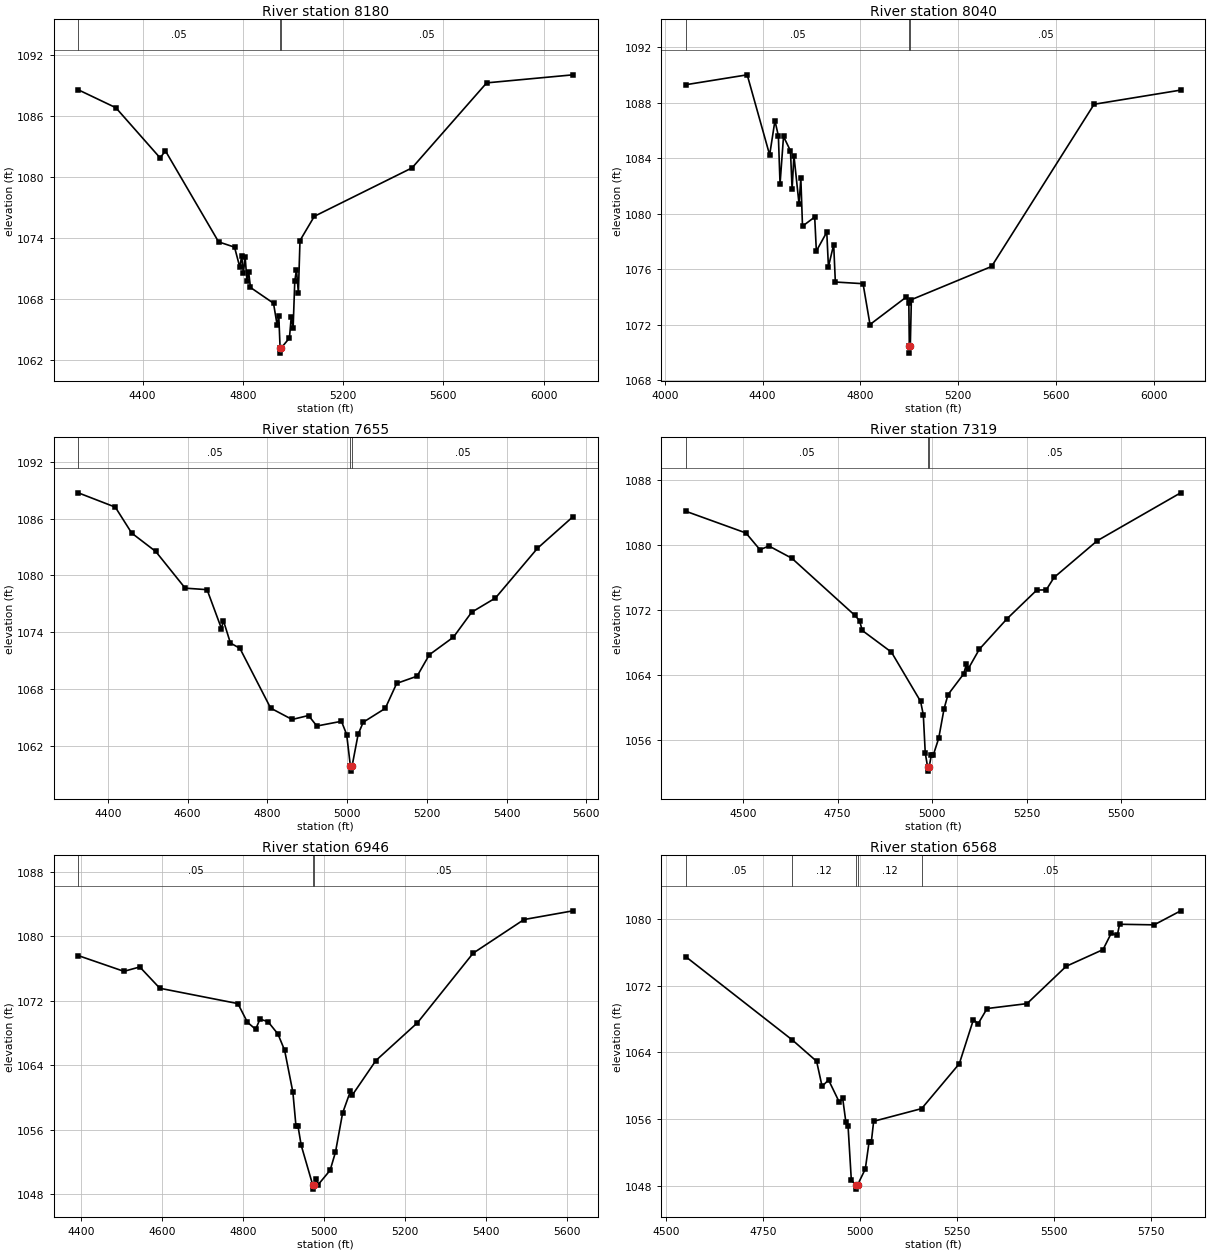
Type RM Length L Ch R = 1 ,8180    ,140,140,140
BEGIN DESCRIPTION:
Upper Denton 51 18.5
END DESCRIPTION:
XS GIS Cut Line= 3
      2194141.54      7273379.44      2193532.13        7272785.
      2192808.17      7271926.27
#Sta/Elev= 30
    4143 1088.54  4292.9 1086.78  4469.6 1081.85  4490.9 1082.54  4703.1  1073.6
  4766.7 1073.08    4788 1071.09    4795 1072.23  4802.1 1070.58  4809.1 1072.09
  4816.3 1069.78  4823.3  1070.6  4830.4 1069.12  4922.3 1067.57  4936.4 1065.48
  4943.4 1066.29  4948.6 1063.17  4948.8 1062.67  4952.6 1063.17  4985.8 1064.15
    4993 1066.19  5000.6 1065.16  5007.2 1069.76  5013.9 1070.87  5021.5 1068.59
    5028 1073.73  5085.2 1076.11  5475.3 1080.87  5773.1 1089.22  6117.5 1090.01
#Mann= 3 ,-1 , 0
    4143     .05       0  4948.6    .033       0  4952.6     .05       0
Bank Sta=4948.6,4952.6
XS Rating Curve= 0 ,0
Exp/Cntr=0.3,0.1

Type RM Length L Ch R = 1 ,8040    ,385,385,385
BEGIN DESCRIPTION:
Upper Denton 51 18.0
END DESCRIPTION:
XS GIS Cut Line= 3
       2194194.4      7273328.41        2193579.        7272660.
      2192882.99      7271788.11
#Sta/Elev= 30
  4086.6 1089.29    4337    1090  4428.9 1084.23  4450.5  1086.7  4464.6  1085.6
  4471.4 1082.14  4485.6 1085.56    4514 1084.53  4520.8 1081.77  4528.2 1084.19
  4549.1  1080.7  4556.5 1082.54  4563.3  1079.1  4613.2 1079.76    4620 1077.31
  4662.6 1078.67  4669.4 1076.18  4690.9 1077.78  4697.7 1075.08  4811.1 1074.96
  4839.5 1072.02  4988.1    1074  4998.4 1073.54  5000.4 1070.46  5000.6 1069.96
  5004.4 1070.46  5008.8 1073.81    5337  1076.2  5756.5 1087.88  6110.8  1088.9
#Mann= 3 ,-1 , 0
  4086.6     .05       0  5000.4    .033       0  5004.4     .05       0
Bank Sta=5000.4,5004.4
XS Rating Curve= 0 ,0
Exp/Cntr=0.3,0.1

Type RM Length L Ch R = 1 ,7655    ,336,336,336
BEGIN DESCRIPTION:
Upper Denton 51 17.0
END DESCRIPTION:
XS GIS Cut Line= 3
      2194328.97      7272473.15        2193679.        7272310.
      2193163.18       7272067.3
#Sta/Elev= 30
    4326 1088.71  4418.8  1087.2    4460 1084.46  4520.2 1082.52    4594 1078.65
  4648.9 1078.49  4684.9 1074.39    4690 1075.21  4707.4 1072.86  4731.2  1072.3
  4808.3 1065.99  4862.1 1064.79  4903.3 1065.21    4924  1064.1  4985.8  1064.6
  4998.9  1063.2  5008.3 1059.84  5008.5 1059.34  5012.3 1059.84  5027.6 1063.22
  5040.3  1064.5  5095.6 1065.96  5124.3  1068.6  5175.4 1069.36  5206.1 1071.62
  5266.6 1073.48  5312.2 1076.11  5371.9 1077.61  5477.3 1082.86  5566.2 1086.19
#Mann= 3 ,-1 , 0
    4326     .05       0  5008.3    .033       0  5012.3     .05       0
Bank Sta=5008.3,5012.3
XS Rating Curve= 0 ,0
Exp/Cntr=0.3,0.1

Type RM Length L Ch R = 1 ,7319    ,373,373,373
BEGIN DESCRIPTION:
Upper Denton 51 16.0
END DESCRIPTION:
XS GIS Cut Line= 3
      2194412.38      7272160.66        2193779.        7272010.
      2193146.69      7271832.52
#Sta/Elev= 30
  4349.3 1084.17  4507.8  1081.5  4544.8 1079.44  4568.6  1079.9  4629.1 1078.39
  4794.8 1071.39    4808 1070.71  4815.3 1069.49  4892.4 1066.82  4969.5 1060.75
  4976.7 1059.09  4981.8  1054.4  4988.1 1052.66  4988.3 1052.16  4992.1 1052.66
  4997.8 1054.13    5003 1054.13  5017.4 1056.21  5031.5 1059.83  5041.9 1061.58
  5083.4 1064.14  5090.8 1065.37  5095.9  1064.8  5124.8 1067.18  5197.7 1070.92
  5276.7 1074.47  5301.6 1074.49  5322.3 1076.02  5436.6 1080.55  5657.1 1086.45
#Mann= 3 ,-1 , 0
  4349.3     .05       0  4988.1    .033       0  4992.1     .05       0
Bank Sta=4988.1,4992.1
XS Rating Curve= 0 ,0
Exp/Cntr=0.3,0.1

Type RM Length L Ch R = 1 ,6946    ,378,378,378
BEGIN DESCRIPTION:
Upper Denton 51 15.0
END DESCRIPTION:
XS GIS Cut Line= 3
        2194428.      7271837.75        2193829.        7271710.
      2193235.27      7271566.91
#Sta/Elev= 30
  4392.4 1077.61  4505.2 1075.66  4544.5  1076.2  4594.1 1073.56  4787.1 1071.66
  4810.6 1069.35    4831 1068.47  4841.7 1069.74  4861.7 1069.41  4886.1 1067.89
  4902.6 1065.88  4923.1 1060.66  4930.6 1056.53  4935.7 1056.48  4943.5 1054.12
  4972.2 1049.16  4972.4 1048.66  4976.2 1049.16  4980.1 1049.92  4985.2 1049.19
  5015.2    1051  5028.4 1053.25    5046 1058.09  5065.2 1060.78  5070.3 1060.34
  5128.3  1064.6  5231.2 1069.29  5368.8 1077.91  5494.6 1082.08  5615.6 1083.16
#Mann= 3 ,-1 , 0
  4392.4     .05       0  4972.2    .033       0  4976.2     .05       0
Bank Sta=4972.2,4976.2
XS Rating Curve= 0 ,0
Exp/Cntr=0.3,0.1

Type RM Length L Ch R = 1 ,6568    ,382,382,382
BEGIN DESCRIPTION:
Upper Denton 51 14.0
END DESCRIPTION:
XS GIS Cut Line= 3
      2194480.07      7271660.66        2194079.        7271460.
      2193372.35      7271031.46
#Sta/Elev= 30
  4551.8 1075.43  4825.9 1065.47  4888.4 1062.92  4902.5 1059.92  4919.2 1060.68
  4947.2 1057.99  4955.5 1058.52  4963.9  1055.6  4969.5 1055.12  4977.9 1048.66
  4989.9  1048.1  4990.1  1047.6  4993.9  1048.1  5013.9 1050.01  5023.5 1053.22
  5029.4 1053.24  5035.4 1055.73  5159.1 1057.25  5256.2 1062.63  5292.6 1067.92
  5304.7 1067.42  5327.7 1069.24  5430.7 1069.83  5531.5  1074.3  5626.5  1076.3
  5647.8 1078.27  5663.3 1078.01  5669.2 1079.34  5758.3 1079.27  5826.7 1080.95
#Mann= 5 ,-1 , 0
  4551.8     .05       0  4825.9     .12       0  4989.9     .07       0
  4993.9     .12       0  5159.1     .05       0
Bank Sta=4989.9,4993.9
XS Rating Curve= 0 ,0
Exp/Cntr=0.3,0.1

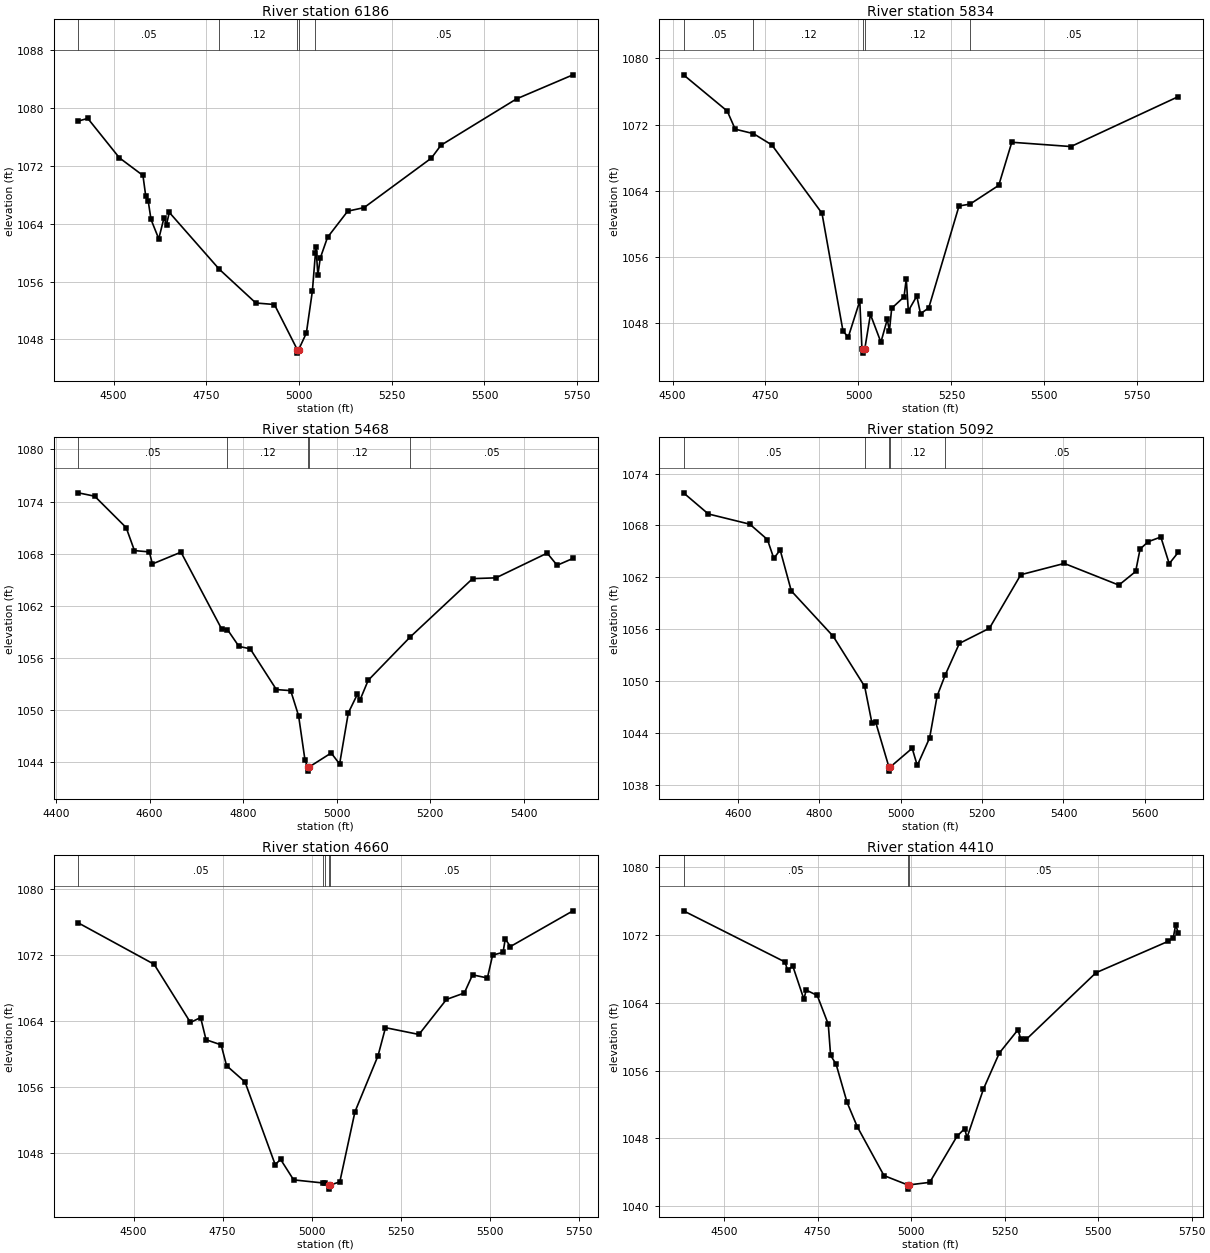
Type RM Length L Ch R = 1 ,6186    ,352,352,352
BEGIN DESCRIPTION:
Upper Denton 51 13.0
END DESCRIPTION:
XS GIS Cut Line= 3
      2194625.86      7271509.59        2194179.        7271110.
      2193485.24      7270868.98
#Sta/Elev= 30
  4404.7 1078.23  4430.3  1078.6  4515.6 1073.14  4579.1  1070.7  4586.6 1067.85
  4593.3 1067.16  4600.8 1064.61  4621.7 1061.93  4635.9 1064.85  4642.6  1063.9
  4650.1 1065.59  4784.9 1057.72  4883.4 1053.05  4933.5 1052.84  4995.1 1046.61
  4995.3 1046.11  4999.1 1046.61  5019.7 1048.89  5035.9 1054.68  5044.2 1059.97
  5045.5  1060.8  5050.8 1056.92  5057.1 1059.25  5076.7 1062.13  5131.2 1065.76
  5175.3 1066.25  5356.7  1073.1  5382.5 1074.88  5586.4  1081.3  5738.6 1084.63
#Mann= 5 ,-1 , 0
  4404.7     .05       0  4784.9     .12       0  4995.1     .07       0
  4999.1     .12       0  5044.2     .05       0
Bank Sta=4995.1,4999.1
XS Rating Curve= 0 ,0
Exp/Cntr=0.3,0.1

Type RM Length L Ch R = 1 ,5834    ,366,366,366
BEGIN DESCRIPTION:
Upper Denton 51 12.0
END DESCRIPTION:
XS GIS Cut Line= 3
      2194771.73      7271233.58        2194429.        7270910.
      2193652.96      7270541.35
#Sta/Elev= 30
  4529.5 1078.02  4647.1 1073.64  4668.5 1071.45  4717.7 1070.91  4767.2 1069.54
  4901.9 1061.29  4958.6 1047.01  4972.7 1046.33  5003.6 1050.69  5009.4 1044.91
    5013 1044.88  5013.2 1044.38    5017 1044.88  5032.2 1049.06  5060.4  1045.7
  5077.6 1048.47  5083.2 1047.04  5089.4  1049.8  5122.6 1051.18  5128.6 1053.37
  5134.1 1049.48  5156.9 1051.28  5166.9 1049.14  5189.1 1049.85  5270.5 1062.17
    5300 1062.39  5377.3 1064.66  5412.4 1069.87  5571.4 1069.35    5860 1075.38
#Mann= 5 ,-1 , 0
  4529.5     .05       0  4717.7     .12       0    5013     .07       0
    5017     .12       0    5300     .05       0
Bank Sta=5013,5017
XS Rating Curve= 0 ,0
Exp/Cntr=0.3,0.1

Type RM Length L Ch R = 1 ,5468    ,376,376,376
BEGIN DESCRIPTION:
Upper Denton 51 11.0
END DESCRIPTION:
XS GIS Cut Line= 3
      2194901.97      7270749.21        2194379.        7270560.
       2193907.1      7270389.81
#Sta/Elev= 30
  4447.7    1075  4482.8 1074.61  4550.1 1070.99  4567.8 1068.34  4599.7 1068.19
  4606.1  1066.8  4667.3 1068.16    4754 1059.33  4766.7 1059.23  4791.2  1057.3
  4815.3 1057.02  4871.3 1052.32  4901.9  1052.2  4918.8  1049.3  4932.5 1044.18
    4938 1043.42  4938.3 1042.92    4942 1043.42  4988.5 1045.01  5006.5 1043.74
  5025.1 1049.63  5044.6 1051.79  5049.9 1051.09  5067.6 1053.39  5157.4 1058.38
  5290.9 1065.11  5340.8  1065.2  5450.3 1068.05  5471.6 1066.65  5505.5 1067.44
#Mann= 5 ,-1 , 0
  4447.7     .05       0  4766.7     .12       0    4938     .07       0
    4942     .12       0  5157.4     .05       0
Bank Sta=4938,4942
XS Rating Curve= 0 ,0
Exp/Cntr=0.3,0.1

Type RM Length L Ch R = 1 ,5092    ,432,432,432
BEGIN DESCRIPTION:
Upper Denton 51 10.0
END DESCRIPTION:
XS GIS Cut Line= 4
      2195037.35      7270525.24        2194579.        7270260.
      2194489.72      7270225.08      2193917.57      7270368.98
#Sta/Elev= 30
  4466.5 1071.77  4527.5 1069.33  4629.4 1068.15  4672.6 1066.38  4688.3 1064.21
    4704 1065.17  4731.3 1060.45  4834.3 1055.21  4911.6 1049.42  4929.4 1045.21
  4938.3 1045.35    4971 1040.15  4971.2 1039.65    4975 1040.15  5028.3 1042.29
  5040.8  1040.3  5071.2 1043.49  5089.6 1048.32  5109.6 1050.76  5144.2 1054.39
  5218.1 1056.14  5295.2 1062.32    5402 1063.62  5536.1 1061.12  5577.3 1062.69
  5588.2 1065.28  5608.2 1066.13  5639.2 1066.67  5659.8 1063.59  5681.9  1064.9
#Mann= 5 ,-1 , 0
  4466.5     .05       0  4911.6     .12       0    4971     .07       0
    4975     .12       0  5109.6     .05       0
Bank Sta=4971,4975
XS Rating Curve= 0 ,0
Exp/Cntr=0.3,0.1

Type RM Length L Ch R = 1 ,4660    ,250,250,250
BEGIN DESCRIPTION:
Upper Denton 51 9.0
END DESCRIPTION:
XS GIS Cut Line= 3
      2195304.72      7270238.25      2194763.04      7269894.49
      2194163.14      7269450.63
#Sta/Elev= 30
  4344.9 1075.86  4557.6 1070.85  4659.6  1063.8  4688.1  1064.4  4703.3 1061.71
  4745.7 1061.09  4760.9 1058.57  4812.6  1056.6  4897.3 1046.59  4912.5 1047.22
    4949 1044.74  5032.4 1044.36  5037.9 1044.35  5048.1 1044.12  5048.4 1043.62
  5052.1 1044.12  5078.6  1044.5  5121.1 1052.99  5185.8 1059.77  5206.7 1063.17
  5300.6 1062.35  5377.8 1066.59  5427.9 1067.37  5450.9 1069.57  5492.6 1069.19
  5507.3 1071.96  5536.5 1072.29  5542.7 1073.89  5557.4    1073  5732.7 1077.32
#Mann= 5 ,-1 , 0
  4344.9     .05       0  5032.4     .12       0  5037.9     .05       0
  5048.1    .033       0  5052.1     .05       0
Bank Sta=5048.1,5052.1
XS Rating Curve= 0 ,0
Exp/Cntr=0.3,0.1

Type RM Length L Ch R = 1 ,4410    ,375,375,375
BEGIN DESCRIPTION:
Upper Denton 51 8.0
END DESCRIPTION:
XS GIS Cut Line= 3
      2195426.22      7270061.15        2194929.        7269710.
      2194353.63      7269287.08
#Sta/Elev= 30
  4391.3 1074.86  4662.7 1068.82  4669.5 1067.85  4683.6 1068.33  4713.2 1064.43
  4719.3  1065.5  4748.9 1064.87  4778.4 1061.47  4784.6  1057.8  4799.3 1056.75
  4828.6 1052.25  4855.9 1049.37  4927.3  1043.6  4990.6  1042.5  4990.9    1042
  4994.6  1042.5  5049.7  1042.8  5122.3 1048.22  5143.1 1049.15  5149.3 1048.07
  5193.3 1053.82  5235.8 1058.07  5285.5 1060.81  5293.6 1059.67  5308.2  1059.7
  5494.2 1067.55  5686.3 1071.24    5701 1071.71  5707.4 1073.23  5714.1 1072.24
#Mann= 3 ,-1 , 0
  4391.3     .05       0  4990.6    .033       0  4994.6     .05       0
Bank Sta=4990.6,4994.6
XS Rating Curve= 0 ,0
Exp/Cntr=0.3,0.1

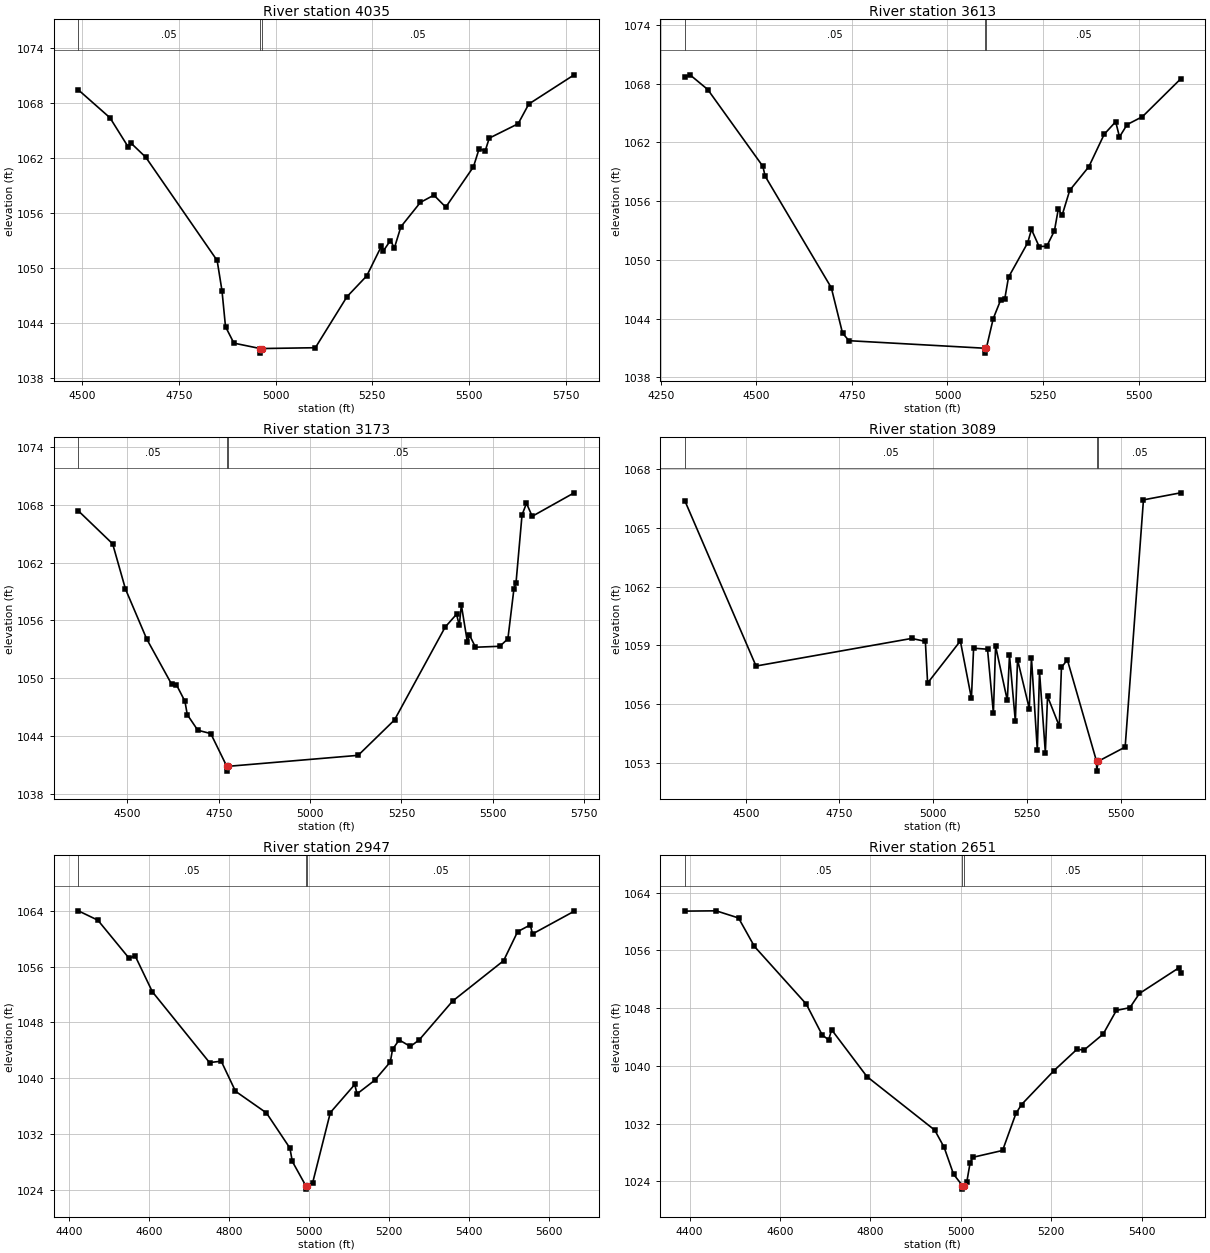
Type RM Length L Ch R = 1 ,4035    ,422,422,422
BEGIN DESCRIPTION:
Upper Denton 51 7.0
END DESCRIPTION:
XS GIS Cut Line= 3
      2195599.85       7269606.3        2195129.        7269410.
      2194374.16       7269255.6
#Sta/Elev= 30
  4490.7 1069.44  4572.5 1066.39  4620.1 1063.17  4625.5 1063.68    4665 1062.08
  4849.2 1050.82  4861.7 1047.53  4870.8  1043.6  4892.5  1041.8  4960.4 1041.21
  4960.6 1040.71  4964.4 1041.21  5102.9  1041.3  5184.6 1046.87  5235.6 1049.14
  5273.3 1052.37  5278.4 1051.86  5296.8    1053    5307 1052.19  5323.8  1054.5
  5374.2 1057.16  5409.1 1057.95  5439.7 1056.64  5511.2 1061.04  5525.6 1062.98
  5541.8 1062.81    5552 1064.17  5626.6 1065.74  5654.1 1067.89  5771.3 1071.08
#Mann= 3 ,-1 , 0
  4490.7     .05       0  4960.4    .033       0  4964.4     .05       0
Bank Sta=4960.4,4964.4
XS Rating Curve= 0 ,0
Exp/Cntr=0.3,0.1

Type RM Length L Ch R = 1 ,3613    ,440,440,440
BEGIN DESCRIPTION:
Upper Denton 51 6.0
END DESCRIPTION:
XS GIS Cut Line= 3
      2195655.41      7269391.02        2195029.        7269110.
      2194419.28      7269137.54
#Sta/Elev= 30
  4312.9 1068.65  4326.5  1068.9  4372.9  1067.4  4517.2 1059.55  4522.9 1058.56
  4696.1 1047.16  4725.5 1042.52  4742.4 1041.75  5097.6 1040.98  5097.8 1040.48
  5101.6 1040.98  5119.6    1044  5139.6 1045.95  5149.6 1045.97  5159.6 1048.23
  5209.7 1051.74  5219.7 1053.11  5239.7 1051.36  5259.7  1051.4  5279.7 1052.97
  5289.8 1055.18  5299.8 1054.56  5319.8 1057.11  5369.8 1059.52  5409.9 1062.83
  5439.9 1064.11  5449.9 1062.56  5469.9 1063.82    5510 1064.63  5609.8 1068.48
#Mann= 3 ,-1 , 0
  4312.9     .05       0  5097.6    .033       0  5101.6     .05       0
Bank Sta=5097.6,5101.6
XS Rating Curve= 0 ,0
Exp/Cntr=0.3,0.1

Type RM Length L Ch R = 1 ,3173    ,84,84,84
BEGIN DESCRIPTION:
Upper Denton 51 5.0
END DESCRIPTION:
XS GIS Cut Line= 3
      2195679.75      7269137.57        2195129.        7268810.
      2194493.12      7268481.76
#Sta/Elev= 30
    4366 1067.39  4459.9 1063.96  4494.9 1059.27    4553 1054.08  4621.2 1049.38
  4634.5 1049.31  4657.7  1047.6    4664 1046.22  4692.7  1044.6  4728.3 1044.25
  4772.1 1040.85  4772.3 1040.35  4776.1 1040.85  5131.5 1041.99    5231 1045.67
  5369.5 1055.31  5400.7 1056.65  5408.2 1055.48  5413.8 1057.61  5430.4 1053.72
    5436 1054.49  5452.5 1053.22    5519 1053.32  5541.1 1054.09  5557.7  1059.3
  5563.3 1059.88  5579.8 1066.97    5592 1068.17  5607.6 1066.82  5722.4 1069.26
#Mann= 3 ,-1 , 0
    4366     .05       0  4772.1    .033       0  4776.1     .05       0
Bank Sta=4772.1,4776.1
XS Rating Curve= 0 ,0
Exp/Cntr=0.3,0.1

Type RM Length L Ch R = 1 ,3089    ,142,142,142
BEGIN DESCRIPTION:
Upper Denton 51 4.5
END DESCRIPTION:
XS GIS Cut Line= 3
      2195714.46      7269085.48      2195141.51      7268731.29
      2194583.24      7268401.88
#Sta/Elev= 30
  4337.6  1066.4  4527.5 1057.95  4942.4 1059.36  4978.9 1059.21  4984.9 1057.08
  5072.2 1059.23  5101.7  1056.3  5107.5 1058.86  5144.6 1058.81  5160.3 1055.54
  5166.1 1058.97  5197.4 1056.19  5203.2 1058.49  5218.8 1055.13  5224.6 1058.28
  5255.9 1055.78  5261.7 1058.37  5277.4 1053.65  5283.2 1057.66  5298.8 1053.53
  5304.6  1056.4  5335.9 1054.88  5341.7 1057.88  5357.4 1058.27  5435.3 1053.08
  5435.6 1052.58  5439.4 1053.08  5511.5 1053.81  5560.3 1066.44  5659.4  1066.8
#Mann= 3 ,-1 , 0
  4337.6     .05       0  5435.3    .033       0  5439.4     .05       0
Bank Sta=5435.3,5439.4
XS Rating Curve= 0 ,0
Exp/Cntr=0.3,0.1

Type RM Length L Ch R = 1 ,2947    ,296,296,296
BEGIN DESCRIPTION:
Upper Denton 51 4.4
END DESCRIPTION:
XS GIS Cut Line= 3
      2195728.35      7268998.68      2195263.04      7268658.38
      2194673.35      7268356.59
#Sta/Elev= 30
  4424.1 1063.97  4472.9 1062.63  4551.1 1057.17  4565.8 1057.55  4609.1 1052.38
  4751.9 1042.25  4781.2 1042.44  4816.8 1038.14  4894.1 1035.04  4952.7 1030.01
  4958.8 1028.09  4992.3 1024.63  4992.6 1024.13  4996.4 1024.63  5009.4    1025
  5053.8 1035.09  5114.8 1039.11  5120.4 1037.76  5164.8 1039.72  5203.6 1042.33
  5209.2 1044.14  5225.8 1045.49  5253.7 1044.55  5275.9  1045.5  5359.1 1051.04
  5486.7 1056.83  5521.8 1060.99  5553.3 1061.95    5559 1060.66    5663 1063.91
#Mann= 3 ,-1 , 0
  4424.1     .05       0  4992.3    .033       0  4996.4     .05       0
Bank Sta=4992.3,4996.4
XS Rating Curve= 0 ,0
Exp/Cntr=0.3,0.1

Type RM Length L Ch R = 1 ,2651    ,362,362,362
BEGIN DESCRIPTION:
Upper Denton 51 4.0
END DESCRIPTION:
XS GIS Cut Line= 3
       2195818.6      7268897.96      2195433.18      7268429.21
      2195026.96      7268154.93
#Sta/Elev= 30
  4389.3 1061.45  4458.7 1061.49  4508.2  1060.5  4543.4 1056.55  4658.1 1048.56
  4693.3 1044.28  4707.6  1043.6  4714.1 1045.01  4792.3 1038.51  4942.3 1031.09
  4963.1  1028.7  4983.9 1024.98  5003.4 1023.41  5003.7 1022.91  5007.5 1023.41
  5013.3 1023.93  5020.4 1026.51  5026.5 1027.32  5092.4 1028.27  5121.9  1033.4
  5134.4 1034.64  5206.3 1039.35  5257.2 1042.31  5272.2 1042.17  5314.9  1044.4
  5344.1 1047.68  5374.1 1048.07  5395.1 1050.03    5482 1053.57  5486.3 1052.81
#Mann= 3 ,-1 , 0
  4389.3     .05       0  5003.4    .033       0  5007.5     .05       0
Bank Sta=5003.4,5007.5
XS Rating Curve= 0 ,0
Exp/Cntr=0.3,0.1