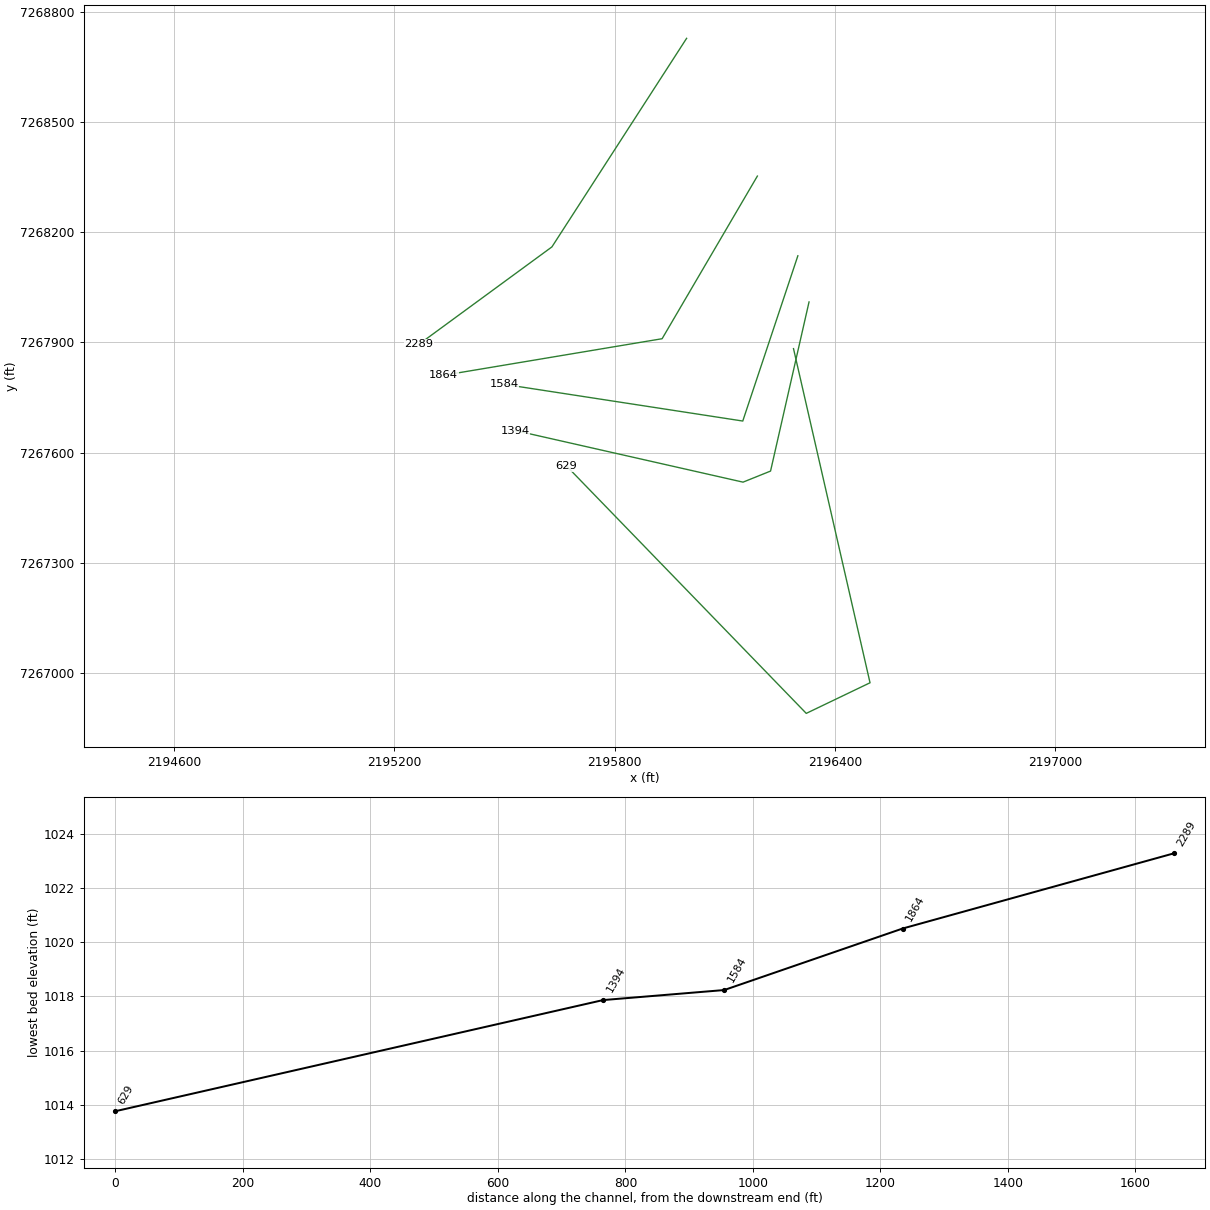
HEC-RAS study Upper Denton 51.prj: Upper Denton 51 Base Level Engineering

--- Upper Denton 51.g01 (geometry) --- (continued)

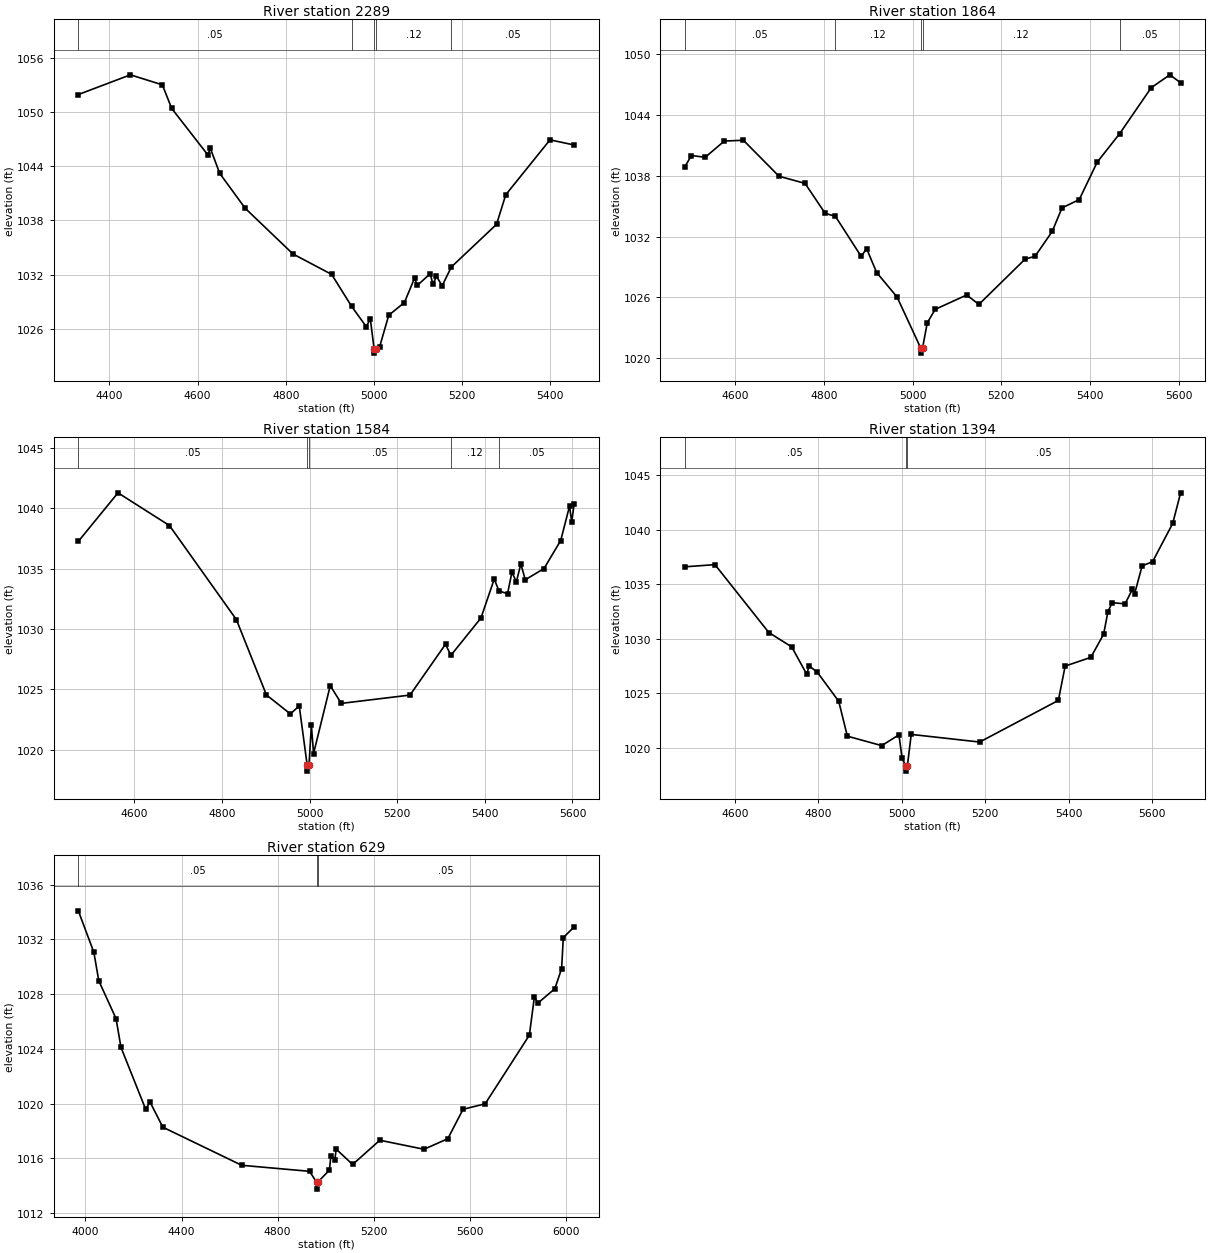
Type RM Length L Ch R = 1 ,2289    ,425,425,425
BEGIN DESCRIPTION:
Upper Denton 51 3.0
END DESCRIPTION:
XS GIS Cut Line= 3
      2195995.69      7268727.84        2195629.        7268160.
      2195266.89      7267894.77
#Sta/Elev= 30
  4329.3 1051.98  4447.4 1054.17  4519.9 1053.06  4541.1 1050.44  4622.9 1045.29
  4628.8 1046.01  4649.9 1043.24  4707.7 1039.36  4816.2 1034.28    4904 1032.01
    4949 1028.48  4982.5 1026.21  4991.7 1027.07  5000.2 1023.77  5000.5 1023.27
  5004.3 1023.77  5012.6 1023.93  5033.4 1027.47    5069 1028.89    5092 1031.59
  5098.3 1030.79  5127.6 1032.09  5133.8 1030.89  5141.6 1031.81  5154.6 1030.75
  5175.6 1032.84    5278 1037.57    5299 1040.86  5399.3 1046.95  5454.1 1046.38
#Mann= 5 ,-1 , 0
  4329.3     .05       0    4949     .12       0  5000.2     .07       0
  5004.3     .12       0  5175.6     .05       0
Bank Sta=5000.2,5004.3
XS Rating Curve= 0 ,0
Exp/Cntr=0.3,0.1

Type RM Length L Ch R = 1 ,1864    ,280,280,280
BEGIN DESCRIPTION:
Upper Denton 51 2.0
END DESCRIPTION:
XS GIS Cut Line= 3
      2196188.39      7268352.83        2195929.        7267910.
      2195333.69      7267810.34
#Sta/Elev= 30
    4487  1038.9  4501.9 1040.01    4533 1039.84    4576 1041.44    4619 1041.52
  4699.1 1037.97  4757.8 1037.26  4803.2  1034.3  4826.2 1034.01  4884.3 1030.05
  4896.5 1030.82  4919.1 1028.46  4965.1 1026.04  5018.4    1021  5018.7  1020.5
  5022.5    1021  5033.1 1023.49  5050.9 1024.82  5121.9 1026.24  5149.4 1025.31
  5253.7 1029.79  5275.9 1030.06  5314.5 1032.51  5336.6 1034.84  5375.4 1035.66
  5415.9 1039.36  5466.3 1042.16  5537.6 1046.71  5579.4 1047.98  5603.8  1047.2
#Mann= 5 ,-1 , 0
    4487     .05       0  4826.2     .12       0  5018.4     .07       0
  5022.5     .12       0  5466.3     .05       0
Bank Sta=5018.4,5022.5
XS Rating Curve= 0 ,0
Exp/Cntr=0.3,0.1

Type RM Length L Ch R = 1 ,1584    ,190,190,190
BEGIN DESCRIPTION:
Upper Denton 51 1.5
END DESCRIPTION:
XS GIS Cut Line= 3
      2196298.61      7268135.83      2196148.62      7267685.87
      2195498.67      7267785.86
#Sta/Elev= 30
    4472 1037.26  4562.5 1041.28    4680 1038.57  4832.8 1030.78  4901.4 1024.54
    4956 1022.97  4976.3 1023.63  4994.4 1018.73  4994.8 1018.23  4998.6 1018.73
    5004 1022.02    5009 1019.69  5047.1 1025.31  5072.3 1023.84  5229.2 1024.53
  5310.2 1028.74  5322.5 1027.82  5391.1 1030.91  5421.4 1034.13  5432.3 1033.16
  5451.8 1032.92  5461.8  1034.7    5472 1033.91  5482.2 1035.39  5492.3 1034.08
  5535.1 1035.01  5573.2 1037.33  5593.3 1040.17  5598.4 1038.87  5603.9 1040.39
#Mann= 5 ,-1 , 0
    4472     .05       0  4994.4    .033       0  4998.6     .05       0
  5322.5     .12       0  5432.3     .05       0
Bank Sta=4994.4,4998.6
XS Rating Curve= 0 ,0
Exp/Cntr=0.3,0.1

Type RM Length L Ch R = 1 ,1394    ,765,765,765
BEGIN DESCRIPTION:
Upper Denton 51 1.0
END DESCRIPTION:
XS GIS Cut Line= 4
      2196329.01      7268010.04      2196224.26      7267549.63
      2196149.32      7267519.49      2195528.98        7267660.
#Sta/Elev= 30
  4479.6 1036.61  4551.9 1036.81  4681.1 1030.58    4736 1029.26  4772.3 1026.73
  4777.4 1027.53  4797.6 1026.93  4848.8 1024.26  4869.4 1021.07  4951.8  1020.2
  4993.1 1021.19  5000.6 1019.07  5009.2 1018.36  5009.6 1017.86  5013.4 1018.36
  5022.6 1021.23  5186.7 1020.53  5375.4 1024.35  5391.7  1027.5  5453.3  1028.3
    5484 1030.43  5494.3  1032.5  5504.5 1033.32  5535.3 1033.21    5553 1034.55
  5558.2 1034.13  5576.3  1036.7  5601.3 1037.08  5649.6 1040.59  5668.6  1043.4
#Mann= 3 ,-1 , 0
  4479.6     .05       0  5009.2    .033       0  5013.4     .05       0
Bank Sta=5009.2,5013.4
XS Rating Curve= 0 ,0
Exp/Cntr=0.3,0.1

Type RM Length L Ch R = 1 ,629     ,0,0,0
BEGIN DESCRIPTION:
Upper Denton 51 0.5
END DESCRIPTION:
XS GIS Cut Line= 4
      2196286.75      7267883.01      2196495.09      7266973.24
      2196321.48      7266889.91      2195668.71      7267563.52
#Sta/Elev= 30
  3970.5 1034.08  4035.1 1031.05  4055.7 1028.97  4127.5 1026.21    4148 1024.11
  4250.6  1019.6  4268.9 1020.12  4322.4 1018.28  4650.7  1015.5  4932.8 1015.06
  4962.6 1014.26    4963 1013.76  4966.9 1014.26  5015.6 1015.15  5021.5 1016.15
  5038.3 1015.91  5043.8 1016.68  5112.3 1015.56  5225.5 1017.33  5409.4 1016.67
  5508.4 1017.44    5572 1019.59    5664 1019.99  5847.9    1025    5869 1027.81
  5883.2 1027.34  5953.9 1028.39  5982.2 1029.86  5989.2 1032.12  6034.4 1032.91
#Mann= 3 ,-1 , 0
  3970.5     .05       0  4962.6    .035       0  4966.9     .05       0
Bank Sta=4962.6,4966.9
XS Rating Curve= 0 ,0
Exp/Cntr=0.3,0.1

Chan Stop Cuts=-1
Use User Specified Reach Order=0
Composite Channel Slope=5