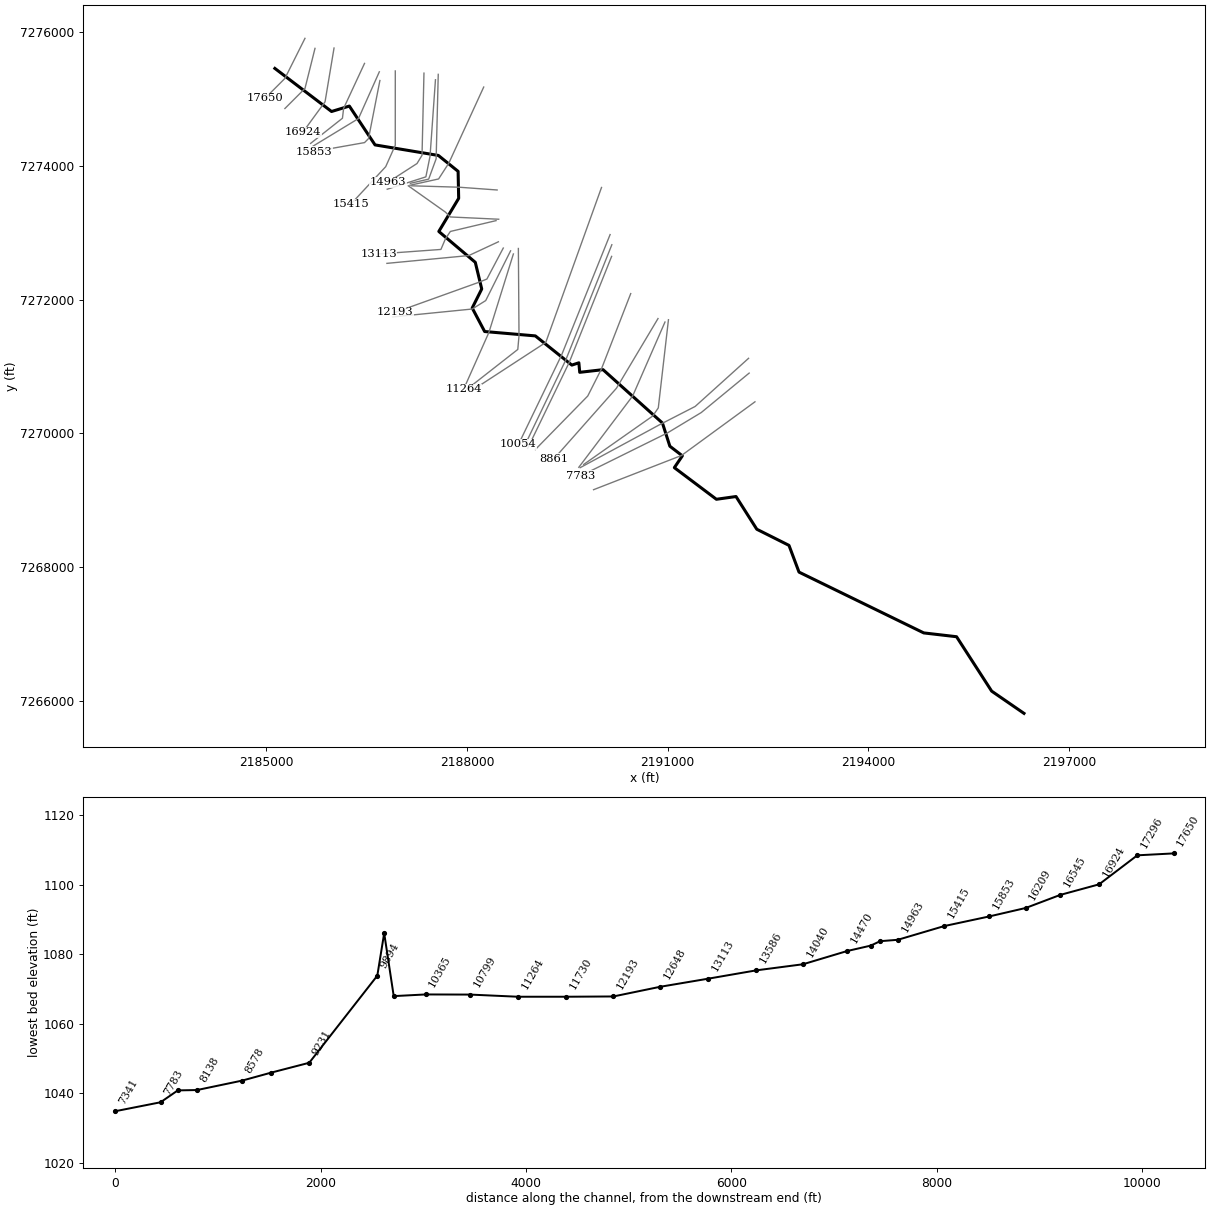
--- Upper Denton 52.prj (project) ---

Proj Title=Upper Denton 52 Base Level Engineering
Current Plan=p01
Default Exp/Contr=0.3,0.1
English Units
Geom File=g01
Flow File=f01
Plan File=p01
Y Axis Title=Elevation
X Axis Title(PF)=Main Channel Distance
X Axis Title(XS)=Station
BEGIN DESCRIPTION:
Upper Denton 52
END DESCRIPTION:
DSS Export Rating Curves= 0
DSS Export Rating Curve Sorted= 0
DSS Export Volume Flow Curves= 0
DXF OffsetX= 0
DXF OffsetY= 0
DXF ScaleX= 1
DXF ScaleY= 10

--- Upper Denton 52.p01 (plan) ---

Plan Title=Multiple Run
Short Identifier=Multiple
Geom File=g01
Flow File=f01
Subcritical Flow
K Sum by GR= 0
Std Step Tol= 0.01
Critical Tol= 0.01
Num of Std Step Trials= 20
Max Error Tol= 0.3
Flow Tol Ratio= 0.001
Split Flow NTrial= 30
Split Flow Tol= 0.02
Split Flow Ratio= 0.02
Log Output Level= 0
Friction Slope Method= 1
Unsteady Friction Slope Method= 2
Unsteady Bridges Friction Slope Method= 1
Parabolic Critical Depth
Global Vel Dist=  1 , 1 , 1
Global Log Level= 0
CheckData=True
Encroach Param= -1, 0, 0, 0
BEGIN DESCRIPTION:
Multiple Run
END DESCRIPTION:

--- Upper Denton 52.f01 (steady flow) ---

Flow Title=Multiple
Number of Profiles=7
Profile Names=10-year,25-year,50-year,1pct_min,100-year,1pct_plu,500-year
River Rch & RM= Upper Denton 52,Reach-1,17650
     589     810     992     603    1203    2401    1776
River Rch & RM= Upper Denton 52,Reach-1,15415
     868    1214    1504     924    1843    3678    2778
River Rch & RM= Upper Denton 52,Reach-1,10365
    1204    1714    2149    1334    2662    5312    4102
River Rch & RM= Upper Denton 52,Reach-1,5050
    1327    1897    2384    1484    2960    5907    4581
Boundary for River Rch & Prof#=Upper Denton 52,Reach-1,1
Up Type=0
Dn Type=3
Dn Slope=0.005
Boundary for River Rch & Prof#=Upper Denton 52,Reach-1,2
Up Type=0
Dn Type=3
Dn Slope=0.005
Boundary for River Rch & Prof#=Upper Denton 52,Reach-1,3
Up Type=0
Dn Type=3
Dn Slope=0.005
Boundary for River Rch & Prof#=Upper Denton 52,Reach-1,4
Up Type=0
Dn Type=3
Dn Slope=0.005
Boundary for River Rch & Prof#=Upper Denton 52,Reach-1,5
Up Type=0
Dn Type=3
Dn Slope=0.005
Boundary for River Rch & Prof#=Upper Denton 52,Reach-1,6
Up Type=0
Dn Type=3
Dn Slope=0.005
Boundary for River Rch & Prof#=Upper Denton 52,Reach-1,7
Up Type=0
Dn Type=3
Dn Slope=0.005

--- Upper Denton 52.g01 (geometry) ---

Geom Title=Existing Conditions
Program Version=4.10

River Reach=Upper Denton 52 ,Reach-1
Reach XY= 30
        2185129.        7275460.      2185976.33       7274815.3
      2186242.38      7274896.48      2186626.55      7274315.46
      2187573.14      7274157.95      2187868.53      7273919.82
      2187876.94      7273515.85      2187580.03      7273020.43
      2188125.46      7272558.53      2188221.67       7272159.9
      2188079.37      7271875.27      2188265.33      7271523.22
      2189023.14      7271457.94      2189568.96      7271021.12
      2189673.81      7271055.37      2189686.92      7270912.92
      2190035.34      7270952.64      2190923.41      7270154.39
      2191034.36       7269807.3      2191221.42      7269663.35
      2191101.36      7269486.62      2191730.28      7269013.37
      2192023.41      7269054.47      2192334.11      7268565.11
      2192815.53      7268323.57      2192965.43      7267923.47
      2194830.56      7267013.81      2195320.72      7266956.94
      2195845.49      7266142.95        2196329.        7265810.

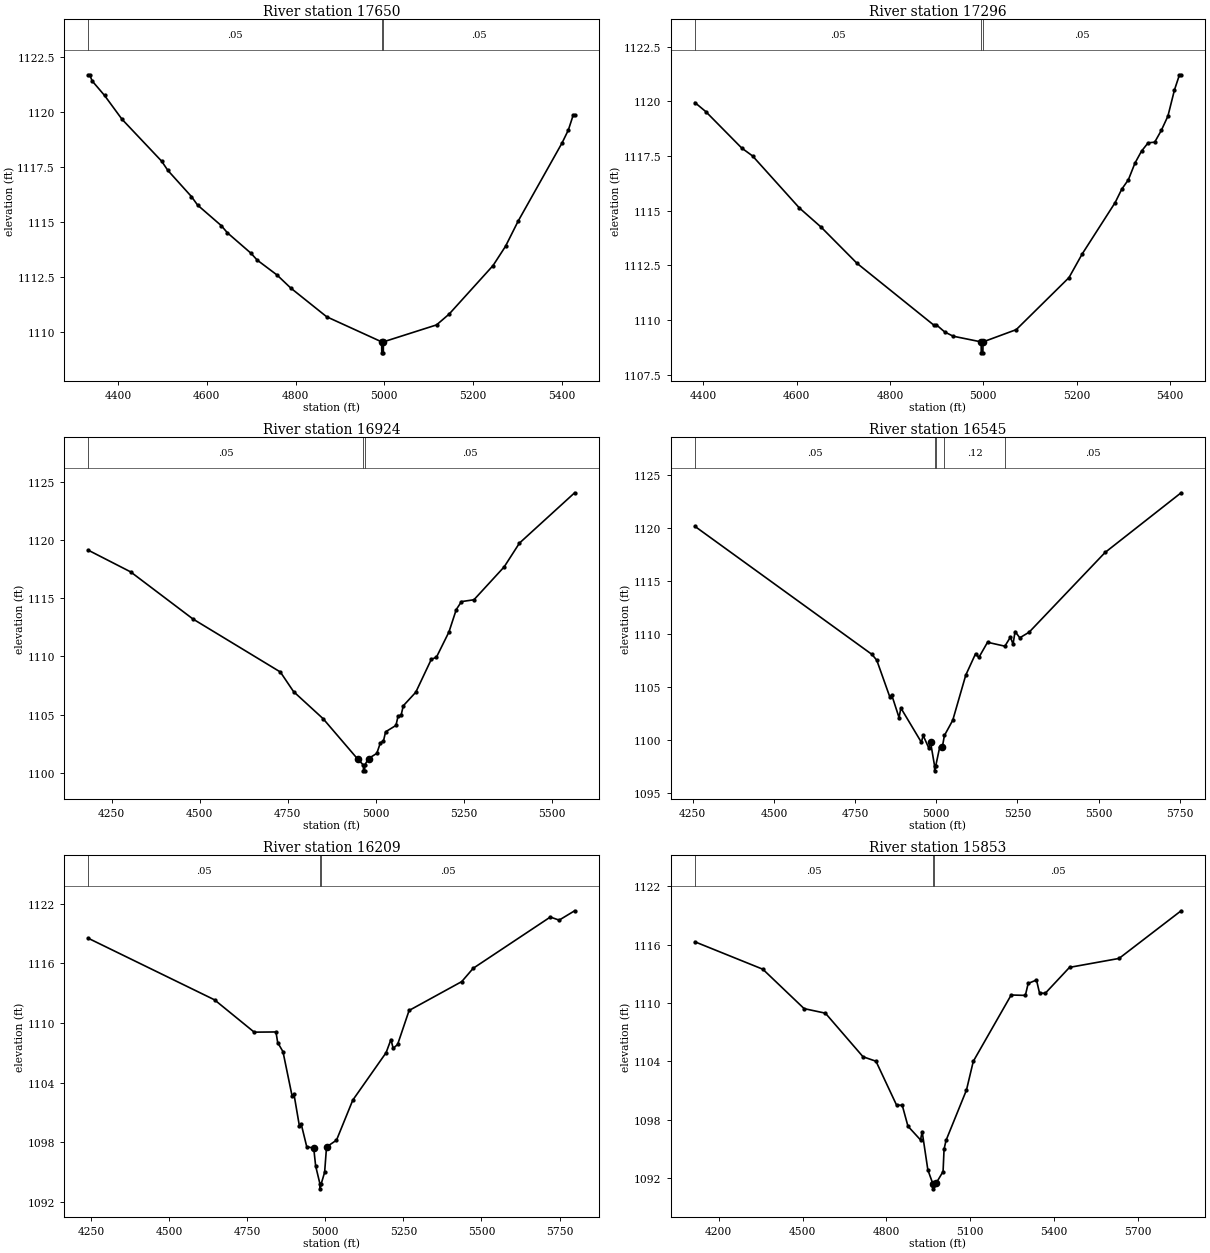
Type RM Length L Ch R = 1 ,17650   ,354,354,354
BEGIN DESCRIPTION:
Upper Denton 52 39.0
END DESCRIPTION:
XS GIS Cut Line= 3
      2185579.01      7275910.01        2185279.        7275310.
        2184979.        7275010.
#Sta/Elev= 29
  4333.5  1121.7  4336.3  1121.7  4341.9 1121.42  4369.8 1120.76    4409 1119.68
  4498.4 1117.77  4512.4 1117.35  4565.5 1116.16  4579.5 1115.77  4632.6 1114.84
  4646.6 1114.51  4699.7 1113.58  4713.6 1113.27  4758.4 1112.59  4789.1    1112
  4870.2 1110.69  4993.9 1109.55  4994.2 1109.05  4997.7 1109.05  4997.9 1109.55
  5117.5 1110.32  5145.8 1110.81  5244.8 1113.02    5273  1113.9  5301.3 1115.04
  5400.3  1118.6  5414.5 1119.19  5425.1 1119.85  5428.6 1119.85
#Mann= 3 ,-1 , 0
  4333.5     .05       0  4993.9    .033       0  4997.9     .05       0
Bank Sta=4993.9,4997.9
XS Rating Curve= 0 ,0
Exp/Cntr=0.3,0.1

Type RM Length L Ch R = 1 ,17296   ,372,372,372
BEGIN DESCRIPTION:
Upper Denton 52 38.0
END DESCRIPTION:
XS GIS Cut Line= 3
      2185728.99      7275759.96        2185579.        7275160.
      2185278.99      7274859.99
#Sta/Elev= 30
  4381.6 1119.94  4404.8 1119.53  4482.1 1117.86  4505.3  1117.5  4605.8 1115.12
  4652.1 1114.25  4729.4 1112.59  4894.4 1109.76  4899.5 1109.78  4917.6 1109.45
  4935.6 1109.26  4995.5    1109  4995.7  1108.5  4999.2  1108.5  4999.5    1109
  5070.7 1109.56  5183.9 1111.94  5212.2 1113.02  5282.9 1115.37    5297 1115.98
  5311.2 1116.41  5325.3 1117.17  5339.4 1117.72  5353.6  1118.1  5367.7 1118.13
  5381.9 1118.67    5396 1119.32  5410.1 1120.52  5420.8 1121.21  5424.3 1121.21
#Mann= 3 ,-1 , 0
  4381.6     .05       0  4995.5    .033       0  4999.5     .05       0
Bank Sta=4995.5,4999.5
XS Rating Curve= 0 ,0
Exp/Cntr=0.3,0.1

Type RM Length L Ch R = 1 ,16924   ,379,379,379
BEGIN DESCRIPTION:
Upper Denton 52 37.0
END DESCRIPTION:
XS GIS Cut Line= 3
      2186013.49      7275764.86        2185879.        7274960.
      2185545.88      7274503.42
#Sta/Elev= 30
  4184.3 1119.14  4304.2 1117.28  4481.4 1113.22  4729.5 1108.66  4767.1 1106.97
    4851 1104.64  4949.6 1101.15  4965.4 1100.65  4965.7 1100.15  4969.2 1100.15
  4969.4 1100.65    4980 1101.21  5003.4 1101.65  5013.8 1102.57  5022.3  1102.7
  5028.5 1103.51  5057.9 1104.06    5064 1104.87  5072.5 1104.93  5078.7 1105.75
  5114.3 1106.92  5158.3 1109.75  5172.9 1109.93  5208.5 1112.11  5229.3 1114.04
    5244 1114.72  5279.5 1114.88  5365.3 1117.71  5408.8 1119.76  5565.5 1124.09
#Mann= 3 ,-1 , 0
  4184.3     .05       0  4965.4    .033       0  4969.4     .05       0
Bank Sta=4949.6,4980
XS Rating Curve= 0 ,0
Exp/Cntr=0.3,0.1

Type RM Length L Ch R = 1 ,16545   ,336,336,336
BEGIN DESCRIPTION:
Upper Denton 52 36.0
END DESCRIPTION:
XS GIS Cut Line= 4
      2186469.23      7275534.87      2186156.72      7274862.11
      2186139.36      7274714.54      2185662.95      7274337.74
#Sta/Elev= 30
  4256.4 1120.13  4802.1 1108.06  4816.7 1107.52    4857 1104.05  4862.5 1104.27
  4885.4 1102.11  4890.9 1103.02  4954.1 1099.79  4959.6 1100.43  4976.9 1099.25
  4982.5 1099.77  4994.6  1097.6  4994.9  1097.1  4998.6  1097.6  5010.4 1099.31
  5018.5 1099.32  5025.1 1100.43  5050.7 1101.86  5090.9 1106.12  5121.2 1108.14
  5131.2 1107.78  5157.9 1109.21  5211.4 1108.84  5228.4  1109.7  5236.4 1109.03
  5242.8 1110.22  5257.3 1109.63  5286.1 1110.16  5520.1 1117.67  5754.2 1123.29
#Mann= 5 ,-1 , 0
  4256.4     .05       0  4994.6    .033       0  4998.6     .05       0
  5025.1     .12       0  5211.4     .05       0
Bank Sta=4982.5,5018.5
XS Rating Curve= 0 ,0
Exp/Cntr=0.3,0.1

Type RM Length L Ch R = 1 ,16209   ,356,356,356
BEGIN DESCRIPTION:
Upper Denton 52 35.0
END DESCRIPTION:
XS GIS Cut Line= 3
      2186690.58      7275408.99        2186379.        7274710.
      2185702.47      7274298.76
#Sta/Elev= 30
  4241.4 1118.52  4645.2 1112.34  4772.3 1109.09    4842 1109.11  4847.5 1108.04
  4864.4 1107.13  4893.9 1102.63  4899.4  1102.9  4917.2 1099.62  4922.6 1099.88
  4940.4 1097.59  4962.9 1097.42  4969.1 1095.63  4982.8 1093.84    4983 1093.34
  4986.8 1093.84  4997.8    1095  5003.9 1097.55  5035.8 1098.23    5088 1102.26
  5194.7 1107.03  5210.2 1108.35  5217.3 1107.46  5231.5 1107.85  5268.3 1111.27
  5436.8 1114.17  5473.6 1115.51  5720.5 1120.66  5748.8 1120.35  5798.4 1121.29
#Mann= 3 ,-1 , 0
  4241.4     .05       0  4982.8    .033       0  4986.8     .05       0
Bank Sta=4962.9,5003.9
XS Rating Curve= 0 ,0
Exp/Cntr=0.3,0.1

Type RM Length L Ch R = 1 ,15853   ,438,438,438
BEGIN DESCRIPTION:
Upper Denton 52 34.0
END DESCRIPTION:
XS GIS Cut Line= 4
      2186699.26      7275278.81        2186529.        7274410.
      2186469.22      7274349.95      2185709.71      7274215.41
#Sta/Elev= 30
  4114.4  1116.3  4357.8 1113.48  4505.6 1109.43  4581.9 1108.96  4716.6 1104.48
    4763 1104.02  4836.7 1099.51  4857.1 1099.49  4877.5 1097.34  4922.5 1095.93
  4928.4 1096.78  4948.8 1092.85  4966.9  1091.4  4967.2  1090.9  4970.9  1091.4
  4979.4 1091.53  5003.3 1092.68  5006.8 1094.97  5013.9 1095.88  5087.1 1101.06
  5111.5 1104.01  5247.2 1110.83    5298 1110.79  5308.1 1112.02  5337.8 1112.37
  5348.7 1111.04  5369.1    1111  5456.1 1113.67  5633.5 1114.59  5855.8 1119.49
#Mann= 3 ,-1 , 0
  4114.4     .05       0  4966.9    .033       0  4970.9     .05       0
Bank Sta=4966.9,4979.4
XS Rating Curve= 0 ,0
Exp/Cntr=0.3,0.1

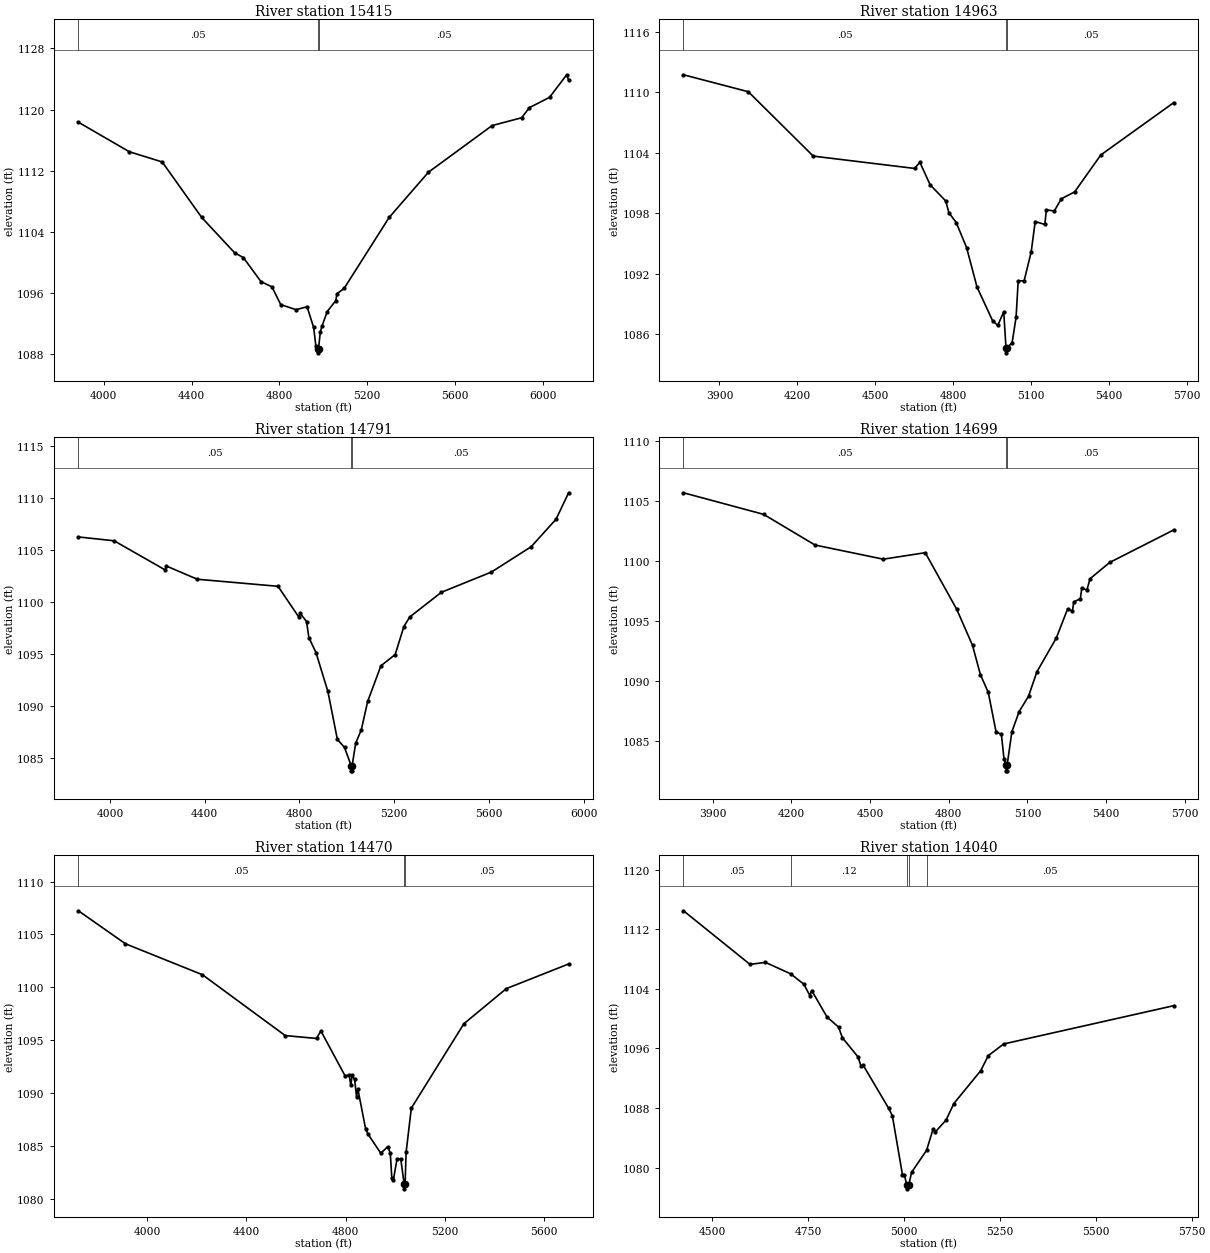
Type RM Length L Ch R = 1 ,15415   ,452,452,452
BEGIN DESCRIPTION:
Upper Denton 52 33.0
END DESCRIPTION:
XS GIS Cut Line= 4
      2186929.29        7275422.        2186929.        7274310.
      2186786.06      7273989.71      2186260.87      7273425.45
#Sta/Elev= 30
  3883.9 1118.34  4115.9 1114.47  4265.9 1113.13  4445.9 1105.86  4595.9 1101.23
  4635.9  1100.6  4715.9 1097.46  4765.9 1096.77  4805.9 1094.45  4875.9 1093.78
  4925.9 1094.17  4955.9 1091.45  4965.9 1089.06  4973.9 1088.63  4974.2 1088.13
    4978 1088.63  4985.9 1090.81  4993.4 1091.59  5017.8 1093.54  5056.7 1094.97
  5062.2 1095.88  5094.5 1096.56  5299.8 1105.86  5478.9 1111.79  5769.1  1117.9
  5903.5 1118.92  5938.6 1120.24  6030.5 1121.59  6108.7 1124.55  6117.5 1123.83
#Mann= 3 ,-1 , 0
  3883.9     .05       0  4973.9    .033       0    4978     .05       0
Bank Sta=4973.9,4978
XS Rating Curve= 0 ,0
Exp/Cntr=0.3,0.1

Type RM Length L Ch R = 1 ,14963   ,172,172,172
BEGIN DESCRIPTION:
Upper Denton 52 32.0
END DESCRIPTION:
XS GIS Cut Line= 4
      2187358.04      7275389.46        2187329.        7274160.
      2187254.09       7274036.8      2186822.89      7273758.86
#Sta/Elev= 30
  3761.6 1111.73  4011.1 1110.05  4261.2 1103.67  4651.3 1102.45  4671.3 1103.06
  4711.3 1100.82  4771.3 1099.22    4783 1098.07  4811.4 1097.09  4851.4  1094.6
  4891.4  1090.7  4951.4 1087.36  4971.4  1086.9  4994.3 1088.25  5002.9 1084.68
  5003.2 1084.18    5007 1084.68  5026.5 1085.18  5041.8  1087.7  5049.9 1091.32
  5072.7 1091.31  5099.9 1094.17  5115.4 1097.19  5152.5  1096.9  5158.4 1098.35
  5188.8 1098.23  5215.9 1099.44  5267.3 1100.13  5367.7 1103.78  5648.6 1108.97
#Mann= 3 ,-1 , 0
  3761.6     .05       0  5002.9    .033       0    5007     .05       0
Bank Sta=5002.9,5007
XS Rating Curve= 0 ,0
Exp/Cntr=0.3,0.1

Type RM Length L Ch R = 1 ,14791   ,92,92,92
BEGIN DESCRIPTION:
Upper Denton 52 31.5
END DESCRIPTION:
XS GIS Cut Line= 4
      2187529.91      7275290.45      2187448.97      7274146.81
      2187386.68      7273837.37      2186808.59      7273652.48
#Sta/Elev= 30
  3866.7 1106.29  4017.5 1105.92  4233.4 1103.11  4238.4 1103.49  4368.4 1102.22
  4709.3 1101.54  4797.4 1098.57  4802.4 1098.96  4829.6 1098.15  4839.6 1096.61
  4869.7 1095.15  4919.8 1091.42  4959.9  1086.8    4990 1086.03  5018.1 1084.28
  5018.4 1083.78  5021.9 1083.78  5022.2 1084.28  5036.9 1086.42    5061 1087.74
  5087.8 1090.47  5143.7 1093.89  5203.8 1094.97  5240.3 1097.65    5265 1098.58
  5398.5 1100.96  5609.9 1102.91  5777.9 1105.35  5882.9    1108  5935.8 1110.54
#Mann= 3 ,-1 , 0
  3866.7     .05       0  5018.1    .033       0  5022.2     .05       0
Bank Sta=5018.1,5022.2
XS Rating Curve= 0 ,0
Exp/Cntr=0.3,0.1

Type RM Length L Ch R = 1 ,14699   ,229,229,229
BEGIN DESCRIPTION:
Upper Denton 52 31.4
END DESCRIPTION:
XS GIS Cut Line= 4
      2187571.58      7275371.25      2187540.11      7274107.74
      2187428.35      7273803.51      2187154.91      7273741.01
#Sta/Elev= 30
  3788.9  1105.7  4094.3  1103.9  4290.3 1101.34  4550.4 1100.16  4710.4  1100.7
  4830.5 1095.97  4890.5 1092.97  4920.5 1090.53  4950.5 1089.05  4980.5 1085.73
  5000.5 1085.56  5010.5  1083.5  5018.4    1083  5018.8  1082.5  5022.3  1082.5
  5022.6    1083  5040.5 1085.76  5068.4 1087.45  5104.3 1088.74  5135.6 1090.75
  5210.2  1093.6  5252.8    1096  5271.2 1095.83  5276.5 1096.59  5301.6 1096.87
    5307 1097.74  5326.8 1097.59    5338 1098.52  5413.6 1099.89  5657.4  1102.6
#Mann= 3 ,-1 , 0
  3788.9     .05       0  5018.4    .033       0  5022.6     .05       0
Bank Sta=5018.4,5022.6
XS Rating Curve= 0 ,0
Exp/Cntr=0.3,0.1

Type RM Length L Ch R = 1 ,14470   ,430,430,430
BEGIN DESCRIPTION:
Upper Denton 52 31.0
END DESCRIPTION:
XS GIS Cut Line= 4
      2188251.28      7275181.14      2187730.65      7274044.61
      2187576.79      7273806.12      2187147.35      7273711.29
#Sta/Elev= 30
  3724.1 1107.24  3913.7 1104.12  4223.8 1101.19  4556.9 1095.44  4682.9 1095.17
  4700.4 1095.88  4797.9 1091.63  4814.3 1091.71  4820.9 1090.73  4826.4 1091.67
  4836.3  1091.3  4843.9 1089.68  4849.4 1090.38  4880.3 1086.65  4889.9 1086.13
  4941.5 1084.32    4970 1084.94  4979.9 1084.31  4986.1 1081.94    4992 1081.74
  5007.2  1083.8  5022.3 1083.73  5035.4 1081.45  5035.8 1080.95  5039.6 1081.45
  5043.5 1084.39  5064.6 1088.58  5276.2 1096.56    5447 1099.88  5697.8 1102.21
#Mann= 3 ,-1 , 0
  3724.1     .05       0  5035.4    .033       0  5039.6     .05       0
Bank Sta=5035.4,5039.6
XS Rating Curve= 0 ,0
Exp/Cntr=0.3,0.1

Type RM Length L Ch R = 1 ,14040   ,454,454,454
BEGIN DESCRIPTION:
Upper Denton 52 30.0
END DESCRIPTION:
XS GIS Cut Line= 3
      2188451.99      7273640.97      2187881.69      7273682.63
      2187176.01      7273703.47
#Sta/Elev= 30
  4425.5 1114.49  4598.9 1107.29  4639.1 1107.56    4705 1106.02  4739.3 1104.62
  4754.8 1103.11  4759.8 1103.77  4799.5 1100.23  4829.6 1098.87  4839.6 1097.44
  4879.7 1094.91  4888.6 1093.59  4893.6 1093.77  4959.9 1087.99  4969.9 1086.96
  4996.2 1079.05  5001.2 1079.05  5007.4 1077.64  5008.1 1077.14  5012.6 1077.64
    5020 1079.35  5059.1 1082.32  5076.3  1085.2  5081.3 1084.75  5110.1 1086.39
  5130.1 1088.59  5200.1    1093  5220.1 1095.04  5260.1  1096.6  5703.3 1101.74
#Mann= 5 ,-1 , 0
  4425.5     .05       0    4705     .12       0  5007.4     .07       0
  5012.6     .12       0  5059.1     .05       0
Bank Sta=5007.4,5012.6
XS Rating Curve= 0 ,0
Exp/Cntr=0.3,0.1

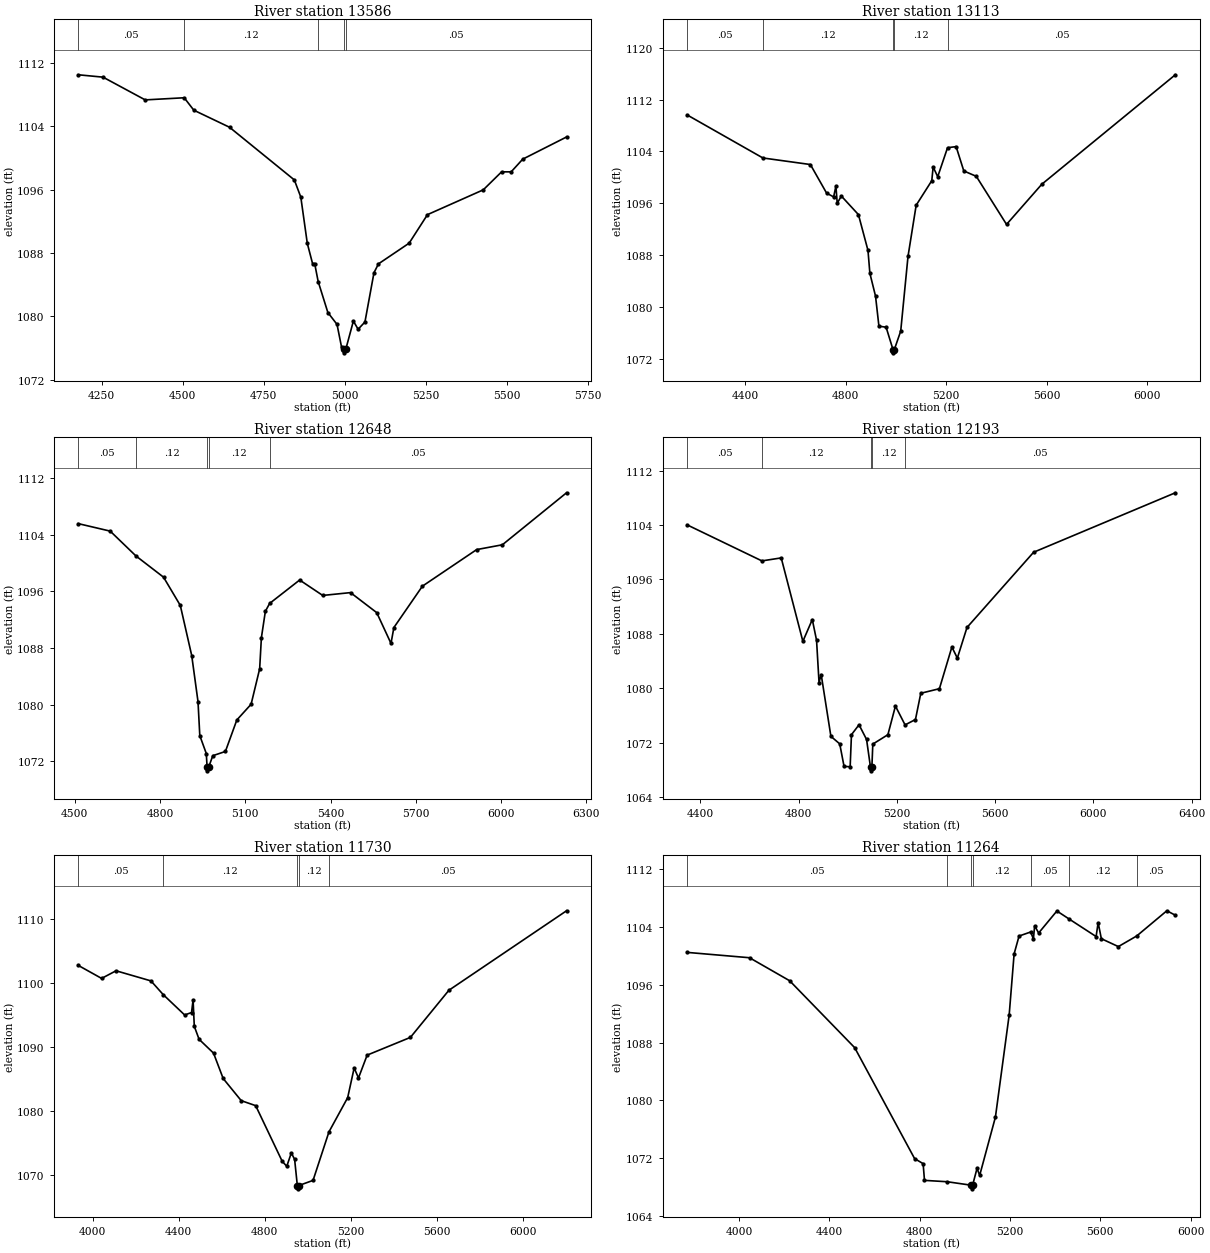
Type RM Length L Ch R = 1 ,13586   ,473,473,473
BEGIN DESCRIPTION:
Upper Denton 52 29.0
END DESCRIPTION:
XS GIS Cut Line= 4
      2188475.45      7273203.47      2187751.58      7273237.42
        2187679.        7273310.      2187123.91      7273703.45
#Sta/Elev= 30
  4177.5 1110.48    4254 1110.18  4384.2 1107.31  4504.6 1107.58  4534.3 1106.01
  4644.5 1103.86  4844.7 1097.21  4864.7 1095.04  4884.7 1089.21    4901 1086.65
  4907.5 1086.65  4918.3 1084.39  4948.2 1080.48  4976.5 1078.98  4990.7 1076.07
  4998.7 1075.89  4999.4 1075.39  5003.9 1075.89    5027  1079.4  5041.6 1078.37
  5062.7 1079.28  5090.6  1085.5  5104.5 1086.62  5199.2 1089.23  5255.8 1092.83
  5428.1 1095.96  5484.7 1098.23  5514.2 1098.23  5549.9 1099.83  5685.2 1102.63
#Mann= 5 ,-1 , 0
  4177.5     .05       0  4504.6     .12       0  4918.3     .05       0
  4998.7    .033       0  5003.9     .05       0
Bank Sta=4998.7,5003.9
XS Rating Curve= 0 ,0
Exp/Cntr=0.3,0.1

Type RM Length L Ch R = 1 ,13113   ,465,465,465
BEGIN DESCRIPTION:
Upper Denton 52 28.0
END DESCRIPTION:
XS GIS Cut Line= 5
      2188436.36      7273182.63      2187752.62      7273020.42
        2187679.        7272910.      2187611.51      7272751.43
      2186679.24      7272683.72
#Sta/Elev= 30
  4168.6 1109.64  4470.3    1103  4659.2 1101.99  4723.8 1097.58  4751.7    1097
  4760.8 1098.67    4766 1096.03  4782.5 1097.13  4850.4 1094.27  4888.4 1088.75
  4895.9 1085.23  4918.4 1081.71  4931.9 1077.08  4960.5 1076.92  4987.9 1073.47
  4988.6 1072.97  4993.2 1073.47  5018.6 1076.32  5047.6 1087.83  5080.1 1095.72
  5142.2  1099.5  5147.6 1101.61  5165.8 1100.11  5204.9 1104.58    5239 1104.75
  5269.6    1101  5319.3 1100.17  5439.6 1092.76  5579.9 1098.95  6111.1 1115.82
#Mann= 5 ,-1 , 0
  4168.6     .05       0  4470.3     .12       0  4987.9     .07       0
  4993.2     .12       0  5204.9     .05       0
Bank Sta=4987.9,4993.2
XS Rating Curve= 0 ,0
Exp/Cntr=0.3,0.1

Type RM Length L Ch R = 1 ,12648   ,455,455,455
BEGIN DESCRIPTION:
Upper Denton 52 27.0
END DESCRIPTION:
XS GIS Cut Line= 3
      2188470.88      7272866.01        2188029.        7272660.
      2186804.21      7272543.09
#Sta/Elev= 30
  4512.5 1105.59  4624.9 1104.53  4715.5 1101.02  4812.5 1098.02  4871.5 1094.03
  4911.7 1086.94  4933.8 1080.43  4940.1 1075.63    4963 1073.09  4965.8 1071.15
  4966.6 1070.65  4971.1 1071.15  4985.8 1072.79  5030.2 1073.39  5070.4 1077.84
  5120.6 1080.06  5150.7 1085.07  5156.8 1089.47  5170.8  1093.2  5185.8 1094.31
  5291.4 1097.62  5372.6 1095.44  5470.4 1095.84  5562.6 1093.01  5612.8 1088.66
  5622.9  1090.9  5723.3 1096.75  5914.2 1101.92  6004.7  1102.6  6230.4 1109.95
#Mann= 5 ,-1 , 0
  4512.5     .05       0  4715.5     .12       0  4965.8     .07       0
  4971.1     .12       0  5185.8     .05       0
Bank Sta=4965.8,4971.1
XS Rating Curve= 0 ,0
Exp/Cntr=0.3,0.1

Type RM Length L Ch R = 1 ,12193   ,463,463,463
BEGIN DESCRIPTION:
Upper Denton 52 26.0
END DESCRIPTION:
XS GIS Cut Line= 4
      2188543.82       7272772.3      2188299.07      7272308.57
        2188179.        7272260.      2186924.05      7271808.73
#Sta/Elev= 30
  4345.8 1104.02  4650.4 1098.72  4729.1 1099.16  4817.2  1086.9  4855.6  1090.1
  4872.9 1087.06    4883 1080.85  4891.8 1082.02  4931.3 1072.94  4967.3 1071.83
  4984.9 1068.51  5009.7 1068.48    5015 1073.18  5045.8 1074.64  5076.5 1072.48
  5092.6 1068.37  5093.4 1067.87  5098.1 1068.37  5101.9  1071.8  5163.3 1073.18
    5194 1077.39  5233.2 1074.62  5275.5 1075.41  5297.2 1079.27    5373 1079.94
  5423.8 1086.07    5446 1084.43  5485.3 1088.94  5756.4 1099.99  6333.3 1108.73
#Mann= 5 ,-1 , 0
  4345.8     .05       0  4650.4     .12       0  5092.6     .07       0
  5098.1     .12       0  5233.2     .05       0
Bank Sta=5092.6,5098.1
XS Rating Curve= 0 ,0
Exp/Cntr=0.3,0.1

Type RM Length L Ch R = 1 ,11730   ,466,466,466
BEGIN DESCRIPTION:
Upper Denton 52 25.0
END DESCRIPTION:
XS GIS Cut Line= 4
      2188653.16      7272730.56      2188281.11      7271986.32
        2188079.        7271860.      2186887.52      7271741.01
#Sta/Elev= 30
  3933.7 1102.68  4042.1 1100.65  4109.2 1101.84  4271.3 1100.26  4328.2 1098.12
  4427.8 1094.94  4459.8 1095.32    4467 1097.28  4472.6 1093.17  4494.9 1091.14
    4562 1088.98  4606.7 1085.02  4690.6 1081.56  4757.7 1080.78  4880.9 1072.09
  4902.1 1071.31  4923.3  1073.4  4938.6 1072.39  4951.2 1068.29    4952 1067.79
  4956.7 1068.29  5024.2 1069.11    5098 1076.68    5185 1082.03  5215.1 1086.67
  5235.2  1085.1  5275.4 1088.67  5476.4 1091.44  5655.2  1098.8  6201.5 1111.21
#Mann= 5 ,-1 , 0
  3933.7     .05       0  4328.2     .12       0  4951.2     .07       0
  4956.7     .12       0    5098     .05       0
Bank Sta=4951.2,4956.7
XS Rating Curve= 0 ,0
Exp/Cntr=0.3,0.1

Type RM Length L Ch R = 1 ,11264   ,465,465,465
BEGIN DESCRIPTION:
Upper Denton 52 24.0
END DESCRIPTION:
XS GIS Cut Line= 3
      2188694.85      7272683.73        2188329.        7271510.
      2187950.05      7270657.67
#Sta/Elev= 30
  3770.1 1100.47  4046.7 1099.73  4224.4 1096.55  4512.4  1087.3  4777.7 1071.97
  4815.5 1071.27  4821.5 1068.96  4922.5 1068.77  5028.8 1068.29  5029.7 1067.79
  5034.6 1068.29  5054.2 1070.62  5065.9 1069.65  5135.6  1077.7  5196.5 1091.81
  5218.4 1100.26  5240.3 1102.73  5291.9 1103.29  5303.8 1102.32  5309.3 1104.14
  5327.1 1103.15  5407.8 1106.19  5462.6 1105.07  5581.5 1102.66  5590.5 1104.58
  5604.7 1102.36    5680 1101.27  5761.4 1102.74  5894.7 1106.22  5932.3 1105.61
#Mann= 7 ,-1 , 0
  3770.1     .05       0  4922.5     .12       0  5028.8     .07       0
  5034.6     .12       0  5291.9     .05       0  5462.6     .12       0
  5761.4     .05       0
Bank Sta=5028.8,5034.6
XS Rating Curve= 0 ,0
Exp/Cntr=0.3,0.1

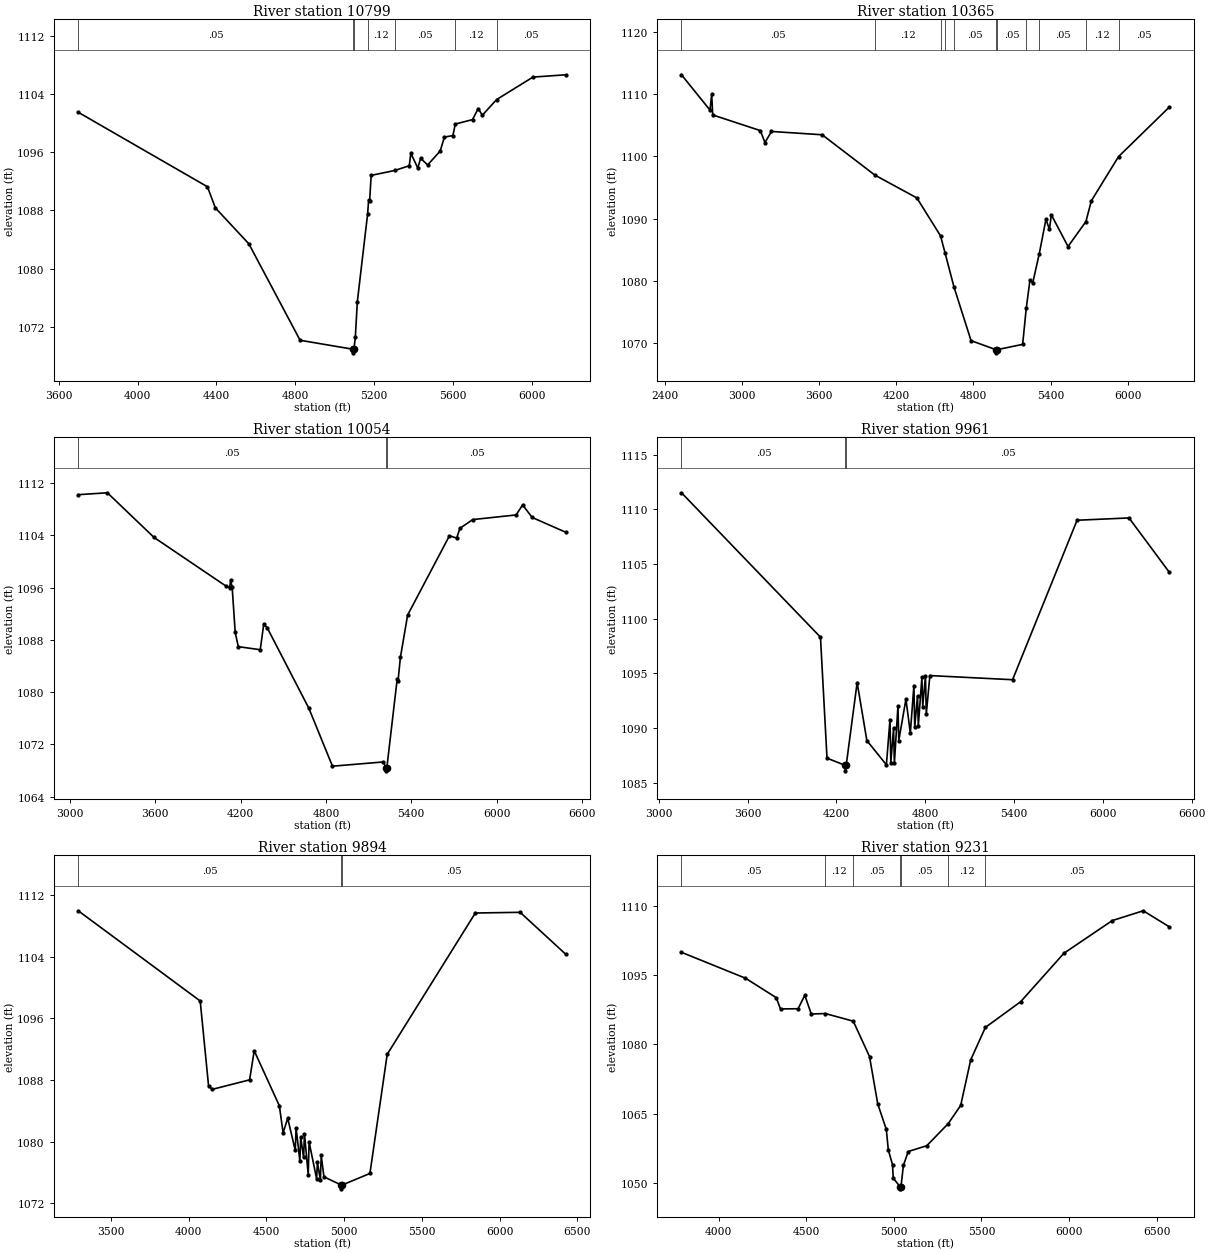
Type RM Length L Ch R = 1 ,10799   ,434,434,434
BEGIN DESCRIPTION:
Upper Denton 52 23.0
END DESCRIPTION:
XS GIS Cut Line= 4
       2188769.5      7272765.55        2188779.        7271460.
      2188760.82      7271255.12       2188002.6      7270661.54
#Sta/Elev= 30
    3699 1101.51  4354.6 1091.26  4394.6 1088.36  4564.6 1083.41  4824.6 1070.14
    5092 1068.91    5093 1068.41  5097.8 1068.91    5105 1070.62    5115 1075.46
  5167.1  1087.5  5172.3 1089.41  5177.3 1089.34  5185.3 1092.83  5306.4 1093.51
  5378.4 1094.16  5386.5 1095.87  5421.7 1093.84  5436.2 1095.18  5471.5 1094.26
  5535.7 1096.19  5556.5  1098.1  5599.9  1098.3  5611.8 1099.89  5699.3  1100.5
  5728.3 1102.02  5749.1  1101.1  5821.6 1103.26  6005.8 1106.35  6173.2 1106.67
#Mann= 7 ,-1 , 0
    3699     .05       0    5092    .033       0  5097.8     .05       0
  5167.1     .12       0  5306.4     .05       0  5611.8     .12       0
  5821.6     .05       0
Bank Sta=5092,5097.8
XS Rating Curve= 0 ,0
Exp/Cntr=0.3,0.1

Type RM Length L Ch R = 1 ,10365   ,311,311,311
BEGIN DESCRIPTION:
Upper Denton 52 22.0
END DESCRIPTION:
XS GIS Cut Line= 3
      2190012.55       7273678.5        2189179.        7271360.
      2188066.77      7270634.72
#Sta/Elev= 30
  2530.7 1113.09  2752.3 1107.42  2765.5 1109.96  2773.5 1106.64  3143.6 1104.13
  3179.7 1102.21  3230.5 1103.99  3624.5 1103.46  4033.9 1096.99  4360.6 1093.32
  4544.5 1087.24  4580.7 1084.43  4649.3 1079.02    4782 1070.41  4976.1 1068.95
  4977.1 1068.45  4982.2 1068.95  5183.1 1069.81  5211.2 1075.61  5240.4 1080.19
  5261.5 1079.67  5312.4 1084.37  5364.2 1089.87  5391.3 1088.29  5406.4  1090.6
  5536.1 1085.52  5675.1 1089.53  5717.2 1092.85  5928.5 1099.95  6322.3 1107.88
#Mann= 11 ,-1 , 0
  2530.7     .05       0  4033.9     .12       0  4544.5     .05       0
  4580.7     .12       0  4649.3     .05       0  4976.1    .033       0
  4982.2     .05       0  5211.2     .12       0  5312.4     .05       0
  5675.1     .12       0  5928.5     .05       0
Bank Sta=4976.1,4982.2
XS Rating Curve= 0 ,0
Exp/Cntr=0.3,0.1

Type RM Length L Ch R = 1 ,10054   ,93,93,93
BEGIN DESCRIPTION:
Upper Denton 52 21.5
END DESCRIPTION:
XS GIS Cut Line= 3
      2190141.01      7272973.84       2189416.2      7271172.65
      2188770.36      7269833.29
#Sta/Elev= 30
  3058.6 1110.22  3263.5 1110.51  3591.3 1103.68  4099.1 1096.21  4123.3 1095.99
  4129.9 1097.09  4140.7 1096.06  4162.2 1089.14  4183.8 1086.97  4338.2  1086.5
  4362.4 1090.36  4386.6 1089.88  4679.4 1077.57    4846 1068.68  5202.9 1069.33
    5222 1068.47    5223 1067.97  5228.3 1068.47  5300.9 1081.99  5306.5 1081.66
  5323.5 1085.33  5374.3  1091.8  5668.3 1103.93  5719.1 1103.58  5741.7 1105.07
  5832.1 1106.41  6137.2 1107.12  6182.4 1108.65  6250.3 1106.73  6487.1 1104.46
#Mann= 3 ,-1 , 0
  3058.6     .05       0    5222    .033       0  5228.3     .05       0
Bank Sta=5222,5228.3
XS Rating Curve= 0 ,0
Exp/Cntr=0.3,0.1

Type RM Length L Ch R = 1 ,9961    ,67,67,67
BEGIN DESCRIPTION:
Upper Denton 52 21.4
END DESCRIPTION:
XS GIS Cut Line= 3
      2190167.08      7272821.99      2189476.96      7271094.53
      2188856.31      7269801.14
#Sta/Elev= 30
  3153.2 1111.51  4092.2 1098.31  4136.3 1087.25  4259.7 1086.59  4260.7 1086.09
    4266 1086.59  4339.9 1094.16  4405.6 1088.86  4537.6 1086.64  4561.9 1090.78
  4567.3 1086.83  4586.1 1089.99  4591.5 1086.81  4615.8 1092.04  4621.2 1088.85
  4669.6 1092.64  4699.3 1089.55  4723.5 1093.89  4728.9 1090.06  4747.8 1092.96
  4753.2 1090.21  4777.4 1094.64  4782.8 1091.97  4801.6 1094.76    4807 1091.27
  4831.3  1094.8    5390 1094.42  5825.9    1109  6176.7 1109.21    6448 1104.26
#Mann= 3 ,-1 , 0
  3153.2     .05       0  4259.7    .033       0    4266     .05       0
Bank Sta=4259.7,4266
XS Rating Curve= 0 ,0
Exp/Cntr=0.3,0.1

Type RM Length L Ch R = 1 ,9894    ,663,663,663
BEGIN DESCRIPTION:
Upper Denton 52 21.0
END DESCRIPTION:
XS GIS Cut Line= 3
       2190163.6      7272647.27        2189529.        7271060.
      2188908.37      7269775.06
#Sta/Elev= 30
  3290.2 1109.98  4074.6 1098.26  4128.4 1087.22  4152.7 1086.78  4392.3 1088.01
    4422 1091.79  4583.5 1084.65  4607.8 1081.13  4637.4 1083.02  4685.9 1078.85
  4691.3 1081.77  4715.5 1077.49  4720.9 1080.56  4739.7 1077.93  4745.1 1081.02
  4769.4 1075.66  4774.8 1079.96  4823.2 1075.16  4828.6 1077.28  4847.5 1074.98
  4852.9 1078.19  4870.4 1075.41  4981.7 1074.35  4982.7 1073.85    4988 1074.35
  5166.2 1075.85  5277.3 1091.33    5844 1109.69  6132.3 1109.78  6426.6 1104.31
#Mann= 3 ,-1 , 0
  3290.2     .05       0  4981.7    .033       0    4988     .05       0
Bank Sta=4981.7,4988
XS Rating Curve= 0 ,0
Exp/Cntr=0.3,0.1

Type RM Length L Ch R = 1 ,9231    ,370,370,370
BEGIN DESCRIPTION:
Upper Denton 52 20.0
END DESCRIPTION:
XS GIS Cut Line= 4
      2190449.18      7272090.61      2190010.82      7270962.15
      2189806.82       7270558.5      2189022.64      7269756.99
#Sta/Elev= 30
  3787.4 1099.92  4152.8 1094.32  4328.1 1090.12  4352.7 1087.68  4453.2 1087.72
  4491.4 1090.63  4528.3 1086.58  4608.9 1086.68  4768.1 1085.03  4860.9 1077.38
  4907.8 1067.14  4956.8 1061.63  4968.1  1057.2  4992.1 1054.02  4996.5 1051.09
  5034.3 1049.28  5035.3 1048.78  5040.7 1049.28  5054.2 1053.83    5082 1056.85
  5187.9 1058.11  5310.6  1062.9  5381.4 1066.82  5438.7 1076.68  5522.5 1083.69
  5723.5 1089.23  5970.9 1099.72  6246.7 1106.78  6423.6  1108.9  6571.6 1105.45
#Mann= 7 ,-1 , 0
  3787.4     .05       0  4608.9     .12       0  4768.1     .05       0
  5034.3    .033       0  5040.7     .05       0  5310.6     .12       0
  5522.5     .05       0
Bank Sta=5034.3,5040.7
XS Rating Curve= 0 ,0
Exp/Cntr=0.3,0.1

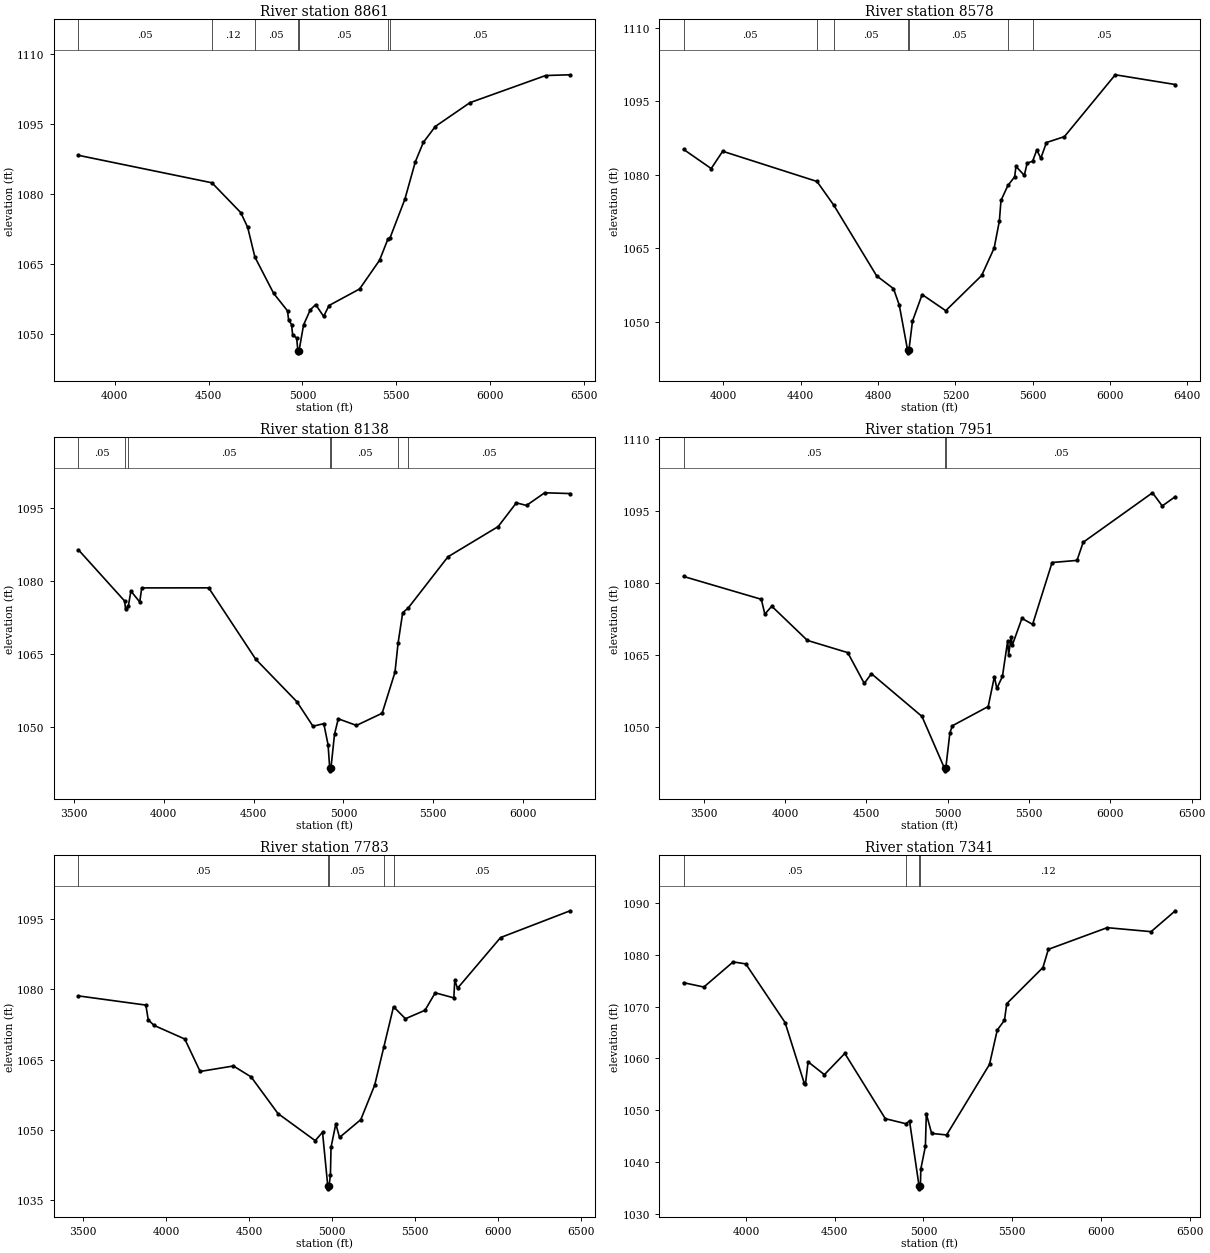
Type RM Length L Ch R = 1 ,8861    ,283,283,283
BEGIN DESCRIPTION:
Upper Denton 52 19.0
END DESCRIPTION:
XS GIS Cut Line= 3
      2190857.18      7271717.38      2190236.51      7270675.69
       2189303.7      7269621.39
#Sta/Elev= 30
  3806.5  1088.3  4517.9 1082.41  4671.5 1076.02  4708.5 1072.85  4746.7  1066.5
  4846.7 1058.71  4920.7 1054.95  4926.5    1053  4942.1 1052.02  4947.9 1049.83
  4969.3 1049.13  4975.9 1046.45  4976.9 1045.95  4982.4 1046.45  5006.3 1051.94
  5042.3 1055.19  5070.8 1056.29  5113.4 1053.76  5141.9  1056.1    5305 1059.65
  5411.2  1065.8  5455.3  1070.3  5467.4 1070.64  5545.9 1078.86  5601.9 1086.92
  5644.6 1091.08  5708.1 1094.48    5893 1099.59  6296.2 1105.41  6426.8 1105.57
#Mann= 7 ,-1 , 0
  3806.5     .05       0  4517.9     .12       0  4746.7     .05       0
  4975.9    .033       0  4982.4     .05       0  5455.3     .12       0
  5467.4     .05       0
Bank Sta=4975.9,4982.4
XS Rating Curve= 0 ,0
Exp/Cntr=0.3,0.1

Type RM Length L Ch R = 1 ,8578    ,440,440,440
BEGIN DESCRIPTION:
Upper Denton 52 18.0
END DESCRIPTION:
XS GIS Cut Line= 3
      2190961.33      7271665.25        2190479.        7270560.
      2189673.13      7269491.93
#Sta/Elev= 30
  3794.1 1085.15  3936.8 1081.24  3996.2 1084.77  4484.1 1078.61  4571.2 1073.76
  4792.8 1059.35    4880 1056.75  4909.9 1053.39  4953.1 1044.15  4954.2 1043.65
  4959.6 1044.15  4978.2 1050.12  5028.1 1055.54  5150.3 1052.25  5336.2 1059.43
  5400.7 1065.01  5427.8 1070.55  5436.1 1074.74  5472.3 1077.82  5506.9 1079.55
  5513.6 1081.69  5556.8 1079.85  5571.4 1082.35  5599.7 1082.74  5621.4 1085.03
  5642.2 1083.34  5671.3 1086.55  5764.2 1087.75  6027.3 1100.37    6338 1098.38
#Mann= 7 ,-1 , 0
  3794.1     .05       0  4484.1     .12       0  4571.2     .05       0
  4953.1    .033       0  4959.6     .05       0  5472.3     .12       0
  5599.7     .05       0
Bank Sta=4953.1,4959.6
XS Rating Curve= 0 ,0
Exp/Cntr=0.3,0.1

Type RM Length L Ch R = 1 ,8138    ,187,187,187
BEGIN DESCRIPTION:
Upper Denton 52 17.0
END DESCRIPTION:
XS GIS Cut Line= 4
      2191013.42      7271700.02      2190861.51      7270380.55
        2190779.        7270260.      2189746.64      7269534.61
#Sta/Elev= 30
  3525.7 1086.33  3782.4 1075.83  3787.7 1074.22  3803.2 1074.74  3817.6 1077.86
  3866.7 1075.62    3878 1078.51  4250.5 1078.52  4512.2 1063.86  4741.7 1055.11
  4830.7 1050.09  4890.9 1050.62  4914.7 1046.31    4924 1041.43    4925 1040.93
  4930.6 1041.43  4950.6 1048.44  4971.5 1051.62  5072.7 1050.26  5215.6 1052.76
  5287.1 1061.18  5304.2 1067.13    5330 1073.42    5360 1074.35  5581.6 1084.89
  5861.3 1091.11  5962.4 1095.98    6019 1095.45  6120.1 1098.05  6261.7 1097.89
#Mann= 7 ,-1 , 0
  3525.7     .05       0  3782.4     .12       0  3803.2     .05       0
    4924    .033       0  4930.6     .05       0  5304.2     .12       0
    5360     .05       0
Bank Sta=4924,4930.6
XS Rating Curve= 0 ,0
Exp/Cntr=0.3,0.1

Type RM Length L Ch R = 1 ,7951    ,168,168,168
BEGIN DESCRIPTION:
Upper Denton 52 16.5
END DESCRIPTION:
XS GIS Cut Line= 4
      2192211.33      7271122.73      2191412.73      7270402.25
      2190881.43      7270129.27      2189693.96      7269486.44
#Sta/Elev= 30
  3376.4 1081.36  3854.2  1076.6  3875.9  1073.5  3918.3 1075.16  4137.4 1068.03
  4385.5 1065.48    4487 1059.07  4531.4 1061.08  4841.9 1052.18  4980.9 1041.33
  4982.1 1040.83  4988.2 1041.33  5013.8 1048.81  5029.5 1050.24  5249.2 1054.24
  5287.3 1060.48  5302.2    1058  5336.7 1060.52  5369.1 1067.98  5374.7 1065.05
  5390.9 1068.78  5396.6 1066.97  5456.6 1072.63  5522.2 1071.37  5642.1 1084.27
  5795.2 1084.71  5833.2 1088.49  6259.3 1098.81  6319.3 1096.06  6399.6 1098.01
#Mann= 3 ,-1 , 0
  3376.4     .05       0  4980.9    .033       0  4988.2     .05       0
Bank Sta=4980.9,4988.2
XS Rating Curve= 0 ,0
Exp/Cntr=0.3,0.1

Type RM Length L Ch R = 1 ,7783    ,442,442,442
BEGIN DESCRIPTION:
Upper Denton 52 16.0
END DESCRIPTION:
XS GIS Cut Line= 4
      2192220.02      7270901.39      2191503.87      7270311.11
       2191000.4      7270007.29       2189703.4      7269365.29
#Sta/Elev= 30
  3471.4 1078.57  3877.7 1076.61  3892.1 1073.46  3927.2 1072.28  4112.3 1069.37
  4204.8 1062.45  4405.2 1063.62  4512.1 1061.29  4673.8 1053.48  4898.4 1047.69
  4942.4 1049.49  4974.3 1037.91  4975.4 1037.41  4981.6 1037.91  4990.1 1040.45
  4993.7 1046.26  5022.5 1051.27  5044.9 1048.37  5173.1 1052.18  5256.9 1059.54
  5312.3 1067.72  5370.3 1076.26  5442.2  1073.7    5560  1075.5  5621.7 1079.23
  5733.8 1078.15  5739.4 1081.89  5756.2  1080.2  6015.6 1091.02  6434.7 1096.73
#Mann= 5 ,-1 , 0
  3471.4     .05       0  4974.3    .033       0  4981.6     .05       0
  5312.3     .12       0  5370.3     .05       0
Bank Sta=4974.3,4981.6
XS Rating Curve= 0 ,0
Exp/Cntr=0.3,0.1

Type RM Length L Ch R = 1 ,7341    ,511,511,511
BEGIN DESCRIPTION:
Upper Denton 52 15.0
END DESCRIPTION:
XS GIS Cut Line= 3
      2192306.83       7270471.7      2191208.73      7269668.75
      2189893.78      7269156.65
#Sta/Elev= 30
  3647.9 1074.62  3761.9 1073.78  3927.1 1078.63  3998.2 1078.25  4219.8 1066.93
  4326.6 1055.35  4334.8  1055.1  4349.5 1059.35  4441.4 1056.87  4556.5 1060.97
  4784.9 1048.37  4900.7  1047.4  4921.2 1047.95  4975.2 1035.33  4976.3 1034.83
  4982.5 1035.33    4985 1038.67  5010.8 1043.05  5015.9 1049.32  5045.8 1045.53
  5130.1 1045.23  5372.1 1058.85  5415.8 1065.48  5456.4 1067.37  5469.4 1070.58
  5673.3 1077.55  5703.8 1081.06  6035.5 1085.24  6282.9 1084.47  6419.4  1088.5
#Mann= 4 ,-1 , 0
  3647.9     .05       0  4900.7     .12       0  4975.2     .07       0
  4982.5     .12       0
Bank Sta=4975.2,4982.5
XS Rating Curve= 0 ,0
Exp/Cntr=0.3,0.1