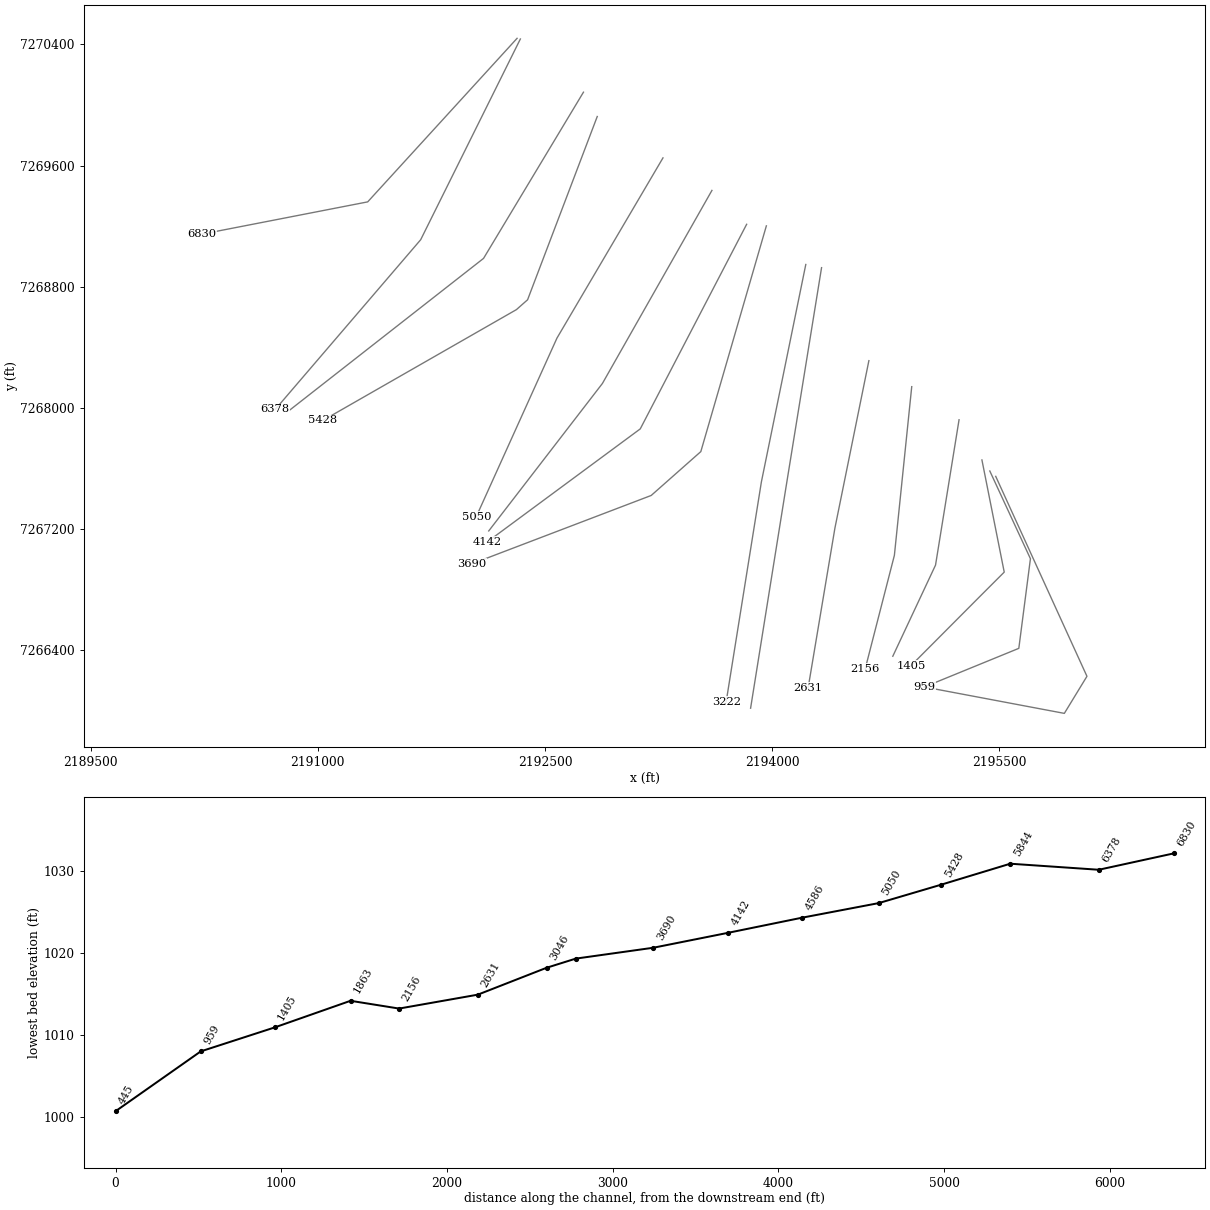
HEC-RAS study Upper Denton 52.prj: Upper Denton 52 Base Level Engineering

--- Upper Denton 52.g01 (geometry) --- (continued)

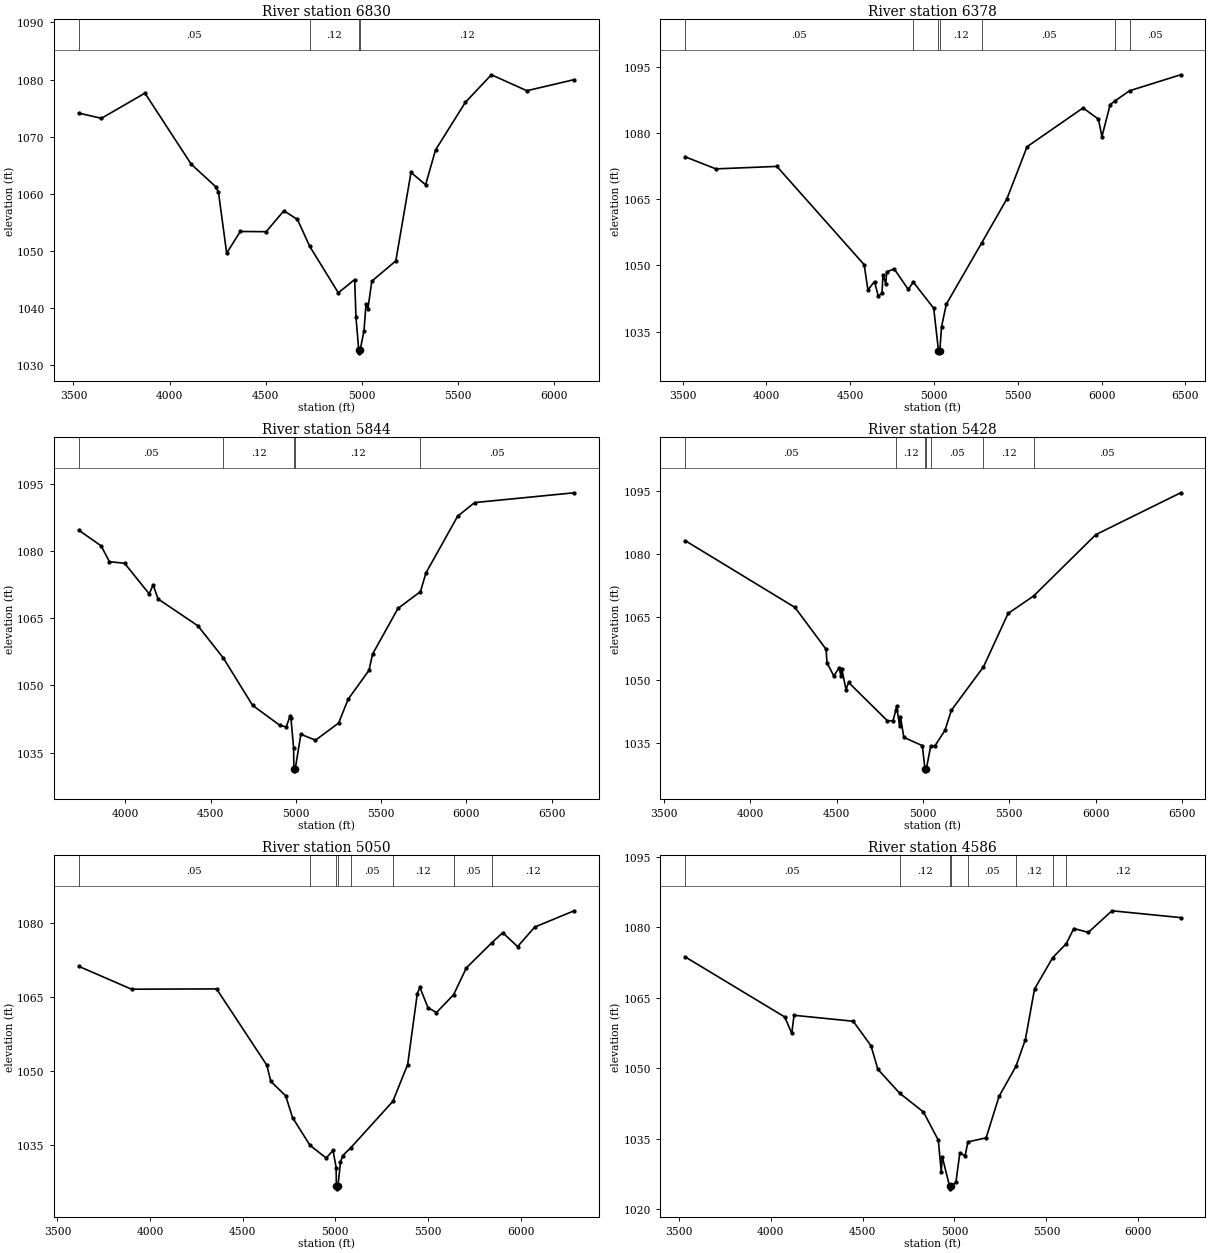
Type RM Length L Ch R = 1 ,6830    ,452,452,452
BEGIN DESCRIPTION:
Upper Denton 52 14.0
END DESCRIPTION:
XS GIS Cut Line= 3
      2192315.49      7270440.58        2191329.        7269360.
      2190236.49      7269147.18
#Sta/Elev= 30
    3527 1074.14  3645.4 1073.22  3871.7 1077.63  4112.2  1065.2  4239.9 1061.26
  4254.1 1060.28  4296.6 1049.63  4367.3 1053.43    4502 1053.39  4593.9 1057.05
  4664.8 1055.53  4728.2 1050.84    4877  1042.7  4962.1 1045.02  4968.9 1038.41
  4983.1  1032.7  4984.2  1032.2  4990.5  1032.7  5010.5 1036.03  5021.1  1040.8
  5030.9 1039.92  5051.3 1044.74  5175.9 1048.28    5255 1063.76  5330.8 1061.59
  5382.4 1067.69  5537.3 1076.01  5672.7 1080.84  5857.2 1078.05  6103.2 1079.99
#Mann= 4 ,-1 , 0
    3527     .05       0  4728.2     .12       0  4983.1     .07       0
  4990.5     .12       0
Bank Sta=4983.1,4990.5
XS Rating Curve= 0 ,0
Exp/Cntr=0.3,0.1

Type RM Length L Ch R = 1 ,6378    ,534,534,534
BEGIN DESCRIPTION:
Upper Denton 52 13.0
END DESCRIPTION:
XS GIS Cut Line= 3
      2192337.19      7270436.21        2191679.        7269110.
      2190718.29      7267988.35
#Sta/Elev= 30
  3514.4 1074.58  3697.9 1071.84  4062.1  1072.4  4583.1 1050.15  4605.6 1044.43
  4644.8 1046.34  4667.2 1043.03  4689.6 1043.71  4695.2 1047.82    4712 1045.89
  4717.6 1048.54  4762.4 1049.19  4846.5 1044.54  4875.9 1046.24  4998.2 1040.28
  5026.6  1030.7  5027.8  1030.2  5034.6  1030.7  5044.9 1036.11  5073.4 1041.22
  5285.6 1055.16  5434.6 1065.02  5555.3 1076.86    5889 1085.63  5981.2 1083.11
    6002 1079.14  6051.4  1086.4  6080.4 1087.23  6166.8 1089.52  6471.8 1093.14
#Mann= 7 ,-1 , 0
  3514.4     .05       0  4875.9     .12       0  5026.6     .07       0
  5034.6     .12       0  5285.6     .05       0  6080.4     .12       0
  6166.8     .05       0
Bank Sta=5026.6,5034.6
XS Rating Curve= 0 ,0
Exp/Cntr=0.3,0.1

Type RM Length L Ch R = 1 ,5844    ,416,416,416
BEGIN DESCRIPTION:
Upper Denton 52 12.0
END DESCRIPTION:
XS GIS Cut Line= 3
      2192753.88      7270084.71      2192094.15       7268986.6
      2190814.53      7267984.59
#Sta/Elev= 30
  3725.3 1084.67  3857.1 1081.16  3905.8 1077.63  3995.1 1077.26  4139.1 1070.44
  4162.4 1072.44  4191.3  1069.3  4424.5 1063.32  4573.9 1056.13  4745.7 1045.55
  4906.4 1041.07  4943.3 1040.76  4964.7 1043.15  4970.5 1042.75  4986.1 1036.06
  4987.8 1031.44    4989 1030.94    4996 1031.44  5028.6  1039.1  5114.5 1037.78
  5250.1 1041.61  5306.1 1046.93  5428.2 1053.37    5449 1056.98  5598.2 1067.19
    5730 1070.94  5762.3 1075.11  5948.1 1087.76  6047.5 1090.81  6631.6    1093
#Mann= 5 ,-1 , 0
  3725.3     .05       0  4573.9     .12       0  4987.8     .07       0
    4996     .12       0    5730     .05       0
Bank Sta=4987.8,4996
XS Rating Curve= 0 ,0
Exp/Cntr=0.3,0.1

Type RM Length L Ch R = 1 ,5428    ,378,378,378
BEGIN DESCRIPTION:
Upper Denton 52 11.0
END DESCRIPTION:
XS GIS Cut Line= 4
      2192845.02       7269924.1      2192384.95      7268713.16
      2192311.16      7268648.06      2191032.78      7267915.69
#Sta/Elev= 30
  3623.9  1083.1  4259.4 1067.22  4439.6 1057.28    4445 1054.05  4484.1 1050.94
  4516.2 1052.91  4524.7 1050.93    4530 1052.68  4554.8 1047.71  4569.7 1049.39
  4794.3 1040.28  4826.4 1040.27  4844.2  1042.9  4847.8 1043.79  4864.7 1039.11
  4870.1 1041.14  4889.5 1036.34  4996.3 1034.37  5011.7 1028.88  5012.9 1028.38
  5019.9 1028.88  5045.1  1034.3  5068.1 1034.24  5127.1 1037.98  5164.5 1042.78
  5350.1 1053.08  5492.7 1065.78  5640.4 1069.93  5999.8  1084.5    6491 1094.46
#Mann= 7 ,-1 , 0
  3623.9     .05       0  4844.2     .12       0  5011.7     .07       0
  5019.9     .12       0  5045.1     .05       0  5350.1     .12       0
  5640.4     .05       0
Bank Sta=5011.7,5019.9
XS Rating Curve= 0 ,0
Exp/Cntr=0.3,0.1

Type RM Length L Ch R = 1 ,5050    ,464,464,464
BEGIN DESCRIPTION:
Upper Denton 52 10.0
END DESCRIPTION:
XS GIS Cut Line= 3
      2193279.07       7269650.7        2192579.        7268460.
       2192046.4      7267280.86
#Sta/Elev= 30
  3614.2 1071.16  3899.8 1066.52  4358.7 1066.58  4630.2 1051.14  4651.7 1047.86
  4731.8 1044.95  4768.9 1040.55  4862.9 1034.94  4950.5 1032.36  4987.6 1033.88
  5004.3  1030.4  5005.6 1026.62  5006.8 1026.12    5014 1026.62  5027.4 1031.46
  5039.3 1032.82  5084.5 1034.48  5310.3 1043.82  5390.5 1051.28  5442.4 1065.62
  5456.3 1066.89  5500.2 1062.79  5545.8 1061.79  5638.3  1065.4  5707.6 1070.85
  5844.7 1075.92  5903.6 1077.96  5983.9 1075.14  6076.4  1079.1  6289.3 1082.39
#Mann= 8 ,-1 , 0
  3614.2     .05       0  4862.9     .12       0  5005.6     .07       0
    5014     .12       0  5084.5     .05       0  5310.3     .12       0
  5638.3     .05       0  5844.7     .12       0
Bank Sta=5005.6,5014
XS Rating Curve= 0 ,0
Exp/Cntr=0.3,0.1

Type RM Length L Ch R = 1 ,4586    ,444,444,444
BEGIN DESCRIPTION:
Upper Denton 52 9.0
END DESCRIPTION:
XS GIS Cut Line= 3
      2193602.37      7269435.78        2192879.        7268160.
      2192128.42       7267185.8
#Sta/Elev= 30
  3534.1 1073.75  4076.7 1060.93  4114.3 1057.42    4127  1061.3  4448.9 1060.03
  4545.6 1054.81  4583.1 1049.79  4701.2 1044.72  4831.2 1040.69    4912 1034.69
  4927.8 1027.96  4933.6 1031.13  4973.5 1024.83  4974.7 1024.33  4981.9 1024.83
  5007.9  1025.8  5028.8 1031.89  5057.8 1031.41  5073.1 1034.33  5171.9 1035.19
  5242.6 1044.03  5334.3 1050.42  5385.7 1056.13  5435.5  1066.9  5534.4 1073.58
  5607.8 1076.53  5649.3 1079.78  5728.2 1078.96  5856.8 1083.56  6230.5 1082.11
#Mann= 8 ,-1 , 0
  3534.1     .05       0  4701.2     .12       0  4973.5     .07       0
  4981.9     .12       0  5073.1     .05       0  5334.3     .12       0
  5534.4     .05       0  5607.8     .12       0
Bank Sta=4973.5,4981.9
XS Rating Curve= 0 ,0
Exp/Cntr=0.3,0.1

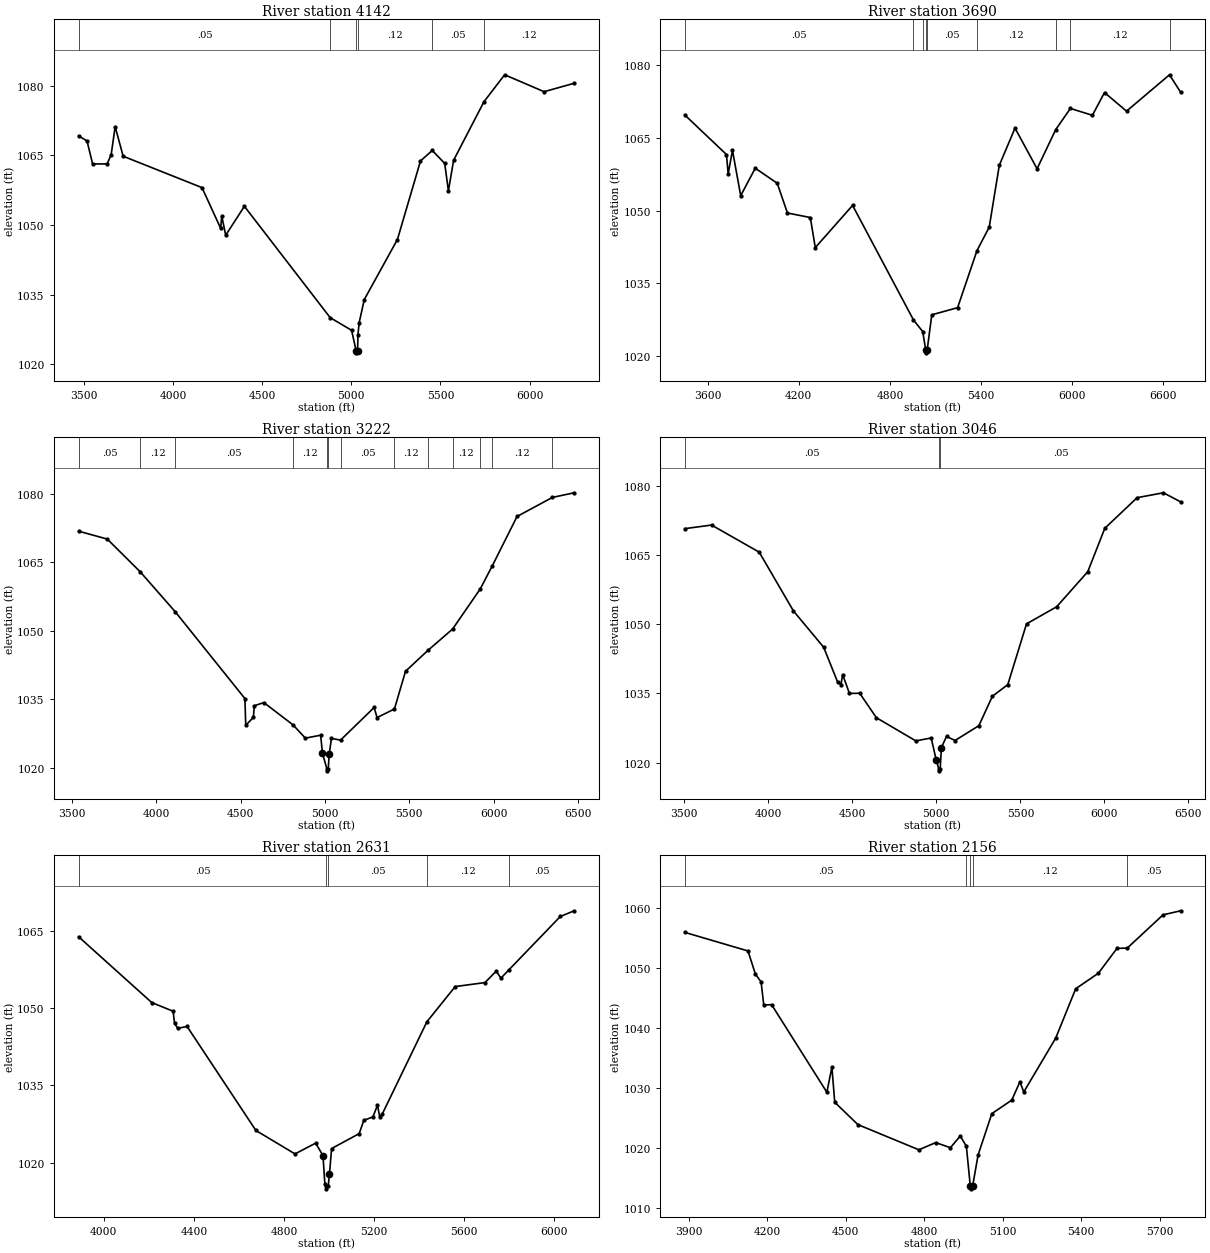
Type RM Length L Ch R = 1 ,4142    ,452,452,452
BEGIN DESCRIPTION:
Upper Denton 52 8.0
END DESCRIPTION:
XS GIS Cut Line= 3
      2193831.55      7269211.83        2193129.        7267860.
      2192119.44      7267113.95
#Sta/Elev= 30
    3471 1069.18  3518.1  1068.1  3549.4 1063.15  3630.8 1063.15  3653.4 1065.15
  3675.9 1071.17  3720.6 1064.81  4162.9 1058.05  4267.8 1049.26  4273.4 1051.96
  4295.8 1047.81  4400.5 1054.03  4881.7 1030.06  5001.8 1027.34  5026.8 1022.99
  5028.1 1022.49  5035.3 1022.99  5037.3 1026.39  5044.2    1029  5072.8 1033.96
  5258.6 1046.88    5388 1063.79  5454.1 1066.05  5523.7 1063.26  5544.6 1057.37
  5573.8 1063.95  5744.1 1076.55  5859.9 1082.34  6081.1  1078.7  6249.8 1080.51
#Mann= 6 ,-1 , 0
    3471     .05       0  4881.7     .12       0  5026.8     .07       0
  5035.3     .12       0  5454.1     .05       0  5744.1     .12       0
Bank Sta=5026.8,5035.3
XS Rating Curve= 0 ,0
Exp/Cntr=0.3,0.1

Type RM Length L Ch R = 1 ,3690    ,468,468,468
BEGIN DESCRIPTION:
Upper Denton 52 7.0
END DESCRIPTION:
XS GIS Cut Line= 4
      2193961.78      7269201.48        2193529.        7267710.
      2193201.35      7267420.19      2192013.89      7266967.08
#Sta/Elev= 30
  3451.6 1069.69  3723.9 1061.59  3735.1 1057.62  3763.5 1062.43  3817.6  1053.1
  3913.3 1058.77    4058 1055.66  4125.1 1049.52  4275.7 1048.59  4308.5 1042.38
  4553.9 1051.09  4954.8 1027.44  5015.3 1025.06  5035.9 1021.16  5037.2 1020.66
  5044.4 1021.16  5075.3 1028.51  5245.1 1029.98  5372.6 1041.76  5453.2  1046.6
  5519.5 1059.36    5623 1067.04  5768.1 1058.65  5890.6 1066.72  5987.3  1071.1
  6132.3 1069.69  6211.9 1074.39  6356.9 1070.54  6639.7 1078.05    6713 1074.44
#Mann= 9 ,-1 , 0
  3451.6     .05       0  4954.8     .12       0  5015.3     .05       0
  5035.9     .07       0  5044.4     .05       0  5372.6     .12       0
  5890.6     .05       0  5987.3     .12       0  6639.7     .05       0
Bank Sta=5035.9,5044.4
XS Rating Curve= 0 ,0
Exp/Cntr=0.3,0.1

Type RM Length L Ch R = 1 ,3222    ,176,176,176
BEGIN DESCRIPTION:
Upper Denton 52 6.0
END DESCRIPTION:
XS GIS Cut Line= 3
      2194222.19      7268946.26        2193929.        7267510.
      2193696.15       7266055.6
#Sta/Elev= 30
  3538.8 1071.83  3708.5  1070.1  3904.5 1062.91  4111.5 1054.19  4524.8 1035.17
  4529.9  1029.3  4575.3 1031.05  4580.4 1033.59  4637.3 1034.28  4810.8 1029.38
  4883.5 1026.49  4974.1 1027.14  4984.5 1023.24  5010.4 1019.83  5011.7 1019.33
  5019.2 1019.83  5024.9 1023.01  5038.2 1026.44  5092.1 1026.06  5291.3 1033.21
  5308.5    1031  5411.7 1032.88  5477.3 1041.13  5610.5 1045.72  5756.4 1050.38
  5920.5 1059.17  5991.2 1064.18  6138.9 1075.05  6348.2 1079.22  6477.6 1080.24
#Mann= 13 ,-1 , 0
  3538.8     .05       0  3904.5     .12       0  4111.5     .05       0
  4810.8     .12       0  5010.4     .07       0  5019.2     .12       0
  5092.1     .05       0  5411.7     .12       0  5610.5     .05       0
  5756.4     .12       0  5920.5     .05       0  5991.2     .12       0
  6348.2     .05       0
Bank Sta=4984.5,5024.9
XS Rating Curve= 0 ,0
Exp/Cntr=0.3,0.1

Type RM Length L Ch R = 1 ,3046    ,415,415,415
BEGIN DESCRIPTION:
Upper Denton 52 5.5
END DESCRIPTION:
XS GIS Cut Line= 3
      2194326.35       7268925.4      2194090.46      7267468.33
      2193857.69      7266014.49
#Sta/Elev= 30
  3505.1 1070.67  3662.5 1071.44  3946.2 1065.57  4149.7 1052.84  4329.7 1044.97
  4412.2 1037.47  4432.4 1036.88  4442.5 1039.06  4483.1 1034.97  4543.9 1035.02
  4643.1 1029.72  4878.1 1024.69  4969.3 1025.34  4999.7 1020.48  5013.9 1018.71
  5015.2 1018.21    5023 1018.71  5030.1 1023.24  5060.5 1025.67  5111.1 1024.78
  5252.9 1027.99  5333.6 1034.37  5425.1 1036.88  5536.5 1050.04  5715.7 1053.74
    5901 1061.34  6002.3 1070.74  6194.7 1077.37    6351 1078.43  6453.5 1076.46
#Mann= 3 ,-1 , 0
  3505.1     .05       0  5013.9    .033       0    5023     .05       0
Bank Sta=4999.7,5030.1
XS Rating Curve= 0 ,0
Exp/Cntr=0.3,0.1

Type RM Length L Ch R = 1 ,2631    ,475,475,475
BEGIN DESCRIPTION:
Upper Denton 52 5.0
END DESCRIPTION:
XS GIS Cut Line= 3
      2194638.86      7268310.82       2194414.9      7267206.65
      2194237.81      7266149.33
#Sta/Elev= 30
  3888.6 1063.84  4212.9 1051.08  4307.8 1049.39  4314.2 1047.05  4328.2 1046.08
  4369.9 1046.43  4675.1 1026.25  4848.6  1021.7  4940.4 1023.79  4972.8 1021.37
  4981.2 1015.79  4986.8 1015.42  4988.2 1014.92    4996 1015.42  5001.6 1017.82
    5011 1022.74  5133.5 1025.64  5153.8 1028.22  5194.4 1028.88  5214.6 1031.16
  5224.8 1028.84  5234.9 1029.36  5433.9 1047.35  5559.4 1054.18  5691.4 1054.95
  5741.9 1057.19  5762.2 1055.81  5797.8 1057.43  6025.8 1067.78  6087.3 1068.89
#Mann= 5 ,-1 , 0
  3888.6     .05       0  4986.8    .033       0    4996     .05       0
  5433.9     .12       0  5797.8     .05       0
Bank Sta=4972.8,5001.6
XS Rating Curve= 0 ,0
Exp/Cntr=0.3,0.1

Type RM Length L Ch R = 1 ,2156    ,293,293,293
BEGIN DESCRIPTION:
Upper Denton 52 4.0
END DESCRIPTION:
XS GIS Cut Line= 3
      2194921.84      7268139.12      2194807.26      7267024.53
      2194614.61      7266274.75
#Sta/Elev= 30
    3886 1055.91  4126.4 1052.83  4154.9 1048.97  4176.6 1047.67  4186.7 1043.84
  4216.9 1043.88    4428  1029.3  4447.3 1033.48  4458.1 1027.64  4546.5 1023.92
  4779.8 1019.72    4844 1020.92  4900.4 1020.07  4938.1 1022.02  4961.4 1020.31
  4976.3 1013.72  4977.6 1013.22  4985.5 1013.72  5006.2 1018.86  5058.7 1025.74
    5135 1027.99    5166 1031.04  5180.9 1029.35  5303.1 1038.33  5379.4 1046.54
  5466.1 1049.12  5537.2 1053.26  5576.6 1053.31  5713.2 1058.84  5780.6 1059.52
#Mann= 5 ,-1 , 0
    3886     .05       0  4961.4     .12       0  4976.3     .07       0
  4985.5     .12       0  5576.6     .05       0
Bank Sta=4976.3,4985.5
XS Rating Curve= 0 ,0
Exp/Cntr=0.3,0.1

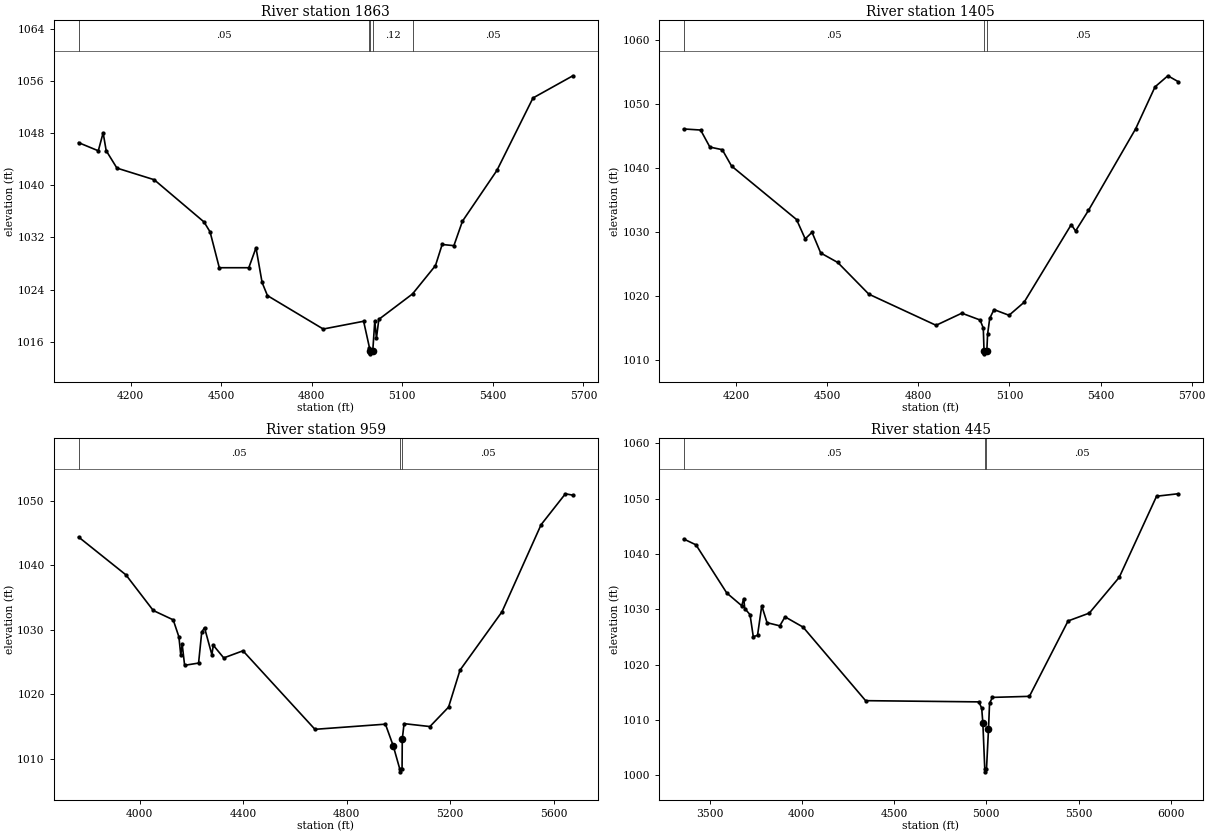
Type RM Length L Ch R = 1 ,1863    ,458,458,458
BEGIN DESCRIPTION:
Upper Denton 52 3.0
END DESCRIPTION:
XS GIS Cut Line= 3
      2195234.33      7267920.32        2195079.        7266960.
      2194796.83      7266357.83
#Sta/Elev= 30
  4027.1 1046.52  4092.5 1045.27  4108.5 1048.02  4118.6 1045.29  4154.2 1042.62
  4277.6 1040.84  4442.8 1034.37  4462.8 1032.85  4493.4 1027.36  4591.2 1027.36
    4615 1030.41  4635.2  1025.1  4652.9 1023.09  4837.8 1017.97  4971.6 1019.16
    4991  1015.1  4992.8 1014.67  4994.1 1014.17    5002 1014.67  5008.6 1019.22
  5014.1 1016.57    5022 1019.45  5133.7 1023.35  5209.7 1027.69  5231.8 1030.92
  5270.7 1030.74    5299 1034.48  5413.2 1042.26  5532.8 1053.36  5664.9 1056.76
#Mann= 5 ,-1 , 0
  4027.1     .05       0    4991     .12       0  4992.8     .07       0
    5002     .12       0  5133.7     .05       0
Bank Sta=4992.8,5002
XS Rating Curve= 0 ,0
Exp/Cntr=0.3,0.1

Type RM Length L Ch R = 1 ,1405    ,446,446,446
BEGIN DESCRIPTION:
Upper Denton 52 2.0
END DESCRIPTION:
XS GIS Cut Line= 4
      2195385.37      7267654.79      2195532.69      7266913.69
        2195379.        7266760.      2194916.66      7266295.39
#Sta/Elev= 30
  4026.6 1046.14  4082.5 1045.97    4113  1043.3  4153.8 1042.89  4184.4 1040.33
  4398.5 1031.95    4427 1028.92  4449.5 1029.95  4478.1 1026.71  4534.3 1025.22
  4636.6 1020.26  4858.1 1015.38    4943 1017.28  5003.1 1016.21  5013.7 1014.95
  5016.1 1011.41  5017.4 1010.91  5025.4 1011.41  5027.8 1013.95  5034.9 1016.47
    5049 1017.84  5098.5 1016.95    5148 1018.98  5303.6 1031.16  5317.7 1030.15
  5360.2 1033.38  5515.7 1046.17  5579.4 1052.73  5621.8 1054.47    5655 1053.57
#Mann= 3 ,-1 , 0
  4026.6     .05       0  5016.1    .033       0  5025.4     .05       0
Bank Sta=5016.1,5025.4
XS Rating Curve= 0 ,0
Exp/Cntr=0.3,0.1

Type RM Length L Ch R = 1 ,959     ,514,514,514
BEGIN DESCRIPTION:
Upper Denton 52 1.0
END DESCRIPTION:
XS GIS Cut Line= 4
      2195437.48      7267581.79       2195705.7      7267002.18
        2195629.        7266410.      2195005.46      7266154.86
#Sta/Elev= 30
  3764.2 1044.38  3947.2 1038.51  4052.7 1032.99  4129.8 1031.54  4151.8  1028.9
    4159 1026.09  4164.5 1027.74  4173.9 1024.49  4227.8 1024.84    4240 1029.64
  4250.7 1030.33  4279.2 1026.13  4284.7  1027.6    4325 1025.64  4399.3 1026.74
  4677.3 1014.57  4949.6 1015.37  4979.8 1012.01  5004.6 1008.48  5005.9 1007.98
  5013.9 1008.48  5014.7 1013.05  5021.6 1015.45  5121.5    1015  5193.5 1018.01
  5237.7 1023.74  5399.8 1032.78    5551 1046.29  5644.9 1051.08  5673.7 1050.86
#Mann= 3 ,-1 , 0
  3764.2     .05       0  5004.6    .033       0  5013.9     .05       0
Bank Sta=4979.8,5014.7
XS Rating Curve= 0 ,0
Exp/Cntr=0.3,0.1

Type RM Length L Ch R = 1 ,445     ,0,0,0
BEGIN DESCRIPTION:
Upper Denton 52 0.5
END DESCRIPTION:
XS GIS Cut Line= 4
      2195476.52      7267546.33      2196078.96      7266225.27
      2195929.65      7265980.33      2195005.16      7266154.74
#Sta/Elev= 30
  3359.4  1042.7  3426.2 1041.64    3593 1032.95  3674.1 1030.65  3685.1 1031.93
  3690.7 1030.14  3719.2 1029.04  3736.7 1025.08  3759.8 1025.29  3782.8 1030.64
  3811.4 1027.59  3880.5 1027.02    3909 1028.64  4006.7 1026.79  4345.7 1013.51
  4959.6 1013.29  4975.1 1012.15  4981.5  1009.4  4991.7 1001.16  4993.1 1000.66
  5001.1 1001.16  5011.9 1008.32  5017.7 1013.03  5033.2  1014.1  5233.7 1014.29
  5443.4  1027.9  5558.4 1029.32  5720.7 1035.78  5923.1 1050.42    6039 1050.86
#Mann= 3 ,-1 , 0
  3359.4     .05       0  4991.7    .033       0  5001.1     .05       0
Bank Sta=4981.5,5011.9
XS Rating Curve= 0 ,0
Exp/Cntr=0.3,0.1

Chan Stop Cuts=-1
Use User Specified Reach Order=0
Composite Channel Slope=5