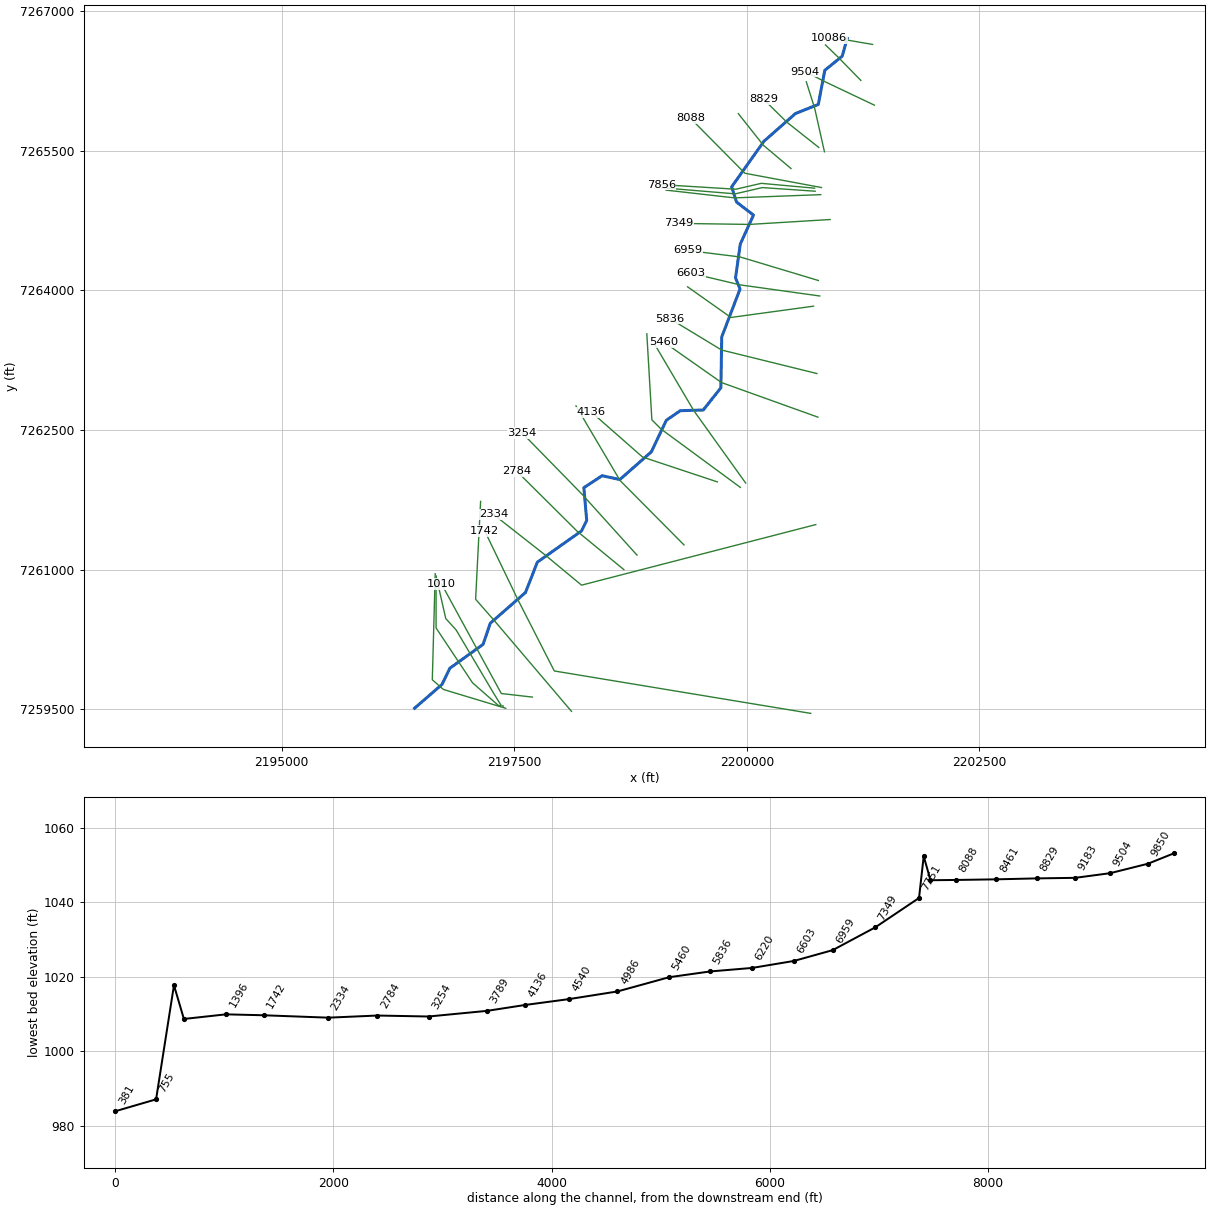
--- Upper Denton 53.prj (project) ---

Proj Title=Upper Denton 53 Base Level Engineering
Current Plan=p01
Default Exp/Contr=0.3,0.1
English Units
Geom File=g01
Flow File=f01
Plan File=p01
BEGIN DESCRIPTION:
Upper Denton 53
END DESCRIPTION:

--- Upper Denton 53.p01 (plan) ---

Plan Title=Multiple Run
Short Identifier=Multiple
Geom File=g01
Flow File=f01
Subcritical Flow
K Sum by GR= 0
Std Step Tol= 0.01
Critical Tol= 0.01
Num of Std Step Trials= 20
Max Error Tol= 0.3
Flow Tol Ratio= 0.001
Split Flow NTrial= 30
Split Flow Tol= 0.02
Split Flow Ratio= 0.02
Log Output Level= 0
Friction Slope Method= 1
Unsteady Friction Slope Method= 2
Unsteady Bridges Friction Slope Method= 1
Parabolic Critical Depth
Global Vel Dist=  1 , 1 , 1
Global Log Level= 0
CheckData=True
Encroach Param= -1, 0, 0, 0
BEGIN DESCRIPTION:
Multiple Run
END DESCRIPTION:

--- Upper Denton 53.f01 (steady flow) ---

Flow Title=Multiple
Number of Profiles=7
Profile Names=10-year,25-year,50-year,1pct_min,100-year,1pct_plu,500-year
River Rch & RM= Upper Denton 53,Reach-1,10086
     566     774     945     573    1143    2281    1678
River Rch & RM= Upper Denton 53,Reach-1,4986
     904    1269    1577     971    1938    3867    2938
Boundary for River Rch & Prof#=Upper Denton 53,Reach-1,1
Up Type=0
Dn Type=3
Dn Slope=0.005
Boundary for River Rch & Prof#=Upper Denton 53,Reach-1,2
Up Type=0
Dn Type=3
Dn Slope=0.005
Boundary for River Rch & Prof#=Upper Denton 53,Reach-1,3
Up Type=0
Dn Type=3
Dn Slope=0.005
Boundary for River Rch & Prof#=Upper Denton 53,Reach-1,4
Up Type=0
Dn Type=3
Dn Slope=0.005
Boundary for River Rch & Prof#=Upper Denton 53,Reach-1,5
Up Type=0
Dn Type=3
Dn Slope=0.005
Boundary for River Rch & Prof#=Upper Denton 53,Reach-1,6
Up Type=0
Dn Type=3
Dn Slope=0.005
Boundary for River Rch & Prof#=Upper Denton 53,Reach-1,7
Up Type=0
Dn Type=3
Dn Slope=0.005

--- Upper Denton 53.g01 (geometry) ---

Geom Title=Existing Conditions

River Reach=Upper Denton 53,Reach-1
Reach XY= 30
      2201079.00      7266710.00      2201025.49      7266518.48
      2200838.30      7266366.67      2200768.39      7265999.94
      2200522.94      7265901.86      2200184.62      7265604.38
      2199836.79      7265113.42      2199889.51      7264950.19
      2200071.77      7264810.32      2199930.04      7264499.56
      2199878.60      7264135.00      2199927.08      7264015.70
      2199730.35      7263500.34      2199721.19      7262953.81
      2199531.70      7262715.36      2199284.45      7262707.82
      2199134.59      7262604.39      2198973.74      7262265.47
      2198635.06      7261967.48      2198445.00      7262009.22
      2198248.44      7261880.55      2198279.20      7261528.41
      2198223.41      7261415.61      2197748.78      7261080.09
      2197621.14      7260753.83      2197242.62      7260423.22
      2197165.60      7260196.70      2196808.82      7259940.38
      2196723.71      7259765.48      2196429.00      7259510.00

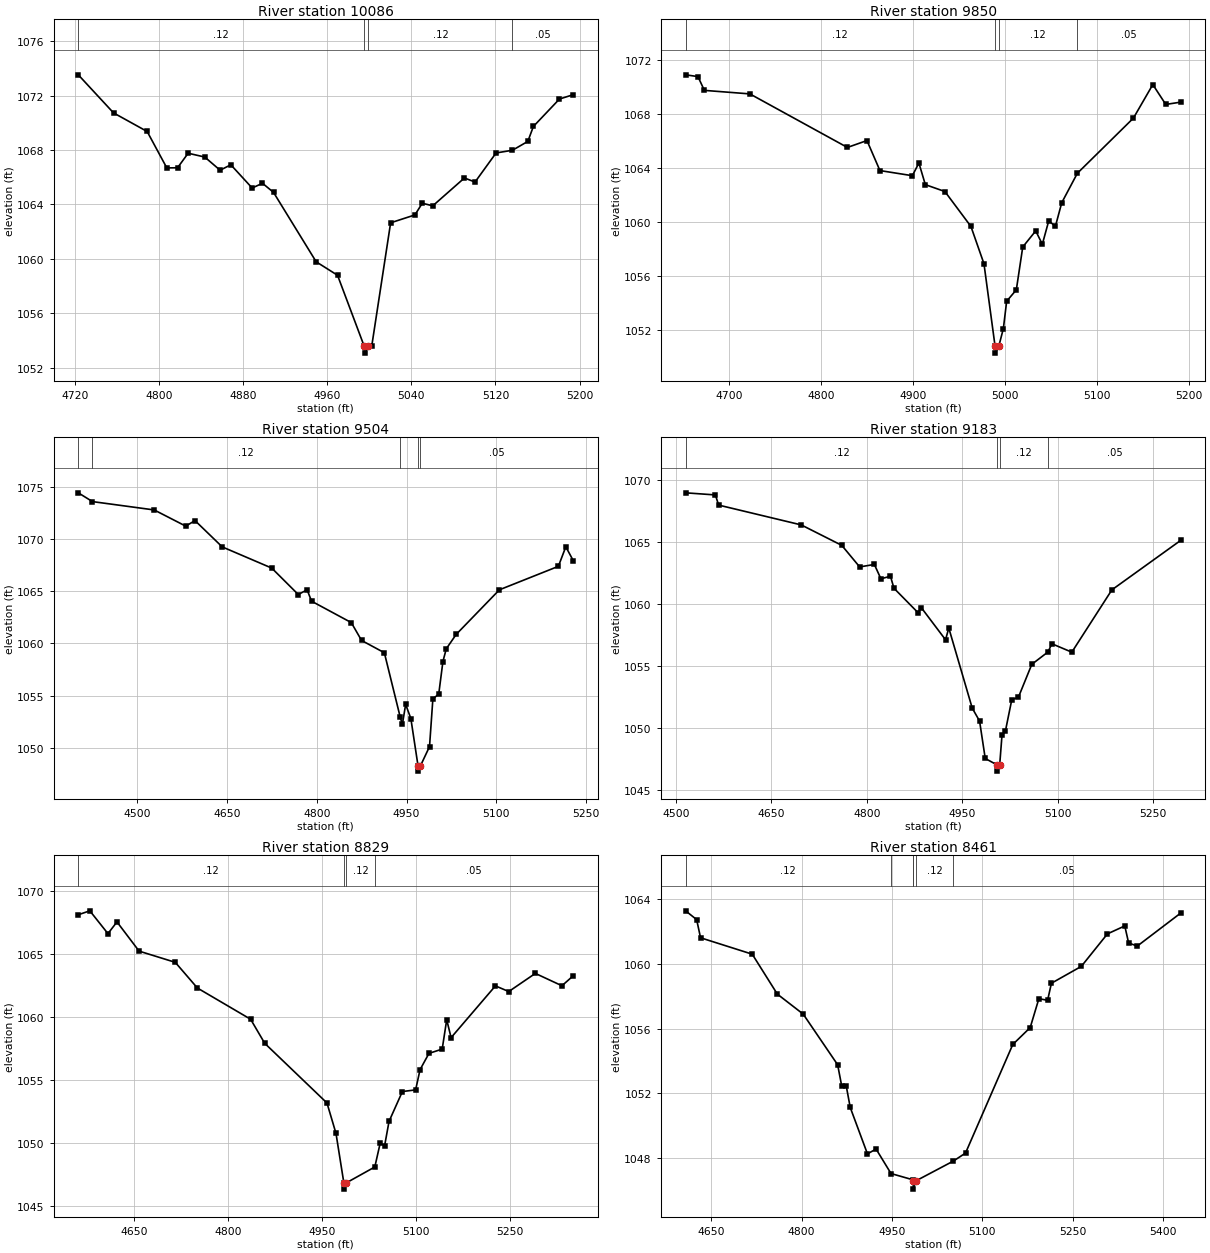
Type RM Length L Ch R = 1,10086,236,236,236
BEGIN DESCRIPTION:
Upper Denton 53 23.5
END DESCRIPTION:
XS GIS Cut Line= 3
      2201351.98      7266644.47      2201079.84      7266691.34
      2200885.83      7266708.27
#Sta/Elev= 30
  4723.2 1073.54  4756.7 1070.74  4788.7 1069.37  4807.4 1066.69  4817.6 1066.70
  4827.7 1067.77  4843.5 1067.49  4858.1 1066.52  4868.3 1066.92  4888.6 1065.21
  4898.4 1065.56  4908.9 1064.89  4949.5 1059.78  4969.8 1058.79  4995.2 1053.56
  4995.5 1053.06  4999.2 1053.56  5002.3 1053.56  5020.3 1062.65  5043.4 1063.23
  5050.4 1064.09  5060.4 1063.90  5090.5 1065.95  5100.6 1065.65  5120.6 1067.79
  5136.2 1067.99  5150.8 1068.64  5156.1 1069.74  5180.9 1071.76  5194.1 1072.08
#Mann=4,-1,0
  4723.2    0.12       0  4995.2    0.07       0  4999.2    0.12       0
  5136.2    0.05       0
Bank Sta=4995.2,4999.2
Exp/Cntr=0.3,0.1

Type RM Length L Ch R = 1,9850,346,346,346
BEGIN DESCRIPTION:
Upper Denton 53 23.0
END DESCRIPTION:
XS GIS Cut Line= 3
      2201225.64      7266257.78      2200979.00      7266510.00
      2200845.47      7266639.25
#Sta/Elev= 30
  4652.3 1070.87  4665.7 1070.74  4672.7 1069.72  4722.2 1069.46  4828.3 1065.50
  4849.6 1066.01  4863.7 1063.79  4899.0 1063.41  4906.1 1064.35  4913.1 1062.75
  4934.4 1062.24  4962.7 1059.66  4976.9 1056.90  4989.0 1050.79  4989.2 1050.29
  4993.0 1050.79  4998.0 1052.11  5001.6 1054.13  5012.1 1054.97  5019.1 1058.14
  5033.2 1059.33  5040.4 1058.34  5047.4 1060.08  5054.6 1059.66  5061.5 1061.41
  5078.5 1063.59  5139.5 1067.67  5160.6 1070.15  5174.7 1068.68  5190.9 1068.85
#Mann=4,-1,0
  4652.3    0.12       0  4989.0    0.07       0  4993.0    0.12       0
  5078.5    0.05       0
Bank Sta=4989,4993
Exp/Cntr=0.3,0.1

Type RM Length L Ch R = 1,9504,321,321,321
BEGIN DESCRIPTION:
Upper Denton 53 22.0
END DESCRIPTION:
XS GIS Cut Line= 3
      2201371.23      7265991.80      2200829.84      7266248.63
      2200626.71      7266352.80
#Sta/Elev= 30
  4401.2 1074.42  4424.9 1073.58  4528.1 1072.78  4580.8 1071.23  4596.3 1071.76
  4641.8 1069.24  4724.6 1067.21  4768.9 1064.68  4783.7 1065.13  4791.1 1064.04
  4857.5 1061.99  4874.7 1060.28  4912.8 1059.10  4939.2 1052.96  4942.9 1052.23
  4948.4 1054.15  4957.1 1052.80  4969.1 1048.26  4969.4 1047.76  4973.1 1048.26
  4988.3 1050.11  4993.9 1054.68  5003.7 1055.14  5010.7 1058.26  5016.3 1059.48
  5032.9 1060.86  5105.1 1065.13  5203.7 1067.38  5216.1 1069.25  5228.7 1067.91
#Mann=5,-1,0
  4401.2    0.05       0  4424.9    0.12       0  4939.2    0.05       0
  4969.1   0.033       0  4973.1    0.05       0
Bank Sta=4969.1,4973.1
Exp/Cntr=0.3,0.1

Type RM Length L Ch R = 1,9183,354,354,354
BEGIN DESCRIPTION:
Upper Denton 53 21.0
END DESCRIPTION:
XS GIS Cut Line= 3
      2200834.51      7265490.48      2200729.00      7265960.00
      2200639.20      7266243.06
#Sta/Elev= 30
  4515.0 1068.97  4561.8 1068.80  4566.9 1067.98  4696.8 1066.38  4760.5 1064.73
  4788.6 1062.99  4811.7 1063.19  4822.0 1062.03  4837.0 1062.24  4842.5 1061.27
  4880.3 1059.30  4885.4 1059.71  4923.6 1057.11  4928.7 1058.06  4965.5 1051.60
  4977.1 1050.55  4986.0 1047.53  5004.7 1047.01  5005.0 1046.51  5008.7 1047.01
  5012.4 1049.45  5017.6 1049.72  5027.7 1052.27  5038.2 1052.48  5059.2 1055.13
  5084.7 1056.13  5090.7 1056.79  5122.1 1056.11  5185.1 1061.14  5293.2 1065.13
#Mann=4,-1,0
  4515.0    0.12       0  5004.7    0.07       0  5008.7    0.12       0
  5084.7    0.05       0
Bank Sta=5004.7,5008.7
Exp/Cntr=0.3,0.1

Type RM Length L Ch R = 1,8829,368,368,368
BEGIN DESCRIPTION:
Upper Denton 53 20.0
END DESCRIPTION:
XS GIS Cut Line= 3
      2200773.30      7265537.38      2200429.00      7265810.00
      2200179.23      7266055.94
#Sta/Elev= 30
  4560.8 1068.15  4579.2 1068.46  4608.1 1066.65  4622.5 1067.58  4657.8 1065.26
  4715.5 1064.37  4750.8 1062.33  4835.7 1059.85  4858.2 1057.94  4957.5 1053.20
  4971.9 1050.78  4984.4 1046.86  4984.6 1046.36  4988.4 1046.86  5033.8 1048.12
  5042.3 1049.99  5049.5 1049.82  5056.5 1051.74  5077.8 1054.11  5098.9 1054.24
  5106.0 1055.85  5120.2 1057.14  5141.3 1057.48  5148.5 1059.81  5155.5 1058.39
  5226.2 1062.50  5247.5 1062.05  5289.9 1063.49  5332.3 1062.51  5350.5 1063.31
#Mann=4,-1,0
  4560.8    0.12       0  4984.4    0.07       0  4988.4    0.12       0
  5033.8    0.05       0
Bank Sta=4984.4,4988.4
Exp/Cntr=0.3,0.1

Type RM Length L Ch R = 1,8461,373,373,373
BEGIN DESCRIPTION:
Upper Denton 53 19.0
END DESCRIPTION:
XS GIS Cut Line= 3
      2200475.14      7265310.80      2200179.00      7265560.00
      2199908.72      7265900.66
#Sta/Elev= 30
  4607.5 1063.25  4625.8 1062.71  4632.3 1061.59  4718.1 1060.58  4759.8 1058.12
  4802.7 1056.89  4859.9 1053.77  4866.5 1052.49  4874.2 1052.46  4880.8 1051.14
  4909.4 1048.28  4923.7 1048.58  4948.5 1047.07  4984.3 1046.69  4985.4 1046.61
  4985.6 1046.11  4989.4 1046.61  5052.1 1047.84  5072.2 1048.33  5150.7 1055.02
  5179.6 1056.06  5194.0 1057.84  5208.5 1057.74  5214.8 1058.79  5264.5 1059.83
  5307.8 1061.83  5336.6 1062.32  5343.0 1061.27  5357.4 1061.08  5429.4 1063.11
#Mann=6,-1,0
  4607.5    0.12       0  4948.5    0.05       0  4984.3    0.12       0
  4985.4    0.07       0  4989.4    0.12       0  5052.1    0.05       0
Bank Sta=4985.4,4989.4
Exp/Cntr=0.3,0.1

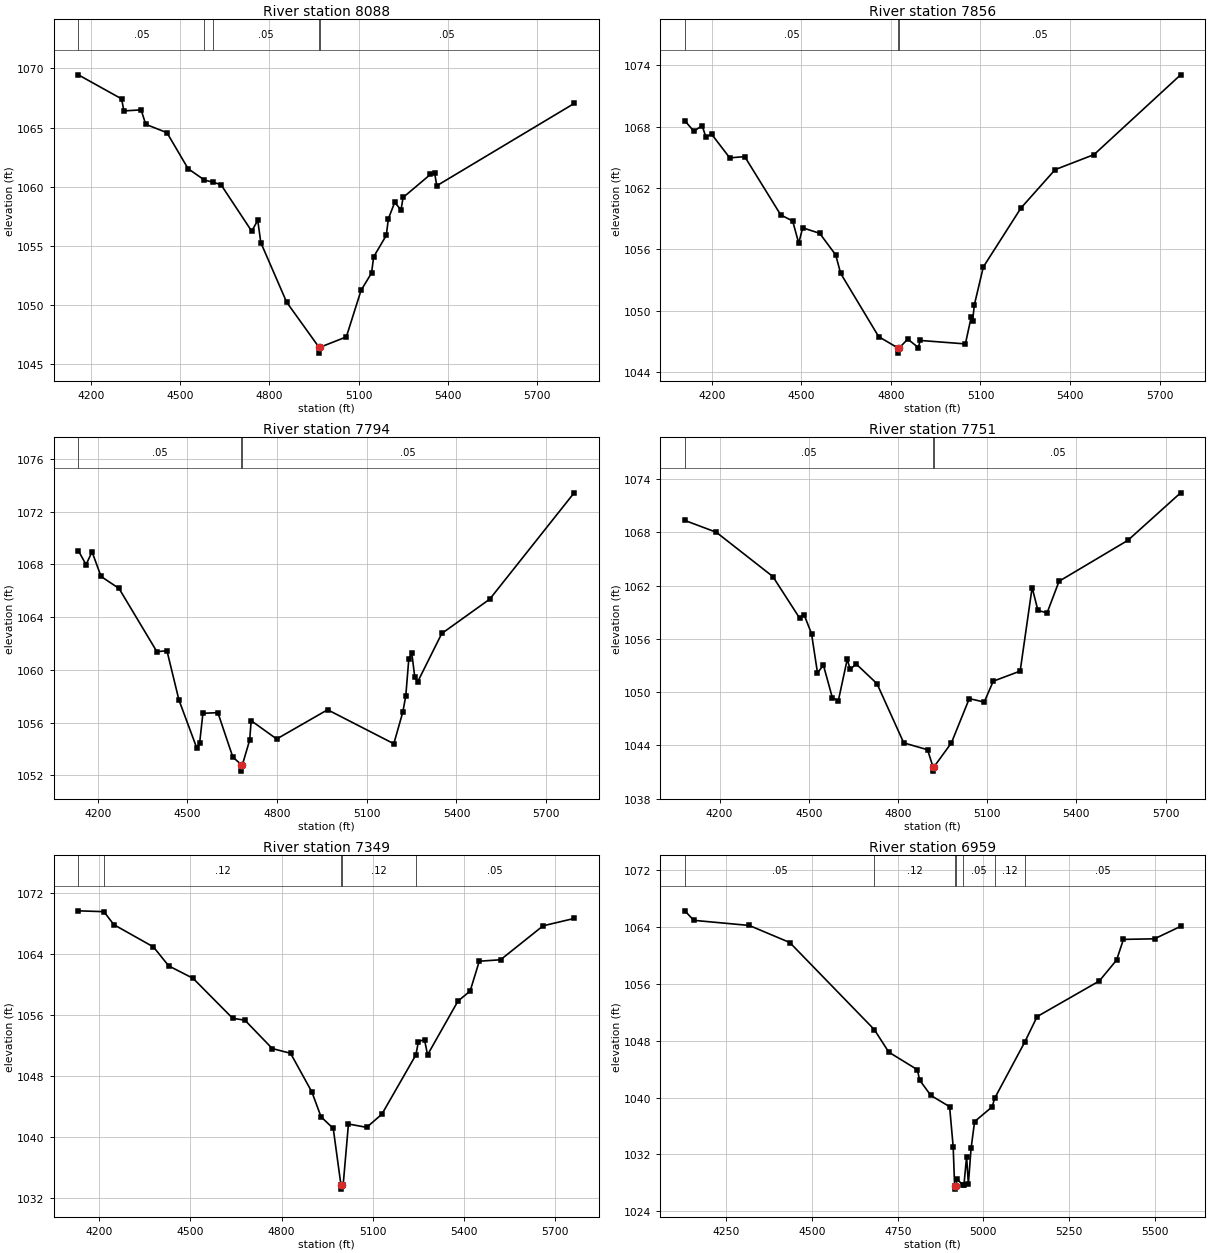
Type RM Length L Ch R = 1,8088,232,232,232
BEGIN DESCRIPTION:
Upper Denton 53 18.0
END DESCRIPTION:
XS GIS Cut Line= 3
      2200801.80      7265106.38      2199979.00      7265260.00
      2199395.53      7265849.44
#Sta/Elev= 30
  4158.2 1069.45  4303.5 1067.42  4311.4 1066.40  4369.1 1066.49  4384.8 1065.27
  4456.1 1064.56  4527.1 1061.52  4582.1 1060.56  4609.8 1060.39  4637.6 1060.17
  4740.9 1056.24  4761.2 1057.16  4771.4 1055.28  4858.4 1050.24  4966.9 1046.44
  4967.1 1045.94  4970.9 1046.44  5058.9 1047.31  5108.3 1051.24  5143.7 1052.71
  5150.7 1054.07  5193.2 1055.89  5200.3 1057.30  5221.5 1058.67  5242.7 1058.04
  5249.7 1059.09  5341.7 1061.04  5355.9 1061.12  5362.9 1060.08  5824.6 1067.03
#Mann=5,-1,0
  4158.2    0.05       0  4582.1    0.12       0  4609.8    0.05       0
  4966.9   0.033       0  4970.9    0.05       0
Bank Sta=4966.9,4970.9
Exp/Cntr=0.3,0.1

Type RM Length L Ch R = 1,7856,62,62,62
BEGIN DESCRIPTION:
Upper Denton 53 17.5
END DESCRIPTION:
XS GIS Cut Line= 4
      2200728.84      7265099.44      2200155.31      7265151.53
      2199882.47      7265088.47      2199079.60      7265137.63
#Sta/Elev= 30
  4109.9 1068.57  4139.9 1067.55  4168.2 1068.08  4180.0 1067.00  4200.1 1067.24
  4260.4 1064.94  4310.6 1065.06  4431.1 1059.37  4471.2 1058.77  4491.3 1056.61
  4504.7 1058.11  4561.6 1057.57  4615.2 1055.46  4631.9 1053.65  4759.1 1047.48
  4823.7 1046.37  4823.9 1045.87  4827.7 1046.37  4856.5 1047.24  4892.4 1046.40
  4897.5 1047.11  5049.5 1046.77  5068.6 1049.35  5073.6 1049.03  5079.5 1050.59
  5109.6 1054.29  5235.5 1060.04  5350.0 1063.79  5480.3 1065.26  5770.2 1073.05
#Mann=3,-1,0
  4109.9    0.05       0  4823.7   0.033       0  4827.7    0.05       0
Bank Sta=4823.7,4827.7
Exp/Cntr=0.3,0.1

Type RM Length L Ch R = 1,7794,43,43,43
BEGIN DESCRIPTION:
Upper Denton 53 17.4
END DESCRIPTION:
XS GIS Cut Line= 4
      2200734.78      7265066.89      2200166.16      7265105.96
      2199875.96      7265038.56      2199087.64      7265103.78
#Sta/Elev= 30
  4134.9 1069.05  4160.7 1067.99  4180.8 1068.96  4210.9 1067.09  4271.0 1066.18
  4397.7 1061.38  4431.4 1061.45  4471.5 1057.71  4531.6 1054.04  4540.8 1054.45
  4551.7 1056.70  4601.8 1056.75  4651.9 1053.37  4680.0 1052.81  4680.2 1052.31
  4684.0 1052.81  4708.1 1054.66  4713.2 1056.14  4798.5 1054.75  4968.9 1056.97
  5190.4 1054.39  5220.5 1056.79  5230.5 1058.03  5240.6 1060.84  5250.6 1061.27
  5260.6 1059.43  5270.7 1059.11  5350.9 1062.76  5511.5 1065.37  5793.8 1073.44
#Mann=3,-1,0
  4134.9    0.05       0  4680.0   0.033       0  4684.0    0.05       0
Bank Sta=4680,4684
Exp/Cntr=0.3,0.1

Type RM Length L Ch R = 1,7751,402,402,402
BEGIN DESCRIPTION:
Upper Denton 53 17.0
END DESCRIPTION:
XS GIS Cut Line= 3
      2200794.86      7265029.99      2199867.75      7264995.27
      2199132.80      7265078.47
#Sta/Elev= 30
  4083.3 1069.35  4189.2 1068.02  4379.4 1063.03  4469.4 1058.35  4484.2 1058.75
  4509.5 1056.59  4529.5 1052.18  4549.5 1053.04  4579.5 1049.38  4599.5 1049.02
  4629.5 1053.70  4639.5 1052.58  4659.6 1053.18  4729.6 1050.96  4819.7 1044.29
  4899.7 1043.52  4917.7 1041.61  4918.0 1041.11  4921.7 1041.61  4979.8 1044.29
  5040.0 1049.28  5090.3 1048.89  5120.5 1051.24  5211.1 1052.38  5251.3 1061.79
  5270.9 1059.21  5301.7 1058.94  5341.9 1062.50  5573.4 1067.11  5750.7 1072.46
#Mann=3,-1,0
  4083.3    0.05       0  4917.7   0.033       0  4921.7    0.05       0
Bank Sta=4917.7,4921.7
Exp/Cntr=0.3,0.1

Type RM Length L Ch R = 1,7349,390,390,390
BEGIN DESCRIPTION:
Upper Denton 53 16.0
END DESCRIPTION:
XS GIS Cut Line= 3
      2200895.53      7264762.63      2200029.00      7264710.00
      2199267.01      7264720.97
#Sta/Elev= 30
  4131.6 1069.67  4215.7 1069.56  4248.3 1067.86  4378.6 1064.94  4428.7 1062.46
  4508.8 1060.83  4639.1 1055.59  4679.1 1055.35  4769.3 1051.63  4829.4 1051.01
  4899.5 1045.94  4929.6 1042.69  4969.7 1041.17  4995.2 1033.72  4995.5 1033.22
  4999.2 1033.72  5002.2 1033.72  5019.7 1041.75  5079.7 1041.31  5129.7 1043.04
  5241.4 1050.80  5249.8 1052.55  5269.8 1052.80  5279.8 1050.81  5379.8 1057.85
  5419.8 1059.16  5449.8 1063.07  5519.8 1063.26  5659.8 1067.71  5761.8 1068.67
#Mann=5,-1,0
  4131.6    0.05       0  4215.7    0.12       0  4995.2    0.07       0
  4999.2    0.12       0  5241.4    0.05       0
Bank Sta=4995.2,4999.2
Exp/Cntr=0.3,0.1

Type RM Length L Ch R = 1,6959,356,356,356
BEGIN DESCRIPTION:
Upper Denton 53 15.0
END DESCRIPTION:
XS GIS Cut Line= 3
      2200769.10      7264107.33      2199929.00      7264360.00
      2199363.41      7264430.17
#Sta/Elev= 30
  4128.6 1066.30  4155.0 1064.96  4316.7 1064.24  4434.9 1061.84  4681.7 1049.58
  4723.9 1046.41  4807.5 1043.93  4813.8 1042.48  4846.8 1040.31  4901.5 1038.73
  4911.9 1033.10  4916.1 1027.62  4916.3 1027.12  4920.1 1027.62  4923.3 1028.50
  4940.5 1027.70  4943.2 1027.64  4951.1 1031.68  4956.3 1027.82  4964.1 1032.84
  4974.5 1036.63  5026.0 1038.72  5032.8 1039.89  5120.4 1047.78  5157.0 1051.41
  5338.4 1056.42  5388.8 1059.36  5408.9 1062.28  5499.6 1062.36  5575.8 1064.11
#Mann=7,-1,0
  4128.6    0.05       0  4681.7    0.12       0  4916.1   0.033       0
  4920.1    0.12       0  4940.5    0.05       0  5032.8    0.12       0
  5120.4    0.05       0
Bank Sta=4916.1,4920.1
Exp/Cntr=0.3,0.1

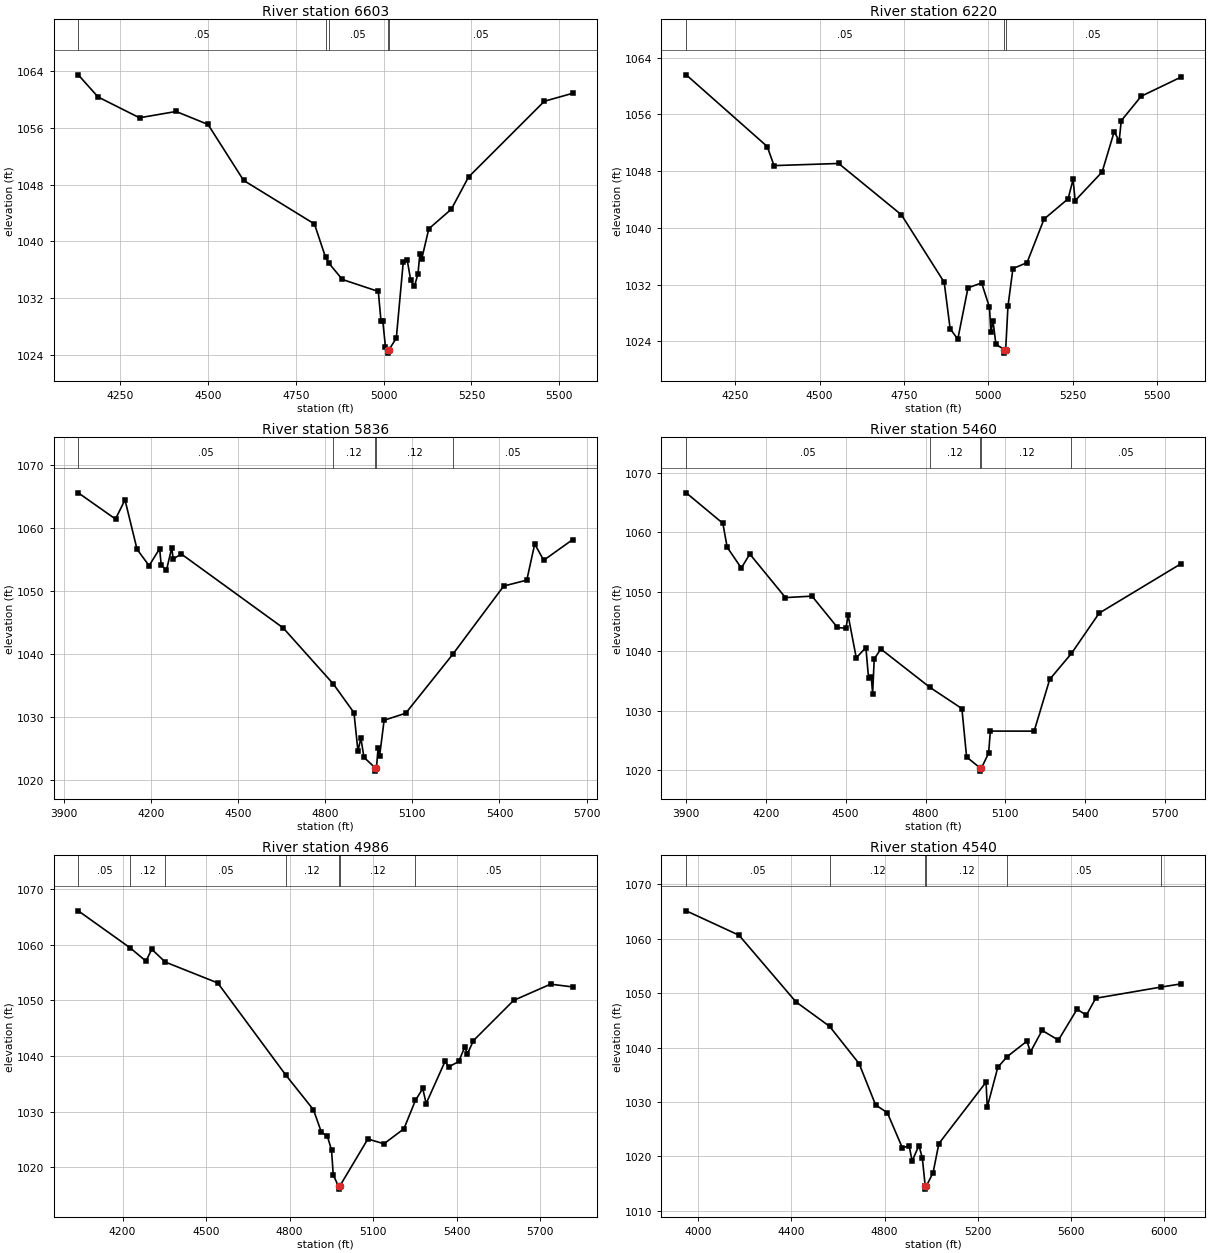
Type RM Length L Ch R = 1,6603,383,383,383
BEGIN DESCRIPTION:
Upper Denton 53 14.0
END DESCRIPTION:
XS GIS Cut Line= 3
      2200784.70      7263940.66      2199929.00      7264060.00
      2199400.31      7264185.21
#Sta/Elev= 30
  4131.0 1063.48  4187.2 1060.36  4305.3 1057.42  4409.4 1058.31  4500.2 1056.48
  4601.5 1048.59  4803.1 1042.44  4834.6 1037.76  4844.0 1036.92  4882.6 1034.61
  4984.9 1032.92  4992.5 1028.75  4997.6 1028.75  5005.3 1025.06  5011.5 1024.72
  5011.8 1024.22  5015.5 1024.72  5036.1 1026.33  5055.8 1037.03  5066.9 1037.42
  5077.2 1034.47  5087.5 1033.62  5097.8 1035.40  5103.2 1038.27  5108.3 1037.48
  5128.6 1041.76  5192.8 1044.53  5241.6 1049.06  5457.4 1059.75  5538.3 1060.88
#Mann=5,-1,0
  4131.0    0.05       0  4834.6    0.12       0  4844.0    0.05       0
  5011.5   0.033       0  5015.5    0.05       0
Bank Sta=5011.5,5015.5
Exp/Cntr=0.3,0.1

Type RM Length L Ch R = 1,6220,384,384,384
BEGIN DESCRIPTION:
Upper Denton 53 13.0
END DESCRIPTION:
XS GIS Cut Line= 3
      2200717.06      7263831.28      2199829.00      7263710.00
      2199363.44      7264039.21
#Sta/Elev= 30
  4104.1 1061.56  4344.4 1051.46  4364.6 1048.77  4556.3 1049.07  4742.4 1041.84
  4869.2 1032.34  4886.9 1025.78  4909.6 1024.32  4939.8 1031.55  4980.2 1032.24
  5003.5 1028.81  5007.8 1025.28  5013.9 1026.93  5022.6 1023.59  5047.6 1022.85
  5047.9 1022.35  5051.6 1022.85  5058.3 1028.92  5073.1 1034.27  5114.9 1035.09
  5165.3 1041.23  5236.7 1044.09  5251.5 1046.83  5257.6 1043.84  5337.7 1047.88
  5373.4 1053.55  5388.2 1052.25  5394.3 1055.09  5453.4 1058.54  5570.6 1061.22
#Mann=3,-1,0
  4104.1    0.05       0  5047.6   0.033       0  5051.6    0.05       0
Bank Sta=5047.6,5051.6
Exp/Cntr=0.3,0.1

Type RM Length L Ch R = 1,5836,376,376,376
BEGIN DESCRIPTION:
Upper Denton 53 12.0
END DESCRIPTION:
XS GIS Cut Line= 3
      2200753.51      7263107.32      2199729.00      7263360.00
      2199176.10      7263695.42
#Sta/Elev= 30
  3950.4 1065.56  4078.6 1061.40  4111.2 1064.45  4152.7 1056.60  4194.2 1054.00
  4230.5 1056.70  4235.7 1054.16  4253.7 1053.24  4272.0 1056.82  4277.1 1055.08
  4305.2 1055.85  4655.6 1044.13  4828.0 1035.25  4899.3 1030.68  4912.9 1024.62
  4923.2 1026.64  4933.5 1023.60  4972.7 1021.91  4973.0 1021.41  4976.7 1021.91
  4982.3 1025.07  4987.4 1023.76  5003.0 1029.48  5077.4 1030.60  5238.9 1039.92
  5414.6 1050.77  5494.1 1051.71  5521.3 1057.44  5552.3 1054.86  5652.3 1058.15
#Mann=5,-1,0
  3950.4    0.05       0  4828.0    0.12       0  4972.7    0.07       0
  4976.7    0.12       0  5238.9    0.05       0
Bank Sta=4972.7,4976.7
Exp/Cntr=0.3,0.1

Type RM Length L Ch R = 1,5460,474,474,474
BEGIN DESCRIPTION:
Upper Denton 53 11.0
END DESCRIPTION:
XS GIS Cut Line= 3
      2200763.92      7262638.57      2199729.00      7263010.00
      2199108.26      7263445.44
#Sta/Elev= 30
  3900.9 1066.64  4038.6 1061.52  4054.9 1057.49  4108.0 1054.00  4139.9 1056.35
  4273.9 1049.03  4373.6 1049.28  4469.2 1044.01  4501.1 1043.87  4509.2 1046.06
  4539.9 1038.91  4576.0 1040.64  4586.1 1035.49  4596.1 1035.69  4601.4 1032.89
  4607.3 1038.73  4632.2 1040.39  4816.8 1033.94  4936.7 1030.38  4954.4 1022.25
  5005.9 1020.37  5006.1 1019.87  5009.9 1020.37  5037.1 1022.89  5043.6 1026.60
  5208.1 1026.59  5266.7 1035.30  5348.2 1039.64  5452.4 1046.42  5758.7 1054.69
#Mann=5,-1,0
  3900.9    0.05       0  4816.8    0.12       0  5005.9    0.07       0
  5009.9    0.12       0  5348.2    0.05       0
Bank Sta=5005.9,5009.9
Exp/Cntr=0.3,0.1

Type RM Length L Ch R = 1,4986,446,446,446
BEGIN DESCRIPTION:
Upper Denton 53 10.0
END DESCRIPTION:
XS GIS Cut Line= 3
      2199987.84      7261930.27      2199429.00      7262710.00
      2199013.96      7263414.53
#Sta/Elev= 30
  4040.8 1066.10  4228.0 1059.41  4284.0 1057.05  4304.9 1059.19  4353.4 1056.89
  4542.0 1053.13  4786.2 1036.59  4885.9 1030.33  4914.0 1026.35  4936.2 1025.53
  4950.9 1023.08  4957.1 1018.60  4976.0 1016.55  4976.3 1016.05  4980.1 1016.55
  5081.4 1025.06  5139.4 1024.21  5210.9 1026.89  5252.6 1032.03  5278.7 1034.15
  5290.9 1031.44  5359.3 1039.07  5371.5 1038.01  5408.1 1039.01  5429.5 1041.58
  5439.4 1040.39  5460.8 1042.76  5605.2 1049.99  5738.0 1052.91  5817.8 1052.41
#Mann=7,-1,0
  4040.8    0.05       0  4228.0    0.12       0  4353.4    0.05       0
  4786.2    0.12       0  4976.0    0.07       0  4980.1    0.12       0
  5252.6    0.05       0
Bank Sta=4976,4980.1
Exp/Cntr=0.3,0.1

Type RM Length L Ch R = 1,4540,404,404,404
BEGIN DESCRIPTION:
Upper Denton 53 9.0
END DESCRIPTION:
XS GIS Cut Line= 4
      2199930.60      7261883.35      2199079.00      7262510.00
      2198979.56      7262609.44      2198925.36      7263534.41
#Sta/Elev= 30
  3947.6 1065.11  4174.5 1060.63  4419.0 1048.39  4563.7 1043.89  4690.5 1037.04
  4761.5 1029.45  4811.7 1028.03  4876.5 1021.56  4905.6 1021.95  4918.2 1019.14
  4947.5 1022.00  4962.1 1019.71  4974.7 1014.49  4975.0 1013.99  4978.8 1014.49
  5008.4 1017.03  5033.2 1022.36  5235.9 1033.64  5241.0 1029.06  5286.3 1036.35
  5325.7 1038.30  5411.6 1041.17  5426.6 1039.19  5476.7 1043.15  5546.8 1041.36
  5626.9 1047.04  5667.0 1045.94  5707.1 1049.05  5985.5 1051.09  6072.1 1051.68
#Mann=6,-1,0
  3947.6    0.05       0  4563.7    0.12       0  4974.7    0.07       0
  4978.8    0.12       0  5325.7    0.05       0  5985.5    0.12       0
Bank Sta=4974.7,4978.8
Exp/Cntr=0.3,0.1

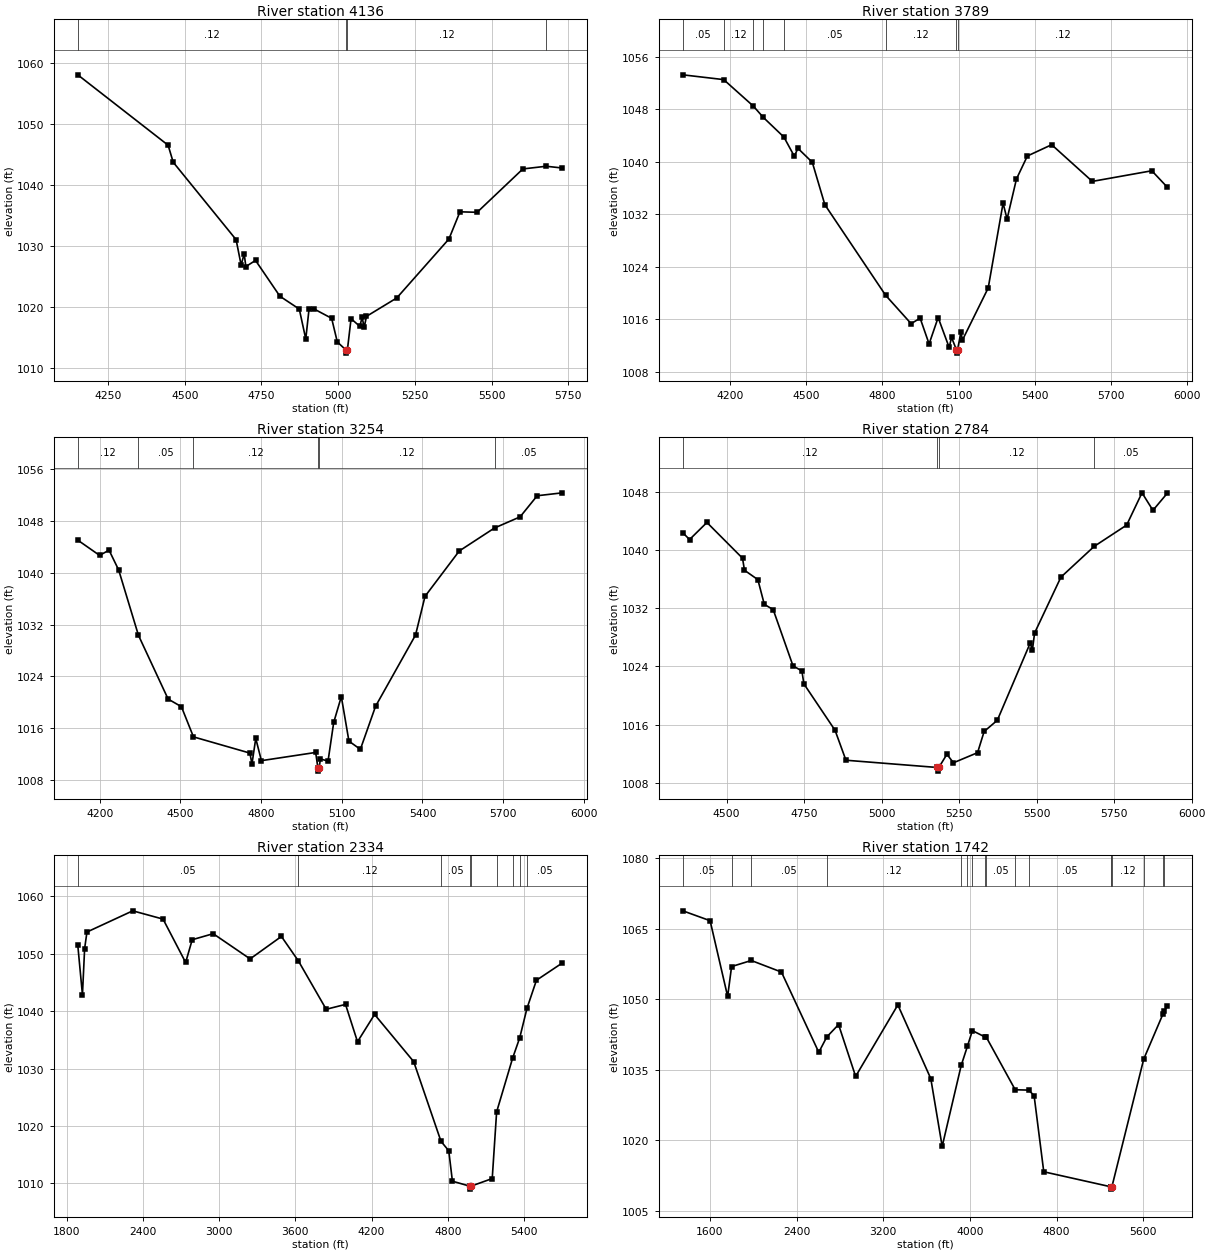
Type RM Length L Ch R = 1,4136,347,347,347
BEGIN DESCRIPTION:
Upper Denton 53 8.0
END DESCRIPTION:
XS GIS Cut Line= 3
      2199684.08      7261942.38      2198879.00      7262210.00
      2198329.89      7262692.38
#Sta/Elev= 30
  4151.4 1058.04  4445.8 1046.50  4462.4 1043.71  4667.4 1031.01  4683.7 1026.87
  4693.8 1028.68  4699.1 1026.60  4730.7 1027.61  4810.1 1021.74  4873.3 1019.63
  4894.4 1014.72  4905.0 1019.61  4920.7 1019.67  4978.7 1018.12  4997.2 1014.24
  5025.7 1012.91  5026.0 1012.41  5030.0 1012.91  5042.0 1018.06  5070.5 1016.80
  5078.1 1018.29  5084.7 1016.62  5092.3 1018.44  5191.0 1021.46  5360.9 1031.12
  5396.9 1035.58  5452.9 1035.50  5601.9 1042.61  5678.0 1043.05  5730.7 1042.76
#Mann=4,-1,0
  4151.4    0.12       0  5025.7    0.07       0  5030.0    0.12       0
  5678.0    0.05       0
Bank Sta=5025.7,5030
Exp/Cntr=0.3,0.1

Type RM Length L Ch R = 1,3789,535,535,535
BEGIN DESCRIPTION:
Upper Denton 53 7.0
END DESCRIPTION:
XS GIS Cut Line= 3
      2199324.68      7261265.30      2198637.17      7261958.02
      2198163.58      7262759.47
#Sta/Elev= 30
  4014.9 1053.25  4175.7 1052.52  4292.7 1048.47  4331.1 1046.78  4412.7 1043.76
  4453.6 1040.84  4467.7 1042.05  4524.3 1039.92  4573.8 1033.45  4812.7 1019.66
  4913.2 1015.33  4948.6 1016.17  4983.9 1012.24  5019.5 1016.26  5062.9 1011.70
  5072.2 1013.24  5091.5 1011.34  5091.9 1010.84  5095.8 1011.34  5109.3 1014.06
  5115.1 1012.83  5216.5 1020.77  5275.0 1033.70  5290.7 1031.27  5327.7 1037.38
  5370.6 1040.88  5466.2 1042.60  5626.2 1037.01  5860.3 1038.63  5921.8 1036.10
#Mann=8,-1,0
  4014.9    0.05       0  4175.7    0.12       0  4292.7    0.05       0
  4331.1    0.12       0  4412.7    0.05       0  4812.7    0.12       0
  5091.5    0.07       0  5095.8    0.12       0
Bank Sta=5091.5,5095.8
Exp/Cntr=0.3,0.1

Type RM Length L Ch R = 1,3254,470,470,470
BEGIN DESCRIPTION:
Upper Denton 53 6.0
END DESCRIPTION:
XS GIS Cut Line= 3
      2198819.49      7261155.91      2198229.00      7261810.00
      2197585.06      7262468.47
#Sta/Elev= 30
  4118.2 1045.07  4199.4 1042.71  4234.5 1043.52  4270.4 1040.44  4343.8 1030.35
  4454.2 1020.48  4503.6 1019.30  4548.4 1014.63  4758.4 1012.12  4765.9 1010.42
  4780.1 1014.39  4801.0 1010.95  5002.9 1012.22  5011.2 1009.83  5011.7 1009.33
  5015.7 1009.83  5020.6 1011.22  5048.9 1010.88  5070.0 1016.87  5098.3 1020.86
  5126.6 1013.97  5169.1 1012.70  5225.6 1019.36  5374.2 1030.38  5409.5 1036.37
  5536.8 1043.39  5668.0 1046.95  5763.1 1048.67  5826.7 1051.94  5920.4 1052.39
#Mann=6,-1,0
  4118.2    0.12       0  4343.8    0.05       0  4548.4    0.12       0
  5011.2    0.07       0  5015.7    0.12       0  5668.0    0.05       0
Bank Sta=5011.2,5015.7
Exp/Cntr=0.3,0.1

Type RM Length L Ch R = 1,2784,450,450,450
BEGIN DESCRIPTION:
Upper Denton 53 5.0
END DESCRIPTION:
XS GIS Cut Line= 3
      2198678.84      7260999.68      2198179.00      7261410.00
      2197528.82      7262055.96
#Sta/Elev= 30
  4358.7 1042.40  4380.4 1041.47  4436.4 1043.82  4551.2 1038.90  4557.6 1037.24
  4600.7 1035.95  4621.5 1032.55  4650.2 1031.82  4714.1 1024.08  4742.7 1023.38
  4749.2 1021.60  4849.7 1015.21  4884.8 1011.09  5179.9 1010.09  5180.4 1009.59
  5184.4 1010.09  5210.5 1011.91  5231.6 1010.74  5309.4 1012.13  5330.6 1015.05
  5373.1 1016.59  5479.2 1027.22  5486.2 1026.23  5493.3 1028.60  5578.2 1036.29
  5685.3 1040.52  5790.3 1043.46  5839.8 1047.90  5875.1 1045.49  5921.9 1047.87
#Mann=4,-1,0
  4358.7    0.12       0  5179.9    0.07       0  5184.4    0.12       0
  5685.3    0.05       0
Bank Sta=5179.9,5184.4
Exp/Cntr=0.3,0.1

Type RM Length L Ch R = 1,2334,592,592,592
BEGIN DESCRIPTION:
Upper Denton 53 4.0
END DESCRIPTION:
XS GIS Cut Line= 4
      2200741.26      7261483.80      2198223.89      7260832.76
      2197829.00      7261160.00      2197276.37      7261593.63
#Sta/Elev= 30
  1886.9 1051.50  1923.7 1042.85  1940.9 1050.91  1959.2 1053.78  2319.7 1057.47
  2558.3 1056.03  2736.2 1048.48  2787.9 1052.44  2953.1 1053.49  3243.8 1049.10
  3490.2 1053.01  3624.1 1048.74  3842.8 1040.33  3995.0 1041.18  4089.3 1034.68
  4223.6 1039.43  4531.8 1031.21  4746.6 1017.34  4807.8 1015.70  4836.5 1010.40
  4976.2 1009.52  4976.7 1009.02  4980.7 1009.52  5150.0 1010.86  5184.6 1022.46
  5310.2 1031.80  5366.5 1035.37  5423.6 1040.49  5498.0 1045.38  5702.4 1048.40
#Mann=9,-1,0
  1886.9    0.05       0  3624.1    0.12       0  4746.6    0.05       0
  4976.2   0.033       0  4980.7    0.05       0  5184.6    0.12       0
  5310.2    0.05       0  5366.5    0.12       0  5423.6    0.05       0
Bank Sta=4976.2,4980.7
Exp/Cntr=0.3,0.1

Type RM Length L Ch R = 1,1742,346,346,346
BEGIN DESCRIPTION:
Upper Denton 53 3.0
END DESCRIPTION:
XS GIS Cut Line= 4
      2200687.03      7259454.71      2197930.92      7259910.45
      2197536.82      7260682.15      2197183.68      7261414.40
#Sta/Elev= 30
  1350.8 1068.83  1602.5 1066.73  1764.4 1050.63  1800.7 1056.98  1982.5 1058.27
  2261.0 1055.81  2605.6 1038.75  2679.4 1042.01  2788.1 1044.65  2945.7 1033.63
  3335.4 1048.83  3639.5 1033.15  3744.5 1018.74  3920.0 1035.95  3977.9 1040.06
  4023.2 1043.36  4143.3 1041.97  4149.5 1042.06  4418.5 1030.79  4543.7 1030.71
  4593.0 1029.53  4682.2 1013.35  5298.6 1010.17  5305.4 1010.16  5306.3 1009.66
  5311.1 1010.16  5604.9 1037.31  5782.4 1046.89  5796.4 1047.63  5823.8 1048.59
#Mann=17,-1,0
  1350.8    0.05       0  1800.7    0.12       0  1982.5    0.05       0
  2679.4    0.12       0  3920.0    0.05       0  3977.9    0.12       0
  4023.2    0.05       0  4143.3    0.12       0  4149.5    0.05       0
  4418.5    0.12       0  4543.7    0.05       0  5298.6    0.12       0
  5305.4   0.033       0  5311.1    0.12       0  5604.9    0.05       0
  5782.4    0.12       0  5796.4    0.05       0
Bank Sta=5305.4,5311.1
Exp/Cntr=0.3,0.1

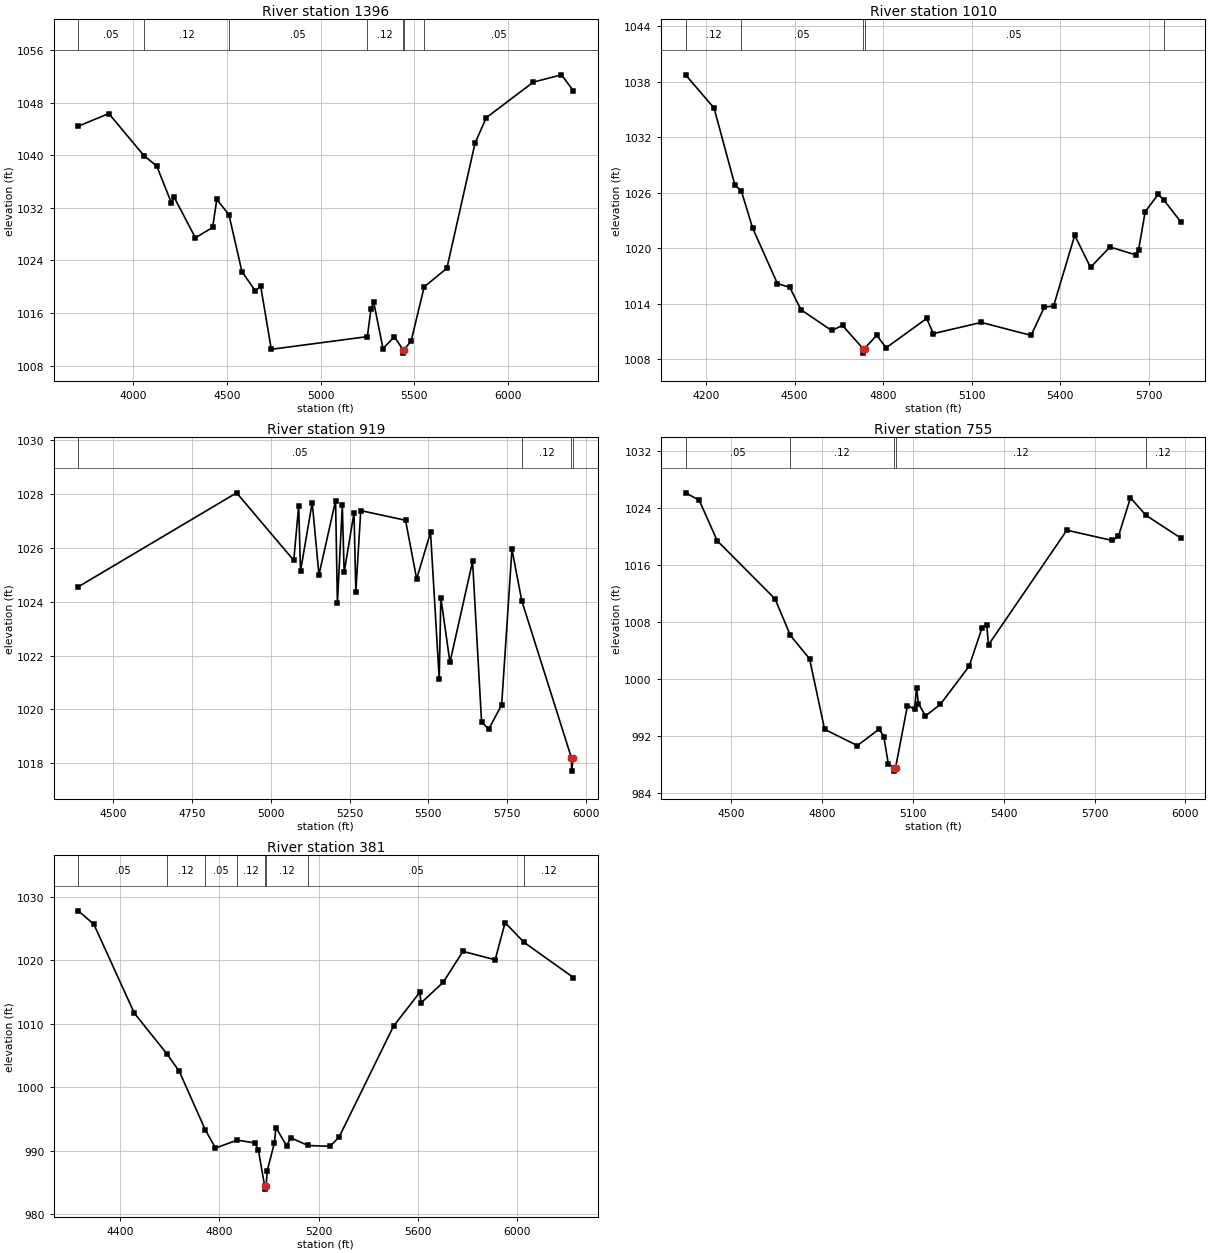
Type RM Length L Ch R = 1,1396,386,386,386
BEGIN DESCRIPTION:
Upper Denton 53 2.0
END DESCRIPTION:
XS GIS Cut Line= 4
      2198115.36      7259476.45      2197279.00      7260460.00
      2197085.24      7260681.44      2197138.82      7261733.36
#Sta/Elev= 30
  3708.7 1044.43  3871.3 1046.35  4058.6 1039.95  4127.2 1038.34  4205.2 1032.74
  4219.5 1033.63  4332.6 1027.45  4424.8 1029.03  4446.8 1033.29  4511.4 1030.97
  4580.8 1022.31  4652.2 1019.38  4680.7 1020.10  4737.2 1010.49  5249.2 1012.42
  5268.8 1016.68  5283.1 1017.66  5332.6 1010.61  5392.7 1012.39  5439.9 1010.41
  5440.8 1009.91  5445.6 1010.41  5482.8 1011.79  5552.2 1019.99  5673.1 1022.82
  5823.3 1041.87  5883.3 1045.73  6133.7 1051.13  6283.9 1052.24  6347.3 1049.81
#Mann=7,-1,0
  3708.7    0.05       0  4058.6    0.12       0  4511.4    0.05       0
  5249.2    0.12       0  5439.9   0.033       0  5445.6    0.12       0
  5552.2    0.05       0
Bank Sta=5439.9,5445.6
Exp/Cntr=0.3,0.1

Type RM Length L Ch R = 1,1010,91,91,91
BEGIN DESCRIPTION:
Upper Denton 53 1.6
END DESCRIPTION:
XS GIS Cut Line= 4
      2197694.81      7259629.82      2197361.49      7259668.01
      2196910.10      7260494.40      2196719.15      7260845.05
#Sta/Elev= 30
  4130.7 1038.77  4227.1 1035.18  4297.6 1026.86  4319.5 1026.21  4358.0 1022.18
  4441.6 1016.20  4483.7 1015.78  4521.6 1013.36  4625.1 1011.12  4662.2 1011.66
  4731.3 1009.17  4732.2 1008.67  4737.0 1009.17  4777.8 1010.60  4810.1 1009.25
  4947.0 1012.42  4969.8 1010.78  5131.8 1011.99  5300.7 1010.59  5345.8 1013.67
  5376.6 1013.74  5448.4 1021.41  5501.9 1017.94  5567.4 1020.15  5654.8 1019.30
  5664.7 1019.86  5687.1 1023.98  5730.8 1025.83  5749.5 1025.26  5807.1 1022.88
#Mann=5,-1,0
  4130.7    0.12       0  4319.5    0.05       0  4731.3   0.033       0
  4737.0    0.05       0  5749.5    0.12       0
Bank Sta=4731.3,4737
Exp/Cntr=0.3,0.1

Type RM Length L Ch R = 1,919,164,164,164
BEGIN DESCRIPTION:
Upper Denton 53 1.5
END DESCRIPTION:
XS GIS Cut Line= 5
      2197354.54      7259548.22      2197279.02      7259670.62
      2196875.37      7260352.04      2196764.26      7260473.57
      2196660.10      7260931.90
#Sta/Elev= 30
  4389.6 1024.56  4891.8 1028.05  5073.1 1025.54  5088.7 1027.57  5094.5 1025.14
  5131.6 1027.69  5153.0 1025.00  5205.7 1027.76  5211.5 1023.95  5227.1 1027.58
  5232.9 1025.09  5264.2 1027.31  5270.0 1024.38  5285.6 1027.39  5427.7 1027.03
  5462.9 1024.85  5506.9 1026.58  5534.5 1021.13  5539.6 1024.16  5568.5 1021.75
  5640.3 1025.50  5668.8 1019.54  5691.5 1019.27  5732.5 1020.17  5765.2 1025.95
  5796.3 1024.04  5953.7 1018.21  5954.6 1017.71  5959.5 1018.21  5960.1 1018.21
#Mann=4,-1,0
  4389.6    0.05       0  5796.3    0.12       0  5953.7   0.033       0
  5959.5    0.12       0
Bank Sta=5953.7,5959.5
Exp/Cntr=0.3,0.1

Type RM Length L Ch R = 1,755,374,374,374
BEGIN DESCRIPTION:
Upper Denton 53 1.4
END DESCRIPTION:
XS GIS Cut Line= 5
      2197383.60      7259533.25      2197330.24      7259539.54
      2197052.46      7259782.60      2196660.10      7260372.87
      2196660.10      7260875.66
#Sta/Elev= 30
  4350.0 1026.19  4394.9 1025.16  4454.7 1019.45  4645.5 1011.29  4695.8 1006.19
  4759.4 1002.88  4809.0  992.98  4917.2  990.71  4989.3  993.02  5004.4  991.98
  5019.4  988.13  5037.6  987.62  5038.5  987.12  5043.4  987.62  5082.5  996.33
  5105.9  995.82  5112.6  998.84  5118.6  996.61  5142.0  994.87  5190.8  996.48
  5286.0 1001.84  5329.1 1007.28  5344.1 1007.62  5350.1 1004.86  5608.7 1020.94
  5758.7 1019.50  5778.7 1020.07  5818.7 1025.49  5869.4 1023.05  5984.4 1019.85
#Mann=5,-1,0
  4350.0    0.05       0  4695.8    0.12       0  5037.6    0.07       0
  5043.4    0.12       0  5869.4    0.12       0
Bank Sta=5037.6,5043.4
Exp/Cntr=0.3,0.1

Type RM Length L Ch R = 1,381,0,0,0
BEGIN DESCRIPTION:
Upper Denton 53 1.0
END DESCRIPTION:
XS GIS Cut Line= 4
      2197409.23      7259509.16      2196739.51      7259711.55
      2196619.72      7259815.72      2196650.96      7260955.72
#Sta/Elev= 30
  4230.2 1027.75  4293.1 1025.63  4456.4 1011.63  4588.1 1005.23  4637.9 1002.47
  4742.9  993.27  4784.1  990.40  4872.2  991.65  4943.7  991.19  4957.0  990.11
  4982.6  984.43  4983.5  983.93  4988.4  984.43  4993.1  986.85  5021.6  991.15
  5028.2  993.63  5070.9  990.77  5088.0  992.02  5157.1  990.80  5246.3  990.67
  5282.9  992.11  5503.0 1009.60  5609.0 1014.92  5614.0 1013.25  5703.1 1016.48
  5783.1 1021.37  5913.2 1020.04  5953.2 1025.89  6029.3 1022.80  6229.0 1017.25
#Mann=8,-1,0
  4230.2    0.05       0  4588.1    0.12       0  4742.9    0.05       0
  4872.2    0.12       0  4982.6    0.07       0  4988.4    0.12       0
  5157.1    0.05       0  6029.3    0.12       0
Bank Sta=4982.6,4988.4
Exp/Cntr=0.3,0.1

Chan Stop Cuts=-1