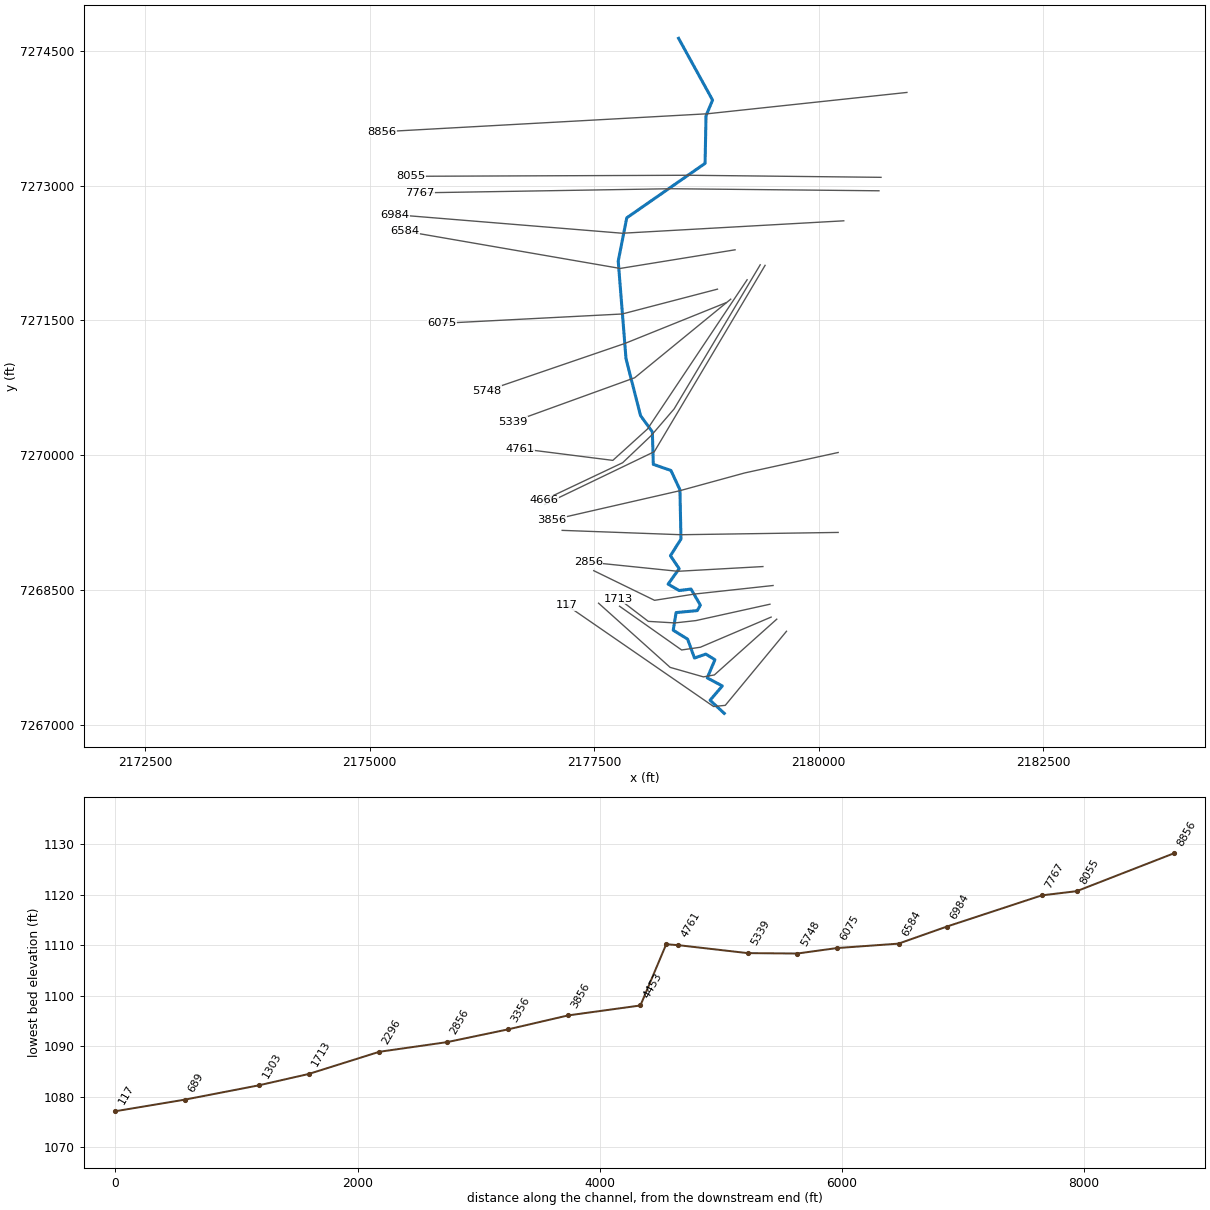
--- Upper Denton 56a.prj (project) ---

Proj Title=Upper Denton 56a Base Level Engineering
Current Plan=p01
Default Exp/Contr=0.3,0.1
English Units
Geom File=g01
Flow File=f01
Plan File=p01
BEGIN DESCRIPTION:
Upper Denton 56a
END DESCRIPTION:

--- Upper Denton 56a.p01 (plan) ---

Plan Title=Multiple Run
Short Identifier=Multiple
Geom File=g01
Flow File=f01
Subcritical Flow
K Sum by GR= 0
Std Step Tol= 0.01
Critical Tol= 0.01
Num of Std Step Trials= 20
Max Error Tol= 0.3
Flow Tol Ratio= 0.001
Split Flow NTrial= 30
Split Flow Tol= 0.02
Split Flow Ratio= 0.02
Log Output Level= 0
Friction Slope Method= 1
Unsteady Friction Slope Method= 2
Unsteady Bridges Friction Slope Method= 1
Parabolic Critical Depth
Global Vel Dist=  1 , 1 , 1
Global Log Level= 0
CheckData=True
Encroach Param= -1, 0, 0, 0
BEGIN DESCRIPTION:
Multiple Run
END DESCRIPTION:

--- Upper Denton 56a.f01 (steady flow) ---

Flow Title=Multiple
Number of Profiles=7
Profile Names=10-year,25-year,50-year,1pct_min,100-year,1pct_plu,500-year
River Rch & RM= Upper Denton 56a,Reach-1,8856
     505     688     837     506    1009    2013    1471
River Rch & RM= Upper Denton 56a,Reach-1,3856
     521     705     854     513    1024    2042    1475
Boundary for River Rch & Prof#=Upper Denton 56a,Reach-1,1
Up Type=0
Dn Type=3
Dn Slope=0.005
Boundary for River Rch & Prof#=Upper Denton 56a,Reach-1,2
Up Type=0
Dn Type=3
Dn Slope=0.005
Boundary for River Rch & Prof#=Upper Denton 56a,Reach-1,3
Up Type=0
Dn Type=3
Dn Slope=0.005
Boundary for River Rch & Prof#=Upper Denton 56a,Reach-1,4
Up Type=0
Dn Type=3
Dn Slope=0.005
Boundary for River Rch & Prof#=Upper Denton 56a,Reach-1,5
Up Type=0
Dn Type=3
Dn Slope=0.005
Boundary for River Rch & Prof#=Upper Denton 56a,Reach-1,6
Up Type=0
Dn Type=3
Dn Slope=0.005
Boundary for River Rch & Prof#=Upper Denton 56a,Reach-1,7
Up Type=0
Dn Type=3
Dn Slope=0.005

--- Upper Denton 56a.g01 (geometry) ---

Geom Title=Existing Conditions

River Reach=Upper Denton 56a,Reach-1
Reach XY= 30
      2178440.40      7274640.03      2178818.63      7273952.76
      2178745.73      7273778.25      2178735.23      7273248.10
      2177863.37      7272641.76      2177768.45      7272159.82
      2177854.96      7271074.35      2178016.74      7270440.37
      2178148.45      7270259.31      2178158.89      7269897.72
      2178355.56      7269829.28      2178455.26      7269614.49
      2178467.02      7269065.88      2178349.68      7268880.58
      2178447.12      7268736.25      2178323.71      7268564.63
      2178446.85      7268493.05      2178578.68      7268509.57
      2178683.02      7268330.17      2178648.06      7268269.67
      2178412.48      7268247.72      2178381.02      7268051.12
      2178540.75      7267952.46      2178617.33      7267741.60
      2178743.30      7267785.59      2178845.18      7267723.07
      2178759.40      7267520.73      2178927.15      7267430.97
      2178791.10      7267271.96      2178948.64      7267125.70

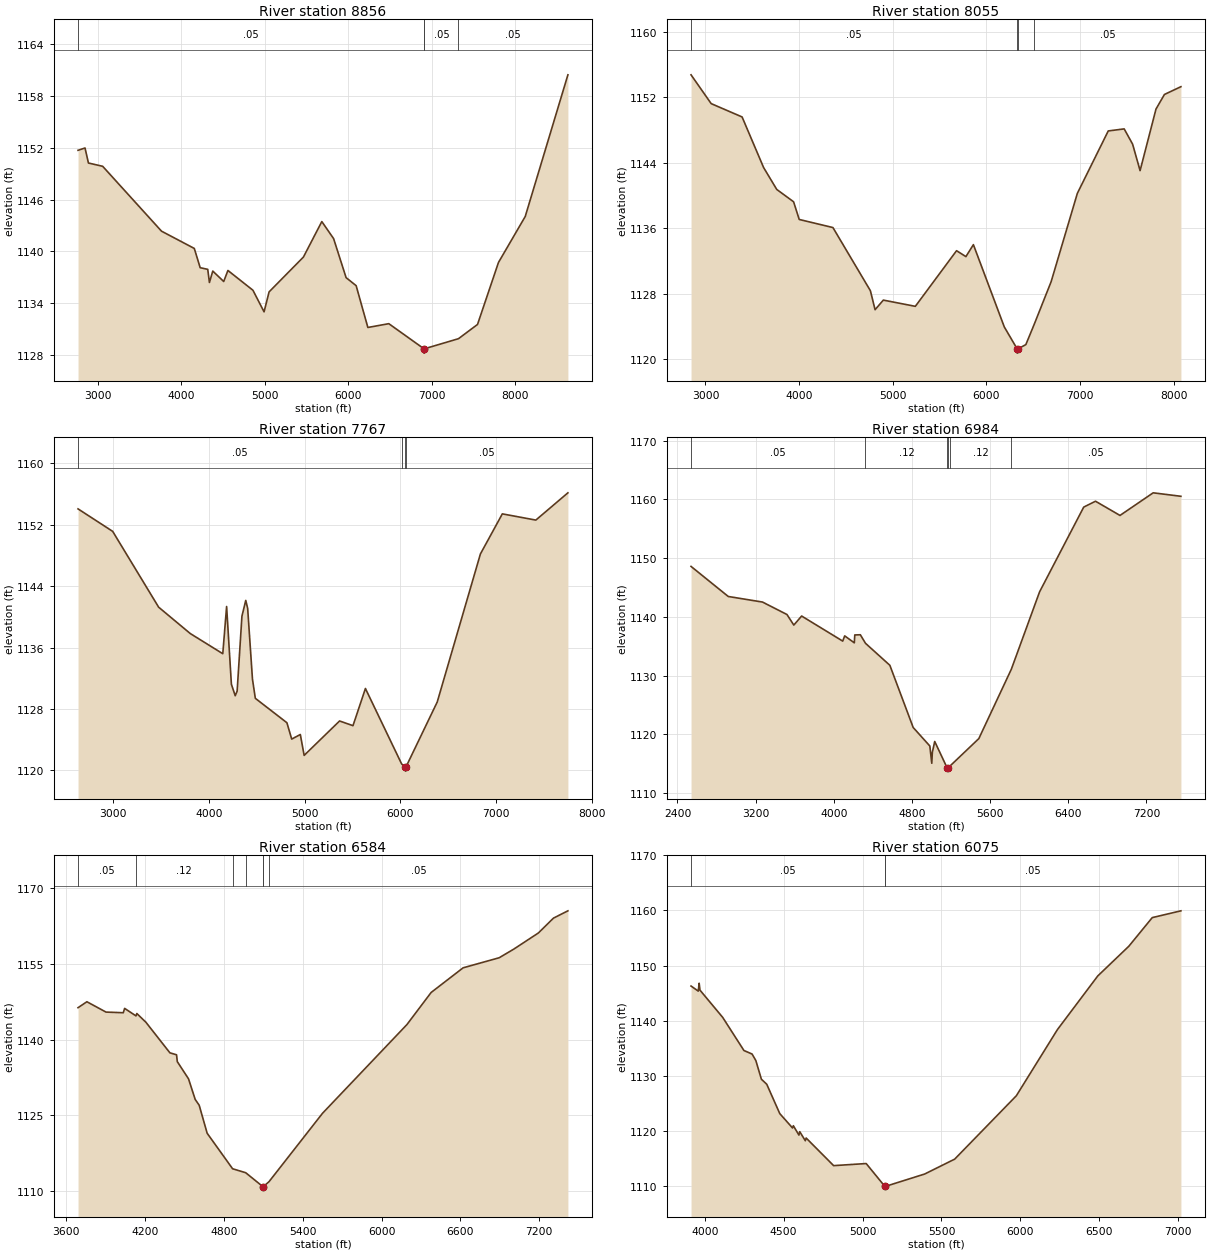
Type RM Length L Ch R = 1,8856,801,801,801
BEGIN DESCRIPTION:
Upper Denton 56a 18.0
END DESCRIPTION:
XS GIS Cut Line= 3
      2180982.13      7274037.77      2178761.59      7273800.33
      2175139.24      7273599.85
#Sta/Elev= 30
  2766.8 1151.71  2850.4 1151.98  2891.3 1150.24  3061.6 1149.86  3765.6 1142.35
  4157.8 1140.35  4228.2 1138.12  4318.7 1137.93  4338.8 1136.41  4379.1 1137.73
  4509.8 1136.52  4560.1 1137.80  4859.4 1135.51  4992.6 1133.01  5052.7 1135.32
  5463.3 1139.35  5683.6 1143.46  5824.5 1141.49  5974.1 1136.97  6094.3 1136.04
  6234.5 1131.20  6484.9 1131.64  6906.3 1128.73  6906.5 1128.23  6910.3 1128.73
  7318.5 1129.90  7546.5 1131.55  7796.9 1138.72  8117.4 1144.05  8627.9 1160.45
#Mann=4,-1,0
  2766.8    0.05       0  6906.3   0.033       0  6910.3    0.05       0
  7318.5    0.05       0
Bank Sta=6906.3,6910.3
Exp/Cntr=0.3,0.1

Type RM Length L Ch R = 1,8055,288,288,288
BEGIN DESCRIPTION:
Upper Denton 56a 17.0
END DESCRIPTION:
XS GIS Cut Line= 3
      2180694.04      7273092.77      2178562.03      7273115.81
      2175462.98      7273104.29
#Sta/Elev= 30
  2846.4 1154.76  3061.4 1151.24  3391.5 1149.61  3621.5 1143.42  3761.5 1140.75
  3941.5 1139.24  4001.5 1137.08  4361.5 1136.09  4761.5 1128.37  4811.6 1126.05
  4899.9 1127.22  5241.6 1126.46  5681.6 1133.26  5781.6 1132.54  5861.6 1134.00
  6191.6 1123.94  6329.6 1121.24  6329.8 1120.74  6333.6 1121.24  6421.6 1121.78
  6512.3 1124.30  6691.6 1129.47  6971.6 1140.27  7301.6 1147.90  7471.6 1148.15
  7561.6 1146.29  7641.6 1143.05  7811.6 1150.58  7901.6 1152.36  8077.6 1153.31
#Mann=4,-1,0
  2846.4    0.05       0  6329.6   0.033       0  6333.6    0.05       0
  6512.3    0.05       0
Bank Sta=6329.6,6333.6
Exp/Cntr=0.3,0.1

Type RM Length L Ch R = 1,7767,783,783,783
BEGIN DESCRIPTION:
Upper Denton 56a 16.0
END DESCRIPTION:
XS GIS Cut Line= 3
      2180670.99      7272942.95      2178354.59      7272965.99
      2175554.08      7272919.90
#Sta/Elev= 30
  2633.6 1154.06  2995.6 1151.13  3475.6 1141.26  3805.6 1137.83  4145.7 1135.20
  4185.7 1141.35  4235.7 1131.22  4275.7 1129.73  4295.7 1130.33  4345.7 1140.08
  4385.7 1142.14  4405.7 1141.10  4455.7 1131.90  4485.7 1129.39  4815.7 1126.21
  4865.7 1124.08  4955.7 1124.68  4995.7 1121.96  5365.8 1126.44  5505.8 1125.83
  5635.8 1130.67  6013.8 1120.85  6053.8 1120.41  6054.1 1119.91  6057.8 1120.41
  6385.9 1128.91  6837.1 1148.19  7066.0 1153.41  7416.0 1152.60  7751.0 1156.15
#Mann=4,-1,0
  2633.6    0.05       0  6013.8    0.05       0  6053.8       0       0
  6057.8    0.05       0
Bank Sta=6053.8,6057.8
Exp/Cntr=0.3,0.1

Type RM Length L Ch R = 1,6984,400,400,400
BEGIN DESCRIPTION:
Upper Denton 56a 15.0
END DESCRIPTION:
XS GIS Cut Line= 3
      2180279.18      7272608.73      2177812.93      7272470.44
      2175277.53      7272677.88
#Sta/Elev= 30
  2539.0 1148.59  2919.8 1143.47  3270.3 1142.52  3520.7 1140.40  3590.8 1138.60
  3671.0 1140.14  4091.6 1135.87  4111.6 1136.76  4210.0 1135.58  4215.0 1136.92
  4271.9 1136.95  4324.4 1135.50  4573.9 1131.75  4812.7 1121.16  4983.0 1118.01
  5003.0 1115.07  5008.6 1116.92  5033.1 1118.78  5161.6 1114.23  5161.8 1113.73
  5165.6 1114.23  5190.2 1114.61  5484.6 1119.27  5817.3 1131.08  6106.7 1144.27
  6558.2 1158.69  6678.6 1159.69  6929.5 1157.27  7269.0 1161.12  7553.0 1160.53
#Mann=6,-1,0
  2539.0    0.05       0  4324.4    0.12       0  5161.6       0       0
  5165.6    0.12       0  5190.2    0.12       0  5817.3    0.05       0
Bank Sta=5161.6,5165.6
Exp/Cntr=0.3,0.1

Type RM Length L Ch R = 1,6584,509,509,509
BEGIN DESCRIPTION:
Upper Denton 56a 14.0
END DESCRIPTION:
XS GIS Cut Line= 3
      2179069.06      7272286.04      2177789.88      7272078.60
      2175393.40      7272493.38
#Sta/Elev= 30
  3690.5 1146.32  3757.9 1147.50  3903.3 1145.45  4035.0 1145.32  4045.1 1146.18
  4131.8 1144.69  4137.8 1145.17  4207.2 1143.43  4389.6 1137.37  4440.2 1136.98
  4446.0 1135.62  4531.4 1132.21  4582.1 1128.13  4612.5 1126.98  4673.2 1121.42
  4866.7 1114.38  4966.7 1113.59  5096.9 1110.84  5097.2 1110.34  5100.9 1110.84
  5144.0 1111.82  5551.1 1125.38  6193.3 1142.97  6377.7 1149.34  6621.2 1154.23
  6895.2 1156.22  7006.9 1157.94  7194.0 1161.14  7308.5 1164.08  7418.5 1165.53
#Mann=7,-1,0
  3690.5    0.05       0  4131.8    0.12       0  4866.7    0.05       0
  4966.7    0.12       0  5096.9    0.07       0  5100.9    0.12       0
  5144.0    0.05       0
Bank Sta=5096.9,5100.9
Exp/Cntr=0.3,0.1

Type RM Length L Ch R = 1,6075,327,327,327
BEGIN DESCRIPTION:
Upper Denton 56a 13.0
END DESCRIPTION:
XS GIS Cut Line= 3
      2178873.17      7271848.11      2177812.93      7271571.52
      2175807.64      7271467.80
#Sta/Elev= 30
  3913.3 1146.29  3959.0 1145.37  3964.7 1146.80  3969.8 1145.55  4114.0 1140.60
  4248.3 1134.60  4300.0 1133.96  4323.8 1132.78  4359.1 1129.39  4393.0 1128.48
  4475.4 1123.16  4556.3 1120.55  4561.5 1120.96  4596.8 1119.26  4602.0 1119.88
  4637.3 1118.24  4642.5 1118.73  4816.7 1113.72  5023.0 1114.10  5141.1 1109.96
  5141.4 1109.46  5145.1 1109.96  5393.5 1112.20  5583.7 1114.90  5974.2 1126.39
  6234.6 1138.39  6490.2 1148.12  6687.1 1153.51  6835.4 1158.70  7017.0 1159.93
#Mann=3,-1,0
  3913.3    0.05       0  5141.1   0.033       0  5145.1    0.05       0
Bank Sta=5141.1,5145.1
Exp/Cntr=0.3,0.1

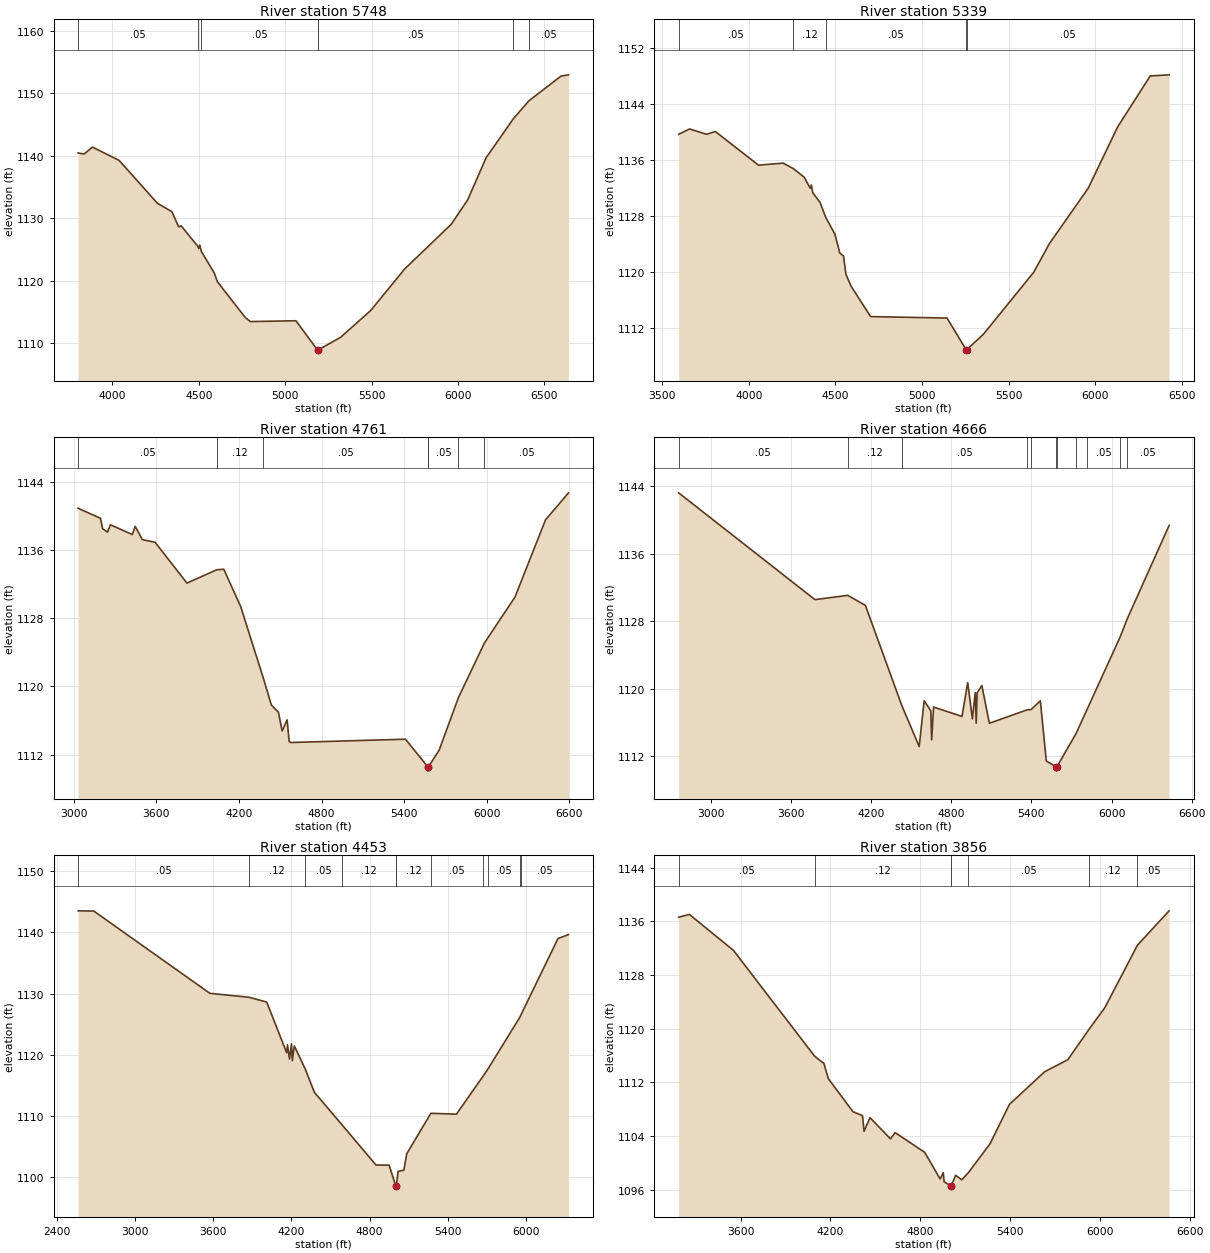
Type RM Length L Ch R = 1,5748,409,409,409
BEGIN DESCRIPTION:
Upper Denton 56a 12.0
END DESCRIPTION:
XS GIS Cut Line= 3
      2178968.86      7271697.20      2177843.83      7271244.06
      2176307.34      7270718.01
#Sta/Elev= 30
  3802.2 1140.42  3837.3 1140.25  3885.6 1141.35  4039.2 1139.24  4261.7 1132.35
  4344.9 1131.02  4384.2 1128.59  4398.7 1128.74  4493.4 1125.53  4500.7 1125.13
  4506.1 1125.67  4515.2 1124.65  4589.4 1121.25  4608.1 1119.81  4769.3 1114.08
  4798.8 1113.43  5062.4 1113.56  5187.3 1108.88  5187.5 1108.38  5191.3 1108.88
  5321.1 1110.92  5495.8 1115.23  5691.4 1121.85  5960.9 1129.01  6056.0 1132.92
  6161.7 1139.61  6318.0 1145.82  6409.5 1148.75  6595.1 1152.71  6639.1 1152.92
#Mann=7,-1,0
  3802.2    0.05       0  4493.4    0.12       0  4515.2    0.05       0
  5187.3   0.033       0  5191.3    0.05       0  6318.0    0.12       0
  6409.5    0.05       0
Bank Sta=5187.3,5191.3
Exp/Cntr=0.3,0.1

Type RM Length L Ch R = 1,5339,578,578,578
BEGIN DESCRIPTION:
Upper Denton 56a 11.0
END DESCRIPTION:
XS GIS Cut Line= 3
      2179020.83      7271736.48      2177951.34      7270861.45
      2176590.23      7270368.39
#Sta/Elev= 30
  3595.8 1139.66  3658.8 1140.42  3757.9 1139.66  3807.4 1140.06  4056.5 1135.26
  4198.6 1135.55  4257.5 1134.77  4319.9 1133.55  4355.1 1131.97  4361.5 1132.44
  4369.4 1131.33  4412.2 1129.93  4443.3 1127.87  4497.2 1125.43  4525.9 1122.71
  4546.7 1122.33  4561.1 1119.69  4589.8 1118.04  4703.2 1113.67  5144.2 1113.46
  5254.1 1108.96  5254.3 1108.46  5258.1 1108.96  5353.3 1111.13  5643.7 1119.97
  5735.6 1124.11  5958.6 1131.97  6128.8 1140.73  6316.4 1147.98  6425.3 1148.14
#Mann=5,-1,0
  3595.8    0.05       0  4257.5    0.12       0  4443.3    0.05       0
  5254.1   0.033       0  5258.1    0.05       0
Bank Sta=5254.1,5258.1
Exp/Cntr=0.3,0.1

Type RM Length L Ch R = 1,4761,95,95,95
BEGIN DESCRIPTION:
Upper Denton 56a 10.5
END DESCRIPTION:
XS GIS Cut Line= 4
      2179203.22      7271952.43      2178093.83      7270290.94
      2177708.41      7269941.98      2176673.04      7270073.20
#Sta/Elev= 30
  3031.8 1140.92  3194.8 1139.74  3209.8 1138.53  3245.8 1138.11  3266.9 1138.98
  3426.1 1137.83  3447.1 1138.79  3498.1 1137.24  3591.3 1136.92  3822.5 1132.13
  4038.5 1133.69  4089.9 1133.76  4213.0 1129.36  4377.5 1120.95  4435.3 1117.81
  4486.4 1116.98  4513.7 1114.77  4549.8 1116.07  4564.5 1113.56  4573.5 1113.41
  5409.0 1113.80  5571.9 1110.55  5572.1 1110.05  5575.9 1110.55  5654.0 1112.52
  5792.6 1118.64  5981.8 1125.08  6204.2 1130.48  6425.9 1139.55  6593.2 1142.73
#Mann=7,-1,0
  3031.8    0.05       0  4038.5    0.12       0  4377.5    0.05       0
  5571.9   0.033       0  5575.9    0.05       0  5792.6    0.12       0
  5981.8    0.05       0
Bank Sta=5571.9,5575.9
Exp/Cntr=0.3,0.1

Type RM Length L Ch R = 1,4666,213,213,213
BEGIN DESCRIPTION:
Upper Denton 56a 10.0
END DESCRIPTION:
XS GIS Cut Line= 5
      2179349.05      7272119.10      2178390.70      7270514.90
      2178135.49      7270218.02      2177817.78      7269915.94
      2176937.58      7269499.27
#Sta/Elev= 30
  2758.7 1143.23  3779.7 1130.56  4024.7 1131.07  4157.1 1129.88  4428.5 1118.05
  4559.9 1113.14  4596.9 1118.56  4646.7 1117.38  4653.3 1113.93  4667.6 1117.82
  4880.4 1116.71  4923.2 1120.72  4958.3 1116.42  4979.2 1119.53  4986.9 1115.90
  4993.5 1119.51  5029.0 1120.37  5085.6 1115.90  5370.3 1117.50  5397.6 1117.52
  5467.0 1118.56  5511.5 1111.42  5586.7 1110.72  5586.9 1110.22  5590.7 1110.72
  5734.8 1114.69  5819.8 1117.64  6066.3 1126.20  6115.2 1128.19  6431.1 1139.36
#Mann=11,-1,0
  2758.7    0.05       0  4024.7    0.12       0  4428.5    0.05       0
  5370.3    0.12       0  5397.6    0.05       0  5586.7   0.033       0
  5590.7    0.05       0  5734.8    0.12       0  5819.8    0.05       0
  6066.3    0.12       0  6115.2    0.05       0
Bank Sta=5586.7,5590.7
Exp/Cntr=0.3,0.1

Type RM Length L Ch R = 1,4453,597,597,597
BEGIN DESCRIPTION:
Upper Denton 56a 9.0
END DESCRIPTION:
XS GIS Cut Line= 3
      2179403.33      7272113.19      2178170.19      7270038.76
      2176948.60      7269451.01
#Sta/Elev= 30
  2560.4 1143.51  2681.4 1143.47  3573.6 1130.04  3874.0 1129.40  4009.9 1128.62
  4163.8 1120.33  4169.6 1121.64  4185.2 1119.33  4200.8 1121.81  4206.6 1119.06
  4222.2 1121.45  4306.8 1117.66  4376.1 1113.89  4592.3 1108.49  4849.4 1102.02
  4950.7 1101.99  5002.1 1098.58  5002.3 1098.08  5006.1 1098.58  5019.4 1100.97
  5063.8 1101.17  5086.0 1103.85  5271.7 1110.46  5467.8 1110.31  5673.5 1116.54
  5713.5 1117.81  5953.4 1126.07  5965.6 1126.61  6248.3 1138.99  6329.3 1139.63
#Mann=11,-1,0
  2560.4    0.05       0  3874.0    0.12       0  4306.8    0.05       0
  4592.3    0.12       0  5002.1    0.07       0  5006.1    0.12       0
  5271.7    0.05       0  5673.5    0.12       0  5713.5    0.05       0
  5953.4    0.12       0  5965.6    0.05       0
Bank Sta=5002.1,5006.1
Exp/Cntr=0.3,0.1

Type RM Length L Ch R = 1,3856,500,500,500
BEGIN DESCRIPTION:
Upper Denton 56a 8.0
END DESCRIPTION:
XS GIS Cut Line= 4
      2180216.64      7270029.65      2179174.99      7269801.79
      2178454.42      7269604.40      2177029.28      7269278.14
#Sta/Elev= 30
  3186.6 1136.63  3258.1 1137.05  3552.7 1131.69  4093.9 1115.94  4156.6 1114.84
  4186.6 1112.56  4350.7 1107.65  4414.6 1107.06  4424.9 1104.73  4464.5 1106.76
  4601.2 1103.60  4632.4 1104.53  4829.4 1101.60  4933.0 1097.62  4953.8 1098.57
  4959.4 1097.20  5003.6 1096.61  5003.8 1096.11  5007.6 1096.61  5036.3 1098.17
  5077.4 1097.50  5121.4 1098.56  5266.7 1102.88  5395.4 1108.73  5631.3 1113.61
  5785.2 1115.38  5927.0 1119.92  6032.3 1123.13  6250.9 1132.47  6462.0 1137.58
#Mann=7,-1,0
  3186.6    0.05       0  4093.9    0.12       0  5003.6    0.07       0
  5007.6    0.12       0  5121.4    0.05       0  5927.0    0.12       0
  6250.9    0.05       0
Bank Sta=5003.6,5007.6
Exp/Cntr=0.3,0.1

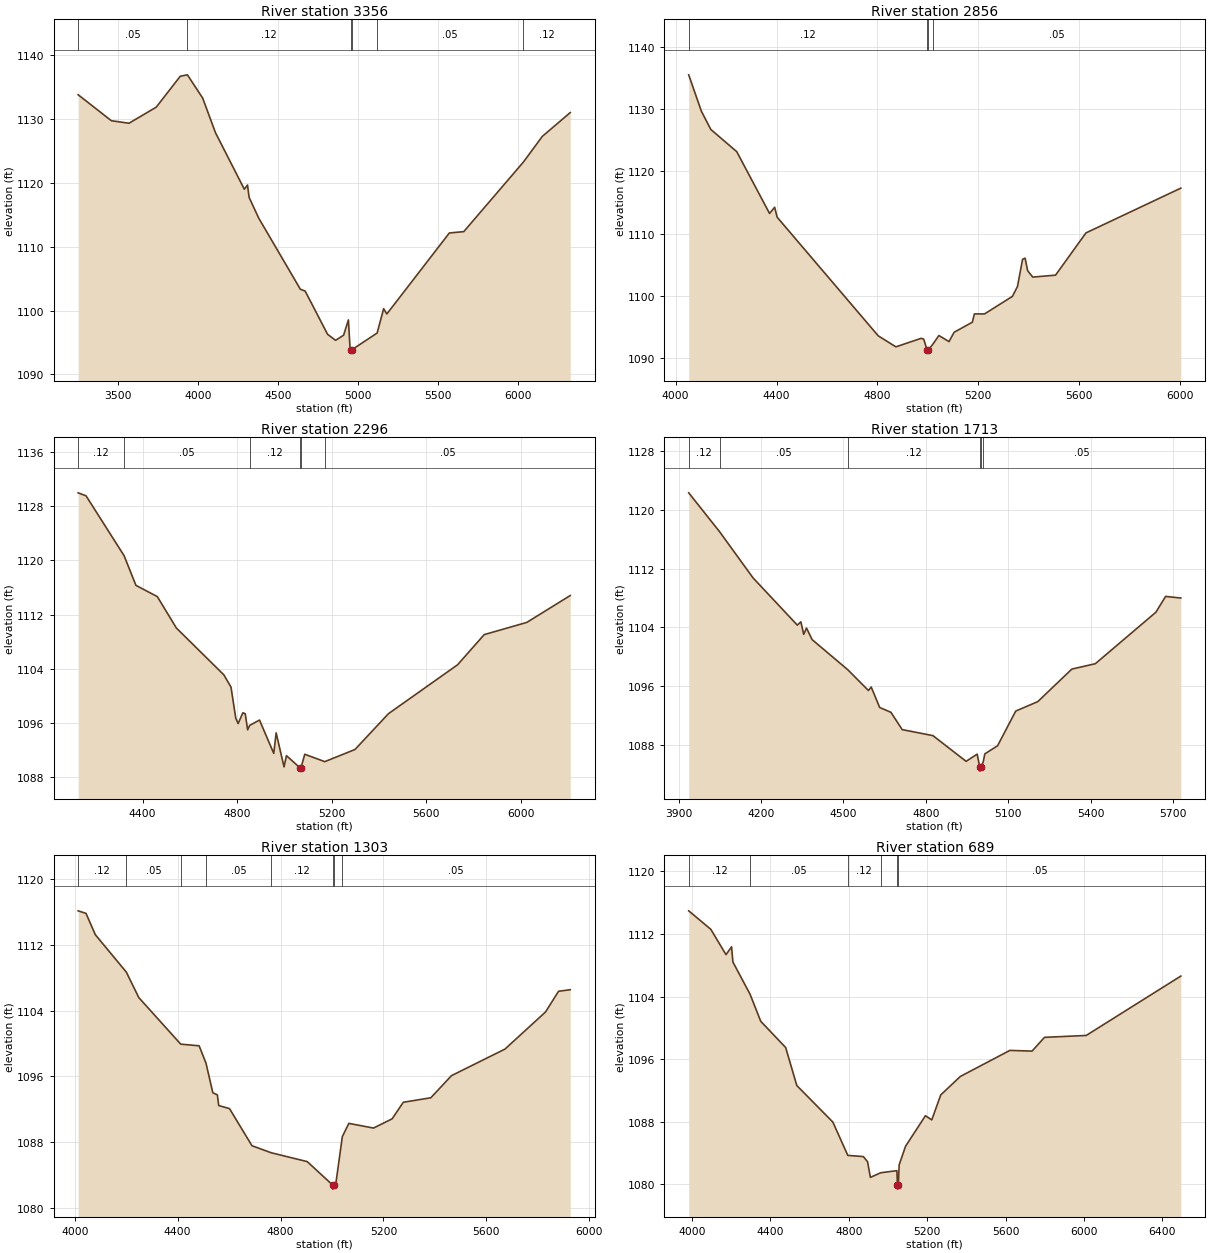
Type RM Length L Ch R = 1,3356,500,500,500
BEGIN DESCRIPTION:
Upper Denton 56a 7.0
END DESCRIPTION:
XS GIS Cut Line= 3
      2180216.70      7269139.90      2178468.79      7269114.42
      2177144.47      7269162.89
#Sta/Elev= 30
  3251.9 1133.84  3459.6 1129.76  3569.6 1129.37  3739.7 1131.89  3889.7 1136.74
  3934.3 1136.96  4029.7 1133.31  4109.7 1127.88  4289.7 1119.02  4309.7 1119.68
  4319.7 1117.74  4379.7 1114.49  4639.7 1103.34  4669.8 1103.05  4809.8 1096.27
  4859.8 1095.33  4909.8 1096.13  4939.8 1098.53  4949.8 1094.18  4955.2 1093.82
  4955.5 1093.32  4959.5 1093.82  5119.2 1096.47  5159.9 1100.29  5179.9 1099.46
  5570.2 1112.16  5660.2 1112.37  6033.0 1123.29  6150.6 1127.30  6325.2 1131.04
#Mann=6,-1,0
  3251.9    0.05       0  3934.3    0.12       0  4955.2    0.07       0
  4959.5    0.12       0  5119.2    0.05       0  6033.0    0.12       0
Bank Sta=4955.2,4959.5
Exp/Cntr=0.3,0.1

Type RM Length L Ch R = 1,2856,560,560,560
BEGIN DESCRIPTION:
Upper Denton 56a 6.0
END DESCRIPTION:
XS GIS Cut Line= 3
      2179379.03      7268760.00      2178432.39      7268707.35
      2177435.02      7268809.60
#Sta/Elev= 30
  4051.9 1135.53  4102.0 1129.69  4139.5 1126.75  4242.2 1123.19  4372.4 1113.25
  4392.5 1114.25  4402.5 1112.65  4803.1 1093.59  4873.2 1091.82  4973.3 1093.19
  4983.4 1093.06  4997.0 1091.31  4997.4 1090.81  5001.4 1091.31  5020.2 1092.27
  5043.6 1093.64  5083.8 1092.66  5103.9 1094.16  5176.2 1095.78  5184.3 1097.11
  5224.6 1097.11  5335.1 1099.93  5355.2 1101.52  5375.3 1105.89  5385.4 1106.07
  5395.4 1104.06  5415.6 1103.03  5506.0 1103.34  5626.7 1110.13  6002.6 1117.32
#Mann=4,-1,0
  4051.9    0.12       0  4997.0    0.07       0  5001.4    0.12       0
  5020.2    0.05       0
Bank Sta=4997,5001.4
Exp/Cntr=0.3,0.1

Type RM Length L Ch R = 1,2296,583,583,583
BEGIN DESCRIPTION:
Upper Denton 56a 5.0
END DESCRIPTION:
XS GIS Cut Line= 4
      2179492.25      7268549.18      2178615.53      7268453.70
      2178172.82      7268384.25      2177495.73      7268714.12
#Sta/Elev= 30
  4127.2 1129.97  4160.6 1129.53  4321.9 1120.68  4371.9 1116.31  4462.4 1114.65
  4542.9 1110.02  4744.1 1103.10  4774.3 1101.29  4794.4 1096.72  4804.4 1095.91
  4824.6 1097.50  4834.6 1097.36  4844.7 1094.99  4853.3 1095.64  4895.0 1096.43
  4955.3 1091.51  4965.4 1094.54  4998.8 1089.52  5009.1 1091.17  5066.1 1089.39
  5066.5 1088.89  5070.5 1089.39  5086.6 1091.38  5171.3 1090.29  5299.1 1092.08
  5440.9 1097.37  5733.5 1104.59  5846.2 1109.04  6026.5 1110.84  6210.4 1114.81
#Mann=6,-1,0
  4127.2    0.12       0  4321.9    0.05       0  4853.3    0.12       0
  5066.1    0.07       0  5070.5    0.12       0  5171.3    0.05       0
Bank Sta=5066.1,5070.5
Exp/Cntr=0.3,0.1

Type RM Length L Ch R = 1,1713,410,410,410
BEGIN DESCRIPTION:
Upper Denton 56a 4.0
END DESCRIPTION:
XS GIS Cut Line= 5
      2179457.49      7268340.84      2178632.89      7268158.56
      2178398.51      7268132.52      2178103.37      7268149.88
      2177773.77      7268401.42
#Sta/Elev= 30
  3937.1 1122.29  4049.4 1117.01  4171.1 1110.74  4332.3 1104.32  4345.2 1104.77
  4355.5 1103.07  4365.7 1103.92  4386.2 1102.35  4516.6 1098.24  4591.0 1095.44
  4601.2 1095.91  4632.0 1093.13  4672.9 1092.48  4713.9 1090.13  4825.8 1089.31
  4946.5 1085.82  4986.8 1086.80  4996.2 1084.99  4996.6 1084.49  5000.7 1084.99
  5008.7 1085.75  5014.7 1086.84  5060.9 1087.93  5127.1 1092.65  5207.3 1093.93
  5331.2 1098.35  5416.7 1099.08  5637.0 1106.07  5672.4 1108.22  5727.7 1108.00
#Mann=6,-1,0
  3937.1    0.12       0  4049.4    0.05       0  4516.6    0.12       0
  4996.2    0.07       0  5000.7    0.12       0  5008.7    0.05       0
Bank Sta=4996.2,5000.7
Exp/Cntr=0.3,0.1

Type RM Length L Ch R = 1,1303,614,614,614
BEGIN DESCRIPTION:
Upper Denton 56a 3.0
END DESCRIPTION:
XS GIS Cut Line= 4
      2179470.57      7268197.63      2178682.42      7267861.79
      2178474.09      7267831.41      2177783.07      7268318.53
#Sta/Elev= 30
  4013.2 1116.15  4043.7 1115.84  4080.1 1113.24  4200.4 1108.69  4249.0 1105.58
  4412.0 1099.91  4483.4 1099.71  4510.2 1097.59  4536.7 1093.99  4554.3 1093.73
  4559.7 1092.43  4601.5 1092.06  4688.8 1087.54  4762.7 1086.69  4903.7 1085.60
  5002.5 1082.75  5002.9 1082.25  5007.0 1082.75  5014.9 1082.93  5040.1 1088.65
  5065.4 1090.26  5161.2 1089.69  5233.5 1090.81  5277.0 1092.83  5384.1 1093.38
  5464.2 1096.07  5672.3 1099.31  5829.9 1103.83  5880.4 1106.35  5925.9 1106.54
#Mann=8,-1,0
  4013.2    0.12       0  4200.4    0.05       0  4412.0    0.12       0
  4510.2    0.05       0  4762.7    0.12       0  5002.5    0.07       0
  5007.0    0.12       0  5040.1    0.05       0
Bank Sta=5002.5,5007
Exp/Cntr=0.3,0.1

Type RM Length L Ch R = 1,689,572,572,572
BEGIN DESCRIPTION:
Upper Denton 56a 2.0
END DESCRIPTION:
XS GIS Cut Line= 5
      2179533.13      7268174.31      2178838.67      7267553.64
      2178717.14      7267531.93      2178346.43      7267637.73
      2177549.62      7268352.23
#Sta/Elev= 30
  3983.8 1114.97  4096.4 1112.61  4174.1 1109.37  4202.5 1110.37  4209.2 1108.43
  4296.6 1104.32  4351.3 1100.85  4478.4 1097.50  4535.3 1092.64  4719.2 1087.97
  4795.5 1083.71  4874.7 1083.56  4896.4 1082.90  4910.6 1080.90  4963.1 1081.49
  5045.9 1081.76  5048.8 1079.90  5049.3 1079.40  5053.3 1079.90  5057.5 1082.51
  5090.1 1084.88  5191.5 1088.78  5223.9 1088.25  5269.6 1091.44  5369.5 1093.80
  5622.2 1097.13  5735.5 1097.04  5799.0 1098.80  6011.7 1099.04  6494.4 1106.63
#Mann=6,-1,0
  3983.8    0.12       0  4296.6    0.05       0  4795.5    0.12       0
  4963.1    0.05       0  5048.8   0.033       0  5053.3    0.05       0
Bank Sta=5048.8,5053.3
Exp/Cntr=0.3,0.1

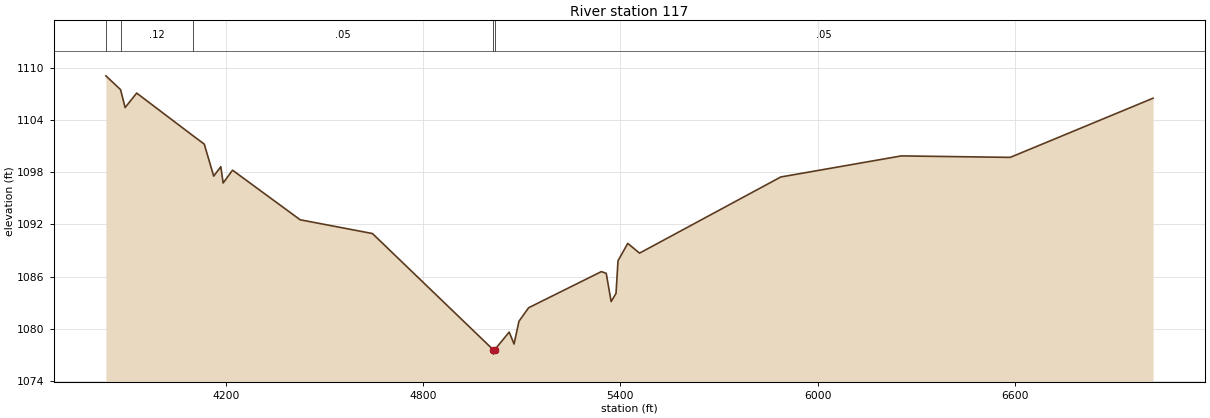
Type RM Length L Ch R = 1,117,0,0,0
BEGIN DESCRIPTION:
Upper Denton 56a 1.0
END DESCRIPTION:
XS GIS Cut Line= 4
      2179641.63      7268039.76      2178960.20      7267215.09
      2178829.99      7267202.07      2177193.88      7268330.42
#Sta/Elev= 30
  3833.5 1109.05  3878.0 1107.47  3892.1 1105.41  3927.2 1107.07  4098.9 1102.17
  4133.0 1101.21  4161.7 1097.54  4183.4 1098.62  4190.4 1096.75  4219.1 1098.22
  4424.9 1092.53  4645.0 1090.95  5012.8 1077.61  5013.2 1077.11  5017.3 1077.61
  5061.3 1079.64  5076.2 1078.27  5091.1 1080.88  5120.4 1082.43  5341.9 1086.58
  5356.8 1086.38  5371.7 1083.14  5386.6 1084.08  5392.6 1087.82  5422.4 1089.82
  5458.2 1088.70  5888.2 1097.44  6255.4 1099.86  6586.7 1099.69  7021.6 1106.48
#Mann=5,-1,0
  3833.5    0.05       0  3878.0    0.12       0  4098.9    0.05       0
  5012.8   0.033       0  5017.3    0.05       0
Bank Sta=5012.8,5017.3
Exp/Cntr=0.3,0.1

Chan Stop Cuts=-1