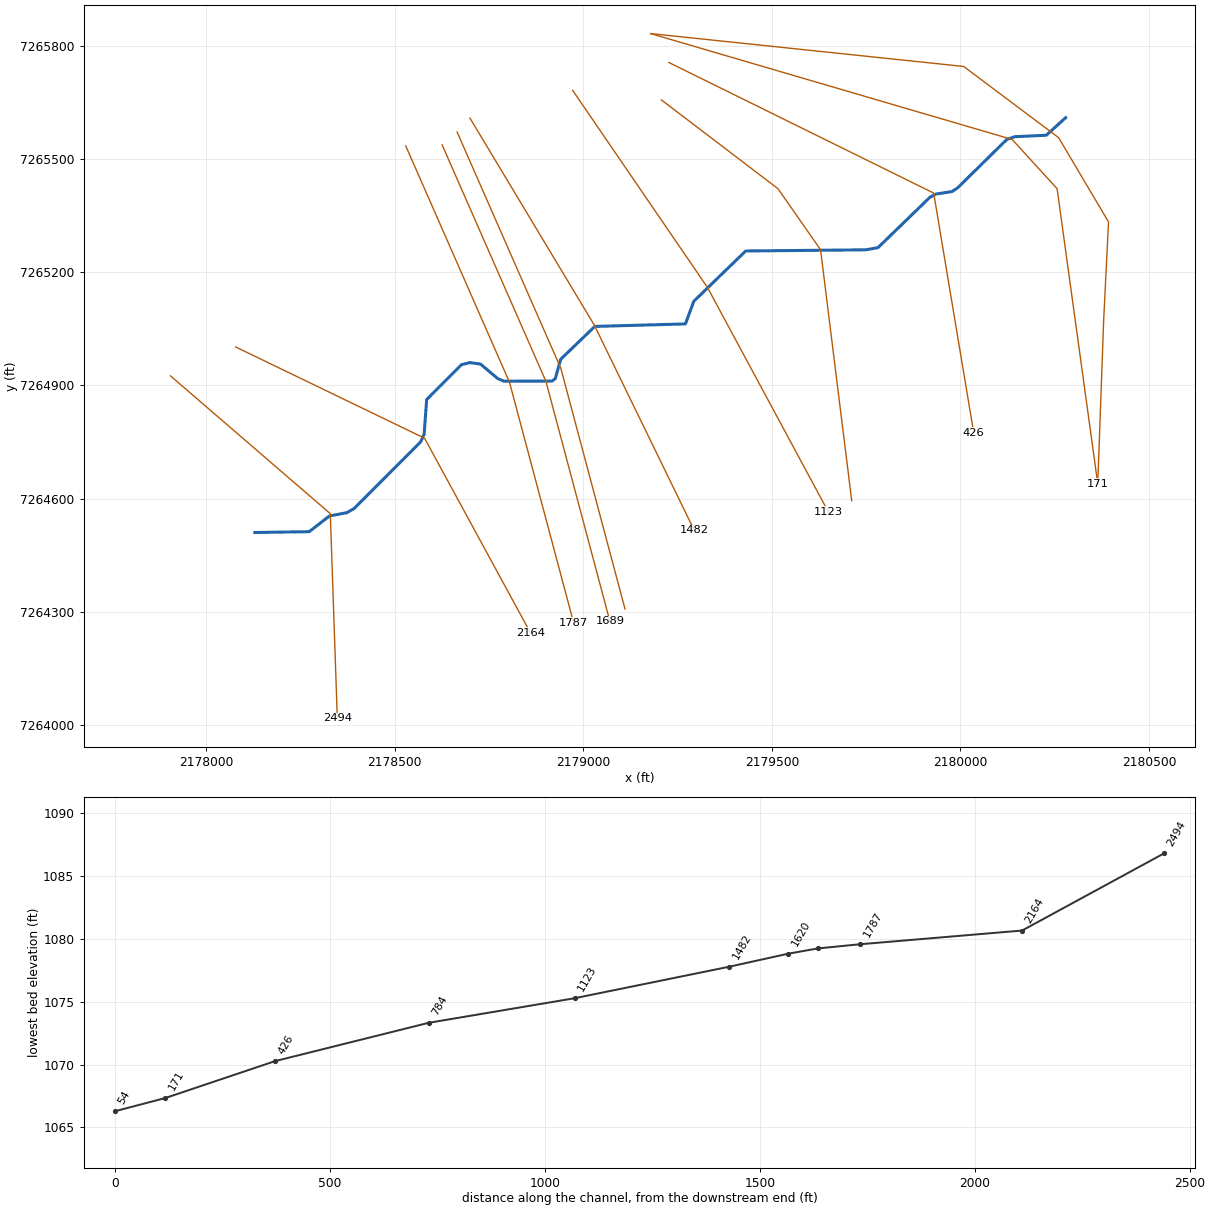
--- Upper Denton 57.prj (project) ---

Proj Title=Upper Denton 57 Base Level Engineering
Current Plan=p01
Default Exp/Contr=0.3,0.1
English Units
Geom File=g01
Flow File=f01
Plan File=p01
BEGIN DESCRIPTION:
Upper Denton 57
END DESCRIPTION:

--- Upper Denton 57.p01 (plan) ---

Plan Title=Multiple Run
Short Identifier=Multiple
Geom File=g01
Flow File=f01
Subcritical Flow
K Sum by GR= 0
Std Step Tol= 0.01
Critical Tol= 0.01
Num of Std Step Trials= 20
Max Error Tol= 0.3
Flow Tol Ratio= 0.001
Split Flow NTrial= 30
Split Flow Tol= 0.02
Split Flow Ratio= 0.02
Log Output Level= 0
Friction Slope Method= 1
Unsteady Friction Slope Method= 2
Unsteady Bridges Friction Slope Method= 1
Parabolic Critical Depth
Global Vel Dist=  1 , 1 , 1
Global Log Level= 0
CheckData=True
Encroach Param= -1, 0, 0, 0
BEGIN DESCRIPTION:
Multiple Run
END DESCRIPTION:

--- Upper Denton 57.f01 (steady flow) ---

Flow Title=Multiple
Number of Profiles=7
Profile Names=10-year,25-year,50-year,1pct_min,100-year,1pct_plu,500-year
River Rch & RM= Upper Denton 57,Reach-1,2494
     484     663     811     493     984    1964    1454
Boundary for River Rch & Prof#=Upper Denton 57,Reach-1,1
Up Type=0
Dn Type=3
Dn Slope=0.005
Boundary for River Rch & Prof#=Upper Denton 57,Reach-1,2
Up Type=0
Dn Type=3
Dn Slope=0.005
Boundary for River Rch & Prof#=Upper Denton 57,Reach-1,3
Up Type=0
Dn Type=3
Dn Slope=0.005
Boundary for River Rch & Prof#=Upper Denton 57,Reach-1,4
Up Type=0
Dn Type=3
Dn Slope=0.005
Boundary for River Rch & Prof#=Upper Denton 57,Reach-1,5
Up Type=0
Dn Type=3
Dn Slope=0.005
Boundary for River Rch & Prof#=Upper Denton 57,Reach-1,6
Up Type=0
Dn Type=3
Dn Slope=0.005
Boundary for River Rch & Prof#=Upper Denton 57,Reach-1,7
Up Type=0
Dn Type=3
Dn Slope=0.005

--- Upper Denton 57.g01 (geometry) ---

Geom Title=Existing Conditions

River Reach=Upper Denton 57,Reach-1
Reach XY= 30
      2178129.00      7264510.00      2178273.09      7264512.19
      2178326.83      7264553.86      2178372.97      7264562.49
      2178392.22      7264573.62      2178568.48      7264750.21
      2178577.83      7264770.48      2178584.52      7264862.44
      2178676.69      7264954.92      2178699.13      7264960.40
      2178727.25      7264956.66      2178772.93      7264918.18
      2178789.51      7264911.22      2178917.17      7264911.61
      2178925.61      7264918.10      2178939.90      7264969.40
      2179030.45      7265056.47      2179270.70      7265063.07
      2179292.74      7265122.95      2179430.46      7265256.46
      2179749.18      7265259.57      2179781.45      7265265.46
      2179919.32      7265399.22      2179935.05      7265407.46
      2179977.35      7265413.98      2179992.21      7265423.63
      2180122.82      7265552.15      2180144.19      7265559.53
      2180227.59      7265563.39      2180279.00      7265610.00

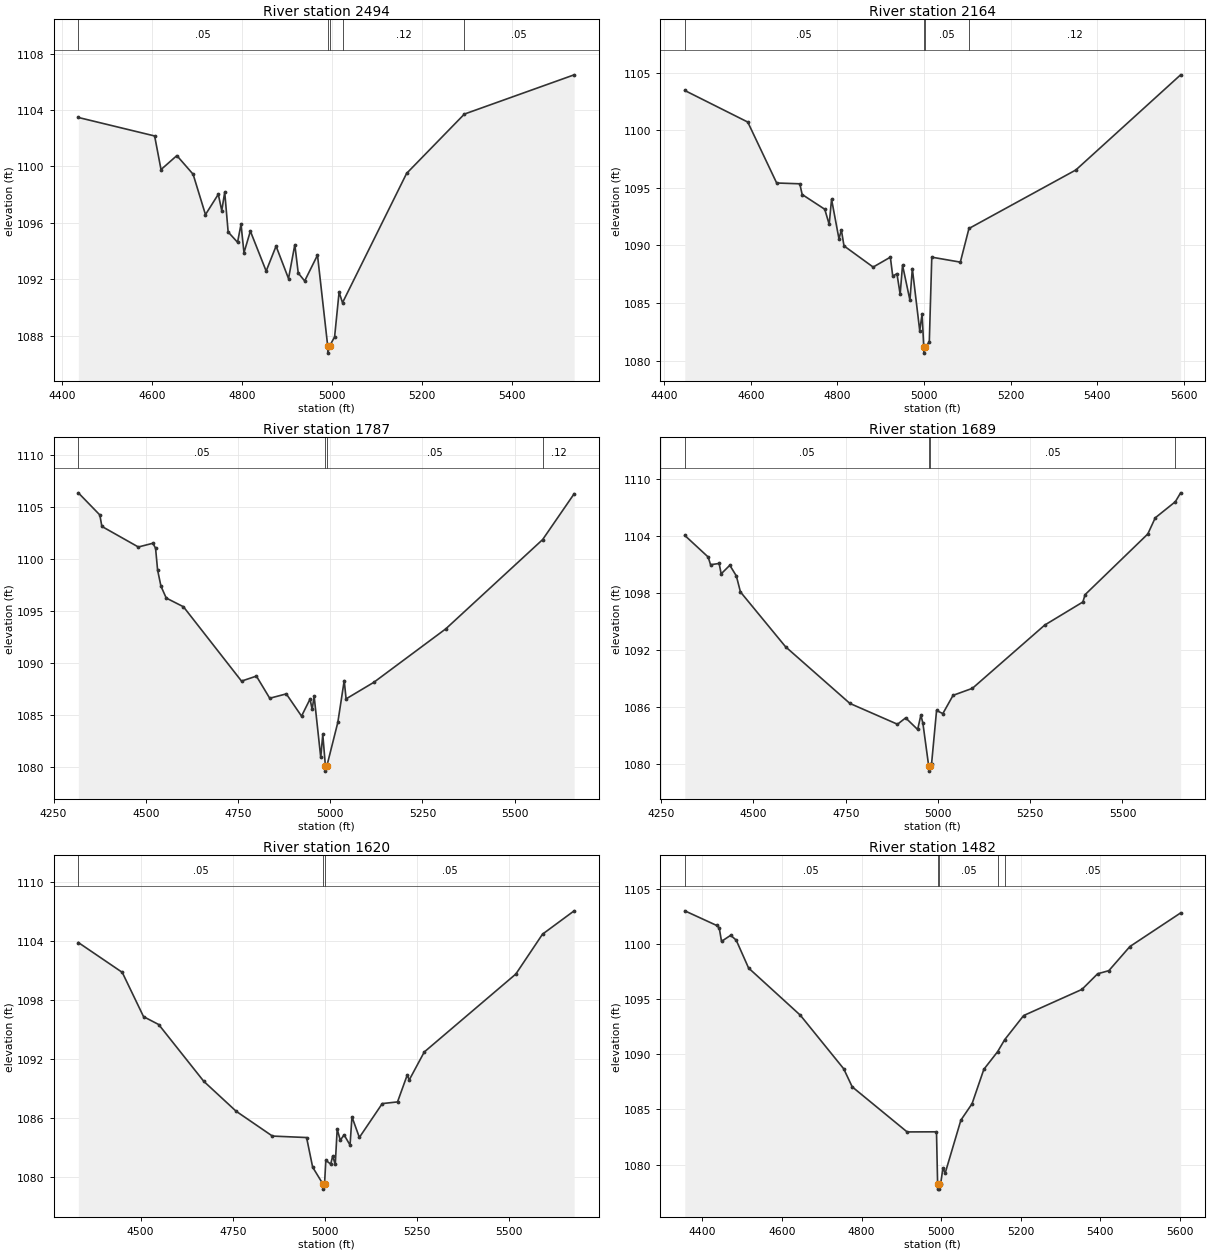
Type RM Length L Ch R = 1,2494,330,330,330
BEGIN DESCRIPTION:
Upper Denton 57 7.0
END DESCRIPTION:
XS GIS Cut Line= 3
      2177905.13      7264925.37      2178329.00      7264560.00
      2178347.59      7264017.83
#Sta/Elev= 30
  4435.4 1103.47  4605.0 1102.16  4619.2 1099.78  4654.4 1100.77  4690.5 1099.45
  4718.0 1096.59  4746.5 1098.03  4754.2 1096.87  4760.8 1098.18  4768.4 1095.36
  4789.3 1094.63  4797.0 1095.90  4803.6 1093.89  4817.8 1095.42  4852.9 1092.59
  4874.9 1094.36  4902.6 1092.06  4916.6 1094.46  4924.2 1092.45  4938.5 1091.89
  4967.0 1093.72  4989.7 1087.28  4990.0 1086.78  4993.7 1087.28  5005.0 1087.92
  5015.0 1091.10  5022.6 1090.35  5165.1 1099.51  5293.5 1103.71  5537.5 1106.49
#Mann=5,-1,0
  4435.4    0.05       0  4989.7   0.033       0  4993.7    0.05       0
  5022.6    0.12       0  5293.5    0.05       0
Bank Sta=4989.7,4993.7
Exp/Cntr=0.3,0.1

Type RM Length L Ch R = 1,2164,377,377,377
BEGIN DESCRIPTION:
Upper Denton 57 6.0
END DESCRIPTION:
XS GIS Cut Line= 3
      2178078.13      7265001.93      2178579.00      7264760.00
      2178860.05      7264243.44
#Sta/Elev= 30
  4447.7 1103.45  4593.0 1100.71  4659.7 1095.42  4713.1 1095.35  4718.6 1094.42
  4770.7 1093.14  4780.9 1091.83  4786.4 1094.01  4803.5 1090.57  4809.0 1091.35
  4815.1 1089.96  4882.4 1088.12  4922.1 1088.98  4927.6 1087.33  4937.3 1087.55
  4944.7 1085.76  4950.2 1088.29  4967.3 1085.24  4972.8 1087.99  4989.9 1082.59
  4995.4 1084.07  4999.2 1081.15  4999.4 1080.65  5003.2 1081.15  5012.0 1081.64
  5017.7 1088.98  5083.6 1088.55  5103.5 1091.47  5350.2 1096.55  5592.0 1104.81
#Mann=4,-1,0
  4447.7    0.05       0  4999.2   0.033       0  5003.2    0.05       0
  5103.5    0.12       0
Bank Sta=4999.2,5003.2
Exp/Cntr=0.3,0.1

Type RM Length L Ch R = 1,1787,98,98,98
BEGIN DESCRIPTION:
Upper Denton 57 5.0
END DESCRIPTION:
XS GIS Cut Line= 3
      2178529.09      7265535.11      2178804.20      7264908.33
      2178974.18      7264270.90
#Sta/Elev= 30
  4317.1 1106.33  4375.4 1104.20  4380.9 1103.10  4479.8 1101.12  4519.3 1101.48
  4526.5 1101.00  4532.0 1098.90  4541.1 1097.35  4555.4 1096.21  4602.1 1095.37
  4759.5 1088.22  4799.9 1088.70  4836.0 1086.57  4880.9 1086.99  4922.2 1084.85
  4945.2 1086.49  4951.0 1085.52  4956.4 1086.75  4974.3 1080.88  4979.8 1083.10
  4986.9 1080.06  4987.1 1079.56  4990.9 1080.06  5020.6 1084.25  5037.9 1088.27
  5043.0 1086.51  5118.1 1088.10  5313.4 1093.25  5575.8 1101.83  5661.3 1106.24
#Mann=4,-1,0
  4317.1    0.05       0  4986.9   0.033       0  4990.9    0.05       0
  5575.8    0.12       0
Bank Sta=4986.9,4990.9
Exp/Cntr=0.3,0.1

Type RM Length L Ch R = 1,1689,69,69,69
BEGIN DESCRIPTION:
Upper Denton 57 4.6
END DESCRIPTION:
XS GIS Cut Line= 3
      2178625.53      7265537.93      2178900.63      7264911.17
      2179070.53      7264274.01
#Sta/Elev= 30
  4313.8 1104.02  4377.1 1101.75  4383.6 1100.94  4406.9 1101.07  4412.4 1099.98
  4435.8 1100.88  4453.5 1099.76  4464.6 1098.08  4586.9 1092.31  4761.3 1086.35
  4890.3 1084.16  4912.4 1084.83  4944.9 1083.61  4953.7 1085.12  4959.1 1084.28
  4975.0 1079.73  4975.3 1079.23  4979.0 1079.73  4982.5 1079.93  4996.2 1085.61
  5013.2 1085.28  5040.9 1087.20  5093.4 1087.94  5289.3 1094.59  5392.8 1097.02
  5398.7 1097.79  5568.7 1104.17  5588.9 1105.87  5643.5 1107.57  5657.7 1108.50
#Mann=4,-1,0
  4313.8    0.05       0  4975.0   0.033       0  4979.0    0.05       0
  5643.5    0.12       0
Bank Sta=4975,4979
Exp/Cntr=0.3,0.1

Type RM Length L Ch R = 1,1620,138,138,138
BEGIN DESCRIPTION:
Upper Denton 57 4.5
END DESCRIPTION:
XS GIS Cut Line= 3
      2178665.22      7265572.00      2178940.33      7264945.20
      2179110.49      7264307.11
#Sta/Elev= 30
  4331.3 1103.86  4450.4 1100.83  4508.2 1096.33  4549.3 1095.53  4671.6 1089.76
  4759.4 1086.72  4857.7 1084.20  4950.4 1084.05  4966.9 1081.04  4995.1 1079.31
  4995.4 1078.81  4999.1 1079.31  5002.6 1081.74  5015.8 1081.35  5021.2 1082.17
  5028.2 1081.32  5033.4 1084.90  5041.9 1083.78  5052.2 1084.32  5068.3 1083.28
  5073.5 1086.15  5093.6 1084.06  5155.7 1087.50  5197.1 1087.67  5223.6 1090.42
  5228.7 1089.89  5269.6 1092.74  5518.0 1100.66  5590.4 1104.71  5676.2 1107.08
#Mann=3,-1,0
  4331.3    0.05       0  4995.1   0.033       0  4999.1    0.05       0
Bank Sta=4995.1,4999.1
Exp/Cntr=0.3,0.1

Type RM Length L Ch R = 1,1482,359,359,359
BEGIN DESCRIPTION:
Upper Denton 57 4.0
END DESCRIPTION:
XS GIS Cut Line= 3
      2178699.27      7265608.83      2179029.00      7265060.00
      2179294.21      7264515.40
#Sta/Elev= 30
  4355.9 1103.02  4436.2 1101.69  4442.4 1101.47  4448.2 1100.25  4471.2 1100.80
  4485.1 1100.36  4516.2 1097.83  4646.2 1093.55  4755.2 1088.69  4776.6 1087.05
  4914.6 1082.96  4988.4 1082.97  4991.2 1078.27  4991.5 1077.77  4995.0 1077.77
  4995.2 1078.27  4998.9 1078.27  5004.6 1079.68  5010.2 1079.22  5049.7 1084.03
  5077.8 1085.52  5107.4 1088.64  5142.0 1090.24  5160.0 1091.34  5207.5 1093.52
  5353.9 1095.89  5393.4 1097.31  5421.5 1097.59  5474.4 1099.78  5601.9 1102.83
#Mann=5,-1,0
  4355.9    0.05       0  4991.2   0.033       0  4995.2    0.05       0
  5142.0    0.12       0  5160.0    0.05       0
Bank Sta=4991.2,4995.2
Exp/Cntr=0.3,0.1

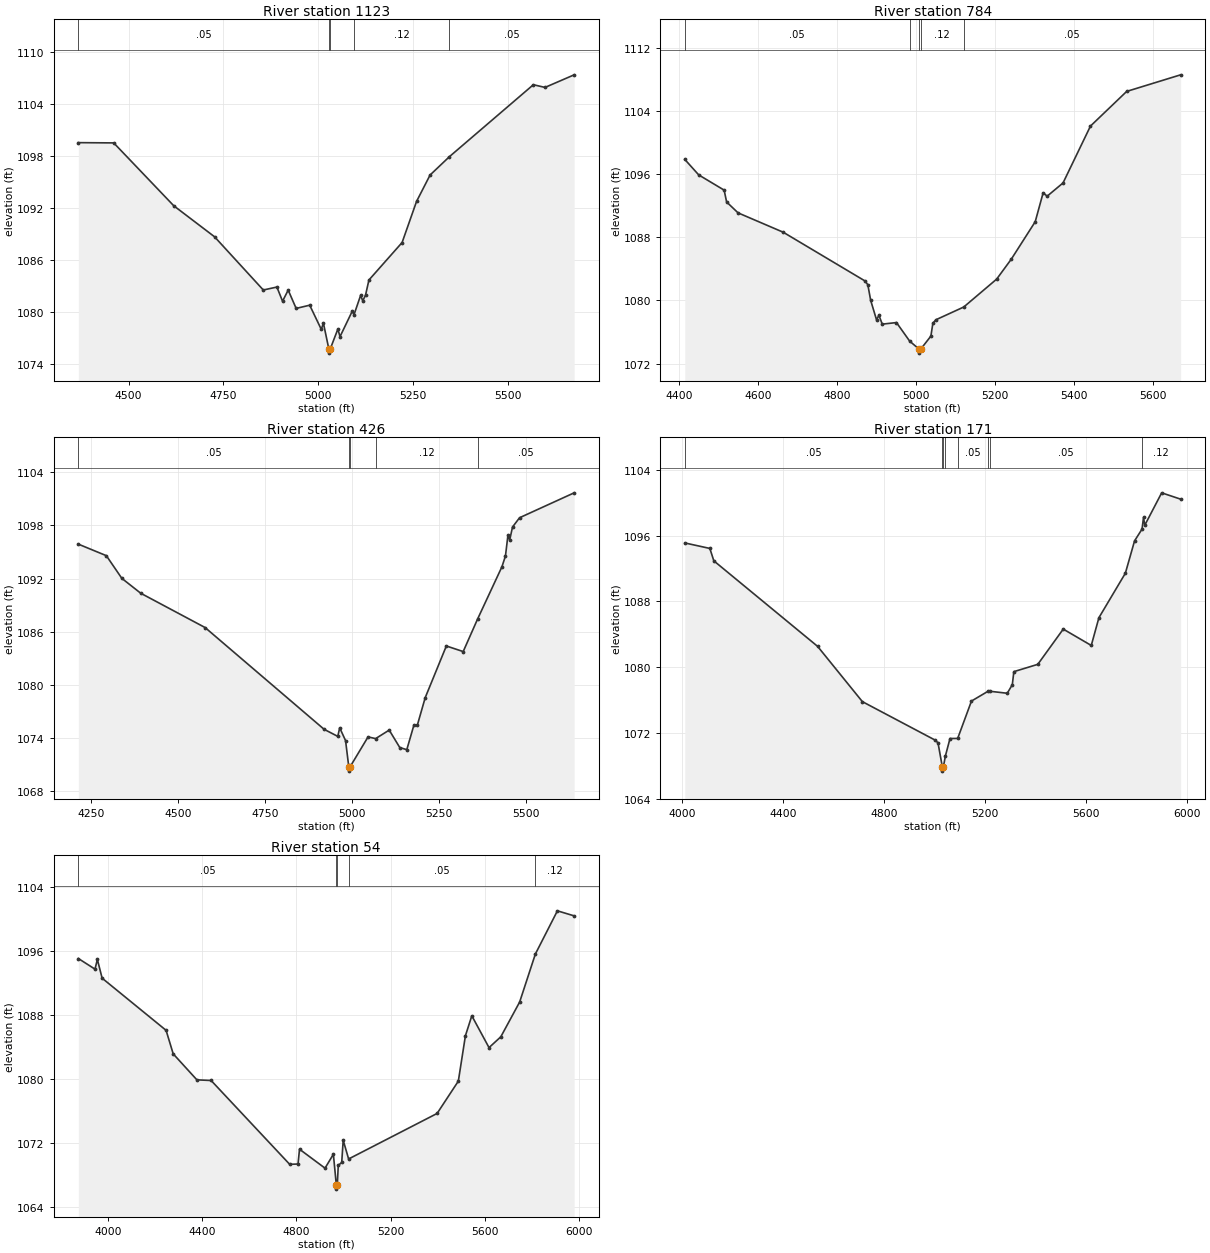
Type RM Length L Ch R = 1,1123,339,339,339
BEGIN DESCRIPTION:
Upper Denton 57 3.0
END DESCRIPTION:
XS GIS Cut Line= 3
      2178971.55      7265682.55      2179329.00      7265160.00
      2179649.34      7264565.19
#Sta/Elev= 30
  4367.1 1099.51  4460.5 1099.48  4619.0 1092.24  4726.6 1088.67  4855.3 1082.54
  4891.2 1082.88  4906.1 1081.25  4921.0 1082.53  4942.0 1080.42  4977.8 1080.79
  5008.3 1078.01  5014.0 1078.72  5028.2 1075.77  5028.5 1075.27  5032.2 1075.77
  5052.1 1078.04  5057.8 1077.17  5090.3 1080.12  5094.7 1079.69  5112.2 1081.92
  5117.8 1081.29  5125.1 1081.94  5134.1 1083.69  5221.7 1088.01  5259.8 1092.74
  5295.5 1095.78  5346.7 1097.90  5568.1 1106.18  5598.9 1105.87  5675.8 1107.32
#Mann=5,-1,0
  4367.1    0.05       0  5028.2   0.033       0  5032.2    0.05       0
  5094.7    0.12       0  5346.7    0.05       0
Bank Sta=5028.2,5032.2
Exp/Cntr=0.3,0.1

Type RM Length L Ch R = 1,784,358,358,358
BEGIN DESCRIPTION:
Upper Denton 57 2.0
END DESCRIPTION:
XS GIS Cut Line= 4
      2179206.91      7265657.07      2179516.06      7265421.66
      2179629.00      7265260.00      2179711.65      7264594.30
#Sta/Elev= 30
  4414.2 1097.85  4449.4 1095.89  4513.9 1093.96  4520.2 1092.46  4549.2 1091.08
  4663.6 1088.63  4870.5 1082.47  4878.0 1081.99  4885.3 1080.00  4900.1 1077.54
  4906.2 1078.11  4914.6 1076.99  4950.7 1077.19  4984.1 1074.84  5008.1 1073.82
  5008.3 1073.32  5012.1 1073.82  5037.9 1075.48  5042.9 1077.10  5050.4 1077.54
  5121.2 1079.16  5204.7 1082.70  5241.8 1085.23  5302.3 1089.96  5322.4 1093.63
  5332.5 1093.19  5372.8 1094.87  5442.3 1102.07  5534.1 1106.46  5670.8 1108.56
#Mann=5,-1,0
  4414.2    0.05       0  4984.1    0.12       0  5008.1    0.07       0
  5012.1    0.12       0  5121.2    0.05       0
Bank Sta=5008.1,5012.1
Exp/Cntr=0.3,0.1

Type RM Length L Ch R = 1,426,255,255,255
BEGIN DESCRIPTION:
Upper Denton 57 1.0
END DESCRIPTION:
XS GIS Cut Line= 3
      2179226.73      7265756.34      2179929.00      7265410.00
      2180035.07      7264775.03
#Sta/Elev= 30
  4212.5 1095.88  4293.1 1094.58  4337.7 1092.02  4392.1 1090.34  4577.3 1086.47
  4919.7 1074.99  4959.1 1074.19  4964.6 1075.16  4981.5 1073.71  4990.7 1070.77
  4991.0 1070.27  4994.7 1070.77  5046.2 1074.13  5068.0 1073.94  5107.1 1074.90
  5137.5 1072.93  5157.7 1072.69  5178.0 1075.44  5188.2 1075.48  5210.7 1078.56
  5271.5 1084.39  5320.0 1083.76  5361.3 1087.42  5431.5 1093.33  5441.6 1094.54
  5448.7 1096.87  5453.8 1096.35  5461.9 1097.81  5482.2 1098.86  5639.3 1101.67
#Mann=5,-1,0
  4212.5    0.05       0  4990.7   0.033       0  4994.7    0.05       0
  5068.0    0.12       0  5361.3    0.05       0
Bank Sta=4990.7,4994.7
Exp/Cntr=0.3,0.1

Type RM Length L Ch R = 1,171,117,117,117
BEGIN DESCRIPTION:
Upper Denton 57 0.5
END DESCRIPTION:
XS GIS Cut Line= 4
      2179178.56      7265832.90      2180137.16      7265552.12
      2180256.28      7265421.66      2180364.03      7264639.08
#Sta/Elev= 30
  4011.2 1095.12  4110.5 1094.45  4126.3 1092.94  4537.6 1082.53  4715.1 1075.80
  5003.3 1071.12  5014.9 1070.79  5032.2 1067.84  5032.4 1067.34  5036.2 1067.84
  5044.2 1069.18  5062.5 1071.31  5092.9 1071.32  5147.6 1075.87  5213.7 1077.07
  5221.3 1077.06  5289.4 1076.82  5309.5 1077.86  5315.6 1079.45  5410.5 1080.34
  5511.4 1084.63  5622.5 1082.64  5652.8 1086.02  5757.6 1091.43  5794.1 1095.37
  5823.8 1096.81  5829.6 1098.22  5834.7 1097.28  5901.6 1101.22  5976.7 1100.45
#Mann=8,-1,0
  4011.2    0.05       0  5032.2   0.033       0  5036.2    0.05       0
  5044.2    0.12       0  5092.9    0.05       0  5213.7    0.12       0
  5221.3    0.05       0  5823.8    0.12       0
Bank Sta=5032.2,5036.2
Exp/Cntr=0.3,0.1

Type RM Length L Ch R = 1,54,0,0,0
BEGIN DESCRIPTION:
Upper Denton 57 0.4
END DESCRIPTION:
XS GIS Cut Line= 6
      2179178.59      7265832.89      2180008.54      7265745.76
      2180260.28      7265556.96      2180392.65      7265333.44
      2180379.63      7265070.85      2180364.05      7264638.90
#Sta/Elev= 30
  3875.2 1095.12  3945.9 1093.79  3956.0 1095.00  3976.2 1092.66  4247.6 1086.14
  4277.8 1083.20  4378.4 1079.95  4438.7 1079.87  4772.1 1069.39  4807.5 1069.43
  4813.8 1071.28  4922.1 1068.91  4957.5 1070.65  4970.1 1066.79  4970.3 1066.29
  4974.1 1066.79  4978.3 1069.26  4992.9 1069.62  4999.2 1072.40  5022.2 1070.06
  5397.7 1075.75  5487.8 1079.79  5517.9 1085.47  5545.0 1087.96  5618.0 1083.98
  5668.0 1085.33  5748.0 1089.68  5814.7 1095.68  5908.2 1101.08  5979.3 1100.45
#Mann=5,-1,0
  3875.2    0.05       0  4970.1    0.07       0  4974.1    0.05       0
  5022.2    0.05       0  5814.7    0.12       0
Bank Sta=4970.1,4974.1
Exp/Cntr=0.3,0.1

Chan Stop Cuts=-1