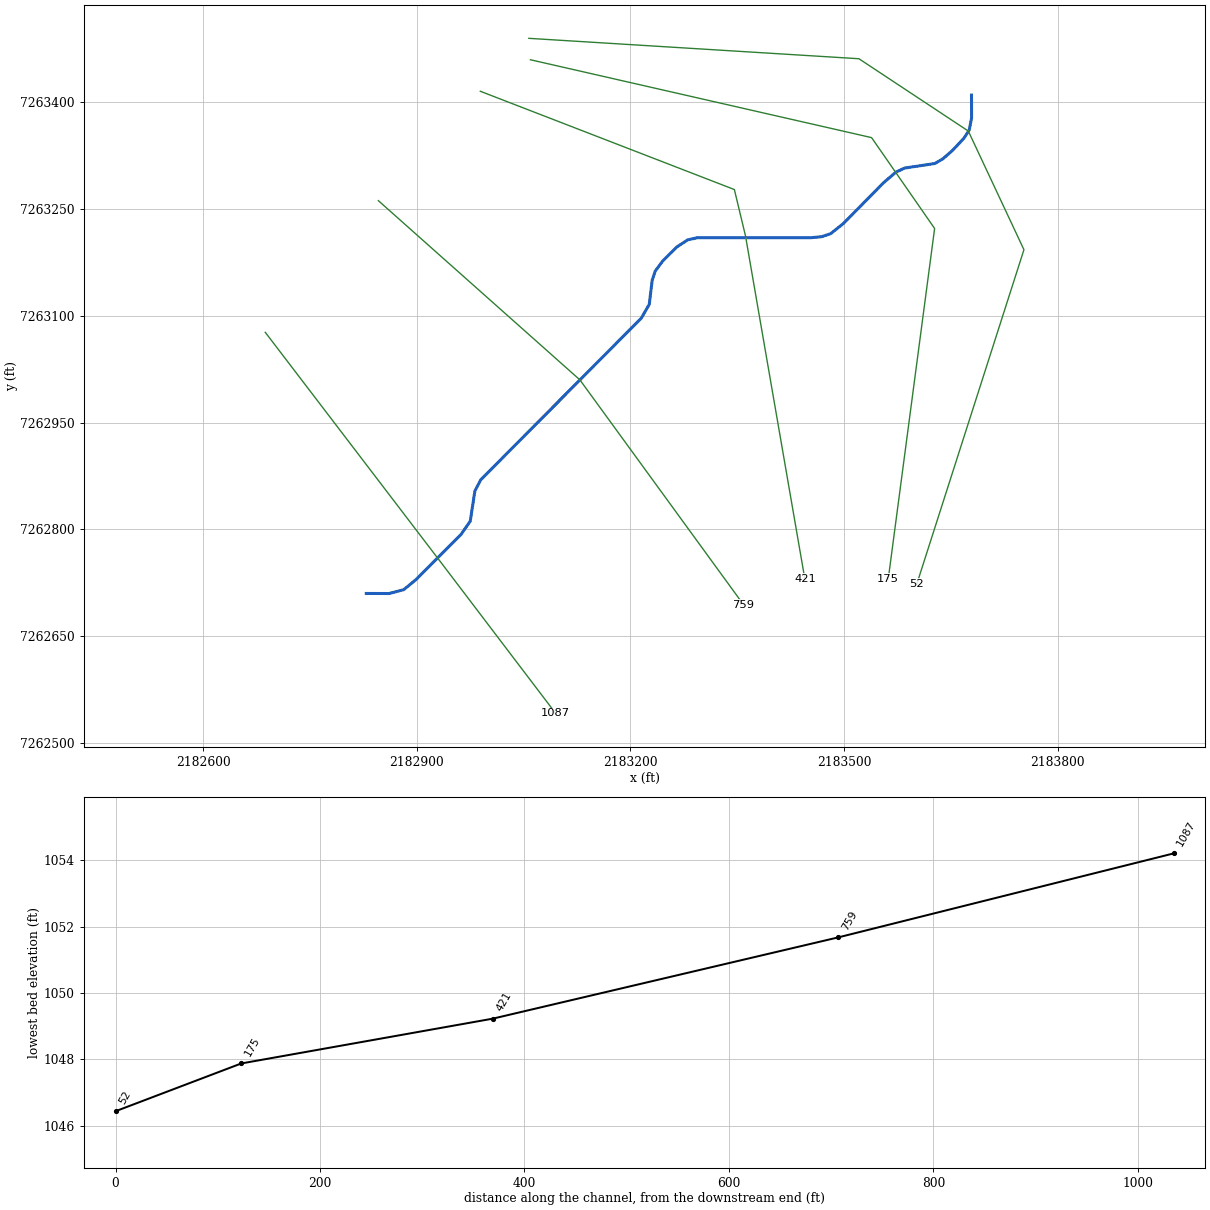
--- Upper Denton 58.prj (project) ---

Proj Title=Upper Denton 58 Base Level Engineering
Current Plan=p01
Default Exp/Contr=0.3,0.1
English Units
Geom File=g01
Flow File=f01
Plan File=p01
Y Axis Title=Elevation
X Axis Title(PF)=Main Channel Distance
X Axis Title(XS)=Station
BEGIN DESCRIPTION:
Upper Denton 58
END DESCRIPTION:
DSS Export Rating Curves= 0
DSS Export Rating Curve Sorted= 0
DSS Export Volume Flow Curves= 0
DXF OffsetX= 0
DXF OffsetY= 0
DXF ScaleX= 1
DXF ScaleY= 10

--- Upper Denton 58.p01 (plan) ---

Plan Title=Multiple Run
Short Identifier=Multiple
Geom File=g01
Flow File=f01
Subcritical Flow
K Sum by GR= 0
Std Step Tol= 0.01
Critical Tol= 0.01
Num of Std Step Trials= 20
Max Error Tol= 0.3
Flow Tol Ratio= 0.001
Split Flow NTrial= 30
Split Flow Tol= 0.02
Split Flow Ratio= 0.02
Log Output Level= 0
Friction Slope Method= 1
Unsteady Friction Slope Method= 2
Unsteady Bridges Friction Slope Method= 1
Parabolic Critical Depth
Global Vel Dist=  1 , 1 , 1
Global Log Level= 0
CheckData=True
Encroach Param= -1, 0, 0, 0
BEGIN DESCRIPTION:
Multiple Run
END DESCRIPTION:

--- Upper Denton 58.f01 (steady flow) ---

Flow Title=Multiple
Program Version=4.10
Number of Profiles= 7
Profile Names=10-year,25-year,50-year,1pct_min,100-year,1pct_plu,500-year
River Rch & RM=Upper Denton 58,Reach-1         ,1087
     391     529     640     386     770    1537    1117
Boundary for River Rch & Prof#=Upper Denton 58,Reach-1         , 1
Up Type= 0
Dn Type= 3
Dn Slope=0.01
Boundary for River Rch & Prof#=Upper Denton 58,Reach-1         , 2
Up Type= 0
Dn Type= 3
Dn Slope=0.01
Boundary for River Rch & Prof#=Upper Denton 58,Reach-1         , 3
Up Type= 0
Dn Type= 3
Dn Slope=0.01
Boundary for River Rch & Prof#=Upper Denton 58,Reach-1         , 4
Up Type= 0
Dn Type= 3
Dn Slope=0.01
Boundary for River Rch & Prof#=Upper Denton 58,Reach-1         , 5
Up Type= 0
Dn Type= 3
Dn Slope=0.01
Boundary for River Rch & Prof#=Upper Denton 58,Reach-1         , 6
Up Type= 0
Dn Type= 3
Dn Slope=0.01
Boundary for River Rch & Prof#=Upper Denton 58,Reach-1         , 7
Up Type= 0
Dn Type= 3
Dn Slope=0.01
DSS Import GetInterval= 0
DSS Import GetPeak= 0
DSS Import FillOption= 0

--- Upper Denton 58.g01 (geometry) ---

Geom Title=Existing Conditions

River Reach=Upper Denton 58,Reach-1
Reach XY= 30
      2182829.00      7262710.00      2182860.89      7262709.92
      2182881.54      7262715.30      2182899.14      7262729.76
      2182962.37      7262793.30      2182975.03      7262811.64
      2182981.53      7262853.95      2182989.78      7262869.68
      2183215.36      7263096.80      2183226.45      7263116.09
      2183230.48      7263149.53      2183234.74      7263162.58
      2183245.46      7263177.14      2183265.33      7263196.77
      2183280.25      7263206.55      2183294.03      7263209.67
      2183454.12      7263209.71      2183468.56      7263211.06
      2183481.45      7263215.47      2183499.15      7263229.64
      2183555.56      7263286.93      2183572.97      7263301.83
      2183585.07      7263307.48      2183627.54      7263313.86
      2183638.97      7263320.56      2183652.85      7263332.73
      2183668.68      7263349.75      2183675.86      7263361.03
      2183679.15      7263377.95      2183679.00      7263410.00

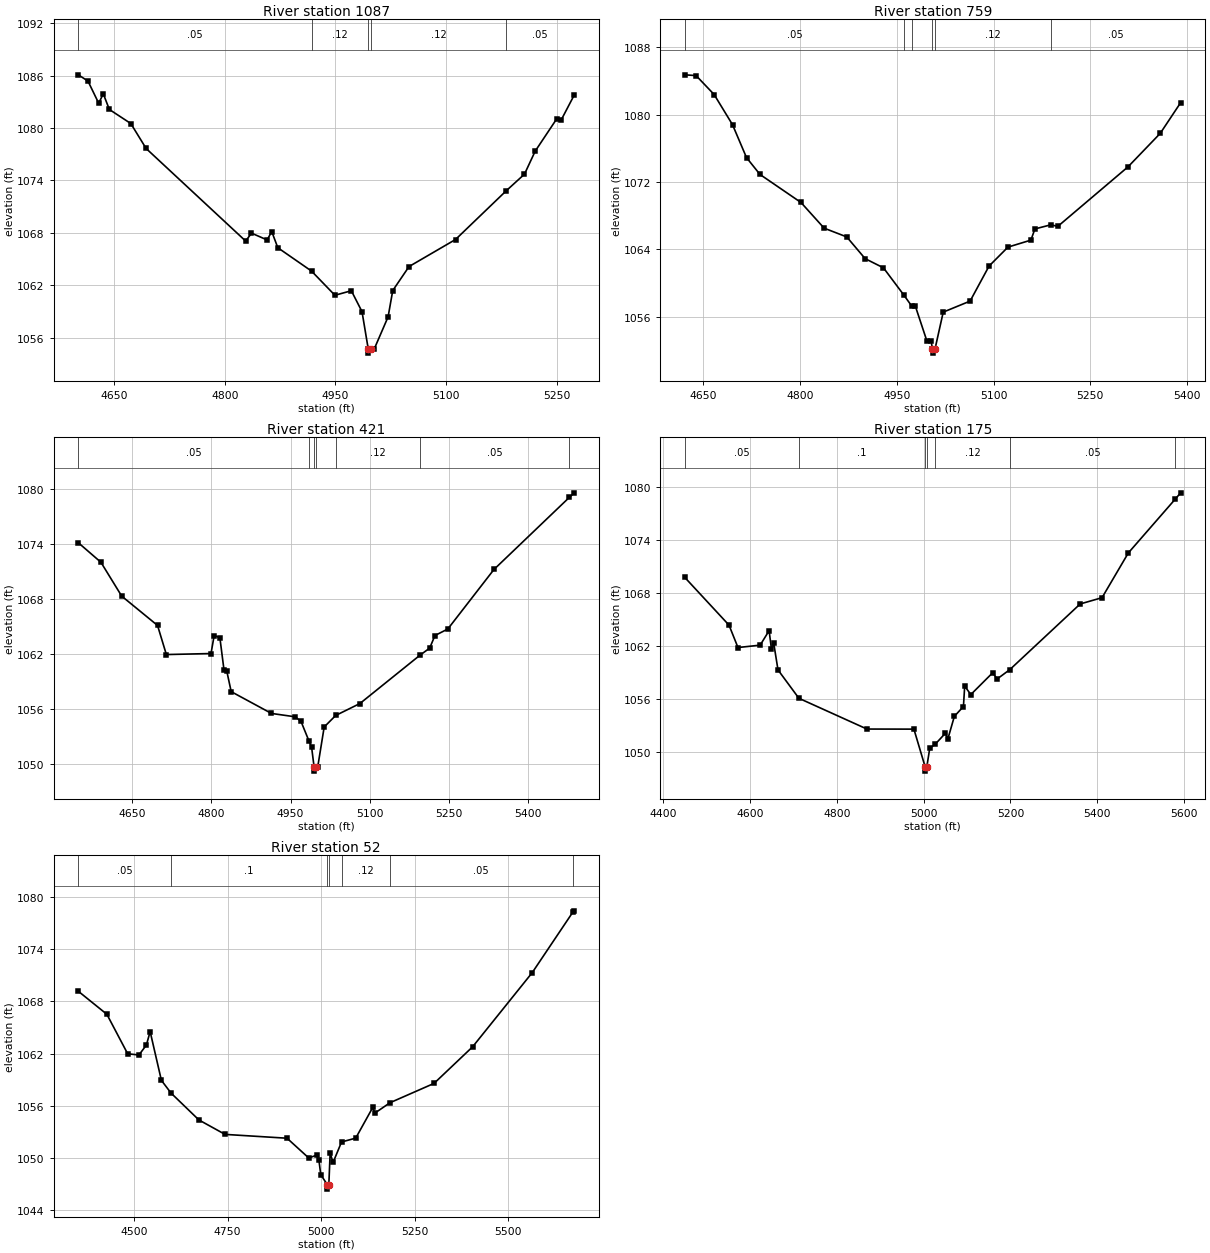
Type RM Length L Ch R = 1,1087,328,328,328
BEGIN DESCRIPTION:
Upper Denton 58 3.0
END DESCRIPTION:
XS GIS Cut Line= 3
      2182687.13      7263076.78      2182929.00      7262760.00
      2183095.01      7262541.59
#Sta/Elev= 30
  4601.0 1086.10  4614.1 1085.38  4628.6 1082.85  4634.9 1083.92  4643.1 1082.13
  4672.2 1080.52  4693.0 1077.66  4828.1 1067.05  4836.0 1067.96  4857.2 1067.18
  4863.5 1068.14  4871.7 1066.29  4917.5 1063.61  4949.2 1060.84  4971.5 1061.36
  4986.0 1058.96  4994.4 1054.71  4994.7 1054.21  4998.4 1054.71  5002.7 1054.71
  5021.4 1058.37  5027.7 1061.38  5049.8 1064.13  5112.9 1067.23  5181.8 1072.82
  5206.5 1074.72  5221.0 1077.35  5250.1 1081.04  5256.4 1080.94  5273.9 1083.77
#Mann=5,-1,0
  4601.0    0.05       0  4917.5    0.12       0  4994.4    0.07       0
  4998.4    0.12       0  5181.8    0.05       0
Bank Sta=4994.4,4998.4
Exp/Cntr=0.3,0.1

Type RM Length L Ch R = 1,759,338,338,338
BEGIN DESCRIPTION:
Upper Denton 58 2.0
END DESCRIPTION:
XS GIS Cut Line= 3
      2182845.96      7263261.70      2183129.00      7263010.00
      2183358.63      7262694.48
#Sta/Elev= 30
  4621.2 1084.73  4638.7 1084.64  4666.7 1082.39  4695.2 1078.81  4716.9 1074.90
  4737.8 1072.90  4801.4 1069.57  4837.3 1066.52  4872.4 1065.48  4900.9 1062.90
  4929.3 1061.81  4961.0 1058.57  4973.4 1057.24  4978.6 1057.30  4996.6 1053.14
  5003.1 1053.14  5005.3 1052.18  5005.6 1051.68  5009.3 1052.18  5022.0 1056.55
  5063.7 1057.86  5093.1 1062.02  5122.4 1064.27  5158.0 1065.10  5164.2 1066.43
  5189.0 1066.92  5199.7 1066.73  5308.7 1073.81  5358.6 1077.78  5390.2 1081.42
#Mann=6,-1,0
  4621.2    0.05       0  4961.0     0.1       0  4973.4    0.12       0
  5005.3    0.07       0  5009.3    0.12       0  5189.0    0.05       0
Bank Sta=5005.3,5009.3
Exp/Cntr=0.3,0.1

Type RM Length L Ch R = 1,421,246,246,246
BEGIN DESCRIPTION:
Upper Denton 58 1.0
END DESCRIPTION:
XS GIS Cut Line= 4
      2182989.18      7263415.34      2183345.97      7263277.31
      2183361.60      7263212.20      2183444.93      7262730.47
#Sta/Elev= 30
  4548.4 1074.17  4591.1 1072.04  4630.5 1068.34  4698.3 1065.14  4715.0 1061.96
  4799.5 1062.07  4805.5 1064.04  4816.3 1063.80  4824.1 1060.27  4829.4 1060.14
  4837.7 1057.91  4913.9 1055.53  4959.0 1055.16  4969.9 1054.65  4984.7 1052.55
  4989.9 1051.84  4994.5 1049.73  4994.7 1049.23  4998.5 1049.73  5001.6 1049.73
  5013.7 1054.05  5035.5 1055.31  5081.3 1056.61  5195.0 1061.89  5213.3 1062.66
  5223.4 1064.04  5247.7 1064.75  5335.0 1071.25  5477.8 1079.13  5486.8 1079.62
#Mann=7,-1,0
  4548.4    0.05       0  4984.7     0.1       0  4994.5    0.07       0
  4998.5     0.1       0  5035.5    0.12       0  5195.0    0.05       0
  5477.8    0.12       0
Bank Sta=4994.5,4998.5
Exp/Cntr=0.3,0.1

Type RM Length L Ch R = 1,175,123,123,123
BEGIN DESCRIPTION:
Upper Denton 58 0.5
END DESCRIPTION:
XS GIS Cut Line= 4
      2183059.52      7263459.60      2183538.68      7263350.23
      2183627.22      7263222.62      2183562.12      7262730.41
#Sta/Elev= 30
  4449.2 1069.79  4551.2 1064.39  4571.8 1061.86  4623.0 1062.13  4643.6 1063.77
  4649.1 1061.65  4654.3 1062.33  4664.1 1059.33  4712.3 1056.12  4869.2 1052.64
  4977.5 1052.63  5003.3 1048.38  5003.5 1047.88  5007.3 1048.38  5014.0 1050.46
  5026.9 1050.94  5049.8 1052.15  5055.9 1051.54  5070.8 1054.08  5091.7 1055.19
  5094.6 1057.50  5108.7 1056.54  5159.2 1059.01  5169.3 1058.30  5198.6 1059.36
  5360.9 1066.79  5411.3 1067.50  5471.9 1072.56  5580.3 1078.66  5592.5 1079.36
#Mann=7,-1,0
  4449.2    0.05       0  4712.3     0.1       0  5003.3    0.07       0
  5007.3     0.1       0  5026.9    0.12       0  5198.6    0.05       0
  5580.3    0.12       0
Bank Sta=5003.3,5007.3
Exp/Cntr=0.3,0.1

Type RM Length L Ch R = 1,52,0,0,0
BEGIN DESCRIPTION:
Upper Denton 58 0.4
END DESCRIPTION:
XS GIS Cut Line= 5
      2183057.34      7263489.68      2183520.90      7263461.03
      2183674.54      7263359.47      2183752.67      7263192.80
      2183602.19      7262723.21
#Sta/Elev= 30
  4350.8 1069.14  4427.1 1066.50  4482.7 1061.97  4512.8 1061.83  4532.8 1062.97
  4542.8 1064.52  4572.9 1058.92  4598.7 1057.46  4673.1 1054.38  4743.2 1052.72
  4908.9 1052.28  4967.0 1050.01  4988.1 1050.34  4994.1 1049.75  4999.1 1048.10
  5016.6 1046.94  5016.8 1046.44  5020.6 1046.94  5024.1 1050.56  5032.0 1049.50
  5054.6 1051.85  5092.5 1052.29  5138.2 1055.82  5143.7 1055.16  5184.0 1056.35
  5301.9 1058.57  5405.1 1062.77  5564.5 1071.28  5672.6 1078.19  5676.6 1078.37
#Mann=7,-1,0
  4350.8    0.05       0  4598.7     0.1       0  5016.6    0.07       0
  5020.6     0.1       0  5054.6    0.12       0  5184.0    0.05       0
  5672.6    0.12       0
Bank Sta=5016.6,5020.6
Exp/Cntr=0.3,0.1

Chan Stop Cuts=-1