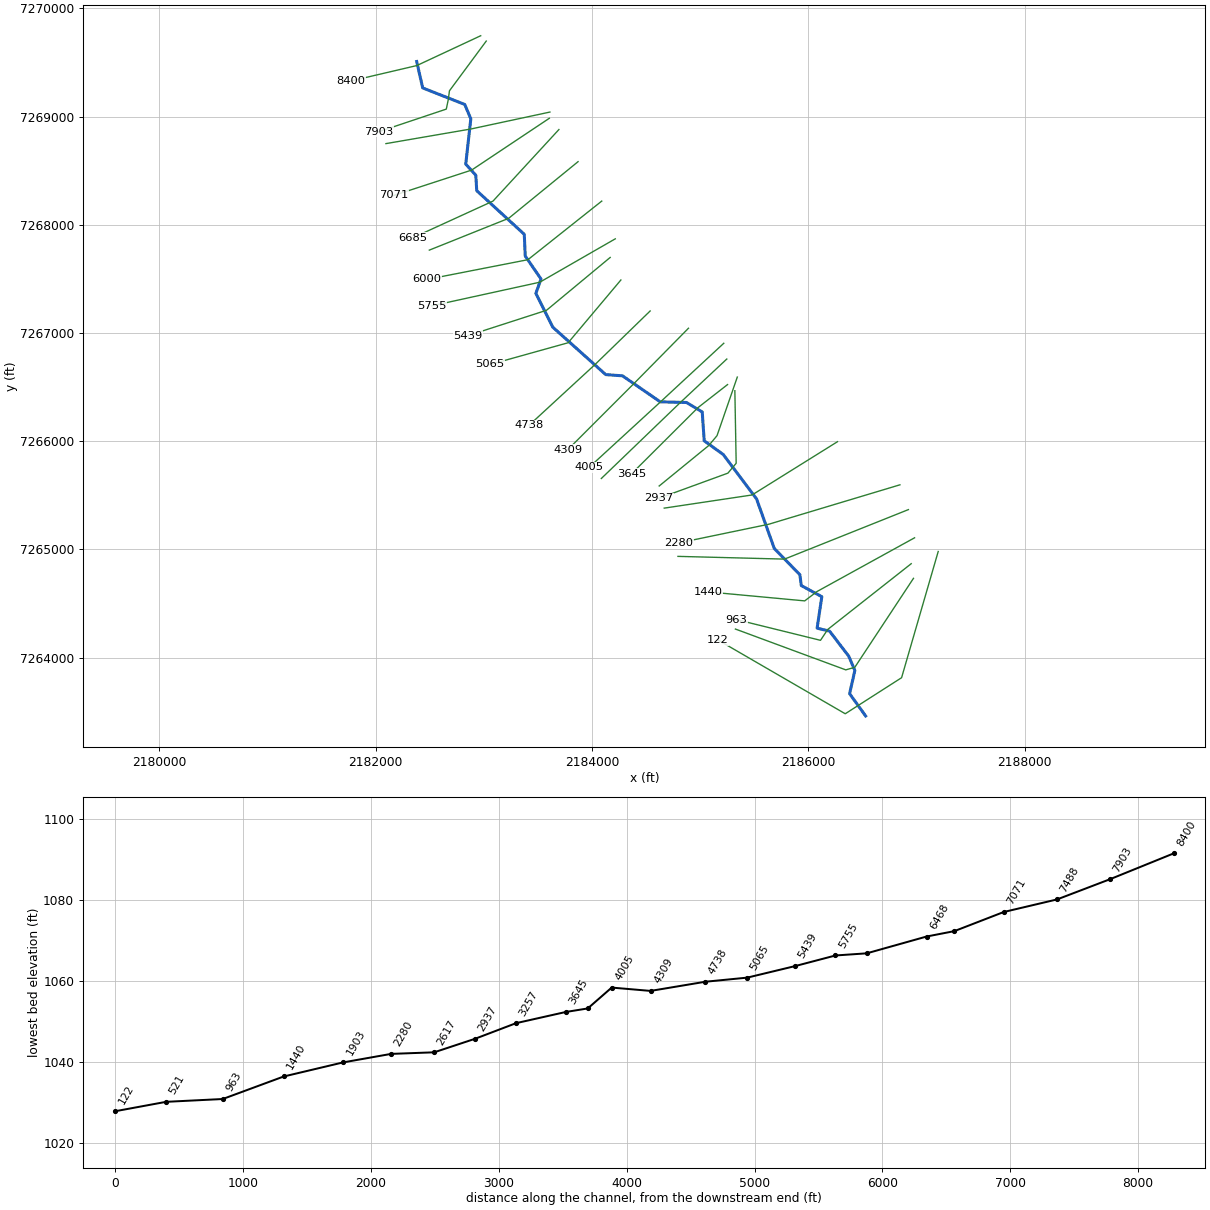
--- Upper Denton 59.prj (project) ---

Proj Title=Upper Denton 59 Base Level Engineering
Current Plan=p01
Default Exp/Contr=0.3,0.1
English Units
Geom File=g01
Flow File=f01
Plan File=p01
Y Axis Title=Elevation
X Axis Title(PF)=Main Channel Distance
X Axis Title(XS)=Station
BEGIN DESCRIPTION:
Upper Denton 59
END DESCRIPTION:
DSS Export Rating Curves= 0
DSS Export Rating Curve Sorted= 0
DSS Export Volume Flow Curves= 0
DXF OffsetX= 0
DXF OffsetY= 0
DXF ScaleX= 1
DXF ScaleY= 10

--- Upper Denton 59.p01 (plan) ---

Plan Title=Multiple Run
Short Identifier=Multiple
Geom File=g01
Flow File=f01
Subcritical Flow
K Sum by GR= 0
Std Step Tol= 0.01
Critical Tol= 0.01
Num of Std Step Trials= 20
Max Error Tol= 0.3
Flow Tol Ratio= 0.001
Split Flow NTrial= 30
Split Flow Tol= 0.02
Split Flow Ratio= 0.02
Log Output Level= 0
Friction Slope Method= 1
Unsteady Friction Slope Method= 2
Unsteady Bridges Friction Slope Method= 1
Parabolic Critical Depth
Global Vel Dist=  1 , 1 , 1
Global Log Level= 0
CheckData=True
Encroach Param= -1, 0, 0, 0
BEGIN DESCRIPTION:
Multiple Run
END DESCRIPTION:

--- Upper Denton 59.f01 (steady flow) ---

Flow Title=Multiple
Number of Profiles=7
Profile Names=10-year,25-year,50-year,1pct_min,100-year,1pct_plu,500-year
River Rch & RM= Upper Denton 59,Reach-1,8400
     484     659     802     485     968    1932    1414
River Rch & RM= Upper Denton 59,Reach-1,2617
     795    1115    1384     852    1699    3391    2573
Boundary for River Rch & Prof#=Upper Denton 59,Reach-1,1
Up Type=0
Dn Type=3
Dn Slope=0.005
Boundary for River Rch & Prof#=Upper Denton 59,Reach-1,2
Up Type=0
Dn Type=3
Dn Slope=0.005
Boundary for River Rch & Prof#=Upper Denton 59,Reach-1,3
Up Type=0
Dn Type=3
Dn Slope=0.005
Boundary for River Rch & Prof#=Upper Denton 59,Reach-1,4
Up Type=0
Dn Type=3
Dn Slope=0.005
Boundary for River Rch & Prof#=Upper Denton 59,Reach-1,5
Up Type=0
Dn Type=3
Dn Slope=0.005
Boundary for River Rch & Prof#=Upper Denton 59,Reach-1,6
Up Type=0
Dn Type=3
Dn Slope=0.005
Boundary for River Rch & Prof#=Upper Denton 59,Reach-1,7
Up Type=0
Dn Type=3
Dn Slope=0.005

--- Upper Denton 59.g01 (geometry) ---

Geom Title=Existing Conditions
Program Version=4.10

River Reach=Upper Denton 59 ,Reach-1
Reach XY= 30
        2182379.        7269510.      2182434.59      7269265.61
      2182823.29      7269112.59      2182879.36      7268980.15
      2182832.54      7268561.47      2182925.44      7268458.52
      2182934.19      7268315.44      2183373.54      7267912.47
      2183382.55      7267711.47      2183528.25      7267499.31
       2183480.8      7267366.11      2183637.14      7267053.94
      2184126.56      7266615.48      2184281.35      7266604.29
      2184630.55      7266363.75      2184873.07      7266357.76
      2185018.66      7266270.12       2185036.8      7266003.79
       2185212.5      7265877.05      2185520.86      7265466.05
      2185684.83       7265007.7      2185921.12      7264766.12
      2185934.25      7264665.44      2186124.01      7264562.55
       2186080.5      7264271.53       2186196.1      7264243.69
      2186373.17       7264012.3       2186429.4      7263880.14
       2186380.8      7263666.11        2186529.        7263460.

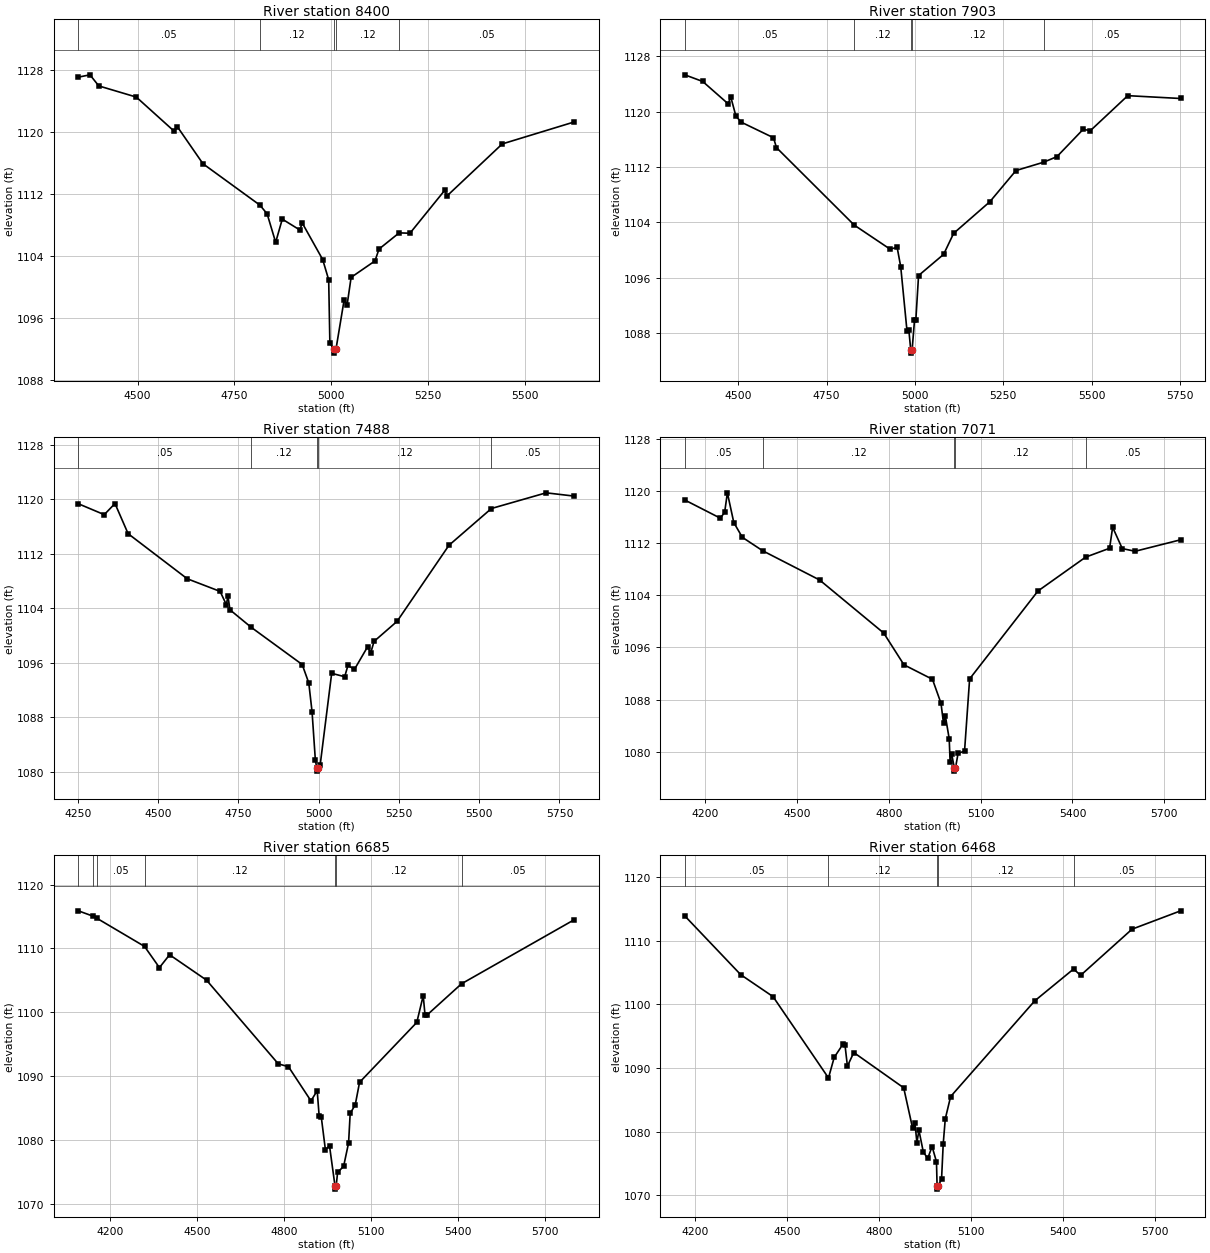
Type RM Length L Ch R = 1 ,8400    ,497,497,497
BEGIN DESCRIPTION:
Upper Denton 59 21.0
END DESCRIPTION:
XS GIS Cut Line= 3
       2182970.6      7269747.93      2182380.28       7269472.3
      2181768.31      7269329.08
#Sta/Elev= 30
  4347.1 1127.05  4377.1 1127.35  4399.9 1125.92  4496.8 1124.48  4593.8 1120.11
  4602.7 1120.66  4668.9 1115.88    4816 1110.54  4834.5 1109.42  4856.5 1105.75
  4873.6 1108.74  4919.3 1107.33  4924.8 1108.27  4977.9 1103.53  4993.4 1100.92
  4996.5 1092.72  5008.2 1091.96  5008.4 1091.46  5012.2 1091.96  5033.2  1098.3
    5041 1097.69  5051.3 1101.23  5112.9 1103.35  5123.3 1104.88  5175.4 1106.97
  5203.2 1106.92  5293.3 1112.48  5298.4 1111.71  5441.5 1118.44  5627.1 1121.27
#Mann= 5 ,-1 , 0
  4347.1     .05       0    4816     .12       0  5008.2     .07       0
  5012.2     .12       0  5175.4     .05       0
Bank Sta=5008.2,5012.2
XS Rating Curve= 0 ,0
Exp/Cntr=0.3,0.1

Type RM Length L Ch R = 1 ,7903    ,415,415,415
BEGIN DESCRIPTION:
Upper Denton 59 20.0
END DESCRIPTION:
XS GIS Cut Line= 5
      2183021.97      7269698.63      2182681.93      7269239.01
      2182671.08      7269157.63      2182652.63      7269069.74
      2182027.17       7268860.1
#Sta/Elev= 30
  4348.5 1125.32  4399.2 1124.36  4471.2 1121.13  4478.5 1122.14  4493.1 1119.37
  4507.8 1118.49  4599.5 1116.23    4608  1114.8    4828 1103.61  4929.3 1100.14
  4949.5 1100.39  4959.6  1097.6  4977.5 1088.25  4982.5 1088.49  4987.9 1085.61
  4988.1 1085.11  4991.9 1085.61  4998.6 1089.83  5002.3 1089.83  5010.1 1096.32
    5081 1099.38  5109.4 1102.42    5212 1106.99  5285.8 1111.49  5363.8 1112.69
  5401.8  1113.5  5475.7 1117.43  5496.7 1117.27  5602.2 1122.31  5751.8  1121.9
#Mann= 5 ,-1 , 0
  4348.5     .05       0    4828     .12       0  4987.9     .07       0
  4991.9     .12       0  5363.8     .05       0
Bank Sta=4987.9,4991.9
XS Rating Curve= 0 ,0
Exp/Cntr=0.3,0.1

Type RM Length L Ch R = 1 ,7488    ,417,417,417
BEGIN DESCRIPTION:
Upper Denton 59 19.0
END DESCRIPTION:
XS GIS Cut Line= 3
      2183610.57      7269042.41      2182881.36      7268886.15
       2182094.9      7268750.73
#Sta/Elev= 30
  4251.9 1119.32  4332.6 1117.72    4366 1119.35  4406.9 1114.93    4591 1108.32
  4693.3 1106.47  4712.7 1104.53  4717.8 1105.79    4724 1103.77    4790 1101.21
  4948.9 1095.75  4969.4 1093.05  4979.6 1088.84  4989.9 1081.74  4994.3 1080.62
  4994.6 1080.12  4998.3 1080.62  5004.8 1080.99  5040.7 1094.46  5081.2 1093.96
  5091.4 1095.62  5111.7 1095.04  5152.3 1098.33  5162.4 1097.47  5172.6 1099.14
  5244.4 1102.08  5405.9 1113.23    5538 1118.62  5708.4 1120.92  5795.7 1120.44
#Mann= 5 ,-1 , 0
  4251.9     .05       0    4790     .12       0  4994.3     .07       0
  4998.3     .12       0    5538     .05       0
Bank Sta=4994.3,4998.3
XS Rating Curve= 0 ,0
Exp/Cntr=0.3,0.1

Type RM Length L Ch R = 1 ,7071    ,386,386,386
BEGIN DESCRIPTION:
Upper Denton 59 18.0
END DESCRIPTION:
XS GIS Cut Line= 3
      2183605.31       7268985.1      2182886.57      7268505.94
      2182167.84      7268271.57
#Sta/Elev= 30
  4133.5 1118.59  4249.3 1115.81  4263.6 1116.68  4272.6 1119.69  4293.6 1115.13
  4321.4 1112.87  4387.8 1110.81  4573.8 1106.33  4783.4 1098.19  4849.5 1093.32
  4942.6  1091.1  4970.4 1087.44  4978.7 1084.35  4984.7 1085.48  4997.3 1081.98
  5000.2 1078.48  5005.4 1079.66  5013.8 1077.52  5014.1 1077.02  5017.8 1077.52
  5026.3 1079.74  5047.4 1080.09    5064 1091.16  5287.3 1104.64    5443 1109.83
  5521.2 1111.19  5531.2 1114.41  5562.7 1111.14  5604.8 1110.73  5753.3 1112.49
#Mann= 5 ,-1 , 0
  4133.5     .05       0  4387.8     .12       0  5013.8     .07       0
  5017.8     .12       0    5443     .05       0
Bank Sta=5013.8,5017.8
XS Rating Curve= 0 ,0
Exp/Cntr=0.3,0.1

Type RM Length L Ch R = 1 ,6685    ,217,217,217
BEGIN DESCRIPTION:
Upper Denton 59 17.0
END DESCRIPTION:
XS GIS Cut Line= 3
      2183693.85      7268880.92      2183084.49      7268219.48
      2182344.93      7267880.95
#Sta/Elev= 30
  4089.4 1115.88  4139.8 1115.05  4153.3 1114.72    4318 1110.31  4369.5 1106.99
  4404.6    1109  4532.2 1105.03  4780.1 1091.92  4815.2 1091.48  4892.9 1086.13
  4914.5 1087.71  4921.3 1083.74  4928.6  1083.6  4942.8 1078.48    4957  1079.1
    4976 1072.81  4976.2 1072.31    4980 1072.81    4985 1074.92  5005.8 1075.89
  5022.9 1079.55  5028.4 1084.16  5045.9 1085.51  5060.8 1089.03  5258.5 1098.41
  5280.7  1102.6    5287 1099.56  5292.5 1099.51  5413.1 1104.46  5802.1 1114.48
#Mann= 7 ,-1 , 0
  4089.4     .05       0  4139.8     .12       0  4153.3     .05       0
    4318     .12       0    4976     .07       0    4980     .12       0
  5413.1     .05       0
Bank Sta=4976,4980
XS Rating Curve= 0 ,0
Exp/Cntr=0.3,0.1

Type RM Length L Ch R = 1 ,6468    ,468,468,468
BEGIN DESCRIPTION:
Upper Denton 59 16.0
END DESCRIPTION:
XS GIS Cut Line= 3
      2183870.95      7268584.07        2183229.        7268060.
      2182495.93      7267766.35
#Sta/Elev= 30
  4166.7 1113.86  4349.2 1104.64  4454.8 1101.19  4635.7 1088.43  4654.4 1091.66
  4683.1 1093.74  4689.5 1093.63  4697.5 1090.28  4718.3 1092.42  4881.2 1086.88
    4910  1080.6  4917.9 1081.32  4924.3 1078.28  4930.9 1080.22  4945.1 1076.83
  4959.5 1075.79  4973.9 1077.67  4988.2 1075.27  4990.2 1071.48  4990.4 1070.98
  4994.2 1071.48  5004.8  1072.6  5010.2 1078.09  5016.9 1082.01  5034.4 1085.51
  5308.9 1100.53  5435.8 1105.53  5458.6 1104.53  5626.5 1111.78  5785.1 1114.66
#Mann= 5 ,-1 , 0
  4166.7     .05       0  4635.7     .12       0  4990.2     .07       0
  4994.2     .12       0  5435.8     .05       0
Bank Sta=4990.2,4994.2
XS Rating Curve= 0 ,0
Exp/Cntr=0.3,0.1

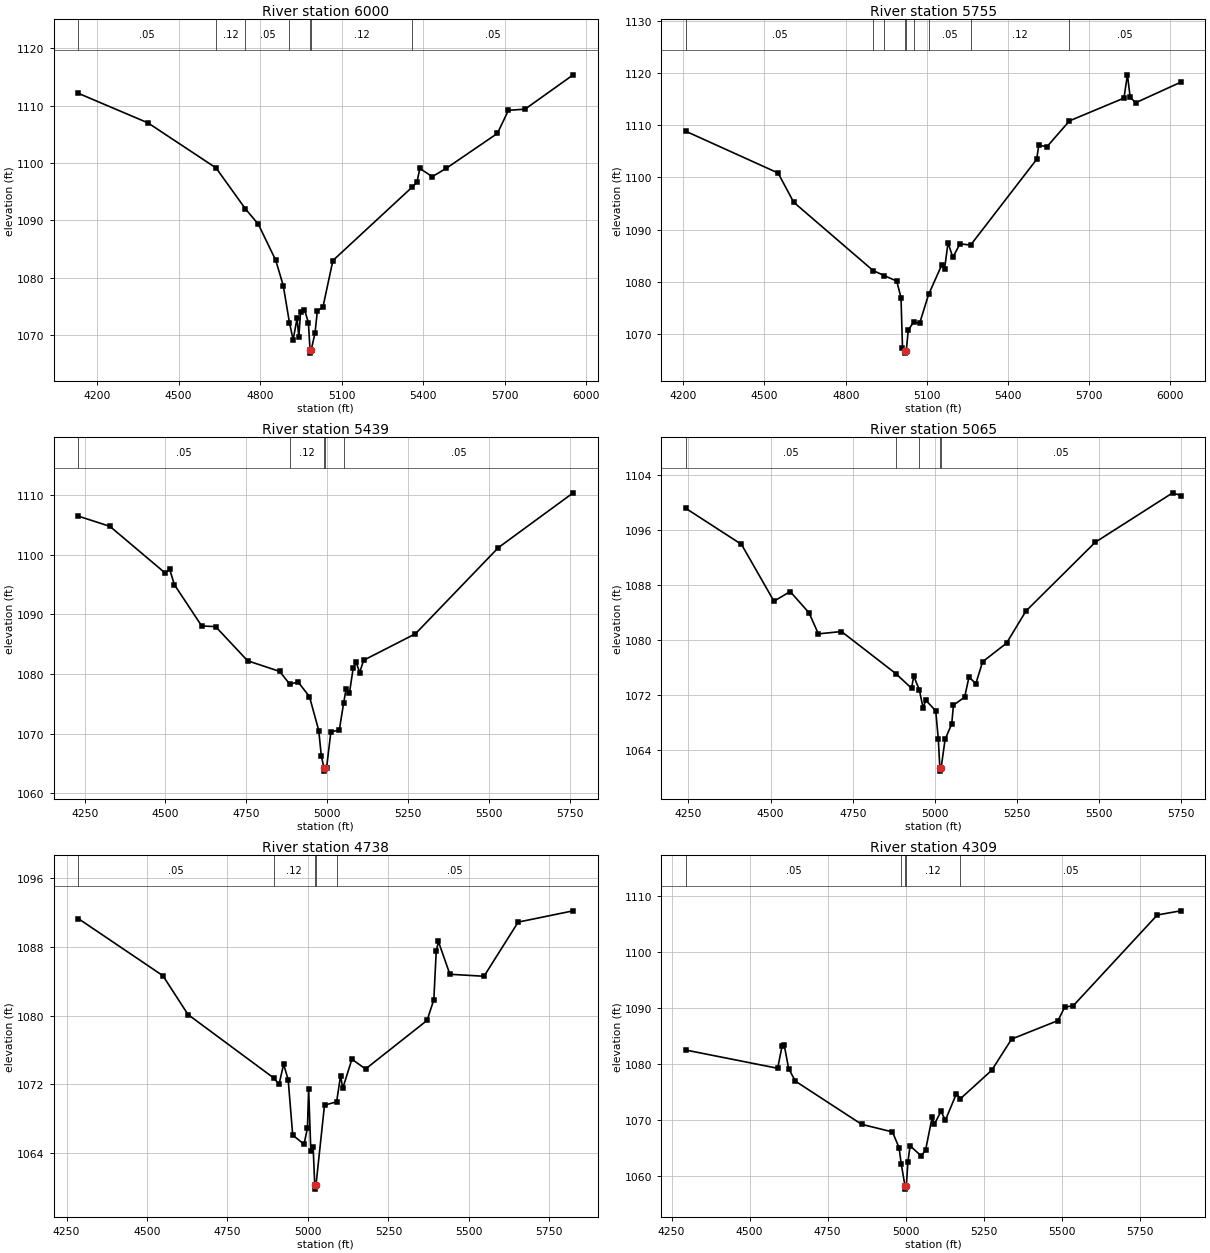
Type RM Length L Ch R = 1 ,6000    ,245,245,245
BEGIN DESCRIPTION:
Upper Denton 59 15.0
END DESCRIPTION:
XS GIS Cut Line= 3
      2184089.71      7268219.49      2183407.41      7267677.81
      2182475.14      7267495.53
#Sta/Elev= 30
  4131.1 1112.16  4387.4    1107    4638 1099.14    4746 1092.01  4793.6 1089.32
  4857.7 1083.03  4885.3 1078.62  4908.2 1072.13  4921.8 1069.18  4936.2 1072.92
  4942.6 1069.61  4949.2  1074.1  4963.4 1074.43  4977.9 1072.15  4983.9 1067.34
  4984.2 1066.84  4987.9 1067.34  5002.3 1070.37  5010.8 1074.22  5031.2 1074.84
    5068 1082.99  5358.6 1095.75  5377.1 1096.63  5387.9 1099.05  5433.8 1097.62
  5485.3 1099.08  5673.2 1105.16  5713.9 1109.19    5775 1109.39  5952.2 1115.38
#Mann= 7 ,-1 , 0
  4131.1     .05       0    4638     .12       0    4746     .05       0
  4908.2     .12       0  4983.9     .07       0  4987.9     .12       0
  5358.6     .05       0
Bank Sta=4983.9,4987.9
XS Rating Curve= 0 ,0
Exp/Cntr=0.3,0.1

Type RM Length L Ch R = 1 ,5755    ,316,316,316
BEGIN DESCRIPTION:
Upper Denton 59 14.0
END DESCRIPTION:
XS GIS Cut Line= 3
      2184214.73      7267870.54      2183516.78      7267469.48
       2182516.8      7267250.74
#Sta/Elev= 30
  4209.1 1108.86  4550.2 1100.85  4607.8 1095.25  4901.3 1082.14  4942.2 1081.19
  4988.6 1080.12  5004.4 1076.95  5009.9 1067.34    5020 1066.81  5020.3 1066.31
    5024 1066.81  5031.1  1070.7  5050.6 1072.25  5073.2 1072.03  5106.4 1077.57
  5155.1 1083.23  5165.4 1082.48  5178.1 1087.47  5196.1 1084.65  5221.9 1087.27
  5261.6 1087.03  5505.6 1103.47  5513.4 1106.17  5544.1 1105.92  5626.9 1110.85
  5828.1 1115.22    5841 1119.68  5851.2 1115.35  5871.7 1114.33  6037.7 1118.26
#Mann= 9 ,-1 , 0
  4209.1     .05       0  4901.3     .12       0  4942.2     .05       0
    5020    .033       0    5024     .05       0  5050.6     .12       0
  5106.4     .05       0  5261.6     .12       0  5626.9     .05       0
Bank Sta=5020,5024
XS Rating Curve= 0 ,0
Exp/Cntr=0.3,0.1

Type RM Length L Ch R = 1 ,5439    ,374,374,374
BEGIN DESCRIPTION:
Upper Denton 59 13.0
END DESCRIPTION:
XS GIS Cut Line= 3
      2184167.81      7267698.64        2183579.        7267210.
      2182850.58      7266974.84
#Sta/Elev= 30
  4230.3 1106.51  4328.1 1104.79  4498.7 1096.97    4513 1097.58  4527.3 1095.01
    4612 1088.06  4654.9 1087.96  4753.9 1082.22  4852.9 1080.44  4884.4 1078.29
  4910.2 1078.65  4945.3  1076.2    4974  1070.5  4981.8 1066.28  4990.2 1064.19
  4990.5 1063.69  4994.2 1064.19  4998.1 1064.19  5011.5  1070.3  5037.5 1070.57
  5050.8 1075.07  5058.5 1077.47    5069 1076.84  5080.8 1081.09    5090 1081.93
  5100.5 1080.24  5112.8 1082.31    5273 1086.75  5529.3 1101.21  5760.9 1110.42
#Mann= 5 ,-1 , 0
  4230.3     .05       0  4884.4     .12       0  4990.2     .07       0
  4994.2     .12       0  5050.8     .05       0
Bank Sta=4990.2,4994.2
XS Rating Curve= 0 ,0
Exp/Cntr=0.3,0.1

Type RM Length L Ch R = 1 ,5065    ,327,327,327
BEGIN DESCRIPTION:
Upper Denton 59 12.0
END DESCRIPTION:
XS GIS Cut Line= 3
      2184266.79      7267490.32        2183779.        7266910.
      2183058.49      7266709.07
#Sta/Elev= 30
  4241.9  1099.2  4411.4 1093.94  4510.3 1085.65  4559.7 1087.05  4616.9 1083.96
  4645.5 1080.88  4715.8 1081.22  4881.4 1075.07  4929.1 1072.94  4935.6 1074.72
  4952.5 1072.74  4964.2 1070.07    4972 1071.22  5002.6 1069.65  5010.4 1065.55
  5015.1 1061.35  5015.3 1060.85  5019.1 1061.35  5031.1 1065.48  5051.3 1067.74
  5056.5 1070.47  5090.7 1071.66  5103.8 1074.58  5124.6 1073.61  5145.3 1076.81
    5218 1079.52  5277.2 1084.21  5487.9 1094.24  5723.7 1101.46    5748 1101.06
#Mann= 5 ,-1 , 0
  4241.9     .05       0  4881.4     .12       0  4952.5     .05       0
  5015.1    .033       0  5019.1     .05       0
Bank Sta=5015.1,5019.1
XS Rating Curve= 0 ,0
Exp/Cntr=0.3,0.1

Type RM Length L Ch R = 1 ,4738    ,429,429,429
BEGIN DESCRIPTION:
Upper Denton 59 11.0
END DESCRIPTION:
XS GIS Cut Line= 3
      2184537.17      7267203.79        2184029.        7266710.
      2183419.15      7266148.27
#Sta/Elev= 30
  4286.5 1091.27  4549.5 1084.63  4627.4 1080.12  4893.1 1072.77  4910.3 1072.03
  4924.4 1074.33  4938.6 1072.57  4952.7 1066.12    4988 1065.05  4998.5 1066.95
  5002.2 1071.44    5009 1064.31  5016.3 1064.69  5021.1 1060.34  5021.4 1059.84
  5025.1 1060.34  5051.5  1069.6  5089.2 1069.98  5101.4 1073.02  5108.2 1071.55
  5136.6 1074.93  5179.1  1073.8  5370.2 1079.44  5391.2 1081.85  5398.6 1087.46
  5405.4 1088.61  5441.1  1084.8  5547.1 1084.57  5653.2 1090.86  5824.2 1092.17
#Mann= 5 ,-1 , 0
  4286.5     .05       0  4893.1     .12       0  5021.1     .07       0
  5025.1     .12       0  5089.2     .05       0
Bank Sta=5021.1,5025.1
XS Rating Curve= 0 ,0
Exp/Cntr=0.3,0.1

Type RM Length L Ch R = 1 ,4309    ,304,304,304
BEGIN DESCRIPTION:
Upper Denton 59 10.0
END DESCRIPTION:
XS GIS Cut Line= 3
      2184891.33      7267044.06      2184405.24      7266551.02
      2183773.62      7265919.41
#Sta/Elev= 30
  4295.5 1082.42  4589.9 1079.16  4604.1 1083.14  4611.1 1083.25  4625.2 1079.11
  4646.5 1076.87  4858.7 1069.16  4957.7 1067.79  4978.8 1064.99  4985.8 1062.09
  4998.1 1058.08  4998.3 1057.58  5002.1 1058.08  5007.1  1062.4  5014.2 1065.32
  5049.6 1063.52  5063.7 1064.52  5084.9 1070.41    5092 1069.18  5113.2 1071.47
  5127.3 1069.89  5162.7 1074.63  5175.5 1073.73  5275.8 1078.81  5339.5 1084.38
    5488 1087.68  5509.2 1090.05  5537.5 1090.36  5806.2 1106.54  5881.1 1107.28
#Mann= 5 ,-1 , 0
  4295.5     .05       0  4985.8     .12       0  4998.1     .07       0
  5002.1     .12       0  5175.5     .05       0
Bank Sta=4998.1,5002.1
XS Rating Curve= 0 ,0
Exp/Cntr=0.3,0.1

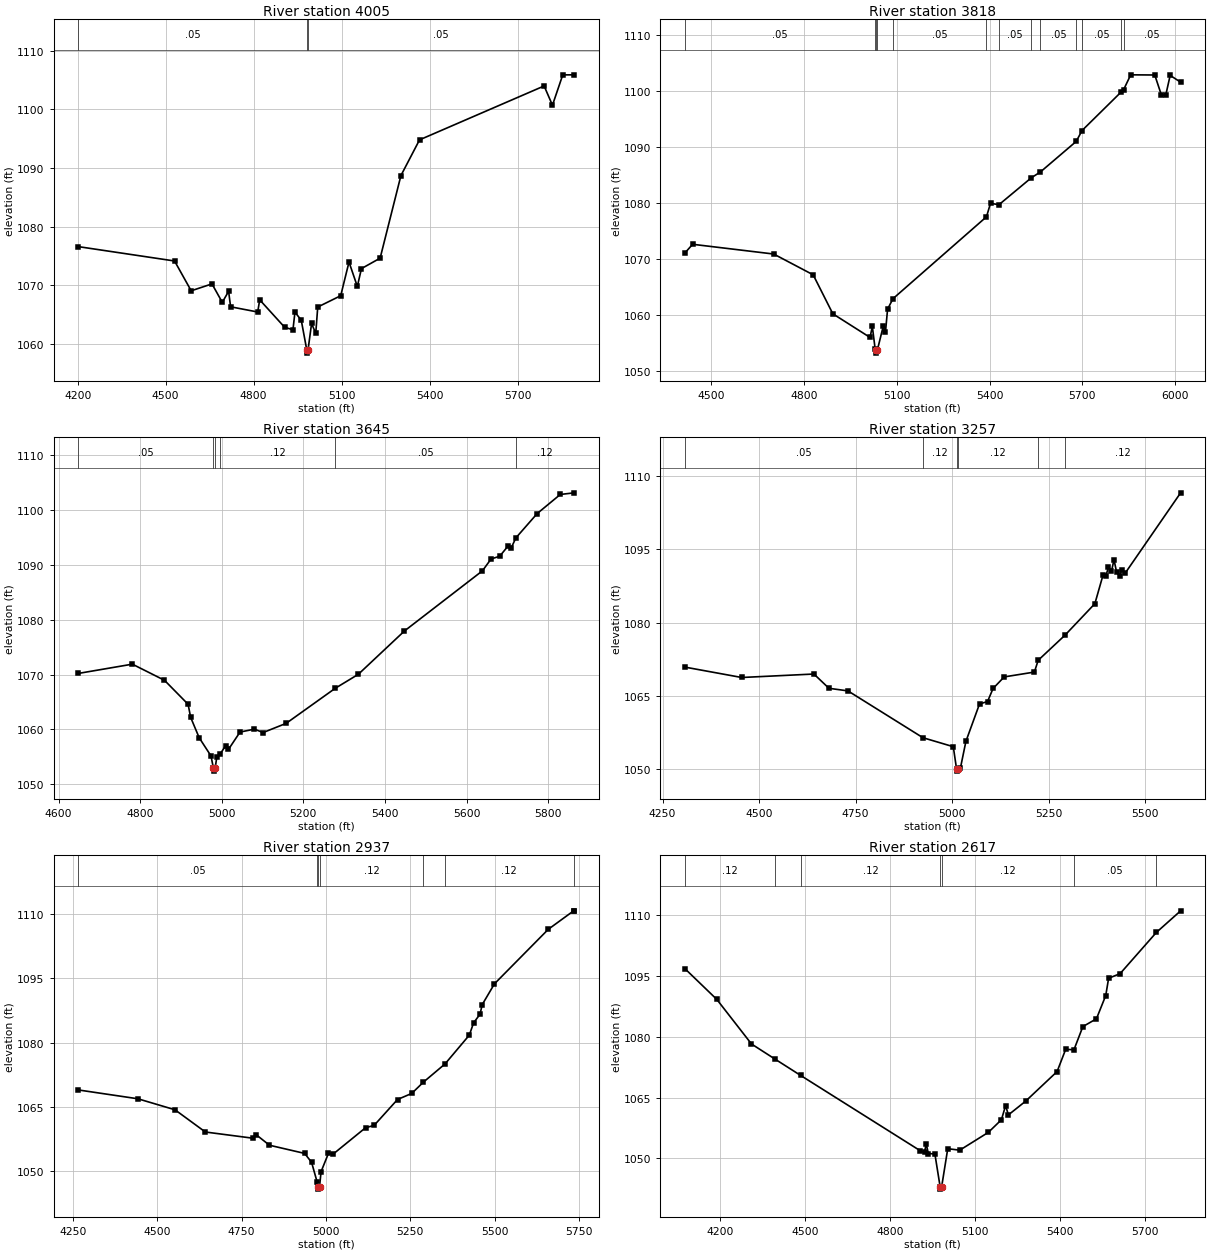
Type RM Length L Ch R = 1 ,4005    ,187,187,187
BEGIN DESCRIPTION:
Upper Denton 59 9.0
END DESCRIPTION:
XS GIS Cut Line= 3
      2185217.73      7266905.18        2184629.        7266360.
      2183974.68      7265759.35
#Sta/Elev= 30
  4202.2 1076.58  4530.3 1074.13    4587 1069.04  4657.9 1070.22    4693 1067.07
  4714.6 1068.95  4721.4 1066.31  4813.8 1065.42  4820.6  1067.5  4905.7 1062.81
    4934 1062.39  4940.8  1065.4  4962.3 1064.02  4981.3  1058.9  4981.6  1058.4
  4985.3  1058.9  4997.5 1063.46  5011.7 1061.77  5018.5 1066.27  5096.8  1068.2
  5125.1 1073.95  5153.5 1069.78  5167.5 1072.83  5231.2 1074.61  5302.1 1088.71
  5365.6 1094.81  5790.4 1104.01  5818.8 1100.72  5853.9  1105.9  5892.8 1105.91
#Mann= 3 ,-1 , 0
  4202.2     .05       0  4981.3    .033       0  4985.3     .05       0
Bank Sta=4981.3,4985.3
XS Rating Curve= 0 ,0
Exp/Cntr=0.3,0.1

Type RM Length L Ch R = 1 ,3818    ,173,173,173
BEGIN DESCRIPTION:
Upper Denton 59 8.5
END DESCRIPTION:
XS GIS Cut Line= 3
      2185245.53      7266759.37      2184814.96      7266356.58
      2184085.83      7265655.22
#Sta/Elev= 30
  4415.9 1071.12  4441.2 1072.69    4703 1070.95  4830.5 1067.24    4894 1060.28
  5014.2 1056.06  5021.5 1058.04  5030.5 1054.06  5033.6 1053.76  5033.9 1053.26
  5037.6 1053.76  5056.7 1058.04  5063.9 1056.96  5070.8 1061.11  5088.3 1062.98
  5390.2  1077.6  5403.2 1080.01  5430.4 1079.75    5535 1084.56  5564.6 1085.61
  5679.9 1091.05  5698.9    1093  5824.7 1099.85  5833.1 1100.29    5856 1102.94
  5933.7 1102.91  5955.1 1099.34  5969.2 1099.32  5983.4 1102.84  6017.2 1101.63
#Mann= 13 ,-1 , 0
  4415.9     .05       0  5030.5     .12       0  5033.6    .033       0
  5037.6     .12       0  5088.3     .05       0  5390.2     .12       0
  5430.4     .05       0    5535     .12       0  5564.6     .05       0
  5679.9     .12       0  5698.9     .05       0  5824.7     .12       0
  5833.1     .05       0
Bank Sta=5033.6,5037.6
XS Rating Curve= 0 ,0
Exp/Cntr=0.3,0.1

Type RM Length L Ch R = 1 ,3645    ,388,388,388
BEGIN DESCRIPTION:
Upper Denton 59 8.0
END DESCRIPTION:
XS GIS Cut Line= 3
      2185252.49      7266523.26        2184979.        7266310.
      2184363.81       7265697.1
#Sta/Elev= 30
  4648.6 1070.21    4781  1071.9  4859.7 1068.96  4917.6 1064.58  4923.9 1062.19
  4944.8 1058.47  4973.7 1055.16  4979.8 1052.88  4980.1 1052.38  4983.8 1052.88
  4988.2 1055.03  4995.8 1055.45  5009.5 1057.01  5016.6 1056.35  5044.9 1059.51
  5080.2 1060.04  5101.5 1059.42    5158  1061.1  5278.5 1067.51  5334.8 1070.05
  5447.9 1077.96  5638.9 1088.93  5660.1 1091.09  5681.3  1091.6  5702.5 1093.52
  5709.6 1093.13    5721 1094.95  5773.2 1099.39  5829.8 1102.87  5863.8 1103.17
#Mann= 6 ,-1 , 0
  4648.6     .05       0  4979.8     .07       0  4983.8     .05       0
  4995.8     .12       0  5278.5     .05       0    5721     .12       0
Bank Sta=4979.8,4983.8
XS Rating Curve= 0 ,0
Exp/Cntr=0.3,0.1

Type RM Length L Ch R = 1 ,3257    ,320,320,320
BEGIN DESCRIPTION:
Upper Denton 59 7.5
END DESCRIPTION:
XS GIS Cut Line= 4
      2185342.72      7266592.65      2185155.24      7266051.02
        2185079.        7265960.      2184620.54      7265585.76
#Sta/Elev= 30
  4307.6 1070.92  4454.9 1068.79  4641.9  1069.5  4680.8 1066.58    4730 1066.05
  4924.1 1056.47  5002.7 1054.63  5011.1 1050.13  5011.4 1049.63  5015.1 1050.13
    5021 1050.18  5035.4 1055.72  5070.6 1063.37  5091.4 1063.87  5105.7 1066.54
  5134.5 1068.91  5212.7  1069.9  5222.5 1072.31  5292.1 1077.46  5369.3  1083.9
  5390.1 1089.67    5398 1089.61  5404.4 1091.37  5412.3 1090.52  5418.8  1092.9
  5425.5 1090.36  5433.2 1089.61  5439.6 1090.85  5447.5 1090.11  5591.3 1106.58
#Mann= 6 ,-1 , 0
  4307.6     .05       0  4924.1     .12       0  5011.1     .07       0
  5015.1     .12       0  5222.5     .05       0  5292.1     .12       0
Bank Sta=5011.1,5015.1
XS Rating Curve= 0 ,0
Exp/Cntr=0.3,0.1

Type RM Length L Ch R = 1 ,2937    ,320,320,320
BEGIN DESCRIPTION:
Upper Denton 59 7.0
END DESCRIPTION:
XS GIS Cut Line= 4
      2185320.17      7266466.48      2185332.32      7265795.81
      2185256.08      7265704.79      2184617.06      7265471.75
#Sta/Elev= 30
  4265.8 1068.95  4442.3 1066.89  4552.3 1064.32  4642.3 1059.13  4782.4 1057.69
  4792.4 1058.53  4832.4 1056.04  4936.6 1054.13  4957.2 1052.05  4973.6 1047.46
  4976.7 1046.29    4977 1045.79  4980.7 1046.29  4985.3 1049.87  5007.3 1054.16
  5021.7 1054.01  5117.2 1060.13  5142.5 1060.67  5211.9 1066.72  5254.1 1068.14
  5288.9 1070.79  5352.8 1075.03  5424.8 1081.76  5437.4 1084.62  5456.7 1086.66
  5462.7 1088.84  5499.3 1093.74  5658.9 1106.47    5734 1110.78  5735.5 1110.78
#Mann= 7 ,-1 , 0
  4265.8     .05       0  4973.6     .12       0  4976.7     .07       0
  4980.7     .12       0  5288.9     .05       0  5352.8     .12       0
    5734     .05       0
Bank Sta=4976.7,4980.7
XS Rating Curve= 0 ,0
Exp/Cntr=0.3,0.1

Type RM Length L Ch R = 1 ,2617    ,337,337,337
BEGIN DESCRIPTION:
Upper Denton 59 6.0
END DESCRIPTION:
XS GIS Cut Line= 3
      2186268.95      7265995.46      2185479.02      7265502.84
      2184667.41      7265381.32
#Sta/Elev= 30
  4074.5 1096.75  4187.6 1089.15  4310.1 1078.18  4392.3  1074.5  4483.7 1070.44
  4906.1 1051.91  4921.4 1051.49  4927.3 1053.63  4934.8 1051.22    4958  1051.1
  4976.7 1042.95  4977.4 1042.45  4981.7 1042.95  5003.4  1052.4  5045.9 1052.04
    5147 1056.43    5193 1059.53  5207.7 1062.98  5217.8 1060.73  5278.5  1064.1
  5389.7 1071.39    5420 1076.86  5449.3 1076.76  5480.7 1082.46  5528.7 1084.38
  5561.6 1090.11  5571.7 1094.36  5612.2 1095.49  5740.4 1105.64  5826.1 1110.96
#Mann= 7 ,-1 , 0
  4074.5     .12       0  4392.3     .05       0  4483.7     .12       0
  4976.7     .07       0  4981.7     .12       0  5449.3     .05       0
  5740.4     .12       0
Bank Sta=4976.7,4981.7
XS Rating Curve= 0 ,0
Exp/Cntr=0.3,0.1

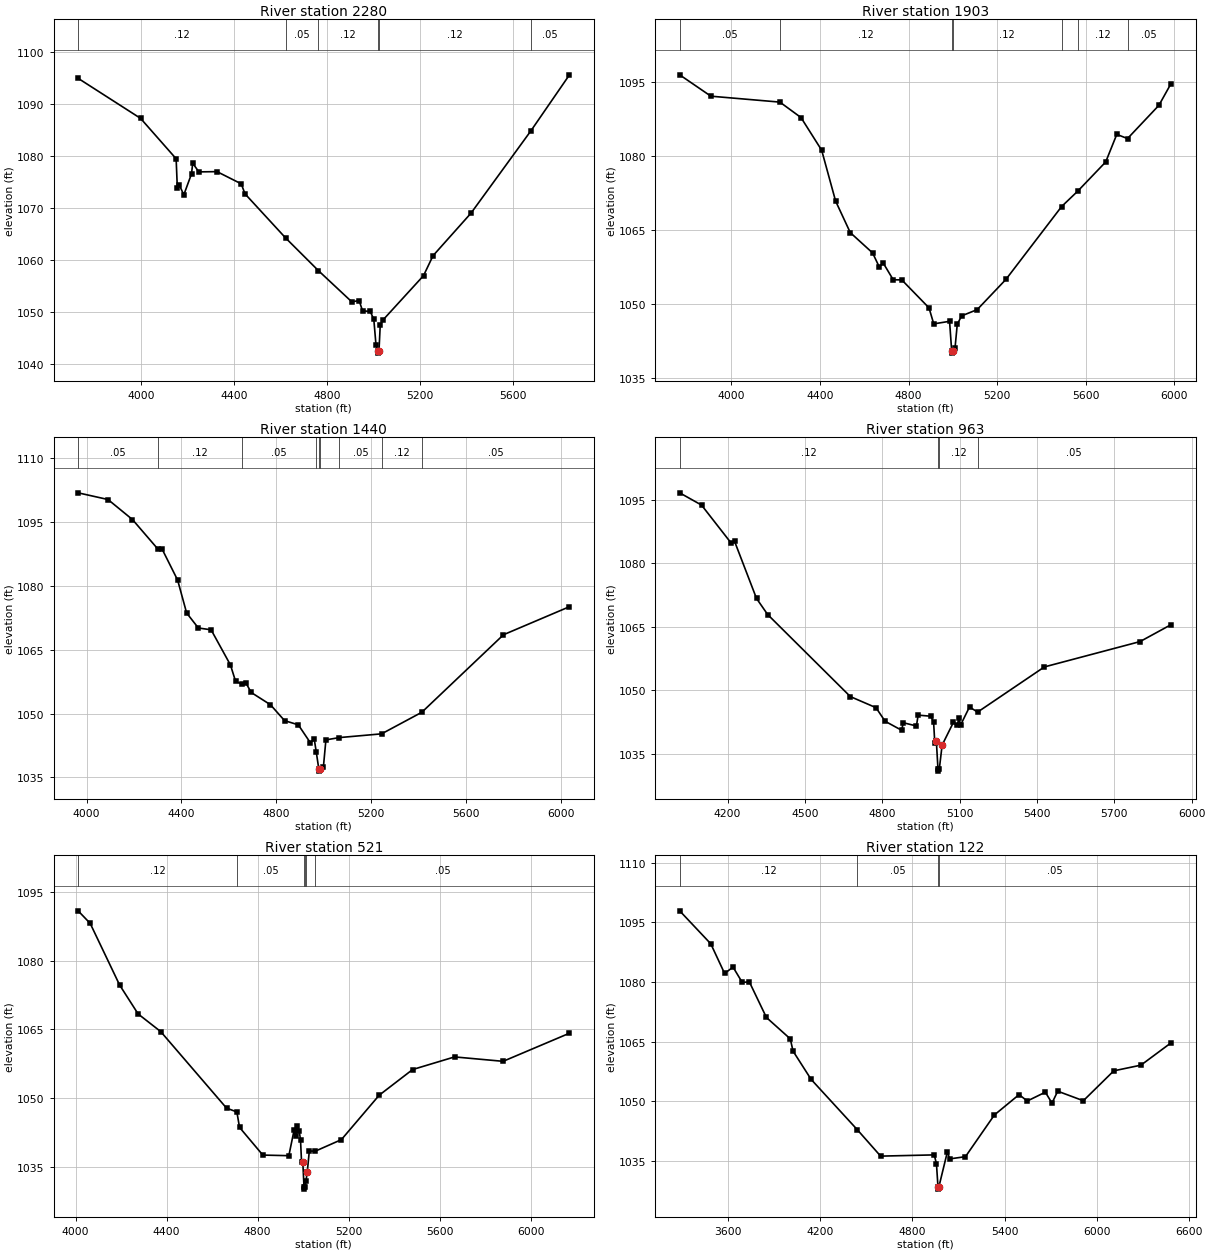
Type RM Length L Ch R = 1 ,2280    ,377,377,377
BEGIN DESCRIPTION:
Upper Denton 59 5.0
END DESCRIPTION:
XS GIS Cut Line= 3
      2186846.18      7265596.73      2185632.67      7265232.15
      2184804.51      7265060.27
#Sta/Elev= 30
  3729.4 1094.98  3997.9 1087.27  4150.9 1079.49  4156.1 1073.82    4165  1074.4
  4183.9 1072.53    4217 1076.58  4222.2 1078.64  4248.5 1076.96  4326.6 1077.01
  4430.9 1074.66  4446.9 1072.74  4621.2 1064.26  4762.1 1057.97  4906.4 1051.93
  4937.7 1052.19  4952.6  1050.2  4985.6 1050.09  5000.9 1048.57  5010.5 1043.53
  5018.1 1042.56  5018.8 1042.06  5023.2 1042.56  5028.7 1047.57  5041.1 1048.48
  5214.7 1056.98  5255.6 1060.82    5419 1069.02  5676.8 1084.89  5842.3 1095.65
#Mann= 6 ,-1 , 0
  3729.4     .12       0  4621.2     .05       0  4762.1     .12       0
  5018.1     .07       0  5023.2     .12       0  5676.8     .05       0
Bank Sta=5018.1,5023.2
XS Rating Curve= 0 ,0
Exp/Cntr=0.3,0.1

Type RM Length L Ch R = 1 ,1903    ,463,463,463
BEGIN DESCRIPTION:
Upper Denton 59 4.0
END DESCRIPTION:
XS GIS Cut Line= 3
      2186924.35      7265367.58        2185779.        7264910.
      2184794.09      7264935.28
#Sta/Elev= 30
  3766.6 1096.36  3907.6 1092.03  4219.1 1090.83  4314.4  1087.7  4407.7 1081.08
  4470.6 1070.78  4536.9 1064.38  4637.7 1060.26  4667.3 1057.47  4686.1 1058.18
  4730.8 1054.82  4769.6 1054.79  4892.3 1049.13  4913.8 1045.88  4985.2  1046.4
  4994.7 1040.45  4995.4 1039.95  4999.8 1040.45    5010 1041.05    5020 1045.81
    5040 1047.51    5110 1048.77    5240 1054.91  5491.1 1069.66  5564.3  1072.8
  5690.2  1078.7  5740.2 1084.29  5788.7 1083.44  5930.3 1090.17  5985.2 1094.59
#Mann= 7 ,-1 , 0
  3766.6     .05       0  4219.1     .12       0  4994.7     .07       0
  4999.8     .12       0  5491.1     .05       0  5564.3     .12       0
  5788.7     .05       0
Bank Sta=4994.7,4999.8
XS Rating Curve= 0 ,0
Exp/Cntr=0.3,0.1

Type RM Length L Ch R = 1 ,1440    ,477,477,477
BEGIN DESCRIPTION:
Upper Denton 59 3.0
END DESCRIPTION:
XS GIS Cut Line= 4
      2186981.66      7265107.17        2186079.        7264610.
        2185966.      7264523.82      2185072.09      7264606.98
#Sta/Elev= 30
  3964.5 1101.87  4090.4  1100.3  4193.6 1095.59  4299.1 1088.76  4318.6 1088.63
  4383.9 1081.36  4421.7 1073.65    4471 1070.12  4524.9 1069.69  4606.4 1061.43
  4628.1 1057.57  4654.9 1056.94  4671.7 1057.21  4693.5 1054.98  4774.9 1052.09
  4834.5 1048.35  4892.3 1047.37  4943.4 1043.13  4959.5    1044    4968 1040.97
  4978.7 1036.99  4979.4 1036.49  4983.8 1036.99  4998.2 1037.56  5008.6 1043.83
  5065.4 1044.37  5243.3 1045.25  5412.8 1050.32  5756.8 1068.53  6034.9 1075.12
#Mann= 9 ,-1 , 0
  3964.5     .05       0  4299.1     .12       0  4654.9     .05       0
    4968     .12       0  4978.7     .07       0  4983.8     .12       0
  5065.4     .05       0  5243.3     .12       0  5412.8     .05       0
Bank Sta=4978.7,4983.8
XS Rating Curve= 0 ,0
Exp/Cntr=0.3,0.1

Type RM Length L Ch R = 1 ,963     ,442,442,442
BEGIN DESCRIPTION:
Upper Denton 59 2.0
END DESCRIPTION:
XS GIS Cut Line= 4
       2186950.4      7264867.59        2186179.        7264260.
      2186111.83      7264159.24      2185332.33      7264351.51
#Sta/Elev= 30
  4014.1 1096.59  4098.9  1093.7  4212.7 1084.82  4227.1 1085.13  4312.1 1071.68
  4355.4 1067.88  4676.2 1048.52  4775.6 1045.91  4810.8 1042.71    4875 1040.58
  4881.5 1042.36  4932.4 1041.59  4939.1 1044.15  4988.8 1043.89  4999.1 1042.43
  5003.6  1037.6  5009.6 1038.15    5016 1031.44  5016.7 1030.94  5021.2 1031.44
  5032.1 1037.08  5075.7 1042.42  5090.7 1041.73  5096.7 1043.36  5104.2 1041.87
  5138.3 1046.08  5169.6 1044.86  5428.7 1055.52  5799.8  1061.5    5920 1065.49
#Mann= 4 ,-1 , 0
  4014.1     .12       0    5016     .07       0  5021.2     .12       0
  5169.6     .05       0
Bank Sta=5009.6,5032.1
XS Rating Curve= 0 ,0
Exp/Cntr=0.3,0.1

Type RM Length L Ch R = 1 ,521     ,399,399,399
BEGIN DESCRIPTION:
Upper Denton 59 1.0
END DESCRIPTION:
XS GIS Cut Line= 4
      2186971.23      7264732.19        2186429.        7263910.
      2186345.38      7263886.11      2185325.38       7264263.4
#Sta/Elev= 30
    4011 1090.83    4064  1088.1  4193.4 1074.68  4274.8 1068.38  4374.1 1064.54
  4663.2 1047.89  4708.7 1047.05  4720.4 1043.69  4822.8 1037.66  4937.1 1037.53
  4959.9 1043.03  4967.3 1041.79  4973.3 1043.93  4982.4 1042.96  4988.4 1040.96
  4992.9  1036.2  4998.5  1036.2  5003.7 1030.75  5004.4 1030.25  5008.9 1030.75
  5012.2 1031.97    5018 1033.96  5027.1 1038.54  5053.2 1038.51  5167.9 1041.02
  5334.3  1050.7    5481 1056.28  5665.4 1059.03  5878.7 1058.07  6170.4 1064.19
#Mann= 6 ,-1 , 0
    4011     .12       0  4708.7     .05       0  5003.7    .033       0
  5008.9     .05       0  5012.2     .12       0  5053.2     .05       0
Bank Sta=4998.5,5018
XS Rating Curve= 0 ,0
Exp/Cntr=0.3,0.1

Type RM Length L Ch R = 1 ,122     ,0,0,0
BEGIN DESCRIPTION:
Upper Denton 59 0.5
END DESCRIPTION:
XS GIS Cut Line= 4
      2187199.95      7264980.44       2186861.4      7263813.75
      2186340.57      7263480.42      2185163.76      7264162.55
#Sta/Elev= 30
  3288.6 1097.92  3490.7 1089.63  3580.6 1082.17  3635.4 1083.77  3695.1 1079.92
  3741.3 1080.06  3852.4  1071.1  4007.5 1065.72  4025.4 1062.64  4142.9 1055.53
  4441.9 1042.92  4594.6 1036.23    4943 1036.54  4957.4 1034.32  4967.5 1028.43
  4968.2 1027.93  4972.7 1028.43  5028.7 1037.34  5042.8 1035.53  5145.9 1036.09
  5333.9 1046.58  5494.5  1051.7  5547.6 1050.09  5665.2 1052.31  5708.2 1049.56
  5745.5 1052.56    5912 1050.16  6109.9 1057.68  6286.4 1059.11    6482 1064.72
#Mann= 4 ,-1 , 0
  3288.6     .12       0  4441.9     .05       0  4967.5    .033       0
  4972.7     .05       0
Bank Sta=4967.5,4972.7
XS Rating Curve= 0 ,0
Exp/Cntr=0.3,0.1

Chan Stop Cuts=-1
Use User Specified Reach Order=0
Composite Channel Slope=5