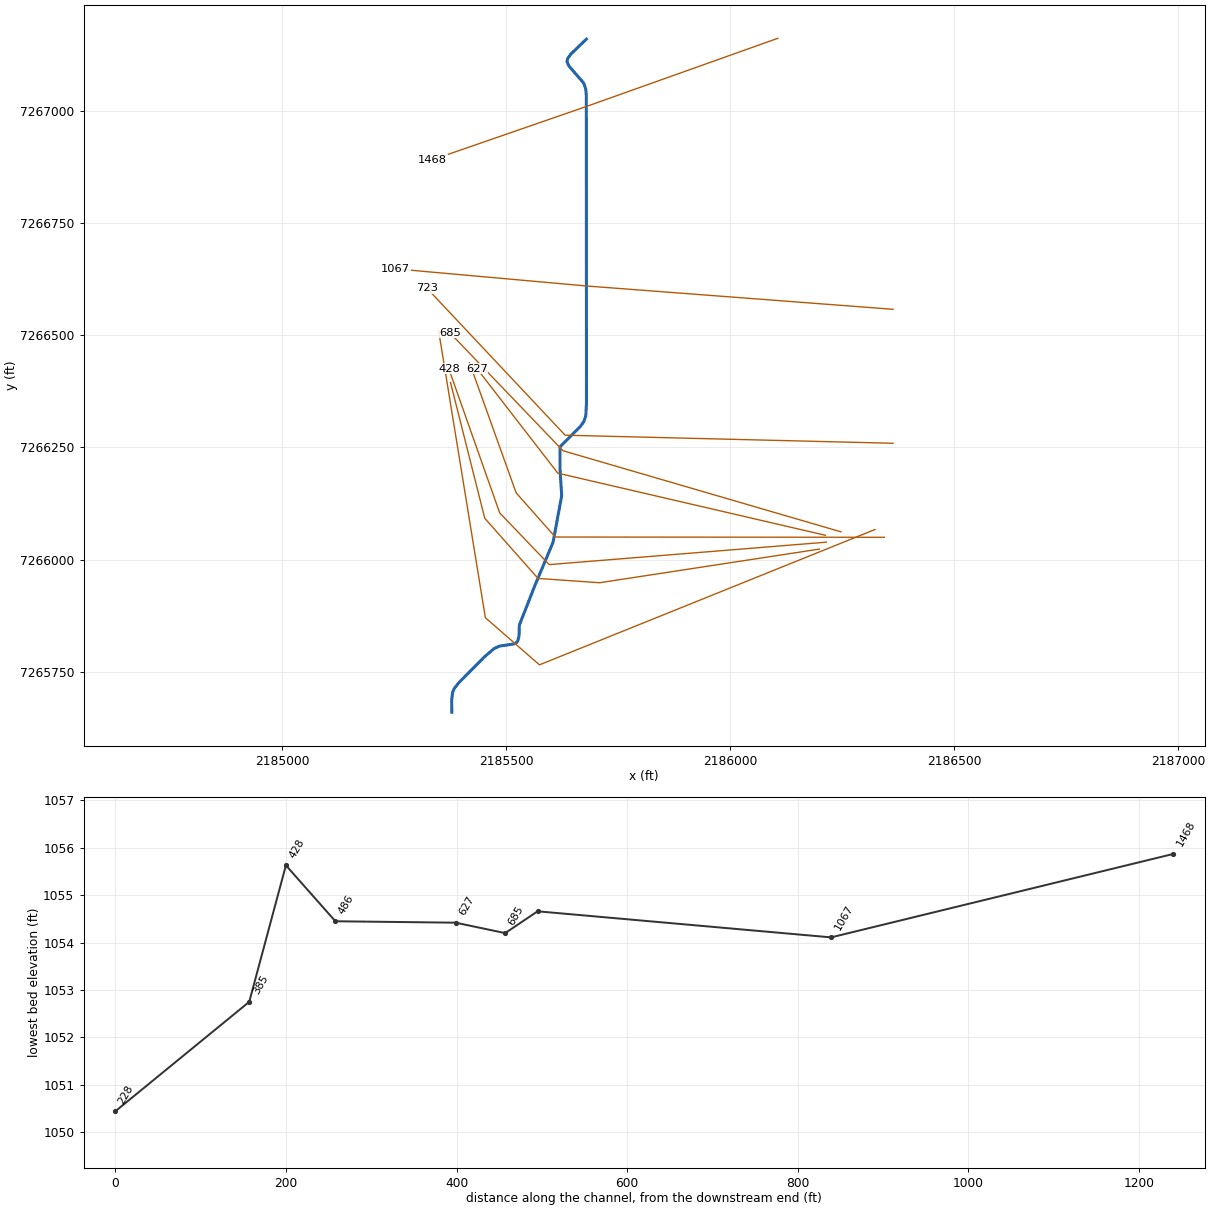
--- Upper Denton 60.prj (project) ---

Proj Title=Upper Denton 60 Base Level Engineering
Current Plan=p01
Default Exp/Contr=0.3,0.1
English Units
Geom File=g01
Flow File=f01
Plan File=p01
BEGIN DESCRIPTION:
Upper Denton 60
END DESCRIPTION:

--- Upper Denton 60.p01 (plan) ---

Plan Title=Multiple Run
Short Identifier=Multiple
Geom File=g01
Flow File=f01
Subcritical Flow
K Sum by GR= 0
Std Step Tol= 0.01
Critical Tol= 0.01
Num of Std Step Trials= 20
Max Error Tol= 0.3
Flow Tol Ratio= 0.001
Split Flow NTrial= 30
Split Flow Tol= 0.02
Split Flow Ratio= 0.02
Log Output Level= 0
Friction Slope Method= 1
Unsteady Friction Slope Method= 2
Unsteady Bridges Friction Slope Method= 1
Parabolic Critical Depth
Global Vel Dist=  1 , 1 , 1
Global Log Level= 0
CheckData=True
Encroach Param= -1, 0, 0, 0
BEGIN DESCRIPTION:
Multiple Run
END DESCRIPTION:

--- Upper Denton 60.f01 (steady flow) ---

Flow Title=Multiple
Number of Profiles=7
Profile Names=10-year,25-year,50-year,1pct_min,100-year,1pct_plu,500-year
River Rch & RM= Upper Denton 60,Reach-1,1468
     454     617     750     454     905    1806    1320
Boundary for River Rch & Prof#=Upper Denton 60,Reach-1,1
Up Type=0
Dn Type=3
Dn Slope=0.005
Boundary for River Rch & Prof#=Upper Denton 60,Reach-1,2
Up Type=0
Dn Type=3
Dn Slope=0.005
Boundary for River Rch & Prof#=Upper Denton 60,Reach-1,3
Up Type=0
Dn Type=3
Dn Slope=0.005
Boundary for River Rch & Prof#=Upper Denton 60,Reach-1,4
Up Type=0
Dn Type=3
Dn Slope=0.005
Boundary for River Rch & Prof#=Upper Denton 60,Reach-1,5
Up Type=0
Dn Type=3
Dn Slope=0.005
Boundary for River Rch & Prof#=Upper Denton 60,Reach-1,6
Up Type=0
Dn Type=3
Dn Slope=0.005
Boundary for River Rch & Prof#=Upper Denton 60,Reach-1,7
Up Type=0
Dn Type=3
Dn Slope=0.005

--- Upper Denton 60.g01 (geometry) ---

Geom Title=Existing Conditions

River Reach=Upper Denton 60,Reach-1
Reach XY= 30
      2185679.00      7267160.00      2185644.54      7267126.84
      2185637.44      7267116.77      2185635.91      7267110.14
      2185640.37      7267100.20      2185673.12      7267062.48
      2185677.69      7267049.58      2185679.14      7267035.12
      2185679.50      7266349.79      2185677.95      7266320.44
      2185673.53      7266307.55      2185665.60      7266296.69
      2185620.35      7266251.53      2185620.35      7266202.31
      2185624.19      7266142.69      2185604.96      7266038.85
      2185564.58      7265942.69      2185529.68      7265854.04
      2185528.98      7265830.20      2185525.94      7265818.30
      2185523.83      7265815.44      2185517.32      7265811.98
      2185485.53      7265807.27      2185473.29      7265801.71
      2185452.26      7265783.69      2185395.56      7265726.74
      2185384.30      7265712.54      2185380.67      7265703.87
      2185378.59      7265685.37      2185379.00      7265660.00

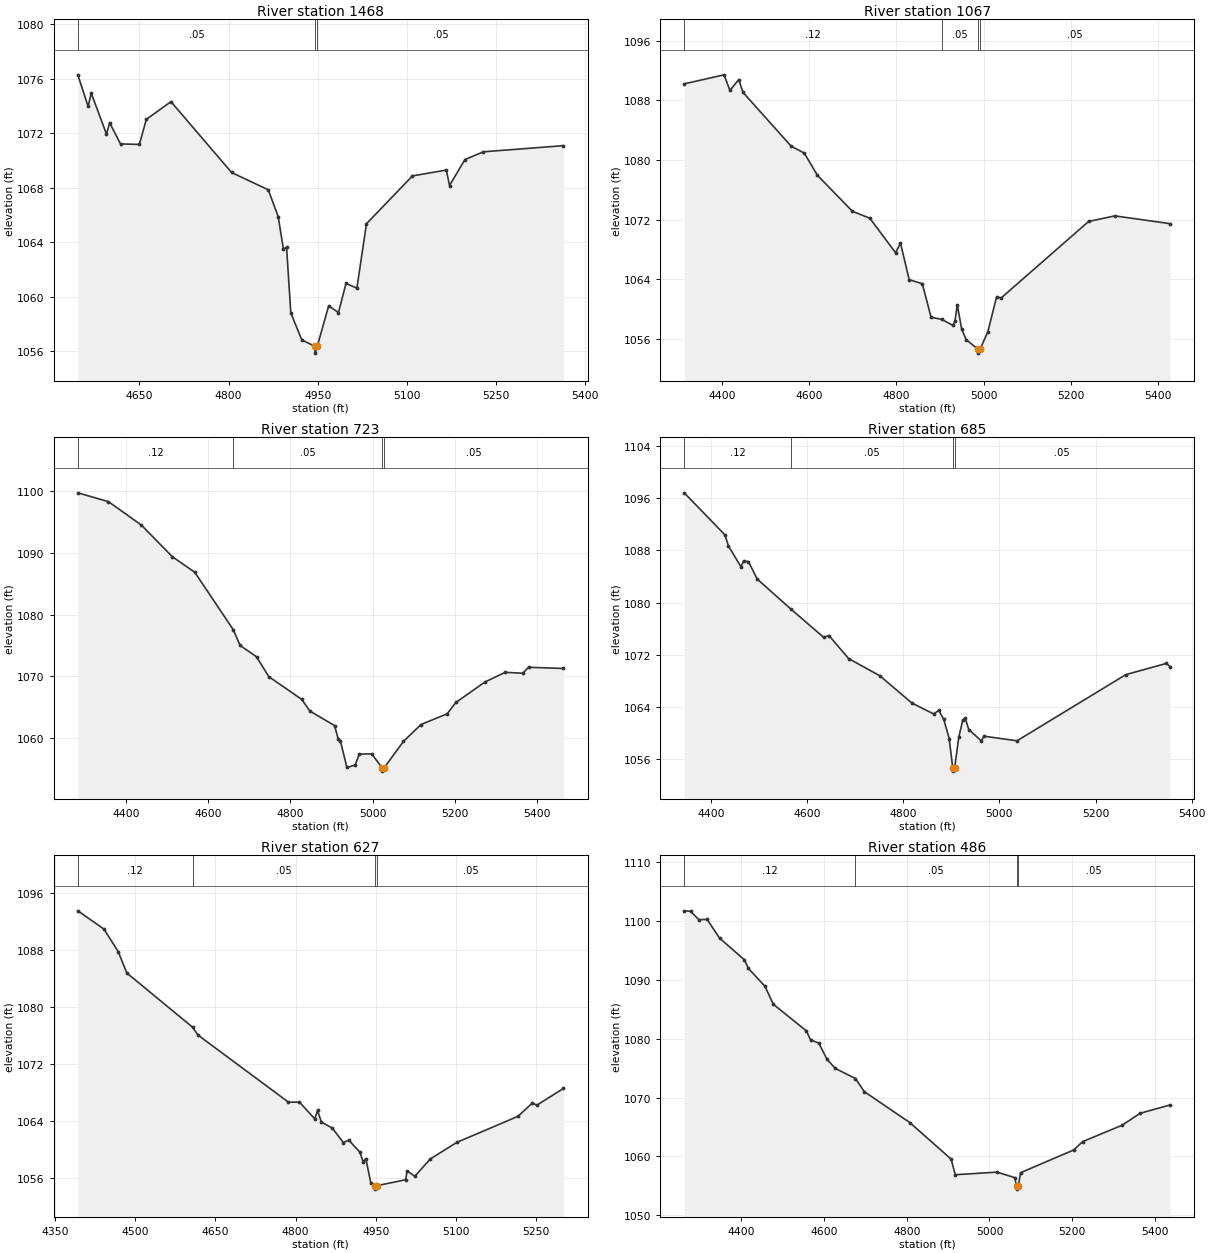
Type RM Length L Ch R = 1,1468,401,401,401
BEGIN DESCRIPTION:
Upper Denton 60 3.0
END DESCRIPTION:
XS GIS Cut Line= 3
      2186106.62      7267162.13      2185679.00      7267010.00
      2185335.82      7266891.31
#Sta/Elev= 30
  4546.5 1076.30  4563.8 1073.98  4569.1 1074.95  4594.7 1071.95  4600.0 1072.78
  4618.3 1071.23  4650.1 1071.19  4661.7 1073.03  4703.2 1074.33  4805.2 1069.13
  4866.9 1067.86  4883.6 1065.89  4892.4 1063.50  4897.7 1063.64  4904.8 1058.82
  4923.3 1056.84  4945.3 1056.37  4945.6 1055.87  4949.3 1056.37  4968.5 1059.34
  4985.0 1058.85  4997.7 1060.99  5016.0 1060.64  5032.1 1065.37  5109.5 1068.88
  5166.5 1069.31  5171.8 1068.17  5197.7 1070.08  5228.8 1070.65  5363.5 1071.10
#Mann=3,-1,0
  4546.5    0.05       0  4945.3   0.033       0  4949.3    0.05       0
Bank Sta=4945.3,4949.3
Exp/Cntr=0.3,0.1

Type RM Length L Ch R = 1,1067,344,344,344
BEGIN DESCRIPTION:
Upper Denton 60 2.0
END DESCRIPTION:
XS GIS Cut Line= 3
      2186363.54      7266557.97      2185679.00      7266610.00
      2185253.22      7266648.17
#Sta/Elev= 30
  4313.5 1090.23  4404.8 1091.44  4418.3 1089.35  4438.4 1090.80  4448.4 1089.08
  4558.7 1081.87  4588.8 1080.94  4618.9 1077.97  4699.1 1073.14  4739.3 1072.20
  4798.3 1067.57  4809.5 1068.87  4829.5 1063.96  4859.6 1063.42  4879.7 1058.92
  4904.5 1058.63  4929.4 1057.84  4934.4 1058.37  4939.8 1060.58  4949.9 1057.34
  4959.9 1055.93  4988.0 1054.61  4988.2 1054.11  4992.0 1054.61  5010.1 1057.01
  5030.1 1061.68  5040.2 1061.50  5241.0 1071.77  5301.2 1072.52  5427.5 1071.48
#Mann=4,-1,0
  4313.5    0.12       0  4904.5    0.05       0  4988.0   0.033       0
  4992.0    0.05       0
Bank Sta=4988,4992
Exp/Cntr=0.3,0.1

Type RM Length L Ch R = 1,723,38,38,38
BEGIN DESCRIPTION:
Upper Denton 60 1.0
END DESCRIPTION:
XS GIS Cut Line= 3
      2186363.55      7266259.35      2185631.88      7266277.31
      2185323.69      7266604.68
#Sta/Elev= 30
  4282.7 1099.71  4357.3 1098.28  4437.3 1094.49  4512.6 1089.37  4567.3 1086.85
  4661.1 1077.53  4677.4 1075.01  4717.4 1073.17  4747.4 1069.95  4827.4 1066.28
  4847.4 1064.38  4907.4 1062.03  4916.5 1059.79  4921.5 1059.55  4937.4 1055.25
  4957.4 1055.65  4967.5 1057.41  4997.5 1057.46  5023.6 1055.16  5023.9 1054.66
  5027.6 1055.16  5075.0 1059.48  5117.5 1062.20  5181.4 1063.95  5202.4 1065.77
  5273.2 1069.09  5322.6 1070.65  5365.1 1070.51  5379.2 1071.47  5464.2 1071.28
#Mann=4,-1,0
  4282.7    0.12       0  4661.1    0.05       0  5023.6   0.033       0
  5027.6    0.05       0
Bank Sta=5023.6,5027.6
Exp/Cntr=0.3,0.1

Type RM Length L Ch R = 1,685,58,58,58
BEGIN DESCRIPTION:
Upper Denton 60 0.99
END DESCRIPTION:
XS GIS Cut Line= 3
      2186247.25      7266061.93      2185627.08      7266242.69
      2185374.72      7266505.60
#Sta/Elev= 30
  4344.3 1096.79  4428.9 1090.36  4436.2 1088.67  4462.4 1085.45  4467.6 1086.34
  4477.9 1086.27  4495.9 1083.61  4566.9 1078.95  4634.1 1074.69  4645.5 1074.94
  4686.2 1071.43  4751.1 1068.80  4818.1 1064.61  4863.3 1062.95  4873.7 1063.49
  4884.1 1062.15  4895.5 1059.19  4902.9 1054.70  4903.2 1054.20  4906.9 1054.70
  4915.4 1059.38  4923.8 1062.02  4929.0 1062.30  4936.2 1060.57  4962.5 1058.82
  4967.7 1059.55  5036.6 1058.84  5263.0 1068.97  5347.6 1070.69  5354.7 1070.21
#Mann=4,-1,0
  4344.3    0.12       0  4566.9    0.05       0  4902.9   0.033       0
  4906.9    0.05       0
Bank Sta=4902.9,4906.9
Exp/Cntr=0.3,0.1

Type RM Length L Ch R = 1,627,141,141,141
BEGIN DESCRIPTION:
Upper Denton 60 0.9
END DESCRIPTION:
XS GIS Cut Line= 3
      2186212.65      7266054.23      2185615.54      7266192.69
      2185434.80      7266426.02
#Sta/Elev= 30
  4392.7 1093.54  4441.5 1090.98  4468.3 1087.80  4484.2 1084.81  4607.3 1077.18
  4617.3 1076.08  4786.5 1066.65  4807.1 1066.65  4835.8 1064.29  4840.9 1065.48
  4848.1 1063.85  4868.7 1062.99  4889.2 1060.96  4899.4 1061.31  4920.0 1059.63
  4926.2 1058.27  4931.4 1058.67  4940.5 1055.33  4948.8 1054.92  4949.0 1054.42
  4952.8 1054.92  5005.7 1055.74  5008.4 1056.97  5022.9 1056.23  5051.8 1058.66
  5101.6 1061.00  5215.7 1064.65  5242.8 1066.53  5251.0 1066.22  5300.8 1068.57
#Mann=4,-1,0
  4392.7    0.12       0  4607.3    0.05       0  4948.8   0.033       0
  4952.8    0.05       0
Bank Sta=4948.8,4952.8
Exp/Cntr=0.3,0.1

Type RM Length L Ch R = 1,486,58,58,58
BEGIN DESCRIPTION:
Upper Denton 60 0.8
END DESCRIPTION:
XS GIS Cut Line= 4
      2186344.34      7266049.74      2185609.77      7266050.38
      2185522.49      7266148.88      2185418.44      7266438.80
#Sta/Elev= 30
  4262.1 1101.76  4277.4 1101.68  4297.4 1100.26  4317.4 1100.30  4347.4 1097.13
  4407.4 1093.44  4417.4 1091.96  4457.4 1088.92  4477.4 1085.88  4557.4 1081.35
  4567.4 1079.84  4587.4 1079.27  4607.4 1076.50  4627.4 1074.97  4676.0 1073.25
  4697.4 1071.02  4807.4 1065.77  4907.4 1059.55  4917.4 1056.90  5018.3 1057.34
  5061.0 1056.41  5065.7 1054.95  5065.9 1054.45  5069.7 1054.95  5075.2 1057.24
  5203.8 1061.11  5225.1 1062.52  5320.7 1065.31  5364.6 1067.35  5436.3 1068.75
#Mann=4,-1,0
  4262.1    0.12       0  4676.0    0.05       0  5065.7   0.033       0
  5069.7    0.05       0
Bank Sta=5065.7,5069.7
Exp/Cntr=0.3,0.1

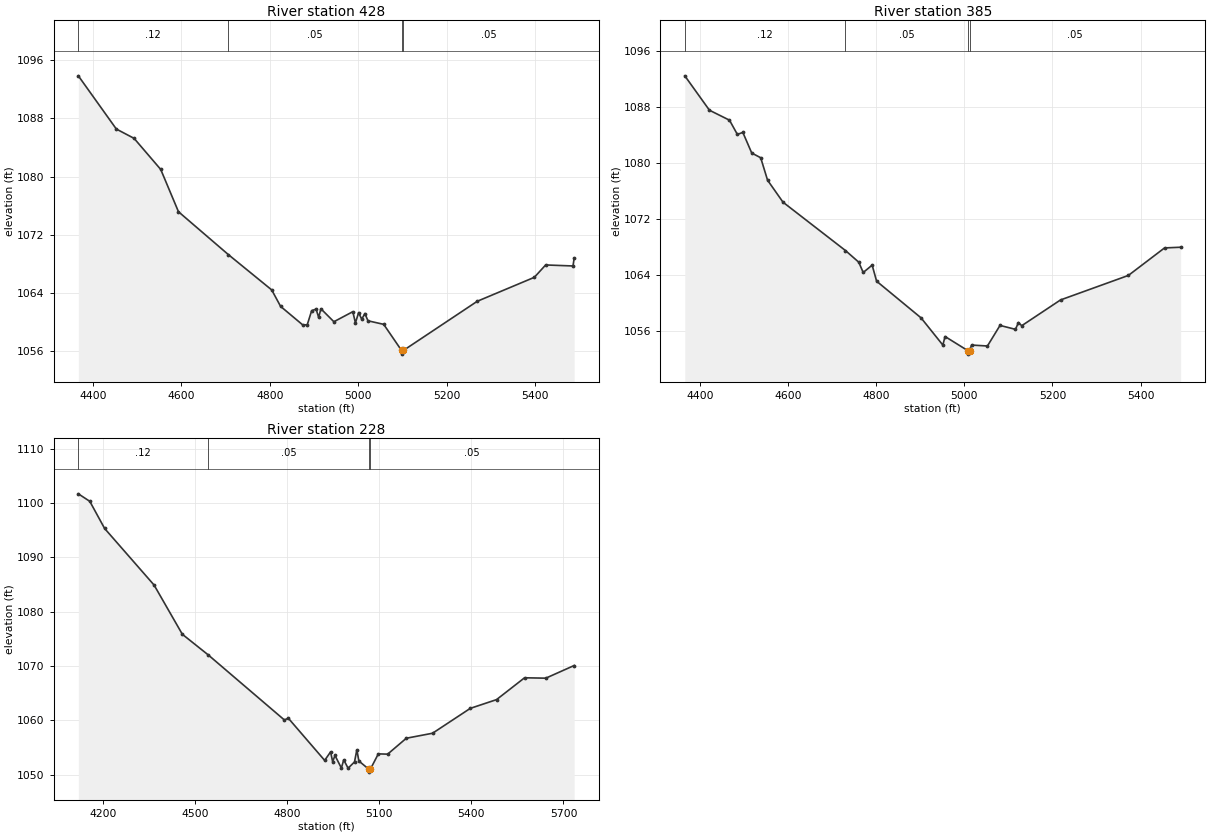
Type RM Length L Ch R = 1,428,43,43,43
BEGIN DESCRIPTION:
Upper Denton 60 0.7
END DESCRIPTION:
XS GIS Cut Line= 4
      2186214.58      7266038.85      2185596.31      7265988.85
      2185485.73      7266104.23      2185372.34      7266425.18
#Sta/Elev= 30
  4367.3 1093.86  4453.2 1086.55  4493.3 1085.27  4553.5 1081.00  4593.6 1075.19
  4706.2 1069.31  4804.3 1064.45  4824.4 1062.19  4874.5 1059.64  4884.6 1059.66
  4894.6 1061.60  4904.6 1061.81  4910.4 1060.68  4915.5 1061.86  4944.8 1060.08
  4987.6 1061.46  4993.5 1059.92  5000.7 1061.33  5007.7 1060.43  5014.9 1061.21
  5021.8 1060.21  5057.4 1059.72  5097.8 1056.13  5098.1 1055.63  5101.8 1056.13
  5268.8 1062.89  5397.8 1066.18  5423.4 1067.88  5485.2 1067.74  5487.8 1068.81
#Mann=4,-1,0
  4367.3    0.12       0  4706.2    0.05       0  5097.8   0.033       0
  5101.8    0.05       0
Bank Sta=5097.8,5101.8
Exp/Cntr=0.3,0.1

Type RM Length L Ch R = 1,385,157,157,157
BEGIN DESCRIPTION:
Upper Denton 60 0.6
END DESCRIPTION:
XS GIS Cut Line= 5
      2186199.19      7266023.46      2185708.81      7265948.46
      2185571.31      7265958.08      2185452.47      7266092.19
      2185376.12      7266394.59
#Sta/Elev= 30
  4365.8 1092.40  4421.7 1087.50  4467.2 1086.08  4485.1 1084.05  4497.5 1084.34
  4517.7 1081.40  4538.0 1080.73  4553.6 1077.53  4588.6 1074.40  4730.3 1067.51
  4760.5 1065.85  4770.6 1064.38  4790.9 1065.43  4801.0 1063.14  4901.8 1057.92
  4951.3 1054.04  4956.3 1055.26  5007.9 1053.25  5008.1 1052.75  5011.9 1053.25
  5016.5 1054.04  5052.5 1053.91  5081.0 1056.84  5116.1 1056.28  5122.8 1057.25
  5130.3 1056.80  5218.3 1060.47  5372.2 1063.96  5454.3 1067.88  5490.8 1067.98
#Mann=4,-1,0
  4365.8    0.12       0  4730.3    0.05       0  5007.9   0.033       0
  5011.9    0.05       0
Bank Sta=5007.9,5011.9
Exp/Cntr=0.3,0.1

Type RM Length L Ch R = 1,228,0,0,0
BEGIN DESCRIPTION:
Upper Denton 60 0.5
END DESCRIPTION:
XS GIS Cut Line= 4
      2186323.20      7266067.08      2185574.51      7265765.43
      2185453.85      7265870.46      2185349.68      7266509.39
#Sta/Elev= 30
  4120.4 1101.68  4157.7 1100.30  4206.0 1095.30  4367.1 1084.88  4459.1 1075.82
  4543.2 1072.03  4791.4 1060.04  4804.1 1060.37  4922.5 1052.60  4941.8 1054.17
  4948.5 1052.36  4956.1 1053.51  4976.9 1051.19  4984.6 1052.70  4998.8 1051.16
  5019.7 1052.32  5027.3 1054.55  5033.9 1052.49  5067.0 1050.94  5067.3 1050.44
  5071.0 1050.94  5097.2 1053.80  5127.6 1053.75  5188.4 1056.68  5273.8 1057.60
  5396.7 1062.18  5482.2 1063.79  5573.4 1067.81  5642.6 1067.74  5734.9 1070.07
#Mann=4,-1,0
  4120.4    0.12       0  4543.2    0.05       0  5067.0   0.033       0
  5071.0    0.05       0
Bank Sta=5067,5071
Exp/Cntr=0.3,0.1

Chan Stop Cuts=-1