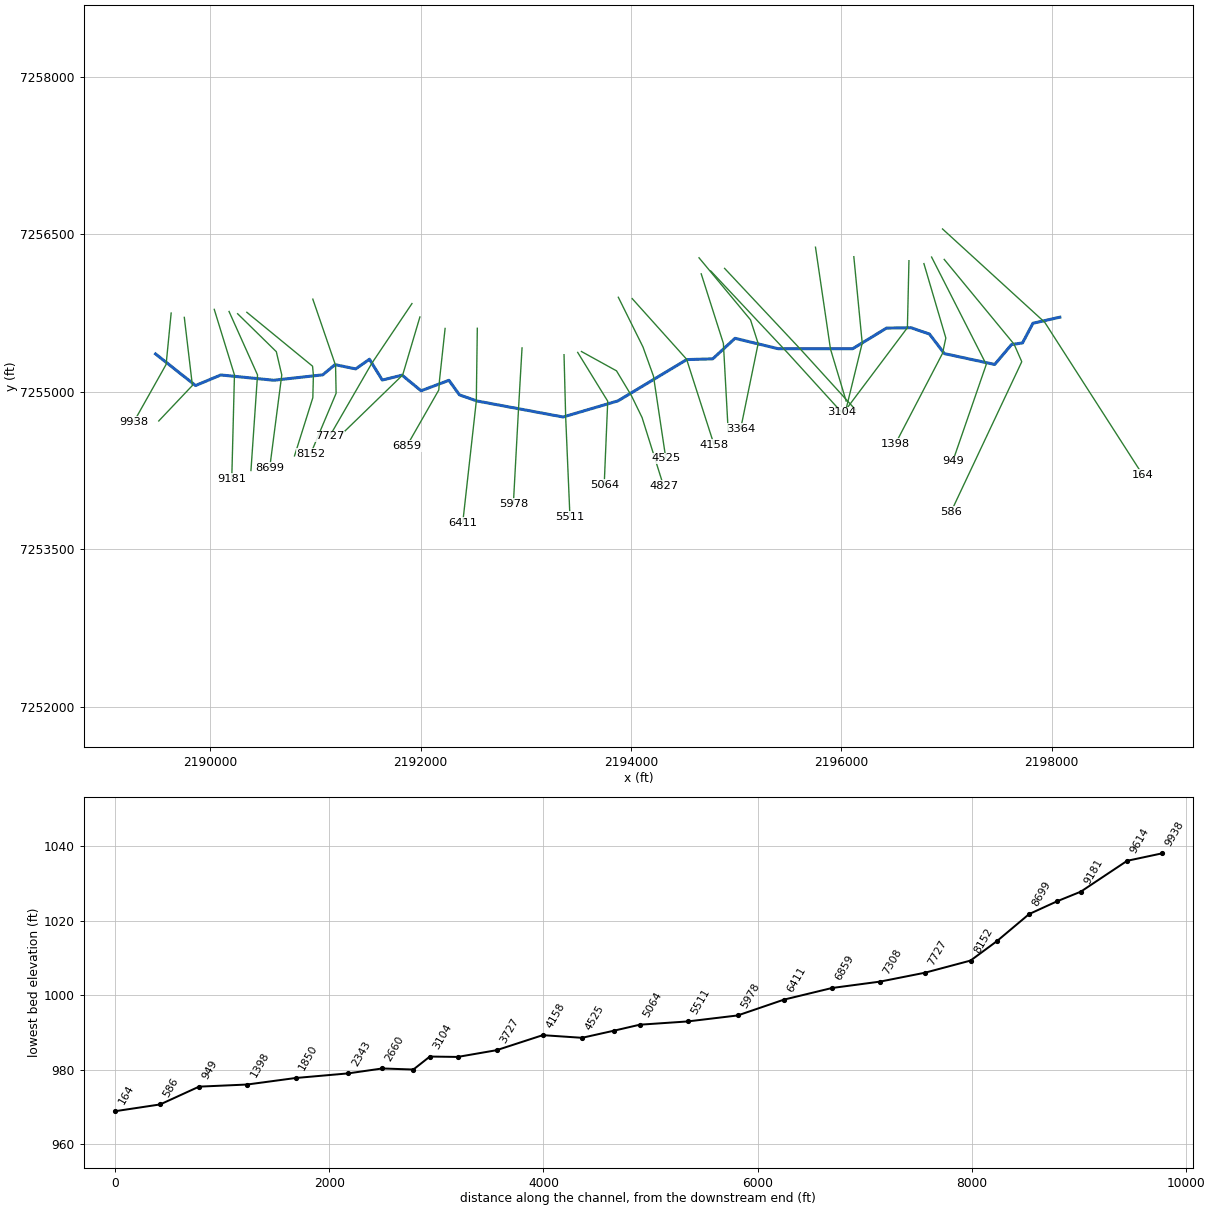
--- Upper Denton 61.prj (project) ---

Proj Title=Upper Denton 61 Base Level Engineering
Current Plan=p01
Default Exp/Contr=0.3,0.1
English Units
Geom File=g01
Flow File=f01
Plan File=p01
Y Axis Title=Elevation
X Axis Title(PF)=Main Channel Distance
X Axis Title(XS)=Station
BEGIN DESCRIPTION:
Upper Denton 61
END DESCRIPTION:
DSS Export Rating Curves= 0
DSS Export Rating Curve Sorted= 0
DSS Export Volume Flow Curves= 0
DXF OffsetX= 0
DXF OffsetY= 0
DXF ScaleX= 1
DXF ScaleY= 10

--- Upper Denton 61.p01 (plan) ---

Plan Title=Multiple Run
Short Identifier=Multiple
Geom File=g01
Flow File=f01
Subcritical Flow
K Sum by GR= 0
Std Step Tol= 0.01
Critical Tol= 0.01
Num of Std Step Trials= 20
Max Error Tol= 0.3
Flow Tol Ratio= 0.001
Split Flow NTrial= 30
Split Flow Tol= 0.02
Split Flow Ratio= 0.02
Log Output Level= 0
Friction Slope Method= 1
Unsteady Friction Slope Method= 2
Unsteady Bridges Friction Slope Method= 1
Parabolic Critical Depth
Global Vel Dist=  1 , 1 , 1
Global Log Level= 0
CheckData=True
Encroach Param= -1, 0, 0, 0
BEGIN DESCRIPTION:
Multiple Run
END DESCRIPTION:

--- Upper Denton 61.f01 (steady flow) ---

Flow Title=Multiple
Program Version=4.10
Number of Profiles= 7
Profile Names=10-year,25-year,50-year,1pct_min,100-year,1pct_plu,500-year
River Rch & RM=Upper Denton 61,Reach-1         ,9938
     708     994    1235     762    1520    3032    2311
River Rch & RM=Upper Denton 61,Reach-1         ,9181
    1013    1447    1819    1134    2263    4515    3515
River Rch & RM=Upper Denton 61,Reach-1         ,4525
    1072    1534    1932    1206    2406    4801    3747
River Rch & RM=Upper Denton 61,Reach-1         ,3727
    1156    1657    2087    1303    2600    5187    4049
Boundary for River Rch & Prof#=Upper Denton 61,Reach-1         , 1
Up Type= 0
Dn Type= 3
Dn Slope=0.0042
Boundary for River Rch & Prof#=Upper Denton 61,Reach-1         , 2
Up Type= 0
Dn Type= 3
Dn Slope=0.0042
Boundary for River Rch & Prof#=Upper Denton 61,Reach-1         , 3
Up Type= 0
Dn Type= 3
Dn Slope=0.0042
Boundary for River Rch & Prof#=Upper Denton 61,Reach-1         , 4
Up Type= 0
Dn Type= 3
Dn Slope=0.0042
Boundary for River Rch & Prof#=Upper Denton 61,Reach-1         , 5
Up Type= 0
Dn Type= 3
Dn Slope=0.0042
Boundary for River Rch & Prof#=Upper Denton 61,Reach-1         , 6
Up Type= 0
Dn Type= 3
Dn Slope=0.0042
Boundary for River Rch & Prof#=Upper Denton 61,Reach-1         , 7
Up Type= 0
Dn Type= 3
Dn Slope=0.0042
DSS Import GetInterval= 0
DSS Import GetPeak= 0
DSS Import FillOption= 0

--- Upper Denton 61.g01 (geometry) ---

Geom Title=Existing Conditions
Program Version=4.10

River Reach=Upper Denton 61 ,Reach-1
Reach XY= 30
        2189479.        7255360.      2189858.95       7255059.4
      2190099.03      7255159.94        2190604.       7255109.6
      2191068.56      7255161.06      2191184.86      7255257.94
      2191382.41      7255217.81       2191512.9      7255309.59
      2191634.83      7255111.54      2191823.11      7255158.04
        2192004.      7255009.41      2192268.71      7255109.03
       2192368.9      7254970.39      2192534.94      7254912.27
      2193354.09      7254759.79      2193877.45      7254913.75
      2194530.55      7255306.25      2194777.75      7255313.45
       2194989.5      7255508.81      2195399.03      7255410.07
      2196108.99      7255410.06      2196430.55      7255606.25
      2196663.78      7255609.48      2196838.81      7255549.49
      2196980.28      7255363.52      2197459.12      7255259.91
      2197619.24      7255449.47      2197723.89      7255465.11
      2197822.81      7255652.15        2198079.        7255710.

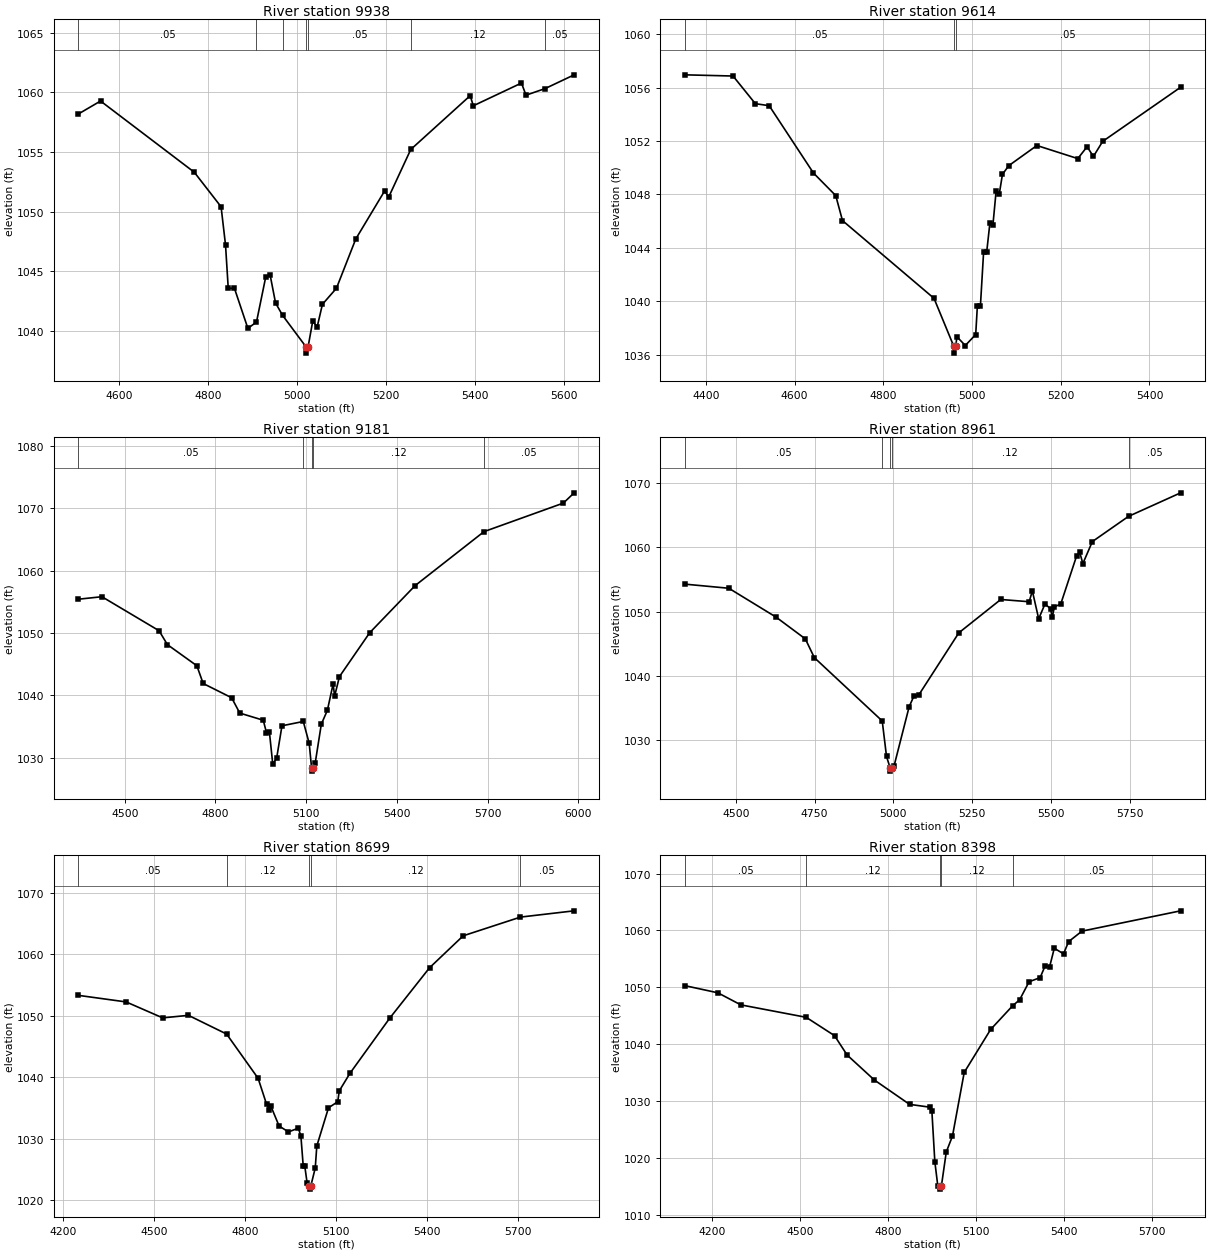
Type RM Length L Ch R = 1 ,9938    ,324,324,324
BEGIN DESCRIPTION:
Upper Denton 61 22.0
END DESCRIPTION:
XS GIS Cut Line= 3
      2189627.05      7255749.73        2189579.        7255260.
      2189273.44      7254716.03
#Sta/Elev= 30
  4507.9 1058.19  4557.9 1059.28  4768.9  1053.3  4829.2  1050.4  4839.2 1047.19
  4845.3 1043.56  4859.3 1043.55  4889.5 1040.19  4908.9 1040.72  4929.6 1044.49
  4939.7 1044.65  4951.8 1042.32  4967.7 1041.28  5020.9 1038.61  5021.2 1038.11
  5024.9 1038.61  5035.4 1040.78  5045.6 1040.33  5057.3 1042.21  5088.9 1043.56
  5132.3 1047.69  5197.3 1051.73  5206.4 1051.21  5256.1 1055.21  5389.9 1059.73
  5396.9 1058.88  5505.3 1060.79  5515.5 1059.77  5558.8 1060.33  5623.9 1061.48
#Mann= 7 ,-1 , 0
  4507.9     .05       0  4908.9     .12       0  4967.7     .05       0
  5020.9    .033       0  5024.9     .05       0  5256.1     .12       0
  5558.8     .05       0
Bank Sta=5020.9,5024.9
XS Rating Curve= 0 ,0
Exp/Cntr=0.3,0.1

Type RM Length L Ch R = 1 ,9614    ,433,433,433
BEGIN DESCRIPTION:
Upper Denton 61 21.0
END DESCRIPTION:
XS GIS Cut Line= 3
      2189752.05      7255708.04        2189829.        7255060.
      2189508.97      7254721.95
#Sta/Elev= 30
  4352.2 1056.95    4461 1056.86  4511.3 1054.79  4542.5 1054.64  4642.3  1049.6
  4692.6 1047.91  4707.8 1046.04  4914.2 1040.22  4958.9 1036.62  4959.2 1036.12
  4962.9 1036.62    4966 1037.34  4984.7 1036.69  5008.2 1037.51  5011.9 1039.62
  5018.8 1039.64    5026 1043.68  5032.9 1043.66  5040.2 1045.86  5047.1 1045.74
  5054.3 1048.27  5061.2    1048  5068.5  1049.5  5082.7 1050.15  5146.2 1051.66
  5238.4 1050.68  5259.4 1051.57  5273.6 1050.84  5294.6 1051.97  5470.3 1056.02
#Mann= 3 ,-1 , 0
  4352.2     .05       0  4958.9    .033       0  4962.9     .05       0
Bank Sta=4958.9,4962.9
XS Rating Curve= 0 ,0
Exp/Cntr=0.3,0.1

Type RM Length L Ch R = 1 ,9181    ,220,220,220
BEGIN DESCRIPTION:
Upper Denton 61 20.0
END DESCRIPTION:
XS GIS Cut Line= 3
      2190036.76      7255784.52        2190229.        7255160.
      2190203.46      7254174.17
#Sta/Elev= 30
  4346.6 1055.42  4424.6 1055.82  4613.6 1050.36  4641.1 1048.13  4738.5 1044.74
  4759.4 1041.89  4853.6  1039.6  4880.4 1037.14  4958.2 1035.99  4968.6 1034.01
  4978.5 1034.08  4989.6 1028.91  5002.5 1029.93    5020  1035.1  5090.5 1035.79
  5110.1 1032.26  5117.9 1028.32  5118.3 1027.82  5122.2 1028.32  5130.1 1029.18
  5150.1 1035.36  5170.1 1037.58  5189.1 1041.81  5194.1 1039.87  5210.1    1043
  5310.1 1050.04  5460.2  1057.6  5688.1 1066.27  5950.4 1070.85  5986.2  1072.5
#Mann= 5 ,-1 , 0
  4346.6     .05       0  5090.5     .12       0  5117.9    .033       0
  5122.2     .12       0  5688.1     .05       0
Bank Sta=5117.9,5122.2
XS Rating Curve= 0 ,0
Exp/Cntr=0.3,0.1

Type RM Length L Ch R = 1 ,8961    ,262,262,262
BEGIN DESCRIPTION:
Upper Denton 61 19.5
END DESCRIPTION:
XS GIS Cut Line= 3
      2190177.58      7255764.25       2190448.4       7255160.1
      2190385.91      7254250.42
#Sta/Elev= 30
    4338 1054.25  4477.8 1053.61  4627.8 1049.13  4720.6 1045.76  4749.2 1042.85
  4964.7 1033.03  4978.3 1027.53  4989.8 1025.75  4990.2 1025.25  4994.2 1025.75
  5002.6 1026.12  5050.3 1035.26  5064.8 1036.83  5080.4 1037.04  5207.9  1046.7
    5341 1051.87  5431.2 1051.52  5441.2 1053.21  5461.3 1048.87  5481.3 1051.17
  5499.2 1050.43  5504.2 1049.11  5511.4 1050.73  5531.4 1051.17  5581.5 1058.59
  5591.6 1059.16  5601.6 1057.44  5631.7 1060.85  5746.5 1064.76  5911.9 1068.41
#Mann= 5 ,-1 , 0
    4338     .05       0  4964.7     .12       0  4989.8     .07       0
  4994.2     .12       0  5746.5     .05       0
Bank Sta=4989.8,4994.2
XS Rating Curve= 0 ,0
Exp/Cntr=0.3,0.1

Type RM Length L Ch R = 1 ,8699    ,301,301,301
BEGIN DESCRIPTION:
Upper Denton 61 19.0
END DESCRIPTION:
XS GIS Cut Line= 4
      2190258.98      7255742.82      2190627.05      7255381.69
        2190679.        7255160.      2190564.55      7254277.53
#Sta/Elev= 30
  4251.7  1053.3  4409.2 1052.23  4529.5 1049.64  4614.4 1050.05  4740.1 1047.01
  4843.9 1039.81  4871.8 1035.59  4881.2 1034.65  4886.3 1035.24  4912.9 1032.07
  4943.7  1031.1  4976.4 1031.71  4984.8 1030.42  4992.5 1025.53  4997.6 1025.53
  5005.1 1022.87    5013  1022.3  5013.4  1021.8  5017.4  1022.3  5032.1 1025.24
  5037.2 1028.81  5075.7 1035.02    5106    1036  5111.3 1037.78  5146.3 1040.62
  5277.4 1049.59  5408.5 1057.78  5519.4 1062.98  5707.9 1066.02  5884.9 1067.04
#Mann= 5 ,-1 , 0
  4251.7     .05       0  4740.1     .12       0    5013     .07       0
  5017.4     .12       0  5707.9     .05       0
Bank Sta=5013,5017.4
XS Rating Curve= 0 ,0
Exp/Cntr=0.3,0.1

Type RM Length L Ch R = 1 ,8398    ,246,246,246
BEGIN DESCRIPTION:
Upper Denton 61 18.5
END DESCRIPTION:
XS GIS Cut Line= 5
      2190346.81      7255756.48      2190971.84      7255243.43
      2190979.65      7255157.49      2190974.45      7254943.95
      2190799.97      7254389.27
#Sta/Elev= 30
  4107.5 1050.29  4220.2 1049.03  4298.4 1046.91  4521.3 1044.72  4617.8  1041.5
  4660.8 1038.09  4753.4 1033.71  4873.6 1029.42  4942.3 1028.93  4949.7 1028.21
  4959.7 1019.36  4969.8 1015.11  4977.6 1015.02    4978 1014.52    4982 1015.02
  4998.7 1021.05  5019.9 1023.85  5059.9 1035.04    5150 1042.59  5225.3 1046.77
  5248.6 1047.79    5281 1050.97  5318.6  1051.7  5335.5 1053.74    5351 1053.61
  5366.9 1056.86  5398.4 1055.88  5415.8 1058.03  5461.3 1059.87  5797.5 1063.44
#Mann= 5 ,-1 , 0
  4107.5     .05       0  4521.3     .12       0  4977.6     .07       0
    4982     .12       0  5225.3     .05       0
Bank Sta=4977.6,4982
XS Rating Curve= 0 ,0
Exp/Cntr=0.3,0.1

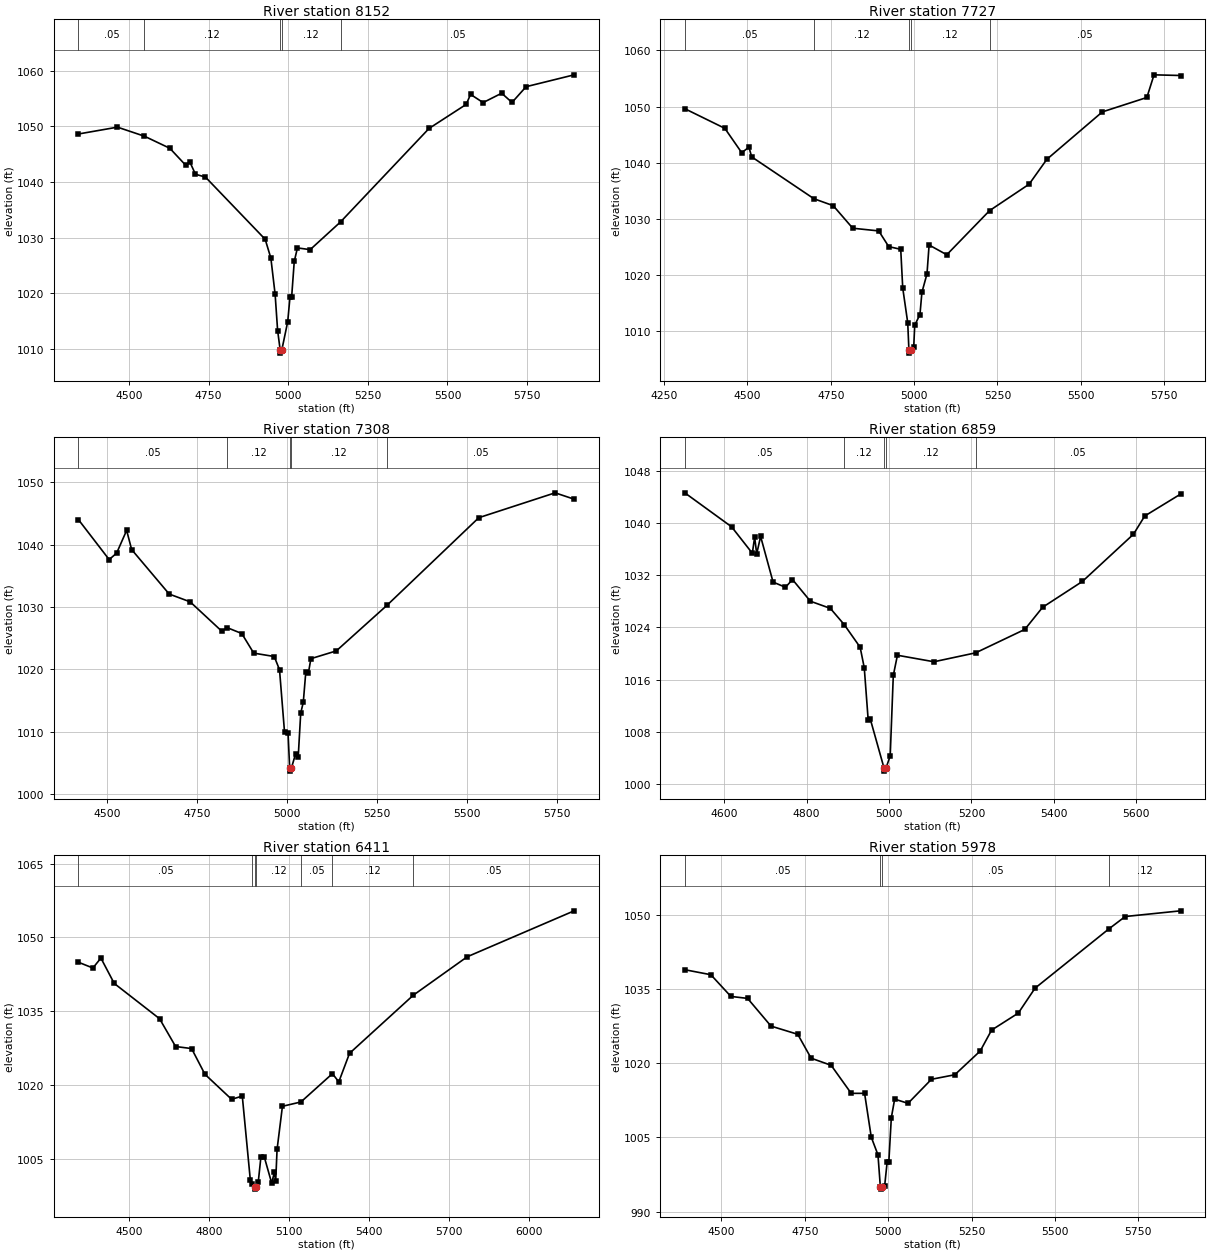
Type RM Length L Ch R = 1 ,8152    ,425,425,425
BEGIN DESCRIPTION:
Upper Denton 61 18.0
END DESCRIPTION:
XS GIS Cut Line= 4
      2190974.27      7255881.69      2191190.59      7255251.24
       2191195.8      7254985.62      2190953.73      7254410.17
#Sta/Elev= 30
  4341.3 1048.62  4464.2 1049.85  4548.6 1048.23  4628.5 1046.06  4677.8 1043.05
    4692 1043.52    4709  1041.4  4740.3 1040.89  4927.9 1029.72  4945.7 1026.35
  4959.1 1019.84  4966.9 1013.36  4975.1  1009.8  4975.6  1009.3  4979.8  1009.8
  4998.6 1014.94  5005.8 1019.42    5011 1019.42  5019.1 1025.76  5029.1 1028.18
  5069.1 1027.87  5164.5 1032.85  5442.3 1049.62    5559 1053.94  5572.5 1055.73
    5612 1054.26  5670.3 1055.94  5702.7 1054.28  5746.9 1057.11  5897.8 1059.24
#Mann= 5 ,-1 , 0
  4341.3     .05       0  4548.6     .12       0  4975.1     .07       0
  4979.8     .12       0  5164.5     .05       0
Bank Sta=4975.1,4979.8
XS Rating Curve= 0 ,0
Exp/Cntr=0.3,0.1

Type RM Length L Ch R = 1 ,7727    ,419,419,419
BEGIN DESCRIPTION:
Upper Denton 61 17.0
END DESCRIPTION:
XS GIS Cut Line= 3
      2191917.13      7255839.75      2191534.34      7255269.47
      2191133.97       7254576.1
#Sta/Elev= 30
  4311.9 1049.62    4432 1046.12  4482.6 1041.78  4504.3 1042.75  4512.6 1041.03
  4699.2 1033.57  4757.2 1032.33  4815.7 1028.31  4893.7 1027.83  4923.7 1025.03
  4959.7 1024.55  4965.7 1017.66  4980.7 1011.46  4984.3 1006.54  4984.9 1006.04
  4989.2 1006.54  4998.7  1007.2  5001.7 1011.02  5017.4 1012.92  5023.2 1016.86
  5038.5 1020.18  5044.8 1025.32  5097.8 1023.58  5226.1 1031.44  5344.9 1036.16
    5398 1040.59  5564.5 1049.05  5698.1 1051.62  5719.6 1055.66  5799.4 1055.54
#Mann= 5 ,-1 , 0
  4311.9     .05       0  4699.2     .12       0  4984.3     .07       0
  4989.2     .12       0  5226.1     .05       0
Bank Sta=4984.3,4989.2
XS Rating Curve= 0 ,0
Exp/Cntr=0.3,0.1

Type RM Length L Ch R = 1 ,7308    ,449,449,449
BEGIN DESCRIPTION:
Upper Denton 61 16.0
END DESCRIPTION:
XS GIS Cut Line= 3
      2191992.66      7255712.14        2191829.        7255160.
      2191253.54      7254600.64
#Sta/Elev= 30
  4419.9 1044.02  4505.6 1037.59  4526.4 1038.63  4554.2 1042.28  4568.1  1039.2
  4672.5 1032.06  4730.8 1030.81  4818.5 1026.11    4834 1026.66  4874.2 1025.73
  4907.5 1022.58  4964.5 1022.04  4979.2 1019.92  4993.2 1009.86  5002.9 1009.77
  5007.4 1004.15    5008 1003.65  5012.3 1004.15    5024 1006.45  5031.1 1005.84
  5038.1 1012.94  5045.3 1014.71  5052.3 1019.59  5059.4 1019.35  5066.4 1021.69
  5137.1 1022.94  5277.5 1030.23  5533.2 1044.31  5745.4  1048.3  5798.3 1047.28
#Mann= 5 ,-1 , 0
  4419.9     .05       0    4834     .12       0  5007.4     .07       0
  5012.3     .12       0  5277.5     .05       0
Bank Sta=5007.4,5012.3
XS Rating Curve= 0 ,0
Exp/Cntr=0.3,0.1

Type RM Length L Ch R = 1 ,6859    ,448,448,448
BEGIN DESCRIPTION:
Upper Denton 61 15.0
END DESCRIPTION:
XS GIS Cut Line= 4
      2192232.26      7255602.82        2192179.        7255110.
      2192172.36      7255016.87      2191868.24      7254484.01
#Sta/Elev= 30
  4504.8 1044.68  4618.3 1039.46  4668.6  1035.4  4674.2 1037.86  4679.2 1035.31
  4688.7 1037.98  4718.9 1030.97    4749 1030.17    4766 1031.36  4809.4 1028.03
  4857.8 1026.93  4891.3 1024.45  4930.1 1020.96  4940.1  1017.8  4949.6 1009.78
  4954.6 1009.95  4987.9 1002.43  4988.5 1001.93    4993 1002.43    5003 1004.28
  5010.5 1016.62  5020.5 1019.73  5109.1 1018.73  5210.2  1020.1  5329.5  1023.7
  5372.7  1027.1  5469.2 1031.07    5593 1038.32  5620.4 1041.12  5707.4 1044.49
#Mann= 5 ,-1 , 0
  4504.8     .05       0  4891.3     .12       0  4987.9     .07       0
    4993     .12       0  5210.2     .05       0
Bank Sta=4987.9,4993
XS Rating Curve= 0 ,0
Exp/Cntr=0.3,0.1

Type RM Length L Ch R = 1 ,6411    ,433,433,433
BEGIN DESCRIPTION:
Upper Denton 61 14.0
END DESCRIPTION:
XS GIS Cut Line= 3
      2192538.68      7255604.58        2192529.        7254910.
        2192400.      7253753.11
#Sta/Elev= 30
  4309.9 1044.97  4364.5 1043.79  4394.5 1045.81  4444.5 1040.65  4614.5 1033.47
  4674.5 1027.82  4734.5  1027.4  4784.5 1022.17  4884.5 1017.08  4924.5 1017.74
  4954.5 1000.74  4962.7  999.76  4971.7  999.31  4972.6  998.81  4977.3  999.31
  4984.5 1000.31  4994.5 1005.43  5007.1 1005.33  5034.7 1000.04  5044.7 1002.22
  5049.7 1000.41  5054.9 1006.88    5075 1015.66  5144.3 1016.54  5262.4  1022.3
  5286.3 1020.63  5326.5 1026.43  5565.7 1038.26  5767.9 1046.08  6168.6 1055.42
#Mann= 7 ,-1 , 0
  4309.9     .05       0  4962.7     .12       0  4971.7     .07       0
  4977.3     .12       0  5144.3     .05       0  5262.4     .12       0
  5565.7     .05       0
Bank Sta=4971.7,4977.3
XS Rating Curve= 0 ,0
Exp/Cntr=0.3,0.1

Type RM Length L Ch R = 1 ,5978    ,467,467,467
BEGIN DESCRIPTION:
Upper Denton 61 13.0
END DESCRIPTION:
XS GIS Cut Line= 3
      2192964.03      7255417.89        2192929.        7254810.
       2192881.6      7253934.28
#Sta/Elev= 30
  4390.7 1038.92  4468.7 1037.91  4528.8 1033.52  4578.9 1033.12    4649 1027.52
  4729.2 1025.86  4769.2 1021.03  4829.3 1019.59  4889.4 1013.92  4929.5 1013.92
  4949.5 1005.06  4969.6 1001.48  4976.7  995.05  4977.6  994.55  4982.4  995.05
  4989.6   995.2  4997.1 1000.01  5002.1 1000.01  5009.6 1008.98  5019.6 1012.75
  5059.7  1011.9  5129.8 1016.76  5199.9 1017.68  5276.1 1022.49  5310.1 1026.71
  5390.2 1030.15  5440.2 1035.18  5661.3 1047.16  5710.6 1049.68  5876.6 1050.83
#Mann= 4 ,-1 , 0
  4390.7     .05       0  4976.7    .033       0  4982.4     .05       0
  5661.3     .12       0
Bank Sta=4976.7,4982.4
XS Rating Curve= 0 ,0
Exp/Cntr=0.3,0.1

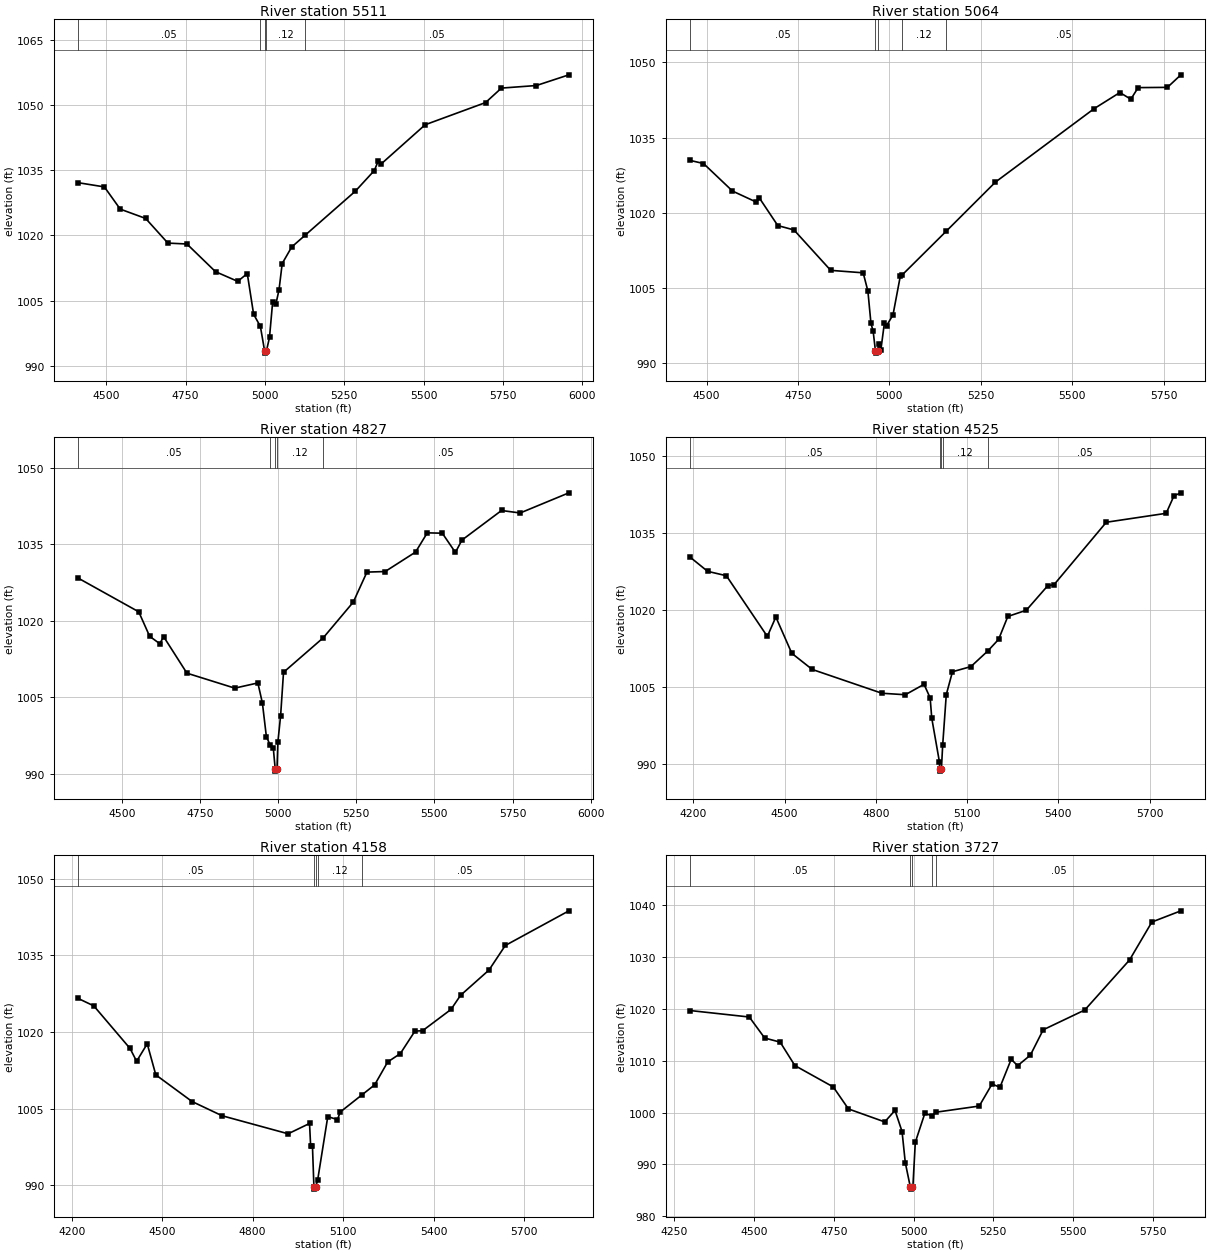
Type RM Length L Ch R = 1 ,5511    ,447,447,447
BEGIN DESCRIPTION:
Upper Denton 61 12.0
END DESCRIPTION:
XS GIS Cut Line= 3
      2193363.34      7255352.76        2193379.        7254760.
      2193419.76      7253807.64
#Sta/Elev= 30
  4411.5 1032.13  4494.3 1031.16  4544.3 1026.05  4624.3 1023.91  4694.4 1018.24
  4754.4 1018.03  4844.4 1011.67  4914.4 1009.44  4944.5 1011.24  4964.5 1001.87
  4985.8  999.08  4999.1  993.44    5000  992.94  5004.8  993.44  5014.5  996.55
  5024.5 1004.77  5034.5 1004.18  5044.5  1007.5  5054.5 1013.54  5084.5 1017.35
    5126    1020  5284.7 1030.16  5344.8 1034.93  5357.5  1037.2  5364.8 1036.34
  5504.9 1045.45  5695.1 1050.55  5745.1 1053.88  5855.2 1054.47  5957.7 1056.93
#Mann= 5 ,-1 , 0
  4411.5     .05       0  4985.8     .12       0  4999.1     .07       0
  5004.8     .12       0    5126     .05       0
Bank Sta=4999.1,5004.8
XS Rating Curve= 0 ,0
Exp/Cntr=0.3,0.1

Type RM Length L Ch R = 1 ,5064    ,237,237,237
BEGIN DESCRIPTION:
Upper Denton 61 11.0
END DESCRIPTION:
XS GIS Cut Line= 3
      2193493.54       7255374.5        2193779.        7254910.
      2193745.35      7254113.21
#Sta/Elev= 30
  4454.8 1030.48  4491.6 1029.86  4570.9 1024.37  4636.1 1022.17  4644.3    1023
  4694.8 1017.49    4739 1016.62  4839.6 1008.56  4928.4 1008.07  4941.3 1004.44
  4949.7  997.98  4955.6  996.48  4961.9  992.56  4962.8  992.06  4967.6  992.56
    4971  993.97  4976.9  992.76  4986.4  998.04  4992.3  997.51    5010  999.69
    5030 1007.42  5035.7 1007.69    5155 1016.32  5290.3 1026.16  5560.5 1040.81
  5630.6 1044.01  5660.6 1042.68  5680.6 1044.99  5760.7 1045.04  5797.5 1047.54
#Mann= 5 ,-1 , 0
  4454.8     .05       0  4961.9    .033       0  4967.6     .05       0
  5035.7     .12       0    5155     .05       0
Bank Sta=4961.9,4967.6
XS Rating Curve= 0 ,0
Exp/Cntr=0.3,0.1

Type RM Length L Ch R = 1 ,4827    ,302,302,302
BEGIN DESCRIPTION:
Upper Denton 61 10.5
END DESCRIPTION:
XS GIS Cut Line= 5
       2193529.1      7255383.21      2193862.47      7255199.16
      2194004.69      7254962.08      2194105.52      7254754.71
       2194309.9      7254103.48
#Sta/Elev= 30
  4359.9  1028.4    4554 1021.77  4588.9 1016.96    4621 1015.52  4633.9 1016.86
  4708.1 1009.72  4861.2 1006.78  4935.1  1007.8  4949.6 1003.86  4962.3  997.28
  4974.2  995.62  4984.6  994.93  4990.5  990.98  4991.4  990.48  4996.4  990.98
  4999.2   996.2  5007.9 1001.37  5017.2 1009.89  5144.5 1016.68  5240.3 1023.67
  5284.1 1029.57  5342.3 1029.68  5439.6  1033.5  5477.2 1037.28  5525.2 1037.21
  5567.1 1033.44  5588.1 1035.86  5714.7 1041.67  5774.3 1041.18  5930.3 1045.14
#Mann= 5 ,-1 , 0
  4359.9     .05       0  4974.2     .12       0  4990.5     .07       0
  4996.4     .12       0  5144.5     .05       0
Bank Sta=4990.5,4996.4
XS Rating Curve= 0 ,0
Exp/Cntr=0.3,0.1

Type RM Length L Ch R = 1 ,4525    ,367,367,367
BEGIN DESCRIPTION:
Upper Denton 61 10.0
END DESCRIPTION:
XS GIS Cut Line= 4
      2193879.83      7255899.67       2194114.2      7255426.59
      2194214.03      7255148.81      2194331.21      7254367.57
#Sta/Elev= 30
  4189.4 1030.23  4247.1 1027.46  4308.8  1026.6  4443.4 1014.78  4471.4 1018.56
  4523.8 1011.49  4590.8 1008.35    4820 1003.71  4896.9 1003.42  4958.4 1005.45
  4978.5 1002.81  4983.8  998.85  5009.2  990.27  5009.4  989.04  5010.4  988.54
  5015.6  989.04  5019.7  993.61  5031.5 1003.44  5051.8  1007.9  5112.4  1008.9
  5168.4 1011.97  5203.4  1014.2  5233.8 1018.67  5294.5 1019.88  5365.2 1024.67
  5385.5 1024.85  5557.4 1037.02  5754.2 1038.76  5779.8 1042.17  5802.5 1042.75
#Mann= 5 ,-1 , 0
  4189.4     .05       0  5009.4    .033       0  5015.6     .05       0
  5019.7     .12       0  5168.4     .05       0
Bank Sta=5009.4,5015.6
XS Rating Curve= 0 ,0
Exp/Cntr=0.3,0.1

Type RM Length L Ch R = 1 ,4158    ,431,431,431
BEGIN DESCRIPTION:
Upper Denton 61 9.0
END DESCRIPTION:
XS GIS Cut Line= 3
      2194011.79      7255886.63        2194529.        7255310.
      2194789.55      7254497.77
#Sta/Elev= 30
  4221.3 1026.57  4273.4 1025.11  4393.7 1016.77  4415.4 1014.27  4450.6 1017.69
    4479 1011.61  4599.3 1006.39  4698.8 1003.61  4917.8 1000.08  4988.8  1002.1
  4992.5  997.67  4998.5  997.67  5003.3  989.75  5004.3  989.25  5009.6  989.75
  5015.7  991.02  5049.3 1003.44  5081.5 1002.86  5090.4 1004.33  5161.2 1007.63
  5204.7 1009.65  5247.9 1014.13    5290 1015.78  5338.4 1020.18  5363.5 1020.24
    5458 1024.42  5489.5 1027.17    5584 1032.13    5638 1036.93  5848.9 1043.71
#Mann= 5 ,-1 , 0
  4221.3     .05       0  5003.3    .033       0  5009.6     .05       0
  5015.7     .12       0  5161.2     .05       0
Bank Sta=5003.3,5009.6
XS Rating Curve= 0 ,0
Exp/Cntr=0.3,0.1

Type RM Length L Ch R = 1 ,3727    ,363,363,363
BEGIN DESCRIPTION:
Upper Denton 61 8.0
END DESCRIPTION:
XS GIS Cut Line= 3
      2194668.01      7256122.81        2194879.        7255460.
      2194924.96      7254619.34
#Sta/Elev= 30
    4300 1019.69  4485.6 1018.44  4533.8 1014.38  4582.3 1013.59  4628.3 1009.07
  4748.6 1004.94  4796.2 1000.69  4909.8  998.19    4942 1000.41  4964.1  996.33
  4974.2  990.34  4989.7  985.71  4990.8  985.21  4996.2  985.71  4998.1  985.71
  5005.6  994.25  5035.6  999.87    5057  999.37  5070.4 1000.06  5205.9 1001.25
    5246  1005.5  5270.7 1004.87    5306 1010.28  5326.1 1009.04  5366.1 1011.08
  5406.2 1015.97  5536.4 1019.79  5676.6 1029.44  5746.7 1036.78  5837.5 1038.94
#Mann= 5 ,-1 , 0
    4300     .05       0  4989.7    .033       0  4996.2     .05       0
    5057     .12       0  5070.4     .05       0
Bank Sta=4989.7,4996.2
XS Rating Curve= 0 ,0
Exp/Cntr=0.3,0.1

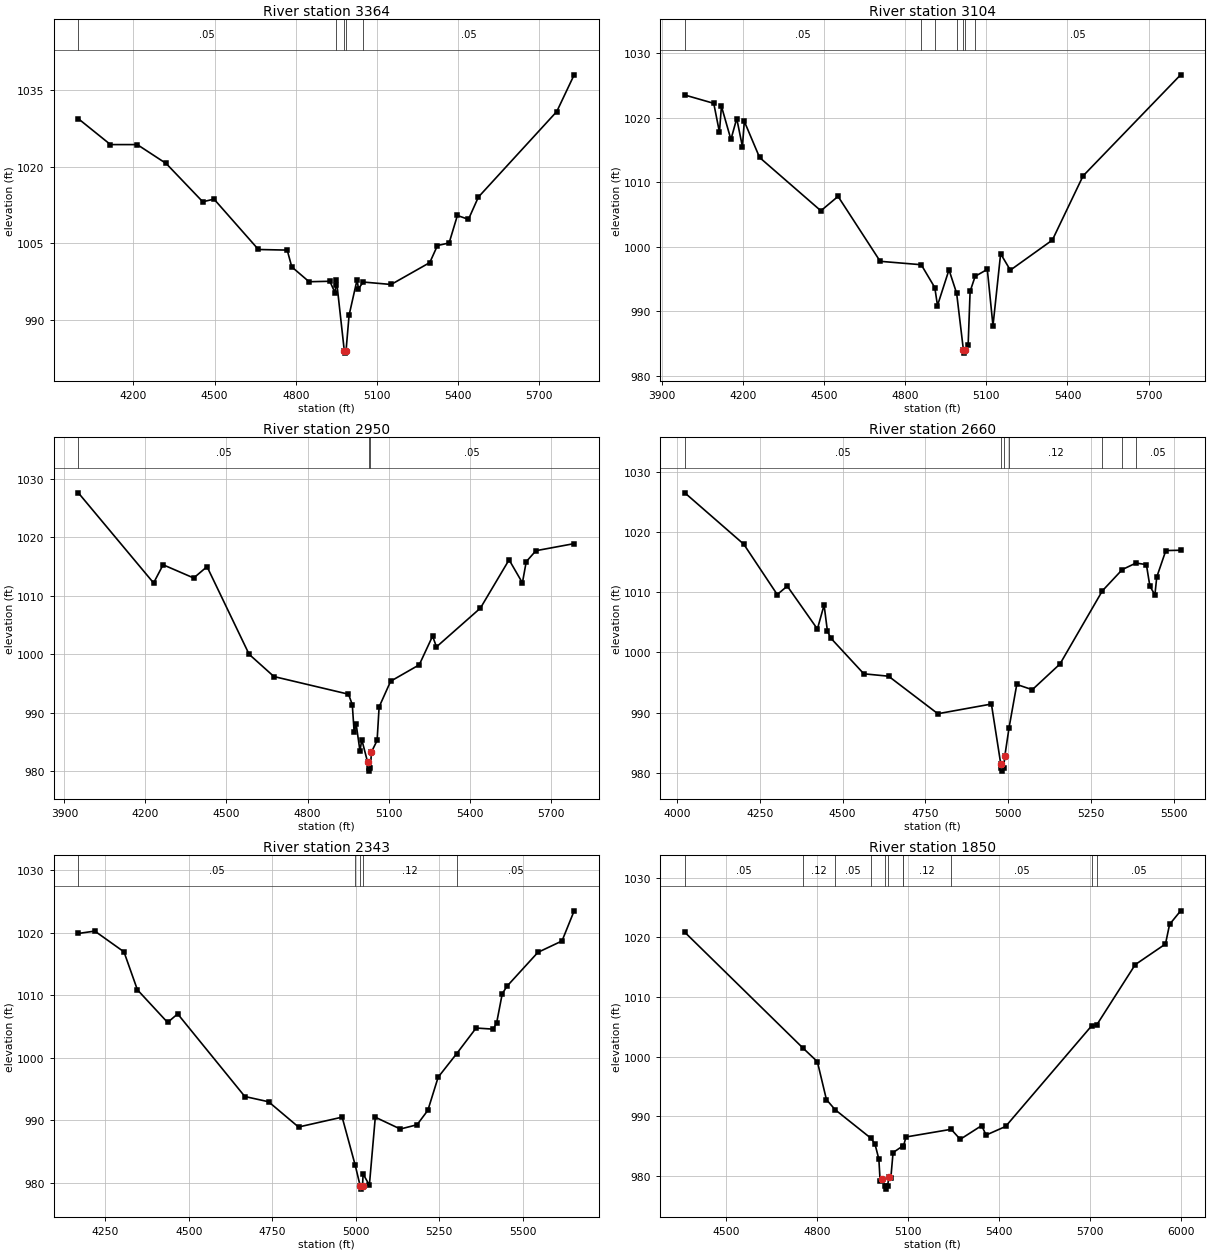
Type RM Length L Ch R = 1 ,3364    ,260,260,260
BEGIN DESCRIPTION:
Upper Denton 61 7.0
END DESCRIPTION:
XS GIS Cut Line= 4
      2194647.21      7256275.52      2195136.77      7255685.27
      2195209.69      7255459.57      2195043.01      7254647.03
#Sta/Elev= 30
  3996.1 1029.43    4115 1024.35    4214 1024.35  4320.8 1020.64  4456.2 1013.12
  4497.9 1013.64    4662 1003.75  4768.5 1003.63  4785.4 1000.33  4849.4  997.42
  4926.1  997.51  4945.5  995.24  4948.8  996.81  4950.7  997.72  4979.5   983.9
  4980.6   983.4  4986.1   983.9  4997.3  990.84  5026.8  997.81  5031.9  996.05
  5049.9  997.36  5152.8  996.88  5295.7 1001.18  5324.1 1004.53  5367.2 1005.03
  5397.8 1010.43  5438.7 1009.67  5475.4 1014.04  5765.3 1030.84  5829.6 1038.05
#Mann= 5 ,-1 , 0
  3996.1     .05       0  4948.8     .12       0  4979.5     .07       0
  4986.1     .12       0  5049.9     .05       0
Bank Sta=4979.5,4986.1
XS Rating Curve= 0 ,0
Exp/Cntr=0.3,0.1

Type RM Length L Ch R = 1 ,3104    ,154,154,154
BEGIN DESCRIPTION:
Upper Denton 61 6.5
END DESCRIPTION:
XS GIS Cut Line= 3
       2194758.3      7256150.55      2195487.47      7255372.77
      2196003.69      7254804.58
#Sta/Elev= 30
  3984.6  1023.5  4091.7 1022.21  4112.7 1017.75  4120.1 1021.76  4155.2 1016.61
  4176.7 1019.86  4197.7  1015.5  4204.7 1019.42  4261.2 1013.82  4487.9 1005.56
  4551.4 1007.79  4707.2  997.73  4859.1   997.2  4909.2  993.66  4919.2  990.88
  4961.7  996.41    4990  992.78    5015     984  5016.1   983.5  5021.6     984
  5032.5  984.74  5039.8  993.06  5058.4   995.4  5103.4  996.48  5124.4  987.74
  5152.7   998.9  5188.6  996.36    5344 1001.02  5457.5 1010.96  5818.4 1026.63
#Mann= 7 ,-1 , 0
  3984.6     .05       0  4859.1     .12       0  4909.2     .05       0
    4990     .12       0    5015     .07       0  5021.6     .12       0
  5058.4     .05       0
Bank Sta=5015,5021.6
XS Rating Curve= 0 ,0
Exp/Cntr=0.3,0.1

Type RM Length L Ch R = 1 ,2950    ,290,290,290
BEGIN DESCRIPTION:
Upper Denton 61 6.4
END DESCRIPTION:
XS GIS Cut Line= 3
      2194890.26      7256174.83      2195619.41      7255397.07
      2196136.79      7254827.61
#Sta/Elev= 30
  3951.6 1027.62  4230.2  1012.2  4265.4 1015.31  4378.7 1013.05    4428 1014.99
  4583.8    1000  4675.7  996.19  4951.7  993.17  4965.8  991.39  4972.7  986.63
    4980  988.09  4994.1  983.48    5001  985.38  5022.5  981.55  5025.8  980.51
  5026.9  980.01  5032.8  980.51  5036.7  983.28  5057.6  985.25  5065.1  990.99
  5107.7  995.39  5213.7   998.2  5263.1 1003.12  5277.3 1001.26  5440.1  1007.9
  5546.2 1016.16  5595.5 1012.22  5609.7 1015.84  5645.6 1017.72  5787.1 1018.93
#Mann= 3 ,-1 , 0
  3951.6     .05       0  5025.8    .033       0  5032.8     .05       0
Bank Sta=5022.5,5036.7
XS Rating Curve= 0 ,0
Exp/Cntr=0.3,0.1

Type RM Length L Ch R = 1 ,2660    ,317,317,317
BEGIN DESCRIPTION:
Upper Denton 61 6.0
END DESCRIPTION:
XS GIS Cut Line= 3
      2195754.83      7256376.22      2195897.19      7255407.49
      2196046.49      7254910.99
#Sta/Elev= 30
  4023.4 1026.51  4201.5 1017.98  4302.6 1009.62  4332.9 1011.02  4423.9  1003.9
  4444.1 1007.88  4454.2 1003.54  4464.3 1002.39  4564.1  996.46  4638.9  996.06
  4787.7  989.83  4949.5  991.44  4977.7   981.5  4979.2   980.8  4980.3   980.3
  4986.2   980.8  4989.9  982.78  5002.9  987.54  5026.1  994.69    5073  993.82
  5156.6  998.09  5284.7 1010.24  5344.8 1013.77  5386.1 1014.85  5417.6 1014.59
  5428.1 1011.03  5443.3 1009.56  5448.9 1012.52  5476.3 1016.92    5521 1016.98
#Mann= 7 ,-1 , 0
  4023.4     .05       0  4979.2    .033       0  4986.2     .05       0
  5002.9     .12       0  5284.7     .05       0  5344.8     .12       0
  5386.1     .05       0
Bank Sta=4977.7,4989.9
XS Rating Curve= 0 ,0
Exp/Cntr=0.3,0.1

Type RM Length L Ch R = 1 ,2343    ,493,493,493
BEGIN DESCRIPTION:
Upper Denton 61 5.0
END DESCRIPTION:
XS GIS Cut Line= 3
      2196119.41      7256285.94      2196199.27      7255463.05
      2196043.13      7254824.62
#Sta/Elev= 30
  4169.5 1019.86  4218.8 1020.24  4306.1 1016.92  4346.3 1010.85  4436.7 1005.63
  4466.8    1007  4667.8  993.79  4738.9  992.95  4828.5  988.91  4959.1  990.49
  4998.3  982.78  5013.1  979.48  5014.2  978.98  5020.1  979.48  5021.8   981.4
  5040.6  979.62  5058.3  990.48  5133.2  988.59  5183.2  989.27  5215.6  991.58
  5246.5  996.88  5302.1 1000.66    5360 1004.74  5411.2 1004.56  5421.5 1005.56
  5438.2 1010.21  5452.4 1011.42    5545 1016.84  5617.1 1018.66  5653.5 1023.48
#Mann= 5 ,-1 , 0
  4169.5     .05       0  4998.3     .12       0  5013.1     .07       0
  5020.1     .12       0  5302.1     .05       0
Bank Sta=5013.1,5020.1
XS Rating Curve= 0 ,0
Exp/Cntr=0.3,0.1

Type RM Length L Ch R = 1 ,1850    ,452,452,452
BEGIN DESCRIPTION:
Upper Denton 61 4.0
END DESCRIPTION:
XS GIS Cut Line= 3
      2196643.72      7256247.81        2196629.        7255610.
      2196028.99      7254809.99
#Sta/Elev= 30
  4362.4 1020.88  4751.7 1001.48  4800.3  999.15  4830.3  992.77  4858.9  991.08
    4977  986.29  4990.4  985.35  5003.5  982.77  5007.7  979.08  5013.9  979.42
  5024.9  978.23  5026.1  977.73  5032.1  978.23  5036.8  979.76  5043.1  979.64
  5050.4  983.87  5083.5  985.01  5084.3  984.85  5093.1  986.49  5242.4  987.78
  5272.3   986.1  5343.1   988.4  5357.7  986.81  5422.3  988.26  5706.4 1005.16
  5723.2 1005.31  5850.4 1015.44  5950.4 1018.91  5963.9  1022.2  6000.4 1024.48
#Mann= 11 ,-1 , 0
  4362.4     .05       0  4751.7     .12       0  4858.9     .05       0
    4977     .12       0  5024.9     .07       0  5032.1     .12       0
  5083.5     .05       0  5084.3     .12       0  5242.4     .05       0
  5706.4     .12       0  5723.2     .05       0
Bank Sta=5013.9,5036.8
XS Rating Curve= 0 ,0
Exp/Cntr=0.3,0.1

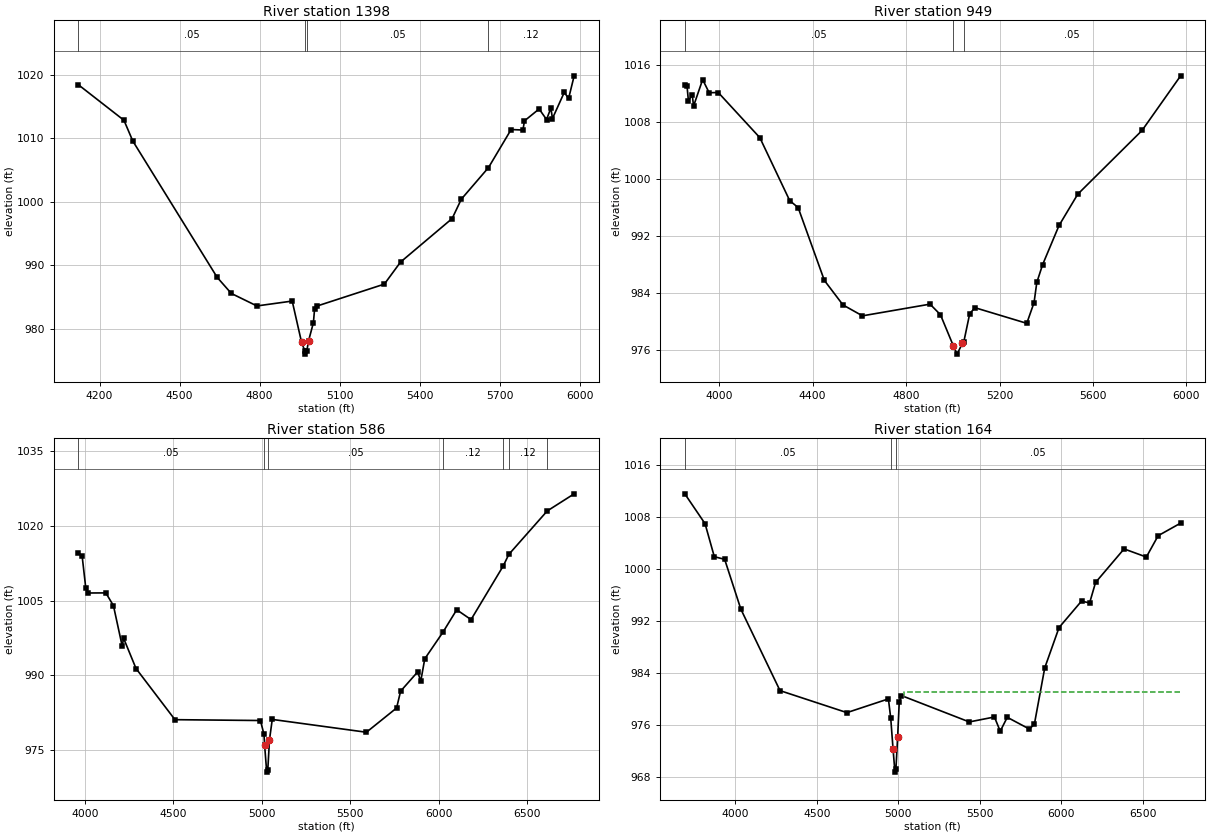
Type RM Length L Ch R = 1 ,1398    ,449,449,449
BEGIN DESCRIPTION:
Upper Denton 61 3.0
END DESCRIPTION:
XS GIS Cut Line= 4
      2196786.09      7256219.96      2196994.41      7255511.66
      2196963.16      7255365.82      2196515.33      7254504.88
#Sta/Elev= 30
  4120.6 1018.42  4291.5 1012.82  4324.8 1009.54  4640.7  988.08  4693.9  985.54
  4789.7  983.57    4922  984.34    4957  977.85  4969.4  976.48  4970.6  975.98
  4976.7  976.48  4983.3  978.08  5001.4  980.92    5006  983.16  5014.6  983.55
  5267.3  987.01  5327.9  990.48  5521.3  997.34  5555.7 1000.39  5657.4 1005.36
  5742.3 1011.36  5786.5 1011.28  5792.4 1012.73  5847.2  1014.6    5875 1012.94
  5891.4 1014.75  5897.1 1013.09  5941.3  1017.2  5957.8 1016.27  5978.5 1019.82
#Mann= 4 ,-1 , 0
  4120.6     .05       0  4969.4    .033       0  4976.7     .05       0
  5657.4     .12       0
Bank Sta=4957,4983.3
XS Rating Curve= 0 ,0
Exp/Cntr=0.3,0.1

Type RM Length L Ch R = 1 ,949     ,363,363,363
BEGIN DESCRIPTION:
Upper Denton 61 2.0
END DESCRIPTION:
XS GIS Cut Line= 3
      2196859.01      7256282.46        2197379.        7255260.
       2197060.4      7254338.09
#Sta/Elev= 30
  3852.8 1013.13  3862.5 1012.97  3868.1 1010.96  3884.7 1011.77  3890.3  1010.2
  3929.2 1013.91  3957.1 1012.07    3996  1012.1    4174 1005.77  4301.9  996.94
    4338  995.96  4450.2  985.75  4529.9  982.31  4613.3  980.78  4902.6  982.42
  4947.1  980.94  5002.5  976.56  5018.5  975.41  5041.4  976.95  5046.7  977.06
  5072.5  981.09  5095.1  981.92  5316.7  979.73  5347.9  982.64  5359.6  985.46
  5384.3  987.94  5454.8  993.45  5534.9  997.84  5810.2 1006.78  5975.3 1014.44
#Mann= 3 ,-1 , 0
  3852.8     .05       0  5002.5    .033       0  5046.7     .05       0
Bank Sta=5002.5,5041.4
XS Rating Curve= 0 ,0
Exp/Cntr=0.3,0.1

Type RM Length L Ch R = 1 ,586     ,422,422,422
BEGIN DESCRIPTION:
Upper Denton 61 1.0
END DESCRIPTION:
XS GIS Cut Line= 4
      2196979.03      7256259.97      2197643.72      7255452.63
      2197716.63      7255285.96      2197044.76      7253858.89
#Sta/Elev= 30
    3962 1014.53  3983.5 1013.94  4004.3 1007.45  4018.6 1006.52  4117.6 1006.54
  4160.7 1003.98  4210.2  995.87    4218  997.46  4288.4  991.39  4508.6  981.14
  4992.1  980.97  5012.3   978.2 5015.87  976.02  5027.7  970.63  5033.9  971.13
  5043.4  977.12  5059.1  981.19  5591.8  978.62  5762.4  983.48  5785.2  986.85
  5881.9  990.72  5899.1  988.85  5921.9  993.34  6024.6  998.66  6102.6 1003.16
  6183.7 1001.19  6365.8 1011.94  6397.1 1014.24  6614.7 1022.96    6767 1026.39
#Mann= 7 ,-1 , 0
    3962     .05       0  5012.3    .033       0  5033.9     .05       0
  6024.6     .12       0  6365.8     .05       0  6397.1     .12       0
  6614.7     .05       0
Bank Sta=5015.87,5043.4
XS Rating Curve= 0 ,0
Exp/Cntr=0.3,0.1

Type RM Length L Ch R = 1 ,164     ,0,0,0
BEGIN DESCRIPTION:
Upper Denton 61 0.5
END DESCRIPTION:
XS GIS Cut Line= 3
      2196963.14      7256549.87      2197935.38      7255660.96
      2198867.65      7254207.87
#Sta/Elev= 30
  3689.2 1011.55  3813.6 1006.96  3870.4 1001.89  3933.9 1001.49  4033.2  993.84
  4273.7  981.32  4684.4  977.94  4939.1  980.05  4953.3  977.11  4967.5   972.4
  4979.2   968.8  4985.3   969.3  4995.9   974.2  5005.6  979.55  5018.1  980.57
  5435.6  976.51  5589.9  977.27  5625.5  975.09  5668.9  977.22    5805  975.41
  5835.4  976.19  5898.8  984.81  5986.7  991.01  6124.5  995.07  6174.3  994.79
  6210.7  997.93  6385.9 1003.09  6522.5 1001.84  6595.2 1005.12    6733 1007.05
#Mann= 3 ,-1 , 0
  3689.2     .05       0  4953.3    .033       0  4985.3     .05       0
#XS Ineff= 2 , 0
                         5034.64          981.05
Permanent Ineff=
       F       F
Bank Sta=4967.5,4995.9
XS Rating Curve= 0 ,0
Exp/Cntr=0.3,0.1

Chan Stop Cuts=-1
Use User Specified Reach Order=0
Composite Channel Slope=5