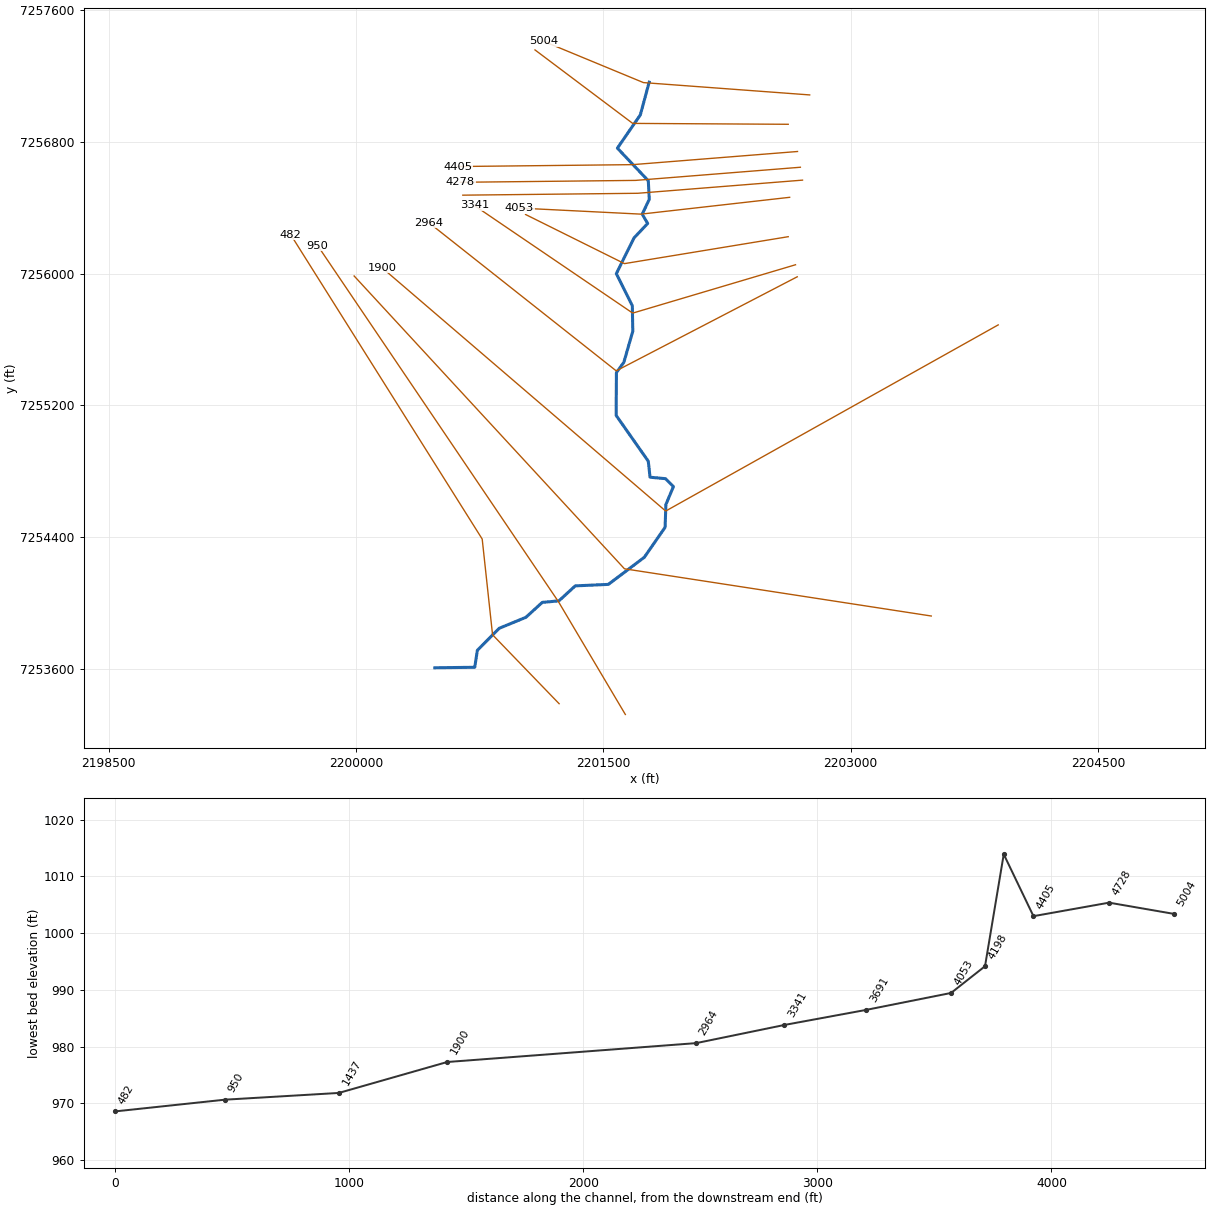
--- Upper Denton 62.prj (project) ---

Proj Title=Upper Denton 62 Base Level Engineering
Current Plan=p01
Default Exp/Contr=0.3,0.1
English Units
Geom File=g01
Flow File=f01
Plan File=p01
BEGIN DESCRIPTION:
Upper Denton 62
END DESCRIPTION:

--- Upper Denton 62.p01 (plan) ---

Plan Title=Multiple Run
Short Identifier=Multiple
Geom File=g01
Flow File=f01
Subcritical Flow
K Sum by GR= 0
Std Step Tol= 0.01
Critical Tol= 0.01
Num of Std Step Trials= 20
Max Error Tol= 0.3
Flow Tol Ratio= 0.001
Split Flow NTrial= 30
Split Flow Tol= 0.02
Split Flow Ratio= 0.02
Log Output Level= 0
Friction Slope Method= 1
Unsteady Friction Slope Method= 2
Unsteady Bridges Friction Slope Method= 1
Parabolic Critical Depth
Global Vel Dist=  1 , 1 , 1
Global Log Level= 0
CheckData=True
Encroach Param= -1, 0, 0, 0
BEGIN DESCRIPTION:
Multiple Run
END DESCRIPTION:

--- Upper Denton 62.f01 (steady flow) ---

Flow Title=Multiple
Number of Profiles=7
Profile Names=10-year,25-year,50-year,1pct_min,100-year,1pct_plu,500-year
River Rch & RM= Upper Denton 62,Reach-1,5004
     632     875    1078     660    1317    2627    1968
River Rch & RM= Upper Denton 62,Reach-1,1437
     619     860    1060     649    1294    2583    1938
Boundary for River Rch & Prof#=Upper Denton 62,Reach-1,1
Up Type=0
Dn Type=3
Dn Slope=0.005
Boundary for River Rch & Prof#=Upper Denton 62,Reach-1,2
Up Type=0
Dn Type=3
Dn Slope=0.005
Boundary for River Rch & Prof#=Upper Denton 62,Reach-1,3
Up Type=0
Dn Type=3
Dn Slope=0.005
Boundary for River Rch & Prof#=Upper Denton 62,Reach-1,4
Up Type=0
Dn Type=3
Dn Slope=0.005
Boundary for River Rch & Prof#=Upper Denton 62,Reach-1,5
Up Type=0
Dn Type=3
Dn Slope=0.005
Boundary for River Rch & Prof#=Upper Denton 62,Reach-1,6
Up Type=0
Dn Type=3
Dn Slope=0.005
Boundary for River Rch & Prof#=Upper Denton 62,Reach-1,7
Up Type=0
Dn Type=3
Dn Slope=0.005

--- Upper Denton 62.g01 (geometry) ---

Geom Title=Existing Conditions

River Reach=Upper Denton 62,Reach-1
Reach XY= 30
      2201779.00      7257160.00      2201725.18      7256961.58
      2201586.08      7256760.00      2201773.55      7256562.45
      2201779.46      7256449.81      2201736.81      7256359.90
      2201769.69      7256303.34      2201687.18      7256216.06
      2201579.74      7255999.31      2201676.76      7255804.07
      2201679.46      7255649.82      2201625.14      7255461.60
      2201580.22      7255399.50      2201578.62      7255139.63
      2201773.44      7254862.36      2201784.11      7254765.11
      2201877.70      7254756.44      2201925.97      7254708.61
      2201880.25      7254599.50      2201875.45      7254461.47
      2201749.42      7254279.77      2201531.45      7254115.47
      2201330.47      7254106.45      2201231.42      7254015.54
      2201130.50      7254006.37      2201031.29      7253915.85
      2200869.32      7253849.24      2200736.88      7253716.12
      2200721.03      7253612.93      2200479.00      7253610.00

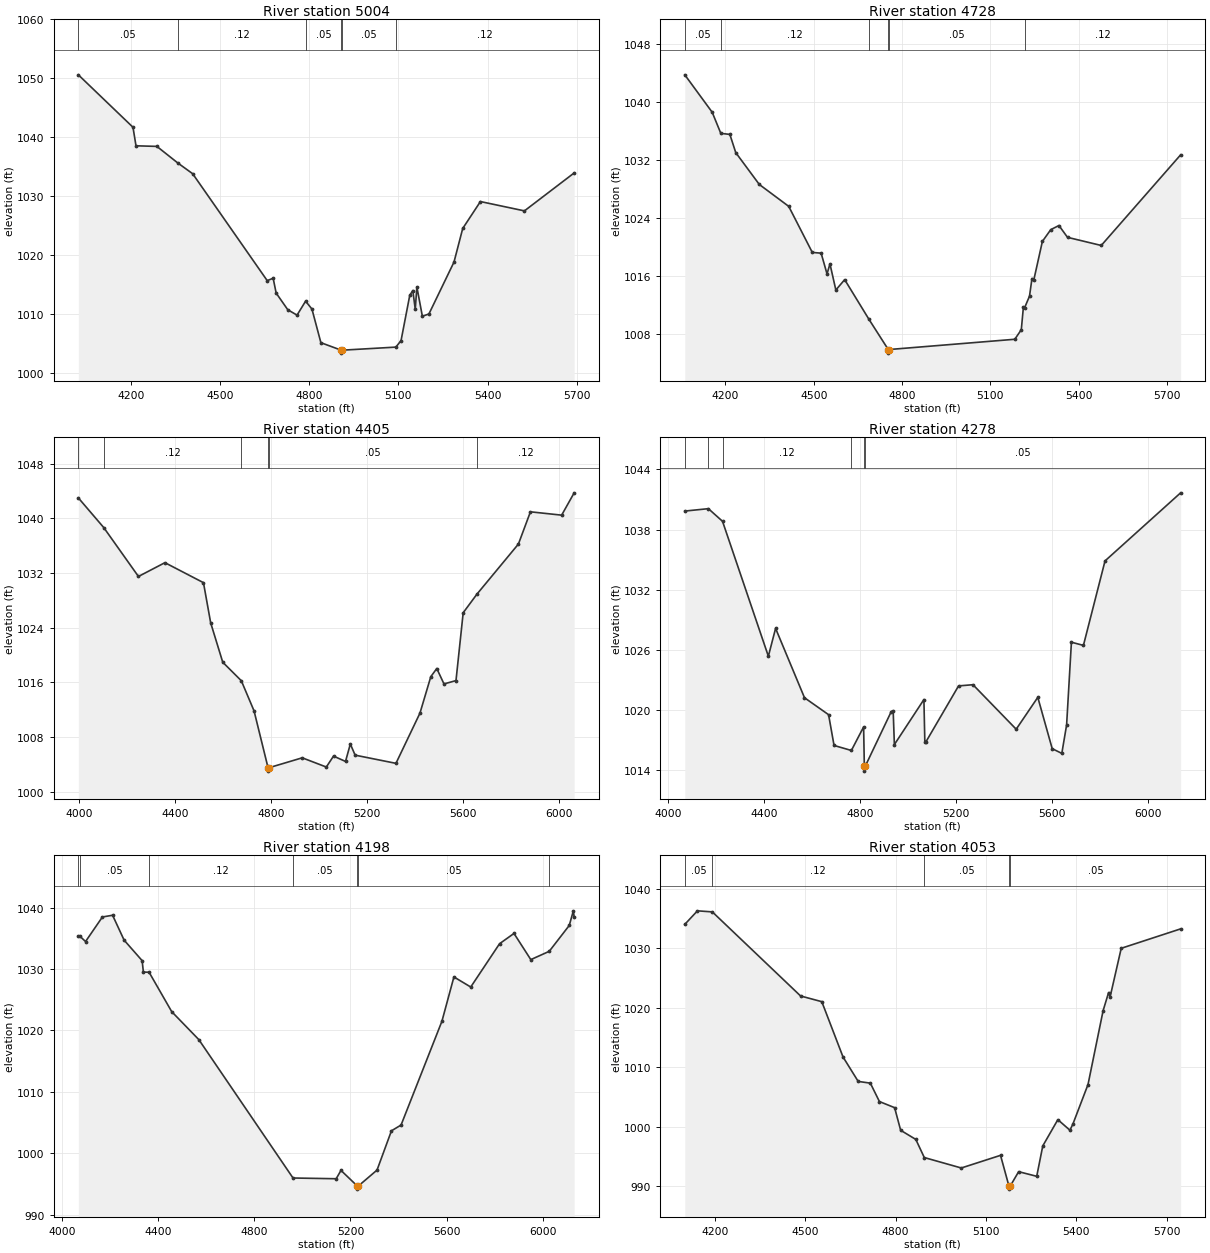
Type RM Length L Ch R = 1,5004,276,276,276
BEGIN DESCRIPTION:
Upper Denton 62 10.5
END DESCRIPTION:
XS GIS Cut Line= 3
      2202752.34      7257082.61      2201744.10      7257157.40
      2201137.71      7257408.14
#Sta/Elev= 30
  4024.1 1050.58  4207.9 1041.69  4218.0 1038.55  4288.2 1038.45  4358.8 1035.63
  4408.5 1033.82  4659.2 1015.70  4679.2 1016.10  4689.3 1013.59  4728.4 1010.76
  4759.5 1009.85  4788.3 1012.22  4809.6 1010.88  4839.7 1005.18  4907.9 1003.91
  4908.1 1003.41  4911.9 1003.91  5091.7 1004.43  5109.2 1005.53  5138.5 1013.20
  5148.8 1014.02  5157.0 1010.85  5162.4 1014.63  5180.9 1009.66  5203.0 1010.05
  5287.3 1018.85  5316.6 1024.54  5376.1 1029.10  5524.1 1027.52  5691.3 1033.95
#Mann=6,-1,0
  4024.1    0.05       0  4358.8    0.12       0  4788.3    0.05       0
  4907.9   0.033       0  4911.9    0.05       0  5091.7    0.12       0
Bank Sta=4907.9,4911.9
Exp/Cntr=0.3,0.1

Type RM Length L Ch R = 1,4728,323,323,323
BEGIN DESCRIPTION:
Upper Denton 62 10.0
END DESCRIPTION:
XS GIS Cut Line= 3
      2202622.14      7256904.66      2201679.00      7256910.00
      2201086.34      7257355.53
#Sta/Elev= 30
  4061.9 1043.74  4155.0 1038.58  4184.3 1035.67  4215.0 1035.53  4235.0 1033.02
  4315.0 1028.63  4415.0 1025.61  4495.1 1019.26  4525.1 1019.16  4545.1 1016.30
  4555.1 1017.68  4575.1 1014.08  4605.1 1015.51  4687.9 1010.02  4753.1 1005.88
  4753.3 1005.38  4757.1 1005.88  5183.1 1007.29  5205.2 1008.61  5212.3 1011.72
  5216.2 1011.61  5233.1 1013.24  5241.4 1015.66  5247.7 1015.47  5276.8 1020.78
  5305.3 1022.40  5333.1 1022.97  5362.2 1021.34  5476.8 1020.22  5746.5 1032.71
#Mann=6,-1,0
  4061.9    0.05       0  4184.3    0.12       0  4687.9    0.05       0
  4753.1   0.033       0  4757.1    0.05       0  5216.2    0.12       0
Bank Sta=4753.1,4757.1
Exp/Cntr=0.3,0.1

Type RM Length L Ch R = 1,4405,127,127,127
BEGIN DESCRIPTION:
Upper Denton 62 9.0
END DESCRIPTION:
XS GIS Cut Line= 3
      2202678.50      7256739.73      2201679.00      7256660.00
      2200616.93      7256648.58
#Sta/Elev= 30
  3997.3 1043.02  4103.4 1038.66  4247.6 1031.51  4357.9 1033.53  4518.4 1030.60
  4548.5 1024.71  4598.7 1018.95  4676.0 1016.24  4729.1 1011.82  4787.3 1003.50
  4787.6 1003.00  4791.3 1003.50  4929.7 1004.95  5030.0 1003.60  5060.0 1005.20
  5110.0 1004.42  5130.0 1006.97  5150.0 1005.34  5320.0 1004.14  5420.0 1011.50
  5465.1 1016.83  5490.0 1018.03  5520.0 1015.77  5570.0 1016.26  5600.0 1026.20
  5657.7 1028.94  5830.0 1036.26  5880.0 1040.98  6010.0 1040.49  6062.1 1043.76
#Mann=6,-1,0
  3997.3    0.05       0  4103.4    0.12       0  4676.0    0.05       0
  4787.3   0.033       0  4791.3    0.05       0  5657.7    0.12       0
Bank Sta=4787.3,4791.3
Exp/Cntr=0.3,0.1

Type RM Length L Ch R = 1,4278,80,80,80
BEGIN DESCRIPTION:
Upper Denton 62 8.5
END DESCRIPTION:
XS GIS Cut Line= 3
      2202695.92      7256644.25      2201696.36      7256564.51
      2200634.26      7256553.10
#Sta/Elev= 30
  4069.3 1039.85  4167.5 1040.09  4226.4 1038.83  4417.3 1025.37  4447.4 1028.15
  4567.8 1021.23  4668.1 1019.54  4690.9 1016.47  4763.0 1015.97  4814.0 1018.32
  4817.0 1014.41  4817.2 1013.91  4821.0 1014.41  4928.9 1019.84  4937.1 1019.94
  4942.1 1016.56  5065.1 1021.05  5069.0 1016.77  5072.0 1016.77  5209.4 1022.41
  5269.4 1022.53  5449.4 1018.09  5539.4 1021.27  5599.4 1016.15  5639.4 1015.68
  5659.4 1018.52  5679.4 1026.77  5729.4 1026.45  5819.4 1034.88  6134.2 1041.67
#Mann=6,-1,0
  4069.3    0.12       0  4167.5    0.05       0  4226.4    0.12       0
  4763.0    0.05       0  4817.0   0.033       0  4821.0    0.05       0
Bank Sta=4817,4821
Exp/Cntr=0.3,0.1

Type RM Length L Ch R = 1,4198,145,145,145
BEGIN DESCRIPTION:
Upper Denton 62 8.4
END DESCRIPTION:
XS GIS Cut Line= 3
      2202708.88      7256566.12      2201709.38      7256486.39
      2200648.62      7256474.99
#Sta/Elev= 30
  4067.6 1035.36  4074.3 1035.33  4097.6 1034.47  4167.8 1038.47  4210.2 1038.75
  4258.1 1034.70  4333.2 1031.36  4338.3 1029.50  4362.0 1029.48  4456.3 1023.06
  4569.1 1018.51  4961.0  995.99  5140.7  995.87  5160.7  997.23  5228.7  994.68
  5228.9  994.18  5232.7  994.68  5310.7  997.28  5370.7 1003.67  5410.7 1004.61
  5580.7 1021.49  5630.7 1028.71  5700.7 1027.07  5820.7 1034.12  5880.7 1035.79
  5950.7 1031.53  6027.4 1032.88  6110.7 1037.09  6127.8 1039.47  6131.1 1038.45
#Mann=7,-1,0
  4067.6    0.12       0  4074.3    0.05       0  4362.0    0.12       0
  4961.0    0.05       0  5228.7   0.033       0  5232.7    0.05       0
  6027.4    0.12       0
Bank Sta=5228.7,5232.7
Exp/Cntr=0.3,0.1

Type RM Length L Ch R = 1,4053,362,362,362
BEGIN DESCRIPTION:
Upper Denton 62 8.0
END DESCRIPTION:
XS GIS Cut Line= 3
      2202630.76      7256461.95      2201729.00      7256360.00
      2200992.12      7256396.75
#Sta/Elev= 30
  4100.5 1034.06  4142.5 1036.34  4191.9 1036.16  4484.7 1022.00  4555.1 1021.04
  4625.6 1011.72  4675.9 1007.61  4716.2 1007.32  4746.3 1004.22  4796.7 1003.19
  4816.8  999.38  4867.1  997.84  4895.2  994.79  5018.0  993.03  5148.2  995.16
  5176.2  989.97  5176.5  989.47  5180.2  989.97  5208.3  992.41  5268.3  991.63
  5288.4  996.75  5338.4 1001.17  5378.5  999.39  5388.5 1000.45  5438.5 1007.09
  5488.6 1019.53  5506.8 1022.58  5511.8 1021.84  5548.7 1030.03  5745.8 1033.30
#Mann=5,-1,0
  4100.5    0.05       0  4191.9    0.12       0  4895.2    0.05       0
  5176.2   0.033       0  5180.2    0.05       0
Bank Sta=5176.2,5180.2
Exp/Cntr=0.3,0.1

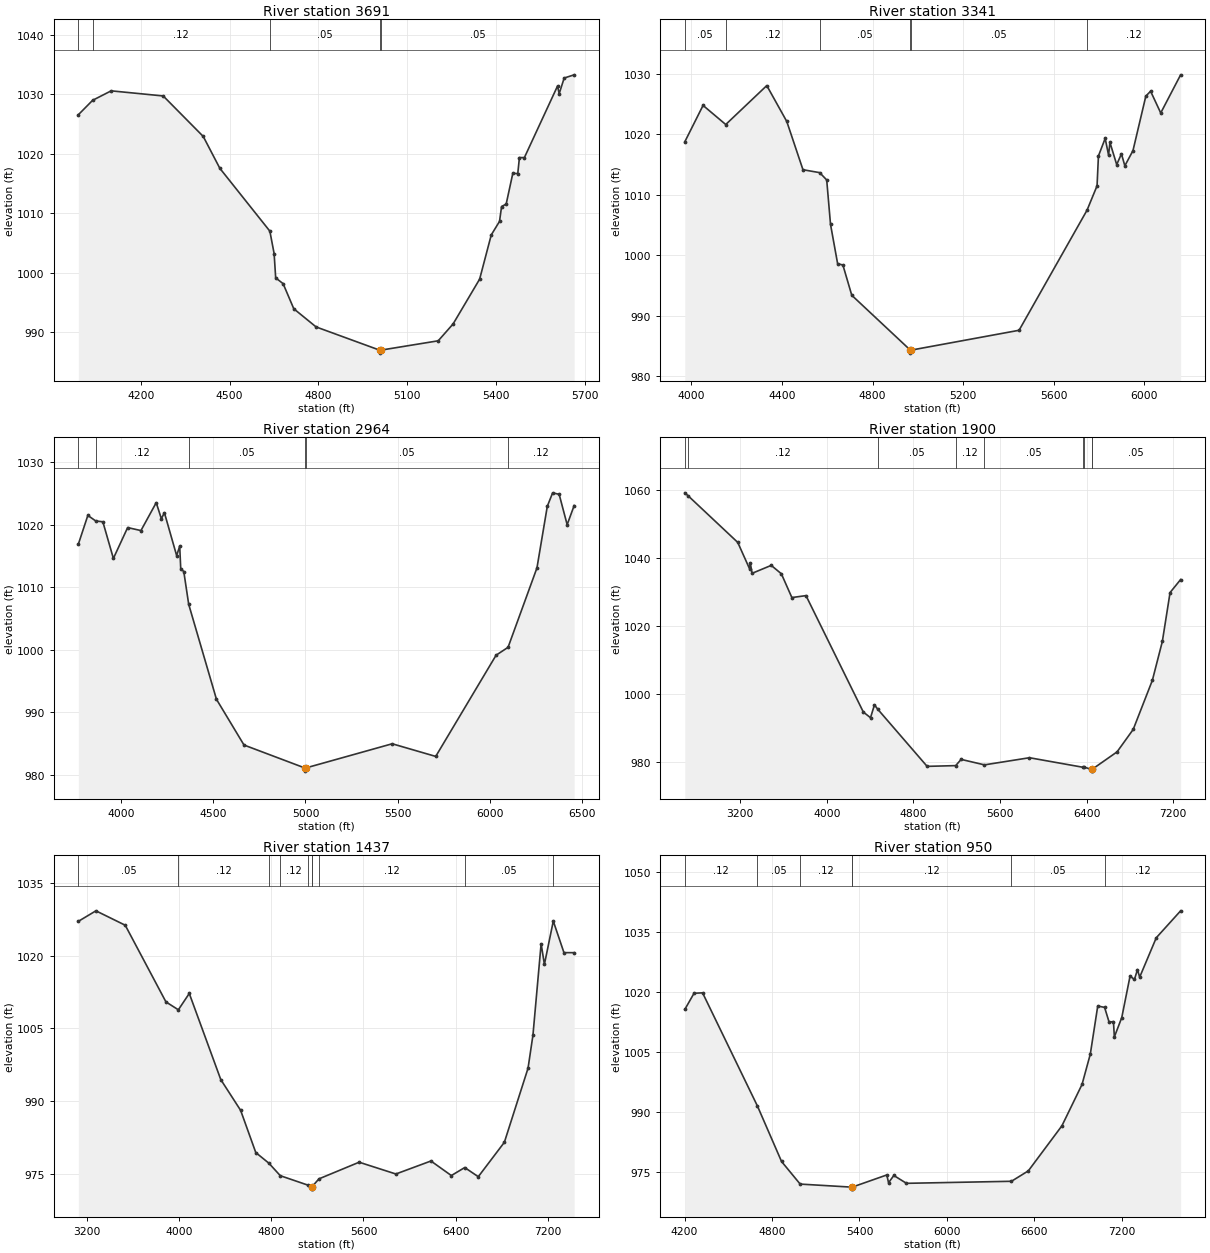
Type RM Length L Ch R = 1,3691,350,350,350
BEGIN DESCRIPTION:
Upper Denton 62 7.0
END DESCRIPTION:
XS GIS Cut Line= 3
      2202622.08      7256223.23      2201629.00      7256060.00
      2201029.26      7256357.77
#Sta/Elev= 30
  3989.0 1026.53  4037.3 1028.96  4100.0 1030.55  4275.9 1029.69  4411.2 1022.89
  4467.3 1017.54  4636.4 1006.98  4650.8 1003.22  4656.1  999.13  4681.2  998.16
  4717.3  993.94  4792.7  990.89  5007.4  986.99  5007.7  986.49  5011.4  986.99
  5205.5  988.56  5255.9  991.40  5345.5  998.92  5384.8 1006.35  5412.7 1008.62
  5419.7 1011.12  5435.2 1011.53  5457.6 1016.68  5474.4 1016.66  5480.0 1019.34
  5496.8 1019.34  5608.8 1031.36  5614.4 1030.07  5631.2 1032.70  5665.0 1033.24
#Mann=5,-1,0
  3989.0    0.05       0  4037.3    0.12       0  4636.4    0.05       0
  5007.4   0.033       0  5011.4    0.05       0
Bank Sta=5007.4,5011.4
Exp/Cntr=0.3,0.1

Type RM Length L Ch R = 1,3341,377,377,377
BEGIN DESCRIPTION:
Upper Denton 62 6.0
END DESCRIPTION:
XS GIS Cut Line= 3
      2202666.35      7256053.09      2201679.00      7255760.00
      2200718.48      7256412.46
#Sta/Elev= 30
  3970.5 1018.79  4051.2 1024.81  4151.4 1021.65  4332.8 1028.09  4421.1 1022.16
  4492.7 1014.17  4566.5 1013.69  4597.6 1012.48  4614.5 1005.12  4645.8  998.64
  4669.2  998.40  4708.4  993.40  4967.1  984.33  4967.4  983.83  4971.1  984.33
  5447.7  987.61  5748.1 1007.48  5792.3 1011.51  5798.4 1016.45  5828.2 1019.35
  5843.2 1016.58  5849.2 1018.69  5879.1 1015.02  5900.1 1016.80  5915.1 1014.82
  5951.0 1017.33  6007.9 1026.35  6028.9 1027.16  6073.7 1023.56  6161.6 1029.87
#Mann=6,-1,0
  3970.5    0.05       0  4151.4    0.12       0  4566.5    0.05       0
  4967.1   0.033       0  4971.1    0.05       0  5748.1    0.12       0
Bank Sta=4967.1,4971.1
Exp/Cntr=0.3,0.1

Type RM Length L Ch R = 1,2964,1064,1064,1064
BEGIN DESCRIPTION:
Upper Denton 62 5.0
END DESCRIPTION:
XS GIS Cut Line= 3
      2202676.83      7255980.20      2201579.00      7255410.00
      2200443.20      7256307.69
#Sta/Elev= 30
  3770.1 1016.88  3821.6 1021.48  3864.1 1020.60  3902.9 1020.46  3959.9 1014.61
  4037.1 1019.54  4109.1 1019.06  4191.9 1023.52  4219.7 1020.95  4236.1 1021.92
  4302.5 1015.06  4319.0 1016.58  4324.6 1012.95  4341.1 1012.52  4367.7 1007.28
  4518.0  992.11  4667.2  984.80  4996.9  981.13  4997.2  980.63  5000.9  981.13
  5469.6  985.00  5705.3  982.98  6032.2  999.15  6097.0 1000.41  6253.5 1013.10
  6309.5 1022.94  6338.4 1025.09  6373.7 1024.85  6417.0 1020.00  6454.9 1023.06
#Mann=6,-1,0
  3770.1    0.05       0  3864.1    0.12       0  4367.7    0.05       0
  4996.9   0.033       0  5000.9    0.05       0  6097.0    0.12       0
Bank Sta=4996.9,5000.9
Exp/Cntr=0.3,0.1

Type RM Length L Ch R = 1,1900,463,463,463
BEGIN DESCRIPTION:
Upper Denton 62 4.0
END DESCRIPTION:
XS GIS Cut Line= 3
      2203895.57      7255688.53      2201879.00      7254560.00
      2200157.42      7256036.22
#Sta/Elev= 30
  2688.7 1059.12  2718.6 1058.27  3177.5 1044.55  3288.1 1036.70  3293.8 1038.47
  3309.8 1035.45  3486.9 1037.79  3580.4 1035.32  3677.4 1028.33  3807.8 1028.90
  4337.4  994.67  4403.7  993.00  4440.1  996.79  4469.7  995.53  4926.5  978.70
  5190.1  978.92  5240.5  980.75  5455.9  979.14  5871.6  981.24  6362.7  978.45
  6375.4  978.49  6444.7  977.80  6444.9  977.30  6448.7  977.80  6680.4  982.96
  6829.7  989.57  7006.4 1003.99  7098.6 1015.42  7169.9 1029.80  7267.4 1033.63
#Mann=9,-1,0
  2688.7    0.05       0  2718.6    0.12       0  4469.7    0.05       0
  5190.1    0.12       0  5455.9    0.05       0  6362.7    0.12       0
  6375.4    0.05       0  6444.7   0.033       0  6448.7    0.05       0
Bank Sta=6444.7,6448.7
Exp/Cntr=0.3,0.1

Type RM Length L Ch R = 1,1437,487,487,487
BEGIN DESCRIPTION:
Upper Denton 62 3.0
END DESCRIPTION:
XS GIS Cut Line= 3
      2203489.76      7253923.75      2201629.00      7254210.00
      2199989.49      7255985.18
#Sta/Elev= 30
  3127.9 1027.07  3280.4 1029.24  3534.6 1026.27  3887.5 1010.46  3995.1 1008.83
  4089.8 1012.20  4363.0  994.44  4535.0  988.10  4666.5  979.39  4780.0  977.20
  4879.0  974.62  5120.4  972.66  5150.0  972.35  5150.3  971.85  5154.0  972.35
  5214.4  973.97  5562.6  977.40  5881.2  974.97  6185.2  977.65  6362.1  974.65
  6478.2  976.30  6595.7  974.41  6821.9  981.51  7027.2  996.79  7069.7 1003.60
  7140.6 1022.46  7169.0 1018.19  7246.0 1027.12  7338.5 1020.62  7427.0 1020.61
#Mann=10,-1,0
  3127.9    0.05       0  3995.1    0.12       0  4780.0    0.05       0
  4879.0    0.12       0  5120.4    0.05       0  5150.0    0.07       0
  5154.0    0.05       0  5214.4    0.12       0  6478.2    0.05       0
  7246.0    0.12       0
Bank Sta=5150,5154
Exp/Cntr=0.3,0.1

Type RM Length L Ch R = 1,950,468,468,468
BEGIN DESCRIPTION:
Upper Denton 62 2.0
END DESCRIPTION:
XS GIS Cut Line= 3
      2201634.28      7253326.95      2201229.00      7254010.00
      2199767.97      7256169.81
#Sta/Elev= 30
  4201.7 1015.55  4265.1 1019.60  4323.6 1019.71  4700.1  991.42  4865.4  977.57
  4993.2  971.92  5346.0  971.16  5346.3  970.66  5350.1  971.16  5587.5  974.20
  5599.7  972.26  5635.8  974.07  5722.6  972.11  6442.9  972.62  6558.5  975.22
  6789.2  986.49  6927.0  996.81  6983.9 1004.40  7034.9 1016.42  7081.9 1016.07
  7112.8 1012.39  7142.7 1012.52  7148.8 1008.69  7199.7 1013.53  7256.6 1023.89
  7286.6 1023.05  7307.6 1025.52  7322.5 1023.62  7436.4 1033.47  7603.5 1040.20
#Mann=7,-1,0
  4201.7    0.12       0  4700.1    0.05       0  4993.2    0.12       0
  5346.0    0.07       0  5350.1    0.12       0  6442.9    0.05       0
  7081.9    0.12       0
Bank Sta=5346,5350.1
Exp/Cntr=0.3,0.1

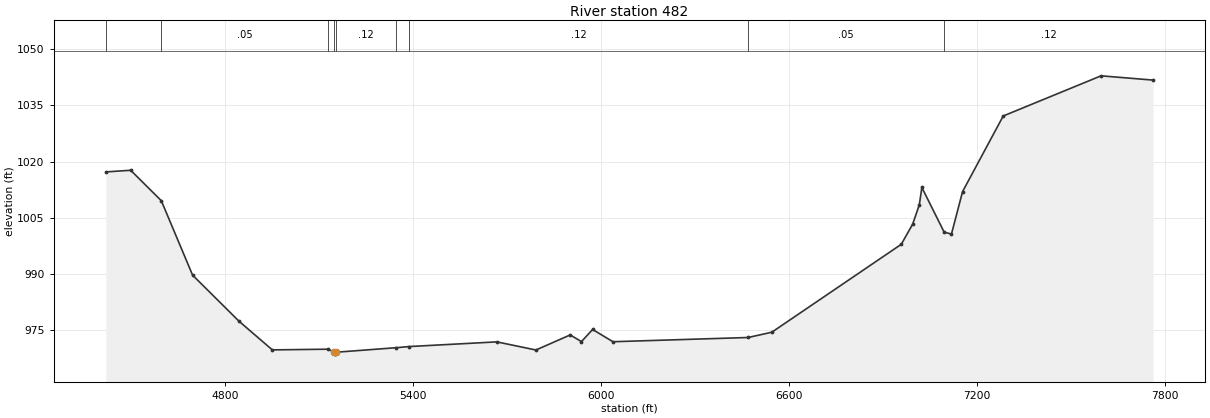
Type RM Length L Ch R = 1,482,0,0,0
BEGIN DESCRIPTION:
Upper Denton 62 1.0
END DESCRIPTION:
XS GIS Cut Line= 4
      2201232.78      7253392.08      2200829.00      7253810.00
      2200766.21      7254390.34      2199605.20      7256234.93
#Sta/Elev= 30
  4418.6 1017.24  4497.7 1017.68  4595.5 1009.56  4695.5  989.68  4844.2  977.35
  4950.2  969.73  5128.2  969.92  5148.5  969.10  5148.8  968.60  5152.6  969.10
  5346.4  970.32  5387.1  970.62  5667.2  971.87  5792.0  969.70  5901.4  973.72
  5937.5  971.95  5973.0  975.18  6038.0  971.91  6469.8  973.04  6545.5  974.45
  6958.8  997.91  6995.3 1003.30  7016.5 1008.47  7024.6 1013.09  7095.7 1001.18
  7119.1 1000.64  7154.6 1011.98  7284.5 1032.17  7597.0 1042.89  7763.0 1041.75
#Mann=9,-1,0
  4418.6    0.12       0  4595.5    0.05       0  5128.2    0.12       0
  5148.5   0.033       0  5152.6    0.12       0  5346.4    0.05       0
  5387.1    0.12       0  6469.8    0.05       0  7095.7    0.12       0
Bank Sta=5148.5,5152.6
Exp/Cntr=0.3,0.1

Chan Stop Cuts=-1