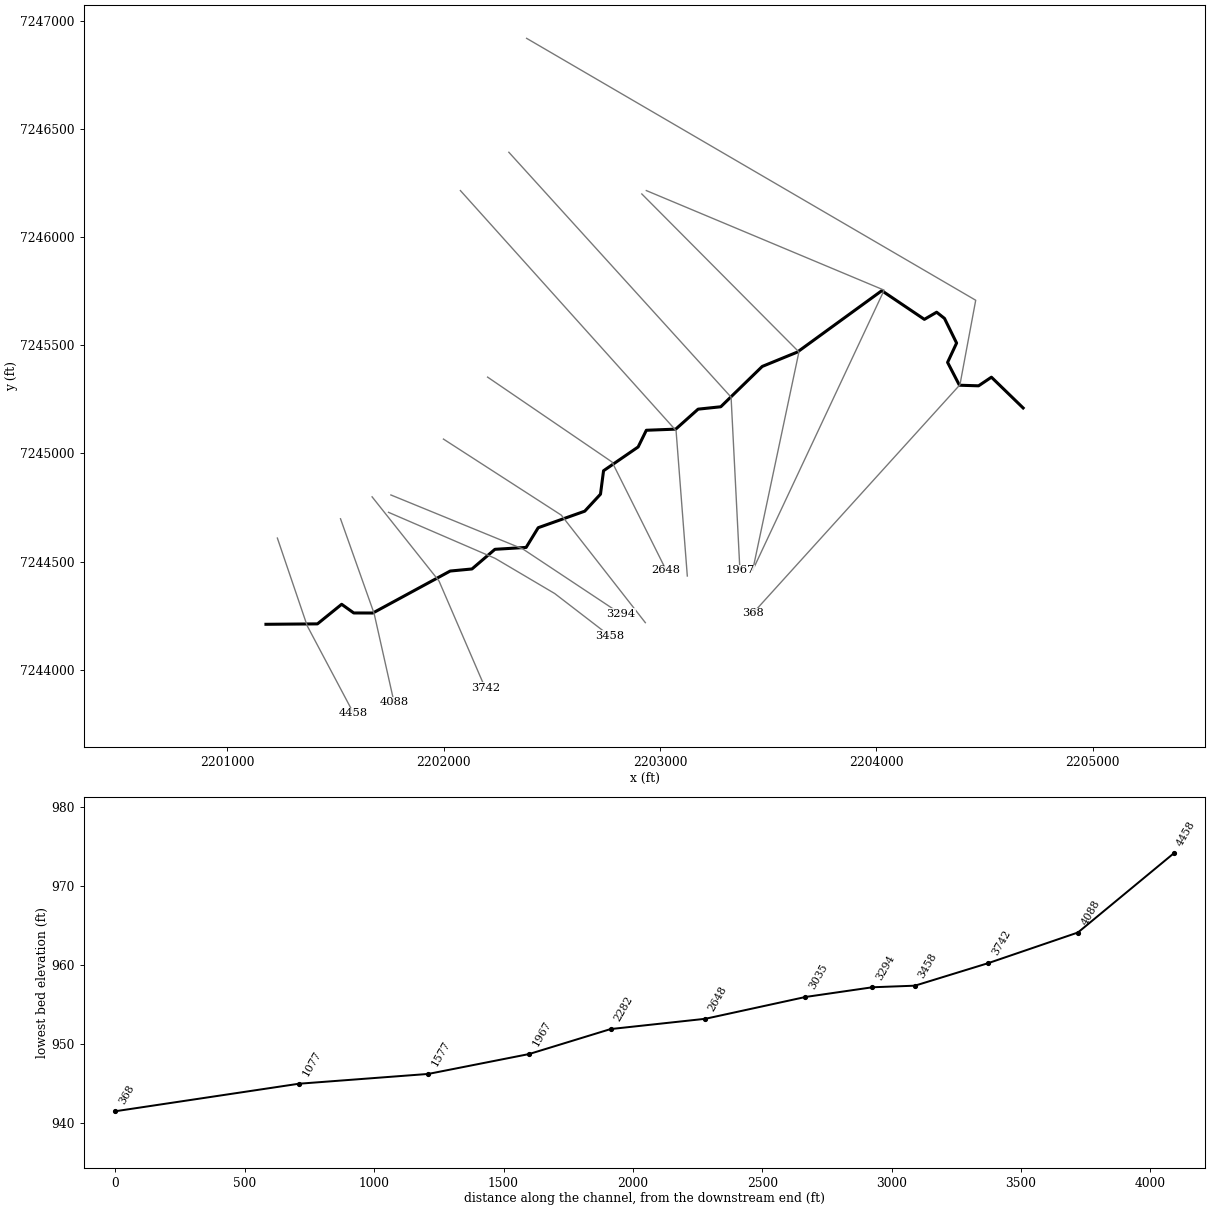
--- Upper Denton 64.prj (project) ---

Proj Title=Upper Denton 64 Base Level Engineering
Current Plan=p01
Default Exp/Contr=0.3,0.1
English Units
Geom File=g01
Flow File=f01
Plan File=p01
BEGIN DESCRIPTION:
Upper Denton 64
END DESCRIPTION:

--- Upper Denton 64.p01 (plan) ---

Plan Title=Multiple Run
Short Identifier=Multiple
Geom File=g01
Flow File=f01
Subcritical Flow
K Sum by GR= 0
Std Step Tol= 0.01
Critical Tol= 0.01
Num of Std Step Trials= 20
Max Error Tol= 0.3
Flow Tol Ratio= 0.001
Split Flow NTrial= 30
Split Flow Tol= 0.02
Split Flow Ratio= 0.02
Log Output Level= 0
Friction Slope Method= 1
Unsteady Friction Slope Method= 2
Unsteady Bridges Friction Slope Method= 1
Parabolic Critical Depth
Global Vel Dist=  1 , 1 , 1
Global Log Level= 0
CheckData=True
Encroach Param= -1, 0, 0, 0
BEGIN DESCRIPTION:
Multiple Run
END DESCRIPTION:

--- Upper Denton 64.f01 (steady flow) ---

Flow Title=Multiple
Number of Profiles=7
Profile Names=10-year,25-year,50-year,1pct_min,100-year,1pct_plu,500-year
River Rch & RM= Upper Denton 64,Reach-1,4458
     798    1128    1409     874    1743    3478    2677
Boundary for River Rch & Prof#=Upper Denton 64,Reach-1,1
Up Type=0
Dn Type=3
Dn Slope=0.005
Boundary for River Rch & Prof#=Upper Denton 64,Reach-1,2
Up Type=0
Dn Type=3
Dn Slope=0.005
Boundary for River Rch & Prof#=Upper Denton 64,Reach-1,3
Up Type=0
Dn Type=3
Dn Slope=0.005
Boundary for River Rch & Prof#=Upper Denton 64,Reach-1,4
Up Type=0
Dn Type=3
Dn Slope=0.005
Boundary for River Rch & Prof#=Upper Denton 64,Reach-1,5
Up Type=0
Dn Type=3
Dn Slope=0.005
Boundary for River Rch & Prof#=Upper Denton 64,Reach-1,6
Up Type=0
Dn Type=3
Dn Slope=0.005
Boundary for River Rch & Prof#=Upper Denton 64,Reach-1,7
Up Type=0
Dn Type=3
Dn Slope=0.005

--- Upper Denton 64.g01 (geometry) ---

Geom Title=Existing Conditions

River Reach=Upper Denton 64,Reach-1
Reach XY= 30
      2201179.00      7244210.00      2201417.05      7244211.92
      2201528.96      7244302.48      2201584.89      7244262.37
      2201673.03      7244262.15      2202030.59      7244456.17
      2202131.36      7244465.76      2202237.44      7244556.59
      2202381.68      7244565.40      2202437.49      7244656.46
      2202652.58      7244732.85      2202725.39      7244811.49
      2202739.51      7244919.81      2202899.43      7245029.74
      2202937.31      7245106.90      2203073.13      7245112.08
      2203176.58      7245204.46      2203281.43      7245215.52
      2203472.94      7245401.86      2203635.05      7245468.16
      2204025.77      7245752.16      2204222.46      7245619.59
      2204279.22      7245652.54      2204315.40      7245624.00
      2204371.44      7245510.00      2204329.79      7245420.68
      2204384.44      7245315.10      2204473.02      7245312.33
      2204532.42      7245352.21      2204679.00      7245210.00

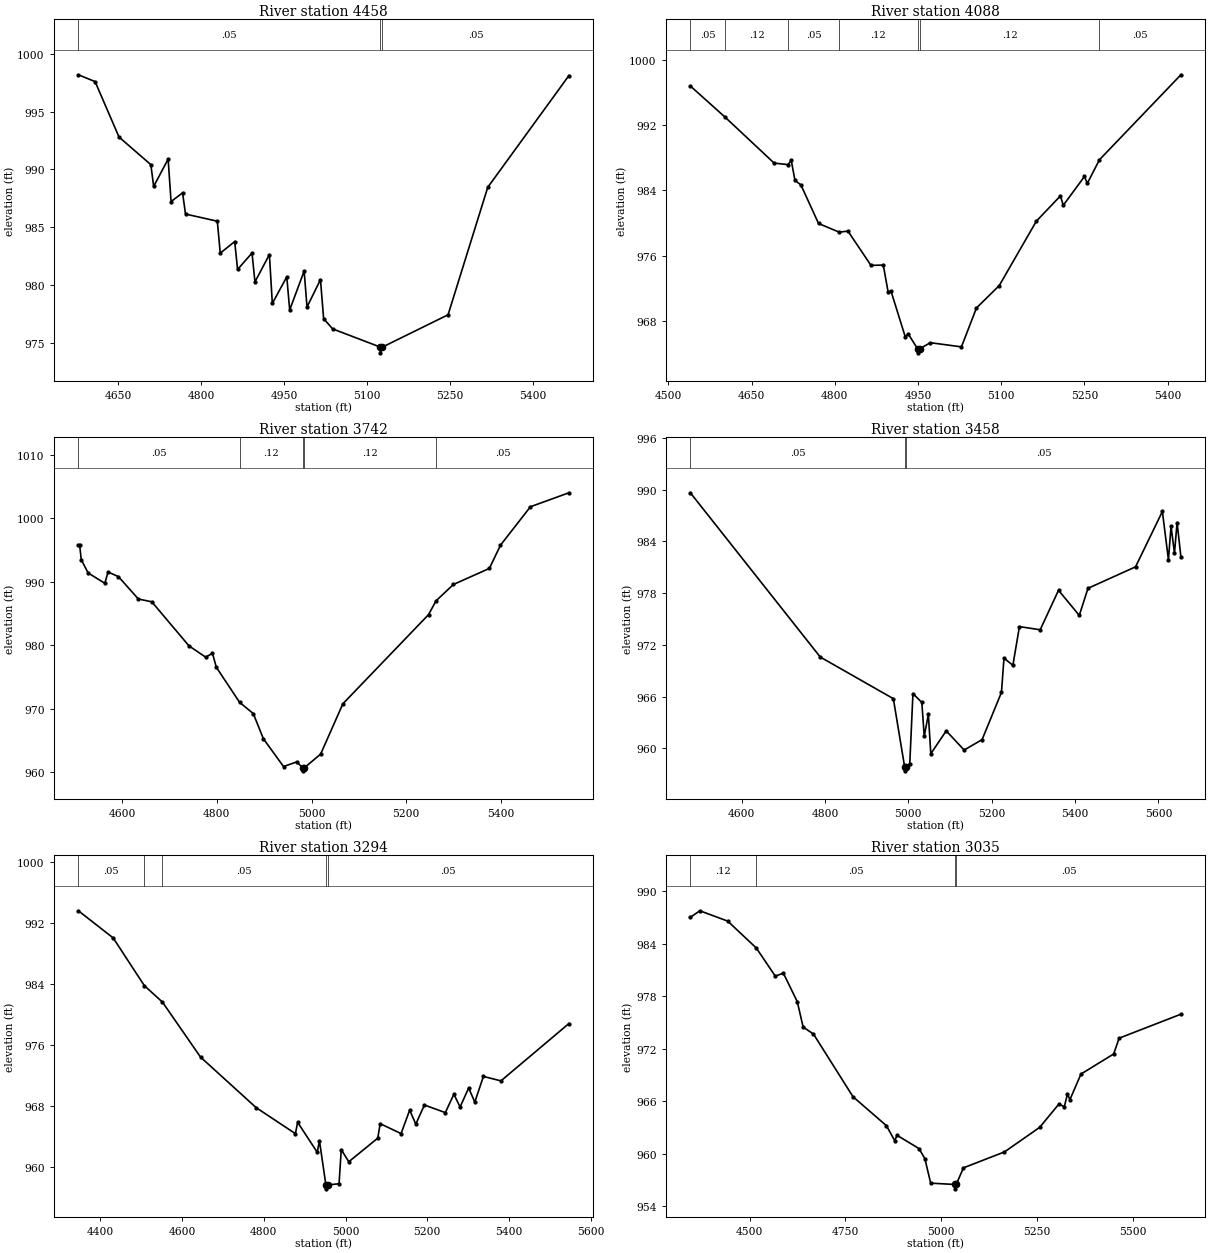
Type RM Length L Ch R = 1,4458,370,370,370
BEGIN DESCRIPTION:
Upper Denton 64 10.0
END DESCRIPTION:
XS GIS Cut Line= 3
      2201231.77      7244608.59      2201369.61      7244203.18
      2201584.23      7243798.24
#Sta/Elev= 30
  4578.6  998.18  4608.8  997.59  4652.0  992.80  4709.5  990.41  4714.7  988.53
  4740.8  990.89  4746.1  987.22  4766.9  987.97  4772.2  986.14  4829.7  985.52
  4835.0  982.76  4861.1  983.76  4866.3  981.35  4892.4  982.77  4897.7  980.27
  4923.8  982.64  4929.1  978.41  4955.2  980.71  4960.5  977.85  4986.6  981.21
  4991.8  978.10  5016.1  980.47  5021.8  977.10  5038.1  976.21  5124.1  974.64
  5124.3  974.14  5128.1  974.64  5246.7  977.43  5318.4  988.45  5465.1  998.11
#Mann=3,-1,0
  4578.6    0.05       0  5124.1   0.033       0  5128.1    0.05       0
Bank Sta=5124.1,5128.1
Exp/Cntr=0.3,0.1

Type RM Length L Ch R = 1,4088,346,346,346
BEGIN DESCRIPTION:
Upper Denton 64 9.0
END DESCRIPTION:
XS GIS Cut Line= 3
      2201523.67      7244697.79      2201679.00      7244260.00
      2201770.98      7243850.43
#Sta/Elev= 30
  4539.5  996.77  4602.4  992.94  4690.5  987.34  4715.5  987.15  4721.4  987.66
  4728.1  985.22  4738.8  984.67  4770.6  979.95  4807.9  978.89  4823.6  979.02
  4865.1  974.83  4887.3  974.86  4896.0  971.58  4901.3  971.66  4926.9  966.09
  4932.2  966.46  4949.0  964.63  4949.2  964.13  4953.0  964.63  4972.2  965.37
  5028.2  964.86  5055.3  969.62  5096.3  972.35  5163.3  980.24  5206.6  983.32
  5211.8  982.18  5250.0  985.70  5255.1  984.85  5276.9  987.74  5423.8  998.14
#Mann=7,-1,0
  4539.5    0.05       0  4602.4    0.12       0  4715.5    0.05       0
  4807.9    0.12       0  4949.0    0.07       0  4953.0    0.12       0
  5276.9    0.05       0
Bank Sta=4949,4953
Exp/Cntr=0.3,0.1

Type RM Length L Ch R = 1,3742,284,284,284
BEGIN DESCRIPTION:
Upper Denton 64 8.0
END DESCRIPTION:
XS GIS Cut Line= 3
      2201669.63      7244799.11      2201979.00      7244410.00
      2202192.59      7243915.35
#Sta/Elev= 30
  4507.7  995.85  4510.3  995.85  4513.8  993.50  4528.3  991.41  4563.5  989.79
  4570.4  991.56  4592.3  990.84  4634.3  987.32  4662.8  986.87  4741.3  979.93
  4776.5  978.16  4790.9  978.76  4799.0  976.57  4848.1  971.05  4877.1  969.27
  4898.3  965.32  4940.9  960.94  4968.8  961.66  4981.2  960.76  4981.4  960.26
  4985.2  960.76  5019.3  962.90  5066.3  970.82  5247.2  984.86  5262.9  987.02
  5299.6  989.60  5375.6  992.13  5399.1  995.79  5462.3 1001.84  5543.6 1004.04
#Mann=5,-1,0
  4507.7    0.05       0  4848.1    0.12       0  4981.2    0.07       0
  4985.2    0.12       0  5262.9    0.05       0
Bank Sta=4981.2,4985.2
Exp/Cntr=0.3,0.1

Type RM Length L Ch R = 1,3458,164,164,164
BEGIN DESCRIPTION:
Upper Denton 64 7.5
END DESCRIPTION:
XS GIS Cut Line= 4
      2201745.62      7244727.56      2202238.22      7244514.89
      2202513.83      7244352.13      2202767.76      7244156.79
#Sta/Elev= 30
  4477.0  989.65  4788.7  970.60  4964.1  965.77  4991.0  957.90  4991.3  957.40
  4995.0  957.90  5003.5  958.24  5011.1  966.36  5032.4  965.33  5038.2  961.40
  5048.1  963.94  5053.9  959.38  5091.0  962.04  5133.9  959.81  5177.0  961.02
  5223.5  966.50  5229.5  970.47  5250.9  969.64  5266.6  974.13  5316.4  973.76
  5360.4  978.34  5410.2  975.43  5431.1  978.57  5545.2  981.06  5609.6  987.48
  5624.1  981.89  5630.4  985.76  5638.6  982.65  5644.9  986.20  5654.0  982.23
#Mann=3,-1,0
  4477.0    0.05       0  4991.0   0.033       0  4995.0    0.05       0
Bank Sta=4991,4995
Exp/Cntr=0.3,0.1

Type RM Length L Ch R = 1,3294,259,259,259
BEGIN DESCRIPTION:
Upper Denton 64 7.0
END DESCRIPTION:
XS GIS Cut Line= 3
      2201756.49      7244807.84      2202366.26      7244558.29
      2202817.68      7244258.79
#Sta/Elev= 30
  4346.1  993.64  4431.3  990.08  4507.4  983.84  4551.9  981.67  4645.0  974.47
  4781.2  967.84  4877.3  964.43  4882.7  965.92  4930.7  961.99  4936.1  963.51
  4951.9  957.70  4952.1  957.20  4955.9  957.70  4984.1  957.87  4989.5  962.34
  5007.9  960.75  5078.8  963.84  5084.8  965.74  5135.9  964.44  5156.9  967.51
  5172.0  965.68  5193.0  968.19  5244.2  967.19  5265.2  969.60  5280.3  967.92
  5301.3  970.42  5316.3  968.57  5337.4  971.93  5380.3  971.35  5546.7  978.86
#Mann=5,-1,0
  4346.1    0.05       0  4507.4    0.12       0  4551.9    0.05       0
  4951.9   0.033       0  4955.9    0.05       0
Bank Sta=4951.9,4955.9
Exp/Cntr=0.3,0.1

Type RM Length L Ch R = 1,3035,387,387,387
BEGIN DESCRIPTION:
Upper Denton 64 6.0
END DESCRIPTION:
XS GIS Cut Line= 3
      2201999.49      7245066.12      2202544.21      7244714.54
      2202932.67      7244217.57
#Sta/Elev= 30
  4345.5  987.00  4370.3  987.75  4442.9  986.57  4517.4  983.50  4567.0  980.28
  4588.1  980.62  4624.4  977.35  4639.6  974.46  4666.6  973.66  4769.6  966.50
  4856.7  963.19  4878.4  961.48  4884.4  962.09  4941.8  960.57  4957.0  959.42
  4972.2  956.62  5034.8  956.47  5035.0  955.97  5038.8  956.47  5057.6  958.37
  5164.6  960.19  5256.5  963.00  5306.3  965.65  5320.7  965.37  5328.9  966.81
  5335.2  966.16  5364.1  969.09  5449.2  971.38  5463.6  973.19  5624.6  975.93
#Mann=4,-1,0
  4345.5    0.12       0  4517.4    0.05       0  5034.8   0.033       0
  5038.8    0.05       0
Bank Sta=5034.8,5038.8
Exp/Cntr=0.3,0.1

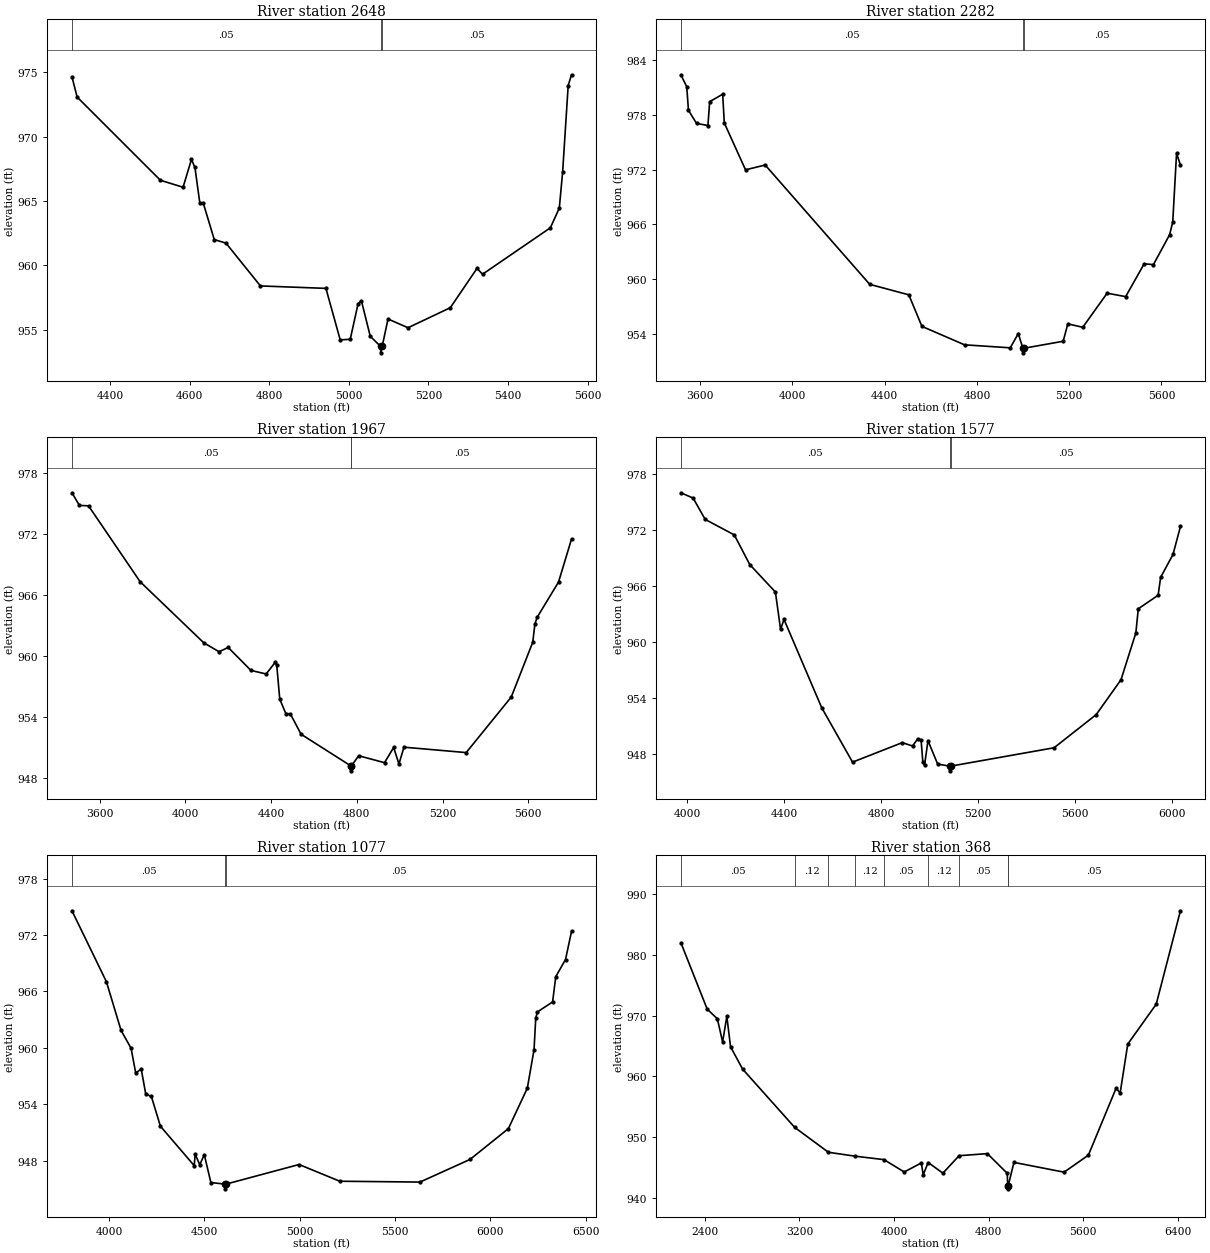
Type RM Length L Ch R = 1,2648,366,366,366
BEGIN DESCRIPTION:
Upper Denton 64 5.0
END DESCRIPTION:
XS GIS Cut Line= 3
      2202203.53      7245352.54      2202779.00      7244960.00
      2203028.99      7244460.02
#Sta/Elev= 30
  4303.9  974.66  4316.9  973.09  4526.3  966.62  4583.2  966.08  4604.2  968.24
  4613.0  967.62  4625.3  964.84  4634.0  964.84  4661.6  962.01  4690.9  961.74
  4777.6  958.41  4942.2  958.22  4978.1  954.22  5003.3  954.26  5022.9  957.01
  5031.3  957.27  5053.6  954.50  5079.6  953.71  5079.8  953.21  5083.6  953.71
  5098.3  955.84  5148.6  955.16  5254.9  956.72  5321.9  959.77  5335.9  959.32
  5506.4  962.93  5528.8  964.46  5537.2  967.28  5551.1  973.98  5559.5  974.82
#Mann=3,-1,0
  4303.9    0.05       0  5079.6   0.033       0  5083.6    0.05       0
Bank Sta=5079.6,5083.6
Exp/Cntr=0.3,0.1

Type RM Length L Ch R = 1,2282,315,315,315
BEGIN DESCRIPTION:
Upper Denton 64 4.0
END DESCRIPTION:
XS GIS Cut Line= 3
      2202077.86      7246214.80      2203074.73      7245105.17
      2203126.69      7244433.23
#Sta/Elev= 30
  3516.5  982.39  3541.9  981.08  3549.4  978.49  3584.5  977.06  3633.8  976.83
  3641.3  979.44  3697.7  980.26  3704.8  977.11  3796.8  971.97  3882.0  972.50
  4335.0  959.42  4504.6  958.27  4561.5  954.81  4746.1  952.79  4944.2  952.46
  4979.3  954.02  4999.0  952.41  4999.2  951.91  5003.0  952.41  5173.8  953.18
  5193.9  955.09  5258.6  954.71  5364.4  958.45  5444.6  958.07  5524.9  961.67
  5565.0  961.58  5635.2  964.86  5648.7  966.24  5665.3  973.78  5682.1  972.48
#Mann=3,-1,0
  3516.5    0.05       0  4999.0   0.033       0  5003.0    0.05       0
Bank Sta=4999,5003
Exp/Cntr=0.3,0.1

Type RM Length L Ch R = 1,1967,390,390,390
BEGIN DESCRIPTION:
Upper Denton 64 3.0
END DESCRIPTION:
XS GIS Cut Line= 3
      2202301.79      7246391.92      2203329.00      7245260.00
      2203369.87      7244459.37
#Sta/Elev= 30
  3471.1  976.02  3505.8  974.78  3548.4  974.74  3789.0  967.30  4086.3  961.30
  4157.3  960.43  4199.8  960.85  4305.9  958.60  4376.9  958.25  4419.0  959.39
  4426.2  959.14  4440.4  955.78  4468.8  954.36  4489.7  954.34  4539.8  952.34
  4770.9  949.25  4771.1  948.75  4774.9  949.25  4808.7  950.23  4929.0  949.55
  4971.6  951.04  4996.3  949.42  5019.7  951.07  5310.0  950.54  5520.3  955.99
  5620.4  961.36  5630.4  963.13  5640.5  963.79  5740.6  967.26  5801.3  971.48
#Mann=3,-1,0
  3471.1    0.05       0  4770.9   0.033       0  4774.9    0.05       0
Bank Sta=4770.9,4774.9
Exp/Cntr=0.3,0.1

Type RM Length L Ch R = 1,1577,500,500,500
BEGIN DESCRIPTION:
Upper Denton 64 2.5
END DESCRIPTION:
XS GIS Cut Line= 3
      2202916.42      7246199.16      2203642.61      7245468.86
      2203429.00      7244460.02
#Sta/Elev= 30
  3974.1  976.00  4024.8  975.43  4074.3  973.15  4194.5  971.49  4258.2  968.32
  4364.2  965.37  4385.4  961.37  4399.6  962.44  4555.1  952.99  4682.4  947.16
  4887.5  949.25  4929.9  948.89  4951.1  949.65  4965.3  949.50  4972.4  947.17
  4979.4  946.83  4993.6  949.46  5033.5  946.96  5082.6  946.73  5082.9  946.23
  5086.6  946.73  5513.9  948.70  5687.7  952.25  5789.9  955.98  5851.2  960.99
  5861.3  963.58  5943.2  965.03  5953.4  966.94  6004.6  969.40  6035.2  972.39
#Mann=3,-1,0
  3974.1    0.05       0  5082.6   0.033       0  5086.6    0.05       0
Bank Sta=5082.6,5086.6
Exp/Cntr=0.3,0.1

Type RM Length L Ch R = 1,1077,709,709,709
BEGIN DESCRIPTION:
Upper Denton 64 2.0
END DESCRIPTION:
XS GIS Cut Line= 3
      2202937.18      7246214.83      2204036.54      7245754.47
      2203429.00      7244460.00
#Sta/Elev= 30
  3804.5  974.59  3985.3  967.04  4062.1  961.86  4115.1  959.94  4138.9  957.33
  4168.1  957.74  4191.9  955.06  4221.1  954.84  4268.6  951.66  4446.0  947.46
  4451.4  948.68  4475.2  947.55  4499.0  948.63  4533.6  945.66  4608.4  945.49
  4608.6  944.99  4612.4  945.49  4996.4  947.58  5209.9  945.80  5630.9  945.71
  5893.6  948.12  6094.9  951.40  6194.3  955.70  6229.6  959.81  6238.5  963.13
  6246.9  963.82  6326.9  964.88  6343.7  967.58  6394.8  969.40  6426.3  972.39
#Mann=3,-1,0
  3804.5    0.05       0  4608.4   0.033       0  4612.4    0.05       0
Bank Sta=4608.4,4612.4
Exp/Cntr=0.3,0.1

Type RM Length L Ch R = 1,368,0,0,0
BEGIN DESCRIPTION:
Upper Denton 64 1.0
END DESCRIPTION:
XS GIS Cut Line= 4
      2202383.90      7246918.53      2204459.80      7245707.87
      2204386.88      7245317.24      2203429.03      7244260.03
#Sta/Elev= 30
  2196.3  981.99  2419.0  971.06  2505.0  969.48  2549.5  965.66  2585.2  969.87
  2616.7  964.87  2718.4  961.21  3159.1  951.62  3444.9  947.52  3671.6  946.88
  3915.2  946.31  4086.2  944.28  4230.9  945.77  4246.6  943.81  4288.9  945.84
  4413.3  944.09  4550.6  946.96  4790.0  947.30  4958.2  944.05  4961.2  942.01
  4961.6  941.51  4965.8  942.01  5014.7  945.86  5439.1  944.25  5644.5  947.05
  5878.4  958.03  5913.5  957.30  5977.7  965.32  6218.3  971.87  6423.4  987.24
#Mann=9,-1,0
  2196.3    0.05       0  3159.1    0.12       0  3444.9    0.05       0
  3671.6    0.12       0  3915.2    0.05       0  4288.9    0.12       0
  4550.6    0.05       0  4961.2   0.033       0  4965.8    0.05       0
Bank Sta=4961.2,4965.8
Exp/Cntr=0.3,0.1

Chan Stop Cuts=-1