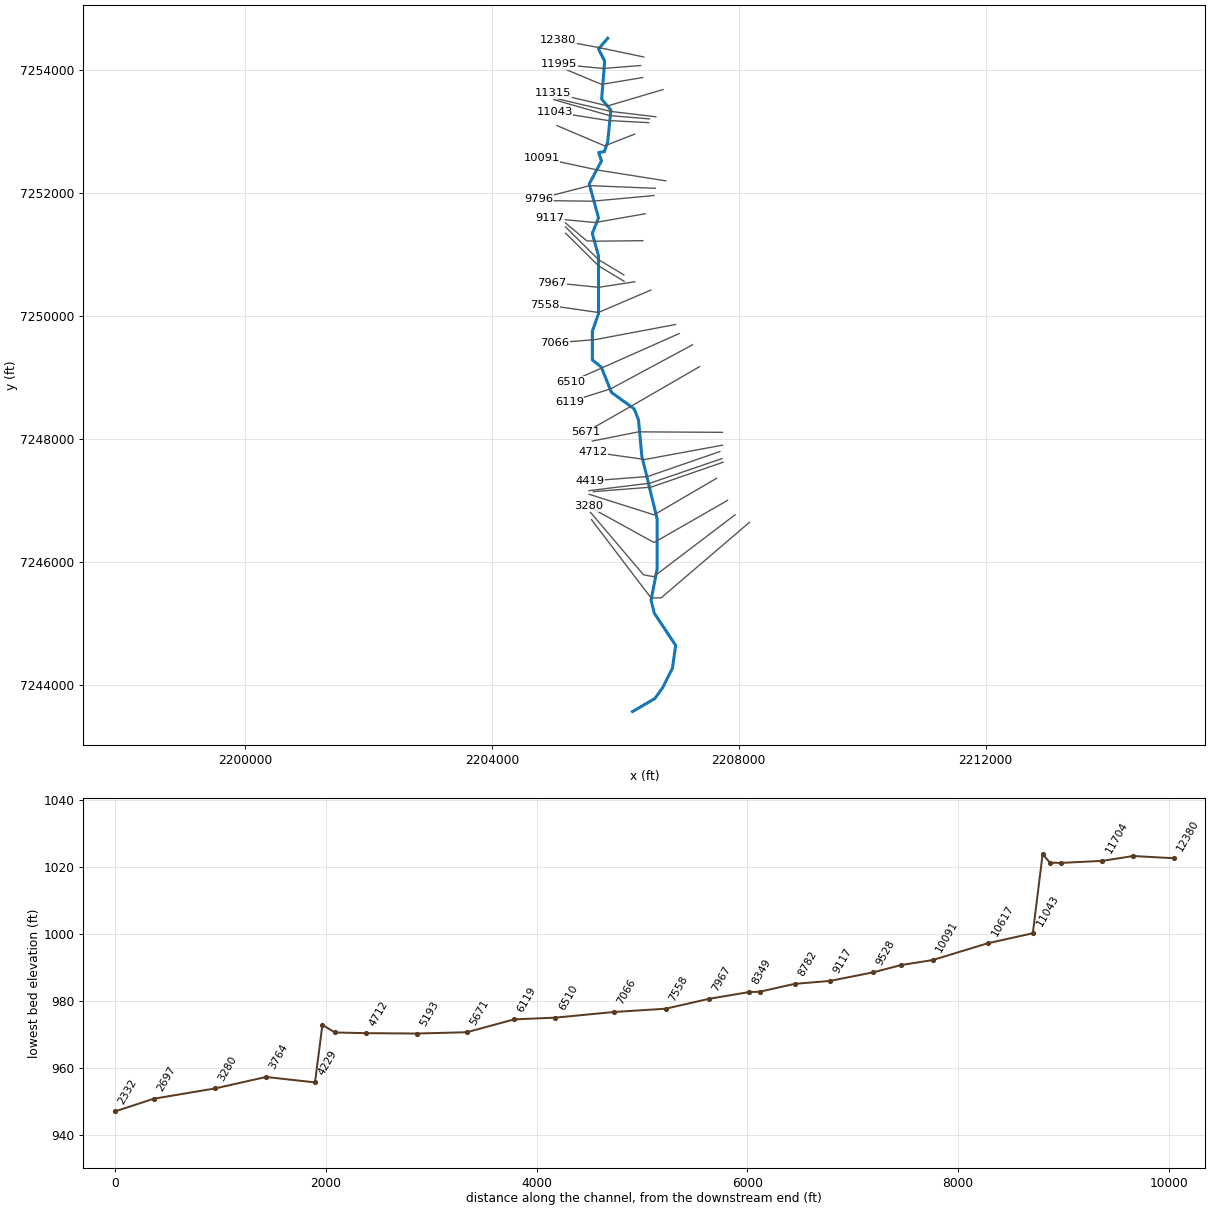
--- Upper Denton 65.prj (project) ---

Proj Title=Upper Denton 65 Base Level Engineering
Current Plan=p01
Default Exp/Contr=0.3,0.1
English Units
Geom File=g01
Flow File=f01
Plan File=p01
Y Axis Title=Elevation
X Axis Title(PF)=Main Channel Distance
X Axis Title(XS)=Station
BEGIN DESCRIPTION:
Upper Denton 65
END DESCRIPTION:
DSS Export Rating Curves= 0
DSS Export Rating Curve Sorted= 0
DSS Export Volume Flow Curves= 0
DXF OffsetX= 0
DXF OffsetY= 0
DXF ScaleX= 1
DXF ScaleY= 10

--- Upper Denton 65.p01 (plan) ---

Plan Title=Multiple Run
Short Identifier=Multiple
Geom File=g01
Flow File=f01
Subcritical Flow
K Sum by GR= 0
Std Step Tol= 0.01
Critical Tol= 0.01
Num of Std Step Trials= 20
Max Error Tol= 0.3
Flow Tol Ratio= 0.001
Split Flow NTrial= 30
Split Flow Tol= 0.02
Split Flow Ratio= 0.02
Log Output Level= 0
Friction Slope Method= 1
Unsteady Friction Slope Method= 2
Unsteady Bridges Friction Slope Method= 1
Parabolic Critical Depth
Global Vel Dist=  1 , 1 , 1
Global Log Level= 0
CheckData=True
Encroach Param= -1, 0, 0, 0
BEGIN DESCRIPTION:
Multiple Run
END DESCRIPTION:

--- Upper Denton 65.f01 (steady flow) ---

Flow Title=Multiple
Program Version=4.10
Number of Profiles= 7
Profile Names=10-year,25-year,50-year,1pct_min,100-year,1pct_plu,500-year
River Rch & RM=Upper Denton 65,Reach-1         ,12380
     584     802     982     597    1191    2377    1759
River Rch & RM=Upper Denton 65,Reach-1         ,7967
     802    1123    1392     855    1707    3406    2577
Boundary for River Rch & Prof#=Upper Denton 65,Reach-1         , 1
Up Type= 0
Dn Type= 3
Dn Slope=0.003
Boundary for River Rch & Prof#=Upper Denton 65,Reach-1         , 2
Up Type= 0
Dn Type= 3
Dn Slope=0.003
Boundary for River Rch & Prof#=Upper Denton 65,Reach-1         , 3
Up Type= 0
Dn Type= 3
Dn Slope=0.003
Boundary for River Rch & Prof#=Upper Denton 65,Reach-1         , 4
Up Type= 0
Dn Type= 3
Dn Slope=0.003
Boundary for River Rch & Prof#=Upper Denton 65,Reach-1         , 5
Up Type= 0
Dn Type= 3
Dn Slope=0.003
Boundary for River Rch & Prof#=Upper Denton 65,Reach-1         , 6
Up Type= 0
Dn Type= 3
Dn Slope=0.003
Boundary for River Rch & Prof#=Upper Denton 65,Reach-1         , 7
Up Type= 0
Dn Type= 3
Dn Slope=0.003
DSS Import GetInterval= 0
DSS Import GetPeak= 0
DSS Import FillOption= 0

--- Upper Denton 65.g01 (geometry) ---

Geom Title=Existing Conditions

River Reach=Upper Denton 65,Reach-1
Reach XY= 30
      2205879.00      7254510.00      2205728.50      7254335.03
      2205829.10      7254139.90      2205780.05      7253520.43
      2205928.76      7253344.78      2205878.48      7252825.21
      2205823.80      7252665.14      2205731.56      7252651.82
      2205777.37      7252516.04      2205578.72      7252139.82
      2205729.29      7251589.61      2205628.60      7251335.00
      2205729.54      7250970.54      2205728.93      7250030.03
      2205629.10      7249744.60      2205629.04      7249280.19
      2205773.48      7249162.44      2205939.78      7248750.32
      2206306.28      7248483.89      2206376.74      7248304.06
      2206430.22      7247720.50      2206679.09      7246689.90
      2206678.93      7245880.03      2206579.77      7245370.69
      2206634.48      7245157.56      2206979.29      7244635.12
      2206926.75      7244265.93      2206770.84      7243953.95
      2206642.56      7243773.49      2206279.00      7243560.00

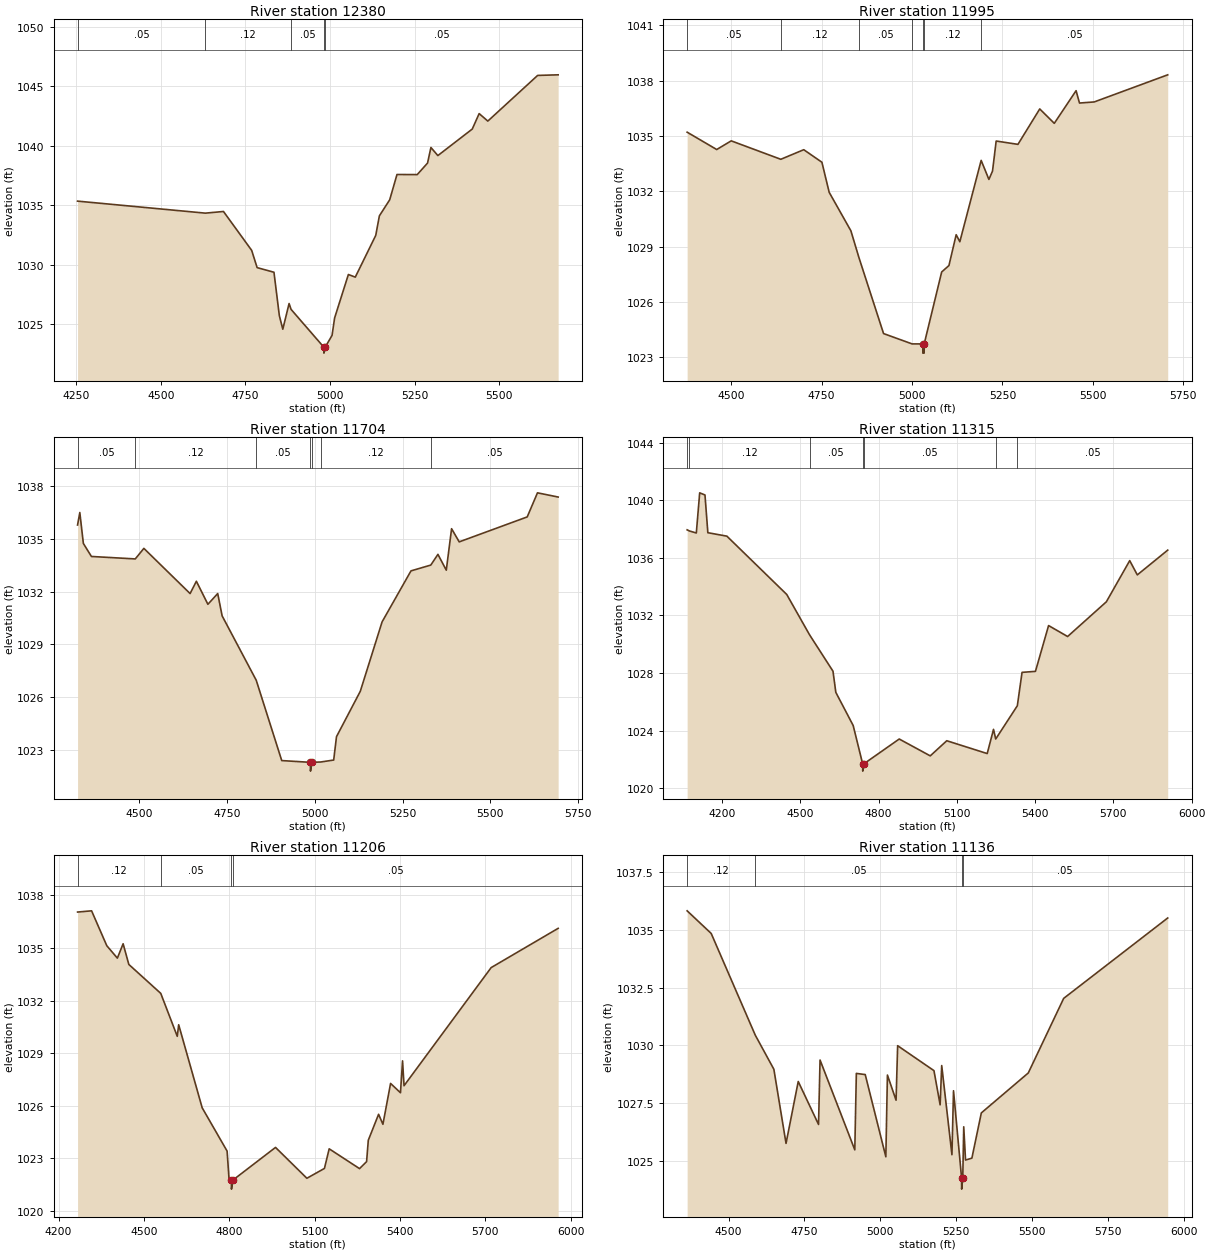
Type RM Length L Ch R = 1,12380,385,385,385
BEGIN DESCRIPTION:
Upper Denton 65 29.0
END DESCRIPTION:
XS GIS Cut Line= 3
      2206462.63      7254205.33      2205729.00      7254360.00
      2205069.44      7254483.10
#Sta/Elev= 30
  4253.9 1035.35  4631.7 1034.34  4685.2 1034.48  4768.6 1031.21  4784.7 1029.76
  4834.5 1029.37  4850.4 1025.72  4860.6 1024.58  4879.2 1026.74  4885.0 1026.25
  4981.9 1023.07  4982.1 1022.57  4985.9 1023.07  5006.2 1024.06  5013.8 1025.53
  5054.5 1029.18  5074.9 1028.96  5135.4 1032.47  5146.1 1034.11  5176.6 1035.46
  5198.2 1037.59  5258.0 1037.58  5288.5 1038.55  5298.5 1039.86  5319.0 1039.18
  5420.7 1041.41  5441.1 1042.71  5466.7 1042.08  5614.0 1045.92  5674.6 1045.97
#Mann=5,-1,0
  4253.9    0.05       0  4631.7    0.12       0  4885.0    0.05       0
  4981.9   0.033       0  4985.9    0.05       0
Bank Sta=4981.9,4985.9
Exp/Cntr=0.3,0.1

Type RM Length L Ch R = 1,11995,291,291,291
BEGIN DESCRIPTION:
Upper Denton 65 28.0
END DESCRIPTION:
XS GIS Cut Line= 3
      2206410.55      7254066.44      2205802.90      7254018.69
      2205086.78      7254088.14
#Sta/Elev= 30
  4378.0 1035.21  4459.8 1034.27  4499.9 1034.74  4637.0 1033.74  4700.5 1034.26
  4750.7 1033.58  4770.8 1031.95  4830.9 1029.86  4853.1 1028.41  4921.2 1024.29
  5000.1 1023.73  5029.6 1023.73  5029.9 1023.23  5033.4 1023.23  5033.6 1023.73
  5081.9 1027.63  5102.0 1027.98  5122.0 1029.65  5132.1 1029.27  5191.1 1033.68
  5212.5 1032.65  5222.5 1033.10  5232.6 1034.73  5292.8 1034.55  5353.1 1036.47
  5393.3 1035.69  5453.6 1037.46  5463.0 1036.79  5503.8 1036.85  5707.0 1038.32
#Mann=7,-1,0
  4378.0    0.05       0  4637.0    0.12       0  4853.1    0.05       0
  5000.1    0.12       0  5029.6   0.033       0  5033.6    0.12       0
  5191.1    0.05       0
Bank Sta=5029.6,5033.6
Exp/Cntr=0.3,0.1

Type RM Length L Ch R = 1,11704,389,389,389
BEGIN DESCRIPTION:
Upper Denton 65 27.0
END DESCRIPTION:
XS GIS Cut Line= 3
      2206445.28      7253871.13      2205779.00      7253760.00
      2205138.87      7254027.36
#Sta/Elev= 30
  4324.1 1035.79  4330.5 1036.50  4340.6 1034.74  4363.6 1034.00  4488.5 1033.86
  4513.0 1034.46  4644.7 1031.89  4662.6 1032.59  4695.4 1031.28  4723.4 1031.89
  4736.0 1030.62  4833.1 1026.96  4905.8 1022.39  4987.4 1022.29  4987.7 1021.79
  4991.4 1022.29  5017.0 1022.31  5053.8 1022.42  5061.8 1023.75  5129.6 1026.33
  5191.7 1030.28  5274.0 1033.18  5330.4 1033.51  5350.8 1034.12  5374.6 1033.22
  5389.7 1035.58  5411.4 1034.83  5605.2 1036.25  5634.4 1037.62  5693.3 1037.38
#Mann=7,-1,0
  4324.1    0.05       0  4488.5    0.12       0  4833.1    0.05       0
  4987.4   0.033       0  4991.4    0.05       0  5017.0    0.12       0
  5330.4    0.05       0
Bank Sta=4987.4,4991.4
Exp/Cntr=0.3,0.1

Type RM Length L Ch R = 1,11315,109,109,109
BEGIN DESCRIPTION:
Upper Denton 65 26.0
END DESCRIPTION:
XS GIS Cut Line= 3
      2206775.10      7253675.81      2205879.00      7253410.00
      2204995.57      7253619.40
#Sta/Elev= 30
  4065.6 1037.94  4074.5 1037.86  4100.8 1037.72  4113.7 1040.51  4134.0 1040.36
  4145.0 1037.74  4218.0 1037.50  4447.5 1033.45  4534.9 1030.65  4624.8 1028.12
  4635.7 1026.65  4702.2 1024.35  4738.6 1021.68  4738.9 1021.18  4742.6 1021.68
  4878.8 1023.41  4997.7 1022.24  5061.1 1023.29  5216.1 1022.40  5240.3 1024.08
  5248.7 1023.41  5331.6 1025.72  5349.7 1028.04  5401.1 1028.11  5451.4 1031.29
  5524.4 1030.53  5672.9 1032.94  5762.5 1035.80  5791.6 1034.81  5908.2 1036.53
#Mann=7,-1,0
  4065.6    0.05       0  4074.5    0.12       0  4534.9    0.05       0
  4738.6   0.033       0  4742.6    0.05       0  5248.7    0.12       0
  5331.6    0.05       0
Bank Sta=4738.6,4742.6
Exp/Cntr=0.3,0.1

Type RM Length L Ch R = 1,11206,70,70,70
BEGIN DESCRIPTION:
Upper Denton 65 25.5
END DESCRIPTION:
XS GIS Cut Line= 3
      2206657.95      7253233.10      2205928.77      7253319.91
      2204999.91      7253541.27
#Sta/Elev= 30
  4266.7 1037.05  4316.0 1037.12  4369.4 1035.13  4406.6 1034.42  4426.8 1035.24
  4446.9 1034.06  4559.1 1032.41  4617.1 1029.96  4622.1 1030.62  4704.7 1025.88
  4792.3 1023.41  4799.4 1021.75  4807.5 1021.74  4807.7 1021.24  4811.5 1021.74
  4962.5 1023.62  5072.7 1021.86  5134.4 1022.42  5151.1 1023.54  5257.8 1022.41
  5282.6 1022.81  5288.6 1024.03  5324.8 1025.51  5340.0 1024.94  5366.9 1027.27
  5401.7 1026.74  5409.0 1028.56  5414.2 1027.14  5720.4 1033.88  5955.9 1036.12
#Mann=4,-1,0
  4266.7    0.12       0  4559.1    0.05       0  4807.5   0.033       0
  4811.5    0.05       0
Bank Sta=4807.5,4811.5
Exp/Cntr=0.3,0.1

Type RM Length L Ch R = 1,11136,93,93,93
BEGIN DESCRIPTION:
Upper Denton 65 25.4
END DESCRIPTION:
XS GIS Cut Line= 3
      2206553.77      7253198.38      2205905.04      7253253.23
      2205008.68      7253510.87
#Sta/Elev= 30
  4363.4 1035.83  4442.7 1034.85  4587.8 1030.45  4649.2 1028.97  4689.3 1025.76
  4729.5 1028.44  4796.4 1026.58  4801.4 1029.37  4915.9 1025.48  4921.0 1028.79
  4950.3 1028.74  5018.2 1025.18  5023.4 1028.72  5051.9 1027.63  5057.1 1029.99
  5176.8 1028.91  5197.1 1027.43  5202.3 1029.13  5236.0 1025.27  5241.2 1028.04
  5267.7 1024.28  5268.0 1023.78  5271.7 1024.28  5274.9 1026.48  5280.8 1025.04
  5301.7 1025.12  5332.9 1027.08  5487.6 1028.81  5604.3 1032.04  5947.1 1035.52
#Mann=4,-1,0
  4363.4    0.12       0  4587.8    0.05       0  5267.7   0.033       0
  5271.7    0.05       0
Bank Sta=5267.7,5271.7
Exp/Cntr=0.3,0.1

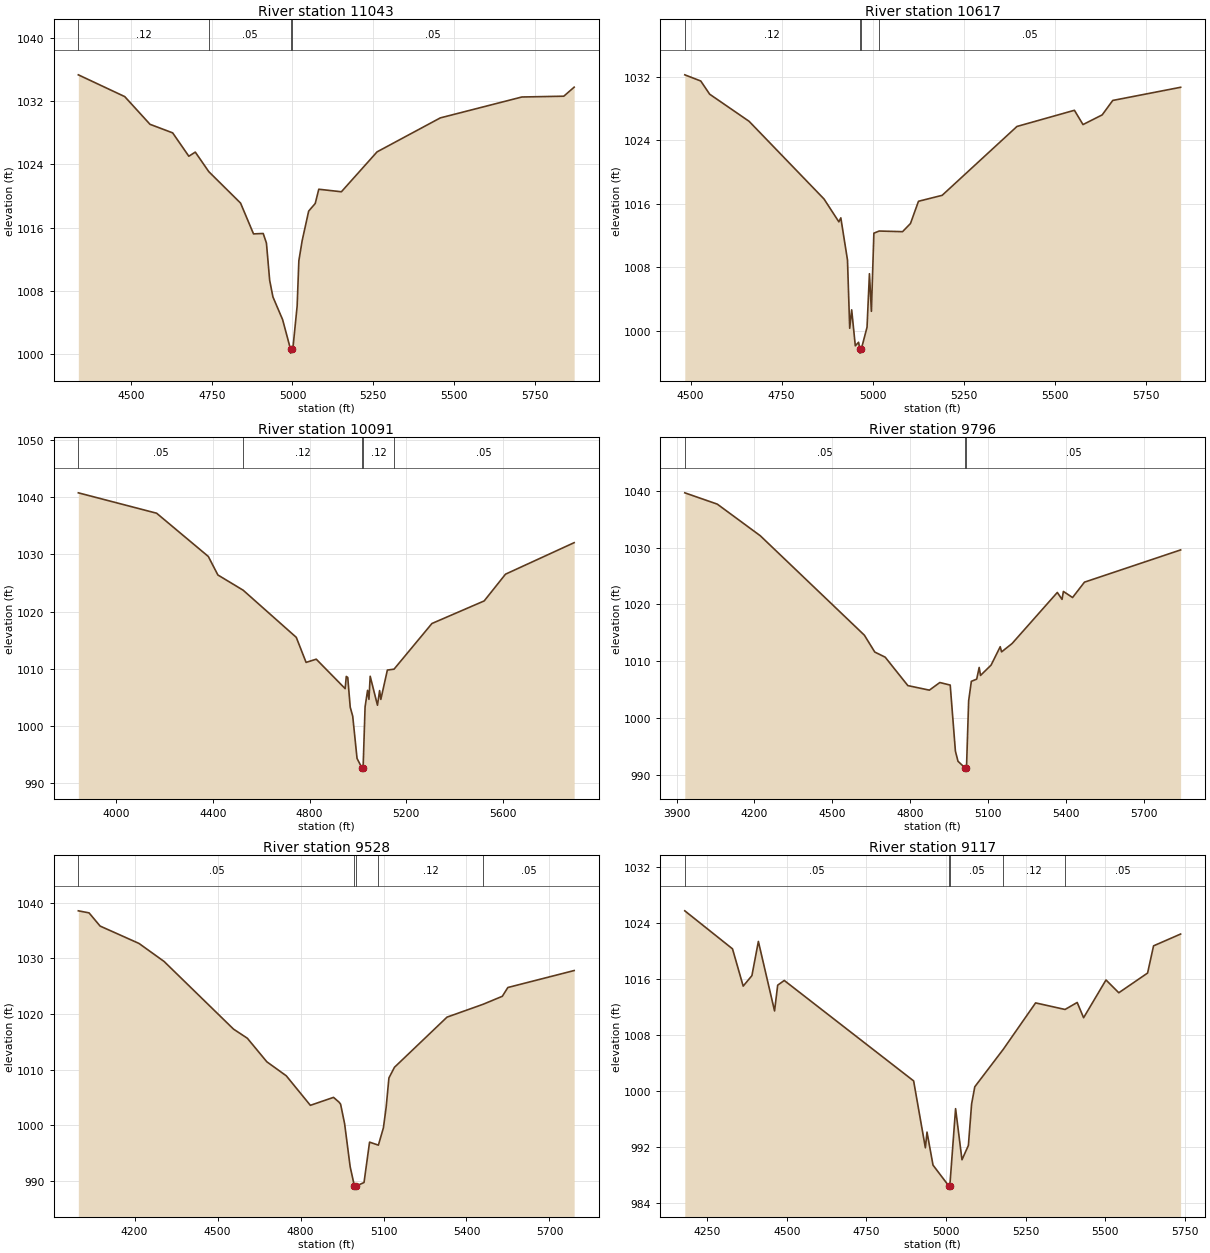
Type RM Length L Ch R = 1,11043,426,426,426
BEGIN DESCRIPTION:
Upper Denton 65 25.0
END DESCRIPTION:
XS GIS Cut Line= 3
      2206540.73      7253137.62      2205881.03      7253172.34
      2205017.34      7253311.23
#Sta/Elev= 30
  4336.9 1035.31  4480.6 1032.56  4558.9 1029.06  4629.0 1027.98  4679.1 1025.03
  4699.1 1025.55  4740.9 1023.08  4839.3 1019.11  4879.4 1015.22  4909.4 1015.27
  4919.4 1014.06  4929.4 1009.36  4939.5 1007.26  4969.5 1004.39  4994.0 1000.66
  4994.3 1000.16  4998.0 1000.66  5001.1 1000.66  5014.5 1006.12  5019.8 1011.83
  5030.0 1014.36  5050.2 1018.10  5070.5 1019.06  5081.5 1020.86  5151.5 1020.54
  5262.0 1025.58  5457.8 1029.87  5710.4 1032.51  5840.2 1032.61  5872.3 1033.75
#Mann=4,-1,0
  4336.9    0.12       0  4740.9    0.05       0  4994.0   0.033       0
  4998.0    0.05       0
Bank Sta=4994,4998
Exp/Cntr=0.3,0.1

Type RM Length L Ch R = 1,10617,526,526,526
BEGIN DESCRIPTION:
Upper Denton 65 24.0
END DESCRIPTION:
XS GIS Cut Line= 3
      2206315.04      7252950.98      2205829.00      7252760.00
      2205056.39      7253089.87
#Sta/Elev= 30
  4484.1 1032.27  4528.0 1031.49  4552.4 1029.83  4660.8 1026.41  4866.6 1016.62
  4907.4 1013.74  4912.8 1014.24  4931.1 1008.93  4937.2 1000.32  4942.6 1002.65
  4952.6  998.11  4961.6  998.56  4965.0  997.69  4965.3  997.19  4969.0  997.69
  4984.8 1000.45  4991.4 1007.20  4996.8 1002.46  5003.6 1012.31  5018.1 1012.58
  5082.4 1012.50  5104.2 1013.53  5126.1 1016.33  5191.2 1017.08  5396.7 1025.76
  5554.6 1027.80  5578.2 1026.00  5630.9 1027.22  5659.9 1029.04  5846.4 1030.70
#Mann=4,-1,0
  4484.1    0.12       0  4965.0    0.07       0  4969.0    0.12       0
  5018.1    0.05       0
Bank Sta=4965,4969
Exp/Cntr=0.3,0.1

Type RM Length L Ch R = 1,10091,295,295,295
BEGIN DESCRIPTION:
Upper Denton 65 23.0
END DESCRIPTION:
XS GIS Cut Line= 3
      2206818.58      7252191.43      2205724.78      7252365.05
      2204804.68      7252564.69
#Sta/Elev= 30
  3844.6 1040.73  4168.2 1037.17  4381.8 1029.62  4421.3 1026.39  4525.8 1023.73
  4745.3 1015.50  4785.8 1011.13  4827.8 1011.69  4947.3 1006.55  4951.9 1008.68
  4958.0 1008.50  4968.2 1003.31  4978.5 1001.75  4996.4  994.36  5017.4  992.65
  5017.6  992.15  5021.4  992.65  5029.6 1003.37  5039.9 1006.25  5045.6 1004.68
  5050.7 1008.71  5080.8 1003.65  5089.6 1006.21  5094.7 1004.67  5121.7 1009.79
  5149.3 1009.95  5305.9 1017.92  5521.8 1021.86  5609.9 1026.53  5893.6 1032.03
#Mann=5,-1,0
  3844.6    0.05       0  4525.8    0.12       0  5017.4    0.07       0
  5021.4    0.12       0  5149.3    0.05       0
Bank Sta=5017.4,5021.4
Exp/Cntr=0.3,0.1

Type RM Length L Ch R = 1,9796,268,268,268
BEGIN DESCRIPTION:
Upper Denton 65 22.0
END DESCRIPTION:
XS GIS Cut Line= 3
      2206649.25      7252069.91      2205585.89      7252113.31
      2204769.89      7251900.63
#Sta/Elev= 30
  3931.9 1039.63  4057.0 1037.64  4222.4 1032.08  4622.7 1014.60  4662.8 1011.63
  4702.8 1010.73  4790.1 1005.73  4872.9 1004.93  4913.0 1006.27  4953.0 1005.82
  4973.0  994.19  4983.0  992.42  5011.6  991.19  5011.8  990.69  5015.6  991.19
  5023.9 1003.06  5034.3 1006.48  5054.9 1006.87  5064.4 1008.92  5069.6 1007.52
  5110.1 1009.33  5145.4 1012.57  5150.6 1011.66  5191.1 1013.13  5365.0 1022.11
  5383.2 1020.89  5388.4 1022.29  5423.7 1021.22  5469.4 1023.92  5839.4 1029.59
#Mann=3,-1,0
  3931.9    0.05       0  5011.6   0.033       0  5015.6    0.05       0
Bank Sta=5011.6,5015.6
Exp/Cntr=0.3,0.1

Type RM Length L Ch R = 1,9528,411,411,411
BEGIN DESCRIPTION:
Upper Denton 65 21.0
END DESCRIPTION:
XS GIS Cut Line= 3
      2206627.60      7251952.73      2205629.00      7251860.00
      2204839.37      7251870.26
#Sta/Elev= 30
  3996.7 1038.55  4035.5 1038.18  4075.4 1035.81  4216.2 1032.68  4306.6 1029.45
  4557.7 1017.28  4607.9 1015.63  4678.2 1011.40  4748.5 1008.88  4835.6 1003.57
  4919.3 1005.00  4939.3 1004.14  4944.9 1003.78  4959.4 1000.27  4979.5  992.52
  4995.1  989.00  4995.3  988.50  4999.1  989.00  5029.6  989.69  5049.6  996.95
  5081.5  996.41  5099.6  999.51  5109.6 1003.23  5119.6 1008.49  5139.6 1010.41
  5329.6 1019.43  5460.0 1021.74  5529.6 1023.18  5549.6 1024.76  5789.3 1027.81
#Mann=5,-1,0
  3996.7    0.05       0  4995.1   0.033       0  4999.1    0.05       0
  5081.5    0.12       0  5460.0    0.05       0
Bank Sta=4995.1,4999.1
Exp/Cntr=0.3,0.1

Type RM Length L Ch R = 1,9117,335,335,335
BEGIN DESCRIPTION:
Upper Denton 65 20.0
END DESCRIPTION:
XS GIS Cut Line= 3
      2206486.49      7251656.50      2205674.86      7251513.27
      2204945.73      7251582.71
#Sta/Elev= 30
  4179.6 1025.74  4329.4 1020.30  4362.9 1014.97  4390.3 1016.47  4410.6 1021.36
  4461.4 1011.42  4471.2 1015.10  4491.8 1015.78  4898.0 1001.41  4934.9  991.84
  4940.0  994.09  4958.9  989.36  5007.7  986.43  5007.9  985.93  5011.7  986.43
  5029.7  997.44  5049.8  990.13  5069.9  992.18  5080.0  998.11  5090.0 1000.57
  5179.9 1005.96  5280.9 1012.57  5373.3 1011.63  5411.5 1012.63  5431.6 1010.45
  5501.9 1015.85  5542.1 1014.02  5632.5 1016.84  5651.2 1020.73  5736.2 1022.42
#Mann=5,-1,0
  4179.6    0.05       0  5007.7   0.033       0  5011.7    0.05       0
  5179.9    0.12       0  5373.3    0.05       0
Bank Sta=5007.7,5011.7
Exp/Cntr=0.3,0.1

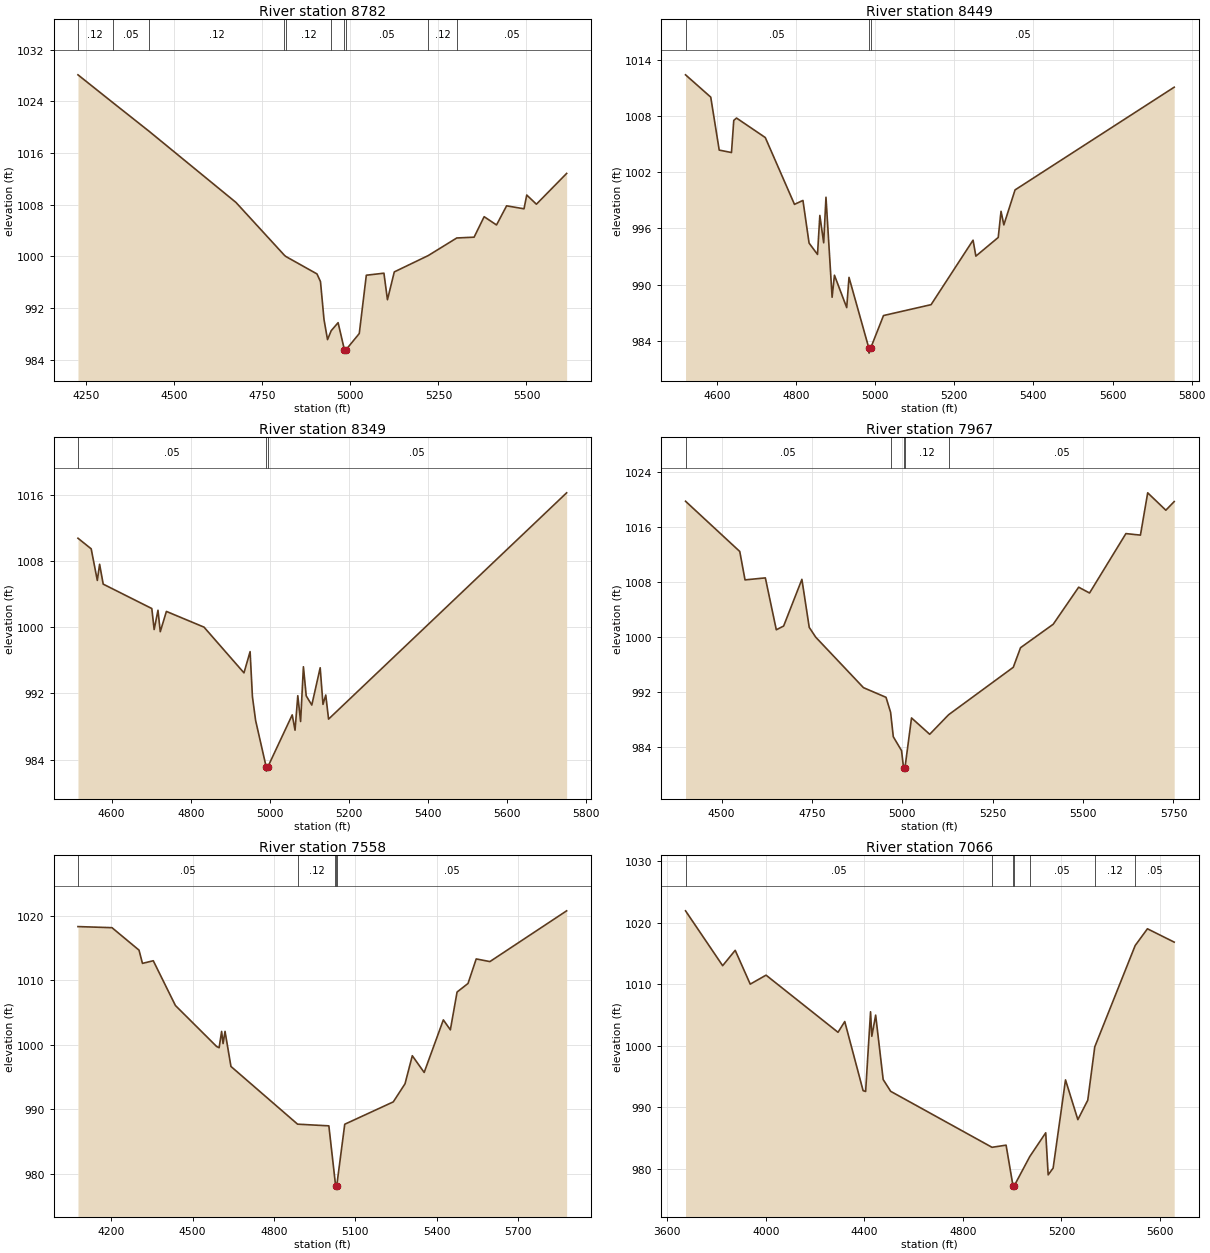
Type RM Length L Ch R = 1,8782,333,333,333
BEGIN DESCRIPTION:
Upper Denton 65 19.0
END DESCRIPTION:
XS GIS Cut Line= 4
      2206447.39      7251218.13      2205679.00      7251210.00
      2205540.53      7251215.17      2205173.43      7251524.58
#Sta/Elev= 30
  4226.9 1028.09  4325.5 1023.81  4428.1 1019.39  4675.3 1008.36  4813.1 1000.17
  4817.1  999.99  4905.3  997.30  4915.3  996.11  4925.3  990.24  4935.3  987.14
  4945.7  988.52  4965.3  989.76  4983.3  985.55  4983.6  985.05  4987.3  985.55
  5025.4  988.08  5045.4  997.10  5095.4  997.41  5105.4  993.31  5124.8  997.61
  5221.2 1000.14  5302.2 1002.86  5351.3 1002.98  5379.9 1006.15  5415.0 1004.87
  5443.6 1007.83  5493.0 1007.37  5500.8 1009.50  5528.2 1008.08  5614.0 1012.84
#Mann=10,-1,0
  4226.9    0.12       0  4325.5    0.05       0  4428.1    0.12       0
  4813.1    0.05       0  4817.1    0.12       0  4945.7    0.05       0
  4983.3   0.033       0  4987.3    0.05       0  5221.2    0.12       0
  5302.2    0.05       0
Bank Sta=4983.3,4987.3
Exp/Cntr=0.3,0.1

Type RM Length L Ch R = 1,8449,100,100,100
BEGIN DESCRIPTION:
Upper Denton 65 18.0
END DESCRIPTION:
XS GIS Cut Line= 3
      2206139.30      7250662.56      2205729.00      7250910.00
      2205193.55      7251443.37
#Sta/Elev= 30
  4521.0 1012.38  4584.7 1010.00  4606.1 1004.35  4637.1 1004.09  4642.9 1007.52
  4649.8 1007.77  4722.5 1005.69  4796.3  998.56  4817.7  998.98  4833.2  994.43
  4854.5  993.22  4860.4  997.38  4870.1  994.46  4875.9  999.32  4891.4  988.65
  4897.3  991.00  4928.3  987.55  4934.1  990.77  4984.5  983.19  4984.8  982.69
  4988.5  983.19  5021.3  986.70  5141.5  987.86  5247.6  994.74  5254.7  993.04
  5311.2  995.03  5318.3  997.82  5325.4  996.37  5353.7 1000.10  5755.9 1011.06
#Mann=3,-1,0
  4521.0    0.05       0  4984.5   0.033       0  4988.5    0.05       0
Bank Sta=4984.5,4988.5
Exp/Cntr=0.3,0.1

Type RM Length L Ch R = 1,8349,382,382,382
BEGIN DESCRIPTION:
Upper Denton 65 17.5
END DESCRIPTION:
XS GIS Cut Line= 3
      2206143.63      7250558.40      2205733.34      7250805.83
      2205197.46      7251339.63
#Sta/Elev= 30
  4514.8 1010.76  4548.2 1009.48  4563.7 1005.66  4569.5 1007.61  4578.6 1005.21
  4701.5 1002.26  4707.4  999.72  4717.1 1002.05  4722.9  999.46  4738.4 1001.91
  4833.5 1000.01  4934.5  994.48  4950.0  997.05  4955.9  991.59  4964.0  988.71
  4990.7  983.10  4991.0  982.60  4994.7  983.10  5056.5  989.40  5063.6  987.55
  5070.6  991.72  5077.7  988.60  5084.8  995.22  5091.9  991.70  5106.0  990.59
  5127.2  995.10  5134.3  990.67  5141.3  991.80  5148.4  988.89  5750.3 1016.25
#Mann=3,-1,0
  4514.8    0.05       0  4990.7   0.033       0  4994.7    0.05       0
Bank Sta=4990.7,4994.7
Exp/Cntr=0.3,0.1

Type RM Length L Ch R = 1,7967,409,409,409
BEGIN DESCRIPTION:
Upper Denton 65 17.0
END DESCRIPTION:
XS GIS Cut Line= 3
      2206317.25      7250549.73      2205729.00      7250460.00
      2204976.05      7250536.71
#Sta/Elev= 30
  4400.1 1019.69  4550.1 1012.41  4564.7 1008.29  4620.9 1008.58  4651.2 1001.06
  4671.5 1001.60  4722.0 1008.37  4742.3 1001.41  4760.2  999.99  4892.3  992.67
  4954.7  991.27  4967.4  989.10  4974.9  985.55  4997.7  983.54  5003.2  981.07
  5003.5  980.57  5007.2  981.07  5025.3  988.28  5075.6  985.91  5127.8  988.74
  5306.8  995.62  5326.9  998.46  5417.3 1001.86  5487.7 1007.23  5517.8 1006.39
  5618.4 1015.00  5658.6 1014.78  5678.7 1020.91  5728.9 1018.39  5752.0 1019.64
#Mann=5,-1,0
  4400.1    0.05       0  4967.4    0.12       0  5003.2    0.07       0
  5007.2    0.12       0  5127.8    0.05       0
Bank Sta=5003.2,5007.2
Exp/Cntr=0.3,0.1

Type RM Length L Ch R = 1,7558,492,492,492
BEGIN DESCRIPTION:
Upper Denton 65 16.0
END DESCRIPTION:
XS GIS Cut Line= 3
      2206577.63      7250415.17      2205726.95      7250050.60
      2204858.94      7250176.46
#Sta/Elev= 30
  4077.2 1018.29  4202.7 1018.12  4302.4 1014.64  4315.1 1012.59  4355.0 1013.00
  4436.6 1006.07  4588.9  999.71  4597.9  999.53  4607.1 1002.05  4612.5 1000.17
  4619.7 1002.06  4641.5  996.63  4887.3  987.69  5002.7  987.43  5026.4  978.60
  5027.6  978.13  5027.9  977.63  5031.7  978.13  5061.3  987.68  5240.3  991.14
  5283.6  993.94  5310.5  998.29  5354.3  995.70  5425.0 1003.84  5450.9 1002.30
  5475.6 1008.15  5516.0 1009.48  5546.3 1013.28  5596.8 1012.87  5879.8 1020.73
#Mann=5,-1,0
  4077.2    0.05       0  4887.3    0.12       0  5026.4    0.05       0
  5027.6    0.07       0  5031.7    0.05       0
Bank Sta=5027.6,5031.7
Exp/Cntr=0.3,0.1

Type RM Length L Ch R = 1,7066,556,556,556
BEGIN DESCRIPTION:
Upper Denton 65 15.0
END DESCRIPTION:
XS GIS Cut Line= 3
      2206976.96      7249855.29      2205679.00      7249610.00
      2205019.46      7249555.80
#Sta/Elev= 30
  3674.6 1021.90  3825.2 1012.98  3876.1 1015.48  3937.1 1009.98  4001.3 1011.44
  4293.3 1002.15  4320.6 1003.90  4395.1  992.66  4405.3  992.53  4425.3 1005.49
  4430.4 1001.50  4446.0 1004.94  4476.5  994.47  4507.0  992.55  4918.1  983.45
  4975.2  983.80  5003.4  977.15  5003.8  976.65  5007.7  977.15  5071.2  981.94
  5136.0  985.81  5146.0  978.97  5166.1  980.07  5216.3  994.41  5266.4  987.95
  5306.6  991.11  5335.0  999.78  5498.9 1016.25  5548.7 1018.98  5657.3 1016.81
#Mann=7,-1,0
  3674.6    0.05       0  4918.1    0.12       0  5003.4    0.07       0
  5007.7    0.12       0  5071.2    0.05       0  5335.0    0.12       0
  5498.9    0.05       0
Bank Sta=5003.4,5007.7
Exp/Cntr=0.3,0.1

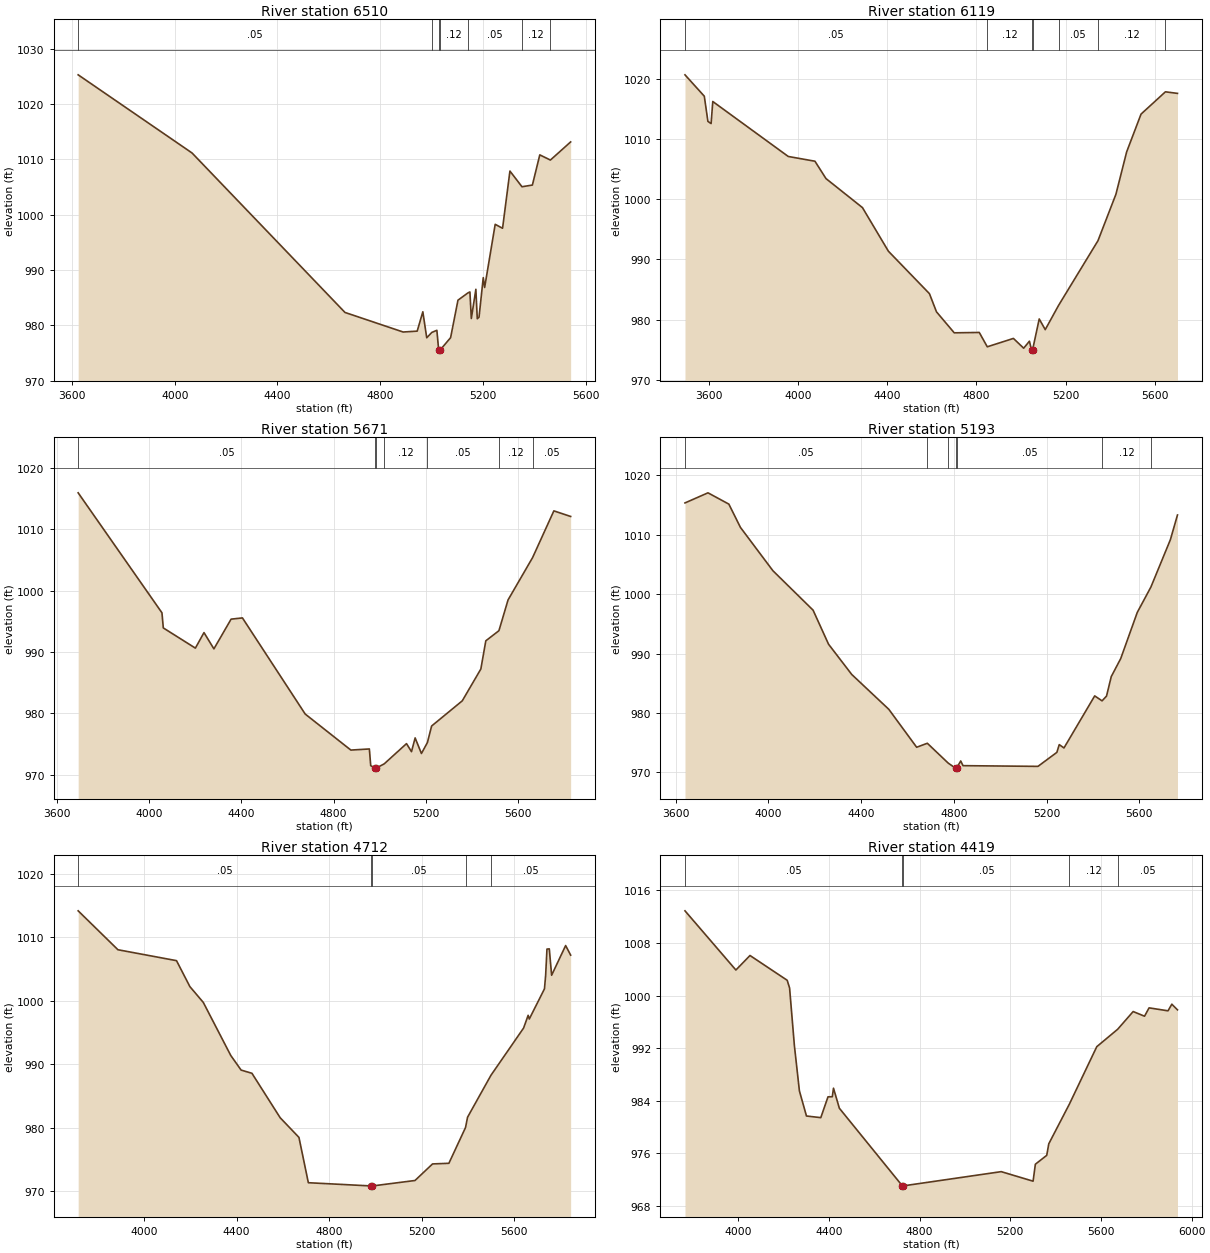
Type RM Length L Ch R = 1,6510,391,391,391
BEGIN DESCRIPTION:
Upper Denton 65 14.0
END DESCRIPTION:
XS GIS Cut Line= 3
      2207035.07      7249707.48      2205750.38      7249134.58
      2205282.82      7248926.78
#Sta/Elev= 30
  3623.8 1025.31  4067.4 1011.17  4663.1  982.32  4889.6  978.78  4944.4  978.94
  4966.3  982.44  4981.5  977.74  5001.2  978.70  5021.0  979.09  5028.2  975.46
  5028.6  974.96  5032.6  975.46  5074.5  977.76  5103.2  984.54  5141.9  985.85
  5149.7  986.03  5155.2  981.22  5172.9  986.51  5178.4  981.18  5185.2  981.46
  5201.7  988.62  5207.1  986.84  5248.2  998.26  5276.9  997.55  5305.6 1007.90
  5352.5 1005.06  5393.1 1005.37  5421.9 1010.83  5463.2 1009.89  5542.1 1013.17
#Mann=7,-1,0
  3623.8    0.05       0  5001.2    0.12       0  5028.2   0.033       0
  5032.6    0.12       0  5141.9    0.05       0  5352.5    0.12       0
  5463.2    0.05       0
Bank Sta=5028.2,5032.6
Exp/Cntr=0.3,0.1

Type RM Length L Ch R = 1,6119,448,448,448
BEGIN DESCRIPTION:
Upper Denton 65 13.0
END DESCRIPTION:
XS GIS Cut Line= 3
      2207252.12      7249525.20      2205929.00      7248810.00
      2205255.62      7248596.39
#Sta/Elev= 30
  3491.6 1020.63  3578.3 1017.08  3594.5 1012.90  3608.8 1012.54  3616.4 1016.20
  3955.1 1007.08  4074.9 1006.29  4124.5 1003.41  4288.2  998.59  4404.5  991.36
  4588.8  984.31  4620.5  981.29  4700.1  977.81  4812.5  977.87  4848.4  975.49
  4965.7  976.88  5011.8  975.26  5037.6  976.42  5047.1  974.94  5047.5  974.44
  5051.5  974.94  5081.6  980.11  5108.6  978.34  5168.7  982.38  5345.3  993.10
  5425.8 1000.80  5474.1 1007.85  5538.6 1014.11  5648.0 1017.81  5702.1 1017.55
#Mann=7,-1,0
  3491.6    0.05       0  4848.4    0.12       0  5047.1    0.07       0
  5051.5    0.12       0  5168.7    0.05       0  5345.3    0.12       0
  5648.0    0.05       0
Bank Sta=5047.1,5051.5
Exp/Cntr=0.3,0.1

Type RM Length L Ch R = 1,5671,478,478,478
BEGIN DESCRIPTION:
Upper Denton 65 12.0
END DESCRIPTION:
XS GIS Cut Line= 3
      2207364.94      7249169.29      2206229.00      7248510.00
      2205515.99      7248101.58
#Sta/Elev= 30
  3692.4 1015.95  4055.7  996.40  4061.5  993.94  4200.6  990.65  4237.9  993.18
  4280.9  990.53  4355.4  995.37  4404.6  995.57  4676.7  979.91  4874.6  974.04
  4954.9  974.22  4960.7  971.50  4980.4  971.11  4980.9  970.61  4984.9  971.11
  5019.4  971.80  5115.9  975.09  5137.5  973.78  5153.3  976.02  5180.6  973.48
  5206.5  975.27  5224.8  977.96  5357.6  982.06  5438.2  987.25  5459.7  991.84
  5516.6  993.49  5556.1  998.50  5662.7 1005.41  5754.7 1013.01  5827.5 1012.10
#Mann=7,-1,0
  3692.4    0.05       0  4980.4   0.033       0  4984.9    0.05       0
  5019.4    0.12       0  5206.5    0.05       0  5516.6    0.12       0
  5662.7    0.05       0
Bank Sta=4980.4,4984.9
Exp/Cntr=0.3,0.1

Type RM Length L Ch R = 1,5193,481,481,481
BEGIN DESCRIPTION:
Upper Denton 65 11.0
END DESCRIPTION:
XS GIS Cut Line= 3
      2207738.19      7248101.59      2206379.00      7248110.00
      2205628.97      7247959.99
#Sta/Elev= 30
  3640.7 1015.36  3739.9 1017.06  3829.9 1015.16  3879.9 1011.24  4019.9 1003.95
  4193.2  997.31  4259.9  991.58  4359.9  986.49  4519.9  980.62  4639.9  974.24
  4685.9  974.91  4776.0  971.57  4807.7  970.72  4808.1  970.22  4812.2  970.72
  4829.9  971.93  4839.9  971.14  5163.1  971.02  5244.7  973.38  5254.9  974.68
  5275.3  974.12  5407.8  982.88  5439.6  982.05  5458.8  982.85  5479.2  986.13
  5520.0  989.16  5591.4  996.93  5650.3 1001.21  5734.2 1009.17  5764.8 1013.33
#Mann=7,-1,0
  3640.7    0.05       0  4685.9    0.12       0  4776.0    0.05       0
  4807.7   0.033       0  4812.2    0.05       0  5439.6    0.12       0
  5650.3    0.05       0
Bank Sta=4807.7,4812.2
Exp/Cntr=0.3,0.1

Type RM Length L Ch R = 1,4712,293,293,293
BEGIN DESCRIPTION:
Upper Denton 65 10.0
END DESCRIPTION:
XS GIS Cut Line= 3
      2207738.21      7247893.26      2206479.00      7247660.00
      2205637.51      7247780.42
#Sta/Elev= 30
  3714.3 1014.17  3886.4 1008.04  4139.8 1006.32  4197.7 1002.23  4255.7  999.74
  4374.6  991.38  4419.4  989.08  4466.1  988.58  4588.2  981.58  4669.5  978.48
  4710.2  971.34  4982.4  970.83  4982.9  970.33  4987.2  970.83  5171.6  971.69
  5247.5  974.30  5318.2  974.40  5390.2  980.03  5399.0  981.66  5500.3  988.27
  5641.5  995.71  5661.1  997.71  5666.1  997.13  5731.7 1001.88  5736.8 1003.98
  5742.5 1008.14  5752.6 1008.18  5762.7 1004.02  5823.3 1008.70  5845.0 1007.19
#Mann=5,-1,0
  3714.3    0.05       0  4982.4   0.033       0  4987.2    0.05       0
  5390.2    0.12       0  5500.3    0.05       0
Bank Sta=4982.4,4987.2
Exp/Cntr=0.3,0.1

Type RM Length L Ch R = 1,4419,120,120,120
BEGIN DESCRIPTION:
Upper Denton 65 9.5
END DESCRIPTION:
XS GIS Cut Line= 3
      2207694.79      7247789.08      2206526.92      7247383.61
      2205594.14      7247311.66
#Sta/Elev= 30
  3765.8 1012.89  3990.3 1003.88  4052.5 1006.09  4216.5 1002.32  4227.1 1001.14
  4248.3  992.36  4270.4  985.48  4301.5  981.66  4364.7  981.41  4396.5  984.58
  4415.4  984.59  4420.7  985.89  4446.6  982.84  4724.3  971.03  4724.8  970.53
  4729.1  971.03  5160.4  973.19  5300.9  971.74  5310.9  974.32  5361.0  975.67
  5370.1  977.43  5460.8  983.46  5581.7  992.21  5673.8  994.86  5742.2  997.56
  5792.3  996.85  5812.4  998.12  5895.9  997.67  5912.7  998.68  5937.6  997.82
#Mann=5,-1,0
  3765.8    0.05       0  4724.3   0.033       0  4729.1    0.05       0
  5460.8    0.12       0  5673.8    0.05       0
Bank Sta=4724.3,4729.1
Exp/Cntr=0.3,0.1

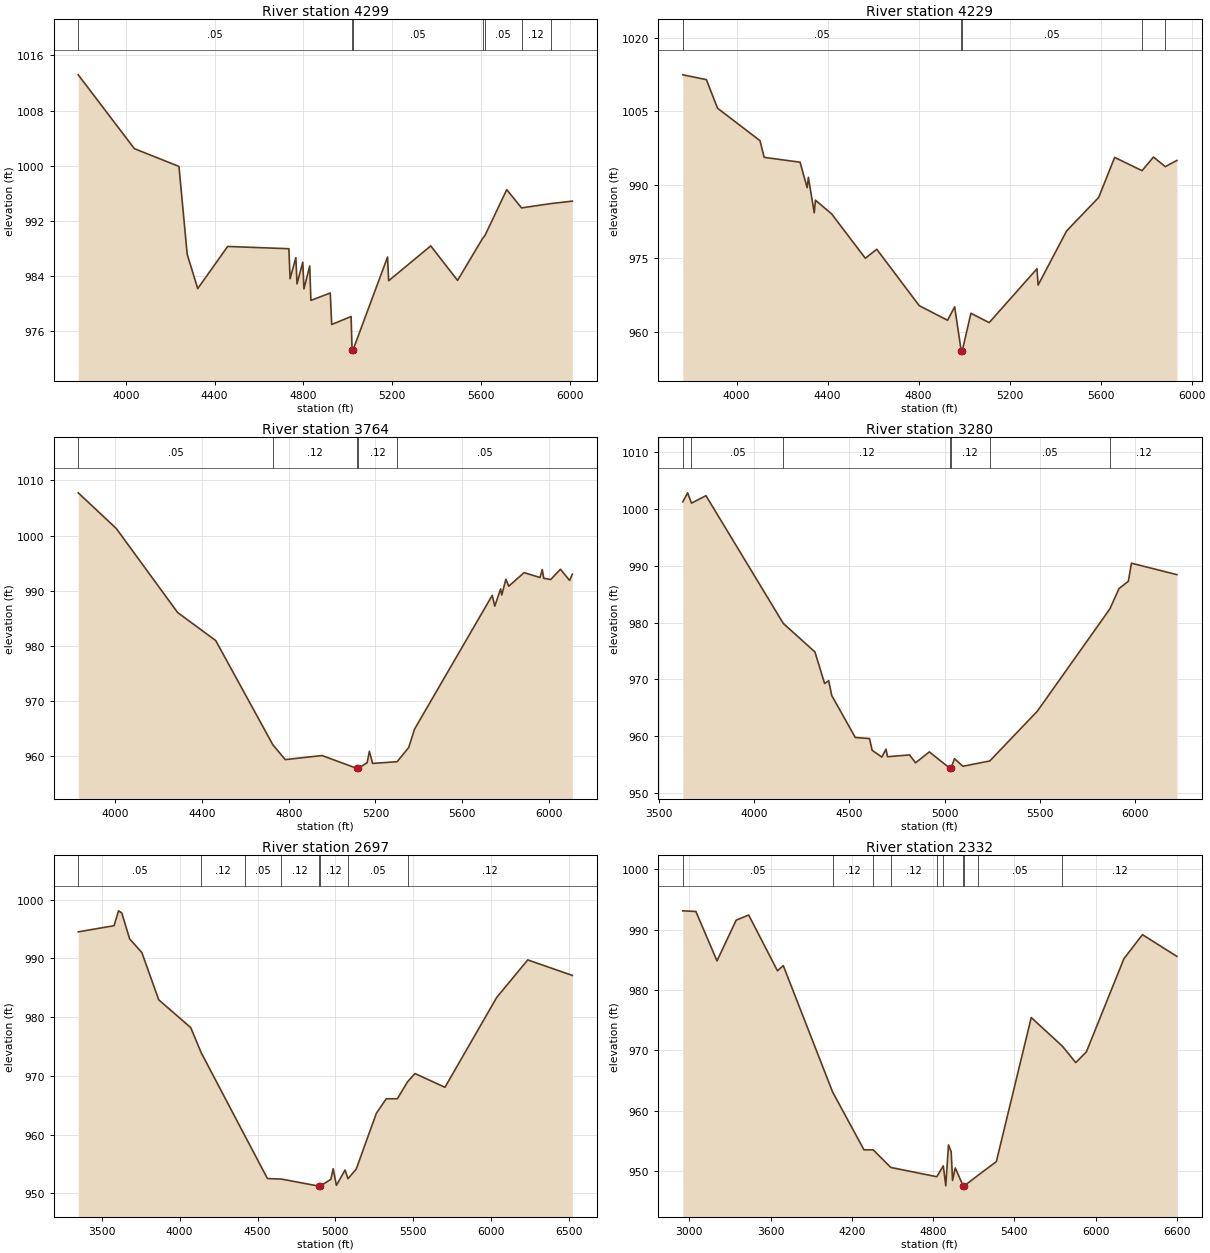
Type RM Length L Ch R = 1,4299,70,70,70
BEGIN DESCRIPTION:
Upper Denton 65 9.4
END DESCRIPTION:
XS GIS Cut Line= 3
      2207728.31      7247674.53      2206565.12      7247275.23
      2205575.57      7247153.71
#Sta/Elev= 30
  3785.2 1013.19  4038.2 1002.47  4239.1  999.89  4276.3  987.12  4323.7  982.15
  4458.6  988.27  4734.6  987.94  4739.9  983.58  4765.9  986.65  4771.2  982.84
  4797.2  985.99  4802.4  982.11  4828.4  985.43  4833.7  980.44  4921.0  981.51
  4927.5  976.94  5015.0  978.10  5019.2  973.28  5019.7  972.78  5024.0  973.28
  5179.2  986.74  5184.2  983.29  5373.8  988.35  5494.7  983.34  5608.1  989.46
  5618.3  989.87  5716.4  996.52  5783.0  993.87  5914.3  994.49  6012.0  994.85
#Mann=7,-1,0
  3785.2    0.05       0  5019.2   0.033       0  5024.0    0.05       0
  5608.1    0.12       0  5618.3    0.05       0  5783.0    0.12       0
  5914.3    0.05       0
Bank Sta=5019.2,5024
Exp/Cntr=0.3,0.1

Type RM Length L Ch R = 1,4229,465,465,465
BEGIN DESCRIPTION:
Upper Denton 65 9.0
END DESCRIPTION:
XS GIS Cut Line= 3
      2207746.90      7247615.48      2206579.00      7247210.00
      2205646.26      7247138.06
#Sta/Elev= 30
  3763.4 1012.45  3867.0 1011.47  3916.0 1005.64  4102.7  999.01  4121.1  995.60
  4278.9  994.61  4310.0  989.40  4315.3  991.52  4341.1  984.28  4346.4  986.86
  4417.5  984.06  4565.7  975.00  4615.9  976.84  4802.7  965.32  4927.2  962.34
  4958.3  965.09  4987.0  956.13  4987.6  955.63  4991.8  956.13  5029.8  963.77
  5110.0  961.86  5320.2  972.86  5325.2  969.52  5450.4  980.58  5591.4  987.42
  5661.6  995.59  5782.0  992.89  5832.2  995.66  5884.4  993.71  5935.2  994.97
#Mann=5,-1,0
  3763.4    0.05       0  4987.0   0.033       0  4991.8    0.05       0
  5782.0    0.12       0  5884.4    0.05       0
Bank Sta=4987,4991.8
Exp/Cntr=0.3,0.1

Type RM Length L Ch R = 1,3764,484,484,484
BEGIN DESCRIPTION:
Upper Denton 65 8.0
END DESCRIPTION:
XS GIS Cut Line= 3
      2207642.72      7247355.05      2206629.00      7246760.00
      2205576.80      7247094.64
#Sta/Elev= 30
  3828.7 1007.76  4003.9 1001.30  4287.1  986.04  4463.0  980.94  4726.5  962.03
  4783.9  959.33  4953.4  960.07  5114.5  957.74  5115.1  957.24  5119.4  957.74
  5161.6  958.76  5172.1  960.84  5186.7  958.64  5299.8  958.95  5353.2  961.52
  5380.1  964.85  5738.7  989.15  5750.5  987.19  5777.5  990.33  5782.7  989.22
  5801.7  992.07  5815.0  990.81  5885.6  993.27  5959.1  992.39  5969.6  993.82
  5976.2  992.25  6008.4  992.02  6053.5  993.89  6095.5  991.86  6108.3  992.99
#Mann=5,-1,0
  3828.7    0.05       0  4726.5    0.12       0  5114.5    0.07       0
  5119.4    0.12       0  5299.8    0.05       0
Bank Sta=5114.5,5119.4
Exp/Cntr=0.3,0.1

Type RM Length L Ch R = 1,3280,583,583,583
BEGIN DESCRIPTION:
Upper Denton 65 7.0
END DESCRIPTION:
XS GIS Cut Line= 3
      2207819.75      7246995.39      2206629.00      7246310.00
      2205563.43      7246899.54
#Sta/Elev= 30
  3626.0 1001.29  3651.3 1002.87  3671.4 1001.05  3747.5 1002.37  4152.9  979.86
  4319.2  974.82  4369.8  969.26  4391.3  969.76  4407.1  967.16  4530.7  959.75
  4605.4  959.56  4619.2  957.49  4670.1  956.30  4691.7  957.69  4699.9  956.36
  4815.3  956.68  4846.9  955.29  4919.1  957.21  5027.2  954.32  5027.8  953.82
  5032.1  954.32  5051.4  956.01  5095.0  954.68  5236.2  955.61  5485.5  964.38
  5866.6  982.44  5913.8  985.99  5963.0  987.28  5979.1  990.47  6217.7  988.45
#Mann=7,-1,0
  3626.0    0.12       0  3671.4    0.05       0  4152.9    0.12       0
  5027.2    0.07       0  5032.1    0.12       0  5236.2    0.05       0
  5866.6    0.12       0
Bank Sta=5027.2,5032.1
Exp/Cntr=0.3,0.1

Type RM Length L Ch R = 1,2697,365,365,365
BEGIN DESCRIPTION:
Upper Denton 65 6.0
END DESCRIPTION:
XS GIS Cut Line= 4
      2207941.23      7246760.98      2206621.82      7245754.06
      2206457.89      7245785.38      2205588.85      7246813.06
#Sta/Elev= 30
  3348.8  994.51  3578.6  995.56  3607.7  998.09  3628.5  997.73  3678.7  993.32
  3757.3  990.99  3865.4  982.96  4071.2  978.22  4138.1  973.96  4418.0  959.86
  4563.7  952.54  4653.6  952.45  4896.4  951.24  4897.0  950.74  4901.4  951.24
  4971.0  952.41  4985.6  954.22  5006.4  951.38  5062.0  953.99  5080.6  952.52
  5133.6  954.14  5262.8  963.64  5326.5  966.11  5397.9  966.12  5463.1  969.00
  5511.1  970.40  5703.4  968.07  6036.3  983.38  6235.1  989.74  6521.3  987.10
#Mann=8,-1,0
  3348.8    0.05       0  4138.1    0.12       0  4418.0    0.05       0
  4653.6    0.12       0  4896.4    0.07       0  4901.4    0.12       0
  5080.6    0.05       0  5463.1    0.12       0
Bank Sta=4896.4,4901.4
Exp/Cntr=0.3,0.1

Type RM Length L Ch R = 1,2332,452,452,452
BEGIN DESCRIPTION:
Upper Denton 65 5.0
END DESCRIPTION:
XS GIS Cut Line= 4
      2208175.64      7246639.48      2206743.34      7245410.00
      2206579.00      7245410.00      2205614.85      7246682.91
#Sta/Elev= 30
  2952.3  993.10  3049.0  992.99  3204.8  984.80  3346.4  991.55  3438.6  992.41
  3651.5  983.16  3694.3  984.02  4058.4  963.08  4290.2  953.49  4358.2  953.48
  4488.3  950.56  4828.0  949.03  4876.1  950.83  4894.3  947.52  4914.3  954.30
  4934.3  953.15  4944.3  948.41  4964.3  950.48  5023.6  947.47  5024.2  946.97
  5028.6  947.47  5132.7  949.26  5267.7  951.53  5525.4  975.41  5755.3  970.67
  5854.1  967.94  5932.6  969.72  6209.9  985.17  6346.6  989.15  6601.1  985.55
#Mann=10,-1,0
  2952.3    0.05       0  4058.4    0.12       0  4358.2    0.05       0
  4488.3    0.12       0  4828.0    0.05       0  4876.1    0.12       0
  5023.6    0.07       0  5028.6    0.12       0  5132.7    0.05       0
  5755.3    0.12       0
Bank Sta=5023.6,5028.6
Exp/Cntr=0.3,0.1