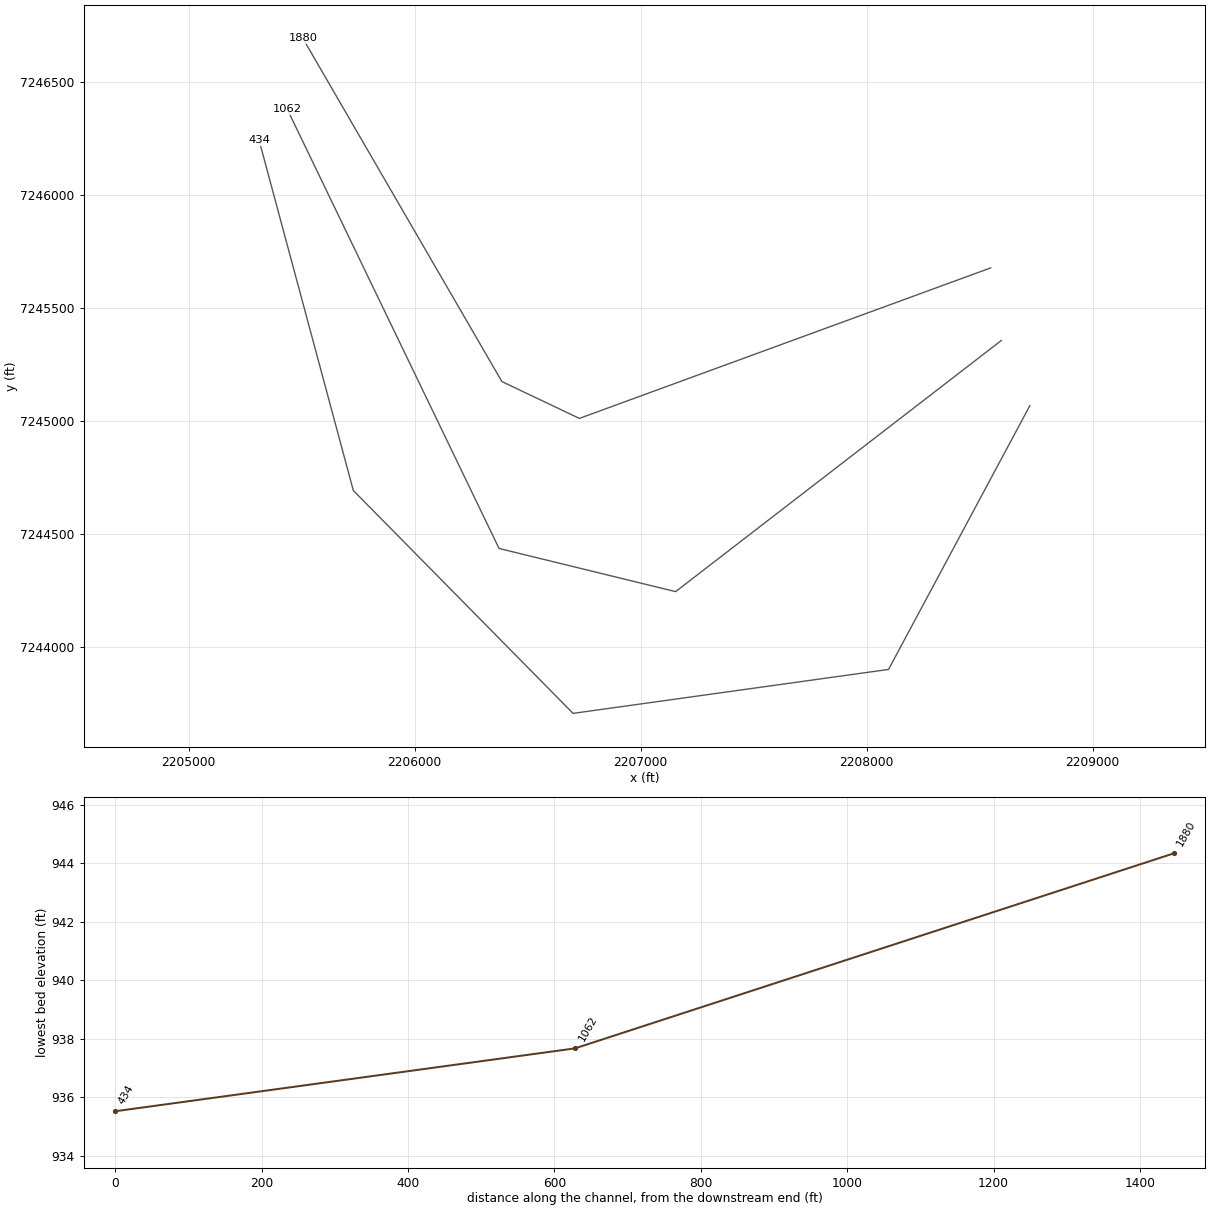
HEC-RAS study Upper Denton 65.prj: Upper Denton 65 Base Level Engineering

--- Upper Denton 65.g01 (geometry) --- (continued)

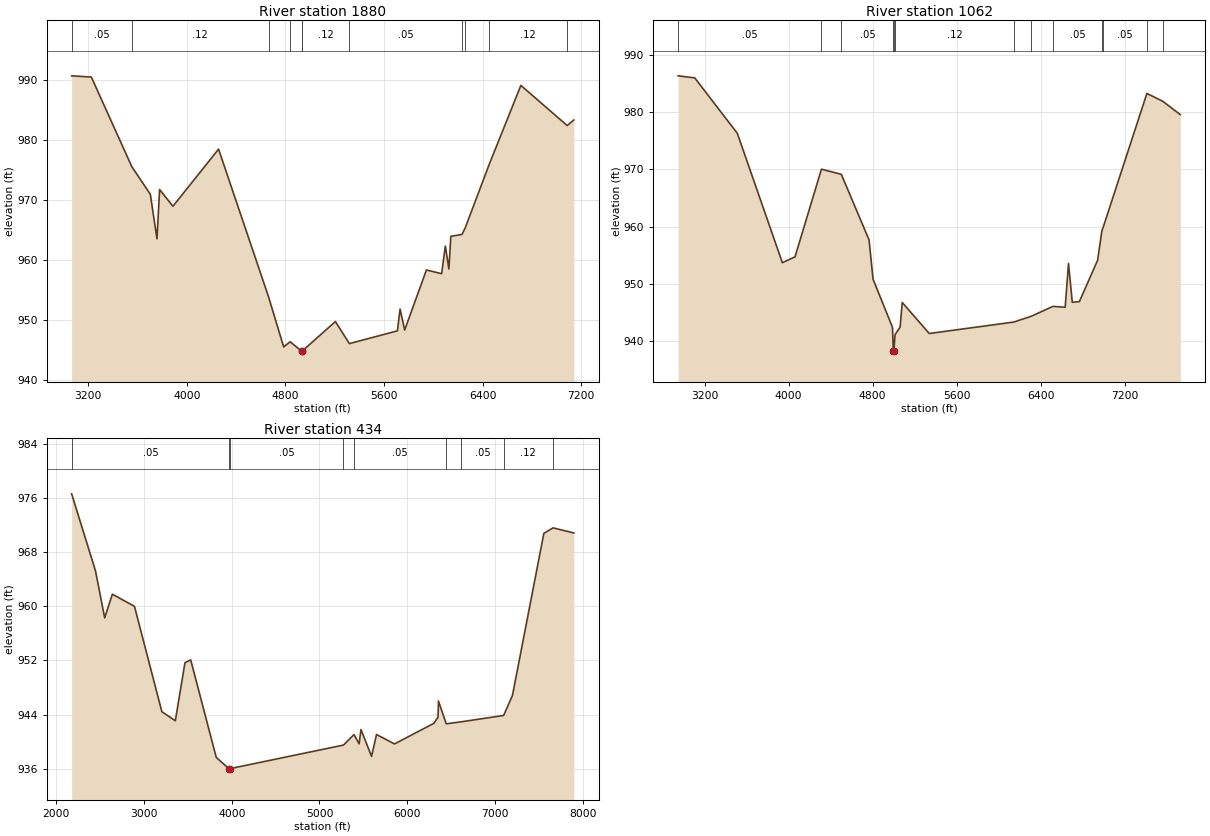
Type RM Length L Ch R = 1,1880,818,818,818
BEGIN DESCRIPTION:
Upper Denton 65 4.0
END DESCRIPTION:
XS GIS Cut Line= 4
      2208548.93      7245675.95      2206729.00      7245010.00
      2206386.19      7245173.00      2205505.49      7246691.56
#Sta/Elev= 30
  3066.6  990.62  3226.3  990.42  3554.2  975.53  3704.8  970.92  3758.7  963.51
  3780.0  971.71  3888.0  968.93  4258.2  978.43  4664.4  953.82  4786.3  945.53
  4838.6  946.40  4931.0  944.84  4931.7  944.34  4936.1  944.84  5205.9  949.76
  5319.1  946.09  5708.8  948.21  5730.3  951.84  5767.6  948.35  5944.0  958.33
  6067.4  957.72  6097.4  962.32  6126.2  958.51  6141.9  963.93  6232.4  964.24
  6258.5  965.33  6455.1  975.99  6710.1  989.03  7085.7  982.35  7139.6  983.28
#Mann=11,-1,0
  3066.6    0.05       0  3554.2    0.12       0  4664.4    0.05       0
  4838.6    0.12       0  4931.0    0.07       0  4936.1    0.12       0
  5319.1    0.05       0  6232.4    0.12       0  6258.5    0.05       0
  6455.1    0.12       0  7085.7    0.05       0
Bank Sta=4931,4936.1
Exp/Cntr=0.3,0.1

Type RM Length L Ch R = 1,1062,628,628,628
BEGIN DESCRIPTION:
Upper Denton 65 3.0
END DESCRIPTION:
XS GIS Cut Line= 4
      2208595.74      7245354.72      2207154.80      7244243.64
      2206373.55      7244434.61      2205436.04      7246379.09
#Sta/Elev= 30
  2948.4  986.38  3106.9  986.02  3512.5  976.31  3941.2  953.67  4061.7  954.70
  4313.4  970.04  4502.7  969.14  4766.8  957.67  4804.8  950.79  4990.1  942.36
  4997.8  938.17  4998.5  937.67  5003.0  938.17  5014.3  941.08  5062.2  942.38
  5082.8  946.71  5340.1  941.28  6144.3  943.28  6311.9  944.30  6518.4  946.03
  6634.4  945.87  6666.2  953.55  6702.2  946.74  6770.1  946.87  6943.7  954.12
  6983.9  959.24  6997.2  959.92  7412.8  983.30  7565.2  981.91  7730.9  979.59
#Mann=13,-1,0
  2948.4    0.05       0  4313.4    0.12       0  4502.7    0.05       0
  4997.8   0.033       0  5003.0    0.05       0  5014.3    0.12       0
  6144.3    0.05       0  6311.9    0.12       0  6518.4    0.05       0
  6983.9    0.12       0  6997.2    0.05       0  7412.8    0.12       0
  7565.2    0.05       0
Bank Sta=4997.8,5003
Exp/Cntr=0.3,0.1

Type RM Length L Ch R = 1,434,0,0,0
BEGIN DESCRIPTION:
Upper Denton 65 2.0
END DESCRIPTION:
XS GIS Cut Line= 5
      2208721.89      7245066.14      2208096.87      7243899.44
      2206701.04      7243705.00      2205728.81      7244691.11
      2205312.14      7246239.76
#Sta/Elev= 30
  2176.5  976.58  2448.7  965.19  2552.7  958.28  2640.4  961.77  2892.3  959.98
  3204.2  944.44  3357.8  943.10  3467.4  951.66  3532.8  952.08  3824.1  937.69
  3969.8  936.02  3970.5  935.52  3975.2  936.02  5272.8  939.51  5393.3  941.06
  5451.7  939.70  5473.0  941.80  5593.2  937.85  5649.7  941.07  5854.9  939.68
  6303.4  942.72  6350.6  943.63  6355.8  946.01  6443.8  942.65  6612.9  942.94
  7098.1  943.88  7198.5  946.83  7556.4  970.75  7660.8  971.56  7897.9  970.81
#Mann=9,-1,0
  2176.5    0.05       0  3969.8    0.04       0  3975.2    0.05       0
  5272.8    0.12       0  5393.3    0.05       0  6443.8    0.12       0
  6612.9    0.05       0  7098.1    0.12       0  7660.8    0.05       0
Bank Sta=3969.8,3975.2
Exp/Cntr=0.3,0.1

Chan Stop Cuts=-1