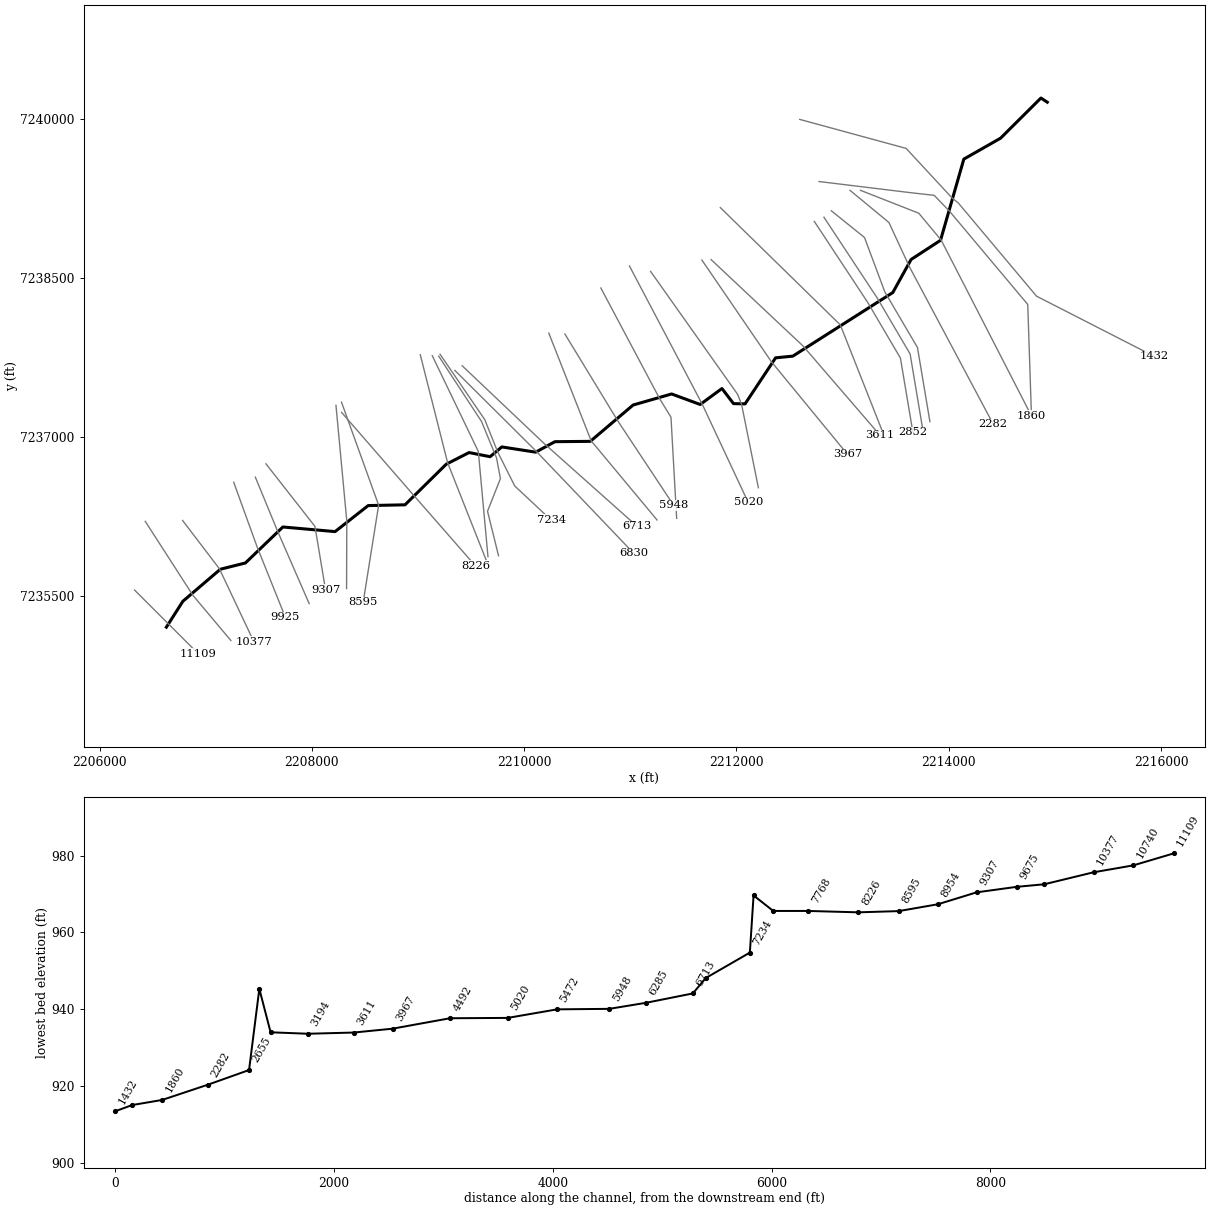
--- Upper Denton 69.prj (project) ---

Proj Title=Upper Denton 69 Base Level Engineering
Current Plan=p01
Default Exp/Contr=0.3,0.1
English Units
Geom File=g01
Flow File=f01
Plan File=p01
Y Axis Title=Elevation
X Axis Title(PF)=Main Channel Distance
X Axis Title(XS)=Station
BEGIN DESCRIPTION:
Upper Denton 69
END DESCRIPTION:
DSS Export Rating Curves= 0
DSS Export Rating Curve Sorted= 0
DSS Export Volume Flow Curves= 0
DXF OffsetX= 0
DXF OffsetY= 0
DXF ScaleX= 1
DXF ScaleY= 10

--- Upper Denton 69.p01 (plan) ---

Plan Title=Multiple Run
Short Identifier=Multiple
Geom File=g01
Flow File=f01
Subcritical Flow
K Sum by GR= 0
Std Step Tol= 0.01
Critical Tol= 0.01
Num of Std Step Trials= 20
Max Error Tol= 0.3
Flow Tol Ratio= 0.001
Split Flow NTrial= 30
Split Flow Tol= 0.02
Split Flow Ratio= 0.02
Log Output Level= 0
Friction Slope Method= 1
Unsteady Friction Slope Method= 2
Unsteady Bridges Friction Slope Method= 1
Parabolic Critical Depth
Global Vel Dist=  1 , 1 , 1
Global Log Level= 0
CheckData=True
Encroach Param= -1, 0, 0, 0
BEGIN DESCRIPTION:
Multiple Run
END DESCRIPTION:

--- Upper Denton 69.f01 (steady flow) ---

Flow Title=Multiple
Program Version=4.10
Number of Profiles= 7
Profile Names=10-year,25-year,50-year,1pct_min,100-year,1pct_plu,500-year
River Rch & RM=Upper Denton 69,Reach-1         ,11109
     616     856    1056     647    1291    2576    1936
River Rch & RM=Upper Denton 69,Reach-1         ,7768
     935    1325    1656    1027    2048    4087    3145
Boundary for River Rch & Prof#=Upper Denton 69,Reach-1         , 1
Up Type= 0
Dn Type= 3
Dn Slope=0.0011
Boundary for River Rch & Prof#=Upper Denton 69,Reach-1         , 2
Up Type= 0
Dn Type= 3
Dn Slope=0.0011
Boundary for River Rch & Prof#=Upper Denton 69,Reach-1         , 3
Up Type= 0
Dn Type= 3
Dn Slope=0.0011
Boundary for River Rch & Prof#=Upper Denton 69,Reach-1         , 4
Up Type= 0
Dn Type= 3
Dn Slope=0.0011
Boundary for River Rch & Prof#=Upper Denton 69,Reach-1         , 5
Up Type= 0
Dn Type= 3
Dn Slope=0.0011
Boundary for River Rch & Prof#=Upper Denton 69,Reach-1         , 6
Up Type= 0
Dn Type= 3
Dn Slope=0.0011
Boundary for River Rch & Prof#=Upper Denton 69,Reach-1         , 7
Up Type= 0
Dn Type= 3
Dn Slope=0.0011
DSS Import GetInterval= 0
DSS Import GetPeak= 0
DSS Import FillOption= 0

--- Upper Denton 69.g01 (geometry) ---

Geom Title=Existing Conditions

River Reach=Upper Denton 69,Reach-1
Reach XY= 30
      2206629.00      7235210.00      2206784.62      7235454.38
      2207137.62      7235756.16      2207373.56      7235815.19
      2207726.55      7236154.53      2208218.52      7236110.94
      2208530.46      7236356.46      2208877.53      7236363.55
      2209265.79      7236746.38      2209480.56      7236856.26
      2209679.10      7236817.33      2209789.62      7236909.39
      2210108.97      7236860.06      2210289.50      7236958.80
      2210623.32      7236962.00      2211026.55      7237304.53
      2211389.51      7237408.80      2211658.63      7237309.63
      2211863.79      7237460.11      2211972.55      7237317.64
      2212081.42      7237315.39      2212369.18      7237749.53
      2212531.44      7237765.48      2213473.53      7238365.26
      2213645.63      7238676.71      2213923.17      7238857.69
      2214142.62      7239623.22      2214488.79      7239820.52
      2214869.00      7240199.11      2214929.00      7240160.00

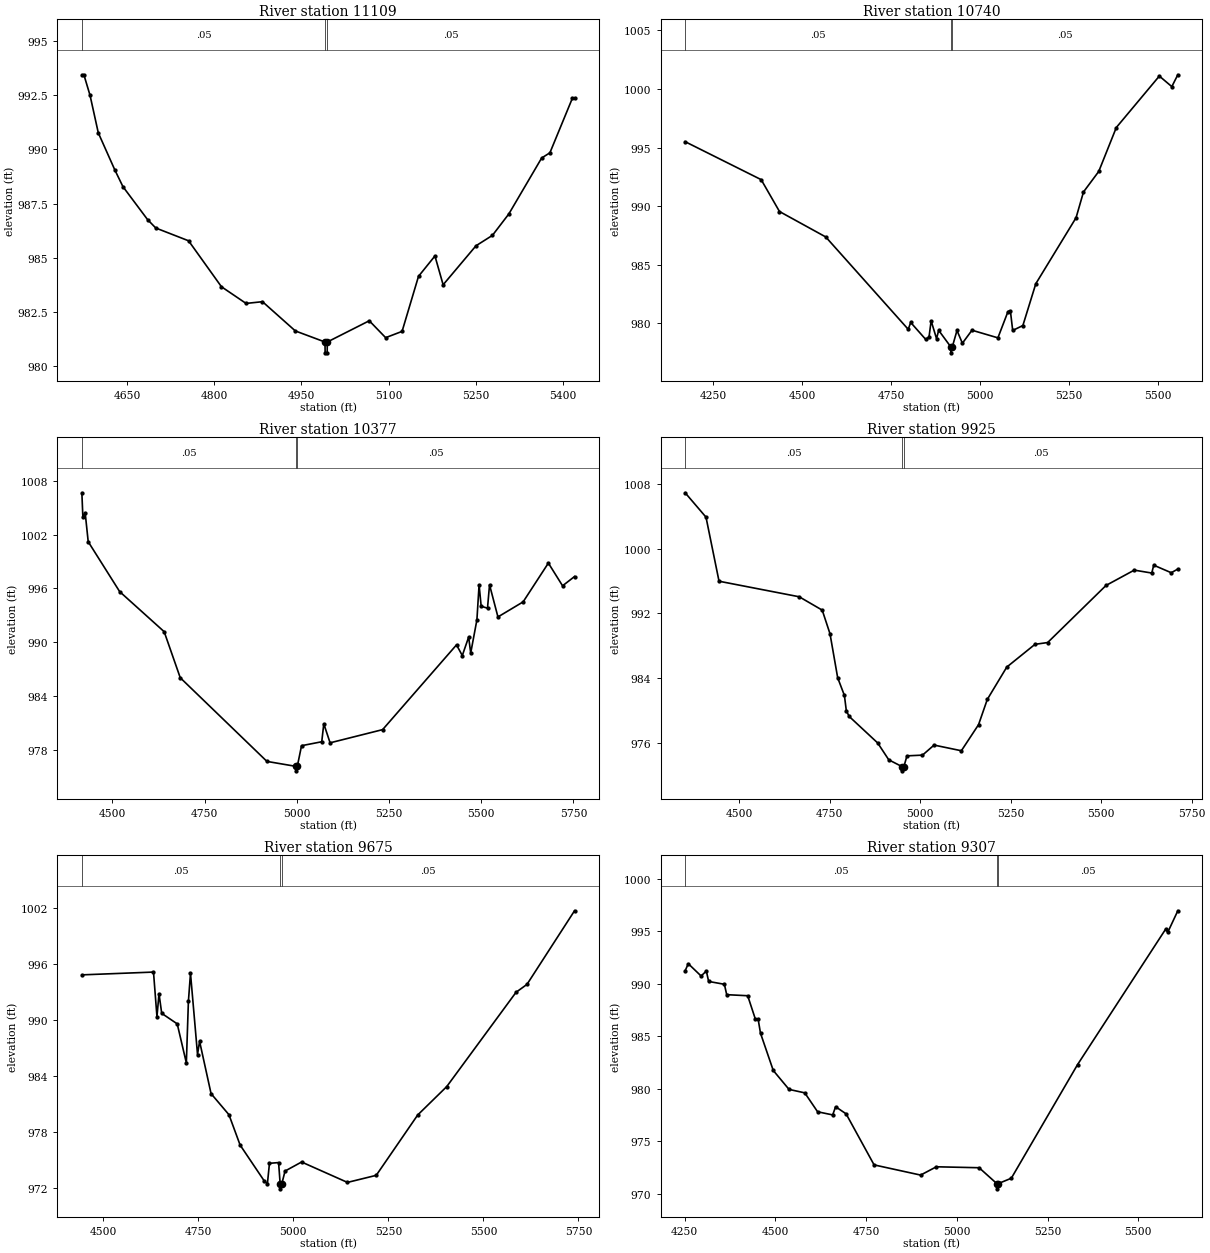
Type RM Length L Ch R = 1,11109,369,369,369
BEGIN DESCRIPTION:
Upper Denton 69 26.0
END DESCRIPTION:
XS GIS Cut Line= 3
      2206329.01      7235559.99      2206629.00      7235260.00
      2206928.99      7234960.01
#Sta/Elev= 30
  4571.8  993.44  4575.3  993.44  4585.9  992.49  4600.1  990.76  4628.4  989.06
  4642.5  988.28  4684.9  986.76  4699.1  986.37  4755.6  985.78  4812.2  983.66
  4854.6  982.89  4882.9  982.97  4939.5  981.62  4990.5  981.11  4990.8  980.61
  4994.3  980.61  4994.5  981.11  5066.8  982.09  5095.0  981.31  5123.3  981.60
  5151.6  984.14  5179.9  985.08  5194.0  983.75  5250.6  985.55  5278.9  986.03
  5307.2  987.02  5363.7  989.60  5377.9  989.84  5416.8  992.37  5420.3  992.37
#Mann=3,-1,0
  4571.8    0.05       0  4990.5    0.04       0  4994.5    0.05       0
Bank Sta=4990.5,4994.5
Exp/Cntr=0.3,0.1

Type RM Length L Ch R = 1,10740,363,363,363
BEGIN DESCRIPTION:
Upper Denton 69 25.0
END DESCRIPTION:
XS GIS Cut Line= 3
      2206430.06      7236207.52      2206879.00      7235510.00
      2207236.67      7235084.20
#Sta/Elev= 30
  4170.3  995.51  4384.1  992.27  4435.6  989.55  4565.7  987.38  4797.6  979.50
  4804.7  980.08  4847.0  978.63  4856.2  978.85  4862.1  980.22  4877.3  978.70
  4883.3  979.41  4917.6  977.99  4917.8  977.49  4921.6  977.99  4934.8  979.40
  4950.0  978.31  4977.0  979.42  5049.9  978.77  5078.2  981.01  5085.0  981.07
  5091.5  979.40  5120.1  979.82  5156.5  983.39  5269.7  989.02  5290.6  991.22
  5333.5  992.97  5382.9  996.72  5503.9 1001.11  5539.0 1000.21  5555.9 1001.22
#Mann=3,-1,0
  4170.3    0.05       0  4917.6   0.033       0  4921.6    0.05       0
Bank Sta=4917.6,4921.6
Exp/Cntr=0.3,0.1

Type RM Length L Ch R = 1,10377,452,452,452
BEGIN DESCRIPTION:
Upper Denton 69 24.0
END DESCRIPTION:
XS GIS Cut Line= 3
      2206781.65      7236216.16      2207129.00      7235760.00
      2207454.20      7235070.72
#Sta/Elev= 30
  4417.3 1006.66  4420.0 1003.98  4426.3 1004.42  4434.5 1001.21  4519.8  995.65
  4640.4  991.19  4684.0  986.06  4919.0  976.74  4997.3  976.19  4997.5  975.69
  5001.3  976.19  5012.8  978.49  5067.6  978.93  5073.1  980.93  5090.2  978.81
  5232.6  980.28  5432.9  989.72  5448.6  988.53  5465.8  990.59  5471.4  988.81
  5488.2  992.51  5494.1  996.42  5499.7  994.03  5516.9  993.80  5522.4  996.41
  5545.2  992.83  5613.5  994.51  5681.9  998.83  5720.4  996.30  5752.8  997.33
#Mann=3,-1,0
  4417.3    0.05       0  4997.3   0.033       0  5001.3    0.05       0
Bank Sta=4997.3,5001.3
Exp/Cntr=0.3,0.1

Type RM Length L Ch R = 1,9925,250,250,250
BEGIN DESCRIPTION:
Upper Denton 69 23.0
END DESCRIPTION:
XS GIS Cut Line= 3
      2207263.42      7236576.40      2207484.77      7235964.43
      2207749.47      7235304.84
#Sta/Elev= 30
  4350.3 1006.89  4407.9 1003.88  4443.9  995.97  4665.5  994.05  4729.1  992.40
  4750.6  989.48  4771.8  984.05  4790.4  981.87  4795.7  979.97  4803.7  979.27
  4882.4  976.00  4913.0  973.92  4950.6  973.06  4950.9  972.56  4954.6  973.06
  4963.3  974.41  5006.2  974.50  5038.2  975.74  5113.6  975.04  5161.1  978.26
  5185.3  981.38  5239.1  985.37  5317.1  988.18  5352.1  988.40  5513.4  995.45
  5591.4  997.34  5639.8  996.98  5645.2  997.95  5693.6  997.02  5711.8  997.47
#Mann=3,-1,0
  4350.3    0.05       0  4950.6   0.033       0  4954.6    0.05       0
Bank Sta=4950.6,4954.6
Exp/Cntr=0.3,0.1

Type RM Length L Ch R = 1,9675,368,368,368
BEGIN DESCRIPTION:
Upper Denton 69 22.0
END DESCRIPTION:
XS GIS Cut Line= 3
      2207467.39      7236624.19      2207679.00      7236110.00
      2207974.61      7235431.97
#Sta/Elev= 30
  4444.0  994.87  4632.4  995.17  4641.5  990.38  4646.9  992.85  4654.0  990.74
  4694.8  989.61  4718.8  985.42  4724.2  992.02  4729.7  995.04  4748.2  986.32
  4753.6  987.74  4783.8  982.12  4830.8  979.86  4860.2  976.60  4924.3  972.71
  4932.0  972.46  4937.4  974.64  4961.4  974.72  4965.6  972.40  4965.8  971.90
  4969.6  972.40  4978.4  973.81  5021.9  974.78  5142.5  972.59  5218.2  973.35
  5327.3  979.83  5403.7  982.88  5585.9  993.00  5614.7  993.85  5739.7 1001.75
#Mann=3,-1,0
  4444.0    0.05       0  4965.6   0.033       0  4969.6    0.05       0
Bank Sta=4965.6,4969.6
Exp/Cntr=0.3,0.1

Type RM Length L Ch R = 1,9307,353,353,353
BEGIN DESCRIPTION:
Upper Denton 69 21.0
END DESCRIPTION:
XS GIS Cut Line= 3
      2207567.26      7236749.99      2208029.00      7236160.00
      2208129.01      7235559.97
#Sta/Elev= 30
  4251.3  991.23  4259.9  991.90  4295.2  990.73  4309.7  991.20  4316.0  990.21
  4359.4  989.94  4365.8  988.95  4423.6  988.85  4444.4  986.66  4452.5  986.59
  4458.9  985.28  4494.1  981.73  4537.5  979.93  4580.9  979.60  4616.2  977.80
  4657.8  977.50  4665.9  978.28  4694.8  977.60  4771.9  972.74  4900.1  971.77
  4943.5  972.56  5061.3  972.47  5110.0  970.96  5110.3  970.46  5114.0  970.96
  5150.0  971.47  5332.5  982.29  5575.8  995.22  5580.9  994.88  5608.8  996.94
#Mann=3,-1,0
  4251.3    0.05       0  5110.0    0.04       0  5114.0    0.05       0
Bank Sta=5110,5114
Exp/Cntr=0.3,0.1

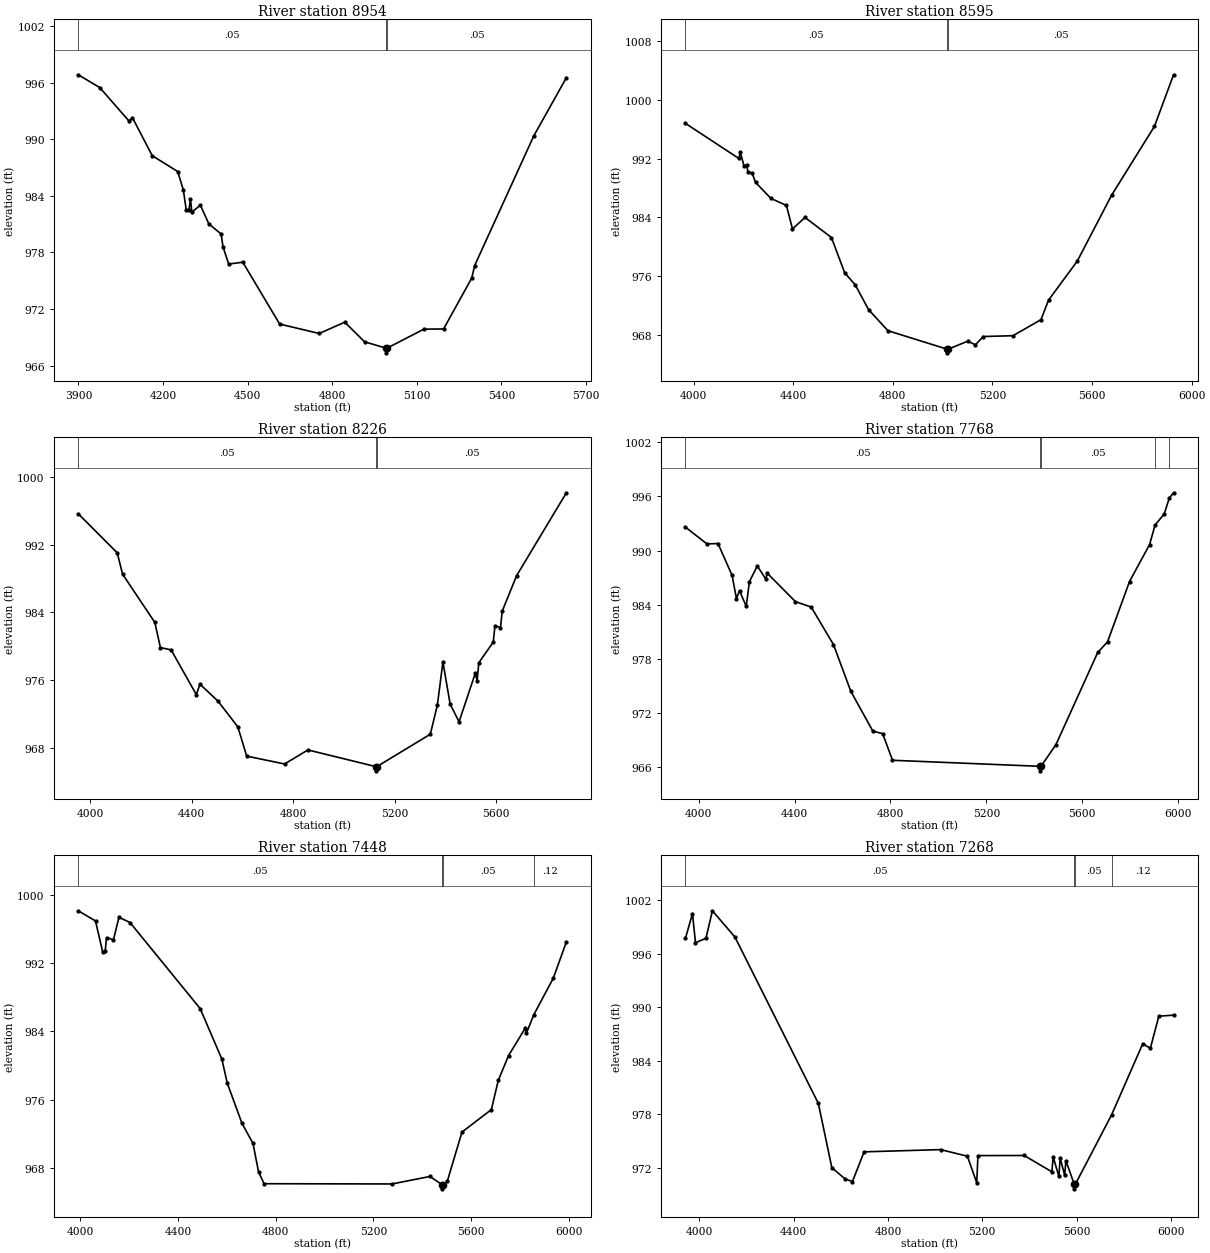
Type RM Length L Ch R = 1,8954,359,359,359
BEGIN DESCRIPTION:
Upper Denton 69 20.0
END DESCRIPTION:
XS GIS Cut Line= 3
      2208226.96      7237301.25      2208329.00      7236210.00
      2208326.79      7235574.42
#Sta/Elev= 30
  3899.2  996.82  3975.3  995.47  4079.2  991.92  4091.3  992.28  4161.6  988.25
  4252.0  986.57  4272.1  984.60  4282.1  982.53  4292.1  982.52  4297.1  983.68
  4302.2  982.26  4332.3  983.01  4362.5  981.02  4406.1  979.95  4412.7  978.59
  4432.8  976.77  4483.0  976.96  4613.6  970.41  4754.2  969.41  4844.6  970.61
  4914.9  968.53  4990.7  967.86  4991.0  967.36  4994.7  967.86  5125.2  969.87
  5195.2  969.89  5295.2  975.29  5305.2  976.59  5515.2  990.35  5630.8  996.51
#Mann=3,-1,0
  3899.2    0.05       0  4990.7    0.04       0  4994.7    0.05       0
Bank Sta=4990.7,4994.7
Exp/Cntr=0.3,0.1

Type RM Length L Ch R = 1,8595,369,369,369
BEGIN DESCRIPTION:
Upper Denton 69 19.0
END DESCRIPTION:
XS GIS Cut Line= 3
      2208279.05      7237331.58      2208629.00      7236360.00
      2208483.15      7235444.33
#Sta/Elev= 30
  3967.4  996.79  4181.7  992.02  4187.8  992.87  4202.9  990.96  4213.2  991.17
  4218.5  990.17  4234.8  990.02  4249.2  988.75  4310.6  986.58  4373.0  985.62
  4397.3  982.42  4447.4  983.99  4553.7  981.26  4606.9  976.45  4649.3  974.82
  4702.5  971.46  4780.5  968.58  5018.3  966.07  5018.6  965.57  5022.3  966.07
  5101.3  967.16  5131.7  966.66  5163.1  967.79  5282.4  967.90  5395.0  970.08
  5425.4  972.74  5541.1  978.07  5678.5  987.01  5850.7  996.39  5927.3 1003.40
#Mann=3,-1,0
  3967.4    0.05       0  5018.3   0.033       0  5022.3    0.05       0
Bank Sta=5018.3,5022.3
Exp/Cntr=0.3,0.1

Type RM Length L Ch R = 1,8226,458,458,458
BEGIN DESCRIPTION:
Upper Denton 69 18.0
END DESCRIPTION:
XS GIS Cut Line= 3
      2208279.07      7237236.10      2208969.14      7236441.86
      2209542.03      7235786.52
#Sta/Elev= 30
  3953.2  995.64  4106.8  991.02  4127.7  988.50  4254.9  982.79  4276.8  979.82
  4319.0  979.55  4418.2  974.26  4432.5  975.49  4503.7  973.49  4581.6  970.45
  4616.7  966.99  4765.8  966.06  4857.9  967.72  5125.4  965.75  5125.6  965.25
  5129.4  965.75  5339.9  969.58  5367.6  973.01  5389.5  978.12  5418.0  973.13
  5453.1  971.05  5516.7  976.76  5524.3  975.91  5530.9  978.03  5587.9  980.47
  5594.5  982.42  5616.3  982.18  5623.0  984.12  5679.9  988.33  5875.8  998.12
#Mann=3,-1,0
  3953.2    0.05       0  5125.4    0.04       0  5129.4    0.05       0
Bank Sta=5125.4,5129.4
Exp/Cntr=0.3,0.1

Type RM Length L Ch R = 1,7768,320,320,320
BEGIN DESCRIPTION:
Upper Denton 69 17.0
END DESCRIPTION:
XS GIS Cut Line= 3
      2209021.22      7237778.71      2209279.00      7236760.00
      2209641.48      7235843.93
#Sta/Elev= 30
  3944.9  992.60  4034.5  990.74  4080.7  990.78  4139.6  987.25  4157.6  984.69
  4170.5  985.56  4198.6  983.83  4211.8  986.56  4244.7  988.30  4280.6  986.83
  4285.7  987.51  4403.6  984.35  4469.6  983.74  4562.5  979.59  4634.7  974.42
  4726.6  970.01  4767.6  969.73  4808.6  966.78  5423.8  966.11  5424.1  965.61
  5428.0  966.11  5490.4  968.51  5664.7  978.72  5705.5  979.89  5797.2  986.57
  5881.0  990.67  5903.9  992.84  5942.1  994.05  5963.2  995.81  5980.9  996.40
#Mann=5,-1,0
  3944.9    0.05       0  5423.8   0.033       0  5428.0    0.05       0
  5903.9    0.12       0  5963.2    0.05       0
Bank Sta=5423.8,5428
Exp/Cntr=0.3,0.1

Type RM Length L Ch R = 1,7448,180,180,180
BEGIN DESCRIPTION:
Upper Denton 69 16.0
END DESCRIPTION:
XS GIS Cut Line= 3
      2209134.08      7237769.98      2209568.10      7236867.21
      2209659.17      7235874.16
#Sta/Elev= 30
  3991.5  998.10  4062.1  996.91  4091.3  993.31  4101.8  993.41  4107.4  994.96
  4135.7  994.72  4158.2  997.34  4203.4  996.73  4490.8  986.67  4579.6  980.77
  4601.7  977.96  4661.7  973.28  4707.0  970.92  4729.6  967.62  4752.2  966.21
  5276.7  966.18  5432.2  967.06  5480.3  966.11  5480.7  965.61  5484.5  966.11
  5502.5  966.47  5562.8  972.24  5683.3  974.87  5711.6  978.29  5753.6  981.18
  5821.6  984.37  5826.6  983.78  5856.9  985.95  5936.6  990.21  5990.4  994.46
#Mann=4,-1,0
  3991.5    0.05       0  5480.3   0.033       0  5484.5    0.05       0
  5856.9    0.12       0
Bank Sta=5480.3,5484.5
Exp/Cntr=0.3,0.1

Type RM Length L Ch R = 1,7268,34,34,34
BEGIN DESCRIPTION:
Upper Denton 69 15.5
END DESCRIPTION:
XS GIS Cut Line= 6
      2209194.81      7237765.69      2209598.48      7237149.33
      2209739.76      7236805.66      2209776.44      7236611.13
      2209654.91      7236302.97      2209758.70      7235883.49
#Sta/Elev= 30
  3941.2  997.74  3971.1 1000.53  3983.9  997.25  4028.3  997.76  4055.6 1000.84
  4151.2  997.89  4504.7  979.24  4562.0  972.03  4619.2  970.74  4649.4  970.47
  4698.9  973.80  5023.2  974.05  5136.7  973.31  5176.4  970.33  5181.5  973.38
  5377.7  973.39  5495.0  971.56  5500.4  973.24  5524.8  971.04  5530.2  973.10
  5549.2  971.18  5554.5  972.81  5590.0  970.15  5590.3  969.65  5594.2  970.15
  5748.0  977.94  5880.6  985.94  5912.4  985.41  5948.6  989.02  6010.9  989.13
#Mann=4,-1,0
  3941.2    0.05       0  5590.0   0.033       0  5594.2    0.05       0
  5748.0    0.12       0
Bank Sta=5590,5594.2
Exp/Cntr=0.3,0.1

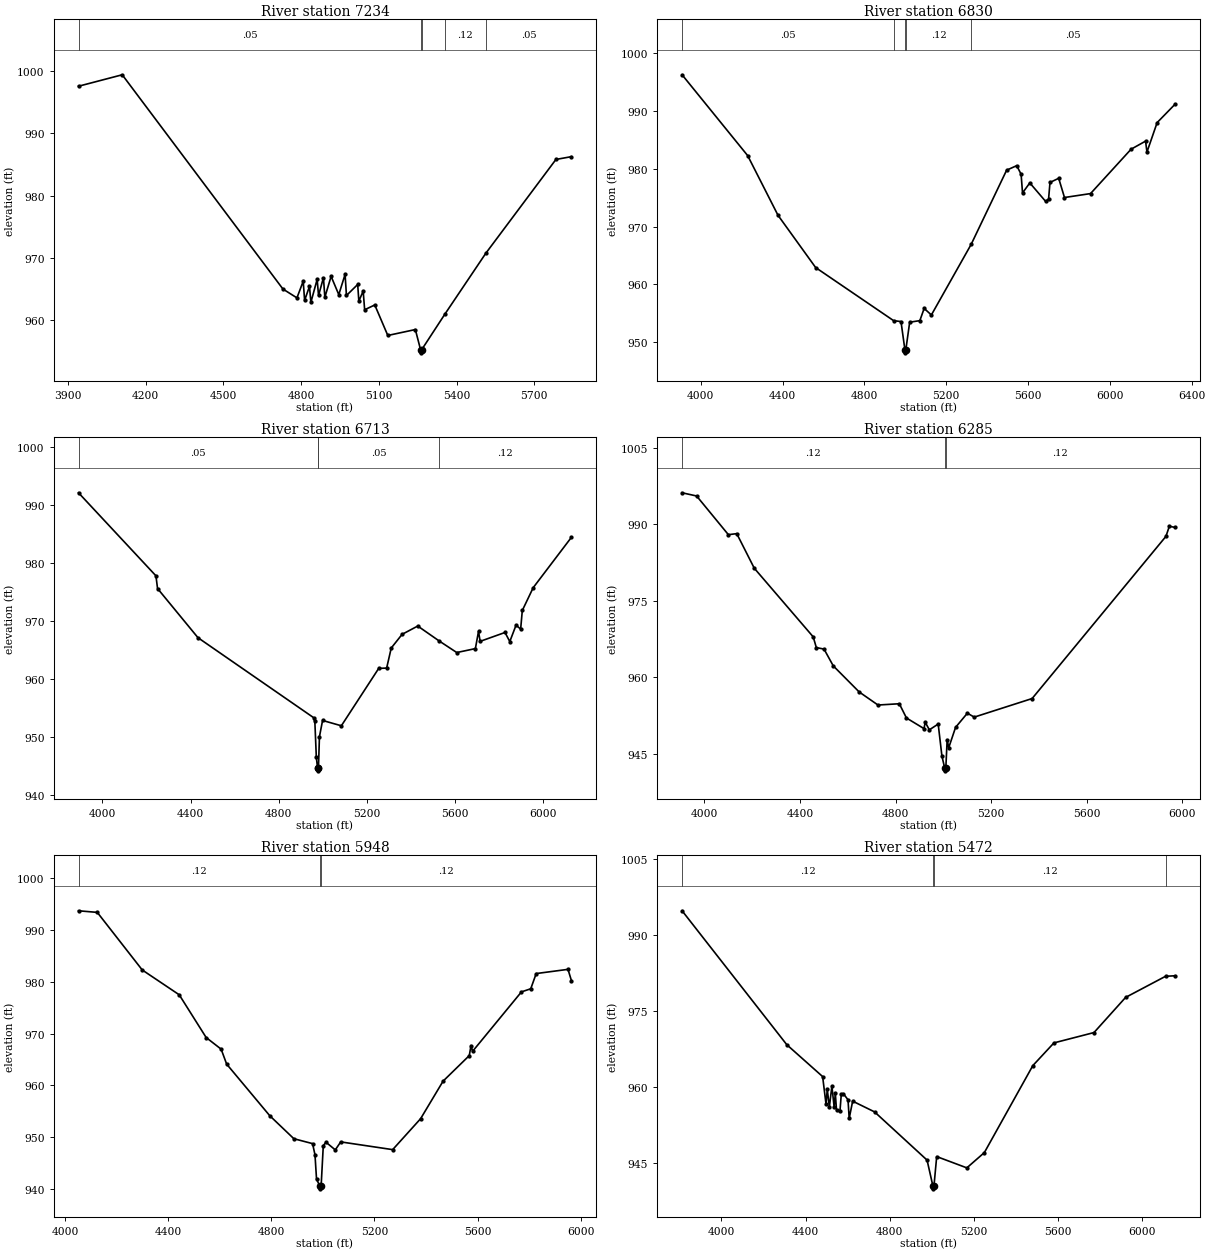
Type RM Length L Ch R = 1,7234,404,404,404
BEGIN DESCRIPTION:
Upper Denton 69 15.4
END DESCRIPTION:
XS GIS Cut Line= 5
      2209207.86      7237783.01      2209628.87      7237166.69
      2209750.39      7236862.87      2209910.98      7236541.69
      2210253.85      7236220.52
#Sta/Elev= 30
  3941.0  997.57  4109.8  999.41  4730.2  964.99  4784.1  963.58  4808.3  966.25
  4813.7  963.17  4832.5  965.43  4837.9  962.86  4862.1  966.55  4867.5  963.96
  4886.4  966.82  4891.8  963.68  4916.0  967.03  4945.6  964.10  4969.9  967.35
  4975.2  963.96  5018.6  965.73  5023.0  963.06  5039.8  964.67  5045.4  961.67
  5084.5  962.44  5134.8  957.54  5241.1  958.49  5261.3  955.25  5261.6  954.75
  5265.5  955.25  5355.5  960.99  5513.2  970.75  5783.7  985.81  5843.5  986.26
#Mann=5,-1,0
  3941.0    0.05       0  5261.3   0.033       0  5265.5    0.05       0
  5355.5    0.12       0  5513.2    0.05       0
Bank Sta=5261.3,5265.5
Exp/Cntr=0.3,0.1

Type RM Length L Ch R = 1,6830,117,117,117
BEGIN DESCRIPTION:
Upper Denton 69 15.0
END DESCRIPTION:
XS GIS Cut Line= 3
      2209346.76      7237631.09      2210114.98      7236867.21
      2211030.75      7235908.04
#Sta/Elev= 30
  3908.9  996.30  4229.5  982.29  4377.9  971.94  4561.8  962.89  4942.8  953.69
  4979.0  953.53  4998.2  948.61  4998.5  948.11  5002.5  948.61  5021.4  953.42
  5071.1  953.69  5092.2  955.81  5127.4  954.67  5321.8  966.90  5495.4  979.77
  5544.7  980.55  5566.1  979.06  5573.0  975.82  5608.6  977.56  5686.3  974.34
  5700.4  974.78  5707.3  977.64  5749.8  978.36  5778.1  975.03  5905.5  975.71
  6103.6  983.40  6174.4  984.80  6181.3  982.91  6231.0  988.01  6318.4  991.19
#Mann=5,-1,0
  3908.9    0.05       0  4942.8    0.12       0  4998.2    0.07       0
  5002.5    0.12       0  5321.8    0.05       0
Bank Sta=4998.2,5002.5
Exp/Cntr=0.3,0.1

Type RM Length L Ch R = 1,6713,428,428,428
BEGIN DESCRIPTION:
Upper Denton 69 14.5
END DESCRIPTION:
XS GIS Cut Line= 3
      2209416.16      7237674.53      2210187.51      7236942.47
      2211064.78      7236160.39
#Sta/Elev= 30
  3891.3  992.06  4243.0  977.74  4250.3  975.55  4433.9  967.07  4959.1  953.28
  4964.7  952.63  4971.4  946.49  4976.8  944.61  4977.1  944.11  4981.1  944.61
  4985.6  950.00  4999.8  952.80  5085.1  951.88  5254.8  961.78  5290.8  961.83
  5311.7  965.29  5361.0  967.65  5432.1  969.08  5529.2  966.51  5609.3  964.51
  5693.8  965.19  5708.0  968.15  5715.5  966.44  5828.4  967.97  5850.1  966.40
  5878.5  969.23  5899.4  968.55  5906.9  971.76  5956.3  975.69  6130.0  984.38
#Mann=4,-1,0
  3891.3    0.05       0  4976.8   0.033       0  4981.1    0.05       0
  5529.2    0.12       0
Bank Sta=4976.8,4981.1
Exp/Cntr=0.3,0.1

Type RM Length L Ch R = 1,6285,337,337,337
BEGIN DESCRIPTION:
Upper Denton 69 14.0
END DESCRIPTION:
XS GIS Cut Line= 3
      2210232.17      7237982.64      2210631.47      7236967.03
      2211252.12      7236220.52
#Sta/Elev= 30
  3907.2  996.17  3968.0  995.54  4100.8  987.96  4135.9  988.16  4209.2  981.38
  4455.7  967.93  4468.8  965.83  4501.0  965.53  4539.7  962.24  4648.1  957.13
  4726.7  954.57  4816.0  954.82  4845.8  952.03  4919.1  949.95  4924.4  951.19
  4941.6  949.71  4978.6  950.84  4994.2  944.56  5006.0  942.17  5006.5  941.67
  5010.5  942.17  5016.1  947.78  5022.6  946.20  5051.3  950.19  5100.7  952.97
  5129.4  952.20  5371.5  955.84  5931.4  987.63  5945.7  989.62  5969.3  989.37
#Mann=3,-1,0
  3907.2    0.12       0  5006.0    0.07       0  5010.5    0.12       0
Bank Sta=5006,5010.5
Exp/Cntr=0.3,0.1

Type RM Length L Ch R = 1,5948,476,476,476
BEGIN DESCRIPTION:
Upper Denton 69 13.0
END DESCRIPTION:
XS GIS Cut Line= 3
      2210384.09      7237973.95      2210879.00      7237160.00
      2211408.38      7236359.40
#Sta/Elev= 30
  4051.8  993.64  4124.7  993.33  4299.1  982.24  4442.6  977.46  4547.1  969.23
  4605.2  966.99  4626.6  964.11  4793.7  954.18  4887.4  949.74  4959.9  948.80
  4969.3  946.65  4975.3  941.96  4988.5  940.59  4989.0  940.09  4993.1  940.59
  5001.5  948.40  5011.9  949.07  5048.0  947.59  5069.1  949.13  5270.7  947.64
  5379.1  953.60  5466.3  960.83  5567.9  965.75  5574.7  967.69  5580.7  966.57
  5770.3  978.02  5806.4  978.62  5827.5  981.55  5950.9  982.36  5964.2  980.19
#Mann=3,-1,0
  4051.8    0.12       0  4988.5    0.07       0  4993.1    0.12       0
Bank Sta=4988.5,4993.1
Exp/Cntr=0.3,0.1

Type RM Length L Ch R = 1,5472,452,452,452
BEGIN DESCRIPTION:
Upper Denton 69 12.0
END DESCRIPTION:
XS GIS Cut Line= 4
      2210722.64      7238407.97      2211279.00      7237360.00
      2211383.46      7237189.64      2211436.81      7236235.67
#Sta/Elev= 30
  3813.5  994.85  4311.0  968.41  4481.2  962.12  4497.5  956.63  4503.2  959.62
  4513.2  956.11  4525.2  960.23  4535.8  956.15  4541.5  958.83  4547.1  955.52
  4563.5  955.27  4569.8  958.63  4579.8  958.74  4601.8  957.54  4607.4  953.86
  4623.8  957.27  4728.0  955.15  4977.4  945.63  5005.4  940.46  5005.9  939.96
  5010.0  940.46  5023.1  946.33  5166.3  944.10  5249.6  947.12  5479.9  964.29
  5580.1  968.77  5770.4  970.81  5920.6  977.75  6110.5  981.92  6155.3  982.02
#Mann=4,-1,0
  3813.5    0.12       0  5005.4    0.07       0  5010.0    0.12       0
  6110.5    0.05       0
Bank Sta=5005.4,5010
Exp/Cntr=0.3,0.1

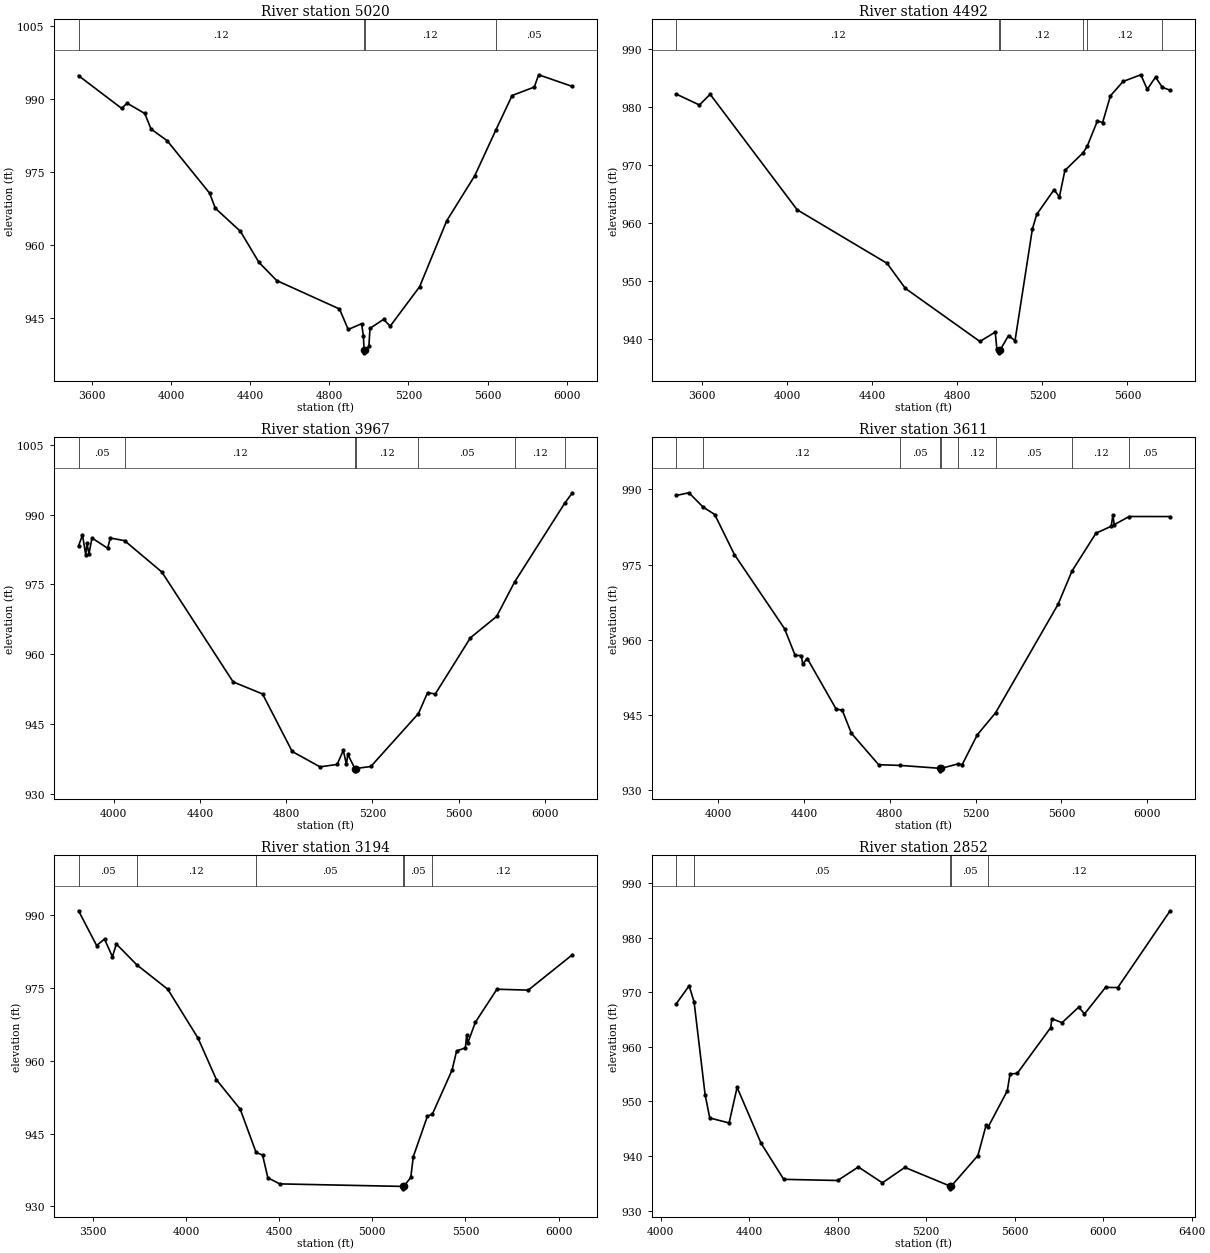
Type RM Length L Ch R = 1,5020,528,528,528
BEGIN DESCRIPTION:
Upper Denton 69 11.0
END DESCRIPTION:
XS GIS Cut Line= 3
      2210991.72      7238616.32      2211679.00      7237310.00
      2212111.50      7236385.44
#Sta/Elev= 30
  3532.2  994.83  3750.1  988.09  3777.8  989.15  3867.0  987.04  3898.7  983.83
  3980.0  981.44  4194.7  970.63  4223.7  967.51  4350.2  962.78  4444.0  956.38
  4533.7  952.63  4851.5  946.76  4895.5  942.54  4963.1  943.73  4972.4  941.22
  4975.6  938.23  4976.2  937.73  4980.4  938.23  5000.1  939.04  5005.5  942.76
  5074.5  944.64  5107.6  943.22  5256.4  951.34  5393.4  964.92  5536.0  974.26
  5642.1  983.64  5724.2  990.74  5836.3  992.48  5858.4  995.01  6029.0  992.60
#Mann=4,-1,0
  3532.2    0.12       0  4975.6    0.07       0  4980.4    0.12       0
  5642.1    0.05       0
Bank Sta=4975.6,4980.4
Exp/Cntr=0.3,0.1

Type RM Length L Ch R = 1,4492,525,525,525
BEGIN DESCRIPTION:
Upper Denton 69 10.0
END DESCRIPTION:
XS GIS Cut Line= 4
      2211191.38      7238564.24      2212012.76      7237403.23
      2212049.66      7237305.58      2212206.93      7236524.63
#Sta/Elev= 30
  3477.4  982.26  3586.3  980.38  3636.7  982.23  4046.1  962.31  4468.8  953.08
  4554.9  948.76  4905.7  939.60  4977.9  941.22  4985.6  938.22  4996.5  938.14
  4997.1  937.64  5001.3  938.14  5040.3  940.63  5070.9  939.73  5152.5  958.97
  5172.9  961.51  5254.5  965.77  5279.6  964.52  5305.5  969.09  5391.2  972.14
  5410.6  973.27  5458.5  977.64  5482.9  977.34  5519.7  981.96  5579.5  984.44
  5662.5  985.59  5693.1  983.09  5732.0  985.18  5764.0  983.43  5800.6  982.92
#Mann=6,-1,0
  3477.4    0.12       0  4996.5    0.07       0  5001.3    0.12       0
  5391.2    0.05       0  5410.6    0.12       0  5764.0    0.05       0
Bank Sta=4996.5,5001.3
Exp/Cntr=0.3,0.1

Type RM Length L Ch R = 1,3967,356,356,356
BEGIN DESCRIPTION:
Upper Denton 69 9.0
END DESCRIPTION:
XS GIS Cut Line= 3
      2211674.64      7238671.49      2212330.04      7237712.26
      2213045.08      7236841.21
#Sta/Elev= 30
  3837.9  983.31  3856.2  985.63  3871.1  981.42  3877.2  983.82  3886.0  981.56
  3900.3  985.00  3972.7  982.79  3985.0  984.99  4051.0  984.43  4224.0  977.68
  4554.3  954.05  4690.6  951.45  4828.1  939.08  4956.8  935.78  5036.2  936.29
  5064.9  939.32  5079.2  936.35  5085.7  938.46  5118.4  935.42  5119.0  934.92
  5123.4  935.42  5192.6  935.86  5413.2  947.25  5455.4  951.73  5491.1  951.45
  5654.0  963.54  5775.3  968.12  5859.0  975.55  6091.4  992.50  6126.6  994.72
#Mann=7,-1,0
  3837.9    0.05       0  4051.0    0.12       0  5118.4    0.07       0
  5123.4    0.12       0  5413.2    0.05       0  5859.0    0.12       0
  6091.4    0.05       0
Bank Sta=5118.4,5123.4
Exp/Cntr=0.3,0.1

Type RM Length L Ch R = 1,3611,417,417,417
BEGIN DESCRIPTION:
Upper Denton 69 8.0
END DESCRIPTION:
XS GIS Cut Line= 3
      2211761.48      7238675.79      2212629.00      7237860.00
      2213354.20      7237017.98
#Sta/Elev= 30
  3804.5  988.81  3863.5  989.34  3928.7  986.52  3983.6  985.01  4075.6  977.02
  4309.0  962.26  4358.7  956.91  4387.0  956.90  4393.9  955.22  4415.3  956.30
  4549.7  946.22  4578.0  946.01  4620.5  941.42  4747.9  935.13  4849.1  934.99
  5035.0  934.41  5035.7  933.91  5040.1  934.41  5117.7  935.29  5137.4  935.16
  5207.7  941.09  5293.4  945.51  5584.0  967.09  5649.1  973.73  5760.8  981.28
  5831.9  982.66  5839.6  984.87  5846.2  982.99  5915.7  984.61  6106.6  984.60
#Mann=9,-1,0
  3804.5    0.05       0  3928.7    0.12       0  4849.1    0.05       0
  5035.0   0.033       0  5040.1    0.05       0  5117.7    0.12       0
  5293.4    0.05       0  5649.1    0.12       0  5915.7    0.05       0
Bank Sta=5035,5040.1
Exp/Cntr=0.3,0.1

Type RM Length L Ch R = 1,3194,342,342,342
BEGIN DESCRIPTION:
Upper Denton 69 7.0
END DESCRIPTION:
XS GIS Cut Line= 3
      2211848.25      7239166.27      2212979.00      7238060.00
      2213371.71      7237065.54
#Sta/Elev= 30
  3422.9  990.89  3519.9  983.73  3562.3  985.06  3604.7  981.42  3625.9  984.04
  3735.2  979.77  3901.6  974.73  4064.3  964.65  4163.4  956.06  4290.7  950.02
  4376.1  941.09  4410.8  940.56  4439.1  935.88  4502.7  934.62  5163.5  934.10
  5164.2  933.60  5168.7  934.10  5206.4  935.94  5219.8  940.22  5295.6  948.55
  5322.9  949.04  5428.2  958.09  5452.5  962.01  5499.4  962.65  5506.6  965.25
  5512.0  963.62  5553.1  967.92  5668.9  974.73  5836.6  974.54  6074.0  981.83
#Mann=6,-1,0
  3422.9    0.05       0  3735.2    0.12       0  4376.1    0.05       0
  5163.5   0.033       0  5168.7    0.05       0  5322.9    0.12       0
Bank Sta=5163.5,5168.7
Exp/Cntr=0.3,0.1

Type RM Length L Ch R = 1,2852,103,103,103
BEGIN DESCRIPTION:
Upper Denton 69 6.5
END DESCRIPTION:
XS GIS Cut Line= 4
      2212733.71      7239036.01      2213237.85      7238270.94
      2213545.32      7237746.98      2213662.50      7237048.19
#Sta/Elev= 30
  4070.1  967.91  4128.2  971.19  4150.7  968.21  4200.5  951.20  4221.5  946.96
  4308.9  946.06  4345.0  952.58  4453.4  942.33  4555.8  935.72  4799.7  935.51
  4893.1  937.99  5001.7  935.08  5103.4  937.91  5307.9  934.48  5308.6  933.98
  5313.1  934.48  5433.5  940.08  5470.7  945.65  5480.9  945.40  5566.4  951.95
  5578.8  955.04  5611.1  955.13  5762.7  963.54  5767.8  965.15  5813.9  964.43
  5889.1  967.28  5915.3  966.04  6010.4  970.90  6065.9  970.87  6302.4  984.94
#Mann=5,-1,0
  4070.1    0.12       0  4150.7    0.05       0  5307.9   0.033       0
  5313.1    0.05       0  5480.9    0.12       0
Bank Sta=5307.9,5313.1
Exp/Cntr=0.3,0.1

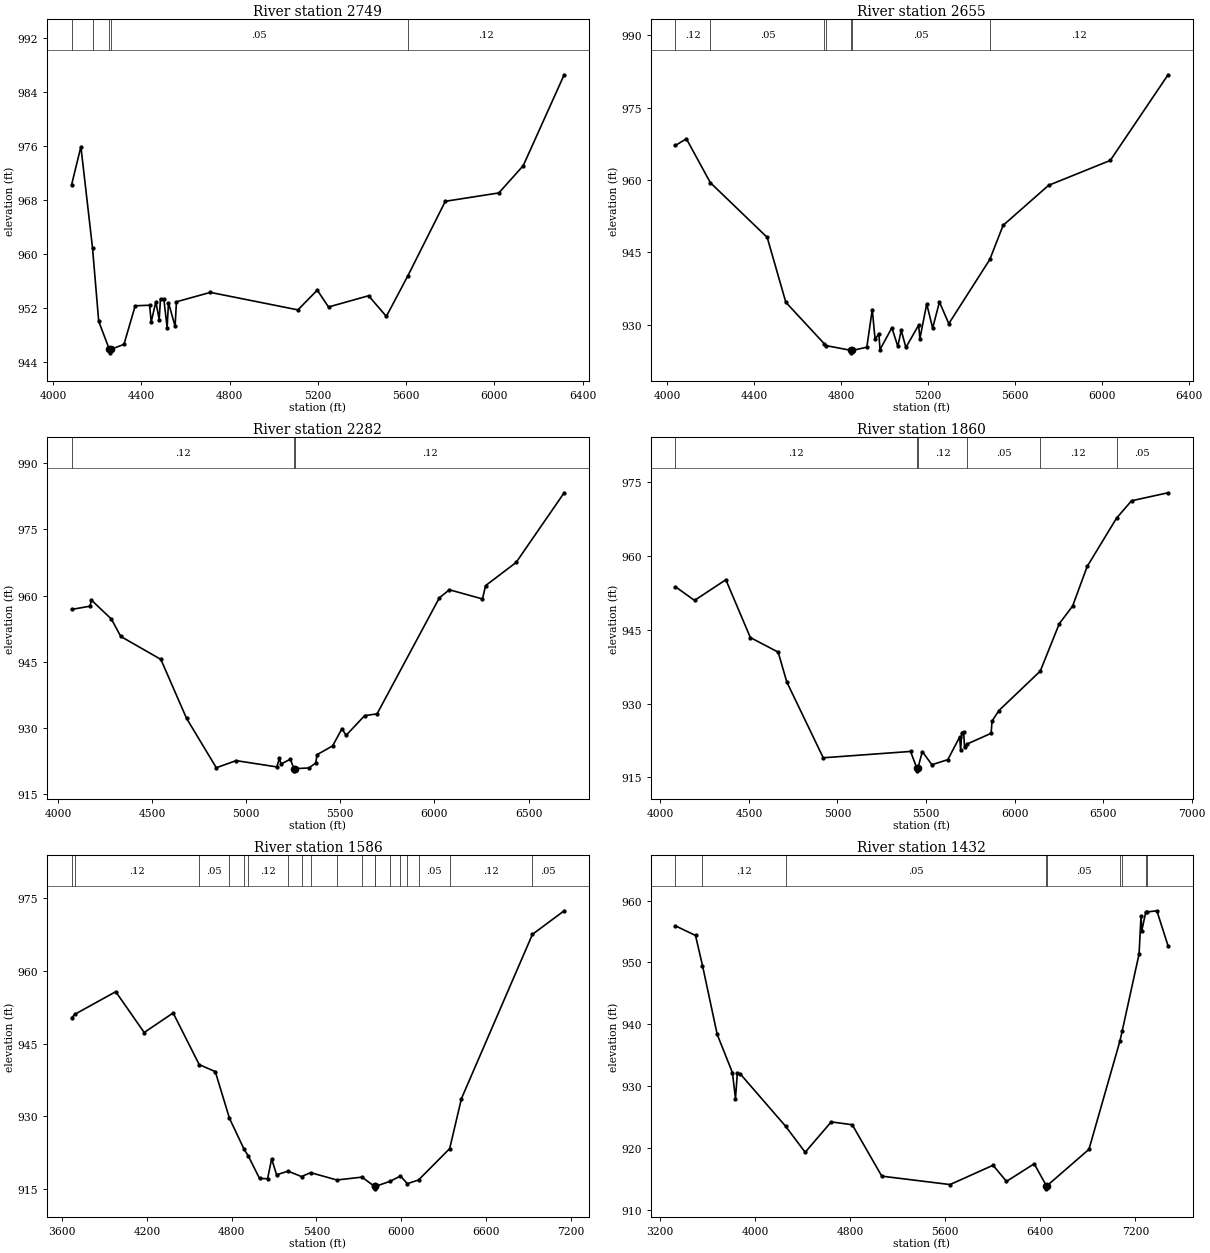
Type RM Length L Ch R = 1,2749,94,94,94
BEGIN DESCRIPTION:
Upper Denton 69 6.0
END DESCRIPTION:
XS GIS Cut Line= 4
      2212824.81      7239075.14      2213329.00      7238310.00
      2213636.46      7237786.04      2213753.65      7237087.23
#Sta/Elev= 30
  4083.7  970.26  4125.8  975.92  4178.5  960.88  4206.5  949.99  4254.9  945.80
  4255.6  945.30  4260.1  945.80  4320.9  946.56  4372.1  952.29  4437.2  952.37
  4444.4  949.89  4465.5  952.88  4480.6  950.25  4486.6  953.34  4501.6  953.30
  4516.7  949.06  4522.7  952.76  4552.8  949.23  4558.8  952.88  4712.5  954.28
  5109.4  951.68  5197.1  954.61  5248.2  952.11  5429.8  953.78  5510.2  950.71
  5607.6  956.73  5777.5  967.81  6020.1  969.05  6130.8  973.11  6316.1  986.60
#Mann=5,-1,0
  4083.7    0.12       0  4178.5    0.05       0  4254.9   0.033       0
  4260.1    0.05       0  5607.6    0.12       0
Bank Sta=4254.9,4260.1
Exp/Cntr=0.3,0.1

Type RM Length L Ch R = 1,2655,373,373,373
BEGIN DESCRIPTION:
Upper Denton 69 5.5
END DESCRIPTION:
XS GIS Cut Line= 5
      2212894.30      7239135.85      2213206.77      7238884.14
      2213398.44      7238370.76      2213705.91      7237846.81
      2213823.10      7237148.01
#Sta/Elev= 30
  4038.3  967.15  4088.4  968.53  4198.8  959.42  4460.1  948.08  4545.7  934.63
  4723.2  925.99  4731.8  925.63  4847.0  924.64  4847.7  924.14  4852.2  924.64
  4918.3  925.31  4943.3  933.12  4956.3  926.93  4973.6  928.15  4978.9  924.82
  5033.5  929.34  5060.8  925.48  5076.5  928.81  5097.9  925.25  5156.6  929.89
  5162.4  927.08  5193.7  934.28  5221.0  929.28  5252.3  934.68  5295.3  930.19
  5483.9  943.50  5545.0  950.57  5754.0  958.87  6038.0  964.04  6303.6  981.80
#Mann=7,-1,0
  4038.3    0.12       0  4198.8    0.05       0  4723.2    0.12       0
  4731.8    0.05       0  4847.0   0.033       0  4852.2    0.05       0
  5483.9    0.12       0
Bank Sta=4847,4852.2
Exp/Cntr=0.3,0.1

Type RM Length L Ch R = 1,2282,422,422,422
BEGIN DESCRIPTION:
Upper Denton 69 5.0
END DESCRIPTION:
XS GIS Cut Line= 4
      2213070.09      7239328.98      2213436.97      7239025.60
      2213629.00      7238610.00      2214419.23      7237124.72
#Sta/Elev= 30
  4072.7  956.88  4170.9  957.62  4177.3  959.02  4284.2  954.69  4333.7  950.77
  4546.8  945.57  4683.2  932.23  4841.4  921.05  4946.5  922.66  5162.9  921.24
  5176.5  923.21  5184.9  921.88  5234.5  922.98  5253.8  920.85  5254.5  920.35
  5259.1  920.85  5333.0  921.00  5369.1  922.11  5376.9  924.02  5459.2  926.00
  5508.8  929.89  5530.8  928.38  5629.3  932.85  5695.2  933.24  6026.0  959.50
  6079.4  961.33  6255.2  959.25  6271.5  962.26  6433.8  967.51  6689.0  983.28
#Mann=3,-1,0
  4072.7    0.12       0  5253.8    0.07       0  5259.1    0.12       0
Bank Sta=5253.8,5259.1
Exp/Cntr=0.3,0.1

Type RM Length L Ch R = 1,1860,274,274,274
BEGIN DESCRIPTION:
Upper Denton 69 4.0
END DESCRIPTION:
XS GIS Cut Line= 4
      2213169.04      7239329.00      2213718.15      7239113.02
      2213929.00      7238860.00      2214778.99      7237203.79
#Sta/Elev= 30
  4085.6  953.72  4193.0  950.95  4370.0  955.15  4508.2  943.41  4665.3  940.45
  4714.1  934.38  4919.8  918.99  5412.7  920.28  5448.8  916.84  5449.6  916.34
  5454.1  916.84  5479.3  920.25  5533.3  917.58  5623.2  918.61  5690.0  923.20
  5695.6  920.59  5701.9  924.11  5712.2  924.25  5717.8  921.15  5732.4  921.79
  5867.5  923.96  5873.1  926.46  5911.9  928.59  6145.1  936.59  6252.7  946.23
  6327.9  949.81  6410.0  957.84  6576.3  967.68  6660.7  971.19  6866.6  972.81
#Mann=6,-1,0
  4085.6    0.12       0  5448.8    0.07       0  5454.1    0.12       0
  5732.4    0.05       0  6145.1    0.12       0  6576.3    0.05       0
Bank Sta=5448.8,5454.1
Exp/Cntr=0.3,0.1

Type RM Length L Ch R = 1,1586,154,154,154
BEGIN DESCRIPTION:
Upper Denton 69 3.5
END DESCRIPTION:
XS GIS Cut Line= 6
      2212778.79      7239411.76      2213633.79      7239307.60
      2213863.82      7239281.56      2214008.42      7239131.10
      2214744.90      7238252.91      2214779.56      7237213.12
#Sta/Elev= 30
  3665.8  950.35  3688.3  951.07  3978.3  955.74  4179.8  947.31  4384.8  951.35
  4569.3  940.68  4683.3  939.23  4783.8  929.57  4887.3  923.18  4916.2  921.85
  4996.5  917.16  5053.7  917.10  5082.3  921.20  5117.4  917.91  5199.0  918.67
  5293.9  917.54  5358.2  918.36  5543.8  916.84  5722.4  917.43  5810.8  915.51
  5811.5  915.01  5816.1  915.51  5918.7  916.54  5994.8  917.65  6043.6  916.08
  6122.5  916.84  6343.1  923.32  6426.5  933.66  6929.2  967.59  7153.8  972.46
#Mann=19,-1,0
  3665.8    0.05       0  3688.3    0.12       0  4569.3    0.05       0
  4783.8    0.12       0  4887.3    0.05       0  4916.2    0.12       0
  5199.0    0.05       0  5293.9    0.12       0  5358.2    0.05       0
  5543.8    0.12       0  5722.4    0.05       0  5810.8    0.07       0
  5816.1    0.05       0  5918.7    0.12       0  5994.8    0.05       0
  6043.6    0.12       0  6122.5    0.05       0  6343.1    0.12       0
  6929.2    0.05       0
Bank Sta=5810.8,5816.1
Exp/Cntr=0.3,0.1

Type RM Length L Ch R = 1,1432,450,450,450
BEGIN DESCRIPTION:
Upper Denton 69 3.0
END DESCRIPTION:
XS GIS Cut Line= 6
      2212596.42      7239997.72      2213599.06      7239724.27
      2214029.00      7239260.00      2214090.89      7239209.22
      2214827.36      7238331.04      2215938.44      7237762.48
#Sta/Elev= 30
  3328.1  955.90  3496.6  954.35  3555.4  949.49  3679.2  938.36  3807.6  932.17
  3833.0  927.99  3849.0  932.09  3872.7  931.99  4255.0  923.52  4419.8  919.31
  4639.2  924.22  4816.1  923.76  5064.7  915.45  5639.5  914.09  6001.2  917.21
  6114.4  914.60  6347.7  917.45  6450.2  913.90  6450.9  913.40  6455.5  913.90
  6808.5  919.78  7069.1  937.27  7089.2  938.97  7230.5  951.35  7247.1  957.53
  7252.7  955.08  7287.4  958.17  7293.7  958.14  7380.3  958.34  7474.4  952.68
#Mann=9,-1,0
  3328.1    0.05       0  3555.4    0.12       0  4255.0    0.05       0
  6450.2   0.033       0  6455.5    0.05       0  7069.1    0.12       0
  7089.2    0.05       0  7287.4    0.12       0  7293.7    0.05       0
Bank Sta=6450.2,6455.5
Exp/Cntr=0.3,0.1