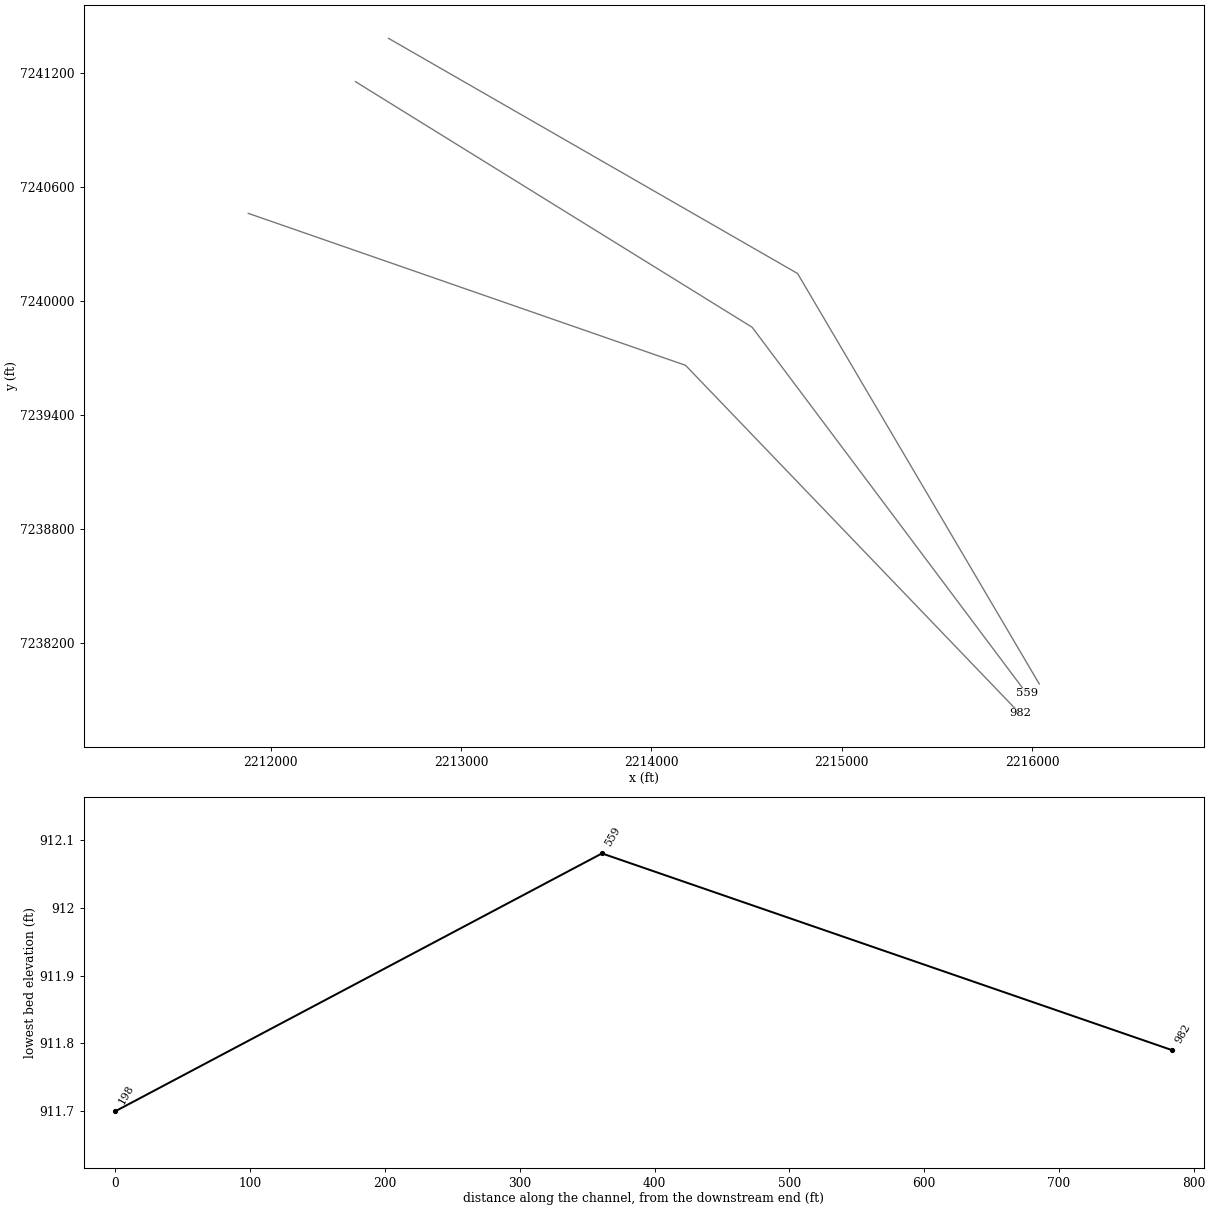
HEC-RAS study Upper Denton 69.prj: Upper Denton 69 Base Level Engineering

--- Upper Denton 69.g01 (geometry) --- (continued)

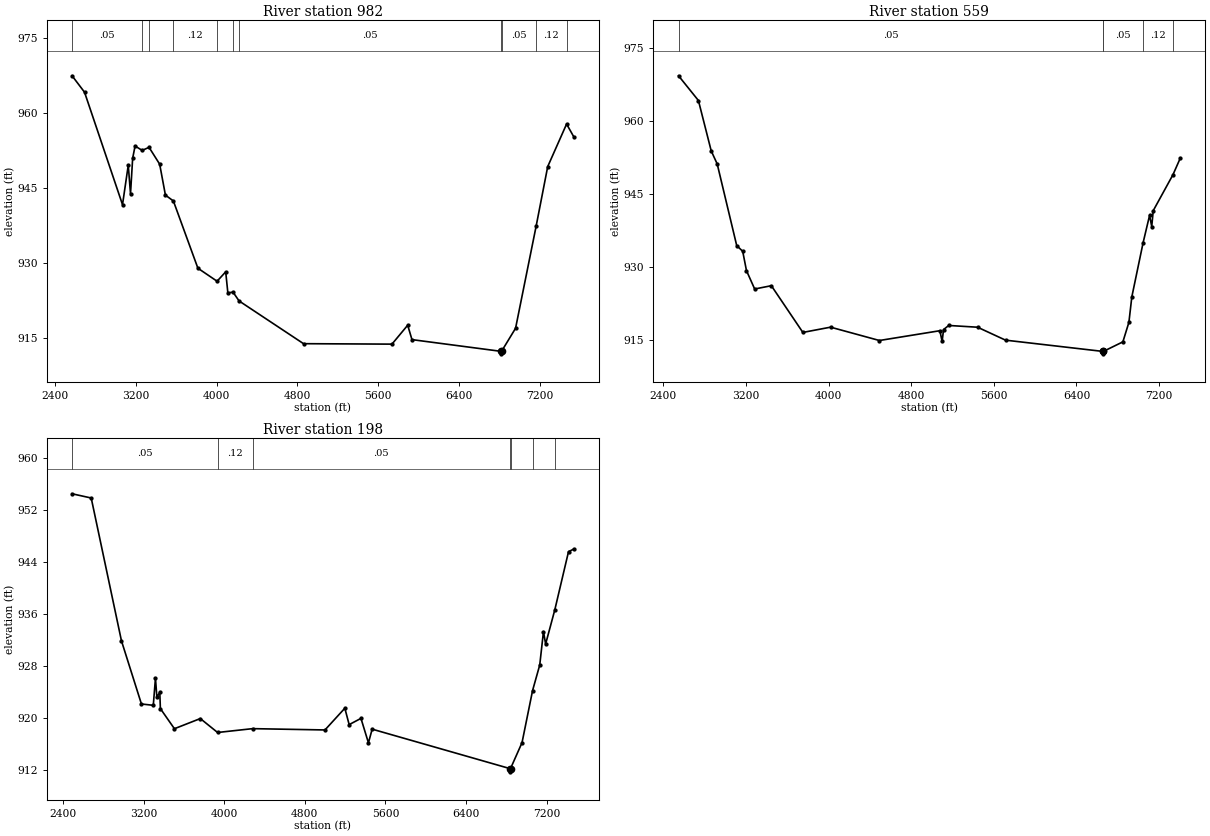
Type RM Length L Ch R = 1,982,423,423,423
BEGIN DESCRIPTION:
Upper Denton 69 2.0
END DESCRIPTION:
XS GIS Cut Line= 3
      2211882.53      7240459.23      2214179.00      7239660.00
      2215934.32      7237829.34
#Sta/Elev= 30
  2568.7  967.36  2692.0  964.08  3068.1  941.60  3125.0  949.49  3147.3  943.78
  3168.5  950.87  3192.5  953.32  3263.0  952.45  3330.8  953.06  3436.0  949.69
  3492.9  943.51  3571.7  942.34  3814.4  928.90  4004.4  926.30  4089.7  928.18
  4110.9  923.99  4162.7  924.11  4222.1  922.36  4860.3  913.82  5735.7  913.73
  5891.4  917.51  5933.8  914.63  6815.2  912.29  6815.9  911.79  6820.5  912.29
  6959.4  916.90  7162.5  937.25  7277.6  949.21  7464.6  957.72  7536.5  955.13
#Mann=11,-1,0
  2568.7    0.05       0  3263.0    0.12       0  3330.8    0.05       0
  3571.7    0.12       0  4004.4    0.05       0  4162.7    0.12       0
  4222.1    0.05       0  6815.2   0.033       0  6820.5    0.05       0
  7162.5    0.12       0  7464.6    0.05       0
Bank Sta=6815.2,6820.5
Exp/Cntr=0.3,0.1

Type RM Length L Ch R = 1,559,361,361,361
BEGIN DESCRIPTION:
Upper Denton 69 1.0
END DESCRIPTION:
XS GIS Cut Line= 3
      2212445.49      7241151.93      2214529.00      7239860.00
      2215970.40      7237934.11
#Sta/Elev= 30
  2548.2  969.21  2740.6  964.13  2864.6  953.77  2922.4  951.10  3111.4  934.32
  3169.3  933.15  3205.9  929.17  3285.1  925.40  3446.6  926.08  3751.7  916.48
  4019.9  917.56  4492.4  914.82  5077.9  916.83  5099.7  914.62  5113.3  917.06
  5163.3  917.91  5442.6  917.55  5713.5  914.89  6654.6  912.58  6655.5  912.08
  6660.4  912.58  6849.2  914.54  6907.6  918.56  6935.8  923.78  7045.3  934.94
  7107.7  940.53  7128.5  938.22  7143.1  941.50  7334.5  948.90  7405.3  952.31
#Mann=5,-1,0
  2548.2    0.05       0  6654.6   0.033       0  6660.4    0.05       0
  7045.3    0.12       0  7334.5    0.05       0
Bank Sta=6654.6,6660.4
Exp/Cntr=0.3,0.1

Type RM Length L Ch R = 1,198,0,0,0
BEGIN DESCRIPTION:
Upper Denton 69 0.5
END DESCRIPTION:
XS GIS Cut Line= 3
      2212619.09      7241379.80      2214767.54      7240142.82
      2216036.64      7237984.26
#Sta/Elev= 30
  2488.6  954.45  2678.7  953.80  2979.1  931.84  3177.4  922.13  3295.2  921.93
  3316.7  926.10  3330.8  923.17  3359.8  923.94  3365.6  921.42  3505.0  918.33
  3762.2  919.89  3933.7  917.75  4281.0  918.34  5000.1  918.14  5197.3  921.48
  5240.3  918.96  5357.5  919.92  5431.7  916.16  5468.8  918.26  6836.9  912.20
  6837.8  911.70  6842.7  912.20  6957.0  916.19  7061.7  924.20  7132.8  928.12
  7169.9  933.27  7191.3  931.35  7282.2  936.59  7418.6  945.55  7471.7  945.96
#Mann=7,-1,0
  2488.6    0.05       0  3933.7    0.12       0  4281.0    0.05       0
  6836.9   0.033       0  6842.7    0.05       0  7061.7    0.12       0
  7282.2    0.05       0
Bank Sta=6836.9,6842.7
Exp/Cntr=0.3,0.1

Chan Stop Cuts=-1