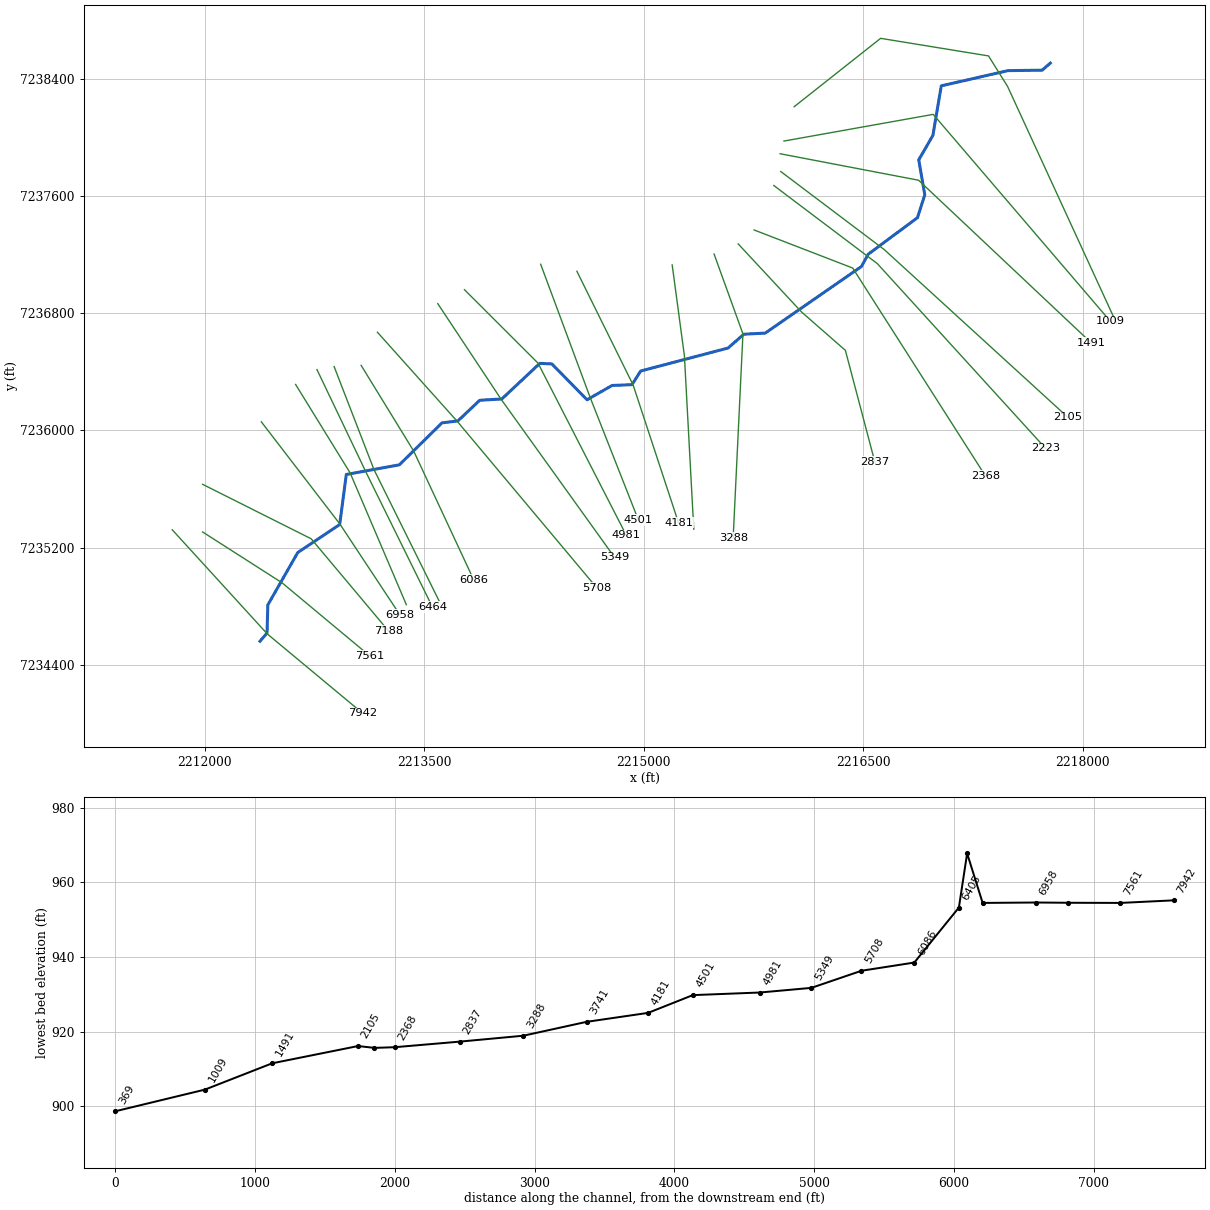
--- Upper Denton 70.prj (project) ---

Proj Title=Upper Denton 70 Base Level Engineering
Current Plan=p01
Default Exp/Contr=0.3,0.1
English Units
Geom File=g01
Flow File=f01
Plan File=p01
Y Axis Title=Elevation
X Axis Title(PF)=Main Channel Distance
X Axis Title(XS)=Station
BEGIN DESCRIPTION:
Upper Denton 70
END DESCRIPTION:
DSS Export Rating Curves= 0
DSS Export Rating Curve Sorted= 0
DSS Export Volume Flow Curves= 0
DXF OffsetX= 0
DXF OffsetY= 0
DXF ScaleX= 1
DXF ScaleY= 10

--- Upper Denton 70.p01 (plan) ---

Plan Title=Multiple Run
Short Identifier=Multiple
Geom File=g01
Flow File=f01
Subcritical Flow
K Sum by GR= 0
Std Step Tol= 0.01
Critical Tol= 0.01
Num of Std Step Trials= 20
Max Error Tol= 0.3
Flow Tol Ratio= 0.001
Split Flow NTrial= 30
Split Flow Tol= 0.02
Split Flow Ratio= 0.02
Log Output Level= 0
Friction Slope Method= 1
Unsteady Friction Slope Method= 2
Unsteady Bridges Friction Slope Method= 1
Parabolic Critical Depth
Global Vel Dist=  1 , 1 , 1
Global Log Level= 0
CheckData=True
Encroach Param= -1, 0, 0, 0
BEGIN DESCRIPTION:
Multiple Run
END DESCRIPTION:

--- Upper Denton 70.f01 (steady flow) ---

Flow Title=Multiple
Program Version=4.10
Number of Profiles= 7
Profile Names=10-year,25-year,50-year,1pct_min,100-year,1pct_plu,500-year
River Rch & RM=Upper Denton 70,Reach-1         ,7942
     677     947    1174     723    1443    2880    2187
River Rch & RM=Upper Denton 70,Reach-1         ,4501
     785    1106    1376     850    1697    3385    2587
Boundary for River Rch & Prof#=Upper Denton 70,Reach-1         , 1
Up Type= 0
Dn Type= 3
Dn Slope=0.009
Boundary for River Rch & Prof#=Upper Denton 70,Reach-1         , 2
Up Type= 0
Dn Type= 3
Dn Slope=0.009
Boundary for River Rch & Prof#=Upper Denton 70,Reach-1         , 3
Up Type= 0
Dn Type= 3
Dn Slope=0.009
Boundary for River Rch & Prof#=Upper Denton 70,Reach-1         , 4
Up Type= 0
Dn Type= 3
Dn Slope=0.009
Boundary for River Rch & Prof#=Upper Denton 70,Reach-1         , 5
Up Type= 0
Dn Type= 3
Dn Slope=0.009
Boundary for River Rch & Prof#=Upper Denton 70,Reach-1         , 6
Up Type= 0
Dn Type= 3
Dn Slope=0.009
Boundary for River Rch & Prof#=Upper Denton 70,Reach-1         , 7
Up Type= 0
Dn Type= 3
Dn Slope=0.009
DSS Import GetInterval= 0
DSS Import GetPeak= 0
DSS Import FillOption= 0

--- Upper Denton 70.g01 (geometry) ---

Geom Title=Existing Conditions
Program Version=4.10

River Reach=Upper Denton 70 ,Reach-1
Reach XY= 30
        2212379.        7234560.      2212427.11      7234615.78
      2212432.75      7234808.45      2212637.13      7235166.07
      2212923.64       7235357.3      2212968.82      7235699.68
      2213331.45      7235765.47      2213622.83      7236052.14
      2213731.43      7236065.52      2213880.47      7236206.46
      2214031.44      7236215.48      2214290.98      7236458.54
      2214373.46      7236454.93      2214613.59      7236210.02
      2214784.94      7236307.75      2214920.68      7236313.11
       2214980.3      7236406.45      2215577.53      7236563.56
      2215684.86      7236657.92      2215831.44      7236665.48
      2216488.97       7237120.7      2216534.63      7237204.35
      2216871.15      7237453.81      2216921.44        7237610.
       2216880.2       7237849.5      2216976.76      7238015.93
      2217034.11      7238354.89       2217489.5      7238458.78
      2217723.22      7238461.89        2217779.        7238510.

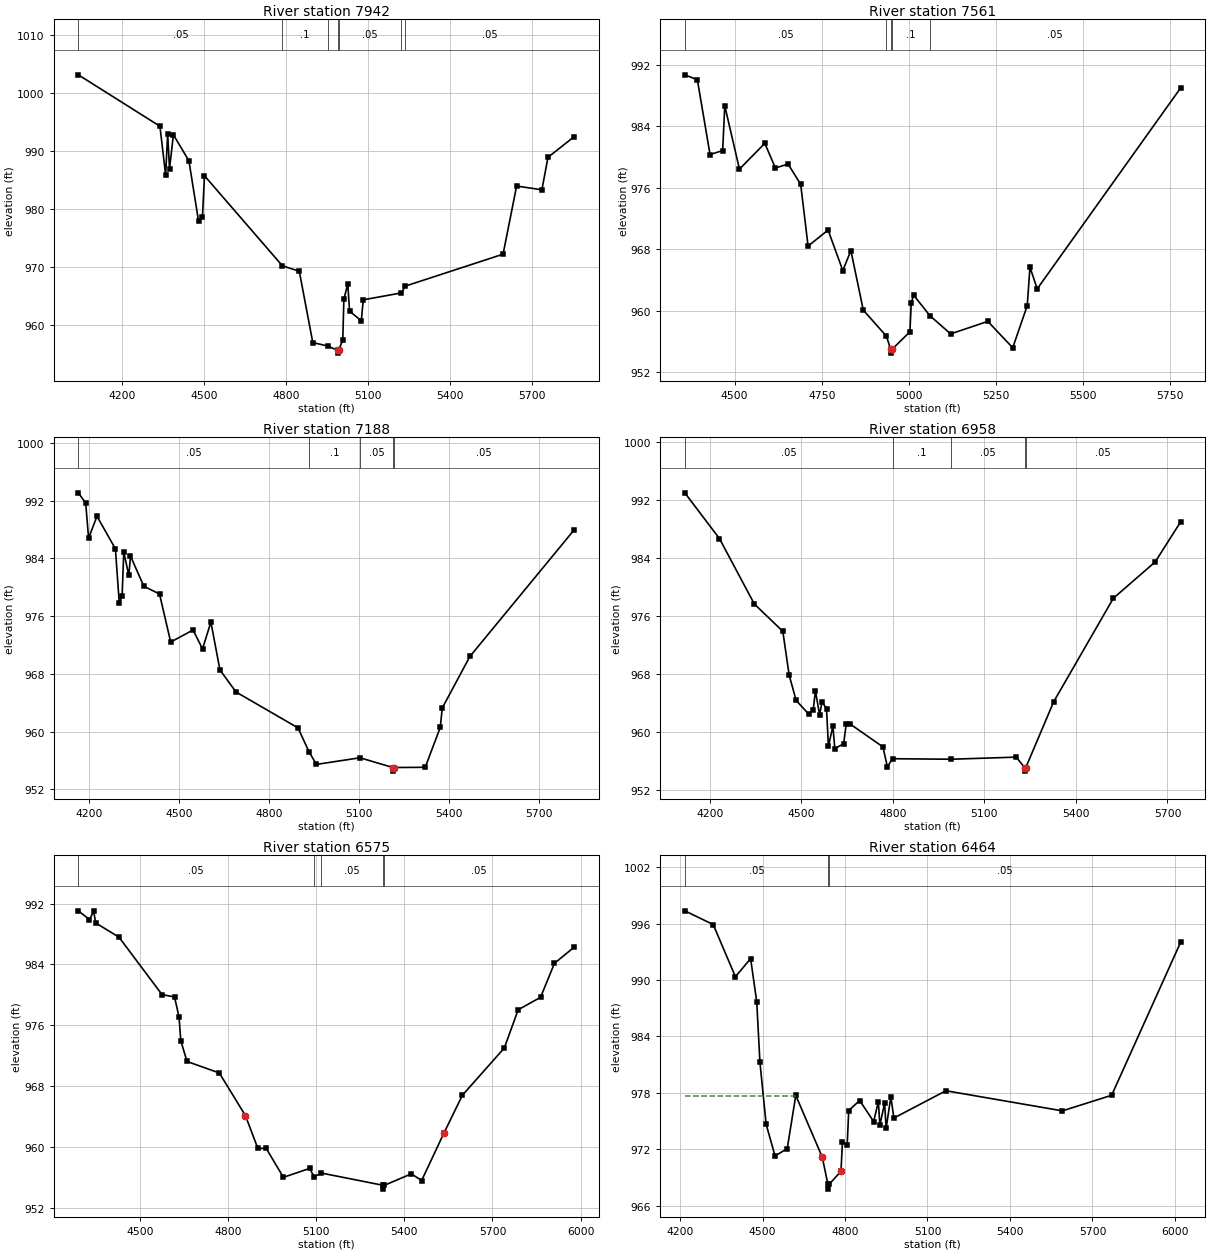
Type RM Length L Ch R = 1 ,7942    ,381,381,381
BEGIN DESCRIPTION:
Upper Denton 70 19.0
END DESCRIPTION:
XS GIS Cut Line= 3
      2211779.61       7235321.5        2212429.        7234610.
      2213081.67      7234067.18
#Sta/Elev= 30
  4040.8 1003.11    4339  994.26  4359.9  985.88  4367.3  992.98  4374.1  986.93
  4388.3  992.78    4445   988.3  4480.2   977.9  4494.4  978.55  4501.8  985.73
  4786.6  970.22  4848.4  969.28  4897.7     957  4951.5  956.41  4988.2  955.68
  4988.5  955.18  4992.2  955.68  5007.4  957.46  5011.3  964.43  5025.6  967.13
  5032.1  962.41  5075.1  960.75  5082.1  964.36  5221.6  965.55  5235.7  966.72
  5593.2  972.22  5642.7  983.96  5735.1  983.31  5757.3   988.9    5853  992.46
#Mann= 7 ,-1 , 0
  4040.8     .05       0  4786.6      .1       0  4951.5     .05       0
  4988.2    .033       0  4992.2     .05       0  5221.6     .12       0
  5235.7     .05       0
Bank Sta=4988.2,4992.2
XS Rating Curve= 0 ,0
Exp/Cntr=0.3,0.1

Type RM Length L Ch R = 1 ,7561    ,373,373,373
BEGIN DESCRIPTION:
Upper Denton 70 18.0
END DESCRIPTION:
XS GIS Cut Line= 3
      2211987.12      7235306.71        2212529.        7234960.
      2213128.98      7234460.02
#Sta/Elev= 30
  4356.7  990.69  4392.8  990.05  4429.2  980.32  4465.5  980.84  4471.5  986.67
  4513.7  978.42  4586.5  981.78  4616.9  978.57  4653.3  979.09  4689.6  976.45
  4710.8  968.41  4768.3   970.5  4810.6  965.23  4833.8  967.83  4869.4  960.09
  4935.7   956.7  4948.1  954.99  4948.3  954.49  4952.1  954.99  5003.3  957.26
  5007.2     961  5013.7  962.05    5061  959.35  5120.4  956.99  5227.1  958.62
  5298.7  955.19  5340.4  960.67  5348.2  965.68    5369  962.85    5781  988.98
#Mann= 5 ,-1 , 0
  4356.7     .05       0  4935.7      .1       0  4948.1     .07       0
  4952.1      .1       0    5061     .05       0
Bank Sta=4948.1,4952.1
XS Rating Curve= 0 ,0
Exp/Cntr=0.3,0.1

Type RM Length L Ch R = 1 ,7188    ,230,230,230
BEGIN DESCRIPTION:
Upper Denton 70 17.0
END DESCRIPTION:
XS GIS Cut Line= 3
      2211987.13      7235632.23        2212729.        7235260.
      2213257.93      7234629.63
#Sta/Elev= 30
  4165.4  993.08  4189.9  991.67  4199.6  986.81  4227.6  989.83    4289  985.32
  4301.8  977.81  4311.3  978.76  4316.9   984.9  4333.7  981.63  4339.3  984.32
  4383.9  980.13    4436  979.07  4473.3  972.41  4547.9  974.08  4579.4  971.46
  4607.3  975.18  4637.4  968.55  4691.1  965.49  4897.7  960.52  4934.1  957.24
  4959.1  955.46  5104.2  956.38  5213.9  955.03  5214.2  954.53  5217.9  955.03
  5321.8  955.06    5372  960.59  5378.5  963.27  5470.9  970.42  5818.3  987.95
#Mann= 5 ,-1 , 0
  4165.4     .05       0  4934.1      .1       0  5104.2     .05       0
  5213.9     .07       0  5217.9     .05       0
Bank Sta=5213.9,5217.9
XS Rating Curve= 0 ,0
Exp/Cntr=0.3,0.1

Type RM Length L Ch R = 1 ,6958    ,383,383,383
BEGIN DESCRIPTION:
Upper Denton 70 16.0
END DESCRIPTION:
XS GIS Cut Line= 3
      2212388.11      7236059.36      2212924.58      7235361.42
      2213335.05      7234740.53
#Sta/Elev= 30
  4118.6  992.97  4232.2  986.66  4346.4  977.64  4439.7  973.88  4460.5  967.85
  4483.3  964.35  4524.9  962.45  4539.4  963.07  4546.6  965.65  4560.2  962.39
  4568.4  964.14  4582.9  963.23  4589.2  958.04  4603.8   960.8  4610.1  957.71
  4639.1  958.37  4647.3  961.03  4660.1   961.1  4767.8  957.94  4782.3  955.21
  4799.6  956.31  4991.2  956.24  5204.4  956.53    5232   955.1  5232.2   954.6
    5236   955.1  5327.2  964.16  5522.9  978.44  5659.9  983.45  5743.2  988.96
#Mann= 5 ,-1 , 0
  4118.6     .05       0  4799.6      .1       0  4991.2     .05       0
    5232    .033       0    5236     .05       0
Bank Sta=5232,5236
XS Rating Curve= 0 ,0
Exp/Cntr=0.3,0.1

Type RM Length L Ch R = 1 ,6575    ,111,111,111
BEGIN DESCRIPTION:
Upper Denton 70 15.5
END DESCRIPTION:
XS GIS Cut Line= 3
       2212622.5      7236314.55       2212994.9      7235710.38
        2213379.      7234810.01
#Sta/Elev= 30
  4289.6  991.05  4327.4  989.91  4341.9  990.98  4348.7  989.46    4428  987.59
  4574.7  980.04  4617.2  979.74  4632.6  977.09  4638.5  973.99  4659.8  971.26
  4769.8  969.75  4858.6  964.15  4901.1  959.83  4929.3  959.85    4988  956.04
  5077.4  957.21  5092.6   956.1  5117.5   956.6  5327.8  954.99  5328.1  954.49
  5331.8  954.99  5423.7   956.5  5458.8  955.62  5535.1  961.89  5597.7  966.83
  5740.3  973.03  5787.5  978.05  5863.8  979.69    5911  984.15  5978.2  986.28
#Mann= 5 ,-1 , 0
  4289.6     .05       0  5092.6      .1       0  5117.5     .05       0
  5327.8    .033       0  5331.8     .05       0
Bank Sta=4858.6,5535.1
XS Rating Curve= 0 ,0
Exp/Cntr=0.3,0.1

Type RM Length L Ch R = 1 ,6464    ,59,59,59
BEGIN DESCRIPTION:
Upper Denton 70 15.0
END DESCRIPTION:
XS GIS Cut Line= 3
      2212768.35      7236416.07      2213109.48      7235702.57
      2213557.09      7234794.34
#Sta/Elev= 30
  4217.3  997.35  4320.7  995.89  4401.4  990.34  4456.7  992.27    4479  987.66
  4490.5  981.27  4513.2  974.65  4545.5  971.29  4589.8  972.06    4621  977.72
  4717.3  971.16  4737.9  968.26  4738.2  967.76  4741.9  968.26  4785.3  969.65
  4790.8  972.81    4808  972.49  4813.5  976.12  4853.3  977.18  4904.2  974.95
  4921.3  977.07  4926.9  974.55    4944  976.92  4949.6  974.23  4966.7  977.57
  4977.8  975.32  5167.1  978.22  5590.7  976.08  5769.8  977.74  6020.7  994.01
#Mann= 3 ,-1 , 0
  4217.3     .05       0  4737.9    .033       0  4741.9     .05       0
#XS Ineff= 2 , 0
         4622.41  977.64
Permanent Ineff=
       F       F
Bank Sta=4717.3,4785.3
XS Rating Curve= 0 ,0
Exp/Cntr=0.3,0.1

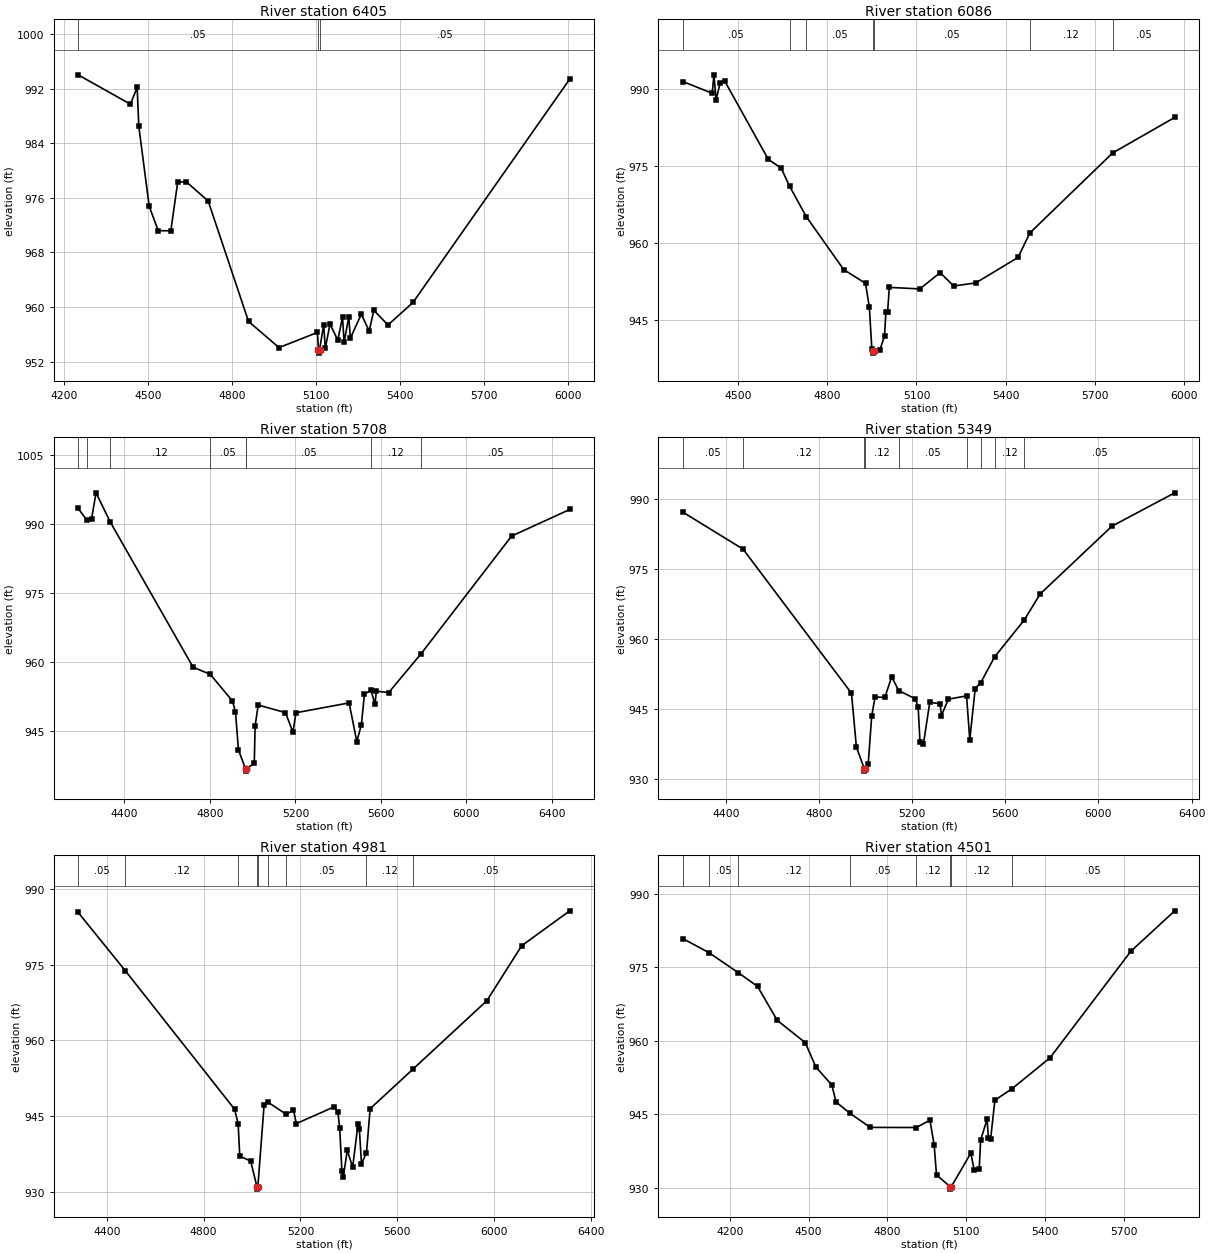
Type RM Length L Ch R = 1 ,6405    ,319,319,319
BEGIN DESCRIPTION:
Upper Denton 70 14.5
END DESCRIPTION:
XS GIS Cut Line= 3
      2212885.54       7236436.9      2213157.65      7235733.44
      2213603.57      7234834.19
#Sta/Elev= 30
  4249.7  994.02  4436.7  989.72  4460.8  992.18  4466.7  986.48  4503.7  974.79
  4535.9  971.19  4581.1  971.17  4605.7  978.27  4635.6  978.38  4714.7  975.54
  4859.1  957.89  4968.1  954.06  5105.5  956.28  5109.1  953.75  5109.3  953.25
  5113.1  953.75  5127.9  957.44  5133.5  953.93  5150.3  957.51  5178.3  955.15
  5195.2  958.55  5200.7  954.83  5217.6  958.54  5223.2  955.44  5262.4  958.95
  5290.4  956.49  5307.2  959.52  5357.7  957.37  5447.3  960.68  6007.7   993.4
#Mann= 3 ,-1 , 0
  4249.7     .05       0  5109.1    .033       0  5113.1     .05       0
Bank Sta=5109.1,5113.1
XS Rating Curve= 0 ,0
Exp/Cntr=0.3,0.1

Type RM Length L Ch R = 1 ,6086    ,378,378,378
BEGIN DESCRIPTION:
Upper Denton 70 14.0
END DESCRIPTION:
XS GIS Cut Line= 3
       2213070.4      7236444.78        2213429.        7235860.
      2213838.63      7234981.25
#Sta/Elev= 30
    4314  991.37  4412.1   989.1  4417.9  992.69  4425.2  987.86  4439.2  991.18
  4454.6  991.44  4601.1  976.22  4644.1  974.55  4672.5  971.02  4728.7   965.1
  4854.9  954.77  4928.4   952.1  4941.3  947.44  4949.7  939.32  4953.5  939.01
  4953.8  938.51  4957.5  939.01  4976.8  939.13  4992.3  941.84    4997  946.53
  5002.7  946.53  5008.6  951.31  5111.1  951.01  5179.7  954.17  5225.5  951.58
  5299.6  952.18  5442.3  957.15  5481.5  961.89  5760.5  977.48  5969.5  984.39
#Mann= 7 ,-1 , 0
    4314     .05       0  4672.5     .12       0  4728.7     .05       0
  4953.5    .033       0  4957.5     .05       0  5481.5     .12       0
  5760.5     .05       0
Bank Sta=4953.5,4957.5
XS Rating Curve= 0 ,0
Exp/Cntr=0.3,0.1

Type RM Length L Ch R = 1 ,5708    ,359,359,359
BEGIN DESCRIPTION:
Upper Denton 70 13.0
END DESCRIPTION:
XS GIS Cut Line= 3
      2213181.51      7236671.33        2213729.        7236060.
      2214678.89      7234926.56
#Sta/Elev= 30
  4183.6  993.41  4222.9  990.97  4246.5   991.2  4267.5   996.8    4333  990.53
  4721.3   958.9  4801.4  957.36  4905.2  951.57  4919.4  949.25  4933.6  940.89
  4966.7  936.81    4967  936.31  4970.7  936.81  5007.5  938.02  5011.4  946.05
  5025.7  950.68  5153.2  949.03  5188.4  944.79  5202.7     949  5451.2  951.14
    5487  942.74  5508.4  946.36  5522.7  952.99  5553.3  953.94  5572.2  950.86
  5578.7   953.7  5635.9  953.37  5787.9  961.83    6211   987.4  6483.1  993.18
#Mann= 8 ,-1 , 0
  4183.6     .12       0  4222.9     .05       0    4333     .12       0
  4801.4     .05       0  4966.7    .033       0  4970.7     .05       0
  5553.3     .12       0  5787.9     .05       0
Bank Sta=4966.7,4970.7
XS Rating Curve= 0 ,0
Exp/Cntr=0.3,0.1

Type RM Length L Ch R = 1 ,5349    ,368,368,368
BEGIN DESCRIPTION:
Upper Denton 70 12.0
END DESCRIPTION:
XS GIS Cut Line= 3
      2213593.83      7236866.67        2214029.        7236210.
      2214800.42       7235134.9
#Sta/Elev= 30
  4216.2  987.26  4473.9  979.34  4939.3  948.44  4960.4  936.91  4994.4  932.22
  4994.7  931.72  4998.4  932.22  5011.3  933.33  5026.1  943.53  5040.8  947.63
  5082.6  947.54    5112  951.96    5142     949  5212.7  947.26  5225.5  945.56
  5233.6  937.95  5248.3  937.55  5275.4  946.47  5319.6  946.18  5325.7  943.64
  5355.2  947.16  5433.5  947.86  5447.3  938.44  5470.6  949.44  5494.3   950.7
    5554  956.24  5681.2  964.14  5749.4  969.72  6057.6  984.27  6327.2  991.43
#Mann= 9 ,-1 , 0
  4216.2     .05       0  4473.9     .12       0  4994.4     .07       0
  4998.4     .12       0    5142     .05       0  5433.5     .12       0
  5494.3     .05       0    5554     .12       0  5681.2     .05       0
Bank Sta=4994.4,4998.4
XS Rating Curve= 0 ,0
Exp/Cntr=0.3,0.1

Type RM Length L Ch R = 1 ,4981    ,480,480,480
BEGIN DESCRIPTION:
Upper Denton 70 11.0
END DESCRIPTION:
XS GIS Cut Line= 3
      2213776.18      7236962.09        2214279.        7236460.
      2214882.24      7235283.75
#Sta/Elev= 30
    4281  985.39  4476.5  973.79  4927.9  946.33  4942.7  943.42  4949.2  937.02
  4994.4  936.06  5020.1  930.98  5020.3  930.48  5024.1  930.98  5049.9  947.18
  5066.1  947.72    5142  945.31  5171.4  946.19    5183  943.48    5340  946.82
    5355  945.76  5362.4  942.59  5371.6  934.05  5377.2  932.91  5393.8  938.16
    5416  934.84  5438.2  943.39  5443.8  942.36  5452.4  935.54  5473.2  937.65
  5488.2  946.43  5663.8  954.22  5970.8  967.87    6115  978.78  6313.5   985.7
#Mann= 9 ,-1 , 0
    4281     .05       0  4476.5     .12       0  4942.7     .05       0
  5020.1    .033       0  5024.1     .05       0  5066.1     .12       0
    5142     .05       0  5473.2     .12       0  5663.8     .05       0
Bank Sta=5020.1,5024.1
XS Rating Curve= 0 ,0
Exp/Cntr=0.3,0.1

Type RM Length L Ch R = 1 ,4501    ,320,320,320
BEGIN DESCRIPTION:
Upper Denton 70 10.0
END DESCRIPTION:
XS GIS Cut Line= 3
      2214296.99       7237135.7      2214635.52      7236224.27
       2214964.7      7235388.32
#Sta/Elev= 30
  4022.7  980.82    4121  977.99  4232.6  973.91  4306.4  971.09  4380.8   964.2
  4487.5  959.64    4528  954.68  4588.7  951.01  4604.8  947.55  4657.9  945.23
  4735.1  942.36  4910.5  942.34    4962  943.83  4978.2  938.78  4987.1  932.66
  5039.2  930.28  5039.5  929.78  5043.4  930.28  5117.8  937.13  5130.6  933.58
  5149.6  933.95    5155  939.76  5179.4     944  5184.8  940.19    5193  940.02
  5209.2  947.91  5273.8  950.22  5418.7  956.53  5726.4  978.26  5893.4  986.51
#Mann= 8 ,-1 , 0
  4022.7     .12       0    4121     .05       0  4232.6     .12       0
  4657.9     .05       0  4910.5     .12       0  5039.2     .07       0
  5043.4     .12       0  5273.8     .05       0
Bank Sta=5039.2,5043.4
XS Rating Curve= 0 ,0
Exp/Cntr=0.3,0.1

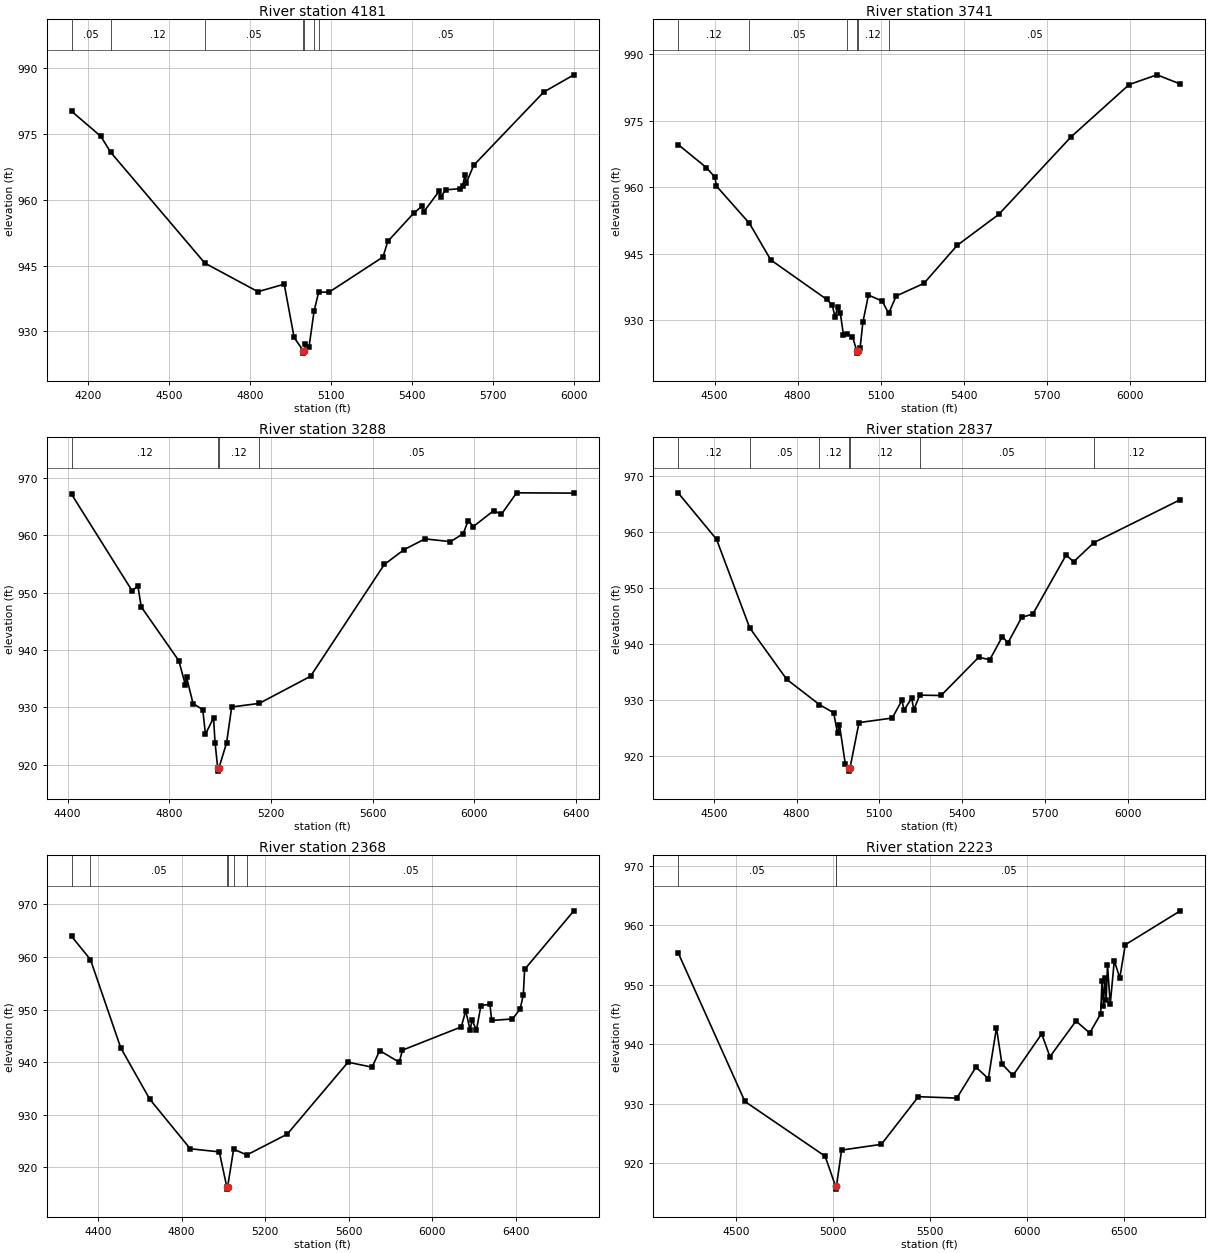
Type RM Length L Ch R = 1 ,4181    ,440,440,440
BEGIN DESCRIPTION:
Upper Denton 70 9.0
END DESCRIPTION:
XS GIS Cut Line= 3
      2214544.36      7237088.02        2214929.        7236310.
      2215238.83      7235369.21
#Sta/Elev= 30
  4140.6  980.21  4248.5  974.51  4285.3  970.84  4633.4  945.57    4830  939.04
  4927.2  940.76  4963.9  928.59    4998  925.52  4998.3  925.02  5002.2  925.52
  5005.7   927.1    5019  926.42  5037.6  934.55  5054.6  938.95  5093.2  938.93
  5292.8  946.96  5310.4  950.52  5405.7  956.92  5437.5  958.58  5442.8  957.23
  5501.1  962.02  5506.3  960.64  5524.4  962.28    5577  962.56  5587.6  963.13
  5596.4  965.78  5601.7  963.95  5628.2  967.88  5887.6  984.61    5999  988.54
#Mann= 7 ,-1 , 0
  4140.6     .05       0  4285.3     .12       0  4633.4     .05       0
    4998    .033       0  5002.2     .05       0  5037.6     .12       0
  5054.6     .05       0
Bank Sta=4998,5002.2
XS Rating Curve= 0 ,0
Exp/Cntr=0.3,0.1

Type RM Length L Ch R = 1 ,3741    ,453,453,453
BEGIN DESCRIPTION:
Upper Denton 70 8.0
END DESCRIPTION:
XS GIS Cut Line= 3
      2215195.42      7237131.37        2215279.        7236510.
      2215342.99      7235325.79
#Sta/Elev= 30
  4368.5  969.63  4470.8  964.41  4501.1  962.28    4507  960.25  4626.1  951.86
  4702.9  943.62  4904.7  934.74  4924.8  933.47  4934.9  930.79    4945  933.04
    4954  931.65  4965.2  926.81  4977.7  927.04    4998  926.35  5013.4  923.12
  5013.7  922.62  5017.6  923.12  5025.5  923.78  5035.5   929.6  5055.6  935.71
  5105.6  934.33  5128.6  931.56  5155.7   935.5  5255.8  938.33    5376  946.91
  5526.2  953.89  5786.6  971.32  5996.9  983.14  6097.1  985.33  6181.4  983.26
#Mann= 6 ,-1 , 0
  4368.5     .12       0  4626.1     .05       0  4977.7     .12       0
  5013.4     .07       0  5017.6     .12       0  5128.6     .05       0
Bank Sta=5013.4,5017.6
XS Rating Curve= 0 ,0
Exp/Cntr=0.3,0.1

Type RM Length L Ch R = 1 ,3288    ,451,451,451
BEGIN DESCRIPTION:
Upper Denton 70 7.0
END DESCRIPTION:
XS GIS Cut Line= 3
      2215481.88      7237205.17        2215679.        7236660.
      2215612.09      7235265.12
#Sta/Elev= 30
  4415.9  967.12  4653.7  950.33  4676.6  951.15  4689.7  947.52  4837.6  938.14
    4863  933.98  4868.3  935.22  4893.6  930.68  4931.8  929.61  4942.4  925.34
  4974.3  928.19  4980.3  923.81  4990.8   919.4  4991.2   918.9  4995.1   919.4
  5025.6  923.83  5045.7  930.08  5154.1   930.7    5356  935.43  5646.4  954.91
  5723.8  957.48  5806.5  959.37  5906.7  958.88  5956.7  960.28  5976.7  962.56
  5996.8  961.52  6076.9  964.29  6106.9  963.64    6167  967.39  6392.1  967.34
#Mann= 4 ,-1 , 0
  4415.9     .12       0  4990.8     .07       0  4995.1     .12       0
  5154.1     .05       0
Bank Sta=4990.8,4995.1
XS Rating Curve= 0 ,0
Exp/Cntr=0.3,0.1

Type RM Length L Ch R = 1 ,2837    ,469,469,469
BEGIN DESCRIPTION:
Upper Denton 70 6.0
END DESCRIPTION:
XS GIS Cut Line= 4
      2215646.78      7237274.64        2216079.        7236810.
      2216378.92      7236547.57      2216579.97      7235785.87
#Sta/Elev= 30
  4370.1  966.93  4509.5  958.64  4629.8  942.85  4764.1  933.68  4882.7  929.18
  4934.1  927.73  4948.3  924.04  4955.1  925.59  4976.6  918.52  4988.4  917.83
  4988.9  917.33  4993.1  917.83    5026  925.98  5146.6  926.79  5181.7  929.96
  5189.3   928.2  5217.3  930.36  5224.4  928.24  5246.2  930.87  5323.6  930.81
  5459.9  937.62  5500.2  937.19  5545.7  941.29  5566.2   940.2  5615.9  944.74
  5656.2  945.32    5777  955.85  5804.1  954.64    5878  958.06    6191  965.71
#Mann= 7 ,-1 , 0
  4370.1     .12       0  4629.8     .05       0  4882.7     .12       0
  4988.4     .07       0  4993.1     .12       0  5246.2     .05       0
    5878     .12       0
Bank Sta=4988.4,4993.1
XS Rating Curve= 0 ,0
Exp/Cntr=0.3,0.1

Type RM Length L Ch R = 1 ,2368    ,145,145,145
BEGIN DESCRIPTION:
Upper Denton 70 5.0
END DESCRIPTION:
XS GIS Cut Line= 3
      2215755.32       7237370.1        2216429.        7237110.
      2217334.58      7235691.35
#Sta/Elev= 30
  4273.4  963.92  4363.3  959.52  4508.7   942.7  4647.8  932.92  4841.5   923.5
  4980.6  922.91    5016  916.32  5016.5  915.82  5020.7  916.32  5049.2  923.43
  5112.3  922.32  5306.1  926.29  5597.1  939.98  5712.2  939.03  5748.6  942.19
  5842.5  939.97  5857.7  942.27  6139.5   946.7  6160.6  949.75  6181.9  946.11
  6191.1  947.99  6212.2  946.08  6233.4  950.76  6276.8     951    6285  947.92
  6384.8  948.21  6421.2  950.09  6436.5  952.75  6442.9  957.65  6678.6  968.79
#Mann= 6 ,-1 , 0
  4273.4     .12       0  4363.3     .05       0    5016    .033       0
  5020.7     .05       0  5049.2     .12       0  5112.3     .05       0
Bank Sta=5016,5020.7
XS Rating Curve= 0 ,0
Exp/Cntr=0.3,0.1

Type RM Length L Ch R = 1 ,2223    ,118,118,118
BEGIN DESCRIPTION:
Upper Denton 70 4.5
END DESCRIPTION:
XS GIS Cut Line= 3
      2215889.87      7237673.91      2216597.33      7237140.07
      2217747.48      7235877.06
#Sta/Elev= 30
  4198.4  955.38  4543.5  930.37  4957.8  921.18  5011.6  916.14  5012.1  915.64
  5016.4  916.14  5043.1   922.2  5248.5  923.17  5439.7  931.18  5638.3  930.94
    5737  936.15  5801.2  934.21  5843.1  942.73  5871.4  936.69  5928.2  934.74
  6076.8  941.74  6119.4   937.9  6253.9   943.9  6324.8  941.88  6381.6   945.1
  6388.3  950.55  6395.8   946.5  6402.5  951.18  6409.9  947.49  6416.7   953.3
  6430.9  946.74  6451.8  954.04  6480.2  951.13  6508.6  956.72  6792.9  962.42
#Mann= 3 ,-1 , 0
  4198.4     .05       0  5011.6    .033       0  5016.4     .05       0
Bank Sta=5011.6,5016.4
XS Rating Curve= 0 ,0
Exp/Cntr=0.3,0.1

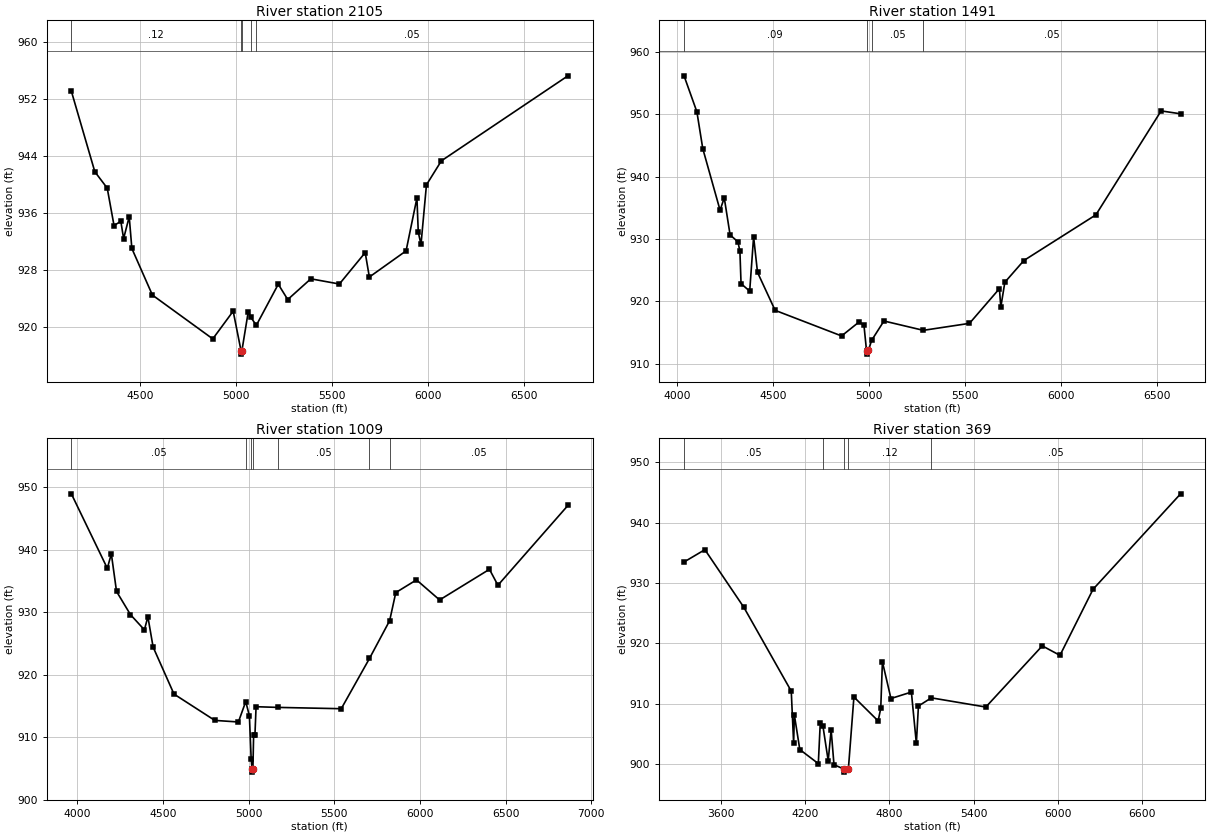
Type RM Length L Ch R = 1 ,2105    ,614,614,614
BEGIN DESCRIPTION:
Upper Denton 70 4.0
END DESCRIPTION:
XS GIS Cut Line= 3
       2215937.6      7237769.41      2216645.07      7237235.55
      2217899.41      7236089.72
#Sta/Elev= 30
  4142.4  953.03  4264.5  941.73  4329.1  939.43  4364.5  934.18  4399.9  934.77
  4414.4  932.35  4443.6  935.41  4457.3  930.96  4564.3  924.42  4878.6  918.27
  4984.8  922.16  5025.6  916.63  5026.2  916.13  5030.4  916.63  5063.5  922.11
    5077  921.28  5105.5  920.18  5219.6  925.94  5268.9  923.79  5389.1   926.7
  5537.8  925.97  5672.2  930.38  5693.8  926.95    5885  930.62  5941.5  938.05
  5948.5  933.23  5962.7  931.54  5991.1  939.89  6068.8  943.26  6727.6  955.19
#Mann= 5 ,-1 , 0
  4142.4     .12       0  5025.6    .033       0  5030.4     .05       0
    5077     .12       0  5105.5     .05       0
Bank Sta=5025.6,5030.4
XS Rating Curve= 0 ,0
Exp/Cntr=0.3,0.1

Type RM Length L Ch R = 1 ,1491    ,482,482,482
BEGIN DESCRIPTION:
Upper Denton 70 3.0
END DESCRIPTION:
XS GIS Cut Line= 3
      2215933.28      7237890.93        2216879.        7237710.
      2218059.99      7236597.55
#Sta/Elev= 30
  4037.5  956.19  4104.4  950.41    4135  944.51  4225.1  934.61  4246.9  936.61
  4277.2  930.66  4318.2  929.53  4328.4  928.03  4334.3  922.83  4379.3  921.62
  4399.7  930.35    4420  924.64  4511.7  918.54  4857.8  914.43  4949.5  916.69
  4974.3  916.13  4987.8  912.01  4988.3  911.51  4997.8  912.13  5014.3  913.73
  5078.3  916.83  5283.4  915.33  5523.7  916.45  5679.5  922.02  5686.8  919.07
  5707.8  923.05  5806.9  926.54  6181.8  933.87  6521.4  950.56  6622.8  950.09
#Mann= 4 ,-1 , 0
  4037.5     .09       0  4987.8     .03       0  5014.3     .05       0
  5283.4     .05       0
Bank Sta=4987.8,4997.8
XS Rating Curve= 0 ,0
Exp/Cntr=0.3,0.1

Type RM Length L Ch R = 1 ,1009    ,640,640,640
BEGIN DESCRIPTION:
Upper Denton 70 2.0
END DESCRIPTION:
XS GIS Cut Line= 3
      2215959.35      7237977.75        2216979.        7238160.
       2218190.2      7236745.12
#Sta/Elev= 30
  3964.6  948.95  4174.4  937.04  4197.9  939.36  4228.2  933.34  4309.6  929.63
  4390.9   927.2  4411.2   929.3  4441.7  924.45  4563.6  916.93  4801.9  912.72
  4939.5  912.47  4982.4  915.73  5003.7  913.46  5014.1  906.53  5019.4  904.95
    5020  904.45  5024.2  904.95  5028.4  910.39  5036.1   910.4  5042.7  914.91
  5169.4   914.8  5539.9  914.59  5704.5  922.62  5822.4  928.67  5858.2  933.16
    5979  935.19    6114  931.98  6404.9  936.88  6454.3  934.33  6862.9  947.09
#Mann= 7 ,-1 , 0
  3964.6     .05       0  4982.4     .12       0  5014.1     .07       0
  5024.2     .12       0  5169.4     .05       0  5704.5     .12       0
  5822.4     .05       0
Bank Sta=5019.4,5024.2
XS Rating Curve= 0 ,0
Exp/Cntr=0.3,0.1

Type RM Length L Ch R = 1 ,369     ,0,0,0
BEGIN DESCRIPTION:
Upper Denton 70 1.0
END DESCRIPTION:
XS GIS Cut Line= 5
      2216028.77      7238212.13      2216619.76       7238679.5
      2217356.88      7238559.34      2217487.08        7238351.
      2218233.62      7236727.72
#Sta/Elev= 30
  3339.5  933.46  3487.8   935.5  3765.1  925.95  4102.3  912.07  4119.2  903.42
  4124.3  908.14  4163.1   902.4  4294.8  900.07  4308.7  906.83  4327.1  906.37
  4365.1  900.55    4386  905.66  4406.3  899.89  4477.6  899.16  4480.6  898.66
  4508.6  899.16  4548.1   911.1  4720.4  907.14    4739  909.23  4750.8  916.93
  4811.6  910.85  4956.9  911.92  4992.3  903.41  5007.1  909.61    5099  910.96
  5486.6  909.44  5888.2  919.57  6014.1     918  6249.3  928.94  6872.2  944.75
#Mann= 5 ,-1 , 0
  3339.5     .05       0  4327.1     .12       0  4477.6     .07       0
  4508.6     .12       0    5099     .05       0
Bank Sta=4477.6,4508.6
XS Rating Curve= 0 ,0
Exp/Cntr=0.3,0.1

Chan Stop Cuts=-1
Use User Specified Reach Order=0
Composite Channel Slope=5