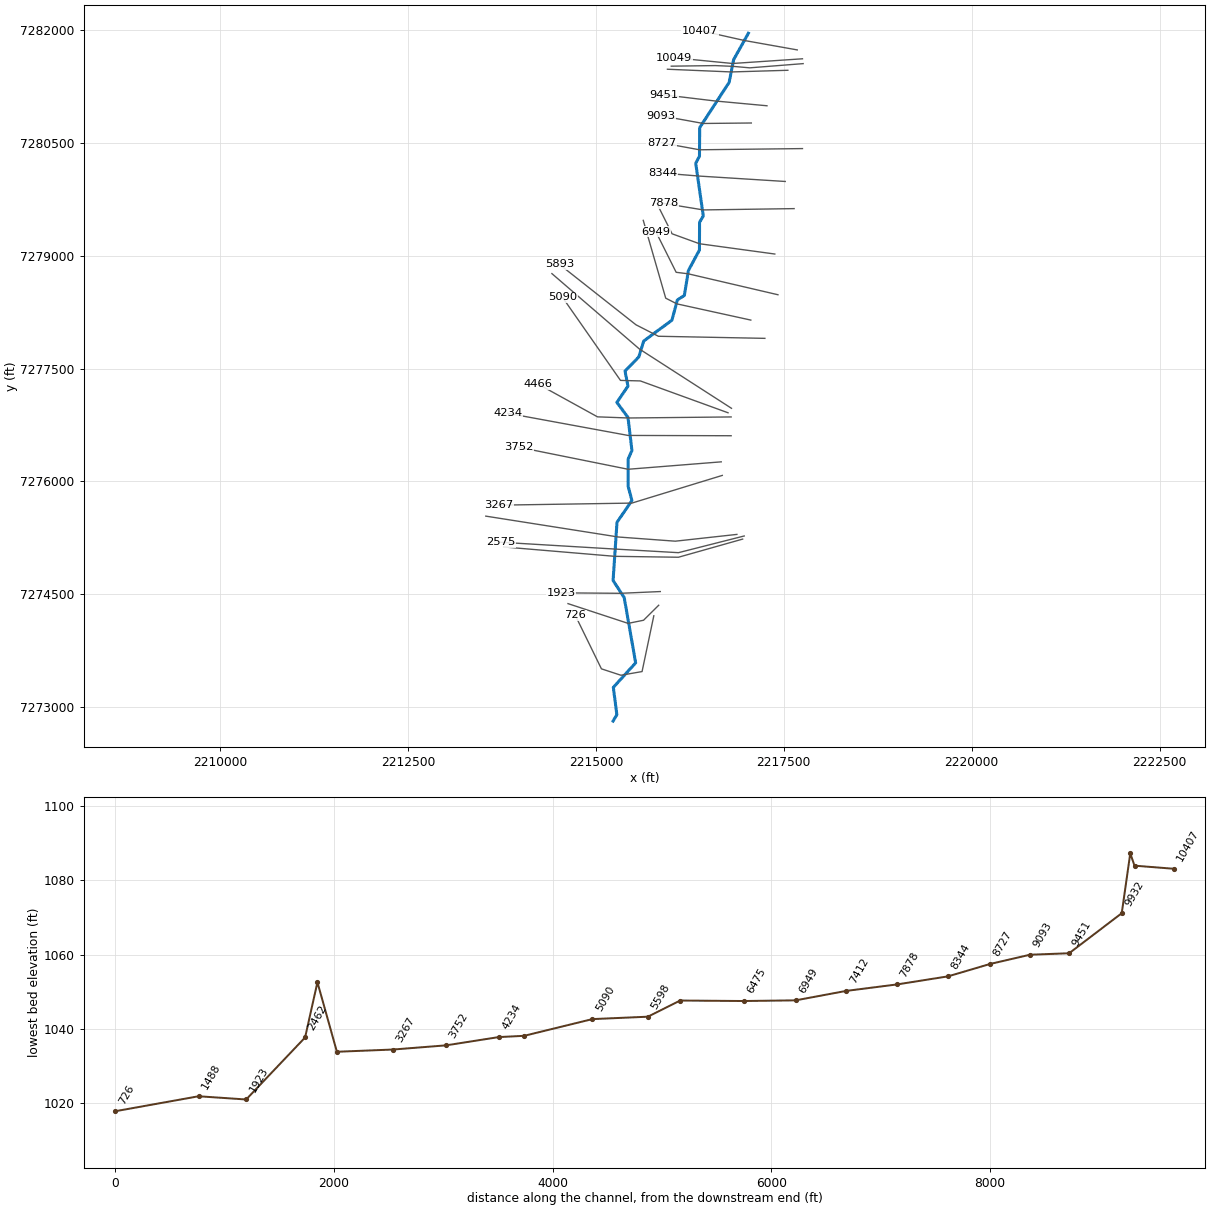
--- Upper Denton 72.prj (project) ---

Proj Title=Upper Denton 72 Base Level Engineering
Current Plan=p01
Default Exp/Contr=0.3,0.1
English Units
Geom File=g01
Flow File=f01
Plan File=p01
Y Axis Title=Elevation
X Axis Title(PF)=Main Channel Distance
X Axis Title(XS)=Station
BEGIN DESCRIPTION:
Upper Denton 72
END DESCRIPTION:
DSS Export Rating Curves= 0
DSS Export Rating Curve Sorted= 0
DSS Export Volume Flow Curves= 0
DXF OffsetX= 0
DXF OffsetY= 0
DXF ScaleX= 1
DXF ScaleY= 10

--- Upper Denton 72.p01 (plan) ---

Plan Title=Multiple Run
Short Identifier=Multiple
Geom File=g01
Flow File=f01
Subcritical Flow
K Sum by GR= 0
Std Step Tol= 0.01
Critical Tol= 0.01
Num of Std Step Trials= 20
Max Error Tol= 0.3
Flow Tol Ratio= 0.001
Split Flow NTrial= 30
Split Flow Tol= 0.02
Split Flow Ratio= 0.02
Log Output Level= 0
Friction Slope Method= 1
Unsteady Friction Slope Method= 2
Unsteady Bridges Friction Slope Method= 1
Parabolic Critical Depth
Global Vel Dist=  1 , 1 , 1
Global Log Level= 0
CheckData=True
Encroach Param= -1, 0, 0, 0
BEGIN DESCRIPTION:
Multiple Run
END DESCRIPTION:

--- Upper Denton 72.f01 (steady flow) ---

Flow Title=Multiple
Program Version=4.10
Number of Profiles= 7
Profile Names=10-year,25-year,50-year,1pct_min,100-year,1pct_plu,500-year
River Rch & RM=Upper Denton 72,Reach-1         ,10407
     741    1043    1299     804    1604    3200    2451
River Rch & RM=Upper Denton 72,Reach-1         ,7412
    1058    1512    1901    1185    2365    4719    3675
River Rch & RM=Upper Denton 72,Reach-1         ,2753
    1171    1679    2116    1322    2638    5263    4114
Boundary for River Rch & Prof#=Upper Denton 72,Reach-1         , 1
Up Type= 0
Dn Type= 3
Dn Slope=0.0055
Boundary for River Rch & Prof#=Upper Denton 72,Reach-1         , 2
Up Type= 0
Dn Type= 3
Dn Slope=0.0055
Boundary for River Rch & Prof#=Upper Denton 72,Reach-1         , 3
Up Type= 0
Dn Type= 3
Dn Slope=0.0055
Boundary for River Rch & Prof#=Upper Denton 72,Reach-1         , 4
Up Type= 0
Dn Type= 3
Dn Slope=0.0055
Boundary for River Rch & Prof#=Upper Denton 72,Reach-1         , 5
Up Type= 0
Dn Type= 3
Dn Slope=0.0055
Boundary for River Rch & Prof#=Upper Denton 72,Reach-1         , 6
Up Type= 0
Dn Type= 3
Dn Slope=0.0055
Boundary for River Rch & Prof#=Upper Denton 72,Reach-1         , 7
Up Type= 0
Dn Type= 3
Dn Slope=0.0055
DSS Import GetInterval= 0
DSS Import GetPeak= 0
DSS Import FillOption= 0

--- Upper Denton 72.g01 (geometry) ---

Geom Title=Existing Conditions
Program Version=4.10

River Reach=Upper Denton 72 ,Reach-1
Reach XY= 30
        2217029.        7281960.      2216832.56      7281608.53
      2216773.46      7281307.58      2216381.24      7280704.07
      2216378.46      7280325.21      2216328.72      7280230.18
      2216428.93      7279530.03      2216379.52      7279444.78
      2216378.05      7279075.96      2216231.24      7278804.07
      2216177.24      7278471.88       2216084.4      7278412.68
      2216012.37      7278143.29      2215636.88      7277866.13
      2215571.12      7277653.87      2215388.13      7277466.74
      2215426.94      7277265.86      2215279.68      7277049.25
      2215427.81      7276849.52      2215479.82        7276410.
      2215429.52      7276294.78       2215428.8      7275934.92
      2215479.55      7275744.52      2215281.24      7275454.07
      2215229.06      7274680.03      2215376.94      7274454.14
       2215529.5      7273584.96      2215232.53      7273258.53
      2215279.41      7272894.83        2215229.        7272810.

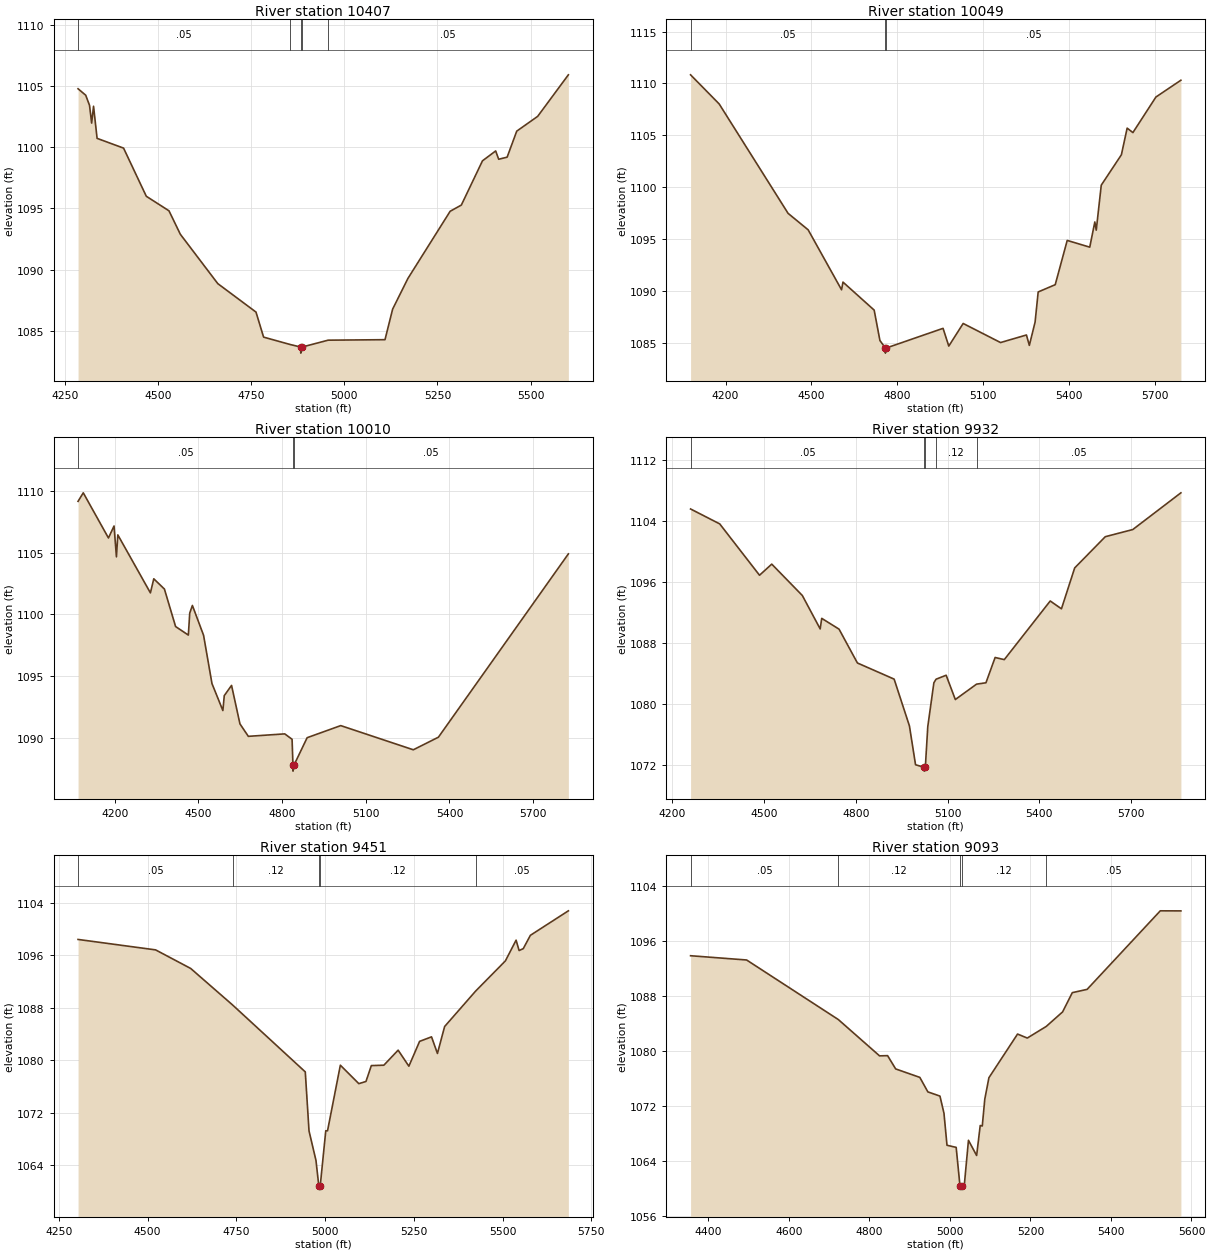
Type RM Length L Ch R = 1 ,10407   ,358,358,358
BEGIN DESCRIPTION:
Upper Denton 72 21.0
END DESCRIPTION:
XS GIS Cut Line= 3
      2217679.31      7281738.48      2216977.91      7281863.48
       2216388.6      7281995.21
#Sta/Elev= 30
  4285.3  1104.8  4305.9 1104.27  4316.1 1103.44  4321.8 1101.99  4326.9 1103.37
  4336.4 1100.74  4407.5 1099.94  4468.5    1096  4529.4 1094.81  4559.9 1092.89
  4660.4 1088.85    4763 1086.52  4783.4 1084.47  4855.5 1083.86  4882.9 1083.66
  4883.2 1083.16  4886.9 1083.66  4956.7 1084.22  5109.3 1084.26  5129.8 1086.76
  5170.8 1089.27  5284.2 1094.77  5314.3 1095.28    5371  1098.9  5406.5 1099.71
  5414.5 1099.03  5437.2  1099.2    5463 1101.33  5519.2 1102.54  5601.6 1105.94
#Mann= 5 ,-1 , 0
  4285.3     .05       0  4855.5    .075       0  4882.9    .033       0
  4886.9    .075       0  4956.7     .05       0
Bank Sta=4882.9,4886.9
XS Rating Curve= 0 ,0
Exp/Cntr=0.3,0.1

Type RM Length L Ch R = 1 ,10049   ,39,39,39
BEGIN DESCRIPTION:
Upper Denton 72 20.5
END DESCRIPTION:
XS GIS Cut Line= 3
       2217748.7      7281620.42      2216818.19      7281557.92
      2216042.23      7281634.13
#Sta/Elev= 30
  4077.9 1110.83  4177.8 1108.02  4418.4 1097.47  4488.5 1095.88  4605.1  1090.1
  4610.1 1090.84    4719 1088.14  4739.1 1085.21  4757.9 1084.49  4758.2 1083.99
  4761.9 1084.49  4959.6 1086.38  4979.6 1084.67  5029.8 1086.85  5160.4 1085.01
  5250.8 1085.74  5260.9 1084.74    5281 1086.98  5291.8 1089.89  5351.3 1090.59
  5393.2 1094.86  5471.9 1094.21  5489.6 1096.64  5494.6 1095.85  5512.1 1100.19
  5582.4 1103.12  5602.5 1105.69  5622.6 1105.26    5703 1108.69  5790.2 1110.31
#Mann= 3 ,-1 , 0
  4077.9     .05       0  4757.9    .033       0  4761.9     .05       0
Bank Sta=4757.9,4761.9
XS Rating Curve= 0 ,0
Exp/Cntr=0.3,0.1

Type RM Length L Ch R = 1 ,10010   ,78,78,78
BEGIN DESCRIPTION:
Upper Denton 72 20.4
END DESCRIPTION:
XS GIS Cut Line= 5
      2217757.64      7281556.08      2217046.75      7281500.09
       2216826.7      7281519.62      2216588.42      7281530.04
      2216003.19      7281522.24
#Sta/Elev= 30
  4068.5 1109.17  4087.2 1109.86  4177.5  1106.2  4197.5 1107.17  4206.1 1104.67
  4211.1 1106.45  4327.9 1101.75    4340 1102.89  4378.1 1102.06  4418.2 1099.02
  4463.9 1098.33  4468.9 1100.11  4478.4 1100.73  4518.5 1098.31  4548.6  1094.4
  4587.7 1092.21  4592.7 1093.42  4618.8 1094.25  4648.9 1091.13    4679 1090.12
  4809.5 1090.32  4835.8 1089.88  4838.9  1087.8  4839.1  1087.3  4842.9  1087.8
  4889.8 1090.01  5010.2 1090.99  5270.4 1089.03  5360.4 1090.05  5826.3 1104.91
#Mann= 3 ,-1 , 0
  4068.5     .05       0  4838.9    .033       0  4842.9     .05       0
Bank Sta=4838.9,4842.9
XS Rating Curve= 0 ,0
Exp/Cntr=0.3,0.1

Type RM Length L Ch R = 1 ,9932    ,481,481,481
BEGIN DESCRIPTION:
Upper Denton 72 20.0
END DESCRIPTION:
XS GIS Cut Line= 3
      2217554.27      7281467.64      2216803.26       7281445.4
      2215952.06      7281481.45
#Sta/Elev= 30
  4259.6 1105.58  4354.9 1103.62    4485 1096.88    4525 1098.34    4625 1094.22
  4683.4 1089.83  4688.4 1091.22  4745.1  1089.8  4805.1 1085.36  4925.2 1083.24
  4975.2  1077.1  4995.2    1072  5023.2 1071.66  5023.5 1071.16  5027.2 1071.66
  5035.2    1077  5055.2 1082.77  5062.4 1083.23  5095.3 1083.75  5125.3 1080.56
  5194.7 1082.58  5225.4 1082.76  5255.4 1086.08  5285.4  1085.8  5435.6  1093.5
  5472.3 1092.47  5515.6 1097.84  5615.7 1101.94  5705.6 1102.88  5862.9  1107.7
#Mann= 5 ,-1 , 0
  4259.6     .05       0  5023.2    .033       0  5027.2     .05       0
  5062.4     .12       0  5194.7     .05       0
Bank Sta=5023.2,5027.2
XS Rating Curve= 0 ,0
Exp/Cntr=0.3,0.1

Type RM Length L Ch R = 1 ,9451    ,358,358,358
BEGIN DESCRIPTION:
Upper Denton 72 19.0
END DESCRIPTION:
XS GIS Cut Line= 3
      2217276.53      7280995.42        2216579.        7281060.
      2215902.76      7281141.11
#Sta/Elev= 30
  4303.9  1098.4  4522.4 1096.81  4621.3 1093.98  4739.5 1088.41  4944.2 1078.22
  4954.7 1069.23  4974.3 1064.73  4982.3 1060.86  4982.6 1060.36  4986.3 1060.86
  5001.9 1069.25  5006.9 1069.25    5043 1079.24  5095.1 1076.43  5115.2 1076.76
  5130.3 1079.18  5165.6 1079.24  5205.8 1081.53  5236.1 1079.09  5266.3 1082.87
  5299.9 1083.56  5316.6 1081.03  5336.8 1085.13    5424 1090.52    5508 1095.13
  5538.2 1098.29  5546.7 1096.71  5558.4    1097  5578.5 1099.03  5685.5 1102.76
#Mann= 5 ,-1 , 0
  4303.9     .05       0  4739.5     .12       0  4982.3     .07       0
  4986.3     .12       0    5424     .05       0
Bank Sta=4982.3,4986.3
XS Rating Curve= 0 ,0
Exp/Cntr=0.3,0.1

Type RM Length L Ch R = 1 ,9093    ,366,366,366
BEGIN DESCRIPTION:
Upper Denton 72 18.0
END DESCRIPTION:
XS GIS Cut Line= 3
      2217068.23      7280766.26        2216429.        7280760.
      2215859.89      7280863.47
#Sta/Elev= 30
    4356  1093.9  4495.2 1093.28  4722.9 1084.62  4825.3 1079.34  4845.3 1079.37
  4865.3 1077.44  4925.3 1076.21  4945.3  1074.1  4975.3 1073.49  4985.3 1070.99
  4992.8 1066.34  5015.6 1066.03    5025 1060.46  5025.3 1059.96    5029 1060.46
  5035.9 1060.61  5046.1 1067.06  5066.4 1064.85  5075.3 1069.21  5080.4 1069.14
  5086.7 1073.06  5096.9 1076.16    5168 1082.51  5192.2 1081.93  5239.3 1083.62
  5279.9 1085.73    5304 1088.53  5340.8 1089.01  5522.5 1100.43  5573.7 1100.42
#Mann= 5 ,-1 , 0
    4356     .05       0  4722.9     .12       0    5025     .07       0
    5029     .12       0  5239.3     .05       0
Bank Sta=5025,5029
XS Rating Curve= 0 ,0
Exp/Cntr=0.3,0.1

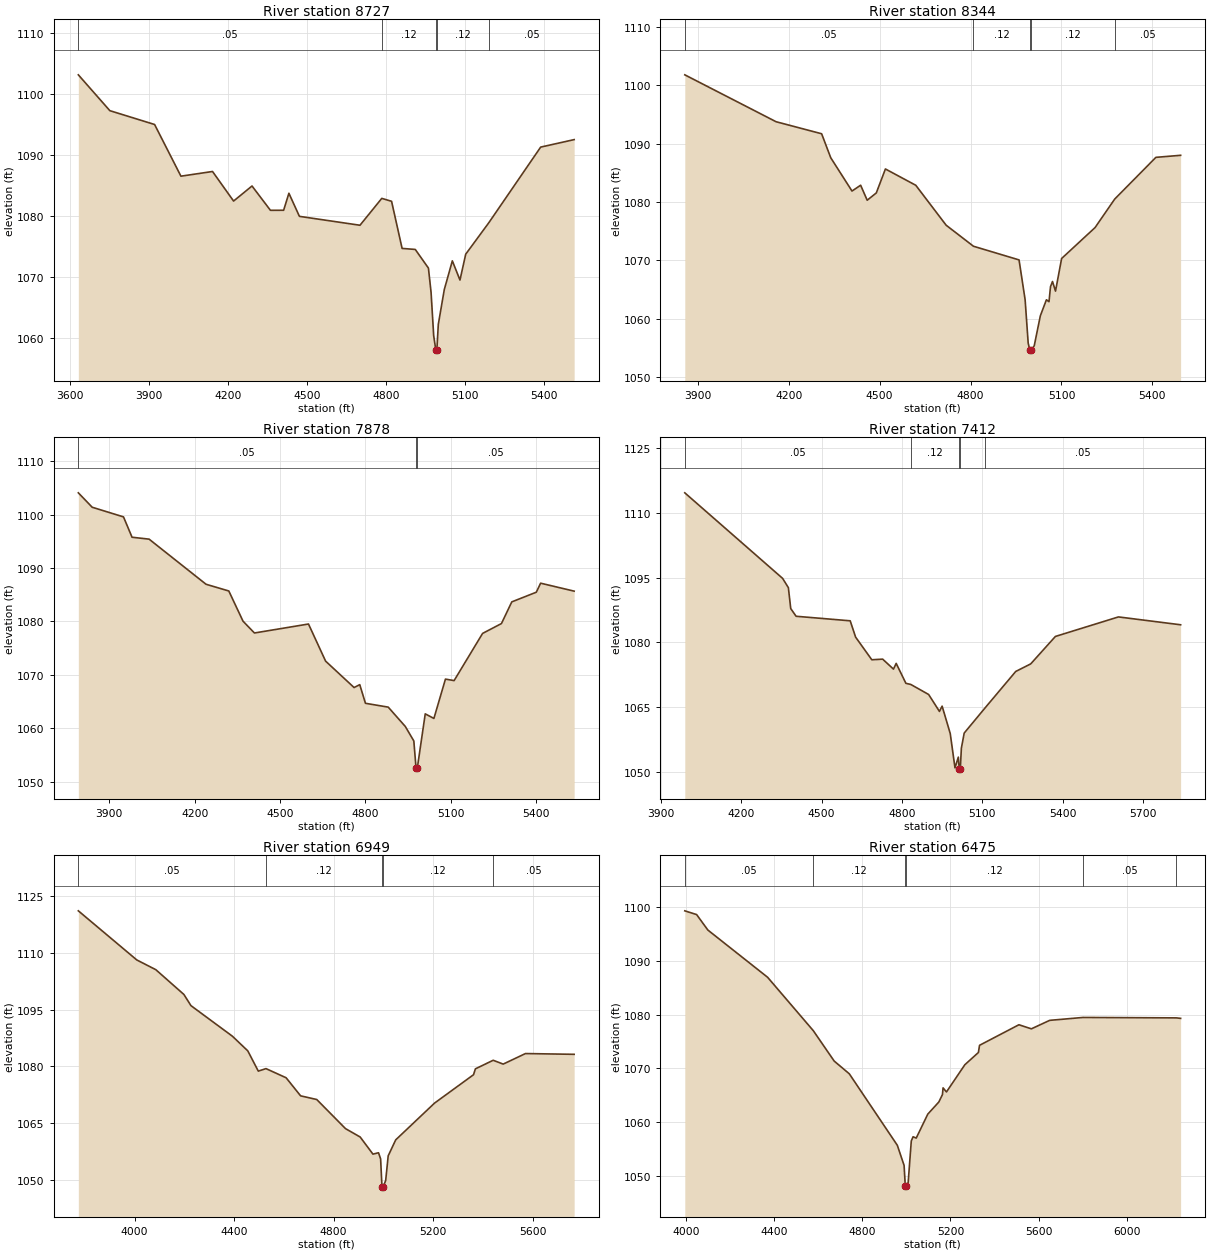
Type RM Length L Ch R = 1 ,8727    ,383,383,383
BEGIN DESCRIPTION:
Upper Denton 72 17.0
END DESCRIPTION:
XS GIS Cut Line= 3
       2217748.7      7280425.98        2216379.        7280410.
      2215873.86      7280502.35
#Sta/Elev= 30
  3630.3 1103.12    3750 1097.24    3920 1094.97    4020 1086.49    4140 1087.26
    4220 1082.41    4290 1084.88    4360 1080.89  4410.1  1080.9  4430.1 1083.69
  4470.1  1079.9  4700.1 1078.44  4782.9 1082.85  4820.1 1082.37  4860.1 1074.64
  4910.1 1074.47  4960.1 1071.41  4970.1 1067.44  4980.1 1060.31  4988.1 1057.96
  4988.3 1057.46  4992.1 1057.96  4997.6 1062.18  5020.4  1067.9  5050.9  1072.6
  5079.9 1069.45  5101.7 1073.69  5189.4 1078.85  5386.4 1091.26  5513.6 1092.49
#Mann= 5 ,-1 , 0
  3630.3     .05       0  4782.9     .12       0  4988.1     .07       0
  4992.1     .12       0  5189.4     .05       0
Bank Sta=4988.1,4992.1
XS Rating Curve= 0 ,0
Exp/Cntr=0.3,0.1

Type RM Length L Ch R = 1 ,8344    ,466,466,466
BEGIN DESCRIPTION:
Upper Denton 72 16.0
END DESCRIPTION:
XS GIS Cut Line= 3
      2217519.54      7279988.48        2216379.        7280060.
      2215887.67      7280099.59
#Sta/Elev= 30
  3857.3 1101.78  4158.4 1093.75  4308.7 1091.69  4338.8 1087.58  4408.9 1081.88
  4437.4 1082.88    4459 1080.31  4489.1 1081.56  4519.1 1085.66  4619.3 1082.87
  4719.5 1076.03  4809.6 1072.43    4960 1070.09    4980 1063.28  4990.1 1055.86
  4995.6 1054.63  4995.8 1054.13  4999.6 1054.63  5010.1 1055.39  5030.2 1060.52
  5050.2 1063.26  5058.8 1062.94  5063.8 1065.52  5070.3 1066.39  5080.3 1064.75
  5100.4 1070.33  5210.8 1075.63  5275.6 1080.51  5411.4 1087.65    5493    1088
#Mann= 5 ,-1 , 0
  3857.3     .05       0  4809.6     .12       0  4995.6     .07       0
  4999.6     .12       0  5275.6     .05       0
Bank Sta=4995.6,4999.6
XS Rating Curve= 0 ,0
Exp/Cntr=0.3,0.1

Type RM Length L Ch R = 1 ,7878    ,466,466,466
BEGIN DESCRIPTION:
Upper Denton 72 15.0
END DESCRIPTION:
XS GIS Cut Line= 3
      2217637.66      7279627.37        2216429.        7279610.
      2215902.77      7279696.61
#Sta/Elev= 30
  3791.3 1104.09    3840 1101.39    3950 1099.58    3980 1095.77    4040 1095.41
    4240 1086.96    4320  1085.7    4370 1080.04    4410 1077.83    4600 1079.51
  4660.1 1072.56  4760.1 1067.61  4780.1 1068.15  4800.1 1064.66  4880.1 1063.94
  4940.1 1060.32  4970.1  1057.6    4978 1052.45  4978.3 1051.95  4982.1 1052.45
  5010.2 1062.68  5040.6 1061.82  5081.2 1069.19  5111.6 1068.91  5211.7 1077.75
    5278  1079.6  5314.3 1083.66  5400.4 1085.47  5415.6 1087.16  5533.4 1085.67
#Mann= 3 ,-1 , 0
  3791.3     .05       0    4978    .033       0  4982.1     .05       0
Bank Sta=4978,4982.1
XS Rating Curve= 0 ,0
Exp/Cntr=0.3,0.1

Type RM Length L Ch R = 1 ,7412    ,463,463,463
BEGIN DESCRIPTION:
Upper Denton 72 14.0
END DESCRIPTION:
XS GIS Cut Line= 4
      2217380.71       7279023.2        2216379.        7279160.
      2216013.96      7279292.45      2215811.68      7279695.94
#Sta/Elev= 30
  3989.1 1114.61  4354.2 1094.81  4375.7 1092.66  4384.5 1087.82  4404.6 1086.04
  4606.5 1084.99  4626.7 1081.21  4687.2 1075.97  4727.6 1076.12    4768 1073.81
  4778.1 1075.14  4814.4 1070.52  4832.7 1070.26  4899.2 1067.94  4939.6 1064.02
  4949.6 1065.24  4979.9  1058.9  4997.6 1050.96  5010.1 1053.44  5013.4  1050.7
  5013.7  1050.2  5017.5  1050.7  5021.4  1055.5    5032 1059.01  5111.2 1064.93
  5224.4 1073.27  5280.3 1075.02  5372.4 1081.37  5607.7 1085.89  5839.8 1084.07
#Mann= 5 ,-1 , 0
  3989.1     .05       0  4832.7     .12       0  5013.4     .07       0
  5017.5     .12       0  5111.2     .05       0
Bank Sta=5013.4,5017.5
XS Rating Curve= 0 ,0
Exp/Cntr=0.3,0.1

Type RM Length L Ch R = 1 ,6949    ,474,474,474
BEGIN DESCRIPTION:
Upper Denton 72 13.0
END DESCRIPTION:
XS GIS Cut Line= 4
      2217422.34      7278481.54        2216229.        7278760.
      2216068.19      7278780.15      2215797.34      7279321.84
#Sta/Elev= 30
  3774.2 1121.04  4009.1 1108.09  4085.7 1105.52  4198.6 1098.98  4226.9 1096.04
  4393.8 1087.96  4455.4 1084.11  4497.6 1078.77  4528.5 1079.43  4609.4 1077.02
  4667.7 1072.25  4732.6 1071.28  4848.1 1063.61  4907.2 1061.39  4958.5 1056.88
  4980.9 1057.24  4989.3 1055.63  4994.9 1048.15  4995.3 1047.65  4999.1 1048.15
  5009.7 1049.94  5019.8 1056.43    5050 1060.64  5206.2 1070.34  5362.8 1077.82
  5370.3 1079.37  5441.8 1081.63  5482.1 1080.62  5571.6  1083.4  5767.3  1083.2
#Mann= 5 ,-1 , 0
  3774.2     .05       0  4528.5     .12       0  4994.9     .07       0
  4999.1     .12       0  5441.8     .05       0
Bank Sta=4994.9,4999.1
XS Rating Curve= 0 ,0
Exp/Cntr=0.3,0.1

Type RM Length L Ch R = 1 ,6475    ,582,582,582
BEGIN DESCRIPTION:
Upper Denton 72 12.0
END DESCRIPTION:
XS GIS Cut Line= 4
      2217061.28      7278144.55        2216079.        7278360.
       2215929.3      7278436.22      2215630.68      7279470.98
#Sta/Elev= 30
    3994 1099.33  4047.7 1098.63  4098.7 1095.75  4369.8 1086.95  4577.4 1076.99
    4672 1071.34  4740.7 1068.96  4958.7 1055.64  4989.4 1051.89    4995 1047.97
  4995.3 1047.47  4999.2 1047.97  5007.9 1048.71  5022.1 1056.45  5030.2 1057.23
  5044.5 1056.98  5096.9 1061.44    5147  1063.7  5163.6  1065.1  5166.3 1066.34
  5181.7 1065.58  5265.2 1070.65  5326.7 1072.93  5331.9 1074.27  5510.6  1078.1
  5567.1 1077.34  5650.3 1078.92  5801.1 1079.46  6225.5 1079.38  6244.6 1079.29
#Mann= 6 ,-1 , 0
    3994     .05       0  4577.4     .12       0    4995     .07       0
  4999.2     .12       0  5801.1     .05       0  6225.5     .12       0
Bank Sta=4995,4999.2
XS Rating Curve= 0 ,0
Exp/Cntr=0.3,0.1

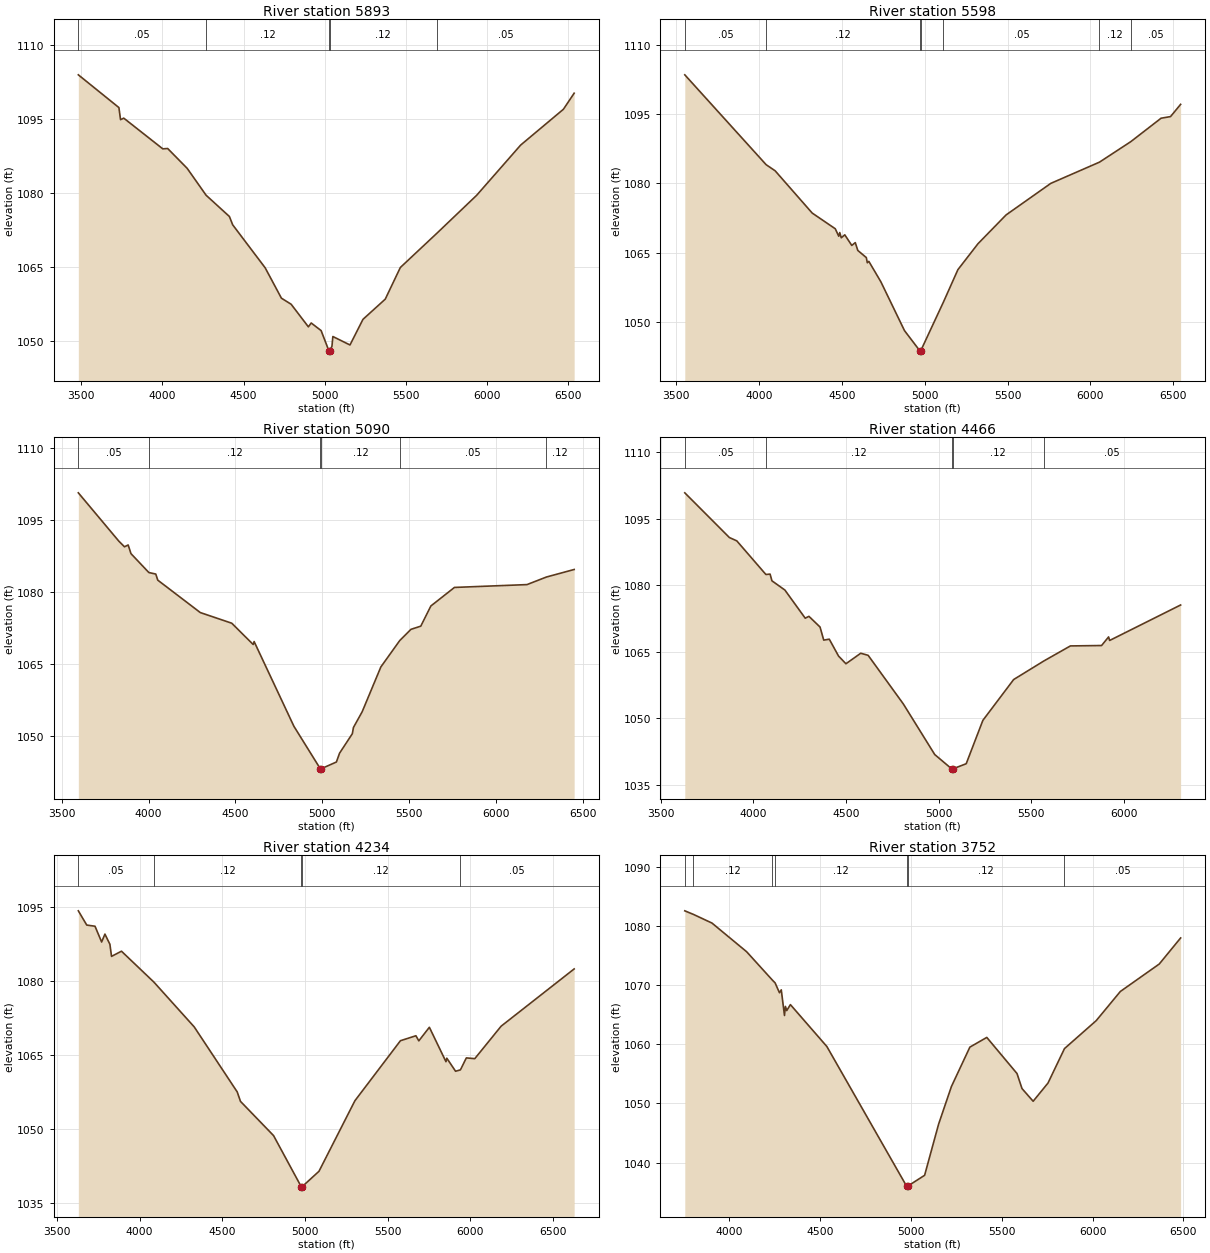
Type RM Length L Ch R = 1 ,5893    ,295,295,295
BEGIN DESCRIPTION:
Upper Denton 72 11.0
END DESCRIPTION:
XS GIS Cut Line= 4
      2217248.77       7277901.5      2215832.08      7277929.28
      2215533.47      7278082.06      2214513.32      7278887.07
#Sta/Elev= 30
  3483.2 1103.92    3733 1097.29    3743 1094.85    3763 1095.15  4003.1 1088.94
  4033.1 1089.01  4153.1    1085  4269.7 1079.55  4413.1 1075.25  4433.2 1073.57
  4633.2 1064.87  4733.2 1058.72  4793.2 1057.49  4899.2 1052.92  4916.6  1053.7
  4977.6 1052.16  5025.1  1048.1  5025.8  1047.6  5030.2  1048.1  5044.2 1048.96
  5049.9 1050.96  5155.3 1049.25  5235.3 1054.44  5372.3 1058.52  5465.3 1064.93
  5689.6 1071.84    5935 1079.54    6206 1089.71  6468.9 1096.95  6535.1  1100.2
#Mann= 5 ,-1 , 0
  3483.2     .05       0  4269.7     .12       0  5025.1     .07       0
  5030.2     .12       0  5689.6     .05       0
Bank Sta=5025.1,5030.2
XS Rating Curve= 0 ,0
Exp/Cntr=0.3,0.1

Type RM Length L Ch R = 1 ,5598    ,508,508,508
BEGIN DESCRIPTION:
Upper Denton 72 10.0
END DESCRIPTION:
XS GIS Cut Line= 3
      2216804.26      7276970.97        2215579.        7277760.
      2214415.41      7278762.61
#Sta/Elev= 30
  3551.2 1103.48  4042.2 1084.03  4096.5 1082.71  4320.3 1073.56  4459.6 1070.16
  4480.7 1068.54  4486.6 1069.34  4495.9  1068.2    4517 1068.85  4559.3 1066.55
  4580.4 1067.16  4595.6 1065.47  4647.1 1063.92    4653  1062.8  4662.3  1063.1
  4734.9 1058.68  4877.7  1048.1  4970.3 1043.74    4971 1043.24  4975.5 1043.74
  5112.4 1054.28    5200 1061.31  5320.7  1066.9  5490.7 1073.15  5760.6 1079.98
  6054.7 1084.58  6243.9 1089.02  6426.6 1094.09  6483.6 1094.44  6544.5 1097.09
#Mann= 7 ,-1 , 0
  3551.2     .05       0  4042.2     .12       0  4970.3     .07       0
  4975.5     .12       0  5112.4     .05       0  6054.7     .12       0
  6243.9     .05       0
Bank Sta=4970.3,4975.5
XS Rating Curve= 0 ,0
Exp/Cntr=0.3,0.1

Type RM Length L Ch R = 1 ,5090    ,624,624,624
BEGIN DESCRIPTION:
Upper Denton 72 9.0
END DESCRIPTION:
XS GIS Cut Line= 4
      2216758.33      7276911.56      2215591.63      7277335.18
      2215327.74      7277342.12      2214557.37      7278445.62
#Sta/Elev= 30
  3596.5  1100.6  3829.8 1090.51  3861.8 1089.35    3883 1089.73  3899.3 1087.92
  4002.2 1083.98  4041.7 1083.67  4053.3  1082.4  4297.9 1075.64  4478.8 1073.42
    4602 1068.98  4607.3  1069.6  4836.2 1051.93  4987.8 1043.09  4988.5 1042.59
    4993 1043.09  5080.4 1044.49  5098.6 1046.33  5172.2  1050.4  5178.3 1051.68
  5228.8 1054.98  5336.1 1064.31  5444.5  1069.8  5508.9 1072.14  5565.6 1072.81
  5623.5 1077.01  5759.2 1080.88  6176.2 1081.47  6288.2 1083.05  6447.5 1084.62
#Mann= 6 ,-1 , 0
  3596.5     .05       0  4002.2     .12       0  4987.8     .07       0
    4993     .12       0  5444.5     .05       0  6288.2     .12       0
Bank Sta=4987.8,4993
XS Rating Curve= 0 ,0
Exp/Cntr=0.3,0.1

Type RM Length L Ch R = 1 ,4466    ,232,232,232
BEGIN DESCRIPTION:
Upper Denton 72 8.0
END DESCRIPTION:
XS GIS Cut Line= 4
      2216799.96      7276856.01       2215431.9      7276842.12
      2215021.72       7276857.4       2214232.3      7277292.53
#Sta/Elev= 30
  3628.7 1100.83  3869.7 1090.75  3909.7    1090    4067 1082.42  4089.7  1082.5
  4099.7 1080.99  4169.7 1078.91  4279.7 1072.56  4299.7 1072.98  4359.7 1070.57
  4379.7 1067.62  4409.7 1067.83  4459.7 1064.03  4499.7 1062.29  4579.7 1064.66
  4619.7 1064.19  4809.7 1053.24  4979.7 1041.82  5071.6 1038.58  5072.5 1038.08
  5077.2 1038.58  5149.8 1039.75  5239.9 1049.53  5406.2 1058.73    5570 1062.93
    5713 1066.31  5881.5  1066.4  5919.4 1068.34  5925.1 1067.54  6308.7 1075.54
#Mann= 5 ,-1 , 0
  3628.7     .05       0    4067     .12       0  5071.6     .07       0
  5077.2     .12       0    5570     .05       0
Bank Sta=5071.6,5077.2
XS Rating Curve= 0 ,0
Exp/Cntr=0.3,0.1

Type RM Length L Ch R = 1 ,4234    ,482,482,482
BEGIN DESCRIPTION:
Upper Denton 72 7.0
END DESCRIPTION:
XS GIS Cut Line= 3
      2216799.92      7276606.01        2215429.        7276610.
       2213827.7      7276904.63
#Sta/Elev= 30
    3629 1094.26  3679.9 1091.37  3729.9 1091.13  3769.9 1087.93  3789.9 1089.53
  3819.9 1087.47  3829.9 1085.01  3889.9 1086.06  4086.2 1079.78  4329.9 1070.69
  4589.9 1057.49  4609.9 1055.56  4809.9 1048.61  4977.1 1038.24    4978 1037.74
  4982.8 1038.24  5084.6 1041.36  5301.9 1055.69  5577.3 1067.88    5671 1068.89
  5688.5 1067.85  5752.3 1070.61  5852.7 1063.62  5857.8 1064.33  5910.8 1061.68
  5940.2 1061.96    5976 1064.39  6027.1 1064.24  6186.3 1070.83  6628.1 1082.46
#Mann= 5 ,-1 , 0
    3629     .05       0  4086.2     .12       0  4977.1     .07       0
  4982.8     .12       0  5940.2     .05       0
Bank Sta=4977.1,4982.8
XS Rating Curve= 0 ,0
Exp/Cntr=0.3,0.1

Type RM Length L Ch R = 1 ,3752    ,485,485,485
BEGIN DESCRIPTION:
Upper Denton 72 6.0
END DESCRIPTION:
XS GIS Cut Line= 3
      2216668.05      7276258.79        2215429.        7276160.
      2213973.82      7276453.18
#Sta/Elev= 30
    3757  1082.6  3804.8 1081.99  3906.5 1080.53  4097.1 1075.68    4239 1070.87
  4253.5 1070.42  4277.7 1068.74  4287.7 1069.23  4305.4 1064.89  4310.4 1066.43
  4317.8 1065.72  4337.9 1066.73  4538.5 1059.64  4977.1 1036.01    4978 1035.51
  4982.8 1036.01  5076.2 1037.85    5153 1046.49  5223.6 1052.87  5325.2 1059.54
  5418.2 1061.18  5584.4 1055.07    5612 1052.52  5673.2 1050.38  5754.9 1053.46
  5845.6 1059.29  6020.1 1064.02  6152.7 1068.95  6366.9  1073.6  6484.4 1078.01
#Mann= 7 ,-1 , 0
    3757     .05       0  3804.8     .12       0    4239     .05       0
  4253.5     .12       0  4977.1     .07       0  4982.8     .12       0
  5845.6     .05       0
Bank Sta=4977.1,4982.8
XS Rating Curve= 0 ,0
Exp/Cntr=0.3,0.1

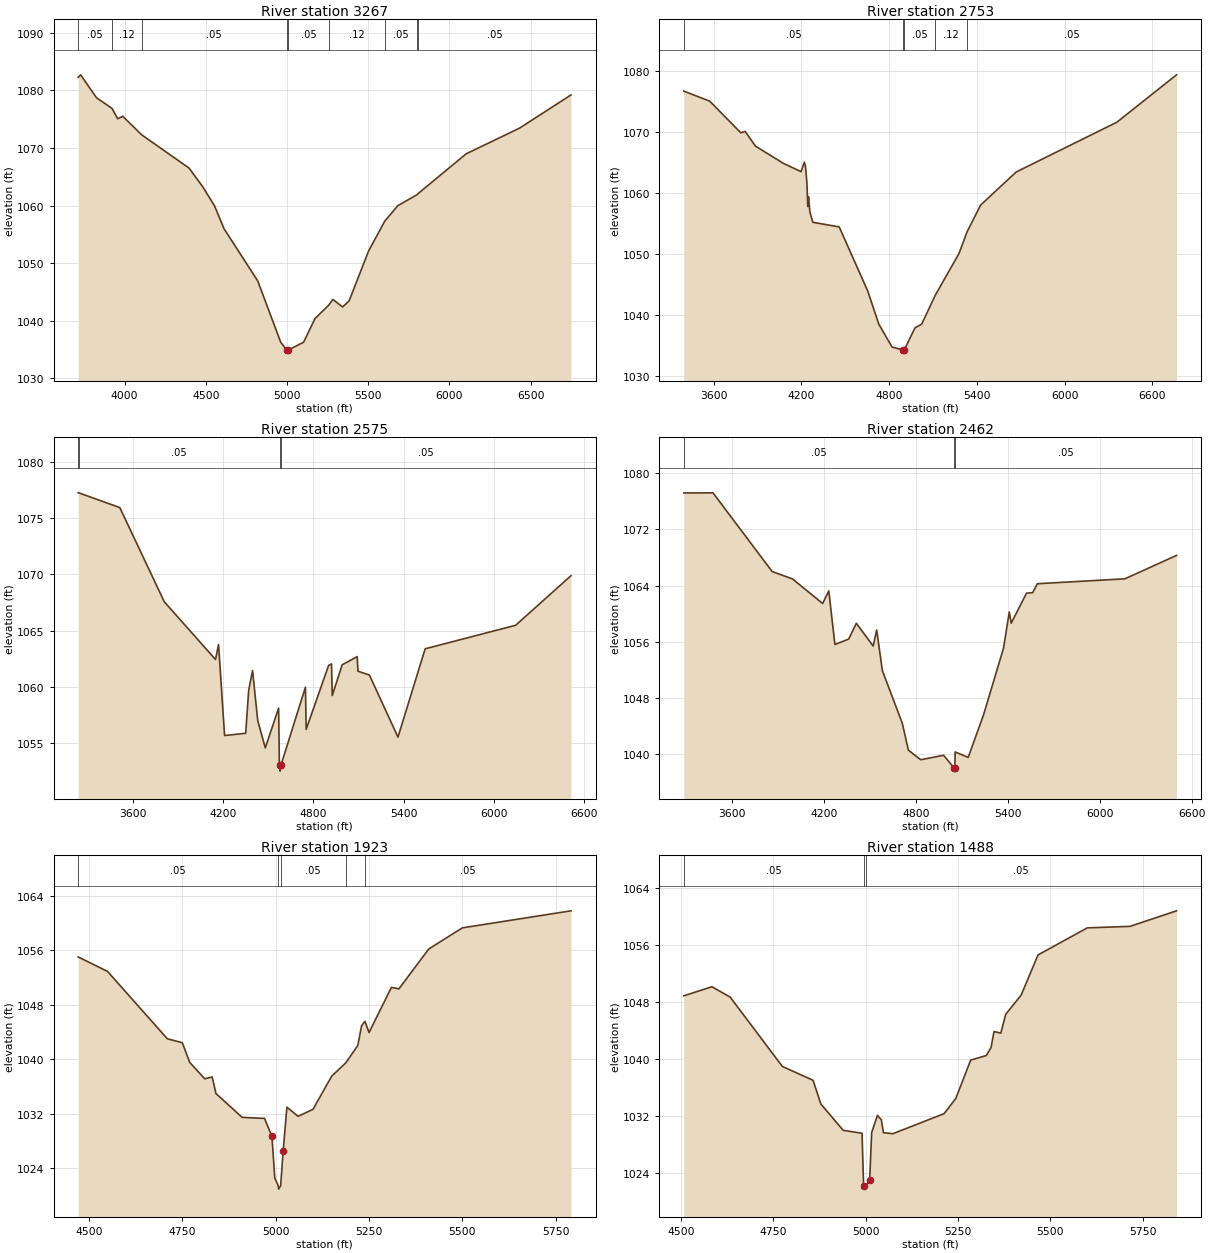
Type RM Length L Ch R = 1 ,3267    ,514,514,514
BEGIN DESCRIPTION:
Upper Denton 72 5.0
END DESCRIPTION:
XS GIS Cut Line= 3
      2216681.88      7276078.23        2215479.        7275710.
      2213703.39      7275682.41
#Sta/Elev= 30
  3714.6 1082.26  3729.5 1082.71  3827.8 1078.72  3922.6 1076.89  3958.1 1075.08
  3989.5  1075.5  4105.2  1072.3  4397.4 1066.51  4481.7 1063.26  4554.3 1059.94
  4612.8 1055.97  4819.9 1046.93  4962.1 1036.23  4999.7 1034.88  5000.6 1034.38
  5005.5 1034.88  5102.6 1036.28  5172.6 1040.38  5257.9 1042.74  5282.6  1043.7
  5342.6  1042.4  5382.6 1043.45  5502.6 1052.11  5602.1  1057.3  5682.7 1059.99
  5799.1 1061.86  5807.2 1062.08  6102.7 1068.98  6432.8 1073.47  6748.4 1079.21
#Mann= 9 ,-1 , 0
  3714.6     .05       0  3922.6     .12       0  4105.2     .05       0
  4999.7    .033       0  5005.5     .05       0  5257.9     .12       0
  5602.1     .05       0  5799.1     .12       0  5807.2     .05       0
Bank Sta=4999.7,5005.5
XS Rating Curve= 0 ,0
Exp/Cntr=0.3,0.1

Type RM Length L Ch R = 1 ,2753    ,178,178,178
BEGIN DESCRIPTION:
Upper Denton 72 4.0
END DESCRIPTION:
XS GIS Cut Line= 4
      2216876.32      7275293.51       2216056.9      7275203.24
      2215299.96      7275258.79      2213536.05      7275536.57
#Sta/Elev= 30
  3395.5 1076.68  3573.9 1075.02  3785.2 1069.85  3815.3 1070.07  3885.8 1067.67
  4076.9 1064.84  4197.6 1063.49  4219.9 1065.04  4227.8 1064.33  4237.8 1061.55
  4243.4 1057.77  4248.4 1059.39  4257.9 1056.89  4277.9  1055.2  4458.4 1054.44
  4653.8 1043.92  4729.1 1038.52  4819.4 1034.78  4896.4 1034.28  4897.5 1033.78
  4902.7 1034.28  4976.8 1037.93  5022.1 1038.51  5114.5 1043.23  5277.2 1050.08
  5331.8  1053.6  5425.2 1058.02  5668.2 1063.43  6356.6 1071.58  6764.5 1079.34
#Mann= 5 ,-1 , 0
  3395.5     .05       0  4896.4    .033       0  4902.7     .05       0
  5114.5     .12       0  5331.8     .05       0
Bank Sta=4896.4,4902.7
XS Rating Curve= 0 ,0
Exp/Cntr=0.3,0.1

Type RM Length L Ch R = 1 ,2575    ,113,113,113
BEGIN DESCRIPTION:
Upper Denton 72 3.5
END DESCRIPTION:
XS GIS Cut Line= 4
      2216973.57      7275272.68      2216098.57      7275050.46
       2215244.4      7275099.07      2213732.22      7275189.24
#Sta/Elev= 30
  3238.4 1077.23  3242.1 1077.23  3514.9 1075.92  3810.6 1067.55  4150.8 1062.43
  4170.8 1063.76  4210.9 1055.68  4351.1 1055.88  4371.1 1059.71  4396.6 1061.45
  4431.2    1057  4481.3 1054.58  4569.8 1058.12  4574.8 1053.08  4578.2 1053.02
  4579.3 1052.52  4584.7 1053.02  4747.9 1059.97  4752.9 1056.23    4902 1061.91
  4921.1 1062.04  4926.1 1059.23  4991.9 1061.96  5091.8 1062.69  5096.8 1061.39
  5172.4 1061.06  5362.8 1055.54  5543.1 1063.38  6144.2 1065.47  6511.6 1069.87
#Mann= 4 ,-1 , 0
  3238.4     .12       0  3242.1     .05       0  4578.2    .033       0
  4584.7     .05       0
Bank Sta=4578.2,4584.7
XS Rating Curve= 0 ,0
Exp/Cntr=0.3,0.1

Type RM Length L Ch R = 1 ,2462    ,539,539,539
BEGIN DESCRIPTION:
Upper Denton 72 3.0
END DESCRIPTION:
XS GIS Cut Line= 4
      2216952.74      7275231.02      2216098.51      7274989.68
      2215251.35      7275001.85      2213773.13      7275126.77
#Sta/Elev= 30
    3283 1077.19  3473.9 1077.21  3860.2 1066.02  3993.5 1064.96  4190.2 1061.47
  4230.2 1063.26  4270.2 1055.64  4360.2 1056.41  4410.2 1058.65  4520.2 1055.42
  4543.1  1057.7  4580.2 1051.92  4710.2 1044.45  4750.2 1040.61  4830.2 1039.25
  4980.3 1039.88  5047.1 1038.13  5048.2 1037.63  5053.6 1038.13  5055.4 1040.36
  5140.7 1039.58  5241.1 1045.64  5371.5 1055.12  5409.1 1060.27  5421.7 1058.67
  5522.1 1062.95  5562.2 1063.01  5592.3 1064.28  6164.3 1064.98  6501.4 1068.31
#Mann= 3 ,-1 , 0
    3283     .05       0  5047.1    .033       0  5053.6     .05       0
Bank Sta=5047.1,5053.6
XS Rating Curve= 0 ,0
Exp/Cntr=0.3,0.1

Type RM Length L Ch R = 1 ,1923    ,435,435,435
BEGIN DESCRIPTION:
Upper Denton 72 2.0
END DESCRIPTION:
XS GIS Cut Line= 3
      2215857.63      7274533.27        2215329.        7274510.
      2214538.16      7274515.91
#Sta/Elev= 30
  4470.9 1054.99  4549.6 1052.86  4709.8 1042.97  4749.8  1042.4  4769.8  1039.5
  4809.9  1037.1  4829.9 1037.37  4839.9 1034.94    4910 1031.44    4970 1031.28
    4990 1028.64  4997.5 1022.54  5006.8  1021.4  5007.8  1020.9  5013.3  1021.4
    5020 1026.49    5030 1032.93    5060 1031.59    5100 1032.62    5150 1037.48
    5188 1039.45    5220    1042    5230 1044.88  5239.2 1045.54    5250 1043.89
    5310 1050.52    5330  1050.3  5410.1 1056.16  5500.1 1059.26  5790.9 1061.76
#Mann= 5 ,-1 , 0
  4470.9     .05       0  5006.8    .033       0  5013.3     .05       0
    5188     .12       0  5239.2     .05       0
Bank Sta=4990,5020
XS Rating Curve= 0 ,0
Exp/Cntr=0.3,0.1

Type RM Length L Ch R = 1 ,1488    ,762,762,762
BEGIN DESCRIPTION:
Upper Denton 72 1.0
END DESCRIPTION:
XS GIS Cut Line= 4
       2215835.9      7274350.99      2215634.45      7274151.52
        2215429.        7274110.      2214629.34      7274372.67
#Sta/Elev= 30
  4507.3 1048.89  4583.6 1050.17  4633.1 1048.71  4774.5 1038.98  4857.6 1037.04
  4878.6 1033.72  4939.2 1030.02  4990.2 1029.61  4994.5 1022.27  4995.6 1021.77
  5001.1 1022.27  5010.9    1023  5016.3 1029.71    5032 1032.12  5042.5 1031.49
  5048.1 1029.69  5074.1 1029.55  5212.4 1032.36  5244.2 1034.49  5284.6 1039.88
  5326.7 1040.51  5339.7 1041.63  5347.7 1043.88  5366.2 1043.66  5379.3 1046.29
  5421.4 1049.01  5466.9 1054.63  5600.4 1058.43  5716.1 1058.64  5842.1 1060.82
#Mann= 3 ,-1 , 0
  4507.3     .05       0  4994.5    .033       0  5001.1     .05       0
Bank Sta=4994.5,5010.9
XS Rating Curve= 0 ,0
Exp/Cntr=0.3,0.1

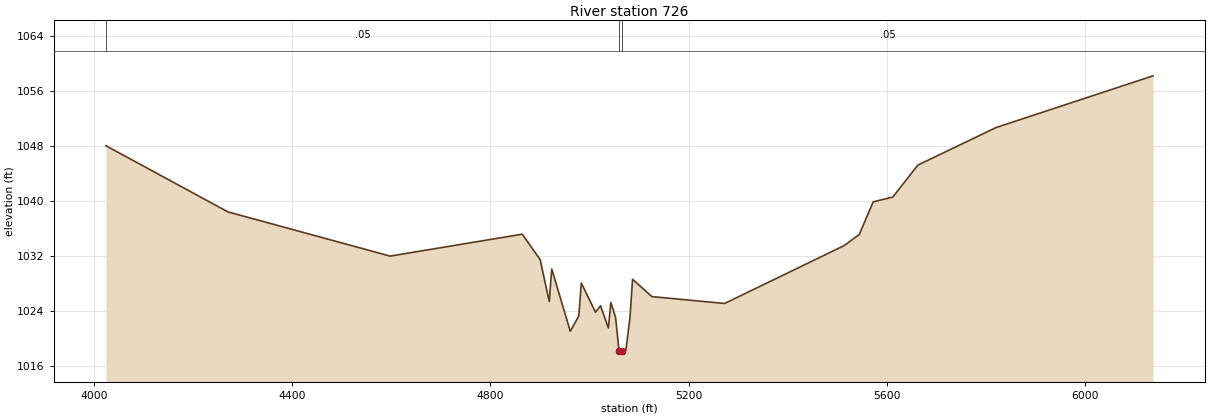
Type RM Length L Ch R = 1 ,726     ,0,0,0
BEGIN DESCRIPTION:
Upper Denton 72 0.5
END DESCRIPTION:
XS GIS Cut Line= 5
      2215770.99      7274211.03      2215614.74      7273468.85
      2215333.51       7273419.9      2215074.19      7273505.08
      2214724.97      7274219.75
#Sta/Elev= 30
  4024.2 1048.05  4270.5 1038.42  4597.5 1031.99    4864 1035.18  4900.1  1031.5
  4918.5 1025.39  4923.6 1030.11    4961 1021.05  4978.1 1023.29  4983.2 1028.08
  5011.8 1023.83  5021.9 1024.77  5037.8 1021.54  5042.8 1025.23  5052.4 1023.04
  5059.2 1018.23  5060.3 1017.73  5065.8 1018.23  5073.1 1018.29  5081.3    1023
  5086.6 1028.62  5125.5  1026.1  5272.2  1025.1  5513.5 1033.52  5543.9 1035.14
    5572 1039.89  5611.5 1040.58  5662.1 1045.23  5819.7 1050.69  6136.5 1058.22
#Mann= 3 ,-1 , 0
  4024.2     .05       0  5059.2    .033       0  5065.8     .05       0
Bank Sta=5059.2,5065.8
XS Rating Curve= 0 ,0
Exp/Cntr=0.3,0.1

Chan Stop Cuts=-1
Use User Specified Reach Order=0
Composite Channel Slope=5