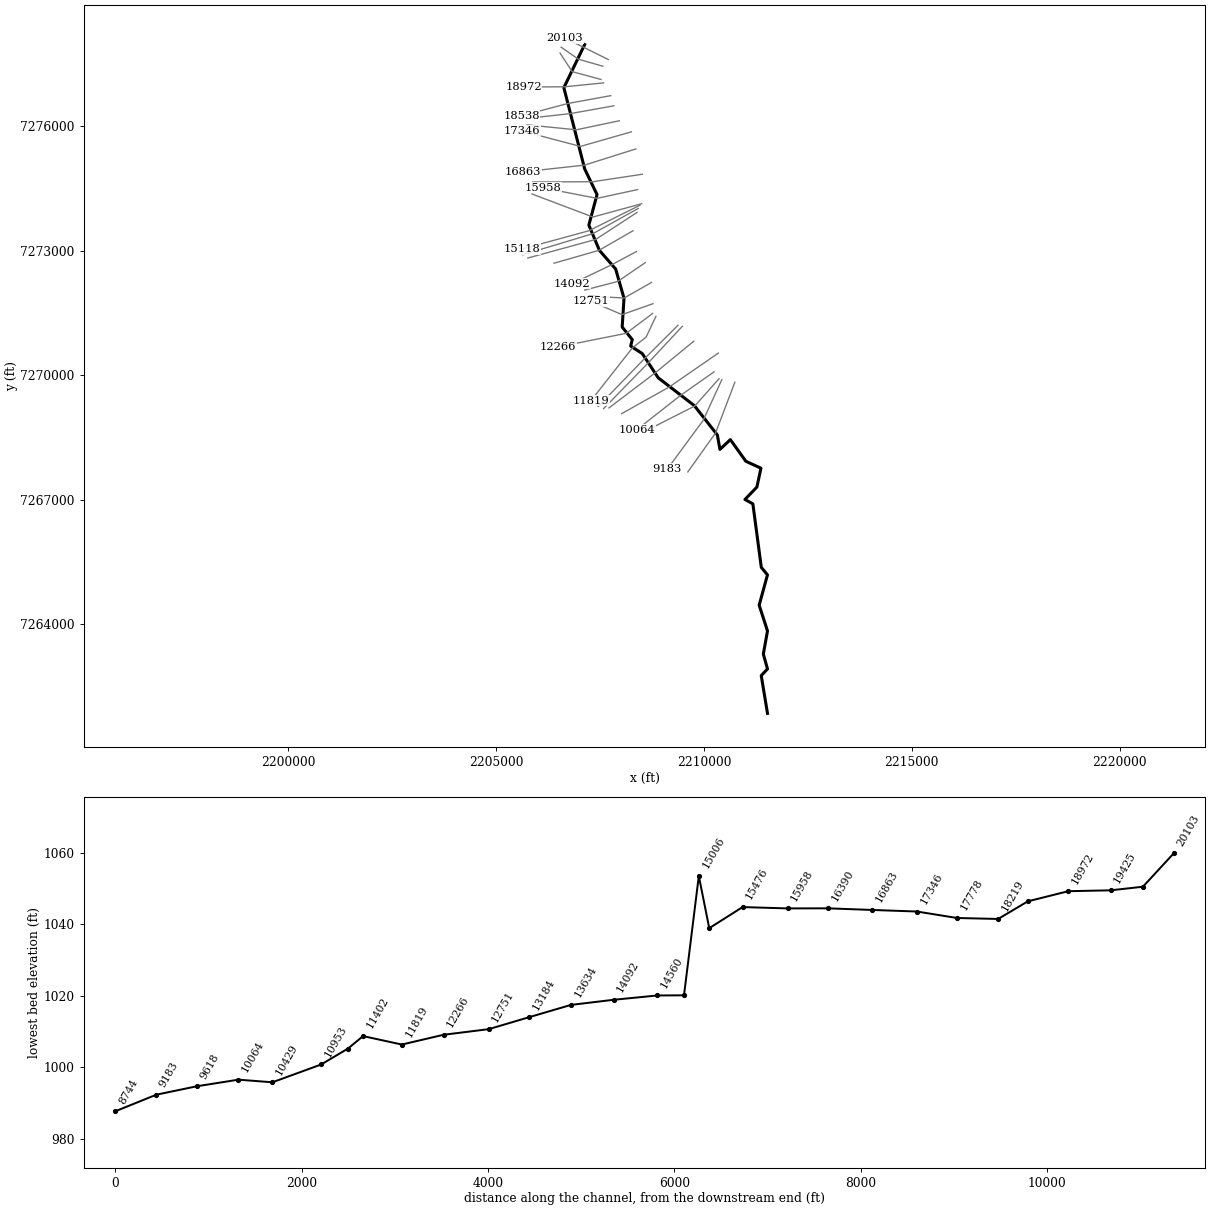
--- Upper Denton 73.prj (project) ---

Proj Title=Upper Denton 73 Base Level Engineering
Current Plan=p01
Default Exp/Contr=0.3,0.1
English Units
Geom File=g01
Flow File=f01
Plan File=p01
Y Axis Title=Elevation
X Axis Title(PF)=Main Channel Distance
X Axis Title(XS)=Station
BEGIN DESCRIPTION:
Upper Denton 73
END DESCRIPTION:
DSS Export Rating Curves= 0
DSS Export Rating Curve Sorted= 0
DSS Export Volume Flow Curves= 0
DXF OffsetX= 0
DXF OffsetY= 0
DXF ScaleX= 1
DXF ScaleY= 10

--- Upper Denton 73.p01 (plan) ---

Plan Title=Multiple Run
Short Identifier=Multiple
Geom File=g01
Flow File=f01
Subcritical Flow
K Sum by GR= 0
Std Step Tol= 0.01
Critical Tol= 0.01
Num of Std Step Trials= 20
Max Error Tol= 0.3
Flow Tol Ratio= 0.001
Split Flow NTrial= 30
Split Flow Tol= 0.02
Split Flow Ratio= 0.02
Log Output Level= 0
Friction Slope Method= 1
Unsteady Friction Slope Method= 2
Unsteady Bridges Friction Slope Method= 1
Parabolic Critical Depth
Global Vel Dist=  1 , 1 , 1
Global Log Level= 0
CheckData=True
Encroach Param= -1, 0, 0, 0
BEGIN DESCRIPTION:
Multiple Run
END DESCRIPTION:

--- Upper Denton 73.f01 (steady flow) ---

Flow Title=Multiple
Program Version=4.10
Number of Profiles= 7
Profile Names=10-year,25-year,50-year,1pct_min,100-year,1pct_plu,500-year
River Rch & RM=Upper Denton 73,Reach-1         ,20103
     850    1204    1505     934    1864    3720    2869
River Rch & RM=Upper Denton 73,Reach-1         ,18538
    1095    1563    1964    1224    2441    4871    3785
River Rch & RM=Upper Denton 73,Reach-1         ,11819
    1360    1962    2484    1557    3107    6200    4882
River Rch & RM=Upper Denton 73,Reach-1         ,10429
    1711    2499    3188    2014    4018    8017    6407
River Rch & RM=Upper Denton 73,Reach-1         ,10064
    1861    2714    3460    2182    4353    8685    6919
River Rch & RM=Upper Denton 73,Reach-1         ,2349
    2058    3010    3844    2427    4843    9663    7720
Boundary for River Rch & Prof#=Upper Denton 73,Reach-1         , 1
Up Type= 0
Dn Type= 3
Dn Slope=0.015
Boundary for River Rch & Prof#=Upper Denton 73,Reach-1         , 2
Up Type= 0
Dn Type= 3
Dn Slope=0.015
Boundary for River Rch & Prof#=Upper Denton 73,Reach-1         , 3
Up Type= 0
Dn Type= 3
Dn Slope=0.015
Boundary for River Rch & Prof#=Upper Denton 73,Reach-1         , 4
Up Type= 0
Dn Type= 3
Dn Slope=0.015
Boundary for River Rch & Prof#=Upper Denton 73,Reach-1         , 5
Up Type= 0
Dn Type= 3
Dn Slope=0.015
Boundary for River Rch & Prof#=Upper Denton 73,Reach-1         , 6
Up Type= 0
Dn Type= 3
Dn Slope=0.015
Boundary for River Rch & Prof#=Upper Denton 73,Reach-1         , 7
Up Type= 0
Dn Type= 3
Dn Slope=0.015
DSS Import GetInterval= 0
DSS Import GetPeak= 0
DSS Import FillOption= 0

--- Upper Denton 73.g01 (geometry) ---

Geom Title=Existing Conditions
Program Version=4.10

River Reach=Upper Denton 73 ,Reach-1
Reach XY= 30
        2207129.        7277960.      2206629.24      7276924.11
      2207131.26      7274965.94      2207427.62      7274350.34
      2207230.88      7273615.72      2207484.83       7273007.7
      2207875.46      7272558.54      2208076.76      7271854.07
      2208032.55      7271161.47      2208275.87      7270858.36
      2208236.37      7270703.66      2208515.39      7270523.24
      2208898.77      7269939.87      2209768.24      7269269.68
      2210323.17       7268562.3       2210384.1      7268214.89
      2210635.54      7268450.77      2211008.52      7267929.27
       2211371.4      7267763.34      2211273.54      7267307.55
      2210986.18      7267009.67      2211177.03      7266904.35
       2211379.9      7265374.71       2211528.5      7265194.79
      2211328.46      7264465.54      2211529.04      7263844.66
      2211428.64      7263287.07      2211528.96      7262930.19
       2211378.5       7262769.3        2211529.        7261860.

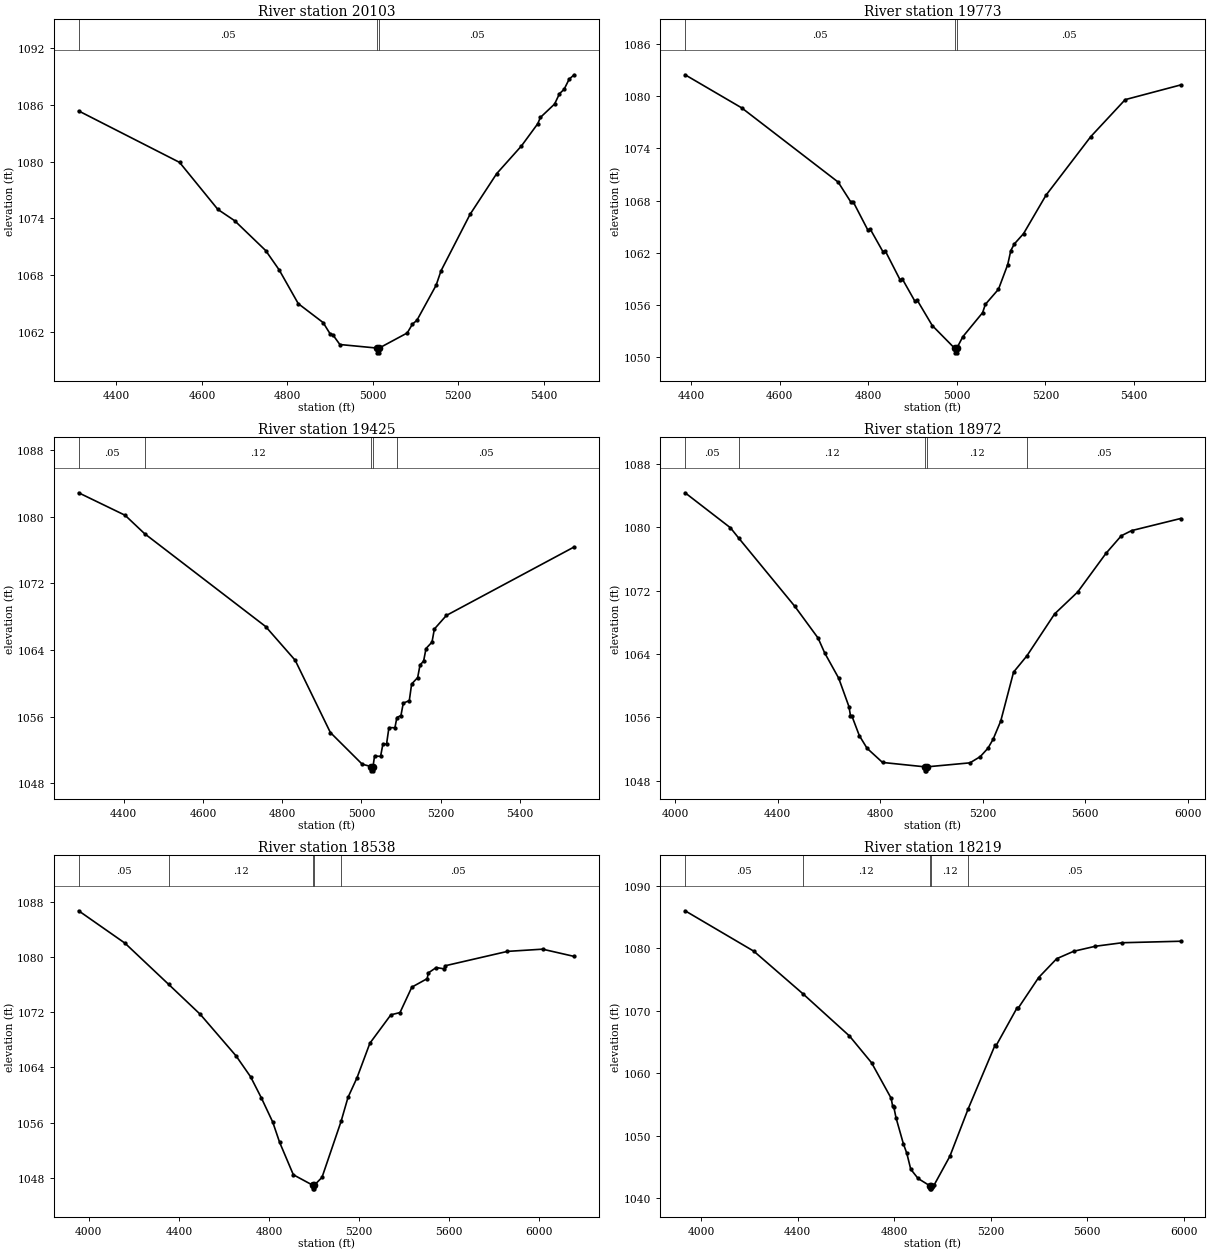
Type RM Length L Ch R = 1 ,20103   ,330,330,330
BEGIN DESCRIPTION:
Upper Denton 73 44.0
END DESCRIPTION:
XS GIS Cut Line= 3
      2207699.35      7277601.73        2207079.        7277910.
       2206657.7      7278112.13
#Sta/Elev= 30
  4311.5 1085.37  4547.8 1079.93  4637.4 1074.96  4676.6 1073.77  4749.4 1070.61
  4780.9 1068.57  4825.6    1065  4883.8    1063  4900.6 1061.78  4906.2 1061.73
    4923 1060.68  5010.8  1060.3    5011  1059.8  5014.5  1059.8  5014.8  1060.3
  5080.7  1061.9    5093 1062.84  5103.4 1063.24  5148.4 1066.95  5159.8 1068.47
  5227.7 1074.43  5290.1 1078.74  5348.1 1081.67  5386.3 1084.02  5392.4 1084.68
  5425.7  1086.1  5437.1 1087.19  5447.9 1087.65  5459.8 1088.73  5471.5 1089.19
#Mann= 3 ,-1 , 0
  4311.5     .05       0  5010.8    .033       0  5014.8     .05       0
Bank Sta=5010.8,5014.8
XS Rating Curve= 0 ,0
Exp/Cntr=0.3,0.1

Type RM Length L Ch R = 1 ,19773   ,348,348,348
BEGIN DESCRIPTION:
Upper Denton 73 43.0
END DESCRIPTION:
XS GIS Cut Line= 3
      2207569.19      7277440.25        2206979.        7277610.
      2206563.99      7277898.57
#Sta/Elev= 30
  4385.9 1082.47  4513.9 1078.66  4731.7 1070.13  4760.2 1067.85  4765.4 1067.89
  4799.1 1064.58  4804.3 1064.71  4832.8 1062.13    4838 1062.23  4871.7 1058.88
  4876.9 1058.97  4905.4  1056.4  4910.6 1056.52  4944.3 1053.63  4995.4 1050.99
  4995.7 1050.49  4999.2 1050.49  4999.4 1050.99  5013.5 1052.35  5058.1 1055.11
  5064.2 1056.06  5093.9  1057.8  5114.8 1060.64  5121.8 1062.25  5129.7 1063.01
  5150.6  1064.2  5201.2 1068.61  5302.5 1075.36  5380.2 1079.61  5505.5  1081.3
#Mann= 3 ,-1 , 0
  4385.9     .05       0  4995.4    .033       0  4999.4     .05       0
Bank Sta=4995.4,4999.4
XS Rating Curve= 0 ,0
Exp/Cntr=0.3,0.1

Type RM Length L Ch R = 1 ,19425   ,453,453,453
BEGIN DESCRIPTION:
Upper Denton 73 42.0
END DESCRIPTION:
XS GIS Cut Line= 3
      2207522.28      7277122.55        2206829.        7277310.
       2206538.9      7277756.45
#Sta/Elev= 30
  4286.4 1082.85  4403.7 1080.15  4452.7 1077.95  4758.3  1066.8  4832.9 1062.75
  4921.7 1054.08    5002 1050.28  5025.3 1049.98  5025.5 1049.48    5029 1049.48
  5029.3 1049.98  5033.2 1051.25  5048.4 1051.22  5054.4 1052.71  5063.5 1052.69
  5069.5 1054.67  5084.6 1054.65  5089.6 1055.88  5099.8 1056.12  5105.7  1057.6
  5120.9 1057.91  5126.8  1059.9    5142 1060.67  5147.9 1062.16  5157.1 1062.67
  5163.1 1064.16  5178.2 1064.93  5184.2  1066.5  5214.5 1068.13    5537 1076.35
#Mann= 5 ,-1 , 0
  4286.4     .05       0  4452.7     .12       0  5025.3     .07       0
  5029.3     .12       0  5089.6     .05       0
Bank Sta=5025.3,5029.3
XS Rating Curve= 0 ,0
Exp/Cntr=0.3,0.1

Type RM Length L Ch R = 1 ,18972   ,434,434,434
BEGIN DESCRIPTION:
Upper Denton 73 41.0
END DESCRIPTION:
XS GIS Cut Line= 3
      2207584.79      7277039.22      2206647.29      7276945.47
      2205657.68      7276940.26
#Sta/Elev= 30
  4039.7 1084.36  4216.4 1079.94  4247.9 1078.67  4467.6 1070.01  4558.1 1066.01
  4583.9 1064.13  4638.5 1060.94  4678.7 1057.33  4684.4 1056.21  4689.4 1056.21
  4718.9 1053.69    4749 1052.09  4809.3  1050.3  4976.2 1049.74  4976.7 1049.24
  4980.4 1049.24  4980.8 1049.74  5150.2 1050.25  5190.2 1051.03  5220.2 1052.09
  5240.2 1053.21  5270.2 1055.53  5320.2 1061.71  5372.1 1063.76  5480.2 1069.06
  5570.2 1071.83  5680.2  1076.7  5740.2 1078.93  5780.2 1079.58  5971.5 1081.11
#Mann= 5 ,-1 , 0
  4039.7     .05       0  4247.9     .12       0  4976.2     .07       0
  4980.8     .12       0  5372.1     .05       0
Bank Sta=4976.2,4980.8
XS Rating Curve= 0 ,0
Exp/Cntr=0.3,0.1

Type RM Length L Ch R = 1 ,18538   ,319,319,319
BEGIN DESCRIPTION:
Upper Denton 73 40.0
END DESCRIPTION:
XS GIS Cut Line= 3
      2207756.66      7276731.92      2206730.62      7276544.42
      2205612.38      7276247.96
#Sta/Elev= 30
  3954.7 1086.68  4160.4 1081.99  4354.1 1076.03    4495 1071.67  4653.7 1065.66
  4718.1 1062.64  4765.6  1059.6  4816.4 1056.08  4846.9 1053.15  4907.9 1048.45
  4995.4 1046.91  4995.9 1046.41  4999.6 1046.41  5000.1 1046.91  5035.1 1048.07
  5119.7 1056.17  5150.5 1059.65  5190.7 1062.51  5247.7  1067.5  5340.8 1071.61
  5381.4 1071.94  5433.9 1075.62    5502 1076.85  5507.1 1077.68  5542.2 1078.46
  5577.2 1078.27  5582.4 1078.72  5858.6  1080.8  6014.2 1081.12  6154.6 1080.07
#Mann= 5 ,-1 , 0
  3954.7     .05       0  4354.1     .12       0  4995.4     .07       0
  5000.1     .12       0  5119.7     .05       0
Bank Sta=4995.4,5000.1
XS Rating Curve= 0 ,0
Exp/Cntr=0.3,0.1

Type RM Length L Ch R = 1 ,18219   ,441,441,441
BEGIN DESCRIPTION:
Upper Denton 73 39.0
END DESCRIPTION:
XS GIS Cut Line= 3
      2207829.56      7276487.13      2206784.21      7276299.58
      2205798.29      7276190.25
#Sta/Elev= 30
  3933.9 1086.03  4218.9 1079.55  4421.8 1072.75  4615.2 1065.97  4706.6 1061.69
  4787.9    1056  4794.2 1054.73  4799.2 1054.55  4808.2 1052.86  4838.7 1048.69
    4853 1047.16  4869.2 1044.62  4899.6 1043.14    4948 1041.98  4948.6 1041.48
  4952.3 1041.48  4952.8 1041.98  4965.5 1042.05  5031.4  1046.7  5107.3  1054.3
  5218.2 1064.46  5223.3 1064.44  5308.9 1070.41  5313.9 1070.39  5399.5 1075.34
  5474.1 1078.35  5544.5 1079.54    5635 1080.35  5745.7 1080.91  5987.9 1081.15
#Mann= 5 ,-1 , 0
  3933.9     .05       0  4421.8     .12       0    4948     .07       0
  4952.8     .12       0  5107.3     .05       0
Bank Sta=4948,4952.8
XS Rating Curve= 0 ,0
Exp/Cntr=0.3,0.1

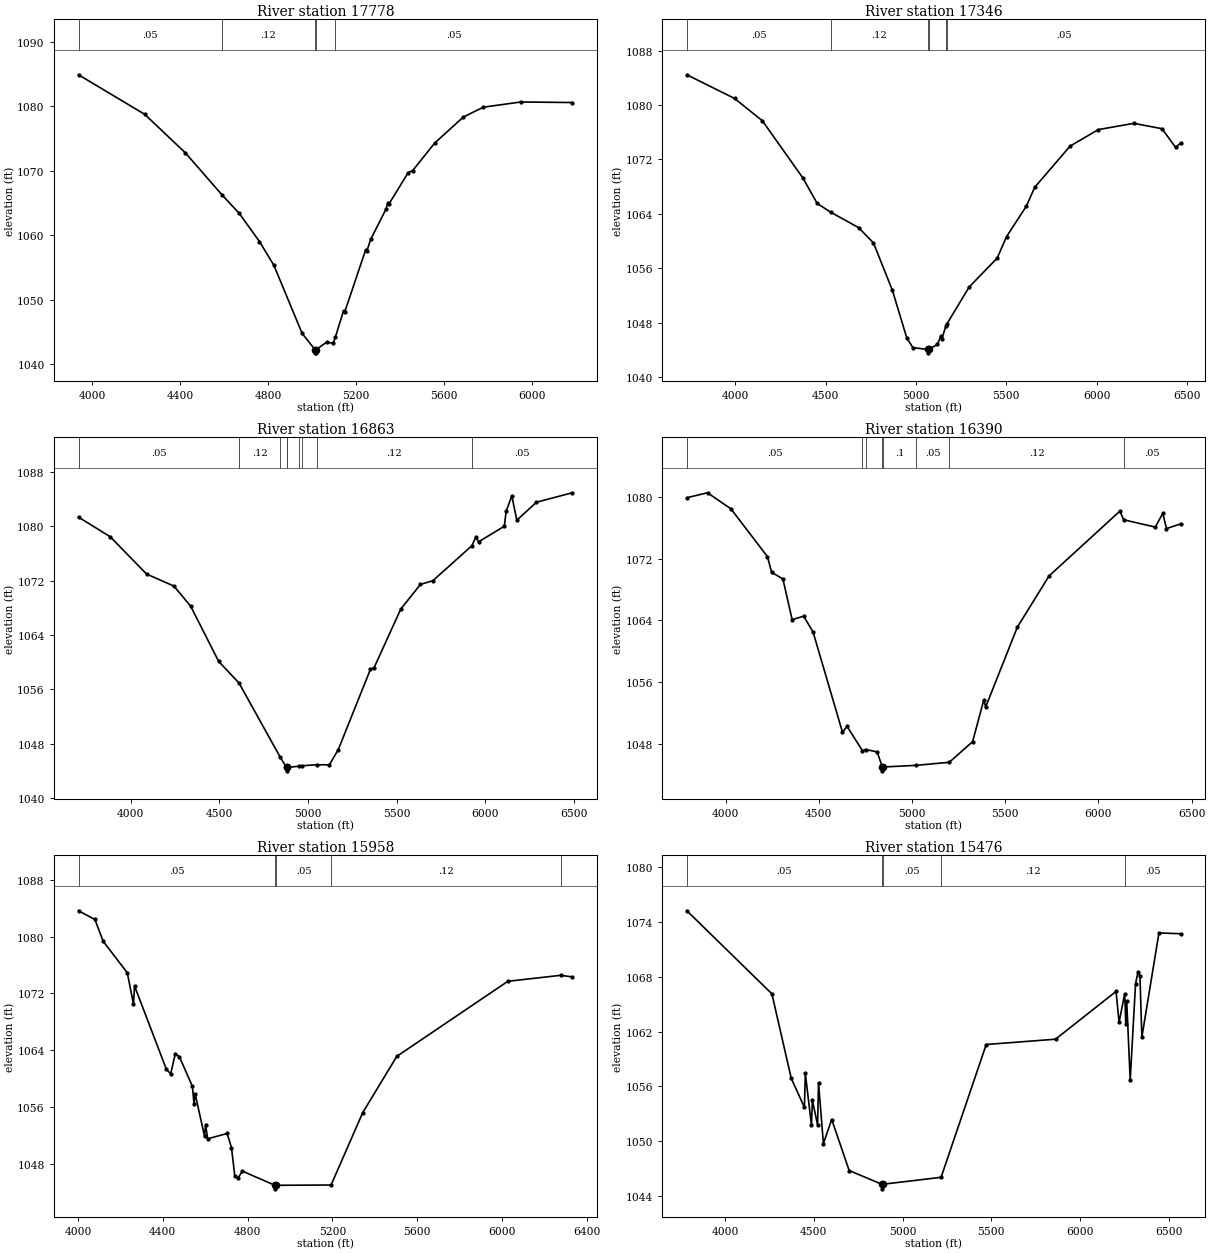
Type RM Length L Ch R = 1 ,17778   ,432,432,432
BEGIN DESCRIPTION:
Upper Denton 73 38.0
END DESCRIPTION:
XS GIS Cut Line= 3
      2207965.04      7276127.77        2206929.        7275910.
      2205746.23       7276028.8
#Sta/Elev= 30
  3936.8 1084.91  4238.1 1078.77  4423.2 1072.79  4589.1  1066.3  4668.5 1063.39
  4760.4 1059.03  4826.1 1055.33  4954.6 1044.77  5013.2 1042.25  5013.7 1041.75
  5017.4 1041.75    5018 1042.25  5065.8 1043.39    5096 1043.24  5105.5 1044.14
  5143.4  1048.3  5148.4 1048.08  5243.7 1057.73  5248.7 1057.49  5266.8 1059.37
  5337.2 1064.11  5343.9 1064.96    5349 1064.81  5437.7 1069.74  5457.8 1070.04
  5558.3 1074.32  5688.9 1078.36  5779.4 1079.88  5950.7 1080.69  6184.2  1080.6
#Mann= 5 ,-1 , 0
  3936.8     .05       0  4589.1     .12       0  5013.2     .07       0
    5018     .12       0  5105.5     .05       0
Bank Sta=5013.2,5018
XS Rating Curve= 0 ,0
Exp/Cntr=0.3,0.1

Type RM Length L Ch R = 1 ,17346   ,483,483,483
BEGIN DESCRIPTION:
Upper Denton 73 37.0
END DESCRIPTION:
XS GIS Cut Line= 3
      2208252.64      7275861.04        2207029.        7275510.
      2205617.26      7275881.88
#Sta/Elev= 30
  3731.6 1084.44  3995.5 1080.96  4149.4 1077.68  4372.6 1069.31  4453.2 1065.52
  4526.9 1064.25  4682.1 1061.97  4764.5 1059.72  4869.4 1052.74  4948.8 1045.75
  4982.5 1044.33    5065 1044.06  5065.7 1043.56  5070.2 1044.06  5118.4  1044.8
  5137.9 1046.06  5143.1 1045.64  5165.3 1047.48    5170 1047.77    5294 1053.23
  5449.3 1057.49    5501 1060.64  5611.3 1065.15  5656.8 1067.89  5853.2 1073.96
  6009.3 1076.38  6205.7  1077.3  6361.7 1076.51  6437.2 1073.75  6464.5 1074.41
#Mann= 6 ,-1 , 0
  3731.6     .05       0  4526.9     .12       0    5065     .07       0
  5070.2     .12       0  5165.3     .12       0    5170     .05       0
Bank Sta=5065,5070.2
XS Rating Curve= 0 ,0
Exp/Cntr=0.3,0.1

Type RM Length L Ch R = 1 ,16863   ,473,473,473
BEGIN DESCRIPTION:
Upper Denton 73 36.0
END DESCRIPTION:
XS GIS Cut Line= 3
      2208362.02      7275449.59        2207129.        7275060.
      2205648.49      7274897.51
#Sta/Elev= 30
  3706.9 1081.36  3885.6 1078.47    4090 1072.99  4244.9  1071.2  4339.3 1068.23
  4496.6 1060.12  4611.4 1056.93  4844.5 1045.97    4879  1044.5  4879.7    1044
  4884.3  1044.5  4947.7 1044.68    4969 1044.76    5049 1044.89  5120.7 1044.89
    5171 1047.14  5352.1 1058.96  5372.2 1059.17  5523.1 1067.83  5633.8 1071.45
  5704.2 1072.01  5923.6 1077.15  5945.6  1078.4  5961.6 1077.73  6106.6 1080.02
  6116.7  1082.2  6148.8  1084.5    6177 1080.91  6287.7 1083.56  6489.4 1084.95
#Mann= 9 ,-1 , 0
  3706.9     .05       0  4611.4     .12       0  4844.5     .05       0
    4879    .033       0  4884.3     .05       0  4947.7      .1       0
    4969     .05       0    5049     .12       0  5923.6     .05       0
Bank Sta=4879,4884.3
XS Rating Curve= 0 ,0
Exp/Cntr=0.3,0.1

Type RM Length L Ch R = 1 ,16390   ,432,432,432
BEGIN DESCRIPTION:
Upper Denton 73 35.0
END DESCRIPTION:
XS GIS Cut Line= 3
      2208518.31      7274840.22        2207329.        7274660.
       2205883.4      7274652.72
#Sta/Elev= 30
  3792.4 1079.95    3903 1080.59  4028.4 1078.51  4224.6 1072.29  4246.8 1070.27
  4307.5 1069.38  4357.1  1064.1  4418.8 1064.55  4469.3 1062.49  4627.2 1049.46
  4651.4 1050.24  4733.9 1047.08  4751.8 1047.22  4813.2 1046.91  4840.9 1044.95
  4841.7 1044.45  4846.2 1044.95    5020 1045.16  5200.1 1045.56  5325.3 1048.25
  5385.3 1053.67  5395.3 1052.75  5565.3 1063.13  5735.3 1069.78  6115.3 1078.21
  6135.7 1077.08  6305.3 1076.13  6345.3 1077.92  6365.3 1075.94  6440.9 1076.54
#Mann= 8 ,-1 , 0
  3792.4     .05       0  4733.9     .12       0  4751.8      .1       0
  4840.9     .07       0  4846.2      .1       0    5020     .05       0
  5200.1     .12       0  6135.7     .05       0
Bank Sta=4840.9,4846.2
XS Rating Curve= 0 ,0
Exp/Cntr=0.3,0.1

Type RM Length L Ch R = 1 ,15958   ,482,482,482
BEGIN DESCRIPTION:
Upper Denton 73 34.0
END DESCRIPTION:
XS GIS Cut Line= 3
      2208403.65      7274470.41        2207429.        7274260.
      2206123.18      7274511.95
#Sta/Elev= 30
    4003 1083.67  4080.3 1082.44  4119.3 1079.36  4232.8 1074.92    4262  1070.5
  4267.1 1073.05    4417  1061.3  4437.4 1060.66  4459.1 1063.51  4478.4 1063.07
  4539.7 1058.89  4547.4 1056.38  4552.5 1057.84  4596.7 1051.88  4601.8  1053.5
  4611.3 1051.49  4703.4 1052.24  4723.9 1050.25  4739.3 1046.29  4754.6 1045.94
    4775 1046.93  4928.6 1044.93  4929.4 1044.43    4934 1044.93  5193.3 1044.97
  5342.2 1055.17  5502.9 1063.12  6026.5 1073.72  6274.7 1074.56    6330 1074.34
#Mann= 5 ,-1 , 0
    4003     .05       0  4928.6    .033       0    4934     .05       0
  5193.3     .12       0  6274.7     .05       0
Bank Sta=4928.6,4934
XS Rating Curve= 0 ,0
Exp/Cntr=0.3,0.1

Type RM Length L Ch R = 1 ,15476   ,358,358,358
BEGIN DESCRIPTION:
Upper Denton 73 33.0
END DESCRIPTION:
XS GIS Cut Line= 3
      2208500.49      7274129.71        2207329.        7273810.
      2205865.08      7274364.08
#Sta/Elev= 30
    3786  1075.2  4264.6 1066.12  4373.4 1056.89  4447.7 1053.71  4452.9 1057.41
  4487.4 1051.75  4492.6 1054.48  4521.9 1051.78  4527.1 1056.39  4554.6 1049.75
  4601.4 1052.38  4699.7  1046.8  4883.6  1045.3  4884.4  1044.8  4889.1  1045.3
  5217.2 1046.06  5471.3 1060.58  5861.5 1061.16  6202.1 1066.38  6219.3 1063.01
    6251 1066.13  6257.1 1062.86  6262.4 1065.33  6281.9 1056.68    6312 1067.22
  6326.2 1068.54  6336.9 1068.03  6347.6 1061.39  6443.8 1072.78  6565.6 1072.69
#Mann= 5 ,-1 , 0
    3786     .05       0  4883.6    .033       0  4889.1     .05       0
  5217.2     .12       0    6251     .05       0
Bank Sta=4883.6,4889.1
XS Rating Curve= 0 ,0
Exp/Cntr=0.3,0.1

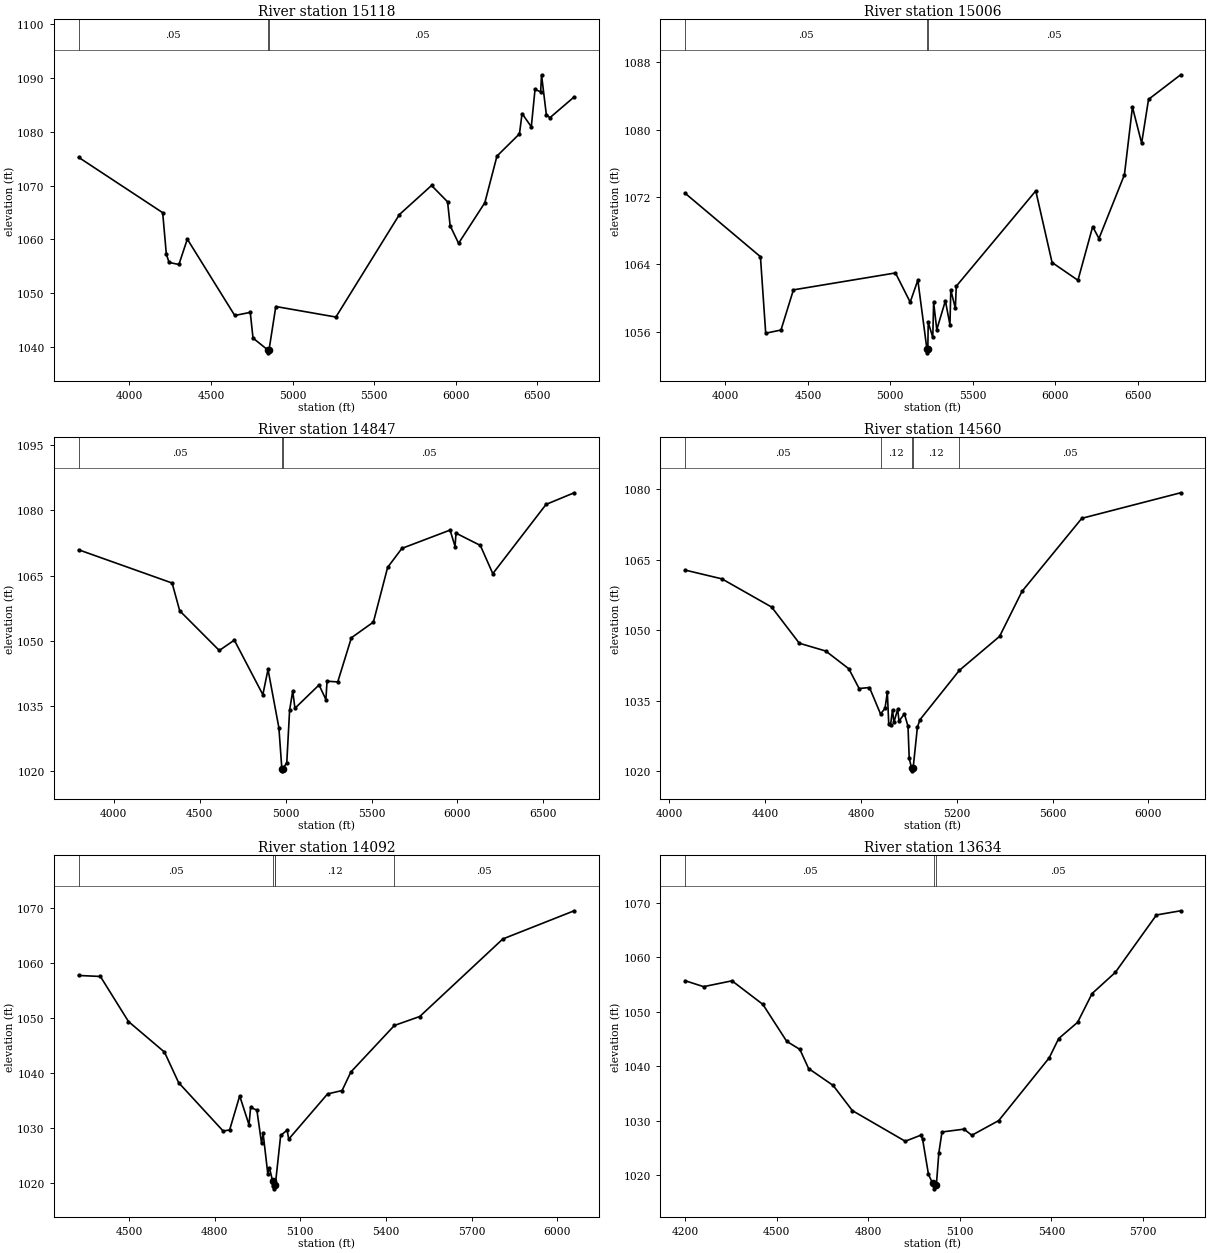
Type RM Length L Ch R = 1 ,15118   ,112,112,112
BEGIN DESCRIPTION:
Upper Denton 73 32.5
END DESCRIPTION:
XS GIS Cut Line= 3
       2208458.8      7274093.25      2207224.83      7273476.67
       2205625.5      7273041.18
#Sta/Elev= 30
  3688.5 1075.28  4203.6 1064.98    4226 1057.27  4242.8 1055.72  4303.1 1055.34
  4354.6 1060.06  4645.3 1045.85  4740.4 1046.43  4757.2 1041.65  4849.2  1039.4
  4850.2  1038.9  4855.2  1039.4  4896.9 1047.52  5265.2 1045.56  5654.4 1064.63
  5851.3 1070.04  5949.7    1067  5965.3 1062.56  6017.1 1059.28  6177.9 1066.83
  6252.3 1075.51  6390.2 1079.65  6406.1 1083.43  6462.8 1080.96  6485.6 1087.92
  6520.2 1087.46  6525.4 1090.64  6554.8 1083.24  6576.8 1082.65  6725.5 1086.52
#Mann= 3 ,-1 , 0
  3688.5     .05       0  4849.2    .033       0  4855.2     .05       0
Bank Sta=4849.2,4855.2
XS Rating Curve= 0 ,0
Exp/Cntr=0.3,0.1

Type RM Length L Ch R = 1 ,15006   ,159,159,159
BEGIN DESCRIPTION:
Upper Denton 73 32.0
END DESCRIPTION:
XS GIS Cut Line= 3
      2208417.14      7274015.13        2207329.        7273410.
      2205642.53      7272900.97
#Sta/Elev= 30
  3754.9 1072.44    4212  1064.9    4244 1055.81  4336.7 1056.19  4412.1 1060.96
  5031.3 1062.97  5120.6  1059.5  5167.1 1062.11  5221.7 1053.98  5222.7 1053.48
  5227.7 1053.98    5230  1057.1  5257.7 1055.31  5262.9 1059.48    5282 1056.24
  5334.2 1059.66  5361.9 1056.81  5367.1 1060.95  5394.8 1058.75  5400.1 1061.39
  5882.6 1072.72  5981.5 1064.21  6138.5  1062.1  6227.9 1068.47  6266.1 1067.06
  6420.6 1074.64  6469.2 1082.67    6525 1078.39  6566.8 1083.59  6761.6 1086.51
#Mann= 3 ,-1 , 0
  3754.9     .05       0  5221.7    .033       0  5227.7     .05       0
Bank Sta=5221.7,5227.7
XS Rating Curve= 0 ,0
Exp/Cntr=0.3,0.1

Type RM Length L Ch R = 1 ,14847   ,287,287,287
BEGIN DESCRIPTION:
Upper Denton 73 31.5
END DESCRIPTION:
XS GIS Cut Line= 3
      2208391.13       7273921.4      2207395.67      7273270.42
      2205762.41      7272822.83
#Sta/Elev= 30
    3796 1070.91  4339.9 1063.27    4384  1056.9  4614.3 1047.78  4701.8 1050.16
  4867.7 1037.64  4897.8 1043.43  4961.1 1030.01  4978.2 1020.64  4979.2 1020.14
  4984.2 1020.64  5006.9 1021.99  5023.4 1034.05  5041.4 1038.47  5054.5 1034.51
  5194.8 1039.87  5234.5 1036.51  5241.2 1040.73  5303.4 1040.56  5382.7  1050.7
  5510.8  1054.3  5593.7 1066.87  5676.7 1071.23  5956.8 1075.43  5986.1 1071.65
  5991.3 1074.73  6132.9 1071.91  6205.5 1065.43  6515.4 1081.33  6678.9    1084
#Mann= 3 ,-1 , 0
    3796     .05       0  4978.2    .033       0  4984.2     .05       0
Bank Sta=4978.2,4984.2
XS Rating Curve= 0 ,0
Exp/Cntr=0.3,0.1

Type RM Length L Ch R = 1 ,14560   ,468,468,468
BEGIN DESCRIPTION:
Upper Denton 73 31.0
END DESCRIPTION:
XS GIS Cut Line= 3
      2208292.15      7273478.67        2207479.        7273010.
      2206392.51      7272697.82
#Sta/Elev= 30
  4065.8 1062.79  4219.5 1060.92  4427.2 1054.92  4542.7 1047.23  4653.1 1045.57
  4749.3  1041.8  4792.4  1037.6  4835.6 1037.81  4881.8 1032.19  4900.5 1033.36
  4910.2 1036.83    4916 1030.13  4923.6  1029.9  4931.8 1033.05  4937.6 1030.43
  4953.3 1033.18  4959.1 1030.65  4981.3 1032.22  4996.5 1029.57  5001.5 1022.77
  5011.8 1020.59  5012.8 1020.09  5017.8 1020.59  5035.6 1029.32    5046 1030.94
  5211.1 1041.47  5378.9 1048.69  5472.6 1058.27  5722.3  1073.8  6134.8 1079.23
#Mann= 5 ,-1 , 0
  4065.8     .05       0  4881.8     .12       0  5011.8     .07       0
  5017.8     .12       0  5211.1     .05       0
Bank Sta=5011.8,5017.8
XS Rating Curve= 0 ,0
Exp/Cntr=0.3,0.1

Type RM Length L Ch R = 1 ,14092   ,458,458,458
BEGIN DESCRIPTION:
Upper Denton 73 30.0
END DESCRIPTION:
XS GIS Cut Line= 3
      2208375.45      7272978.66        2207779.        7272660.
      2206823.72      7272202.78
#Sta/Elev= 30
  4323.8 1057.74    4400 1057.56  4498.4 1049.35  4624.4 1043.79    4674 1038.22
    4830 1029.41  4852.6 1029.62  4887.8 1035.81  4920.4 1030.56  4926.1 1033.72
    4948 1033.22  4964.3 1027.22  4969.9 1028.97  4986.2 1021.63  4991.9 1022.74
  5002.8 1020.36  5005.6 1019.39  5006.6 1018.89  5011.7 1019.39  5012.6 1019.62
  5031.3 1028.61  5053.9 1029.58  5059.5 1027.94  5195.5 1036.17  5246.4 1036.79
  5277.2 1040.17  5429.6 1048.64  5518.4 1050.27  5809.3 1064.39  6059.1 1069.52
#Mann= 5 ,-1 , 0
  4323.8     .05       0  5005.6    .033       0  5011.7     .05       0
  5012.6     .12       0  5429.6     .05       0
Bank Sta=5002.8,5012.6
XS Rating Curve= 0 ,0
Exp/Cntr=0.3,0.1

Type RM Length L Ch R = 1 ,13634   ,450,450,450
BEGIN DESCRIPTION:
Upper Denton 73 29.0
END DESCRIPTION:
XS GIS Cut Line= 3
      2208589.06      7272713.07        2207929.        7272260.
       2207132.3      7272052.01
#Sta/Elev= 30
  4199.4 1055.67  4260.1 1054.58  4353.1 1055.65  4454.2 1051.33  4532.4 1044.54
  4575.5 1043.06  4604.1 1039.55  4684.6 1036.44  4747.6 1031.82  4920.8  1026.2
  4971.6  1027.3  4977.6 1026.62    4997 1020.11  5010.3 1018.51  5014.5 1017.96
  5015.6 1017.46  5020.7 1017.96  5022.8 1018.13    5031 1024.08  5041.3  1027.9
  5113.7 1028.42    5139 1027.29  5227.4    1030  5392.7 1041.51  5423.7 1045.05
  5485.7 1048.03  5533.3 1053.32  5609.1 1057.18  5744.1 1067.74  5823.4 1068.51
#Mann= 3 ,-1 , 0
  4199.4     .05       0  5014.5    .033       0  5020.7     .05       0
Bank Sta=5010.3,5022.8
XS Rating Curve= 0 ,0
Exp/Cntr=0.3,0.1

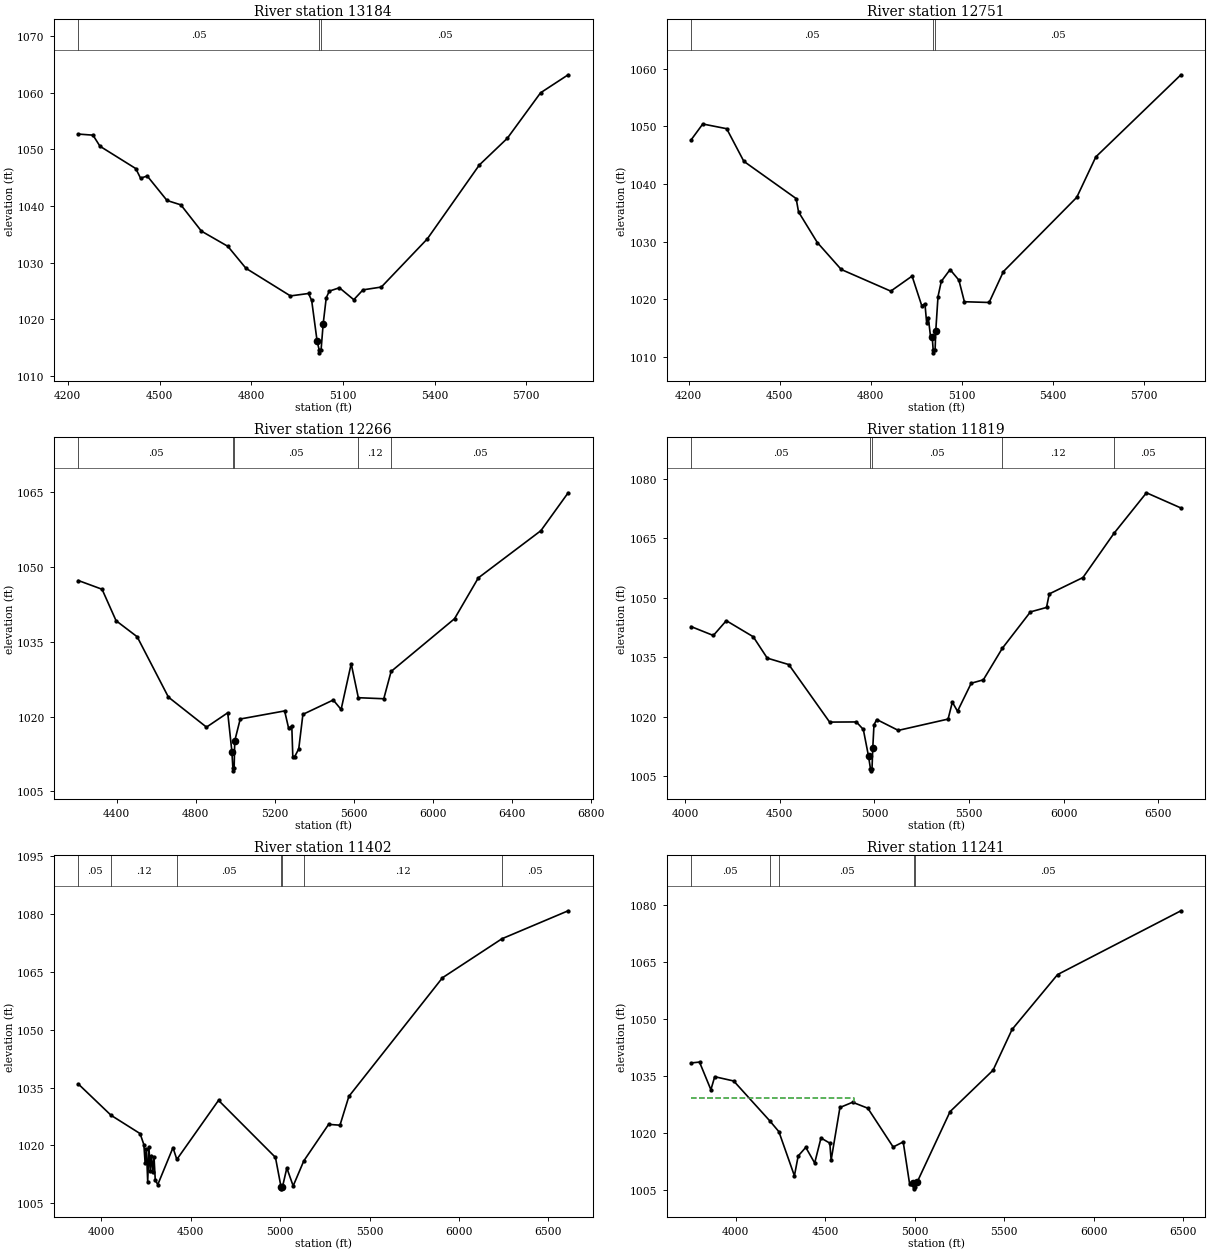
Type RM Length L Ch R = 1 ,13184   ,433,433,433
BEGIN DESCRIPTION:
Upper Denton 73 28.0
END DESCRIPTION:
XS GIS Cut Line= 3
      2208740.47      7272235.94        2208079.        7271860.
       2207238.8       7271906.1
#Sta/Elev= 30
  4234.5 1052.72  4282.4 1052.53  4305.2 1050.57  4422.3 1046.62  4438.1 1044.91
  4459.8 1045.31  4524.6 1040.97  4569.8  1040.2  4637.1 1035.55  4723.6 1032.86
  4782.7 1028.98  4928.3 1024.09  4987.4 1024.52  4997.8 1023.28  5015.4 1016.15
  5022.3 1014.52  5023.3 1014.02  5028.5 1014.52  5035.4 1019.16  5045.4 1023.75
  5055.4 1024.94  5088.5 1025.53  5135.5 1023.42  5165.6 1025.16  5225.7 1025.66
  5375.9 1034.17  5546.2 1047.25  5637.8 1051.98  5746.5 1060.02  5836.8 1063.21
#Mann= 3 ,-1 , 0
  4234.5     .05       0  5022.3    .033       0  5028.5     .05       0
Bank Sta=5015.4,5035.4
XS Rating Curve= 0 ,0
Exp/Cntr=0.3,0.1

Type RM Length L Ch R = 1 ,12751   ,485,485,485
BEGIN DESCRIPTION:
Upper Denton 73 27.0
END DESCRIPTION:
XS GIS Cut Line= 3
      2208775.23      7271723.81        2208029.        7271460.
      2207273.74      7271784.46
#Sta/Elev= 30
  4208.4 1047.64  4246.8  1050.4  4325.6 1049.58  4382.1 1043.92  4554.4 1037.46
  4562.3 1035.14  4624.1 1029.83  4702.9 1025.15  4866.1 1021.39  4936.3    1024
  4968.1 1018.87  4978.7 1019.19  4984.4 1015.83  4989.7 1016.81  4997.2 1013.45
  5002.6 1013.45  5005.8 1011.18  5006.8 1010.68  5012.1 1011.18  5014.4 1014.55
  5021.7 1020.44  5032.5 1023.08  5061.5 1025.13  5090.5  1023.3  5108.6 1019.55
  5190.1 1019.42  5237.2 1024.79  5478.8 1037.67  5541.6 1044.69  5821.9 1058.94
#Mann= 3 ,-1 , 0
  4208.4     .05       0  5005.8    .033       0  5012.1     .05       0
Bank Sta=5002.6,5014.4
XS Rating Curve= 0 ,0
Exp/Cntr=0.3,0.1

Type RM Length L Ch R = 1 ,12266   ,447,447,447
BEGIN DESCRIPTION:
Upper Denton 73 26.0
END DESCRIPTION:
XS GIS Cut Line= 3
      2208766.57      7271489.45        2208129.        7271010.
      2206483.77      7270682.18
#Sta/Elev= 30
  4206.8 1047.26  4326.6 1045.51  4397.5  1039.2    4504 1035.99  4661.9 1023.89
  4854.4 1017.87  4961.8 1020.75  4982.7 1012.97  4987.8 1009.61  4988.9 1009.11
  4994.1 1009.61  4997.2 1015.13  5024.9  1019.5  5249.2 1021.12  5269.6 1017.62
  5285.5 1018.12  5290.6 1011.91  5300.2 1011.97  5320.6  1013.5  5341.6 1020.43
  5494.9 1023.31  5534.7 1021.41  5585.7 1030.58  5621.7 1023.77  5750.3 1023.56
  5787.3 1029.03  6107.8  1039.6  6228.1 1047.79  6544.2 1057.25  6682.1 1064.85
#Mann= 5 ,-1 , 0
  4206.8     .05       0  4987.8    .033       0  4994.1     .05       0
  5621.7     .12       0  5787.3     .05       0
Bank Sta=4982.7,4997.2
XS Rating Curve= 0 ,0
Exp/Cntr=0.3,0.1

Type RM Length L Ch R = 1 ,11819   ,417,417,417
BEGIN DESCRIPTION:
Upper Denton 73 25.0
END DESCRIPTION:
XS GIS Cut Line= 4
      2208844.66      7271419.98      2208608.65       7270918.6
        2208279.        7270660.       2207283.1      7269389.93
#Sta/Elev= 30
  4031.8 1042.72  4149.3 1040.48  4217.7 1044.21    4360 1040.16  4433.9 1034.78
  4547.8 1033.15  4763.4 1018.66  4904.6  1018.7  4941.4  1016.8  4968.8 1010.09
  4979.2 1006.88  4980.4 1006.38  4987.3 1006.88  4991.3 1012.13  4997.7 1017.97
  5012.2 1019.31  5126.1 1016.57  5389.1 1019.42  5411.6 1023.69  5438.9 1021.39
  5511.2 1028.45  5575.3 1029.31  5675.5 1037.25    5824 1046.42    5909 1047.54
  5923.4 1050.95  6101.5 1055.08  6265.1  1066.2  6436.9 1076.43  6618.9  1072.6
#Mann= 5 ,-1 , 0
  4031.8     .05       0  4979.2    .033       0  4987.3     .05       0
  5675.5     .12       0  6265.1     .05       0
Bank Sta=4968.8,4991.3
XS Rating Curve= 0 ,0
Exp/Cntr=0.3,0.1

Type RM Length L Ch R = 1 ,11402   ,161,161,161
BEGIN DESCRIPTION:
Upper Denton 73 24.0
END DESCRIPTION:
XS GIS Cut Line= 3
      2209374.15      7271202.95        2208579.        7270410.
      2207455.74      7269249.82
#Sta/Elev= 30
  3872.4 1035.91  4055.1 1027.81  4217.5 1023.06  4238.7 1020.19  4245.8 1015.31
  4252.9 1019.13    4260 1010.62    4267 1019.51  4274.1 1013.38  4281.2 1017.38
  4288.3 1012.99  4295.3  1017.1  4302.4 1010.94  4316.5 1009.85  4401.4 1019.42
  4422.9 1016.36    4656 1031.68  4974.1 1016.89  5005.3 1009.24  5006.5 1008.74
  5013.4 1009.24  5037.7 1014.14  5073.2 1009.49  5132.5 1015.98  5271.2 1025.45
  5334.8 1025.24  5384.4  1032.7  5907.7 1063.46  6240.2 1073.57  6610.2 1080.82
#Mann= 7 ,-1 , 0
  3872.4     .05       0  4055.1     .12       0  4422.9     .05       0
  5005.3    .033       0  5013.4     .05       0  5132.5     .12       0
  6240.2     .05       0
Bank Sta=5005.3,5013.4
XS Rating Curve= 0 ,0
Exp/Cntr=0.3,0.1

Type RM Length L Ch R = 1 ,11241   ,288,288,288
BEGIN DESCRIPTION:
Upper Denton 73 23.5
END DESCRIPTION:
XS GIS Cut Line= 3
      2209478.37      7271176.96      2208627.65      7270265.48
      2207585.96      7269197.75
#Sta/Elev= 30
    3750 1038.42    3797 1038.65  3860.6 1031.37    3882  1034.8  3988.1 1033.67
  4188.6 1023.24  4240.7 1020.33  4327.6  1008.7  4348.6 1013.92  4391.1 1016.19
  4440.9 1012.07  4476.1 1018.66  4525.5  1017.3  4532.8 1012.81  4582.1 1026.69
  4652.9 1028.07    4738  1026.5  4879.6 1016.29  4935.9 1017.62  4971.5 1006.59
  4992.2 1006.72  4995.7 1005.77  4996.9 1005.27  5003.8 1005.77  5013.9 1007.05
  5197.8  1025.6  5438.1  1036.5  5544.3 1047.23  5798.9 1061.69  6488.5 1078.49
#Mann= 5 ,-1 , 0
    3750     .05       0  4188.6     .12       0  4240.7     .05       0
  4995.7    .033       0  5003.8     .05       0
#XS Ineff= 2 , 0
         4660.29 1029.32
Permanent Ineff=
       F       F
Bank Sta=4992.2,5013.9
XS Rating Curve= 0 ,0
Exp/Cntr=0.3,0.1

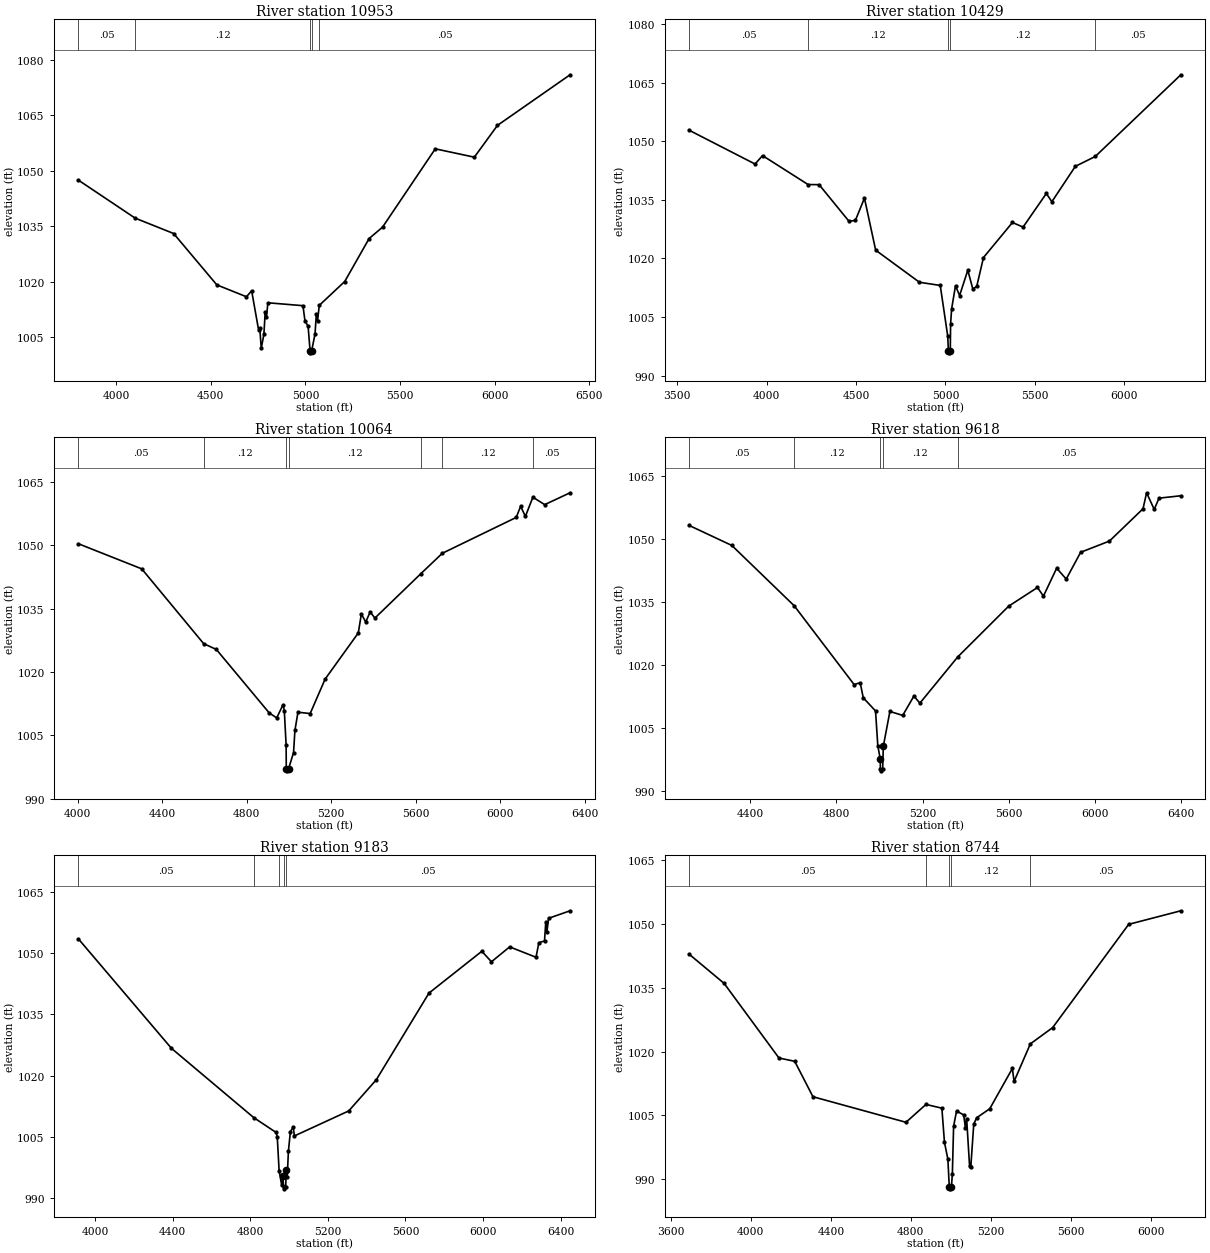
Type RM Length L Ch R = 1 ,10953   ,524,524,524
BEGIN DESCRIPTION:
Upper Denton 73 23.0
END DESCRIPTION:
XS GIS Cut Line= 3
      2209756.16      7270821.06        2208829.        7270060.
       2207716.2      7269215.13
#Sta/Elev= 30
  3800.7 1047.45  4100.2  1037.2  4303.5 1033.04  4531.6 1019.17  4688.1 1015.96
  4715.6 1017.57  4751.9  1007.1  4758.4 1007.56  4766.3 1002.02  4780.3 1005.82
  4787.1 1011.74  4793.6 1010.38  4801.4 1014.33  4986.6 1013.55    4997 1009.53
  5013.8 1007.94  5024.3 1001.31  5025.5 1000.81  5032.4 1001.31  5050.4 1005.95
  5057.4  1011.4  5063.7 1009.48  5072.7 1013.63  5207.2 1020.08  5336.1 1031.69
  5406.8 1034.75  5685.5 1055.92  5891.7 1053.66  6014.1 1062.26  6397.4 1075.92
#Mann= 5 ,-1 , 0
  3800.7     .05       0  4100.2     .12       0  5024.3     .07       0
  5032.4     .12       0  5072.7     .05       0
Bank Sta=5024.3,5032.4
XS Rating Curve= 0 ,0
Exp/Cntr=0.3,0.1

Type RM Length L Ch R = 1 ,10429   ,365,365,365
BEGIN DESCRIPTION:
Upper Denton 73 22.0
END DESCRIPTION:
XS GIS Cut Line= 3
       2210346.4      7270534.57      2209165.84       7269718.6
      2208020.02      7269076.24
#Sta/Elev= 30
  3567.1 1052.79  3935.2 1044.15  3977.2 1046.31  4231.7  1038.9  4293.4 1038.87
  4460.4  1029.5  4496.2 1029.72  4546.9 1035.41  4609.7  1022.1  4854.4 1013.89
  4970.7 1013.08  5012.7 1000.04  5016.2  996.33  5017.7  995.83  5026.8  996.33
  5028.6 1003.26  5034.4 1007.12    5056 1013.01  5078.8 1010.49  5124.7 1016.96
    5153 1012.16  5174.7 1012.84  5212.4 1020.22  5374.4 1029.19  5433.7 1028.01
  5563.9 1036.61  5594.7  1034.5  5725.9 1043.55  5837.3 1046.08  6315.8 1066.99
#Mann= 5 ,-1 , 0
  3567.1     .05       0  4231.7     .12       0  5016.2     .07       0
  5026.8     .12       0  5837.3     .05       0
Bank Sta=5016.2,5026.8
XS Rating Curve= 0 ,0
Exp/Cntr=0.3,0.1

Type RM Length L Ch R = 1 ,10064   ,446,446,446
BEGIN DESCRIPTION:
Upper Denton 73 21.0
END DESCRIPTION:
XS GIS Cut Line= 3
      2210243.98      7270083.19        2209429.        7269510.
      2208383.42      7268687.79
#Sta/Elev= 30
  4003.7 1050.35  4303.2 1044.41  4596.3 1026.69  4656.4 1025.31  4906.4 1010.29
  4942.1  1009.1  4971.7 1012.21  4977.9 1010.85  4986.5 1002.62  4987.3  997.06
  4988.8  996.56  4998.1  997.06  5021.7  1000.9  5028.1 1006.12  5042.5 1010.45
  5100.3 1010.13  5170.9 1018.28  5328.1 1029.23  5342.5  1033.7  5363.3 1031.82
  5384.1 1034.19  5406.7 1032.75  5624.4 1043.28  5725.8  1048.1  6075.4 1056.59
  6096.3 1059.23  6118.8 1056.83  6154.2 1061.38  6210.1 1059.62  6330.2 1062.43
#Mann= 7 ,-1 , 0
  4003.7     .05       0  4596.3     .12       0  4987.3     .07       0
  4998.1     .12       0  5624.4     .05       0  5725.8     .12       0
  6154.2     .05       0
Bank Sta=4987.3,4998.1
XS Rating Curve= 0 ,0
Exp/Cntr=0.3,0.1

Type RM Length L Ch R = 1 ,9618    ,435,435,435
BEGIN DESCRIPTION:
Upper Denton 73 20.0
END DESCRIPTION:
XS GIS Cut Line= 3
        2210362.      7269916.49        2209779.        7269260.
      2208528.85      7268624.93
#Sta/Elev= 30
  4117.7 1053.14  4315.4 1048.38  4604.7 1034.02  4882.4 1015.27  4910.8 1015.69
    4925 1012.11  4981.9 1008.98  4992.4 1000.75    5004  997.44  5004.2  995.22
  5005.7  994.72    5015  995.22  5018.1 1000.58  5048.5 1008.86  5107.9 1007.92
  5159.8 1012.51  5187.7 1010.84  5363.2 1021.84  5599.3 1033.92  5732.9 1038.37
  5760.7 1036.32  5821.9 1042.96  5866.4 1040.38  5933.2 1046.75  6066.7 1049.42
  6222.5 1057.11  6239.1 1060.92  6274.4 1056.97  6296.8 1059.64  6397.9 1060.21
#Mann= 5 ,-1 , 0
  4117.7     .05       0  4604.7     .12       0  5004.2     .07       0
    5015     .12       0  5363.2     .05       0
Bank Sta=5004,5018.1
XS Rating Curve= 0 ,0
Exp/Cntr=0.3,0.1

Type RM Length L Ch R = 1 ,9183    ,439,439,439
BEGIN DESCRIPTION:
Upper Denton 73 19.0
END DESCRIPTION:
XS GIS Cut Line= 3
      2210431.48       7269895.7        2209979.        7268910.
      2209119.76      7267743.98
#Sta/Elev= 30
  3915.2 1053.43  4394.6 1026.69  4817.8 1009.79  4933.8 1006.13  4939.6 1005.02
  4949.1  996.83  4962.6  993.19  4968.1  995.52  4972.3  992.86  4973.8  992.36
  4983.3  992.86  4985.5  997.01    4991  995.31    4997 1001.53  5007.1 1006.29
  5021.7 1007.51    5028 1005.29  5307.9  1011.4  5449.8 1019.01  5721.3  1040.2
  5993.5 1050.41  6043.2 1047.85    6137 1051.49  6272.8 1048.95  6287.4 1052.52
  6316.5 1052.93  6322.9 1057.46  6329.1 1055.24  6337.5 1058.47  6448.2 1060.31
#Mann= 5 ,-1 , 0
  3915.2     .05       0  4817.8     .12       0  4949.1     .05       0
  4972.3    .033       0  4983.3     .05       0
Bank Sta=4968.1,4985.5
XS Rating Curve= 0 ,0
Exp/Cntr=0.3,0.1

Type RM Length L Ch R = 1 ,8744    ,427,427,427
BEGIN DESCRIPTION:
Upper Denton 73 18.0
END DESCRIPTION:
XS GIS Cut Line= 3
      2210743.96      7269833.15        2210279.        7268610.
      2209612.03      7267673.46
#Sta/Elev= 30
  3691.7 1042.91  3866.2 1036.06  4140.5 1018.51  4219.3 1017.73  4310.5  1009.4
  4775.6 1003.39  4875.6 1007.59  4955.1 1006.71  4968.1  998.68  4985.2  994.69
  4992.1  988.24  4993.6  987.74  5003.1  988.24  5007.6  991.33  5013.8 1002.46
  5028.5 1006.03  5064.2 1005.13  5072.8 1002.07  5078.9 1004.28  5093.7  993.06
  5099.8  992.92  5114.6 1002.99  5129.3 1004.46  5194.5 1006.57  5307.6 1016.04
  5316.2    1013  5397.5 1021.83  5509.2 1025.66  5889.2 1049.94    6150 1053.13
#Mann= 5 ,-1 , 0
  3691.7     .05       0  4875.6     .12       0  4992.1     .07       0
  5003.1     .12       0  5397.5     .05       0
Bank Sta=4992.1,5003.1
XS Rating Curve= 0 ,0
Exp/Cntr=0.3,0.1