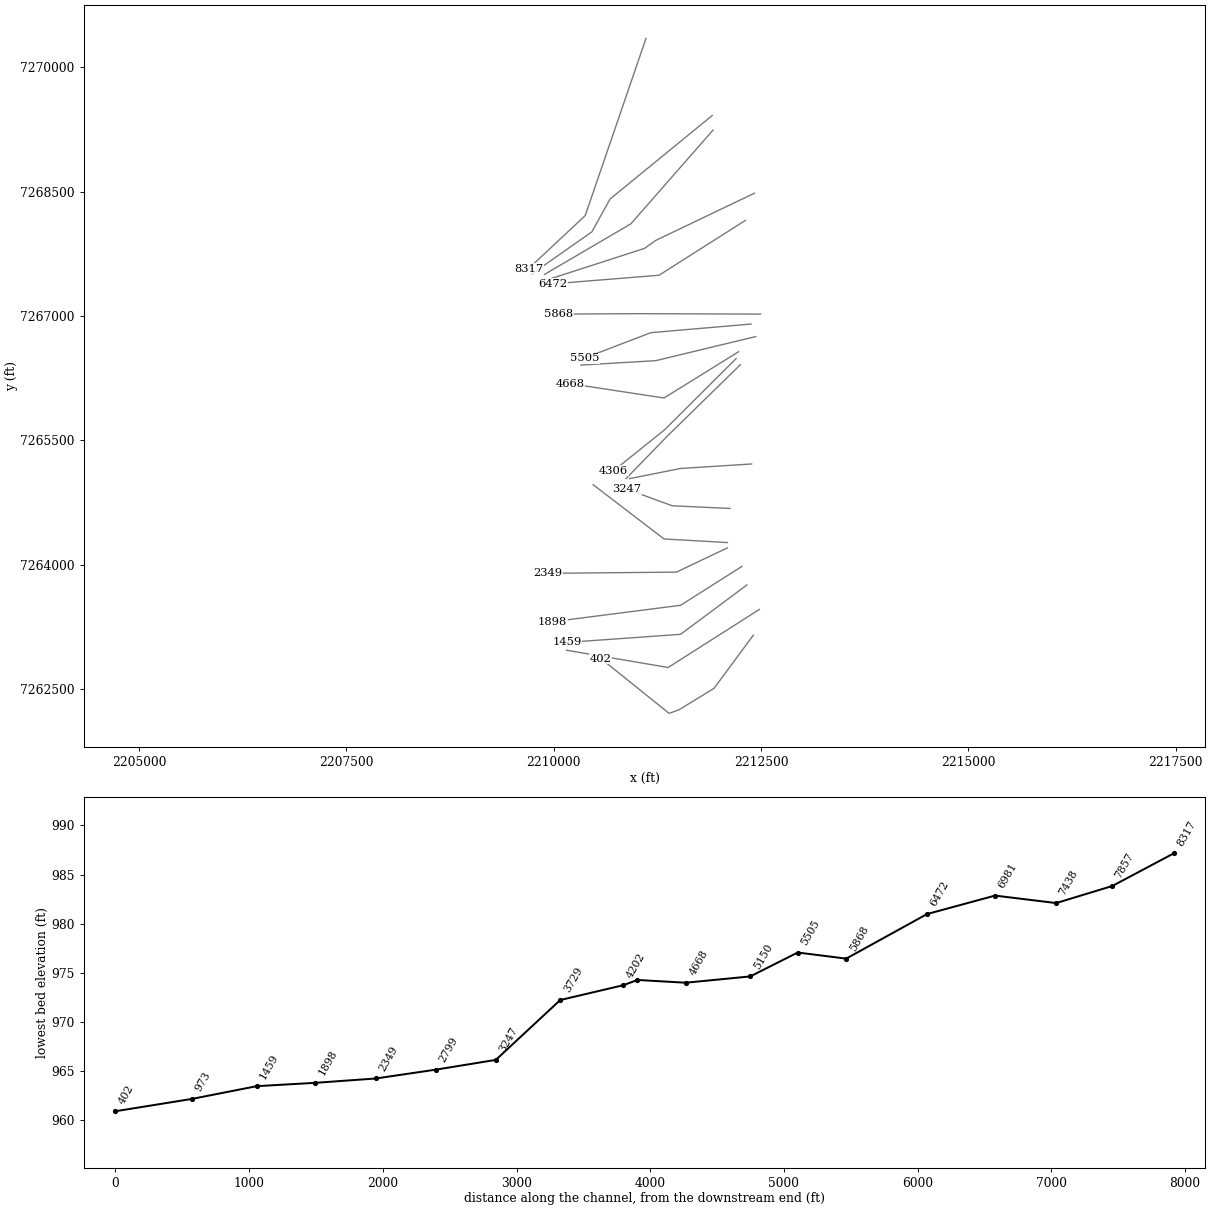
HEC-RAS study Upper Denton 73.prj: Upper Denton 73 Base Level Engineering

--- Upper Denton 73.g01 (geometry) --- (continued)

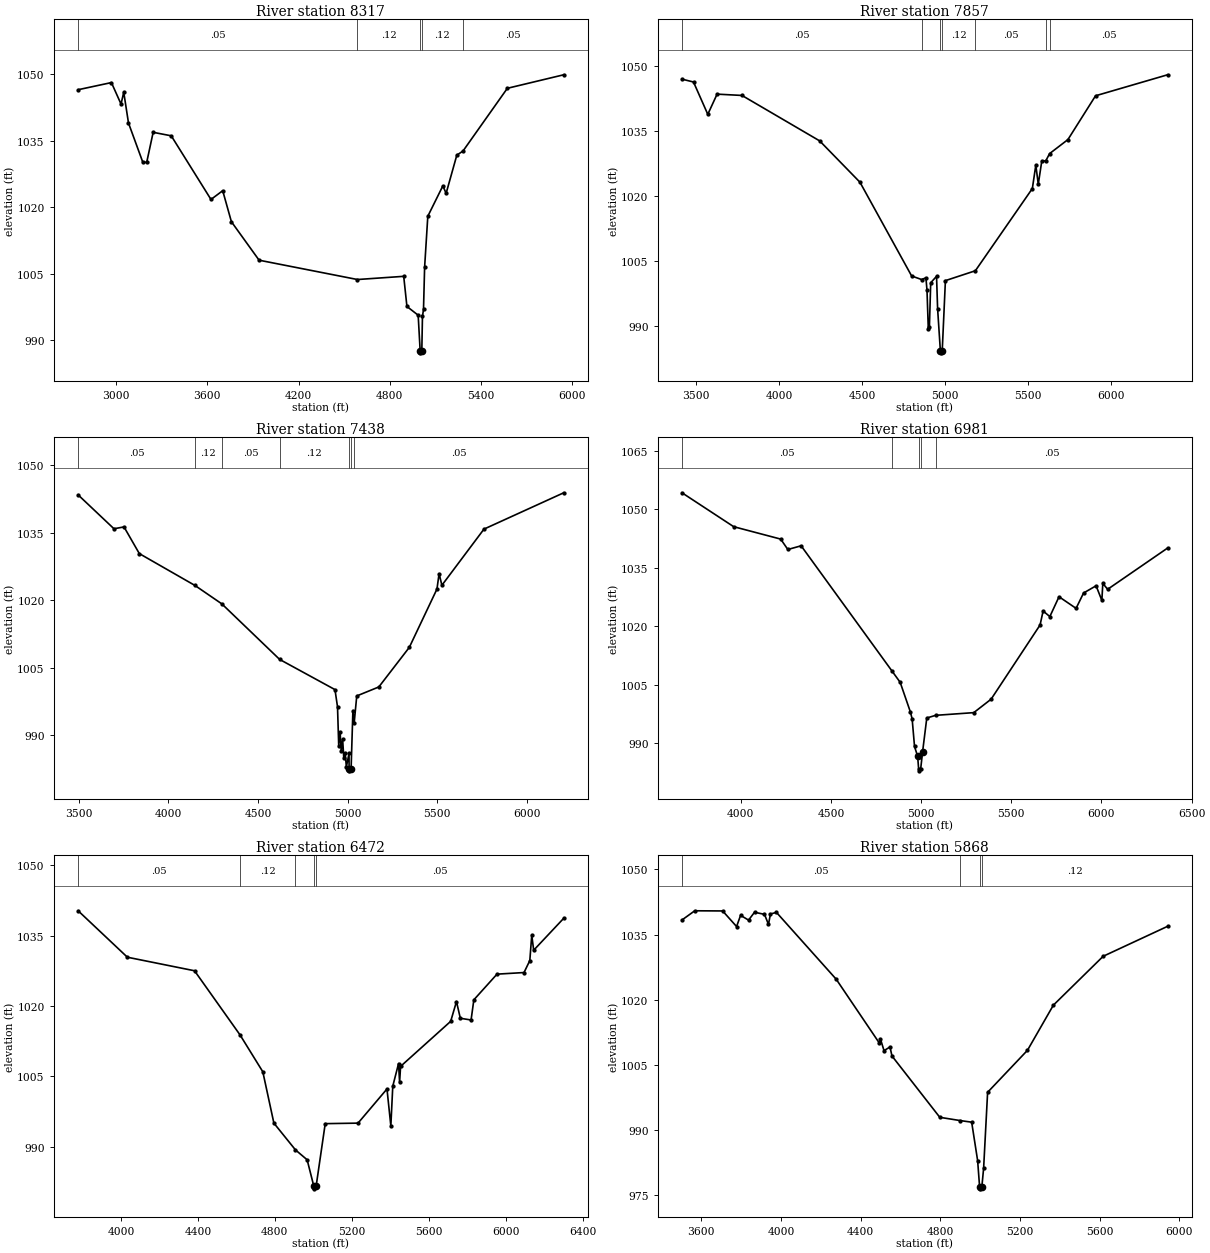
Type RM Length L Ch R = 1 ,8317    ,460,460,460
BEGIN DESCRIPTION:
Upper Denton 73 17.0
END DESCRIPTION:
XS GIS Cut Line= 3
      2211112.04      7270347.11        2210379.        7268210.
      2209695.34      7267569.28
#Sta/Elev= 30
  2749.4 1046.52  2968.4 1048.13  3031.8 1043.28  3049.6 1045.95  3080.9    1039
  3174.7  1030.2  3200.7 1030.12  3243.2 1036.91  3362.3 1036.12  3623.8 1021.76
    3701 1023.74  3758.2 1016.74  3940.5 1008.06  4587.9  1003.7  4892.4 1004.42
  4913.6  997.62  4987.6  995.65  5000.6  987.66  5002.1  987.16  5011.6  987.66
  5015.8  995.38  5022.7  996.95    5030 1006.46    5051 1017.97  5150.1 1024.83
  5171.6 1023.14    5242 1031.76  5282.7 1032.69  5574.6 1046.84  5945.7 1049.89
#Mann= 5 ,-1 , 0
  2749.4     .05       0  4587.9     .12       0  5000.6     .07       0
  5011.6     .12       0  5282.7     .05       0
Bank Sta=5000.6,5011.6
XS Rating Curve= 0 ,0
Exp/Cntr=0.3,0.1

Type RM Length L Ch R = 1 ,7857    ,419,419,419
BEGIN DESCRIPTION:
Upper Denton 73 16.0
END DESCRIPTION:
XS GIS Cut Line= 4
      2211910.62       7269416.5        2210679.        7268410.
      2210459.25      7268013.74        2209737.      7267506.78
#Sta/Elev= 30
    3415 1047.02  3484.4 1046.36  3570.5  1038.9  3626.5 1043.56  3776.5 1043.26
  4244.6 1032.77  4487.3 1023.23  4798.9 1001.58  4858.4 1000.77    4885 1001.15
  4891.4  998.27  4899.3  989.28  4905.8  989.74  4913.7 1000.01  4948.9 1001.51
  4955.3  994.04  4971.9  984.34  4973.5  983.84  4983.2  984.34  5002.3 1000.51
  5182.8 1002.79  5526.2 1021.77  5547.1 1027.18  5561.9 1022.77  5582.8 1028.06
  5607.4 1028.18  5630.1 1029.83  5740.5 1033.07    5907 1043.18  6341.1 1048.03
#Mann= 7 ,-1 , 0
    3415     .05       0  4858.4     .12       0  4971.9     .07       0
  4983.2     .12       0  5182.8     .05       0  5607.4     .12       0
  5630.1     .05       0
Bank Sta=4971.9,4983.2
XS Rating Curve= 0 ,0
Exp/Cntr=0.3,0.1

Type RM Length L Ch R = 1 ,7438    ,457,457,457
BEGIN DESCRIPTION:
Upper Denton 73 15.0
END DESCRIPTION:
XS GIS Cut Line= 3
      2211920.21      7269240.33        2210929.        7268110.
       2209888.9       7267500.7
#Sta/Elev= 30
  3496.7 1043.46  3696.6 1035.93  3752.6 1036.34    3838 1030.41  4148.6 1023.32
  4298.3 1019.23  4620.8 1006.88  4929.4 1000.17  4943.6  996.35  4950.3  987.74
  4957.8  990.78  4964.5  986.48  4972.1  989.18  4978.7  984.89  4986.3  986.06
    4993  982.97  5007.9  986.02  5008.1  982.61  5009.6  982.11  5019.4  982.61
  5029.4  995.51  5036.7  992.81  5050.9  998.76    5174 1000.76  5344.1 1009.56
  5498.4 1022.53  5510.2 1025.95  5525.9 1023.37  5760.5 1035.85  6205.5 1043.93
#Mann= 7 ,-1 , 0
  3496.7     .05       0  4148.6     .12       0  4298.3     .05       0
  4620.8     .12       0  5008.1     .07       0  5019.4     .12       0
  5036.7     .05       0
Bank Sta=5008.1,5019.4
XS Rating Curve= 0 ,0
Exp/Cntr=0.3,0.1

Type RM Length L Ch R = 1 ,6981    ,509,509,509
BEGIN DESCRIPTION:
Upper Denton 73 14.0
END DESCRIPTION:
XS GIS Cut Line= 4
      2212420.16      7268479.87        2211229.        7267910.
      2211092.06      7267813.22       2209946.2      7267443.42
#Sta/Elev= 30
  3674.3  1054.2    3961  1045.5  4221.4 1042.32  4261.2 1039.65  4334.8  1040.6
  4839.6 1008.41  4883.9 1005.58  4940.9  997.93  4950.4  996.16  4963.5  989.12
  4980.7   986.6  4986.3  983.37  4987.9  982.87  4997.6  983.37  5008.3  987.78
  5031.5  996.43  5080.9  997.11  5291.9   997.8  5388.1 1001.25  5659.5 1020.28
  5676.4 1023.87  5713.7 1022.44  5764.6 1027.53  5859.2 1024.55  5900.7 1028.49
  5970.1 1030.34  6002.1 1026.59  6007.4 1030.96  6034.2 1029.44  6366.5 1040.02
#Mann= 5 ,-1 , 0
  3674.3     .05       0  4839.6     .12       0  4986.3     .07       0
  4997.6     .12       0  5080.9     .05       0
Bank Sta=4980.7,5008.3
XS Rating Curve= 0 ,0
Exp/Cntr=0.3,0.1

Type RM Length L Ch R = 1 ,6472    ,604,604,604
BEGIN DESCRIPTION:
Upper Denton 73 13.0
END DESCRIPTION:
XS GIS Cut Line= 3
      2212310.82      7268151.77      2211269.14       7267490.3
       2209983.3      7267386.19
#Sta/Elev= 30
  3777.7 1040.32  4033.7 1030.41  4382.7 1027.52  4619.1 1013.84  4737.6 1005.97
  4795.2  995.01  4907.3   989.3    4968  987.19  5003.1  981.49  5004.6  980.99
  5014.5  981.49    5062   994.9  5232.5  995.01    5383  1002.3  5403.1  994.43
  5413.1 1002.89  5443.2 1007.73  5448.6 1003.72  5453.7 1007.12  5714.1 1016.73
  5744.2 1020.95  5764.3 1017.38  5820.1 1017.02  5834.5 1021.32  5954.9  1026.8
  6095.3 1027.14  6125.4  1029.7  6135.5 1035.11  6145.5  1031.9  6301.7 1038.72
#Mann= 5 ,-1 , 0
  3777.7     .05       0  4619.1     .12       0  4907.3     .05       0
  5003.1    .033       0  5014.5     .05       0
Bank Sta=5003.1,5014.5
XS Rating Curve= 0 ,0
Exp/Cntr=0.3,0.1

Type RM Length L Ch R = 1 ,5868    ,363,363,363
BEGIN DESCRIPTION:
Upper Denton 73 12.0
END DESCRIPTION:
XS GIS Cut Line= 3
      2212493.12      7267021.55       2210993.1      7267026.76
      2210055.64      7267021.55
#Sta/Elev= 30
  3502.7 1038.37  3566.8 1040.49  3706.8 1040.45  3776.8 1036.86  3796.8 1039.44
  3836.8 1038.34  3866.8 1040.15  3916.8 1039.67  3936.8 1037.36  3946.8 1039.75
  3976.8 1040.12  4276.8 1024.73  4493.9 1009.99  4498.9 1010.97  4516.8 1008.28
  4546.8 1009.13  4556.8 1007.05  4796.8  992.93  4899.1  992.18  4956.8  991.81
  4986.8  982.93  4996.5  976.96  4998.1  976.46    5008  976.96  5016.8  981.22
  5036.8  998.69  5236.8 1008.36  5366.8 1018.75  5616.8 1030.01  5940.2 1036.91
#Mann= 4 ,-1 , 0
  3502.7     .05       0  4899.1     .12       0  4996.5     .07       0
    5008     .12       0
Bank Sta=4996.5,5008
XS Rating Curve= 0 ,0
Exp/Cntr=0.3,0.1

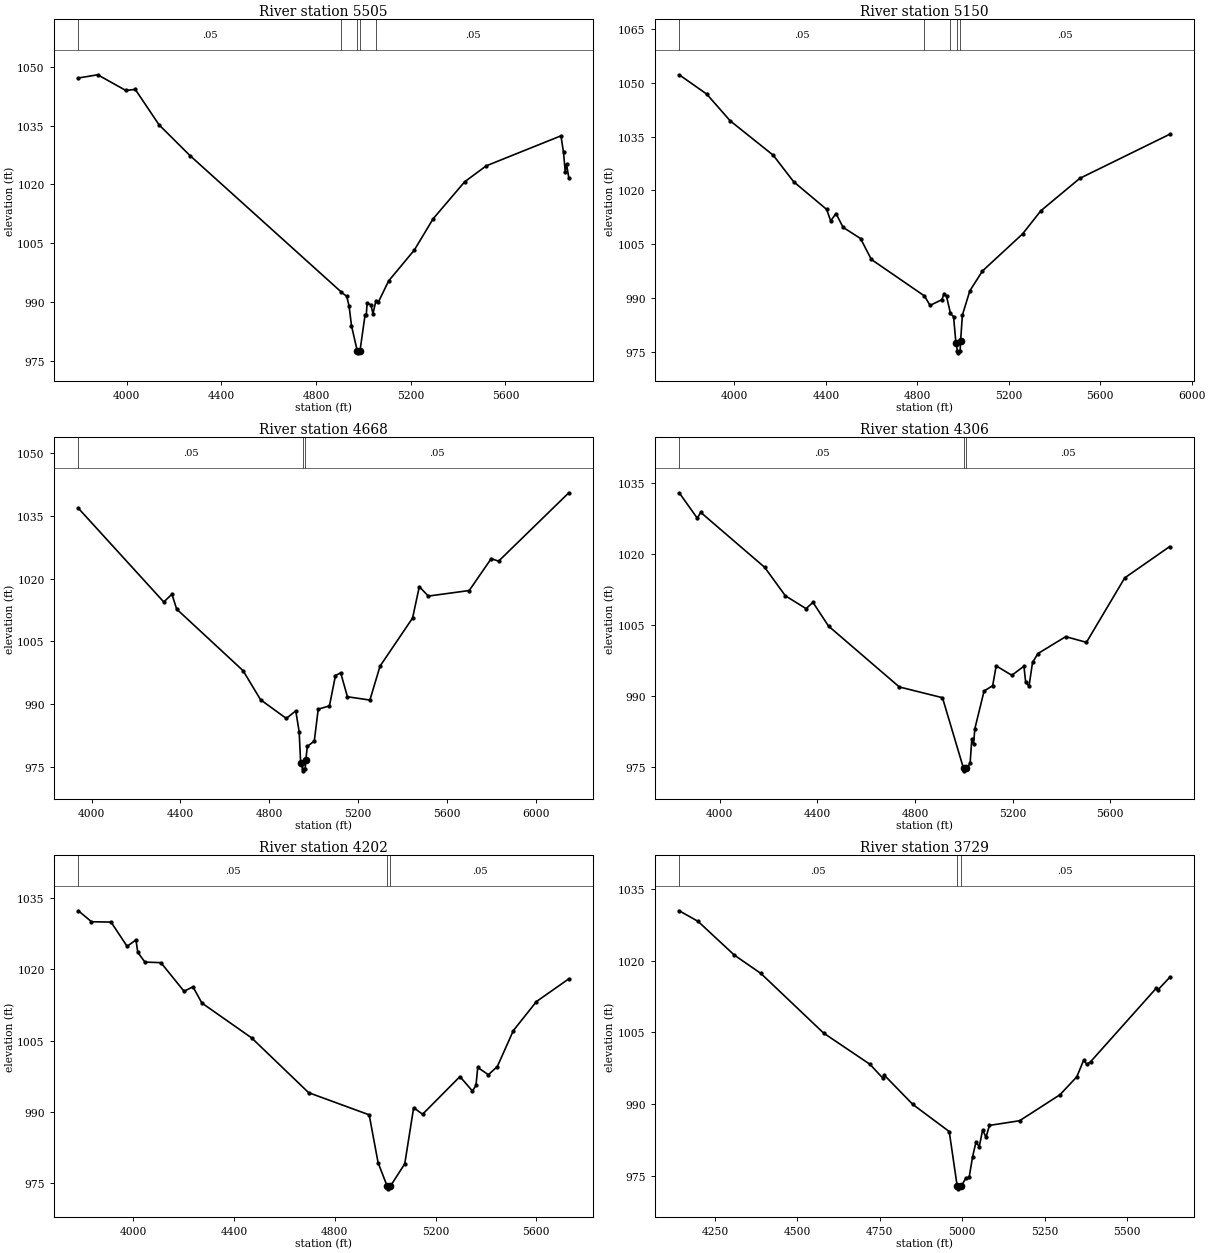
Type RM Length L Ch R = 1 ,5505    ,355,355,355
BEGIN DESCRIPTION:
Upper Denton 73 11.0
END DESCRIPTION:
XS GIS Cut Line= 3
      2212378.48      7266901.76      2211170.18      7266797.59
      2210368.11       7266490.3
#Sta/Elev= 30
    3796 1047.13  3877.7 1047.95  3996.2 1043.96  4036.4 1044.22  4136.7  1035.2
  4267.2 1027.37  4906.4  992.59  4929.7  991.46  4939.7  988.96  4949.7  983.99
  4974.1  977.58  4975.7  977.08  4985.6  977.58  5006.9  986.67  5012.1  986.67
  5015.7  989.67  5031.5  989.35  5040.4  987.08  5053.3  990.41  5063.6  990.05
  5106.4  995.39  5215.3 1003.29  5294.7 1011.26  5427.7 1020.67  5518.9 1024.74
  5834.6 1032.39  5845.3 1028.15  5852.6 1023.26    5858 1025.25  5867.7 1021.67
#Mann= 5 ,-1 , 0
    3796     .05       0  4906.4     .12       0  4974.1     .07       0
  4985.6     .12       0  5053.3     .05       0
Bank Sta=4974.1,4985.6
XS Rating Curve= 0 ,0
Exp/Cntr=0.3,0.1

Type RM Length L Ch R = 1 ,5150    ,482,482,482
BEGIN DESCRIPTION:
Upper Denton 73 10.0
END DESCRIPTION:
XS GIS Cut Line= 3
      2212435.77      7266750.71        2211229.        7266460.
      2210326.45      7266406.97
#Sta/Elev= 30
  3758.3 1052.22  3878.4 1046.85  3981.3 1039.37  4169.3 1029.79    4259 1022.38
    4403 1014.67  4420.8 1011.46  4444.1 1013.52    4475 1009.67  4551.7 1006.53
  4598.8  1000.7  4831.1  990.52  4855.6  987.88    4907  989.48  4917.3  991.18
  4927.6   990.4  4944.9  985.65  4958.5  984.72  4968.7  977.42  4975.5  975.15
  4977.1  974.65    4987  975.15  4989.3  977.98    4997  985.17  5029.6  991.95
  5084.8  997.48  5260.2 1007.82  5340.2 1014.28  5510.5 1023.32  5903.7 1035.62
#Mann= 5 ,-1 , 0
  3758.3     .05       0  4831.1     .12       0  4944.9     .05       0
  4975.5    .033       0    4987     .05       0
Bank Sta=4968.7,4989.3
XS Rating Curve= 0 ,0
Exp/Cntr=0.3,0.1

Type RM Length L Ch R = 1 ,4668    ,362,362,362
BEGIN DESCRIPTION:
Upper Denton 73 9.0
END DESCRIPTION:
XS GIS Cut Line= 3
      2212229.64      7266568.42        2211329.        7266010.
      2210193.61      7266182.95
#Sta/Elev= 30
  3940.3 1036.82  4324.9  1014.4  4361.5 1016.27  4382.8  1012.7  4681.7  997.98
  4760.8  991.01  4876.6  986.54  4919.1  988.36  4934.4  983.37  4941.2  975.84
    4950  974.51  4951.6  974.01  4961.5  974.51  4964.7  976.68  4971.1  979.86
  5002.5  981.13  5020.2  988.75  5070.8  989.55  5097.9  996.81  5121.4  997.45
  5151.7  991.73  5252.9  990.94  5298.6  999.06  5445.1 1010.56  5475.4 1018.07
  5515.9 1015.81  5700.2 1017.14  5799.1 1024.77  5832.3 1024.16  6148.5 1040.52
#Mann= 3 ,-1 , 0
  3940.3     .05       0    4950    .033       0  4961.5     .05       0
Bank Sta=4941.2,4964.7
XS Rating Curve= 0 ,0
Exp/Cntr=0.3,0.1

Type RM Length L Ch R = 1 ,4306    ,104,104,104
BEGIN DESCRIPTION:
Upper Denton 73 8.5
END DESCRIPTION:
XS GIS Cut Line= 3
      2212198.42      7266485.11      2211337.33      7265627.71
      2210719.19       7265130.9
#Sta/Elev= 30
  3834.9 1032.89  3908.8 1027.54    3923 1028.76  4184.6 1017.19  4269.5 1011.18
  4354.3 1008.48  4382.6 1009.79  4446.2  1004.8  4736.1  991.97  4912.9   989.7
  4999.1  974.79  5000.6  974.29  5010.6  974.79    5026  975.87  5033.1  981.05
  5040.2  979.95  5045.4  983.17  5083.2   991.1  5118.4  992.24  5132.8  996.41
  5196.8  994.43  5246.4  996.34  5253.2  993.11  5267.2   992.1  5281.6  997.14
  5303.9  999.01  5417.5 1002.57  5502.4 1001.37  5659.1 1014.95  5843.1 1021.55
#Mann= 3 ,-1 , 0
  3834.9     .05       0  4999.1    .033       0  5010.6     .05       0
Bank Sta=4999.1,5010.6
XS Rating Curve= 0 ,0
Exp/Cntr=0.3,0.1

Type RM Length L Ch R = 1 ,4202    ,473,473,473
BEGIN DESCRIPTION:
Upper Denton 73 8.0
END DESCRIPTION:
XS GIS Cut Line= 3
      2212250.49      7266412.19        2211379.        7265560.
      2210870.26      7265037.17
#Sta/Elev= 30
  3781.2 1032.34  3833.3 1030.03    3911 1029.96  3974.8 1024.85    4010  1026.2
  4017.2 1023.59  4045.5 1021.53  4109.1 1021.41  4201.1 1015.38  4236.4 1016.33
  4271.8 1012.91  4469.7 1005.55    4696  994.02  4936.5  989.35  4971.9  979.28
  5008.4  974.26    5010  973.76    5020  974.26  5077.9  979.04  5113.2  990.86
  5148.6  989.47  5297.1  997.41  5346.7  994.37  5360.8  995.55  5367.8  999.33
  5410.2   997.8  5445.7  999.53  5509.3  1007.1  5601.1 1013.22  5729.6    1018
#Mann= 3 ,-1 , 0
  3781.2     .05       0  5008.4    .033       0    5020     .05       0
Bank Sta=5008.4,5020
XS Rating Curve= 0 ,0
Exp/Cntr=0.3,0.1

Type RM Length L Ch R = 1 ,3729    ,482,482,482
BEGIN DESCRIPTION:
Upper Denton 73 7.0
END DESCRIPTION:
XS GIS Cut Line= 3
       2212385.9      7265214.26        2211529.        7265160.
        2210913.      7265037.39
#Sta/Elev= 30
  4141.8 1030.42  4198.8 1028.21    4309 1021.14  4389.2 1017.32  4579.6 1004.83
  4719.9  998.31    4759  995.41    4764  995.99  4850.1   989.9  4960.3  984.24
  4984.6  972.75  4986.2  972.25  4996.2  972.75  5010.6  974.47  5020.8  974.69
  5031.1  978.97  5041.2  981.96  5051.4  981.09  5061.6  984.58  5071.8  983.04
  5082.2  985.52  5173.7   986.5  5296.1  991.94  5347.1  995.69  5367.5  999.12
  5377.7  998.28  5388.8  998.84  5588.1 1014.24  5593.2 1013.89  5628.5 1016.48
#Mann= 3 ,-1 , 0
  4141.8     .05       0  4984.6    .033       0  4996.2     .05       0
Bank Sta=4984.6,4996.2
XS Rating Curve= 0 ,0
Exp/Cntr=0.3,0.1

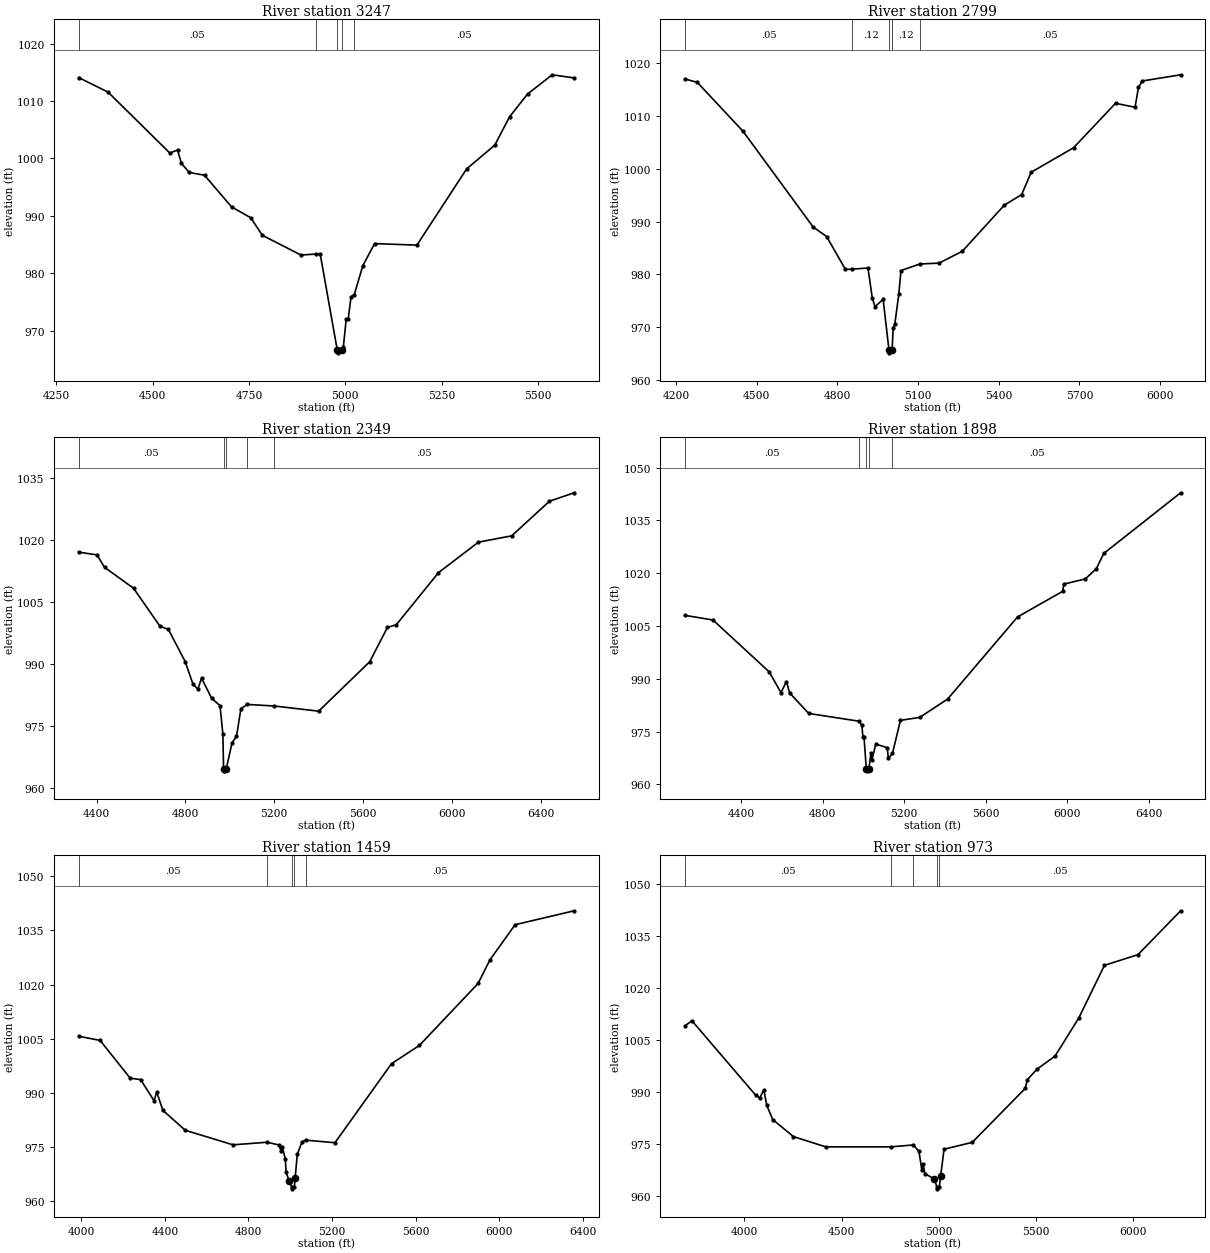
Type RM Length L Ch R = 1 ,3247    ,448,448,448
BEGIN DESCRIPTION:
Upper Denton 73 6.0
END DESCRIPTION:
XS GIS Cut Line= 3
      2212125.49       7264677.8        2211429.        7264710.
       2210875.5      7264912.17
#Sta/Elev= 30
  4307.7 1014.09  4384.3 1011.54  4544.4 1000.95  4564.5 1001.46  4574.5  999.17
  4594.5  997.57  4634.5  997.08  4704.6  991.58  4754.7  989.67  4784.7  986.62
  4884.8  983.19  4922.7  983.35  4934.9  983.35  4979.1  966.66  4980.7  966.16
  4990.7  966.66  4994.9  967.14  5002.4  972.06  5007.6  972.06  5014.9  975.91
  5023.3  976.29  5045.4  981.32    5076  985.18  5185.9  984.91    5315  998.18
  5388.2 1002.33  5426.5 1007.26  5473.4 1011.23  5537.2 1014.57  5594.2 1014.02
#Mann= 5 ,-1 , 0
  4307.7     .05       0  4922.7     .12       0  4979.1     .07       0
  4990.7     .12       0  5023.3     .05       0
Bank Sta=4979.1,4990.7
XS Rating Curve= 0 ,0
Exp/Cntr=0.3,0.1

Type RM Length L Ch R = 1 ,2799    ,450,450,450
BEGIN DESCRIPTION:
Upper Denton 73 5.0
END DESCRIPTION:
XS GIS Cut Line= 3
      2212094.21      7264266.34        2211329.        7264310.
      2210474.45      7264964.25
#Sta/Elev= 30
  4233.5 1016.98  4278.8 1016.35  4449.1 1007.08  4709.5  988.99  4759.6  987.18
  4829.7  980.96  4853.7  980.99  4913.5  981.23  4929.8  975.47  4939.9  973.89
  4969.9  975.31  4991.7  965.67  4993.3  965.17  5003.3  965.67  5007.2  969.89
  5013.5  970.66    5028  976.23  5036.3  980.74  5106.5  981.98  5177.6  982.14
  5264.4  984.39  5420.6  993.12    5485  995.11  5520.4  999.34  5678.2 1003.98
  5834.1 1012.39  5906.7 1011.63  5919.3 1015.38  5933.8 1016.61  6076.2 1017.78
#Mann= 5 ,-1 , 0
  4233.5     .05       0  4853.7     .12       0  4991.7     .07       0
  5003.3     .12       0  5106.5     .05       0
Bank Sta=4991.7,5003.3
XS Rating Curve= 0 ,0
Exp/Cntr=0.3,0.1

Type RM Length L Ch R = 1 ,2349    ,451,451,451
BEGIN DESCRIPTION:
Upper Denton 73 4.0
END DESCRIPTION:
XS GIS Cut Line= 3
      2212094.22       7264202.8        2211479.        7263910.
       2209927.6      7263895.51
#Sta/Elev= 30
  4318.7 1017.16  4401.6  1016.5  4435.3  1013.5  4566.1 1008.43  4685.1  999.25
  4723.2  998.46  4798.7  990.71  4833.9  985.23  4856.1  984.03  4872.4  986.69
  4917.8  981.84  4955.7  980.03  4968.7  973.13  4971.8  964.77  4973.5  964.27
    4984  964.77    5010  971.05    5030  972.59    5050  979.32  5078.5  980.33
  5200.5  979.95  5400.1   978.7  5630.1  990.64  5710.1  998.95  5750.1  999.61
  5940.1  1012.2  6120.1 1019.58  6270.1 1021.11  6440.1 1029.48  6551.5 1031.52
#Mann= 5 ,-1 , 0
  4318.7     .05       0  4971.8    .033       0    4984     .05       0
  5078.5     .12       0  5200.5     .05       0
Bank Sta=4971.8,4984
XS Rating Curve= 0 ,0
Exp/Cntr=0.3,0.1

Type RM Length L Ch R = 1 ,1898    ,439,439,439
BEGIN DESCRIPTION:
Upper Denton 73 3.0
END DESCRIPTION:
XS GIS Cut Line= 3
      2212268.23      7263978.82        2211529.        7263510.
      2209984.88      7263312.18
#Sta/Elev= 30
  4125.2 1008.01  4261.8 1006.71    4538  991.96  4595.6  986.07  4622.7  989.19
  4637.9     986    4732  980.14  4977.1  977.95  4992.9  976.76  4997.6  973.57
  5003.1  973.57  5014.6  964.33  5016.3  963.83  5026.8  964.33  5037.9  968.96
  5042.9  967.05  5061.1  971.46  5117.6  970.39  5122.6  967.37  5142.9  968.76
    5182  978.18  5276.9  979.02  5413.9  984.25  5756.7 1007.56  5978.5 1014.86
  5983.9  1016.9  6089.4 1018.38  6143.2 1021.26  6180.1 1025.62  6557.3 1042.86
#Mann= 5 ,-1 , 0
  4125.2     .05       0  4977.1     .12       0  5014.6     .07       0
  5026.8     .12       0  5142.9     .05       0
Bank Sta=5014.6,5026.8
XS Rating Curve= 0 ,0
Exp/Cntr=0.3,0.1

Type RM Length L Ch R = 1 ,1459    ,486,486,486
BEGIN DESCRIPTION:
Upper Denton 73 2.0
END DESCRIPTION:
XS GIS Cut Line= 3
       2212328.6      7263754.88        2211529.        7263160.
       2210156.7      7263062.17
#Sta/Elev= 30
  3986.8 1005.71  4089.7 1004.54  4233.6   994.1  4283.7   993.7  4347.8  987.86
  4360.8  990.25    4390  985.21  4497.3  979.69  4725.8  975.67  4889.8  976.38
  4946.9  975.61  4955.3  973.92  4961.5  975.18  4976.1  971.84  4980.3  968.13
  4993.4  965.75  5007.3  963.99  5009.1  963.49  5019.6  963.99  5023.5  966.47
  5033.5  973.01  5056.2  976.46  5073.2  976.96    5214  976.25  5484.7  998.11
  5618.2 1003.16  5899.1  1020.3  5955.9 1026.82  6076.2 1036.55  6359.2 1040.41
#Mann= 5 ,-1 , 0
  3986.8     .05       0  4889.8     .12       0  5007.3     .07       0
  5019.6     .12       0  5073.2     .05       0
Bank Sta=4993.4,5023.5
XS Rating Curve= 0 ,0
Exp/Cntr=0.3,0.1

Type RM Length L Ch R = 1 ,973     ,571,571,571
BEGIN DESCRIPTION:
Upper Denton 73 1.0
END DESCRIPTION:
XS GIS Cut Line= 3
      2212479.02      7263460.01        2211379.        7262760.
      2210152.72      7262968.22
#Sta/Elev= 30
  3695.7 1009.29  3731.3 1010.65  4058.1  989.24  4079.3  988.38  4100.4  990.75
  4115.7  986.27  4146.1  982.19  4252.8  977.26  4418.8   974.3    4753   974.3
  4869.5  974.85    4898  972.98  4913.2  967.52  4919.1  969.43  4928.4  966.56
  4976.7  965.07  4990.5  962.69  4992.2  962.19  5002.8  962.69  5009.7  965.99
  5027.2  973.63    5172   975.6  5444.2  991.16    5456  993.73  5504.5  996.69
    5598 1000.51  5719.7 1011.47  5851.6 1026.67    6024 1029.75  6243.4 1042.41
#Mann= 5 ,-1 , 0
  3695.7     .05       0    4753     .12       0  4869.5     .05       0
  4990.5    .033       0  5002.8     .05       0
Bank Sta=4976.7,5009.7
XS Rating Curve= 0 ,0
Exp/Cntr=0.3,0.1

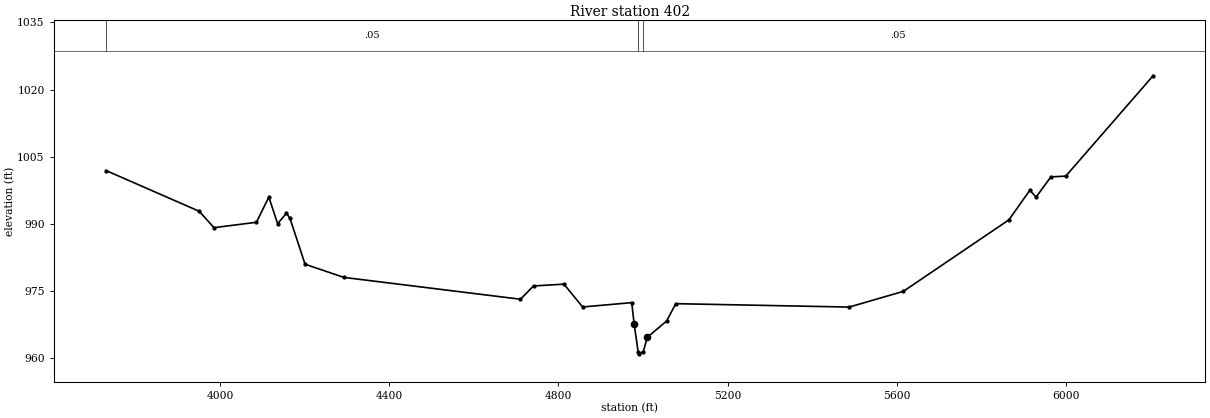
Type RM Length L Ch R = 1 ,402     ,0,0,0
BEGIN DESCRIPTION:
Upper Denton 73 0.5
END DESCRIPTION:
XS GIS Cut Line= 5
      2212406.24      7263149.27       2211932.3      7262508.66
      2211509.21      7262249.58      2211390.63      7262206.58
      2210567.73      7262868.02
#Sta/Elev= 30
  3730.9 1001.88  3950.5  992.81  3985.9  989.13  4086.1  990.34  4115.4  995.97
  4136.2  990.01  4157.1  992.38  4165.4   991.2    4201  980.97  4292.7  978.02
  4710.3  973.14  4741.1  976.11  4813.1  976.51  4857.2  971.41  4973.3  972.38
  4979.1  967.54  4988.4  961.44  4990.1  960.94  5000.7  961.44    5010  964.63
    5056  968.29  5077.3  972.15  5487.4  971.39  5615.4   974.9    5865  990.88
  5914.6  997.51    5929  995.94  5964.2 1000.48  5999.4 1000.65  6205.8 1023.07
#Mann= 3 ,-1 , 0
  3730.9     .05       0  4988.4    .033       0  5000.7     .05       0
Bank Sta=4979.1,5010
XS Rating Curve= 0 ,0
Exp/Cntr=0.3,0.1

Chan Stop Cuts=-1
Use User Specified Reach Order=0
Composite Channel Slope=5