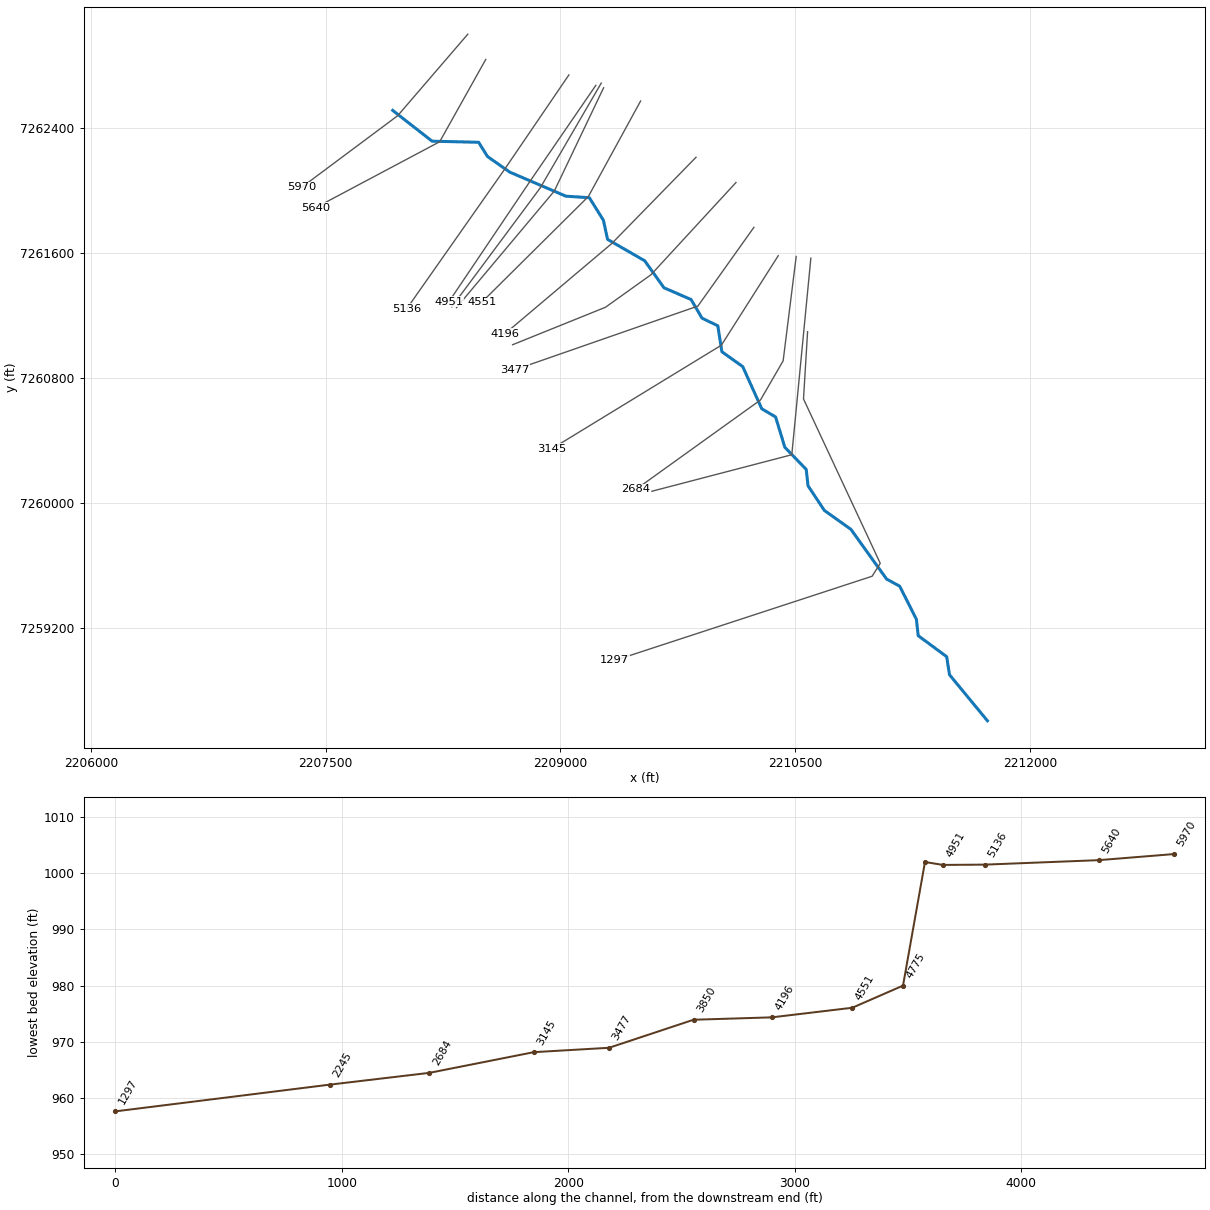
--- Upper Denton 77.prj (project) ---

Proj Title=Upper Denton 77 Base Level Engineering
Current Plan=p01
Default Exp/Contr=0.3,0.1
English Units
Geom File=g01
Flow File=f01
Plan File=p01
BEGIN DESCRIPTION:
Upper Denton 77
END DESCRIPTION:

--- Upper Denton 77.p01 (plan) ---

Plan Title=Multiple Run
Short Identifier=Multiple
Geom File=g01
Flow File=f01
Subcritical Flow
K Sum by GR= 0
Std Step Tol= 0.01
Critical Tol= 0.01
Num of Std Step Trials= 20
Max Error Tol= 0.3
Flow Tol Ratio= 0.001
Split Flow NTrial= 30
Split Flow Tol= 0.02
Split Flow Ratio= 0.02
Log Output Level= 0
Friction Slope Method= 1
Unsteady Friction Slope Method= 2
Unsteady Bridges Friction Slope Method= 1
Parabolic Critical Depth
Global Vel Dist=  1 , 1 , 1
Global Log Level= 0
CheckData=True
Encroach Param= -1, 0, 0, 0
BEGIN DESCRIPTION:
Multiple Run
END DESCRIPTION:

--- Upper Denton 77.f01 (steady flow) ---

Flow Title=Multiple
Number of Profiles=7
Profile Names=10-year,25-year,50-year,1pct_min,100-year,1pct_plu,500-year
River Rch & RM= Upper Denton 77,Reach-1,5970
     709     994    1235     762    1521    3036    2313
River Rch & RM= Upper Denton 77,Reach-1,2684
     815    1148    1430     884    1764    3520    2693
Boundary for River Rch & Prof#=Upper Denton 77,Reach-1,1
Up Type=0
Dn Type=3
Dn Slope=0.005
Boundary for River Rch & Prof#=Upper Denton 77,Reach-1,2
Up Type=0
Dn Type=3
Dn Slope=0.005
Boundary for River Rch & Prof#=Upper Denton 77,Reach-1,3
Up Type=0
Dn Type=3
Dn Slope=0.005
Boundary for River Rch & Prof#=Upper Denton 77,Reach-1,4
Up Type=0
Dn Type=3
Dn Slope=0.005
Boundary for River Rch & Prof#=Upper Denton 77,Reach-1,5
Up Type=0
Dn Type=3
Dn Slope=0.005
Boundary for River Rch & Prof#=Upper Denton 77,Reach-1,6
Up Type=0
Dn Type=3
Dn Slope=0.005
Boundary for River Rch & Prof#=Upper Denton 77,Reach-1,7
Up Type=0
Dn Type=3
Dn Slope=0.005

--- Upper Denton 77.g01 (geometry) ---

Geom Title=Existing Conditions

River Reach=Upper Denton 77,Reach-1
Reach XY= 30
      2207929.00      7262510.00      2208180.46      7262313.54
      2208477.74      7262306.52      2208534.64      7262215.65
      2208676.71      7262115.85      2209034.94      7261962.27
      2209185.48      7261952.30      2209275.17      7261808.41
      2209301.72      7261686.11      2209539.00      7261549.35
      2209662.29      7261376.63      2209835.34      7261301.97
      2209905.17      7261182.87      2210006.29      7261133.90
      2210032.08      7260968.31      2210165.39      7260873.24
      2210287.07      7260603.68      2210375.47      7260551.51
      2210434.52      7260357.57      2210571.14      7260216.17
      2210582.63      7260111.50      2210687.15      7259953.93
      2210856.14      7259833.84      2211084.65      7259515.63
      2211168.31      7259469.98      2211275.17      7259258.41
      2211286.74      7259153.55      2211468.49      7259019.81
      2211486.86      7258903.83      2211729.00      7258610.00

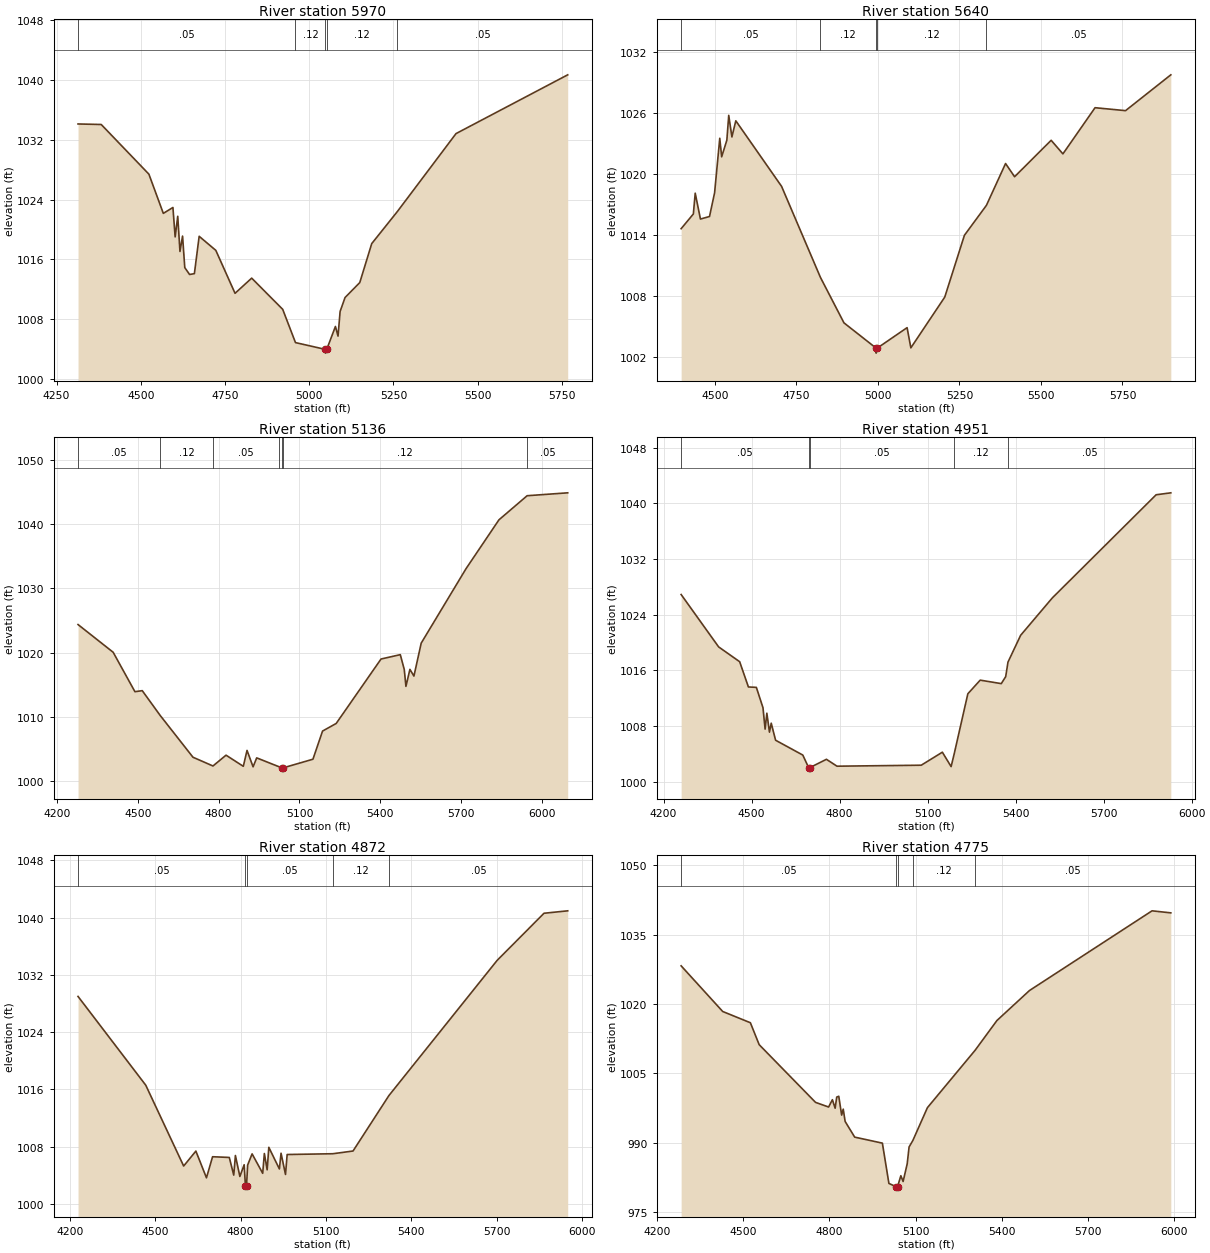
Type RM Length L Ch R = 1,5970,330,330,330
BEGIN DESCRIPTION:
Upper Denton 77 10.5
END DESCRIPTION:
XS GIS Cut Line= 3
      2208408.74      7262997.41      2207960.80      7262476.55
      2207346.26      7262018.25
#Sta/Elev= 30
  4313.8 1034.13  4382.7 1034.06  4524.2 1027.41  4567.0 1022.16  4595.5 1022.95
  4602.1 1019.01  4609.8 1021.77  4616.4 1017.06  4624.1 1019.12  4630.7 1014.90
  4644.9 1013.98  4659.2 1014.09  4673.4 1019.09  4722.8 1017.21  4779.9 1011.46
  4829.3 1013.49  4921.4 1009.31  4959.3 1004.86  5048.1 1003.95  5048.4 1003.45
  5052.1 1003.95  5077.9 1007.02  5085.6 1005.73  5091.8 1009.03  5106.4 1010.89
  5150.2 1012.90  5185.6 1018.11  5261.8 1022.41  5435.8 1032.84  5767.4 1040.71
#Mann=5,-1,0
  4313.8    0.05       0  4959.3    0.12       0  5048.1    0.07       0
  5052.1    0.12       0  5261.8    0.05       0
Bank Sta=5048.1,5052.1
Exp/Cntr=0.3,0.1

Type RM Length L Ch R = 1,5640,504,504,504
BEGIN DESCRIPTION:
Upper Denton 77 10.0
END DESCRIPTION:
XS GIS Cut Line= 3
      2208523.30      7262835.92      2208229.00      7262310.00
      2207434.80      7261888.03
#Sta/Elev= 30
  4396.4 1014.63  4433.9 1016.08  4439.6 1018.13  4455.6 1015.58  4483.4 1015.83
  4499.0 1018.16  4514.9 1023.54  4520.7 1021.71  4536.6 1023.35  4542.4 1025.80
  4552.1 1023.67  4564.1 1025.26  4704.5 1018.80  4823.7 1009.83  4895.9 1005.35
  4994.2 1002.87  4994.4 1002.37  4998.2 1002.87  5089.5 1004.88  5101.0 1002.89
  5205.0 1007.89  5265.3 1013.98  5332.8 1016.93  5391.5 1021.05  5419.2 1019.75
  5531.3 1023.34  5567.4 1022.00  5666.0 1026.55  5759.5 1026.26  5898.4 1029.79
#Mann=5,-1,0
  4396.4    0.05       0  4823.7    0.12       0  4994.2    0.07       0
  4998.2    0.12       0  5332.8    0.05       0
Bank Sta=4994.2,4998.2
Exp/Cntr=0.3,0.1

Type RM Length L Ch R = 1,5136,185,185,185
BEGIN DESCRIPTION:
Upper Denton 77 9.0
END DESCRIPTION:
XS GIS Cut Line= 3
      2209054.58      7262737.00      2208643.09      7262132.80
      2208019.10      7261243.61
#Sta/Elev= 30
  4278.1 1024.36  4408.5 1020.05  4489.3 1013.92  4516.5 1014.08  4583.3 1010.21
  4704.7 1003.73  4778.9 1002.37  4827.4 1004.05  4891.5 1002.32  4905.3 1004.79
  4927.8 1002.24  4941.2 1003.63  5024.1 1002.25  5034.6 1002.07  5034.9 1001.57
  5038.6 1002.07  5149.9 1003.42  5185.6 1007.80  5236.2 1008.98  5402.6 1019.00
  5474.1 1019.68  5488.9 1017.36  5495.0 1014.75  5509.8 1017.39  5524.7 1016.35
  5551.7 1021.47  5718.1 1033.05  5840.2 1040.64  5944.8 1044.39  6095.4 1044.84
#Mann=7,-1,0
  4278.1    0.05       0  4583.3    0.12       0  4778.9    0.05       0
  5024.1    0.12       0  5034.6   0.033       0  5038.6    0.12       0
  5944.8    0.05       0
Bank Sta=5034.6,5038.6
Exp/Cntr=0.3,0.1

Type RM Length L Ch R = 1,4951,79,79,79
BEGIN DESCRIPTION:
Upper Denton 77 8.0
END DESCRIPTION:
XS GIS Cut Line= 3
      2209226.53      7262670.04      2208811.50      7262065.00
      2208288.93      7261289.06
#Sta/Elev= 30
  4259.8 1026.91  4387.6 1019.38  4459.3 1017.25  4489.1 1013.62  4516.2 1013.56
  4538.8 1010.64  4546.0 1007.56  4552.0 1009.85  4560.9 1007.12  4566.9 1008.41
  4581.8 1005.96  4674.5 1003.83  4694.4 1002.02  4694.6 1001.52  4698.4 1002.02
  4755.1 1003.22  4791.0 1002.23  5078.2 1002.37  5150.2 1004.24  5180.1 1002.17
  5191.0 1004.08  5237.1 1012.64  5279.2 1014.60  5351.1 1014.10  5366.1 1015.10
  5373.9 1017.19  5417.1 1021.05  5525.0 1026.42  5878.9 1041.25  5929.0 1041.53
#Mann=5,-1,0
  4259.8    0.05       0  4694.4   0.033       0  4698.4    0.05       0
  5191.0    0.12       0  5373.9    0.05       0
Bank Sta=4694.4,4698.4
Exp/Cntr=0.3,0.1

Type RM Length L Ch R = 1,4872,97,97,97
BEGIN DESCRIPTION:
Upper Denton 77 7.6
END DESCRIPTION:
XS GIS Cut Line= 3
      2209261.50      7262684.99      2208871.50      7262015.00
      2208306.52      7261255.03
#Sta/Elev= 30
  4228.2 1028.99  4466.5 1016.57  4599.7 1005.27  4642.7 1007.36  4679.9 1003.62
  4701.4 1006.57  4760.2 1006.47  4775.9 1004.00  4781.7 1006.74  4797.4 1003.81
  4812.5 1005.45  4816.9 1002.54  4817.2 1002.04  4820.9 1002.54  4824.7 1005.40
  4840.4 1006.97  4877.7 1004.25  4883.5 1007.02  4893.4 1004.74  4899.2 1007.89
  4936.4 1004.86  4942.2 1007.06  4957.9 1004.09  4963.7 1006.88  5124.3 1006.99
  5195.4 1007.37  5321.7 1015.13  5702.2 1034.03  5867.0 1040.62  5950.4 1040.96
#Mann=5,-1,0
  4228.2    0.05       0  4816.9   0.033       0  4820.9    0.05       0
  5124.3    0.12       0  5321.7    0.05       0
Bank Sta=4816.9,4820.9
Exp/Cntr=0.3,0.1

Type RM Length L Ch R = 1,4775,224,224,224
BEGIN DESCRIPTION:
Upper Denton 77 7.5
END DESCRIPTION:
XS GIS Cut Line= 3
      2209276.50      7262654.99      2208961.50      7261995.00
      2208336.47      7261249.96
#Sta/Elev= 30
  4283.9 1028.26  4428.5 1018.39  4524.8 1015.96  4555.4 1011.22  4751.6  998.74
  4797.0  997.74  4810.2  999.32  4819.7  997.48  4825.3  999.89  4832.4 1000.06
  4842.4  995.99  4847.9  997.28  4854.5  994.62  4887.8  991.23  4984.1  989.93
  5006.8  981.22  5032.8  980.49  5033.0  979.99  5036.8  980.49  5048.4  982.89
  5056.2  981.64  5070.5  985.47  5077.0  989.10  5090.1  990.50  5140.8  997.60
  5306.7 1010.00  5382.7 1016.44  5495.9 1022.92  5922.4 1040.15  5987.7 1039.71
#Mann=5,-1,0
  4283.9    0.05       0  5032.8   0.033       0  5036.8    0.05       0
  5090.1    0.12       0  5306.7    0.05       0
Bank Sta=5032.8,5036.8
Exp/Cntr=0.3,0.1

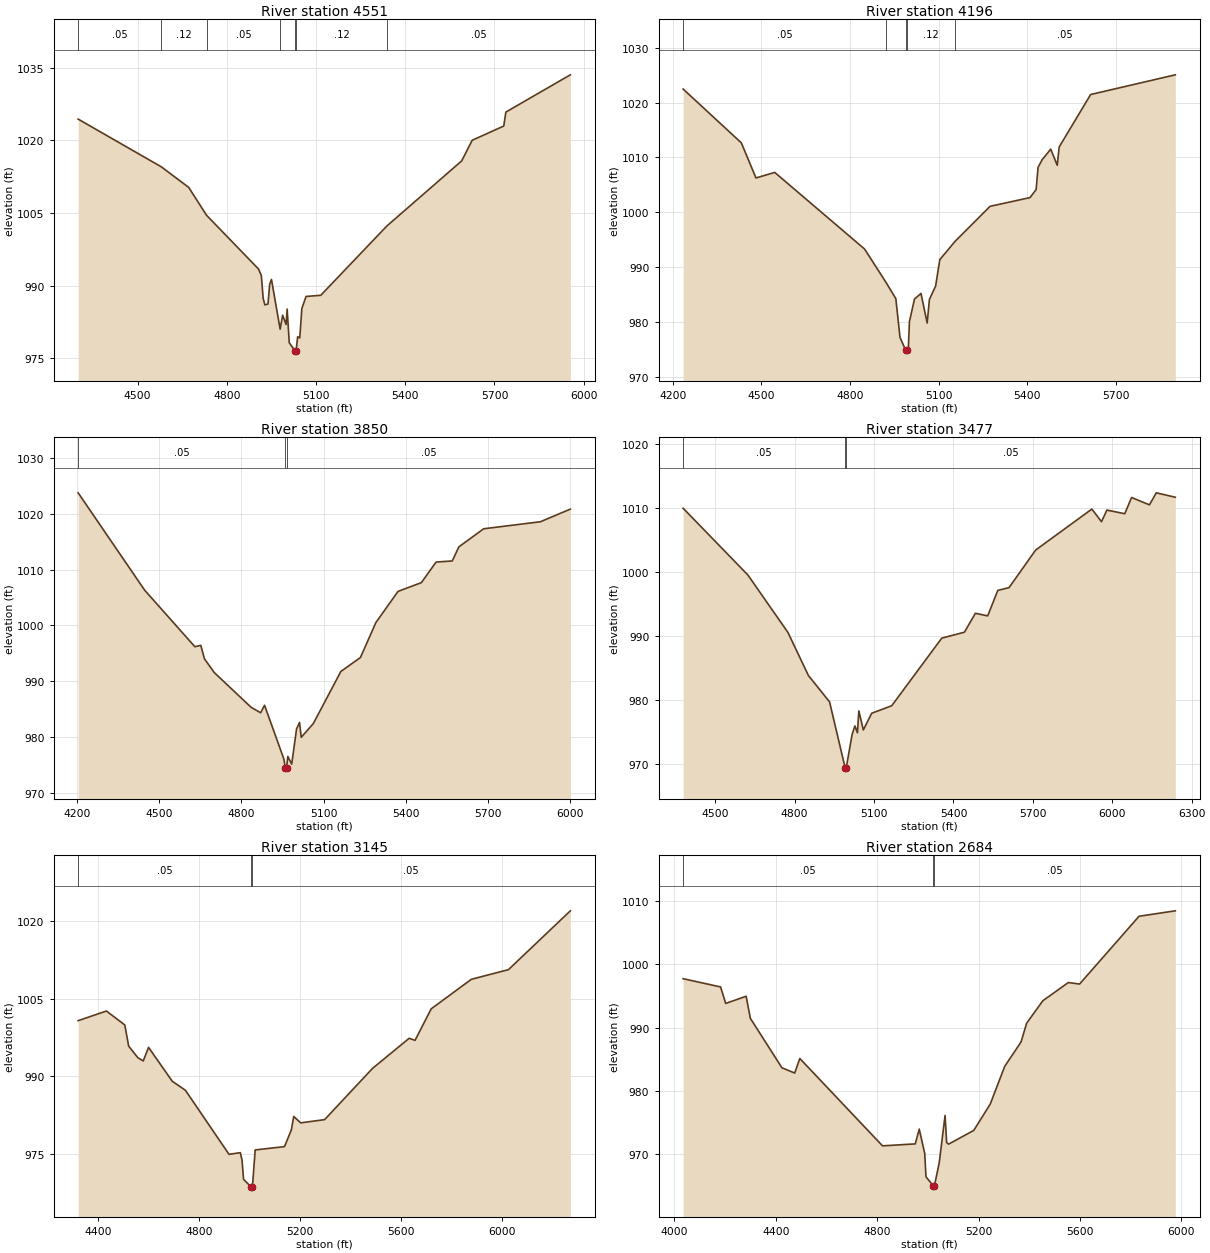
Type RM Length L Ch R = 1,4551,355,355,355
BEGIN DESCRIPTION:
Upper Denton 77 7.0
END DESCRIPTION:
XS GIS Cut Line= 3
      2209512.89      7262570.32      2209179.00      7261960.00
      2208497.88      7261284.45
#Sta/Elev= 30
  4300.2 1024.35  4580.3 1014.48  4672.0 1010.25  4732.1 1004.49  4906.3  993.43
  4916.1  992.10  4922.4  987.33  4928.1  986.00  4938.5  986.17  4944.2  990.25
  4950.3  991.25  4979.4  980.97  4987.8  983.86  4999.4  981.95  5003.0  985.14
  5010.0  978.19  5029.2  976.54  5029.5  976.04  5033.2  976.54  5038.3  979.43
  5045.4  979.17  5052.4  985.26  5066.6  987.74  5116.1  987.98  5338.2 1002.28
  5589.8 1015.72  5625.2 1019.98  5731.3 1022.92  5738.4 1025.80  5955.2 1033.49
#Mann=7,-1,0
  4300.2    0.05       0  4580.3    0.12       0  4732.1    0.05       0
  4979.4    0.12       0  5029.2    0.07       0  5033.2    0.12       0
  5338.2    0.05       0
Bank Sta=5029.2,5033.2
Exp/Cntr=0.3,0.1

Type RM Length L Ch R = 1,4196,346,346,346
BEGIN DESCRIPTION:
Upper Denton 77 6.0
END DESCRIPTION:
XS GIS Cut Line= 3
      2209867.07      7262210.94      2209329.00      7261660.00
      2208643.55      7261081.10
#Sta/Elev= 30
  4234.5 1022.47  4431.7 1012.66  4481.3 1006.26  4544.9 1007.27  4849.1  993.31
  4923.0  987.12  4955.1  984.26  4969.2  977.20  4988.5  974.83  4988.8  974.33
  4992.5  974.83  4997.5  975.17  5001.1  980.06  5018.3  984.19  5040.3  985.21
  5061.2  979.82  5068.9  984.13  5089.8  986.54  5104.1  991.38  5156.2  994.73
  5274.4 1001.09  5409.6 1002.68  5430.4 1004.15  5436.9 1008.20  5451.2 1009.62
  5479.8 1011.51  5501.9 1008.57  5508.4 1011.90  5615.0 1021.47  5901.8 1025.06
#Mann=5,-1,0
  4234.5    0.05       0  4923.0    0.12       0  4988.5    0.07       0
  4992.5    0.12       0  5156.2    0.05       0
Bank Sta=4988.5,4992.5
Exp/Cntr=0.3,0.1

Type RM Length L Ch R = 1,3850,373,373,373
BEGIN DESCRIPTION:
Upper Denton 77 5.0
END DESCRIPTION:
XS GIS Cut Line= 4
      2210122.27      7262049.47      2209579.00      7261460.00
      2209288.93      7261252.59      2208695.17      7261013.01
#Sta/Elev= 30
  4203.3 1023.74  4446.1 1006.32  4629.8  996.18  4651.4  996.42  4665.0  994.00
  4700.7  991.55  4835.1  985.34  4870.2  984.35  4884.4  985.70  4955.3  976.03
  4960.7  974.40  4960.9  973.90  4964.7  974.40  4969.5  976.53  4983.7  975.15
  5001.5  981.48  5012.3  982.62  5018.5  979.96  5062.7  982.42  5163.4  991.76
  5234.7  994.24  5291.2 1000.50  5372.2 1006.09  5457.6 1007.66  5511.2 1011.34
  5570.3 1011.54  5594.5 1014.06  5685.0 1017.30  5892.4 1018.56  6001.8 1020.82
#Mann=3,-1,0
  4203.3    0.05       0  4960.7   0.033       0  4964.7    0.05       0
Bank Sta=4960.7,4964.7
Exp/Cntr=0.3,0.1

Type RM Length L Ch R = 1,3477,332,332,332
BEGIN DESCRIPTION:
Upper Denton 77 4.0
END DESCRIPTION:
XS GIS Cut Line= 3
      2210236.85      7261763.02      2209879.00      7261260.00
      2208705.58      7260851.55
#Sta/Elev= 30
  4378.5 1010.02  4623.2  999.58  4774.5  990.60  4851.9  983.86  4931.9  979.73
  4990.8  969.40  4991.0  968.90  4994.8  969.40  5017.0  974.63  5027.6  975.97
  5037.2  974.90  5042.5  978.32  5059.4  975.34  5091.1  977.95  5166.8  979.13
  5355.8  989.70  5441.4  990.63  5482.9  993.59  5529.4  993.18  5567.6  997.17
  5610.0  997.60  5710.6 1003.48  5923.0 1009.89  5959.4 1007.91  5979.9 1009.73
  6047.3 1009.16  6073.1 1011.70  6140.6 1010.55  6166.4 1012.43  6238.3 1011.74
#Mann=3,-1,0
  4378.5    0.05       0  4990.8   0.033       0  4994.8    0.05       0
Bank Sta=4990.8,4994.8
Exp/Cntr=0.3,0.1

Type RM Length L Ch R = 1,3145,461,461,461
BEGIN DESCRIPTION:
Upper Denton 77 3.0
END DESCRIPTION:
XS GIS Cut Line= 3
      2210392.45      7261581.92      2210029.00      7261010.00
      2208944.55      7260347.56
#Sta/Elev= 30
  4321.8 1000.74  4433.7 1002.61  4506.5  999.91  4521.8  995.81  4558.2  993.57
  4579.4  992.94  4600.5  995.57  4694.5  989.00  4746.2  987.28  4919.0  974.86
  4963.9  975.18  4970.6  973.74  4976.6  970.02  5005.2  968.62  5005.4  968.12
  5009.2  968.62  5013.0  969.38  5022.6  975.71  5138.7  976.35  5165.9  979.60
  5175.2  982.19  5202.7  980.95  5297.5  981.58  5487.2  991.50  5632.2  997.33
  5655.5  996.93  5719.4 1003.03  5878.3 1008.75  6025.2 1010.62  6270.2 1022.01
#Mann=3,-1,0
  4321.8    0.05       0  5005.2   0.033       0  5009.2    0.05       0
Bank Sta=5005.2,5009.2
Exp/Cntr=0.3,0.1

Type RM Length L Ch R = 1,2684,439,439,439
BEGIN DESCRIPTION:
Upper Denton 77 2.0
END DESCRIPTION:
XS GIS Cut Line= 4
      2210507.04      7261576.71      2210423.71      7260910.06
      2210279.00      7260660.00      2209482.52      7260088.24
#Sta/Elev= 30
  4034.5  997.74  4182.3  996.43  4202.5  993.82  4283.1  994.96  4299.6  991.47
  4424.2  983.64  4474.6  982.80  4494.8  985.11  4820.9  971.28  4950.1  971.59
  4965.8  973.93  4987.4  970.07  4992.4  966.39  5021.5  964.93  5021.7  964.43
  5025.5  964.93  5044.5  968.58  5067.7  976.09  5073.8  971.81  5081.4  971.55
  5180.7  973.72  5245.7  977.88  5303.0  983.87  5367.3  987.72  5389.2  990.68
  5453.3  994.25  5553.9  997.13  5598.1  996.89  5832.7 1007.62  5975.7 1008.48
#Mann=3,-1,0
  4034.5    0.05       0  5021.5   0.033       0  5025.5    0.05       0
Bank Sta=5021.5,5025.5
Exp/Cntr=0.3,0.1

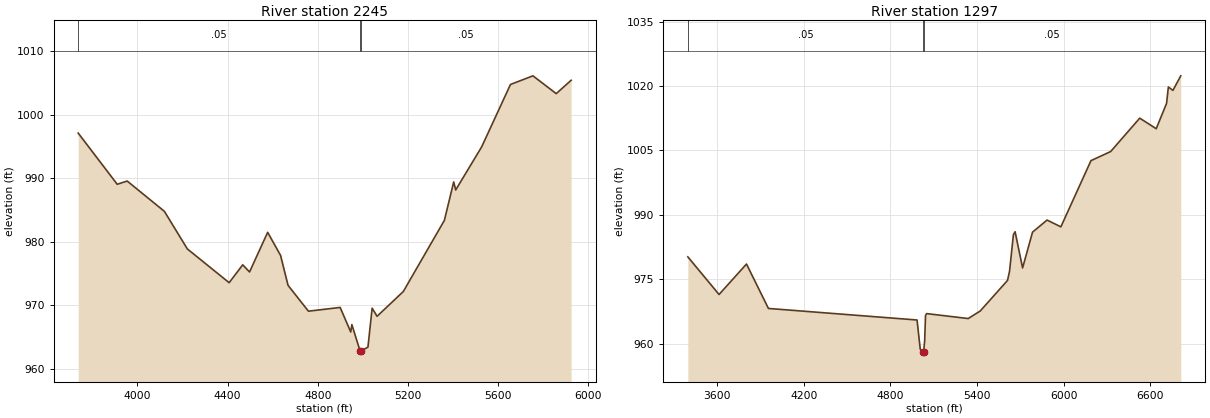
Type RM Length L Ch R = 1,2245,948,948,948
BEGIN DESCRIPTION:
Upper Denton 77 1.0
END DESCRIPTION:
XS GIS Cut Line= 3
      2210600.79      7261566.33      2210479.00      7260310.00
      2209585.16      7260076.72
#Sta/Elev= 30
  3737.5  997.08  3910.6  989.03  3954.8  989.54  4119.7  984.78  4221.8  978.86
  4407.0  973.56  4467.2  976.37  4497.4  975.24  4577.8  981.48  4635.0  977.85
  4668.2  973.14  4758.6  969.08  4899.3  969.67  4946.2  965.81  4951.2  966.97
  4987.6  962.83  4987.9  962.33  4991.7  962.83  5022.5  963.43  5041.1  969.55
  5063.0  968.28  5179.3  972.17  5361.4  983.35  5402.8  989.40  5411.7  988.14
  5526.8  994.91  5654.6 1004.72  5754.2 1006.08  5857.5 1003.28  5923.5 1005.38
#Mann=3,-1,0
  3737.5    0.05       0  4987.6   0.033       0  4991.7    0.05       0
Bank Sta=4987.6,4991.7
Exp/Cntr=0.3,0.1

Type RM Length L Ch R = 1,1297,0,0,0
BEGIN DESCRIPTION:
Upper Denton 77 0.5
END DESCRIPTION:
XS GIS Cut Line= 5
      2210579.84      7261096.09      2210553.80      7260666.38
      2211044.25      7259616.03      2210992.17      7259533.57
      2209347.22      7258995.38
#Sta/Elev= 30
  3395.1  980.22  3611.6  971.45  3801.9  978.55  3954.0  968.20  4984.5  965.51
  5006.8  958.69  5026.0  958.06  5026.3  957.56  5030.1  958.06  5037.4  960.72
  5043.3  966.57  5051.1  967.00  5339.2  965.85  5422.4  967.60  5611.8  974.73
  5626.0  976.89  5652.6  985.38  5664.4  986.07  5716.3  977.64  5785.3  985.98
  5886.1  988.79  5981.7  987.21  6190.5 1002.63  6327.0 1004.75  6528.6 1012.53
  6642.9 1010.07  6714.6 1015.97  6727.1 1019.79  6758.6 1019.00  6813.1 1022.39
#Mann=3,-1,0
  3395.1    0.05       0  5026.0    0.04       0  5030.1    0.05       0
Bank Sta=5026,5030.1
Exp/Cntr=0.3,0.1

Chan Stop Cuts=-1