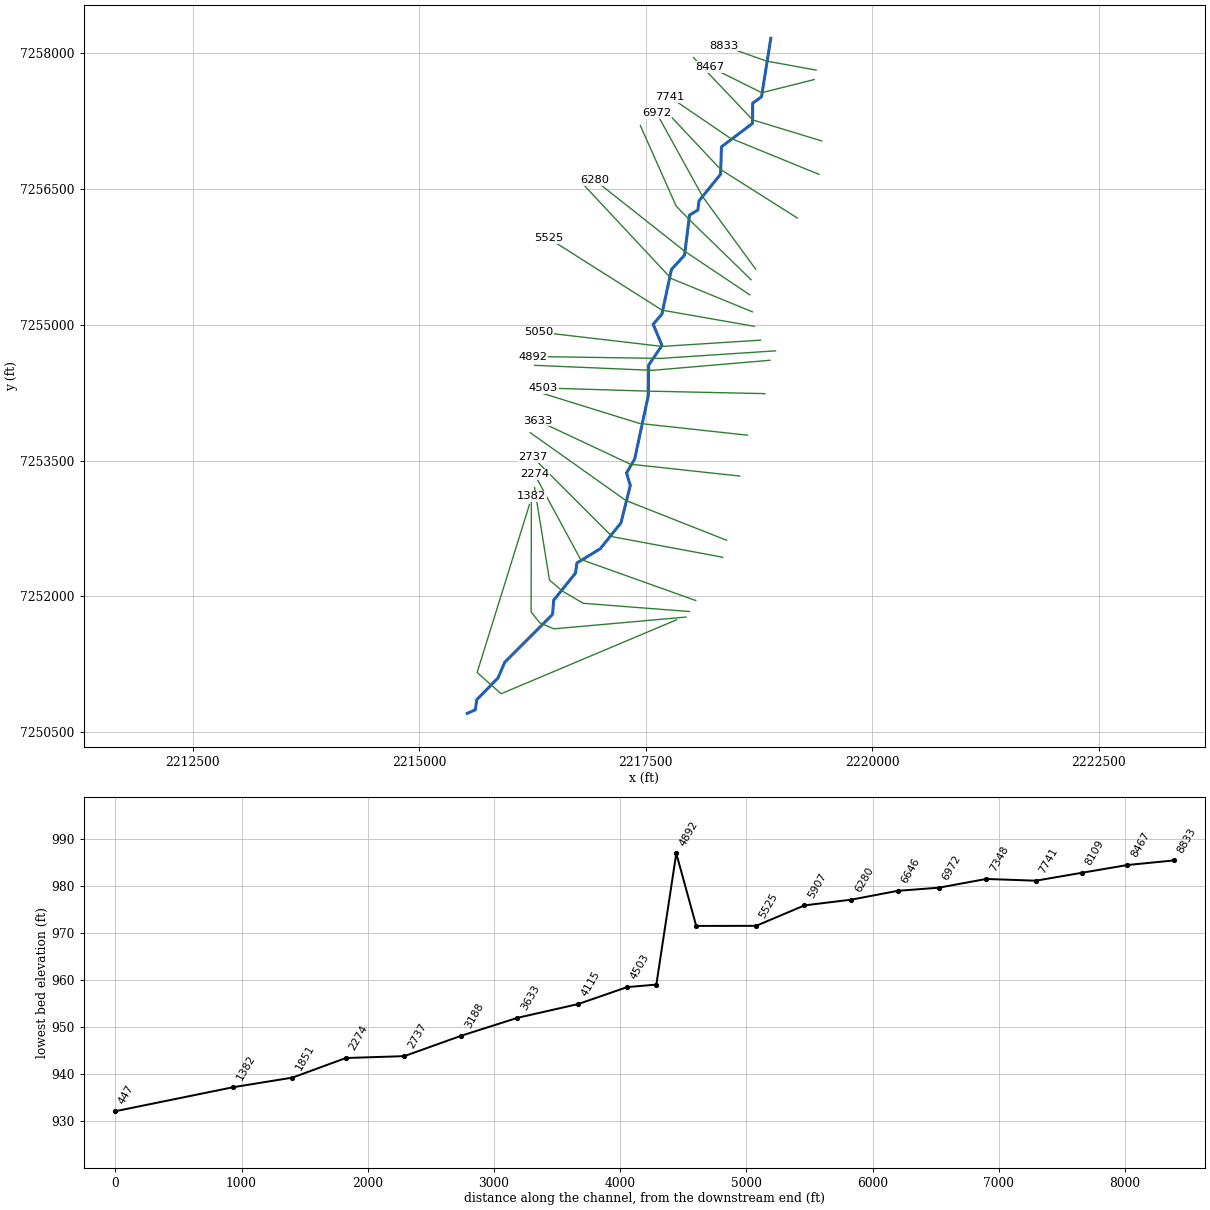
--- Upper Denton 79.prj (project) ---

Proj Title=Upper Denton 79 Base Level Engineering
Current Plan=p01
Default Exp/Contr=0.3,0.1
English Units
Geom File=g01
Flow File=f01
Plan File=p01
Y Axis Title=Elevation
X Axis Title(PF)=Main Channel Distance
X Axis Title(XS)=Station
BEGIN DESCRIPTION:
Upper Denton 79
END DESCRIPTION:
DSS Export Rating Curves= 0
DSS Export Rating Curve Sorted= 0
DSS Export Volume Flow Curves= 0
DXF OffsetX= 0
DXF OffsetY= 0
DXF ScaleX= 1
DXF ScaleY= 10

--- Upper Denton 79.p01 (plan) ---

Plan Title=Multiple Run
Short Identifier=Multiple
Geom File=g01
Flow File=f01
Subcritical Flow
K Sum by GR= 0
Std Step Tol= 0.01
Critical Tol= 0.01
Num of Std Step Trials= 20
Max Error Tol= 0.3
Flow Tol Ratio= 0.001
Split Flow NTrial= 30
Split Flow Tol= 0.02
Split Flow Ratio= 0.02
Log Output Level= 0
Friction Slope Method= 1
Unsteady Friction Slope Method= 2
Unsteady Bridges Friction Slope Method= 1
Parabolic Critical Depth
Global Vel Dist=  1 , 1 , 1
Global Log Level= 0
CheckData=True
Encroach Param= -1, 0, 0, 0
BEGIN DESCRIPTION:
Multiple Run
END DESCRIPTION:

--- Upper Denton 79.f01 (steady flow) ---

Flow Title=Multiple
Number of Profiles=7
Profile Names=10-year,25-year,50-year,1pct_min,100-year,1pct_plu,500-year
River Rch & RM= Upper Denton 79,Reach-1,8833
     596     820    1006     612    1222    2438    1809
River Rch & RM= Upper Denton 79,Reach-1,5050
     715     994    1227     752    1500    2993    2248
Boundary for River Rch & Prof#=Upper Denton 79,Reach-1,1
Up Type=0
Dn Type=3
Dn Slope=0.005
Boundary for River Rch & Prof#=Upper Denton 79,Reach-1,2
Up Type=0
Dn Type=3
Dn Slope=0.005
Boundary for River Rch & Prof#=Upper Denton 79,Reach-1,3
Up Type=0
Dn Type=3
Dn Slope=0.005
Boundary for River Rch & Prof#=Upper Denton 79,Reach-1,4
Up Type=0
Dn Type=3
Dn Slope=0.005
Boundary for River Rch & Prof#=Upper Denton 79,Reach-1,5
Up Type=0
Dn Type=3
Dn Slope=0.005
Boundary for River Rch & Prof#=Upper Denton 79,Reach-1,6
Up Type=0
Dn Type=3
Dn Slope=0.005
Boundary for River Rch & Prof#=Upper Denton 79,Reach-1,7
Up Type=0
Dn Type=3
Dn Slope=0.005

--- Upper Denton 79.g01 (geometry) ---

Geom Title=Existing Conditions
Program Version=4.10

River Reach=Upper Denton 79 ,Reach-1
Reach XY= 30
        2218879.        7258160.      2218776.98      7257515.69
      2218679.68      7257444.16      2218677.36      7257221.83
      2218334.45      7256962.47      2218325.46      7256661.46
       2218086.9      7256366.12      2218073.71      7256265.49
      2217982.48      7256208.74      2217926.76      7255765.91
      2217782.48      7255608.73      2217676.92      7255115.86
      2217580.97       7255004.1       2217678.3       7254770.7
      2217531.06      7254554.14      2217527.78       7254220.5
      2217376.76      7253515.93      2217287.05      7253363.32
      2217328.61      7253225.28      2217225.18      7252811.58
      2216996.05      7252526.49      2216739.51      7252369.81
      2216723.48      7252257.57      2216482.55      7251958.53
      2216471.19      7251803.79      2215942.47      7251273.57
      2215868.24      7251100.32      2215634.52      7250862.43
      2215618.74       7250749.9        2215529.        7250710.

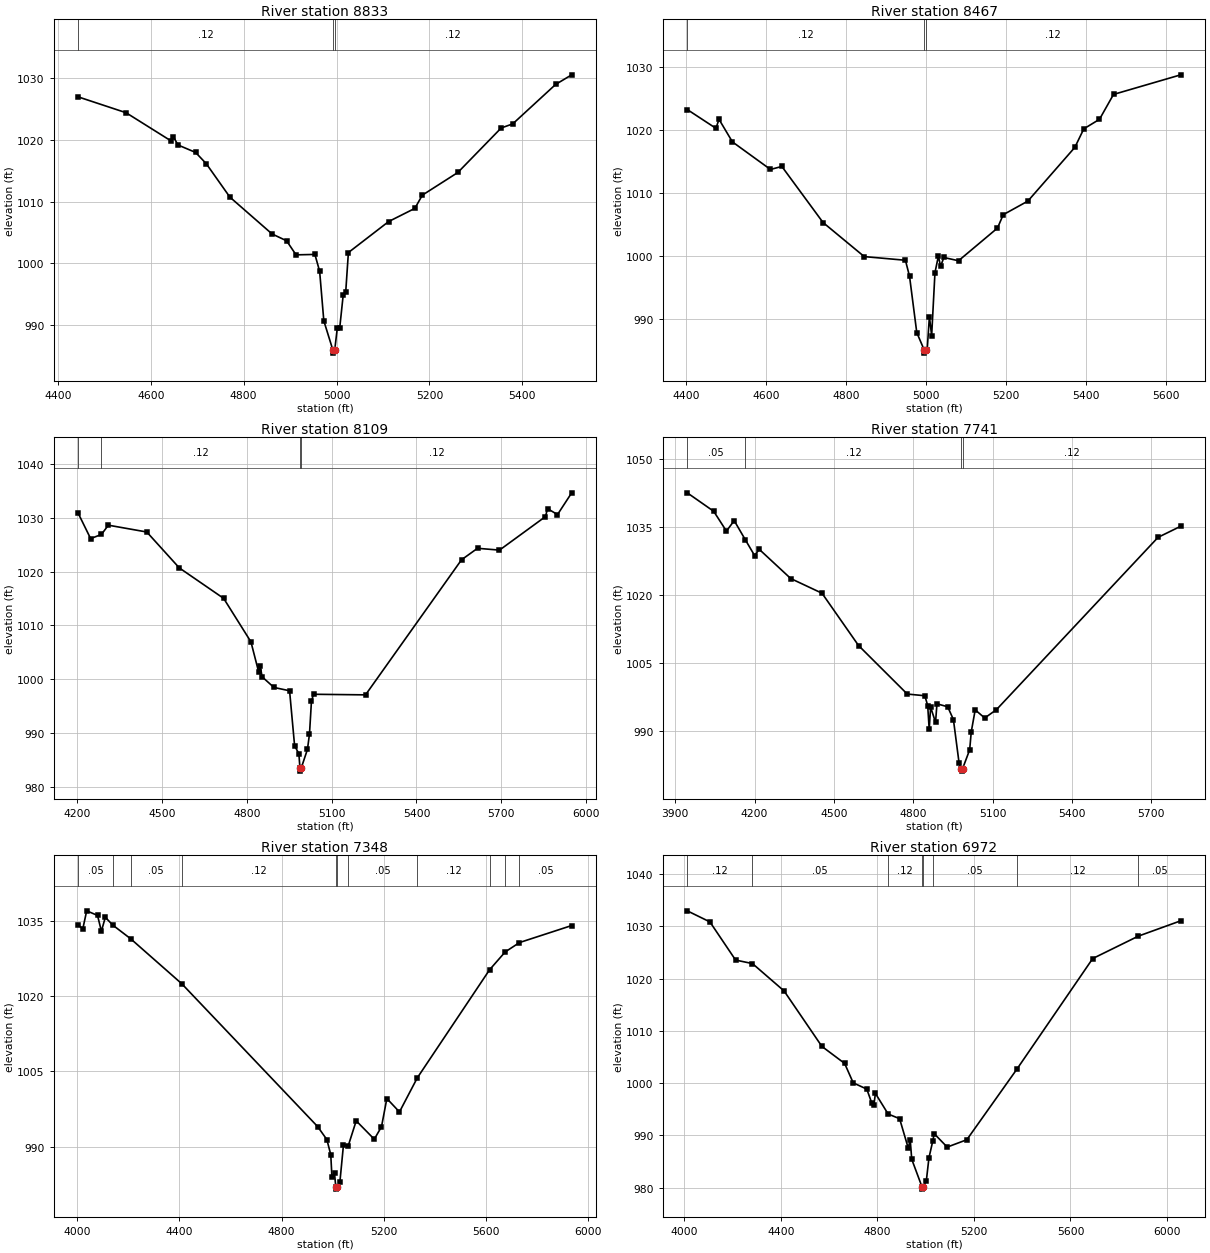
Type RM Length L Ch R = 1 ,8833    ,366,366,366
BEGIN DESCRIPTION:
Upper Denton 79 20.0
END DESCRIPTION:
XS GIS Cut Line= 3
      2219380.28      7257809.02        2218829.        7257910.
      2218355.94      7258078.13
#Sta/Elev= 30
  4443.8 1026.95  4546.8 1024.39  4643.4 1019.84  4648.5 1020.53  4658.6 1019.17
  4696.6 1017.96  4719.6 1016.13  4770.4 1010.73  4861.2 1004.77  4892.4 1003.67
  4912.8 1001.39  4953.4 1001.46  4963.6  998.74  4972.6  990.72  4992.1  985.99
  4992.3  985.49  4996.1  985.99  5001.7  989.61  5006.9  989.61  5014.4  994.94
  5019.7  995.31  5025.5 1001.76  5112.2 1006.78  5168.6 1008.91  5184.7 1011.05
  5261.2 1014.72  5354.5 1021.92  5379.3 1022.58  5471.8 1028.97  5506.3 1030.52
#Mann= 3 ,-1 , 0
  4443.8     .12       0  4992.1     .07       0  4996.1     .12       0
Bank Sta=4992.1,4996.1
XS Rating Curve= 0 ,0
Exp/Cntr=0.3,0.1

Type RM Length L Ch R = 1 ,8467    ,358,358,358
BEGIN DESCRIPTION:
Upper Denton 79 19.0
END DESCRIPTION:
XS GIS Cut Line= 3
      2219358.54      7257704.85        2218779.        7257560.
      2218208.42      7257843.73
#Sta/Elev= 30
    4403 1023.18  4474.7  1020.2  4482.4 1021.63  4515.9 1018.05  4611.2 1013.67
  4639.6 1014.15  4742.7 1005.25  4845.8  999.84  4948.8  999.26  4959.1  996.71
  4977.2  987.78  4995.8  985.02    4996  984.52  4999.8  985.02  5003.2  985.02
  5008.8  990.33  5014.4  987.29  5022.7   997.3  5031.2   999.9  5036.8  998.31
    5045   999.7  5081.6  999.18  5179.1 1004.37  5193.5 1006.49  5255.1 1008.65
  5372.7 1017.18  5395.1 1020.12  5434.3 1021.63  5469.4 1025.58  5637.6 1028.69
#Mann= 3 ,-1 , 0
    4403     .12       0  4995.8     .07       0  4999.8     .12       0
Bank Sta=4995.8,4999.8
XS Rating Curve= 0 ,0
Exp/Cntr=0.3,0.1

Type RM Length L Ch R = 1 ,8109    ,368,368,368
BEGIN DESCRIPTION:
Upper Denton 79 18.0
END DESCRIPTION:
XS GIS Cut Line= 3
      2219441.01      7257027.78        2218679.        7257260.
      2218026.12      7257947.89
#Sta/Elev= 30
    4204 1030.85  4247.9 1026.14  4286.1 1026.92  4310.6 1028.64  4446.5 1027.37
  4561.5 1020.69  4718.3 1015.02  4814.8 1006.93  4842.4 1001.27  4847.6 1002.45
  4854.2 1000.43  4896.1  998.45  4951.4  997.83  4969.2  987.59  4984.2  986.14
  4988.2  983.38  4988.4  982.88  4992.2  983.38  5014.6  986.93  5021.8  989.78
  5028.7  995.85    5036  997.18    5220  997.07  5559.4  1022.2    5616 1024.34
  5693.7    1024  5856.3 1030.24  5863.6 1031.72  5898.8 1030.61    5949 1034.66
#Mann= 4 ,-1 , 0
    4204     .05       0  4286.1     .12       0  4988.2     .07       0
  4992.2     .12       0
Bank Sta=4988.2,4992.2
XS Rating Curve= 0 ,0
Exp/Cntr=0.3,0.1

Type RM Length L Ch R = 1 ,7741    ,393,393,393
BEGIN DESCRIPTION:
Upper Denton 79 17.0
END DESCRIPTION:
XS GIS Cut Line= 3
      2219410.68      7256658.84        2218429.        7257060.
      2217762.68      7257512.98
#Sta/Elev= 30
  3945.5 1042.64  4045.5 1038.56  4093.6 1034.19    4123  1036.5    4165 1032.28
  4200.4 1028.76  4217.4 1030.18  4336.8 1023.71    4455 1020.47  4593.2 1008.92
  4777.5   998.2  4843.9  997.83  4854.7  995.67  4860.4  990.43  4865.8   995.3
  4884.4  991.95  4889.8  996.05  4930.4  995.39    4952  992.57  4973.6  982.89
  4982.4  981.68  4982.6  981.18  4986.4  981.68  5013.5  985.89  5019.5  989.87
  5034.4  994.71  5070.4  992.91  5114.8  994.76  5725.9 1032.81  5811.7 1035.26
#Mann= 4 ,-1 , 0
  3945.5     .05       0    4165     .12       0  4982.4     .07       0
  4986.4     .12       0
Bank Sta=4982.4,4986.4
XS Rating Curve= 0 ,0
Exp/Cntr=0.3,0.1

Type RM Length L Ch R = 1 ,7348    ,376,376,376
BEGIN DESCRIPTION:
Upper Denton 79 16.0
END DESCRIPTION:
XS GIS Cut Line= 3
       2219171.9       7256177.1        2218329.        7256710.
      2217687.58      7257392.33
#Sta/Elev= 30
  4003.3 1034.17  4021.3 1033.38  4036.5 1036.97  4078.9 1036.06  4094.2 1032.91
  4109.5 1035.69  4138.4 1034.14  4208.7 1031.41  4409.3 1022.44  4941.4  994.01
  4977.6  991.42  4992.9  988.42  4997.6   983.9  5007.6  984.72  5012.5  982.05
  5012.7  981.55  5016.5  982.05  5028.6  982.92  5042.8  990.41  5061.3  990.16
  5092.6  995.15  5163.4  991.49  5191.7  993.97  5212.7  999.59  5262.1  996.92
  5331.9  1003.7  5615.2 1025.23  5676.3 1028.78  5732.4 1030.65    5937 1034.04
#Mann= 11 ,-1 , 0
  4003.3     .05       0  4138.4     .12       0  4208.7     .05       0
  4409.3     .12       0  5012.5     .07       0  5016.5     .12       0
  5061.3     .05       0  5331.9     .12       0  5615.2     .05       0
  5676.3     .12       0  5732.4     .05       0
Bank Sta=5012.5,5016.5
XS Rating Curve= 0 ,0
Exp/Cntr=0.3,0.1

Type RM Length L Ch R = 1 ,6972    ,326,326,326
BEGIN DESCRIPTION:
Upper Denton 79 15.0
END DESCRIPTION:
XS GIS Cut Line= 3
      2218711.89      7255612.81        2218129.        7256410.
      2217618.35      7257335.51
#Sta/Elev= 30
  4012.4 1032.98  4106.2 1030.86  4212.7 1023.55  4282.5 1022.88  4413.5 1017.64
  4570.2 1007.02  4664.4 1003.76    4700 1000.04  4756.3  998.84  4777.2  996.13
  4785.7  995.83  4791.9  998.02  4844.7  994.07  4892.2  993.18  4927.8  987.57
  4936.2  989.12  4942.4  985.42  4984.4  980.19  4984.7  979.69  4988.4  980.19
  5002.8  981.25  5013.7  985.66  5029.8  988.95  5035.5   990.3  5089.4  987.74
  5170.7  989.15  5378.1 1002.66  5692.2 1023.84  5881.6 1028.14    6057 1031.07
#Mann= 8 ,-1 , 0
  4012.4     .12       0  4282.5     .05       0  4844.7     .12       0
  4984.4     .07       0  4988.4     .12       0  5029.8     .05       0
  5378.1     .12       0  5881.6     .05       0
Bank Sta=4984.4,4988.4
XS Rating Curve= 0 ,0
Exp/Cntr=0.3,0.1

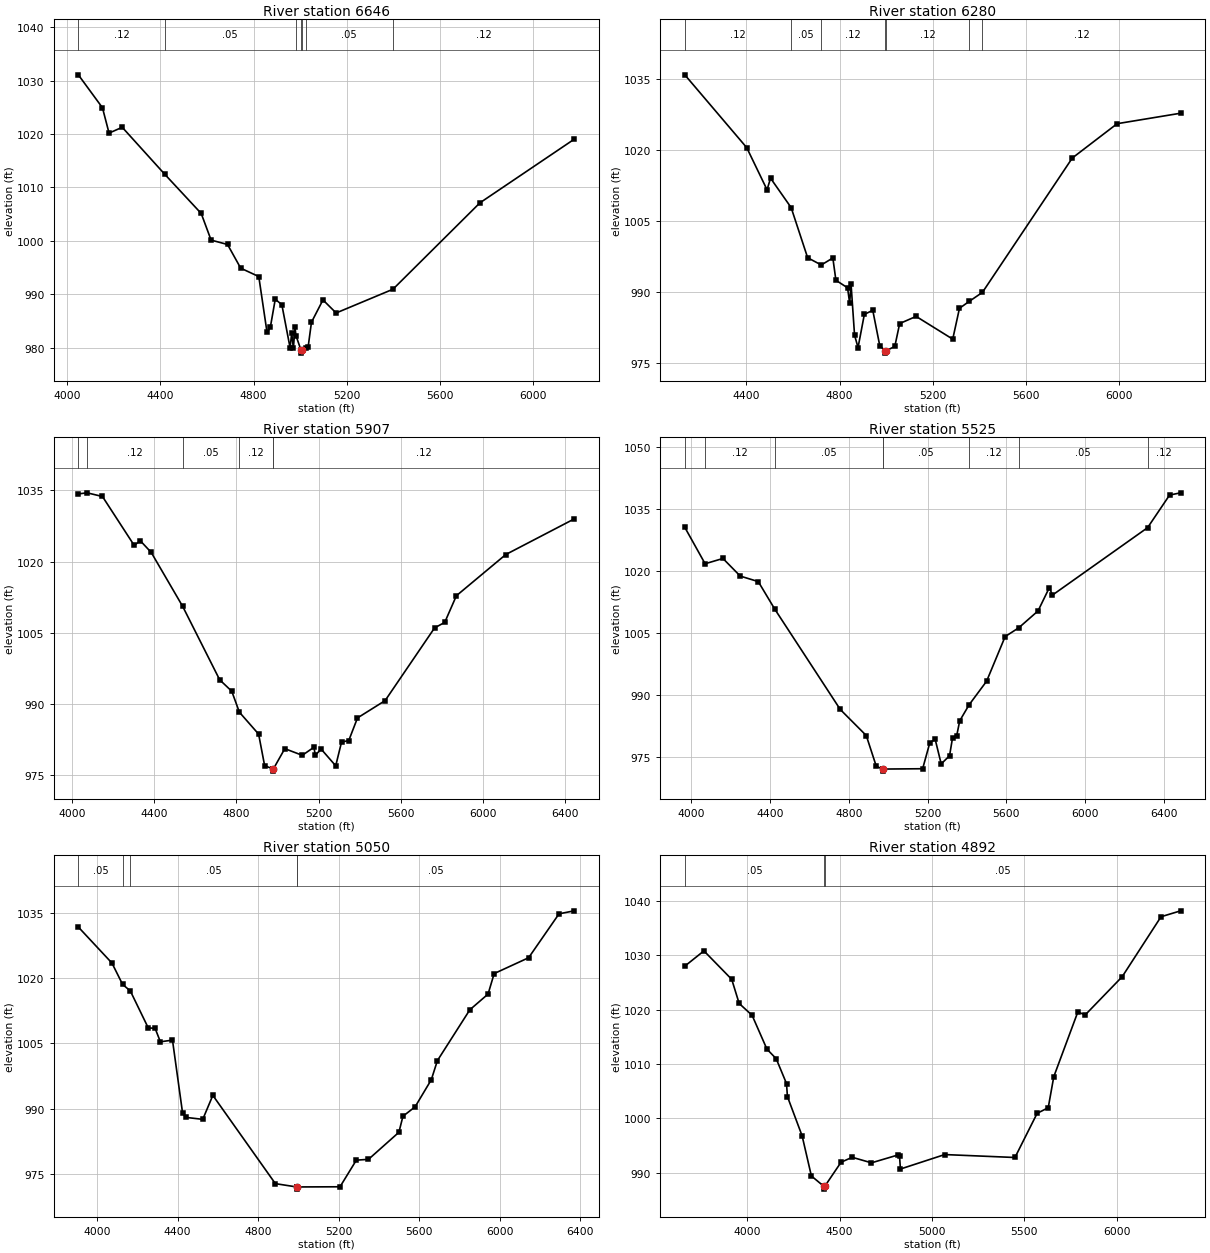
Type RM Length L Ch R = 1 ,6646    ,366,366,366
BEGIN DESCRIPTION:
Upper Denton 79 14.0
END DESCRIPTION:
XS GIS Cut Line= 4
       2218661.5      7255495.78        2217979.        7256160.
      2217835.12      7256308.27      2217439.78      7257196.06
#Sta/Elev= 30
    4047 1031.07  4150.7 1024.91    4179 1020.17  4235.6 1021.26  4417.4 1012.52
  4575.1 1005.14  4617.5 1000.16  4688.2  999.34  4744.8  994.91  4822.5  993.34
    4858  982.88  4872.1  983.85  4893.3   989.1  4921.6  988.08    4957  980.02
    4964  982.78  4971.2   979.9  4978.1  983.82  4982.3  982.29  5004.4  979.52
  5004.7  979.02  5008.4  979.52  5023.5  979.96  5034.7  980.22  5048.9   984.8
  5098.3  988.97  5154.9  986.53  5399.1  990.97  5772.9 1007.13  6177.8 1019.02
#Mann= 7 ,-1 , 0
    4047     .12       0  4417.4     .05       0  4982.3     .12       0
  5004.4     .07       0  5008.4     .12       0  5023.5     .05       0
  5399.1     .12       0
Bank Sta=5004.4,5008.4
XS Rating Curve= 0 ,0
Exp/Cntr=0.3,0.1

Type RM Length L Ch R = 1 ,6280    ,373,373,373
BEGIN DESCRIPTION:
Upper Denton 79 13.0
END DESCRIPTION:
XS GIS Cut Line= 3
      2218647.64      7255329.09        2217929.        7255810.
      2216939.28        7256593.
#Sta/Elev= 30
  4135.7 1035.87  4401.4  1020.5  4488.5 1011.62  4503.5 1014.06  4591.9 1007.85
  4662.6  997.28  4721.1  995.75  4770.7  997.23  4783.8  992.53  4833.8  990.93
  4842.8  987.69  4848.8  991.73  4863.8  980.94  4878.8  978.32  4905.8  985.32
  4941.9  986.19  4971.9  978.73  4995.4  977.65  4995.6  977.15  4999.4  977.65
  5036.5  978.57  5057.3  983.39  5127.9   984.9  5284.9   980.1  5313.8  986.61
    5356  988.08  5412.3  989.97  5797.8 1018.32  5990.1 1025.56  6262.4 1027.77
#Mann= 7 ,-1 , 0
  4135.7     .12       0  4591.9     .05       0  4721.1     .12       0
  4995.4     .07       0  4999.4     .12       0    5356     .05       0
  5412.3     .12       0
Bank Sta=4995.4,4999.4
XS Rating Curve= 0 ,0
Exp/Cntr=0.3,0.1

Type RM Length L Ch R = 1 ,5907    ,382,382,382
BEGIN DESCRIPTION:
Upper Denton 79 12.0
END DESCRIPTION:
XS GIS Cut Line= 3
      2218675.41       7255141.6        2217779.        7255510.
      2216793.82      7256564.83
#Sta/Elev= 30
  4031.2 1034.27  4073.6  1034.5  4148.5 1033.73  4303.1 1023.43  4332.5 1024.42
  4385.8 1021.96  4539.1 1010.58    4719  995.14  4777.7  992.74  4814.7  988.33
  4908.4  983.71  4937.7  977.06  4976.7  976.42    4977  975.92  4980.7  976.42
  5035.8  980.65  5120.8  979.25  5177.4  980.94  5184.3  979.27  5212.6  980.56
  5283.5  977.04  5311.8  982.03    5347  982.36  5389.5  987.12  5523.8  990.76
  5764.6 1006.07    5814 1007.23  5870.7 1012.84    6111 1021.51  6443.7    1029
#Mann= 6 ,-1 , 0
  4031.2     .05       0  4073.6     .12       0  4539.1     .05       0
  4814.7     .12       0  4976.7     .07       0  4980.7     .12       0
Bank Sta=4976.7,4980.7
XS Rating Curve= 0 ,0
Exp/Cntr=0.3,0.1

Type RM Length L Ch R = 1 ,5525    ,475,475,475
BEGIN DESCRIPTION:
Upper Denton 79 11.0
END DESCRIPTION:
XS GIS Cut Line= 3
      2218696.27      7254981.87        2217679.        7255160.
       2216425.4       7255954.1
#Sta/Elev= 30
  3967.6 1030.48  4070.7 1021.68  4161.2 1022.96  4249.1  1018.7  4340.5 1017.37
  4424.2 1010.72  4756.7  986.47  4888.7  980.17  4939.4  972.76  4971.2  972.07
  4971.4  971.57  4975.2  972.07  5174.9  972.15  5211.4  978.46  5238.5  979.25
    5269  973.32  5311.4  975.28  5326.6  979.63  5347.8  980.16  5363.1  983.73
  5410.7   987.6  5499.5   993.3  5593.6 1004.08  5662.8 1006.21  5760.5 1010.28
  5818.2 1015.94  5833.4  1014.1  6316.6  1030.4  6428.3 1038.28  6484.3 1038.82
#Mann= 8 ,-1 , 0
  3967.6     .05       0  4070.7     .12       0  4424.2     .05       0
  4971.2    .033       0  4975.2     .05       0  5410.7     .12       0
  5662.8     .05       0  6316.6     .12       0
Bank Sta=4971.2,4975.2
XS Rating Curve= 0 ,0
Exp/Cntr=0.3,0.1

Type RM Length L Ch R = 1 ,5050    ,158,158,158
BEGIN DESCRIPTION:
Upper Denton 79 10.0
END DESCRIPTION:
XS GIS Cut Line= 3
      2218765.72       7254829.1        2217679.        7254760.
      2216314.29      7254919.38
#Sta/Elev= 30
  3907.1 1031.73  4074.2 1023.45  4126.9 1018.56  4165.3 1017.06  4254.5 1008.56
  4288.3 1008.49  4314.6 1005.38  4374.8 1005.76  4424.9  989.02  4442.2  988.02
  4525.1  987.57  4575.2  993.08  4885.8  972.81  4991.5  972.05  4991.8  971.55
  4995.5  972.05    5207  972.09    5288   978.2  5348.4  978.39  5499.4   984.6
  5519.5  988.28    5580  990.45  5660.5  996.68  5690.7 1001.06  5851.8 1012.73
  5942.4 1016.34  5972.6 1021.04  6143.8 1024.68  6294.8 1034.76    6370 1035.45
#Mann= 5 ,-1 , 0
  3907.1     .05       0  4126.9     .12       0  4165.3     .05       0
  4991.5    .033       0  4995.5     .05       0
Bank Sta=4991.5,4995.5
XS Rating Curve= 0 ,0
Exp/Cntr=0.3,0.1

Type RM Length L Ch R = 1 ,4892    ,158,158,158
BEGIN DESCRIPTION:
Upper Denton 79 9.5
END DESCRIPTION:
XS GIS Cut Line= 3
      2218932.33      7254711.04      2217661.51      7254627.71
      2216252.91      7254648.53
#Sta/Elev= 30
    3663 1028.02  3766.5 1030.83  3916.9 1025.59    3957 1021.16  4027.1 1018.97
  4107.3 1012.75  4157.4 1010.99  4213.2 1006.42  4218.2 1004.02  4297.7  996.79
  4347.8  989.41  4415.9  987.49  4416.2  986.99  4419.9  987.49  4508.1  991.93
  4568.3  992.85  4672.9  991.83  4818.8   993.3  4824.5  993.13  4829.5  990.69
  5069.1  993.35  5449.1  992.81  5569.1 1000.94  5629.1 1001.97  5659.1 1007.68
  5789.2 1019.59  5829.2 1019.05  6029.2 1026.08  6239.2 1037.11  6345.3  1038.2
#Mann= 3 ,-1 , 0
    3663     .05       0  4415.9    .033       0  4419.9     .05       0
Bank Sta=4415.9,4419.9
XS Rating Curve= 0 ,0
Exp/Cntr=0.3,0.1

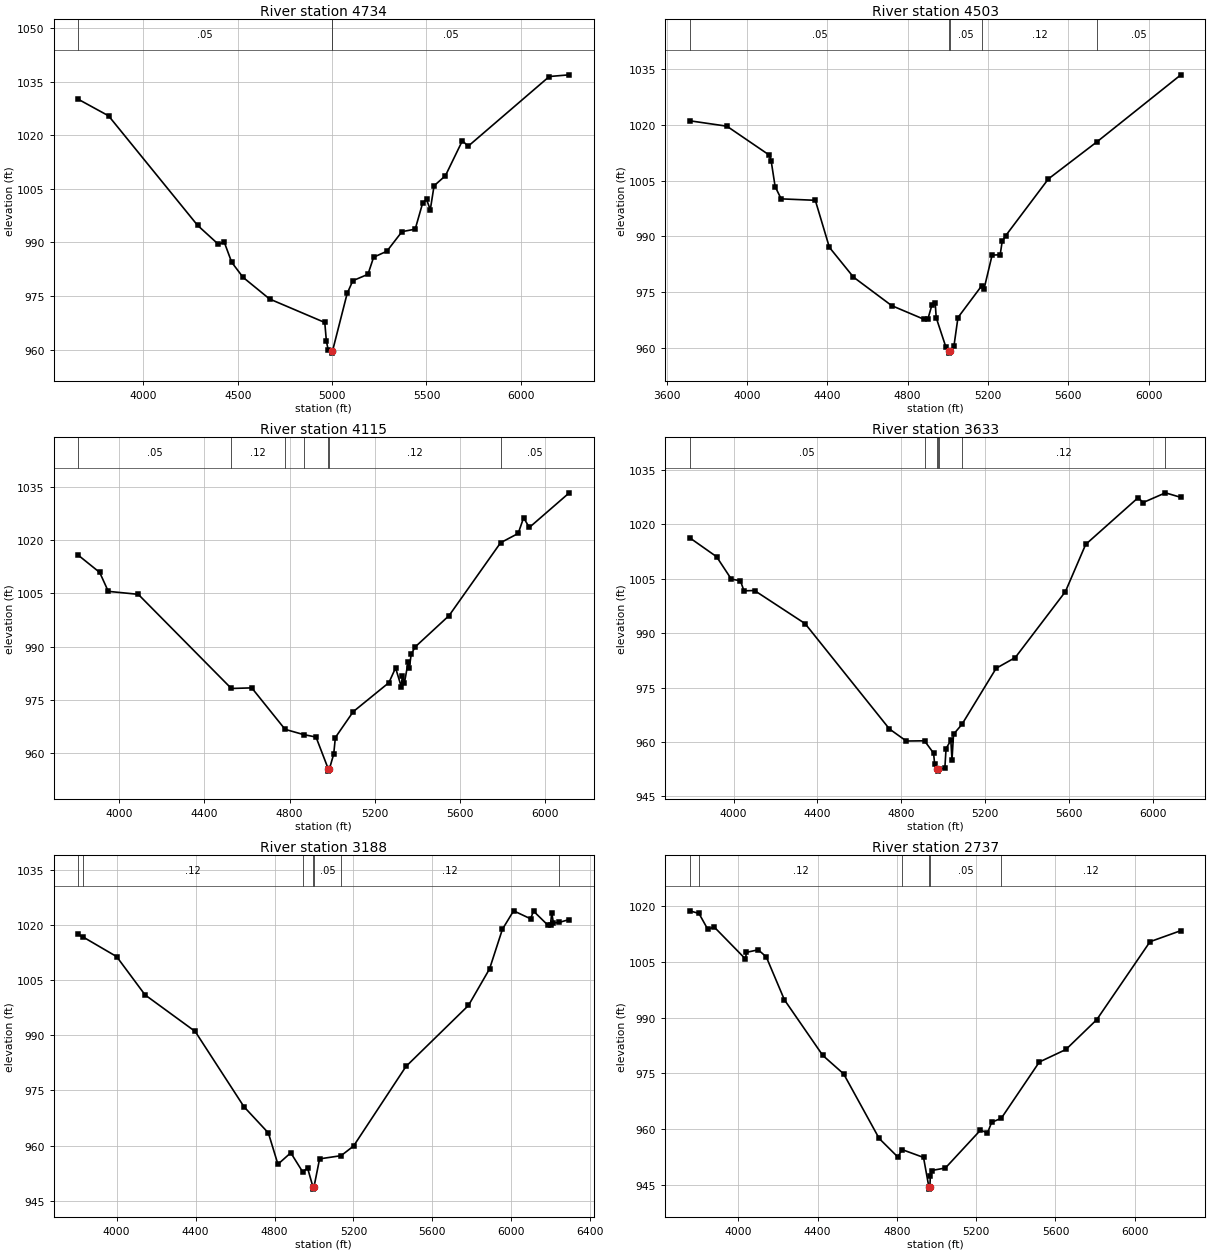
Type RM Length L Ch R = 1 ,4734    ,231,231,231
BEGIN DESCRIPTION:
Upper Denton 79 9.4
END DESCRIPTION:
XS GIS Cut Line= 3
      2218869.87      7254606.88      2217571.24      7254495.77
       2216273.3      7254551.29
#Sta/Elev= 30
    3654 1030.08  3815.5 1025.42  4287.2  994.79  4397.6  989.48  4427.7   990.2
  4467.8  984.47    4528  980.26  4668.6   974.2    4961  967.63  4969.6  962.39
  4979.6  959.85  4997.6  959.56  4997.9  959.06  5001.6  959.56  5079.7  975.76
  5109.8  979.32  5189.8   981.1  5219.9  985.89  5289.9  987.55    5370  993.03
  5440.1  993.73  5480.1 1001.12  5500.1 1002.05  5520.1  999.16  5540.1 1005.86
  5600.2 1008.67  5690.3 1018.48  5720.3  1016.9  6150.7 1036.42  6256.5 1036.89
#Mann= 3 ,-1 , 0
    3654     .05       0  4997.6    .033       0  5001.6     .05       0
Bank Sta=4997.6,5001.6
XS Rating Curve= 0 ,0
Exp/Cntr=0.3,0.1

Type RM Length L Ch R = 1 ,4503    ,388,388,388
BEGIN DESCRIPTION:
Upper Denton 79 9.0
END DESCRIPTION:
XS GIS Cut Line= 3
      2218814.26      7254238.82      2217515.68       7254266.6
      2216369.88      7254301.32
#Sta/Elev= 30
  3714.8 1021.08  3900.1 1019.62  4110.1 1011.88  4120.2 1010.36  4140.2 1003.35
  4170.2 1000.06  4340.2  999.67  4410.2  987.01  4530.2  978.99  4720.3  971.32
  4880.3  967.66  4900.3  967.66  4920.3   971.4  4937.1  972.05  4942.1  968.07
  4990.3  960.15  5007.5  959.03  5007.8  958.53  5011.6  959.03  5030.4  960.44
  5050.4  968.11    5168  976.62  5180.4  975.85  5220.4  984.92  5260.5  985.01
  5270.5   988.6  5288.2  990.16  5500.6 1005.43  5743.7 1015.47    6160 1033.45
#Mann= 5 ,-1 , 0
  3714.8     .05       0  5007.5    .033       0  5011.6     .05       0
    5168     .12       0  5743.7     .05       0
Bank Sta=5007.5,5011.6
XS Rating Curve= 0 ,0
Exp/Cntr=0.3,0.1

Type RM Length L Ch R = 1 ,4115    ,482,482,482
BEGIN DESCRIPTION:
Upper Denton 79 8.0
END DESCRIPTION:
XS GIS Cut Line= 3
      2218619.85      7253780.49        2217429.        7253910.
      2216369.84      7254238.83
#Sta/Elev= 30
  3806.5 1015.78  3907.9 1010.89  3948.2 1005.56    4089 1004.72  4526.3   978.2
  4622.1  978.37  4778.6  966.69  4865.8  965.21  4923.9  964.52  4982.2  955.42
  4982.5  954.92  4986.3  955.42    5007  959.72  5014.8  964.39  5098.6  971.66
  5266.1  979.83  5297.6  983.99  5324.3  978.71  5329.5  981.85  5339.4  979.87
  5356.8  985.64  5362.1  983.88  5370.8  987.84  5389.4  989.89  5548.9  998.73
  5790.8 1019.25  5873.4 1021.87  5898.9 1026.28  5925.8 1023.55  6113.4 1033.31
#Mann= 7 ,-1 , 0
  3806.5     .05       0  4526.3     .12       0  4778.6     .05       0
  4865.8     .12       0  4982.2     .07       0  4986.3     .12       0
  5790.8     .05       0
Bank Sta=4982.2,4986.3
XS Rating Curve= 0 ,0
Exp/Cntr=0.3,0.1

Type RM Length L Ch R = 1 ,3633    ,445,445,445
BEGIN DESCRIPTION:
Upper Denton 79 7.0
END DESCRIPTION:
XS GIS Cut Line= 3
      2218536.52       7253329.1        2217329.        7253460.
      2216307.33      7253940.22
#Sta/Elev= 30
  3790.2 1016.31  3918.5 1011.09  3988.9 1004.91  4032.3 1004.45  4049.2 1001.68
  4099.5 1001.77  4340.9  992.64  4743.3   963.6  4823.7  960.28  4910.6  960.34
  4953.9  956.93    4959  953.89  4972.5  952.48  4972.9  951.98  4976.7  952.48
  4980.8  952.52  5007.6  952.72  5013.4  958.19  5036.2  960.48  5041.8  955.09
    5049  962.14  5089.1  964.86  5252.5  980.33  5343.7  983.29  5582.8 1001.46
  5679.6 1014.48  5930.4 1027.39  5953.2 1026.01  6060.1  1028.7  6133.7 1027.45
#Mann= 7 ,-1 , 0
  3790.2     .05       0  4910.6     .12       0  4972.5    .033       0
  4976.7     .12       0  4980.8     .05       0  5089.1     .12       0
  6060.1     .05       0
Bank Sta=4972.5,4976.7
XS Rating Curve= 0 ,0
Exp/Cntr=0.3,0.1

Type RM Length L Ch R = 1 ,3188    ,451,451,451
BEGIN DESCRIPTION:
Upper Denton 79 6.0
END DESCRIPTION:
XS GIS Cut Line= 3
      2218390.68      7252620.77        2217279.        7253060.
      2216224.02      7253808.26
#Sta/Elev= 30
  3804.7 1017.35  3831.8 1016.61    4000 1011.34    4144 1000.94  4397.9  991.01
  4645.2  970.55  4768.8  963.43  4817.2  954.93  4882.3  958.04  4942.1   952.9
  4967.7  953.84  4995.2  948.67  4995.5  948.17  4999.5  948.67  5028.3  956.39
  5137.3  957.26  5200.5  959.88  5465.9  981.49  5782.5  998.07  5889.5 1008.01
  5954.7 1018.78  6011.3 1023.78  6097.4 1021.62  6112.2  1023.7  6183.6 1019.96
  6198.3 1019.99  6204.5 1023.26  6213.1 1020.49  6243.1 1020.65  6293.4 1021.41
#Mann= 7 ,-1 , 0
  3804.7     .05       0  3831.8     .12       0  4942.1     .05       0
  4995.2    .033       0  4999.5     .05       0  5137.3     .12       0
  6243.1     .05       0
Bank Sta=4995.2,4999.5
XS Rating Curve= 0 ,0
Exp/Cntr=0.3,0.1

Type RM Length L Ch R = 1 ,2737    ,463,463,463
BEGIN DESCRIPTION:
Upper Denton 79 5.0
END DESCRIPTION:
XS GIS Cut Line= 3
      2218349.03      7252433.26        2217129.        7252660.
      2216254.08      7253535.14
#Sta/Elev= 30
  3754.4 1018.82  3801.1 1018.12    3846 1013.82  3877.5 1014.49  4035.8 1005.85
  4040.9 1007.63  4100.3 1008.32  4140.9  1006.4  4232.5  994.83  4425.7  979.88
  4531.3  974.88  4710.5  957.48  4805.5  952.44  4825.3   954.5  4934.3  952.37
  4961.6  944.33    4962  943.83    4966  944.33  4968.9  947.41    4975  948.84
  5044.8  949.53  5221.6  959.72    5257  958.98  5278.2  961.83    5327  962.94
  5518.6  978.08  5652.9  981.46  5808.5   989.5  6077.2  1010.5  6232.8 1013.48
#Mann= 6 ,-1 , 0
  3754.4     .05       0  3801.1     .12       0  4825.3     .05       0
  4961.6    .033       0    4966     .05       0    5327     .12       0
Bank Sta=4961.6,4966
XS Rating Curve= 0 ,0
Exp/Cntr=0.3,0.1

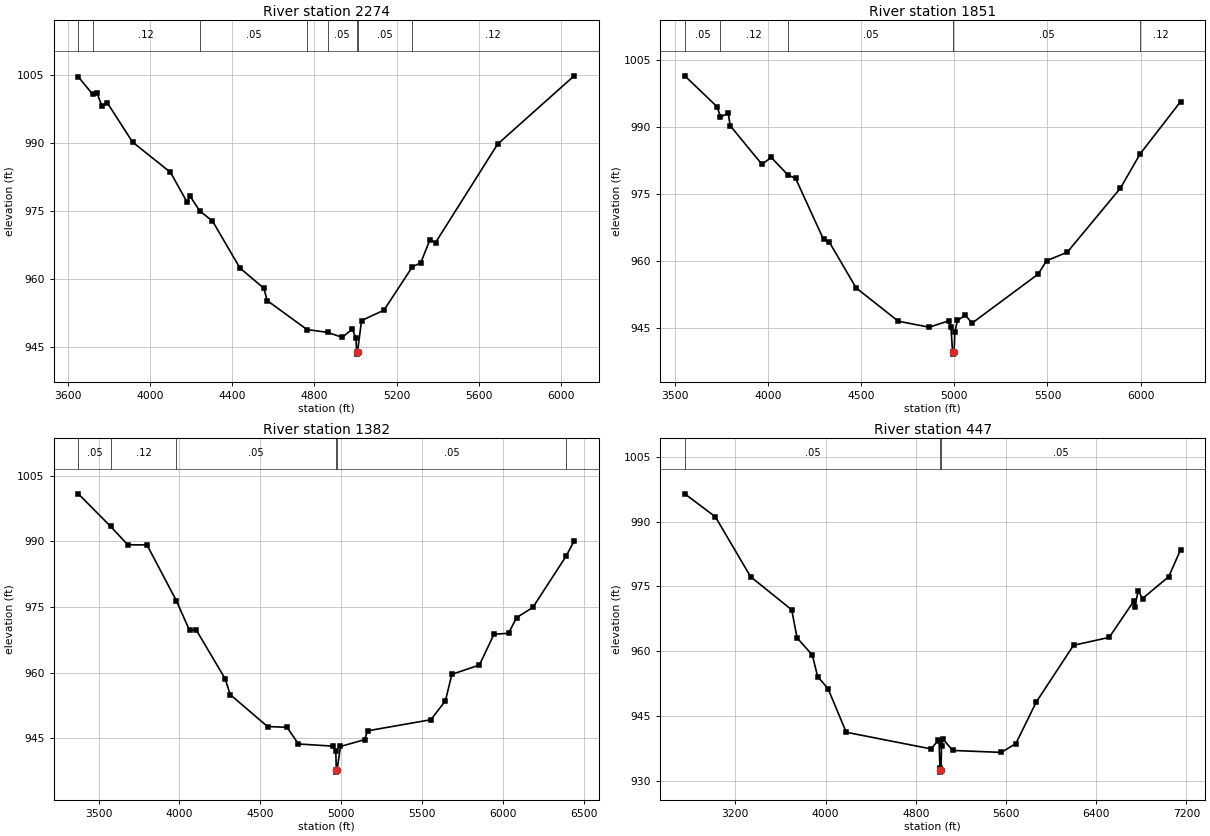
Type RM Length L Ch R = 1 ,2274    ,423,423,423
BEGIN DESCRIPTION:
Upper Denton 79 4.0
END DESCRIPTION:
XS GIS Cut Line= 3
      2218051.33      7251955.34        2216779.        7252410.
      2216271.85      7253348.52
#Sta/Elev= 30
  3648.4 1004.52  3718.1  1000.7  3738.8 1001.05  3764.3     998  3788.9  998.85
  3912.9  990.15  4097.7  983.49  4179.4  976.86  4192.5  978.29  4241.1  974.95
  4302.6  972.75  4436.7  962.39  4553.5  957.93    4569  955.24  4763.4  948.85
  4863.9  948.22  4935.8  947.13  4984.1  948.94  5002.4  946.94  5005.4  943.93
  5005.8  943.43  5009.8  943.93  5029.5  950.83  5138.9  953.11  5277.7   962.7
  5317.8  963.51  5362.6  968.58  5390.2     968  5692.9  989.69  6066.3 1004.75
#Mann= 8 ,-1 , 0
  3648.4     .05       0  3718.1     .12       0  4241.1     .05       0
  4763.4     .12       0  4863.9     .05       0  5005.4    .033       0
  5009.8     .05       0  5277.7     .12       0
Bank Sta=5005.4,5009.8
XS Rating Curve= 0 ,0
Exp/Cntr=0.3,0.1

Type RM Length L Ch R = 1 ,1851    ,469,469,469
BEGIN DESCRIPTION:
Upper Denton 79 3.0
END DESCRIPTION:
XS GIS Cut Line= 5
       2217981.9       7251833.8      2216808.25      7251924.97
        2216579.        7252060.      2216436.76      7252181.03
      2216271.83      7253200.97
#Sta/Elev= 30
  3552.1 1001.49  3725.5  994.57  3743.8  992.35  3785.7  993.08  3795.7  990.35
  3966.2  981.71  4016.4  983.24    4107  979.28  4146.8   978.6  4297.2  964.91
  4327.3  964.38  4472.1  954.08  4698.4  946.63  4864.6  945.28  4972.1  946.73
  4981.7   945.3  4990.2  939.76  4990.6  939.26  4994.7  939.76  4998.6  939.76
  5002.5  944.23  5016.8  946.81  5059.6  947.95  5094.7  946.18  5449.7  957.14
  5495.1  960.14  5606.5  962.05  5891.9  976.37  5998.1  984.05  6215.3  995.73
#Mann= 6 ,-1 , 0
  3552.1     .05       0  3743.8     .12       0    4107     .05       0
  4990.2    .033       0  4994.7     .05       0  5998.1     .12       0
Bank Sta=4990.2,4998.6
XS Rating Curve= 0 ,0
Exp/Cntr=0.3,0.1

Type RM Length L Ch R = 1 ,1382    ,935,935,935
BEGIN DESCRIPTION:
Upper Denton 79 2.0
END DESCRIPTION:
XS GIS Cut Line= 5
      2217942.87      7251773.04       2216484.5      7251642.83
        2216329.        7251710.      2216233.64      7251829.29
      2216237.11       7253105.3
#Sta/Elev= 30
  3375.3  1000.9  3574.2  993.45  3680.4  989.25  3799.5   989.2  3980.4  976.48
  4061.9  969.65  4102.1  969.84  4282.8  958.53  4312.9  954.97  4543.8  947.65
  4664.3  947.48  4734.6  943.66  4947.4  943.17  4965.3  942.07  4968.6  937.72
  4969.1  937.22  4973.2  937.72  4994.4  943.09  5144.1  944.66  5161.3  946.67
  5552.3  949.21  5642.3  953.52  5682.3   959.6  5852.3  961.72  5942.3  968.76
  6032.3     969  6082.3  972.58  6182.3   974.9  6386.7  986.57  6437.6  990.12
#Mann= 6 ,-1 , 0
  3375.3     .05       0  3574.2     .12       0  3980.4     .05       0
  4968.6    .033       0  4973.2     .05       0  6386.7     .12       0
Bank Sta=4968.6,4973.2
XS Rating Curve= 0 ,0
Exp/Cntr=0.3,0.1

Type RM Length L Ch R = 1 ,447     ,0,0,0
BEGIN DESCRIPTION:
Upper Denton 79 1.0
END DESCRIPTION:
XS GIS Cut Line= 4
       2217838.7      7251742.67      2215902.91      7250926.68
      2215638.15      7251161.06      2216215.42       7253014.4
#Sta/Elev= 30
  2752.5   996.4  3023.5  991.09  3335.7  977.25  3700.4   969.6  3747.8  963.12
  3882.7  959.17  3930.2  954.17  4021.9  951.39  4183.7  941.31  4936.6  937.46
  5000.1   939.5  5006.8  939.27  5014.3  933.07  5018.7   932.6  5019.2   932.1
  5023.3   932.6  5028.6  938.16  5042.8   939.7  5127.2  937.11  5559.7  936.66
  5687.5  938.71  5868.1  948.28  6198.6  961.41    6515  963.23  6734.7  971.69
  6739.9  970.18  6772.4  974.02  6810.2   972.2  7043.1  977.28    7148  983.51
#Mann= 3 ,-1 , 0
  2752.5     .05       0  5018.7     .04       0  5023.3     .05       0
Bank Sta=5018.7,5023.3
XS Rating Curve= 0 ,0
Exp/Cntr=0.3,0.1

Chan Stop Cuts=-1
Use User Specified Reach Order=0
Composite Channel Slope=5