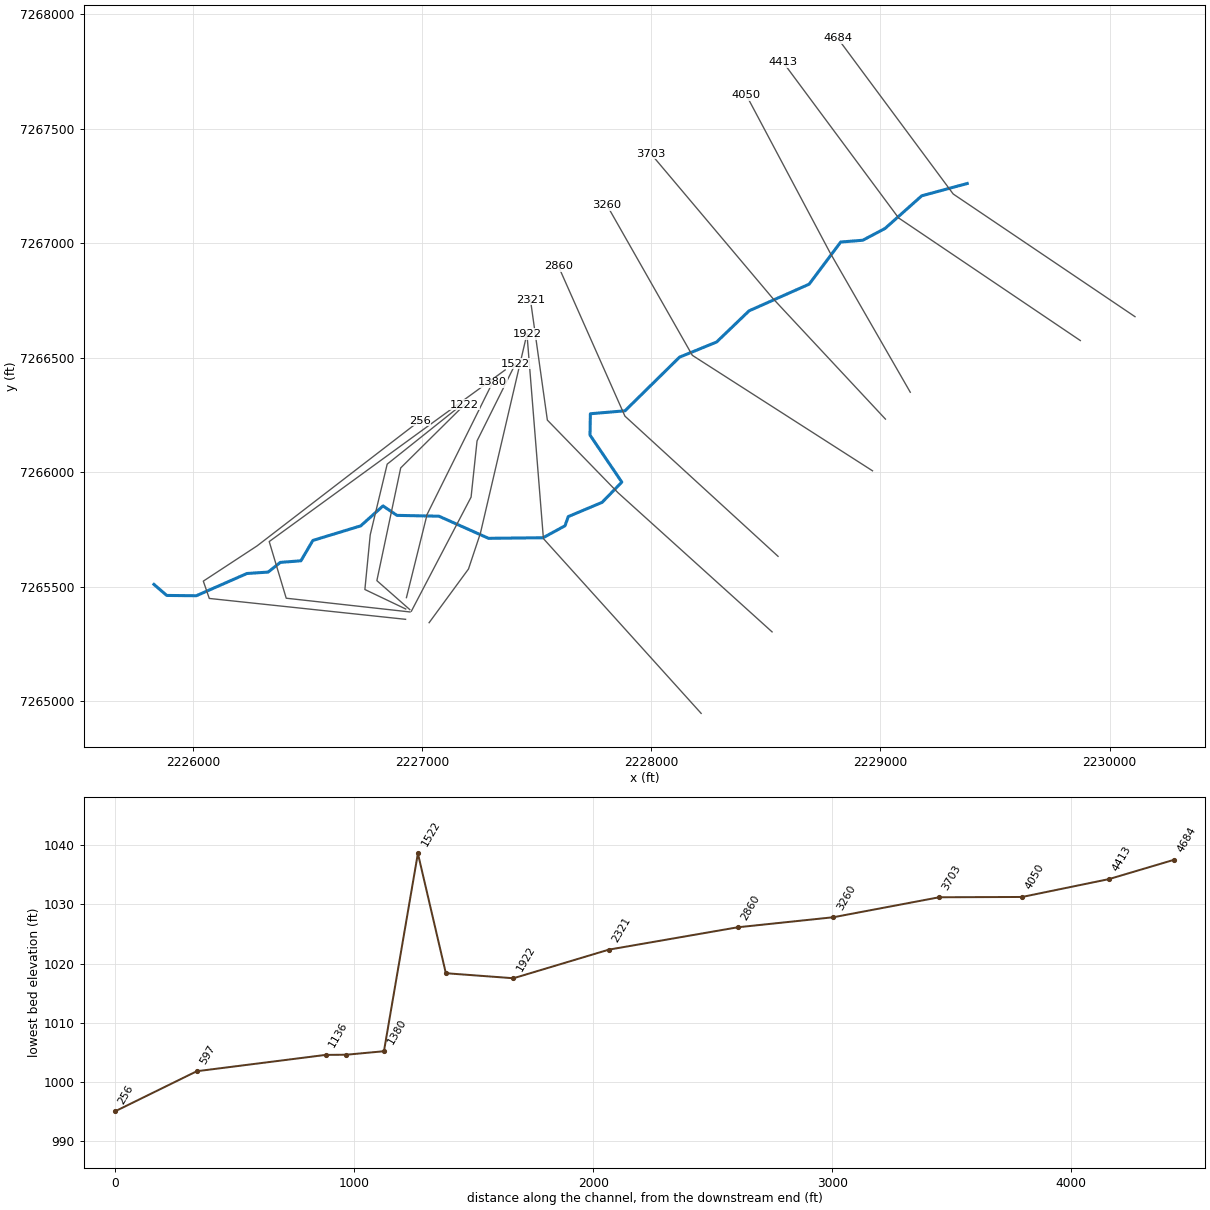
--- Upper Denton 82.prj (project) ---

Proj Title=Upper Denton 82 Base Level Engineering
Current Plan=p01
Default Exp/Contr=0.3,0.1
English Units
Geom File=g01
Flow File=f01
Plan File=p01
BEGIN DESCRIPTION:
Upper Denton 82
END DESCRIPTION:

--- Upper Denton 82.p01 (plan) ---

Plan Title=Multiple Run
Short Identifier=Multiple
Geom File=g01
Flow File=f01
Subcritical Flow
K Sum by GR= 0
Std Step Tol= 0.01
Critical Tol= 0.01
Num of Std Step Trials= 20
Max Error Tol= 0.3
Flow Tol Ratio= 0.001
Split Flow NTrial= 30
Split Flow Tol= 0.02
Split Flow Ratio= 0.02
Log Output Level= 0
Friction Slope Method= 1
Unsteady Friction Slope Method= 2
Unsteady Bridges Friction Slope Method= 1
Parabolic Critical Depth
Global Vel Dist=  1 , 1 , 1
Global Log Level= 0
CheckData=True
Encroach Param= -1, 0, 0, 0
BEGIN DESCRIPTION:
Multiple Run
END DESCRIPTION:

--- Upper Denton 82.f01 (steady flow) ---

Flow Title=Multiple
Number of Profiles=7
Profile Names=10-year,25-year,50-year,1pct_min,100-year,1pct_plu,500-year
River Rch & RM= Upper Denton 82,Reach-1,4684
     880    1263    1594    1000    1995    3981    3134
River Rch & RM= Upper Denton 82,Reach-1,3260
     918    1315    1658    1039    2073    4136    3249
Boundary for River Rch & Prof#=Upper Denton 82,Reach-1,1
Up Type=0
Dn Type=3
Dn Slope=0.005
Boundary for River Rch & Prof#=Upper Denton 82,Reach-1,2
Up Type=0
Dn Type=3
Dn Slope=0.005
Boundary for River Rch & Prof#=Upper Denton 82,Reach-1,3
Up Type=0
Dn Type=3
Dn Slope=0.005
Boundary for River Rch & Prof#=Upper Denton 82,Reach-1,4
Up Type=0
Dn Type=3
Dn Slope=0.005
Boundary for River Rch & Prof#=Upper Denton 82,Reach-1,5
Up Type=0
Dn Type=3
Dn Slope=0.005
Boundary for River Rch & Prof#=Upper Denton 82,Reach-1,6
Up Type=0
Dn Type=3
Dn Slope=0.005
Boundary for River Rch & Prof#=Upper Denton 82,Reach-1,7
Up Type=0
Dn Type=3
Dn Slope=0.005

--- Upper Denton 82.g01 (geometry) ---

Geom Title=Existing Conditions

River Reach=Upper Denton 82,Reach-1
Reach XY= 30
      2229379.00      7267260.00      2229180.50      7267206.38
      2229020.38      7267063.84      2228923.06      7267012.33
      2228826.56      7267004.48      2228689.00      7266820.63
      2228426.70      7266704.17      2228285.06      7266568.14
      2228122.94      7266501.86      2227885.19      7266267.82
      2227733.92      7266254.96      2227732.44      7266161.58
      2227871.24      7265956.58      2227785.09      7265868.14
      2227637.62      7265806.15      2227623.24      7265765.95
      2227527.47      7265713.74      2227289.50      7265711.22
      2227073.06      7265807.74      2226889.43      7265811.39
      2226828.90      7265852.67      2226731.43      7265765.55
      2226522.68      7265701.93      2226470.65      7265613.19
      2226380.67      7265606.11      2226327.41      7265563.85
      2226234.97      7265557.65      2226013.78      7265460.50
      2225884.79      7265461.88      2225829.00      7265510.00

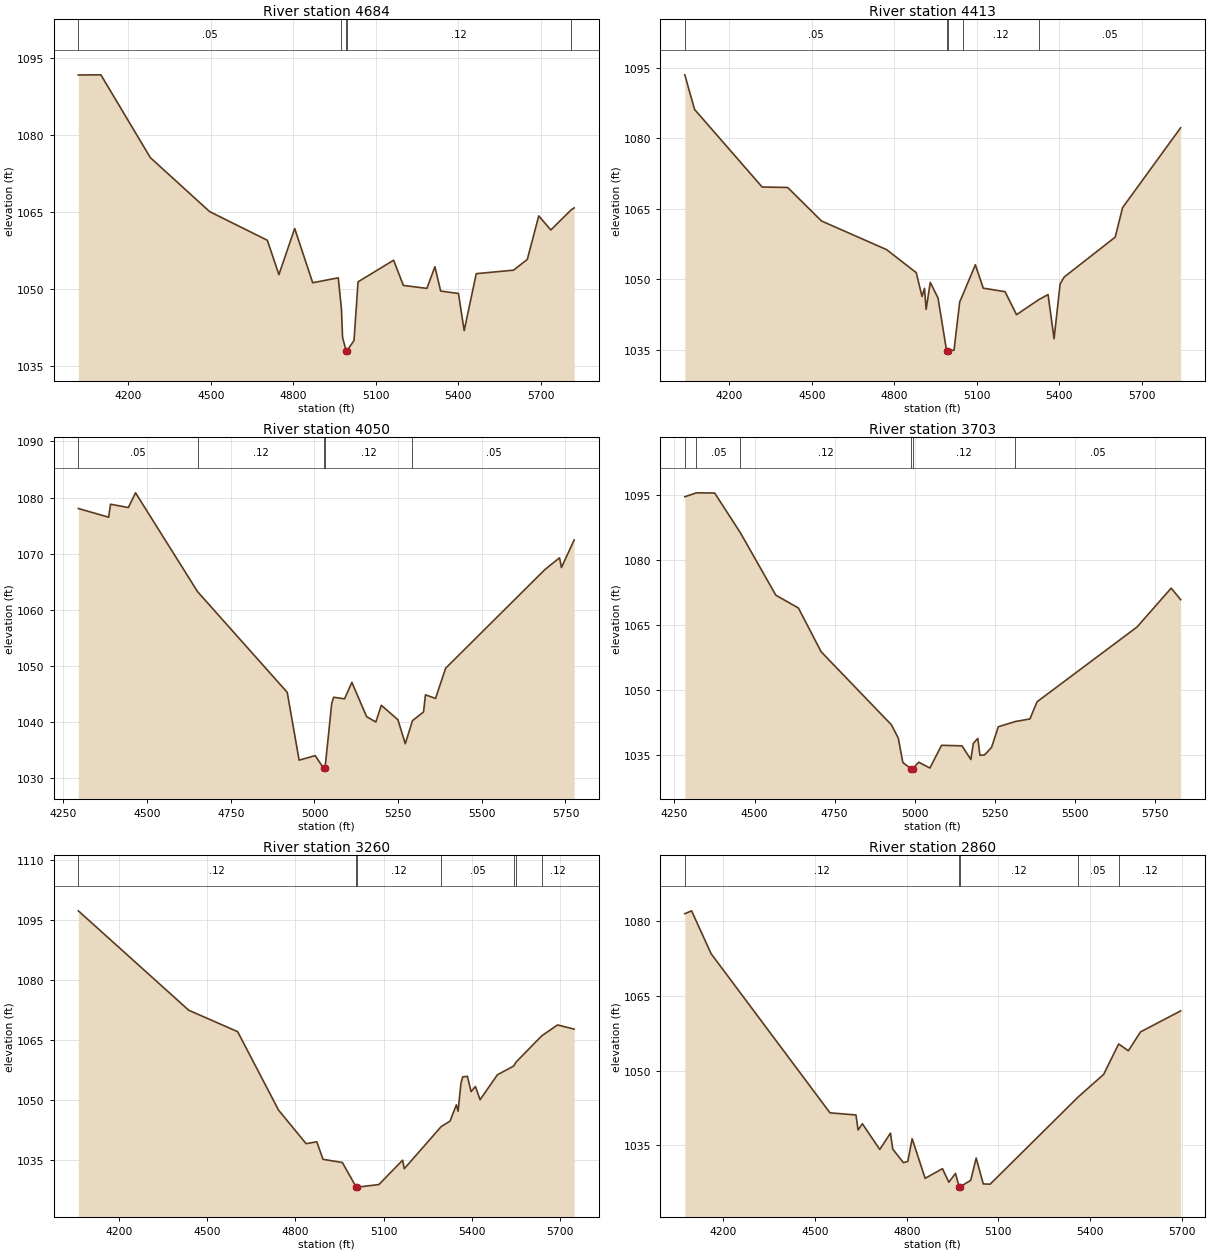
Type RM Length L Ch R = 1,4684,271,271,271
BEGIN DESCRIPTION:
Upper Denton 82 9.5
END DESCRIPTION:
XS GIS Cut Line= 3
      2230111.29      7266678.68      2229317.72      7267214.17
      2228813.78      7267893.65
#Sta/Elev= 30
  4018.3 1091.76  4100.3 1091.79  4280.2 1075.65  4496.0 1065.12  4705.8 1059.54
  4747.8 1052.84  4805.2 1061.83  4870.7 1051.26  4963.7 1052.22  4975.3 1046.08
  4979.3 1040.62  4991.9 1038.04  4992.1 1037.54  4995.9 1038.04  5021.0 1040.00
  5035.6 1051.44  5165.0 1055.65  5200.4 1050.74  5286.0 1050.16  5315.2 1054.39
  5336.1 1049.64  5400.8 1049.17  5421.6 1041.93  5465.5 1053.03  5601.1 1053.71
  5651.2 1055.81  5692.9 1064.29  5736.7 1061.55  5811.1 1065.49  5821.6 1065.85
#Mann=5,-1,0
  4018.3    0.05       0  4975.3    0.12       0  4991.9    0.07       0
  4995.9    0.12       0  5811.1    0.05       0
Bank Sta=4991.9,4995.9
Exp/Cntr=0.3,0.1

Type RM Length L Ch R = 1,4413,363,363,363
BEGIN DESCRIPTION:
Upper Denton 82 9.0
END DESCRIPTION:
XS GIS Cut Line= 3
      2229872.60      7266574.49      2229079.00      7267110.00
      2228574.85      7267789.77
#Sta/Elev= 30
  4037.9 1093.53  4073.5 1086.16  4319.3 1069.65  4412.2 1069.55  4535.1 1062.42
  4772.0 1056.32  4879.9 1051.42  4900.9 1046.35  4909.8 1048.09  4915.8 1043.60
  4930.8 1049.36  4959.1 1046.02  4990.3 1034.79  4990.5 1034.29  4994.3 1034.79
  5017.2 1034.91  5038.0 1045.20  5051.4 1047.01  5094.9 1053.10  5123.6 1048.12
  5202.9 1047.37  5244.6 1042.47  5324.6 1045.64  5359.4 1046.76  5381.2 1037.35
  5403.2 1049.01  5417.9 1050.48  5603.6 1058.98  5630.6 1065.27  5841.6 1082.26
#Mann=5,-1,0
  4037.9    0.05       0  4990.3   0.033       0  4994.3    0.05       0
  5051.4    0.12       0  5324.6    0.05       0
Bank Sta=4990.3,4994.3
Exp/Cntr=0.3,0.1

Type RM Length L Ch R = 1,4050,347,347,347
BEGIN DESCRIPTION:
Upper Denton 82 8.0
END DESCRIPTION:
XS GIS Cut Line= 3
      2229130.38      7266348.83      2228779.00      7266960.00
      2228414.68      7267645.75
#Sta/Elev= 30
  4294.5 1078.05  4385.0 1076.50  4390.7 1078.81  4443.9 1078.22  4465.5 1080.84
  4650.9 1063.23  4918.7 1045.30  4954.2 1033.22  5002.3 1034.03  5027.6 1031.77
  5027.9 1031.27  5031.6 1031.77  5051.6 1043.32  5057.3 1044.43  5089.9 1044.15
  5111.9 1047.08  5155.8 1040.98  5183.5 1040.02  5199.8 1043.00  5249.4 1040.43
  5271.4 1036.15  5292.9 1040.26  5326.0 1041.82  5331.7 1044.86  5361.8 1044.22
  5392.0 1049.60  5688.4 1067.16  5732.3 1069.27  5738.0 1067.53  5776.0 1072.44
#Mann=5,-1,0
  4294.5    0.05       0  4650.9    0.12       0  5027.6    0.07       0
  5031.6    0.12       0  5292.9    0.05       0
Bank Sta=5027.6,5031.6
Exp/Cntr=0.3,0.1

Type RM Length L Ch R = 1,3703,443,443,443
BEGIN DESCRIPTION:
Upper Denton 82 7.0
END DESCRIPTION:
XS GIS Cut Line= 3
      2229021.93      7266231.59      2228529.00      7266760.00
      2227997.58      7267390.48
#Sta/Elev= 30
  4282.3 1094.67  4318.4 1095.58  4375.5 1095.54  4455.7 1086.35  4566.5 1071.90
  4636.8 1068.95  4707.7 1058.83  4927.0 1041.94  4948.5 1038.86  4962.7 1033.21
  4989.0 1031.72  4989.3 1031.22  4993.0 1031.72  5012.1 1033.28  5047.2 1031.94
  5083.4 1037.19  5147.3 1037.07  5175.0 1033.90  5182.4 1037.60  5196.7 1038.79
  5203.3 1034.89  5217.6 1034.96  5239.6 1036.72  5260.5 1041.48  5313.7 1042.69
  5359.3 1043.29  5381.4 1047.25  5693.5 1064.55  5800.1 1073.54  5829.5 1070.88
#Mann=6,-1,0
  4282.3    0.12       0  4318.4    0.05       0  4455.7    0.12       0
  4989.0    0.07       0  4993.0    0.12       0  5313.7    0.05       0
Bank Sta=4989,4993
Exp/Cntr=0.3,0.1

Type RM Length L Ch R = 1,3260,400,400,400
BEGIN DESCRIPTION:
Upper Denton 82 6.0
END DESCRIPTION:
XS GIS Cut Line= 3
      2228965.51      7266005.90      2228179.00      7266510.00
      2227806.59      7267164.82
#Sta/Elev= 30
  4061.2 1097.31  4437.1 1072.49  4603.4 1067.15  4742.6 1047.57  4836.5 1039.19
  4872.8 1039.66  4893.9 1035.28  4959.8 1034.48  5007.1 1028.34  5007.3 1027.84
  5011.1 1028.34  5084.0 1028.98  5164.8 1035.06  5170.5 1032.93  5296.5 1043.48
  5326.2 1044.81  5347.8 1048.88  5353.6 1047.27  5363.5 1054.30  5369.4 1055.86
  5385.3 1056.00  5398.0 1052.18  5412.7 1053.46  5428.5 1050.16  5487.6 1056.39
  5543.0 1058.57  5550.8 1059.54  5638.4 1066.11  5692.3 1068.83  5748.7 1067.78
#Mann=7,-1,0
  4061.2    0.12       0  5007.1    0.07       0  5011.1    0.12       0
  5296.5    0.05       0  5543.0    0.12       0  5550.8    0.05       0
  5638.4    0.12       0
Bank Sta=5007.1,5011.1
Exp/Cntr=0.3,0.1

Type RM Length L Ch R = 1,2860,539,539,539
BEGIN DESCRIPTION:
Upper Denton 82 5.0
END DESCRIPTION:
XS GIS Cut Line= 3
      2228553.18      7265632.63      2227884.74      7266244.64
      2227593.98      7266899.94
#Sta/Elev= 30
  4073.4 1081.56  4095.6 1082.14  4159.7 1073.50  4548.8 1041.49  4633.9 1041.06
  4640.7 1038.04  4654.9 1039.29  4711.6 1034.12  4746.7 1037.41  4754.1 1034.20
  4789.3 1031.46  4803.5 1031.72  4817.7 1036.29  4860.2 1028.31  4916.9 1030.26
  4937.9 1027.53  4959.5 1029.31  4971.4 1026.64  4971.7 1026.14  4975.5 1026.64
  5009.5 1027.92  5027.3 1032.40  5050.6 1027.18  5073.1 1027.14  5360.1 1044.62
  5444.8 1049.24  5493.7 1055.35  5525.5 1053.99  5565.4 1057.78  5696.6 1062.00
#Mann=5,-1,0
  4073.4    0.12       0  4971.4    0.07       0  4975.5    0.12       0
  5360.1    0.05       0  5493.7    0.12       0
Bank Sta=4971.4,4975.5
Exp/Cntr=0.3,0.1

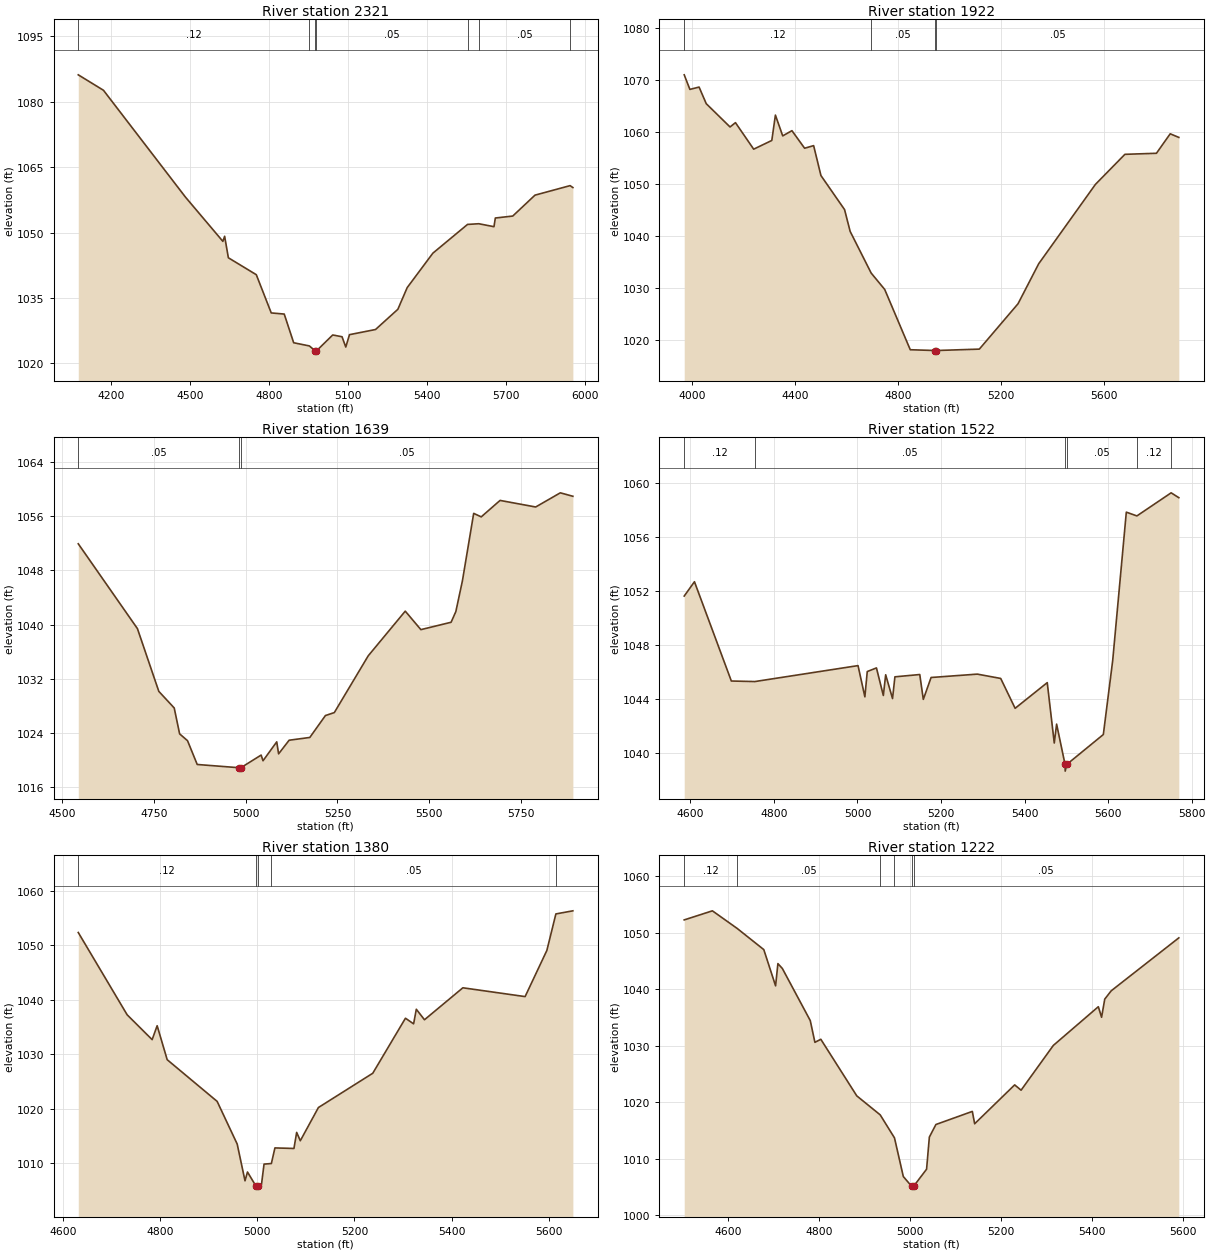
Type RM Length L Ch R = 1,2321,399,399,399
BEGIN DESCRIPTION:
Upper Denton 82 4.0
END DESCRIPTION:
XS GIS Cut Line= 4
      2228527.12      7265302.78      2227854.36      7265910.44
      2227546.20      7266227.28      2227472.41      7266752.48
#Sta/Elev= 30
  4076.5 1086.13  4172.2 1082.59  4483.8 1058.10  4625.8 1047.97  4632.5 1049.14
  4646.7 1044.21  4752.8 1040.33  4809.6 1031.57  4858.9 1031.31  4894.8 1024.74
  4954.3 1024.01  4976.9 1022.86  4977.3 1022.36  4981.1 1022.86  5043.1 1026.52
  5078.5 1026.11  5092.7 1023.75  5106.8 1026.59  5205.7 1027.77  5290.5 1032.40
  5326.0 1037.37  5423.5 1045.26  5555.2 1051.85  5598.0 1052.01  5655.7 1051.33
  5660.8 1053.32  5727.0 1053.77  5811.5 1058.56  5944.9 1060.74  5955.4 1060.30
#Mann=7,-1,0
  4076.5    0.12       0  4954.3    0.05       0  4976.9   0.033       0
  4981.1    0.05       0  5555.2    0.12       0  5598.0    0.05       0
  5944.9    0.12       0
Bank Sta=4976.9,4981.1
Exp/Cntr=0.3,0.1

Type RM Length L Ch R = 1,1922,283,283,283
BEGIN DESCRIPTION:
Upper Denton 82 3.0
END DESCRIPTION:
XS GIS Cut Line= 3
      2228217.52      7264947.10      2227529.00      7265710.00
      2227457.13      7266603.36
#Sta/Elev= 30
  3968.0 1070.94  3990.1 1068.14  4025.8 1068.59  4053.7 1065.40  4146.3 1060.93
  4167.3 1061.76  4238.2 1056.67  4308.7 1058.34  4322.7 1063.21  4351.1 1059.22
  4387.0 1060.22  4436.3 1056.85  4471.4 1057.35  4499.8 1051.61  4591.7 1045.07
  4613.4 1040.89  4695.2 1032.89  4747.9 1029.74  4847.3 1018.17  4943.9 1018.02
  4944.2 1017.52  4948.1 1018.02  5116.0 1018.29  5266.5 1027.00  5346.8 1034.67
  5567.5 1049.91  5682.2 1055.68  5804.8 1055.88  5858.4 1059.62  5891.9 1058.93
#Mann=4,-1,0
  3968.0    0.12       0  4695.2    0.05       0  4943.9   0.033       0
  4948.1    0.05       0
Bank Sta=4943.9,4948.1
Exp/Cntr=0.3,0.1

Type RM Length L Ch R = 1,1639,117,117,117
BEGIN DESCRIPTION:
Upper Denton 82 2.5
END DESCRIPTION:
XS GIS Cut Line= 4
      2227030.08      7265342.94      2227201.93      7265577.28
      2227254.01      7265733.53      2227457.14      7266603.33
#Sta/Elev= 30
  4543.5 1051.92  4704.8 1039.40  4763.1 1030.14  4805.1 1027.69  4819.8 1023.87
  4841.4 1022.86  4867.8 1019.35  4982.4 1018.87  4982.7 1018.37  4986.7 1018.87
  5042.1 1020.74  5047.2 1019.90  5084.6 1022.69  5089.7 1020.92  5118.4 1022.93
  5174.8 1023.34  5217.3 1026.57  5241.6 1027.01  5334.1 1035.39  5435.0 1041.98
  5477.6 1039.25  5560.0 1040.34  5572.9 1041.91  5590.8 1046.44  5621.6 1056.41
  5642.1 1055.89  5693.5 1058.32  5790.6 1057.35  5857.8 1059.44  5892.0 1058.93
#Mann=3,-1,0
  4543.5    0.05       0  4982.4   0.033       0  4986.7    0.05       0
Bank Sta=4982.4,4986.7
Exp/Cntr=0.3,0.1

Type RM Length L Ch R = 1,1522,142,142,142
BEGIN DESCRIPTION:
Upper Denton 82 2.4
END DESCRIPTION:
XS GIS Cut Line= 4
      2226952.70      7265393.18      2227213.26      7265891.00
      2227239.32      7266136.49      2227406.63      7266472.48
#Sta/Elev= 30
  4585.3 1051.60  4609.8 1052.66  4698.1 1045.31  4754.4 1045.27  5001.4 1046.45
  5017.8 1044.14  5023.5 1046.01  5045.5 1046.28  5062.0 1044.24  5067.6 1045.77
  5084.0 1044.01  5089.7 1045.62  5149.2 1045.79  5157.7 1043.95  5176.3 1045.57
  5287.0 1045.82  5343.0 1045.50  5377.5 1043.29  5454.4 1045.19  5471.2 1040.72
  5476.8 1042.12  5497.0 1039.14  5497.4 1038.64  5501.3 1039.14  5588.7 1041.35
  5611.1 1046.83  5643.7 1057.81  5669.0 1057.53  5751.0 1059.24  5769.4 1058.88
#Mann=6,-1,0
  4585.3    0.12       0  4754.4    0.05       0  5497.0   0.033       0
  5501.3    0.05       0  5669.0    0.12       0  5751.0    0.05       0
Bank Sta=5497,5501.3
Exp/Cntr=0.3,0.1

Type RM Length L Ch R = 1,1380,158,158,158
BEGIN DESCRIPTION:
Upper Denton 82 2.0
END DESCRIPTION:
XS GIS Cut Line= 3
      2226931.10      7265452.29      2227021.25      7265815.56
      2227307.88      7266392.93
#Sta/Elev= 30
  4631.1 1052.38  4731.8 1037.24  4783.3 1032.67  4793.6 1035.23  4814.3 1028.98
  4917.2 1021.31  4958.5 1013.46  4974.6 1006.70  4979.7 1008.32  4997.5 1005.67
  4997.9 1005.17  5001.8 1005.67  5008.5 1006.01  5013.8 1009.77  5028.9 1009.88
  5036.2 1012.75  5075.4 1012.65  5081.0 1015.61  5088.5 1014.07  5125.8 1020.18
  5237.8 1026.49  5305.1 1036.61  5321.9 1035.58  5327.5 1038.26  5344.3 1036.33
  5423.4 1042.21  5551.6 1040.59  5596.4 1049.08  5615.0 1055.80  5650.0 1056.37
#Mann=5,-1,0
  4631.1    0.12       0  4997.5    0.07       0  5001.8    0.12       0
  5028.9    0.05       0  5615.0    0.12       0
Bank Sta=4997.5,5001.8
Exp/Cntr=0.3,0.1

Type RM Length L Ch R = 1,1222,86,86,86
BEGIN DESCRIPTION:
Upper Denton 82 1.6
END DESCRIPTION:
XS GIS Cut Line= 4
      2226945.83      7265400.00      2226802.02      7265526.47
      2226906.05      7266018.54      2227184.62      7266294.39
#Sta/Elev= 30
  4503.6 1052.28  4565.5 1053.89  4619.6 1050.79  4678.4 1047.02  4704.3 1040.60
  4709.4 1044.54  4719.2 1043.67  4780.5 1034.44  4790.7 1030.59  4803.7 1031.13
  4882.7 1021.10  4934.1 1017.74  4965.5 1013.66  4984.9 1006.81  5003.2 1005.08
  5003.6 1004.58  5007.5 1005.08  5036.0 1008.11  5042.1 1013.80  5056.5 1016.03
  5136.5 1018.35  5141.6 1016.16  5229.5 1023.05  5243.6 1022.11  5314.4 1030.04
  5413.3 1036.90  5420.4 1035.03  5427.4 1038.25  5441.6 1039.72  5590.1 1049.10
#Mann=6,-1,0
  4503.6    0.12       0  4619.6    0.05       0  4934.1    0.12       0
  4965.5    0.05       0  5003.2   0.033       0  5007.5    0.05       0
Bank Sta=5003.2,5007.5
Exp/Cntr=0.3,0.1

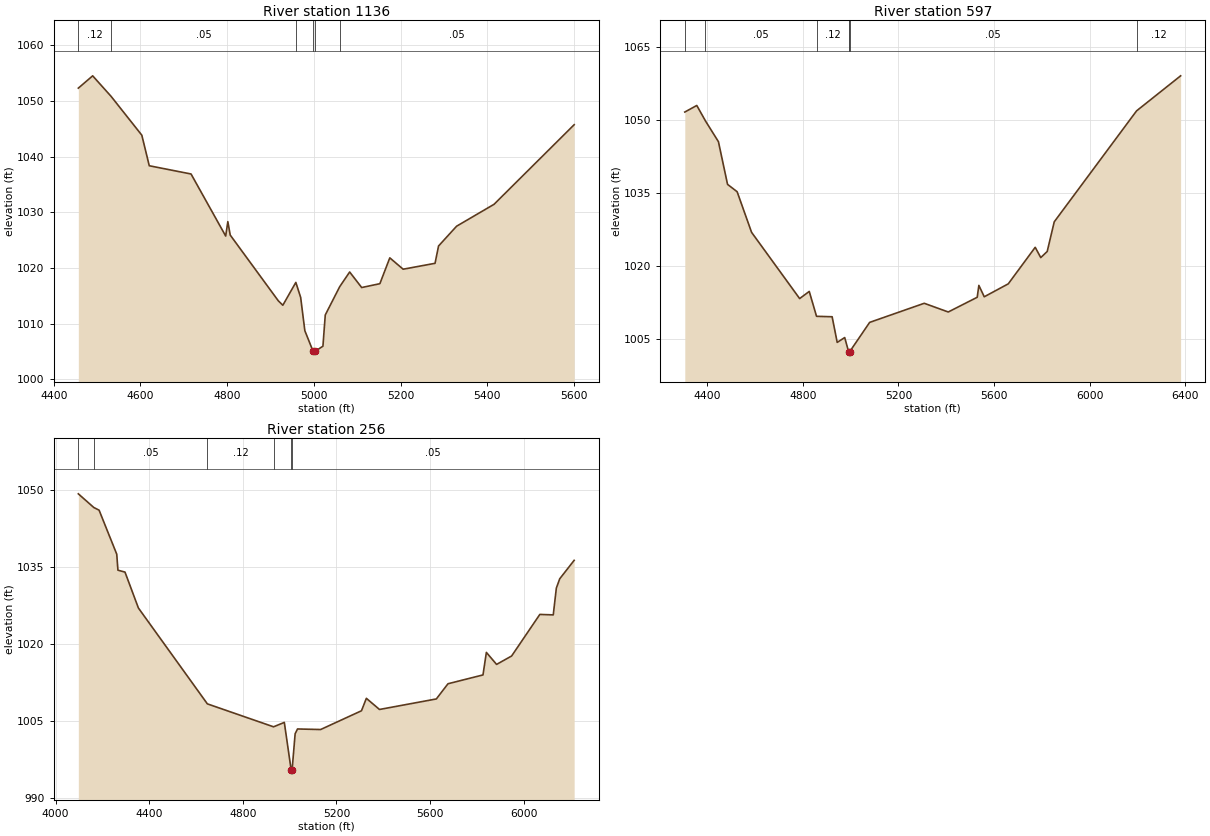
Type RM Length L Ch R = 1,1136,539,539,539
BEGIN DESCRIPTION:
Upper Denton 82 1.5
END DESCRIPTION:
XS GIS Cut Line= 5
      2226928.00      7265402.74      2226749.70      7265487.78
      2226773.01      7265726.42      2226847.08      7266035.00
      2227151.58      7266277.78
#Sta/Elev= 30
  4456.6 1052.32  4489.7 1054.53  4532.1 1050.85  4603.1 1043.87  4620.3 1038.38
  4716.7 1036.90  4796.6 1025.76  4801.6 1028.34  4807.1 1025.93  4918.2 1014.11
  4928.5 1013.33  4958.5 1017.43  4969.6 1014.74  4979.3 1008.75  4998.3 1005.05
  4998.6 1004.55  5002.6 1005.05  5021.0 1005.97  5026.4 1011.58  5059.7 1016.66
  5082.7 1019.30  5110.4 1016.51  5152.4 1017.20  5175.3 1021.84  5206.1 1019.80
  5279.7 1020.86  5287.8 1023.97  5329.4 1027.52  5415.9 1031.46  5600.7 1045.75
#Mann=6,-1,0
  4456.6    0.12       0  4532.1    0.05       0  4958.5    0.12       0
  4998.3    0.07       0  5002.6    0.12       0  5059.7    0.05       0
Bank Sta=4998.3,5002.6
Exp/Cntr=0.3,0.1

Type RM Length L Ch R = 1,597,341,341,341
BEGIN DESCRIPTION:
Upper Denton 82 1.0
END DESCRIPTION:
XS GIS Cut Line= 4
      2226946.76      7265389.77      2226406.34      7265449.79
      2226332.14      7265697.07      2227361.96      7266446.04
#Sta/Elev= 30
  4306.0 1051.60  4356.2 1052.95  4392.6 1049.76  4446.8 1045.50  4484.9 1036.72
  4525.1 1035.20  4585.5 1026.85  4786.7 1013.22  4826.9 1014.69  4857.4 1009.57
  4922.7 1009.48  4943.9 1004.20  4975.3 1005.20  4991.6 1002.30  4991.8 1002.29
  4992.2 1001.79  4996.2 1002.29  5079.7 1008.32  5308.2 1012.25  5408.7 1010.46
  5530.0 1013.49  5536.8 1015.93  5559.4 1013.59  5659.9 1016.25  5772.7 1023.77
  5795.9 1021.65  5822.9 1022.91  5852.3 1029.01  6196.9 1051.84  6381.3 1059.05
#Mann=7,-1,0
  4306.0    0.12       0  4392.6    0.05       0  4857.4    0.12       0
  4991.6    0.05       0  4991.8   0.033       0  4996.2    0.05       0
  6196.9    0.12       0
Bank Sta=4991.8,4996.2
Exp/Cntr=0.3,0.1

Type RM Length L Ch R = 1,256,0,0,0
BEGIN DESCRIPTION:
Upper Denton 82 0.5
END DESCRIPTION:
XS GIS Cut Line= 5
      2226927.29      7265357.64      2226070.51      7265448.79
      2226044.47      7265524.31      2226278.85      7265677.95
      2226989.79      7266224.83
#Sta/Elev= 30
  4097.0 1049.25  4163.0 1046.59  4185.8 1046.06  4261.2 1037.48  4266.2 1034.37
  4296.4 1034.00  4353.7 1027.00  4648.4 1008.32  4931.2 1003.85  4977.2 1004.71
  5006.2  995.52  5006.6  995.02  5010.6  995.52  5023.4 1002.49  5033.6 1003.43
  5132.3 1003.32  5307.0 1006.98  5327.8 1009.40  5383.9 1007.23  5626.8 1009.28
  5676.6 1012.24  5826.1 1013.96  5840.6 1018.35  5884.2 1016.01  5948.5 1017.65
  6069.0 1025.75  6126.4 1025.66  6139.6 1030.88  6154.1 1032.70  6215.7 1036.29
#Mann=6,-1,0
  4097.0    0.12       0  4163.0    0.05       0  4648.4    0.12       0
  4931.2    0.05       0  5006.2   0.033       0  5010.6    0.05       0
Bank Sta=5006.2,5010.6
Exp/Cntr=0.3,0.1

Chan Stop Cuts=-1