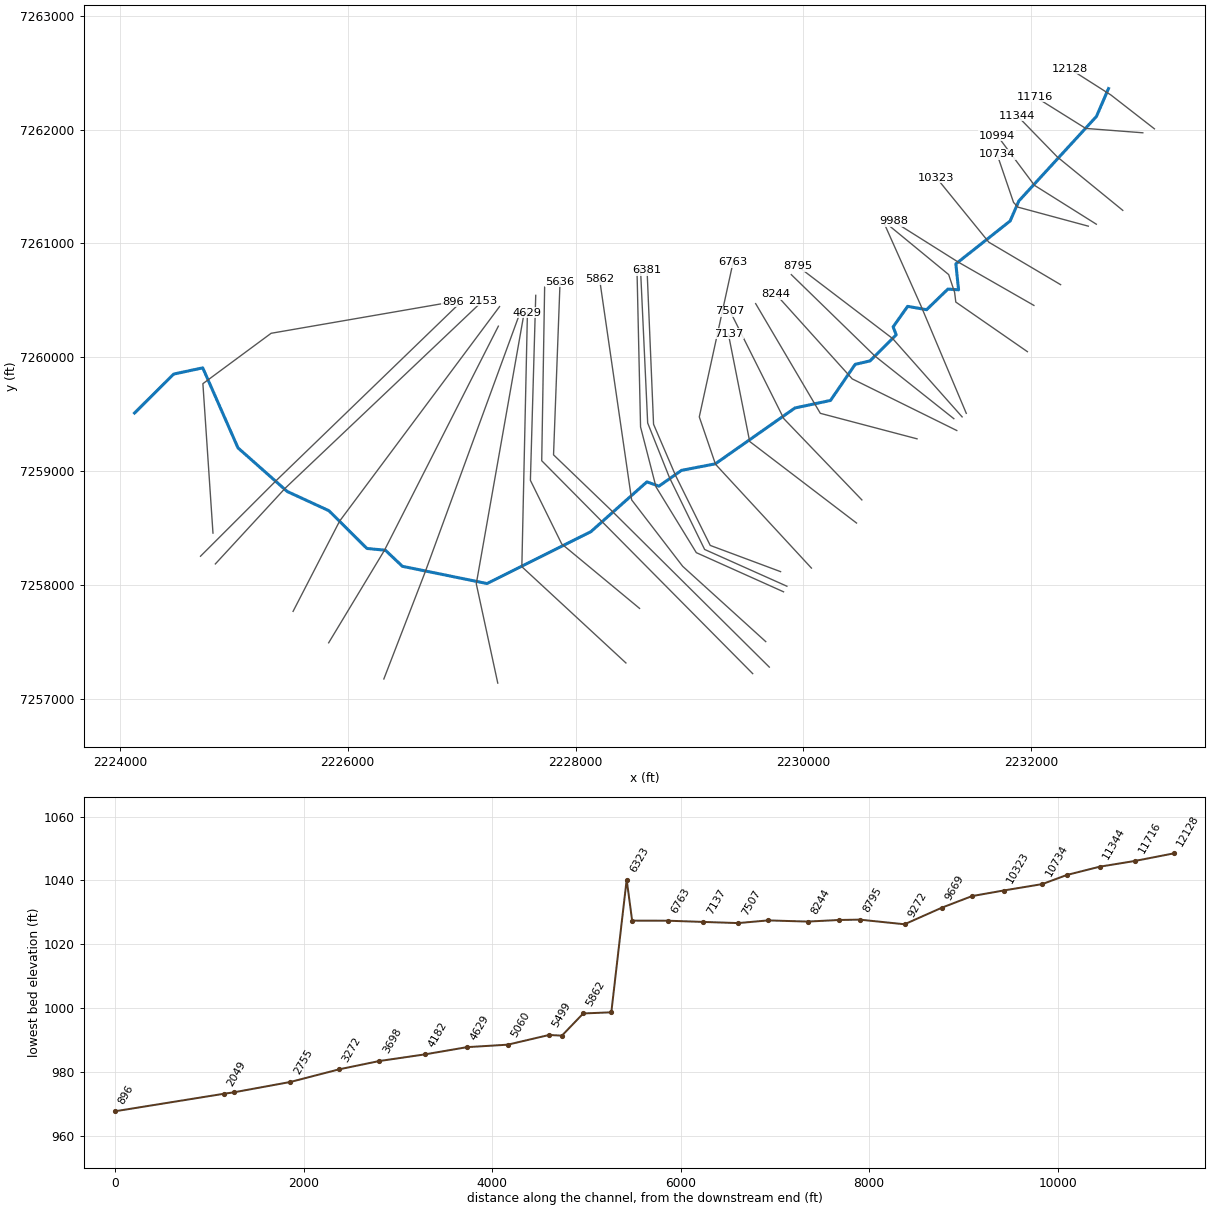
--- Upper Denton 84.prj (project) ---

Proj Title=Upper Denton 84 Base Level Engineering
Current Plan=p01
Default Exp/Contr=0.3,0.1
English Units
Geom File=g01
Flow File=f01
Plan File=p01
Y Axis Title=Elevation
X Axis Title(PF)=Main Channel Distance
X Axis Title(XS)=Station
BEGIN DESCRIPTION:
Upper Denton 84
END DESCRIPTION:
DSS Export Rating Curves= 0
DSS Export Rating Curve Sorted= 0
DSS Export Volume Flow Curves= 0
DXF OffsetX= 0
DXF OffsetY= 0
DXF ScaleX= 1
DXF ScaleY= 10

--- Upper Denton 84.p01 (plan) ---

Plan Title=Multiple Run
Short Identifier=Multiple
Geom File=g01
Flow File=f01
Subcritical Flow
K Sum by GR= 0
Std Step Tol= 0.01
Critical Tol= 0.01
Num of Std Step Trials= 20
Max Error Tol= 0.3
Flow Tol Ratio= 0.001
Split Flow NTrial= 30
Split Flow Tol= 0.02
Split Flow Ratio= 0.02
Log Output Level= 0
Friction Slope Method= 1
Unsteady Friction Slope Method= 2
Unsteady Bridges Friction Slope Method= 1
Parabolic Critical Depth
Global Vel Dist=  1 , 1 , 1
Global Log Level= 0
CheckData=True
Encroach Param= -1, 0, 0, 0
BEGIN DESCRIPTION:
Multiple Run
END DESCRIPTION:

--- Upper Denton 84.f01 (steady flow) ---

Flow Title=Multiple
Program Version=4.10
Number of Profiles= 7
Profile Names=10-year,25-year,50-year,1pct_min,100-year,1pct_plu,500-year
River Rch & RM=Upper Denton 84,Reach-1         ,12128
     883    1264    1593     998    1990    3971    3117
River Rch & RM=Upper Denton 84,Reach-1         ,5862
    1188    1720    2184    1376    2746    5479    4354
Boundary for River Rch & Prof#=Upper Denton 84,Reach-1         , 1
Up Type= 0
Dn Type= 3
Dn Slope=0.004
Boundary for River Rch & Prof#=Upper Denton 84,Reach-1         , 2
Up Type= 0
Dn Type= 3
Dn Slope=0.004
Boundary for River Rch & Prof#=Upper Denton 84,Reach-1         , 3
Up Type= 0
Dn Type= 3
Dn Slope=0.004
Boundary for River Rch & Prof#=Upper Denton 84,Reach-1         , 4
Up Type= 0
Dn Type= 3
Dn Slope=0.004
Boundary for River Rch & Prof#=Upper Denton 84,Reach-1         , 5
Up Type= 0
Dn Type= 3
Dn Slope=0.004
Boundary for River Rch & Prof#=Upper Denton 84,Reach-1         , 6
Up Type= 0
Dn Type= 3
Dn Slope=0.004
Boundary for River Rch & Prof#=Upper Denton 84,Reach-1         , 7
Up Type= 0
Dn Type= 3
Dn Slope=0.004
DSS Import GetInterval= 0
DSS Import GetPeak= 0
DSS Import FillOption= 0

--- Upper Denton 84.g01 (geometry) ---

Geom Title=Existing Conditions
Program Version=4.10

River Reach=Upper Denton 84 ,Reach-1
Reach XY= 30
        2232679.        7262360.      2232573.38      7262115.62
      2231892.54      7261373.54      2231815.38      7261196.79
      2231339.06        7260820.       2231362.6      7260592.39
      2231269.01      7260598.75      2231082.42       7260417.8
      2230915.35      7260446.81      2230788.32      7260266.66
      2230815.35      7260196.67      2230585.17      7259967.86
      2230454.99      7259937.33       2230238.8      7259620.48
      2229926.57      7259554.48      2229227.44      7259063.76
      2228930.58      7259006.17       2228732.4      7258867.83
      2228626.46      7258904.99      2228135.13      7258467.88
      2227223.03      7258012.14       2226480.5      7258163.61
      2226331.45      7258304.53      2226168.88      7258320.35
      2225835.32      7258651.93      2225469.32      7258820.78
      2225037.16      7259203.95      2224727.75      7259906.64
      2224472.83      7259852.14        2224129.        7259510.

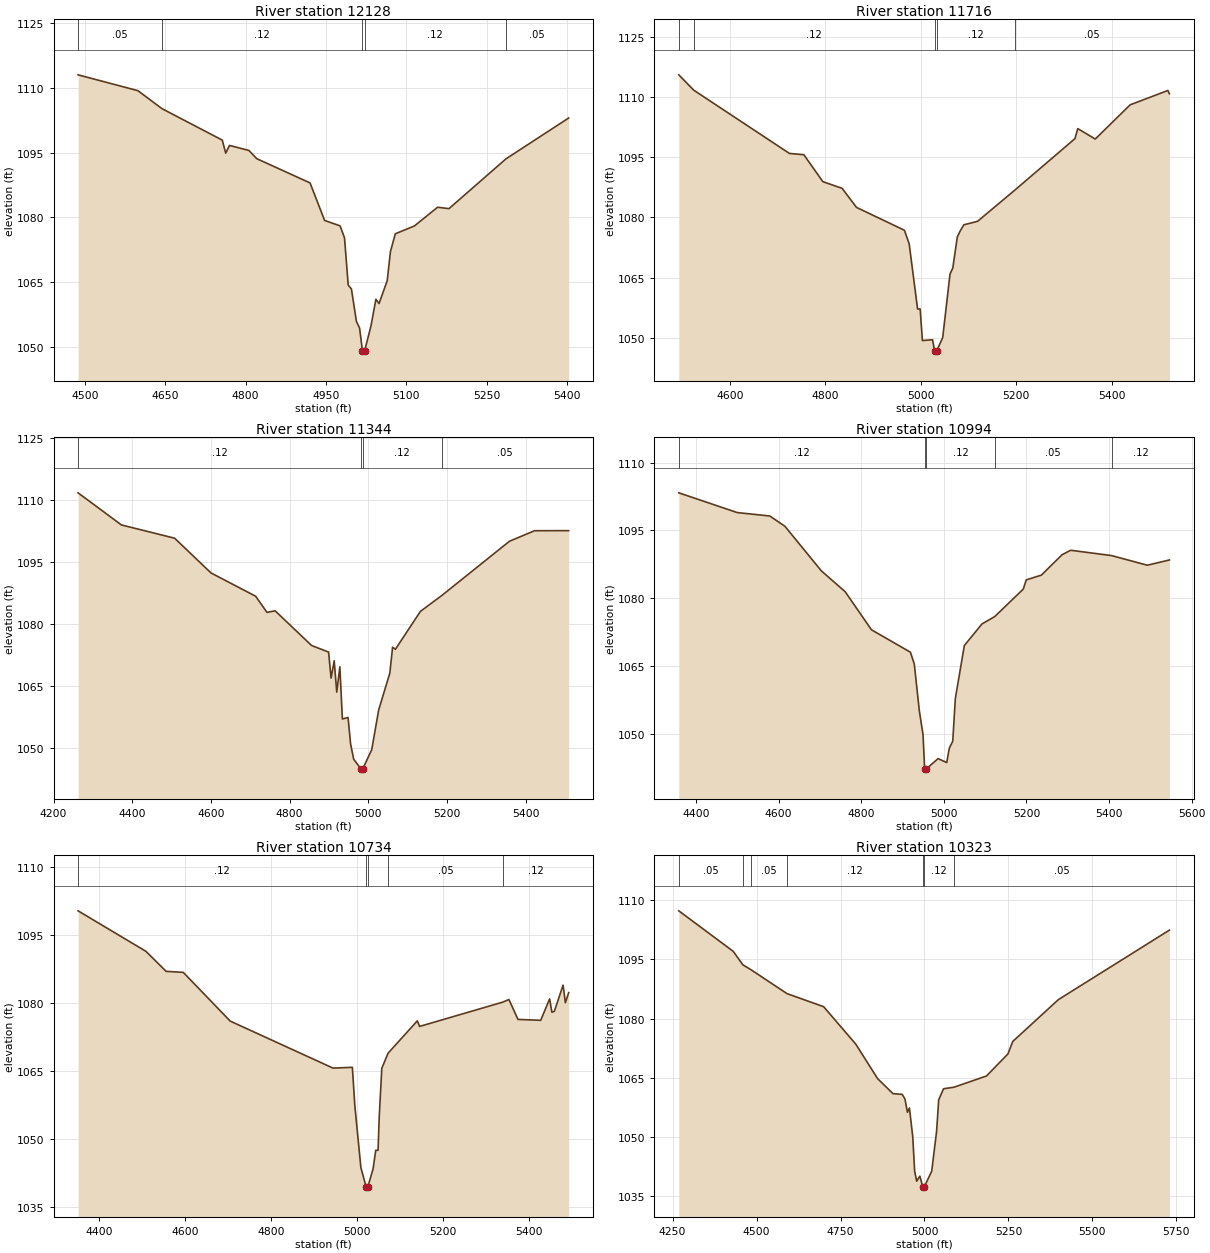
Type RM Length L Ch R = 1 ,12128   ,412,412,412
BEGIN DESCRIPTION:
Upper Denton 84 28.0
END DESCRIPTION:
XS GIS Cut Line= 3
      2233082.03      7262006.32      2232700.12       7262303.6
      2232336.15      7262535.41
#Sta/Elev= 30
  4487.3 1113.08    4599  1109.4    4644 1105.22  4756.4 1097.93  4762.8 1094.91
  4769.9 1096.69  4806.2 1095.53  4820.6 1093.63  4920.2 1087.99  4947.4 1079.28
  4976.2 1078.03  4984.5 1075.25  4991.4 1064.29  4997.4 1063.38  5006.7 1055.85
  5012.6 1054.31    5018 1048.99  5018.3 1048.49    5022 1048.99  5033.8 1054.76
  5043.1 1060.99    5049    1060  5064.2 1065.32  5070.2 1072.05  5079.3 1076.19
  5114.9    1078  5158.2 1082.35  5179.4 1082.02  5285.7 1093.57  5402.8 1103.06
#Mann= 5 ,-1 , 0
  4487.3     .05       0    4644     .12       0    5018     .07       0
    5022     .12       0  5285.7     .05       0
Bank Sta=5018,5022
XS Rating Curve= 0 ,0
Exp/Cntr=0.3,0.1

Type RM Length L Ch R = 1 ,11716   ,372,372,372
BEGIN DESCRIPTION:
Upper Denton 84 27.0
END DESCRIPTION:
XS GIS Cut Line= 3
      2232980.09      7261971.57        2232479.        7262010.
      2232033.95      7262288.37
#Sta/Elev= 30
    4493  1115.6  4524.3 1111.77  4724.8 1095.97  4754.9 1095.66  4794.7 1088.93
  4835.1 1087.26  4865.2  1082.5  4965.5  1076.8  4975.5 1073.42  4993.1 1057.14
  4998.5 1057.14  5003.2 1049.26  5024.4 1049.46  5028.9 1046.62  5029.2 1046.12
  5032.9 1046.62  5045.7 1049.99    5061 1065.83  5066.9 1067.39  5076.3 1075.11
  5082.2 1076.58  5089.9 1078.15  5118.8 1079.03  5196.2 1086.76  5322.7 1099.67
  5328.6 1102.17  5365.2 1099.57  5438.3 1108.11  5517.3 1111.69  5520.5 1110.87
#Mann= 5 ,-1 , 0
    4493     .05       0  4524.3     .12       0  5028.9     .07       0
  5032.9     .12       0  5196.2     .05       0
Bank Sta=5028.9,5032.9
XS Rating Curve= 0 ,0
Exp/Cntr=0.3,0.1

Type RM Length L Ch R = 1 ,11344   ,350,350,350
BEGIN DESCRIPTION:
Upper Denton 84 26.0
END DESCRIPTION:
XS GIS Cut Line= 3
      2232804.31      7261290.12        2232229.        7261760.
      2231877.64      7262121.31
#Sta/Elev= 30
  4262.3 1111.82  4372.5 1104.03  4507.6 1100.82  4600.2 1092.39  4713.6 1086.74
  4742.4 1082.83  4763.2  1083.2  4855.8 1074.79  4898.9 1073.21  4905.3 1066.89
  4913.2 1071.09  4919.7 1063.49  4927.6 1069.64    4934 1056.97  4948.4 1057.34
  4954.9 1050.91  4962.8 1047.21  4981.6 1044.83  4981.8 1044.33  4985.6 1044.83
  5008.6 1049.53  5026.3 1059.19  5054.6  1068.1  5061.6 1074.37  5068.8 1073.88
  5132.3 1083.07  5186.9 1086.94  5358.7 1100.08  5422.4 1102.63  5509.1 1102.65
#Mann= 4 ,-1 , 0
  4262.3     .12       0  4981.6     .07       0  4985.6     .12       0
  5186.9     .05       0
Bank Sta=4981.6,4985.6
XS Rating Curve= 0 ,0
Exp/Cntr=0.3,0.1

Type RM Length L Ch R = 1 ,10994   ,260,260,260
BEGIN DESCRIPTION:
Upper Denton 84 25.0
END DESCRIPTION:
XS GIS Cut Line= 3
      2232572.05      7261168.64        2232029.        7261510.
      2231701.84      7261947.72
#Sta/Elev= 30
  4358.2 1103.32  4499.7 1098.95  4578.6 1098.19  4615.1 1095.92  4703.4 1086.05
  4761.1 1081.43  4824.7 1073.01    4919 1068.05  4928.4 1065.44  4940.6 1055.09
  4949.6 1049.76  4953.5 1042.23  4953.7 1041.73  4957.5 1042.23  4986.1  1044.5
  5006.9 1043.62  5013.2  1046.8  5021.5 1048.35  5027.8  1057.8  5049.6 1069.53
  5092.4 1074.31  5123.3 1075.94  5192.4 1082.03  5199.4 1084.05  5236.2 1085.11
  5286.2 1089.62  5307.1 1090.61  5406.1 1089.43  5492.6  1087.3  5546.1 1088.46
#Mann= 5 ,-1 , 0
  4358.2     .12       0  4953.5     .07       0  4957.5     .12       0
  5123.3     .05       0  5406.1     .12       0
Bank Sta=4953.5,4957.5
XS Rating Curve= 0 ,0
Exp/Cntr=0.3,0.1

Type RM Length L Ch R = 1 ,10734   ,411,411,411
BEGIN DESCRIPTION:
Upper Denton 84 24.0
END DESCRIPTION:
XS GIS Cut Line= 4
      2232501.62       7261151.4      2231885.31      7261318.07
      2231845.37      7261359.73      2231701.27      7261781.64
#Sta/Elev= 30
    4351 1100.31  4509.1 1091.36    4556 1086.95  4595.9 1086.72  4705.1 1075.97
  4944.4 1065.59  4989.5 1065.76  4995.2 1057.36  5009.3 1043.63  5021.5 1039.37
  5021.8 1038.87  5025.5 1039.37  5037.7 1043.35  5043.9 1047.44  5049.3 1047.44
  5052.1 1054.96    5058 1065.55  5072.7 1068.89  5140.7 1076.02    5146 1074.79
  5339.2 1080.14  5353.9 1080.73    5375 1076.34  5427.9 1076.14  5448.7 1080.87
  5453.9 1077.93  5459.6 1078.12    5480  1083.9  5485.3 1080.02    5493 1082.25
#Mann= 5 ,-1 , 0
    4351     .12       0  5021.5     .07       0  5025.5     .12       0
  5072.7     .05       0  5339.2     .12       0
Bank Sta=5021.5,5025.5
XS Rating Curve= 0 ,0
Exp/Cntr=0.3,0.1

Type RM Length L Ch R = 1 ,10323   ,335,335,335
BEGIN DESCRIPTION:
Upper Denton 84 23.0
END DESCRIPTION:
XS GIS Cut Line= 3
      2232258.59       7260637.5        2231629.        7261010.
      2231168.99      7261575.88
#Sta/Elev= 30
  4268.5 1107.24  4430.7 1096.99  4459.1  1093.6  4484.3  1092.3  4590.5 1086.31
  4699.7    1083  4795.3 1073.55  4860.6 1064.79  4906.5    1061  4933.7 1060.82
  4941.9 1059.66  4949.3 1056.29  4955.2 1057.38    4965 1050.22  4970.8 1041.37
  4976.8 1038.87  4986.4 1040.15  4995.1 1037.36  4995.4 1036.86  4999.1 1037.36
  5021.6 1041.41    5036  1051.4  5042.4 1059.45  5056.8 1062.24  5088.2 1062.64
  5184.6 1065.47  5248.5 1071.05  5262.9  1074.2  5398.7 1084.78  5729.3 1102.36
#Mann= 7 ,-1 , 0
  4268.5     .05       0  4459.1     .12       0  4484.3     .05       0
  4590.5     .12       0  4995.1     .07       0  4999.1     .12       0
  5088.2     .05       0
Bank Sta=4995.1,4999.1
XS Rating Curve= 0 ,0
Exp/Cntr=0.3,0.1

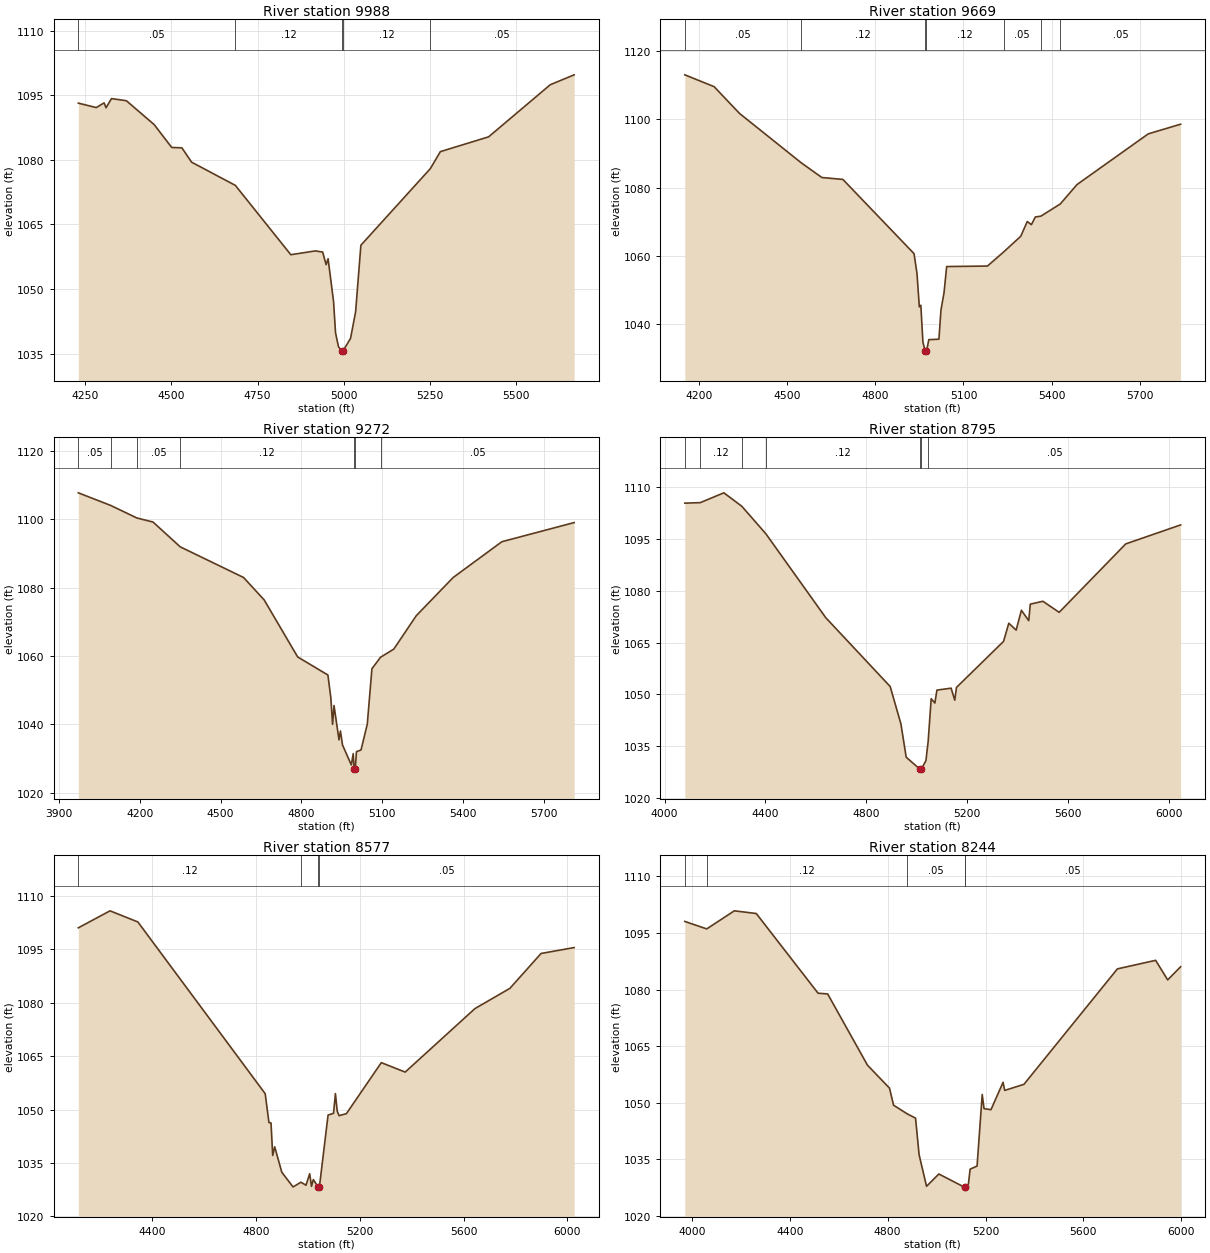
Type RM Length L Ch R = 1 ,9988    ,319,319,319
BEGIN DESCRIPTION:
Upper Denton 84 22.0
END DESCRIPTION:
XS GIS Cut Line= 3
      2232024.22      7260455.21      2231357.53      7260837.16
      2230789.84      7261194.79
#Sta/Elev= 30
  4229.8  1093.2  4281.9 1092.17  4304.5 1093.26  4310.3 1092.13  4326.1 1094.26
  4369.3 1093.76  4449.8 1088.23  4500.9  1082.9  4530.4 1082.82  4558.5 1079.49
  4685.6 1074.09  4846.6 1057.98  4917.4 1058.86    4939  1058.6  4949.1 1055.67
  4954.8 1057.05  4970.7 1047.09  4976.4 1039.84  4984.9 1036.62    4994 1035.61
  4994.2 1035.11    4998 1035.61    5020 1038.54  5034.7 1044.71    5050 1060.18
  5251.7 1077.99  5280.7 1081.93  5420.8 1085.37  5599.8 1097.48  5669.1 1099.78
#Mann= 5 ,-1 , 0
  4229.8     .05       0  4685.6     .12       0    4994     .07       0
    4998     .12       0  5251.7     .05       0
Bank Sta=4994,4998
XS Rating Curve= 0 ,0
Exp/Cntr=0.3,0.1

Type RM Length L Ch R = 1 ,9669    ,397,397,397
BEGIN DESCRIPTION:
Upper Denton 84 21.0
END DESCRIPTION:
XS GIS Cut Line= 5
      2231966.91      7260048.96      2231338.43      7260484.73
      2231328.01       7260569.8      2231275.93      7260726.05
      2230756.83      7261153.14
#Sta/Elev= 30
  4151.7  1113.1  4251.3 1109.64  4337.8 1101.79  4547.7 1087.32  4618.1 1082.99
  4689.7 1082.43  4931.9 1060.66  4941.9 1054.83  4949.9 1045.04    4955 1045.52
  4962.1 1034.69  4970.2 1031.99  4970.4 1031.49  4974.2 1031.99  4982.2 1035.45
  5016.5 1035.57  5023.5 1044.11    5034 1049.27  5042.9 1056.88  5181.6 1057.02
    5237 1061.17    5295 1065.75  5317.2 1070.09  5331.3 1069.16  5344.5 1071.41
  5363.6 1071.66  5429.5 1075.23  5486.6 1080.93    5729 1095.79  5839.1 1098.62
#Mann= 7 ,-1 , 0
  4151.7     .05       0  4547.7     .12       0  4970.2     .07       0
  4974.2     .12       0    5237     .05       0  5363.6     .12       0
  5429.5     .05       0
Bank Sta=4970.2,4974.2
XS Rating Curve= 0 ,0
Exp/Cntr=0.3,0.1

Type RM Length L Ch R = 1 ,9272    ,477,477,477
BEGIN DESCRIPTION:
Upper Denton 84 20.0
END DESCRIPTION:
XS GIS Cut Line= 3
      2231430.46      7259507.26        2231029.        7260460.
      2230701.29      7261194.77
#Sta/Elev= 30
  3972.7 1107.75  4093.2 1104.04    4190 1100.38  4249.6  1099.2  4350.5 1091.94
  4585.2 1082.97  4661.8  1076.4  4785.9 1059.71  4898.1 1054.42  4908.9 1047.79
  4915.4 1039.97  4920.8 1045.49  4939.1 1035.44  4944.5 1038.03  4952.3 1033.92
  4984.9 1028.09    4992  1031.4  4995.4 1026.78  4995.7 1026.28  4999.4 1026.78
  5003.9 1031.97  5020.9 1032.48  5044.1 1040.05  5061.3 1056.26  5093.3 1059.62
  5142.5 1062.01  5225.6 1071.77  5362.5 1082.96  5543.1 1093.44  5811.1 1099.04
#Mann= 7 ,-1 , 0
  3972.7     .05       0  4093.2     .12       0    4190     .05       0
  4350.5     .12       0  4995.4     .07       0  4999.4     .12       0
  5093.3     .05       0
Bank Sta=4995.4,4999.4
XS Rating Curve= 0 ,0
Exp/Cntr=0.3,0.1

Type RM Length L Ch R = 1 ,8795    ,218,218,218
BEGIN DESCRIPTION:
Upper Denton 84 19.0
END DESCRIPTION:
XS GIS Cut Line= 3
      2231393.97      7259476.07      2230784.61      7260163.55
      2229952.64      7260797.93
#Sta/Elev= 30
  4080.3 1105.46  4141.5  1105.6  4235.1 1108.45  4306.4 1104.54  4401.6 1096.57
  4639.1 1072.22  4894.2 1052.27  4936.8 1041.42  4957.7 1031.77  5013.1 1028.23
  5013.3 1027.73  5017.1 1028.23  5035.9 1030.77  5044.7 1036.33  5056.7 1048.74
  5071.3 1047.48  5079.5 1051.23  5135.7 1051.79  5150.2 1048.31  5156.9 1052.01
  5343.5 1065.36  5364.3 1070.63  5393.4 1068.63  5414.2 1074.39  5443.3 1071.37
  5449.5 1076.16  5499.4    1077  5563.9 1073.79  5827.8 1093.64  6045.2 1099.14
#Mann= 7 ,-1 , 0
  4080.3     .05       0  4141.5     .12       0  4306.4     .05       0
  4401.6     .12       0  5013.1     .07       0  5017.1     .12       0
  5044.7     .05       0
Bank Sta=5013.1,5017.1
XS Rating Curve= 0 ,0
Exp/Cntr=0.3,0.1

Type RM Length L Ch R = 1 ,8577    ,333,333,333
BEGIN DESCRIPTION:
Upper Denton 84 18.0
END DESCRIPTION:
XS GIS Cut Line= 3
       2231321.1       7259460.4        2230629.        7260010.
       2229894.5      7260725.55
#Sta/Elev= 30
  4116.5 1101.09  4238.5 1105.87  4345.8 1102.74    4836 1054.46  4850.5 1046.34
  4858.5 1046.21  4864.9 1037.09  4872.6 1039.52  4900.1 1032.35  4943.4 1028.23
  4973.5 1029.57  4993.1 1028.72  5007.4 1031.95  5014.3 1028.41  5021.5 1030.31
  5040.6 1028.12  5040.9 1027.62  5044.6 1028.12  5078.1 1048.43  5099.2 1048.95
  5106.4 1054.48  5113.4 1049.53  5120.5 1048.28  5148.8 1048.84  5283.1 1063.18
  5375.1 1060.53  5643.7 1078.38  5778.2 1084.07  5898.3 1093.88  6025.7 1095.54
#Mann= 4 ,-1 , 0
  4116.5     .12       0  4973.5     .05       0  5040.6    .033       0
  5044.6     .05       0
Bank Sta=5040.6,5044.6
XS Rating Curve= 0 ,0
Exp/Cntr=0.3,0.1

Type RM Length L Ch R = 1 ,8244    ,421,421,421
BEGIN DESCRIPTION:
Upper Denton 84 17.0
END DESCRIPTION:
XS GIS Cut Line= 3
      2231347.11      7259356.26        2230429.        7259810.
       2229758.6      7260554.14
#Sta/Elev= 30
  3971.4 1098.05  4061.1 1096.07  4173.7 1100.86  4263.4 1100.15  4515.9 1079.03
  4555.1 1078.84  4717.8 1059.96  4807.6 1053.89  4824.4 1049.36  4879.7 1047.08
  4914.2 1045.93  4928.6 1036.24  4959.1 1027.87  5009.3 1031.13  5114.2 1027.62
  5114.5 1027.12  5118.2 1027.62  5130.1 1028.46  5137.1 1032.41  5165.5 1033.23
  5186.5 1052.19  5193.9 1048.45  5222.3 1048.17  5271.7 1055.42  5278.4 1053.28
  5356.9 1054.88  5738.8 1085.48    5895 1087.74  5944.3 1082.56  5997.1 1086.04
#Mann= 5 ,-1 , 0
  3971.4     .05       0  4061.1     .12       0  4879.7     .05       0
  5114.2    .033       0  5118.2     .05       0
Bank Sta=5114.2,5118.2
XS Rating Curve= 0 ,0
Exp/Cntr=0.3,0.1

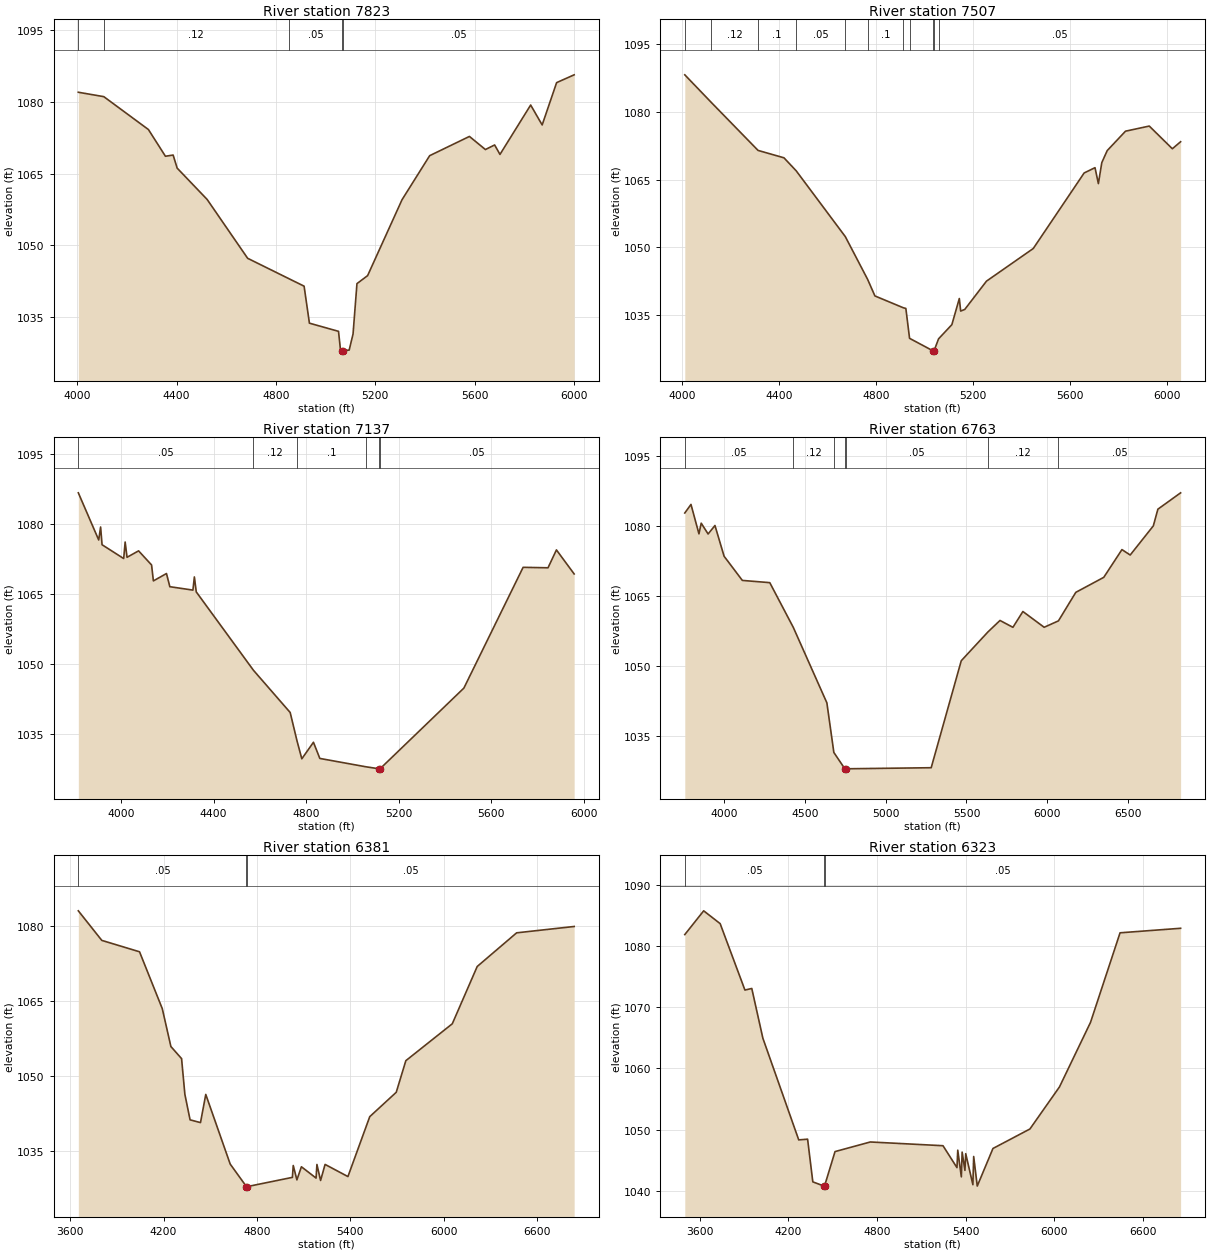
Type RM Length L Ch R = 1 ,7823    ,316,316,316
BEGIN DESCRIPTION:
Upper Denton 84 16.0
END DESCRIPTION:
XS GIS Cut Line= 3
      2230998.11      7259283.36      2230149.19       7259507.3
      2229581.49      7260470.84
#Sta/Elev= 30
  4004.3 1081.99  4106.9 1081.07  4286.5  1074.2    4355 1068.62    4386 1068.87
  4402.2 1066.14    4523 1059.59    4686  1047.3  4852.2 1043.04  4913.3 1041.48
  4934.7 1033.75  5051.9 1032.04  5059.5  1028.3  5065.5 1027.99  5065.8 1027.49
  5069.5 1027.99  5094.8 1028.13  5110.4 1031.49  5126.1 1042.01    5169 1043.68
  5307.6 1059.54  5418.9 1068.74    5579 1072.76  5643.3 1070.02  5680.5 1070.98
  5701.9    1069  5825.5 1079.32  5871.8 1075.16    5930    1084  6000.6 1085.63
#Mann= 5 ,-1 , 0
  4004.3     .05       0  4106.9     .12       0  4852.2     .05       0
  5065.5    .033       0  5069.5     .05       0
Bank Sta=5065.5,5069.5
XS Rating Curve= 0 ,0
Exp/Cntr=0.3,0.1

Type RM Length L Ch R = 1 ,7507    ,370,370,370
BEGIN DESCRIPTION:
Upper Denton 84 15.0
END DESCRIPTION:
XS GIS Cut Line= 3
       2230513.8      7258746.86        2229829.        7259460.
      2229357.53      7260403.13
#Sta/Elev= 30
  4011.3 1088.13  4120.5 1082.03  4313.2 1071.43  4419.9  1069.8  4470.4 1066.92
  4672.8 1052.38  4764.6 1042.95  4794.8 1039.28  4911.7 1036.67  4922.2 1036.52
  4937.5 1029.92  5034.3 1027.15  5034.6 1026.65  5038.3 1027.15    5057 1029.81
  5111.8 1032.94  5142.5 1038.71  5148.1 1035.94  5164.9  1036.3  5254.4 1042.55
  5447.2 1049.76  5656.9 1066.45  5701.6 1067.62  5715.5  1064.1  5729.6 1068.73
  5751.9 1071.39  5827.3 1075.68  5925.2 1076.81  6020.3  1071.8  6054.4 1073.35
#Mann= 11 ,-1 , 0
  4011.3     .05       0  4120.5     .12       0  4313.2      .1       0
  4470.4     .05       0  4672.8     .12       0  4764.6      .1       0
  4911.7     .05       0  4937.5      .1       0  5034.3     .07       0
  5038.3      .1       0    5057     .05       0
Bank Sta=5034.3,5038.3
XS Rating Curve= 0 ,0
Exp/Cntr=0.3,0.1

Type RM Length L Ch R = 1 ,7137    ,374,374,374
BEGIN DESCRIPTION:
Upper Denton 84 14.0
END DESCRIPTION:
XS GIS Cut Line= 3
      2230466.91      7258543.76        2229529.        7259260.
      2229341.92      7260205.14
#Sta/Elev= 30
  3815.2 1086.63  3903.3 1076.53  3911.5 1079.31  3917.8 1075.51  4011.3 1072.55
  4017.6 1076.09  4025.8 1072.82  4075.7  1074.2  4131.9 1071.17  4139.7 1067.76
  4196.3 1069.34  4210.8 1066.52  4310.6 1065.79  4316.9 1068.61  4325.1  1065.4
  4572.2 1048.62  4731.1 1039.57  4760.8 1033.46  4781.4 1029.65  4831.7 1033.19
  4859.2 1029.73  5059.7 1027.93  5115.6 1027.51  5115.9 1027.01  5119.6 1027.51
  5482.1  1044.8  5738.2 1070.67  5845.8 1070.57  5882.2  1074.4  5958.8 1069.25
#Mann= 6 ,-1 , 0
  3815.2     .05       0  4572.2     .12       0  4760.8      .1       0
  5059.7     .05       0  5115.6     .07       0  5119.6     .05       0
Bank Sta=5115.6,5119.6
XS Rating Curve= 0 ,0
Exp/Cntr=0.3,0.1

Type RM Length L Ch R = 1 ,6763    ,382,382,382
BEGIN DESCRIPTION:
Upper Denton 84 13.0
END DESCRIPTION:
XS GIS Cut Line= 4
      2230071.04      7258147.96        2229229.        7259060.
      2229086.69      7259476.05      2229383.52      7260835.19
#Sta/Elev= 30
  3754.6 1082.76  3792.9  1084.6  3842.3 1078.29  3856.4 1080.58    3899 1078.26
  3941.5 1080.08  3998.2 1073.48  4111.2  1068.3  4281.2 1067.82  4426.8 1058.23
    4635 1042.03  4678.2 1031.39  4746.4 1027.89  4746.6 1027.39  4750.4 1027.89
  5281.3 1028.12  5467.6 1051.07  5632.4 1057.23  5707.6 1059.71  5787.7 1058.24
  5849.5 1061.63  5981.2 1058.25  6069.7 1059.62  6177.3 1065.74  6350.6 1068.96
  6463.2 1074.91  6514.4 1073.75  6657.7    1080  6685.9 1083.58  6826.8 1087.09
#Mann= 7 ,-1 , 0
  3754.6     .05       0  4426.8     .12       0  4678.2     .05       0
  4746.4    .033       0  4750.4     .05       0  5632.4     .12       0
  6069.7     .05       0
Bank Sta=4746.4,4750.4
XS Rating Curve= 0 ,0
Exp/Cntr=0.3,0.1

Type RM Length L Ch R = 1 ,6381    ,58,58,58
BEGIN DESCRIPTION:
Upper Denton 84 12.0
END DESCRIPTION:
XS GIS Cut Line= 5
      2229800.28      7258116.66      2229182.74      7258346.98
        2228879.        7258960.      2228685.25      7259411.14
      2228628.36      7260762.53
#Sta/Elev= 30
  3652.2 1083.06    3803 1077.15  4045.6 1074.87  4191.8  1063.5  4247.1 1055.93
  4315.8 1053.51    4337 1046.37  4370.5 1041.27  4437.4 1040.72  4471.3 1046.35
  4628.3 1032.43  4732.8 1027.92    4733 1027.42  4736.8 1027.92    5028 1029.77
  5033.5 1032.14    5057 1029.27    5086 1031.89  5180.2 1029.63  5185.7 1032.35
  5209.2 1029.15  5238.2 1032.36    5385 1029.93  5525.3 1041.91  5695.5 1046.78
  5757.2  1053.1  6055.8 1060.48  6215.9 1071.93  6469.2 1078.66    6839 1079.93
#Mann= 3 ,-1 , 0
  3652.2     .05       0  4732.8    .033       0  4736.8     .05       0
Bank Sta=4732.8,4736.8
XS Rating Curve= 0 ,0
Exp/Cntr=0.3,0.1

Type RM Length L Ch R = 1 ,6323    ,163,163,163
BEGIN DESCRIPTION:
Upper Denton 84 11.6
END DESCRIPTION:
XS GIS Cut Line= 5
      2229855.77      7257988.63      2229133.52      7258311.56
       2228824.5      7258943.51      2228633.52      7259422.67
      2228571.02      7260769.89
#Sta/Elev= 30
  3497.5 1081.84  3625.4 1085.72    3737 1083.63  3904.9 1072.78  3951.3 1073.04
  4026.4 1064.92  4269.4 1048.31  4329.5 1048.43  4364.8 1041.46  4440.1 1040.77
  4440.3 1040.27  4444.1 1040.77  4515.2  1046.4  4754.4 1047.97  5246.7 1047.36
  5341.4 1043.78  5346.8 1046.63    5371 1042.27  5376.4 1046.32  5395.3 1043.33
  5400.7 1046.06  5449.2    1041  5454.6  1045.6  5478.9 1040.77  5585.3 1046.91
  5835.6 1050.09  6035.8 1056.96  6246.1  1067.5  6446.3 1082.13  6856.6 1082.87
#Mann= 3 ,-1 , 0
  3497.5     .05       0  4440.1    .033       0  4444.1     .05       0
Bank Sta=4440.1,4444.1
XS Rating Curve= 0 ,0
Exp/Cntr=0.3,0.1

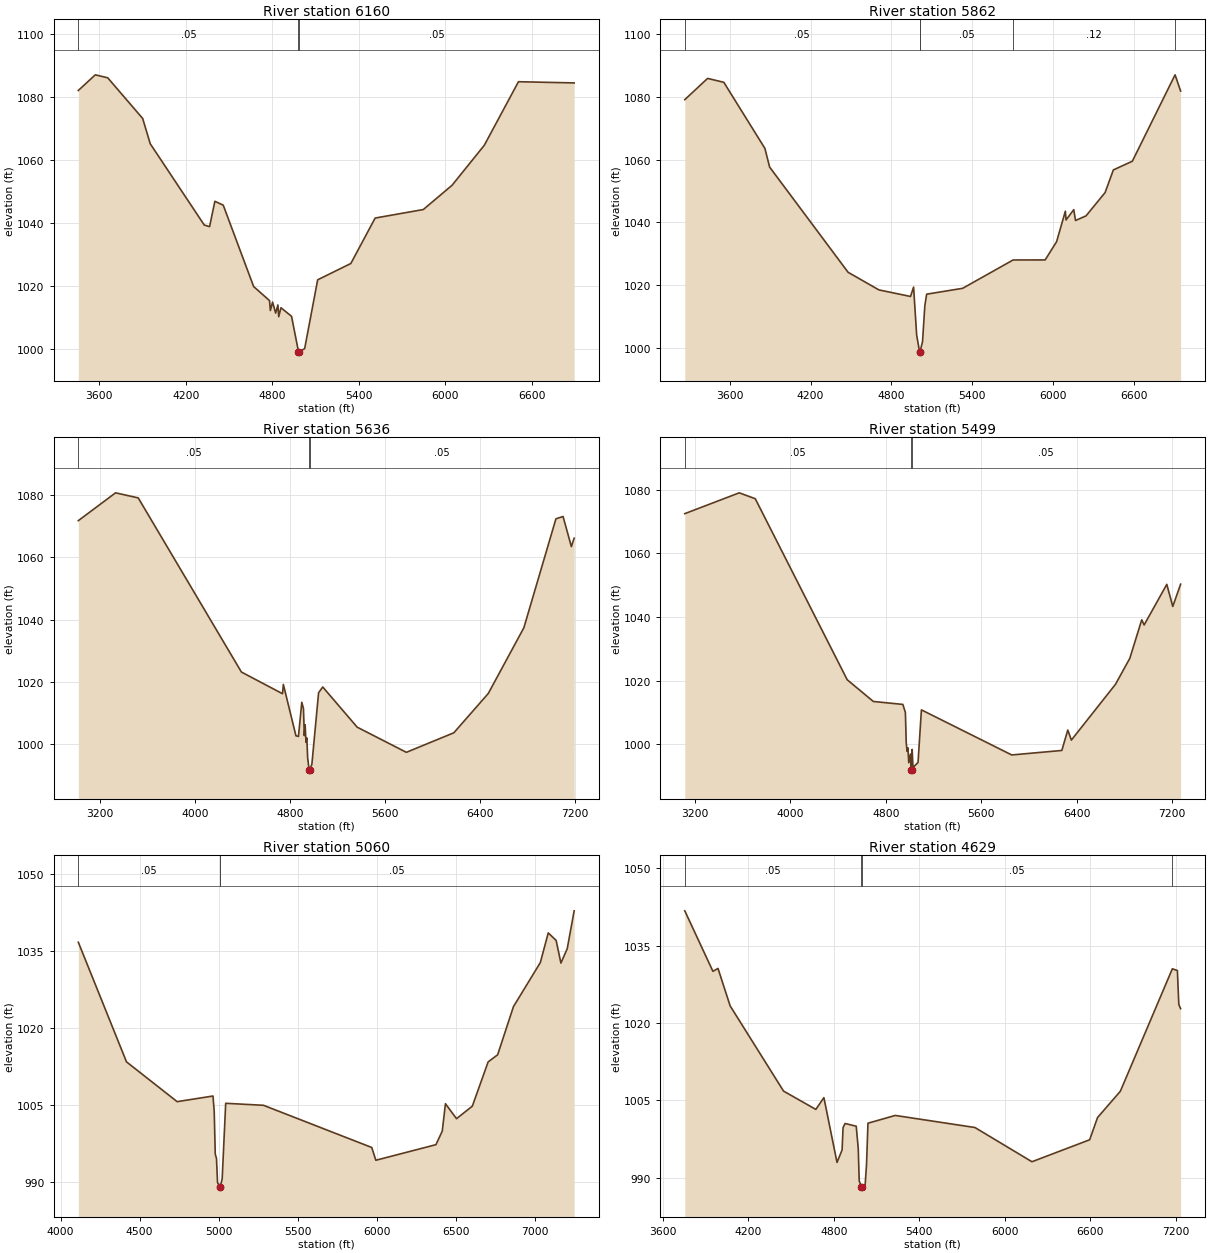
Type RM Length L Ch R = 1 ,6160    ,298,298,298
BEGIN DESCRIPTION:
Upper Denton 84 11.5
END DESCRIPTION:
XS GIS Cut Line= 5
      2229826.26       7257939.6      2229060.65      7258283.34
      2228706.49      7258861.47      2228571.07      7259387.51
      2228539.85      7260766.34
#Sta/Elev= 30
    3454  1082.1  3571.6 1087.07  3658.1 1086.12  3900.4 1073.21  3952.6  1065.2
  4327.7 1039.36  4364.5 1038.86  4401.2  1046.9  4459.2 1045.68  4670.1 1019.83
  4780.3 1015.36  4786.1 1012.21  4801.6 1014.89  4822.9 1011.39  4838.3 1013.98
  4844.2 1010.24  4859.6 1013.09  4933.1 1010.38  4981.2  999.18  4981.4  998.68
  4985.2  999.18  5023.9 1000.08  5114.3 1021.96  5344.4 1027.15  5513.1 1041.58
    5847 1044.28    6047 1052.01  6270.3  1064.7  6507.2 1084.88  6893.6  1084.5
#Mann= 3 ,-1 , 0
    3454     .05       0  4981.2    .033       0  4985.2     .05       0
Bank Sta=4981.2,4985.2
XS Rating Curve= 0 ,0
Exp/Cntr=0.3,0.1

Type RM Length L Ch R = 1 ,5862    ,226,226,226
BEGIN DESCRIPTION:
Upper Denton 84 11.0
END DESCRIPTION:
XS GIS Cut Line= 4
      2229670.03      7257502.09      2228940.86      7258163.55
      2228492.94      7258746.89      2228211.69      7260684.43
#Sta/Elev= 30
    3267 1079.08  3436.1 1085.85  3556.4 1084.61  3861.2 1063.55  3896.3 1057.59
  4478.2 1024.08  4706.6 1018.47  4941.4 1016.37  4964.1 1019.36  4986.9 1004.07
  5008.2  998.82  5008.6  998.32  5012.4  998.82  5030.5 1002.03  5047.4 1013.38
  5060.8  1017.1  5328.1 1018.97  5702.3    1028  5939.9 1028.01  6024.8 1033.82
  6089.9 1043.55    6095 1040.75  6152.1 1044.03  6165.1 1040.58  6243.1 1042.05
  6384.6 1049.48  6445.8 1056.69  6586.7 1059.46  6903.7 1086.99  6944.8 1081.84
#Mann= 5 ,-1 , 0
    3267     .05       0  5008.2    .033       0  5012.4     .05       0
  5702.3     .12       0  6903.7     .05       0
Bank Sta=5008.2,5012.4
XS Rating Curve= 0 ,0
Exp/Cntr=0.3,0.1

Type RM Length L Ch R = 1 ,5636    ,137,137,137
BEGIN DESCRIPTION:
Upper Denton 84 10.5
END DESCRIPTION:
XS GIS Cut Line= 4
      2229701.26      7257278.15      2228310.65      7258658.34
      2227807.18      7259142.72      2227864.47      7260663.53
#Sta/Elev= 30
    3017  1071.8    3331 1080.73    3522  1079.1  4391.7 1023.19  4738.2 1016.23
  4745.3 1019.21  4851.4 1002.73  4872.5 1002.51  4900.8 1013.47    4915 1011.44
  4922.1 1002.77  4929.1 1006.24  4936.2 1000.62  4943.3 1002.02  4950.3  995.59
  4962.4  991.87  4962.7  991.37  4966.6  991.87  4985.7  993.53  5042.3 1016.53
  5077.5 1018.39  5367.5 1005.49  5782.3  997.41  6182.6 1003.68  6472.8  1016.3
    6773 1037.42  7043.2 1072.39  7103.2 1073.13  7173.3 1063.46  7196.8 1066.16
#Mann= 3 ,-1 , 0
    3017     .05       0  4962.4    .033       0  4966.6     .05       0
Bank Sta=4962.4,4966.6
XS Rating Curve= 0 ,0
Exp/Cntr=0.3,0.1

Type RM Length L Ch R = 1 ,5499    ,439,439,439
BEGIN DESCRIPTION:
Upper Denton 84 10.0
END DESCRIPTION:
XS GIS Cut Line= 4
      2229555.42      7257220.87        2228229.        7258560.
      2227703.44      7259091.05      2227729.04      7260615.84
#Sta/Elev= 30
  3115.4 1072.44  3571.9 1078.98  3706.2 1077.13    4477 1020.27  4696.2 1013.45
  4943.7 1012.52  4964.9 1009.98    4972 1000.42    4979  997.78  4986.1   998.9
  4993.2  994.21  5007.3  996.93  5012.3  992.07  5012.6  991.57  5016.5  992.07
  5021.5  998.38  5028.5  992.71  5070.9   994.3  5099.2 1010.81  5856.4  996.65
  6276.4  998.06  6326.4 1004.47  6356.4 1001.32  6726.5 1018.85  6846.5 1027.01
  6946.5  1039.1  6966.5 1037.48  7156.5 1050.23  7206.6 1043.29  7272.4 1050.29
#Mann= 3 ,-1 , 0
  3115.4     .05       0  5012.3    .033       0  5016.5     .05       0
Bank Sta=5012.3,5016.5
XS Rating Curve= 0 ,0
Exp/Cntr=0.3,0.1

Type RM Length L Ch R = 1 ,5060    ,431,431,431
BEGIN DESCRIPTION:
Upper Denton 84 9.0
END DESCRIPTION:
XS GIS Cut Line= 4
      2228562.42      7257793.73        2227879.        7258360.
      2227604.06      7258918.76      2227650.93       7260543.8
#Sta/Elev= 30
  4112.4 1036.68  4417.1 1013.35  4737.5 1005.59  4964.1 1006.69  4971.9 1003.63
  4978.4  995.36  4986.3   994.5  4992.8  989.82  5006.3  989.03  5006.6  988.53
  5010.5  989.03  5022.2  990.54  5044.5 1005.27  5283.6 1004.88  5968.3  996.65
  5994.1  994.16  6374.2   997.2  6414.2  999.84  6434.3 1005.19  6504.3 1002.27
  6604.3 1004.71  6704.4 1013.35  6764.4 1014.73  6864.4 1024.12  7034.5 1032.72
  7084.5  1038.5  7134.5 1037.04  7164.6 1032.62  7204.6 1035.42  7248.4 1042.81
#Mann= 3 ,-1 , 0
  4112.4     .05       0  5006.3     .04       0  5010.5     .05       0
Bank Sta=5006.3,5010.5
XS Rating Curve= 0 ,0
Exp/Cntr=0.3,0.1

Type RM Length L Ch R = 1 ,4629    ,447,447,447
BEGIN DESCRIPTION:
Upper Denton 84 8.0
END DESCRIPTION:
XS GIS Cut Line= 3
      2228442.63      7257314.56        2227529.        7258160.
      2227578.01      7260392.68
#Sta/Elev= 30
  3755.2 1041.73  3952.5    1030  3988.2 1030.56  4073.2  1023.3    4448 1006.77
  4674.3 1003.22    4731  1005.5  4822.9  992.94  4858.5  995.35  4865.3  999.68
  4879.5 1000.49  4957.7  999.96  4971.9  995.65  4978.7  989.33  4994.4  988.26
  4994.8  987.76  4998.7  988.26    5020  988.49    5030  992.57    5040 1000.54
  5231.4 1002.05  5790.2  999.71  6190.3  993.07  6595.1  997.33  6650.4 1001.64
  6810.4 1006.74  7175.2 1030.49  7210.5 1030.15  7220.5 1023.58  7233.2 1022.76
#Mann= 4 ,-1 , 0
  3755.2     .05       0  4994.4     .04       0  4998.7     .05       0
  7175.2     .12       0
Bank Sta=4994.4,4998.7
XS Rating Curve= 0 ,0
Exp/Cntr=0.3,0.1

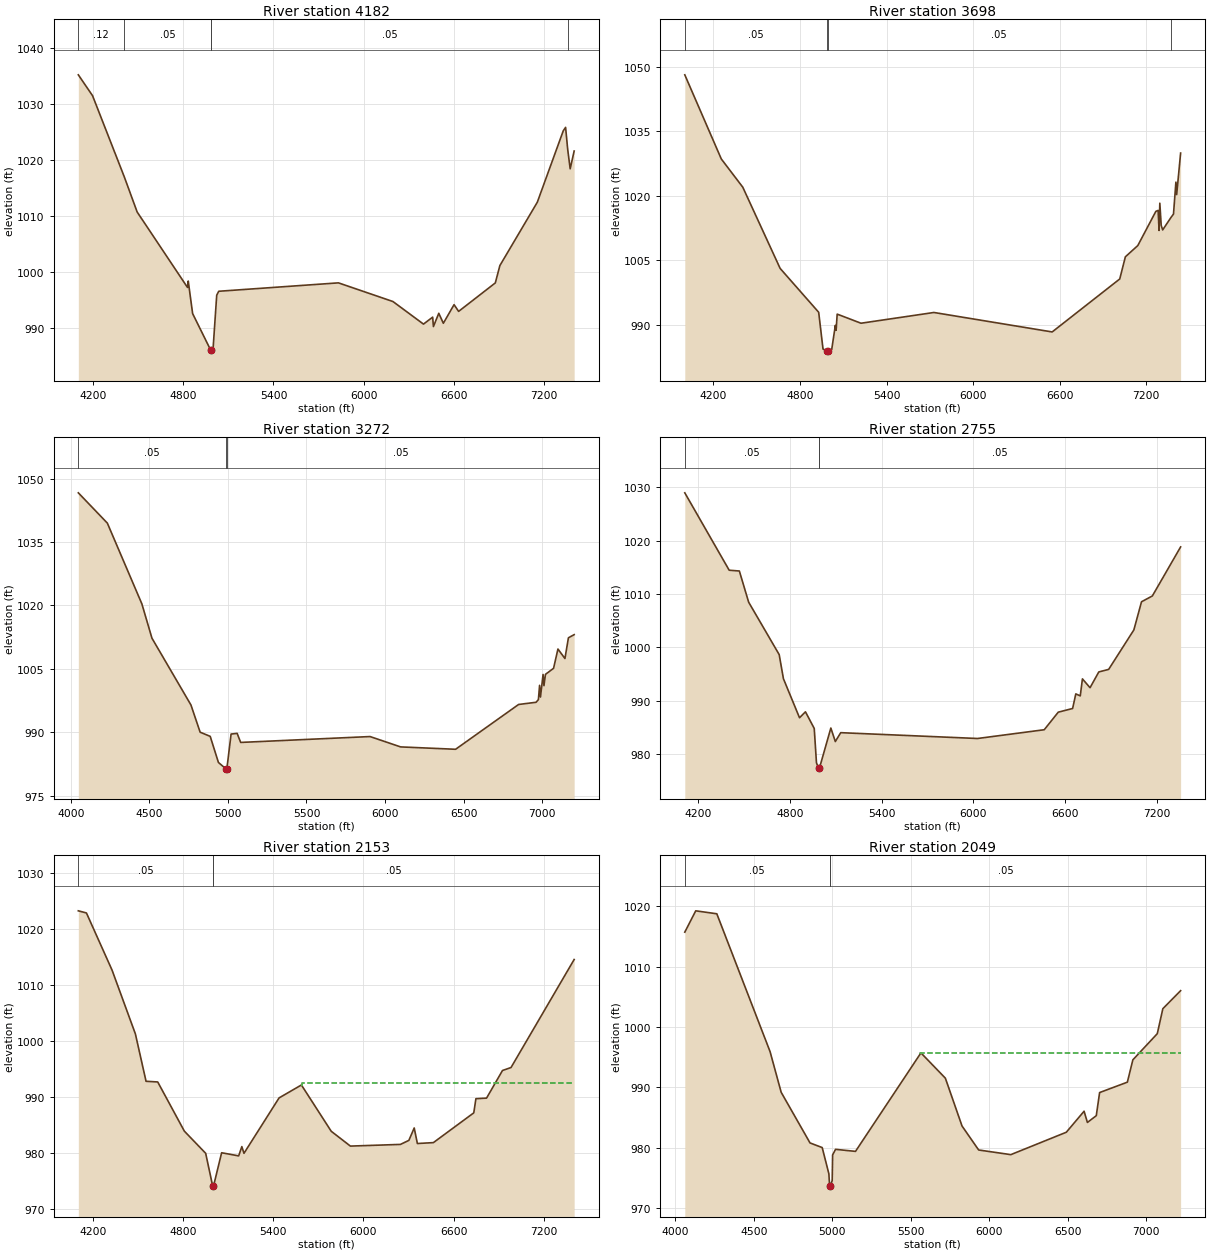
Type RM Length L Ch R = 1 ,4182    ,484,484,484
BEGIN DESCRIPTION:
Upper Denton 84 7.0
END DESCRIPTION:
XS GIS Cut Line= 3
      2227317.59      7257137.56        2227129.        7258010.
      2227546.58      7260376.04
#Sta/Elev= 30
  4103.2 1035.16  4197.8 1031.43  4408.1 1016.99  4494.1 1010.68  4828.6  997.22
  4833.7  998.35  4862.8  992.55  4983.4  985.99  4983.8  985.49  4987.8  985.99
  4998.3  986.12  5022.9  995.83  5036.4  996.53  5831.8  998.03    6194   994.7
  6397.1  990.67    6458  991.91  6463.1  990.23  6498.7   992.6  6529.1  990.82
  6600.2  994.14  6630.6  992.94  6874.4  998.02  6904.8 1001.12  7153.5 1012.42
  7326.1 1025.17  7341.5 1025.78  7355.4 1021.87    7372 1018.39  7398.4 1021.56
#Mann= 5 ,-1 , 0
  4103.2     .12       0  4408.1     .05       0  4983.4     .04       0
  4987.8     .05       0  7355.4     .12       0
Bank Sta=4983.4,4987.8
XS Rating Curve= 0 ,0
Exp/Cntr=0.3,0.1

Type RM Length L Ch R = 1 ,3698    ,426,426,426
BEGIN DESCRIPTION:
Upper Denton 84 6.0
END DESCRIPTION:
XS GIS Cut Line= 3
      2226317.61        7257174.        2226679.        7258110.
      2227514.96      7260396.43
#Sta/Elev= 30
  4001.2 1048.19  4254.2 1028.61  4403.3 1022.03  4662.2 1003.13  4929.5  992.92
  4959.6  984.36  4987.3  983.91  4987.8  983.41  4991.8  983.91  5019.8  984.24
    5045  989.87  5050.3  988.73  5057.8  992.49  5222.9  990.37  5728.6  992.87
  6548.4  988.34  7016.9 1000.67  7055.9 1005.83  7142.2 1008.45  7267.1  1016.4
  7283.1 1016.63  7289.5 1011.96  7294.8 1018.31  7304.4 1013.12  7314.7 1012.09
  7370.9 1014.93  7389.6 1015.78  7406.3 1023.22  7411.6 1020.31    7439 1029.98
#Mann= 4 ,-1 , 0
  4001.2     .05       0  4987.3    .033       0  4991.8     .05       0
  7370.9     .12       0
Bank Sta=4987.3,4991.8
XS Rating Curve= 0 ,0
Exp/Cntr=0.3,0.1

Type RM Length L Ch R = 1 ,3272    ,517,517,517
BEGIN DESCRIPTION:
Upper Denton 84 5.0
END DESCRIPTION:
XS GIS Cut Line= 3
      2225833.23      7257491.69      2226322.81      7258304.18
      2227322.83      7260272.97
#Sta/Elev= 30
  4047.7 1046.66  4232.5 1039.49  4452.3 1020.38  4516.4 1012.27  4764.9  996.45
  4823.2  990.02  4887.3  989.04  4939.7  982.86  4988.6  981.31  4989.1  980.81
  4993.2  981.31  5020.3  989.58  5058.9  989.74  5081.3   987.6    5905  988.99
  6099.7  986.54  6449.7  985.98  6850.8  996.58  6962.1   997.1  6976.9  997.74
  6984.4 1001.11    6990  998.34  7006.6 1003.68  7012.2 1001.03  7021.7  1003.7
  7073.4 1005.14  7101.3  1009.7  7145.8 1007.45    7168 1012.36  7204.5  1013.1
#Mann= 3 ,-1 , 0
  4047.7     .05       0  4988.6     .04       0  4993.2     .05       0
Bank Sta=4988.6,4993.2
XS Rating Curve= 0 ,0
Exp/Cntr=0.3,0.1

Type RM Length L Ch R = 1 ,2755    ,602,602,602
BEGIN DESCRIPTION:
Upper Denton 84 4.0
END DESCRIPTION:
XS GIS Cut Line= 3
      2225520.71       7257767.7        2225929.        7258560.
      2227333.22       7260444.8
#Sta/Elev= 30
  4113.3 1028.96  4403.5 1014.47    4470 1014.32  4530.9 1008.48  4730.4  998.67
  4758.2  994.15  4863.4  986.84  4902.1  987.96  4959.6  984.84  4974.2   978.4
  4988.4  977.35  4988.9  976.85    4993  977.35  5068.2  984.92  5097.4  982.39
  5132.8  984.05  6027.2  982.96  6463.3   984.6    6555  987.89  6648.9  988.58
  6669.7  991.31  6698.9  990.94    6713  994.12  6762.9  992.47  6819.9  995.42
  6884.5   995.9  7049.3 1003.29  7099.3 1008.56  7170.2 1009.65    7355 1018.83
#Mann= 3 ,-1 , 0
  4113.3     .05       0  4988.4    .033       0    4993     .05       0
Bank Sta=4988.4,4993
XS Rating Curve= 0 ,0
Exp/Cntr=0.3,0.1

Type RM Length L Ch R = 1 ,2153    ,104,104,104
BEGIN DESCRIPTION:
Upper Denton 84 3.0
END DESCRIPTION:
XS GIS Cut Line= 3
      2224838.44      7258184.39      2225453.01      7258851.05
      2227186.37      7260495.92
#Sta/Elev= 30
  4104.3 1023.32  4158.2 1022.94  4328.3 1012.74  4483.7 1001.32  4554.5  992.86
  4632.2  992.74  4809.2  983.95  4950.9  979.99  4997.9  974.09  4998.4  973.59
  5002.6  974.09    5057  980.09  5170.3  979.53  5191.3  981.19  5205.5  979.99
  5438.9  989.89  5587.4   992.2  5785.6  983.93    5913  981.28  6245.5  981.58
  6301.7   982.3  6337.3  984.52  6358.3  981.74  6464.7   981.9  6733.3  987.22
  6747.5  989.75  6818.2  989.85  6924.2  994.79  6980.9  995.32  7400.6 1014.62
#Mann= 3 ,-1 , 0
  4104.3     .05       0  4997.9    .033       0  5002.6     .05       0
#XS Ineff= 2 , 0
                         5592.55          992.62
Permanent Ineff=
       F       F
Bank Sta=4997.9,5002.6
XS Rating Curve= 0 ,0
Exp/Cntr=0.3,0.1

Type RM Length L Ch R = 1 ,2049    ,1153,1153,1153
BEGIN DESCRIPTION:
Upper Denton 84 2.0
END DESCRIPTION:
XS GIS Cut Line= 3
      2224708.25      7258252.12      2225374.89      7258918.76
      2226968.67      7260460.46
#Sta/Elev= 30
  4060.5  1015.7  4130.2 1019.23  4264.6 1018.74    4604  995.92  4674.7  989.19
  4858.6   980.8  4936.3  980.03  4978.8  975.69  4983.5  973.65    4984  973.15
  4988.2  973.65    5000  974.59  5002.6  978.81  5021.3  979.74  5148.4   979.4
  5565.6  995.71  5721.3  991.52  5827.5   983.6  5933.5  979.63  6138.5  978.86
  6492.2  982.57  6605.4  986.05  6626.5  984.19  6683.1  985.31  6704.4  989.14
  6881.2  990.86  6916.4  994.56    7072  998.89  7107.5 1003.03  7220.7 1006.01
#Mann= 3 ,-1 , 0
  4060.5     .05       0  4983.5    .033       0  4988.2     .05       0
#XS Ineff= 2 , 0
                         5559.98          995.65
Permanent Ineff=
       F       F
Bank Sta=4983.5,4988.2
XS Rating Curve= 0 ,0
Exp/Cntr=0.3,0.1

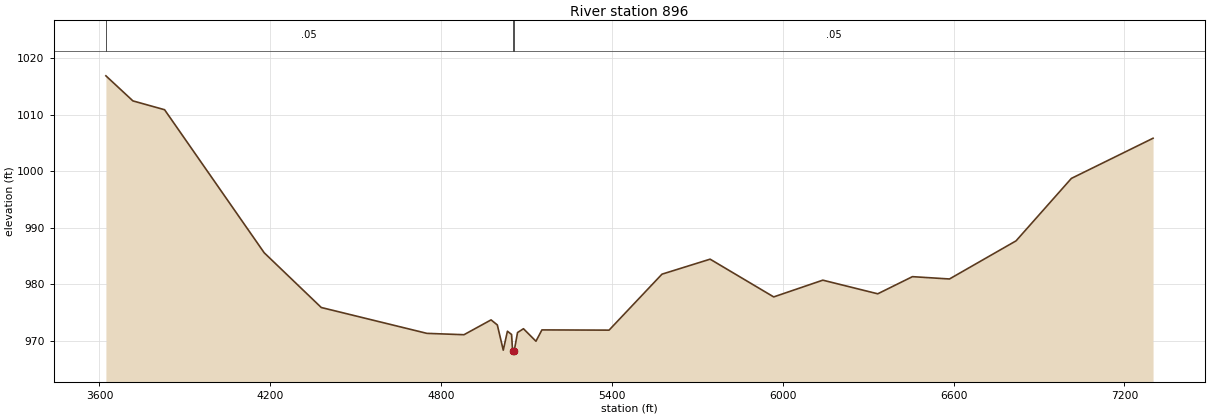
Type RM Length L Ch R = 1 ,896     ,0,0,0
BEGIN DESCRIPTION:
Upper Denton 84 1.0
END DESCRIPTION:
XS GIS Cut Line= 4
      2224817.59      7258455.27      2224729.06      7259767.72
      2225328.01      7260210.43      2226921.74      7260486.47
#Sta/Elev= 30
  3622.6 1016.85  3717.5 1012.42  3828.7 1010.86  4178.6  985.58    4379  975.91
  4749.9  971.34  4880.2   971.1  4975.3  973.72  4997.3  972.83  5018.2  968.37
  5032.8  971.72  5047.4  971.14    5051  968.17  5051.8  967.67  5056.3  968.17
  5068.3  971.48  5089.1  972.16    5133  969.95  5153.9  971.95  5389.8  971.91
  5575.6   981.8  5744.7  984.45    5968  977.78  6140.5  980.74  6333.4  978.33
  6455.2  981.36  6585.3  980.95  6819.2  987.69  7013.4  998.72  7300.3 1005.82
#Mann= 3 ,-1 , 0
  3622.6     .05       0    5051     .04       0  5056.3     .05       0
Bank Sta=5051,5056.3
XS Rating Curve= 0 ,0
Exp/Cntr=0.3,0.1

Chan Stop Cuts=-1
Use User Specified Reach Order=0
Composite Channel Slope=5