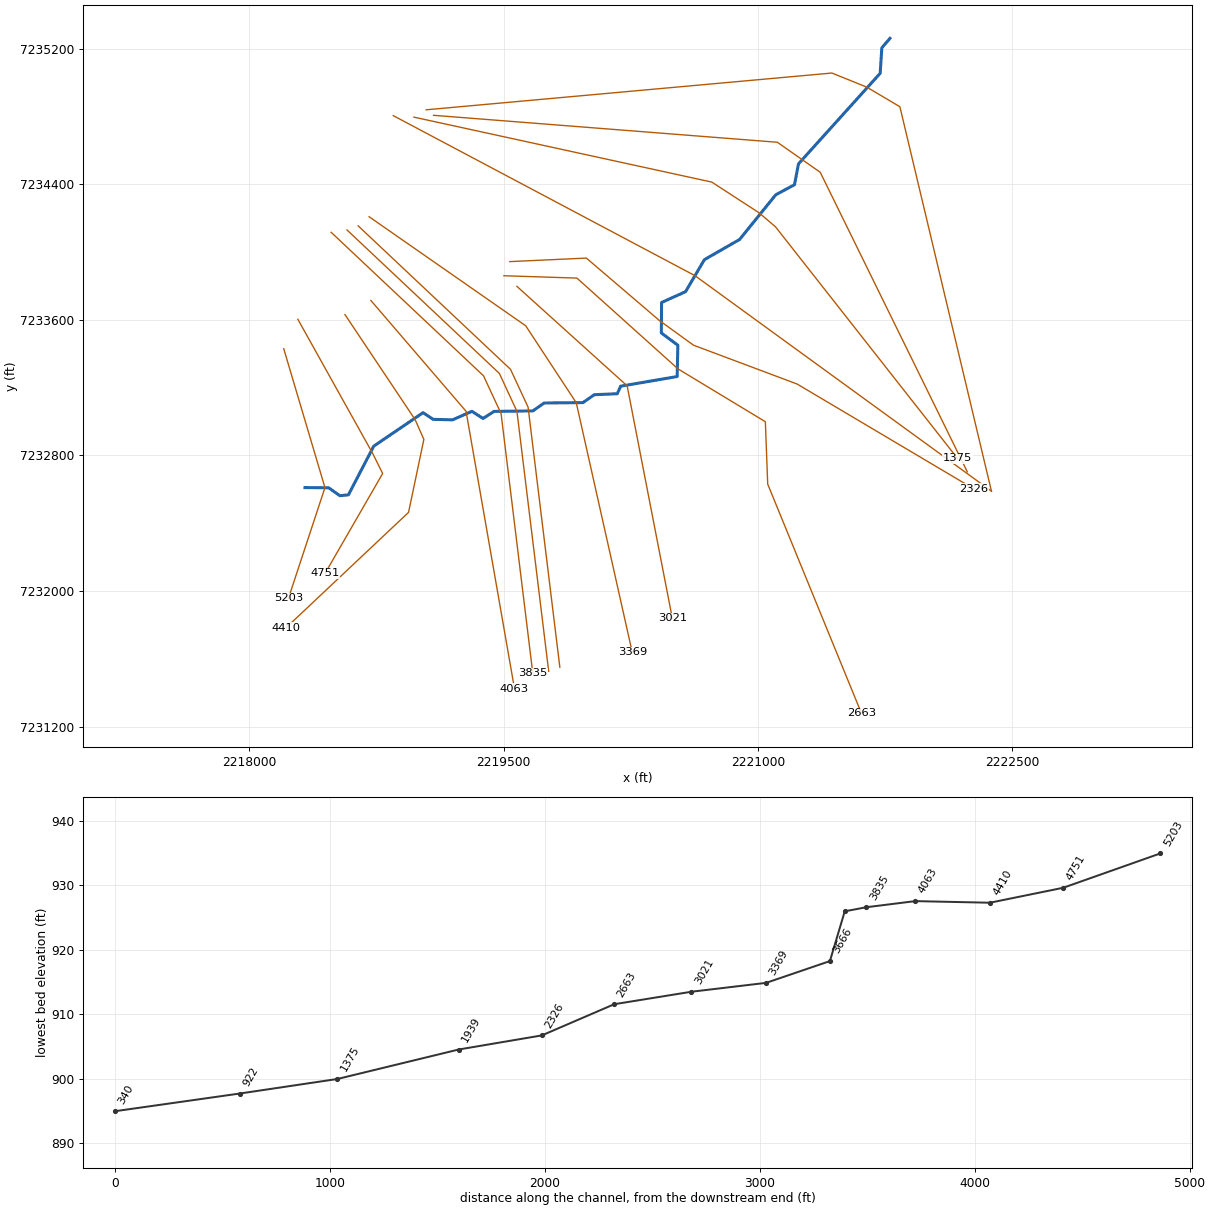
--- Upper Denton 89.prj (project) ---

Proj Title=Upper Denton 89 Base Level Engineering
Current Plan=p01
Default Exp/Contr=0.3,0.1
English Units
Geom File=g01
Flow File=f01
Plan File=p01
Y Axis Title=Elevation
X Axis Title(PF)=Main Channel Distance
X Axis Title(XS)=Station
BEGIN DESCRIPTION:
Upper Denton 89
END DESCRIPTION:
DSS Export Rating Curves= 0
DSS Export Rating Curve Sorted= 0
DSS Export Volume Flow Curves= 0
DXF OffsetX= 0
DXF OffsetY= 0
DXF ScaleX= 1
DXF ScaleY= 10

--- Upper Denton 89.p01 (plan) ---

Plan Title=Multiple Run
Short Identifier=Multiple
Geom File=g01
Flow File=f01
Subcritical Flow
K Sum by GR= 0
Std Step Tol= 0.01
Critical Tol= 0.01
Num of Std Step Trials= 20
Max Error Tol= 0.3
Flow Tol Ratio= 0.001
Split Flow NTrial= 30
Split Flow Tol= 0.02
Split Flow Ratio= 0.02
Log Output Level= 0
Friction Slope Method= 1
Unsteady Friction Slope Method= 2
Unsteady Bridges Friction Slope Method= 1
Parabolic Critical Depth
Global Vel Dist=  1 , 1 , 1
Global Log Level= 0
CheckData=True
Encroach Param= -1, 0, 0, 0
BEGIN DESCRIPTION:
Multiple Run
END DESCRIPTION:

--- Upper Denton 89.f01 (steady flow) ---

Flow Title=Multiple
Number of Profiles=7
Profile Names=10-year,25-year,50-year,1pct_min,100-year,1pct_plu,500-year
River Rch & RM= Upper Denton 89,Reach-1,5203
     423     575     700     424     846    1688    1238
River Rch & RM= Upper Denton 89,Reach-1,2663
     662     921    1138     699    1394    2781    2096
Boundary for River Rch & Prof#=Upper Denton 89,Reach-1,1
Up Type=0
Dn Type=3
Dn Slope=0.005
Boundary for River Rch & Prof#=Upper Denton 89,Reach-1,2
Up Type=0
Dn Type=3
Dn Slope=0.005
Boundary for River Rch & Prof#=Upper Denton 89,Reach-1,3
Up Type=0
Dn Type=3
Dn Slope=0.005
Boundary for River Rch & Prof#=Upper Denton 89,Reach-1,4
Up Type=0
Dn Type=3
Dn Slope=0.005
Boundary for River Rch & Prof#=Upper Denton 89,Reach-1,5
Up Type=0
Dn Type=3
Dn Slope=0.005
Boundary for River Rch & Prof#=Upper Denton 89,Reach-1,6
Up Type=0
Dn Type=3
Dn Slope=0.005
Boundary for River Rch & Prof#=Upper Denton 89,Reach-1,7
Up Type=0
Dn Type=3
Dn Slope=0.005

--- Upper Denton 89.g01 (geometry) ---

Geom Title=Existing Conditions

River Reach=Upper Denton 89,Reach-1
Reach XY= 30
      2218329.00      7232610.00      2218468.53      7232608.81
      2218535.17      7232561.76      2218585.34      7232567.36
      2218734.59      7232854.39      2219025.68      7233051.96
      2219084.86      7233012.45      2219199.14      7233009.62
      2219313.66      7233059.77      2219378.99      7233017.59
      2219444.16      7233059.34      2219673.06      7233062.26
      2219739.50      7233108.78      2219968.50      7233111.22
      2220034.95      7233157.72      2220170.53      7233163.47
      2220190.97      7233208.02      2220524.00      7233265.01
      2220528.00      7233449.71      2220430.64      7233521.84
      2220432.06      7233701.72      2220573.39      7233765.59
      2220684.62      7233954.38      2220892.24      7234073.62
      2221105.22      7234337.02      2221215.74      7234396.35
      2221239.52      7234519.78      2221721.19      7235053.81
      2221730.91      7235204.21      2221779.00      7235260.00

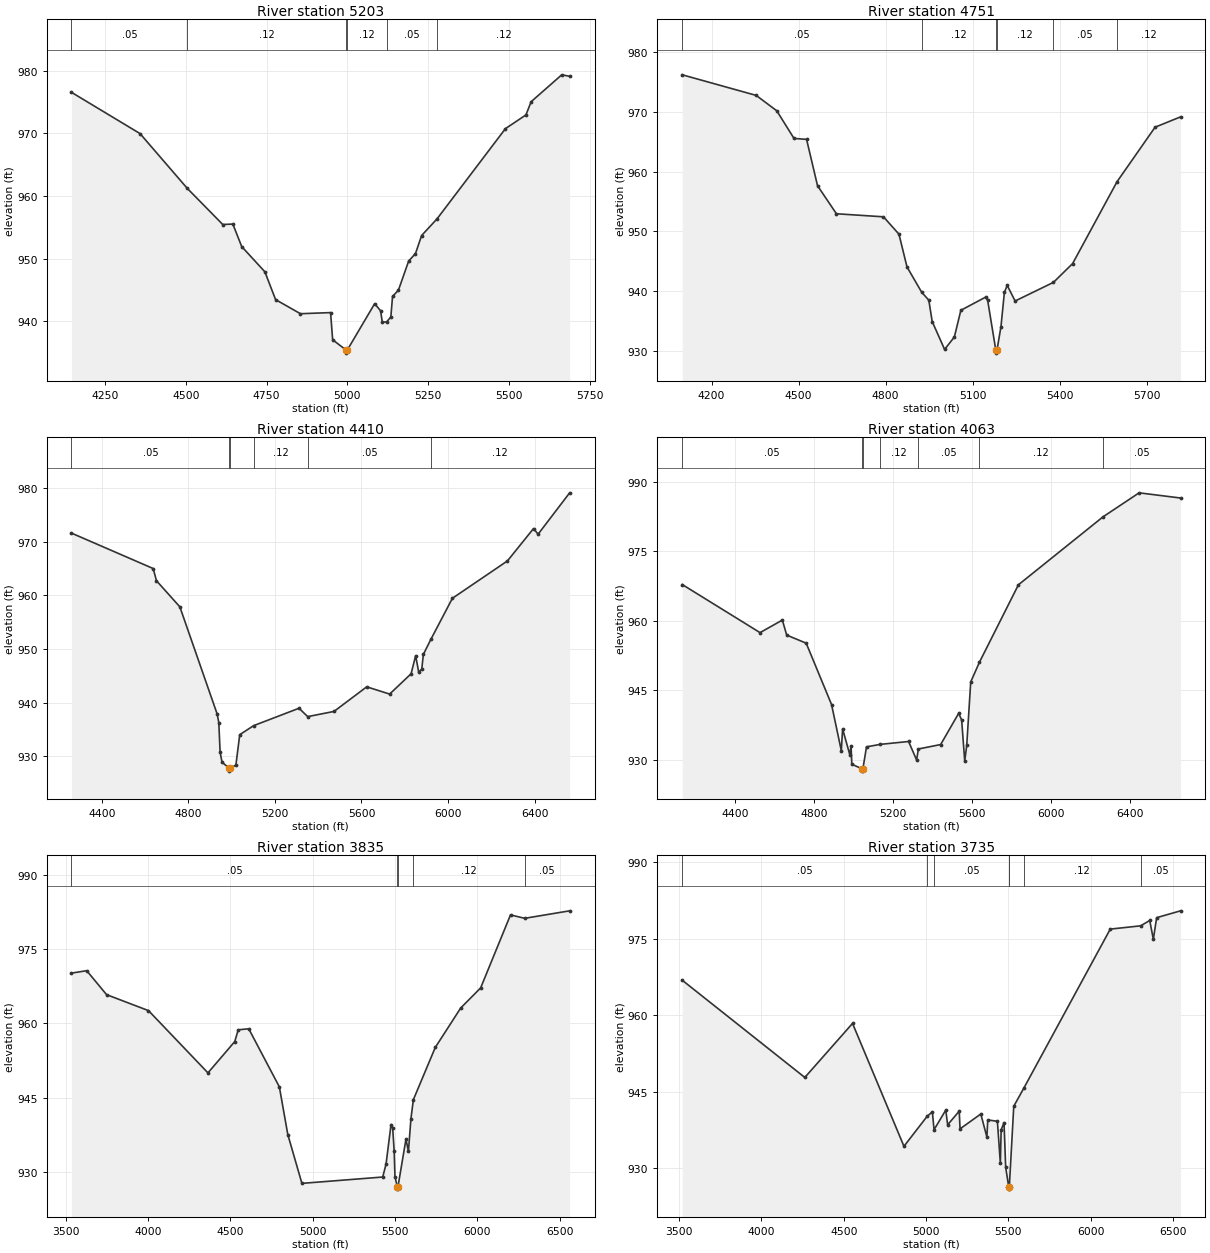
Type RM Length L Ch R = 1,5203,452,452,452
BEGIN DESCRIPTION:
Upper Denton 89 9.0
END DESCRIPTION:
XS GIS Cut Line= 3
      2218203.76      7233429.00      2218446.81      7232609.57
      2218231.53      7231956.77
#Sta/Elev= 30
  4146.2  976.55  4358.5  969.96  4504.7  961.22  4614.5  955.45  4645.8  955.52
  4673.2  951.93  4744.9  947.90  4778.1  943.46  4855.0  941.21  4948.3  941.39
  4954.7  937.05  4996.1  935.42  4996.3  934.92  5000.1  935.42  5084.7  942.81
  5103.1  941.68  5108.4  939.86  5121.8  939.90  5134.8  940.69  5140.1  943.96
  5158.4  944.98  5190.0  949.62  5211.1  950.81  5230.1  953.69  5278.1  956.37
  5489.5  970.75  5553.0  972.94  5569.1  975.05  5663.8  979.34  5688.3  979.11
#Mann=6,-1,0
  4146.2    0.05       0  4504.7    0.12       0  4996.1    0.07       0
  5000.1    0.12       0  5121.8    0.05       0  5278.1    0.12       0
Bank Sta=4996.1,5000.1
Exp/Cntr=0.3,0.1

Type RM Length L Ch R = 1,4751,341,341,341
BEGIN DESCRIPTION:
Upper Denton 89 8.0
END DESCRIPTION:
XS GIS Cut Line= 4
      2218287.10      7233602.62      2218729.00      7232810.00
      2218787.09      7232692.90      2218447.48      7232103.78
#Sta/Elev= 30
  4099.0  976.24  4353.9  972.79  4424.8  970.21  4484.2  965.58  4527.6  965.42
  4565.3  957.66  4630.5  952.95  4792.8  952.44  4846.2  949.53  4873.9  944.04
  4924.4  939.81  4949.2  938.46  4960.8  934.89  5003.6  930.21  5037.3  932.30
  5059.7  936.77  5144.8  938.97  5152.1  938.45  5180.2  930.09  5180.4  929.59
  5184.2  930.09  5198.0  934.02  5209.8  939.76  5219.5  940.95  5246.8  938.33
  5379.0  941.45  5445.1  944.60  5598.4  958.33  5729.5  967.46  5817.2  969.19
#Mann=6,-1,0
  4099.0    0.05       0  4924.4    0.12       0  5180.2    0.07       0
  5184.2    0.12       0  5379.0    0.05       0  5598.4    0.12       0
Bank Sta=5180.2,5184.2
Exp/Cntr=0.3,0.1

Type RM Length L Ch R = 1,4410,347,347,347
BEGIN DESCRIPTION:
Upper Denton 89 7.0
END DESCRIPTION:
XS GIS Cut Line= 5
      2218564.88      7233630.39      2218979.00      7233010.00
      2219030.15      7232894.29      2218939.87      7232463.74
      2218218.58      7231784.06
#Sta/Elev= 30
  4259.0  971.60  4636.9  965.00  4652.0  962.73  4760.1  957.87  4932.8  937.89
  4940.3  936.30  4946.3  930.77  4955.3  928.93  4989.4  927.77  4989.6  927.27
  4993.4  927.77  5019.3  928.41  5037.1  934.06  5101.4  935.74  5311.1  938.98
  5351.3  937.42  5473.0  938.39  5624.2  942.97  5730.2  941.62  5829.3  945.40
  5850.4  948.78  5864.5  945.70  5878.7  946.26  5886.0  949.01  5921.8  951.89
  6020.3  959.46  6274.8  966.42  6395.4  972.45  6416.4  971.39  6562.4  979.10
#Mann=6,-1,0
  4259.0    0.05       0  4989.4   0.033       0  4993.4    0.05       0
  5101.4    0.12       0  5351.3    0.05       0  5921.8    0.12       0
Bank Sta=4989.4,4993.4
Exp/Cntr=0.3,0.1

Type RM Length L Ch R = 1,4063,228,228,228
BEGIN DESCRIPTION:
Upper Denton 89 6.0
END DESCRIPTION:
XS GIS Cut Line= 3
      2218717.63      7233713.75      2219279.00      7233060.00
      2219564.61      7231423.53
#Sta/Elev= 30
  4134.3  967.81  4527.9  957.43  4641.0  960.14  4662.9  956.90  4761.7  955.15
  4890.1  941.90  4939.5  931.94  4946.1  936.63  4982.3  931.10  4988.9  932.95
  4992.7  929.01  5044.8  928.02  5045.0  927.52  5048.8  928.02  5067.1  932.76
  5136.9  933.30  5280.2  933.92  5320.9  929.92  5329.6  932.30  5442.6  933.26
  5534.0  940.02  5548.9  938.56  5564.5  929.69  5574.6  933.06  5594.9  946.78
  5638.9  951.03  5836.4  967.76  6264.7  982.43  6447.6  987.62  6657.2  986.50
#Mann=7,-1,0
  4134.3    0.05       0  5044.8   0.033       0  5048.8    0.05       0
  5136.9    0.12       0  5329.6    0.05       0  5638.9    0.12       0
  6264.7    0.05       0
Bank Sta=5044.8,5048.8
Exp/Cntr=0.3,0.1

Type RM Length L Ch R = 1,3835,100,100,100
BEGIN DESCRIPTION:
Upper Denton 89 5.5
END DESCRIPTION:
XS GIS Cut Line= 4
      2218483.53      7234115.69      2219381.98      7233269.33
      2219485.52      7233046.15      2219672.62      7231513.67
#Sta/Elev= 30
  3535.3  970.12  3628.0  970.61  3748.5  965.78  4003.0  962.56  4363.9  950.01
  4526.6  956.32  4547.6  958.69  4611.5  958.90  4797.3  947.19  4848.6  937.58
  4934.2  927.73  5424.8  929.01  5445.0  931.62  5475.2  939.59  5485.3  938.86
  5494.2  934.30  5499.3  929.04  5513.5  927.07  5513.7  926.57  5517.5  927.07
  5565.9  936.65  5580.8  934.18  5596.1  940.79  5611.0  944.62  5743.9  955.14
  5898.3  963.09  6019.2  967.14  6200.5  981.86  6286.9  981.17  6559.5  982.68
#Mann=5,-1,0
  3535.3    0.05       0  5513.5   0.033       0  5517.5    0.05       0
  5611.0    0.12       0  6286.9    0.05       0
Bank Sta=5513.5,5517.5
Exp/Cntr=0.3,0.1

Type RM Length L Ch R = 1,3735,69,69,69
BEGIN DESCRIPTION:
Upper Denton 89 5.0
END DESCRIPTION:
XS GIS Cut Line= 4
      2218577.03      7234129.53      2219475.46      7233283.18
      2219579.00      7233060.00      2219766.26      7231526.22
#Sta/Elev= 30
  3519.6  966.86  4263.6  947.82  4553.3  958.41  4865.7  934.33  5007.5  940.25
  5038.2  941.07  5048.4  937.58  5119.7  941.43  5130.9  938.54  5201.3  941.22
  5206.3  937.75  5332.4  940.66  5369.4  936.13  5374.5  939.50  5433.1  939.23
  5451.0  931.03  5456.0  937.58  5473.4  938.97  5483.5  930.19  5501.6  926.44
  5501.9  925.94  5505.6  926.44  5532.5  942.18  5593.3  945.71  6118.5  976.89
  6303.0  977.53  6358.2  978.58  6380.1  974.90  6400.2  979.13  6545.1  980.47
#Mann=7,-1,0
  3519.6    0.05       0  5007.5    0.12       0  5048.4    0.05       0
  5501.6   0.033       0  5505.6    0.05       0  5593.3    0.12       0
  6303.0    0.05       0
Bank Sta=5501.6,5505.6
Exp/Cntr=0.3,0.1

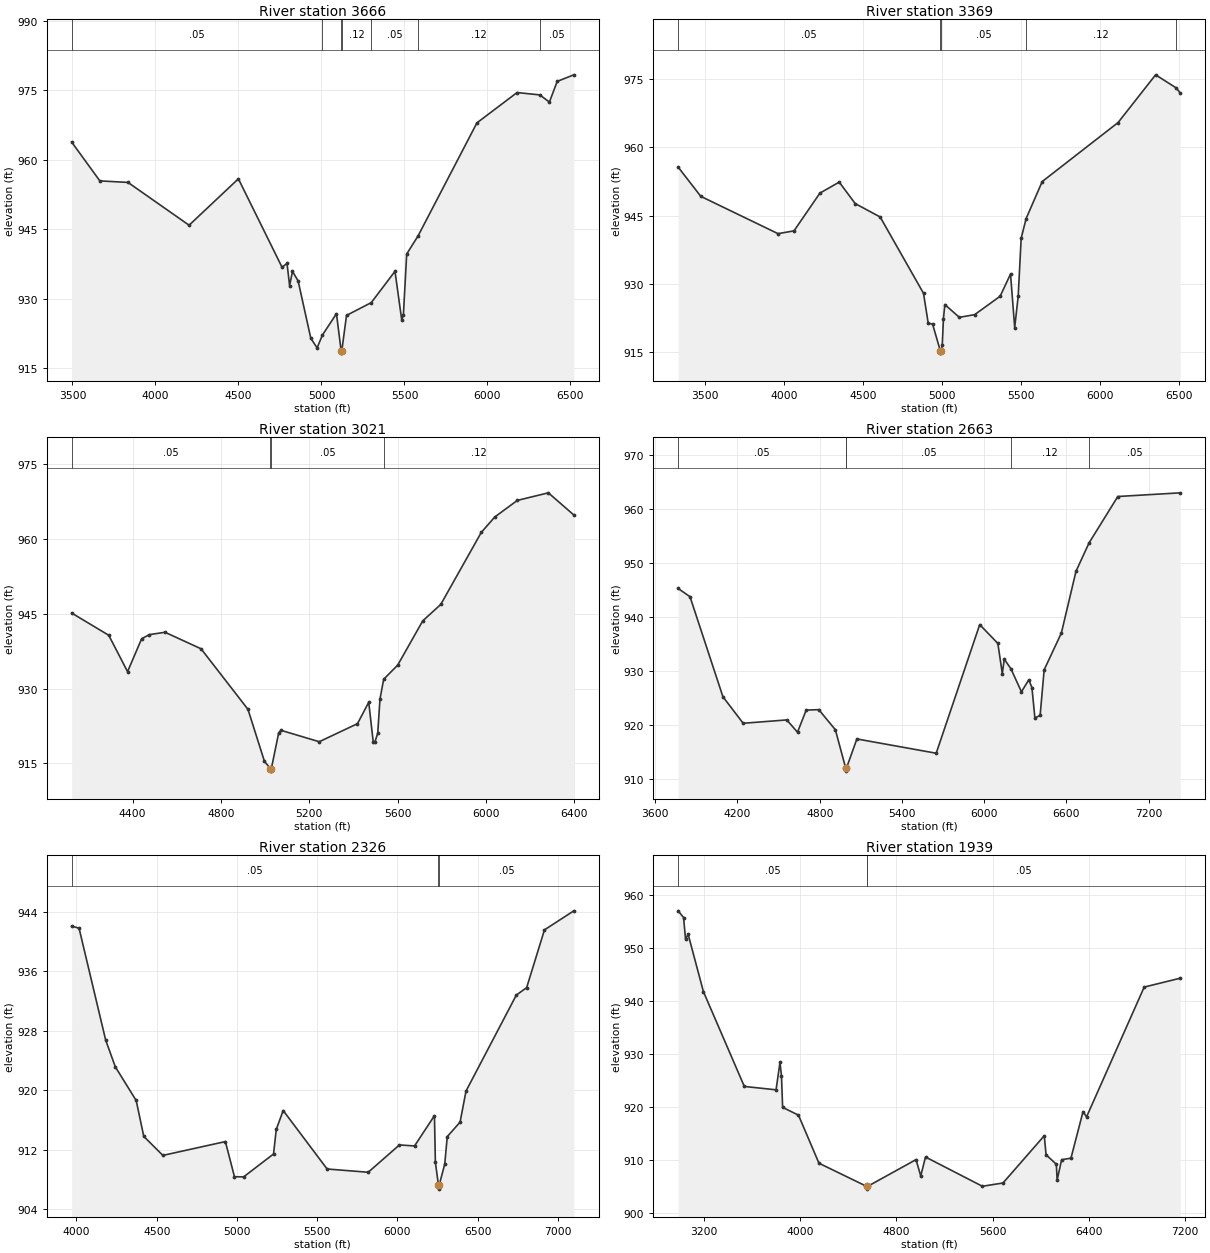
Type RM Length L Ch R = 1,3666,297,297,297
BEGIN DESCRIPTION:
Upper Denton 89 4.5
END DESCRIPTION:
XS GIS Cut Line= 4
      2218642.80      7234153.77      2219541.24      7233307.42
      2219644.78      7233084.24      2219832.04      7231550.46
#Sta/Elev= 30
  3494.9  963.84  3664.8  955.44  3834.3  955.11  4202.5  945.86  4499.4  955.89
  4762.2  936.80  4792.5  937.59  4808.0  932.80  4825.4  935.89  4859.4  933.81
  4935.8  921.41  4973.9  919.36  5005.5  922.12  5090.3  926.74  5118.5  918.72
  5118.8  918.22  5122.5  918.72  5150.8  926.37  5300.1  929.14  5442.9  935.90
  5483.2  925.47  5493.3  926.36  5513.4  939.64  5581.6  943.53  5936.6  967.98
  6178.3  974.53  6315.6  974.02  6373.2  972.47  6420.1  976.94  6520.4  978.36
#Mann=7,-1,0
  3494.9    0.05       0  5005.5    0.12       0  5118.5   0.033       0
  5122.5    0.12       0  5300.1    0.05       0  5581.6    0.12       0
  6315.6    0.05       0
Bank Sta=5118.5,5122.5
Exp/Cntr=0.3,0.1

Type RM Length L Ch R = 1,3369,348,348,348
BEGIN DESCRIPTION:
Upper Denton 89 4.0
END DESCRIPTION:
XS GIS Cut Line= 4
      2218707.23      7234207.66      2219630.70      7233564.50
      2219929.00      7233110.00      2220259.32      7231637.30
#Sta/Elev= 30
  3330.6  955.69  3474.1  949.26  3962.8  941.07  4063.9  941.68  4228.0  949.97
  4350.2  952.39  4451.4  947.67  4609.3  944.73  4883.6  927.98  4913.7  921.36
  4940.8  921.25  4990.1  915.34  4990.3  914.84  4994.1  915.34  5002.2  916.54
  5009.9  922.43  5018.7  925.50  5110.5  922.70  5207.5  923.29  5368.6  927.33
  5434.4  932.21  5460.8  920.44  5482.9  927.34  5501.8  940.07  5533.0  944.37
  5635.0  952.51  6115.3  965.47  6352.5  975.94  6481.9  973.09  6508.9  971.94
#Mann=5,-1,0
  3330.6    0.05       0  4990.1   0.033       0  4994.1    0.05       0
  5533.0    0.12       0  6481.9    0.05       0
Bank Sta=4990.1,4994.1
Exp/Cntr=0.3,0.1

Type RM Length L Ch R = 1,3021,358,358,358
BEGIN DESCRIPTION:
Upper Denton 89 3.0
END DESCRIPTION:
XS GIS Cut Line= 3
      2219578.79      7233797.04      2220229.00      7233210.00
      2220495.42      7231838.75
#Sta/Elev= 30
  4124.6  945.14  4292.5  940.68  4377.7  933.39  4441.3  939.98  4476.4  940.81
  4547.4  941.28  4710.3  937.97  4922.5  925.85  4997.2  915.42  5024.4  913.96
  5024.7  913.46  5028.4  913.96  5061.7  921.13  5071.9  921.64  5245.1  919.35
  5418.3  922.97  5469.2  927.25  5489.6  919.29  5496.7  919.25  5510.0  921.07
  5520.1  927.91  5536.9  931.87  5600.1  934.69  5713.7  943.57  5795.2  946.86
  5978.6  961.29  6039.7  964.38  6141.6  967.70  6282.1  969.22  6397.5  964.78
#Mann=4,-1,0
  4124.6    0.05       0  5024.4   0.033       0  5028.4    0.05       0
  5536.9    0.12       0
Bank Sta=5024.4,5028.4
Exp/Cntr=0.3,0.1

Type RM Length L Ch R = 1,2663,337,337,337
BEGIN DESCRIPTION:
Upper Denton 89 2.0
END DESCRIPTION:
XS GIS Cut Line= 6
      2219502.32      7233859.57      2219932.92      7233845.68
      2220529.00      7233310.00      2221044.03      7232998.46
      2221057.92      7232630.40      2221610.87      7231278.00
#Sta/Elev= 30
  3766.9  945.31  3853.6  943.79  4093.7  925.29  4241.5  920.38  4559.6  921.00
  4637.9  918.73  4701.4  922.82  4793.2  922.90  4914.1  919.18  4990.1  912.03
  4990.4  911.53  4994.1  912.03  5071.1  917.48  5649.7  914.84  5967.2  938.63
  6099.6  935.15  6132.0  929.56  6146.2  932.24  6194.7  930.47  6271.6  926.20
  6325.1  928.41  6348.1  926.99  6369.7  921.37  6407.9  921.83  6437.3  930.27
  6562.8  937.06  6669.7  948.50  6764.9  953.74  6974.7  962.32  7430.6  963.00
#Mann=5,-1,0
  3766.9    0.05       0  4990.1   0.033       0  4994.1    0.05       0
  6194.7    0.12       0  6764.9    0.05       0
Bank Sta=4990.1,4994.1
Exp/Cntr=0.3,0.1

Type RM Length L Ch R = 1,2326,387,387,387
BEGIN DESCRIPTION:
Upper Denton 89 1.5
END DESCRIPTION:
XS GIS Cut Line= 6
      2219537.12      7233942.90      2219988.48      7233963.74
      2220419.03      7233595.68      2220620.42      7233449.85
      2221231.53      7233220.68      2222273.19      7232602.63
#Sta/Elev= 30
  3969.8  942.10  4016.0  941.81  4181.9  926.75  4242.0  923.15  4372.1  918.62
  4419.4  913.79  4538.5  911.23  4928.2  913.09  4984.8  908.36  5042.0  908.34
  5228.4  911.42  5245.5  914.73  5288.6  917.27  5562.4  909.40  5818.7  908.96
  6013.3  912.64  6107.4  912.50  6231.6  916.58  6237.4  910.31  6256.8  907.19
  6257.1  906.69  6260.8  907.19  6295.8  910.07  6311.5  913.76  6391.4  915.71
  6428.4  919.89  6742.1  932.81  6806.4  933.81  6917.5  941.59  7100.6  944.15
#Mann=3,-1,0
  3969.8    0.05       0  6256.8   0.033       0  6260.8    0.05       0
Bank Sta=6256.8,6260.8
Exp/Cntr=0.3,0.1

Type RM Length L Ch R = 1,1939,564,564,564
BEGIN DESCRIPTION:
Upper Denton 89 1.0
END DESCRIPTION:
XS GIS Cut Line= 3
      2218849.61      7234804.00      2220629.00      7233860.00
      2222377.38      7232588.72
#Sta/Elev= 30
  2985.7  957.02  3031.1  955.76  3047.4  951.68  3069.4  952.57  3195.7  941.79
  3536.2  923.88  3800.1  923.24  3832.7  928.41  3845.3  925.88  3854.7  919.93
  3986.6  918.46  4156.9  909.39  4555.7  905.00  4556.0  904.50  4559.7  905.00
  4964.2  910.07  5003.1  906.99  5042.9  910.56  5515.9  905.04  5687.4  905.66
  6030.6  914.58  6045.3  910.99  6131.0  909.19  6137.5  906.19  6174.6  910.05
  6252.4  910.34  6352.8  919.12  6382.2  918.14  6861.4  942.63  7161.7  944.31
#Mann=3,-1,0
  2985.7    0.05       0  4555.7    0.04       0  4559.7    0.05       0
Bank Sta=4555.7,4559.7
Exp/Cntr=0.3,0.1

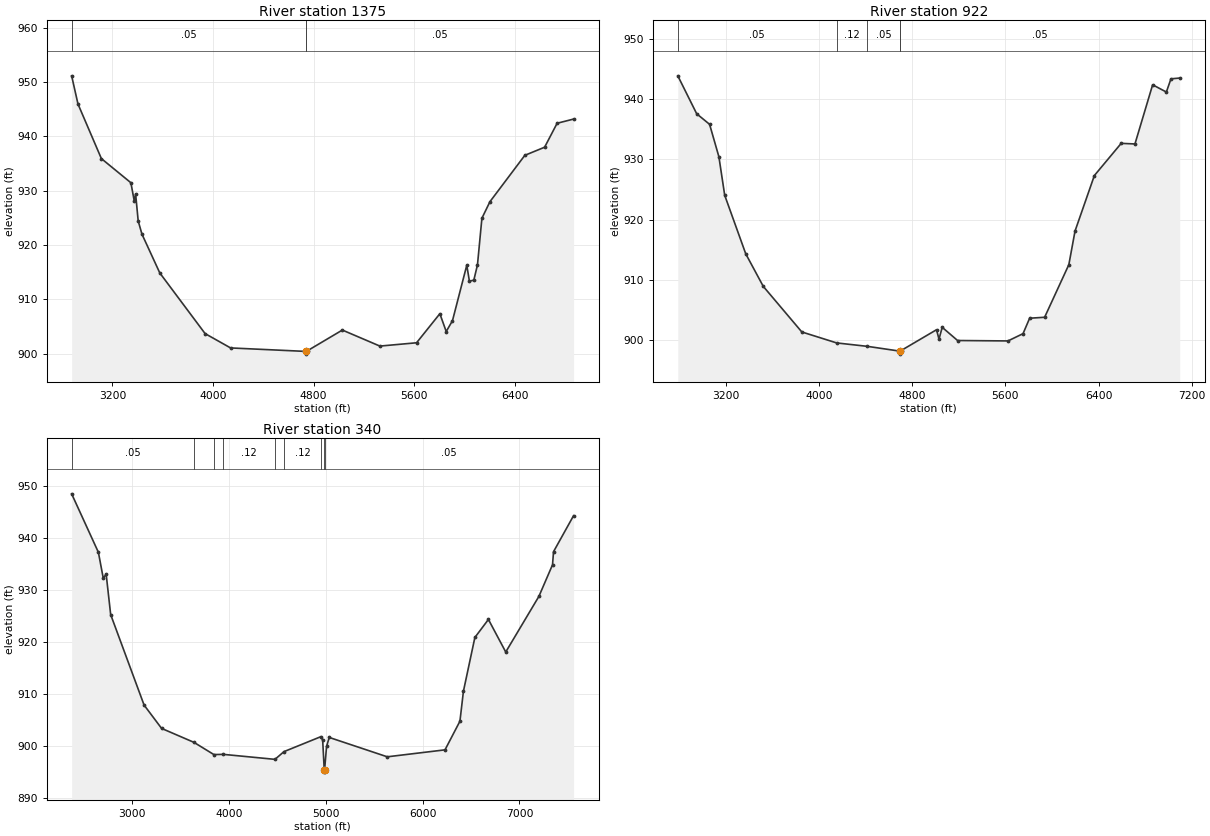
Type RM Length L Ch R = 1,1375,453,453,453
BEGIN DESCRIPTION:
Upper Denton 89 0.8
END DESCRIPTION:
XS GIS Cut Line= 5
      2218971.67      7234795.12      2220727.98      7234412.06
      2221006.25      7234231.37      2221103.82      7234148.25
      2222176.07      7232783.57
#Sta/Elev= 30
  2875.4  951.15  2925.9  945.96  3111.9  935.92  3346.9  931.47  3374.2  928.03
  3384.4  929.42  3404.9  924.44  3434.8  922.01  3576.8  914.87  3937.1  903.71
  4139.9  901.07  4738.4  900.43  4738.7  899.93  4742.4  900.43  5029.1  904.36
  5327.7  901.41  5619.6  902.02  5804.8  907.37  5855.4  904.09  5905.2  906.08
  6019.0  916.29  6039.9  913.36  6075.1  913.55  6104.0  916.35  6139.3  924.94
  6203.4  927.99  6480.9  936.52  6638.2  938.01  6737.6  942.42  6868.5  943.19
#Mann=3,-1,0
  2875.4    0.05       0  4738.4   0.033       0  4742.4    0.05       0
Bank Sta=4738.4,4742.4
Exp/Cntr=0.3,0.1

Type RM Length L Ch R = 1,922,582,582,582
BEGIN DESCRIPTION:
Upper Denton 89 0.7
END DESCRIPTION:
XS GIS Cut Line= 4
      2219087.31      7234805.97      2221114.67      7234646.96
      2221367.64      7234469.88      2222234.95      7232702.72
#Sta/Elev= 30
  2786.4  943.88  2948.6  937.58  3059.3  935.83  3139.2  930.45  3189.3  924.04
  3369.9  914.33  3520.3  908.93  3851.4  901.36  4150.8  899.54  4415.1  898.97
  4691.9  898.18  4692.2  897.68  4695.9  898.18  5008.4  901.73  5029.7  900.17
  5057.2  902.13  5189.3  899.94  5622.1  899.87  5751.5  901.08  5808.1  903.64
  5936.9  903.80  6144.9  912.53  6198.0  918.11  6364.2  927.33  6594.6  932.67
  6712.7  932.57  6864.5  942.39  6982.5  941.19  7021.9  943.38  7097.3  943.51
#Mann=5,-1,0
  2786.4    0.05       0  4150.8    0.12       0  4415.1    0.05       0
  4691.9    0.04       0  4695.9    0.05       0
Bank Sta=4691.9,4695.9
Exp/Cntr=0.3,0.1

Type RM Length L Ch R = 1,340,0,0,0
BEGIN DESCRIPTION:
Upper Denton 89 0.6
END DESCRIPTION:
XS GIS Cut Line= 5
      2219043.95      7234838.49      2221436.30      7235055.32
      2221642.29      7234972.21      2221837.44      7234856.56
      2222377.36      7232588.77
#Sta/Elev= 30
  2376.5  948.52  2652.7  937.26  2702.9  932.28  2733.0  933.05  2779.6  925.26
  3124.6  907.84  3305.3  903.35  3639.8  900.66  3845.2  898.31  3943.1  898.35
  4475.9  897.39  4569.1  898.88  4950.0  901.76  4968.4  901.11  4984.5  895.43
  4984.7  894.93  4988.5  895.43  5008.6  899.88  5036.1  901.61  5635.3  897.88
  6231.5  899.22  6385.7  904.74  6421.7  910.51  6539.9  920.86  6679.7  924.33
  6858.6  918.06  7200.9  928.77  7341.7  934.86  7352.0  937.38  7558.8  944.31
#Mann=9,-1,0
  2376.5    0.05       0  3639.8    0.12       0  3845.2    0.05       0
  3943.1    0.12       0  4475.9    0.05       0  4569.1    0.12       0
  4950.0    0.05       0  4984.5   0.033       0  4988.5    0.05       0
Bank Sta=4984.5,4988.5
Exp/Cntr=0.3,0.1

Chan Stop Cuts=-1