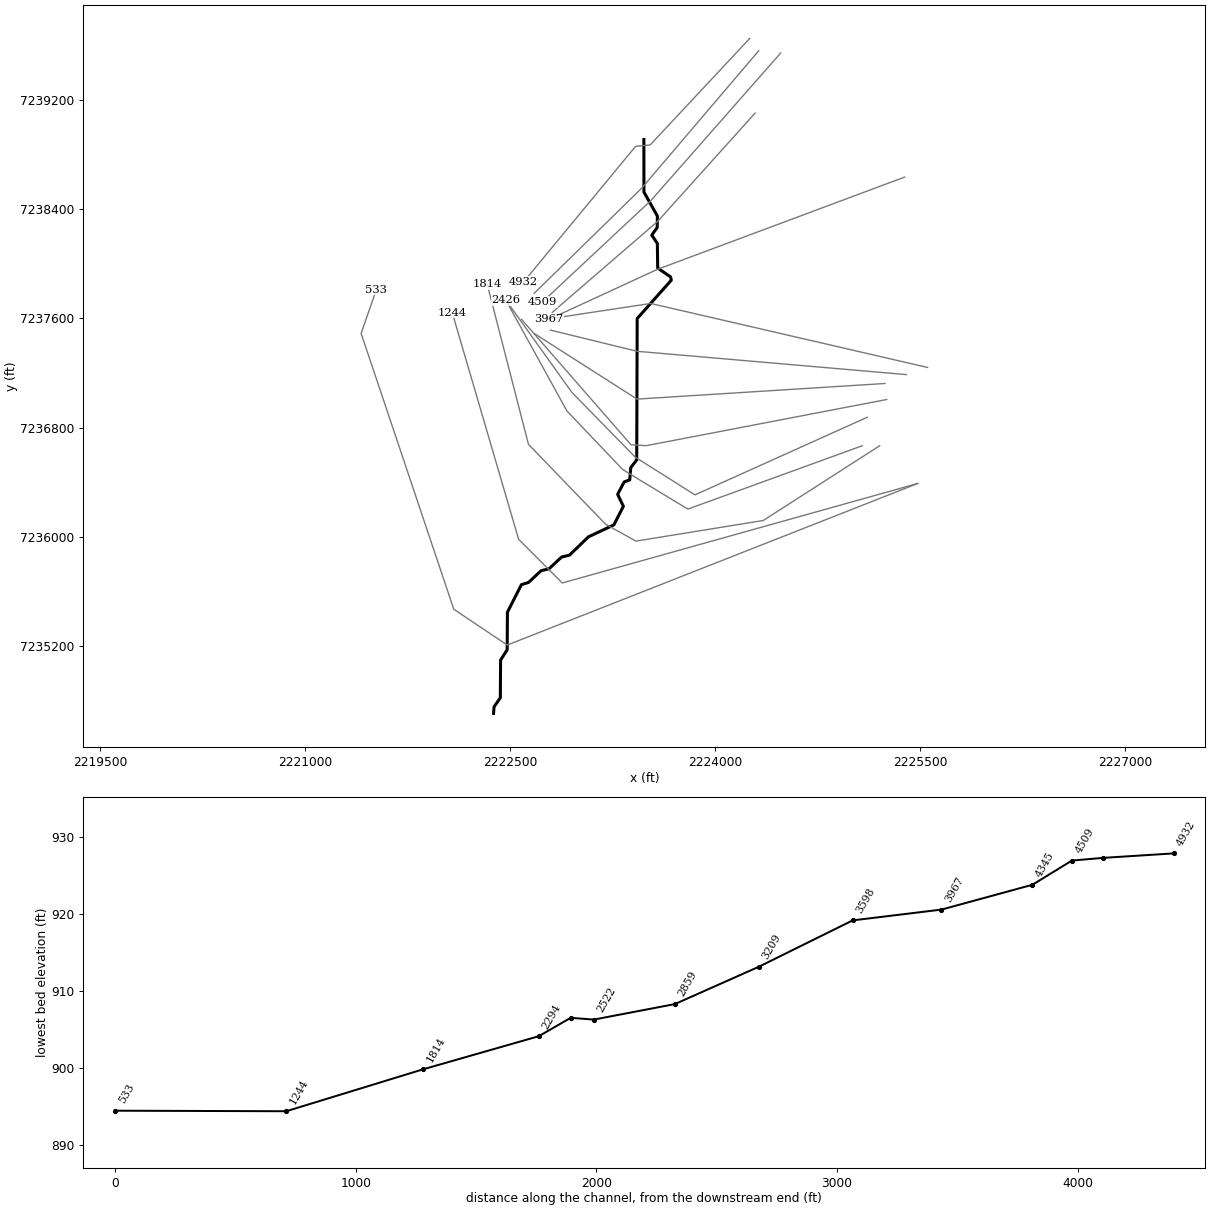
--- Upper Denton 90.prj (project) ---

Proj Title=Upper Denton 90 Base Level Engineering
Current Plan=p01
Default Exp/Contr=0.3,0.1
English Units
Geom File=g01
Flow File=f01
Plan File=p01
BEGIN DESCRIPTION:
Upper Denton 90
END DESCRIPTION:

--- Upper Denton 90.p01 (plan) ---

Plan Title=Multiple Run
Short Identifier=Multiple
Geom File=g01
Flow File=f01
Subcritical Flow
K Sum by GR= 0
Std Step Tol= 0.01
Critical Tol= 0.01
Num of Std Step Trials= 20
Max Error Tol= 0.3
Flow Tol Ratio= 0.001
Split Flow NTrial= 30
Split Flow Tol= 0.02
Split Flow Ratio= 0.02
Log Output Level= 0
Friction Slope Method= 1
Unsteady Friction Slope Method= 2
Unsteady Bridges Friction Slope Method= 1
Parabolic Critical Depth
Global Vel Dist=  1 , 1 , 1
Global Log Level= 0
CheckData=True
Encroach Param= -1, 0, 0, 0
BEGIN DESCRIPTION:
Multiple Run
END DESCRIPTION:

--- Upper Denton 90.f01 (steady flow) ---

Flow Title=Multiple
Number of Profiles=7
Profile Names=10-year,25-year,50-year,1pct_min,100-year,1pct_plu,500-year
River Rch & RM= Upper Denton 90,Reach-1,4932
     430     584     710     430     858    1712    1254
River Rch & RM= Upper Denton 90,Reach-1,3967
     912    1295    1622    1009    2013    4016    3109
River Rch & RM= Upper Denton 90,Reach-1,533
     904    1283    1606     998    1991    3973    3069
Boundary for River Rch & Prof#=Upper Denton 90,Reach-1,1
Up Type=0
Dn Type=3
Dn Slope=0.005
Boundary for River Rch & Prof#=Upper Denton 90,Reach-1,2
Up Type=0
Dn Type=3
Dn Slope=0.005
Boundary for River Rch & Prof#=Upper Denton 90,Reach-1,3
Up Type=0
Dn Type=3
Dn Slope=0.005
Boundary for River Rch & Prof#=Upper Denton 90,Reach-1,4
Up Type=0
Dn Type=3
Dn Slope=0.005
Boundary for River Rch & Prof#=Upper Denton 90,Reach-1,5
Up Type=0
Dn Type=3
Dn Slope=0.005
Boundary for River Rch & Prof#=Upper Denton 90,Reach-1,6
Up Type=0
Dn Type=3
Dn Slope=0.005
Boundary for River Rch & Prof#=Upper Denton 90,Reach-1,7
Up Type=0
Dn Type=3
Dn Slope=0.005

--- Upper Denton 90.g01 (geometry) ---

Geom Title=Existing Conditions

River Reach=Upper Denton 90,Reach-1
Reach XY= 30
      2223479.00      7238910.00      2223479.51      7238525.21
      2223577.91      7238349.45      2223576.51      7238265.49
      2223536.56      7238210.00      2223577.62      7238149.56
      2223580.16      7237969.44      2223674.23      7237904.36
      2223679.57      7237880.41      2223430.05      7237599.57
      2223426.63      7236565.53      2223382.88      7236508.33
      2223375.50      7236418.48      2223334.99      7236404.20
      2223287.06      7236313.34      2223328.86      7236225.41
      2223259.38      7236089.52      2223072.94      7236001.86
      2222935.05      7235868.16      2222876.72      7235854.13
      2222785.04      7235768.18      2222726.72      7235754.13
      2222634.74      7235668.30      2222582.67      7235651.81
      2222480.36      7235450.35      2222478.48      7235175.22
      2222430.38      7235100.34      2222428.40      7234823.89
      2222382.65      7234758.49      2222379.00      7234710.00

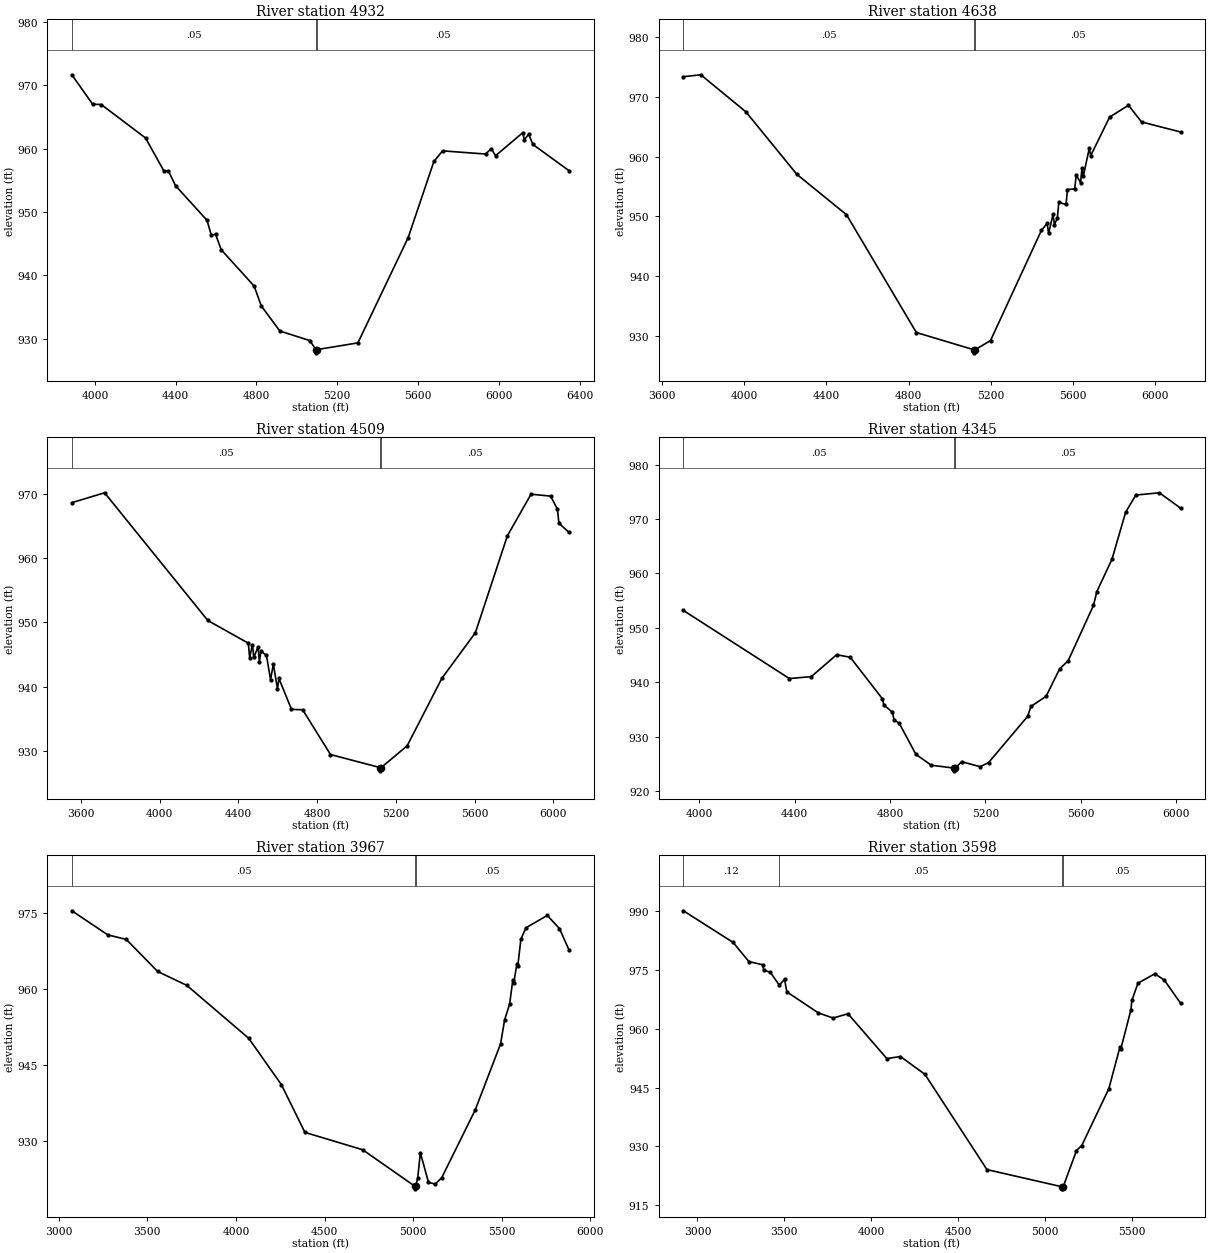
Type RM Length L Ch R = 1,4932,294,294,294
BEGIN DESCRIPTION:
Upper Denton 90 10.5
END DESCRIPTION:
XS GIS Cut Line= 4
      2224254.13      7239650.39      2223525.23      7238870.30
      2223418.17      7238859.57      2222599.27      7237868.31
#Sta/Elev= 30
  3885.9  971.63  3988.9  966.99  4031.4  966.94  4250.7  961.67  4342.5  956.42
  4364.0  956.48  4399.2  954.15  4555.0  948.70  4576.0  946.38  4597.5  946.48
  4625.5  944.05  4788.5  938.33  4823.7  935.21  4915.6  931.25  5064.1  929.74
  5094.0  928.31  5094.3  927.81  5098.0  928.31  5301.9  929.38  5550.7  945.96
  5678.4  957.99  5721.4  959.64  5933.7  959.14  5962.4  959.99  5983.2  958.87
  6118.7  962.52  6125.2  961.36  6147.4  962.28  6168.2  960.65  6346.9  956.52
#Mann=3,-1,0
  3885.9    0.05       0  5094.0   0.033       0  5098.0    0.05       0
Bank Sta=5094,5098
Exp/Cntr=0.3,0.1

Type RM Length L Ch R = 1,4638,129,129,129
BEGIN DESCRIPTION:
Upper Denton 90 10.0
END DESCRIPTION:
XS GIS Cut Line= 3
      2224319.22      7239559.23      2223463.31      7238554.01
      2222676.05      7237784.10
#Sta/Elev= 30
  3703.5  973.32  3788.3  973.64  4007.9  967.45  4256.1  957.02  4497.7  950.29
  4838.1  930.62  5119.6  927.73  5119.8  927.23  5123.6  927.73  5199.3  929.28
  5446.9  947.65  5475.2  948.84  5482.2  947.16  5503.5  950.34  5510.5  948.64
  5524.6  949.69  5531.8  952.33  5567.1  952.00  5574.2  954.49  5609.5  954.59
  5616.6  956.88  5637.8  955.66  5644.9  958.04  5651.9  956.81  5680.2  961.35
  5687.2  960.13  5779.2  966.57  5871.1  968.55  5934.8  965.77  6124.9  964.09
#Mann=3,-1,0
  3703.5    0.05       0  5119.6   0.033       0  5123.6    0.05       0
Bank Sta=5119.6,5123.6
Exp/Cntr=0.3,0.1

Type RM Length L Ch R = 1,4509,164,164,164
BEGIN DESCRIPTION:
Upper Denton 90 9.4
END DESCRIPTION:
XS GIS Cut Line= 3
      2224480.65      7239543.58      2223530.15      7238462.87
      2222735.87      7237720.68
#Sta/Elev= 30
  3553.6  968.67  3720.0  970.21  4244.6  950.31  4450.5  946.77  4457.2  944.51
  4471.4  946.56  4478.1  944.56  4499.9  946.20  4506.5  943.84  4514.1  945.53
  4542.5  944.88  4563.4  941.10  4577.7  943.52  4598.6  939.63  4606.1  941.27
  4669.7  936.46  4726.6  936.40  4868.0  929.42  5121.0  927.38  5121.2  926.88
  5125.0  927.38  5257.3  930.77  5434.2  941.31  5604.2  948.40  5766.8  963.50
  5887.0  969.99  5986.2  969.69  6021.4  967.66  6028.7  965.45  6079.9  964.05
#Mann=3,-1,0
  3553.6    0.05       0  5121.0   0.033       0  5125.0    0.05       0
Bank Sta=5121,5125
Exp/Cntr=0.3,0.1

Type RM Length L Ch R = 1,4345,378,378,378
BEGIN DESCRIPTION:
Upper Denton 90 9.0
END DESCRIPTION:
XS GIS Cut Line= 3
      2224293.16      7239103.48      2223579.00      7238310.00
      2222808.79      7237645.16
#Sta/Elev= 30
  3933.6  953.20  4378.2  940.69  4470.1  941.05  4576.2  945.07  4633.0  944.61
  4767.6  937.01  4774.3  935.83  4810.2  934.52  4816.9  933.10  4838.6  932.49
  4908.8  926.76  4973.1  924.77  5069.9  924.24  5070.2  923.74  5073.9  924.24
  5100.4  925.42  5178.3  924.50  5213.4  925.25  5376.9  933.73  5391.1  935.57
  5454.7  937.43  5511.8  942.50  5546.9  943.94  5653.3  954.12  5667.6  956.68
  5731.2  962.63  5788.2  971.24  5831.0  974.40  5929.7  974.82  6018.6  972.00
#Mann=3,-1,0
  3933.6    0.05       0  5069.9    0.04       0  5073.9    0.05       0
Bank Sta=5069.9,5073.9
Exp/Cntr=0.3,0.1

Type RM Length L Ch R = 1,3967,369,369,369
BEGIN DESCRIPTION:
Upper Denton 90 8.0
END DESCRIPTION:
XS GIS Cut Line= 3
      2225386.90      7238634.74      2223579.00      7237960.00
      2222783.41      7237593.38
#Sta/Elev= 30
  3074.0  975.53  3276.7  970.77  3381.3  969.86  3558.4  963.52  3722.9  960.77
  4072.0  950.31  4256.5  941.14  4389.4  931.69  4715.5  928.25  5010.4  921.02
  5010.7  920.52  5014.4  921.02  5025.7  922.58  5040.9  927.67  5086.8  921.79
  5124.8  921.47  5161.2  922.70  5350.4  936.12  5493.6  949.20  5516.6  953.98
  5545.0  957.11  5562.5  961.84  5568.0  961.32  5585.4  964.91  5590.9  964.68
  5608.4  969.93  5636.9  972.16  5757.2  974.61  5826.0  972.01  5879.7  967.79
#Mann=3,-1,0
  3074.0    0.05       0  5010.4    0.04       0  5014.4    0.05       0
Bank Sta=5010.4,5014.4
Exp/Cntr=0.3,0.1

Type RM Length L Ch R = 1,3598,389,389,389
BEGIN DESCRIPTION:
Upper Denton 90 7.0
END DESCRIPTION:
XS GIS Cut Line= 3
      2225556.23      7237241.50      2223529.00      7237710.00
      2222756.67      7237593.07
#Sta/Elev= 30
  2919.3  990.18  3205.1  982.10  3296.2  977.21  3376.1  976.37  3381.2  974.99
  3418.8  974.50  3471.6  971.15  3501.5  972.68  3514.5  969.46  3696.5  964.07
  3781.2  962.77  3866.7  963.86  4090.6  952.40  4168.6  952.94  4309.4  948.39
  4666.6  924.04  5101.2  919.62  5101.4  919.12  5105.2  919.62  5182.0  928.90
  5212.4  930.19  5368.3  944.72  5432.0  955.31  5437.1  954.88  5495.5  964.87
  5500.8  967.28  5536.0  971.68  5633.3  974.09  5687.7  972.46  5781.1  966.56
#Mann=4,-1,0
  2919.3    0.12       0  3471.6    0.05       0  5101.2   0.033       0
  5105.2    0.05       0
Bank Sta=5101.2,5105.2
Exp/Cntr=0.3,0.1

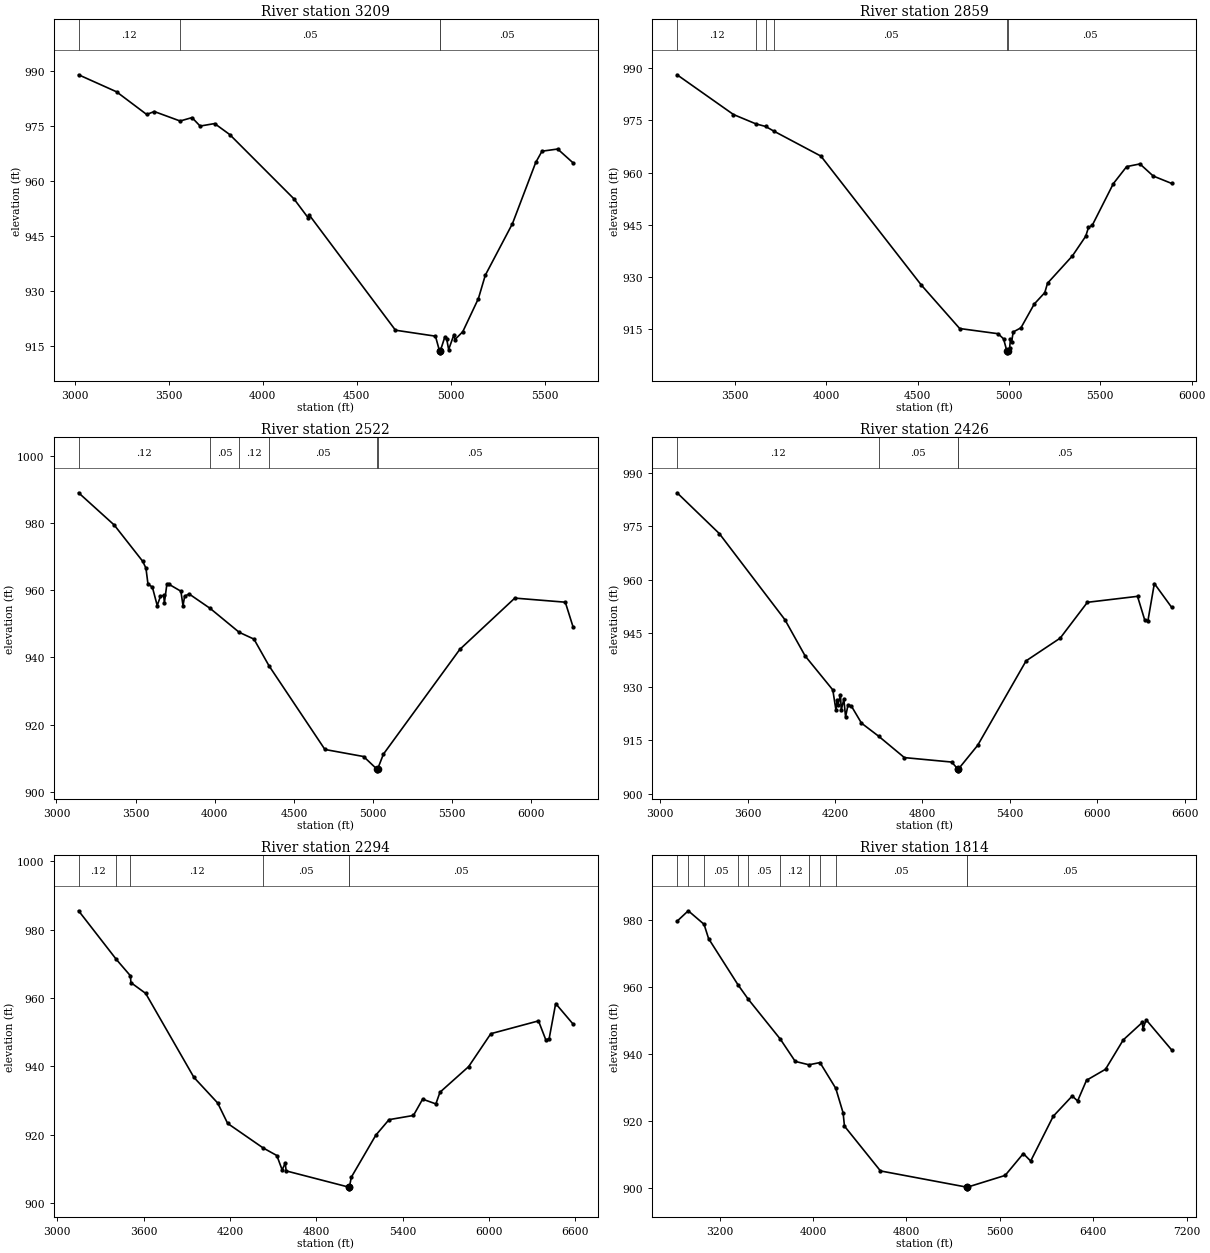
Type RM Length L Ch R = 1,3209,350,350,350
BEGIN DESCRIPTION:
Upper Denton 90 6.0
END DESCRIPTION:
XS GIS Cut Line= 3
      2225399.92      7237189.43      2223429.00      7237360.00
      2222795.77      7237514.95
#Sta/Elev= 30
  3021.7  989.03  3223.4  984.39  3384.0  978.19  3424.1  979.00  3561.7  976.41
  3624.9  977.34  3668.1  975.03  3745.3  975.71  3825.6  972.71  4166.9  955.17
  4244.1  949.88  4249.1  950.71  4707.0  919.30  4919.7  917.67  4941.4  913.62
  4941.6  913.12  4945.4  913.62  4969.9  917.50  4979.9  916.79  4989.9  914.02
  5018.2  918.11  5023.4  916.74  5065.0  918.89  5148.2  927.95  5184.7  934.30
  5329.4  948.41  5453.0  965.09  5486.4  968.17  5569.7  968.76  5651.9  964.97
#Mann=4,-1,0
  3021.7    0.12       0  3561.7    0.05       0  4941.4   0.033       0
  4945.4    0.05       0
Bank Sta=4941.4,4945.4
Exp/Cntr=0.3,0.1

Type RM Length L Ch R = 1,2859,337,337,337
BEGIN DESCRIPTION:
Upper Denton 90 5.0
END DESCRIPTION:
XS GIS Cut Line= 3
      2225243.70      7237124.33      2223429.00      7237010.00
      2222678.59      7237488.90
#Sta/Elev= 30
  3181.7  988.08  3490.6  976.67  3613.8  973.98  3666.4  973.25  3713.0  971.87
  3969.6  964.73  4519.0  927.74  4729.5  915.24  4939.9  913.75  4969.9  912.27
  4988.0  908.76  4988.2  908.26  4992.0  908.76  5003.0  909.69  5007.6  912.15
  5013.5  911.35  5022.8  914.25  5065.1  915.45  5137.9  922.27  5195.5  925.54
  5210.7  928.25  5346.9  936.09  5419.7  941.73  5434.9  944.24  5456.1  944.92
  5571.1  956.83  5643.9  961.72  5716.7  962.49  5789.4  959.02  5890.2  956.89
#Mann=6,-1,0
  3181.7    0.12       0  3613.8    0.05       0  3666.4    0.12       0
  3713.0    0.05       0  4988.0    0.04       0  4992.0    0.05       0
Bank Sta=4988,4992
Exp/Cntr=0.3,0.1

Type RM Length L Ch R = 1,2522,96,96,96
BEGIN DESCRIPTION:
Upper Denton 90 4.0
END DESCRIPTION:
XS GIS Cut Line= 4
      2225256.73      7237007.14      2223497.59      7236669.47
      2223384.75      7236675.98      2222583.41      7237594.32
#Sta/Elev= 30
  3140.1  989.02  3365.3  979.42  3545.1  968.62  3565.5  966.58  3578.3  961.87
  3606.2  960.92  3636.7  955.45  3657.1  958.18  3677.2  958.46  3682.2  956.33
  3697.8  961.84  3708.0  961.86  3786.2  959.72  3799.7  955.38  3809.8  958.24
  3838.2  958.90  3971.6  954.58  4154.3  947.49  4247.7  945.46  4342.4  937.54
  4695.7  912.61  4940.0  910.51  5024.3  906.75  5024.5  906.25  5028.3  906.75
  5065.2  911.22  5547.4  942.39  5894.9  957.67  6213.8  956.45  6263.2  949.04
#Mann=6,-1,0
  3140.1    0.12       0  3971.6    0.05       0  4154.3    0.12       0
  4342.4    0.05       0  5024.3    0.04       0  5028.3    0.05       0
Bank Sta=5024.3,5028.3
Exp/Cntr=0.3,0.1

Type RM Length L Ch R = 1,2426,132,132,132
BEGIN DESCRIPTION:
Upper Denton 90 3.5
END DESCRIPTION:
XS GIS Cut Line= 5
      2225113.48      7236876.93      2223853.06      7236309.22
      2223415.56      7236585.26      2222952.02      7237059.22
      2222468.13      7237735.63
#Sta/Elev= 30
  3115.8  984.40  3405.9  972.96  3856.0  948.83  3994.9  938.67  4184.6  929.16
  4206.5  923.46  4214.1  926.24  4219.6  924.81  4237.3  927.83  4242.7  923.52
  4260.4  926.58  4272.3  921.59  4289.0  924.96  4312.2  924.63  4381.6  919.84
  4499.4  916.18  4676.0  910.19  5000.9  908.94  5042.7  906.98  5042.9  906.48
  5046.7  906.98  5179.0  913.63  5511.5  937.31  5745.4  943.67  5932.1  953.71
  6276.1  955.38  6326.5  948.62  6347.4  948.51  6391.6  958.97  6510.1  952.31
#Mann=4,-1,0
  3115.8    0.12       0  4499.4    0.05       0  5042.7   0.033       0
  5046.7    0.05       0
Bank Sta=5042.7,5046.7
Exp/Cntr=0.3,0.1

Type RM Length L Ch R = 1,2294,480,480,480
BEGIN DESCRIPTION:
Upper Denton 90 3.0
END DESCRIPTION:
XS GIS Cut Line= 6
      2225077.01      7236668.59      2223800.98      7236205.06
      2223431.19      7236429.01      2223321.81      7236496.72
      2222915.56      7236923.81      2222467.98      7237735.70
#Sta/Elev= 30
  3148.8  985.49  3411.5  971.23  3508.9  966.46  3512.3  964.46  3614.8  961.31
  3950.0  936.72  4114.9  929.23  4184.2  923.25  4429.6  916.10  4525.9  913.85
  4562.8  909.64  4584.1  911.64  4590.6  909.35  5025.8  904.60  5026.1  904.10
  5029.8  904.60  5043.2  907.50  5213.1  919.79  5305.2  924.35  5474.7  925.58
  5538.6  930.35  5630.5  928.96  5659.1  932.38  5858.0  939.87  6012.2  949.51
  6343.4  953.26  6394.7  947.65  6417.5  948.09  6462.7  958.33  6583.9  952.31
#Mann=6,-1,0
  3148.8    0.12       0  3411.5    0.05       0  3508.9    0.12       0
  4429.6    0.05       0  5025.8    0.04       0  5029.8    0.05       0
Bank Sta=5025.8,5029.8
Exp/Cntr=0.3,0.1

Type RM Length L Ch R = 1,1814,570,570,570
BEGIN DESCRIPTION:
Upper Denton 90 2.0
END DESCRIPTION:
XS GIS Cut Line= 6
      2225204.65      7236668.61      2224353.06      7236121.72
      2223420.77      7235970.68      2223199.42      7236093.94
      2222634.31      7236679.01      2222332.23      7237850.90
#Sta/Elev= 30
  2836.5  979.76  2932.2  982.88  3067.5  978.84  3106.4  974.56  3359.3  960.70
  3445.7  956.47  3720.7  944.52  3848.0  937.88  3965.6  936.87  4059.9  937.53
  4194.9  929.84  4257.9  922.50  4269.4  918.55  4577.7  905.16  5317.6  900.31
  5317.8  899.81  5321.6  900.31  5645.0  903.82  5800.6  910.35  5863.5  908.11
  6056.6  921.49  6219.4  927.56  6265.2  926.05  6341.4  932.24  6504.1  935.53
  6656.0  944.30  6819.3  949.53  6824.5  947.54  6852.2  950.31  7070.0  941.32
#Mann=11,-1,0
  2836.5    0.05       0  2932.2    0.12       0  3067.5    0.05       0
  3359.3    0.12       0  3445.7    0.05       0  3720.7    0.12       0
  3965.6    0.05       0  4059.9    0.12       0  4194.9    0.05       0
  5317.6    0.04       0  5321.6    0.05       0
Bank Sta=5317.6,5321.6
Exp/Cntr=0.3,0.1

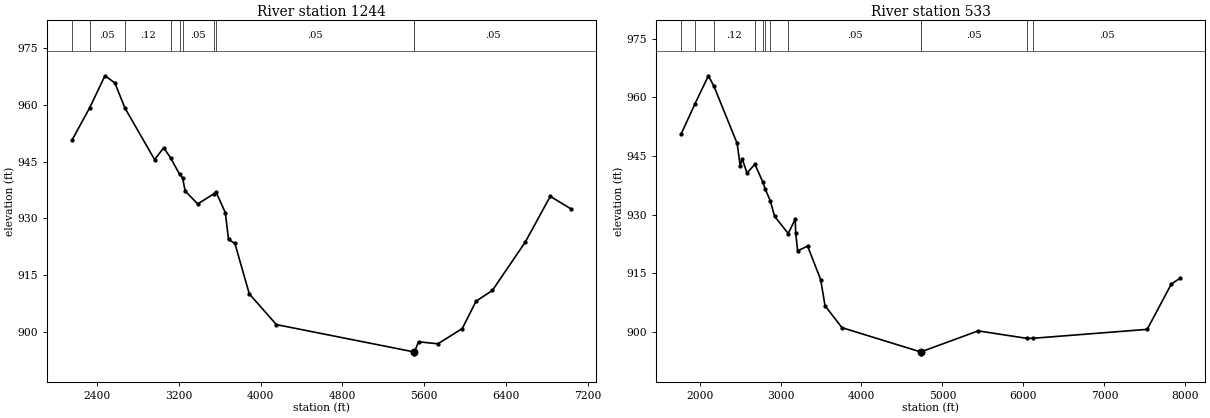
Type RM Length L Ch R = 1,1244,711,711,711
BEGIN DESCRIPTION:
Upper Denton 90 1.0
END DESCRIPTION:
XS GIS Cut Line= 4
      2225483.23      7236392.54      2222881.90      7235664.34
      2222562.45      7235983.79      2222076.35      7237643.47
#Sta/Elev= 30
  2155.5  950.61  2327.4  959.07  2478.4  967.57  2575.3  965.68  2673.7  959.07
  2963.6  945.50  3053.0  948.63  3119.4  945.98  3207.8  941.62  3237.2  940.69
  3262.6  937.22  3385.3  933.83  3543.9  936.50  3564.9  936.95  3655.3  931.51
  3686.4  924.47  3748.7  923.43  3889.4  910.15  4154.2  902.06  5500.6  894.86
  5500.9  894.36  5504.6  894.86  5544.3  897.54  5733.6  897.00  5971.5  901.02
  6107.0  908.23  6266.1  911.05  6587.7  923.79  6832.1  935.83  7038.0  932.47
#Mann=10,-1,0
  2155.5    0.12       0  2327.4    0.05       0  2673.7    0.12       0
  3119.4    0.05       0  3207.8    0.12       0  3237.2    0.05       0
  3543.9    0.12       0  3564.9    0.05       0  5500.6    0.04       0
  5504.6    0.05       0
Bank Sta=5500.6,5504.6
Exp/Cntr=0.3,0.1

Type RM Length L Ch R = 1,533,0,0,0
BEGIN DESCRIPTION:
Upper Denton 90 0.5
END DESCRIPTION:
XS GIS Cut Line= 5
      2225483.25      7236392.55      2222479.00      7235210.00
      2222087.68      7235472.34      2221409.67      7237490.73
      2221520.79      7237810.20
#Sta/Elev= 30
  1771.8  950.61  1945.0  958.44  2109.5  965.54  2178.0  962.84  2464.2  948.25
  2502.0  942.52  2526.4  944.31  2586.0  940.66  2683.5  942.92  2782.6  938.32
  2810.0  936.62  2874.0  933.56  2926.3  929.60  3095.2  925.20  3181.8  928.89
  3187.2  925.42  3211.6  920.78  3334.7  921.98  3495.9  913.42  3549.6  906.74
  3758.7  901.13  4729.2  894.93  4729.9  894.43  4734.2  894.93  5440.1  900.30
  6043.2  898.39  6112.9  898.40  7527.9  900.69  7827.3  912.32  7939.0  913.81
#Mann=12,-1,0
  1771.8    0.12       0  1945.0    0.05       0  2178.0    0.12       0
  2683.5    0.05       0  2782.6    0.12       0  2810.0    0.05       0
  2874.0    0.12       0  3095.2    0.05       0  4729.2    0.04       0
  4734.2    0.05       0  6043.2    0.12       0  6112.9    0.05       0
Bank Sta=4729.2,4734.2
Exp/Cntr=0.3,0.1

Chan Stop Cuts=-1