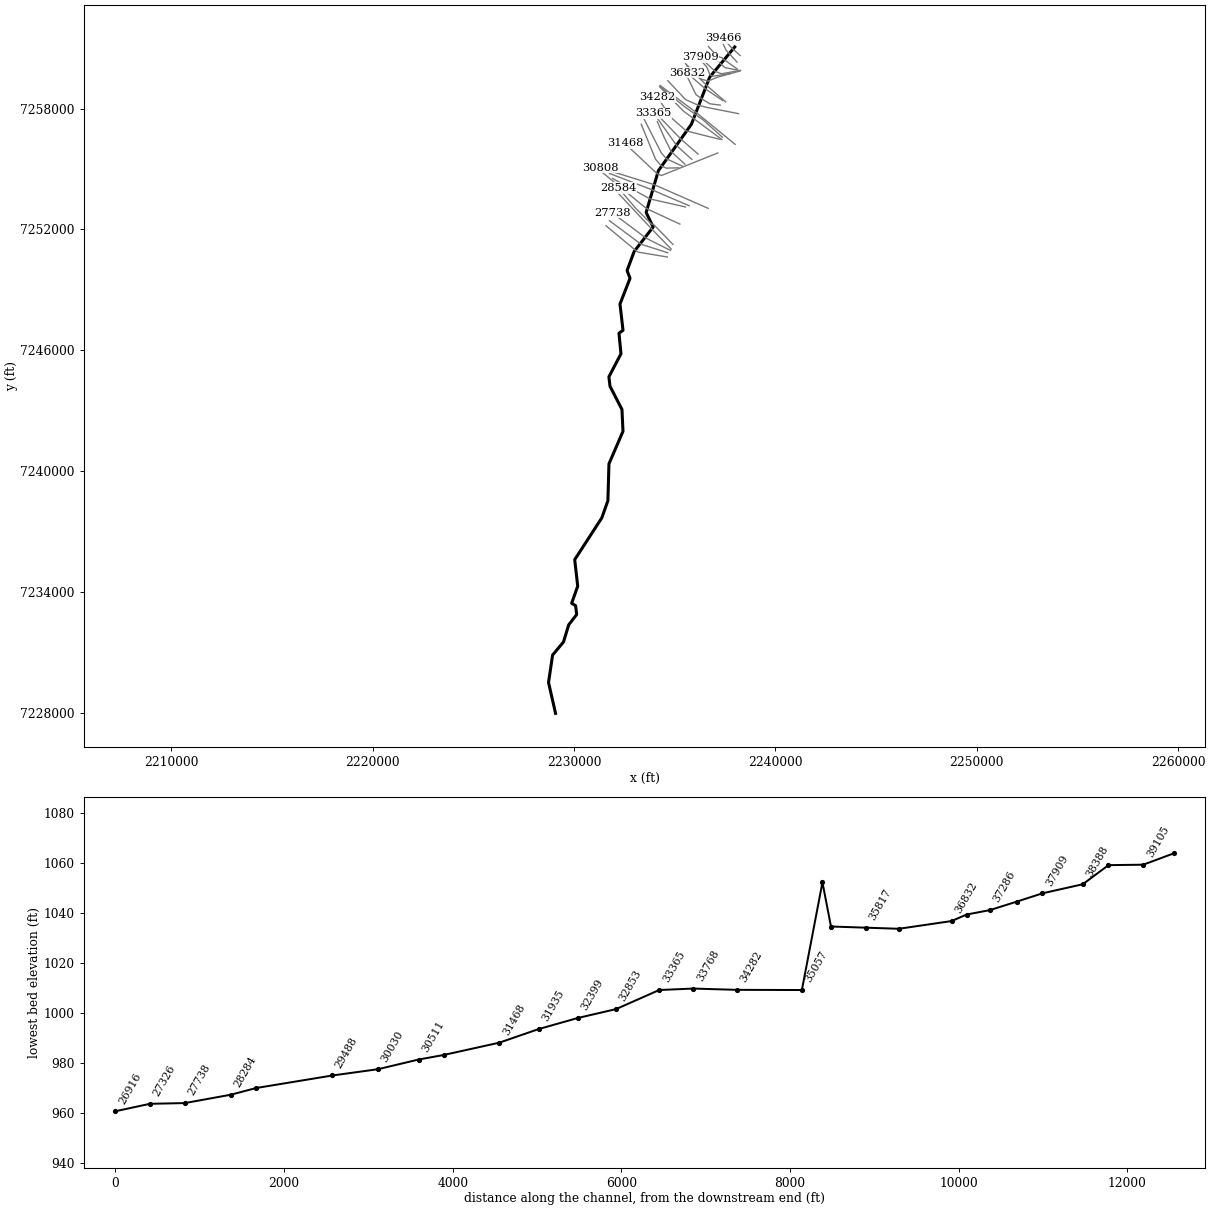
--- Upper Denton 93.prj (project) ---

Proj Title=Upper Denton 93 Base Level Engineering
Current Plan=p01
Default Exp/Contr=0.3,0.1
English Units
Geom File=g01
Flow File=f01
Plan File=p01
Y Axis Title=Elevation
X Axis Title(PF)=Main Channel Distance
X Axis Title(XS)=Station
BEGIN DESCRIPTION:
Upper Denton 93
END DESCRIPTION:
DSS Export Rating Curves= 0
DSS Export Rating Curve Sorted= 0
DSS Export Volume Flow Curves= 0
DXF OffsetX= 0
DXF OffsetY= 0
DXF ScaleX= 1
DXF ScaleY= 10

--- Upper Denton 93.p01 (plan) ---

Plan Title=Multiple Run
Short Identifier=Multiple
Geom File=g01
Flow File=f01
Subcritical Flow
K Sum by GR= 0
Std Step Tol= 0.01
Critical Tol= 0.01
Num of Std Step Trials= 20
Max Error Tol= 0.3
Flow Tol Ratio= 0.001
Split Flow NTrial= 30
Split Flow Tol= 0.02
Split Flow Ratio= 0.02
Log Output Level= 0
Friction Slope Method= 1
Unsteady Friction Slope Method= 2
Unsteady Bridges Friction Slope Method= 1
Parabolic Critical Depth
Global Vel Dist=  1 , 1 , 1
Global Log Level= 0
CheckData=True
Encroach Param= -1, 0, 0, 0
BEGIN DESCRIPTION:
Multiple Run
END DESCRIPTION:

--- Upper Denton 93.f01 (steady flow) ---

Flow Title=Multiple
Program Version=4.10
Number of Profiles= 7
Profile Names=10-year,25-year,50-year,1pct_min,100-year,1pct_plu,500-year
River Rch & RM=Upper Denton 93,Reach-1         ,39466
     917    1318    1665    1045    2086    4162    3283
River Rch & RM=Upper Denton 93,Reach-1         ,35402
    1162    1690    2152    1361    2716    5420    4339
River Rch & RM=Upper Denton 93,Reach-1         ,33768
    1203    1749    2227    1408    2808    5604    4480
River Rch & RM=Upper Denton 93,Reach-1         ,30808
    1606    2369    3044    1940    3870    7723    6279
River Rch & RM=Upper Denton 93,Reach-1         ,28584
    1738    2562    3292    2096    4182    8344    6772
River Rch & RM=Upper Denton 93,Reach-1         ,23909
    2536    3782    4895    3134    6253   12476   10245
River Rch & RM=Upper Denton 93,Reach-1         ,15072
    2713    4053    5252    3365    6715   13398   11023
River Rch & RM=Upper Denton 93,Reach-1         ,14824
    2713    4053    5252    3365    6715   13398   11023
River Rch & RM=Upper Denton 93,Reach-1         ,12461
    3148    4726    6144    3948    7878   15718   13002
River Rch & RM=Upper Denton 93,Reach-1         ,8841
    3381    5089    6627    4265    8509   16978   14086
River Rch & RM=Upper Denton 93,Reach-1         ,8401
    3429    5144    6684    4290    8560   17079   14097
Boundary for River Rch & Prof#=Upper Denton 93,Reach-1         , 1
Up Type= 0
Dn Type= 3
Dn Slope=0.005
Boundary for River Rch & Prof#=Upper Denton 93,Reach-1         , 2
Up Type= 0
Dn Type= 3
Dn Slope=0.005
Boundary for River Rch & Prof#=Upper Denton 93,Reach-1         , 3
Up Type= 0
Dn Type= 3
Dn Slope=0.005
Boundary for River Rch & Prof#=Upper Denton 93,Reach-1         , 4
Up Type= 0
Dn Type= 3
Dn Slope=0.005
Boundary for River Rch & Prof#=Upper Denton 93,Reach-1         , 5
Up Type= 0
Dn Type= 3
Dn Slope=0.005
Boundary for River Rch & Prof#=Upper Denton 93,Reach-1         , 6
Up Type= 0
Dn Type= 3
Dn Slope=0.005
Boundary for River Rch & Prof#=Upper Denton 93,Reach-1         , 7
Up Type= 0
Dn Type= 3
Dn Slope=0.005
DSS Import GetInterval= 0
DSS Import GetPeak= 0
DSS Import FillOption= 0

--- Upper Denton 93.g01 (geometry) ---

Geom Title=Existing Conditions
Program Version=4.10

River Reach=Upper Denton 93 ,Reach-1
Reach XY= 30
        2237979.        7261060.      2236737.16      7259566.05
      2235825.49      7257218.48      2234182.83      7254908.42
      2233578.88       7252839.9      2233927.18      7252116.12
      2232982.51      7250901.52      2232631.25      7249954.06
      2232778.06      7249570.49      2232279.21      7248291.73
       2232429.5      7246987.07      2232229.04       7246841.9
      2232327.62      7245819.66      2231728.61      7244678.34
      2231782.76      7244211.56      2232376.76      7243054.07
      2232427.95      7241970.44      2231731.26      7240354.06
      2231678.73      7238525.11      2231376.79      7237671.29
      2230030.19      7235595.17      2230179.22      7234278.68
      2229878.67      7233430.15      2230075.46        7233309.
      2230127.65      7232869.66      2229732.48      7232358.73
      2229473.53      7231507.55      2228932.54      7230858.54
      2228729.52      7229494.78        2229079.        7227960.

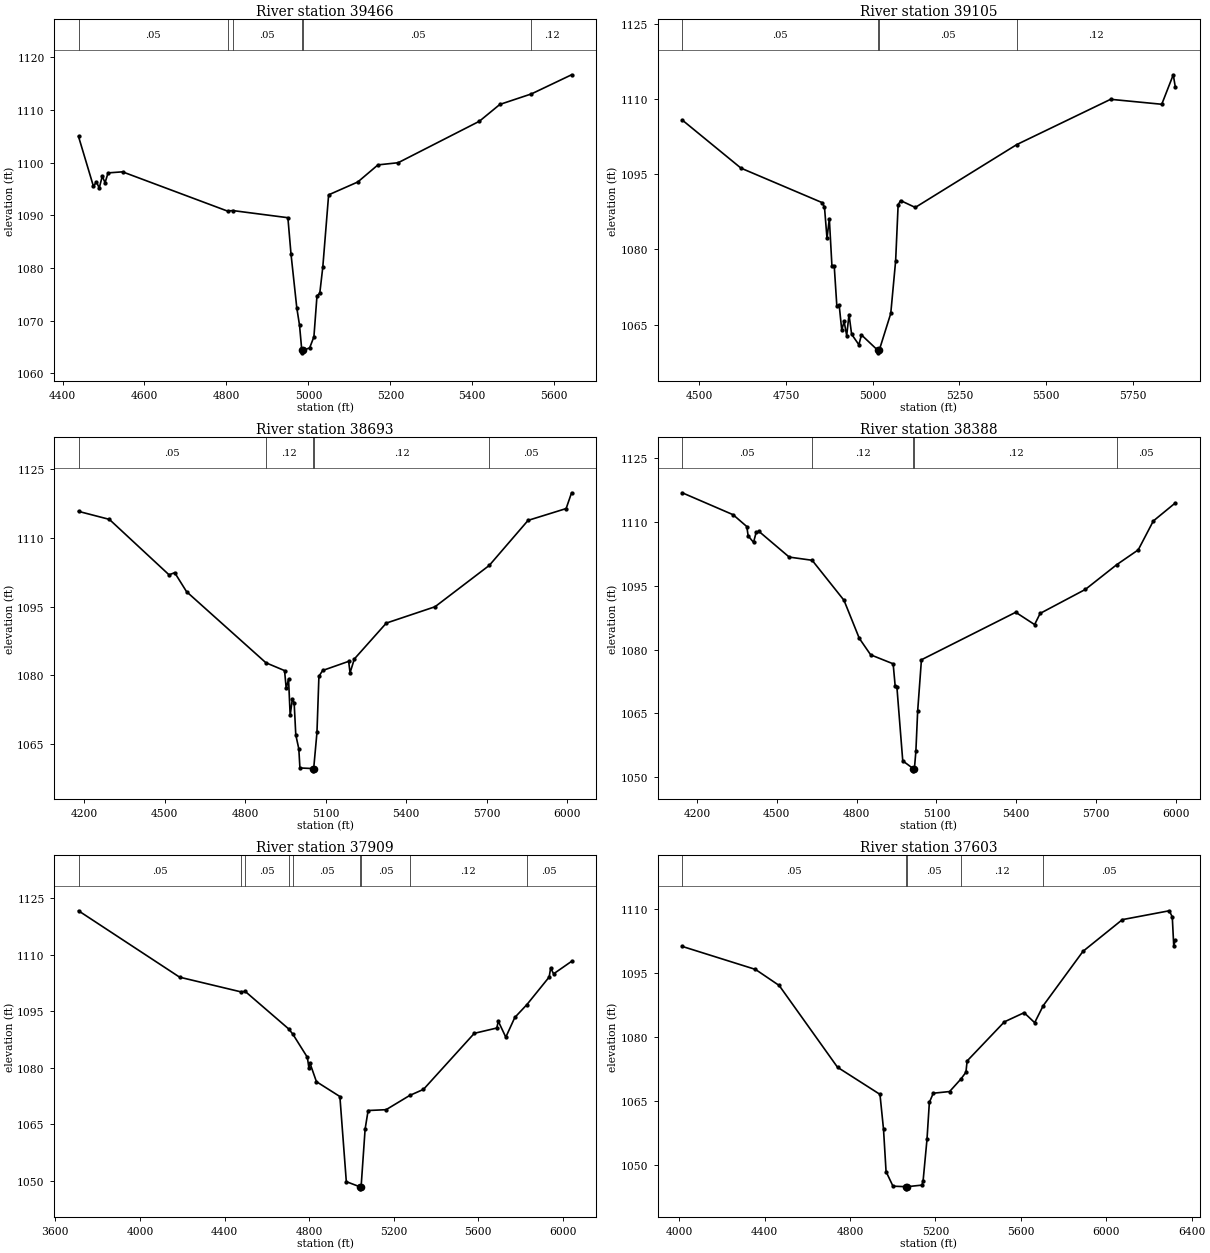
Type RM Length L Ch R = 1 ,39466   ,361,361,361
BEGIN DESCRIPTION:
Upper Denton 93 84.0
END DESCRIPTION:
XS GIS Cut Line= 3
      2238246.06       7260635.2        2237829.        7261010.
      2237399.67       7261488.1
#Sta/Elev= 30
    4439 1104.95  4475.4 1095.49  4482.8 1096.31  4489.6 1095.16    4497 1097.39
  4503.8 1096.17  4511.2 1098.03  4546.4 1098.23  4802.9 1090.77    4815 1090.88
    4950 1089.52  4957.5 1082.69  4971.7 1072.41  4978.4 1069.09  4983.9 1064.36
  4984.2 1063.86  4987.9 1064.36  5003.1  1064.8  5013.5 1066.91    5021 1074.68
  5027.8 1075.17  5035.2 1080.15  5049.4 1093.86  5120.5  1096.3  5169.8 1099.55
  5219.1 1099.96  5417.2 1107.83  5467.3 1111.03  5544.4 1113.03  5642.3 1116.66
#Mann= 6 ,-1 , 0
    4439     .05       0  4802.9     .12       0    4815     .05       0
  4983.9    .033       0  4987.9     .05       0  5544.4     .12       0
Bank Sta=4983.9,4987.9
XS Rating Curve= 0 ,0
Exp/Cntr=0.3,0.1

Type RM Length L Ch R = 1 ,39105   ,412,412,412
BEGIN DESCRIPTION:
Upper Denton 93 83.0
END DESCRIPTION:
XS GIS Cut Line= 4
      2238094.11      7260305.38        2237729.        7260710.
      2237553.75      7260889.14      2237284.78      7261455.29
#Sta/Elev= 30
  4450.4 1105.84  4619.9 1096.23  4853.8 1089.35  4860.7 1088.47    4868 1082.21
  4874.7 1086.13  4882.2 1076.73  4888.9 1076.63  4896.4 1068.66  4903.1 1068.88
  4910.6 1063.86  4917.3 1065.63  4924.8 1062.79  4931.5 1066.99    4939 1063.06
  4959.9 1060.96  4967.4 1062.92  5014.6 1059.84  5014.9 1059.34  5018.6 1059.84
  5051.9  1067.2    5066 1077.72  5073.2 1088.89  5080.2 1089.76  5122.6 1088.38
  5415.5 1100.94  5686.2 1109.98  5833.7 1108.99  5866.9 1114.88  5872.8 1112.43
#Mann= 4 ,-1 , 0
  4450.4     .05       0  5014.6    .033       0  5018.6     .05       0
  5415.5     .12       0
Bank Sta=5014.6,5018.6
XS Rating Curve= 0 ,0
Exp/Cntr=0.3,0.1

Type RM Length L Ch R = 1 ,38693   ,305,305,305
BEGIN DESCRIPTION:
Upper Denton 93 82.0
END DESCRIPTION:
XS GIS Cut Line= 5
      2238098.45      7259969.01       2237429.4      7260444.84
      2237360.61      7260518.05      2237111.04      7260596.17
       2236670.5      7261080.12
#Sta/Elev= 30
    4179 1115.85  4293.9  1114.1  4516.5 1101.98  4537.4 1102.46  4581.7  1098.3
  4877.4 1082.77  4946.9 1081.06    4953 1077.15  4961.7 1079.23  4967.8 1071.26
  4975.9 1074.86  4982.6 1074.04  4988.7 1067.01    5000 1063.96  5004.1 1059.79
  5051.4 1059.66  5051.7 1059.16  5055.4 1059.66  5067.6 1067.54  5074.9 1079.83
    5089 1081.09  5185.7 1083.08  5190.9 1080.58  5206.9  1083.6    5326 1091.44
  5507.6 1095.01  5709.9 1104.05  5854.3 1113.88  5996.1 1116.46  6016.4 1119.91
#Mann= 5 ,-1 , 0
    4179     .05       0  4877.4     .12       0  5051.4     .07       0
  5055.4     .12       0  5709.9     .05       0
Bank Sta=5051.4,5055.4
XS Rating Curve= 0 ,0
Exp/Cntr=0.3,0.1

Type RM Length L Ch R = 1 ,38388   ,479,479,479
BEGIN DESCRIPTION:
Upper Denton 93 81.0
END DESCRIPTION:
XS GIS Cut Line= 4
      2238131.86      7259908.27      2237494.47      7260033.32
      2237338.91      7260168.66      2236597.86      7260836.03
#Sta/Elev= 30
  4144.7  1116.8  4335.8 1111.65  4387.3 1108.87  4392.4 1106.67  4412.6 1105.16
  4422.8 1107.57    4433 1107.73  4546.7  1101.7  4632.9 1100.95  4752.5 1091.56
  4810.1 1082.62  4852.8 1078.75  4937.3 1076.64  4944.9 1071.42  4951.5 1071.09
  4973.4 1053.85  5013.2 1052.01  5013.5 1051.51  5017.2 1052.01  5022.7 1056.08
  5029.4  1065.5  5043.6 1077.59  5397.9 1088.74  5468.9 1085.85  5489.8 1088.48
  5659.7 1094.11  5777.8 1099.93  5858.3 1103.39  5915.1 1110.18  5997.7 1114.41
#Mann= 5 ,-1 , 0
  4144.7     .05       0  4632.9     .12       0  5013.2     .07       0
  5017.2     .12       0  5777.8     .05       0
Bank Sta=5013.2,5017.2
XS Rating Curve= 0 ,0
Exp/Cntr=0.3,0.1

Type RM Length L Ch R = 1 ,37909   ,306,306,306
BEGIN DESCRIPTION:
Upper Denton 93 80.0
END DESCRIPTION:
XS GIS Cut Line= 4
      2238267.28      7259901.32      2237328.03      7259727.79
      2237004.71      7259847.47      2236253.96      7260554.83
#Sta/Elev= 30
  3709.6 1121.61  4187.8    1104  4475.9 1100.13  4498.2 1100.21  4703.4 1090.28
  4723.3 1088.87  4791.7 1082.75  4798.9 1079.98  4804.2 1081.17  4834.6 1076.29
  4945.5 1072.35  4975.9 1049.78  5041.8 1048.37  5042.1 1047.87  5045.8 1048.37
  5064.8 1063.72    5079 1068.64    5164 1068.86  5275.5 1072.63  5340.8 1074.25
  5581.1 1089.11  5687.5 1090.52  5694.4 1092.33    5730 1088.09  5772.5 1093.31
  5829.8 1096.73  5935.1 1104.04    5942 1106.43  5956.1 1104.89    6041  1108.2
#Mann= 9 ,-1 , 0
  3709.6     .05       0  4475.9     .12       0  4498.2     .05       0
  4703.4     .12       0  4723.3     .05       0  5041.8    .033       0
  5045.8     .05       0  5275.5     .12       0  5829.8     .05       0
Bank Sta=5041.8,5045.8
XS Rating Curve= 0 ,0
Exp/Cntr=0.3,0.1

Type RM Length L Ch R = 1 ,37603   ,317,317,317
BEGIN DESCRIPTION:
Upper Denton 93 79.0
END DESCRIPTION:
XS GIS Cut Line= 5
       2237777.7       7259741.6       2236881.9      7259606.18
      2236753.43      7259672.16      2236583.29      7260074.93
      2236027.73       7260679.1
#Sta/Elev= 30
  4014.8 1101.19  4357.3 1095.82  4468.6 1092.06  4741.7 1072.95  4940.5 1066.61
  4957.1 1058.45    4969 1048.56  5001.4 1045.15  5062.9 1045.03  5063.1 1044.53
  5066.9 1045.03  5137.1  1045.4  5142.5 1046.45  5160.6 1056.07  5171.7 1064.73
    5190 1066.88  5266.5 1067.27  5319.8 1070.22    5343 1071.79  5348.5 1074.42
  5522.9 1083.56  5615.4  1085.7  5664.7 1083.37  5705.1 1087.37    5891 1100.04
  6075.3 1107.45  6294.8 1109.52    6309  1108.1  6315.8 1101.37  6323.2 1102.59
#Mann= 5 ,-1 , 0
  4014.8     .05       0  5062.9    .033       0  5066.9     .05       0
  5319.8     .12       0  5705.1     .05       0
Bank Sta=5062.9,5066.9
XS Rating Curve= 0 ,0
Exp/Cntr=0.3,0.1

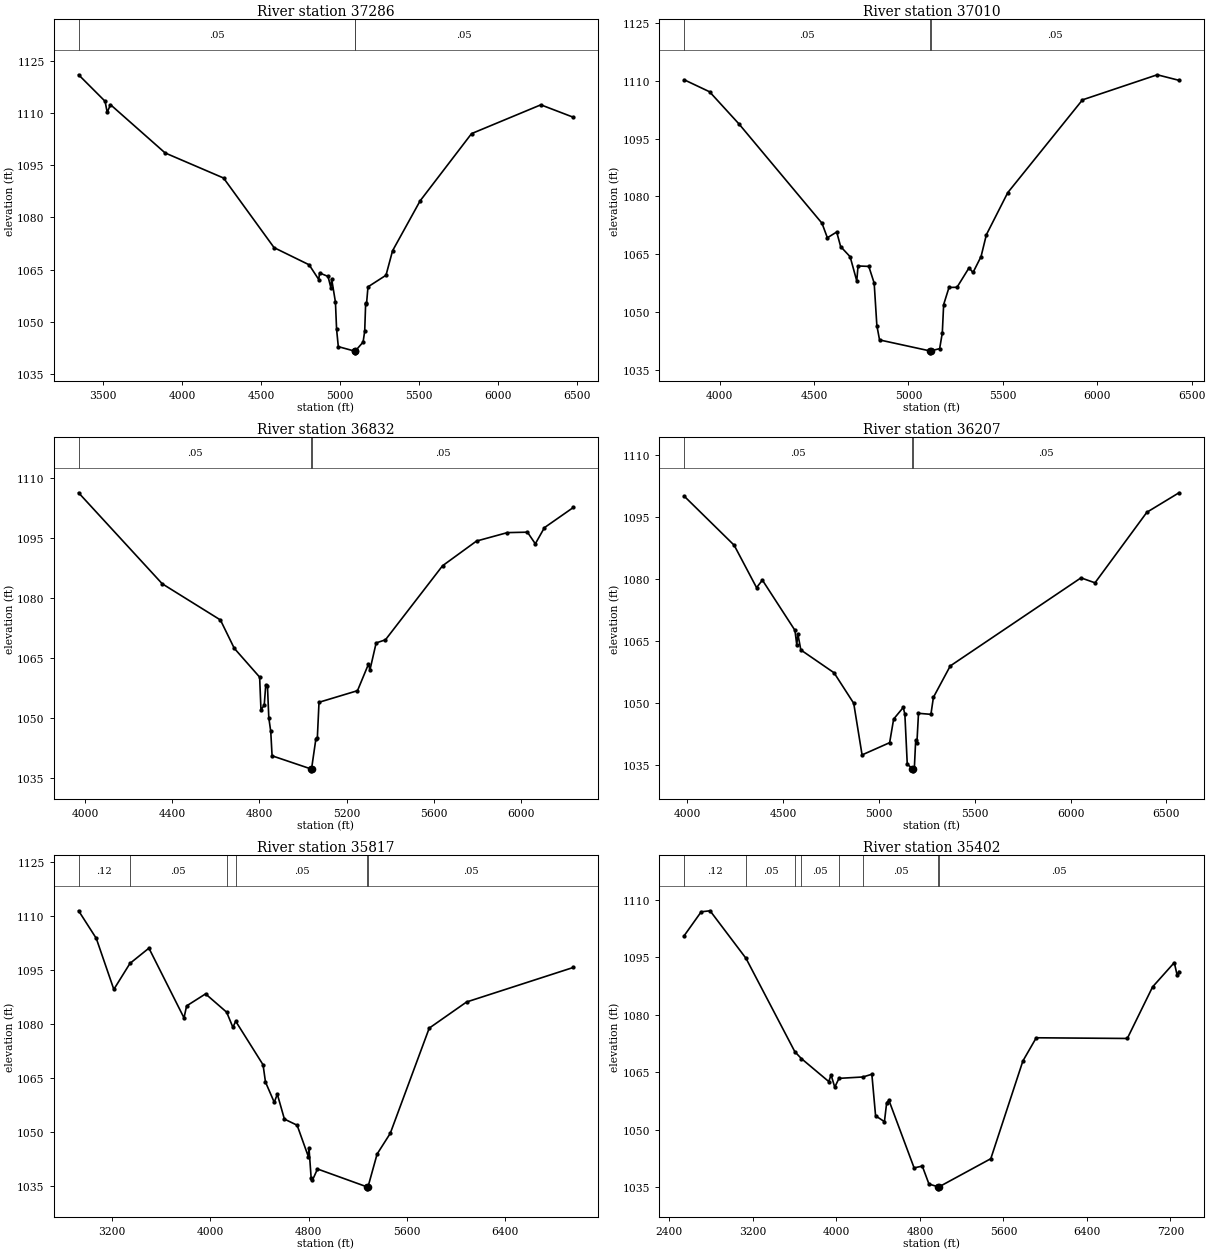
Type RM Length L Ch R = 1 ,37286   ,276,276,276
BEGIN DESCRIPTION:
Upper Denton 93 78.0
END DESCRIPTION:
XS GIS Cut Line= 5
      2238253.47      7259870.08      2237107.59       7259554.1
      2236663.98      7259366.59      2236327.95      7259457.71
      2235530.57      7260232.31
#Sta/Elev= 30
  3344.9 1120.93  3512.4 1113.33  3525.9 1110.14  3546.6 1112.36  3892.4  1098.5
    4262 1091.31  4581.7 1071.33  4803.4 1066.41  4864.1 1062.19  4869.6 1064.07
  4922.9 1063.07  4940.7 1059.87  4946.1 1062.27  4969.8 1055.71  4977.1 1047.89
    4988 1042.93  5090.8 1041.65  5091.1 1041.15  5094.8 1041.65  5144.7 1044.23
    5155 1047.39  5161.1 1055.52  5166.2 1055.06  5175.7 1060.08  5289.7 1063.41
  5331.2 1070.44  5505.6 1084.76    5831 1104.05  6269.3 1112.31    6475 1108.74
#Mann= 3 ,-1 , 0
  3344.9     .05       0  5090.8    .033       0  5094.8     .05       0
Bank Sta=5090.8,5094.8
XS Rating Curve= 0 ,0
Exp/Cntr=0.3,0.1

Type RM Length L Ch R = 1 ,37010   ,178,178,178
BEGIN DESCRIPTION:
Upper Denton 93 77.0
END DESCRIPTION:
XS GIS Cut Line= 3
      2237523.97      7258335.73        2236629.        7259110.
      2235604.65      7260118.36
#Sta/Elev= 30
  3812.1 1110.26  3946.4 1107.15  4102.2  1098.8    4542 1073.02  4570.5 1069.25
  4619.9 1070.75  4640.7 1066.97  4691.1 1064.32  4726.2 1058.04  4732.9 1061.93
  4789.9 1061.82  4818.4 1057.48  4832.6 1046.46  4846.9 1042.73  5113.7 1039.88
    5114 1039.38  5117.7 1039.88  5165.2 1040.47  5179.3 1044.56  5186.4 1051.91
  5214.7 1056.35  5257.2  1056.4  5320.8 1061.44    5342 1060.24  5384.5 1064.37
  5412.7 1070.04  5525.9 1080.96  5921.8 1105.05  6317.8 1111.56  6432.9 1110.12
#Mann= 3 ,-1 , 0
  3812.1     .05       0  5113.7    .033       0  5117.7     .05       0
Bank Sta=5113.7,5117.7
XS Rating Curve= 0 ,0
Exp/Cntr=0.3,0.1

Type RM Length L Ch R = 1 ,36832   ,625,625,625
BEGIN DESCRIPTION:
Upper Denton 93 76.0
END DESCRIPTION:
XS GIS Cut Line= 3
      2237392.28      7258390.93      2236538.15      7258963.82
      2235597.92      7259775.68
#Sta/Elev= 30
  3969.8 1106.29  4353.6 1083.54  4620.7 1074.49  4684.2 1067.41  4800.7  1060.2
  4806.8 1052.01  4821.8 1053.18  4828.7 1058.22  4836.7 1057.86  4842.8 1050.01
  4851.7 1046.63  4857.8 1040.53    5035 1037.27  5035.3 1036.77    5039 1037.27
  5058.9 1044.78  5065.5 1044.98  5073.2 1053.91  5249.8 1056.81  5300.3 1063.46
  5306.9 1061.98  5335.4 1068.75  5378.1 1069.53  5640.3 1088.05  5796.1 1094.22
  5937.6 1096.33  6029.8 1096.44  6065.9 1093.53  6107.7 1097.57  6240.5 1102.62
#Mann= 3 ,-1 , 0
  3969.8     .05       0    5035    .033       0    5039     .05       0
Bank Sta=5035,5039
XS Rating Curve= 0 ,0
Exp/Cntr=0.3,0.1

Type RM Length L Ch R = 1 ,36207   ,390,390,390
BEGIN DESCRIPTION:
Upper Denton 93 75.0
END DESCRIPTION:
XS GIS Cut Line= 5
      2237253.38      7258172.16      2236736.06      7258238.13
      2236326.34      7258495.07      2236052.04      7258696.46
        2235511.      7259806.28
#Sta/Elev= 30
  3985.1 1100.09  4245.6 1088.23  4362.5 1077.97  4392.8  1079.8  4562.6 1067.65
    4572 1064.16  4577.9 1066.74  4593.3 1062.91  4766.5 1057.39  4869.1 1050.01
  4912.6 1037.53  5056.4 1040.49  5077.3  1046.2  5127.4 1049.01  5135.8 1047.38
  5148.3  1035.3  5175.6 1034.18  5175.9 1033.68  5179.6 1034.18  5185.4 1034.44
  5192.3 1041.15  5198.5 1040.38  5206.9 1047.59  5271.7 1047.34  5284.7 1051.46
  5372.5 1059.04  6054.2 1080.34  6127.3 1079.14  6397.8  1096.2  6565.2 1100.91
#Mann= 3 ,-1 , 0
  3985.1     .05       0  5175.6    .033       0  5179.6     .05       0
Bank Sta=5175.6,5179.6
XS Rating Curve= 0 ,0
Exp/Cntr=0.3,0.1

Type RM Length L Ch R = 1 ,35817   ,415,415,415
BEGIN DESCRIPTION:
Upper Denton 93 74.0
END DESCRIPTION:
XS GIS Cut Line= 5
      2238170.09      7257746.23      2236584.42      7258058.27
      2236138.84       7258179.1      2235534.68      7258446.46
       2234656.2      7259383.96
#Sta/Elev= 30
  2929.5 1111.41  3073.3 1103.74    3216 1089.56  3347.2 1096.78  3501.4 1101.02
  3786.7 1081.64  3807.9 1084.97    3962 1088.31  4133.5 1083.22  4184.2 1079.02
  4207.1 1080.71  4429.5  1068.6  4449.2  1063.8  4520.5 1058.18  4545.6 1060.43
    4603 1053.51  4706.6  1051.8  4797.6 1043.09  4802.8 1045.56  4820.6 1037.09
    4831 1036.51  4872.1 1039.64  5278.5 1034.62  5278.7 1034.12  5282.5 1034.62
    5357  1043.8  5463.8 1049.54  5780.7 1078.79  6084.6 1086.06  6952.7 1095.66
#Mann= 6 ,-1 , 0
  2929.5     .12       0  3347.2     .05       0  4133.5     .12       0
  4207.1     .05       0  5278.5    .033       0  5282.5     .05       0
Bank Sta=5278.5,5282.5
XS Rating Curve= 0 ,0
Exp/Cntr=0.3,0.1

Type RM Length L Ch R = 1 ,35402   ,101,101,101
BEGIN DESCRIPTION:
Upper Denton 93 73.0
END DESCRIPTION:
XS GIS Cut Line= 3
      2238000.83      7256222.78      2236086.76      7257786.74
      2234273.24       7259147.6
#Sta/Elev= 30
  2542.1 1100.66  2704.8 1106.88  2789.8 1107.15  3134.2 1094.73  3602.1 1070.36
  3664.9 1068.57  3926.6 1062.59  3948.9 1064.31  3984.1 1061.12  4024.8 1063.42
  4254.3 1063.78  4339.5 1064.49  4375.3 1053.64    4460 1052.12  4481.5 1057.09
  4503.1 1057.68  4744.3 1040.05  4822.6 1040.53  4886.5 1035.85  4976.7 1035.09
  4977.2 1034.59  4981.4 1035.09  5478.7 1042.45  5786.2 1067.96  5914.1 1074.01
  6786.4 1073.83  7028.6 1087.29  7236.5 1093.63    7264 1090.31  7281.2  1091.3
#Mann= 8 ,-1 , 0
  2542.1     .12       0  3134.2     .05       0  3602.1     .12       0
  3664.9     .05       0  4024.8     .12       0  4254.3     .05       0
  4976.7    .033       0  4981.4     .05       0
Bank Sta=4976.7,4981.4
XS Rating Curve= 0 ,0
Exp/Cntr=0.3,0.1

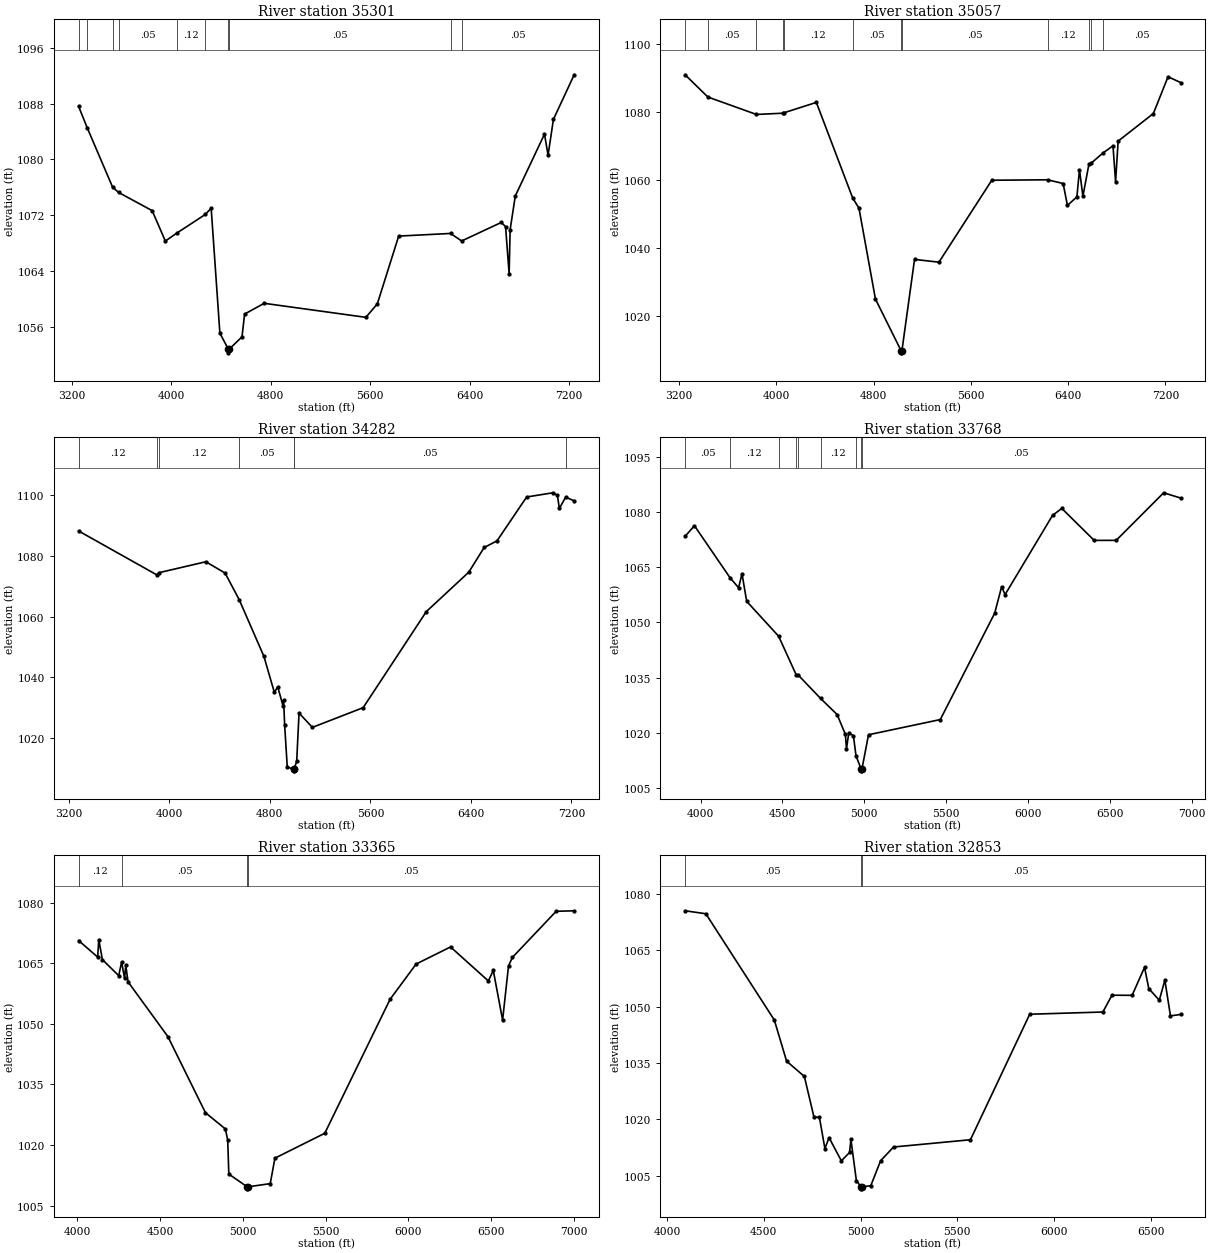
Type RM Length L Ch R = 1 ,35301   ,244,244,244
BEGIN DESCRIPTION:
Upper Denton 93 72.5
END DESCRIPTION:
XS GIS Cut Line= 5
      2237362.79      7256578.71      2236407.94      7257438.07
      2236056.38      7257685.47      2235479.12      7258102.13
      2234269.61      7259086.22
#Sta/Elev= 30
  3254.7  1087.6  3325.1 1084.48  3527.7 1076.04  3575.7 1075.27  3846.1 1072.66
  3952.2  1068.3  4045.3 1069.45  4274.3 1072.12  4320.7 1073.01  4390.9 1055.08
  4459.6 1052.77  4460.1 1052.27  4464.3 1052.77  4568.7 1054.56  4589.6 1057.83
  4747.3 1059.37  5565.3 1057.36  5657.3  1059.3  5828.9 1069.01  6246.2 1069.39
  6335.3 1068.31  6653.4 1070.96  6688.6 1070.38  6717.3  1063.6  6725.3 1069.91
  6766.9 1074.77  7001.7 1083.63  7030.5 1080.61  7073.6 1085.75  7240.4 1092.14
#Mann= 10 ,-1 , 0
  3254.7     .12       0  3325.1     .05       0  3527.7     .12       0
  3575.7     .05       0  4045.3     .12       0  4274.3     .05       0
  4459.6    .033       0  4464.3     .05       0  6246.2     .12       0
  6335.3     .05       0
Bank Sta=4459.6,4464.3
XS Rating Curve= 0 ,0
Exp/Cntr=0.3,0.1

Type RM Length L Ch R = 1 ,35057   ,775,775,775
BEGIN DESCRIPTION:
Upper Denton 93 72.0
END DESCRIPTION:
XS GIS Cut Line= 4
      2237341.08      7256461.52      2235943.53      7257498.83
       2235422.7      7257880.78      2234243.05      7259090.79
#Sta/Elev= 30
  3249.5 1090.86  3437.2 1084.32  3836.3  1079.2  4055.4 1079.57  4061.7 1079.68
  4329.2 1082.74  4628.2 1054.64  4679.8 1051.66  4815.4 1024.94    5028 1009.65
  5028.5 1009.15  5032.7 1009.65  5136.9 1036.61  5337.6 1035.79  5772.3 1059.87
  6231.1    1060  6359.3 1058.91  6394.5 1052.46  6472.4    1055  6493.6 1062.95
  6521.8 1055.16    6571 1064.53    6590 1064.89  6687.1 1067.89  6769.3 1069.98
  6790.6 1059.43  6811.7 1071.37  7101.6 1079.48    7222 1090.28  7325.7 1088.58
#Mann= 12 ,-1 , 0
  3249.5     .12       0  3437.2     .05       0  3836.3     .12       0
  4055.4     .05       0  4061.7     .12       0  4628.2     .05       0
    5028    .033       0  5032.7     .05       0  6231.1     .12       0
    6571     .05       0    6590     .12       0  6687.1     .05       0
Bank Sta=5028,5032.7
XS Rating Curve= 0 ,0
Exp/Cntr=0.3,0.1

Type RM Length L Ch R = 1 ,34282   ,514,514,514
BEGIN DESCRIPTION:
Upper Denton 93 70.0
END DESCRIPTION:
XS GIS Cut Line= 4
      2237249.91       7256470.2      2235565.93       7256891.2
      2234832.42       7257537.9        2234138.      7258553.49
#Sta/Elev= 30
    3278 1088.24  3899.4  1073.8  3920.6 1074.53  4290.8  1078.1  4443.7 1074.37
  4555.6 1065.64  4752.9 1046.91  4835.4 1035.12  4862.9 1036.87  4904.1 1030.73
  4909.3 1032.61  4917.9 1024.17  4938.5 1010.52  4989.2 1009.73  4989.9 1009.23
  4994.2 1009.73  5013.8 1012.56  5032.2 1028.27  5138.4 1023.54  5542.6 1030.04
  6045.4 1061.69  6383.3 1074.68  6505.9  1082.8  6607.5 1084.97  6843.8 1099.43
  7053.1 1100.82    7089 1099.95  7103.9 1095.66  7154.1 1099.36    7222 1098.17
#Mann= 7 ,-1 , 0
    3278     .12       0  3899.4     .05       0  3920.6     .12       0
  4555.6     .05       0  4989.2    .033       0  4994.2     .05       0
  7154.1     .12       0
Bank Sta=4989.2,4994.2
XS Rating Curve= 0 ,0
Exp/Cntr=0.3,0.1

Type RM Length L Ch R = 1 ,33768   ,403,403,403
BEGIN DESCRIPTION:
Upper Denton 93 69.0
END DESCRIPTION:
XS GIS Cut Line= 3
      2236159.67      7255739.72        2235329.        7256460.
      2233986.09      7257843.86
#Sta/Elev= 30
    3905 1073.37  3962.2 1076.25  4179.2 1062.16  4231.9 1059.43  4252.8 1063.22
  4281.3 1055.74  4476.4 1046.27  4585.3 1035.66    4597 1035.69  4732.9 1029.38
    4834 1025.01  4884.4 1019.63    4891 1015.68  4905.2 1020.06  4933.7 1019.24
  4949.2 1013.84  4980.5 1010.24  4981.2 1009.74  4985.6 1010.24  5025.7 1019.53
  5464.2 1023.65  5796.6  1052.5    5839  1059.7  5860.1 1057.56    6150 1079.04
  6206.6 1080.95  6404.7 1072.27    6539 1072.28  6829.1 1085.19  6932.8 1083.76
#Mann= 9 ,-1 , 0
    3905     .05       0  4179.2     .12       0  4476.4     .05       0
  4585.3     .12       0    4597     .05       0  4732.9     .12       0
  4949.2     .05       0  4980.5    .033       0  4985.6     .05       0
Bank Sta=4980.5,4985.6
XS Rating Curve= 0 ,0
Exp/Cntr=0.3,0.1

Type RM Length L Ch R = 1 ,33365   ,512,512,512
BEGIN DESCRIPTION:
Upper Denton 93 68.0
END DESCRIPTION:
XS GIS Cut Line= 3
      2235847.16      7255475.85      2235111.06       7256142.5
      2233951.32      7257774.48
#Sta/Elev= 30
  4007.8 1070.61  4122.9 1066.52  4129.6 1070.84  4151.2 1065.91  4249.9 1061.92
  4267.6 1065.28  4285.7 1061.22  4292.5 1064.48  4306.7 1060.38  4547.3 1046.84
  4774.3 1028.01  4894.7 1023.98  4908.9 1021.21  4915.6 1012.81  5026.9 1009.66
  5027.5 1009.16    5032 1009.66    5166 1010.45  5194.1 1016.75  5495.6 1022.91
  5890.4 1056.08  6047.8  1064.8  6255.7 1069.03  6484.4 1060.61    6514 1063.23
  6570.5 1050.93  6606.2 1064.35  6629.5 1066.43    6894 1077.85    7003 1077.98
#Mann= 4 ,-1 , 0
  4007.8     .12       0  4267.6     .05       0  5026.9    .033       0
    5032     .05       0
Bank Sta=5026.9,5032
XS Rating Curve= 0 ,0
Exp/Cntr=0.3,0.1

Type RM Length L Ch R = 1 ,32853   ,454,454,454
BEGIN DESCRIPTION:
Upper Denton 93 67.0
END DESCRIPTION:
XS GIS Cut Line= 4
      2235499.97      7255239.71      2234826.34      7255857.78
       2234481.9      7256550.83      2234131.88      7257350.88
#Sta/Elev= 30
  4093.1 1075.48  4200.3 1074.69  4554.3 1046.42  4617.8 1035.47  4709.6 1031.41
  4759.4 1020.56  4787.3 1020.57  4815.7 1012.23  4837.3 1015.11  4900.8 1008.97
  4943.3 1011.18  4950.1 1014.69  4978.5  1003.7  5002.7 1002.01  5003.4 1001.51
  5007.9 1002.01  5053.2 1002.37  5103.6 1008.98  5170.8 1012.64  5568.1 1014.57
  5874.5 1047.96  6252.6 1048.55  6299.4 1053.02  6403.8 1052.99    6468 1060.44
  6489.8 1054.79  6544.2 1051.69    6573 1057.02  6601.9 1047.52  6654.5  1047.9
#Mann= 3 ,-1 , 0
  4093.1     .05       0  5002.7    .033       0  5007.9     .05       0
Bank Sta=5002.7,5007.9
XS Rating Curve= 0 ,0
Exp/Cntr=0.3,0.1

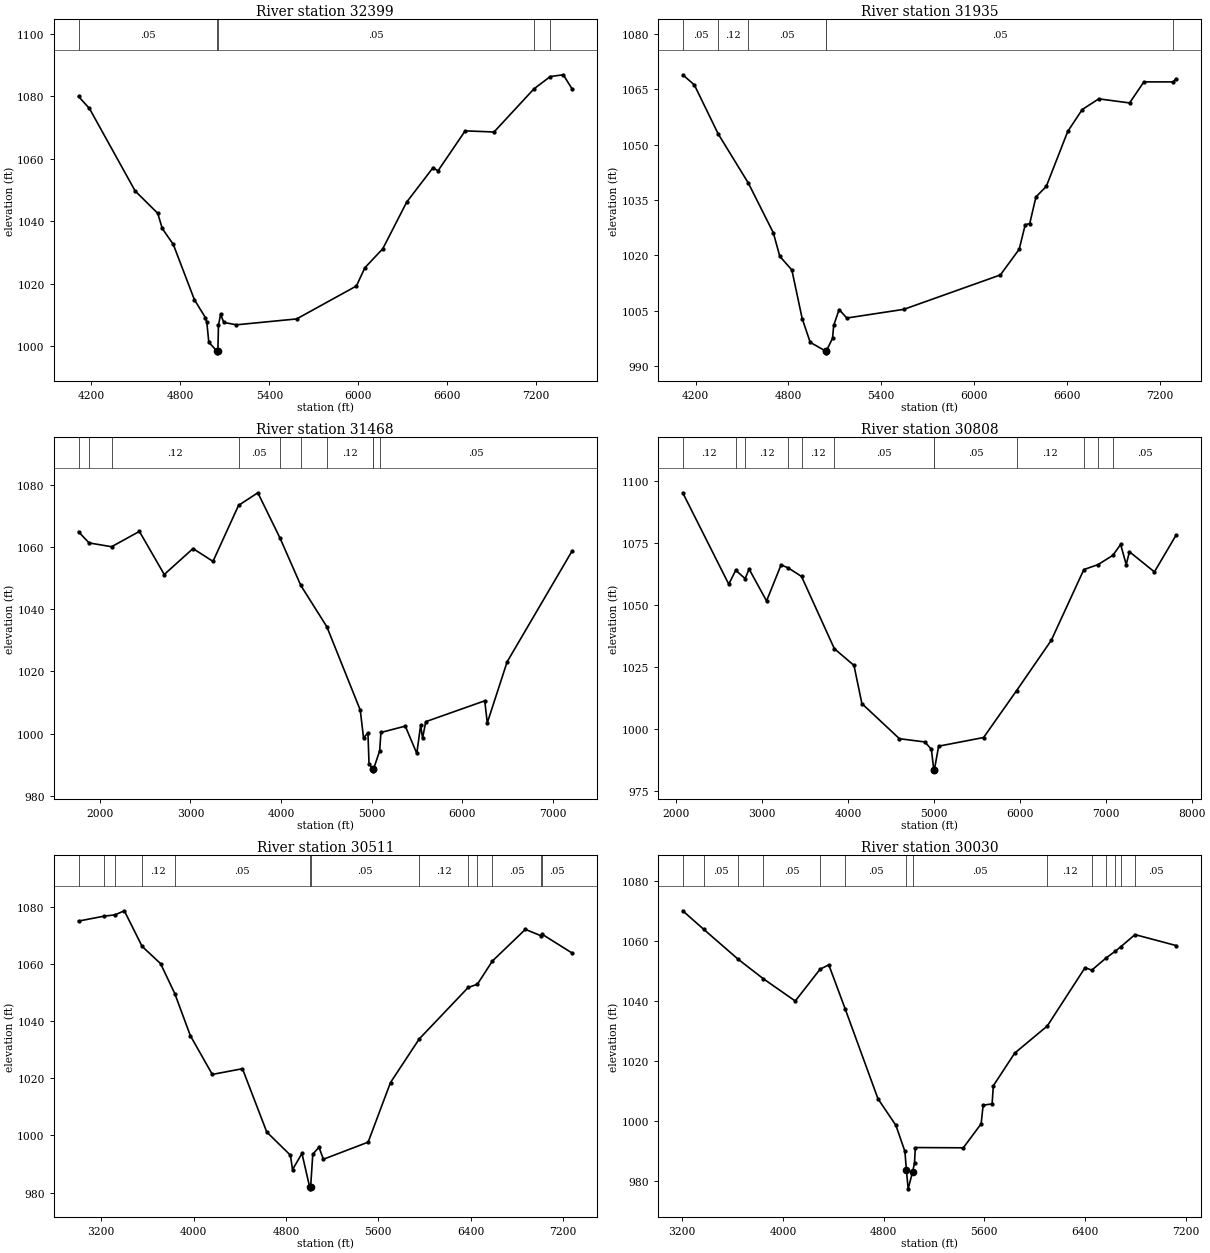
Type RM Length L Ch R = 1 ,32399   ,464,464,464
BEGIN DESCRIPTION:
Upper Denton 93 66.0
END DESCRIPTION:
XS GIS Cut Line= 4
      2235383.62      7255135.56        2234579.        7255510.
      2234333.29      7255795.28      2233395.92      7257635.29
#Sta/Elev= 30
  4112.8    1080  4186.1 1076.18  4494.6 1049.77  4647.3 1042.59  4677.6 1037.75
  4751.8 1032.67  4894.6 1014.94  4968.7 1009.22  4978.2 1007.72  4991.6 1001.34
  5047.6  998.45  5048.3  997.95  5052.8  998.45  5056.8 1006.73    5071 1010.32
  5092.7 1007.69  5177.5 1006.92  5584.1  1008.8  5987.3 1019.34  6044.2 1025.17
  6165.2 1031.26  6326.5 1046.19  6504.4 1057.22  6537.6 1056.18  6721.1 1068.99
  6915.7 1068.63  7184.3  1082.4    7295 1086.37  7382.7 1086.94  7441.8 1082.46
#Mann= 5 ,-1 , 0
  4112.8     .05       0  5047.6    .033       0  5052.8     .05       0
  7184.3     .12       0    7295     .05       0
Bank Sta=5047.6,5052.8
XS Rating Curve= 0 ,0
Exp/Cntr=0.3,0.1

Type RM Length L Ch R = 1 ,31935   ,467,467,467
BEGIN DESCRIPTION:
Upper Denton 93 65.0
END DESCRIPTION:
XS GIS Cut Line= 5
      2235183.93      7255057.43      2234576.34      7255040.07
        2234329.        7255160.      2234043.36      7255486.25
      2233335.02       7257218.9
#Sta/Elev= 30
  4117.3 1068.95  4192.3 1066.21  4346.5 1052.89  4540.7  1039.6  4702.5 1026.09
  4744.4  1019.7  4822.2    1016  4888.9 1002.82  4940.8  996.37  5039.7  994.02
  5040.4  993.52  5044.9  994.02    5085  997.46  5092.6 1000.98  5127.7 1005.27
    5177 1002.96  5545.7 1005.32  6169.4 1014.65  6291.2 1021.64  6329.7 1028.25
  6359.1  1028.6  6399.2 1035.81    6466 1038.67  6604.5 1053.57  6698.3 1059.53
  6805.2 1062.42  7004.2 1061.31  7096.4 1067.02  7285.7 1067.02  7305.5 1067.89
#Mann= 6 ,-1 , 0
  4117.3     .05       0  4346.5     .12       0  4540.7     .05       0
  5039.7    .033       0  5044.9     .05       0  7285.7     .12       0
Bank Sta=5039.7,5044.9
XS Rating Curve= 0 ,0
Exp/Cntr=0.3,0.1

Type RM Length L Ch R = 1 ,31468   ,660,660,660
BEGIN DESCRIPTION:
Upper Denton 93 64.0
END DESCRIPTION:
XS GIS Cut Line= 4
      2237137.12      7255795.28      2234341.97      7254675.48
        2234129.        7254760.      2232519.02      7256272.73
#Sta/Elev= 30
  1763.8 1064.83  1880.4 1061.25  2128.8 1060.03  2435.9 1064.94  2710.4 1051.11
    3028 1059.44  3248.6 1055.32    3531 1073.31  3743.9 1077.35  3989.3 1062.77
  4218.7 1047.58    4506 1034.33  4874.9 1007.57  4910.9  998.63  4959.5 1000.29
  4971.8  990.35  5015.3  988.57    5016  988.07  5020.7  988.57  5089.4  994.51
    5103 1000.39  5372.1 1002.43  5499.1  993.67  5541.6 1002.71    5563  998.56
  5598.2 1003.86  6249.3 1010.55  6277.6 1003.48  6496.9 1023.08  7213.2 1058.63
#Mann= 10 ,-1 , 0
  1763.8     .12       0  1880.4     .05       0  2128.8     .12       0
    3531     .05       0  3989.3     .12       0  4218.7     .05       0
    4506     .12       0  5015.3     .07       0  5020.7     .12       0
  5089.4     .05       0
Bank Sta=5015.3,5020.7
XS Rating Curve= 0 ,0
Exp/Cntr=0.3,0.1

Type RM Length L Ch R = 1 ,30808   ,297,297,297
BEGIN DESCRIPTION:
Upper Denton 93 63.0
END DESCRIPTION:
XS GIS Cut Line= 3
      2236659.67      7253043.54       2233968.7      7254224.09
      2231286.41      7255057.43
#Sta/Elev= 30
  2073.1 1095.31  2608.9 1058.45  2690.2 1064.04  2799.7 1060.69    2846 1064.53
  3049.3 1051.67  3218.3 1066.23  3302.6 1064.99  3456.6 1061.55  3838.7 1032.42
  4067.4 1025.67  4159.6 1010.27  4596.4  996.11    4893  994.79  4968.6  991.83
  4996.7  983.64  4997.8  983.14  5004.1  983.64  5053.4  993.09  5576.8  996.58
  5960.3 1015.45  6365.1 1035.79  6744.5 1064.33  6912.2 1066.37  7083.5 1070.11
  7172.8 1074.46  7237.9 1066.37  7275.7 1071.52  7566.4 1063.39  7820.4 1078.33
#Mann= 12 ,-1 , 0
  2073.1     .12       0  2690.2     .05       0  2799.7     .12       0
  3302.6     .05       0  3456.6     .12       0  3838.7     .05       0
  4996.7    .033       0  5004.1     .05       0  5960.3     .12       0
  6744.5     .05       0  6912.2     .12       0  7083.5     .05       0
Bank Sta=4996.7,5004.1
XS Rating Curve= 0 ,0
Exp/Cntr=0.3,0.1

Type RM Length L Ch R = 1 ,30511   ,481,481,481
BEGIN DESCRIPTION:
Upper Denton 93 62.0
END DESCRIPTION:
XS GIS Cut Line= 3
      2235713.47      7253173.76        2233879.        7253960.
      2231755.14      7254779.66
#Sta/Elev= 30
  3004.5 1075.01  3224.9 1076.72  3320.3 1077.18    3401 1078.61  3554.7 1066.16
  3714.8 1060.12  3837.6 1049.66  3972.2 1034.95  4162.6 1021.35  4423.7 1023.35
  4634.1  1001.2    4839  993.08  4857.1  988.05  4938.7   993.7  5006.3  981.82
  5007.4  981.32  5013.7  981.82  5032.5  993.43  5086.1  995.88  5124.5  991.67
  5511.8  997.66  5705.5 1018.52  5954.2 1033.77  6378.2 1051.78  6457.6 1052.91
  6587.3 1061.01    6873 1072.11  7011.4 1069.81  7020.9 1070.33  7276.9 1063.84
#Mann= 13 ,-1 , 0
  3004.5     .05       0  3224.9     .12       0  3320.3     .05       0
  3554.7     .12       0  3837.6     .05       0  5006.3    .033       0
  5013.7     .05       0  5954.2     .12       0  6378.2     .05       0
  6457.6     .12       0  6587.3     .05       0  7011.4     .12       0
  7020.9     .05       0
Bank Sta=5006.3,5013.7
XS Rating Curve= 0 ,0
Exp/Cntr=0.3,0.1

Type RM Length L Ch R = 1 ,30030   ,542,542,542
BEGIN DESCRIPTION:
Upper Denton 93 61.0
END DESCRIPTION:
XS GIS Cut Line= 3
      2235531.16      7253112.99        2233779.        7253510.
      2231912.69      7254527.22
#Sta/Elev= 30
  3203.5 1070.07  3369.7 1063.91  3645.7 1053.86  3844.7 1047.41  4097.8 1040.01
  4295.4 1050.62  4364.4 1052.06  4495.2 1037.31  4755.2 1007.45  4897.5  998.61
  4969.3  989.91  4981.1  983.68  4994.9  977.45    5030  983.06  5045.6  986.08
  5051.8   991.2  5433.5  991.12    5575  999.11  5591.1 1005.33  5662.3 1005.74
    5672 1011.79  5841.8 1022.65  6100.9  1031.7  6400.9 1051.12  6454.4  1050.3
  6568.9 1054.37    6642 1056.62  6683.4 1058.03  6797.9 1062.13  7125.6 1058.48
#Mann= 14 ,-1 , 0
  3203.5     .12       0  3369.7     .05       0  3645.7     .12       0
  3844.7     .05       0  4295.4     .12       0  4495.2     .05       0
  4981.1    .033       0    5030     .05       0  6100.9     .12       0
  6454.4     .05       0  6568.9     .12       0    6642     .05       0
  6683.4     .12       0  6797.9     .05       0
Bank Sta=4981.1,5030
XS Rating Curve= 0 ,0
Exp/Cntr=0.3,0.1

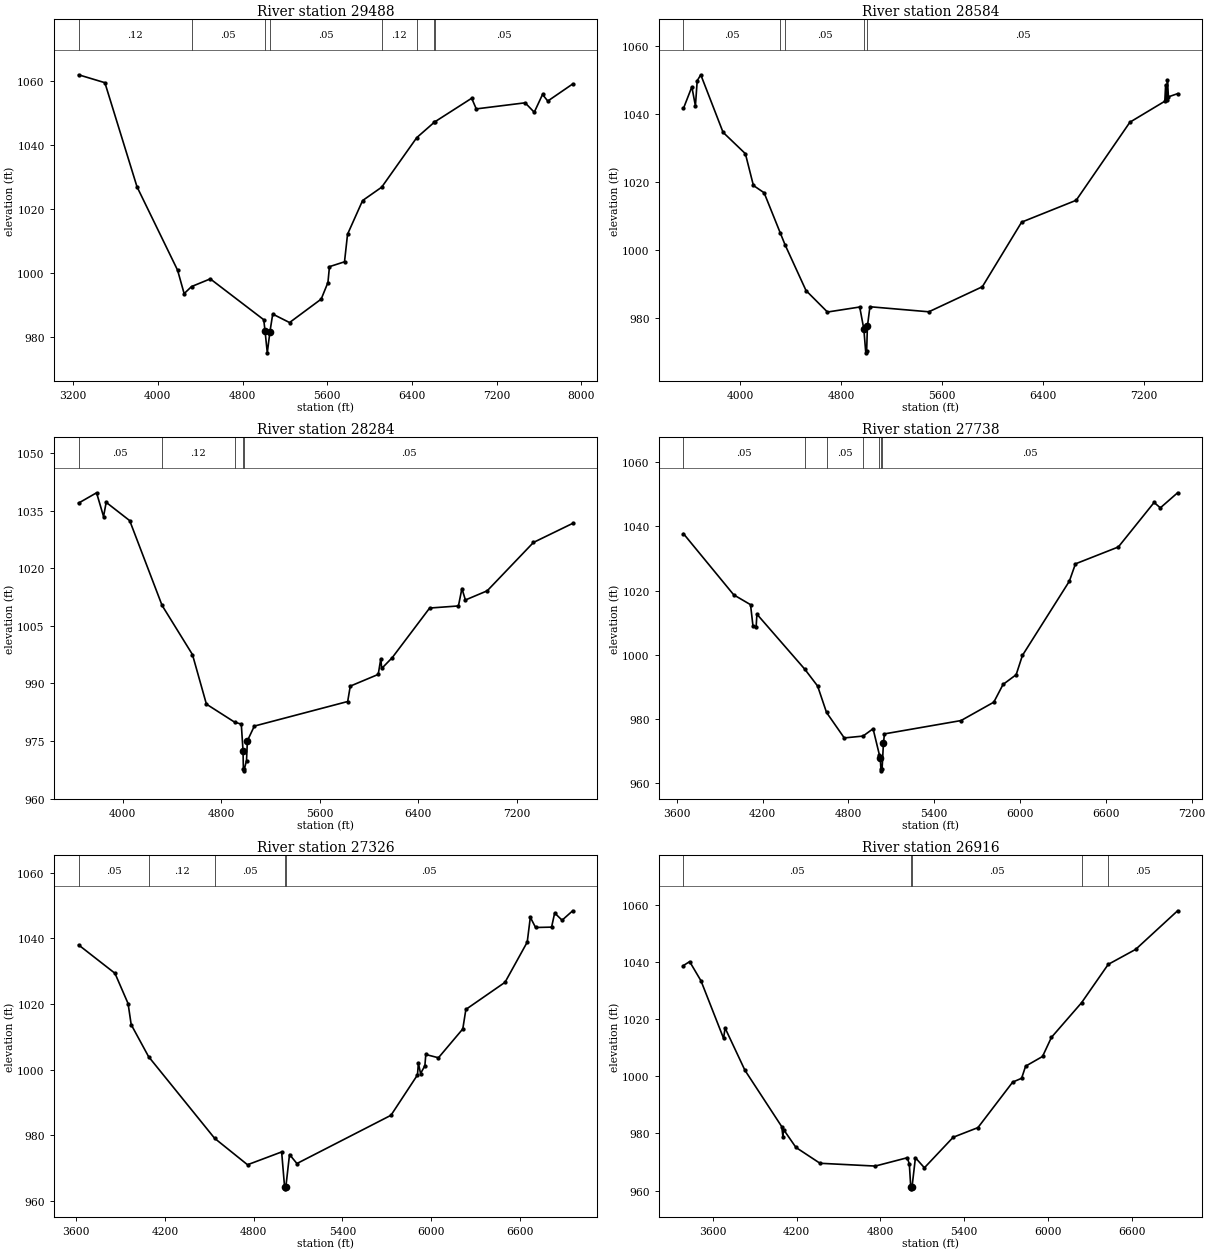
Type RM Length L Ch R = 1 ,29488   ,904,904,904
BEGIN DESCRIPTION:
Upper Denton 93 60.0
END DESCRIPTION:
XS GIS Cut Line= 4
      2235253.43      7252262.29      2233699.61      7252982.78
      2233508.63       7253104.3      2231399.29      7254831.71
#Sta/Elev= 30
  3251.5 1062.04    3500 1059.56  3803.4 1026.94  4186.4 1000.83  4248.4  993.48
  4318.1  995.69  4495.3   998.1  5000.1   985.3  5012.4  981.72  5033.5  974.93
  5057.7  981.37  5084.8  987.07  5243.7  984.42  5542.3  991.76  5606.1  996.96
  5620.5 1001.93  5762.6 1003.45  5791.3 1012.09  5933.4 1022.64  6113.7 1026.83
    6445 1042.36  6611.1 1047.19  6613.1 1047.25  6963.4 1054.69  7006.5 1051.35
    7468 1053.26  7554.1  1050.3  7632.3 1055.87  7681.9 1053.81    7917 1059.16
#Mann= 8 ,-1 , 0
  3251.5     .12       0  4318.1     .05       0  5012.4    .033       0
  5057.7     .05       0  6113.7     .12       0    6445     .05       0
  6611.1     .12       0  6613.1     .05       0
Bank Sta=5012.4,5057.7
XS Rating Curve= 0 ,0
Exp/Cntr=0.3,0.1

Type RM Length L Ch R = 1 ,28584   ,300,300,300
BEGIN DESCRIPTION:
Upper Denton 93 59.0
END DESCRIPTION:
XS GIS Cut Line= 6
      2234907.96      7251254.97      2233953.08       7252238.5
      2233885.37      7252259.34       2233843.7      7252261.94
      2233078.08      7253027.57       2232199.6      7254053.61
#Sta/Elev= 30
    3552 1041.61  3618.4 1047.93  3646.7 1042.34  3660.9 1049.73  3689.2 1051.47
  3865.9 1034.59  4042.8 1028.32  4106.4    1019  4191.3 1016.86    4319 1005.11
  4356.5 1001.67  4523.6  988.17  4693.4  981.88  4949.1  983.35  4981.8  976.87
  4997.2  969.91  5004.1  970.41  5010.1  977.68  5030.1  983.43    5497  981.95
  5921.2   989.3  6232.7 1008.25  6665.1 1014.66    7091 1037.56  7367.6 1043.71
  7374.2 1048.57  7381.9    1044  7388.5 1049.91  7396.2    1045  7468.9 1045.93
#Mann= 5 ,-1 , 0
    3552     .05       0    4319     .12       0  4356.5     .05       0
  4981.8    .033       0  5010.1     .05       0
#XS Ineff= 2 , 0
                         5031.99          983.33
Permanent Ineff=
       F       F
Bank Sta=4981.8,5010.1
XS Rating Curve= 0 ,0
Exp/Cntr=0.3,0.1

Type RM Length L Ch R = 1 ,28284   ,546,546,546
BEGIN DESCRIPTION:
Upper Denton 93 58.0
END DESCRIPTION:
XS GIS Cut Line= 3
      2234824.57      7251018.92      2233866.27        7252005.
      2232067.67       7253928.6
#Sta/Elev= 30
  3643.4 1036.98  3789.5 1039.67  3846.1 1033.48  3867.4 1037.18  4058.3 1032.41
  4320.8 1010.33  4567.4  997.52  4680.5  984.61  4909.1  979.92  4963.5  979.39
  4977.6   972.5  4980.5  967.73  4981.7  967.23  4988.7  967.73  5005.9  969.91
  5012.9  975.06  5069.4  978.89  5826.6  985.29  5847.6   989.3  6074.3  992.35
  6095.3  996.45  6102.6   993.9  6187.6   996.7  6491.5 1009.64    6725 1010.19
  6753.3 1014.72  6781.6 1011.74  6958.5 1014.13  7333.6 1026.73  7651.9  1031.7
#Mann= 5 ,-1 , 0
  3643.4     .05       0  4320.8     .12       0  4909.1     .05       0
  4980.5    .033       0  4988.7     .05       0
Bank Sta=4977.6,5012.9
XS Rating Curve= 0 ,0
Exp/Cntr=0.3,0.1

Type RM Length L Ch R = 1 ,27738   ,412,412,412
BEGIN DESCRIPTION:
Upper Denton 93 57.0
END DESCRIPTION:
XS GIS Cut Line= 3
      2234783.68       7250954.8        2233579.        7251560.
       2231893.5      7252824.25
#Sta/Elev= 30
  3646.3 1037.75    3998 1018.69  4115.2 1015.64    4132 1009.12  4154.3 1008.66
  4159.9 1012.68  4494.7  995.53  4584.2   990.3  4646.6  982.07  4770.6  974.13
    4902  974.71  4972.1  976.99  5016.9  968.74  5022.6  967.85  5026.8  964.38
    5028  963.88    5035  964.38  5044.5  972.42  5051.7  975.39  5587.1  979.54
  5816.3  985.27  5880.9  990.79  5972.6  993.82  6016.3  999.82  6344.5 1022.95
  6387.1 1028.35  6687.1 1033.61  6937.1 1047.47  6980.9  1045.8  7101.4 1050.49
#Mann= 7 ,-1 , 0
  3646.3     .05       0  4494.7     .12       0  4646.6     .05       0
    4902     .12       0  5016.9     .05       0  5026.8     .07       0
    5035     .05       0
Bank Sta=5022.6,5044.5
XS Rating Curve= 0 ,0
Exp/Cntr=0.3,0.1

Type RM Length L Ch R = 1 ,27326   ,410,410,410
BEGIN DESCRIPTION:
Upper Denton 93 56.0
END DESCRIPTION:
XS GIS Cut Line= 3
      2234648.25      7250840.23        2233329.        7251260.
      2231757.62      7252428.76
#Sta/Elev= 30
  3615.6 1038.03  3861.8 1029.37  3950.6 1020.13  3971.6 1013.71  4089.5 1003.92
  4536.2  979.01  4758.7  970.95  4989.5  974.86  5009.5   964.1  5010.7   963.6
  5017.7   964.1  5042.8  974.07  5092.8  971.32    5729  986.04  5908.4  998.35
  5914.6 1001.96  5929.2  998.78  5958.5 1001.15  5964.7 1004.59  6050.2 1003.59
    6215 1012.39  6235.8 1018.34  6500.7 1026.62  6650.9 1038.88  6671.8 1046.45
  6707.4 1043.34  6815.7 1043.45  6836.5 1047.77  6886.6 1045.56  6958.4 1048.44
#Mann= 5 ,-1 , 0
  3615.6     .05       0  4089.5     .12       0  4536.2     .05       0
  5009.5     .04       0  5017.7     .05       0
Bank Sta=5009.5,5017.7
XS Rating Curve= 0 ,0
Exp/Cntr=0.3,0.1

Type RM Length L Ch R = 1 ,26916   ,490,490,490
BEGIN DESCRIPTION:
Upper Denton 93 55.0
END DESCRIPTION:
XS GIS Cut Line= 4
      2234632.57       7250626.7      2233174.26      7250871.49
      2232913.84      7251074.62      2231585.75      7252178.75
#Sta/Elev= 30
  3390.6 1038.79  3434.8 1040.16  3515.9 1033.44  3677.7 1013.28  3688.3 1016.94
  3830.2 1002.14  4093.9  982.39  4102.1  978.94  4107.1  981.37  4195.3  975.12
  4367.6  969.57  4763.1  968.59  4992.6  971.51  5007.1  969.24  5017.2  961.12
  5018.5  960.62  5025.9  961.12  5050.5  971.51  5114.8  967.99  5320.9  978.68
  5497.9  982.05  5746.6  997.98  5810.4  999.32  5839.1 1003.56  5960.1 1006.95
  6023.9 1013.64  6239.2 1025.75  6430.3 1039.19  6626.7 1044.44  6926.7 1057.95
#Mann= 5 ,-1 , 0
  3390.6     .05       0  5017.2    .033       0  5025.9     .05       0
  6239.2     .12       0  6430.3     .05       0
Bank Sta=5017.2,5025.9
XS Rating Curve= 0 ,0
Exp/Cntr=0.3,0.1