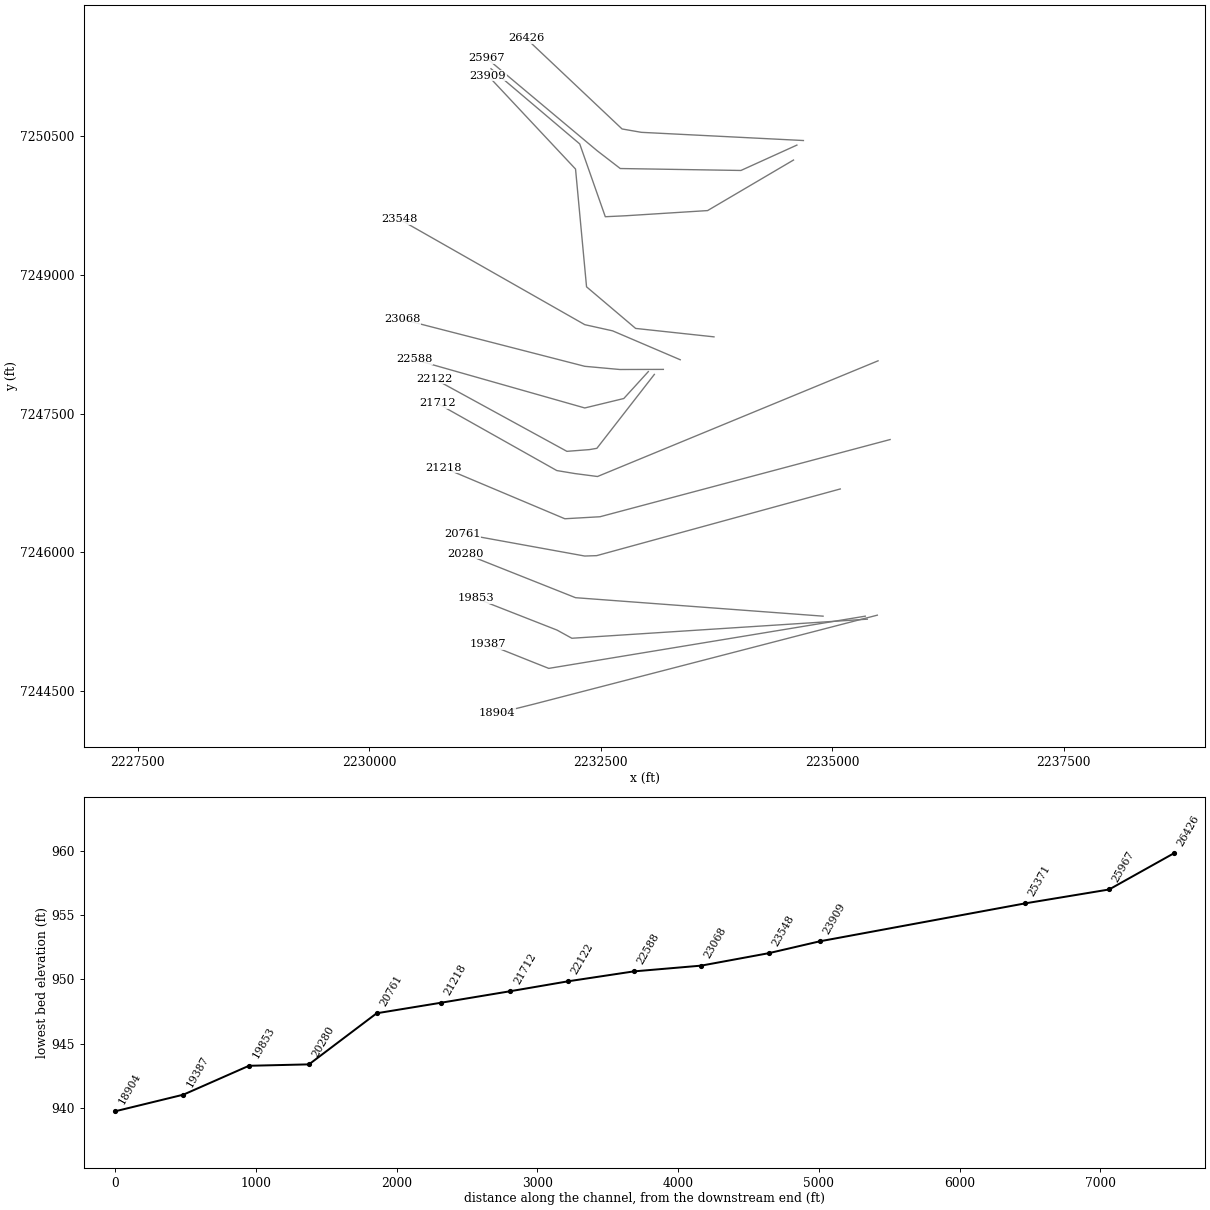
HEC-RAS study Upper Denton 93.prj: Upper Denton 93 Base Level Engineering

--- Upper Denton 93.g01 (geometry) --- (continued)

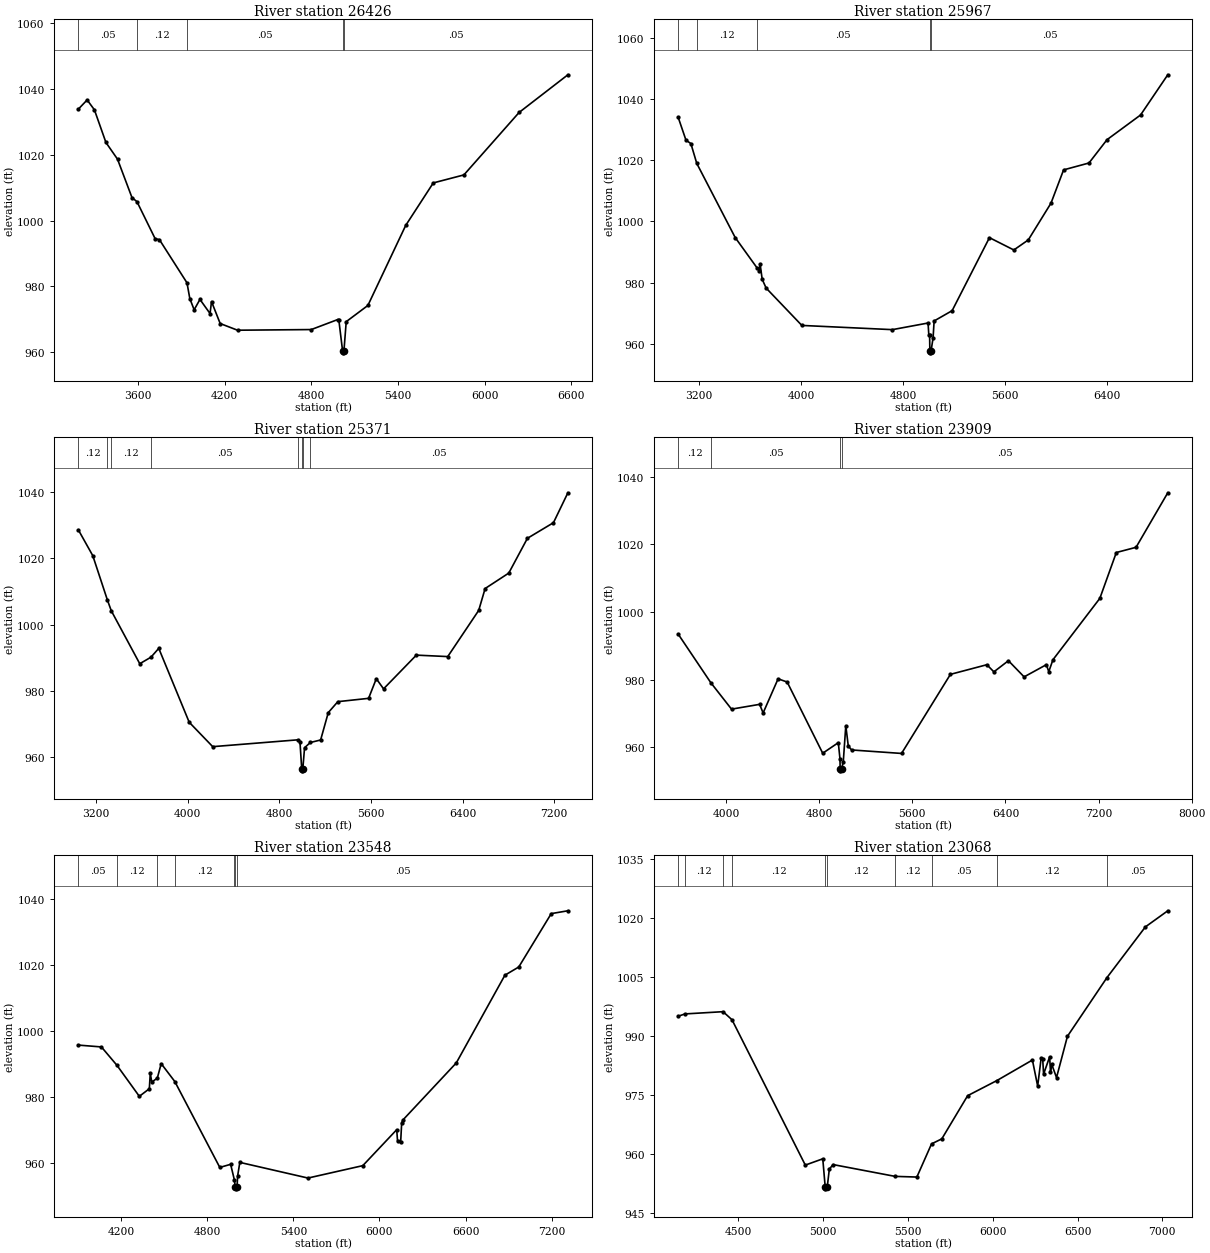
Type RM Length L Ch R = 1 ,26426   ,459,459,459
BEGIN DESCRIPTION:
Upper Denton 93 54.0
END DESCRIPTION:
XS GIS Cut Line= 4
      2234689.88      7250449.62      2232939.88      7250538.16
      2232731.55      7250574.62      2231695.07       7251553.8
#Sta/Elev= 30
  3186.4 1033.82  3247.4 1036.62  3297.7 1033.62  3377.5  1023.7  3457.6 1018.64
  3557.8 1006.97  3592.3 1005.73    3718   994.5    3748  994.18  3938.7  981.08
  3958.3   976.3  3988.3  972.89  4028.4  976.04  4098.4  971.75  4108.5  975.39
  4168.5  968.72  4288.7  966.69  4799.3  966.89  4981.8  969.92  4990.3  969.68
  5016.3  960.32  5017.6  959.82  5025.2  960.32  5041.2  969.29  5191.2  974.21
    5453  998.51  5643.9 1011.42  5855.9 1013.85  6238.2 1032.82    6576 1044.26
#Mann= 5 ,-1 , 0
  3186.4     .05       0  3592.3     .12       0  3938.7     .05       0
  5016.3    .033       0  5025.2     .05       0
Bank Sta=5016.3,5025.2
XS Rating Curve= 0 ,0
Exp/Cntr=0.3,0.1

Type RM Length L Ch R = 1 ,25967   ,596,596,596
BEGIN DESCRIPTION:
Upper Denton 93 53.0
END DESCRIPTION:
XS GIS Cut Line= 5
      2234619.38      7250400.24      2234015.23      7250126.13
      2232712.02       7250147.1      2232462.02      7250339.81
        2231268.      7251340.25
#Sta/Elev= 30
  3036.2 1034.04  3097.2 1026.58  3135.4  1025.5  3181.7    1019  3482.9  994.75
  3653.1  984.89  3673.1  983.88  3678.6  986.11  3694.8  981.08  3725.9   978.2
  4005.9  965.98    4716   964.6    4996  966.77    5002  962.78  5008.1  962.78
  5010.1  957.51  5011.4  957.01    5019  957.51  5035.4   961.9  5043.5  967.44
  5184.8  970.81  5477.5   994.7  5668.8  990.67    5782  993.95  5960.2 1005.98
  6059.1 1016.88  6258.2 1019.13    6400 1026.77  6662.8 1034.84  6876.4    1048
#Mann= 5 ,-1 , 0
  3036.2     .05       0  3181.7     .12       0  3653.1     .05       0
  5010.1    .033       0    5019     .05       0
Bank Sta=5010.1,5019
XS Rating Curve= 0 ,0
Exp/Cntr=0.3,0.1

Type RM Length L Ch R = 1 ,25371   ,1462,1462,1462
BEGIN DESCRIPTION:
Upper Denton 93 52.0
END DESCRIPTION:
XS GIS Cut Line= 6
      2234582.94      7250238.79      2233655.14      7249692.69
      2232769.31      7249636.68      2232550.56      7249626.26
      2232274.52      7250412.72      2231316.33      7251225.11
#Sta/Elev= 30
  3045.9 1028.59    3172 1020.81    3299  1007.5  3333.5 1004.19    3582  988.23
  3679.6  990.19  3747.9  992.86  4013.6  970.58  4218.8  963.22  4961.7  965.28
  4980.3  964.67  4995.9  956.43  4997.2  955.93  5004.9  956.43  5020.4  962.89
    5071  964.48  5160.6  965.23  5227.4  973.49  5310.9  976.79  5579.3  977.79
  5646.5  983.71    5710  980.65  5996.1  990.82  6270.1  990.38  6540.3  1004.3
  6596.3  1010.9  6802.9 1015.56  6965.4 1026.04  7192.8 1030.75  7318.8 1039.77
#Mann= 8 ,-1 , 0
  3045.9     .12       0    3299     .05       0  3333.5     .12       0
  3679.6     .05       0  4961.7     .12       0  4995.9     .07       0
  5004.9     .12       0    5071     .05       0
Bank Sta=4995.9,5004.9
XS Rating Curve= 0 ,0
Exp/Cntr=0.3,0.1

Type RM Length L Ch R = 1 ,23909   ,361,361,361
BEGIN DESCRIPTION:
Upper Denton 93 51.0
END DESCRIPTION:
XS GIS Cut Line= 5
      2233724.35      7248328.28      2232877.99      7248419.43
      2232348.03      7248868.81      2232229.15      7250141.41
      2231284.16      7251150.34
#Sta/Elev= 30
  3588.2  993.42  3868.8  979.03  4046.2  971.23  4287.6  972.65  4317.7   970.1
  4446.4  980.21  4524.4  979.25  4829.8  958.18  4963.7  961.31    4978  956.55
  4979.7  953.47  4981.4  952.97  4991.8  953.47  5006.6  955.72  5028.1  966.34
  5049.4  960.33    5078  959.15  5507.1  958.12  5927.1  981.53  6240.3  984.38
  6300.5  982.27  6425.5  985.57  6560.3  980.78  6751.3  984.39  6772.3  982.32
  6807.8  985.84    7211 1004.02  7352.6 1017.59  7522.1 1019.13  7794.8 1035.27
#Mann= 4 ,-1 , 0
  3588.2     .12       0  3868.8     .05       0  4979.7     .04       0
  4991.8     .05       0
Bank Sta=4979.7,4991.8
XS Rating Curve= 0 ,0
Exp/Cntr=0.3,0.1

Type RM Length L Ch R = 1 ,23548   ,480,480,480
BEGIN DESCRIPTION:
Upper Denton 93 49.0
END DESCRIPTION:
XS GIS Cut Line= 4
      2233359.77      7248080.88      2232629.36      7248393.25
        2232329.        7248460.      2230322.54      7249602.04
#Sta/Elev= 30
  3902.2  995.62    4063  995.06  4171.1   989.5  4327.2  980.09  4396.9  982.39
  4403.3  987.03  4414.2   984.4  4452.6  985.63  4479.5     990  4574.3  984.58
  4887.8  958.54  4963.3  959.48  4989.1   954.8  4995.7  952.55  4997.3  952.05
  5007.8  952.55  5012.2  955.99  5027.3  960.07  5502.2  955.32  5884.1  959.08
  6120.4  969.98  6126.2  966.52  6147.8  966.17  6154.9  971.99  6163.7  972.93
  6535.5  990.22  6874.2 1016.81  6970.7 1019.29    7197 1035.47    7313 1036.33
#Mann= 7 ,-1 , 0
  3902.2     .05       0  4171.1     .12       0  4452.6     .05       0
  4574.3     .12       0  4989.1     .05       0  4995.7     .04       0
  5007.8     .05       0
Bank Sta=4995.7,5007.8
XS Rating Curve= 0 ,0
Exp/Cntr=0.3,0.1

Type RM Length L Ch R = 1 ,23068   ,480,480,480
BEGIN DESCRIPTION:
Upper Denton 93 48.0
END DESCRIPTION:
XS GIS Cut Line= 4
      2233177.47      7247976.72      2232708.58      7247975.49
        2232329.        7248010.      2230355.74      7248517.84
#Sta/Elev= 30
  4144.6     995  4184.9  995.58  4409.1  996.15  4461.7   994.1  4894.2  957.12
  4997.2  958.72  5011.5  951.58  5013.2  951.08  5023.7  951.58  5035.9  956.12
  5058.3  957.25  5423.7  954.25  5552.2  954.08  5638.8  962.52  5699.4   963.8
  5851.7  974.78  6024.3  978.63  6233.7  983.85  6264.7  977.23  6285.4  984.37
  6294.6  983.99  6299.7  980.27  6335.3  984.66  6340.4  980.87  6347.3  982.78
    6376  979.39  6440.3  989.89  6673.6 1004.83  6900.1 1017.72  7032.2 1021.82
#Mann= 10 ,-1 , 0
  4144.6     .05       0  4184.9     .12       0  4409.1     .05       0
  4461.7     .12       0  5011.5     .07       0  5023.7     .12       0
  5423.7     .12       0  5638.8     .05       0  6024.3     .12       0
  6673.6     .05       0
Bank Sta=5011.5,5023.7
XS Rating Curve= 0 ,0
Exp/Cntr=0.3,0.1

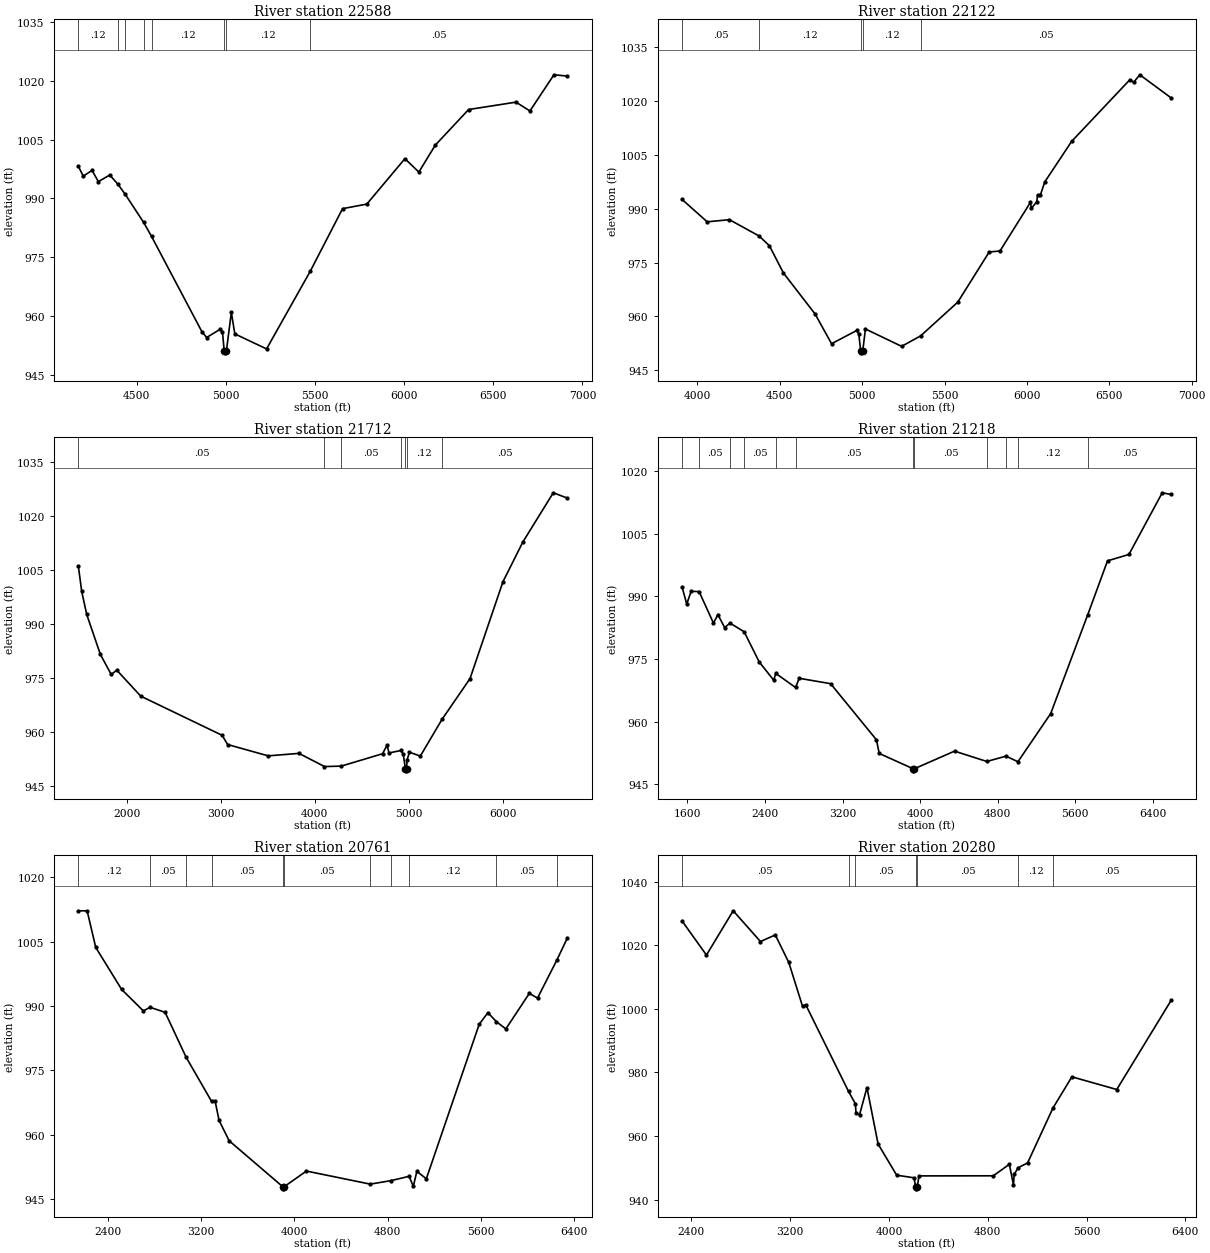
Type RM Length L Ch R = 1 ,22588   ,466,466,466
BEGIN DESCRIPTION:
Upper Denton 93 47.0
END DESCRIPTION:
XS GIS Cut Line= 4
      2233015.16      7247952.87      2232750.38      7247662.05
        2232329.        7247560.      2230485.95      7248083.81
#Sta/Elev= 30
  4173.1  998.22  4200.9   995.7  4250.2  997.16  4285.4  994.29  4349.5  995.98
  4395.9  993.59  4436.2  991.06  4539.1  983.91  4583.9   980.3  4866.2  956.02
  4892.8  954.54  4969.1  956.66  4981.6  955.86  4991.3  951.13    4993  950.63
  5003.5  951.13  5031.2  960.93  5050.8  955.46  5228.7  951.63  5473.2  971.39
  5654.9   987.4  5790.8  988.56  6004.5 1000.14  6082.7  996.73  6174.7 1003.59
  6361.8 1012.68  6627.3 1014.56  6705.5 1012.31  6840.1 1021.54    6916 1021.21
#Mann= 8 ,-1 , 0
  4173.1     .12       0  4395.9     .05       0  4436.2     .12       0
  4539.1     .05       0  4583.9     .12       0  4991.3     .07       0
  5003.5     .12       0  5473.2     .05       0
Bank Sta=4991.3,5003.5
XS Rating Curve= 0 ,0
Exp/Cntr=0.3,0.1

Type RM Length L Ch R = 1 ,22122   ,410,410,410
BEGIN DESCRIPTION:
Upper Denton 93 46.0
END DESCRIPTION:
XS GIS Cut Line= 5
      2233080.25      7247922.48      2232459.59      7247123.86
        2232379.        7247110.       2232135.8       7247091.3
      2230703.94      7247874.94
#Sta/Elev= 30
  3906.4  992.63  4059.2  986.39  4194.1  986.99  4373.4  982.46  4436.6  979.73
  4521.7  972.13  4714.4  960.67    4814   952.4  4967.1   956.1  4979.3   955.1
    4991  950.36  4992.7  949.86  5003.2  950.36  5019.7  956.51  5239.4  951.67
  5354.8  954.59  5580.3     964    5771  977.98  5836.4  978.26  6021.3  991.81
    6027  990.15  6059.3  991.94    6065  993.94  6081.1  993.78  6108.6  997.54
  6271.7 1008.83  6625.5 1026.04  6647.3 1025.27  6685.2 1027.39  6875.8 1020.93
#Mann= 5 ,-1 , 0
  3906.4     .05       0  4373.4     .12       0    4991     .07       0
  5003.2     .12       0  5354.8     .05       0
Bank Sta=4991,5003.2
XS Rating Curve= 0 ,0
Exp/Cntr=0.3,0.1

Type RM Length L Ch R = 1 ,21712   ,494,494,494
BEGIN DESCRIPTION:
Upper Denton 93 45.0
END DESCRIPTION:
XS GIS Cut Line= 5
      2235495.82      7248069.38      2232466.31      7246819.39
      2232222.06      7246851.17      2232026.74      7246883.72
      2230735.51      7247610.72
#Sta/Elev= 30
  1484.5 1006.04  1520.6  998.92  1573.8  992.53  1719.1  981.43  1834.7  975.85
  1893.4  977.06  2148.9  969.83  3014.2  958.96  3072.9   956.4    3504  953.25
  3831.7  953.94  4103.3  950.28  4281.1   950.4  4720.9  953.84  4769.1  956.23
  4789.3  954.05  4915.5  954.74  4940.6  953.78  4964.7  949.59  4966.4  949.09
  4976.9  949.59  4980.9  952.06  5007.1  954.26  5122.7  953.19  5352.6  963.35
  5651.1   974.7  6002.3 1001.65  6213.4 1012.65    6537 1026.32  6687.9 1024.83
#Mann= 7 ,-1 , 0
  1484.5     .05       0  4103.3     .12       0  4281.1     .05       0
  4915.5     .12       0  4964.7     .07       0  4976.9     .12       0
  5352.6     .05       0
Bank Sta=4964.7,4976.9
XS Rating Curve= 0 ,0
Exp/Cntr=0.3,0.1

Type RM Length L Ch R = 1 ,21218   ,457,457,457
BEGIN DESCRIPTION:
Upper Denton 93 44.0
END DESCRIPTION:
XS GIS Cut Line= 4
      2235626.07       7247218.7      2232493.32      7246384.59
      2232113.55      7246362.89      2230803.82      7246914.92
#Sta/Elev= 30
  1544.5  992.23  1592.9  988.13  1638.2  991.17  1720.5  991.11  1868.6  983.55
    1914  985.62  1983.8  982.49    2039  983.56    2185  981.49  2339.8  974.28
    2490  969.88  2510.6  971.52  2714.8  968.15  2752.2  970.35  3076.4  969.06
  3549.1  955.61  3577.4  952.36  3927.2  948.69  3928.9  948.19  3939.7  948.69
  4354.2  952.91  4687.1  950.43  4884.7  951.71  5007.8  950.37  5345.4  961.89
  5727.8  985.58  5931.4  998.47  6152.2    1000  6495.7 1014.77  6588.1 1014.36
#Mann= 12 ,-1 , 0
  1544.5     .12       0  1720.5     .05       0    2039     .12       0
    2185     .05       0  2510.6     .12       0  2714.8     .05       0
  3927.2    .033       0  3939.7     .05       0  4687.1     .12       0
  4884.7     .05       0  5007.8     .12       0  5727.8     .05       0
Bank Sta=3927.2,3939.7
XS Rating Curve= 0 ,0
Exp/Cntr=0.3,0.1

Type RM Length L Ch R = 1 ,20761   ,481,481,481
BEGIN DESCRIPTION:
Upper Denton 93 43.0
END DESCRIPTION:
XS GIS Cut Line= 4
      2235087.81      7246684.83      2232457.63      7245964.35
        2232329.        7245960.       2231006.8      7246200.12
#Sta/Elev= 30
  2144.6 1012.23  2220.4 1012.21  2294.5 1003.67  2516.6  993.88  2703.3  988.87
  2760.2  989.72  2889.9  988.54  3069.8  978.09  3288.9  967.76  3318.8  967.84
  3353.2  963.34  3439.4  958.59  3899.7  947.87  3901.5  947.37  3912.2  947.87
    4103  951.52  4650.7  948.47  4830.1  949.29  4984.6  950.29  5020.7  947.96
  5051.2  951.44  5132.5  949.72  5586.4  985.75    5661  988.47  5732.7   986.4
  5815.2  984.67  6016.7  992.96  6087.2  991.87  6251.8 1000.65  6344.2 1005.93
#Mann= 11 ,-1 , 0
  2144.6     .12       0  2760.2     .05       0  3069.8     .12       0
  3288.9     .05       0  3899.7     .07       0  3912.2     .05       0
  4650.7     .12       0  4830.1     .05       0  4984.6     .12       0
  5732.7     .05       0  6251.8     .12       0
Bank Sta=3899.7,3912.2
XS Rating Curve= 0 ,0
Exp/Cntr=0.3,0.1

Type RM Length L Ch R = 1 ,20280   ,427,427,427
BEGIN DESCRIPTION:
Upper Denton 93 42.0
END DESCRIPTION:
XS GIS Cut Line= 3
      2234902.13      7245310.38        2232229.        7245510.
       2231039.3      7245983.13
#Sta/Elev= 30
  2324.3 1027.64  2521.8 1016.92  2738.6 1030.84  2959.2 1021.17  3079.5 1023.24
  3188.5  1014.6  3300.1 1000.78  3325.8 1001.29  3672.5  974.02  3728.2  970.12
  3732.8  967.14  3761.4  966.67  3821.6  975.22  3911.8  957.49  4062.3  947.68
  4202.7  946.86  4216.5  943.89  4218.2  943.39    4229  943.89  4242.8  947.46
  4844.4  947.49  4974.8   951.1  5007.6   944.7  5014.3  947.98  5046.7  950.04
  5122.3  951.54  5327.5  968.79  5481.1  978.62  5844.3  974.63  6285.2 1002.69
#Mann= 7 ,-1 , 0
  2324.3     .05       0  3672.5     .12       0  3728.2     .05       0
  4216.5    .033       0    4229     .05       0  5046.7     .12       0
  5327.5     .05       0
Bank Sta=4216.5,4229
XS Rating Curve= 0 ,0
Exp/Cntr=0.3,0.1

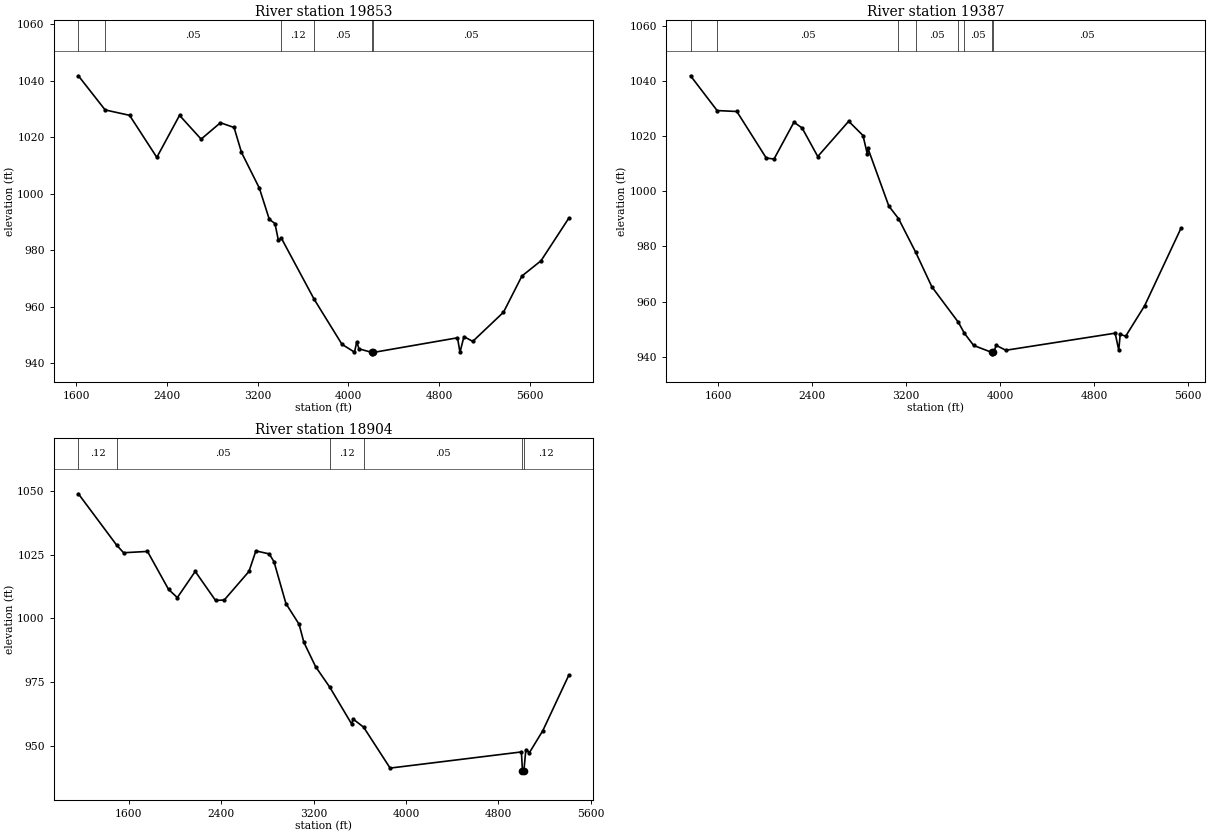
Type RM Length L Ch R = 1 ,19853   ,466,466,466
BEGIN DESCRIPTION:
Upper Denton 93 41.0
END DESCRIPTION:
XS GIS Cut Line= 4
      2235379.59      7245277.82       2232189.5      7245071.66
        2232029.        7245160.      2231148.67      7245505.36
#Sta/Elev= 30
  1619.8 1041.74  1855.8 1029.65  2071.3 1027.74  2311.8 1012.85  2512.2 1027.73
  2702.6 1019.31    2873 1025.11  2993.3 1023.43  3058.7  1014.6  3216.4 1001.95
  3303.9  990.93    3354  989.41  3384.1  983.48  3411.6  984.15  3700.2  962.57
  3945.2  946.65  4055.5  943.88  4075.5  947.47  4095.5  945.05  4209.5  943.78
  4211.3  943.28    4222  943.78  4964.2  948.96    4986  943.84  5021.2  949.37
  5098.7  947.69  5369.9  958.01  5532.6  970.84  5700.7  976.23  5945.4  991.28
#Mann= 6 ,-1 , 0
  1619.8     .12       0  1855.8     .05       0  3411.6     .12       0
  3700.2     .05       0  4209.5     .04       0    4222     .05       0
Bank Sta=4209.5,4222
XS Rating Curve= 0 ,0
Exp/Cntr=0.3,0.1

Type RM Length L Ch R = 1 ,19387   ,483,483,483
BEGIN DESCRIPTION:
Upper Denton 93 40.0
END DESCRIPTION:
XS GIS Cut Line= 4
      2235357.95      7245310.38      2231939.94      7244746.14
        2231779.        7244810.      2231279.03      7245009.99
#Sta/Elev= 30
  1362.6 1041.97    1589 1029.34  1756.8 1029.01  2007.4 1012.11  2073.5 1011.75
  2243.3 1025.12  2312.9 1023.01    2446 1012.66  2709.5 1025.46  2831.2 1020.29
  2867.9 1013.59    2873 1015.67  3051.2  994.68  3133.5  990.13  3280.8  977.84
  3417.8  965.35  3643.7  952.47    3694  948.54  3773.7  944.07  3929.7  941.53
  3931.4  941.03  3942.2  941.53  3966.3   944.1  4047.4  942.33  4978.5  948.53
  5009.4  942.39  5021.6  948.07  5068.7  947.46  5230.2  958.53  5538.5  986.56
#Mann= 8 ,-1 , 0
  1362.6     .12       0    1589     .05       0  3133.5     .12       0
  3280.8     .05       0  3643.7     .12       0    3694     .05       0
  3929.7     .04       0  3942.2     .05       0
Bank Sta=3929.7,3942.2
XS Rating Curve= 0 ,0
Exp/Cntr=0.3,0.1

Type RM Length L Ch R = 1 ,18904   ,430,430,430
BEGIN DESCRIPTION:
Upper Denton 93 39.0
END DESCRIPTION:
XS GIS Cut Line= 3
      2235488.08      7245321.21        2231779.        7244360.
      2231379.02        7244260.
#Sta/Elev= 30
  1164.2 1048.86    1497 1028.62  1555.8 1025.72  1762.4 1026.24  1944.8 1011.32
  2020.7 1008.12  2175.6 1018.39  2351.2 1007.01  2426.7 1007.17  2640.5 1018.38
  2700.5 1026.44  2816.1 1025.27  2857.4 1022.18  2960.7 1005.77  3074.4  997.66
  3115.7  990.58  3217.9  980.97    3340  972.96  3528.9  958.55  3542.6  960.43
  3633.2  957.26  3862.2  941.21  4998.4  947.55  5007.6  940.24  5009.3  939.74
  5020.1  940.24    5037  948.45    5068  947.28  5183.9  955.91  5408.1  977.61
#Mann= 6 ,-1 , 0
  1164.2     .12       0    1497     .05       0    3340     .12       0
  3633.2     .05       0  5007.6    .033       0  5020.1     .12       0
Bank Sta=5007.6,5020.1
XS Rating Curve= 0 ,0
Exp/Cntr=0.3,0.1