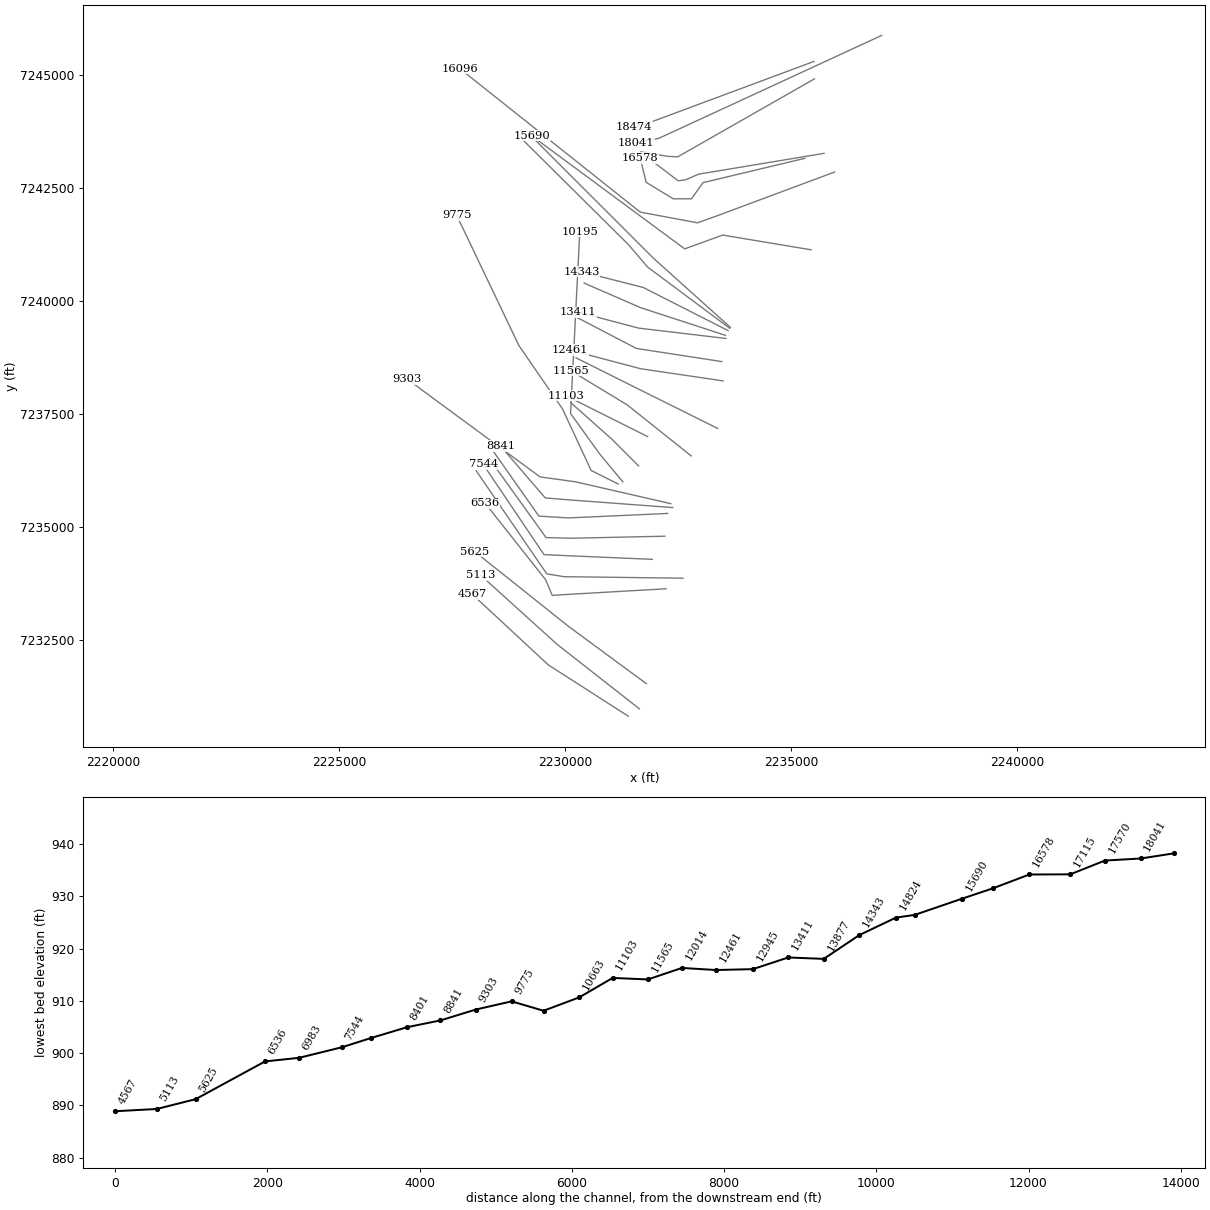
HEC-RAS study Upper Denton 93.prj: Upper Denton 93 Base Level Engineering

--- Upper Denton 93.g01 (geometry) --- (continued)

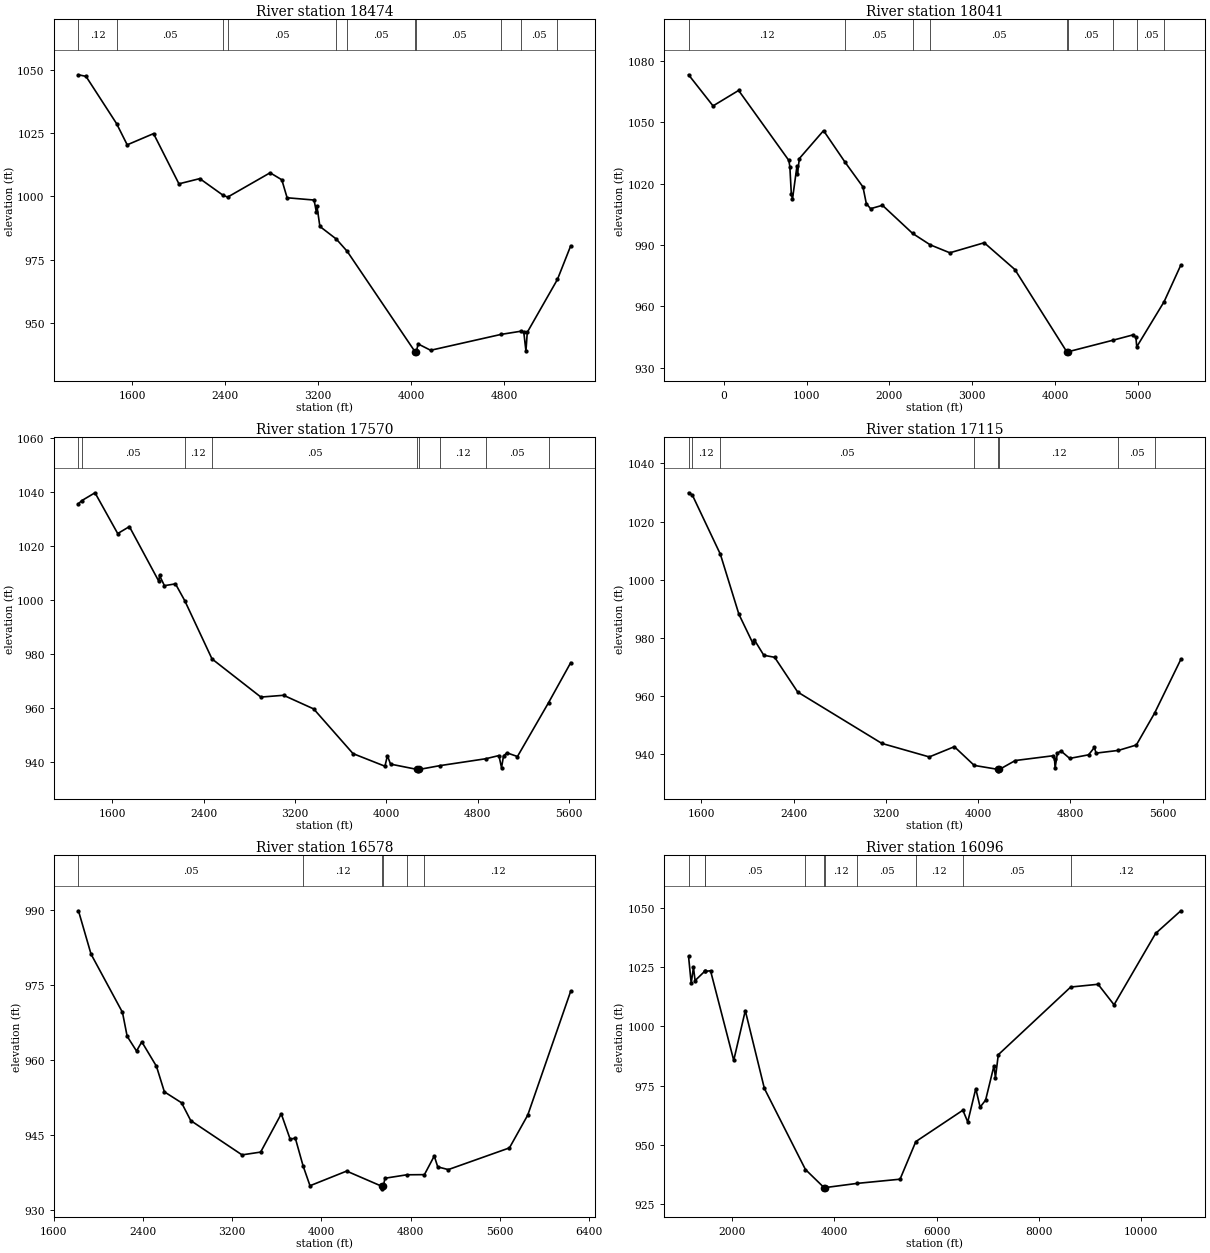
Type RM Length L Ch R = 1 ,18474   ,433,433,433
BEGIN DESCRIPTION:
Upper Denton 93 38.0
END DESCRIPTION:
XS GIS Cut Line= 3
      2235509.79      7245310.36        2231879.        7243960.
      2231528.98      7243859.99
#Sta/Elev= 30
  1135.9 1047.97  1200.8 1047.34  1463.8  1028.7  1555.5 1020.31  1782.3 1024.74
  2000.9 1004.91  2180.5 1006.97  2383.4 1000.31  2420.7  999.68  2785.8 1009.27
  2886.5 1006.51  2932.2  999.41  3164.3  998.51    3184  993.78  3189.3  996.02
  3214.3  988.09  3355.6  983.11  3448.8   978.3  4032.5  938.68  4034.3  938.18
    4045  938.68  4060.1  941.69  4167.8  939.19  4775.2  945.47  4944.3  946.71
  4969.5  946.44  4988.3  938.89  4999.8  946.29  5259.4  967.16  5373.7  980.43
#Mann= 11 ,-1 , 0
  1135.9     .12       0  1463.8     .05       0  2383.4     .12       0
  2420.7     .05       0  3355.6     .12       0  3448.8     .05       0
  4032.5    .033       0    4045     .05       0  4775.2     .12       0
  4944.3     .05       0  5259.4     .12       0
Bank Sta=4032.5,4045
XS Rating Curve= 0 ,0
Exp/Cntr=0.3,0.1

Type RM Length L Ch R = 1 ,18041   ,471,471,471
BEGIN DESCRIPTION:
Upper Denton 93 37.0
END DESCRIPTION:
XS GIS Cut Line= 3
      2237007.23      7245885.46        2232079.        7243610.
      2231578.98        7243510.
#Sta/Elev= 30
  -423.6 1073.24  -128.2 1058.01   180.2 1065.58     786 1031.34   798.3 1028.28
   815.8 1015.07   830.1 1012.43   884.6 1028.75   890.1 1024.91   913.1 1032.28
  1204.9 1045.92  1464.1 1030.48  1680.2 1018.37  1720.6 1010.26    1772 1007.73
  1915.2 1009.39  2279.5  995.62  2491.5  990.05  2728.2  986.15  3143.1  991.07
  3512.9  977.97  4139.2  937.71    4141  937.21  4151.8  937.71  4699.5  943.42
  4938.5     946  4972.9  944.78    4983  940.16  5313.3  962.25  5514.5  980.12
#Mann= 9 ,-1 , 0
  -423.6     .12       0  1464.1     .05       0  2279.5     .12       0
  2491.5     .05       0  4139.2    .033       0  4151.8     .05       0
  4699.5     .12       0    4983     .05       0  5313.3     .12       0
Bank Sta=4139.2,4151.8
XS Rating Curve= 0 ,0
Exp/Cntr=0.3,0.1

Type RM Length L Ch R = 1 ,17570   ,455,455,455
BEGIN DESCRIPTION:
Upper Denton 93 36.0
END DESCRIPTION:
XS GIS Cut Line= 4
      2235522.12      7244925.26       2232494.1      7243199.06
        2232279.        7243210.      2231679.05      7243309.99
#Sta/Elev= 30
  1304.3 1035.73  1331.5 1036.84    1449 1039.79  1647.8 1024.69  1750.1 1027.26
  2007.9    1007  2013.7 1009.18  2056.9 1005.39  2153.4 1006.06  2234.1  999.89
  2473.5  978.25  2901.1  964.13  3099.9  964.79  3363.5  959.74  3707.8  943.19
  3987.2  938.52  4008.8  942.41  4036.2   939.3  4271.9  937.31  4273.7  936.81
  4284.5  937.31  4470.3  938.75  4869.9  941.29  4985.1  942.47  5007.7  937.96
  5025.4  942.37  5055.9  943.47  5147.1  942.11  5420.1   962.1  5613.4  976.86
#Mann= 9 ,-1 , 0
  1304.3     .12       0  1331.5     .05       0  2234.1     .12       0
  2473.5     .05       0  4271.9    .033       0  4284.5     .05       0
  4470.3     .12       0  4869.9     .05       0  5420.1     .12       0
Bank Sta=4271.9,4284.5
XS Rating Curve= 0 ,0
Exp/Cntr=0.3,0.1

Type RM Length L Ch R = 1 ,17115   ,537,537,537
BEGIN DESCRIPTION:
Upper Denton 93 35.0
END DESCRIPTION:
XS GIS Cut Line= 5
      2235732.55      7243276.79      2232954.59      7242815.79
      2232669.86      7242690.79       2232503.2      7242669.96
      2231728.99      7243260.01
#Sta/Elev= 30
  1488.2 1029.91    1521 1029.13  1763.9 1008.76  1924.7  988.09  2046.6  978.03
  2059.5  979.22  2140.6  973.97  2234.5  973.27  2434.5  961.31  3164.4  943.62
  3575.4  938.97  3792.8  942.49  3965.3  936.05  4171.7  934.68  4173.5  934.18
  4184.3  934.68  4321.2  937.73  4646.2  939.36  4661.6  938.13  4666.6  935.15
  4686.5  940.27  4716.8  941.04    4793  938.46  4957.2   939.7  5007.1  942.24
  5021.7  940.28  5215.8  941.22  5370.9  943.07  5529.1  954.04  5756.5  972.53
#Mann= 8 ,-1 , 0
  1488.2     .05       0    1521     .12       0  1763.9     .05       0
  3965.3     .12       0  4171.7     .07       0  4184.3     .12       0
  5215.8     .05       0  5529.1     .12       0
Bank Sta=4171.7,4184.3
XS Rating Curve= 0 ,0
Exp/Cntr=0.3,0.1

Type RM Length L Ch R = 1 ,16578   ,482,482,482
BEGIN DESCRIPTION:
Upper Denton 93 34.0
END DESCRIPTION:
XS GIS Cut Line= 6
      2235308.73      7243166.48      2233055.28      7242628.29
      2232798.34      7242270.65      2232395.56      7242270.65
      2231796.28      7242635.89      2231663.84      7243174.25
#Sta/Elev= 30
  1820.7  989.76  1933.5  981.09  2215.4  969.45  2257.5  964.66  2341.6  961.71
  2388.9  963.55  2520.3  958.66  2591.5  953.55  2745.7  951.36    2828   947.8
  3288.1  940.94  3455.1   941.5  3640.2  949.15  3719.3  944.12  3766.5  944.27
  3835.9  938.74  3897.9  934.77  4226.6   937.7  4543.2  934.65  4544.9  934.15
  4555.8  934.65  4570.4  936.27  4766.9  936.96  4924.4  936.99  5012.9  940.72
  5043.9  938.54  5138.7     938  5687.2  942.34  5851.5   948.9  6236.9  973.68
#Mann= 6 ,-1 , 0
  1820.7     .05       0  3835.9     .12       0  4543.2     .07       0
  4555.8     .12       0  4766.9     .05       0  4924.4     .12       0
Bank Sta=4543.2,4555.8
XS Rating Curve= 0 ,0
Exp/Cntr=0.3,0.1

Type RM Length L Ch R = 1 ,16096   ,406,406,406
BEGIN DESCRIPTION:
Upper Denton 93 33.0
END DESCRIPTION:
XS GIS Cut Line= 5
       2235968.5      7242864.41       2233378.2      7241899.12
      2232933.75       7241739.4      2231666.07      7241976.17
       2227675.6      7245149.79
#Sta/Elev= 30
  1150.3 1029.37  1201.8 1018.07  1245.8  1024.8  1277.8 1019.21  1467.6 1023.16
  1477.1 1023.09  1580.1 1023.36  2033.3  985.62  2259.6 1006.56  2632.8  973.77
  3435.6  939.63  3800.5  931.99  3802.2  931.49  3813.1  931.99  4443.5  933.78
  5285.4  935.55  5593.9   951.4  6514.1  964.61  6609.1  959.66  6766.1  973.69
    6851   965.9  6958.4  968.87  7121.7   983.3  7150.6  978.32  7206.6  987.99
  8622.5  1016.5  9157.7 1017.66    9470 1009.02 10282.1 1039.07 10775.1 1048.62
#Mann= 10 ,-1 , 0
  1150.3     .05       0  1467.6     .12       0  1477.1     .05       0
  3435.6     .12       0  3800.5    .033       0  3813.1     .12       0
  4443.5     .05       0  5593.9     .12       0  6514.1     .05       0
  8622.5     .12       0
Bank Sta=3800.5,3813.1
XS Rating Curve= 0 ,0
Exp/Cntr=0.3,0.1

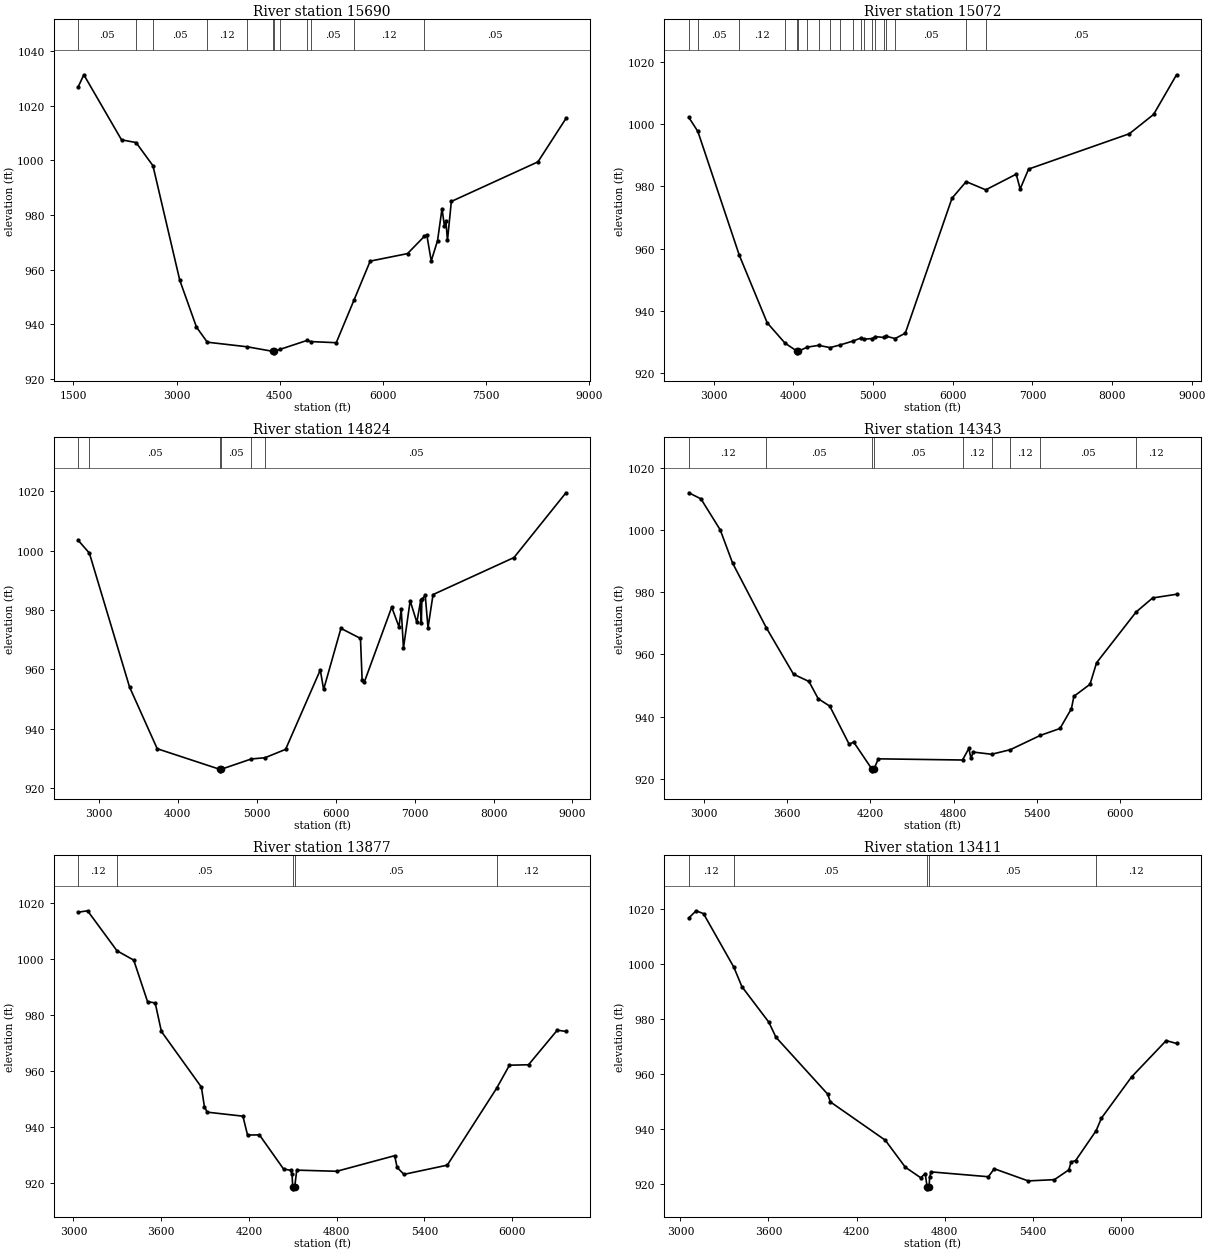
Type RM Length L Ch R = 1 ,15690   ,618,618,618
BEGIN DESCRIPTION:
Upper Denton 93 32.0
END DESCRIPTION:
XS GIS Cut Line= 4
      2235447.66      7241142.17      2233489.31      7241468.57
      2232649.03      7241163.01      2229264.41      7243665.22
#Sta/Elev= 30
  1571.8 1026.92  1653.2  1031.3  2200.7 1007.49  2412.4 1006.49  2657.7  998.01
  3047.2  956.11  3290.5  938.92  3447.7  933.41  4028.4  931.72  4408.8  930.01
  4410.6  929.51  4421.4  930.01  4508.8  930.82  4896.1  934.04  4951.4  933.63
  5321.8  933.22  5581.2   948.9  5815.1  963.09  6357.9  965.84  6602.1  972.16
  6637.6  972.77  6702.2  963.14  6794.2  970.59  6858.9  982.27  6894.4  975.93
  6915.2  977.84  6938.3  970.65  6994.6  984.93  8253.4  999.42  8660.4 1015.31
#Mann= 12 ,-1 , 0
  1571.8     .05       0  2412.4     .12       0  2657.7     .05       0
  3447.7     .12       0  4028.4     .05       0  4408.8    .033       0
  4421.4     .05       0  4508.8     .05       0  4896.1     .12       0
  4951.4     .05       0  5581.2     .12       0  6602.1     .05       0
Bank Sta=4408.8,4421.4
XS Rating Curve= 0 ,0
Exp/Cntr=0.3,0.1

Type RM Length L Ch R = 1 ,15072   ,248,248,248
BEGIN DESCRIPTION:
Upper Denton 93 31.0
END DESCRIPTION:
XS GIS Cut Line= 3
      2233662.63      7239424.06      2231952.53      7240960.55
      2229247.03      7243665.17
#Sta/Elev= 30
  2685.7  1002.2  2799.1  997.68  3320.5  957.77  3669.9   936.1    3893  929.57
  4045.6  926.93  4047.3  926.43  4058.2  926.93  4174.3  928.27  4316.5  928.84
  4458.8  928.12  4578.8  928.92  4743.4  930.19  4851.7  931.24  4885.7  930.83
  4988.3  931.03  5025.7  931.67  5132.2  931.37  5160.6   931.8    5276  931.03
    5404  932.75  5990.9  976.21  6168.5  981.53  6414.5  978.89    6797  983.93
  6846.5  979.17  6952.5  985.57  8218.2  996.95  8522.3 1003.16  8810.2 1015.92
#Mann= 20 ,-1 , 0
  2685.7     .12       0  2799.1     .05       0  3320.5     .12       0
    3893     .05       0  4045.6    .033       0  4058.2     .12       0
  4174.3     .12       0  4316.5     .12       0  4458.8     .12       0
  4578.8     .05       0  4743.4     .12       0  4851.7     .05       0
  4885.7     .12       0  4988.3     .05       0  5025.7     .12       0
  5132.2     .05       0  5160.6     .12       0    5276     .05       0
  6168.5     .12       0  6414.5     .05       0
Bank Sta=4045.6,4058.2
XS Rating Curve= 0 ,0
Exp/Cntr=0.3,0.1

Type RM Length L Ch R = 1 ,14824   ,481,481,481
BEGIN DESCRIPTION:
Upper Denton 93 30.0
END DESCRIPTION:
XS GIS Cut Line= 4
      2233645.23      7239406.73        2231829.        7240760.
      2231405.65      7241255.68      2229090.56      7243552.55
#Sta/Elev= 30
  2739.3 1003.44  2880.1  999.16  3389.2   954.1  3739.6  933.34  4533.8   926.4
  4535.6   925.9  4546.8   926.4  4931.1  929.89  5105.1  930.31    5366  933.13
  5805.3  959.82  5847.8  953.29  6066.9  973.83  6314.4  970.45  6335.6  956.37
  6363.9  955.82  6710.4  980.96  6802.3  974.34  6830.6  980.25  6858.9  967.19
  6943.8   983.1  7028.6  975.87  7078.1  983.33  7085.2  975.48  7092.2  983.58
  7134.7  984.95    7170  974.04  7233.7   985.2    8259  997.66  8917.3 1019.45
#Mann= 6 ,-1 , 0
  2739.3     .12       0  2880.1     .05       0  4533.8     .07       0
  4546.8     .05       0  4931.1     .12       0  5105.1     .05       0
Bank Sta=4533.8,4546.8
XS Rating Curve= 0 ,0
Exp/Cntr=0.3,0.1

Type RM Length L Ch R = 1 ,14343   ,466,466,466
BEGIN DESCRIPTION:
Upper Denton 93 29.0
END DESCRIPTION:
XS GIS Cut Line= 3
      2233610.55      7239354.62        2231729.        7240310.
      2230363.96      7240656.73
#Sta/Elev= 30
  2889.4 1011.94  2976.9 1009.98  3116.1 1000.01  3205.2  989.34  3449.1   968.5
  3644.7  953.62    3756  951.29  3822.8  945.75  3906.2  943.36  4046.3   931.1
  4078.7  931.82  4211.3  923.06  4213.1  922.56  4224.4  923.06  4256.7  926.42
    4864  926.04  4909.9  929.78  4924.5  926.57  4941.2  928.59  5073.9  927.89
  5208.9  929.36  5425.8  933.96  5567.1  936.17  5649.6  942.53  5667.5  946.51
  5783.7  950.38  5831.2  957.31  6116.6  973.63  6235.5  978.13    6408  979.32
#Mann= 9 ,-1 , 0
  2889.4     .12       0  3449.1     .05       0  4211.3     .07       0
  4224.4     .05       0    4864     .12       0  5073.9     .05       0
  5208.9     .12       0  5425.8     .05       0  6116.6     .12       0
Bank Sta=4211.3,4224.4
XS Rating Curve= 0 ,0
Exp/Cntr=0.3,0.1

Type RM Length L Ch R = 1 ,13877   ,466,466,466
BEGIN DESCRIPTION:
Upper Denton 93 28.0
END DESCRIPTION:
XS GIS Cut Line= 3
      2233549.73      7239250.48        2231679.        7239860.
      2230424.71      7240405.01
#Sta/Elev= 30
  3032.5 1016.81  3096.4 1017.32  3297.4 1003.04  3411.9   999.7  3506.5  984.87
  3558.7  984.41  3601.2  974.22  3874.7  954.34  3895.7  947.22  3915.1   945.4
  4158.6  943.97  4190.2  937.23  4271.4  937.29  4436.2  925.12  4484.7  924.63
  4494.8  923.18  4499.2  918.52    4501  918.02  4512.3  918.52  4526.7   924.7
  4800.2  924.29  5196.3  929.86    5213  925.67  5259.9  923.19  5556.1  926.48
  5893.9  953.97  5981.3  962.17  6111.7  962.33  6308.4  974.69  6367.6  974.23
#Mann= 5 ,-1 , 0
  3032.5     .12       0  3297.4     .05       0  4499.2    .033       0
  4512.3     .05       0  5893.9     .12       0
Bank Sta=4499.2,4512.3
XS Rating Curve= 0 ,0
Exp/Cntr=0.3,0.1

Type RM Length L Ch R = 1 ,13411   ,466,466,466
BEGIN DESCRIPTION:
Upper Denton 93 27.0
END DESCRIPTION:
XS GIS Cut Line= 3
      2233558.38      7239181.04        2231629.        7239410.
      2230294.53      7239762.63
#Sta/Elev= 30
  3057.1 1016.73  3106.8 1019.34  3157.2 1018.29  3364.1  998.81    3419  991.75
  3602.6  978.83  3650.6  973.39  4003.1  952.71  4021.2   949.9  4395.8  935.96
  4532.5  926.14  4637.5  922.31  4667.7  923.86  4681.3  918.79  4683.1  918.29
  4694.4  918.79  4697.9  922.56    4708  924.45  5098.1  922.69  5138.3  925.59
  5369.5  921.17  5548.2  921.63  5646.2  925.18    5662  928.03    5693  928.58
  5832.3  939.42  5868.9  944.01  6073.5  958.93  6309.9  972.17  6380.3  971.11
#Mann= 5 ,-1 , 0
  3057.1     .12       0  3364.1     .05       0  4681.3    .033       0
  4694.4     .05       0  5832.3     .12       0
Bank Sta=4681.3,4694.4
XS Rating Curve= 0 ,0
Exp/Cntr=0.3,0.1

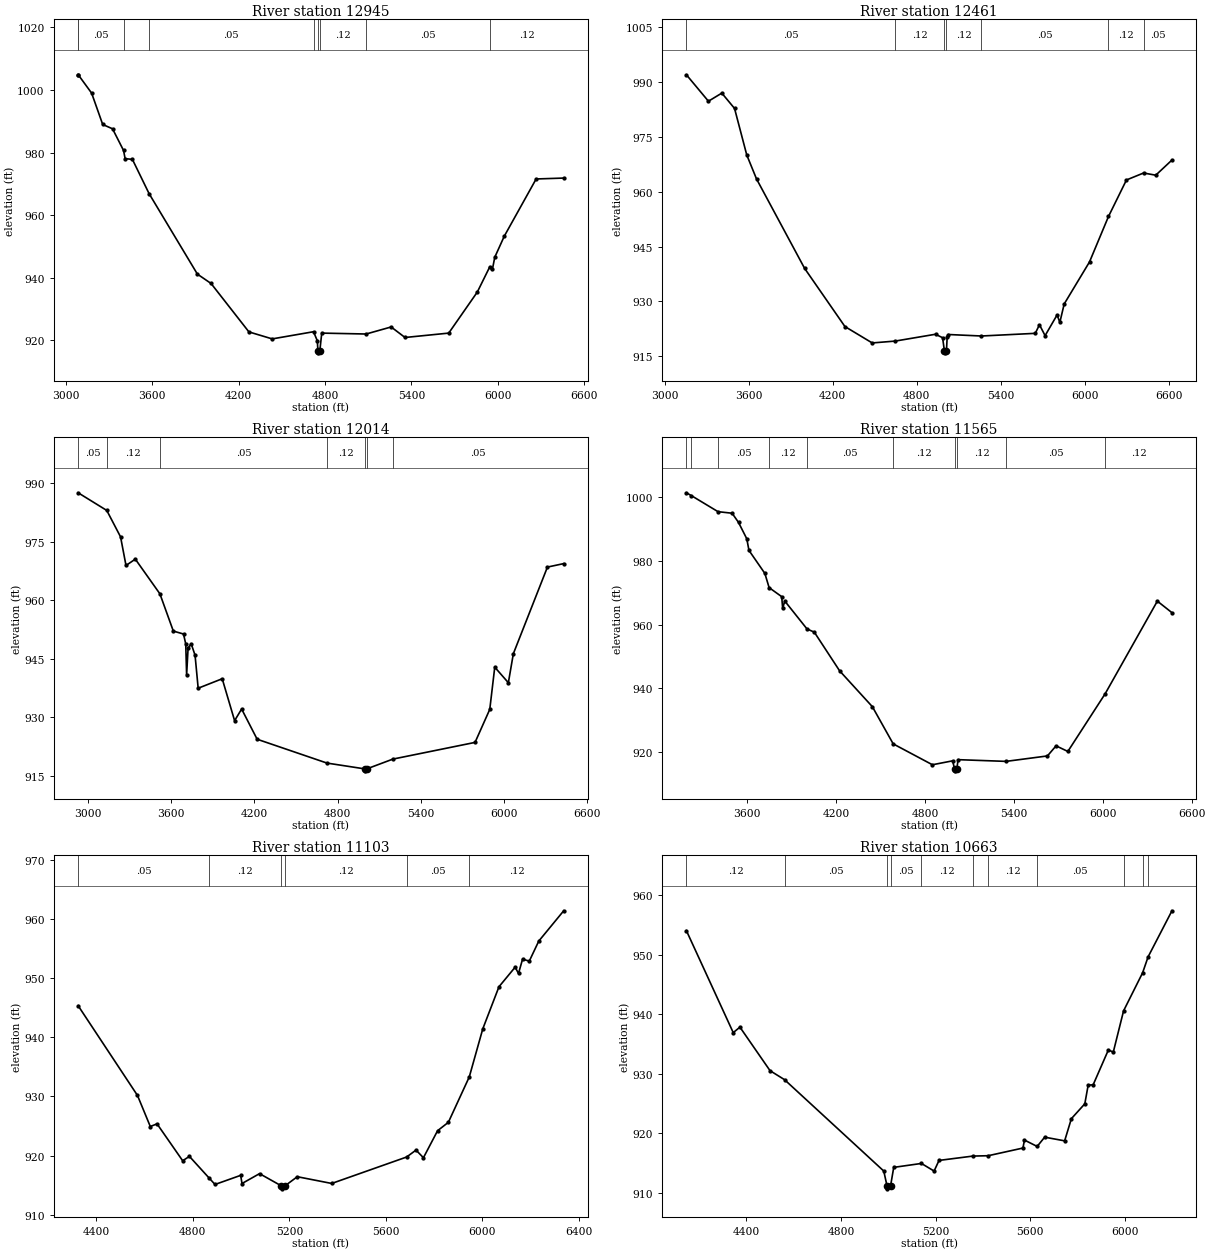
Type RM Length L Ch R = 1 ,12945   ,484,484,484
BEGIN DESCRIPTION:
Upper Denton 93 26.0
END DESCRIPTION:
XS GIS Cut Line= 3
      2233471.62      7238668.88        2231579.        7238960.
       2230286.4      7239634.76
#Sta/Elev= 30
  3085.1 1004.82  3085.9 1004.82  3178.8  998.97  3255.8  988.95  3324.1  987.58
  3400.7  980.65  3411.5  978.05  3462.1  977.81  3578.1  966.87  3913.5  941.19
  4008.5   938.2  4271.5  922.74  4433.4  920.51  4720.3   922.8    4747  919.86
  4750.6  916.56  4752.5  916.06  4763.7  916.56  4777.4  922.36  5085.7  922.07
  5259.4  924.32  5355.9  920.96  5659.5  922.36  5858.2  935.48  5945.1  943.57
    5963  942.77  5979.5   946.6  6045.7  953.33  6266.6  971.56  6458.1  971.85
#Mann= 9 ,-1 , 0
  3085.1     .12       0  3085.9     .05       0  3400.7     .12       0
  3578.1     .05       0  4720.3     .12       0  4750.6     .07       0
  4763.7     .12       0  5085.7     .05       0  5945.1     .12       0
Bank Sta=4750.6,4763.7
XS Rating Curve= 0 ,0
Exp/Cntr=0.3,0.1

Type RM Length L Ch R = 1 ,12461   ,447,447,447
BEGIN DESCRIPTION:
Upper Denton 93 25.0
END DESCRIPTION:
XS GIS Cut Line= 3
      2233499.27      7238242.02        2231679.        7238510.
      2230104.61      7238925.19
#Sta/Elev= 30
  3156.1  992.04  3313.5   984.8  3409.1  987.02    3500  982.82  3587.2  970.08
  3656.9  963.52  4000.4  939.02  4288.4  923.09  4483.3   918.6  4647.5  919.11
  4935.3  920.98  4985.9  920.03  4999.1  916.39  5001.1  915.89  5013.5  916.39
  5018.7  920.27    5027  920.91  5263.4   920.5  5647.9  921.23  5677.8  923.58
  5718.1   920.6  5803.9  926.28  5823.3  924.22  5854.4  929.27  6035.3  940.79
  6170.9  953.24  6299.1  963.23  6421.4  965.14  6508.4  964.54  6624.2  968.69
#Mann= 7 ,-1 , 0
  3156.1     .05       0  4647.5     .12       0  4999.1     .07       0
  5013.5     .12       0  5263.4     .05       0  6170.9     .12       0
  6421.4     .05       0
Bank Sta=4999.1,5013.5
XS Rating Curve= 0 ,0
Exp/Cntr=0.3,0.1

Type RM Length L Ch R = 1 ,12014   ,449,449,449
BEGIN DESCRIPTION:
Upper Denton 93 24.0
END DESCRIPTION:
XS GIS Cut Line= 3
      2233379.88      7237189.51        2231529.        7238110.
        2230244.      7238752.02
#Sta/Elev= 30
  2928.3  987.58    3135  983.05  3234.5  976.27  3273.7  968.94  3340.9  970.57
  3518.2  961.68  3615.2  952.12  3688.7  951.37  3704.8  948.82  3711.1  940.89
  3721.6  947.71    3744  948.88    3772  945.93  3794.4  937.47  3967.9   939.9
  4057.3  929.15    4108  932.14    4220  924.39  4723.8  918.28  4996.6  916.79
  4998.6  916.29    5011  916.79  5199.3   919.3  5792.2  923.58  5898.5  932.05
  5934.4  942.87  6032.6  938.88  6068.6  946.32  6314.5  968.53  6431.9  969.42
#Mann= 7 ,-1 , 0
  2928.3     .05       0    3135     .12       0  3518.2     .05       0
  4723.8     .12       0  4996.6     .07       0    5011     .12       0
  5199.3     .05       0
Bank Sta=4996.6,5011
XS Rating Curve= 0 ,0
Exp/Cntr=0.3,0.1

Type RM Length L Ch R = 1 ,11565   ,462,462,462
BEGIN DESCRIPTION:
Upper Denton 93 23.0
END DESCRIPTION:
XS GIS Cut Line= 3
      2232793.96      7236581.85        2231379.        7237710.
      2230124.67      7238469.88
#Sta/Elev= 30
  3190.9  1001.4    3225 1000.49  3404.1  995.47  3499.3  994.98  3542.5   992.1
  3598.5  986.94    3613  983.31  3720.3  976.08    3749  971.62    3834  968.78
  3840.4  965.12  3854.8   967.4  4004.7  958.64  4054.1  957.63  4224.7  945.49
  4445.7  934.23  4586.3  922.55  4850.8     916    4987  917.23  5001.1  914.59
  5003.1  914.09  5015.5  914.59  5023.8   917.6  5347.7  917.06  5626.9  918.77
  5685.1  921.94  5764.6  920.18  6016.2  938.28  6368.5  967.38  6467.1  963.75
#Mann= 10 ,-1 , 0
  3190.9     .05       0    3225     .12       0  3404.1     .05       0
    3749     .12       0  4004.7     .05       0  4586.3     .12       0
  5001.1     .07       0  5015.5     .12       0  5347.7     .05       0
  6016.2     .12       0
Bank Sta=5001.1,5015.5
XS Rating Curve= 0 ,0
Exp/Cntr=0.3,0.1

Type RM Length L Ch R = 1 ,11103   ,440,440,440
BEGIN DESCRIPTION:
Upper Denton 93 22.0
END DESCRIPTION:
XS GIS Cut Line= 3
      2231829.02      7237009.99        2231229.        7237310.
      2230028.98      7237910.01
#Sta/Elev= 30
  4324.6  945.35  4570.6  930.17  4623.7  924.92  4651.6  925.37  4757.9  919.13
  4785.8  919.87  4867.2  916.22    4892  915.12  4998.2  916.66  5003.8  915.28
  5076.5  916.95    5167  914.88    5169  914.38  5181.7  914.88    5233  916.43
  5375.6  915.29    5686  919.76    5725  920.93  5755.7  919.64  5814.4  924.21
  5859.1  925.63  5945.8  933.31  6001.7  941.43  6068.8  948.55  6135.8  951.86
  6149.8   950.8  6166.6  953.22  6194.5  952.89  6233.7  956.27  6337.1   961.4
#Mann= 6 ,-1 , 0
  4324.6     .05       0  4867.2     .12       0    5167     .07       0
  5181.7     .12       0    5686     .05       0  5945.8     .12       0
Bank Sta=5167,5181.7
XS Rating Curve= 0 ,0
Exp/Cntr=0.3,0.1

Type RM Length L Ch R = 1 ,10663   ,468,468,468
BEGIN DESCRIPTION:
Upper Denton 93 21.0
END DESCRIPTION:
XS GIS Cut Line= 3
        2231629.        7236360.        2231029.        7236960.
      2230128.99      7237760.01
#Sta/Elev= 30
  4146.5  954.07  4344.5  936.92  4372.8  937.84  4500.1  930.52  4561.3  929.01
  4980.9  913.64  4994.6  911.15  4996.6  910.65  5009.6  911.15    5023  914.26
    5140  914.92  5193.6  913.64  5214.5  915.43  5357.8  916.16  5422.3  916.22
  5569.1  917.51  5575.8  918.85  5629.3  917.78  5661.1  919.34  5745.5  918.72
    5774  922.45  5830.8  924.95    5845   928.1    5866  928.14  5930.3     934
  5951.2  933.65  5994.7  940.59    6075  946.97  6098.4  949.67  6199.2  957.41
#Mann= 11 ,-1 , 0
  4146.5     .12       0  4561.3     .05       0  4994.6    .033       0
  5009.6     .05       0    5140     .12       0  5357.8     .05       0
  5422.3     .12       0  5629.3     .05       0  5994.7     .12       0
    6075     .05       0  6098.4     .12       0
Bank Sta=4994.6,5009.6
XS Rating Curve= 0 ,0
Exp/Cntr=0.3,0.1

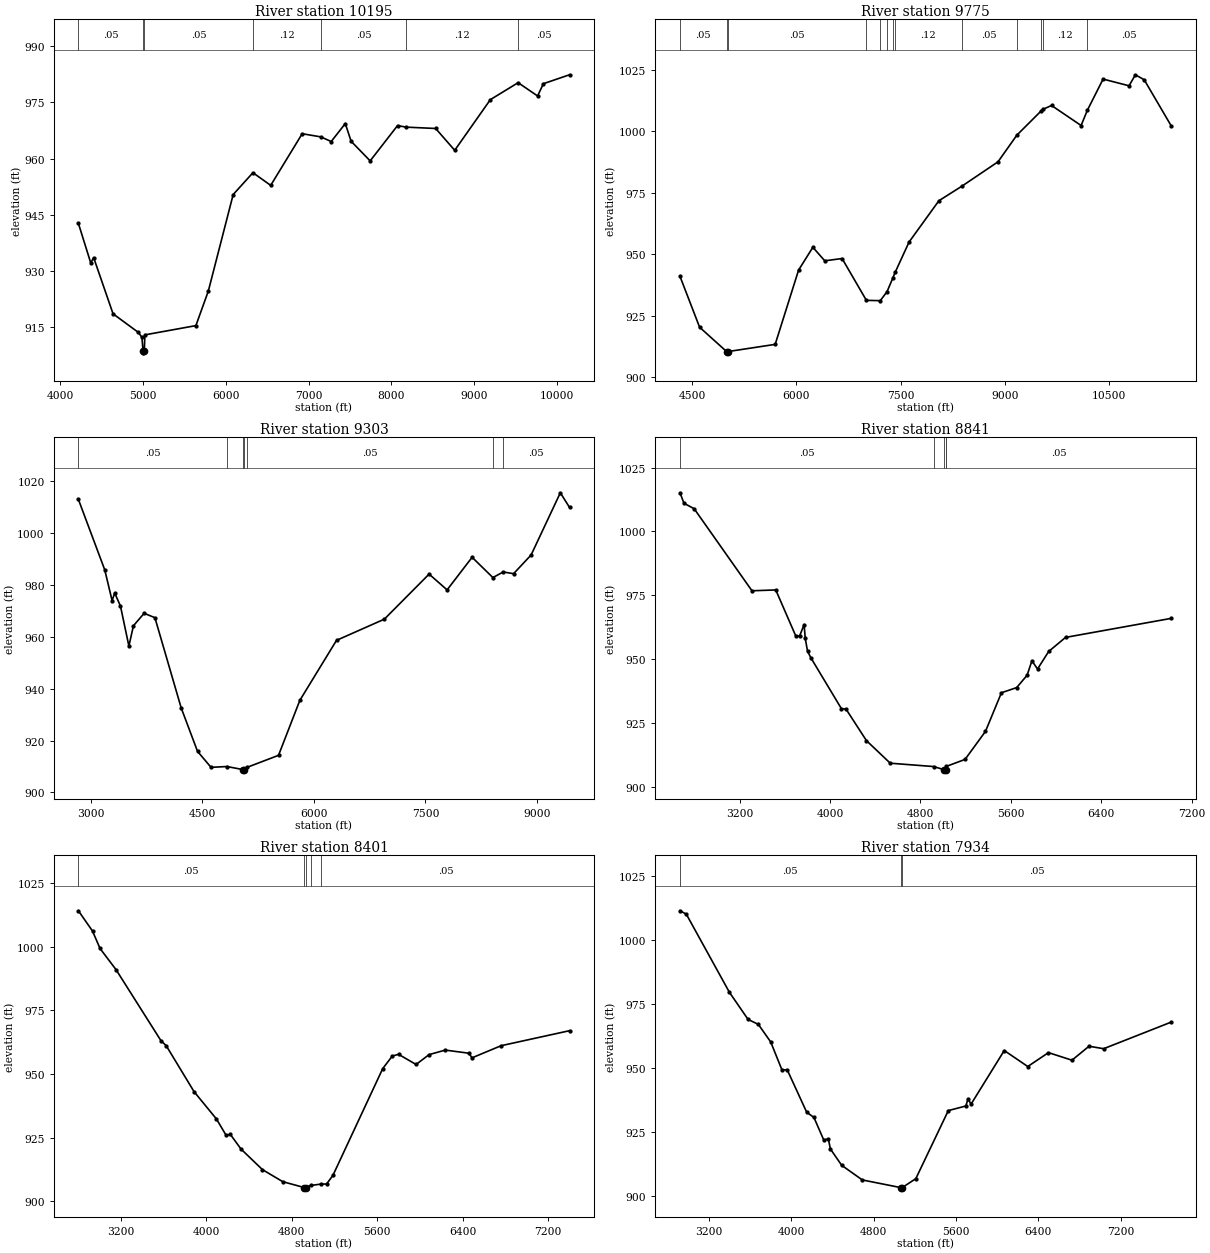
Type RM Length L Ch R = 1 ,10195   ,420,420,420
BEGIN DESCRIPTION:
Upper Denton 93 20.0
END DESCRIPTION:
XS GIS Cut Line= 4
      2231278.98      7236010.02        2230779.        7236610.
      2230123.71      7237520.16      2230327.93      7241544.97
#Sta/Elev= 30
    4219  942.67    4368  932.12  4403.2  933.53  4637.5  918.53  4943.4  913.56
  4986.3  912.24  4999.9  908.61  5001.9  908.11  5014.9  908.61  5022.1  912.91
  5638.2  915.38  5788.6  924.62  6088.6  950.38  6327.2  956.21  6541.9  952.83
  6922.4  966.62  7146.7  965.78  7272.8  964.54    7443  969.33  7513.4   964.6
  7743.4  959.37  8073.9  968.79    8177  968.38  8534.5  968.02  8764.7  962.19
  9195.3  975.72  9530.8  980.25    9766   976.7  9836.1  979.98 10151.5  982.36
#Mann= 7 ,-1 , 0
    4219     .05       0  4999.9    .033       0  5014.9     .05       0
  6327.2     .12       0  7146.7     .05       0    8177     .12       0
  9530.8     .05       0
Bank Sta=4999.9,5014.9
XS Rating Curve= 0 ,0
Exp/Cntr=0.3,0.1

Type RM Length L Ch R = 1 ,9775    ,472,472,472
BEGIN DESCRIPTION:
Upper Denton 93 19.0
END DESCRIPTION:
XS GIS Cut Line= 5
      2231179.01        7235960.        2230579.        7236260.
      2229945.99      7237621.37      2228980.88      7239023.62
      2227602.23      7241909.58
#Sta/Elev= 30
  4322.6  940.96  4604.9  920.31  4994.6   910.4  4996.6   909.9  5009.6   910.4
  5693.4  913.34  6030.4  943.51  6236.3  952.78  6407.6  947.29    6657  948.22
    7007  931.23  7206.7  931.09  7304.6  934.76  7388.3  940.33  7421.3   942.6
  7621.6  954.92  8051.7  971.71  8379.3  977.55  8902.3   987.5  9174.4  998.35
  9519.2 1008.05  9545.4 1008.77  9673.5  1010.4 10099.2 1002.26   10189 1008.43
   10416 1021.12   10790  1018.4 10880.7 1022.87   11008 1020.85 11395.4  1002.2
#Mann= 13 ,-1 , 0
  4322.6     .05       0  4994.6    .033       0  5009.6     .05       0
    7007     .12       0  7206.7     .05       0  7304.6     .12       0
  7388.3     .05       0  7421.3     .12       0  8379.3     .05       0
  9174.4     .12       0  9519.2     .05       0  9545.4     .12       0
   10189     .05       0
Bank Sta=4994.6,5009.6
XS Rating Curve= 0 ,0
Exp/Cntr=0.3,0.1

Type RM Length L Ch R = 1 ,9303    ,462,462,462
BEGIN DESCRIPTION:
Upper Denton 93 18.0
END DESCRIPTION:
XS GIS Cut Line= 4
      2232340.63      7235526.09        2230229.        7236010.
      2229449.96      7236116.38      2226508.48      7238281.09
#Sta/Elev= 30
  2833.3 1012.88  3187.7  985.74  3286.4  973.92  3321.6  976.83  3399.2  971.77
  3512.1  956.41  3573.6  964.23  3717.3  969.02  3862.1  967.33  4215.5  932.58
  4435.2  915.84    4617  909.68  4831.5  909.99  5042.6  908.83  5044.6  908.33
  5057.6  908.83  5101.8  909.68  5524.5   914.3  5811.6   935.5  6304.5   958.6
  6947.9  966.76  7549.6  984.12  7791.8  978.04  8128.1   990.6  8407.7  982.78
  8546.2  984.94  8685.9  984.28  8921.9   991.5  9314.6 1015.45  9438.1 1009.82
#Mann= 7 ,-1 , 0
  2833.3     .05       0  4831.5     .12       0  5042.6     .07       0
  5057.6     .12       0  5101.8     .05       0  8407.7     .12       0
  8546.2     .05       0
Bank Sta=5042.6,5057.6
XS Rating Curve= 0 ,0
Exp/Cntr=0.3,0.1

Type RM Length L Ch R = 1 ,8841    ,440,440,440
BEGIN DESCRIPTION:
Upper Denton 93 17.0
END DESCRIPTION:
XS GIS Cut Line= 4
      2232383.99      7235439.29        2230079.        7235610.
      2229563.98      7235652.92      2228573.65      7236801.65
#Sta/Elev= 30
  2672.7 1015.15  2707.8 1011.04    2798 1008.91  3309.4  976.77    3520   977.1
  3696.6  959.11  3730.6  959.01  3770.7  963.54  3780.7  958.19  3800.8  953.17
  3829.5   950.6  4100.3  930.64  4141.7  930.43  4322.2  918.09  4532.8  909.25
  4916.3  907.94  5005.9  906.76  5007.9  906.26  5022.3  906.76  5026.6  907.96
  5194.7  910.74  5375.4  921.72  5516.4  936.84  5651.4  938.86  5743.5  943.69
  5786.3  949.37  5835.7  946.13  5934.4     953  6083.6  958.51  7017.5  965.96
#Mann= 5 ,-1 , 0
  2672.7     .05       0  4916.3     .12       0  5005.9     .07       0
  5022.3     .12       0  5026.6     .05       0
Bank Sta=5005.9,5022.3
XS Rating Curve= 0 ,0
Exp/Cntr=0.3,0.1

Type RM Length L Ch R = 1 ,8401    ,467,467,467
BEGIN DESCRIPTION:
Upper Denton 93 16.0
END DESCRIPTION:
XS GIS Cut Line= 4
      2232271.15      7235309.08        2230079.        7235210.
      2229422.95      7235249.53      2228416.99       7236680.6
#Sta/Elev= 30
  2800.8 1014.12  2933.1 1006.15  3003.2  999.33  3153.3  991.01  3573.7  963.15
  3623.8  961.13  3884.1  943.12  4094.3  932.37  4184.4  925.99  4224.7   926.3
  4324.5  920.56  4524.7  912.51  4714.9  907.78  4916.9  905.46  4918.9  904.96
  4933.4  905.46  4975.5  906.28  5077.6  906.84  5125.4  906.84  5185.5  910.26
  5651.9  952.18  5741.1  957.07  5799.7  957.78  5964.2  953.78  6086.1  957.65
  6237.7  959.43  6459.8   958.2  6487.8  956.38  6761.4  961.16  7401.7  967.04
#Mann= 5 ,-1 , 0
  2800.8     .05       0  4916.9     .07       0  4933.4     .05       0
  4975.5     .12       0  5077.6     .05       0
Bank Sta=4916.9,4933.4
XS Rating Curve= 0 ,0
Exp/Cntr=0.3,0.1

Type RM Length L Ch R = 1 ,7934    ,390,390,390
BEGIN DESCRIPTION:
Upper Denton 93 15.0
END DESCRIPTION:
XS GIS Cut Line= 4
       2232210.4      7234805.61        2230129.        7234760.
      2229580.31      7234775.63       2228330.4      7236515.37
#Sta/Elev= 30
  2918.1  1011.3  2979.5 1009.98  3398.6  979.51  3579.7  968.96  3679.7  967.02
  3799.7  960.18  3909.7   949.2  3959.8  949.35  4149.8  932.76  4219.8  930.75
  4315.1  921.97  4359.8  922.38  4379.9  918.45  4489.9  912.08  4689.9  906.39
  5061.7  903.42  5063.7  902.92  5078.3  903.42  5210.1  906.89  5525.9  933.42
  5696.4  935.21  5717.2     938  5746.7  935.92  6069.6  956.83    6298   950.6
  6499.3  956.01  6727.7  953.06  6893.4   958.5  7035.8  957.54  7691.1  967.89
#Mann= 3 ,-1 , 0
  2918.1     .05       0  5061.7    .033       0  5078.3     .05       0
Bank Sta=5061.7,5078.3
XS Rating Curve= 0 ,0
Exp/Cntr=0.3,0.1

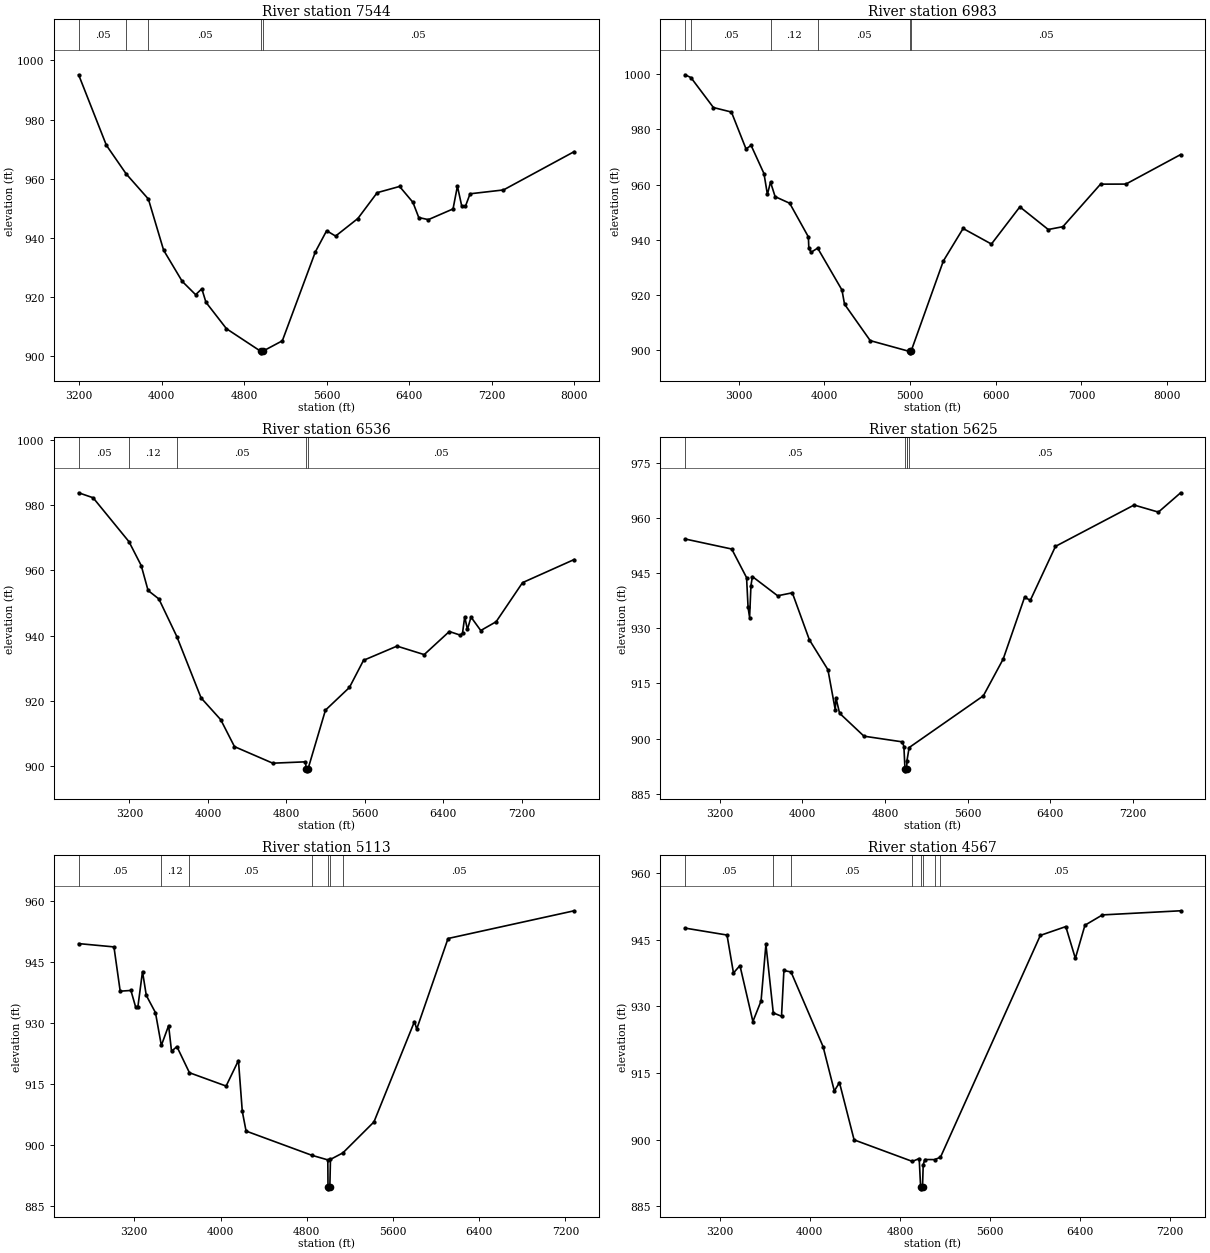
Type RM Length L Ch R = 1 ,7544    ,561,561,561
BEGIN DESCRIPTION:
Upper Denton 93 14.0
END DESCRIPTION:
XS GIS Cut Line= 4
      2231932.55      7234293.46      2230109.69      7234371.58
      2229536.77      7234397.63       2228191.3      7236394.13
#Sta/Elev= 30
  3194.4  995.14  3463.5  971.31  3655.8  961.61  3870.7  953.13  4018.7  935.82
  4198.9  925.29    4329  920.78  4389.1  922.77  4429.1  918.22  4627.9  909.28
  4961.2  901.62  4963.2  901.12  4977.9  901.62  5169.8  905.19  5490.1  935.26
  5599.4  942.41  5686.3   940.6  5902.2  946.54  6089.7  955.28  6306.8  957.38
  6435.9  952.03  6492.9  946.87  6585.9  946.16  6825.3  949.78  6867.7  957.48
  6909.7  950.75  6945.9  950.72  6990.6   954.9  7314.5   956.2    8000  969.15
#Mann= 5 ,-1 , 0
  3194.4     .05       0  3655.8     .12       0  3870.7     .05       0
  4961.2    .033       0  4977.9     .05       0
Bank Sta=4961.2,4977.9
XS Rating Curve= 0 ,0
Exp/Cntr=0.3,0.1

Type RM Length L Ch R = 1 ,6983    ,447,447,447
BEGIN DESCRIPTION:
Upper Denton 93 13.0
END DESCRIPTION:
XS GIS Cut Line= 4
      2232609.64      7233876.79        2229979.        7233910.
      2229597.53      7233972.28      2228035.12      7236255.14
#Sta/Elev= 30
  2373.7  999.69  2441.7  998.68  2704.4  987.84  2914.4  986.21  3084.4   972.9
  3144.4  974.12  3294.4  963.95  3334.4   956.4  3370.6  960.88  3424.4  955.61
  3594.4  953.22  3812.8  941.04  3817.8  936.91  3844.5  935.48  3920.7  936.99
  4204.5  921.84  4234.5  916.71  4534.5  903.53  4993.7  899.61  4995.7  899.11
  5010.4  899.61  5387.8  932.33  5618.5  944.09    5949  938.46  6280.8  951.91
  6612.2  943.72  6783.1  944.74  7222.6  960.13  7518.5  960.15  8157.4  970.83
#Mann= 6 ,-1 , 0
  2373.7     .12       0  2441.7     .05       0  3370.6     .12       0
  3920.7     .05       0  4993.7     .04       0  5010.4     .05       0
Bank Sta=4993.7,5010.4
XS Rating Curve= 0 ,0
Exp/Cntr=0.3,0.1

Type RM Length L Ch R = 1 ,6536    ,911,911,911
BEGIN DESCRIPTION:
Upper Denton 93 12.0
END DESCRIPTION:
XS GIS Cut Line= 5
      2232236.47      7233642.42        2229929.        7233510.
      2229719.06      7233494.85      2229571.49      7233842.07
      2228234.66      7235534.82
#Sta/Elev= 30
    2681  983.85  2828.7  982.32  3194.5  968.83  3319.5   961.5  3389.6  953.83
  3499.8  951.23  3682.7  939.69  3930.5  920.82  4130.9  914.13  4271.1  905.86
  4661.7  900.77  4994.8  901.19    5004  898.92    5006  898.42  5020.7  898.92
  5199.2  917.06  5443.9  924.04  5587.9  932.38  5929.4  936.74  6206.7  934.13
  6463.2  941.23    6577  940.09  6597.8  940.74  6620.3  945.74  6647.8  941.87
  6684.5  945.66  6783.8  941.53  6940.8  944.23  7210.2  956.24    7737  963.34
#Mann= 5 ,-1 , 0
    2681     .05       0  3194.5     .12       0  3682.7     .05       0
    5004     .04       0  5020.7     .05       0
Bank Sta=5004,5020.7
XS Rating Curve= 0 ,0
Exp/Cntr=0.3,0.1

Type RM Length L Ch R = 1 ,5625    ,512,512,512
BEGIN DESCRIPTION:
Upper Denton 93 10.0
END DESCRIPTION:
XS GIS Cut Line= 3
      2231802.38      7231541.74        2230079.        7232810.
      2228001.64      7234466.01
#Sta/Elev= 30
    2865  954.28  3316.2  951.55    3460  943.77  3474.6  935.65  3489.3  932.92
  3502.4  941.61  3516.3  944.06  3760.8  938.83  3902.8  939.64  4067.9  926.85
  4247.4  918.72  4318.6   907.8  4324.8  911.11  4360.3  906.88  4596.3  900.64
  4968.1  899.09  4982.8  897.83  4993.2  891.71  4995.2  891.21  5010.1  891.71
  5011.9  893.88  5033.5  897.54  5751.8  911.62    5944  921.63  6150.6   938.4
  6206.9  937.62  6449.9  952.27  7210.7  963.52  7446.1  961.59  7661.4  966.85
#Mann= 5 ,-1 , 0
    2865     .05       0  4993.2     .04       0  5010.1     .05       0
  5011.9      .1       0  5033.5     .05       0
Bank Sta=4993.2,5010.1
XS Rating Curve= 0 ,0
Exp/Cntr=0.3,0.1

Type RM Length L Ch R = 1 ,5113    ,546,546,546
BEGIN DESCRIPTION:
Upper Denton 93 9.0
END DESCRIPTION:
XS GIS Cut Line= 3
      2231646.16      7230986.16        2229829.        7232410.
       2228131.2      7233945.63
#Sta/Elev= 30
  2683.4  949.48  3011.1  948.67    3069  937.81  3168.4  937.99  3211.8  933.98
  3232.6  933.86    3276  942.63  3311.2  936.77  3396.2  932.55  3450.9   924.5
  3518.3  929.37  3545.4  923.07  3595.2  924.22  3711.5  917.81  4051.8  914.54
  4166.2   920.8  4201.8  908.35    4237   903.5    4846  897.57  4995.3  896.43
  4997.2  889.83  4999.2  889.33  5014.3  889.83    5020  896.55  5135.3  898.15
  5423.5  905.74  5799.3  930.36  5820.3  928.51  6110.9  950.73  7281.2  957.53
#Mann= 7 ,-1 , 0
  2683.4     .05       0  3450.9     .12       0  3711.5     .05       0
    4846      .1       0  4997.2     .07       0  5014.3      .1       0
  5135.3     .05       0
Bank Sta=4997.2,5014.3
XS Rating Curve= 0 ,0
Exp/Cntr=0.3,0.1

Type RM Length L Ch R = 1 ,4567    ,574,574,574
BEGIN DESCRIPTION:
Upper Denton 93 8.0
END DESCRIPTION:
XS GIS Cut Line= 3
      2231403.11      7230821.22        2229629.        7231960.
      2227948.24      7233520.88
#Sta/Elev= 30
  2892.1  947.58  3264.4  946.02  3321.8  937.48  3379.3  939.15  3494.3  926.56
  3566.9  931.17    3610  943.92  3675.4   928.5  3748.6  927.74  3769.8  938.04
    3833  937.71  4117.9   920.9  4217.7  910.92  4263.3  912.82  4393.4  899.92
    4911  895.07  4971.5  895.72  4984.1   889.4  4986.1   888.9  5001.2   889.4
  5007.3  894.33  5021.5   895.5  5107.6  895.48  5160.6  896.01  6047.6  945.94
  6273.8  947.92  6358.8  940.77  6443.9  948.23  6599.2  950.55    7294  951.48
#Mann= 8 ,-1 , 0
  2892.1     .05       0  3675.4     .12       0    3833     .05       0
    4911     .12       0  4984.1     .07       0  5001.2     .12       0
  5107.6      .1       0  5160.6     .05       0
Bank Sta=4984.1,5001.2
XS Rating Curve= 0 ,0
Exp/Cntr=0.3,0.1