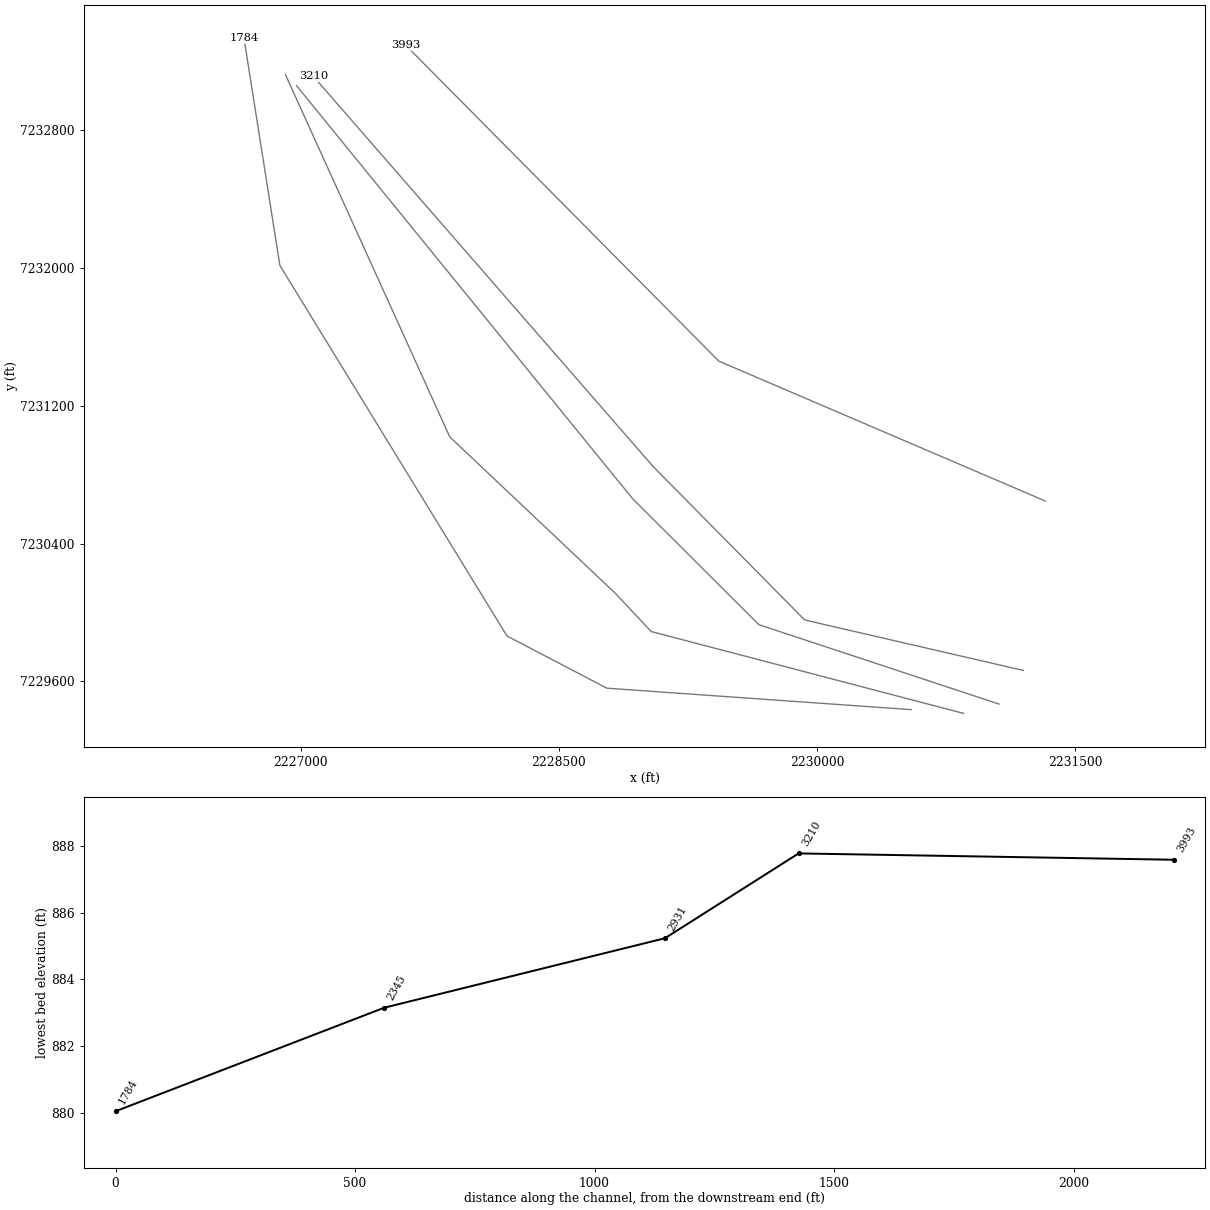
HEC-RAS study Upper Denton 93.prj: Upper Denton 93 Base Level Engineering

--- Upper Denton 93.g01 (geometry) --- (continued)

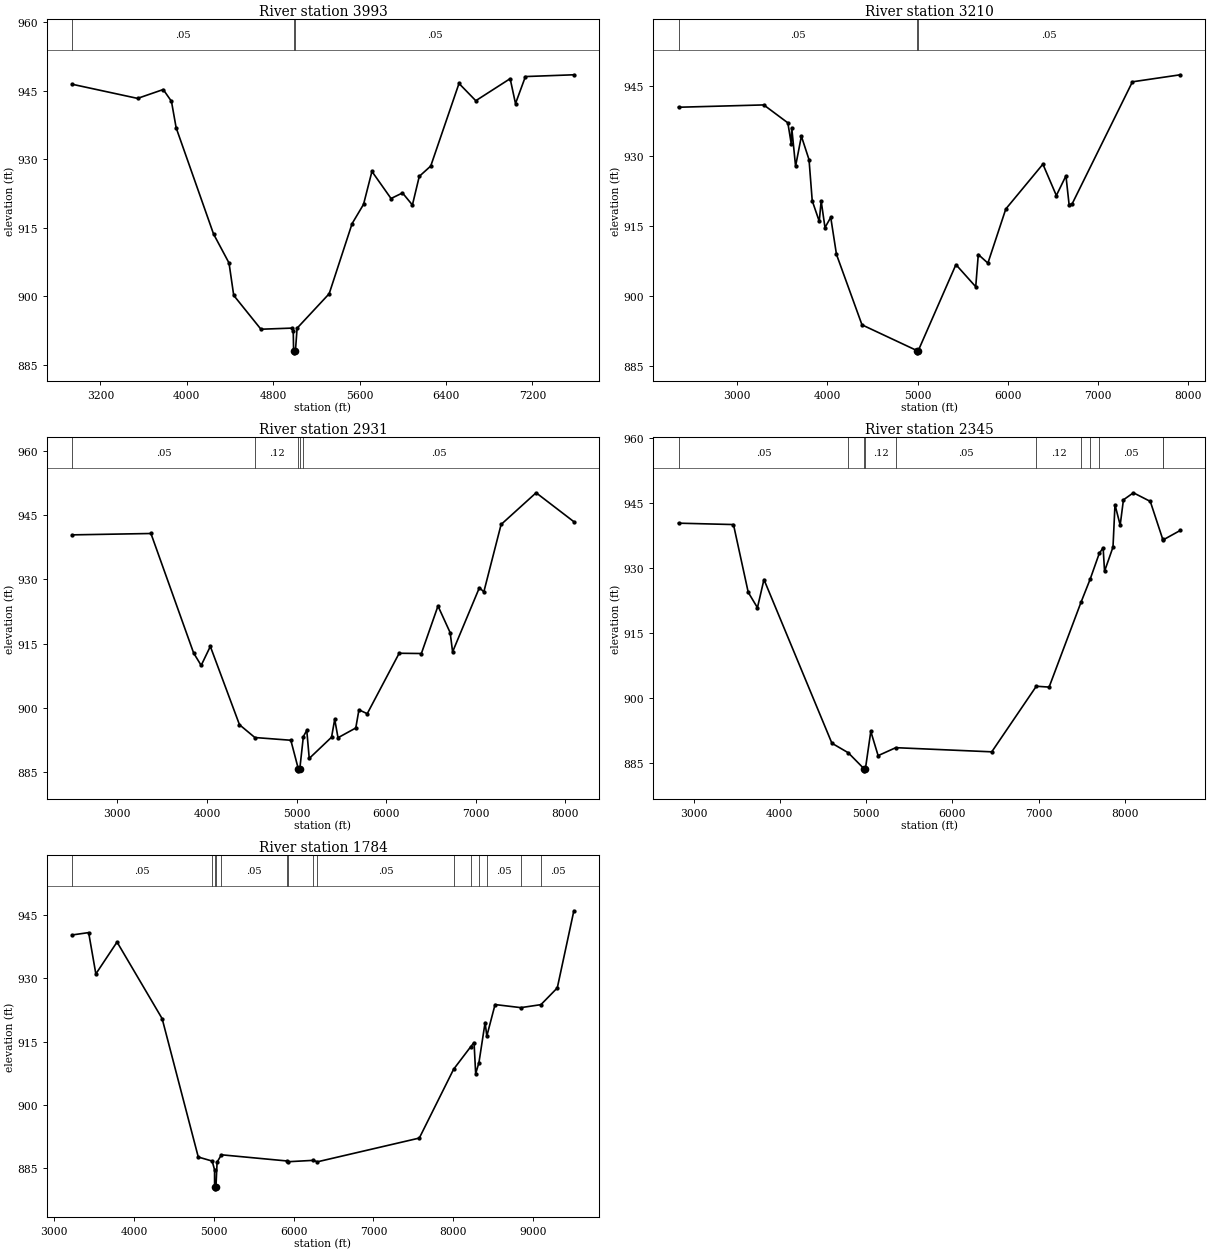
Type RM Length L Ch R = 1 ,3993    ,783,783,783
BEGIN DESCRIPTION:
Upper Denton 93 7.0
END DESCRIPTION:
XS GIS Cut Line= 3
      2231324.92      7230647.64        2229429.        7231460.
      2227609.82      7233295.07
#Sta/Elev= 30
  2937.4  946.39  3543.9  943.29  3781.5  945.23  3857.7  942.65  3901.2  936.85
  4247.5   913.6  4390.8  907.25  4434.3  900.16  4686.3  892.75  4978.3     893
  4985.5  892.27  4988.8  888.08  4990.8  887.58  5005.9  888.08  5021.2  892.98
  5318.2  900.52  5530.4  915.87  5636.4  920.09  5714.2   927.3    5891  921.37
  5997.1  922.59    6089  919.95  6152.6  926.22  6258.7  928.48  6520.4  946.56
  6675.9  942.78  6994.1  947.61  7043.6  942.15  7135.5  948.07    7584  948.46
#Mann= 3 ,-1 , 0
  2937.4     .05       0  4988.8     .04       0  5005.9     .05       0
Bank Sta=4988.8,5005.9
XS Rating Curve= 0 ,0
Exp/Cntr=0.3,0.1

Type RM Length L Ch R = 1 ,3210    ,279,279,279
BEGIN DESCRIPTION:
Upper Denton 93 6.0
END DESCRIPTION:
XS GIS Cut Line= 4
      2231197.31      7229663.26      2229927.83      7229956.22
      2229048.92      7230845.98      2227074.12      7233113.74
#Sta/Elev= 30
  2351.4  940.49    3296  940.99  3562.8  937.14  3600.5  932.63  3605.6  936.12
  3648.4  927.83  3712.7  934.28  3797.5  929.24  3832.9  920.41  3910.7     916
  3931.9  920.38  3974.3  914.66    4038  916.85  4101.6   908.9  4384.4  893.78
  4991.4  888.27  4993.4  887.77  5008.7  888.27  5425.4  906.71  5644.7  901.96
  5673.2  908.88  5779.6  907.03    5978  918.65  6389.1  928.27  6538.2  921.54
  6644.5  925.77  6679.6  919.56  6714.7  919.81  7381.2  945.95    7912  947.46
#Mann= 3 ,-1 , 0
  2351.4     .05       0  4991.4    .033       0  5008.7     .05       0
Bank Sta=4991.4,5008.7
XS Rating Curve= 0 ,0
Exp/Cntr=0.3,0.1

Type RM Length L Ch R = 1 ,2931    ,586,586,586
BEGIN DESCRIPTION:
Upper Denton 93 5.0
END DESCRIPTION:
XS GIS Cut Line= 4
      2231056.33      7229467.93      2229661.72      7229928.84
        2228929.        7230660.      2226976.43      7233059.53
#Sta/Elev= 30
  2496.2   940.4    3376  940.72    3852  912.79  3936.3  909.87  4038.5  914.33
  4363.7  896.01  4535.2  893.02  4936.5  892.38  5019.5  885.73  5021.5  885.23
  5036.8  885.73  5076.3  893.24  5114.3   894.7  5141.9  888.13  5390.8  893.09
    5426  897.28  5462.7  892.97  5660.9  895.25  5696.3   899.5  5788.7  898.59
  6144.9  912.72  6392.7  912.66    6578  923.77  6713.8  917.54    6741  913.05
  7039.8  928.05  7089.4  927.07  7282.1  942.83  7672.5  950.24  8093.7  943.48
#Mann= 5 ,-1 , 0
  2496.2     .05       0  4535.2     .12       0  5019.5     .07       0
  5036.8     .12       0  5076.3     .05       0
Bank Sta=5019.5,5036.8
XS Rating Curve= 0 ,0
Exp/Cntr=0.3,0.1

Type RM Length L Ch R = 1 ,2345    ,561,561,561
BEGIN DESCRIPTION:
Upper Denton 93 4.0
END DESCRIPTION:
XS GIS Cut Line= 5
      2230850.17      7229413.68      2229036.01      7229889.19
        2228829.        7230110.       2227866.2      7231019.59
      2226911.34      7233124.62
#Sta/Elev= 30
  2826.5  940.35  3463.1  940.03  3634.1  924.38  3740.7  920.83  3816.3  927.33
  4603.6  889.53  4793.4  887.32  4974.7  883.65  4976.7  883.15    4992  883.65
  5054.2  892.26  5139.1  886.66  5343.5   888.5  6455.7  887.54  6971.9  902.69
  7120.2  902.49  7489.4  922.06  7595.6   927.4  7701.7  933.39  7746.1  934.66
  7762.6  929.25  7860.5  934.83  7883.5  944.62  7943.7   939.9  7981.4  945.74
  8096.8  947.37  8292.4  945.38  8434.6  936.77  8444.7  936.52  8640.6  938.68
#Mann= 11 ,-1 , 0
  2826.5     .05       0  4793.4     .12       0  4974.7     .07       0
    4992     .12       0  5343.5     .05       0  6971.9     .12       0
  7489.4     .05       0  7595.6     .12       0  7701.7     .05       0
  8434.6     .12       0  8444.7     .05       0
Bank Sta=4974.7,4992
XS Rating Curve= 0 ,0
Exp/Cntr=0.3,0.1

Type RM Length L Ch R = 1 ,1784    ,0,0,0
BEGIN DESCRIPTION:
Upper Denton 93 3.0
END DESCRIPTION:
XS GIS Cut Line= 5
      2230546.28      7229435.39        2228779.        7229560.
      2228198.54      7229863.04       2226879.1      7232015.82
      2226670.78      7233335.15
#Sta/Elev= 30
  3224.2  940.31    3432  940.87  3522.2  931.06  3787.6  938.63  4352.7  920.45
  4805.4   887.6  4979.8  886.64  5009.7  884.55  5009.8  880.55  5011.8  880.05
  5027.1  880.55    5041  886.38  5095.2  888.13  5914.5  886.67  5935.4  886.49
  6244.4  886.81  6298.9  886.47  7574.8   892.1  8004.8  908.44  8217.8  913.75
  8260.8  914.78  8281.1  907.38  8322.2  910.03  8399.1  919.52  8420.8  916.31
    8524  923.79  8847.3  923.06  9098.7  923.77  9303.6  927.74  9511.3  946.05
#Mann= 15 ,-1 , 0
  3224.2     .05       0  4979.8     .12       0  5009.8     .07       0
  5027.1     .12       0  5095.2     .05       0  5914.5     .12       0
  5935.4     .05       0  6244.4     .12       0  6298.9     .05       0
  8004.8     .12       0  8217.8     .05       0  8322.2     .12       0
  8420.8     .05       0  8847.3     .12       0  9098.7     .05       0
Bank Sta=5009.8,5027.1
XS Rating Curve= 0 ,0
Exp/Cntr=0.3,0.1

Chan Stop Cuts=-1
Use User Specified Reach Order=0
Composite Channel Slope=5