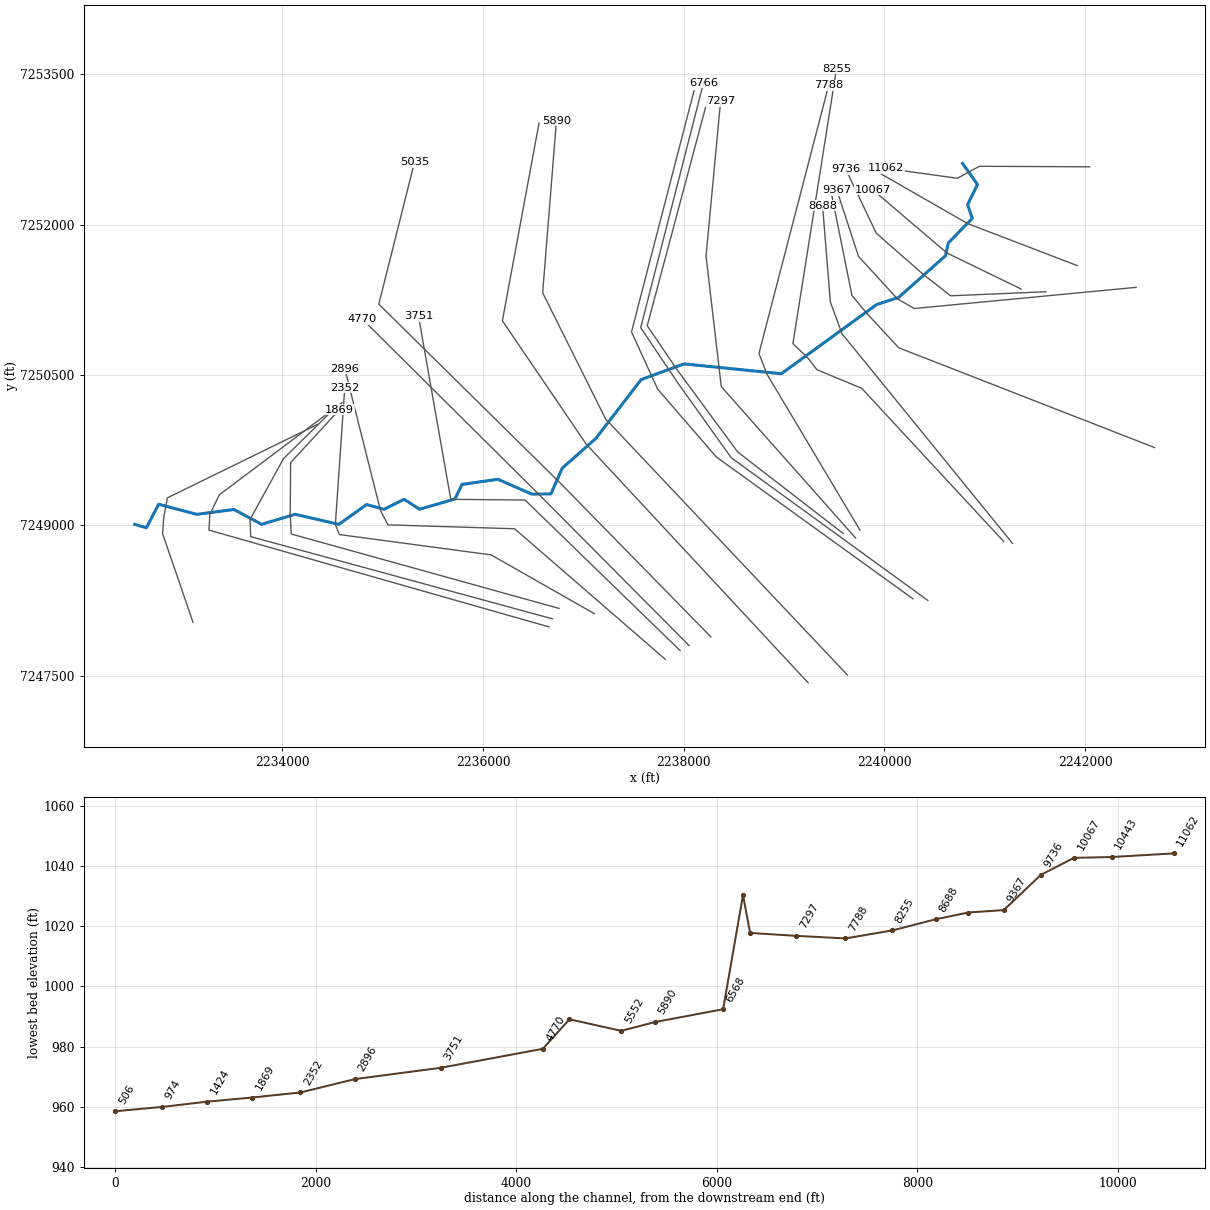
--- Upper Denton 94.prj (project) ---

Proj Title=Upper Denton 94 Base Level Engineering
Current Plan=p01
Default Exp/Contr=0.3,0.1
English Units
Geom File=g01
Flow File=f01
Plan File=p01
Y Axis Title=Elevation
X Axis Title(PF)=Main Channel Distance
X Axis Title(XS)=Station
BEGIN DESCRIPTION:
Upper Denton 94
END DESCRIPTION:
DSS Export Rating Curves= 0
DSS Export Rating Curve Sorted= 0
DSS Export Volume Flow Curves= 0
DXF OffsetX= 0
DXF OffsetY= 0
DXF ScaleX= 1
DXF ScaleY= 10

--- Upper Denton 94.p01 (plan) ---

Plan Title=Multiple Run
Short Identifier=Multiple
Geom File=g01
Flow File=f01
Subcritical Flow
K Sum by GR= 0
Std Step Tol= 0.01
Critical Tol= 0.01
Num of Std Step Trials= 20
Max Error Tol= 0.3
Flow Tol Ratio= 0.001
Split Flow NTrial= 30
Split Flow Tol= 0.02
Split Flow Ratio= 0.02
Log Output Level= 0
Friction Slope Method= 1
Unsteady Friction Slope Method= 2
Unsteady Bridges Friction Slope Method= 1
Parabolic Critical Depth
Global Vel Dist=  1 , 1 , 1
Global Log Level= 0
CheckData=True
Encroach Param= -1, 0, 0, 0
BEGIN DESCRIPTION:
Multiple Run
END DESCRIPTION:

--- Upper Denton 94.f01 (steady flow) ---

Flow Title=Multiple
Number of Profiles=7
Profile Names=10-year,25-year,50-year,1pct_min,100-year,1pct_plu,500-year
River Rch & RM= Upper Denton 94,Reach-1,11062
     898    1286    1621    1015    2026    4042    3171
River Rch & RM= Upper Denton 94,Reach-1,8255
    1326    1932    2463    1557    3106    6198    4959
River Rch & RM= Upper Denton 94,Reach-1,1869
    1361    1982    2526    1596    3184    6353    5078
Boundary for River Rch & Prof#=Upper Denton 94,Reach-1,1
Up Type=0
Dn Type=3
Dn Slope=0.005
Boundary for River Rch & Prof#=Upper Denton 94,Reach-1,2
Up Type=0
Dn Type=3
Dn Slope=0.005
Boundary for River Rch & Prof#=Upper Denton 94,Reach-1,3
Up Type=0
Dn Type=3
Dn Slope=0.005
Boundary for River Rch & Prof#=Upper Denton 94,Reach-1,4
Up Type=0
Dn Type=3
Dn Slope=0.005
Boundary for River Rch & Prof#=Upper Denton 94,Reach-1,5
Up Type=0
Dn Type=3
Dn Slope=0.005
Boundary for River Rch & Prof#=Upper Denton 94,Reach-1,6
Up Type=0
Dn Type=3
Dn Slope=0.005
Boundary for River Rch & Prof#=Upper Denton 94,Reach-1,7
Up Type=0
Dn Type=3
Dn Slope=0.005

--- Upper Denton 94.g01 (geometry) ---

Geom Title=Existing Conditions
Program Version=4.10

River Reach=Upper Denton 94 ,Reach-1
Reach XY= 30
        2240779.        7252610.      2240928.07      7252399.52
      2240829.61      7252199.37      2240875.87      7252061.63
      2240636.86      7251816.17      2240609.53      7251689.46
      2240142.54      7251273.54      2239922.83      7251202.14
      2238973.06      7250512.26        2238004.      7250610.41
       2237576.7      7250454.17      2237123.41      7249865.61
      2236789.35      7249570.12      2236677.55      7249313.53
      2236484.93      7249312.24      2236149.04      7249459.95
      2235790.81      7249408.38      2235720.72      7249263.06
      2235368.35      7249161.04      2235213.78      7249260.09
      2235013.61      7249160.08      2234840.99       7249208.2
      2234563.61      7249010.08        2234129.      7249110.82
      2233794.22      7249010.49       2233518.5      7249158.81
      2233149.03      7249110.07       2232768.3      7249210.71
      2232645.73      7248976.23        2232529.        7249010.

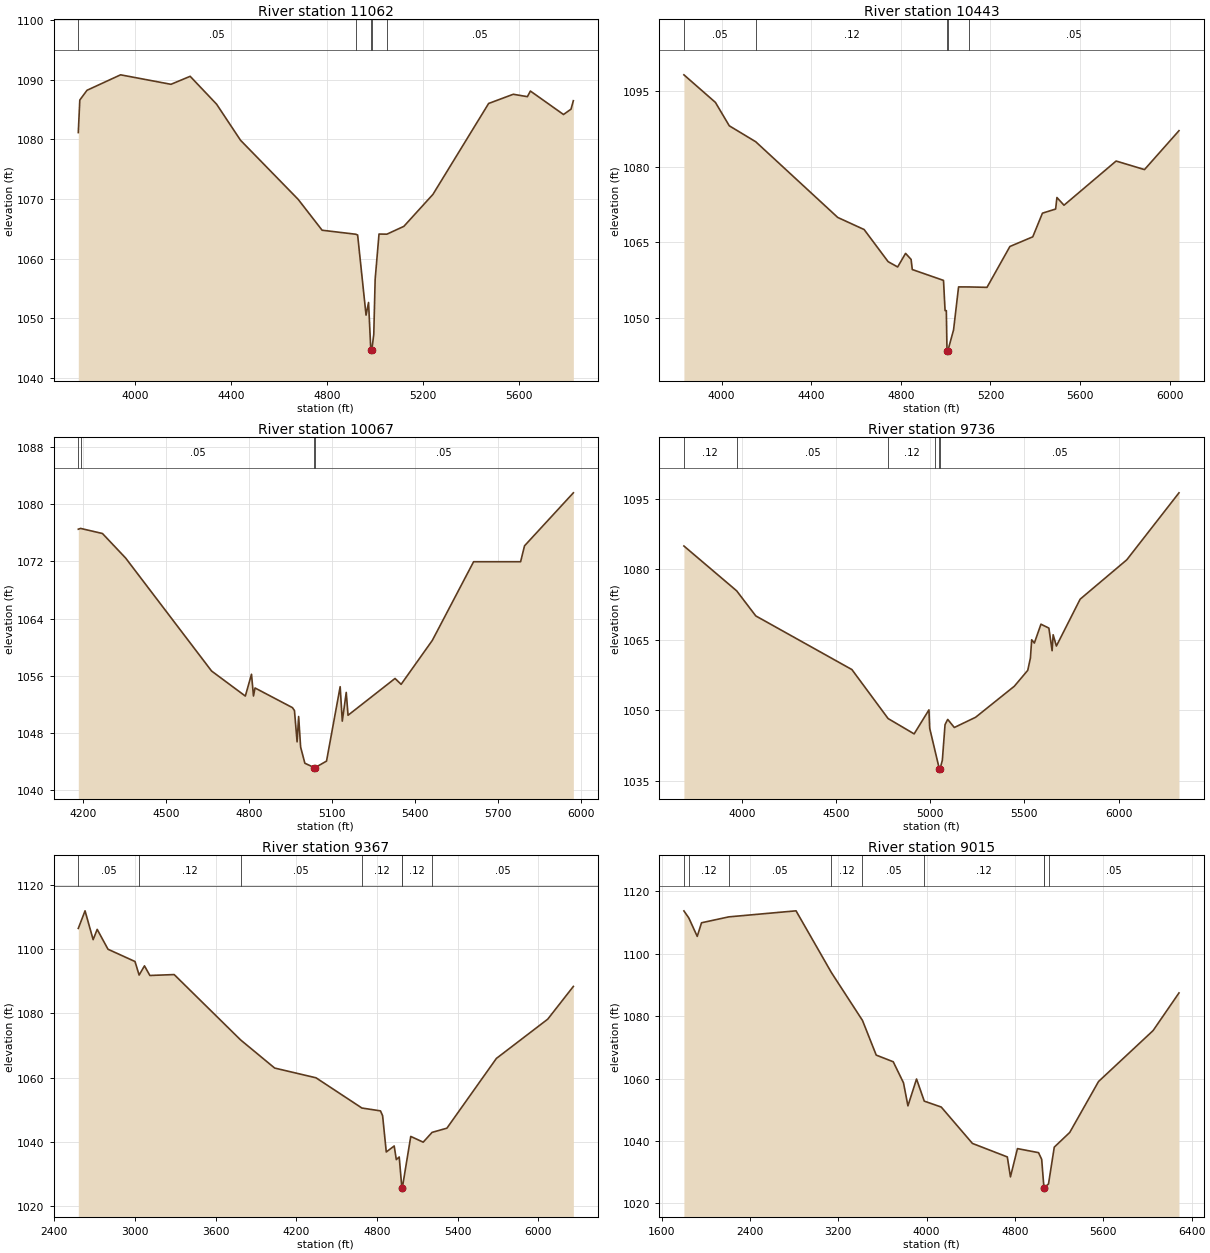
Type RM Length L Ch R = 1 ,11062   ,619,619,619
BEGIN DESCRIPTION:
Upper Denton 94 22.0
END DESCRIPTION:
XS GIS Cut Line= 4
      2242045.34      7252575.74      2240946.39      7252580.95
      2240727.64      7252461.16      2240019.28      7252560.12
#Sta/Elev= 30
  3762.1 1081.14  3768.4 1086.59  3798.4 1088.23  3938.4 1090.82  4148.4 1089.23
  4228.4 1090.57  4338.4 1085.91  4438.4 1079.85  4678.5 1069.95  4778.5 1064.77
  4918.6  1064.1  4926.5 1063.97  4961.6 1050.54    4972 1052.66  4981.5 1044.67
  4981.8 1044.17  4985.5 1044.67  4993.8 1047.33  4999.5 1056.52  5015.6 1064.13
  5048.4 1064.11  5119.2 1065.42  5240.4 1070.78  5472.6 1086.02  5575.2 1087.56
  5634.1 1087.16  5646.7  1088.1  5784.6 1084.17  5815.9 1085.06  5825.7 1086.48
#Mann= 5 ,-1 , 0
  3762.1     .05       0  4918.6     .12       0  4981.5     .07       0
  4985.5     .12       0  5048.4     .05       0
Bank Sta=4981.5,4985.5
XS Rating Curve= 0 ,0
Exp/Cntr=0.3,0.1

Type RM Length L Ch R = 1 ,10443   ,376,376,376
BEGIN DESCRIPTION:
Upper Denton 94 21.0
END DESCRIPTION:
XS GIS Cut Line= 3
      2241920.35      7251591.37        2240829.        7252010.
      2239925.58      7252528.86
#Sta/Elev= 30
  3831.4 1098.27  3972.1 1092.79    4034 1088.14  4152.2 1084.97  4518.3 1069.93
  4636.1 1067.53  4743.2 1061.15  4785.8 1060.09  4821.2 1062.79  4845.9 1061.59
  4851.2 1059.58  4990.6 1057.42  4997.6 1051.42  5003.2 1051.42  5006.2 1043.47
  5006.4 1042.97  5010.2 1043.47  5035.5 1047.59  5057.9 1056.13  5106.5 1056.12
  5184.8 1056.04  5287.1 1064.16  5389.2 1066.08  5432.4 1070.78  5491.3  1071.6
  5497.1 1073.89  5528.7 1072.36  5761.4 1081.14  5888.1 1079.44  6042.1 1087.17
#Mann= 5 ,-1 , 0
  3831.4     .05       0  4152.2     .12       0  5006.2     .07       0
  5010.2     .12       0  5106.5     .05       0
Bank Sta=5006.2,5010.2
XS Rating Curve= 0 ,0
Exp/Cntr=0.3,0.1

Type RM Length L Ch R = 1 ,10067   ,331,331,331
BEGIN DESCRIPTION:
Upper Denton 94 20.0
END DESCRIPTION:
XS GIS Cut Line= 3
      2241363.09      7251356.98      2240623.48      7251716.37
      2239884.87      7252345.75
#Sta/Elev= 30
  4181.2 1076.47  4189.6 1076.58  4268.7 1075.87  4352.5 1072.45  4663.8 1056.67
  4786.1 1053.17  4808.4 1056.22  4815.6 1053.18  4821.2  1054.3  4956.5 1051.56
    4964 1051.15  4973.5 1046.78  4979.1 1050.32  4986.3 1046.05  5001.7 1043.79
  5035.2 1043.19  5035.5 1042.69  5039.2 1043.19  5080.1 1044.09  5129.5 1054.48
  5137.2 1049.67  5151.5 1053.68    5158 1050.49  5328.2 1055.63  5350.2 1054.81
  5463.3 1060.95  5612.7 1071.93  5782.9 1071.93  5797.1 1074.15  5973.9 1081.55
#Mann= 4 ,-1 , 0
  4181.2     .12       0  4189.6     .05       0  5035.2    .033       0
  5039.2     .05       0
Bank Sta=5035.2,5039.2
XS Rating Curve= 0 ,0
Exp/Cntr=0.3,0.1

Type RM Length L Ch R = 1 ,9736    ,369,369,369
BEGIN DESCRIPTION:
Upper Denton 94 19.0
END DESCRIPTION:
XS GIS Cut Line= 5
      2241610.49      7251329.87      2240659.94      7251289.29
        2240379.        7251510.      2239919.78      7251913.17
      2239613.97      7252553.74
#Sta/Elev= 30
  3691.3  1084.9  3971.4 1075.37  4073.1 1070.03  4583.6 1058.62  4775.9  1048.2
  4914.1 1044.94  4992.8 1050.05  4996.8 1046.14  5024.7 1041.42  5047.8 1037.52
  5048.1 1037.02  5051.8 1037.52    5064 1039.33  5078.3 1046.91  5092.5 1048.02
  5127.6  1046.3  5240.5 1048.47  5446.5 1055.08  5517.6 1058.46  5531.8 1061.07
  5538.5 1064.96  5552.7 1064.26  5587.8 1068.27  5629.9 1067.44    5647 1062.63
  5652.6 1066.02  5669.7 1063.62  5795.9 1073.59  6043.8 1081.97  6320.9 1096.21
#Mann= 6 ,-1 , 0
  3691.3     .12       0  3971.4     .05       0  4775.9     .12       0
  5024.7     .05       0  5047.8     .07       0  5051.8     .05       0
Bank Sta=5047.8,5051.8
XS Rating Curve= 0 ,0
Exp/Cntr=0.3,0.1

Type RM Length L Ch R = 1 ,9367    ,352,352,352
BEGIN DESCRIPTION:
Upper Denton 94 18.0
END DESCRIPTION:
XS GIS Cut Line= 5
      2242508.93      7251373.71      2240298.01      7251162.58
        2240129.        7251260.      2239741.79      7251683.25
      2239527.14      7252341.11
#Sta/Elev= 30
  2579.4 1106.44  2629.6 1111.91  2689.8 1102.95    2720 1106.14  2800.3 1099.96
  3001.2 1096.14  3031.8 1091.93  3071.6 1094.79  3111.7  1091.8  3292.6 1092.08
  3786.6 1071.75  4039.8    1063  4347.3 1059.97  4688.5 1050.57  4826.7 1049.68
  4842.5  1048.2  4869.8  1036.9  4928.7 1038.76  4944.5 1034.52    4966 1035.34
  4985.6 1025.84  4985.8 1025.34  4989.6 1025.84  5051.9 1041.73  5144.4 1039.95
  5210.3 1042.99  5320.7  1044.3  5688.8    1066  6070.6 1078.21  6261.1 1088.39
#Mann= 7 ,-1 , 0
  2579.4     .05       0  3031.8     .12       0  3786.6     .05       0
  4688.5     .12       0  4985.6     .07       0  4989.6     .12       0
  5210.3     .05       0
Bank Sta=4985.6,4989.6
XS Rating Curve= 0 ,0
Exp/Cntr=0.3,0.1

Type RM Length L Ch R = 1 ,9015    ,327,327,327
BEGIN DESCRIPTION:
Upper Denton 94 17.0
END DESCRIPTION:
XS GIS Cut Line= 5
      2242691.21      7249776.47      2240143.59      7250770.85
        2239829.        7251110.      2239676.98      7251292.42
       2239470.7      7252319.87
#Sta/Elev= 30
  1802.6 1113.72  1846.9 1111.47  1923.1 1105.56  1962.1 1109.92  2208.2 1111.81
  2817.8 1113.75  3138.5 1093.94  3419.6 1078.61    3544  1067.5  3697.9 1065.37
  3790.9 1058.62  3831.1 1051.23    3909 1059.84    3979 1052.75  4132.7 1050.85
  4415.1 1039.19    4731 1034.86  4759.3 1028.47  4822.8 1037.53  5013.7 1036.23
  5042.3 1034.08  5062.4 1025.04  5062.7 1024.54  5066.4 1025.04    5104 1026.21
  5156.2    1038  5296.2 1042.71  5556.8 1059.03  6050.9 1075.36  6285.4 1087.43
#Mann= 9 ,-1 , 0
  1802.6     .05       0  1846.9     .12       0  2208.2     .05       0
  3138.5     .12       0  3419.6     .05       0    3979     .12       0
  5062.4     .07       0  5066.4     .12       0    5104     .05       0
Bank Sta=5062.4,5066.4
XS Rating Curve= 0 ,0
Exp/Cntr=0.3,0.1

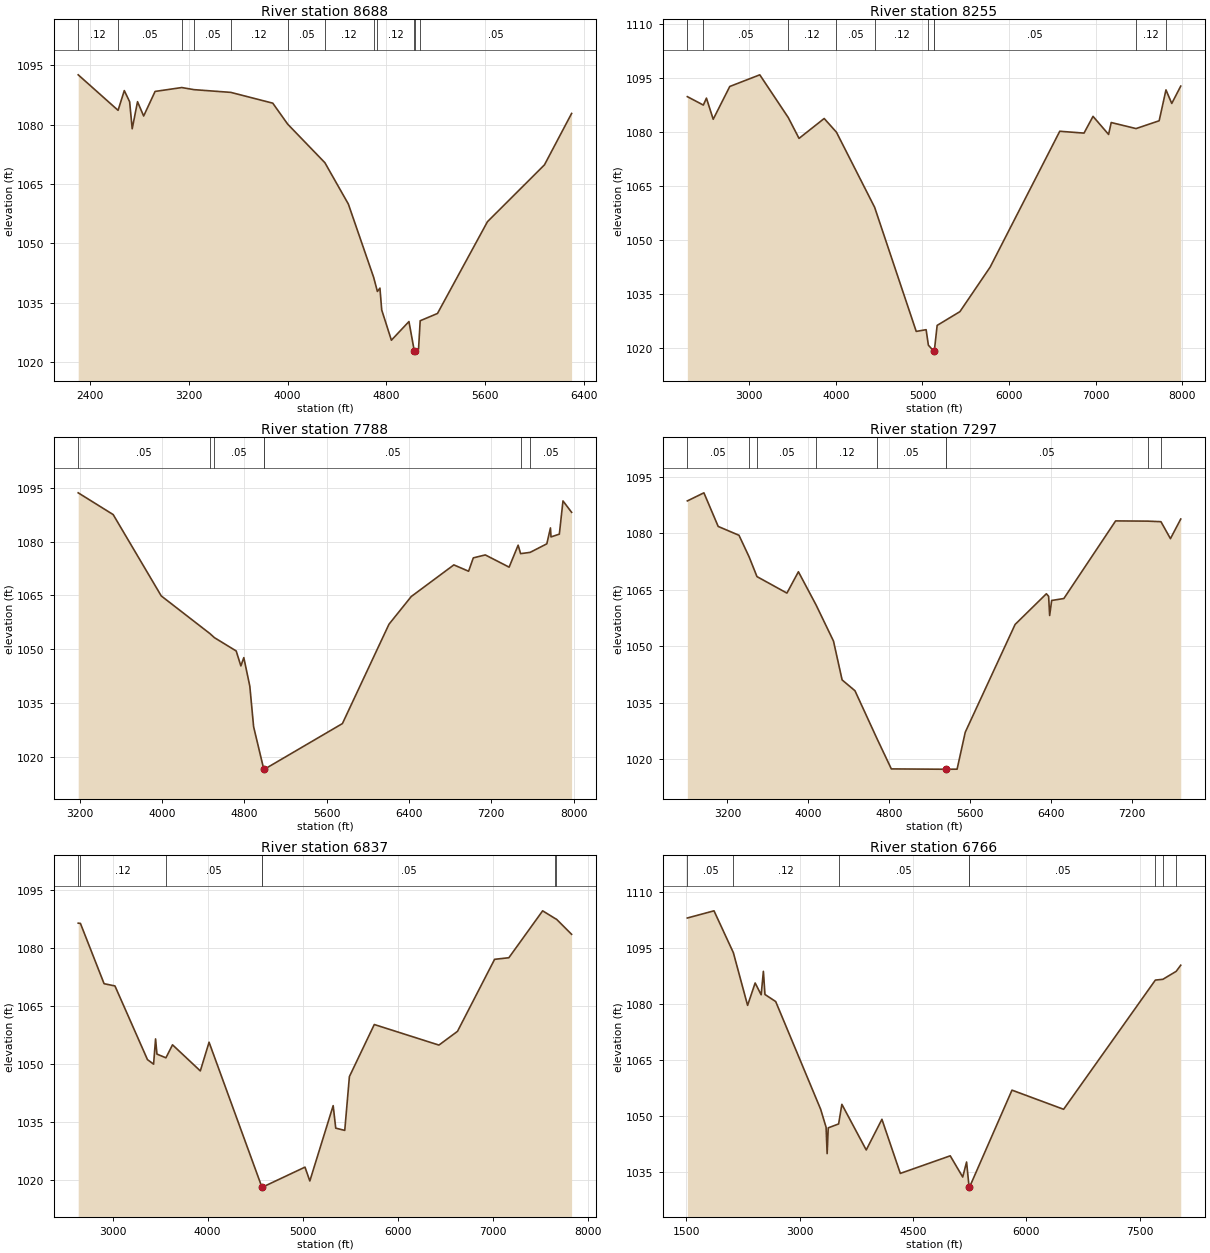
Type RM Length L Ch R = 1 ,8688    ,433,433,433
BEGIN DESCRIPTION:
Upper Denton 94 16.0
END DESCRIPTION:
XS GIS Cut Line= 4
      2241276.26      7248821.62        2239579.        7250910.
      2239462.02      7251226.13      2239383.95      7252188.99
#Sta/Elev= 30
  2304.6 1092.54  2627.3 1083.58  2677.8 1088.56  2720.9 1085.75  2741.7 1078.92
  2784.8 1085.76  2834.4 1082.14    2927 1088.35  3143.4 1089.33  3241.4  1088.8
  3539.7 1088.11  3879.5 1085.39  4000.8 1080.08  4301.6 1070.36  4491.5 1059.93
  4696.6  1041.4  4726.6 1037.87  4747.2 1038.71  4761.6  1033.2  4839.9 1025.56
  4982.1 1030.27  5025.7  1022.8  5025.9  1022.3  5029.7  1022.8  5059.7  1023.3
  5073.1 1030.47  5213.1 1032.31  5617.6 1055.47  6079.1 1069.82  6298.8 1082.79
#Mann= 12 ,-1 , 0
  2304.6     .12       0  2627.3     .05       0  3143.4     .12       0
  3241.4     .05       0  3539.7     .12       0  4000.8     .05       0
  4301.6     .12       0  4696.6     .05       0  4726.6     .12       0
  5025.7     .07       0  5029.7     .12       0  5073.1     .05       0
Bank Sta=5025.7,5029.7
XS Rating Curve= 0 ,0
Exp/Cntr=0.3,0.1

Type RM Length L Ch R = 1 ,8255    ,467,467,467
BEGIN DESCRIPTION:
Upper Denton 94 15.0
END DESCRIPTION:
XS GIS Cut Line= 6
      2241189.45      7248838.98      2239774.52      7250366.76
      2239327.47      7250552.96      2239240.67       7250665.8
      2239088.76      7250813.37      2239522.78      7253552.53
#Sta/Elev= 30
  2286.9 1089.92  2471.4 1087.58  2507.1 1089.51  2585.3 1083.63  2776.4 1092.75
  3122.8 1095.99  3451.2 1084.11  3575.8 1078.31  3866.1 1083.84  4007.6 1080.03
  4448.3 1059.14  4928.3 1024.62  5042.4  1025.1  5068.7 1020.79  5132.3 1019.08
  5132.7 1018.58  5136.6 1019.08  5169.7 1026.29  5432.5 1030.12  5781.4 1042.51
  6584.7 1080.29  6864.7 1079.78  6968.7 1084.44  7148.2 1079.41  7178.6 1082.72
  7465.1 1081.04  7731.8 1083.21  7810.6  1091.8  7877.2 1088.03    7981 1092.85
#Mann= 10 ,-1 , 0
  2286.9     .12       0  2471.4     .05       0  3451.2     .12       0
  4007.6     .05       0  4448.3     .12       0  5068.7     .05       0
  5132.3     .07       0  5136.6     .05       0  7465.1     .12       0
  7810.6     .05       0
Bank Sta=5132.3,5136.6
XS Rating Curve= 0 ,0
Exp/Cntr=0.3,0.1

Type RM Length L Ch R = 1 ,7788    ,491,491,491
BEGIN DESCRIPTION:
Upper Denton 94 14.0
END DESCRIPTION:
XS GIS Cut Line= 4
      2239757.15      7248951.85        2238829.        7250510.
      2238750.21      7250713.98      2239444.65      7253387.56
#Sta/Elev= 30
  3186.4  1093.6  3526.2 1087.53  3993.5 1064.83  4466.6 1054.31  4510.3 1053.18
  4721.6 1049.47  4767.2  1045.3  4795.6 1047.61    4854 1039.66    4891 1028.31
    4990 1016.44  4990.4 1015.94  4994.4 1016.44  5753.9 1029.21  6206.4 1056.93
  6422.7 1064.66  6836.7 1073.49  6980.1 1071.72  7025.8 1075.45  7142.3 1076.27
  7373.9 1072.86  7461.5 1078.99  7485.4 1076.63  7577.9 1076.98  7740.2 1079.37
  7775.6 1083.81  7780.8  1081.3  7861.9 1082.07  7897.3 1091.34    7981 1088.16
#Mann= 7 ,-1 , 0
  3186.4     .05       0  4466.6     .12       0  4510.3     .05       0
    4990    .033       0  4994.4     .05       0  7485.4     .12       0
  7577.9     .05       0
Bank Sta=4990,4994.4
XS Rating Curve= 0 ,0
Exp/Cntr=0.3,0.1

Type RM Length L Ch R = 1 ,7297    ,460,460,460
BEGIN DESCRIPTION:
Upper Denton 94 13.0
END DESCRIPTION:
XS GIS Cut Line= 4
      2239713.76       7248873.7      2238374.78      7250383.69
      2238222.87      7251685.77      2238368.27      7253231.38
#Sta/Elev= 30
  2804.1 1088.58  2967.9 1090.73  3109.2  1081.8    3315 1079.45  3414.9 1073.73
  3492.9 1068.47  3789.2 1064.09  3902.9 1069.76  4078.9 1060.87    4250 1051.34
  4335.3 1041.02  4462.4 1038.15    4679  1025.5  4822.2 1017.38  5359.8 1017.29
  5360.3 1016.79  5364.6 1017.29  5472.9 1017.31  5553.5 1027.12  6046.8 1055.76
  6356.1 1063.91  6378.5 1063.23  6388.5 1058.14  6408.6 1062.13  6529.1 1062.65
  7041.4 1083.27  7359.1 1083.21  7489.7 1083.06  7583.8 1078.56  7685.6 1083.77
#Mann= 9 ,-1 , 0
  2804.1     .05       0  3414.9     .12       0  3492.9     .05       0
  4078.9     .12       0    4679     .05       0  5359.8    .033       0
  5364.6     .05       0  7359.1     .12       0  7489.7     .05       0
Bank Sta=5359.8,5364.6
XS Rating Curve= 0 ,0
Exp/Cntr=0.3,0.1

Type RM Length L Ch R = 1 ,6837    ,71,71,71
BEGIN DESCRIPTION:
Upper Denton 94 12.0
END DESCRIPTION:
XS GIS Cut Line= 5
      2239590.07      7248918.83      2238537.54      7249732.65
        2237929.        7250560.      2237636.93      7250991.33
       2238233.5      7253225.74
#Sta/Elev= 30
  2637.8 1086.54  2661.3 1086.47  2910.2 1070.88  3024.3 1070.31  3366.6 1051.25
  3430.9 1050.08  3451.7 1056.61  3466.2 1052.68  3560.7 1051.72  3630.1 1055.08
  3922.6 1048.33  4014.6 1055.75  4570.8 1018.26  4571.4 1017.76  4575.6 1018.26
  5023.8 1023.45  5074.7 1019.87  5320.3 1039.35  5347.3 1033.53  5442.2 1032.95
  5491.1 1046.86  5752.9 1060.33    6433 1055.01  6628.3 1058.56  7018.8 1077.19
  7168.8  1077.6  7524.3 1089.73  7658.2  1087.7  7669.8 1087.56  7828.9 1083.66
#Mann= 7 ,-1 , 0
  2637.8     .05       0  2661.3     .12       0  3560.7     .05       0
  4570.8    .033       0  4575.6     .05       0  7658.2     .12       0
  7669.8     .05       0
Bank Sta=4570.8,4575.6
XS Rating Curve= 0 ,0
Exp/Cntr=0.3,0.1

Type RM Length L Ch R = 1 ,6766    ,198,198,198
BEGIN DESCRIPTION:
Upper Denton 94 11.5
END DESCRIPTION:
XS GIS Cut Line= 5
      2240433.58      7248250.95      2238474.02      7249674.81
      2237945.36      7250414.93      2237571.77      7250971.79
      2238198.75      7253416.32
#Sta/Elev= 30
  1516.2 1102.95  1868.7 1104.87  2124.8 1093.66    2313 1079.55  2412.9 1085.55
  2492.5 1082.38  2521.9 1088.66  2542.7 1082.47  2684.9 1080.57  3279.3 1051.73
  3351.3  1046.9  3365.1 1039.85  3379.8 1046.75    3517  1047.8  3559.9 1053.05
  3882.2 1040.83  4089.7 1049.04  4333.1 1034.55  4993.3 1039.26  5158.4 1033.58
  5209.4  1037.6  5242.9 1030.84  5243.5 1030.34  5247.8 1030.84  5810.1 1056.85
  6492.9 1051.72  7706.4 1086.32  7805.8 1086.53  7981.6 1088.66  8042.2 1090.31
#Mann= 8 ,-1 , 0
  1516.2     .05       0  2124.8     .12       0    3517     .05       0
  5242.9    .033       0  5247.8     .05       0  7706.4     .12       0
  7805.8     .05       0  7981.6     .12       0
Bank Sta=5242.9,5247.8
XS Rating Curve= 0 ,0
Exp/Cntr=0.3,0.1

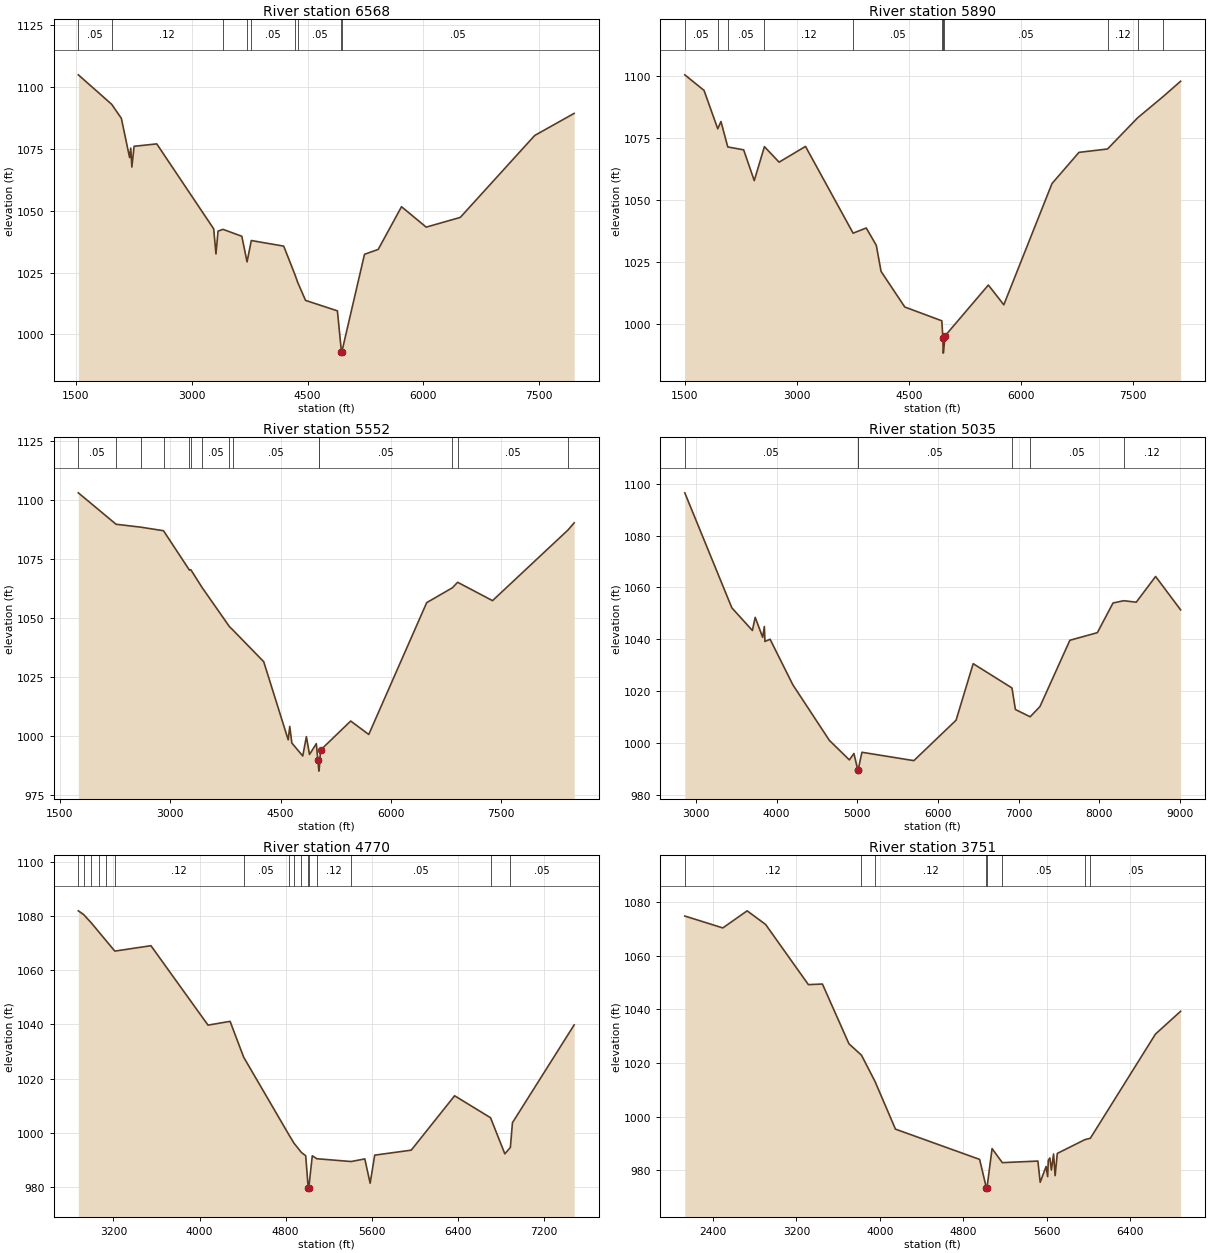
Type RM Length L Ch R = 1 ,6568    ,678,678,678
BEGIN DESCRIPTION:
Upper Denton 94 11.4
END DESCRIPTION:
XS GIS Cut Line= 5
      2240284.54      7248267.78      2238325.99      7249681.86
      2237740.94      7250358.54      2237480.14       7250929.5
       2238103.5      7253335.02
#Sta/Elev= 30
  1530.8 1104.97  1962.6 1093.06  2088.1 1087.38  2194.9 1071.51  2209.6 1075.35
  2224.3 1067.68    2253 1076.07  2546.9 1077.04  3284.3 1042.68  3313.7 1032.53
  3340.7 1041.77  3404.8 1042.48  3648.6 1039.68  3716.3 1029.33  3771.5 1037.96
  4191.4 1035.69  4338.9    1024  4371.3 1021.13  4474.4 1013.74  4886.9 1009.52
  4939.1  992.92  4939.7  992.42    4944  992.92  5237.9 1032.39  5415.5 1034.37
  5717.2 1051.63  6037.2 1043.38  6478.6 1047.31  7442.5 1080.44  7953.7 1089.38
#Mann= 9 ,-1 , 0
  1530.8     .05       0  1962.6     .12       0  3404.8     .05       0
  3716.3     .12       0  3771.5     .05       0  4338.9     .12       0
  4371.3     .05       0  4939.1    .033       0    4944     .05       0
Bank Sta=4939.1,4944
XS Rating Curve= 0 ,0
Exp/Cntr=0.3,0.1

Type RM Length L Ch R = 1 ,5890    ,338,338,338
BEGIN DESCRIPTION:
Upper Denton 94 10.0
END DESCRIPTION:
XS GIS Cut Line= 4
       2239631.6      7247507.85      2237222.71      7250059.97
      2236594.84      7251319.39      2236732.16      7253036.23
#Sta/Elev= 30
    1498 1100.44    1756 1094.15  1939.2 1078.67  1982.2 1081.61  2073.6 1071.35
  2286.4 1070.17    2428 1057.76  2564.1 1071.46  2760.6 1065.21  3114.2 1071.56
  3751.8 1036.56  3927.7 1038.65    4062 1031.67    4126 1021.14    4444 1006.77
  4939.5 1001.21  4953.2  994.36  4953.3   994.3  4958.1  988.67  4958.7  988.17
    4963  988.67  4981.6  995.09  5562.7 1015.64  5769.7 1007.67  6414.7 1056.58
  6775.9 1069.16  7158.1 1070.52  7560.8 1083.08  7905.9 1091.75    8137 1097.86
#Mann= 12 ,-1 , 0
    1498     .05       0  1939.2     .12       0  2073.6     .05       0
  2564.1     .12       0  3751.8     .05       0  4939.5     .12       0
  4953.2     .05       0  4958.1     .04       0    4963     .05       0
  7158.1     .12       0  7560.8     .05       0  7905.9     .12       0
Bank Sta=4953.3,4981.6
XS Rating Curve= 0 ,0
Exp/Cntr=0.3,0.1

Type RM Length L Ch R = 1 ,5552    ,517,517,517
BEGIN DESCRIPTION:
Upper Denton 94 9.0
END DESCRIPTION:
XS GIS Cut Line= 4
      2239240.96      7247429.74        2237029.        7249810.
      2236193.48      7251040.48      2236558.64      7253011.33
#Sta/Elev= 30
  1750.4  1103.1  2263.4 1089.79  2599.4 1088.56  2908.5 1087.05    3261 1070.37
  3279.9 1070.54  3430.8 1063.11  3803.6 1046.49  3852.1    1045    4271 1031.58
  4603.8   998.5  4624.8 1004.18  4653.1  997.15  4801.6  991.65    4851  999.85
  4893.5   992.3  4985.9  996.88  5007.2  989.89  5019.5  985.74  5020.3  985.24
  5024.8  985.74  5043.2  994.14  5453.4 1006.46  5698.9 1000.77  6486.6 1056.59
  6836.1 1062.89  6907.2 1065.22  7381.6 1057.44  8408.1 1087.37  8491.5 1090.39
#Mann= 14 ,-1 , 0
  1750.4     .05       0  2263.4     .12       0  2599.4     .05       0
  2908.5     .12       0    3261     .05       0  3279.9     .12       0
  3430.8     .05       0  3803.6     .12       0  3852.1     .05       0
  5019.5     .04       0  5024.8     .05       0  6836.1     .12       0
  6907.2     .05       0  8408.1     .12       0
Bank Sta=5007.2,5043.2
XS Rating Curve= 0 ,0
Exp/Cntr=0.3,0.1

Type RM Length L Ch R = 1 ,5035    ,265,265,265
BEGIN DESCRIPTION:
Upper Denton 94 8.5
END DESCRIPTION:
XS GIS Cut Line= 4
       2238271.5        7247888.      2236784.94      7249407.12
      2234961.93      7251206.32      2235317.33      7252620.75
#Sta/Elev= 30
    2863 1096.52    3446 1052.13  3700.6 1043.38  3735.9 1048.45  3827.9 1040.75
  3849.1 1044.91  3856.2 1039.13  3919.8    1040  4202.7 1022.39  4655.3 1000.94
  4902.8  993.42  4959.4  995.89  5006.2  989.58    5007  989.08  5011.6  989.58
  5058.3  996.36  5701.8  993.13  6225.1 1008.74  6437.2 1030.56    6918 1021.19
  6960.5 1012.87  7143.4 1010.06  7264.6    1014  7635.6  1039.6  7976.3 1042.53
  8170.5 1053.99  8303.8 1054.87  8458.4  1054.3  8698.1 1064.23  9008.2 1051.34
#Mann= 6 ,-1 , 0
    2863     .05       0  5006.2    .033       0  5011.6     .05       0
    6918     .12       0  7143.4     .05       0  8303.8     .12       0
Bank Sta=5006.2,5011.6
XS Rating Curve= 0 ,0
Exp/Cntr=0.3,0.1

Type RM Length L Ch R = 1 ,4770    ,1019,1019,1019
BEGIN DESCRIPTION:
Upper Denton 94 8.0
END DESCRIPTION:
XS GIS Cut Line= 3
      2238054.45      7247801.24      2236567.92      7249298.62
      2234796.49      7251058.24
#Sta/Elev= 30
  2874.2 1081.83  2924.4 1080.43  2995.9 1077.33  3068.8 1073.86  3130.3 1070.93
  3213.3 1066.99  3548.9 1068.98  4079.3 1039.71  4284.3  1041.1  4410.2 1027.92
  4828.4  999.47  4877.5  996.24  4946.7   992.8  4986.9  991.57  5009.9  979.78
  5010.7  979.28  5015.3  979.78    5048  991.57  5090.4  990.48  5408.9  989.45
  5535.9  990.42  5585.4  981.46  5627.9   991.8  5967.3  993.64  6370.3 1013.68
    6704  1005.6    6837  992.28  6888.4  994.66  6907.7 1003.76    7481 1039.79
#Mann= 16 ,-1 , 0
  2874.2     .05       0  2924.4     .12       0  2995.9     .05       0
  3068.8     .12       0  3130.3     .05       0  3213.3     .12       0
  4410.2     .05       0  4828.4     .12       0  4877.5     .05       0
  4946.7     .12       0  5009.9     .07       0  5015.3     .12       0
  5090.4     .12       0  5408.9     .05       0    6704     .12       0
  6888.4     .05       0
Bank Sta=5009.9,5015.3
XS Rating Curve= 0 ,0
Exp/Cntr=0.3,0.1

Type RM Length L Ch R = 1 ,3751    ,855,855,855
BEGIN DESCRIPTION:
Upper Denton 94 6.0
END DESCRIPTION:
XS GIS Cut Line= 4
      2237964.93      7247750.91      2236419.66      7249252.76
        2235679.        7249260.      2235357.43      7251088.18
#Sta/Elev= 30
  2130.6 1074.84  2494.8  1070.4  2728.1 1076.78  2905.1  1071.7  3315.1 1049.25
  3449.6 1049.47    3704 1027.17    3824 1022.92  3954.1 1013.09  4149.5  995.34
  4956.1  984.05  5020.7  973.46  5021.7  972.96  5026.6  973.46  5075.4  988.09
  5173.5  982.84  5514.5  983.43  5536.6  975.52  5593.3  981.42  5608.1  977.64
  5614.2   983.7    5629   984.6  5643.8  980.08  5664.8  986.07  5679.6  977.99
  5700.5  986.28  5964.8  991.42  6017.1  991.93  6641.2  1030.8  6882.4 1039.31
#Mann= 8 ,-1 , 0
  2130.6     .12       0    3824     .05       0  3954.1     .12       0
  5020.7     .07       0  5026.6     .12       0  5173.5     .05       0
  5964.8     .12       0  6017.1     .05       0
Bank Sta=5020.7,5026.6
XS Rating Curve= 0 ,0
Exp/Cntr=0.3,0.1

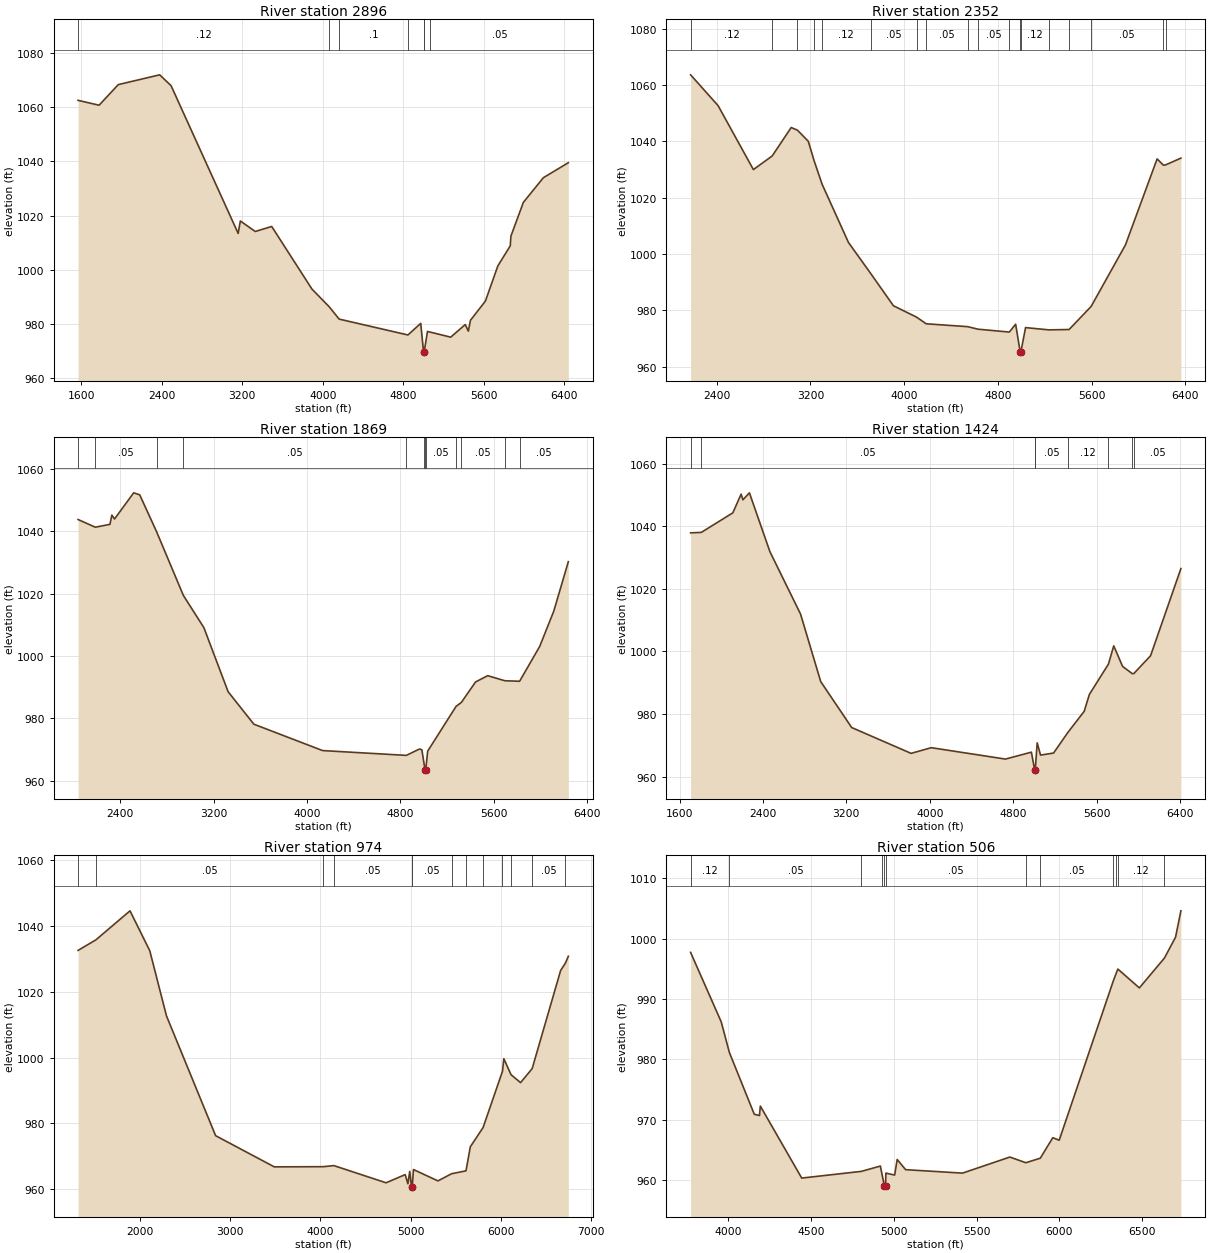
Type RM Length L Ch R = 1 ,2896    ,544,544,544
BEGIN DESCRIPTION:
Upper Denton 94 5.0
END DESCRIPTION:
XS GIS Cut Line= 5
      2237817.33      7247664.13      2236315.49       7248966.3
      2235052.47      7249005.37      2234978.78      7249148.52
      2234622.88      7250563.46
#Sta/Elev= 30
  1568.4 1062.53  1777.4 1060.73  1968.2 1068.34  2379.5 1071.95  2492.7 1067.94
  3159.2 1013.41  3180.9    1018  3329.2 1014.12  3492.5 1015.97  3892.8  992.84
  4063.2  986.36  4162.5  981.78  4846.1  975.92  4973.1  980.21  5001.1  969.72
  5002.1  969.22  5007.4  969.72  5040.2  977.22  5068.4  976.97    5271  975.11
  5415.4  979.77  5446.3  977.34    5467  981.32  5615.9  988.45  5739.3 1001.41
  5862.6 1008.82  5869.1  1012.4  5992.8 1024.86  6191.6 1033.97  6439.8 1039.51
#Mann= 7 ,-1 , 0
  1568.4     .12       0  4063.2     .05       0  4162.5      .1       0
  4846.1     .12       0  5001.1     .07       0  5007.4     .12       0
  5068.4     .05       0
Bank Sta=5001.1,5007.4
XS Rating Curve= 0 ,0
Exp/Cntr=0.3,0.1

Type RM Length L Ch R = 1 ,2352    ,483,483,483
BEGIN DESCRIPTION:
Upper Denton 94 4.0
END DESCRIPTION:
XS GIS Cut Line= 5
      2237109.78      7248119.94      2236081.11      7248705.89
      2234569.32       7248908.5        2234529.        7249010.
      2234622.88      7250372.49
#Sta/Elev= 30
  2177.5 1063.64  2412.2 1052.69  2713.3 1029.98  2873.7 1034.81    3036 1044.93
  3088.7 1043.99  3181.6 1040.05  3232.1 1033.05  3299.6 1024.79  3524.9 1004.07
  3713.3  993.14  3908.3  981.61  4106.2  977.56  4187.7   975.2  4542.6  974.18
    4630  973.28  4897.2  972.26  4951.4  975.05    4990  965.28    4991  964.78
  4996.3  965.28    5036  973.85  5235.2  973.04  5407.6  973.17  5595.3  981.35
    5888 1003.18  6158.6 1033.77  6212.6 1031.54  6230.2 1031.63  6361.6 1034.05
#Mann= 18 ,-1 , 0
  2177.5     .12       0  2873.7     .05       0  3088.7     .12       0
  3232.1     .05       0  3299.6     .12       0  3713.3     .05       0
  4106.2      .1       0  4187.7     .05       0  4542.6      .1       0
    4630     .05       0  4897.2     .12       0    4990     .07       0
  4996.3     .12       0  5235.2     .05       0  5407.6     .12       0
  5595.3     .05       0  6212.6     .12       0  6230.2     .05       0
Bank Sta=4990,4996.3
XS Rating Curve= 0 ,0
Exp/Cntr=0.3,0.1

Type RM Length L Ch R = 1 ,1869    ,445,445,445
BEGIN DESCRIPTION:
Upper Denton 94 3.0
END DESCRIPTION:
XS GIS Cut Line= 5
       2236758.2      7248172.03      2234088.93      7248914.22
        2234079.        7249110.      2234083.42      7249625.96
      2234570.59      7250155.24
#Sta/Elev= 30
  2037.8 1043.78  2185.9 1041.32  2311.1 1042.23  2327.6  1045.2  2350.5 1043.95
  2514.4 1052.34  2566.3  1051.7  2711.3 1039.84  2940.3 1019.44  3116.4 1009.09
    3324  988.55  3544.6  978.14  4133.6  969.68  4851.3  968.14  4964.3  970.19
  4984.3  969.93  4999.2   966.4  5011.2  963.59  5012.2  963.09  5017.6  963.59
  5034.4  969.51  5277.3  983.84  5322.7  985.12  5444.4  991.68  5548.5   993.7
  5696.3  992.07    5822  991.91  5994.2 1003.08  6114.4 1014.36  6239.7 1030.27
#Mann= 12 ,-1 , 0
  2037.8     .12       0  2185.9     .05       0  2711.3     .12       0
  2940.3     .05       0  4851.3     .12       0  4999.2     .05       0
  5011.2    .033       0  5017.6     .05       0  5277.3     .12       0
  5322.7     .05       0  5696.3     .12       0    5822     .05       0
Bank Sta=5011.2,5017.6
XS Rating Curve= 0 ,0
Exp/Cntr=0.3,0.1

Type RM Length L Ch R = 1 ,1424    ,450,450,450
BEGIN DESCRIPTION:
Upper Denton 94 2.0
END DESCRIPTION:
XS GIS Cut Line= 5
      2236693.13      7248067.86      2233685.28      7248888.18
        2233679.        7249060.      2234012.64      7249665.88
      2234527.41      7250172.84
#Sta/Elev= 30
  1705.8 1037.89  1808.4 1038.03  2111.1 1044.29  2190.5 1050.27  2207.6 1048.44
    2270 1050.68  2466.7 1031.87  2760.6 1011.93  2954.1  990.35  3251.2  975.66
  3821.3  967.41  4014.8  969.22  4726.4  965.58  4975.4  967.79    5006  962.23
    5007  961.73  5012.4  962.23    5031  970.77  5063.1  966.85  5188.1  967.51
  5323.9  974.03  5481.6  980.84    5532  986.27  5714.5  995.94  5765.3 1001.77
  5850.1  995.21  5943.2  992.88  5958.7  992.94  6118.8  998.62  6409.6 1026.47
#Mann= 8 ,-1 , 0
  1705.8     .12       0  1808.4     .05       0    5006    .033       0
  5012.4     .05       0  5323.9     .12       0  5714.5     .05       0
  5943.2     .12       0  5958.7     .05       0
Bank Sta=5006,5012.4
XS Rating Curve= 0 ,0
Exp/Cntr=0.3,0.1

Type RM Length L Ch R = 1 ,974     ,468,468,468
BEGIN DESCRIPTION:
Upper Denton 94 1.0
END DESCRIPTION:
XS GIS Cut Line= 5
      2236657.98      7247987.68      2233268.61      7248953.28
        2233279.        7249110.      2233372.78      7249304.85
      2234595.39      7250223.81
#Sta/Elev= 30
  1319.1 1032.57  1516.5 1035.77  1894.2  1044.6  2112.9 1032.47  2297.7 1012.67
  2841.8  976.23  3491.2  966.75  4032.5   966.8    4151  967.13  4728.6  961.91
  4940.3   964.4  4970.3   961.6  4990.4  965.38  5011.3  960.48  5012.3  959.98
  5017.7  960.48  5031.6  965.94  5302.9  962.48  5453.6  964.66  5613.1  965.54
  5661.1  972.85  5802.5  978.71  6017.2  995.83  6031.9  999.64  6112.1  994.77
  6217.2  992.36  6345.6  996.62  6660.8 1026.47  6712.7 1028.65  6746.1 1030.78
#Mann= 13 ,-1 , 0
  1319.1     .12       0  1516.5     .05       0  4032.5     .12       0
    4151     .05       0  5011.3    .033       0  5017.7     .05       0
  5453.6     .12       0  5613.1     .05       0  5802.5     .12       0
  6017.2     .05       0  6112.1     .12       0  6345.6     .05       0
  6712.7     .12       0
Bank Sta=5011.3,5017.7
XS Rating Curve= 0 ,0
Exp/Cntr=0.3,0.1

Type RM Length L Ch R = 1 ,506     ,0,0,0
BEGIN DESCRIPTION:
Upper Denton 94 0.5
END DESCRIPTION:
XS GIS Cut Line= 5
      2233110.18      7248034.77      2232807.68      7248916.82
      2232818.06      7249073.54      2232854.96      7249274.39
      2234354.44      7250008.51
#Sta/Elev= 30
  3771.5  997.73  3956.7  986.22  4005.9  981.16  4156.4  970.93  4187.7  970.72
  4192.9  972.29  4443.1  960.37  4803.8  961.48  4918.4  962.36  4929.5  960.83
  4943.2  959.04  4944.3  958.54  4949.9  959.04  4951.6  961.19  5004.7  960.87
  5020.1  963.45    5071  961.76  5414.9  961.19  5701.1  963.85  5797.6  962.91
  5884.9  963.66  5960.5  967.05  5999.3  966.64  6327.3  993.09  6343.4  994.24
  6353.7  994.97  6483.8  991.85  6635.5   996.8  6702.5 1000.25  6734.8 1004.61
#Mann= 12 ,-1 , 0
  3771.5     .12       0  4005.9     .05       0  4803.8     .12       0
  4929.5     .05       0  4943.2    .033       0  4949.9     .05       0
  5797.6     .12       0  5884.9     .05       0  6327.3     .12       0
  6343.4     .05       0  6353.7     .12       0  6635.5     .05       0
Bank Sta=4943.2,4949.9
XS Rating Curve= 0 ,0
Exp/Cntr=0.3,0.1

Chan Stop Cuts=-1
Use User Specified Reach Order=0
Composite Channel Slope=5