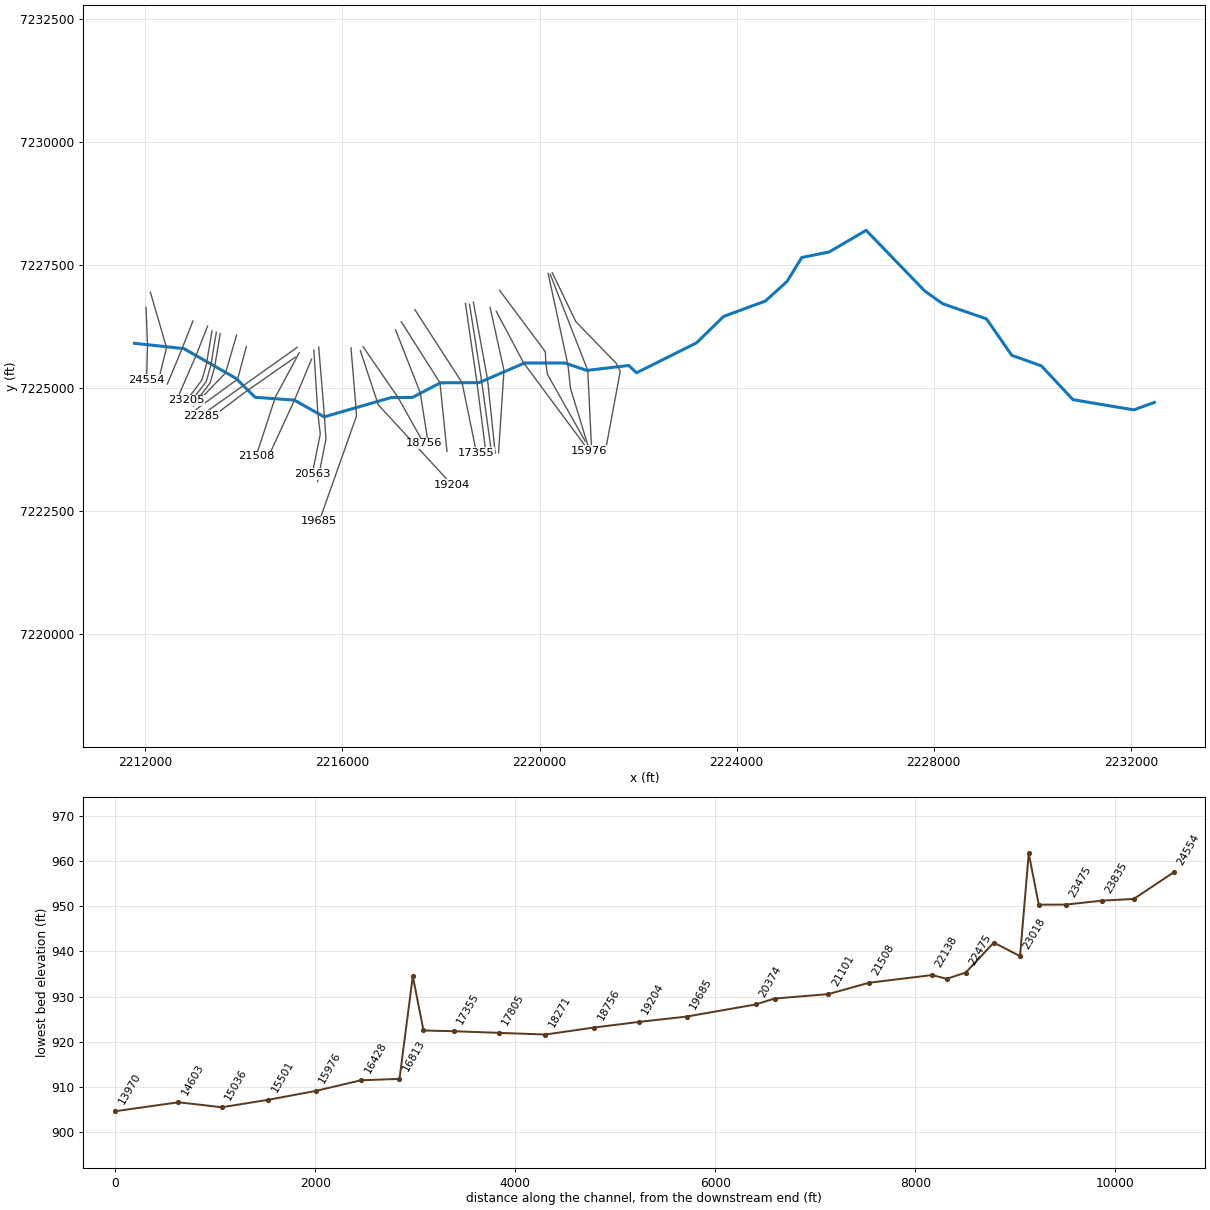
--- Upper Denton 98.prj (project) ---

Proj Title=Upper Denton 98 Base Level Engineering
Current Plan=p01
Default Exp/Contr=0.3,0.1
English Units
Geom File=g01
Flow File=f01
Plan File=p01
Y Axis Title=Elevation
X Axis Title(PF)=Main Channel Distance
X Axis Title(XS)=Station
BEGIN DESCRIPTION:
Upper Denton 98
END DESCRIPTION:
DSS Export Rating Curves= 0
DSS Export Rating Curve Sorted= 0
DSS Export Volume Flow Curves= 0
DXF OffsetX= 0
DXF OffsetY= 0
DXF ScaleX= 1
DXF ScaleY= 10

--- Upper Denton 98.p01 (plan) ---

Plan Title=Multiple Run
Short Identifier=Multiple
Geom File=g01
Flow File=f01
Subcritical Flow
K Sum by GR= 0
Std Step Tol= 0.01
Critical Tol= 0.01
Num of Std Step Trials= 20
Max Error Tol= 0.3
Flow Tol Ratio= 0.001
Split Flow NTrial= 30
Split Flow Tol= 0.02
Split Flow Ratio= 0.02
Log Output Level= 0
Friction Slope Method= 1
Unsteady Friction Slope Method= 2
Unsteady Bridges Friction Slope Method= 1
Parabolic Critical Depth
Global Vel Dist=  1 , 1 , 1
Global Log Level= 0
CheckData=True
Encroach Param= -1, 0, 0, 0
BEGIN DESCRIPTION:
Multiple Run
END DESCRIPTION:

--- Upper Denton 98.f01 (steady flow) ---

Flow Title=Multiple
Program Version=4.10
Number of Profiles= 7
Profile Names=10-year,25-year,50-year,1pct_min,100-year,1pct_plu,500-year
River Rch & RM=Upper Denton 98,Reach-1         ,24554
     878    1249    1566     975    1944    3880    3008
River Rch & RM=Upper Denton 98,Reach-1         ,21508
    1031    1477    1861    1162    2319    4626    3615
River Rch & RM=Upper Denton 98,Reach-1         ,19685
    1164    1674    2113    1323    2639    5265    4131
River Rch & RM=Upper Denton 98,Reach-1         ,19204
    1841    2700    3456    2188    4365    8710    6998
River Rch & RM=Upper Denton 98,Reach-1         ,17805
    1841    2700    3456    2188    4365    8710    6998
River Rch & RM=Upper Denton 98,Reach-1         ,13970
    1923    2826    3621    2295    4579    9136    7354
River Rch & RM=Upper Denton 98,Reach-1         ,13203
    2351    3473    4465    2837    5661   11296    9142
River Rch & RM=Upper Denton 98,Reach-1         ,9468
    2364    3467    4436    2805    5596   11165    8942
Boundary for River Rch & Prof#=Upper Denton 98,Reach-1         , 1
Up Type= 0
Dn Type= 3
Dn Slope=0.002
Boundary for River Rch & Prof#=Upper Denton 98,Reach-1         , 2
Up Type= 0
Dn Type= 3
Dn Slope=0.002
Boundary for River Rch & Prof#=Upper Denton 98,Reach-1         , 3
Up Type= 0
Dn Type= 3
Dn Slope=0.002
Boundary for River Rch & Prof#=Upper Denton 98,Reach-1         , 4
Up Type= 0
Dn Type= 3
Dn Slope=0.002
Boundary for River Rch & Prof#=Upper Denton 98,Reach-1         , 5
Up Type= 0
Dn Type= 3
Dn Slope=0.002
Boundary for River Rch & Prof#=Upper Denton 98,Reach-1         , 6
Up Type= 0
Dn Type= 3
Dn Slope=0.002
Boundary for River Rch & Prof#=Upper Denton 98,Reach-1         , 7
Up Type= 0
Dn Type= 3
Dn Slope=0.002
DSS Import GetInterval= 0
DSS Import GetPeak= 0
DSS Import FillOption= 0

--- Upper Denton 98.g01 (geometry) ---

Geom Title=Existing Conditions

River Reach=Upper Denton 98,Reach-1
Reach XY= 30
      2211779.00      7225910.00      2212782.41      7225802.19
      2213835.38      7225201.99      2214230.55      7224813.75
      2215023.47      7224757.61      2215628.90      7224417.32
      2216989.50      7224808.80      2217423.07      7224812.24
      2217988.65      7225108.64      2218773.07      7225112.24
      2219694.22      7225509.49      2220515.08      7225509.32
      2220958.95      7225359.40      2221810.79      7225459.92
      2221968.14      7225311.01      2223185.19      7225917.86
      2223737.62      7226456.16      2224585.19      7226767.85
      2225023.82      7227165.42      2225322.66      7227651.98
      2225877.53      7227763.54      2226629.10      7228202.69
      2227815.79      7226973.63      2228180.50      7226713.62
      2229070.38      7226406.16      2229584.47      7225665.26
      2230185.17      7225452.14      2230826.71      7224765.84
      2232058.95      7224559.41      2232479.00      7224710.00

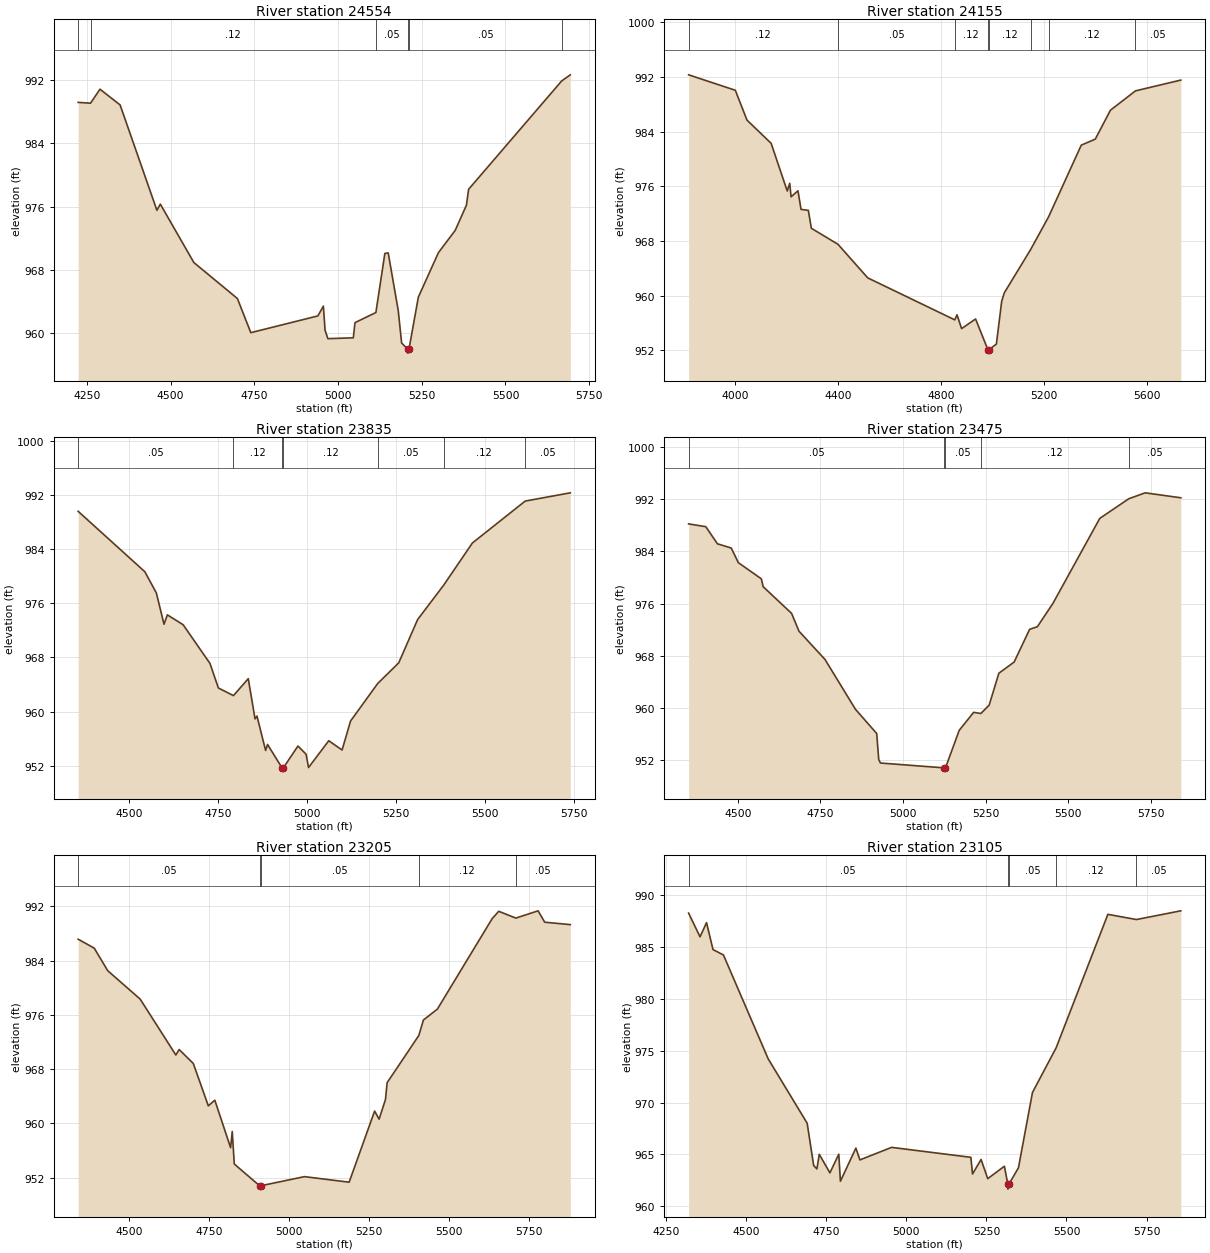
Type RM Length L Ch R = 1,24554,399,399,399
BEGIN DESCRIPTION:
Upper Denton 98 49.0
END DESCRIPTION:
XS GIS Cut Line= 3
      2212014.27      7226635.17      2212045.52      7225864.29
      2212024.69      7225166.41
#Sta/Elev= 30
  4223.9  989.20  4260.8  989.10  4289.1  990.87  4349.2  988.88  4459.1  975.54
  4469.3  976.32  4569.4  968.93  4699.5  964.37  4739.5  960.05  4939.7  962.17
  4956.2  963.41  4961.2  960.37  4969.7  959.29  5045.6  959.40  5050.6  961.32
  5113.0  962.60  5139.8  970.08  5149.8  970.15  5179.8  962.84  5189.8  958.75
  5207.8  957.96  5208.0  957.46  5211.8  957.96  5239.8  964.55  5299.8  970.18
  5349.9  973.00  5383.3  976.18  5389.9  978.20  5667.9  991.92  5693.6  992.69
#Mann=6,-1,0
  4223.9    0.05       0  4260.8    0.12       0  5113.0    0.05       0
  5207.8    0.07       0  5211.8    0.05       0  5667.9    0.12       0
Bank Sta=5207.8,5211.8
Exp/Cntr=0.3,0.1

Type RM Length L Ch R = 1,24155,320,320,320
BEGIN DESCRIPTION:
Upper Denton 98 48.0
END DESCRIPTION:
XS GIS Cut Line= 3
      2212102.83      7226947.58      2212430.94      7225822.62
      2212254.07      7225104.72
#Sta/Elev= 30
  3819.9  992.33  4001.2  990.07  4046.5  985.70  4140.3  982.30  4202.8  975.32
  4212.5  976.45  4217.7  974.47  4244.5  975.35  4256.4  972.63  4284.7  972.48
  4296.5  969.86  4399.7  967.52  4515.3  962.60  4853.4  956.45  4862.0  957.19
  4879.9  955.17  4934.2  956.58  4982.0  952.08  4982.3  951.58  4986.0  952.08
  5015.0  952.91  5035.6  959.18  5045.9  960.42  5148.3  966.77  5217.5  971.52
  5344.6  982.03  5399.1  982.92  5457.9  987.15  5555.0  989.98  5731.1  991.56
#Mann=8,-1,0
  3819.9    0.12       0  4399.7    0.05       0  4853.4    0.12       0
  4982.0    0.07       0  4986.0    0.12       0  5148.3    0.05       0
  5217.5    0.12       0  5555.0    0.05       0
Bank Sta=4982,4986
Exp/Cntr=0.3,0.1

Type RM Length L Ch R = 1,23835,360,360,360
BEGIN DESCRIPTION:
Upper Denton 98 47.0
END DESCRIPTION:
XS GIS Cut Line= 3
      2212967.38      7226364.25      2212729.00      7225760.00
      2212446.98      7225084.04
#Sta/Elev= 30
  4356.8  989.59  4544.1  980.66  4576.4  977.53  4597.9  972.90  4607.3  974.29
  4651.6  972.83  4726.9  967.12  4750.6  963.48  4792.9  962.36  4834.5  964.86
  4853.5  958.92  4858.9  959.34  4883.2  954.25  4888.6  955.14  4929.1  951.70
  4929.4  951.20  4933.1  951.70  4974.1  954.91  4996.9  953.69  5003.7  951.73
  5060.5  955.69  5097.9  954.32  5121.7  958.60  5198.0  964.15  5257.0  967.20
  5310.1  973.60  5382.7  978.64  5463.9  984.91  5612.1  991.10  5738.8  992.32
#Mann=7,-1,0
  4356.8    0.05       0  4792.9    0.12       0  4929.1    0.07       0
  4933.1    0.12       0  5198.0    0.05       0  5382.7    0.12       0
  5612.1    0.05       0
Bank Sta=4929.1,4933.1
Exp/Cntr=0.3,0.1

Type RM Length L Ch R = 1,23475,270,270,270
BEGIN DESCRIPTION:
Upper Denton 98 46.0
END DESCRIPTION:
XS GIS Cut Line= 3
      2213264.28      7226260.14      2213029.00      7225660.00
      2212691.34      7224885.08
#Sta/Elev= 30
  4351.1  988.22  4403.1  987.79  4438.3  985.17  4480.1  984.52  4501.6  982.28
  4571.2  979.80  4576.8  978.59  4662.7  974.51  4685.1  971.78  4763.8  967.45
  4856.1  959.81  4920.5  956.09  4926.6  952.10  4931.9  951.57  5124.6  950.83
  5124.9  950.33  5128.6  950.83  5170.2  956.58  5213.9  959.34  5235.7  959.16
  5260.8  960.44  5290.2  965.33  5336.5  967.05  5383.3  972.06  5406.8  972.46
  5453.6  976.01  5595.7  989.06  5683.4  992.07  5733.1  992.98  5841.0  992.22
#Mann=5,-1,0
  4351.1    0.05       0  5124.6   0.033       0  5128.6    0.05       0
  5235.7    0.12       0  5683.4    0.05       0
Bank Sta=5124.6,5128.6
Exp/Cntr=0.3,0.1

Type RM Length L Ch R = 1,23205,100,100,100
BEGIN DESCRIPTION:
Upper Denton 98 45.5
END DESCRIPTION:
XS GIS Cut Line= 4
      2213352.82      7226161.18      2213240.46      7225486.04
      2213149.69      7225166.37      2212837.17      7224749.67
#Sta/Elev= 30
  4340.8  987.15  4391.1  985.83  4433.2  982.51  4534.6  978.32  4646.1  970.08
  4656.3  970.89  4700.5  968.84  4747.5  962.59  4767.8  963.43  4817.1  956.42
  4822.2  958.82  4828.6  954.02  4907.7  950.82  4907.9  950.32  4911.7  950.82
  5048.0  952.16  5187.4  951.34  5267.0  961.82  5281.0  960.63  5300.9  963.53
  5306.1  966.00  5405.2  972.97  5419.4  975.24  5463.1  976.85  5634.0  990.16
  5654.8  991.26  5708.3  990.26  5777.7  991.33  5798.5  989.65  5878.4  989.30
#Mann=5,-1,0
  4340.8    0.05       0  4907.7   0.033       0  4911.7    0.05       0
  5405.2    0.12       0  5708.3    0.05       0
Bank Sta=4907.7,4911.7
Exp/Cntr=0.3,0.1

Type RM Length L Ch R = 1,23105,87,87,87
BEGIN DESCRIPTION:
Upper Denton 98 45.0
END DESCRIPTION:
XS GIS Cut Line= 4
      2213441.36      7226135.11      2213329.00      7225460.00
      2213238.23      7225140.33      2212926.23      7224724.33
#Sta/Elev= 30
  4320.3  988.28  4355.9  985.99  4376.2  987.36  4396.4  984.76  4429.0  984.24
  4568.8  974.21  4690.4  968.00  4710.7  963.92  4720.8  963.59  4728.2  965.00
  4761.4  963.21  4789.1  965.01  4794.2  962.40  4842.5  965.60  4855.1  964.46
  4954.0  965.67  5201.5  964.71  5206.7  963.10  5233.4  964.50  5254.2  962.65
  5306.2  963.85  5316.8  962.14  5317.1  961.64  5320.8  962.14  5350.1  963.70
  5393.9  970.97  5467.5  975.26  5629.3  988.16  5718.5  987.66  5857.0  988.50
#Mann=5,-1,0
  4320.3    0.05       0  5316.8   0.033       0  5320.8    0.05       0
  5467.5    0.12       0  5718.5    0.05       0
Bank Sta=5316.8,5320.8
Exp/Cntr=0.3,0.1

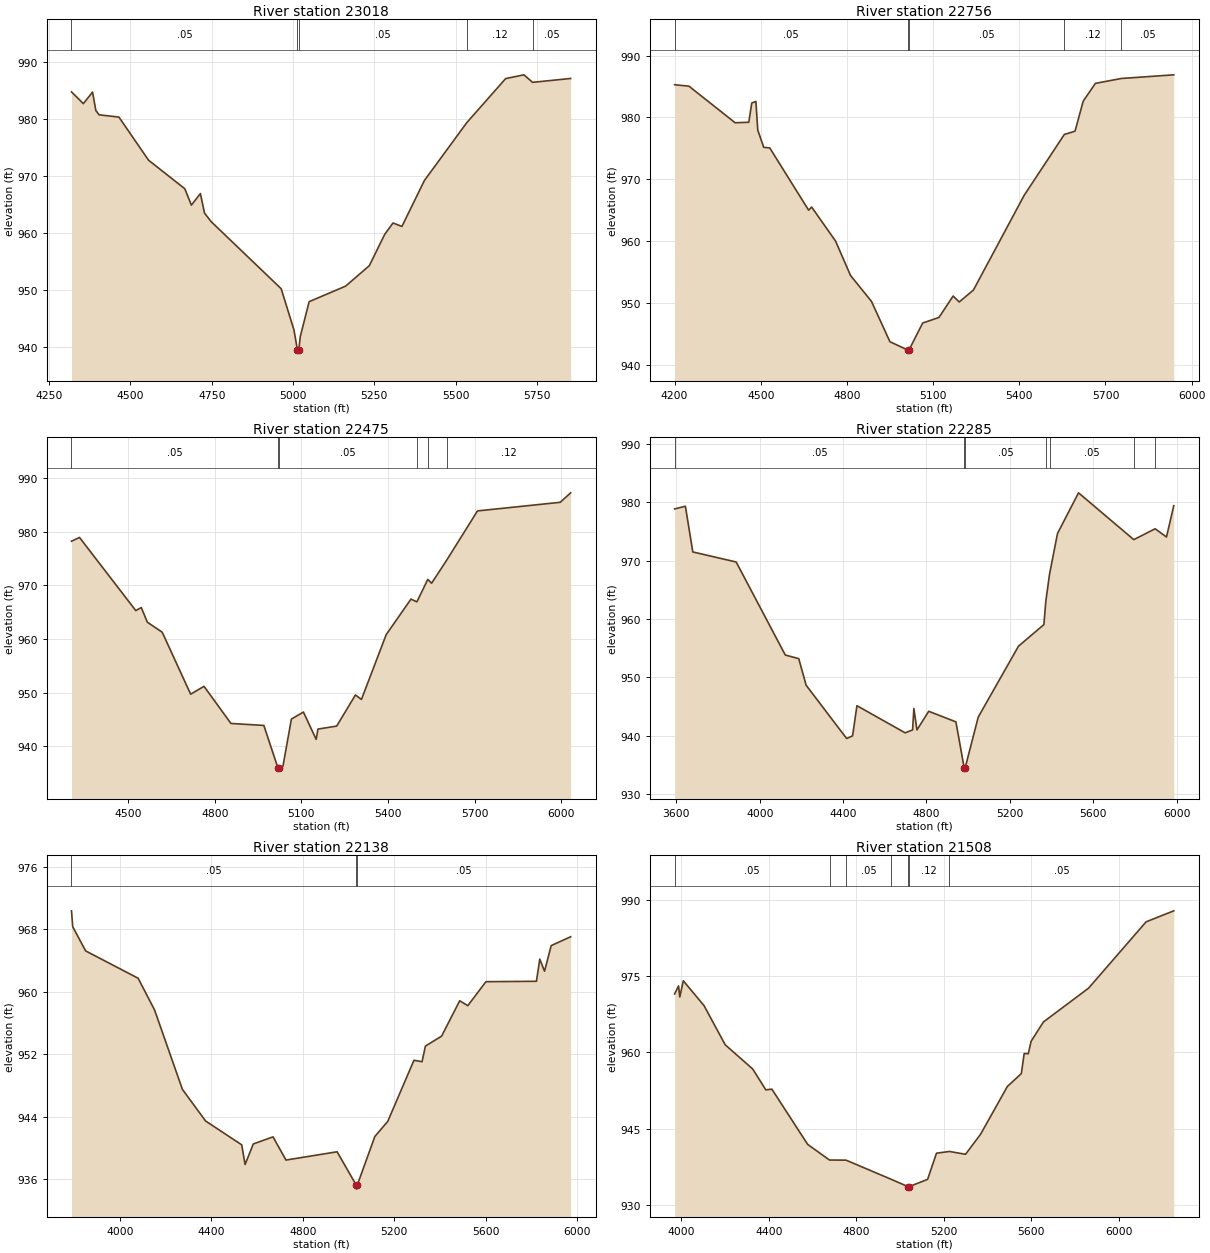
Type RM Length L Ch R = 1,23018,262,262,262
BEGIN DESCRIPTION:
Upper Denton 98 44.5
END DESCRIPTION:
XS GIS Cut Line= 4
      2213519.48      7226103.88      2213407.13      7225428.75
      2213316.36      7225109.08      2213004.91      7224693.82
#Sta/Elev= 30
  4318.5  984.82  4354.9  982.75  4383.3  984.78  4393.4  981.54  4403.5  980.79
  4464.4  980.39  4555.6  972.82  4667.1  967.81  4687.4  964.93  4715.1  966.96
  4727.9  963.52  4748.2  962.03  4963.6  950.25  5002.9  943.03  5013.8  939.44
  5014.0  938.94  5017.8  939.44  5022.4  941.84  5049.7  947.98  5161.8  950.70
  5234.8  954.29  5282.3  959.81  5307.8  961.79  5335.2  961.19  5404.3  969.25
  5535.1  979.44  5654.3  987.15  5710.6  987.81  5737.1  986.49  5854.3  987.17
#Mann=5,-1,0
  4318.5    0.05       0  5013.8   0.033       0  5017.8    0.05       0
  5535.1    0.12       0  5737.1    0.05       0
Bank Sta=5013.8,5017.8
Exp/Cntr=0.3,0.1

Type RM Length L Ch R = 1,22756,281,281,281
BEGIN DESCRIPTION:
Upper Denton 98 44.0
END DESCRIPTION:
XS GIS Cut Line= 3
      2213852.82      7226077.83      2213629.00      7225310.00
      2212977.82      7224635.12
#Sta/Elev= 30
  4200.2  985.28  4250.0  985.05  4410.9  979.14  4458.3  979.22  4468.8  982.33
  4483.1  982.58  4489.6  977.96  4510.4  975.17  4531.3  975.08  4666.7  965.02
  4677.1  965.53  4760.4  960.04  4812.5  954.48  4885.4  950.30  4949.7  943.78
  5012.0  942.44  5012.3  941.94  5016.0  942.44  5063.7  946.80  5120.3  947.70
  5169.6  951.16  5191.0  950.20  5240.4  952.13  5417.1  967.43  5556.8  977.25
  5594.1  977.78  5622.4  982.62  5664.9  985.50  5755.4  986.29  5937.8  986.88
#Mann=5,-1,0
  4200.2    0.05       0  5012.0   0.033       0  5016.0    0.05       0
  5556.8    0.12       0  5755.4    0.05       0
Bank Sta=5012,5016
Exp/Cntr=0.3,0.1

Type RM Length L Ch R = 1,22475,190,190,190
BEGIN DESCRIPTION:
Upper Denton 98 43.0
END DESCRIPTION:
XS GIS Cut Line= 3
      2214050.72      7225843.41      2213873.65      7225182.00
      2213029.87      7224567.39
#Sta/Elev= 30
  4303.8  978.25  4331.5  978.95  4526.5  965.29  4545.4  965.86  4566.6  963.12
  4617.9  961.26  4716.4  949.69  4762.8  951.15  4856.0  944.22  4969.9  943.85
  5019.3  935.82  5019.5  935.32  5023.3  935.82  5036.0  936.22  5065.3  945.04
  5107.0  946.35  5151.1  941.25  5157.3  943.17  5222.2  943.73  5287.1  949.54
  5307.9  948.71  5393.7  960.81  5479.5  967.44  5499.9  966.92  5537.6  971.11
  5551.0  970.41  5603.9  974.77  5709.7  983.90  5996.3  985.51  6032.4  987.28
#Mann=6,-1,0
  4303.8    0.05       0  5019.3   0.033       0  5023.3    0.05       0
  5499.9    0.12       0  5537.6    0.05       0  5603.9    0.12       0
Bank Sta=5019.3,5023.3
Exp/Cntr=0.3,0.1

Type RM Length L Ch R = 1,22285,147,147,147
BEGIN DESCRIPTION:
Upper Denton 98 42.5
END DESCRIPTION:
XS GIS Cut Line= 3
      2215081.97      7225827.82      2213951.77      7225025.75
      2213128.84      7224442.40
#Sta/Elev= 30
  3591.8  978.85  3643.4  979.31  3679.1  971.48  3887.0  969.76  4122.7  953.82
  4187.2  953.20  4222.8  948.64  4417.0  939.52  4445.5  939.97  4466.4  945.14
  4697.7  940.49  4733.4  940.99  4739.5  944.66  4754.3  940.99  4810.9  944.18
  4941.3  942.37  4981.1  934.43  4981.3  933.93  4985.1  934.43  5048.3  943.19
  5241.5  955.34  5363.3  959.04  5372.5  963.02  5390.4  967.67  5428.5  974.64
  5529.4  981.61  5794.5  973.59  5897.0  975.45  5951.4  974.04  5986.4  979.41
#Mann=7,-1,0
  3591.8    0.05       0  4981.1   0.033       0  4985.1    0.05       0
  5372.5    0.12       0  5390.4    0.05       0  5794.5    0.12       0
  5897.0    0.05       0
Bank Sta=4981.1,4985.1
Exp/Cntr=0.3,0.1

Type RM Length L Ch R = 1,22138,630,630,630
BEGIN DESCRIPTION:
Upper Denton 98 42.0
END DESCRIPTION:
XS GIS Cut Line= 3
      2215045.52      7225629.91      2214045.52      7224932.00
      2213275.41      7224354.41
#Sta/Elev= 30
  3788.8  970.38  3794.0  968.35  3850.7  965.25  4080.1  961.75  4151.7  957.71
  4273.8  947.52  4375.0  943.48  4532.9  940.43  4547.7  937.91  4583.5  940.54
  4669.8  941.45  4726.5  938.48  4949.9  939.54  5033.9  935.26  5034.1  934.76
  5037.9  935.26  5115.0  941.50  5171.3  943.43  5285.9  951.25  5321.3  951.07
  5335.9  953.07  5406.7  954.34  5485.9  958.87  5521.3  958.24  5600.5  961.31
  5821.3  961.36  5835.9  964.20  5856.7  962.65  5885.9  965.93  5970.9  967.06
#Mann=3,-1,0
  3788.8    0.05       0  5033.9   0.033       0  5037.9    0.05       0
Bank Sta=5033.9,5037.9
Exp/Cntr=0.3,0.1

Type RM Length L Ch R = 1,21508,407,407,407
BEGIN DESCRIPTION:
Upper Denton 98 41.0
END DESCRIPTION:
XS GIS Cut Line= 3
      2215123.67      7225718.50      2214639.27      7224817.41
      2214248.66      7223619.52
#Sta/Elev= 30
  3969.2  971.50  3987.1  973.08  3992.8  970.91  4009.0  974.09  4103.7  969.20
  4200.5  961.49  4326.3  956.72  4386.4  952.61  4414.0  952.75  4577.9  941.86
  4677.7  938.79  4753.0  938.77  4960.1  934.99  5036.4  933.56  5037.2  933.06
  5042.0  933.56  5126.2  934.98  5166.8  940.13  5226.0  940.48  5299.7  939.92
  5368.7  943.88  5491.1  953.28  5554.9  955.81  5568.0  959.77  5586.8  959.73
  5599.6  962.17  5655.9  965.98  5862.5  972.64  6125.5  985.70  6252.2  987.87
#Mann=7,-1,0
  3969.2    0.05       0  4677.7    0.12       0  4753.0    0.05       0
  4960.1    0.12       0  5036.4    0.07       0  5042.0    0.12       0
  5226.0    0.05       0
Bank Sta=5036.4,5042
Exp/Cntr=0.3,0.1

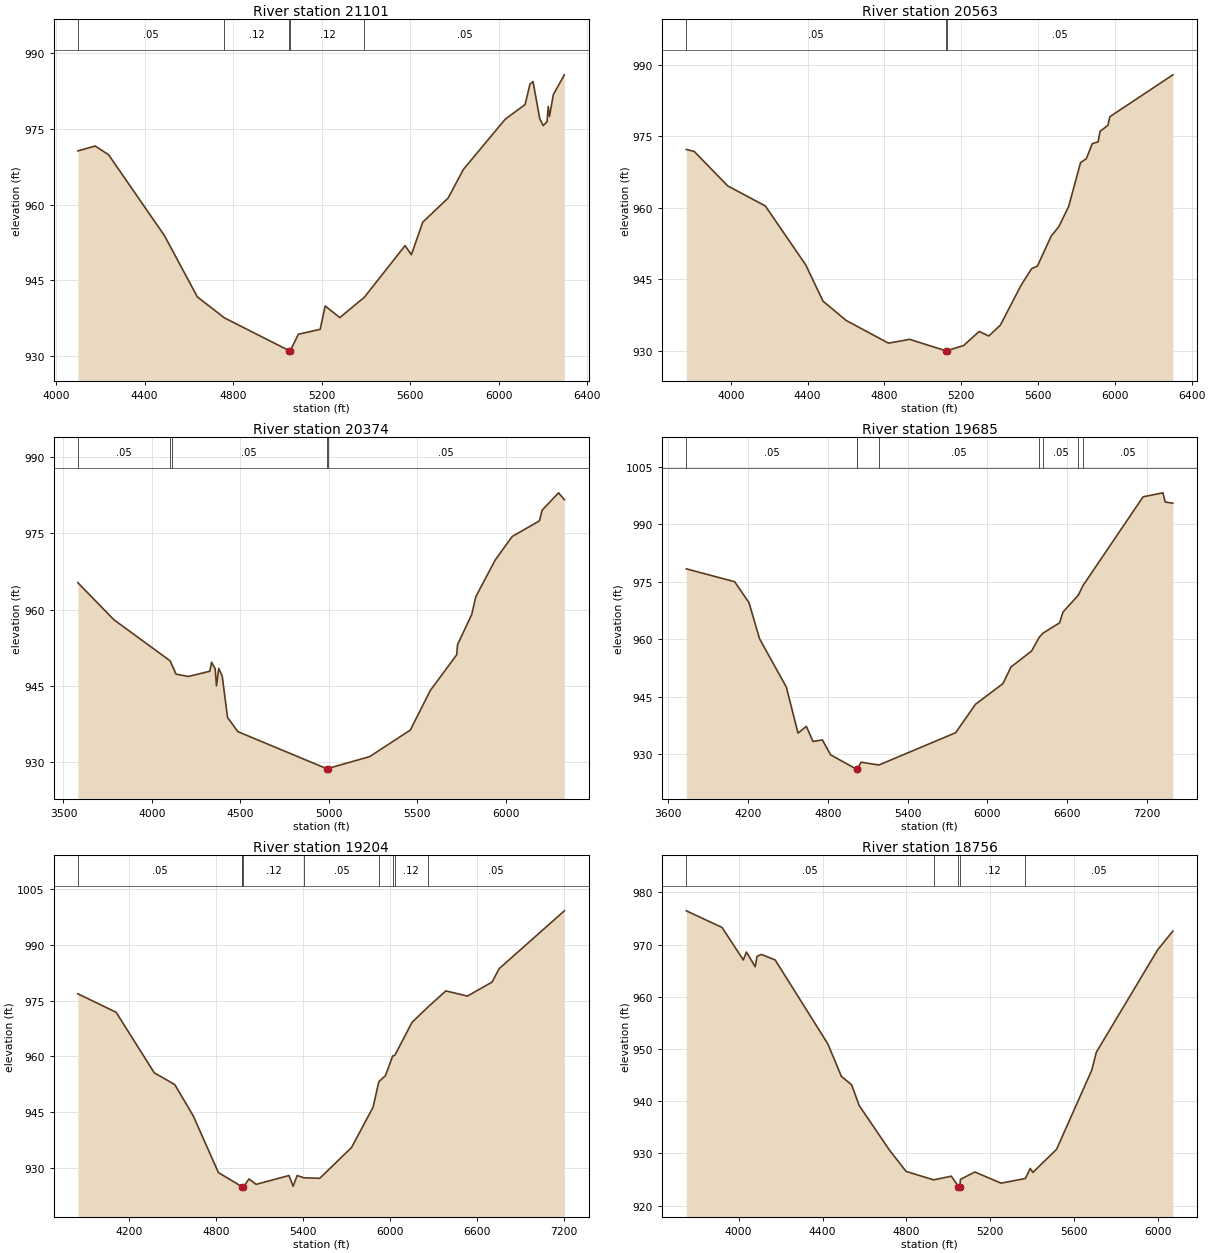
Type RM Length L Ch R = 1,21101,538,538,538
BEGIN DESCRIPTION:
Upper Denton 98 40.0
END DESCRIPTION:
XS GIS Cut Line= 3
      2215373.65      7225588.24      2215029.00      7224760.00
      2214483.51      7223578.87
#Sta/Elev= 30
  4098.8  970.66  4177.1  971.63  4237.7  969.90  4490.3  953.84  4638.5  941.71
  4761.0  937.54  5053.2  931.05  5054.0  930.55  5058.8  931.05  5095.0  934.30
  5193.6  935.27  5216.2  939.91  5282.3  937.60  5393.5  941.65  5577.2  951.88
  5605.6  950.06  5657.0  956.53  5771.7  961.31  5840.6  966.99  6029.6  976.95
  6119.4  979.86  6141.4  983.90  6155.3  984.42  6185.5  977.06  6201.2  975.68
  6218.6  976.46  6224.1  979.47  6229.6  977.50  6247.1  981.84  6296.9  985.75
#Mann=5,-1,0
  4098.8    0.05       0  4761.0    0.12       0  5053.2    0.07       0
  5058.8    0.12       0  5393.5    0.05       0
Bank Sta=5053.2,5058.8
Exp/Cntr=0.3,0.1

Type RM Length L Ch R = 1,20563,189,189,189
BEGIN DESCRIPTION:
Upper Denton 98 39.0
END DESCRIPTION:
XS GIS Cut Line= 4
      2215420.52      7225770.58      2215498.65      7224525.75
      2215550.44      7224065.84      2215388.42      7223258.43
#Sta/Elev= 30
  3768.5  972.23  3809.2  971.83  3984.1  964.60  4179.9  960.40  4390.3  948.05
  4480.5  940.45  4600.7  936.42  4821.1  931.66  4931.4  932.46  5119.3  930.07
  5120.2  929.57  5125.0  930.07  5212.8  931.17  5293.3  934.11  5343.6  933.16
  5404.0  935.45  5510.7  943.72  5566.7  947.28  5596.7  947.80  5668.5  954.09
  5708.9  956.10  5759.9  960.34  5821.3  969.48  5851.7  970.32  5882.3  973.45
  5912.9  973.83  5923.1  976.03  5963.8  977.29  5974.1  979.10  6302.1  987.87
#Mann=3,-1,0
  3768.5    0.05       0  5119.3   0.033       0  5125.0    0.05       0
Bank Sta=5119.3,5125
Exp/Cntr=0.3,0.1

Type RM Length L Ch R = 1,20374,689,689,689
BEGIN DESCRIPTION:
Upper Denton 98 38.0
END DESCRIPTION:
XS GIS Cut Line= 4
      2215519.48      7225833.07      2215634.07      7224442.41
      2215665.84      7223965.83      2215496.92      7223106.48
#Sta/Elev= 30
  3581.5  965.32  3785.3  958.03  4102.6  949.96  4111.2  949.30  4136.4  947.33
  4206.7  946.88  4327.1  947.91  4337.1  949.69  4357.2  948.39  4364.7  945.03
  4377.3  948.47  4397.3  946.89  4427.4  938.80  4485.8  936.02  4986.4  928.76
  4987.3  928.26  4992.2  928.76  5229.8  931.11  5459.7  936.33  5572.7  944.12
  5721.8  951.15  5726.9  953.16  5807.0  959.09  5829.7  962.56  5939.4  969.78
  6035.3  974.41  6189.5  977.49  6204.4  979.58  6297.4  983.00  6330.3  981.66
#Mann=5,-1,0
  3581.5    0.05       0  4102.6    0.12       0  4111.2    0.05       0
  4986.4   0.033       0  4992.2    0.05       0
Bank Sta=4986.4,4992.2
Exp/Cntr=0.3,0.1

Type RM Length L Ch R = 1,19685,481,481,481
BEGIN DESCRIPTION:
Upper Denton 98 37.0
END DESCRIPTION:
XS GIS Cut Line= 4
      2216174.00      7225819.13      2216279.00      7224560.00
      2216285.40      7224432.40      2215528.51      7222295.97
#Sta/Elev= 30
  3736.9  978.35  4100.1  974.99  4207.7  969.56  4287.9  960.07  4488.6  947.53
  4576.6  935.50  4639.2  937.27  4689.3  933.32  4759.6  933.73  4822.3  929.82
  5017.1  926.09  5018.2  925.59  5023.7  926.09  5050.5  927.92  5184.2  927.18
  5761.6  935.61  5910.7  943.02  6116.3  948.39  6178.1  952.76  6332.5  956.92
  6390.8  960.54  6419.2  961.60  6543.4  964.28  6569.0  967.10  6684.6  971.52
  6717.8  973.92  7170.8  997.14  7319.9  998.18  7337.4  995.78  7394.7  995.48
#Mann=8,-1,0
  3736.9    0.05       0  5017.1   0.033       0  5023.7    0.05       0
  5184.2    0.05       0  6390.8    0.12       0  6419.2    0.05       0
  6684.6    0.12       0  6717.8    0.05       0
Bank Sta=5017.1,5023.7
Exp/Cntr=0.3,0.1

Type RM Length L Ch R = 1,19204,448,448,448
BEGIN DESCRIPTION:
Upper Denton 98 36.0
END DESCRIPTION:
XS GIS Cut Line= 3
      2216363.53      7225760.50      2216729.00      7224660.00
      2218218.33      7223043.76
#Sta/Elev= 30
  3844.5  976.83  4108.5  971.86  4371.9  955.62  4513.2  952.46  4639.9  944.13
  4814.4  928.84  4977.2  925.05  4979.7  924.90  4980.7  924.40  4986.3  924.90
  5025.4  927.14  5074.7  925.68  5301.5  928.05  5329.9  925.17  5357.7  928.05
  5403.7  927.45  5513.6  927.30  5733.1  935.57  5881.7  946.39  5921.5  953.24
  5966.7  954.84  6017.2  960.14  6031.6  960.29  6150.5  969.16  6259.4  973.23
  6384.1  977.60  6532.7  976.21  6702.8  979.97  6752.1  983.59  7201.9  999.09
#Mann=9,-1,0
  3844.5    0.05       0  4977.2    0.12       0  4979.7    0.07       0
  4986.3    0.12       0  5403.7    0.05       0  5921.5    0.12       0
  6017.2    0.05       0  6031.6    0.12       0  6259.4    0.05       0
Bank Sta=4979.7,4986.3
Exp/Cntr=0.3,0.1

Type RM Length L Ch R = 1,18756,485,485,485
BEGIN DESCRIPTION:
Upper Denton 98 35.0
END DESCRIPTION:
XS GIS Cut Line= 3
      2216419.95      7225838.64      2217129.00      7224810.00
      2217652.61      7223876.80
#Sta/Elev= 30
  3750.7  976.45  3920.8  973.27  4022.2  967.05  4037.1  968.56  4079.0  965.75
  4087.8  967.74  4108.8  968.10  4174.1  967.05  4425.3  950.97  4489.9  944.75
  4538.8  943.13  4574.9  939.16  4720.7  930.54  4798.5  926.55  4929.8  924.93
  5013.8  925.64  5048.0  923.66  5049.1  923.16  5054.7  923.66  5057.4  925.02
  5126.2  926.44  5251.0  924.30  5367.2  925.20  5389.9  927.12  5402.8  926.36
  5515.7  930.78  5683.5  945.94  5705.2  949.37  5997.6  968.98  6070.1  972.57
#Mann=5,-1,0
  3750.7    0.05       0  4929.8    0.12       0  5048.0    0.07       0
  5054.7    0.12       0  5367.2    0.05       0
Bank Sta=5048,5054.7
Exp/Cntr=0.3,0.1

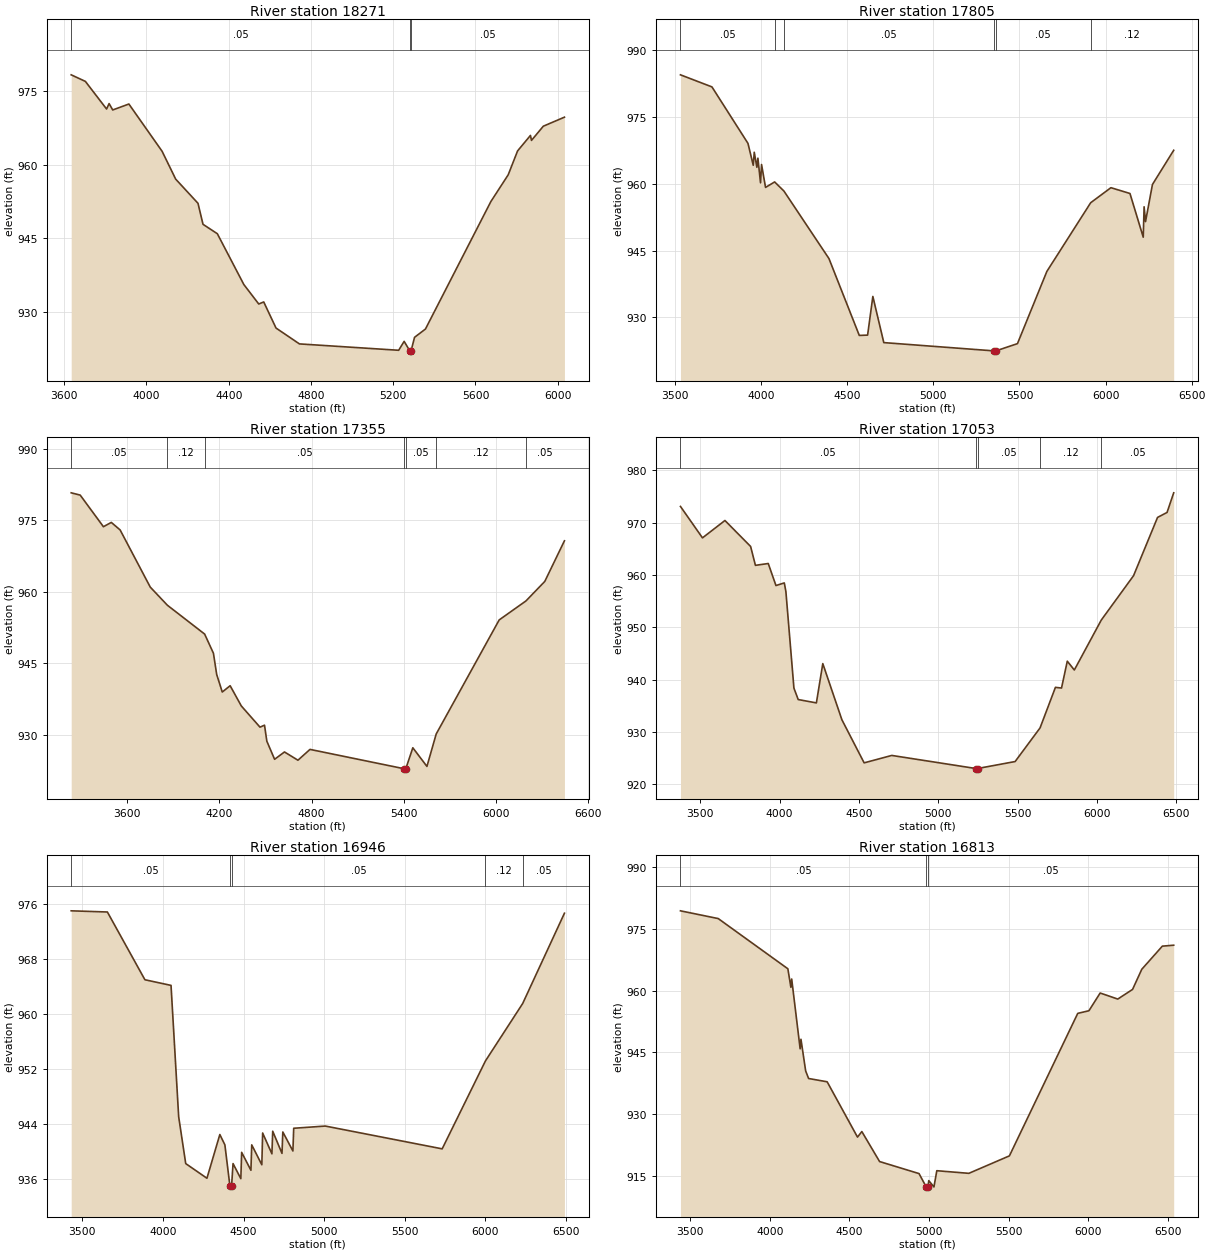
Type RM Length L Ch R = 1,18271,466,466,466
BEGIN DESCRIPTION:
Upper Denton 98 34.0
END DESCRIPTION:
XS GIS Cut Line= 3
      2217079.66      7226181.55      2217579.00      7224910.00
      2217739.38      7223889.91
#Sta/Elev= 30
  3633.9  978.33  3702.9  976.99  3806.0  971.36  3818.2  972.47  3835.8  971.17
  3914.4  972.38  4076.0  962.75  4142.0  957.08  4250.5  952.15  4274.9  947.87
  4344.6  945.95  4473.6  935.59  4546.0  931.63  4570.2  932.05  4630.0  926.73
  4743.8  923.50  5226.5  922.20  5253.1  924.02  5280.0  922.12  5281.1  921.62
  5286.9  922.12  5303.7  924.84  5356.7  926.53  5674.6  952.49  5759.2  957.96
  5804.8  962.83  5867.3  965.98  5872.4  964.97  5929.9  967.86  6032.6  969.70
#Mann=3,-1,0
  3633.9    0.05       0  5280.0   0.033       0  5286.9    0.05       0
Bank Sta=5280,5286.9
Exp/Cntr=0.3,0.1

Type RM Length L Ch R = 1,17805,450,450,450
BEGIN DESCRIPTION:
Upper Denton 98 33.0
END DESCRIPTION:
XS GIS Cut Line= 3
      2217194.81      7226347.41      2217979.00      7225110.00
      2218121.87      7223717.28
#Sta/Elev= 30
  3530.7  984.40  3713.6  981.69  3922.9  969.02  3953.4  964.12  3959.3  967.04
  3974.6  963.66  3980.5  965.71  3995.7  960.18  4001.7  964.29  4024.9  959.15
  4077.7  960.38  4131.4  958.35  4393.2  943.20  4569.4  925.96  4617.7  926.03
  4648.2  934.70  4711.8  924.35  5352.4  922.49  5353.9  921.99  5362.7  922.49
  5488.2  924.12  5659.1  940.32  5913.6  955.72  6031.1  959.09  6141.7  957.79
  6218.8  947.99  6223.8  954.81  6232.1  951.48  6272.3  959.81  6395.7  967.48
#Mann=6,-1,0
  3530.7    0.05       0  4077.7    0.12       0  4131.4    0.05       0
  5352.4   0.033       0  5362.7    0.05       0  5913.6    0.12       0
Bank Sta=5352.4,5362.7
Exp/Cntr=0.3,0.1

Type RM Length L Ch R = 1,17355,302,302,302
BEGIN DESCRIPTION:
Upper Denton 98 32.0
END DESCRIPTION:
XS GIS Cut Line= 3
      2217470.81      7226592.27      2218429.00      7225110.00
      2218720.45      7223693.07
#Sta/Elev= 30
  3235.0  980.75  3293.7  980.27  3444.8  973.64  3496.2  974.54  3553.6  972.96
  3749.7  960.97  3861.0  957.17  4103.9  951.11  4161.2  947.08  4182.3  942.64
  4218.6  938.95  4270.0  940.27  4342.6  936.03  4464.2  931.58  4493.7  931.99
  4508.9  928.63  4559.4  924.83  4623.7  926.37  4711.4  924.64  4789.9  926.91
  5403.0  922.85  5404.5  922.35  5413.7  922.85  5459.4  927.25  5551.3  923.34
  5611.6  930.14  6021.8  954.08  6196.3  958.07  6318.7  962.16  6446.6  970.68
#Mann=7,-1,0
  3235.0    0.05       0  3861.0    0.12       0  4103.9    0.05       0
  5403.0   0.033       0  5413.7    0.05       0  5611.6    0.12       0
  6196.3    0.05       0
Bank Sta=5403,5413.7
Exp/Cntr=0.3,0.1

Type RM Length L Ch R = 1,17053,107,107,107
BEGIN DESCRIPTION:
Upper Denton 98 31.5
END DESCRIPTION:
XS GIS Cut Line= 3
      2218496.88      7226717.24      2218731.25      7225107.86
      2218918.75      7223639.14
#Sta/Elev= 30
  3375.4  973.10  3514.1  967.09  3655.6  970.41  3817.3  965.45  3847.6  961.84
  3928.4  962.19  3976.9  957.98  4029.5  958.48  4039.6  956.81  4090.1  938.38
  4117.1  936.19  4231.6  935.55  4272.0  943.06  4392.3  932.33  4532.4  924.09
  4706.5  925.51  5236.2  923.01  5237.6  922.51  5246.9  923.01  5483.5  924.34
  5640.6  930.77  5737.4  938.52  5775.8  938.39  5812.1  943.52  5856.5  941.84
  6026.2  951.38  6229.5  959.86  6380.7  971.00  6440.5  971.95  6482.4  975.70
#Mann=5,-1,0
  3375.4    0.05       0  5236.2   0.033       0  5246.9    0.05       0
  5640.6    0.12       0  6026.2    0.05       0
Bank Sta=5236.2,5246.9
Exp/Cntr=0.3,0.1

Type RM Length L Ch R = 1,16946,133,133,133
BEGIN DESCRIPTION:
Upper Denton 98 31.0
END DESCRIPTION:
XS GIS Cut Line= 3
      2218580.20      7226701.65      2218825.00      7225144.31
      2219028.13      7223675.55
#Sta/Elev= 30
  3431.3  974.94  3655.7  974.77  3888.5  964.93  4050.5  964.11  4097.9  945.03
  4141.6  938.23  4273.2  936.10  4353.2  942.45  4384.5  940.95  4415.5  935.02
  4416.9  934.52  4426.2  935.02  4435.1  938.23  4483.4  936.04  4488.5  939.86
  4546.0  937.26  4551.0  940.95  4613.6  938.06  4618.7  942.67  4676.2  939.65
  4681.2  942.93  4738.7  939.71  4743.8  942.82  4806.4  940.06  4811.4  943.36
  5007.4  943.68  5732.2  940.37  6000.6  953.14  6231.6  961.48  6490.5  974.59
#Mann=5,-1,0
  3431.3    0.05       0  4415.5   0.033       0  4426.2    0.05       0
  6000.6    0.12       0  6231.6    0.05       0
Bank Sta=4415.5,4426.2
Exp/Cntr=0.3,0.1

Type RM Length L Ch R = 1,16813,385,385,385
BEGIN DESCRIPTION:
Upper Denton 98 30.5
END DESCRIPTION:
XS GIS Cut Line= 3
      2218658.34      7226743.25      2218944.79      7225180.77
      2219101.04      7223680.81
#Sta/Elev= 30
  3439.5  979.34  3676.6  977.46  4113.8  965.28  4132.7  960.79  4137.8  962.80
  4190.9  945.86  4196.0  948.18  4225.6  940.48  4244.1  938.66  4360.5  937.86
  4551.0  924.44  4578.2  925.79  4689.6  918.51  4937.3  915.59  4982.8  912.32
  4984.2  911.82  4993.5  912.32  4998.3  913.88  5030.9  912.35  5048.9  916.29
  5250.0  915.65  5504.7  919.89  5933.7  954.46  6004.0  955.10  6074.4  959.40
  6185.0  957.93  6277.8  960.27  6335.8  965.16  6464.8  970.77  6536.1  971.00
#Mann=3,-1,0
  3439.5    0.05       0  4982.8   0.033       0  4993.5    0.05       0
Bank Sta=4982.8,4993.5
Exp/Cntr=0.3,0.1

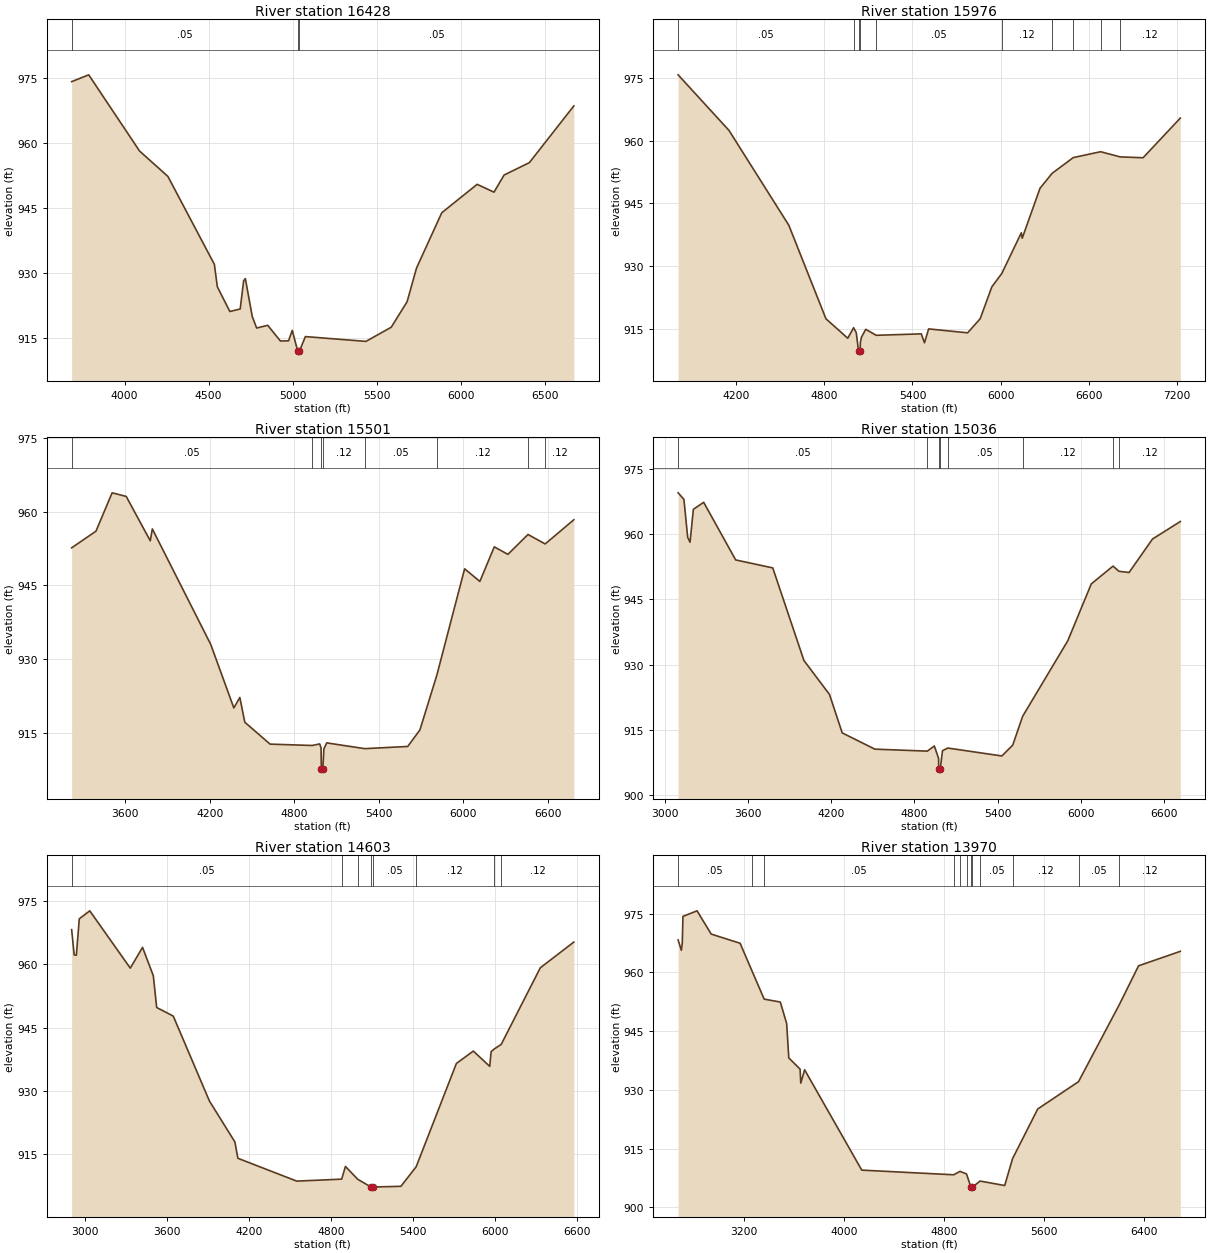
Type RM Length L Ch R = 1,16428,452,452,452
BEGIN DESCRIPTION:
Upper Denton 98 30.0
END DESCRIPTION:
XS GIS Cut Line= 3
      2218996.87      7226639.14      2219279.00      7225360.00
      2219168.75      7223686.01
#Sta/Elev= 30
  3684.9  974.20  3786.4  975.78  4089.0  958.18  4257.5  952.32  4534.0  932.01
  4551.5  926.84  4626.1  921.12  4687.6  921.71  4708.1  928.23  4718.3  928.72
  4759.3  919.97  4785.4  917.31  4851.4  917.93  4926.7  914.32  4975.5  914.35
  4997.3  916.77  5029.5  912.01  5031.0  911.51  5040.3  912.01  5075.4  915.33
  5435.7  914.22  5586.1  917.49  5680.4  923.37  5736.4  931.14  5886.7  943.93
  6097.2  950.49  6197.4  948.68  6257.5  952.64  6407.8  955.50  6672.4  968.60
#Mann=3,-1,0
  3684.9    0.05       0  5029.5   0.033       0  5040.3    0.05       0
Bank Sta=5029.5,5040.3
Exp/Cntr=0.3,0.1

Type RM Length L Ch R = 1,15976,475,475,475
BEGIN DESCRIPTION:
Upper Denton 98 29.0
END DESCRIPTION:
XS GIS Cut Line= 3
      2219121.87      7226560.99      2219679.00      7225510.00
      2221006.36      7223723.70
#Sta/Elev= 30
  3806.2  975.79  4152.4  962.47  4559.0  939.78  4811.6  917.38  4959.9  912.72
  4999.6  915.25  5017.6  914.07  5033.1  909.66  5034.6  909.16  5043.9  909.66
  5045.6  911.76  5053.1  912.99  5082.3  914.86  5153.0  913.43  5459.9  913.77
  5481.6  911.63  5509.9  914.96  5774.9  914.02  5860.4  917.40  5939.7  925.04
  6007.2  928.22  6140.0  937.97  6146.2  936.67  6267.2  948.63  6349.5  952.21
  6493.6  955.98  6679.5  957.38  6812.5  956.14  6968.1  955.94  7221.2  965.43
#Mann=10,-1,0
  3806.2    0.05       0  4999.6    0.12       0  5033.1    0.07       0
  5043.9    0.12       0  5153.0    0.05       0  6007.2    0.12       0
  6349.5    0.05       0  6493.6    0.12       0  6679.5    0.05       0
  6812.5    0.12       0
Bank Sta=5033.1,5043.9
Exp/Cntr=0.3,0.1

Type RM Length L Ch R = 1,15501,465,465,465
BEGIN DESCRIPTION:
Upper Denton 98 28.0
END DESCRIPTION:
XS GIS Cut Line= 5
      2219191.17      7226983.87      2220118.23      7225739.11
      2220129.00      7225510.00      2220159.90      7225280.77
      2220924.77      7223927.94
#Sta/Elev= 30
  3218.6  952.67  3391.3  956.06  3506.0  963.87  3606.1  963.14  3777.0  954.10
  3791.7  956.52  4206.7  932.99  4370.5  920.07  4413.1  922.20  4448.5  917.16
  4627.9  912.70  4926.8  912.42  4980.0  912.74  4990.0  911.95  4992.1  907.70
  4993.6  907.20  5002.9  907.70  5010.1  911.73  5030.3  912.95  5299.8  911.78
  5605.5  912.22  5692.1  915.59  5812.2  926.72  6009.7  948.40  6117.9  945.83
  6220.4  952.87  6317.2  951.34  6459.8  955.39  6581.8  953.46  6785.4  958.39
#Mann=8,-1,0
  3218.6    0.05       0  4926.8    0.12       0  4992.1    0.07       0
  5002.9    0.12       0  5299.8    0.05       0  5812.2    0.12       0
  6459.8    0.05       0  6581.8    0.12       0
Bank Sta=4992.1,5002.9
Exp/Cntr=0.3,0.1

Type RM Length L Ch R = 1,15036,433,433,433
BEGIN DESCRIPTION:
Upper Denton 98 27.0
END DESCRIPTION:
XS GIS Cut Line= 4
      2220175.52      7227327.66      2220579.00      7225460.00
      2220628.65      7224994.31      2220992.72      7223803.29
#Sta/Elev= 30
  3094.5  969.45  3136.4  967.95  3163.7  959.21  3180.5  958.11  3204.6  965.67
  3279.1  967.27  3510.0  954.04  3777.6  952.21  4002.6  930.95  4186.8  923.17
  4278.9  914.33  4514.2  910.60  4893.1  910.14  4943.9  911.32  4974.6  908.47
  4974.9  906.05  4976.5  905.55  4986.4  906.05  5002.7  910.24  5041.0  910.85
  5431.2  909.03  5509.5  911.52  5581.1  918.14  5907.2  935.50  6076.4  948.53
  6233.5  952.63  6276.2  951.43  6349.2  951.16  6518.3  958.84  6719.0  962.86
#Mann=8,-1,0
  3094.5    0.05       0  4893.1    0.12       0  4974.9    0.07       0
  4986.4    0.12       0  5041.0    0.05       0  5581.1    0.12       0
  6233.5    0.05       0  6276.2    0.12       0
Bank Sta=4974.9,4986.4
Exp/Cntr=0.3,0.1

Type RM Length L Ch R = 1,14603,633,633,633
BEGIN DESCRIPTION:
Upper Denton 98 26.0
END DESCRIPTION:
XS GIS Cut Line= 3
      2220217.19      7227312.01      2220979.00      7225360.00
      2221055.73      7223785.97
#Sta/Elev= 30
  2903.8  968.23  2922.3  962.24  2938.2  962.16  2959.6  970.80  3036.3  972.69
  3332.5  959.09  3422.1  964.02  3500.9  957.28  3525.4  949.75  3646.6  947.71
  3911.2  927.55  4097.5  917.83  4119.0  913.97  4549.5  908.55  4877.9  909.02
  4905.4  912.03  4994.9  909.00  5092.3  907.15  5093.9  906.65  5103.8  907.15
  5310.9  907.32  5422.4  911.95  5716.5  936.47  5840.2  939.41  5960.3  935.78
  5970.4  939.28  5992.6  939.89  6044.2  941.00  6330.0  959.17  6575.1  965.28
#Mann=8,-1,0
  2903.8    0.05       0  4877.9    0.12       0  4994.9    0.05       0
  5092.3   0.033       0  5103.8    0.05       0  5422.4    0.12       0
  5992.6    0.05       0  6044.2    0.12       0
Bank Sta=5092.3,5103.8
Exp/Cntr=0.3,0.1

Type RM Length L Ch R = 1,13970,318,318,318
BEGIN DESCRIPTION:
Upper Denton 98 25.0
END DESCRIPTION:
XS GIS Cut Line= 5
      2220258.84      7227343.32      2220738.02      7226348.48
      2221555.73      7225504.73      2221639.06      7225343.27
      2221352.61      7223806.84
#Sta/Elev= 30
  2670.5  968.26  2696.4  965.62  2703.7  967.38  2709.2  974.27  2822.3  975.69
  2935.5  969.76  3167.2  967.41  3265.5  960.13  3359.9  953.16  3489.5  952.41
  3540.3  946.92  3557.3  938.16  3647.8  935.29  3653.4  931.72  3684.2  935.12
  4142.1  909.52  4878.3  908.33  4929.2  909.20  4981.2  908.55  5016.7  905.17
  5018.3  904.67  5028.4  905.17  5089.8  906.73  5287.3  905.59  5350.3  912.45
  5551.8  925.12  5878.7  932.09  6206.3  951.79  6359.9  961.66  6694.3  965.35
#Mann=12,-1,0
  2670.5    0.05       0  3265.5    0.12       0  3359.9    0.05       0
  4878.3    0.12       0  4929.2    0.05       0  4981.2    0.12       0
  5016.7    0.07       0  5028.4    0.12       0  5089.8    0.05       0
  5350.3    0.12       0  5878.7    0.05       0  6206.3    0.12       0
Bank Sta=5016.7,5028.4
Exp/Cntr=0.3,0.1