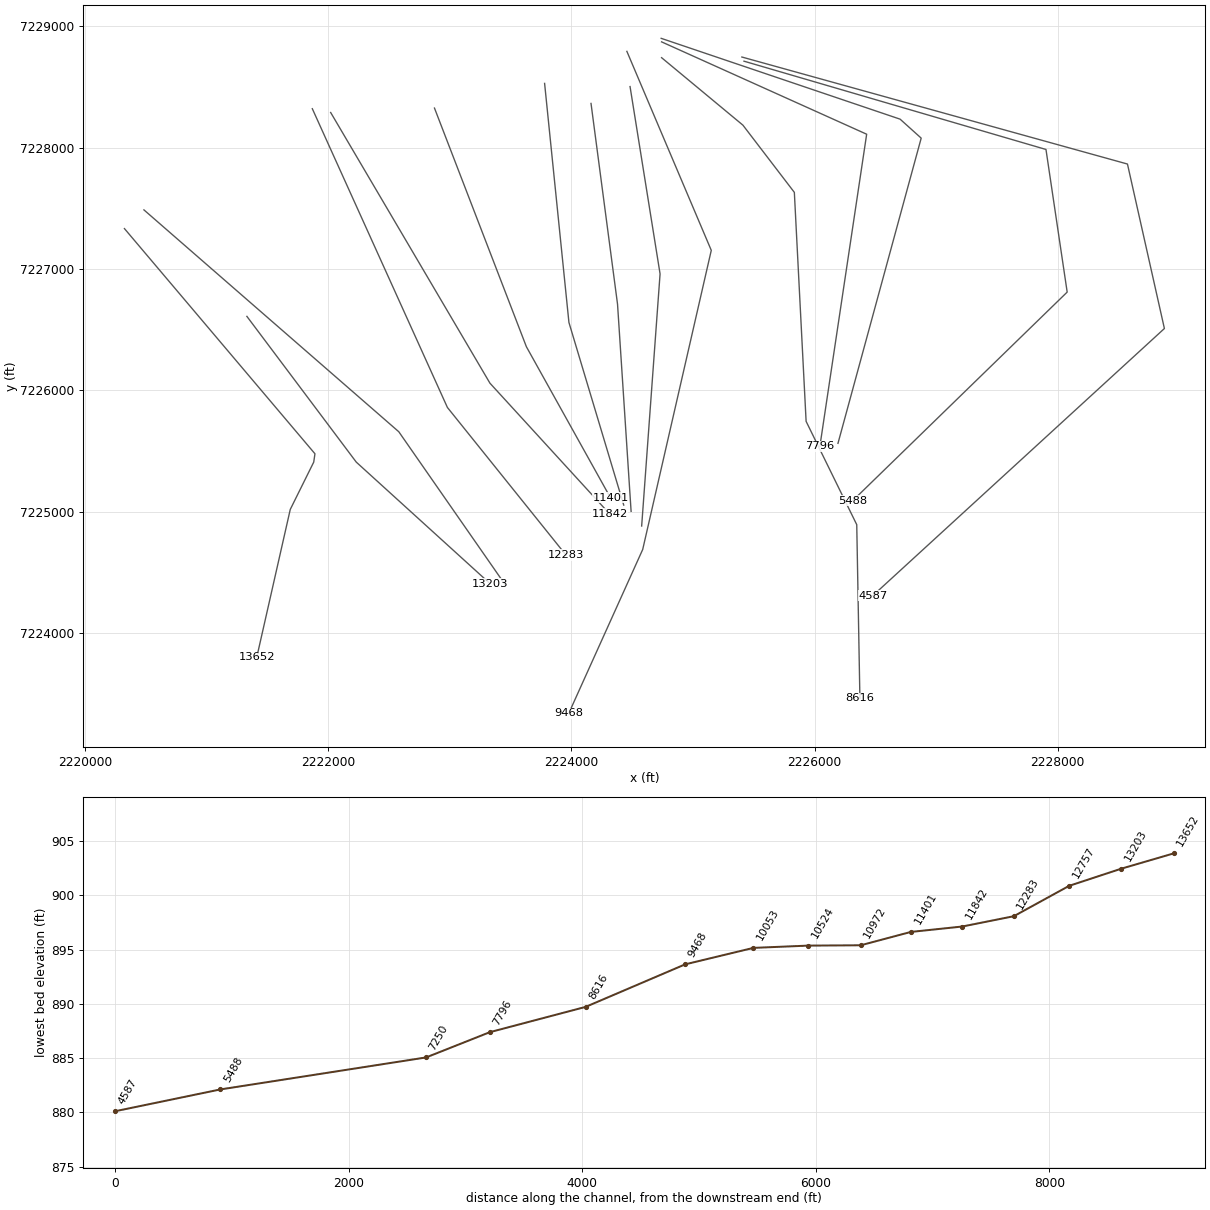
HEC-RAS study Upper Denton 98.prj: Upper Denton 98 Base Level Engineering

--- Upper Denton 98.g01 (geometry) --- (continued)

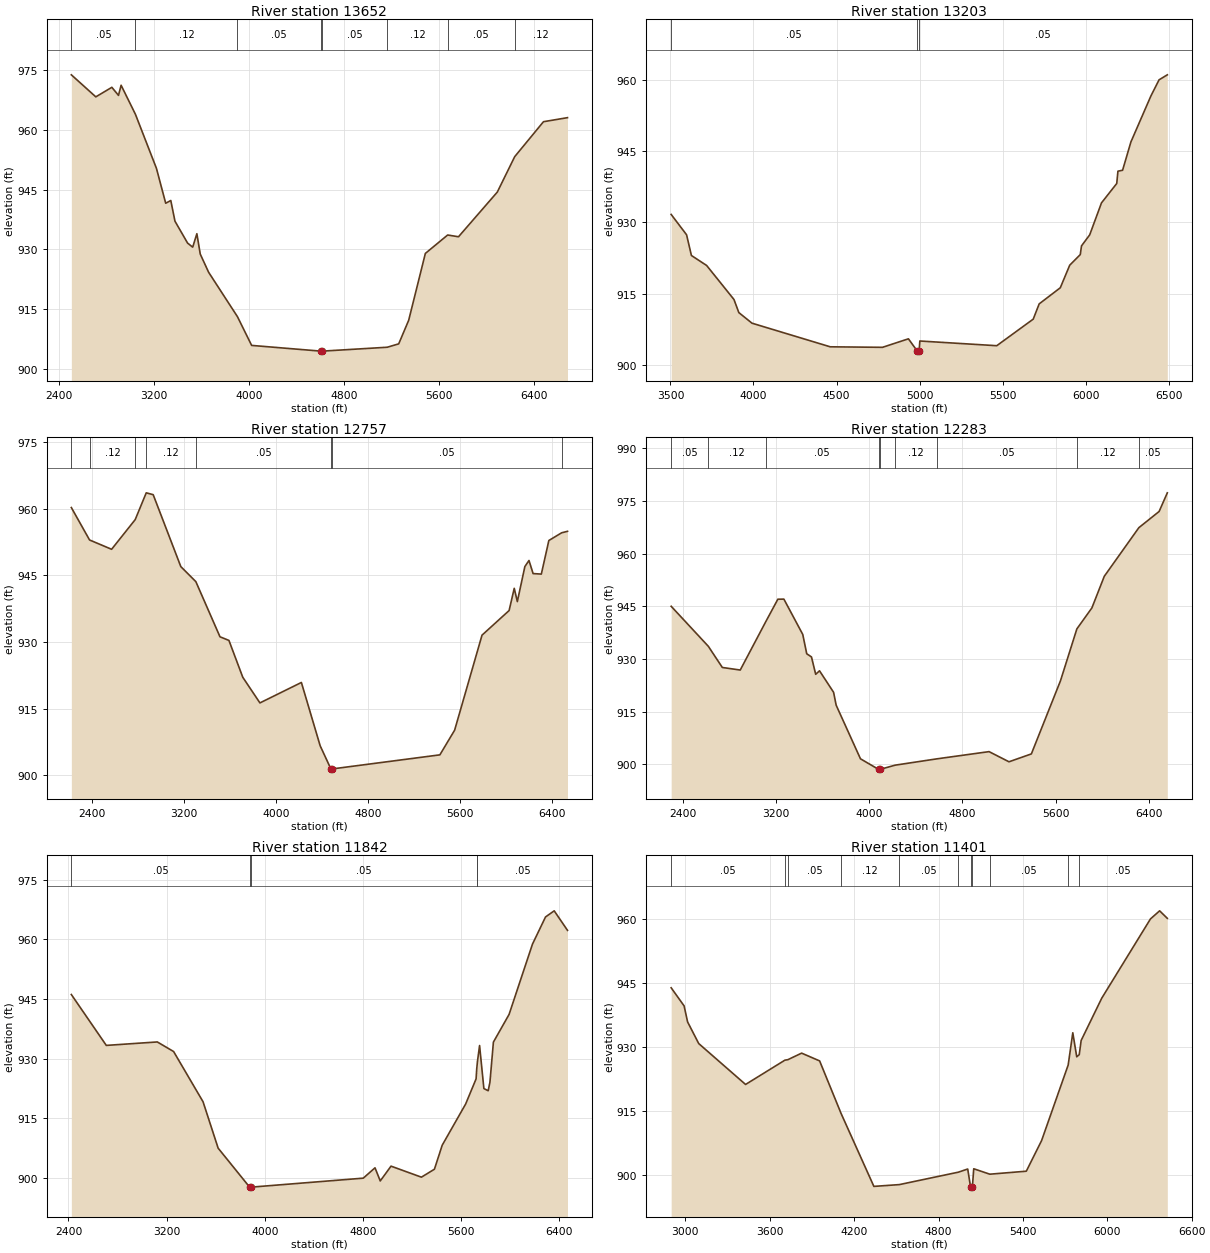
Type RM Length L Ch R = 1,13652,449,449,449
BEGIN DESCRIPTION:
Upper Denton 98 24.0
END DESCRIPTION:
XS GIS Cut Line= 5
      2220321.34      7227332.87      2221889.06      7225478.69
      2221879.00      7225410.00      2221685.94      7225020.36
      2221410.28      7223803.27
#Sta/Elev= 30
  2503.0  973.86  2709.1  968.32  2844.3  970.72  2900.2  968.69  2922.3  971.24
  3042.9  963.94  3220.0  950.34  3298.0  941.57  3340.9  942.26  3376.0  937.06
  3482.6  931.54  3525.5  930.53  3560.6  933.91  3589.2  928.78  3659.5  924.22
  3902.5  913.05  4022.1  905.82  4605.2  904.38  4606.8  903.88  4616.9  904.38
  5164.6  905.36  5261.2  906.21  5345.3  912.14  5485.7  928.95  5673.6  933.58
  5765.0  933.14  6092.0  944.38  6238.7  953.29  6480.9  962.07  6683.3  963.09
#Mann=8,-1,0
  2503.0    0.05       0  3042.9    0.12       0  3902.5    0.05       0
  4605.2    0.04       0  4616.9    0.05       0  5164.6    0.12       0
  5673.6    0.05       0  6238.7    0.12       0
Bank Sta=4605.2,4616.9
Exp/Cntr=0.3,0.1

Type RM Length L Ch R = 1,13203,446,446,446
BEGIN DESCRIPTION:
Upper Denton 98 23.0
END DESCRIPTION:
XS GIS Cut Line= 3
      2221329.00      7226609.99      2222229.00      7225410.00
      2223329.00      7224410.00
#Sta/Elev= 30
  3504.5  931.65  3597.2  927.37  3626.4  923.01  3718.0  920.91  3882.6  913.75
  3911.8  911.00  3991.0  908.77  4461.8  903.80  4776.4  903.69  4932.6  905.48
  4984.7  902.97  4986.5  902.47  4997.3  902.97  5001.4  905.02  5464.3  904.03
  5683.9  909.62  5719.8  912.83  5846.8  916.22  5903.6  920.97  5967.1  923.20
  5974.5  925.03  6023.8  927.35  6094.8  934.08  6186.7  938.16  6193.8  940.75
  6221.8  940.94  6271.8  946.89  6392.1  956.56  6441.4  959.97  6491.1  961.02
#Mann=3,-1,0
  3504.5    0.05       0  4984.7    0.04       0  4997.3    0.05       0
Bank Sta=4984.7,4997.3
Exp/Cntr=0.3,0.1

Type RM Length L Ch R = 1,12757,474,474,474
BEGIN DESCRIPTION:
Upper Denton 98 22.0
END DESCRIPTION:
XS GIS Cut Line= 3
      2220481.92      7227486.81      2222579.00      7225660.00
      2223454.97      7224399.59
#Sta/Elev= 30
  2218.8  960.32  2377.2  953.01  2569.0  950.91  2774.3  957.60  2870.4  963.64
  2930.8  963.22  3171.0  947.01  3302.0  943.61  3511.8  931.18  3589.7  930.36
  3710.2  922.05  3859.3  916.27  4220.0  920.88  4383.3  906.61  4476.4  901.39
  4478.2  900.89  4489.2  901.39  5424.7  904.56  5553.0  910.12  5791.4  931.55
  6027.0  937.10  6071.6  942.11  6098.6  939.12  6164.1  947.02  6199.9  948.38
  6235.7  945.43  6307.3  945.32  6372.7  952.89  6484.1  954.63  6534.9  954.96
#Mann=8,-1,0
  2218.8    0.05       0  2377.2    0.12       0  2774.3    0.05       0
  2870.4    0.12       0  3302.0    0.05       0  4476.4   0.033       0
  4489.2    0.05       0  6484.1    0.12       0
Bank Sta=4476.4,4489.2
Exp/Cntr=0.3,0.1

Type RM Length L Ch R = 1,12283,441,441,441
BEGIN DESCRIPTION:
Upper Denton 98 21.0
END DESCRIPTION:
XS GIS Cut Line= 3
      2221867.37      7228320.10      2222979.00      7225860.00
      2223954.18      7224645.18
#Sta/Elev= 30
  2300.4  945.02  2619.2  933.63  2739.4  927.60  2893.1  926.87  3110.1  940.51
  3215.9  947.03  3267.6  947.06  3429.5  937.01  3463.7  931.50  3504.3  930.60
  3540.5  925.66  3573.4  926.65  3694.1  920.53  3716.1  916.87  3924.7  901.60
  4080.1  898.59  4081.9  898.09  4092.9  898.59  4222.7  899.79  4583.4  901.60
  5028.0  903.64  5199.2  900.75  5391.2  902.99  5640.9  923.80  5781.6  938.58
  5910.5  944.55  6016.9  953.56  6313.6  967.40  6487.4  972.01  6557.8  977.32
#Mann=9,-1,0
  2300.4    0.05       0  2619.2    0.12       0  3110.1    0.05       0
  4080.1   0.033       0  4092.9    0.05       0  4222.7    0.12       0
  4583.4    0.05       0  5781.6    0.12       0  6313.6    0.05       0
Bank Sta=4080.1,4092.9
Exp/Cntr=0.3,0.1

Type RM Length L Ch R = 1,11842,441,441,441
BEGIN DESCRIPTION:
Upper Denton 98 20.0
END DESCRIPTION:
XS GIS Cut Line= 3
      2222018.41      7228288.86      2223329.00      7226060.00
      2224314.64      7224982.28
#Sta/Elev= 30
  2423.3  946.10  2708.4  933.30  3124.3  934.17  3257.2  931.76  3497.4  919.12
  3620.4  907.45  3877.3  897.64  3879.1  897.14  3890.1  897.64  4803.9  899.90
  4899.6  902.50  4942.5  899.20  5030.2  902.92  5278.1  900.15  5384.2  902.15
  5447.7  908.19  5638.9  918.56  5724.0  924.88  5729.0  927.34  5735.3  929.31
  5752.4  933.27  5787.5  922.44  5822.6  921.90  5836.8  924.00  5865.2  934.13
  5992.9  941.09  6184.0  958.80  6290.1  965.61  6361.0  967.16  6469.4  962.25
#Mann=5,-1,0
  2423.3    0.05       0  3877.3   0.033       0  3890.1    0.05       0
  5729.0    0.12       0  5735.3    0.05       0
Bank Sta=3877.3,3890.1
Exp/Cntr=0.3,0.1

Type RM Length L Ch R = 1,11401,429,429,429
BEGIN DESCRIPTION:
Upper Denton 98 19.0
END DESCRIPTION:
XS GIS Cut Line= 3
      2222872.59      7228325.28      2223629.00      7226360.00
      2224320.48      7225117.01
#Sta/Elev= 30
  2898.7  943.81  2990.8  939.56  3015.4  935.82  3094.7  930.74  3427.8  921.16
  3707.9  926.86  3728.1  926.96  3826.3  928.50  3954.4  926.68  4107.2  914.35
  4340.2  897.28  4521.5  897.70  4940.8  900.61  5007.4  901.35  5027.9  897.14
  5029.7  896.64  5040.7  897.14  5050.3  901.41  5164.8  900.14  5424.2  900.84
  5532.8  908.01  5721.9  925.72  5754.7  933.27  5782.7  927.64  5800.6  928.14
  5814.2  931.47  5960.5  941.37  6307.0  959.94  6372.2  961.84  6426.9  960.08
#Mann=11,-1,0
  2898.7    0.05       0  3707.9    0.12       0  3728.1    0.05       0
  4107.2    0.12       0  4521.5    0.05       0  4940.8    0.12       0
  5027.9    0.07       0  5040.7    0.12       0  5164.8    0.05       0
  5721.9    0.12       0  5800.6    0.05       0
Bank Sta=5027.9,5040.7
Exp/Cntr=0.3,0.1

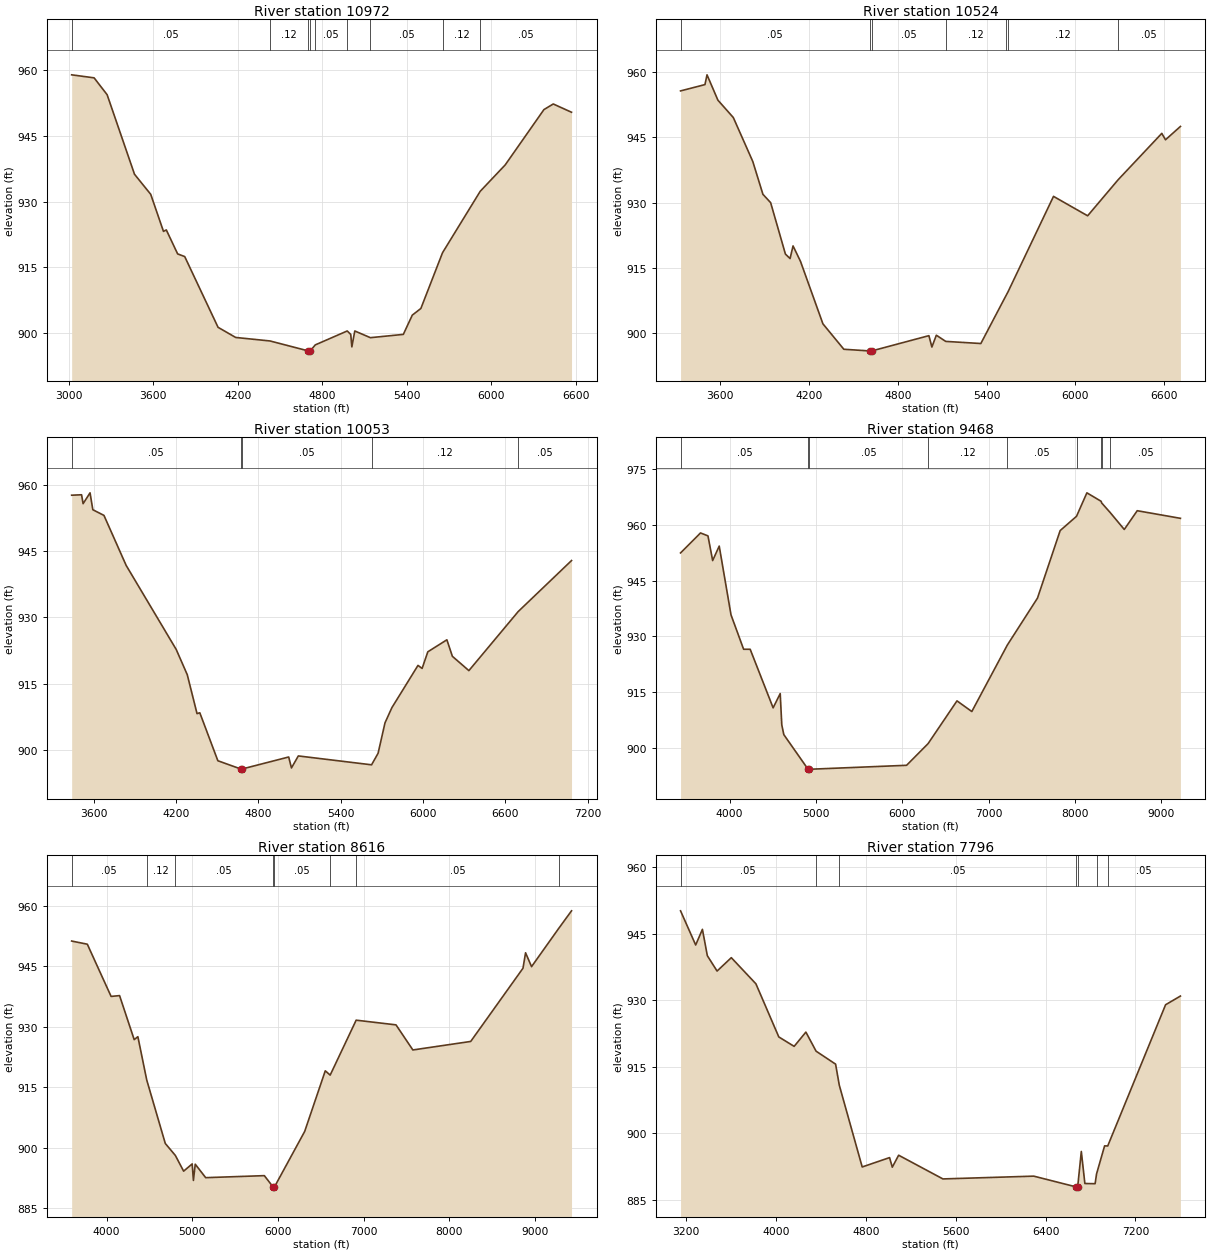
Type RM Length L Ch R = 1,10972,448,448,448
BEGIN DESCRIPTION:
Upper Denton 98 18.0
END DESCRIPTION:
XS GIS Cut Line= 3
      2223778.82      7228528.45      2223979.00      7226560.00
      2224429.86      7225056.24
#Sta/Elev= 30
  3021.4  958.99  3180.7  958.30  3273.2  954.45  3467.5  936.28  3582.7  931.69
  3673.2  923.22  3693.3  923.56  3773.7  918.08  3824.0  917.47  4060.6  901.31
  4185.8  898.99  4429.3  898.19  4702.1  895.91  4703.9  895.41  4714.9  895.91
  4750.8  897.29  4977.5  900.47  5002.6  899.69  5010.4  896.84  5031.3  900.47
  5142.1  898.94  5375.8  899.69  5439.5  904.09  5500.4  905.61  5654.2  918.35
  5921.7  932.38  6099.1  938.41  6374.1  951.05  6440.3  952.33  6569.9  950.44
#Mann=9,-1,0
  3021.4    0.05       0  4429.3    0.12       0  4702.1    0.07       0
  4714.9    0.12       0  4750.8    0.05       0  4977.5    0.12       0
  5142.1    0.05       0  5654.2    0.12       0  5921.7    0.05       0
Bank Sta=4702.1,4714.9
Exp/Cntr=0.3,0.1

Type RM Length L Ch R = 1,10524,471,471,471
BEGIN DESCRIPTION:
Upper Denton 98 17.0
END DESCRIPTION:
XS GIS Cut Line= 3
      2224160.77      7228363.48      2224379.00      7226710.00
      2224490.60      7225004.57
#Sta/Elev= 30
  3332.2  955.72  3497.1  957.17  3511.0  959.42  3584.5  953.59  3688.7  949.59
  3820.2  939.48  3888.6  931.93  3940.9  930.00  4040.7  918.17  4072.0  917.14
  4092.2  920.05  4142.6  916.49  4294.0  902.12  4435.2  896.27  4610.3  895.88
  4612.1  895.38  4623.1  895.88  5010.0  899.40  5030.1  896.78  5060.1  899.50
  5123.7  898.08  5360.8  897.59  5527.6  908.41  5544.2  909.47  5851.8  931.45
  6082.3  926.98  6288.7  935.29  6583.4  945.95  6608.2  944.47  6709.1  947.54
#Mann=7,-1,0
  3332.2    0.05       0  4610.3    0.04       0  4623.1    0.05       0
  5123.7    0.12       0  5527.6    0.05       0  5544.2    0.12       0
  6288.7    0.05       0
Bank Sta=4610.3,4623.1
Exp/Cntr=0.3,0.1

Type RM Length L Ch R = 1,10053,585,585,585
BEGIN DESCRIPTION:
Upper Denton 98 16.0
END DESCRIPTION:
XS GIS Cut Line= 3
      2224481.95      7228502.40      2224729.00      7226960.00
      2224577.52      7224883.78
#Sta/Elev= 30
  3438.5  957.65  3510.7  957.75  3522.0  955.73  3572.6  958.19  3592.8  954.36
  3673.9  953.08  3835.9  941.75  4200.5  922.73  4281.5  916.99  4352.4  908.19
  4372.7  908.38  4504.3  897.52  4670.1  895.67  4671.9  895.17  4682.9  895.67
  5020.6  898.37  5040.7  895.89  5090.8  898.61  5624.7  896.60  5672.3  899.22
  5722.5  906.09  5772.6  909.53  5963.1  919.11  5993.2  918.43  6034.8  922.19
  6173.7  924.91  6213.8  921.17  6334.1  917.93  6693.5  931.30  7082.3  942.85
#Mann=5,-1,0
  3438.5    0.05       0  4670.1    0.04       0  4682.9    0.05       0
  5624.7    0.12       0  6693.5    0.05       0
Bank Sta=4670.1,4682.9
Exp/Cntr=0.3,0.1

Type RM Length L Ch R = 1,9468,852,852,852
BEGIN DESCRIPTION:
Upper Denton 98 15.0
END DESCRIPTION:
XS GIS Cut Line= 4
      2224455.89      7228792.22      2225150.35      7227153.74
      2224586.11      7224690.63      2223977.61      7223340.95
#Sta/Elev= 30
  3432.6  952.44  3663.5  957.83  3750.0  957.04  3804.3  950.39  3880.3  954.29
  4016.6  935.77  4162.7  926.49  4238.7  926.49  4504.4  910.70  4586.3  914.55
  4604.6  906.11  4628.2  903.48  4909.1  894.15  4911.0  893.65  4922.5  894.15
  6049.4  895.22  6298.4  901.06  6632.9  912.58  6804.6  909.71  7215.2  927.60
  7564.8  940.27  7827.5  958.47  8016.9  962.32  8136.8  968.64  8301.1  966.37
  8309.2  965.88  8409.6  963.24  8569.7  958.77  8719.5  963.82  9219.6  961.77
#Mann=9,-1,0
  3432.6    0.05       0  4909.1    0.04       0  4922.5    0.05       0
  6298.4    0.12       0  7215.2    0.05       0  8016.9    0.12       0
  8301.1    0.05       0  8309.2    0.12       0  8409.6    0.05       0
Bank Sta=4909.1,4922.5
Exp/Cntr=0.3,0.1

Type RM Length L Ch R = 1,8616,820,820,820
BEGIN DESCRIPTION:
Upper Denton 98 14.0
END DESCRIPTION:
XS GIS Cut Line= 6
      2224741.48      7228740.27      2225410.77      7228184.56
      2225833.94      7227631.17      2225930.73      7225745.46
      2226347.40      7224894.77      2226373.42      7223463.71
#Sta/Elev= 30
  3593.3  951.21  3776.1  950.43  4053.5  937.49  4152.5  937.69  4323.0  926.78
  4366.0  927.51  4469.4  916.78  4685.9  901.05  4803.7  898.07  4899.9  894.18
  4999.7  895.98  5014.2  891.89  5035.4  895.91  5157.5  892.57  5841.9  893.07
  5945.3  890.23  5947.3  889.73  5958.8  890.23  6312.5  904.02  6552.9  919.05
  6610.2  917.99  6913.4  931.60  7378.2  930.44  7575.1  924.22  8250.1  926.33
  8860.2  944.47  8890.2  948.30  8960.2  944.87  9275.7  954.30  9426.6  958.70
#Mann=8,-1,0
  3593.3    0.05       0  4469.4    0.12       0  4803.7    0.05       0
  5945.3    0.04       0  5958.8    0.05       0  6610.2    0.12       0
  6913.4    0.05       0  9275.7    0.12       0
Bank Sta=5945.3,5958.8
Exp/Cntr=0.3,0.1

Type RM Length L Ch R = 1,7796,546,546,546
BEGIN DESCRIPTION:
Upper Denton 98 13.0
END DESCRIPTION:
XS GIS Cut Line= 3
      2224741.46      7228870.48      2226429.00      7228110.00
      2226043.79      7225538.57
#Sta/Elev= 30
  3149.3  950.19  3284.0  942.48  3344.0  946.01  3387.9  940.06  3474.6  936.60
  3601.3  939.62  3820.5  933.72  4024.1  921.74  4160.9  919.61  4265.4  922.83
  4356.0  918.53  4529.9  915.60  4562.9  910.84  4766.8  892.40  5010.4  894.51
  5034.8  892.35  5091.3  895.05  5485.6  889.70  6294.6  890.33  6672.1  887.90
  6674.0  887.40  6685.6  887.90  6717.9  895.90  6749.6  888.67  6840.6  888.62
  6853.9  890.86  6925.3  897.16  6953.1  897.14  7468.3  929.00  7600.4  930.96
#Mann=7,-1,0
  3149.3    0.05       0  4356.0    0.12       0  4562.9    0.05       0
  6672.1    0.04       0  6685.6    0.05       0  6853.9    0.12       0
  6953.1    0.05       0
Bank Sta=6672.1,6685.6
Exp/Cntr=0.3,0.1

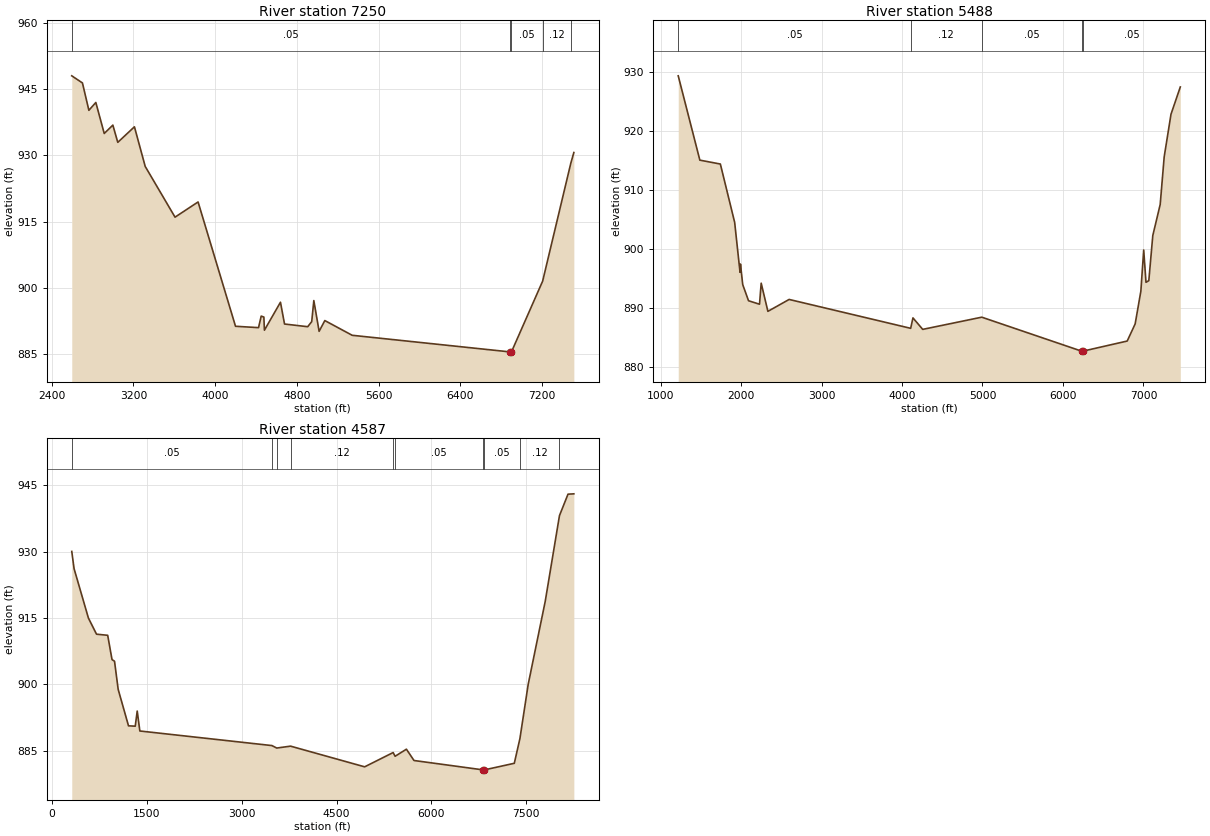
Type RM Length L Ch R = 1,7250,1762,1762,1762
BEGIN DESCRIPTION:
Upper Denton 98 12.5
END DESCRIPTION:
XS GIS Cut Line= 4
      2224738.04      7228899.54      2226704.12      7228234.01
      2226877.73      7228077.76      2226192.97      7225564.72
#Sta/Elev= 30
  2595.9  948.02  2700.4  946.41  2763.3  940.22  2831.4  941.99  2913.6  934.98
  2998.1  936.87  3046.1  932.97  3209.2  936.49  3314.8  927.52  3606.6  916.05
  3832.1  919.49  4198.5  891.37  4423.8  891.06  4449.9  893.67  4476.1  893.45
  4481.4  890.48  4638.5  896.81  4678.2  891.88  4905.1  891.27  4944.3  892.42
  4965.0  897.18  5016.8  890.23  5072.7  892.66  5340.5  889.33  6885.7  885.57
  6887.7  885.07  6899.2  885.57  7204.6  901.59  7479.9  928.23  7509.8  930.67
#Mann=5,-1,0
  2595.9    0.05       0  6885.7    0.04       0  6899.2    0.05       0
  7204.6    0.12       0  7479.9    0.05       0
Bank Sta=6885.7,6899.2
Exp/Cntr=0.3,0.1

Type RM Length L Ch R = 1,5488,901,901,901
BEGIN DESCRIPTION:
Upper Denton 98 12.0
END DESCRIPTION:
XS GIS Cut Line= 4
      2225419.43      7228711.43      2227904.51      7227984.42
      2228079.00      7226810.00      2226313.74      7225091.88
#Sta/Elev= 30
  1218.6  929.35  1487.3  915.04  1742.2  914.38  1919.8  904.49  1986.7  896.01
  1991.9  897.41  2020.1  893.92  2092.2  891.18  2228.8  890.59  2249.6  894.16
  2333.0  889.38  2596.8  891.40  4107.3  886.50  4135.8  888.27  4257.1  886.32
  4990.9  888.39  6233.0  882.62  6234.9  882.12  6246.5  882.62  6798.4  884.34
  6897.4  887.25  6968.1  892.79  7003.6  899.79  7031.9  894.31  7067.2  894.59
  7116.6  902.25  7208.6  907.52  7258.0  915.58  7342.9  922.84  7458.5  927.46
#Mann=5,-1,0
  1218.6    0.05       0  4107.3    0.12       0  4990.9    0.05       0
  6233.0   0.033       0  6246.5    0.05       0
Bank Sta=6233,6246.5
Exp/Cntr=0.3,0.1

Type RM Length L Ch R = 1,4587,0,0,0
BEGIN DESCRIPTION:
Upper Denton 98 10.0
END DESCRIPTION:
XS GIS Cut Line= 4
      2225402.08      7228745.68      2228575.09      7227864.41
      2228879.00      7226510.00      2226478.98      7224309.98
#Sta/Elev= 30
   314.1  930.06   350.6  926.16   576.9  915.00   705.3  911.33   882.0  911.08
   950.5  905.58   990.0  905.21  1047.8  898.84  1211.1  890.59  1317.6  890.51
  1348.8  893.93  1390.3  889.42  3478.1  886.12  3554.4  885.56  3772.4  885.99
  4944.1  881.31  5394.4  884.54  5425.7  883.70  5604.2  885.30  5724.5  882.74
  6821.5  880.61  6823.4  880.11  6835.0  880.61  7309.8  882.11  7398.8  887.71
  7529.3  899.96  7798.2  918.72  8023.9  938.17  8158.9  943.02  8251.1  943.10
#Mann=10,-1,0
   314.1    0.05       0  3478.1    0.12       0  3554.4    0.05       0
  3772.4    0.12       0  5394.4     0.1       0  5425.7    0.05       0
  6821.5    0.07       0  6835.0    0.05       0  7398.8    0.12       0
  8023.9    0.05       0
Bank Sta=6821.5,6835
Exp/Cntr=0.3,0.1

Chan Stop Cuts=-1