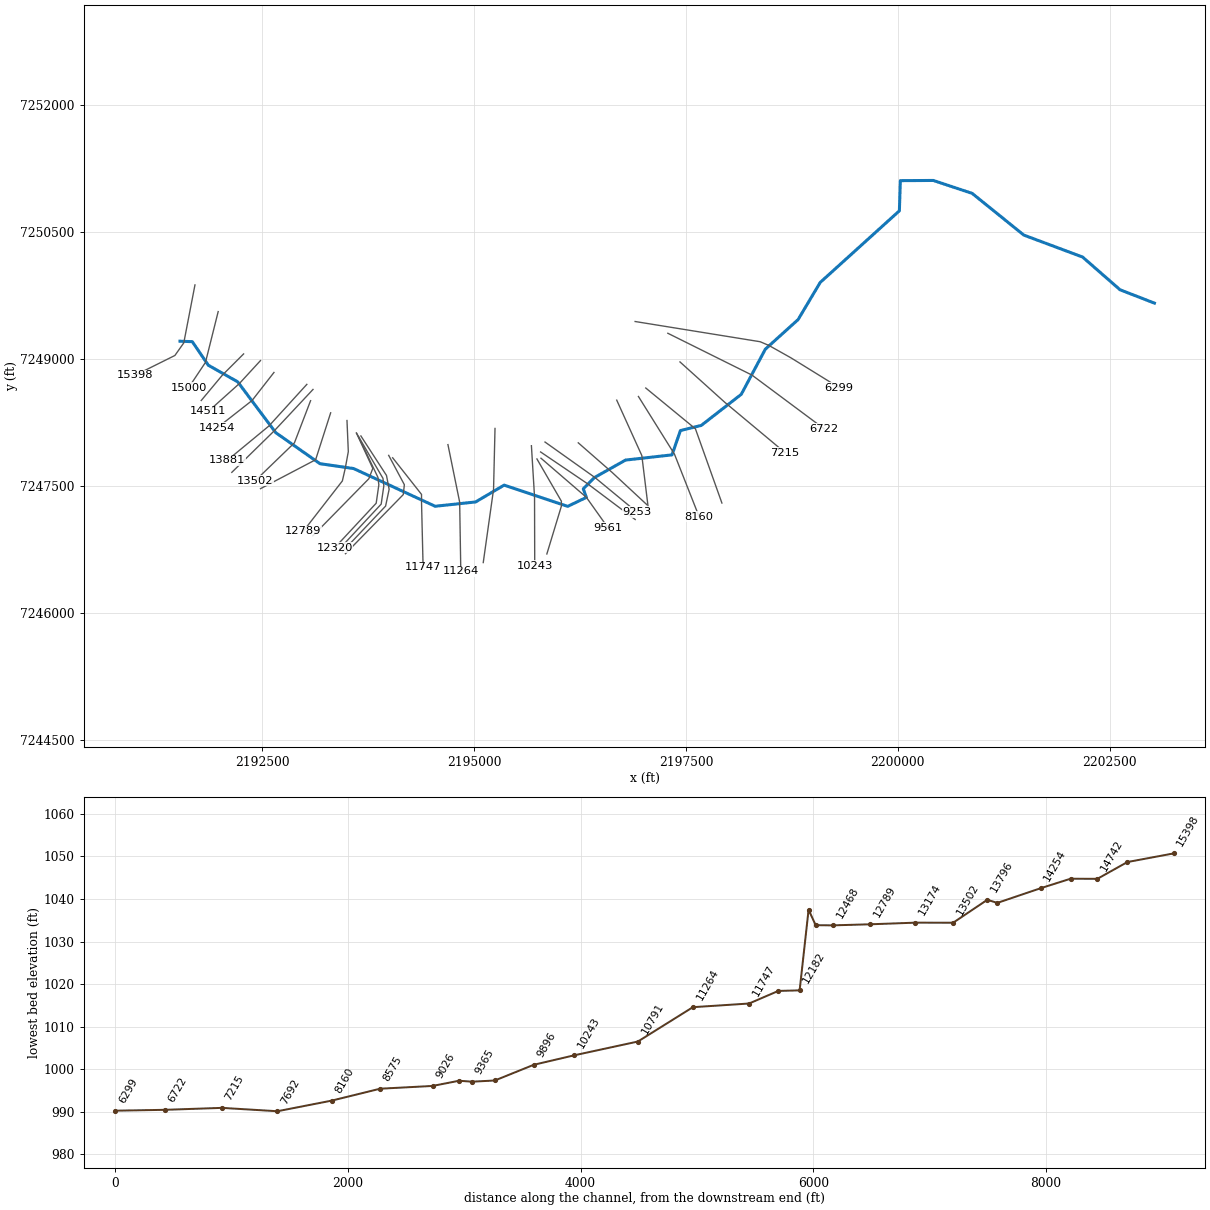
--- WELLS BRANCH.prj (project) ---

Proj Title=WELLS BRANCH Base Level Engineering
Current Plan=p01
Default Exp/Contr=0.3,0.1
English Units
Geom File=g01
Flow File=f01
Plan File=p01
Y Axis Title=Elevation
X Axis Title(PF)=Main Channel Distance
X Axis Title(XS)=Station
BEGIN DESCRIPTION:
WELLS BRANCH
END DESCRIPTION:
DSS Export Rating Curves= 0
DSS Export Rating Curve Sorted= 0
DSS Export Volume Flow Curves= 0
DXF OffsetX= 0
DXF OffsetY= 0
DXF ScaleX= 1
DXF ScaleY= 10

--- WELLS BRANCH.p01 (plan) ---

Plan Title=Multiple Run
Short Identifier=Multiple
Geom File=g01
Flow File=f01
Subcritical Flow
K Sum by GR= 0
Std Step Tol= 0.01
Critical Tol= 0.01
Num of Std Step Trials= 20
Max Error Tol= 0.3
Flow Tol Ratio= 0.001
Split Flow NTrial= 30
Split Flow Tol= 0.02
Split Flow Ratio= 0.02
Log Output Level= 0
Friction Slope Method= 1
Unsteady Friction Slope Method= 2
Unsteady Bridges Friction Slope Method= 1
Parabolic Critical Depth
Global Vel Dist=  1 , 1 , 1
Global Log Level= 0
CheckData=True
Encroach Param= -1, 0, 0, 0
BEGIN DESCRIPTION:
Multiple Run
END DESCRIPTION:

--- WELLS BRANCH.f01 (steady flow) ---

Flow Title=Multiple
Number of Profiles=7
Profile Names=10-year,25-year,50-year,1pct_min,100-year,1pct_plu,500-year
River Rch & RM= WELLS BRANCH,Reach-1,15398
     644     893    1100     673    1343    2679    2006
River Rch & RM= WELLS BRANCH,Reach-1,11264
     938    1323    1650    1019    2033    4057    3101
River Rch & RM= WELLS BRANCH,Reach-1,6089
    1119    1592    1995    1238    2470    4929    3803
Boundary for River Rch & Prof#=WELLS BRANCH,Reach-1,1
Up Type=0
Dn Type=3
Dn Slope=0.005
Boundary for River Rch & Prof#=WELLS BRANCH,Reach-1,2
Up Type=0
Dn Type=3
Dn Slope=0.005
Boundary for River Rch & Prof#=WELLS BRANCH,Reach-1,3
Up Type=0
Dn Type=3
Dn Slope=0.005
Boundary for River Rch & Prof#=WELLS BRANCH,Reach-1,4
Up Type=0
Dn Type=3
Dn Slope=0.005
Boundary for River Rch & Prof#=WELLS BRANCH,Reach-1,5
Up Type=0
Dn Type=3
Dn Slope=0.005
Boundary for River Rch & Prof#=WELLS BRANCH,Reach-1,6
Up Type=0
Dn Type=3
Dn Slope=0.005
Boundary for River Rch & Prof#=WELLS BRANCH,Reach-1,7
Up Type=0
Dn Type=3
Dn Slope=0.005

--- WELLS BRANCH.g01 (geometry) ---

Geom Title=Existing Conditions
Program Version=4.10

River Reach=WELLS BRANCH    ,Reach-1
Reach XY= 30
        2191529.        7249210.      2191673.63      7249204.88
      2191862.33      7248926.65      2192209.37      7248730.48
      2192658.85      7248129.63      2193180.47      7247763.54
      2193577.45      7247706.25      2194539.69      7247260.77
      2195017.17      7247311.64        2195354.      7247510.41
      2196104.04      7247259.51      2196324.34      7247365.26
      2196288.16      7247466.71       2196419.2      7247599.52
      2196787.47      7247806.51      2197335.52      7247867.68
      2197434.41      7248154.82       2197681.3      7248215.83
      2198152.84      7248582.85      2198436.86      7249116.17
      2198823.38      7249465.62      2199084.59      7249904.39
      2200018.82       7250750.3      2200030.22      7251106.57
       2200418.5      7251108.78       2200877.5      7250956.39
      2201487.49      7250463.53      2202181.31      7250204.17
      2202622.83      7249817.86        2203029.        7249660.

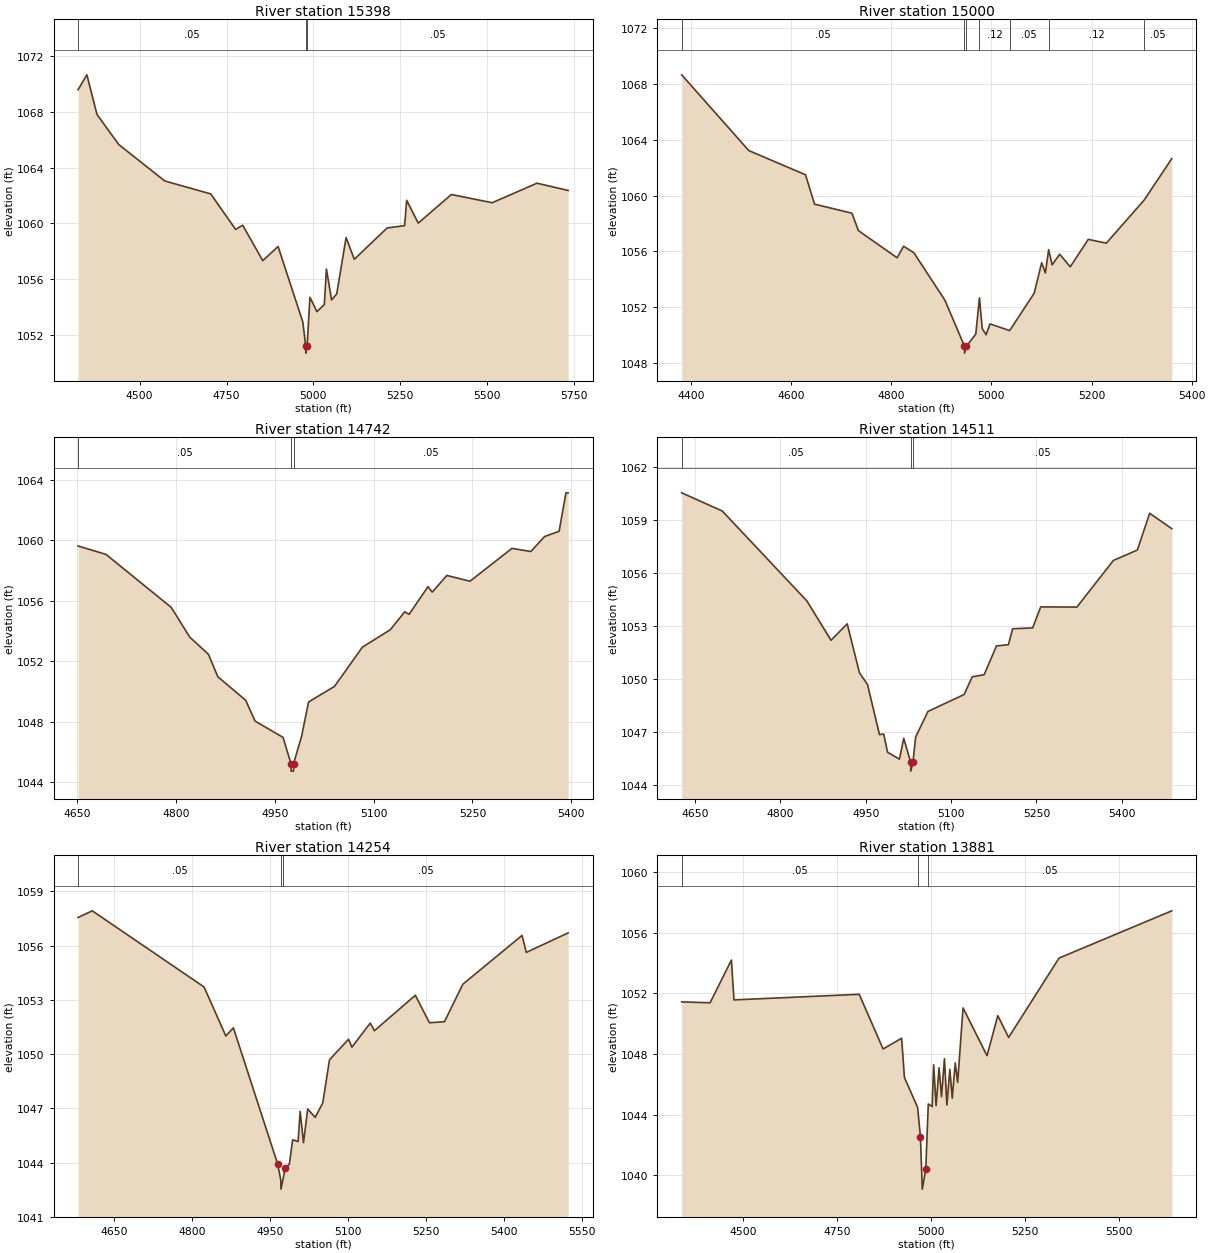
Type RM Length L Ch R = 1 ,15398   ,398,398,398
BEGIN DESCRIPTION:
WELLS BRANCH 36.5
END DESCRIPTION:
XS GIS Cut Line= 4
      2191704.99      7249874.92      2191572.92      7249190.03
      2191468.01      7249041.55      2190993.19      7248805.44
#Sta/Elev= 30
    4323 1069.57  4348.4 1070.64  4377.5  1067.8    4440 1065.65  4572.4 1063.04
  4704.8 1062.11  4776.1 1059.57  4796.5 1059.87  4854.4 1057.33  4898.3 1058.35
  4969.6 1052.93  4977.8 1051.21  4978.1 1050.71  4981.8 1051.21    4990 1054.71
    5010 1053.68  5031.3 1054.19  5037.4 1056.73  5052.2 1054.52    5067 1054.95
    5094 1058.99  5117.5 1057.43  5211.9 1059.67  5262.3 1059.84  5268.2 1061.65
  5301.5 1060.02  5396.7 1062.07  5514.2 1061.48    5643 1062.88  5732.6 1062.36
#Mann= 3 ,-1 , 0
    4323     .05       0  4977.8    .033       0  4981.8     .05       0
Bank Sta=4977.8,4981.8
XS Rating Curve= 0 ,0
Exp/Cntr=0.3,0.1

Type RM Length L Ch R = 1 ,15000   ,258,258,258
BEGIN DESCRIPTION:
WELLS BRANCH 36.0
END DESCRIPTION:
XS GIS Cut Line= 3
      2191978.99      7249559.97        2191829.        7248960.
      2191628.99      7248659.99
#Sta/Elev= 30
  4381.3 1068.67  4515.3 1063.23  4628.7 1061.49  4646.7 1059.38  4721.4 1058.73
  4734.3 1057.48  4811.6 1055.53  4824.5 1056.36  4845.1 1055.89    4907 1052.49
  4946.2 1049.18  4946.4 1048.68  4950.2 1049.18  4968.8 1050.05  4976.1 1052.65
  4981.7 1050.44  4989.4    1050  4997.2 1050.78  5036.5  1050.3  5085.4 1052.98
  5100.4 1055.17  5107.9 1054.44  5114.3 1056.11  5121.4 1055.02  5136.4 1055.79
  5157.5 1054.88  5193.5 1056.85  5229.6 1056.58  5305.3 1059.68  5360.3 1062.65
#Mann= 7 ,-1 , 0
  4381.3     .05       0  4946.2     .07       0  4950.2     .05       0
  4976.1     .12       0  5036.5     .05       0  5114.3     .12       0
  5305.3     .05       0
Bank Sta=4946.2,4950.2
XS Rating Curve= 0 ,0
Exp/Cntr=0.3,0.1

Type RM Length L Ch R = 1 ,14742   ,231,231,231
BEGIN DESCRIPTION:
WELLS BRANCH 35.0
END DESCRIPTION:
XS GIS Cut Line= 3
      2192279.02      7249060.02        2192029.        7248810.
        2191779.        7248510.
#Sta/Elev= 30
  4651.2 1059.62  4693.7 1059.06  4792.7 1055.56  4820.9 1053.59  4849.2 1052.46
  4863.4 1050.98  4905.8 1049.42  4919.9 1048.05  4962.4 1046.97  4974.5 1045.24
  4974.8 1044.74  4978.3 1044.74  4978.5 1045.24  4990.6 1047.04  5001.2 1049.31
  5040.6 1050.34  5082.9 1052.93  5125.2 1054.08  5147.3 1055.27  5153.8  1055.1
  5182.5 1056.93    5189 1056.57  5211.1 1057.67  5246.3 1057.29    5310 1059.46
  5338.7 1059.25  5359.5 1060.24  5381.6 1060.59    5392 1063.13  5395.3 1063.13
#Mann= 3 ,-1 , 0
  4651.2     .05       0  4974.5    .033       0  4978.5     .05       0
Bank Sta=4974.5,4978.5
XS Rating Curve= 0 ,0
Exp/Cntr=0.3,0.1

Type RM Length L Ch R = 1 ,14511   ,257,257,257
BEGIN DESCRIPTION:
WELLS BRANCH 34.0
END DESCRIPTION:
XS GIS Cut Line= 3
      2192478.41      7248981.64        2192229.        7248710.
      2191862.59      7248381.31
#Sta/Elev= 30
  4626.7 1060.52    4698 1059.49  4846.6  1054.4  4889.1 1052.17  4917.5  1053.1
    4939 1050.33  4953.2 1049.66  4974.2 1046.83  4981.6 1046.86  4988.4 1045.83
  5009.3 1045.44  5016.8 1046.62    5029 1045.26  5029.2 1044.76    5033 1045.26
  5037.7 1046.69  5059.4 1048.14  5122.9  1049.1  5137.1  1050.1  5158.1 1050.22
  5179.7 1051.85  5200.7 1051.92  5208.2 1052.82  5243.3 1052.87  5257.5 1054.06
    5321 1054.05  5385.1 1056.69  5427.2 1057.28  5448.9 1059.36  5487.7 1058.49
#Mann= 3 ,-1 , 0
  4626.7     .05       0    5029    .033       0    5033     .05       0
Bank Sta=5029,5033
XS Rating Curve= 0 ,0
Exp/Cntr=0.3,0.1

Type RM Length L Ch R = 1 ,14254   ,373,373,373
BEGIN DESCRIPTION:
WELLS BRANCH 33.0
END DESCRIPTION:
XS GIS Cut Line= 3
      2192637.31      7248841.07        2192379.        7248510.
      2191968.01      7248187.39
#Sta/Elev= 30
  4580.3 1057.55  4607.6 1057.92  4822.6 1053.71  4864.5    1051    4879 1051.45
    4964 1043.93  4970.2 1043.03  4970.4 1042.53  4974.2 1043.03  4978.5 1043.71
  4986.6 1043.91    4993 1045.26  5003.4 1045.16  5007.4 1046.83  5013.8  1045.1
  5021.9 1046.96  5036.3  1046.5  5050.8 1047.29  5063.8 1049.68  5100.5 1050.82
  5106.9 1050.38  5142.1 1051.71  5150.2 1051.29  5228.9 1053.25    5256 1051.73
  5284.9 1051.79  5320.2 1053.86  5434.1 1056.56  5442.2 1055.62  5522.7  1056.7
#Mann= 3 ,-1 , 0
  4580.3     .05       0  4970.2    .033       0  4974.2     .05       0
Bank Sta=4964,4978.5
XS Rating Curve= 0 ,0
Exp/Cntr=0.3,0.1

Type RM Length L Ch R = 1 ,13881   ,85,85,85
BEGIN DESCRIPTION:
WELLS BRANCH 32.0
END DESCRIPTION:
XS GIS Cut Line= 3
      2193025.29       7248700.4        2192579.        7248210.
      2192085.23        7247802.
#Sta/Elev= 30
  4336.9 1051.44  4412.5 1051.38  4469.2  1054.2    4476 1051.57  4809.1 1051.94
  4872.6 1048.33  4921.9 1049.04  4929.4 1046.45  4964.5 1044.47  4971.9 1042.55
  4976.9 1039.08  4986.1 1040.38  4992.9  1044.7  5003.2 1044.53  5007.1 1047.29
  5013.6 1044.59  5021.5 1047.09    5028 1045.18  5035.8 1047.69  5042.3 1044.63
  5050.2 1046.99  5056.6 1045.08  5064.5 1047.41    5071 1046.13  5085.3 1051.04
  5149.1 1047.89  5177.8 1050.53  5206.5 1049.09  5340.6 1054.33  5640.5 1057.45
#Mann= 3 ,-1 , 0
  4336.9     .05       0  4964.5    .033       0  4992.9     .05       0
Bank Sta=4971.9,4986.1
XS Rating Curve= 0 ,0
Exp/Cntr=0.3,0.1

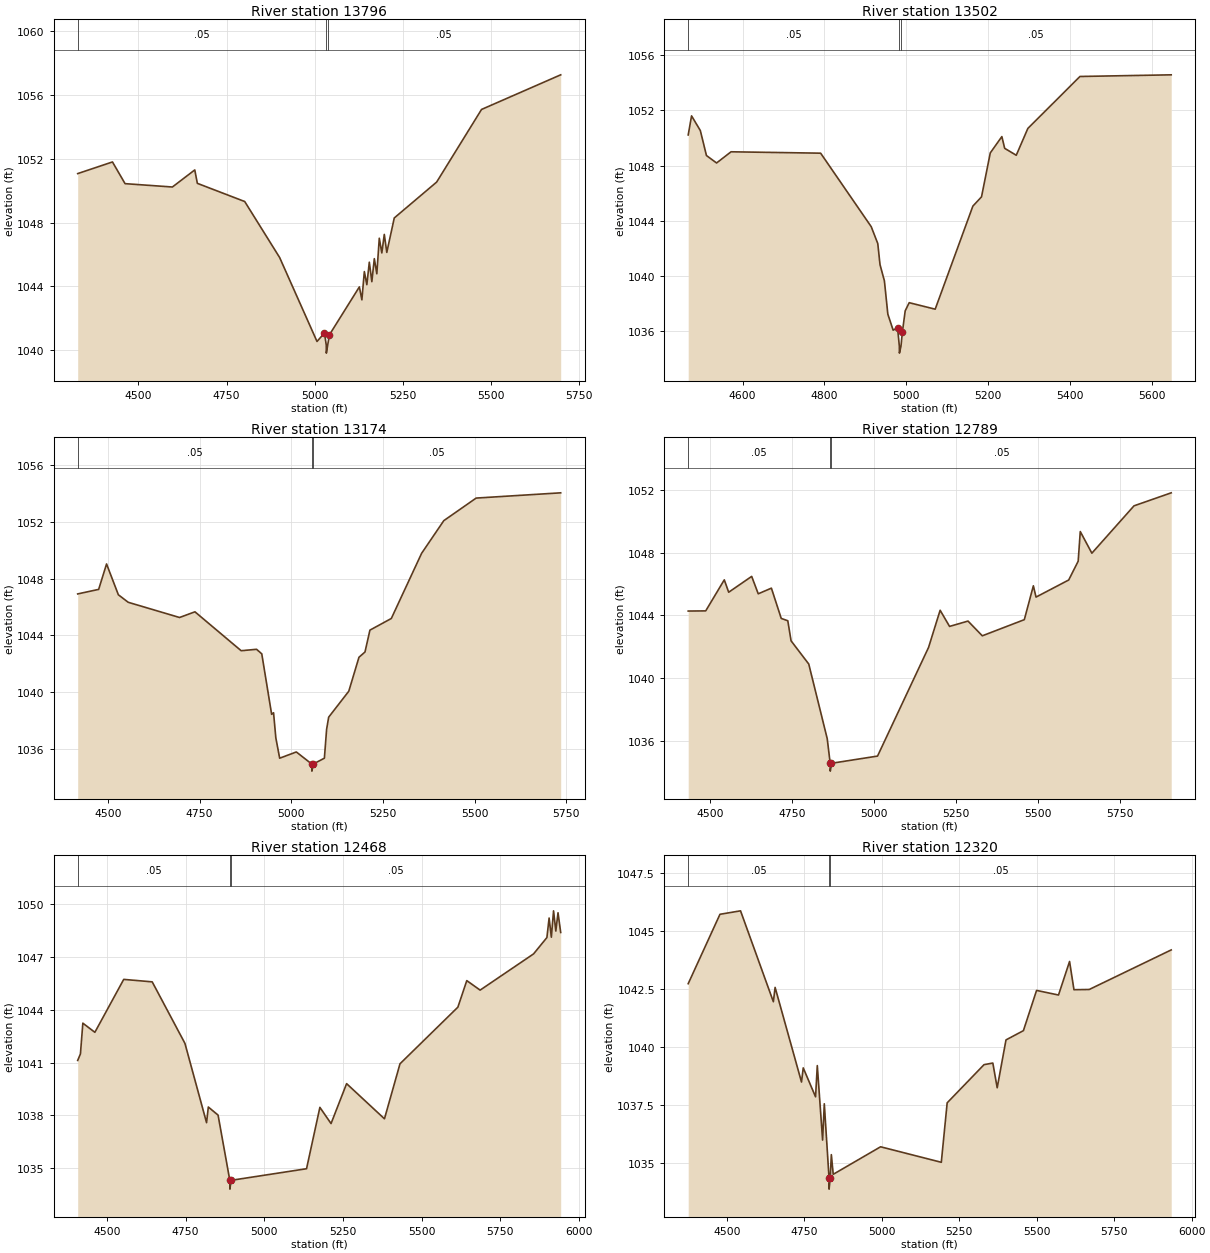
Type RM Length L Ch R = 1 ,13796   ,294,294,294
BEGIN DESCRIPTION:
WELLS BRANCH 31.5
END DESCRIPTION:
XS GIS Cut Line= 3
      2193098.22      7248640.51      2192642.49      7248153.53
       2192139.9      7247661.36
#Sta/Elev= 30
  4327.7 1051.07  4426.4  1051.8  4462.1 1050.44  4596.4 1050.23  4659.9  1051.3
  4667.2 1050.46  4801.6 1049.32  4900.7 1045.81  5006.7 1040.55  5027.8 1041.08
    5033 1040.32  5033.2 1039.82    5037 1040.32    5042 1040.97  5126.9 1043.97
    5134 1043.16    5141 1044.93  5148.1 1044.11  5155.1 1045.52  5162.3  1044.3
  5169.3 1045.74  5176.4 1044.79  5183.4 1047.02  5190.6  1046.1  5197.6 1047.26
  5204.7 1046.13  5225.9 1048.29  5346.2 1050.54  5473.5 1055.09  5698.1 1057.26
#Mann= 3 ,-1 , 0
  4327.7     .05       0    5033    .033       0    5037     .05       0
Bank Sta=5027.8,5042
XS Rating Curve= 0 ,0
Exp/Cntr=0.3,0.1

Type RM Length L Ch R = 1 ,13502   ,328,328,328
BEGIN DESCRIPTION:
WELLS BRANCH 31.0
END DESCRIPTION:
XS GIS Cut Line= 3
      2193069.56      7248507.67        2192879.        7248010.
      2192413.64      7247560.09
#Sta/Elev= 30
  4467.1 1050.22  4475.3  1051.6  4496.7 1050.54  4511.7 1048.73  4536.4 1048.19
  4571.8    1049  4790.7  1048.9  4914.3 1043.58  4930.3 1042.36  4935.8 1040.83
  4946.5 1039.66  4954.9 1037.25  4967.9 1036.09  4978.6 1036.27    4983 1034.93
  4983.2 1034.43    4987 1034.93  4990.3 1035.93  4997.3 1037.49  5007.1 1038.08
  5070.6 1037.61  5162.7 1045.07  5183.8 1045.74  5205.2 1048.92  5233.5  1050.1
  5240.4 1049.25  5268.7 1048.75    5297 1050.69  5424.3 1054.45  5647.3 1054.57
#Mann= 3 ,-1 , 0
  4467.1     .05       0    4983    .033       0    4987     .05       0
Bank Sta=4978.6,4990.3
XS Rating Curve= 0 ,0
Exp/Cntr=0.3,0.1

Type RM Length L Ch R = 1 ,13174   ,385,385,385
BEGIN DESCRIPTION:
WELLS BRANCH 30.0
END DESCRIPTION:
XS GIS Cut Line= 3
      2193306.56      7248364.51        2193129.        7247810.
      2192478.46      7247468.65
#Sta/Elev= 30
  4417.5 1046.92  4474.7 1047.24  4496.2 1049.03  4528.4 1046.86  4555.3 1046.33
  4695.2 1045.26  4737.2 1045.66  4863.2 1042.92  4905.2 1043.02  4919.4  1042.7
  4946.3 1038.44  4951.5 1038.55  4957.7 1036.79  4968.2 1035.35  5013.6 1035.79
  5055.7 1034.94    5056 1034.44  5059.7 1034.94  5090.1 1035.35  5096.2 1037.39
  5101.8 1038.24  5156.7 1040.07  5184.4 1042.46  5200.8 1042.83  5214.3 1044.37
  5272.6 1045.19  5355.2 1049.78  5415.7 1052.08  5503.9 1053.67  5734.4 1054.04
#Mann= 3 ,-1 , 0
  4417.5     .05       0  5055.7    .033       0  5059.7     .05       0
Bank Sta=5055.7,5059.7
XS Rating Curve= 0 ,0
Exp/Cntr=0.3,0.1

Type RM Length L Ch R = 1 ,12789   ,321,321,321
BEGIN DESCRIPTION:
WELLS BRANCH 29.0
END DESCRIPTION:
XS GIS Cut Line= 5
      2193499.26      7248273.33      2193514.88      7247906.13
        2193479.        7247710.      2193444.57      7247559.78
      2192983.81      7246966.26
#Sta/Elev= 30
  4433.1 1044.27  4486.5 1044.28  4543.1 1046.26  4556.5 1045.47  4626.6 1046.48
  4646.6 1045.37  4686.7 1045.73  4716.7  1043.8  4736.7 1043.65  4746.7 1042.37
  4800.6 1040.89  4856.9 1036.13  4865.9 1034.56  4866.1 1034.06  4869.9 1034.56
  5010.3 1035.02  5165.8 1041.95  5201.1 1044.32  5229.8 1043.29  5286.1 1043.63
  5329.6 1042.69  5457.7 1043.72  5485.3 1045.88  5493.4 1045.16    5593 1046.25
  5621.9 1047.45  5628.3 1049.34  5663.6 1047.96  5792.1 1050.98  5905.5 1051.81
#Mann= 3 ,-1 , 0
  4433.1     .05       0  4865.9    .033       0  4869.9     .05       0
Bank Sta=4865.9,4869.9
XS Rating Curve= 0 ,0
Exp/Cntr=0.3,0.1

Type RM Length L Ch R = 1 ,12468   ,148,148,148
BEGIN DESCRIPTION:
WELLS BRANCH 28.0
END DESCRIPTION:
XS GIS Cut Line= 4
      2193611.23      7248124.89      2193803.94      7247708.22
      2193757.07      7247585.82      2193095.64      7246911.37
#Sta/Elev= 30
  4407.1 1041.13  4415.8  1041.5  4423.5 1043.25  4461.7 1042.73  4553.4 1045.74
  4643.9  1045.6  4747.9  1042.1  4816.6 1037.59  4822.2 1038.48  4853.2 1038.02
  4890.5 1034.31  4890.8 1033.81  4894.5 1034.31  5134.3 1034.97  5176.7 1038.46
  5212.2 1037.54  5261.6 1039.81  5381.9 1037.81  5431.3 1040.94  5615.2 1044.16
  5643.5 1045.67  5685.9 1045.13  5855.7 1047.19  5898.1 1048.12  5905.1 1049.23
  5912.2 1048.14  5919.2 1049.64  5926.4 1048.49  5933.4 1049.53  5941.9 1048.41
#Mann= 3 ,-1 , 0
  4407.1     .05       0  4890.5    .033       0  4894.5     .05       0
Bank Sta=4890.5,4894.5
XS Rating Curve= 0 ,0
Exp/Cntr=0.3,0.1

Type RM Length L Ch R = 1 ,12320   ,61,61,61
BEGIN DESCRIPTION:
WELLS BRANCH 27.7
END DESCRIPTION:
XS GIS Cut Line= 5
      2193635.34      7248082.49      2193864.71      7247601.45
      2193875.13      7247512.91      2193843.88      7247296.76
      2193354.28      7246770.71
#Sta/Elev= 30
  4374.9 1042.73  4477.4 1045.73  4543.8 1045.88  4649.8 1041.95  4655.4 1042.57
  4740.6 1038.48  4746.2 1039.09    4786 1037.84  4791.6 1039.19  4808.7 1035.97
  4814.2 1037.54  4829.4 1034.35  4829.7 1033.85  4833.4 1034.35  4836.9 1035.34
    4843 1034.49  4995.9 1035.68  5191.9 1035.01  5210.8 1037.58  5329.8 1039.23
  5358.2  1039.3  5372.3 1038.23  5400.7  1040.3  5456.9  1040.7  5499.4 1042.44
  5570.2 1042.24  5605.9 1043.69  5620.1 1042.47  5669.4 1042.48    5934 1044.19
#Mann= 3 ,-1 , 0
  4374.9     .05       0  4829.4    .033       0  4833.4     .05       0
Bank Sta=4829.4,4833.4
XS Rating Curve= 0 ,0
Exp/Cntr=0.3,0.1

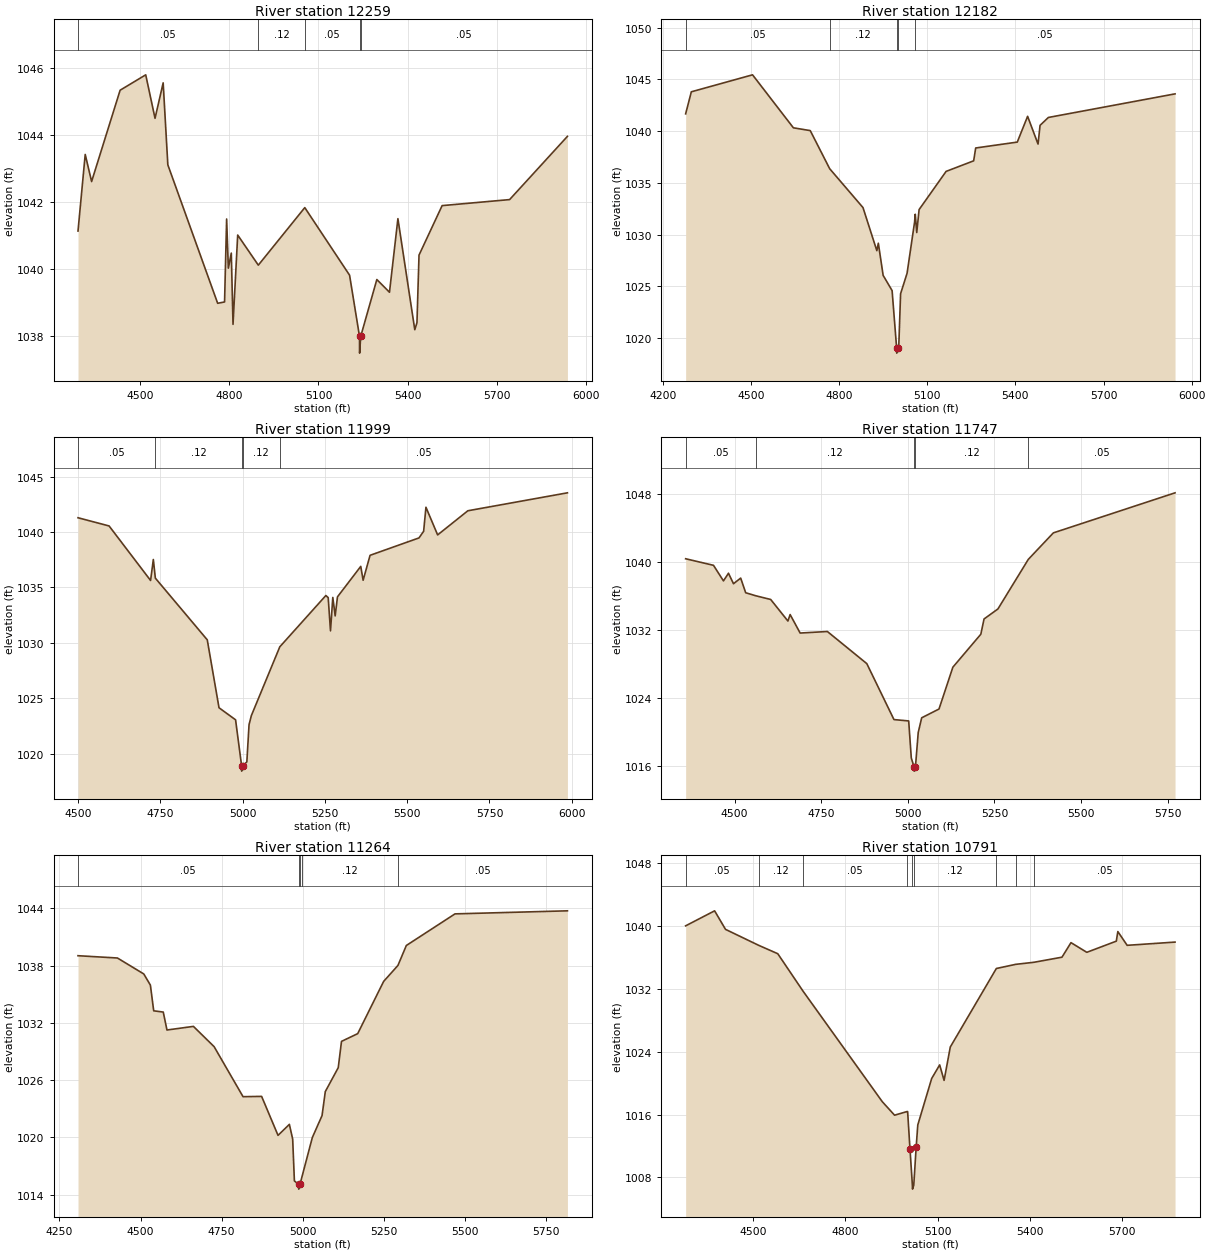
Type RM Length L Ch R = 1 ,12259   ,77,77,77
BEGIN DESCRIPTION:
WELLS BRANCH 27.6
END DESCRIPTION:
XS GIS Cut Line= 5
      2193611.21      7248124.93      2193923.74      7247591.03
      2193934.15      7247502.49       2193902.9      7247286.34
      2193413.66      7246760.67
#Sta/Elev= 30
  4292.1 1041.13  4316.3 1043.42  4337.8 1042.61  4433.6 1045.34  4519.6  1045.8
  4550.9  1044.5  4578.2 1045.56  4593.9 1043.11  4761.3 1038.97  4784.5 1039.01
  4791.4 1041.49  4797.2 1040.02  4807.1 1040.47  4812.9 1038.34  4828.6 1041.01
  4897.9 1040.11    5054 1041.83  5204.5 1039.81  5237.9 1037.98  5238.2 1037.48
  5241.9 1037.98  5296.1 1039.68  5338.6  1039.3  5366.9  1041.5  5423.6 1038.18
  5430.9 1038.39  5437.8 1040.41  5515.5 1041.89  5742.2 1042.07  5936.4 1043.96
#Mann= 5 ,-1 , 0
  4292.1     .05       0  4897.9     .12       0    5054     .05       0
  5237.9     .07       0  5241.9     .05       0
Bank Sta=5237.9,5241.9
XS Rating Curve= 0 ,0
Exp/Cntr=0.3,0.1

Type RM Length L Ch R = 1 ,12182   ,183,183,183
BEGIN DESCRIPTION:
WELLS BRANCH 27.5
END DESCRIPTION:
XS GIS Cut Line= 5
      2193663.29      7248091.07       2193965.4      7247624.88
      2193996.65      7247460.82      2193954.99      7247262.91
      2193445.09      7246724.39
#Sta/Elev= 30
  4277.1 1041.66  4296.5 1043.79  4504.9 1045.43    4644 1040.31  4701.4 1040.04
  4767.5 1036.36    4881  1032.6  4928.1 1028.44  4933.2 1029.16  4949.6 1026.05
  4980.1 1024.58  4995.5 1019.04  4995.8 1018.54  4999.5 1019.04  5002.6 1019.04
    5009 1024.28  5031.1 1026.26  5056.5 1031.18  5058.9 1031.96    5064 1030.19
    5072 1032.41    5164  1036.1  5257.8 1037.12  5264.7 1038.36  5406.3 1038.93
  5441.5 1041.42    5477 1038.74  5483.9 1040.55  5512.2 1041.31  5943.5 1043.59
#Mann= 5 ,-1 , 0
  4277.1     .05       0  4767.5     .12       0  4995.5     .07       0
  4999.5     .12       0  5056.5     .05       0
Bank Sta=4995.5,4999.5
XS Rating Curve= 0 ,0
Exp/Cntr=0.3,0.1

Type RM Length L Ch R = 1 ,11999   ,252,252,252
BEGIN DESCRIPTION:
WELLS BRANCH 27.0
END DESCRIPTION:
XS GIS Cut Line= 4
      2193991.46      7247861.84      2194176.34      7247515.51
      2194163.32      7247398.32      2193481.04      7246700.42
#Sta/Elev= 30
  4500.3 1041.28  4594.7 1040.54  4720.7 1035.62  4729.1 1037.51  4735.2 1035.83
  4892.9 1030.26  4928.6 1024.13  4978.9 1023.04  4997.1 1018.91  4997.3 1018.41
  5001.1 1018.91  5013.1 1019.24  5019.8  1022.6  5026.8 1023.42  5113.2 1029.63
  5253.1 1034.26  5260.2 1034.07  5267.2 1031.07  5274.2 1034.09  5281.4 1032.42
  5288.4 1034.14  5359.1 1036.89  5366.3 1035.64  5387.4 1037.89    5536 1039.46
  5550.1 1040.06  5557.1 1042.23  5592.6 1039.73  5684.4 1041.91  5986.8 1043.53
#Mann= 5 ,-1 , 0
  4500.3     .05       0  4735.2     .12       0  4997.1     .07       0
  5001.1     .12       0  5113.2     .05       0
Bank Sta=4997.1,5001.1
XS Rating Curve= 0 ,0
Exp/Cntr=0.3,0.1

Type RM Length L Ch R = 1 ,11747   ,483,483,483
BEGIN DESCRIPTION:
WELLS BRANCH 26.0
END DESCRIPTION:
XS GIS Cut Line= 4
      2194038.35      7247833.19        2194379.      7247400.93
        2194379.        7247310.       2194397.7      7246538.91
#Sta/Elev= 30
  4358.7 1040.38  4439.1 1039.61  4467.9 1037.78  4482.3 1038.68  4496.8 1037.45
  4517.6 1038.11    4532 1036.39  4561.6 1036.03  4604.2  1035.6  4653.9 1033.07
  4660.3 1033.83  4689.2 1031.66  4767.8 1031.84  4881.6 1028.07    4960  1021.5
  5002.5 1021.34    5010 1016.99    5018 1015.95  5018.2 1015.45    5022 1015.95
    5030 1019.98    5040 1021.71    5090 1022.74    5130 1027.65  5210.7 1031.52
    5220 1033.31  5260.1 1034.49  5347.8 1040.31  5420.1 1043.42  5771.3 1048.12
#Mann= 5 ,-1 , 0
  4358.7     .05       0  4561.6     .12       0    5018     .07       0
    5022     .12       0  5347.8     .05       0
Bank Sta=5018,5022
XS Rating Curve= 0 ,0
Exp/Cntr=0.3,0.1

Type RM Length L Ch R = 1 ,11264   ,473,473,473
BEGIN DESCRIPTION:
WELLS BRANCH 25.0
END DESCRIPTION:
XS GIS Cut Line= 3
       2194690.7      7247988.84        2194829.        7247310.
      2194842.57       7246493.2
#Sta/Elev= 30
  4307.2 1039.03  4428.8 1038.79  4510.1 1037.12  4530.5 1035.95  4540.7 1033.26
  4570.2 1033.13  4581.6 1031.25  4663.2 1031.63    4727 1029.51  4816.3 1024.27
  4873.6  1024.3  4924.2 1020.22  4959.2 1021.37  4969.4 1019.83  4974.7 1015.45
  4987.6 1015.09    4988 1014.59    4992 1015.09  4997.6 1015.82    5030 1019.99
    5060 1022.29    5070  1024.8    5110 1027.31    5120 1030.06    5170 1030.87
    5250 1036.34  5294.1 1038.01    5320  1040.1  5470.1 1043.41  5816.9 1043.73
#Mann= 5 ,-1 , 0
  4307.2     .05       0  4987.6     .07       0    4992     .05       0
  4997.6     .12       0  5294.1     .05       0
Bank Sta=4987.6,4992
XS Rating Curve= 0 ,0
Exp/Cntr=0.3,0.1

Type RM Length L Ch R = 1 ,10791   ,548,548,548
BEGIN DESCRIPTION:
WELLS BRANCH 24.0
END DESCRIPTION:
XS GIS Cut Line= 3
      2195246.25       7248179.8        2195229.        7247460.
      2195107.36      7246595.62
#Sta/Elev= 30
    4280 1040.03  4374.3 1041.94  4409.8 1039.58  4517.7 1037.55  4579.9 1036.48
  4661.7 1031.74    4920 1017.65    4960 1015.93  5000.4 1016.39  5002.5 1016.39
  5010.1 1011.68    5018 1007.02  5018.4 1006.52  5022.5 1007.02  5030.3 1011.87
  5035.6 1014.69  5080.8  1020.6  5106.8 1022.33  5121.2 1020.36  5141.4 1024.61
  5291.3  1034.6  5354.5 1035.13  5413.4 1035.39  5504.9 1036.04  5534.2 1037.89
  5585.7 1036.66  5681.7 1038.08  5686.7  1039.3    5717 1037.55  5872.9 1037.96
#Mann= 9 ,-1 , 0
    4280     .05       0  4517.7     .12       0  4661.7     .05       0
  5000.4     .12       0    5018    .033       0  5022.5     .12       0
  5291.3     .05       0  5354.5     .12       0  5413.4     .05       0
Bank Sta=5010.1,5030.3
XS Rating Curve= 0 ,0
Exp/Cntr=0.3,0.1

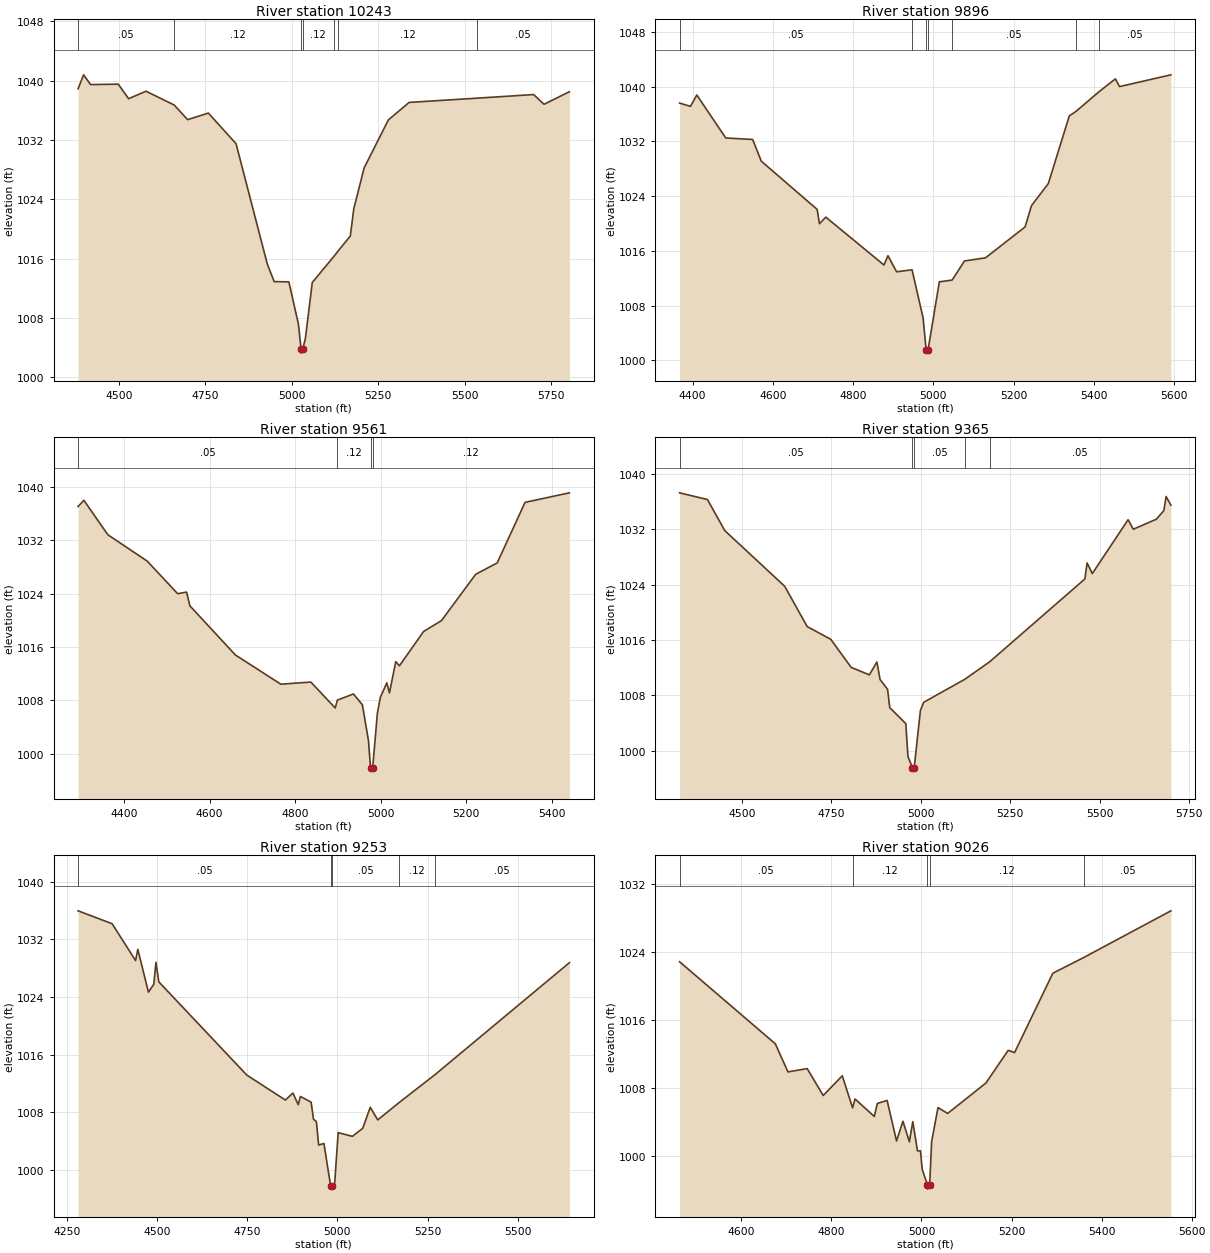
Type RM Length L Ch R = 1 ,10243   ,347,347,347
BEGIN DESCRIPTION:
WELLS BRANCH 23.0
END DESCRIPTION:
XS GIS Cut Line= 3
      2195675.93      7247975.87      2195712.83      7247370.37
        2195715.       7246556.6
#Sta/Elev= 30
  4382.6 1038.93  4398.5  1040.8  4418.5 1039.49  4498.7 1039.54  4528.7 1037.58
  4578.8 1038.59  4660.4 1036.73  4699.1 1034.76  4759.2 1035.64  4839.2 1031.52
  4929.5  1015.3  4949.5 1012.92  4991.9 1012.89  5019.6 1007.19  5027.3 1003.78
  5027.8 1003.28  5031.8 1003.78  5039.6 1005.22  5059.6  1012.8  5122.6 1016.35
  5134.8 1017.08  5169.6 1019.07  5179.6 1022.73  5209.6 1028.26  5279.6 1034.72
  5339.6 1037.08  5535.4 1037.65  5699.6 1038.14  5729.6 1036.83    5803 1038.52
#Mann= 7 ,-1 , 0
  4382.6     .05       0  4660.4     .12       0  5027.3     .07       0
  5031.8     .12       0  5122.6     .05       0  5134.8     .12       0
  5535.4     .05       0
Bank Sta=5027.3,5031.8
XS Rating Curve= 0 ,0
Exp/Cntr=0.3,0.1

Type RM Length L Ch R = 1 ,9896    ,335,335,335
BEGIN DESCRIPTION:
WELLS BRANCH 22.0
END DESCRIPTION:
XS GIS Cut Line= 4
      2195741.03       7247819.6      2196029.67      7247320.46
        2196029.        7247260.      2195858.22      7246697.61
#Sta/Elev= 30
  4367.4 1037.61  4394.6 1037.13  4410.3 1038.79  4482.5 1032.51  4549.5 1032.29
  4571.1 1029.12  4710.3 1022.07  4716.1 1019.97  4731.9 1020.94  4876.9 1013.94
  4886.8  1015.3  4908.4 1012.95  4946.9 1013.24  4974.4 1006.22    4982 1001.56
  4982.6 1001.06  4986.9 1001.56  5014.9 1011.48  5046.8 1011.74  5077.6 1014.53
    5130 1014.99  5228.6  1019.5  5244.8 1022.63  5286.6 1025.84  5338.9 1035.73
  5355.7  1036.4  5412.8 1039.26  5453.8 1041.15  5464.1 1040.02  5592.2 1041.74
#Mann= 7 ,-1 , 0
  4367.4     .05       0  4946.9     .12       0    4982     .07       0
  4986.9     .12       0  5046.8     .05       0  5355.7     .12       0
  5412.8     .05       0
Bank Sta=4982,4986.9
XS Rating Curve= 0 ,0
Exp/Cntr=0.3,0.1

Type RM Length L Ch R = 1 ,9561    ,196,196,196
BEGIN DESCRIPTION:
WELLS BRANCH 21.0
END DESCRIPTION:
XS GIS Cut Line= 3
      2195788.77      7247828.28      2196324.81      7247366.03
      2196580.88      7247005.79
#Sta/Elev= 30
  4292.1 1037.08  4305.6 1038.02  4361.7 1032.85  4453.9 1028.89  4525.1    1024
    4546 1024.24  4553.7 1022.18  4660.1 1014.81  4766.5 1010.42  4836.7 1010.74
  4893.8 1006.85  4898.9 1008.03  4936.5 1008.95  4957.4 1007.33  4971.7 1001.93
  4976.5  997.87  4977.2  997.37  4981.5  997.87  4992.5 1006.07  4999.4 1008.44
  5014.6 1010.62  5020.8 1009.11  5035.5  1013.8  5044.1 1013.18  5100.7 1018.33
  5142.5 1019.96  5222.5 1026.91  5272.9 1028.62  5338.1 1037.71  5441.9 1039.14
#Mann= 4 ,-1 , 0
  4292.1     .05       0  4898.9     .12       0  4976.5     .07       0
  4981.5     .12       0
Bank Sta=4976.5,4981.5
XS Rating Curve= 0 ,0
Exp/Cntr=0.3,0.1

Type RM Length L Ch R = 1 ,9365    ,112,112,112
BEGIN DESCRIPTION:
WELLS BRANCH 20.5
END DESCRIPTION:
XS GIS Cut Line= 3
      2195784.43      7247902.06      2196342.14      7247524.19
      2196901.06       7247104.2
#Sta/Elev= 30
  4325.8 1037.22  4403.7 1036.25  4452.1 1031.77  4619.4 1023.75  4682.4 1017.93
  4748.2  1016.1  4805.2 1012.05  4856.1 1010.97  4877.1 1012.83    4886  1010.3
    4907 1008.88    4913 1006.25  4957.9 1003.94  4963.9  999.21  4976.4  997.59
    4977  997.09  4981.4  997.59  4998.7 1005.85    5008 1007.02  5122.7 1010.33
  5192.1 1012.85  5458.2  1024.8  5464.4 1027.11    5479 1025.58    5579 1033.34
  5593.5 1031.97  5658.1 1033.42  5678.9 1034.66  5685.2 1036.69  5698.6 1035.44
#Mann= 5 ,-1 , 0
  4325.8     .05       0  4976.4    .033       0  4981.4     .05       0
  5122.7     .12       0  5192.1     .05       0
Bank Sta=4976.4,4981.4
XS Rating Curve= 0 ,0
Exp/Cntr=0.3,0.1

Type RM Length L Ch R = 1 ,9253    ,227,227,227
BEGIN DESCRIPTION:
WELLS BRANCH 20.4
END DESCRIPTION:
XS GIS Cut Line= 3
      2195836.51      7248019.25      2196425.47      7247600.58
      2196919.45       7247192.4
#Sta/Elev= 30
  4280.4 1035.96  4374.8 1034.17  4439.9 1029.05  4446.1 1030.61  4475.6 1024.67
  4490.4 1025.76  4496.5  1028.8  4504.3  1026.1  4748.6 1013.15  4855.6 1009.68
  4876.5 1010.65  4891.3 1009.04  4897.4 1010.18    4927 1009.39  4933.7 1007.01
  4941.7 1006.68  4947.9 1003.43  4962.6 1003.65    4981  997.81  4981.6  997.31
    4986  997.81  4992.2  997.97  5002.1 1005.16  5041.6 1004.64  5070.3 1005.76
  5091.1 1008.68  5111.9 1006.92  5171.7 1009.35  5269.9 1013.17  5643.8 1028.76
#Mann= 5 ,-1 , 0
  4280.4     .05       0    4981    .033       0    4986     .05       0
  5171.7     .12       0  5269.9     .05       0
Bank Sta=4981,4986
XS Rating Curve= 0 ,0
Exp/Cntr=0.3,0.1

Type RM Length L Ch R = 1 ,9026    ,451,451,451
BEGIN DESCRIPTION:
WELLS BRANCH 20.0
END DESCRIPTION:
XS GIS Cut Line= 3
      2196228.99      7248010.01        2196629.        7247660.
      2197038.78      7247279.23
#Sta/Elev= 30
    4463 1022.88  4675.6 1013.21  4703.6  1009.9  4746.3 1010.29  4781.9 1007.12
  4824.2 1009.44  4847.1 1005.67  4852.6 1006.71  4895.3 1004.65    4902 1006.18
  4923.8 1006.54  4944.7 1001.76  4958.9 1004.09  4973.2 1001.67  4980.8 1004.04
  4991.2  1000.6  4997.9  1000.6  5001.6  998.45  5013.3  996.59  5013.9  996.09
  5018.3  996.59  5022.6 1001.69  5036.8  1005.7  5058.3 1005.01  5143.3  1008.6
  5192.6 1012.44  5206.8 1012.18  5291.8 1021.53  5361.1  1023.4  5553.9 1028.88
#Mann= 5 ,-1 , 0
    4463     .05       0  4847.1     .12       0  5013.3     .07       0
  5018.3     .12       0  5361.1     .05       0
Bank Sta=5013.3,5018.3
XS Rating Curve= 0 ,0
Exp/Cntr=0.3,0.1

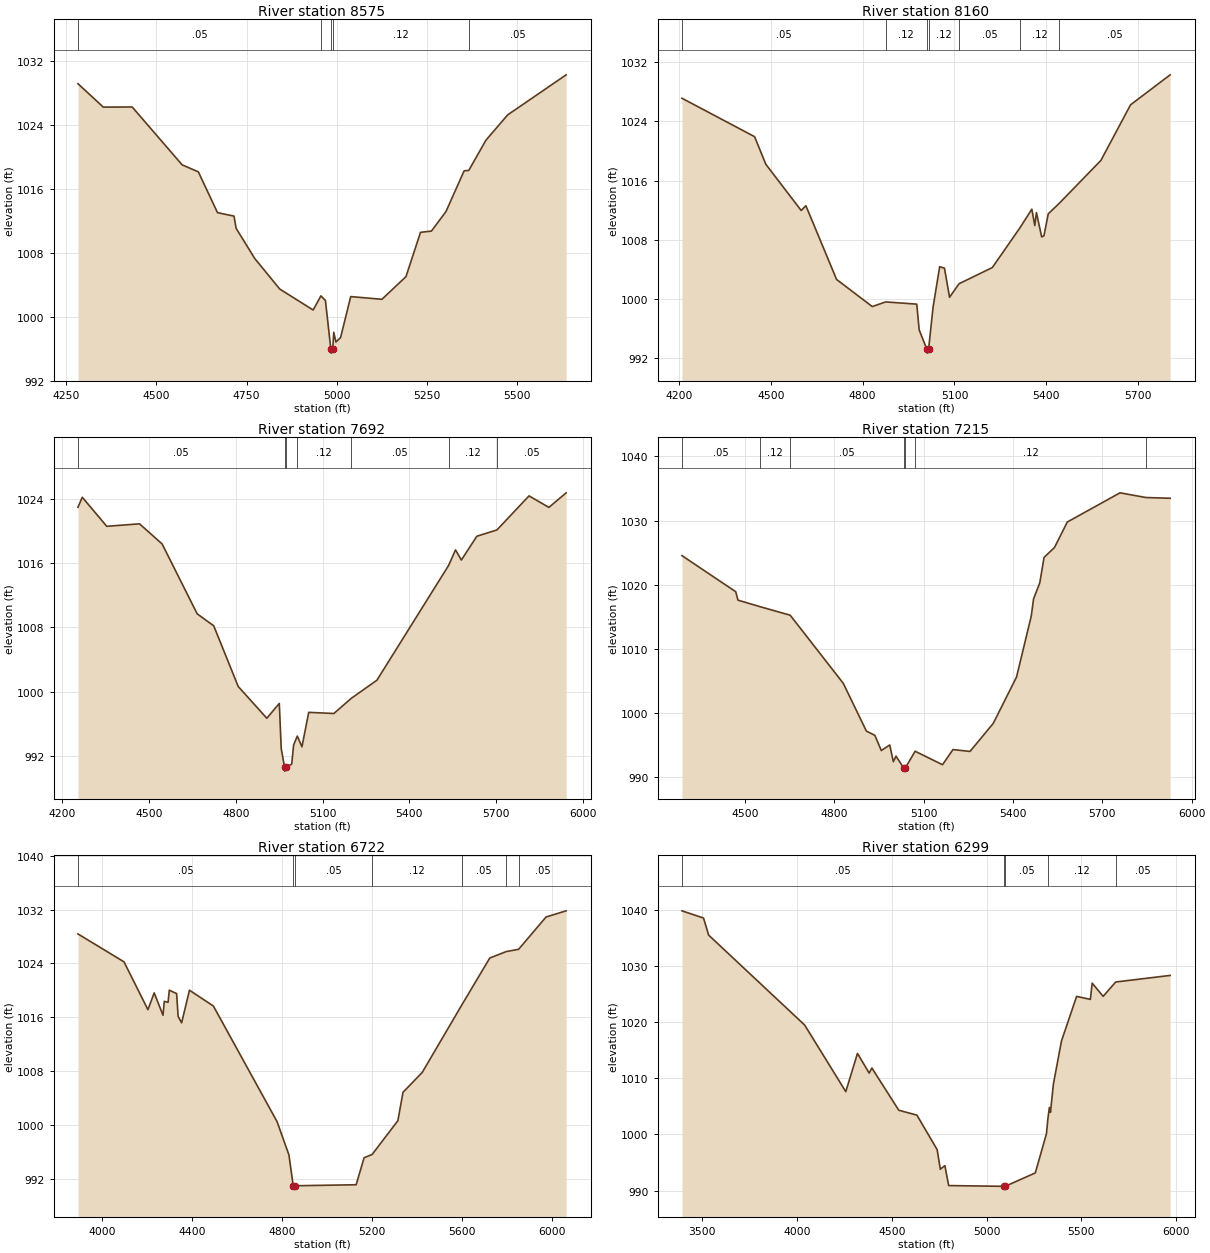
Type RM Length L Ch R = 1 ,8575    ,415,415,415
BEGIN DESCRIPTION:
WELLS BRANCH 19.0
END DESCRIPTION:
XS GIS Cut Line= 3
      2196682.86      7248514.07        2196979.        7247860.
      2197056.15      7247229.28
#Sta/Elev= 30
  4282.5 1029.18  4352.7 1026.25  4432.9 1026.26  4571.5 1019.01  4616.3 1018.14
  4669.4 1013.03  4715.1  1012.6  4721.1 1011.06  4772.8 1007.28  4842.1 1003.46
  4934.5 1000.84  4956.1 1002.61  4968.6 1002.03  4983.6  995.94  4984.3  995.44
  4988.8  995.94  4991.7  998.05  4997.7  996.83  5010.6  997.39  5038.7 1002.52
  5125.2 1002.18  5191.9 1005.02  5232.2 1010.57  5262.4 1010.72  5302.7 1013.16
  5353.1 1018.27    5366 1018.32  5413.5  1022.1    5474 1025.28  5635.9 1030.29
#Mann= 5 ,-1 , 0
  4282.5     .05       0  4956.1     .12       0  4983.6     .07       0
  4988.8     .12       0    5366     .05       0
Bank Sta=4983.6,4988.8
XS Rating Curve= 0 ,0
Exp/Cntr=0.3,0.1

Type RM Length L Ch R = 1 ,8160    ,468,468,468
BEGIN DESCRIPTION:
WELLS BRANCH 18.0
END DESCRIPTION:
XS GIS Cut Line= 3
      2196938.98       7248557.4       2197364.3      7247876.01
      2197654.55      7247139.58
#Sta/Elev= 30
  4209.8 1027.14  4447.1 1021.94  4483.7 1018.21  4599.3 1011.95  4614.6  1012.6
  4714.9 1002.62  4831.5  998.95  4875.2  999.58  4976.8  999.28  4984.8  995.78
  5010.1  993.15  5010.8  992.65  5015.4  993.15  5030.2   998.9  5051.7 1004.34
  5067.3 1004.15    5084 1000.21  5114.9 1002.04  5223.7 1004.23  5314.6 1009.65
  5352.7 1012.13  5362.4 1009.92  5367.8 1011.67  5384.9 1008.38  5392.2 1008.52
  5406.4  1011.5  5442.7 1012.94  5578.4 1018.73  5675.2 1026.25  5804.6 1030.31
#Mann= 7 ,-1 , 0
  4209.8     .05       0  4875.2     .12       0  5010.1     .07       0
  5015.4     .12       0  5114.9     .05       0  5314.6     .12       0
  5442.7     .05       0
Bank Sta=5010.1,5015.4
XS Rating Curve= 0 ,0
Exp/Cntr=0.3,0.1

Type RM Length L Ch R = 1 ,7692    ,477,477,477
BEGIN DESCRIPTION:
WELLS BRANCH 17.0
END DESCRIPTION:
XS GIS Cut Line= 3
      2197025.77      7248657.26       2197611.7      7248175.49
      2197924.09      7247299.06
#Sta/Elev= 30
  4253.6 1022.92  4268.6 1024.17  4353.3 1020.56  4466.6 1020.87  4544.8 1018.37
  4666.1 1009.69  4723.4  1008.2  4808.1 1000.66  4907.1  996.72  4950.2  998.56
  4956.9  992.97  4968.3  990.65  4969.1  990.15  4973.6  990.65  4993.2  991.02
  4999.7   993.4  5012.5   994.5  5028.6  993.17    5052  997.45  5139.1  997.31
  5199.8  999.21  5287.9 1001.44  5535.8 1015.69  5559.9 1017.63  5580.1 1016.37
  5633.7 1019.33  5703.2 1020.11  5814.2 1024.34    5883 1022.91  5942.6 1024.72
#Mann= 7 ,-1 , 0
  4253.6     .05       0  4968.3    .033       0  4973.6     .05       0
  5012.5     .12       0  5199.8     .05       0  5535.8     .12       0
  5703.2     .05       0
Bank Sta=4968.3,4973.6
XS Rating Curve= 0 ,0
Exp/Cntr=0.3,0.1

Type RM Length L Ch R = 1 ,7215    ,493,493,493
BEGIN DESCRIPTION:
WELLS BRANCH 16.0
END DESCRIPTION:
XS GIS Cut Line= 3
      2197429.39      7248965.44      2197958.92      7248487.99
      2198669.74       7247894.2
#Sta/Elev= 30
  4288.6 1024.54  4469.2 1018.91  4476.6  1017.6  4552.2 1016.56    4652 1015.25
  4830.1 1004.64  4907.9  997.18  4936.3  996.52  4957.9  994.15  4986.3  995.02
  4998.3  992.41  5007.2  993.27  5033.2  991.44  5033.9  990.94  5038.6  991.44
  5071.6  994.04  5163.4  991.94  5198.6   994.3  5255.8  994.01  5333.9  998.39
    5412 1005.61  5461.4 1015.11  5469.2 1017.79  5490.1  1020.3  5504.4 1024.26
  5539.5 1025.81  5582.5 1029.78  5759.5 1034.33  5846.1  1033.6  5927.8 1033.48
#Mann= 7 ,-1 , 0
  4288.6     .05       0  4552.2     .12       0    4652     .05       0
  5033.2    .033       0  5038.6     .05       0  5071.6     .12       0
  5846.1     .05       0
Bank Sta=5033.2,5038.6
XS Rating Curve= 0 ,0
Exp/Cntr=0.3,0.1

Type RM Length L Ch R = 1 ,6722    ,423,423,423
BEGIN DESCRIPTION:
WELLS BRANCH 15.0
END DESCRIPTION:
XS GIS Cut Line= 3
      2197286.16      7249303.97        2198279.        7248810.
      2199130.81      7248175.48
#Sta/Elev= 30
  3891.3 1028.39  4096.1 1024.24  4202.5 1017.14  4230.4 1019.63  4269.6 1016.31
  4275.2 1018.37    4292 1018.23  4297.6 1020.03  4330.1 1019.53  4336.8 1016.14
  4352.4 1015.18  4387.2 1020.03  4493.6 1017.68  4776.9  1000.5  4829.5  995.57
  4848.7  990.98  4849.8  990.48    4855  990.98  5128.5  991.13  5163.9  995.14
  5199.9  995.64  5314.1 1000.65  5336.9 1004.86  5422.5 1007.82  5597.1 1017.76
  5722.8 1024.81  5796.3 1025.77    5851  1026.1  5972.9  1030.9  6062.4 1031.82
#Mann= 7 ,-1 , 0
  3891.3     .05       0  4848.7    .033       0    4855     .05       0
  5199.9     .12       0  5597.1     .05       0  5796.3     .12       0
    5851     .05       0
Bank Sta=4848.7,4855
XS Rating Curve= 0 ,0
Exp/Cntr=0.3,0.1

Type RM Length L Ch R = 1 ,6299    ,210,210,210
BEGIN DESCRIPTION:
WELLS BRANCH 14.0
END DESCRIPTION:
XS GIS Cut Line= 5
      2196899.93      7249442.85      2198375.59      7249204.14
        2198479.        7249160.      2198740.17      7249013.17
      2199308.76       7248661.6
#Sta/Elev= 30
    3393 1039.78  3506.7  1038.5  3533.9 1035.46  4040.4 1019.46  4257.2 1007.62
  4318.9 1014.42  4380.6 1010.92  4394.9 1011.82  4536.8 1004.31  4632.5 1003.44
  4739.3   997.3  4755.9  993.82  4779.9  994.46  4800.1  990.91  5091.8  990.78
  5092.8  990.28  5098.1  990.78  5256.9  993.16  5315.8 1000.13  5322.8  1002.6
  5331.2 1004.81  5337.1 1003.94  5352.4 1008.96    5395 1016.62  5474.9 1024.56
  5547.5 1024.03    5557 1026.92  5614.9 1024.57  5681.2 1027.12  5968.4 1028.29
#Mann= 5 ,-1 , 0
    3393     .05       0  5091.8    .033       0  5098.1     .05       0
  5322.8     .12       0  5681.2     .05       0
Bank Sta=5091.8,5098.1
XS Rating Curve= 0 ,0
Exp/Cntr=0.3,0.1