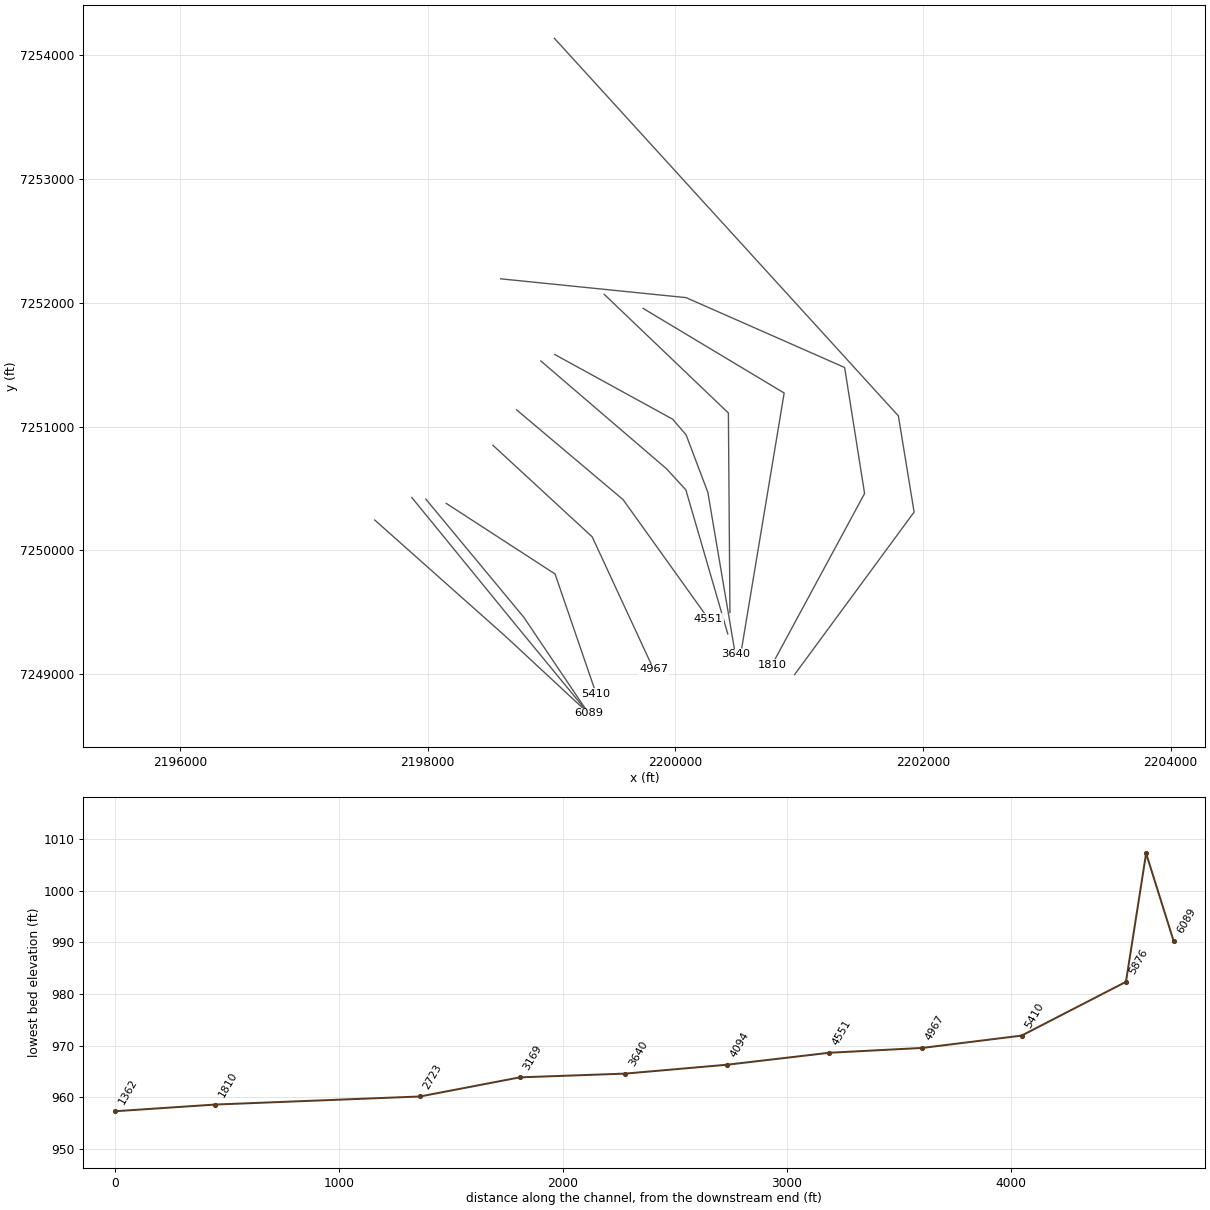
HEC-RAS study WELLS BRANCH.prj: WELLS BRANCH Base Level Engineering

--- WELLS BRANCH.g01 (geometry) --- (continued)

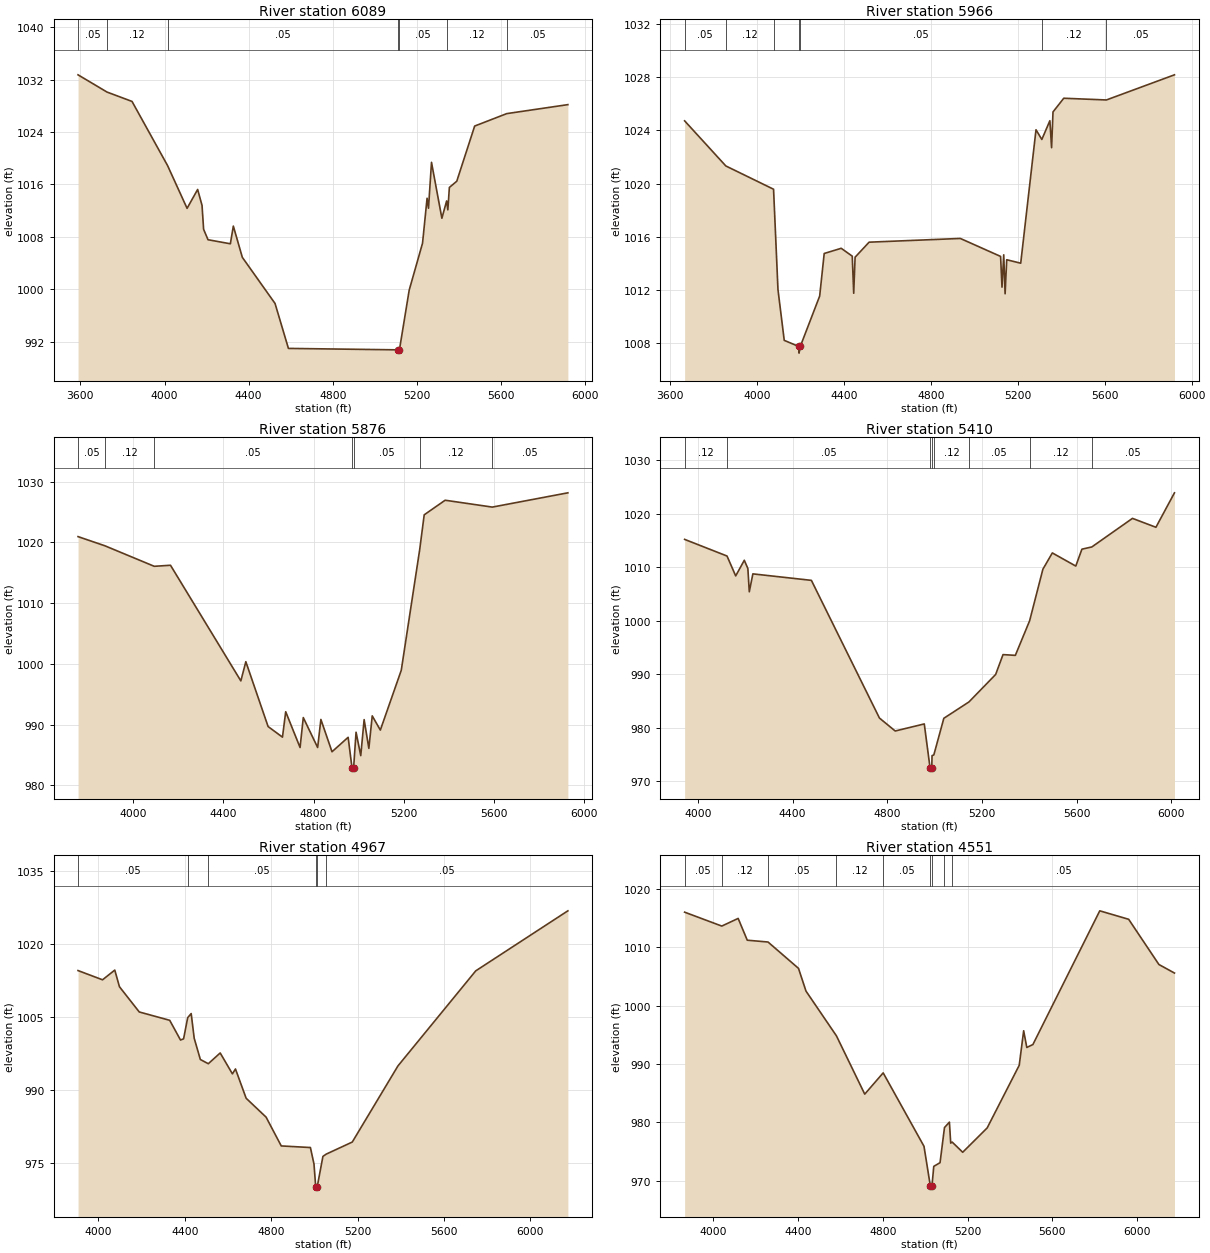
Type RM Length L Ch R = 1 ,6089    ,123,123,123
BEGIN DESCRIPTION:
WELLS BRANCH 13.5
END DESCRIPTION:
XS GIS Cut Line= 3
      2197572.62      7250245.82      2198631.66      7249303.96
      2199299.18      7248684.13
#Sta/Elev= 30
  3588.9 1032.73  3726.6  1030.1  3845.5 1028.67  4014.6 1018.87  4107.2 1012.35
  4157.4 1015.23  4178.3  1012.8  4185.8 1009.15  4206.7 1007.56  4312.9 1006.94
  4327.1 1009.64  4369.8 1004.87  4525.3  997.83  4588.9  990.97  5109.6  990.75
  5110.7  990.25  5116.5  990.75  5162.9  999.86  5226.4 1007.04  5247.9 1013.89
  5254.7 1012.37  5268.9 1019.37  5318.3 1010.84  5340.9 1013.48  5346.6 1012.12
  5353.9 1015.54  5389.1 1016.49  5474.1 1024.91  5626.7 1026.81  5917.1 1028.18
#Mann= 7 ,-1 , 0
  3588.9     .05       0  3726.6     .12       0  4014.6     .05       0
  5109.6    .033       0  5116.5     .05       0  5340.9     .12       0
  5626.7     .05       0
Bank Sta=5109.6,5116.5
XS Rating Curve= 0 ,0
Exp/Cntr=0.3,0.1

Type RM Length L Ch R = 1 ,5966    ,90,90,90
BEGIN DESCRIPTION:
WELLS BRANCH 13.4
END DESCRIPTION:
XS GIS Cut Line= 3
      2197872.31      7250427.34      2198718.67      7249390.01
      2199299.35      7248684.17
#Sta/Elev= 30
  3668.2 1024.72  3857.7 1021.33  4077.2 1019.58  4097.5 1012.04  4126.3 1008.22
  4193.2 1007.76  4194.3 1007.26  4200.1 1007.76  4289.3 1011.55  4310.1 1014.75
  4388.3 1015.14  4439.1 1014.55  4445.8 1011.76  4452.2 1014.47  4516.6  1015.6
  4936.2 1015.88  5121.3 1014.53  5127.8 1012.22  5135.7 1014.65  5142.1 1011.72
  5149.5 1014.28  5213.9 1014.02  5284.2 1024.05    5311 1023.32    5348 1024.73
  5355.9  1022.7  5362.4 1025.39  5411.9 1026.42  5607.8 1026.29    5921 1028.18
#Mann= 7 ,-1 , 0
  3668.2     .05       0  3857.7     .12       0  4077.2     .05       0
  4193.2    .033       0  4200.1     .05       0    5311     .12       0
  5607.8     .05       0
Bank Sta=4193.2,4200.1
XS Rating Curve= 0 ,0
Exp/Cntr=0.3,0.1

Type RM Length L Ch R = 1 ,5876    ,466,466,466
BEGIN DESCRIPTION:
WELLS BRANCH 13.0
END DESCRIPTION:
XS GIS Cut Line= 3
      2197984.99      7250415.04      2198776.92        7249460.
       2199299.5      7248684.14
#Sta/Elev= 30
  3753.8 1020.97  3873.7 1019.45  4092.4 1016.08  4164.6 1016.25  4477.1  997.21
  4499.3 1000.37  4598.2  989.69    4662  987.95  4676.4  992.13  4740.2  986.24
  4754.5  991.17  4818.3  986.24  4832.7  990.86  4882.1  985.54  4953.8  987.92
  4971.1  982.85  4972.2  982.35    4978  982.85  4988.9  988.76  5009.8   984.9
  5024.8  990.83  5045.8   986.1  5060.8  991.45  5096.8  989.11  5189.8  998.96
  5271.5 1018.79  5291.7 1024.56  5384.7 1026.96  5594.2 1025.83  5929.9 1028.18
#Mann= 7 ,-1 , 0
  3753.8     .05       0  3873.7     .12       0  4092.4     .05       0
  4971.1    .033       0    4978     .05       0  5271.5     .12       0
  5594.2     .05       0
Bank Sta=4971.1,4978
XS Rating Curve= 0 ,0
Exp/Cntr=0.3,0.1

Type RM Length L Ch R = 1 ,5410    ,443,443,443
BEGIN DESCRIPTION:
WELLS BRANCH 12.0
END DESCRIPTION:
XS GIS Cut Line= 3
      2198149.88      7250380.37        2199029.        7249810.
      2199360.65      7248844.41
#Sta/Elev= 30
  3944.2 1015.18  4123.3 1012.07  4159.9 1008.36  4196.2 1011.28  4211.3 1009.74
  4217.3  1005.4  4232.4 1008.74  4479.6 1007.53    4767  981.83  4833.6  979.41
  4956.4  980.73  4981.1  972.42  4982.2  971.92    4988  972.42  4989.2  974.81
  4996.7  974.94    5039  981.78  5145.2  984.84  5257.8  989.96    5289  993.67
    5341  993.53  5401.3  999.98  5457.4 1009.61  5497.2 1012.65  5596.3  1010.2
  5622.2 1013.35  5664.2 1013.77  5835.7  1019.1  5934.8 1017.44  6013.1 1023.87
#Mann= 8 ,-1 , 0
  3944.2     .12       0  4123.3     .05       0  4981.1     .07       0
    4988     .05       0  4996.7     .12       0  5145.2     .05       0
  5401.3     .12       0  5664.2     .05       0
Bank Sta=4981.1,4988
XS Rating Curve= 0 ,0
Exp/Cntr=0.3,0.1

Type RM Length L Ch R = 1 ,4967    ,416,416,416
BEGIN DESCRIPTION:
WELLS BRANCH 11.0
END DESCRIPTION:
XS GIS Cut Line= 3
      2198527.49      7250849.11        2199329.        7250110.
      2199824.62      7249040.54
#Sta/Elev= 30
  3905.4 1014.46  4018.9 1012.56  4075.6 1014.56  4097.2 1011.14    4189 1005.95
  4330.2 1004.23  4380.1 1000.18  4394.3 1000.42  4413.4 1004.78  4429.5 1005.62
  4443.6 1000.53    4472  996.18  4508.8  995.31  4563.9  997.52  4620.6  993.22
  4634.7  994.23  4684.1  988.21  4776.5  984.33  4846.8  978.41  4981.8  978.08
  4998.4  974.69  5006.3  970.03  5007.4  969.53  5013.4  970.03  5039.8  976.26
  5055.7  976.74  5175.8  979.21  5387.5  994.87  5747.7  1014.4  6174.4 1026.74
#Mann= 6 ,-1 , 0
  3905.4     .05       0  4413.4     .12       0  4508.8     .05       0
  5006.3    .033       0  5013.4     .05       0  5055.7     .05       0
Bank Sta=5006.3,5013.4
XS Rating Curve= 0 ,0
Exp/Cntr=0.3,0.1

Type RM Length L Ch R = 1 ,4551    ,457,457,457
BEGIN DESCRIPTION:
WELLS BRANCH 10.0
END DESCRIPTION:
XS GIS Cut Line= 3
       2198718.5      7251135.53        2199579.        7250410.
      2200267.97      7249447.16
#Sta/Elev= 30
  3866.2    1016  4041.4 1013.62  4118.6 1014.93  4161.5  1011.2  4259.4 1010.89
  4403.1 1006.38  4438.4 1002.49  4582.1  994.82  4715.4  984.85  4802.3  988.49
  4994.8  975.92  5024.9  969.09  5026.1  968.59  5032.2  969.09  5040.9  972.49
  5070.4  973.11  5091.4  979.13  5114.6  980.06  5120.7  976.47  5127.8  976.64
  5177.3   974.9  5292.7  979.07  5443.8  989.79  5464.7   995.7  5479.5  992.84
  5508.2  993.34  5823.5 1016.23  5959.8 1014.78  6102.4 1007.04  6175.7 1005.58
#Mann= 9 ,-1 , 0
  3866.2     .05       0  4041.4     .12       0  4259.4     .05       0
  4582.1     .12       0  4802.3     .05       0  5024.9    .033       0
  5032.2     .05       0  5091.4     .12       0  5127.8     .05       0
Bank Sta=5024.9,5032.2
XS Rating Curve= 0 ,0
Exp/Cntr=0.3,0.1

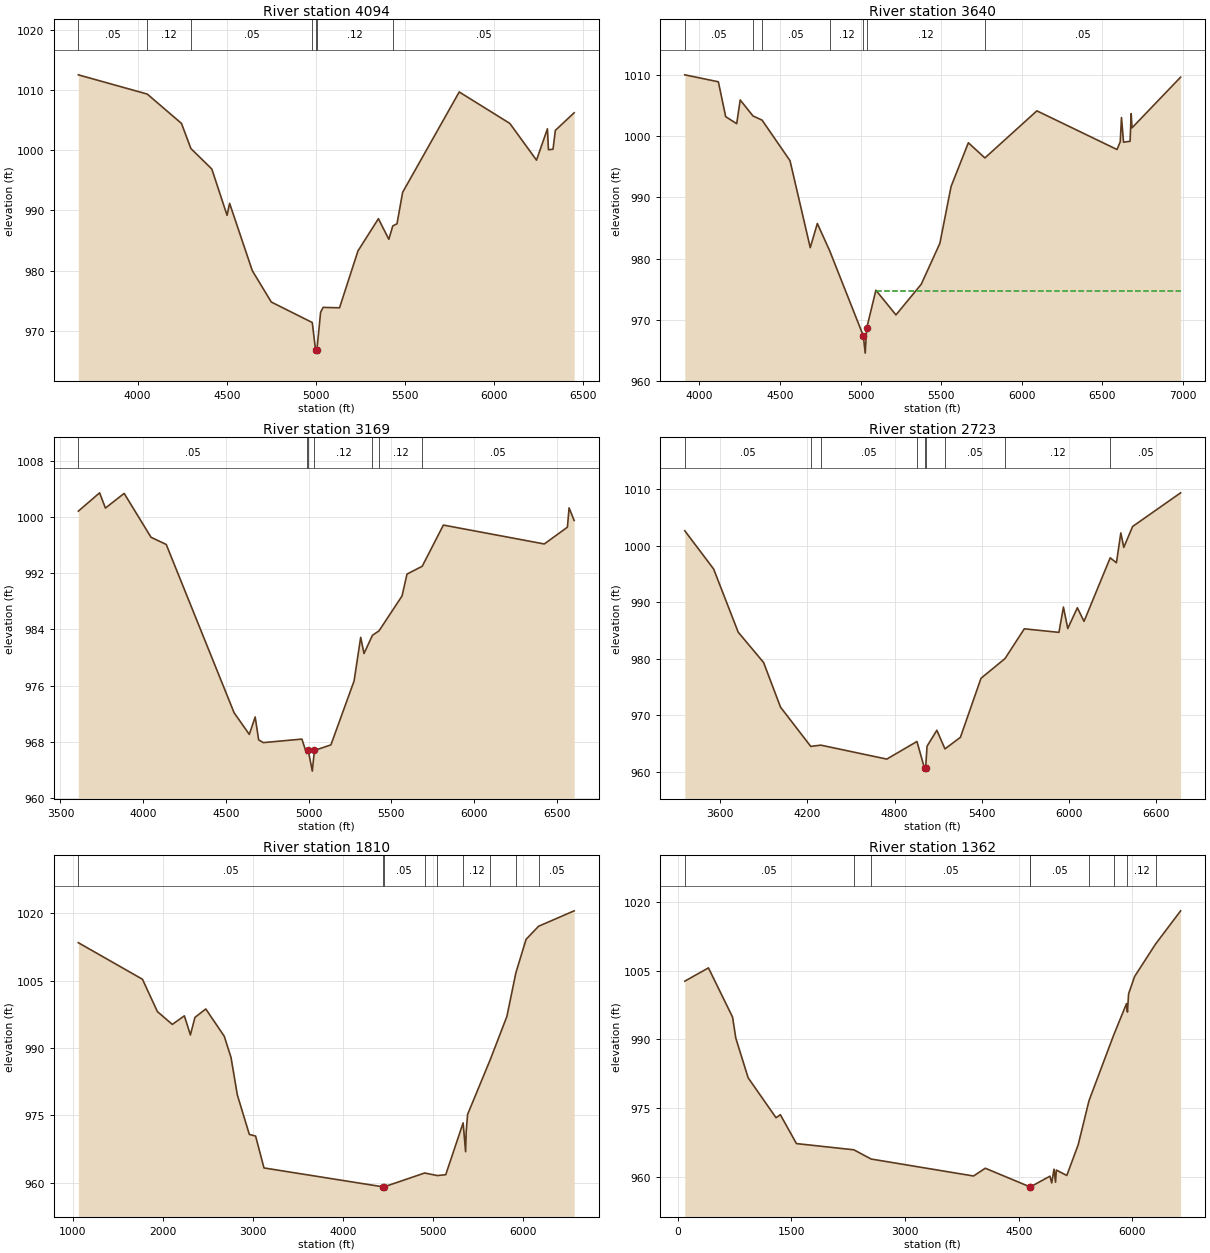
Type RM Length L Ch R = 1 ,4094    ,454,454,454
BEGIN DESCRIPTION:
WELLS BRANCH 9.0
END DESCRIPTION:
XS GIS Cut Line= 4
       2198913.8      7251530.51        2199929.        7250660.
      2200085.66      7250488.86      2200424.09      7249326.04
#Sta/Elev= 30
    3668 1012.56  4054.5 1009.36  4246.4 1004.48  4299.2  1000.3  4416.5   996.9
  4502.1  989.19  4516.4  991.18  4643.7  979.98  4750.1  974.77  4979.9  971.36
  4998.4  966.77  4999.5  966.27  5005.7  966.77  5026.6  973.08  5040.8  973.88
  5132.7  973.81  5236.1  983.27  5350.7  988.63  5409.2   985.2  5431.3  987.43
  5454.9  987.78  5486.6  993.02  5803.9 1009.71  6087.6 1004.48  6237.3  998.37
  6298.5 1003.58  6304.3  1000.1  6329.7 1000.18    6343 1003.32  6448.4 1006.25
#Mann= 7 ,-1 , 0
    3668     .05       0  4054.5     .12       0  4299.2     .05       0
  4979.9     .12       0  4998.4     .07       0  5005.7     .12       0
  5431.3     .05       0
Bank Sta=4998.4,5005.7
XS Rating Curve= 0 ,0
Exp/Cntr=0.3,0.1

Type RM Length L Ch R = 1 ,3640    ,471,471,471
BEGIN DESCRIPTION:
WELLS BRANCH 8.0
END DESCRIPTION:
XS GIS Cut Line= 5
      2199026.62      7251582.61        2199979.        7251060.
      2200087.63      7250933.26      2200262.98      7250469.62
      2200484.96      7249160.77
#Sta/Elev= 30
  3909.4 1010.06  4117.7 1008.92  4163.1 1003.22  4231.4 1002.07  4253.2 1005.95
  4332.4 1003.34    4389 1002.65  4562.3  996.02  4687.8   981.8  4731.8  985.75
  4809.5  981.22  5017.1  967.38  5028.9  964.55    5038  968.63  5095.1  974.84
  5219.6   970.8  5376.6  975.82  5491.9  982.49  5561.7  991.81  5668.8  998.95
  5771.4  996.47  6094.1 1004.17  6591.1  997.85  6611.4  999.12  6618.9 1003.08
  6631.7  999.04  6672.3  999.19  6679.2 1003.72  6684.3 1001.39  6985.9 1009.68
#Mann= 7 ,-1 , 0
  3909.4     .05       0  4332.4     .12       0    4389     .05       0
  4809.5     .12       0  5017.1     .07       0    5038     .12       0
  5771.4     .05       0
#XS Ineff= 2 , 0
                         5093.88          974.76
Permanent Ineff=
       F       F
Bank Sta=5017.1,5038
XS Rating Curve= 0 ,0
Exp/Cntr=0.3,0.1

Type RM Length L Ch R = 1 ,3169    ,446,446,446
BEGIN DESCRIPTION:
WELLS BRANCH 7.0
END DESCRIPTION:
XS GIS Cut Line= 3
      2199425.96       7252068.7        2200429.        7251110.
      2200441.56      7249499.26
#Sta/Elev= 30
  3607.9 1000.83  3736.6 1003.44  3771.8 1001.27    3885 1003.36  4047.6  997.11
  4139.5  996.09  4549.9  972.13  4641.8  969.05  4677.3  971.53  4698.4  968.27
  4726.7  967.88    4960  968.38  4988.3  966.32  4997.9  966.81  5022.8  963.82
  5035.4  966.76  5135.4  967.56  5275.4  976.66  5315.4  982.87  5335.4  980.56
  5386.4  983.16  5426.2  983.79  5565.4  988.76  5595.4  991.87  5687.6  992.99
  5815.4  998.85  6425.5  996.16  6565.5  998.55  6575.5  1001.3  6606.2  999.51
#Mann= 7 ,-1 , 0
  3607.9     .05       0  4988.3     .12       0  4997.9    .033       0
  5035.4     .12       0  5386.4     .05       0  5426.2     .12       0
  5687.6     .05       0
Bank Sta=4997.9,5035.4
XS Rating Curve= 0 ,0
Exp/Cntr=0.3,0.1

Type RM Length L Ch R = 1 ,2723    ,913,913,913
BEGIN DESCRIPTION:
WELLS BRANCH 6.0
END DESCRIPTION:
XS GIS Cut Line= 3
      2199740.14      7251955.05       2200879.5      7251271.43
      2200537.23      7249213.92
#Sta/Elev= 30
  3355.6 1002.67  3554.2   995.9  3723.3  984.72  3898.2  979.35  4014.9  971.44
    4223  964.49  4292.7  964.71  4746.6  962.24  4954.3  965.36  5006.4  960.61
  5007.6  960.11  5013.9  960.61  5023.9  964.52  5091.3  967.35  5147.3  964.05
  5253.5  966.09  5395.4  976.55  5561.1  980.05  5693.6  985.31  5932.1  984.68
  5963.1  989.16    5993  985.36  6058.9  989.04    6105  986.63  6285.1  997.88
    6328  997.01  6358.3 1002.29  6378.7  999.73  6439.5 1003.43  6770.1 1009.39
#Mann= 9 ,-1 , 0
  3355.6     .05       0    4223     .12       0  4292.7     .05       0
  4954.3     .12       0  5006.4     .07       0  5013.9     .12       0
  5147.3     .05       0  5561.1     .12       0  6285.1     .05       0
Bank Sta=5006.4,5013.9
XS Rating Curve= 0 ,0
Exp/Cntr=0.3,0.1

Type RM Length L Ch R = 1 ,1810    ,448,448,448
BEGIN DESCRIPTION:
WELLS BRANCH 4.0
END DESCRIPTION:
XS GIS Cut Line= 5
      2198590.05      7252193.74       2200087.4      7252041.83
      2201367.78       7251477.6        2201529.        7250460.
      2200780.37      7249074.43
#Sta/Elev= 30
  1060.6 1013.44  1773.2  1005.3  1939.4  998.09  2104.9  995.24  2238.8  997.15
  2305.9   992.9  2356.2   996.8  2476.8  998.68    2682  992.61  2757.4  987.86
  2827.4  979.54  2960.8  970.74  3030.4  970.37  3123.7  963.27  4448.8  959.05
    4450  958.55  4456.5  959.05  4908.8  962.14  5050.1  961.57  5142.9  961.76
  5336.3  973.31  5363.9  966.88  5370.2  971.28  5385.8  975.19  5639.6  987.49
  5822.6  997.02  5922.6 1006.75  6035.8 1014.19  6174.4  1017.1    6570 1020.54
#Mann= 9 ,-1 , 0
  1060.6     .05       0  4448.8     .07       0  4456.5     .05       0
  4908.8     .12       0  5050.1     .05       0  5336.3     .12       0
  5639.6     .05       0  5922.6     .12       0  6174.4     .05       0
Bank Sta=4448.8,4456.5
XS Rating Curve= 0 ,0
Exp/Cntr=0.3,0.1

Type RM Length L Ch R = 1 ,1362    ,0,0,0
BEGIN DESCRIPTION:
WELLS BRANCH 3.0
END DESCRIPTION:
XS GIS Cut Line= 4
      2199024.03      7254136.02      2201801.81      7251086.97
        2201929.        7250310.       2200963.2      7248996.89
#Sta/Elev= 30
    93.6 1002.73   405.7 1005.63     724  994.87   766.6  990.27   929.4   981.6
  1297.6  972.86  1354.4  973.53  1566.5  967.21  2323.6  965.85  2552.7  963.83
    3903  960.12  4058.4  961.82    4647  957.75  4648.2  957.25  4654.8  957.75
    4911  960.08  4934.6  958.61    4965  961.61  4985.3  958.76  4995.4  961.42
    5134  960.24  5284.5  966.98  5426.4  976.57    5750  990.84  5921.7  997.82
  5933.9  995.97    5949  999.96  6028.2 1003.74  6304.1 1010.83  6635.6 1018.11
#Mann= 9 ,-1 , 0
    93.6     .05       0  2323.6     .12       0  2552.7     .05       0
    4647    .033       0  4654.8     .05       0  5426.4     .12       0
    5750     .05       0  5933.9     .12       0  6304.1     .05       0
Bank Sta=4647,4654.8
XS Rating Curve= 0 ,0
Exp/Cntr=0.3,0.1

Chan Stop Cuts=-1
Use User Specified Reach Order=0
Composite Channel Slope=5