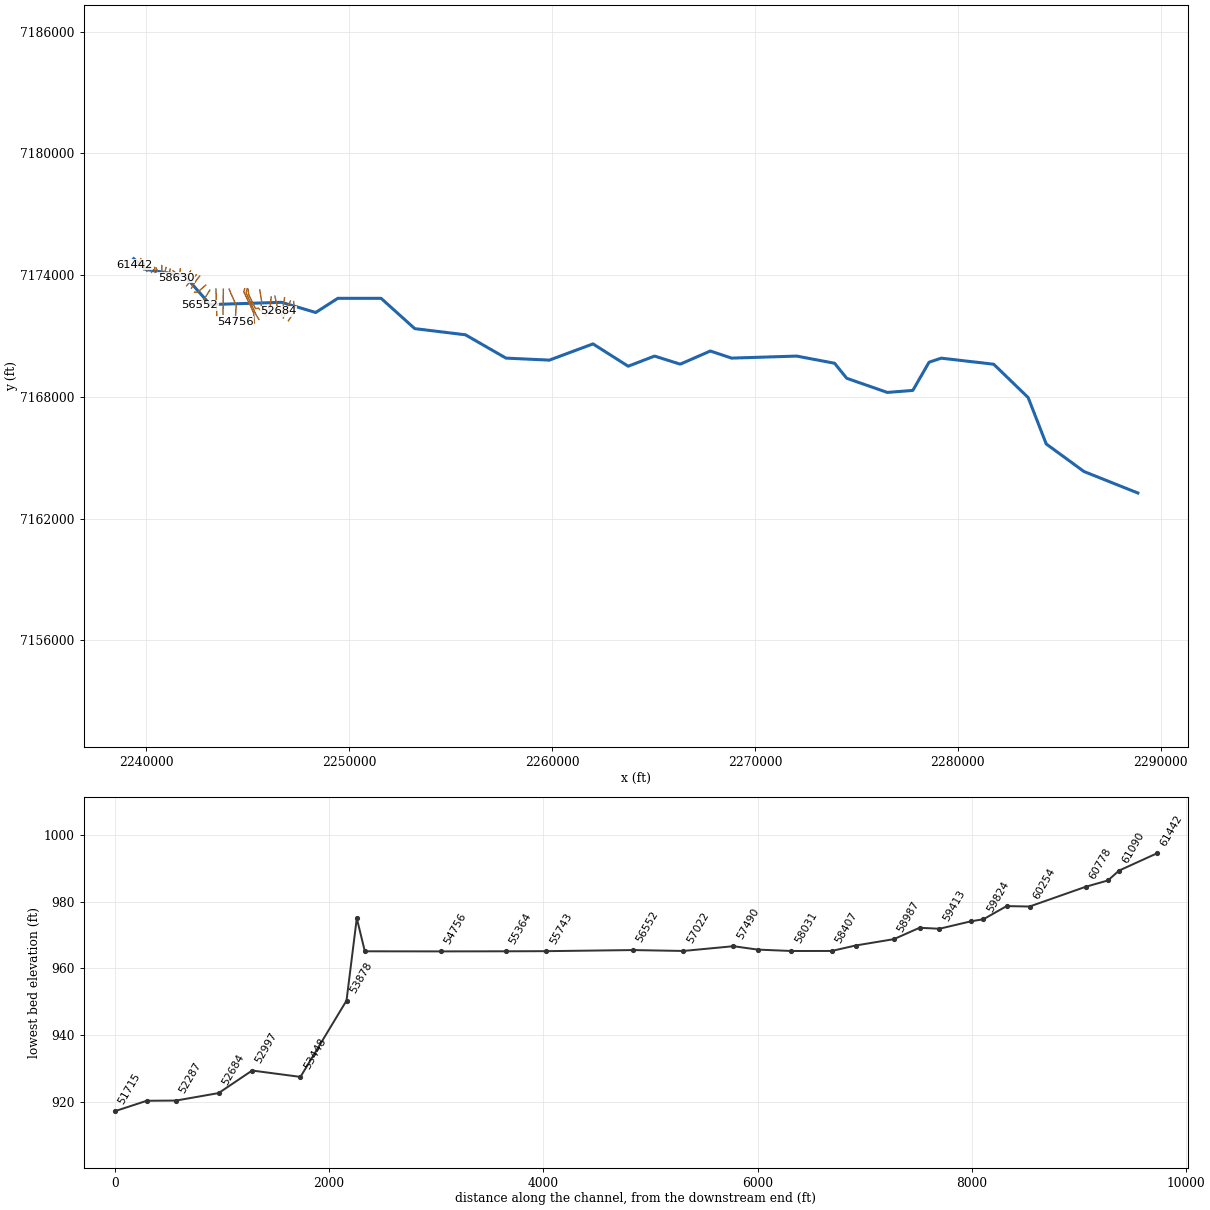
--- Black Creek.prj (project) ---

Proj Title=Black Creek Base Level Engineering
Current Plan=p01
Default Exp/Contr=0.3,0.1
English Units
Geom File=g01
Flow File=f01
Plan File=p01
BEGIN DESCRIPTION:
Black Creek
END DESCRIPTION:

--- Black Creek.p01 (plan) ---

Plan Title=Multiple Run
Short Identifier=Multiple
Geom File=g01
Flow File=f01
Subcritical Flow
K Sum by GR= 0
Std Step Tol= 0.01
Critical Tol= 0.01
Num of Std Step Trials= 20
Max Error Tol= 0.3
Flow Tol Ratio= 0.001
Split Flow NTrial= 30
Split Flow Tol= 0.02
Split Flow Ratio= 0.02
Log Output Level= 0
Friction Slope Method= 1
Unsteady Friction Slope Method= 2
Unsteady Bridges Friction Slope Method= 1
Parabolic Critical Depth
Global Vel Dist=  1 , 1 , 1
Global Log Level= 0
CheckData=True
Encroach Param= -1, 0, 0, 0
BEGIN DESCRIPTION:
Multiple Run
END DESCRIPTION:

--- Black Creek.f01 (steady flow) ---

Flow Title=Multiple
Number of Profiles=7
Profile Names=10-year,25-year,50-year,1pct_min,100-year,1pct_plu,500-year
River Rch & RM= Black Creek,Reach-1,61442
     551     758     929     567    1131    2257    1679
River Rch & RM= Black Creek,Reach-1,58987
     846    1190    1481     916    1827    3645    2786
River Rch & RM= Black Creek,Reach-1,55743
    1626    2372    3025    1911    3813    7607    6079
River Rch & RM= Black Creek,Reach-1,52684
    1871    2745    3514    2228    4445    8869    7136
River Rch & RM= Black Creek,Reach-1,50119
    2282    3375    4344    2767    5520   11014    8948
River Rch & RM= Black Creek,Reach-1,48374
    2555    3795    4899    3128    6241   12453   10168
River Rch & RM= Black Creek,Reach-1,47421
    2642    3918    5053    3223    6430   12829   10449
River Rch & RM= Black Creek,Reach-1,43300
    3027    4498    5809    3709    7401   14766   12050
River Rch & RM= Black Creek,Reach-1,40932
    3233    4815    6230    3983    7948   15858   12977
River Rch & RM= Black Creek,Reach-1,40466
    3236    4815    6225    3977    7936   15835   12939
River Rch & RM= Black Creek,Reach-1,38591
    3456    5152    6669    4265    8509   16978   13899
River Rch & RM= Black Creek,Reach-1,36925
    3595    5358    6934    4433    8844   17646   14435
River Rch & RM= Black Creek,Reach-1,33076
    3875    5791    7508    4808    9593   19140   15708
River Rch & RM= Black Creek,Reach-1,32534
    3969    5933    7693    4926    9829   19612   16097
River Rch & RM= Black Creek,Reach-1,30919
    4201    6282    8148    5217   10409   20769   17044
River Rch & RM= Black Creek,Reach-1,26950
    4465    6678    8662    5545   11065   22077   18110
River Rch & RM= Black Creek,Reach-1,18488
    4850    7269    9442    6052   12076   24094   19813
River Rch & RM= Black Creek,Reach-1,15760
    4958    7428    9646    6181   12332   24605   20216
River Rch & RM= Black Creek,Reach-1,12487
    4903    7329    9502    6078   12127   24197   19813
Boundary for River Rch & Prof#=Black Creek,Reach-1,1
Up Type=0
Dn Type=3
Dn Slope=0.005
Boundary for River Rch & Prof#=Black Creek,Reach-1,2
Up Type=0
Dn Type=3
Dn Slope=0.005
Boundary for River Rch & Prof#=Black Creek,Reach-1,3
Up Type=0
Dn Type=3
Dn Slope=0.005
Boundary for River Rch & Prof#=Black Creek,Reach-1,4
Up Type=0
Dn Type=3
Dn Slope=0.005
Boundary for River Rch & Prof#=Black Creek,Reach-1,5
Up Type=0
Dn Type=3
Dn Slope=0.005
Boundary for River Rch & Prof#=Black Creek,Reach-1,6
Up Type=0
Dn Type=3
Dn Slope=0.005
Boundary for River Rch & Prof#=Black Creek,Reach-1,7
Up Type=0
Dn Type=3
Dn Slope=0.005

--- Black Creek.g01 (geometry) ---

Geom Title=Existing Conditions

River Reach=Black Creek,Reach-1
Reach XY= 30
      2239379.00      7174810.00      2239956.18      7174287.11
      2241889.45      7173971.45      2243144.16      7172549.76
      2246658.82      7172660.28      2248349.46      7172159.45
      2249439.50      7172858.78      2251573.06      7172857.73
      2253230.47      7171363.55      2255729.00      7171060.00
      2257729.00      7169910.00      2259868.50      7169811.20
      2262018.95      7170610.80      2263753.78      7169509.76
      2265053.87      7170010.30      2266318.66      7169610.86
      2267803.88      7170260.12      2268853.88      7169909.88
      2272058.97      7170009.94      2273927.50      7169656.54
      2274526.45      7168915.73      2276529.00      7168217.55
      2277785.48      7168317.69      2278584.44      7169704.82
      2279184.93      7169907.75      2281772.97      7169608.38
      2283470.84      7167966.05      2284362.33      7165676.65
      2286226.70      7164315.83      2288879.00      7163260.00

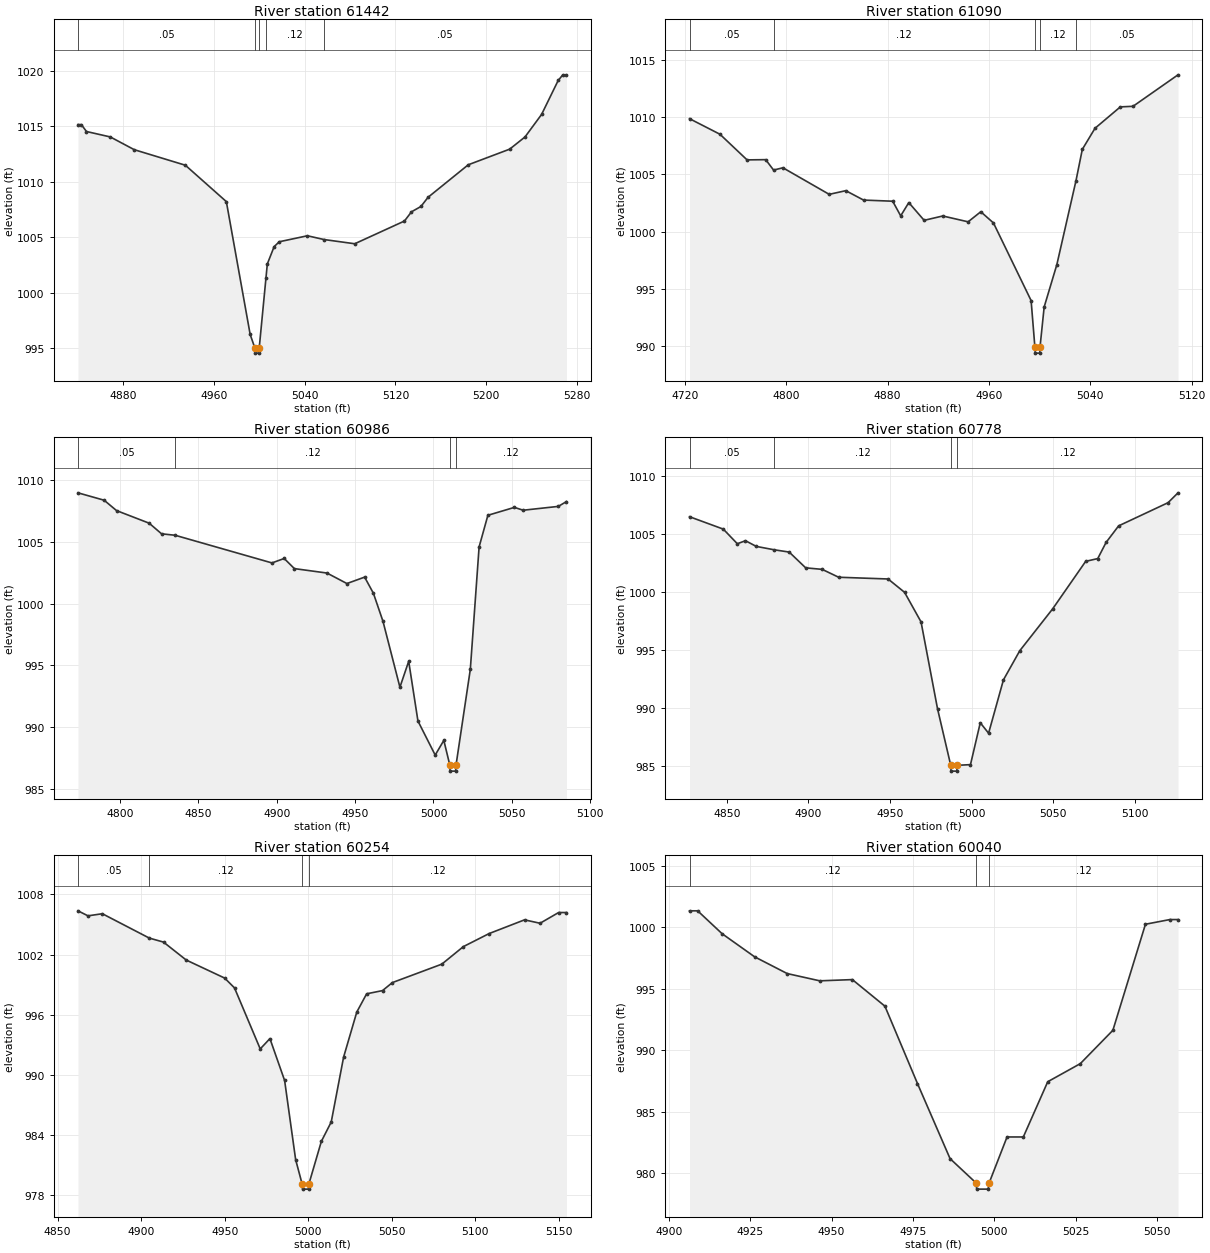
Type RM Length L Ch R = 1,61442,352,352,352
BEGIN DESCRIPTION:
Black Creek 97.0
END DESCRIPTION:
XS GIS Cut Line= 3
      2239729.00      7174810.00      2239629.00      7174660.00
      2239428.98      7174509.98
#Sta/Elev= 30
  4840.4 1015.14  4843.4 1015.14  4847.9 1014.52  4868.9 1014.03  4890.0 1012.88
  4935.0 1011.48  4971.1 1008.20  4992.1  996.22  4996.1  995.04  4996.4  994.54
  4999.9  994.54  5000.1  995.04  5006.0 1001.31  5007.2 1002.58  5013.2 1004.14
  5017.7 1004.58  5042.5 1005.12  5057.2 1004.78  5084.2 1004.40  5128.0 1006.45
  5134.2 1007.28  5142.5 1007.76  5148.8 1008.59  5184.2 1011.52  5220.7 1012.93
  5234.2 1014.03  5248.8 1016.06  5263.4 1019.12  5267.5 1019.63  5270.7 1019.63
#Mann=5,-1,0
  4840.4    0.05       0  4996.1   0.033       0  5000.1    0.05       0
  5006.0    0.12       0  5057.2    0.05       0
Bank Sta=4996.1,5000.1
Exp/Cntr=0.3,0.1

Type RM Length L Ch R = 1,61090,104,104,104
BEGIN DESCRIPTION:
Mapping XS ca11dfd4
END DESCRIPTION:
XS GIS Cut Line= 3
      2239832.52      7174629.37      2239721.77      7174478.71
      2239523.54      7174470.27
#Sta/Elev= 30
  4723.8 1009.87  4747.8 1008.51  4769.2 1006.27  4783.9 1006.29  4790.1 1005.38
  4797.5 1005.58  4834.0 1003.26  4847.1 1003.58  4861.1 1002.76  4884.1 1002.66
  4890.4 1001.38  4896.8 1002.54  4908.9 1000.99  4923.6 1001.37  4943.6 1000.86
  4953.6 1001.74  4963.6 1000.76  4993.3  993.98  4996.3  989.89  4996.6  989.39
  5000.1  989.39  5000.3  989.89  5003.6  993.42  5013.6  997.12  5028.7 1004.45
  5033.7 1007.19  5043.7 1009.03  5063.7 1010.90  5073.7 1010.95  5109.2 1013.70
#Mann=5,-1,0
  4723.8    0.05       0  4790.1    0.12       0  4996.3    0.07       0
  5000.3    0.12       0  5028.7    0.05       0
Bank Sta=4996.3,5000.3
Exp/Cntr=0.3,0.1

Type RM Length L Ch R = 1,60986,208,208,208
BEGIN DESCRIPTION:
Mapping XS abcaf551
END DESCRIPTION:
XS GIS Cut Line= 3
      2239850.55      7174612.87      2239739.76      7174477.63
      2239679.44      7174354.99
#Sta/Elev= 30
  4773.3 1008.97  4790.0 1008.37  4797.9 1007.53  4818.7 1006.51  4826.6 1005.65
  4835.3 1005.53  4897.0 1003.29  4904.8 1003.65  4911.3 1002.83  4932.1 1002.47
  4944.8 1001.62  4956.1 1002.14  4961.7 1000.83  4967.8  998.56  4978.6  993.22
  4984.2  995.32  4990.1  990.48  5001.1  987.72  5006.6  988.91  5010.4  986.92
  5010.6  986.42  5014.1  986.42  5014.4  986.92  5023.5  994.67  5029.1 1004.59
  5034.7 1007.15  5051.6 1007.79  5057.2 1007.56  5079.6 1007.87  5084.8 1008.26
#Mann=4,-1,0
  4773.3    0.05       0  4835.3    0.12       0  5010.4    0.07       0
  5014.4    0.12       0
Bank Sta=5010.4,5014.4
Exp/Cntr=0.3,0.1

Type RM Length L Ch R = 1,60778,524,524,524
BEGIN DESCRIPTION:
Mapping XS 7bb9f1ae
END DESCRIPTION:
XS GIS Cut Line= 2
      2239908.47      7174560.55      2239867.60      7174263.95
#Sta/Elev= 30
  4827.1 1006.46  4847.8 1005.39  4856.4 1004.13  4861.4 1004.39  4868.0 1003.90
  4878.9 1003.61  4888.2 1003.41  4898.3 1002.05  4908.4 1001.92  4918.5 1001.24
  4948.8 1001.09  4958.9  999.94  4969.0  997.39  4979.1  989.90  4987.2  985.02
  4987.4  984.52  4990.9  984.52  4991.2  985.02  4999.3  985.08  5005.3  988.69
  5010.4  987.79  5019.5  992.39  5029.5  994.90  5049.7  998.52  5069.9 1002.61
  5077.3 1002.85  5082.4 1004.24  5090.1 1005.67  5120.4 1007.67  5126.5 1008.52
#Mann=4,-1,0
  4827.1    0.05       0  4878.9    0.12       0  4987.2    0.07       0
  4991.2    0.12       0
Bank Sta=4987.2,4991.2
Exp/Cntr=0.3,0.1

Type RM Length L Ch R = 1,60254,214,214,214
BEGIN DESCRIPTION:
Mapping XS ceed16a1
END DESCRIPTION:
XS GIS Cut Line= 2
      2240183.09      7174435.09      2240029.00      7174186.58
#Sta/Elev= 30
  4862.2 1006.36  4868.2 1005.86  4876.8 1006.07  4904.9 1003.64  4913.4 1003.24
  4927.0 1001.45  4950.0  999.65  4955.9  998.67  4971.3  992.58  4977.1  993.61
  4985.9  989.43  4992.5  981.53  4996.4  979.09  4996.7  978.59  5000.2  978.59
  5000.4  979.09  5007.9  983.36  5013.8  985.29  5021.2  991.76  5029.1  996.26
  5035.0  998.08  5044.5  998.40  5050.4  999.20  5080.0 1001.04  5092.9 1002.79
  5108.3 1004.09  5129.5 1005.46  5138.8 1005.12  5149.9 1006.19  5154.6 1006.19
#Mann=4,-1,0
  4862.2    0.05       0  4904.9    0.12       0  4996.4    0.07       0
  5000.4    0.12       0
Bank Sta=4996.4,5000.4
Exp/Cntr=0.3,0.1

Type RM Length L Ch R = 1,60040,216,216,216
BEGIN DESCRIPTION:
Black Creek 94.0
END DESCRIPTION:
XS GIS Cut Line= 3
      2240229.00      7174309.96      2240229.00      7174210.00
      2240229.00      7174159.96
#Sta/Elev= 22
  4906.4 1001.34  4908.9 1001.34  4916.4  999.48  4926.4  997.60  4936.4  996.24
  4946.4  995.65  4956.4  995.75  4966.4  993.59  4976.4  987.30  4986.4  981.20
  4994.4  979.22  4994.6  978.72  4998.1  978.72  4998.4  979.22  5003.9  982.96
  5008.9  982.96  5016.4  987.45  5026.4  988.92  5036.4  991.63  5046.4 1000.25
  5053.9 1000.63  5056.4 1000.63
#Mann=3,-1,0
  4906.4    0.12       0  4994.4    0.07       0  4998.4    0.12       0
Bank Sta=4994.4,4998.4
Exp/Cntr=0.3,0.1

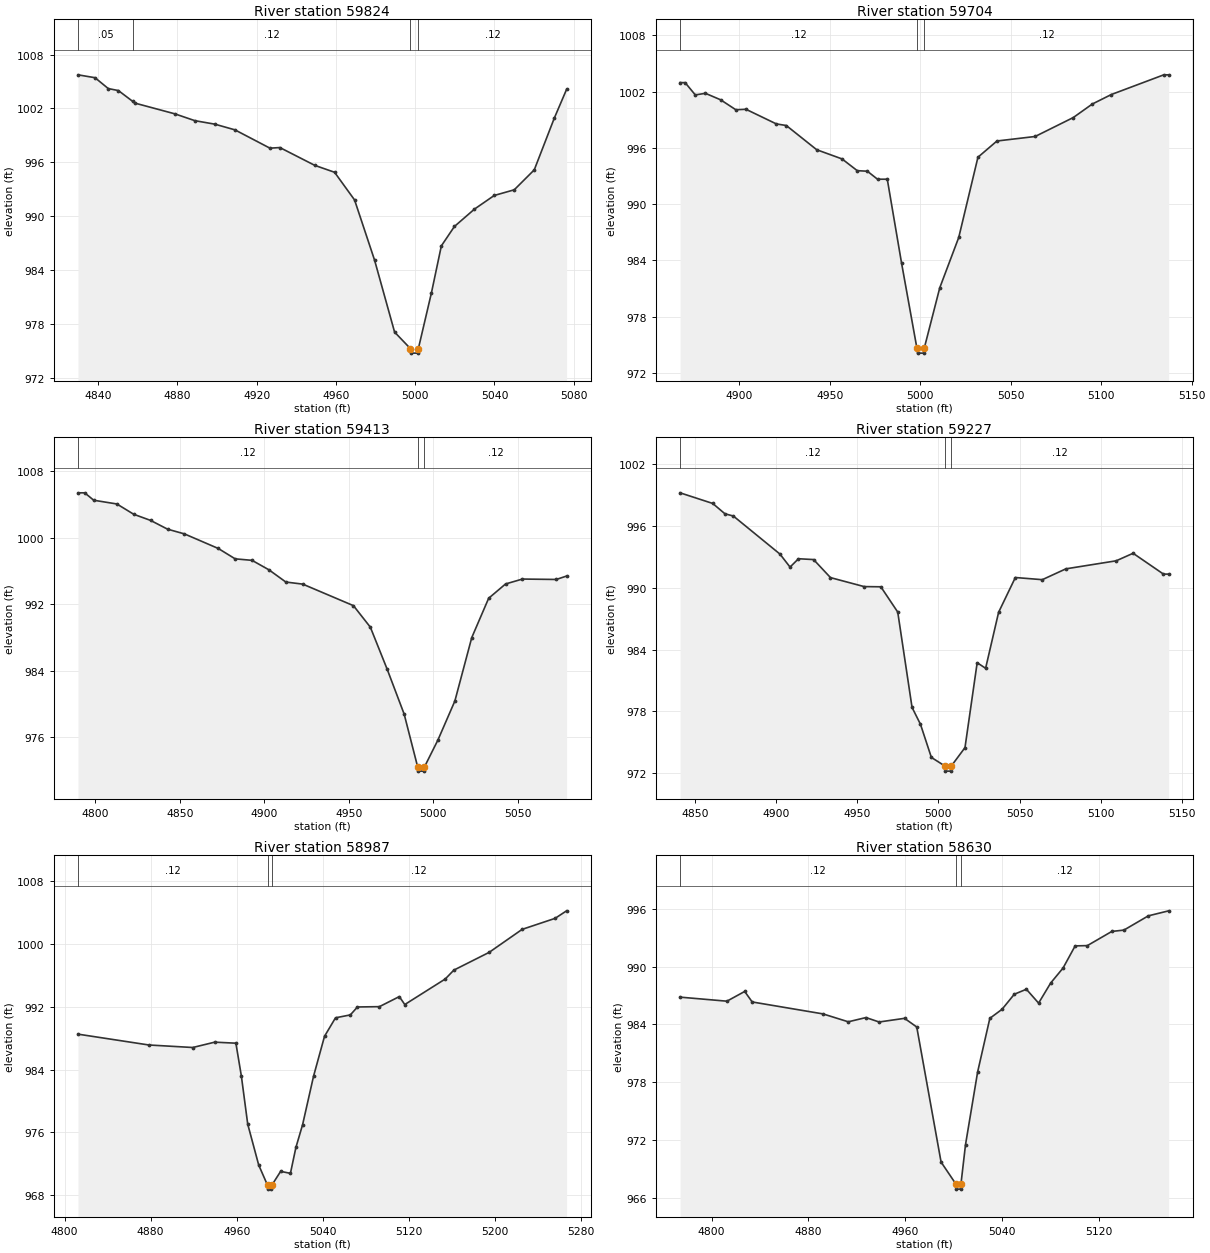
Type RM Length L Ch R = 1,59824,120,120,120
BEGIN DESCRIPTION:
Mapping XS e55607a7
END DESCRIPTION:
XS GIS Cut Line= 2
      2240401.94      7174378.58      2240431.85      7174133.80
#Sta/Elev= 30
  4829.8 1005.74  4838.4 1005.42  4845.1 1004.21  4850.2 1003.99  4857.4 1002.79
  4858.6 1002.59  4878.7 1001.40  4888.8 1000.64  4898.9 1000.25  4909.0  999.62
  4926.7  997.58  4931.7  997.65  4949.3  995.67  4959.3  994.90  4969.4  991.82
  4979.5  985.12  4989.6  977.12  4997.6  975.28  4997.9  974.78  5001.4  974.78
  5001.6  975.28  5008.2  981.49  5013.2  986.71  5019.8  988.87  5029.9  990.80
  5039.9  992.32  5050.0  992.95  5060.1  995.17  5070.2 1000.92  5076.4 1004.12
#Mann=4,-1,0
  4829.8    0.05       0  4857.4    0.12       0  4997.6    0.07       0
  5001.6    0.12       0
Bank Sta=4997.6,5001.6
Exp/Cntr=0.3,0.1

Type RM Length L Ch R = 1,59704,291,291,291
BEGIN DESCRIPTION:
Black Creek 93.0
END DESCRIPTION:
XS GIS Cut Line= 3
      2240478.98      7174360.04      2240529.00      7174260.00
      2240579.01      7174109.96
#Sta/Elev= 30
  4867.3 1002.95  4870.1 1002.95  4875.7 1001.64  4881.3 1001.81  4889.7 1001.12
  4898.1 1000.06  4903.7 1000.11  4920.5  998.55  4926.0  998.38  4942.8  995.80
  4956.8  994.82  4965.2  993.57  4970.8  993.51  4976.4  992.66  4981.8  992.66
  4989.7  983.71  4998.2  974.63  4998.5  974.13  5002.0  974.13  5002.2  974.63
  5010.8  981.09  5021.3  986.46  5031.9  995.00  5042.4  996.73  5063.5  997.21
  5084.6  999.23  5095.1 1000.67  5105.6 1001.68  5134.6 1003.78  5137.3 1003.78
#Mann=3,-1,0
  4867.3    0.12       0  4998.2    0.07       0  5002.2    0.12       0
Bank Sta=4998.2,5002.2
Exp/Cntr=0.3,0.1

Type RM Length L Ch R = 1,59413,186,186,186
BEGIN DESCRIPTION:
Mapping XS 6b133f0f
END DESCRIPTION:
XS GIS Cut Line= 2
      2240763.84      7174473.01      2240768.11      7174183.94
#Sta/Elev= 30
  4789.7 1005.39  4793.7 1005.39  4799.0 1004.50  4812.7 1004.05  4822.7 1002.81
  4832.7 1002.07  4842.7 1001.02  4852.7 1000.45  4872.7  998.70  4882.7  997.45
  4892.7  997.27  4902.7  996.13  4912.7  994.66  4922.7  994.41  4952.7  991.82
  4962.7  989.23  4972.7  984.15  4982.7  978.78  4990.7  972.42  4991.0  971.92
  4994.5  971.92  4994.7  972.42  5002.7  975.67  5012.7  980.35  5022.7  987.98
  5032.7  992.71  5042.7  994.43  5052.7  995.02  5072.7  994.97  5078.8  995.38
#Mann=3,-1,0
  4789.7    0.12       0  4990.7    0.07       0  4994.7    0.12       0
Bank Sta=4990.7,4994.7
Exp/Cntr=0.3,0.1

Type RM Length L Ch R = 1,59227,240,240,240
BEGIN DESCRIPTION:
Mapping XS ec418358
END DESCRIPTION:
XS GIS Cut Line= 2
      2240971.71      7174379.45      2240894.26      7174088.80
#Sta/Elev= 30
  4841.0  999.19  4861.1  998.16  4868.6  997.16  4873.8  996.94  4902.5  993.25
  4908.7  991.99  4913.9  992.80  4923.2  992.72  4933.6  990.97  4954.3  990.10
  4964.6  990.08  4975.0  987.63  4983.8  978.39  4989.0  976.75  4995.7  973.54
  5004.0  972.71  5004.3  972.21  5007.8  972.21  5008.0  972.71  5016.4  974.49
  5023.9  982.72  5029.1  982.18  5037.1  987.61  5047.4  990.98  5064.0  990.77
  5078.5  991.82  5109.5  992.60  5119.9  993.33  5138.6  991.31  5141.8  991.31
#Mann=3,-1,0
  4841.0    0.12       0  5004.0    0.07       0  5008.0    0.12       0
Bank Sta=5004,5008
Exp/Cntr=0.3,0.1

Type RM Length L Ch R = 1,58987,357,357,357
BEGIN DESCRIPTION:
Mapping XS 36d4fc64
END DESCRIPTION:
XS GIS Cut Line= 2
      2241174.08      7174294.60      2241083.72      7173849.48
#Sta/Elev= 30
  4812.5  988.52  4878.4  987.14  4919.2  986.82  4939.6  987.50  4959.3  987.37
  4964.4  983.18  4970.3  977.06  4980.5  971.86  4988.7  969.29  4988.9  968.79
  4992.4  968.79  4992.7  969.29  5000.9  971.05  5010.0  970.80  5015.1  974.10
  5021.3  976.99  5031.5  983.17  5041.7  988.25  5051.9  990.60  5065.7  990.97
  5072.3  991.98  5092.7  992.02  5111.2  993.30  5116.3  992.29  5153.9  995.54
  5161.9  996.67  5194.7  998.93  5225.4 1001.86  5256.0 1003.26  5266.7 1004.22
#Mann=3,-1,0
  4812.5    0.12       0  4988.7    0.07       0  4992.7    0.12       0
Bank Sta=4988.7,4992.7
Exp/Cntr=0.3,0.1

Type RM Length L Ch R = 1,58630,223,223,223
BEGIN DESCRIPTION:
Mapping XS f5822515
END DESCRIPTION:
XS GIS Cut Line= 3
      2241312.76      7174217.92      2241446.24      7174119.47
      2241475.31      7173883.31
#Sta/Elev= 30
  4774.0  986.82  4812.7  986.40  4827.4  987.41  4833.6  986.32  4892.1  985.08
  4913.0  984.26  4927.6  984.70  4938.5  984.24  4959.5  984.62  4969.6  983.72
  4989.7  969.70  5002.1  967.39  5002.3  966.89  5005.8  966.89  5006.1  967.39
  5009.9  971.51  5019.9  979.05  5030.0  984.62  5040.1  985.56  5050.2  987.12
  5060.2  987.64  5070.3  986.20  5080.3  988.29  5090.5  989.84  5100.5  992.14
  5110.6  992.17  5130.8  993.64  5140.8  993.78  5161.0  995.26  5177.8  995.78
#Mann=3,-1,0
  4774.0    0.12       0  5002.1    0.07       0  5006.1    0.12       0
Bank Sta=5002.1,5006.1
Exp/Cntr=0.3,0.1

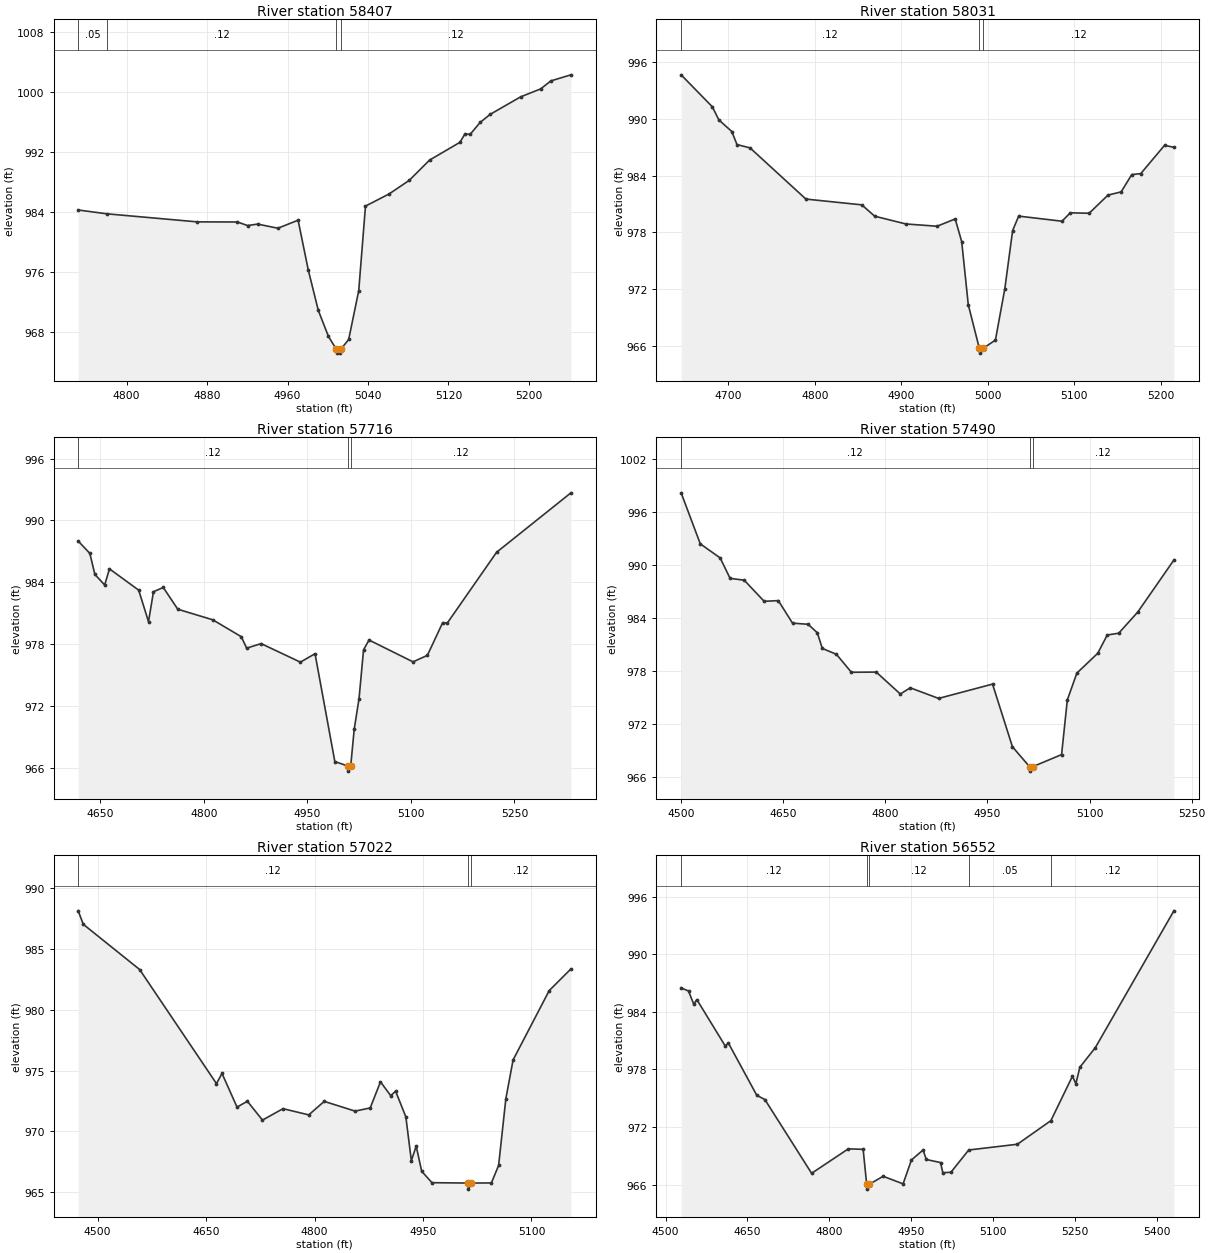
Type RM Length L Ch R = 1,58407,376,376,376
BEGIN DESCRIPTION:
Mapping XS 5e1fc7cf
END DESCRIPTION:
XS GIS Cut Line= 2
      2241673.53      7174307.55      2241623.18      7173820.15
#Sta/Elev= 30
  4751.8  984.33  4780.4  983.82  4870.0  982.75  4910.2  982.73  4920.2  982.26
  4930.3  982.45  4950.4  981.90  4970.5  982.97  4980.6  976.34  4990.6  970.94
  5000.7  967.47  5008.6  965.75  5008.9  965.25  5012.5  965.25  5012.9  965.75
  5020.8  967.07  5030.8  973.59  5037.5  984.85  5061.0  986.47  5081.1  988.29
  5101.2  990.98  5131.4  993.35  5136.5  994.49  5141.5  994.40  5151.5  996.00
  5161.5  997.08  5191.7  999.41  5211.8 1000.48  5221.8 1001.54  5241.8 1002.35
#Mann=4,-1,0
  4751.8    0.05       0  4780.4    0.12       0  5008.6    0.07       0
  5012.9    0.12       0
Bank Sta=5008.6,5012.9
Exp/Cntr=0.3,0.1

Type RM Length L Ch R = 1,58031,315,315,315
BEGIN DESCRIPTION:
Black Creek 89.0
END DESCRIPTION:
XS GIS Cut Line= 3
      2242179.03      7174210.04      2241979.00      7173910.00
      2241878.23      7173726.56
#Sta/Elev= 30
  4645.3  994.65  4681.4  991.27  4688.9  989.89  4703.9  988.66  4709.9  987.28
  4725.0  986.93  4789.6  981.52  4854.2  980.91  4869.2  979.71  4905.2  978.89
  4941.3  978.65  4962.3  979.42  4969.8  977.02  4977.4  970.36  4990.2  965.74
  4990.6  965.24  4994.6  965.74  5008.8  966.62  5019.7  972.06  5028.7  978.19
  5035.7  979.72  5085.8  979.18  5095.4  980.07  5117.2  980.02  5139.0  981.94
  5154.2  982.28  5166.5  984.11  5176.9  984.21  5204.4  987.20  5215.2  986.99
#Mann=3,-1,0
  4645.3    0.12       0  4990.2    0.07       0  4994.6    0.12       0
Bank Sta=4990.2,4994.6
Exp/Cntr=0.3,0.1

Type RM Length L Ch R = 1,57716,226,226,226
BEGIN DESCRIPTION:
Mapping XS d4f49638
END DESCRIPTION:
XS GIS Cut Line= 3
      2242460.74      7174012.43      2242321.85      7173880.31
      2241988.45      7173478.26
#Sta/Elev= 30
  4617.8  988.00  4634.7  986.80  4642.0  984.76  4656.2  983.73  4663.1  985.30
  4705.5  983.23  4719.7  980.17  4726.9  983.08  4741.1  983.49  4762.1  981.38
  4812.9  980.35  4854.2  978.71  4861.9  977.60  4882.9  978.04  4939.8  976.24
  4961.0  977.06  4989.7  966.59  5008.3  966.16  5008.7  965.66  5012.7  966.16
  5017.8  969.74  5024.8  972.71  5031.3  977.43  5039.2  978.39  5103.0  976.27
  5123.8  976.90  5146.0  980.08  5152.5  980.02  5224.1  986.91  5331.8  992.68
#Mann=3,-1,0
  4617.8    0.12       0  5008.3    0.07       0  5012.7    0.12       0
Bank Sta=5008.3,5012.7
Exp/Cntr=0.3,0.1

Type RM Length L Ch R = 1,57490,468,468,468
BEGIN DESCRIPTION:
Black Creek 88.0
END DESCRIPTION:
XS GIS Cut Line= 3
      2242629.01      7173960.01      2242329.00      7173560.00
      2242229.01      7173360.02
#Sta/Elev= 30
  4500.2  998.18  4528.3  992.41  4557.5  990.81  4572.1  988.50  4592.9  988.29
  4622.1  985.90  4642.9  985.98  4663.8  983.43  4686.7  983.30  4700.2  982.34
  4707.5  980.57  4728.3  979.90  4750.2  977.87  4786.7  977.89  4822.1  975.41
  4836.7  976.11  4878.3  974.91  4957.5  976.53  4986.7  969.44  5011.9  967.18
  5012.4  966.68  5016.4  967.18  5058.9  968.55  5067.3  974.73  5081.3  977.77
  5112.0  980.02  5126.0  982.09  5142.8  982.29  5170.7  984.68  5223.8  990.57
#Mann=3,-1,0
  4500.2    0.12       0  5011.9    0.07       0  5016.4    0.12       0
Bank Sta=5011.9,5016.4
Exp/Cntr=0.3,0.1

Type RM Length L Ch R = 1,57022,470,470,470
BEGIN DESCRIPTION:
Black Creek 87.0
END DESCRIPTION:
XS GIS Cut Line= 3
      2242929.01      7173510.01      2242529.00      7173160.00
      2242379.02      7173160.00
#Sta/Elev= 30
  4473.1  988.15  4480.2  987.04  4558.1  983.32  4664.4  973.93  4672.0  974.77
  4692.8  972.00  4707.1  972.48  4728.0  970.93  4756.4  971.87  4792.0  971.36
  4813.4  972.47  4856.1  971.67  4877.0  971.93  4891.2  974.08  4905.4  972.94
  4912.1  973.31  4926.3  971.20  4933.9  967.59  4940.6  968.79  4948.2  966.72
  4962.4  965.78  5012.4  965.75  5012.8  965.25  5016.9  965.75  5044.6  965.76
  5054.6  967.20  5064.6  972.69  5074.6  975.88  5124.6  981.59  5154.6  983.37
#Mann=3,-1,0
  4473.1    0.12       0  5012.4    0.07       0  5016.9    0.12       0
Bank Sta=5012.4,5016.9
Exp/Cntr=0.3,0.1

Type RM Length L Ch R = 1,56552,809,809,809
BEGIN DESCRIPTION:
Black Creek 86.0
END DESCRIPTION:
XS GIS Cut Line= 3
      2243128.98      7173259.96      2242879.00      7172860.00
      2242628.98      7172509.98
#Sta/Elev= 30
  4528.6  986.50  4542.1  986.18  4551.6  984.82  4557.4  985.28  4609.3  980.45
  4615.2  980.74  4667.1  975.30  4681.9  974.86  4767.4  967.17  4834.6  969.72
  4861.7  969.67  4868.2  966.02  4868.7  965.52  4872.8  966.02  4898.3  966.86
  4934.8  966.07  4950.1  968.56  4971.4  969.60  4977.3  968.61  5003.3  968.29
  5007.6  967.23  5022.4  967.28  5054.9  969.60  5144.0  970.20  5205.3  972.66
  5244.8  977.30  5251.0  976.51  5258.3  978.23  5286.6  980.27  5430.4  994.54
#Mann=5,-1,0
  4528.6    0.12       0  4868.2    0.07       0  4872.8    0.12       0
  5054.9    0.05       0  5205.3    0.12       0
Bank Sta=4868.2,4872.8
Exp/Cntr=0.3,0.1

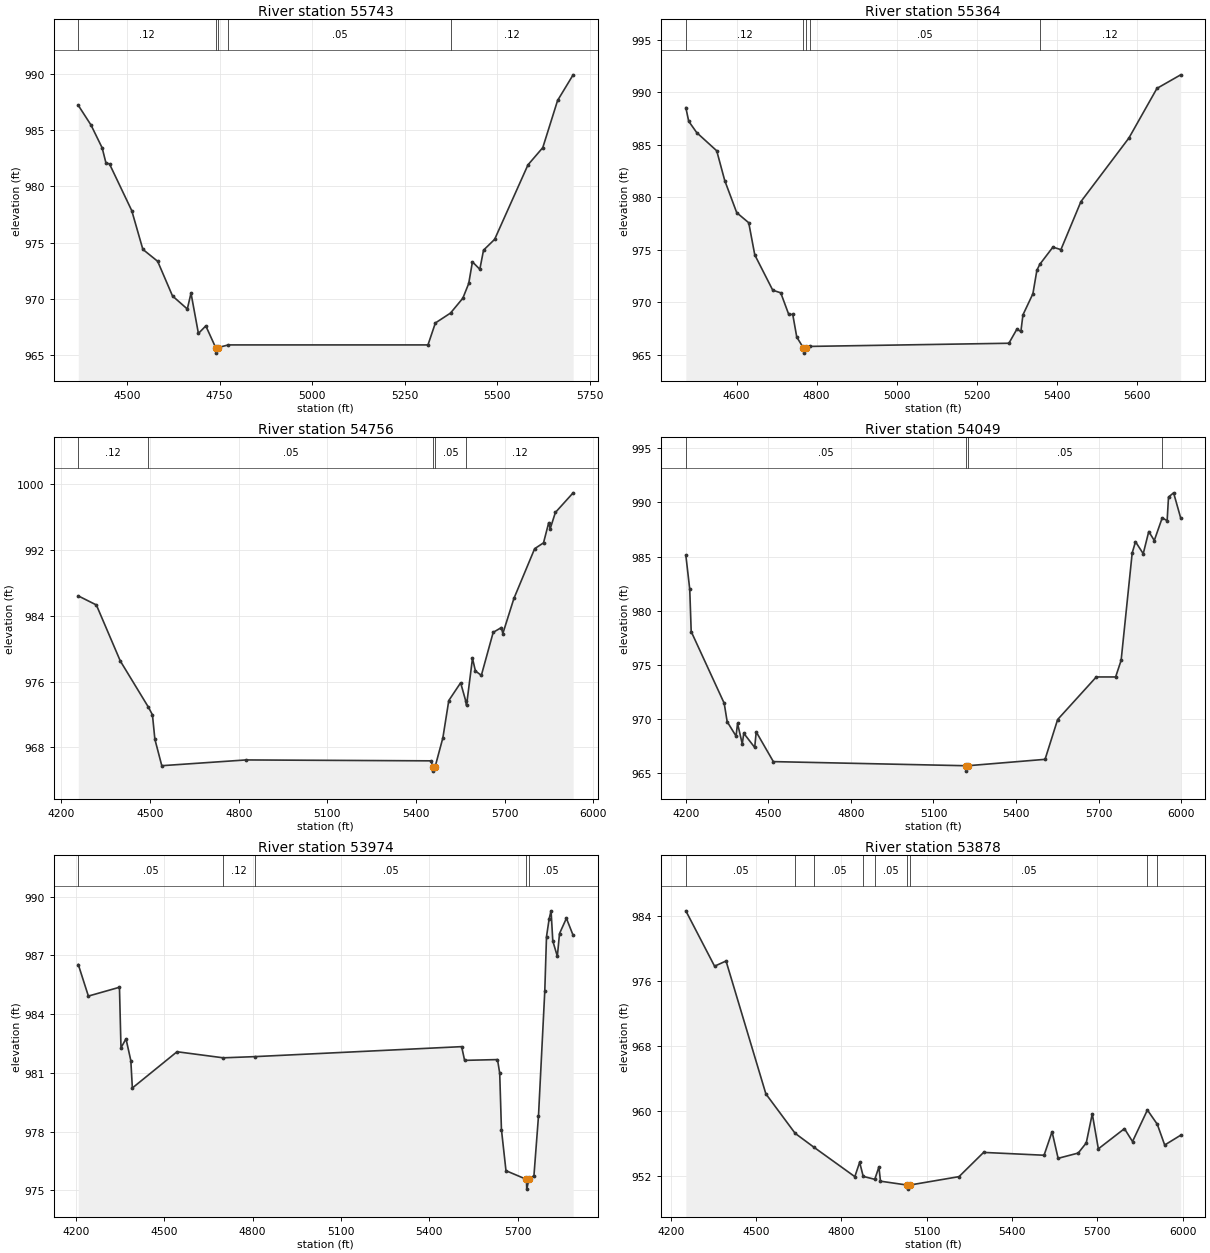
Type RM Length L Ch R = 1,55743,379,379,379
BEGIN DESCRIPTION:
Mapping XS 9fca779c
END DESCRIPTION:
XS GIS Cut Line= 2
      2243430.28      7173314.43      2243473.71      7171978.04
#Sta/Elev= 30
  4368.2  987.21  4402.7  985.45  4432.7  983.43  4442.7  982.12  4452.7  981.99
  4512.7  977.85  4542.7  974.41  4582.7  973.35  4622.8  970.27  4662.8  969.11
  4672.8  970.52  4692.8  966.94  4712.8  967.61  4739.3  965.69  4740.4  965.19
  4746.4  965.69  4773.7  965.92  5313.1  965.92  5333.1  967.87  5374.0  968.75
  5407.3  970.07  5423.2  971.38  5433.2  973.30  5453.2  972.64  5463.2  974.34
  5493.2  975.30  5583.3  981.92  5623.3  983.45  5663.3  987.64  5705.3  989.92
#Mann=5,-1,0
  4368.2    0.12       0  4739.3   0.033       0  4746.4    0.12       0
  4773.7    0.05       0  5374.0    0.12       0
Bank Sta=4739.3,4746.4
Exp/Cntr=0.3,0.1

Type RM Length L Ch R = 1,55364,608,608,608
BEGIN DESCRIPTION:
Mapping XS c985c7bd
END DESCRIPTION:
XS GIS Cut Line= 2
      2243796.57      7173307.20      2243778.12      7172070.73
#Sta/Elev= 30
  4473.0  988.52  4480.2  987.22  4500.2  986.14  4550.2  984.41  4570.2  981.58
  4600.2  978.52  4630.2  977.56  4645.3  974.50  4690.2  971.14  4710.2  970.89
  4730.2  968.83  4740.2  968.83  4750.2  966.68  4766.7  965.65  4767.8  965.15
  4773.8  965.65  4783.7  965.79  5280.3  966.09  5300.3  967.43  5310.3  967.21
  5315.4  968.79  5340.3  970.80  5350.3  973.04  5357.5  973.60  5390.3  975.24
  5410.3  975.00  5460.3  979.57  5580.3  985.63  5650.3  990.35  5709.6  991.64
#Mann=5,-1,0
  4473.0    0.12       0  4766.7   0.033       0  4773.8    0.12       0
  4783.7    0.05       0  5357.5    0.12       0
Bank Sta=4766.7,4773.8
Exp/Cntr=0.3,0.1

Type RM Length L Ch R = 1,54756,707,707,707
BEGIN DESCRIPTION:
Black Creek 82.0
END DESCRIPTION:
XS GIS Cut Line= 3
      2244079.02      7173309.96      2244429.00      7172510.00
      2244379.00      7171710.03
#Sta/Elev= 30
  4257.1  986.42  4318.3  985.32  4399.3  978.51  4494.5  972.89  4508.1  971.96
  4516.3  969.00  4539.7  965.78  4824.6  966.48  5450.9  966.37  5457.3  965.62
  5458.4  965.12  5464.5  965.62  5491.0  969.17  5511.0  973.70  5551.1  975.86
  5568.1  973.68  5571.1  973.11  5591.2  978.83  5601.2  977.29  5621.2  976.76
  5661.3  981.99  5688.9  982.57  5693.9  981.84  5731.4  986.11  5801.6  992.16
  5831.6  992.87  5849.2  995.32  5854.2  994.58  5871.7  996.56  5931.8  998.95
#Mann=5,-1,0
  4257.1    0.12       0  4494.5    0.05       0  5457.3   0.033       0
  5464.5    0.05       0  5568.1    0.12       0
Bank Sta=5457.3,5464.5
Exp/Cntr=0.3,0.1

Type RM Length L Ch R = 1,54049,75,75,75
BEGIN DESCRIPTION:
Mapping XS 91f56b85
END DESCRIPTION:
XS GIS Cut Line= 5
      2244849.78      7173325.04      2244800.37      7173180.71
      2245145.57      7172466.33      2245286.77      7172135.57
      2245327.98      7171644.40
#Sta/Elev= 30
  4200.0  985.12  4214.2  981.98  4219.5  978.06  4339.4  971.43  4350.3  969.72
  4382.5  968.39  4388.0  969.56  4405.1  967.67  4410.6  968.65  4450.3  967.34
  4455.8  968.78  4518.1  966.03  5216.7  965.65  5217.9  965.15  5225.2  965.65
  5505.6  966.24  5551.3  969.92  5691.8  973.86  5762.1  973.86  5782.1  975.40
  5822.3  985.33  5834.3  986.37  5862.4  985.26  5882.5  987.31  5902.6  986.48
  5931.5  988.58  5949.3  988.31  5954.3  990.50  5972.8  990.89  5998.5  988.57
#Mann=4,-1,0
  4200.0    0.05       0  5216.7   0.033       0  5225.2    0.05       0
  5931.5    0.12       0
Bank Sta=5216.7,5225.2
Exp/Cntr=0.3,0.1

Type RM Length L Ch R = 1,53974,96,96,96
BEGIN DESCRIPTION:
Mapping XS a8c36036
END DESCRIPTION:
XS GIS Cut Line= 5
      2244974.40      7173335.43      2244915.72      7173135.28
      2245080.56      7172774.54      2245402.41      7172057.63
      2245552.63      7171810.54
#Sta/Elev= 30
  4208.0  986.53  4242.3  984.92  4347.8  985.37  4353.0  982.28  4370.0  982.74
  4386.4  981.63  4391.6  980.23  4543.3  982.08  4700.2  981.77  4806.5  981.83
  5509.7  982.34  5519.7  981.64  5631.4  981.68  5638.9  980.99  5644.8  978.11
  5660.2  976.01  5729.6  975.57  5730.8  975.07  5738.1  975.57  5755.2  975.76
  5770.6  978.80  5792.0  985.18  5797.8  987.95  5806.9  988.87  5813.3  989.27
  5819.2  987.73  5834.6  986.95  5842.0  988.11  5865.4  988.89  5888.2  988.02
#Mann=5,-1,0
  4208.0    0.05       0  4700.2    0.12       0  4806.5    0.05       0
  5729.6   0.033       0  5738.1    0.05       0
Bank Sta=5729.6,5738.1
Exp/Cntr=0.3,0.1

Type RM Length L Ch R = 1,53878,430,430,430
BEGIN DESCRIPTION:
Mapping XS 1d369abd
END DESCRIPTION:
XS GIS Cut Line= 5
      2245013.59      7173310.20      2245051.10      7173027.33
      2245380.40      7172349.96      2245524.40      7172372.09
      2245924.61      7171986.15
#Sta/Elev= 30
  4253.1  984.67  4354.2  977.84  4394.5  978.48  4534.6  962.09  4637.6  957.22
  4702.7  955.53  4847.4  951.88  4864.4  953.65  4876.9  951.91  4917.6  951.55
  4932.1  953.08  4937.6  951.32  5031.6  950.84  5032.8  950.34  5040.1  950.84
  5213.8  951.88  5300.3  954.87  5512.9  954.52  5541.0  957.42  5562.3  954.14
  5633.0  954.79  5661.3  956.04  5682.4  959.63  5703.8  955.31  5795.6  957.80
  5823.9  956.21  5876.3  960.10  5911.1  958.34  5937.1  955.78  5993.3  956.99
#Mann=9,-1,0
  4253.1    0.05       0  4637.6    0.12       0  4702.7    0.05       0
  4876.9    0.12       0  4917.6    0.05       0  5031.6   0.033       0
  5040.1    0.05       0  5876.3    0.12       0  5911.1    0.05       0
Bank Sta=5031.6,5040.1
Exp/Cntr=0.3,0.1

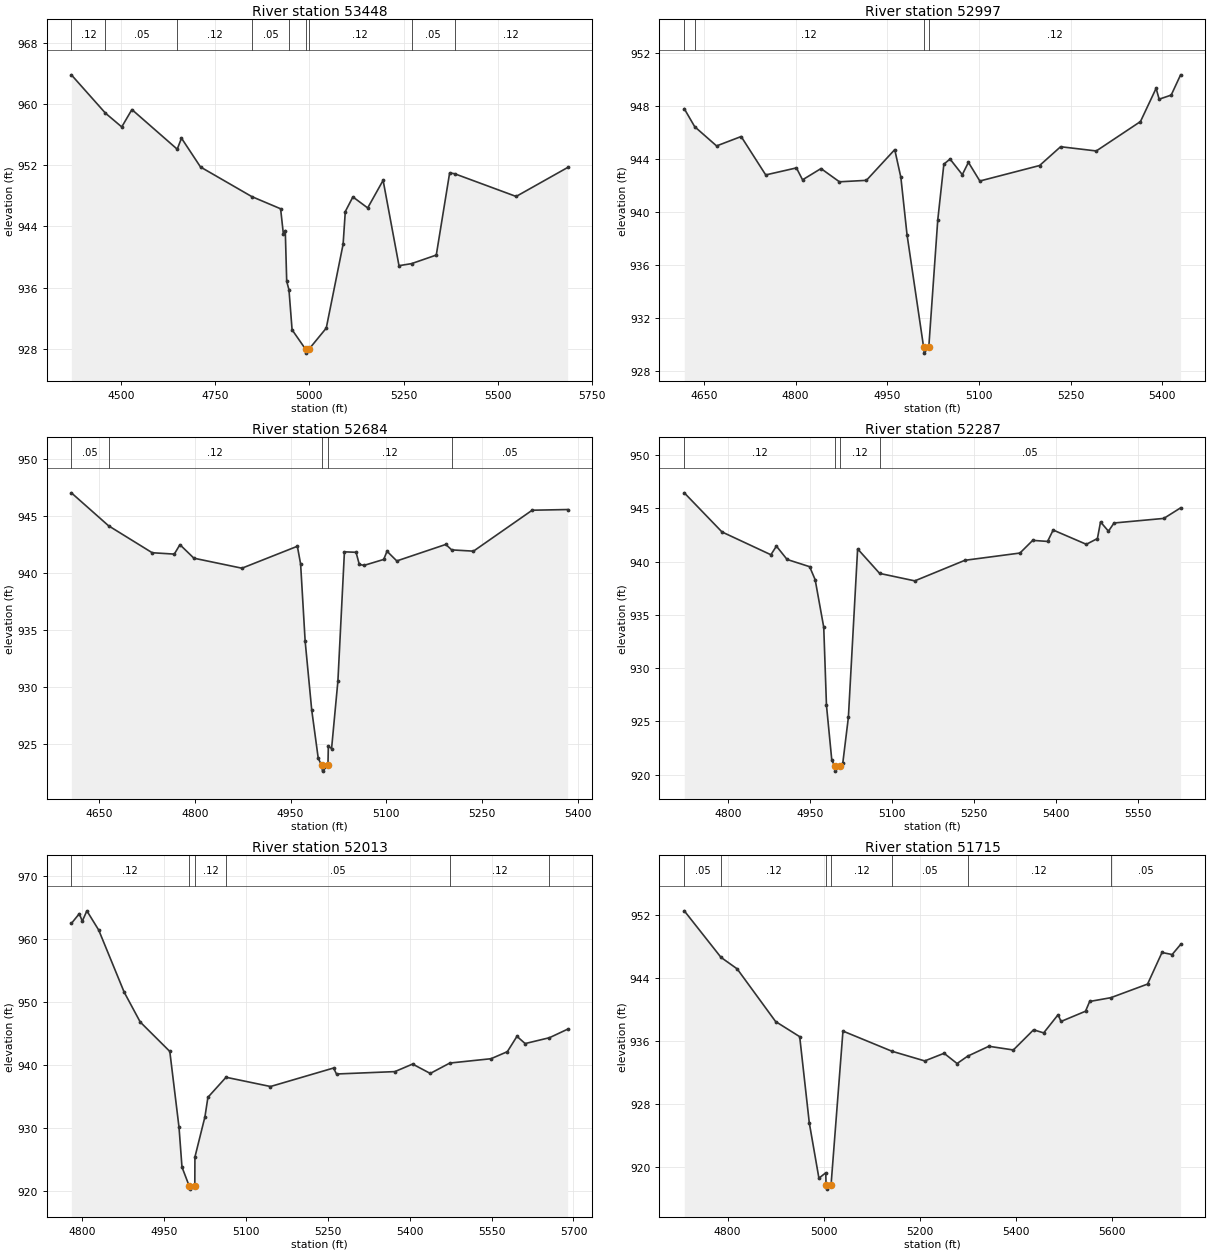
Type RM Length L Ch R = 1,53448,451,451,451
BEGIN DESCRIPTION:
Mapping XS 88a67692
END DESCRIPTION:
XS GIS Cut Line= 4
      2245592.65      7173268.83      2245685.22      7172703.14
      2245653.96      7172486.97      2246019.71      7172107.05
#Sta/Elev= 30
  4367.3  963.82  4457.9  958.81  4501.2  957.01  4528.2  959.28  4648.6  954.10
  4660.0  955.54  4710.6  951.77  4846.9  947.90  4923.4  946.31  4930.7  943.03
  4935.8  943.46  4939.6  936.83  4945.6  935.72  4953.9  930.49  4989.9  927.94
  4991.2  927.44  4998.5  927.94  5044.7  930.71  5089.5  941.68  5095.3  945.95
  5115.5  947.86  5154.8  946.42  5195.8  950.03  5238.0  938.87  5271.4  939.14
  5337.1  940.26  5372.6  951.00  5385.9  950.89  5549.3  947.92  5686.3  951.71
#Mann=9,-1,0
  4367.3    0.12       0  4457.9    0.05       0  4648.6    0.12       0
  4846.9    0.05       0  4945.6    0.12       0  4989.9    0.07       0
  4998.5    0.12       0  5271.4    0.05       0  5385.9    0.12       0
Bank Sta=4989.9,4998.5
Exp/Cntr=0.3,0.1

Type RM Length L Ch R = 1,52997,313,313,313
BEGIN DESCRIPTION:
Mapping XS b73f35e0
END DESCRIPTION:
XS GIS Cut Line= 2
      2246155.22      7172922.56      2246069.83      7172114.66
#Sta/Elev= 30
  4617.8  947.81  4634.9  946.45  4670.7  945.00  4710.9  945.71  4751.1  942.81
  4801.4  943.34  4811.4  942.44  4841.6  943.29  4871.8  942.29  4915.9  942.40
  4962.3  944.72  4972.3  942.63  4982.4  938.30  5009.4  929.85  5010.7  929.35
  5018.1  929.85  5032.7  939.40  5042.7  943.62  5052.8  944.01  5072.9  942.83
  5082.9  943.76  5101.6  942.35  5199.4  943.52  5233.8  944.94  5292.2  944.62
  5364.5  946.84  5390.1  949.35  5395.1  948.53  5414.8  948.84  5430.2  950.37
#Mann=4,-1,0
  4617.8    0.05       0  4634.9    0.12       0  5009.4    0.07       0
  5018.1    0.12       0
Bank Sta=5009.4,5018.1
Exp/Cntr=0.3,0.1

Type RM Length L Ch R = 1,52684,397,397,397
BEGIN DESCRIPTION:
Mapping XS 82f038de
END DESCRIPTION:
XS GIS Cut Line= 2
      2246336.07      7172967.30      2246505.72      7172208.84
#Sta/Elev= 30
  4606.7  947.06  4665.0  944.16  4733.3  941.79  4767.9  941.67  4776.7  942.50
  4798.6  941.31  4873.8  940.43  4960.6  942.36  4965.7  940.80  4972.8  934.01
  4983.1  927.95  4993.3  923.71  4998.6  923.08  5000.0  922.58  5008.5  923.08
  5009.1  924.76  5014.2  924.57  5024.1  930.51  5034.3  941.87  5052.5  941.83
  5057.6  940.76  5065.1  940.68  5095.8  941.20  5101.0  941.92  5116.3  941.07
  5193.0  942.52  5202.3  942.04  5236.4  941.93  5328.3  945.53  5383.9  945.59
#Mann=5,-1,0
  4606.7    0.05       0  4665.0    0.12       0  4998.6    0.07       0
  5008.5    0.12       0  5202.3    0.05       0
Bank Sta=4998.6,5008.5
Exp/Cntr=0.3,0.1

Type RM Length L Ch R = 1,52287,274,274,274
BEGIN DESCRIPTION:
Mapping XS a94fdf1b
END DESCRIPTION:
XS GIS Cut Line= 2
      2246814.36      7172886.50      2246670.98      7171989.68
#Sta/Elev= 30
  4719.6  946.45  4788.6  942.78  4878.1  940.64  4888.2  941.45  4907.7  940.20
  4949.0  939.52  4959.1  938.30  4974.8  933.84  4979.8  926.51  4989.5  921.39
  4994.5  920.84  4995.9  920.34  5004.8  920.84  5009.7  921.11  5019.9  925.39
  5036.8  941.19  5077.1  938.89  5141.4  938.19  5233.1  940.12  5333.8  940.80
  5357.2  941.99  5384.4  941.89  5394.6  942.96  5455.3  941.62  5475.6  942.16
  5481.3  943.72  5495.8  942.85  5506.0  943.62  5597.1  944.05  5627.8  945.04
#Mann=4,-1,0
  4719.6    0.12       0  4994.5    0.07       0  5004.8    0.12       0
  5077.1    0.05       0
Bank Sta=4994.5,5004.8
Exp/Cntr=0.3,0.1

Type RM Length L Ch R = 1,52013,298,298,298
BEGIN DESCRIPTION:
Mapping XS e45ca06b
END DESCRIPTION:
XS GIS Cut Line= 2
      2247100.60      7172726.21      2246748.51      7171888.17
#Sta/Elev= 30
  4780.4  962.52  4795.0  964.08  4800.4  962.88  4808.8  964.53  4830.5  961.47
  4877.1  951.60  4906.5  946.85  4960.7  942.17  4977.6  930.08  4983.0  923.78
  4996.2  920.77  4997.6  920.27  5006.5  920.77  5006.7  925.37  5025.1  931.79
  5030.5  934.87  5063.7  938.06  5145.1  936.59  5260.6  939.53  5266.0  938.58
  5372.9  938.96  5405.4  940.16  5437.7  938.67  5473.5  940.32  5549.0  941.01
  5578.9  942.13  5596.5  944.57  5611.5  943.42  5656.0  944.35  5689.4  945.71
#Mann=6,-1,0
  4780.4    0.12       0  4996.2    0.07       0  5006.5    0.12       0
  5063.7    0.05       0  5473.5    0.12       0  5656.0    0.05       0
Bank Sta=4996.2,5006.5
Exp/Cntr=0.3,0.1

Type RM Length L Ch R = 1,51715,153,153,153
BEGIN DESCRIPTION:
Mapping XS e0b20710
END DESCRIPTION:
XS GIS Cut Line= 3
      2247263.60      7172699.91      2247282.36      7172170.75
      2247002.58      7171752.74
#Sta/Elev= 30
  4709.8  952.47  4786.2  946.56  4819.8  945.10  4899.8  938.41  4949.9  936.49
  4969.9  925.53  4989.9  918.52  5004.1  919.20  5004.8  917.63  5006.2  917.13
  5015.1  917.63  5039.9  937.20  5141.8  934.64  5210.0  933.41  5250.3  934.38
  5277.3  933.08  5299.2  934.01  5343.4  935.27  5394.4  934.80  5436.4  937.36
  5457.5  936.97  5487.5  939.28  5493.5  938.42  5544.5  939.72  5553.1  940.96
  5597.2  941.44  5673.6  943.17  5703.6  947.18  5724.7  946.92  5742.3  948.20
#Mann=7,-1,0
  4709.8    0.05       0  4786.2    0.12       0  5004.8    0.07       0
  5015.1    0.12       0  5141.8    0.05       0  5299.2    0.12       0
  5597.2    0.05       0
Bank Sta=5004.8,5015.1
Exp/Cntr=0.3,0.1