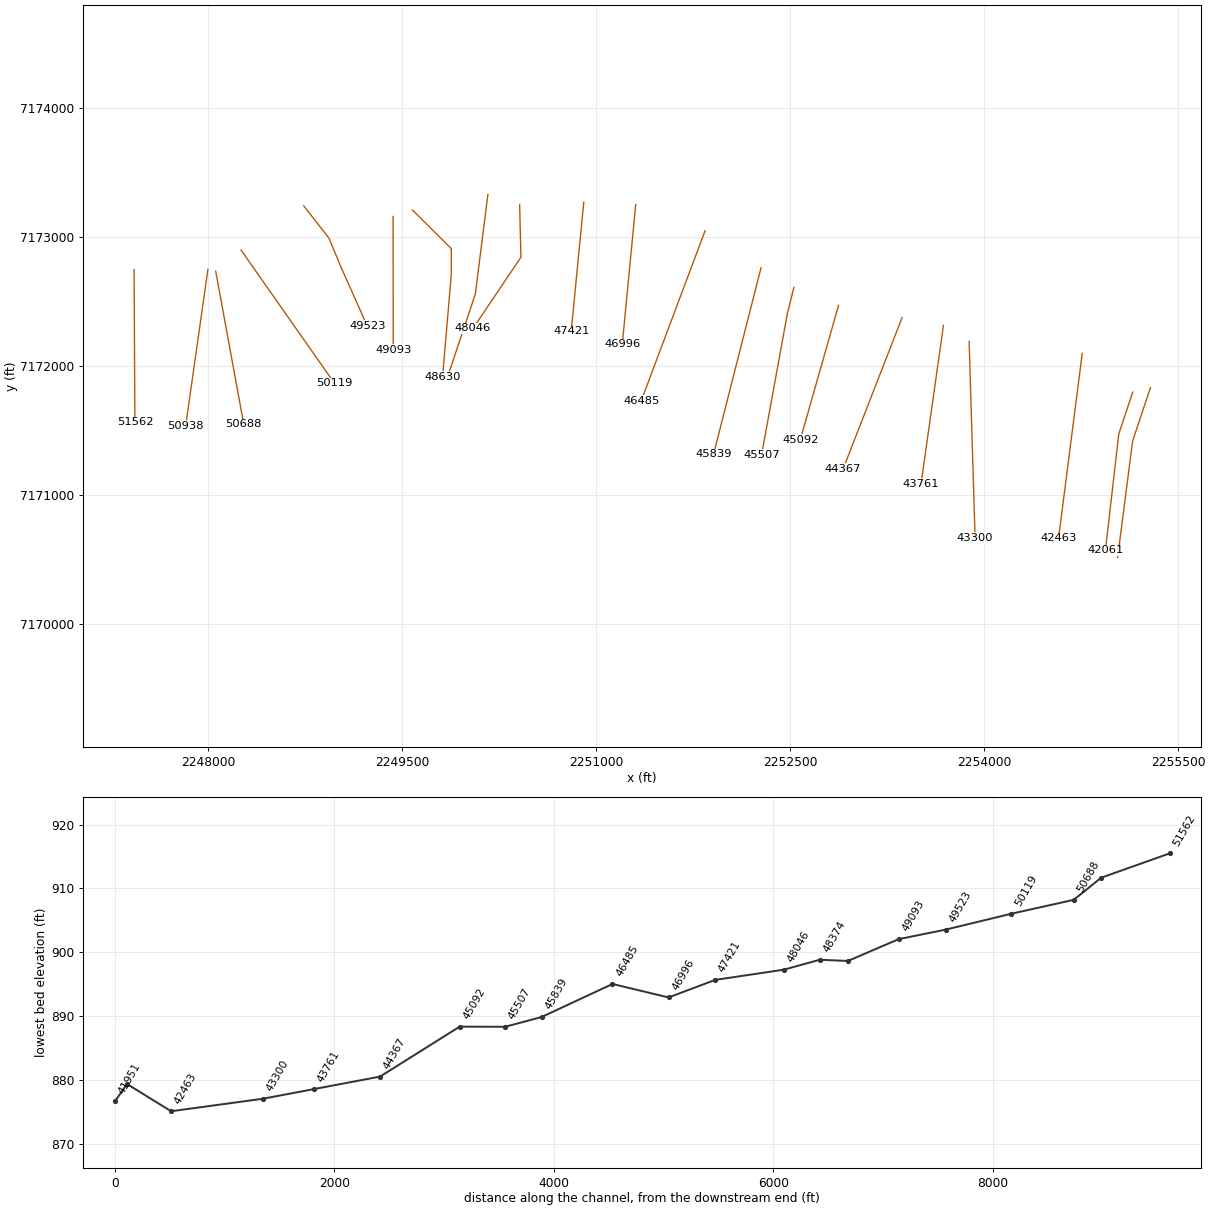
HEC-RAS study Black Creek.prj: Black Creek Base Level Engineering

--- Black Creek.g01 (geometry) --- (continued)

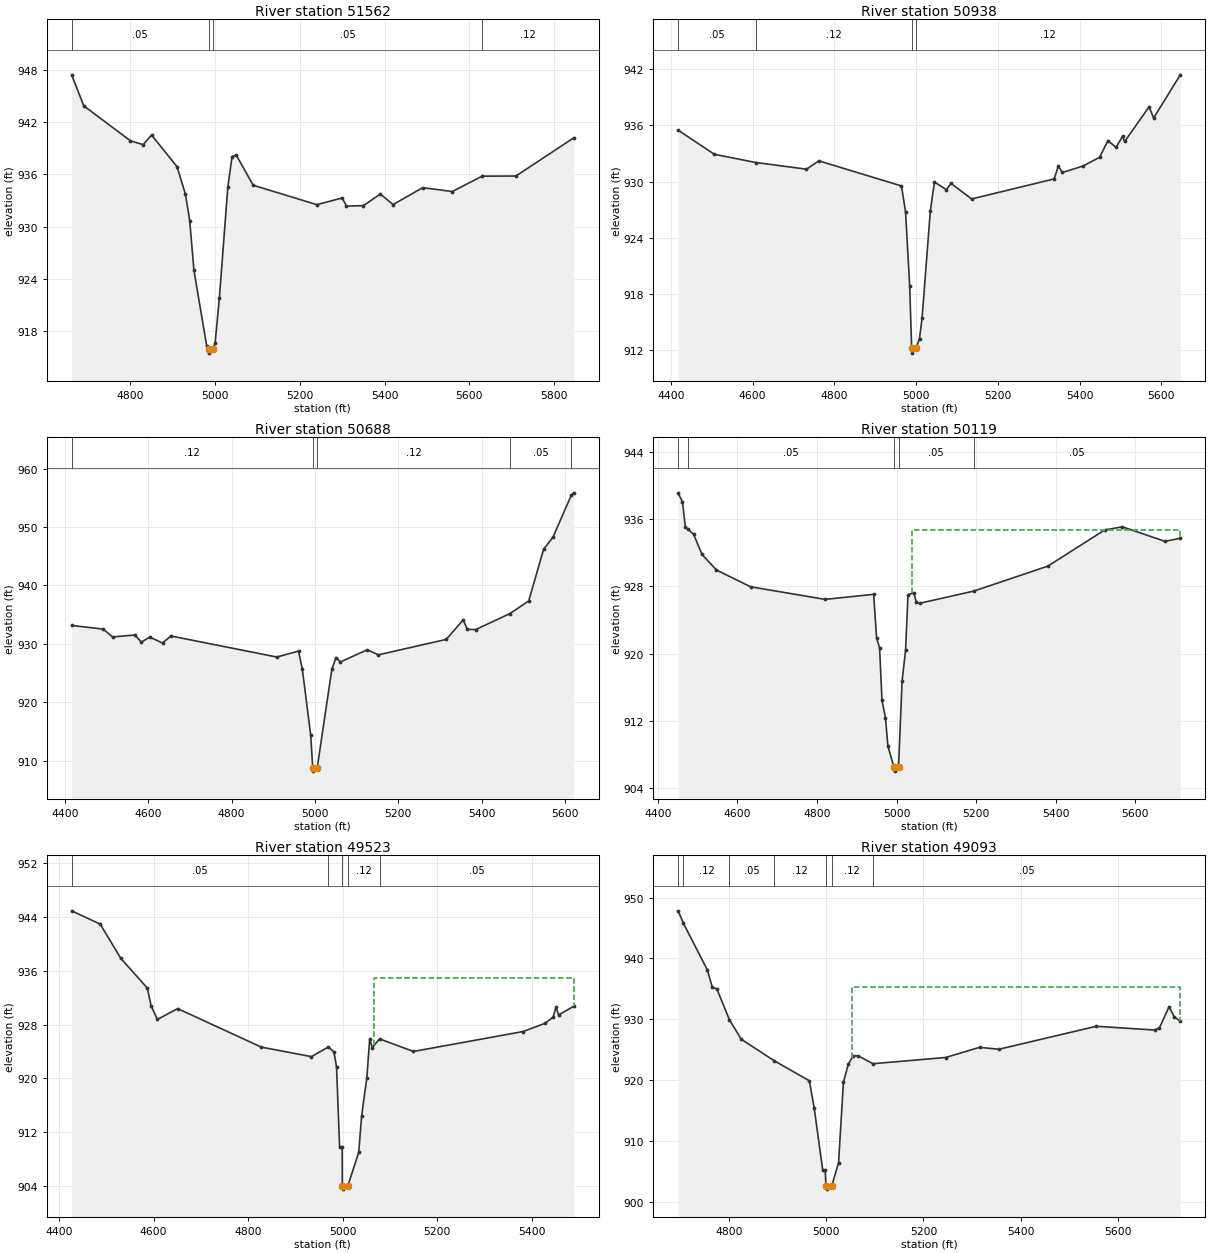
Type RM Length L Ch R = 1,51562,624,624,624
BEGIN DESCRIPTION:
Mapping XS 9e4dfc80
END DESCRIPTION:
XS GIS Cut Line= 2
      2247425.58      7172748.59      2247431.53      7171563.30
#Sta/Elev= 30
  4661.4  947.44  4690.0  943.88  4800.0  939.87  4830.0  939.42  4850.0  940.53
  4910.0  936.90  4930.0  933.73  4940.0  930.71  4950.0  925.00  4980.0  916.35
  4984.8  915.98  4986.2  915.48  4995.1  915.98  5000.0  916.64  5010.0  921.78
  5030.0  934.53  5040.0  938.05  5050.0  938.21  5090.0  934.76  5240.0  932.53
  5300.0  933.30  5310.0  932.36  5350.0  932.42  5390.0  933.75  5420.0  932.54
  5490.0  934.48  5560.0  934.04  5630.1  935.80  5710.0  935.82  5846.7  940.21
#Mann=4,-1,0
  4661.4    0.05       0  4984.8   0.033       0  4995.1    0.05       0
  5630.1    0.12       0
Bank Sta=4984.8,4995.1
Exp/Cntr=0.3,0.1

Type RM Length L Ch R = 1,50938,250,250,250
BEGIN DESCRIPTION:
Mapping XS 2d754198
END DESCRIPTION:
XS GIS Cut Line= 2
      2247996.72      7172750.98      2247824.27      7171534.44
#Sta/Elev= 30
  4417.8  935.49  4506.5  932.91  4608.0  932.03  4731.9  931.32  4762.2  932.21
  4964.2  929.53  4974.3  926.77  4984.4  918.83  4989.2  912.17  4990.7  911.67
  4999.7  912.17  5008.4  913.23  5014.7  915.42  5034.9  926.87  5045.0  929.95
  5074.3  929.13  5085.4  929.81  5135.9  928.14  5337.9  930.28  5348.0  931.65
  5358.1  930.97  5408.6  931.66  5449.0  932.59  5469.2  934.36  5489.4  933.66
  5505.2  934.83  5510.3  934.28  5570.2  937.98  5581.2  936.79  5646.5  941.40
#Mann=4,-1,0
  4417.8    0.05       0  4608.0    0.12       0  4989.2    0.07       0
  4999.7    0.12       0
Bank Sta=4989.2,4999.7
Exp/Cntr=0.3,0.1

Type RM Length L Ch R = 1,50688,569,569,569
BEGIN DESCRIPTION:
Mapping XS af37c50f
END DESCRIPTION:
XS GIS Cut Line= 2
      2248056.81      7172734.56      2248273.53      7171548.60
#Sta/Elev= 30
  4415.9  933.14  4491.7  932.51  4514.3  931.17  4567.5  931.50  4583.2  930.29
  4603.5  931.14  4634.0  930.13  4654.3  931.33  4908.5  927.73  4960.5  928.75
  4969.5  925.75  4989.8  914.36  4994.7  908.70  4996.2  908.20  5005.3  908.70
  5040.6  925.65  5050.8  927.65  5061.0  926.88  5125.3  928.97  5152.5  928.11
  5315.1  930.75  5355.8  934.07  5365.9  932.47  5386.3  932.44  5468.2  935.18
  5513.1  937.32  5548.9  946.17  5571.4  948.24  5615.3  955.42  5621.5  955.84
#Mann=5,-1,0
  4415.9    0.12       0  4994.7    0.07       0  5005.3    0.12       0
  5468.2    0.05       0  5615.3    0.12       0
Bank Sta=4994.7,5005.3
Exp/Cntr=0.3,0.1

Type RM Length L Ch R = 1,50119,596,596,596
BEGIN DESCRIPTION:
Mapping XS a25eb3cc
END DESCRIPTION:
XS GIS Cut Line= 2
      2248253.01      7172899.05      2248976.40      7171863.98
#Sta/Elev= 30
  4450.8  939.11  4461.8  938.02  4469.0  935.07  4476.1  934.75  4489.9  934.17
  4510.8  931.79  4547.2  929.93  4632.9  927.94  4820.4  926.44  4942.5  927.04
  4949.8  921.88  4957.4  920.67  4963.5  914.43  4972.2  912.37  4978.3  908.98
  4993.4  906.52  4995.0  906.02  5005.1  906.52  5014.0  916.72  5022.8  920.42
  5028.9  927.01  5043.7  927.21  5049.8  926.07  5058.5  925.98  5194.5  927.43
  5380.3  930.39  5523.4  934.69  5567.9  935.07  5675.1  933.34  5713.6  933.71
#Mann=5,-1,0
  4450.8    0.12       0  4476.1    0.05       0  4993.4    0.07       0
  5005.1    0.05       0  5194.5    0.05       0
#XS Ineff=2,0
       0                 5039.10    0.00  934.74
Permanent Ineff=
       F       F
Bank Sta=4993.4,5005.1
Exp/Cntr=0.3,0.1

Type RM Length L Ch R = 1,49523,430,430,430
BEGIN DESCRIPTION:
Black Creek 70.0
END DESCRIPTION:
XS GIS Cut Line= 4
      2248737.28      7173243.02      2248932.08      7172992.61
      2249029.00      7172760.00      2249229.00      7172310.00
#Sta/Elev= 30
  4426.9  944.90  4487.2  942.93  4530.7  937.85  4586.8  933.43  4594.9  930.78
  4608.1  928.76  4651.0  930.37  4827.7  924.65  4933.9  923.23  4969.6  924.67
  4981.5  923.93  4986.9  921.71  4993.4  909.83  4998.9  909.83  4999.1  904.04
  5000.7  903.54  5010.9  904.04  5033.8  909.01  5039.9  914.39  5050.9  920.05
  5057.0  925.85  5062.5  924.58  5077.8  925.87  5149.4  924.00  5381.2  926.96
  5427.7  928.18  5444.8  929.11  5451.0  930.59  5456.5  929.43  5488.6  930.72
#Mann=5,-1,0
  4426.9    0.05       0  4969.6    0.12       0  4999.1    0.07       0
  5010.9    0.12       0  5077.8    0.05       0
#XS Ineff=2,0
       0                 5066.60    0.00  934.93
Permanent Ineff=
       F       F
Bank Sta=4999.1,5010.9
Exp/Cntr=0.3,0.1

Type RM Length L Ch R = 1,49093,463,463,463
BEGIN DESCRIPTION:
Black Creek 69.0
END DESCRIPTION:
XS GIS Cut Line= 3
      2249429.00      7173160.04      2249429.00      7172860.00
      2249430.07      7172127.14
#Sta/Elev= 30
  4695.4  947.82  4706.4  945.75  4755.4  938.12  4765.4  935.33  4775.4  934.91
  4800.8  929.92  4825.4  926.69  4893.0  923.16  4965.4  919.86  4975.4  915.31
  4992.9  905.13  4997.9  905.13  4999.5  902.54  5001.1  902.04  5011.3  902.54
  5025.4  906.37  5035.4  919.61  5045.4  922.59  5055.4  923.94  5065.4  923.98
  5096.2  922.67  5245.4  923.69  5315.4  925.36  5355.4  925.05  5555.4  928.83
  5675.4  928.21  5685.4  928.57  5705.4  932.08  5715.4  930.40  5728.3  929.65
#Mann=7,-1,0
  4695.4    0.05       0  4706.4    0.12       0  4800.8    0.05       0
  4893.0    0.12       0  4999.5    0.07       0  5011.3    0.12       0
  5096.2    0.05       0
#XS Ineff=2,0
       0                 5053.10    0.00  935.21
Permanent Ineff=
       F       F
Bank Sta=4999.5,5011.3
Exp/Cntr=0.3,0.1

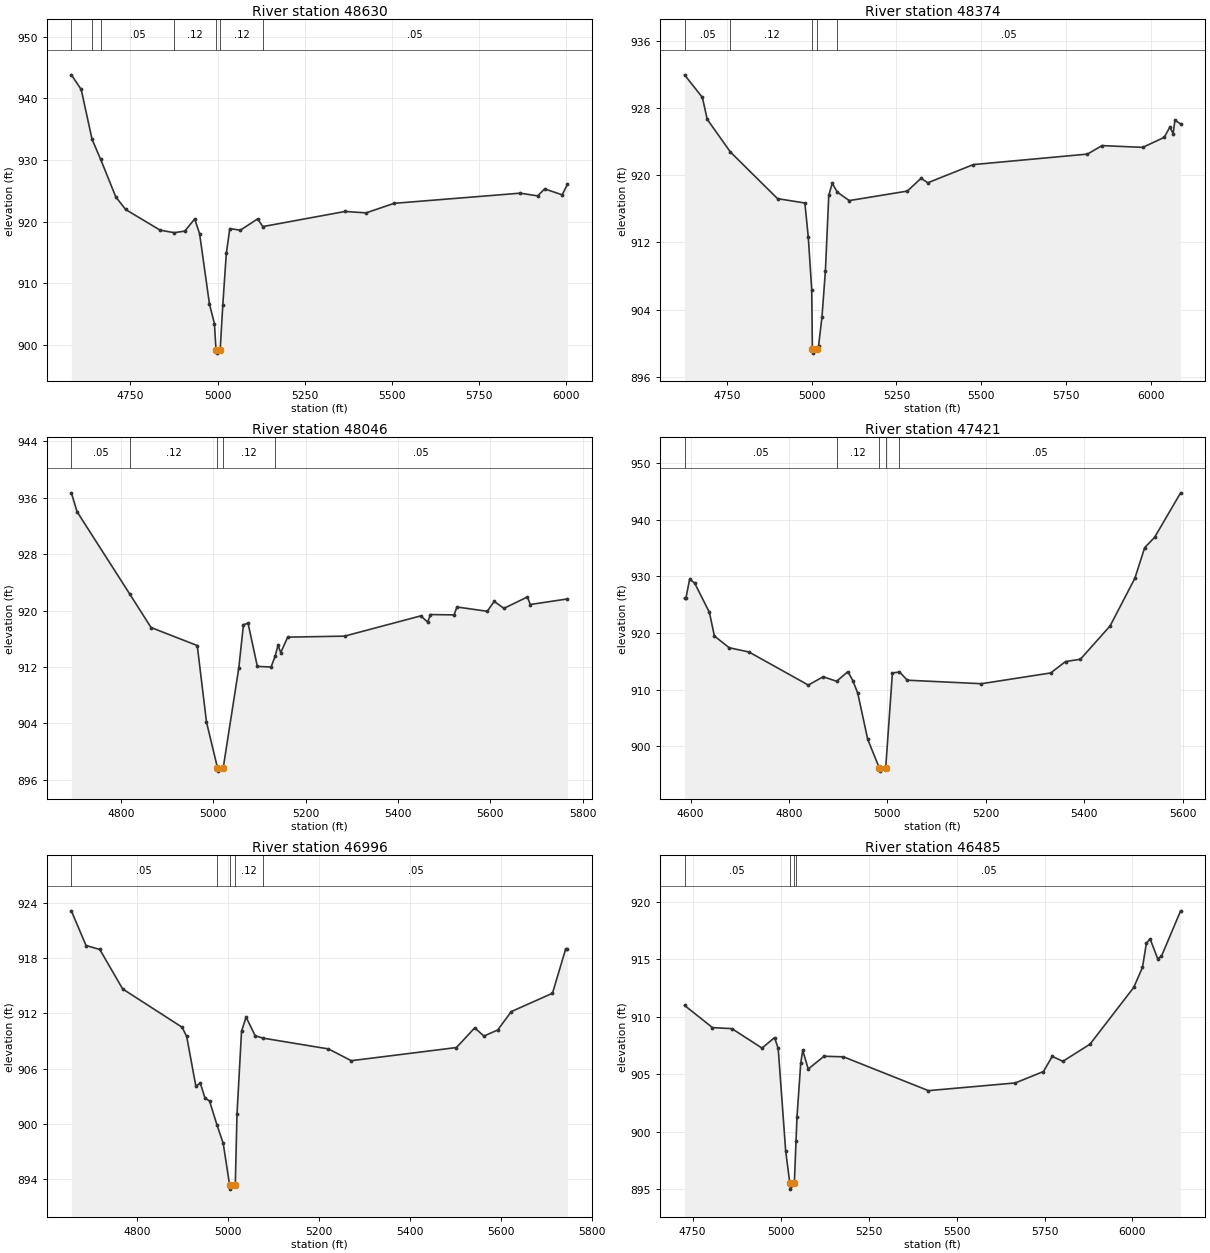
Type RM Length L Ch R = 1,48630,256,256,256
BEGIN DESCRIPTION:
Black Creek 68.0
END DESCRIPTION:
XS GIS Cut Line= 4
      2249578.97      7173210.03      2249879.00      7172910.00
      2249879.00      7172710.00      2249811.26      7171914.99
#Sta/Elev= 30
  4580.6  943.84  4608.9  941.46  4639.9  933.38  4664.7  930.10  4707.9  924.02
  4736.2  921.96  4835.2  918.60  4875.6  918.19  4905.9  918.45  4934.2  920.42
  4948.3  918.03  4976.6  906.59  4990.8  903.41  4995.4  899.12  4997.1  898.62
  5007.3  899.12  5014.9  906.52  5024.9  914.83  5034.9  918.86  5064.9  918.59
  5114.9  920.44  5129.5  919.18  5365.5  921.64  5425.7  921.41  5506.0  922.96
  5867.3  924.61  5917.5  924.17  5937.6  925.31  5987.7  924.34  6002.8  926.03
#Mann=7,-1,0
  4580.6    0.05       0  4639.9    0.12       0  4664.7    0.05       0
  4875.6    0.12       0  4995.4    0.07       0  5007.3    0.12       0
  5129.5    0.05       0
Bank Sta=4995.4,5007.3
Exp/Cntr=0.3,0.1

Type RM Length L Ch R = 1,48374,328,328,328
BEGIN DESCRIPTION:
Mapping XS a4e0b971
END DESCRIPTION:
XS GIS Cut Line= 3
      2250162.26      7173332.21      2250064.75      7172557.47
      2249848.36      7171910.03
#Sta/Elev= 30
  4624.9  931.92  4677.5  929.23  4691.8  926.63  4760.1  922.74  4899.3  917.19
  4979.9  916.67  4990.0  912.58  5000.1  906.35  5002.0  899.31  5003.7  898.81
  5014.5  899.31  5020.2  899.64  5030.3  903.10  5040.4  908.56  5050.4  917.58
  5060.5  919.01  5076.0  917.95  5110.9  916.96  5282.3  918.09  5322.6  919.61
  5342.7  919.08  5476.9  921.24  5813.6  922.49  5856.5  923.50  5976.8  923.29
  6040.0  924.48  6056.8  925.71  6066.3  924.92  6071.6  926.51  6088.4  926.08
#Mann=5,-1,0
  4624.9    0.05       0  4760.1    0.12       0  5002.0    0.07       0
  5014.5    0.12       0  5076.0    0.05       0
Bank Sta=5002,5014.5
Exp/Cntr=0.3,0.1

Type RM Length L Ch R = 1,48046,625,625,625
BEGIN DESCRIPTION:
Mapping XS 2967516b
END DESCRIPTION:
XS GIS Cut Line= 3
      2250407.51      7173252.53      2250417.54      7172843.70
      2250046.99      7172291.45
#Sta/Elev= 30
  4692.8  936.67  4705.3  933.98  4819.4  922.32  4865.4  917.59  4965.4  915.04
  4985.4  904.20  5009.1  897.75  5010.9  897.25  5021.7  897.75  5055.4  911.89
  5065.4  917.99  5075.4  918.20  5095.5  912.09  5125.2  911.99  5134.1  913.55
  5140.2  915.07  5146.2  914.04  5161.2  916.23  5284.2  916.37  5449.3  919.24
  5464.3  918.36  5470.3  919.43  5521.3  919.38  5527.7  920.50  5593.3  919.89
  5608.3  921.29  5629.3  920.31  5680.3  921.92  5686.4  920.85  5766.8  921.64
#Mann=5,-1,0
  4692.8    0.05       0  4819.4    0.12       0  5009.1    0.07       0
  5021.7    0.12       0  5134.1    0.05       0
Bank Sta=5009.1,5021.7
Exp/Cntr=0.3,0.1

Type RM Length L Ch R = 1,47421,425,425,425
BEGIN DESCRIPTION:
Mapping XS 1974134c
END DESCRIPTION:
XS GIS Cut Line= 2
      2250903.59      7173270.27      2250806.09      7172267.40
#Sta/Elev= 30
  4587.9  926.09  4590.5  926.09  4598.2  929.47  4608.3  928.82  4638.4  923.63
  4648.5  919.47  4678.6  917.40  4718.8  916.65  4839.3  910.82  4869.5  912.29
  4896.8  911.49  4919.7  913.19  4929.8  911.59  4939.8  909.35  4959.9  901.28
  4983.7  896.15  4985.5  895.65  4996.4  896.15  5010.1  912.95  5024.5  913.13
  5040.3  911.68  5191.0  911.06  5331.7  912.96  5361.8  914.97  5391.9  915.37
  5452.2  921.24  5502.5  929.63  5522.6  935.06  5542.6  936.86  5595.5  944.71
#Mann=5,-1,0
  4587.9    0.05       0  4896.8    0.12       0  4983.7    0.07       0
  4996.4    0.12       0  5024.5    0.05       0
Bank Sta=4983.7,4996.4
Exp/Cntr=0.3,0.1

Type RM Length L Ch R = 1,46996,511,511,511
BEGIN DESCRIPTION:
Mapping XS 1ca7fd61
END DESCRIPTION:
XS GIS Cut Line= 2
      2251305.25      7173252.20      2251201.46      7172167.35
#Sta/Elev= 30
  4656.3  923.15  4688.6  919.38  4718.8  918.95  4769.0  914.66  4899.6  910.50
  4909.7  909.49  4929.7  904.13  4939.8  904.40  4949.8  902.81  4959.9  902.48
  4976.5  899.84  4990.0  897.86  5003.8  893.40  5005.6  892.90  5016.5  893.40
  5020.2  901.03  5030.2  910.05  5040.2  911.60  5060.3  909.56  5077.9  909.31
  5221.1  908.14  5271.3  906.86  5502.3  908.29  5542.5  910.43  5562.6  909.54
  5592.8  910.19  5622.9  912.20  5713.3  914.19  5742.3  919.01  5746.1  919.01
#Mann=5,-1,0
  4656.3    0.05       0  4976.5    0.12       0  5003.8    0.07       0
  5016.5    0.12       0  5077.9    0.05       0
Bank Sta=5003.8,5016.5
Exp/Cntr=0.3,0.1

Type RM Length L Ch R = 1,46485,646,646,646
BEGIN DESCRIPTION:
Mapping XS b032a715
END DESCRIPTION:
XS GIS Cut Line= 2
      2251841.88      7173049.21      2251347.75      7171728.84
#Sta/Elev= 30
  4727.0  910.98  4806.4  909.05  4861.6  908.96  4947.1  907.27  4982.7  908.18
  4993.1  907.25  5014.4  898.32  5026.3  895.51  5028.0  895.01  5039.0  895.51
  5043.8  899.19  5046.5  901.26  5057.2  905.97  5062.9  907.07  5078.5  905.45
  5123.5  906.56  5178.7  906.51  5420.2  903.57  5666.8  904.24  5747.0  905.23
  5771.9  906.55  5802.2  906.12  5879.3  907.61  6003.5  912.54  6028.4  914.28
  6039.5  916.38  6050.1  916.76  6071.5  915.05  6082.2  915.24  6136.8  919.20
#Mann=4,-1,0
  4727.0    0.05       0  5026.3    0.04       0  5039.0    0.05       0
  5043.8    0.05       0
Bank Sta=5026.3,5039
Exp/Cntr=0.3,0.1

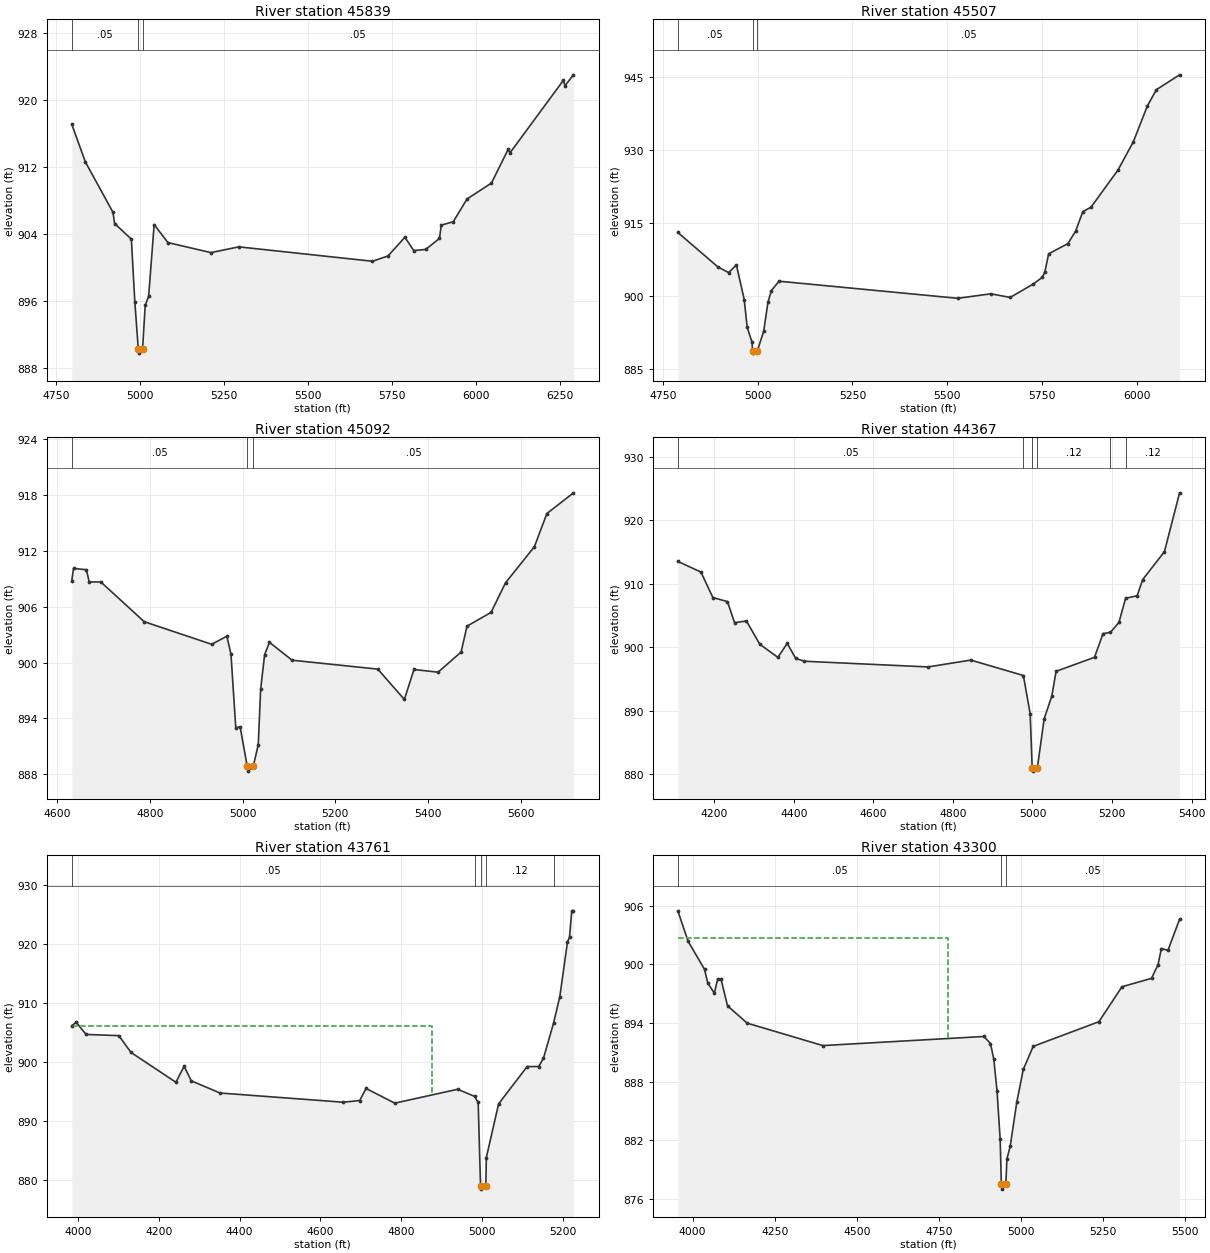
Type RM Length L Ch R = 1,45839,332,332,332
BEGIN DESCRIPTION:
Mapping XS 260a31bb
END DESCRIPTION:
XS GIS Cut Line= 2
      2252274.58      7172762.10      2251907.11      7171313.18
#Sta/Elev= 30
  4796.3  917.16  4837.0  912.65  4918.9  906.66  4924.1  905.30  4973.9  903.44
  4984.2  895.97  4994.5  890.33  4996.3  889.83  5007.3  890.33  5015.1  895.53
  5025.4  896.63  5041.8  905.18  5082.8  903.03  5211.1  901.83  5293.7  902.52
  5692.2  900.80  5738.4  901.43  5788.9  903.67  5815.1  902.08  5850.8  902.21
  5891.9  903.53  5897.1  905.11  5932.9  905.52  5973.9  908.23  6046.8  910.14
  6096.8  914.19  6101.9  913.74  6260.7  922.39  6265.8  921.77  6291.1  923.06
#Mann=3,-1,0
  4796.3    0.05       0  4994.5   0.033       0  5007.3    0.05       0
Bank Sta=4994.5,5007.3
Exp/Cntr=0.3,0.1

Type RM Length L Ch R = 1,45507,415,415,415
BEGIN DESCRIPTION:
Black Creek 61.0
END DESCRIPTION:
XS GIS Cut Line= 3
      2252529.00      7172610.00      2252479.00      7172410.00
      2252279.00      7171309.99
#Sta/Elev= 30
  4789.1  913.10  4894.8  906.02  4923.1  904.85  4943.7  906.42  4964.3  899.31
  4972.1  893.64  4984.9  890.52  4986.3  888.80  4988.1  888.30  4999.1  888.80
  5015.6  892.78  5027.0  898.75  5035.9  901.16  5056.2  903.08  5527.6  899.57
  5615.3  900.49  5666.1  899.75  5727.1  902.50  5751.2  903.89  5757.6  904.94
  5767.7  908.71  5818.5  910.81  5838.9  913.37  5857.9  917.37  5879.5  918.29
  5950.7  925.93  5991.3  931.74  6028.2  939.10  6052.3  942.46  6113.3  945.50
#Mann=3,-1,0
  4789.1    0.05       0  4986.3   0.033       0  4999.1    0.05       0
Bank Sta=4986.3,4999.1
Exp/Cntr=0.3,0.1

Type RM Length L Ch R = 1,45092,725,725,725
BEGIN DESCRIPTION:
Mapping XS d7dedcb6
END DESCRIPTION:
XS GIS Cut Line= 2
      2252874.49      7172470.48      2252578.51      7171428.92
#Sta/Elev= 30
  4631.1  908.75  4634.9  910.12  4662.8  909.98  4668.7  908.67  4694.0  908.66
  4787.5  904.39  4933.1  901.96  4965.8  902.83  4974.7  900.90  4985.1  892.98
  4994.5  893.08  5009.8  888.82  5011.6  888.32  5022.7  888.82  5033.6  891.16
  5038.8  897.15  5047.4  900.86  5057.8  902.17  5106.6  900.25  5291.6  899.29
  5348.9  896.03  5369.7  899.25  5421.7  898.96  5471.4  901.13  5484.1  903.91
  5536.0  905.39  5567.2  908.57  5629.6  912.46  5656.4  916.02  5713.9  918.25
#Mann=3,-1,0
  4631.1    0.05       0  5009.8   0.033       0  5022.7    0.05       0
Bank Sta=5009.8,5022.7
Exp/Cntr=0.3,0.1

Type RM Length L Ch R = 1,44367,606,606,606
BEGIN DESCRIPTION:
Mapping XS a4eb0409
END DESCRIPTION:
XS GIS Cut Line= 3
      2253366.18      7172376.26      2253291.24      7172183.25
      2252909.72      7171200.67
#Sta/Elev= 30
  4108.6  913.54  4166.7  911.86  4196.6  907.85  4233.3  907.21  4251.1  903.89
  4281.0  904.15  4314.7  900.48  4360.0  898.42  4383.5  900.62  4405.0  898.25
  4426.4  897.81  4737.5  896.91  4844.8  897.99  4977.1  895.56  4994.2  889.53
  4999.2  880.99  5001.0  880.49  5012.2  880.99  5029.4  888.76  5048.6  892.32
  5059.3  896.22  5155.9  898.43  5177.3  902.16  5196.0  902.36  5217.3  903.93
  5234.0  907.73  5263.1  908.13  5277.1  910.69  5331.6  915.07  5369.7  924.35
#Mann=6,-1,0
  4108.6    0.05       0  4977.1    0.12       0  4999.2    0.07       0
  5012.2    0.12       0  5196.0    0.05       0  5234.0    0.12       0
Bank Sta=4999.2,5012.2
Exp/Cntr=0.3,0.1

Type RM Length L Ch R = 1,43761,461,461,461
BEGIN DESCRIPTION:
Mapping XS 76a34cd3
END DESCRIPTION:
XS GIS Cut Line= 3
      2253685.63      7172315.12      2253653.95      7172090.37
      2253512.45      7171086.57
#Sta/Elev= 30
  3985.1  906.20  3996.0  906.79  4020.6  904.72  4101.4  904.52  4131.7  901.67
  4242.7  896.62  4262.9  899.32  4280.7  896.86  4351.9  894.80  4656.8  893.24
  4697.2  893.53  4712.8  895.57  4783.9  893.08  4939.6  895.44  4981.2  894.23
  4990.1  893.21  4996.0  879.02  4997.8  878.52  5009.0  879.02  5010.3  883.87
  5040.6  892.96  5111.2  899.28  5139.8  899.29  5151.6  900.69  5176.7  906.68
  5192.0  911.12  5210.9  920.36  5216.0  921.21  5221.5  925.66  5225.8  925.66
#Mann=5,-1,0
  3985.1    0.05       0  4981.2    0.12       0  4996.0    0.04       0
  5009.0    0.12       0  5176.7    0.05       0
#XS Ineff=2,0
    0.00 4876.70  906.15               0
Permanent Ineff=
       F       F
Bank Sta=4996,5009
Exp/Cntr=0.3,0.1

Type RM Length L Ch R = 1,43300,837,837,837
BEGIN DESCRIPTION:
Mapping XS f77b9555
END DESCRIPTION:
XS GIS Cut Line= 2
      2253884.14      7172191.14      2253930.41      7170664.64
#Sta/Elev= 30
  3955.0  905.46  3986.2  902.35  4036.2  899.48  4046.2  898.07  4066.2  897.04
  4076.2  898.48  4086.2  898.50  4106.2  895.75  4166.2  893.98  4396.3  891.69
  4886.6  892.62  4906.6  891.90  4916.6  890.33  4926.6  887.05  4936.1  882.12
  4939.7  877.52  4941.7  877.02  4953.4  877.52  4956.6  880.11  4966.6  881.38
  4986.6  885.90  5006.6  889.26  5036.6  891.61  5236.7  894.13  5306.8  897.70
  5396.8  898.56  5416.8  899.97  5426.8  901.61  5446.8  901.42  5482.2  904.60
#Mann=3,-1,0
  3955.0    0.05       0  4939.7   0.033       0  4953.4    0.05       0
#XS Ineff=2,0
    0.00 4778.60  902.65               0
Permanent Ineff=
       F       F
Bank Sta=4939.7,4953.4
Exp/Cntr=0.3,0.1

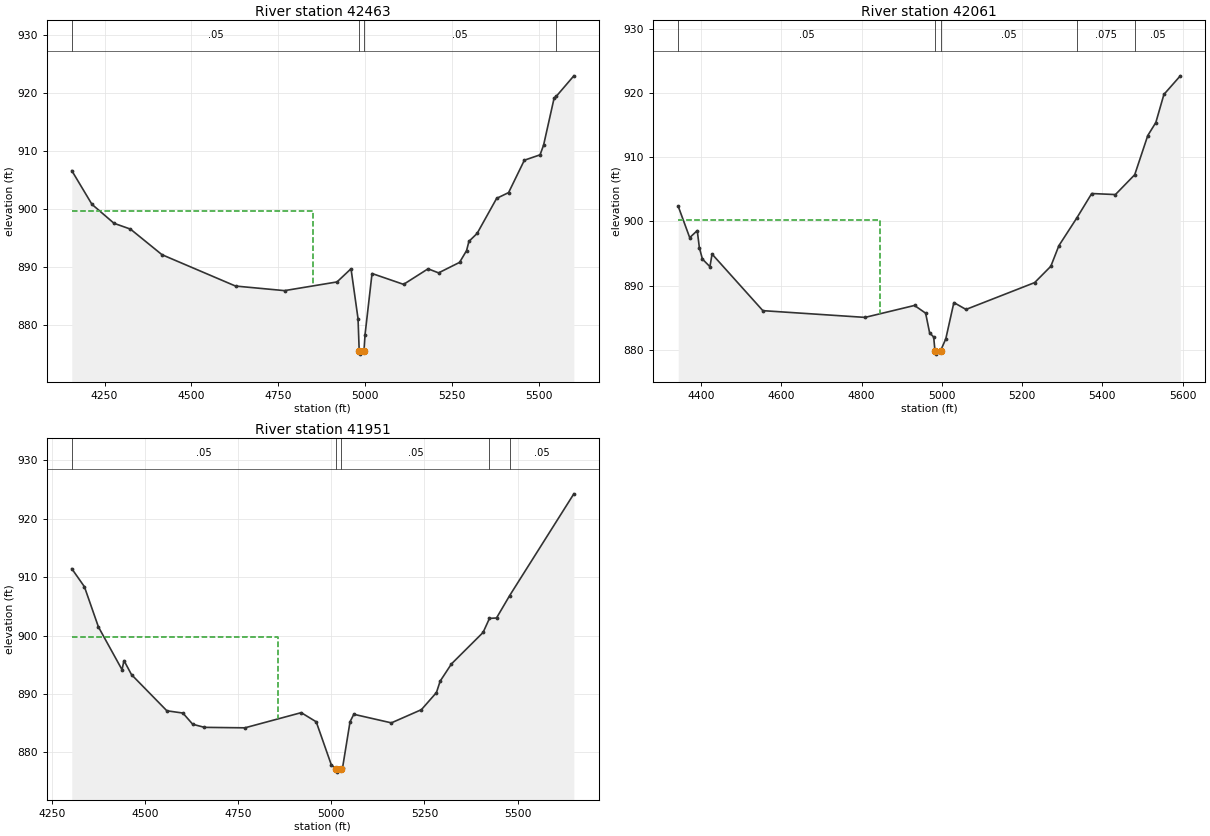
Type RM Length L Ch R = 1,42463,402,402,402
BEGIN DESCRIPTION:
Mapping XS 2f8d6829
END DESCRIPTION:
XS GIS Cut Line= 2
      2254759.17      7172097.66      2254575.93      7170663.62
#Sta/Elev= 30
  4155.7  906.68  4213.8  900.87  4277.4  897.60  4324.7  896.60  4415.5  892.19
  4627.2  886.79  4768.3  886.00  4919.5  887.50  4959.8  889.77  4980.0  881.16
  4983.4  875.56  4985.4  875.06  4997.1  875.56  5000.2  878.44  5020.3  888.95
  5111.1  887.08  5181.6  889.76  5211.9  889.06  5272.4  890.87  5292.5  892.90
  5299.3  894.49  5322.8  895.85  5379.1  901.90  5413.5  902.89  5458.9  908.47
  5504.2  909.40  5514.3  911.08  5544.6  919.18  5550.7  919.47  5601.4  923.01
#Mann=4,-1,0
  4155.7    0.05       0  4983.4   0.033       0  4997.1    0.05       0
  5550.7    0.12       0
#XS Ineff=2,0
    0.00 4848.90  899.75               0
Permanent Ineff=
       F       F
Bank Sta=4983.4,4997.1
Exp/Cntr=0.3,0.1

Type RM Length L Ch R = 1,42061,110,110,110
BEGIN DESCRIPTION:
Mapping XS ea6363a7
END DESCRIPTION:
XS GIS Cut Line= 3
      2255149.88      7171797.18      2255041.62      7171471.59
      2254938.49      7170569.38
#Sta/Elev= 30
  4343.0  902.35  4371.6  897.47  4390.4  898.57  4395.7  895.88  4403.3  894.13
  4422.0  892.95  4427.3  894.91  4553.9  886.10  4808.5  885.05  4931.8  886.91
  4959.5  885.71  4969.5  882.64  4979.6  881.99  4982.8  879.83  4984.8  879.33
  4996.6  879.83  5009.8  881.72  5029.9  887.36  5060.1  886.29  5231.2  890.47
  5271.5  893.01  5291.6  896.22  5336.5  900.56  5373.4  904.34  5432.5  904.18
  5480.6  907.27  5513.1  913.37  5533.2  915.40  5553.3  919.77  5594.2  922.67
#Mann=5,-1,0
  4343.0    0.05       0  4982.8   0.033       0  4996.6    0.05       0
  5336.5   0.075       0  5480.6    0.05       0
#XS Ineff=2,0
    0.00 4844.60  900.19               0
Permanent Ineff=
       F       F
Bank Sta=4982.8,4996.6
Exp/Cntr=0.3,0.1

Type RM Length L Ch R = 1,41951,386,386,386
BEGIN DESCRIPTION:
Mapping XS fa18228b
END DESCRIPTION:
XS GIS Cut Line= 3
      2255286.91      7171832.17      2255148.92      7171418.01
      2255032.86      7170514.07
#Sta/Elev= 30
  4303.3  911.47  4337.2  908.38  4374.9  901.48  4438.2  894.16  4443.5  895.72
  4463.7  893.31  4558.6  887.12  4601.6  886.73  4628.0  884.81  4659.6  884.28
  4768.1  884.20  4919.3  886.80  4959.6  885.23  5000.0  877.87  5013.2  877.11
  5015.2  876.61  5027.0  877.11  5030.2  877.32  5050.4  885.25  5060.5  886.52
  5161.3  885.05  5241.9  887.31  5282.3  890.24  5292.3  892.20  5322.6  895.15
  5407.5  900.54  5424.7  902.95  5443.6  903.02  5479.0  906.87  5651.2  924.29
#Mann=5,-1,0
  4303.3    0.05       0  5013.2   0.033       0  5027.0    0.05       0
  5424.7   0.075       0  5479.0    0.05       0
#XS Ineff=2,0
    0.00 4856.80  899.74               0
Permanent Ineff=
       F       F
Bank Sta=5013.2,5027
Exp/Cntr=0.3,0.1