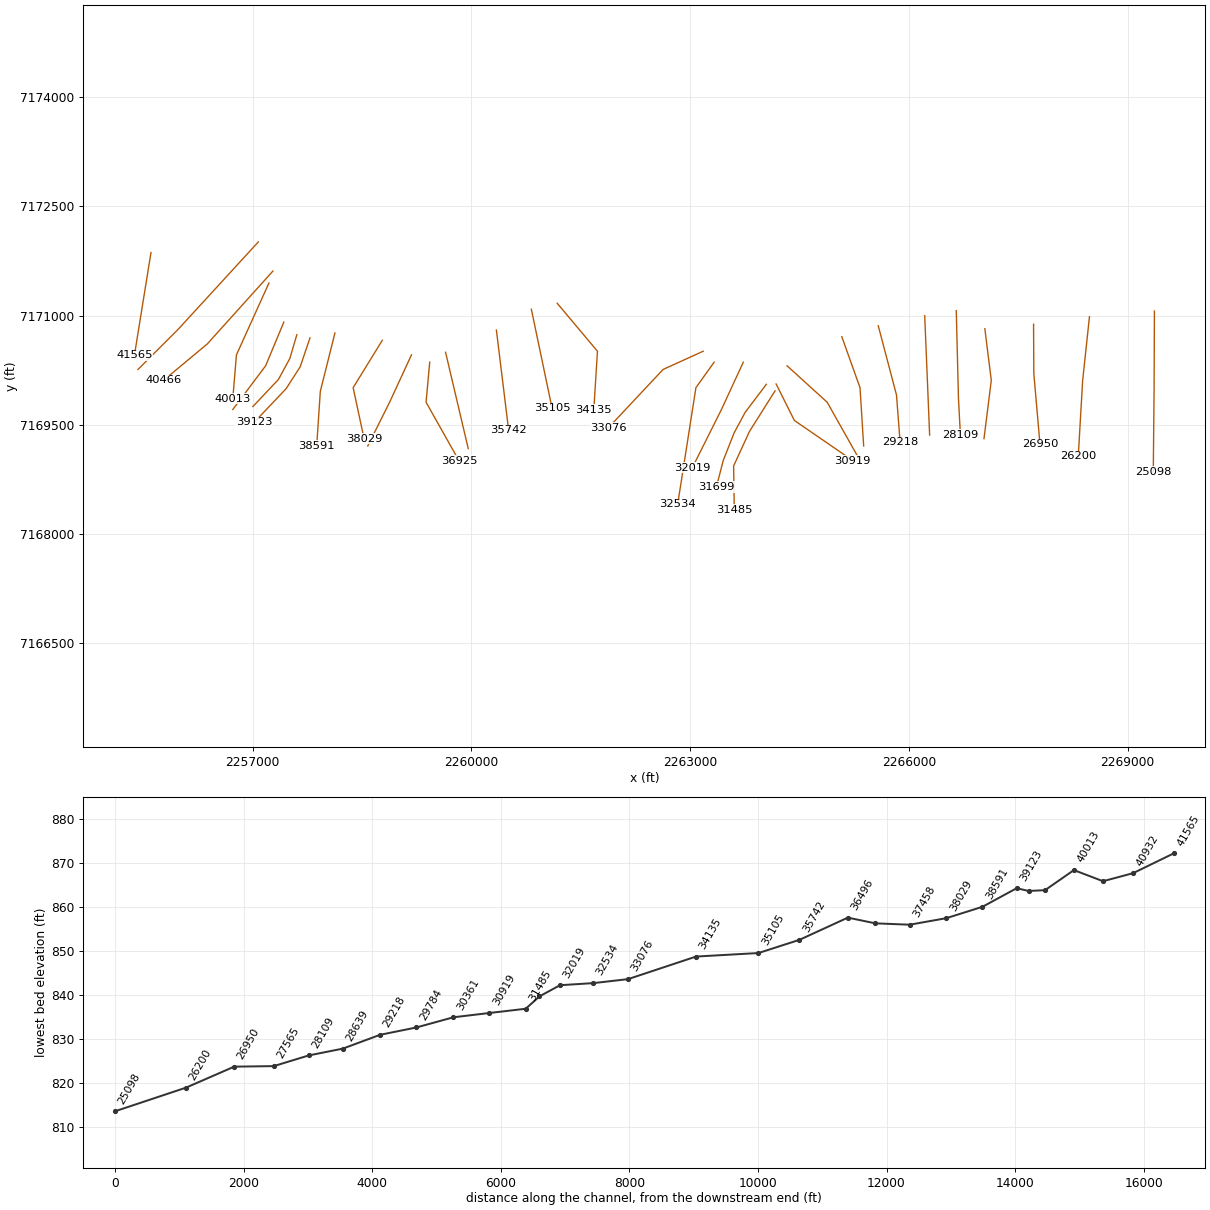
HEC-RAS study Black Creek.prj: Black Creek Base Level Engineering

--- Black Creek.g01 (geometry) --- (continued)

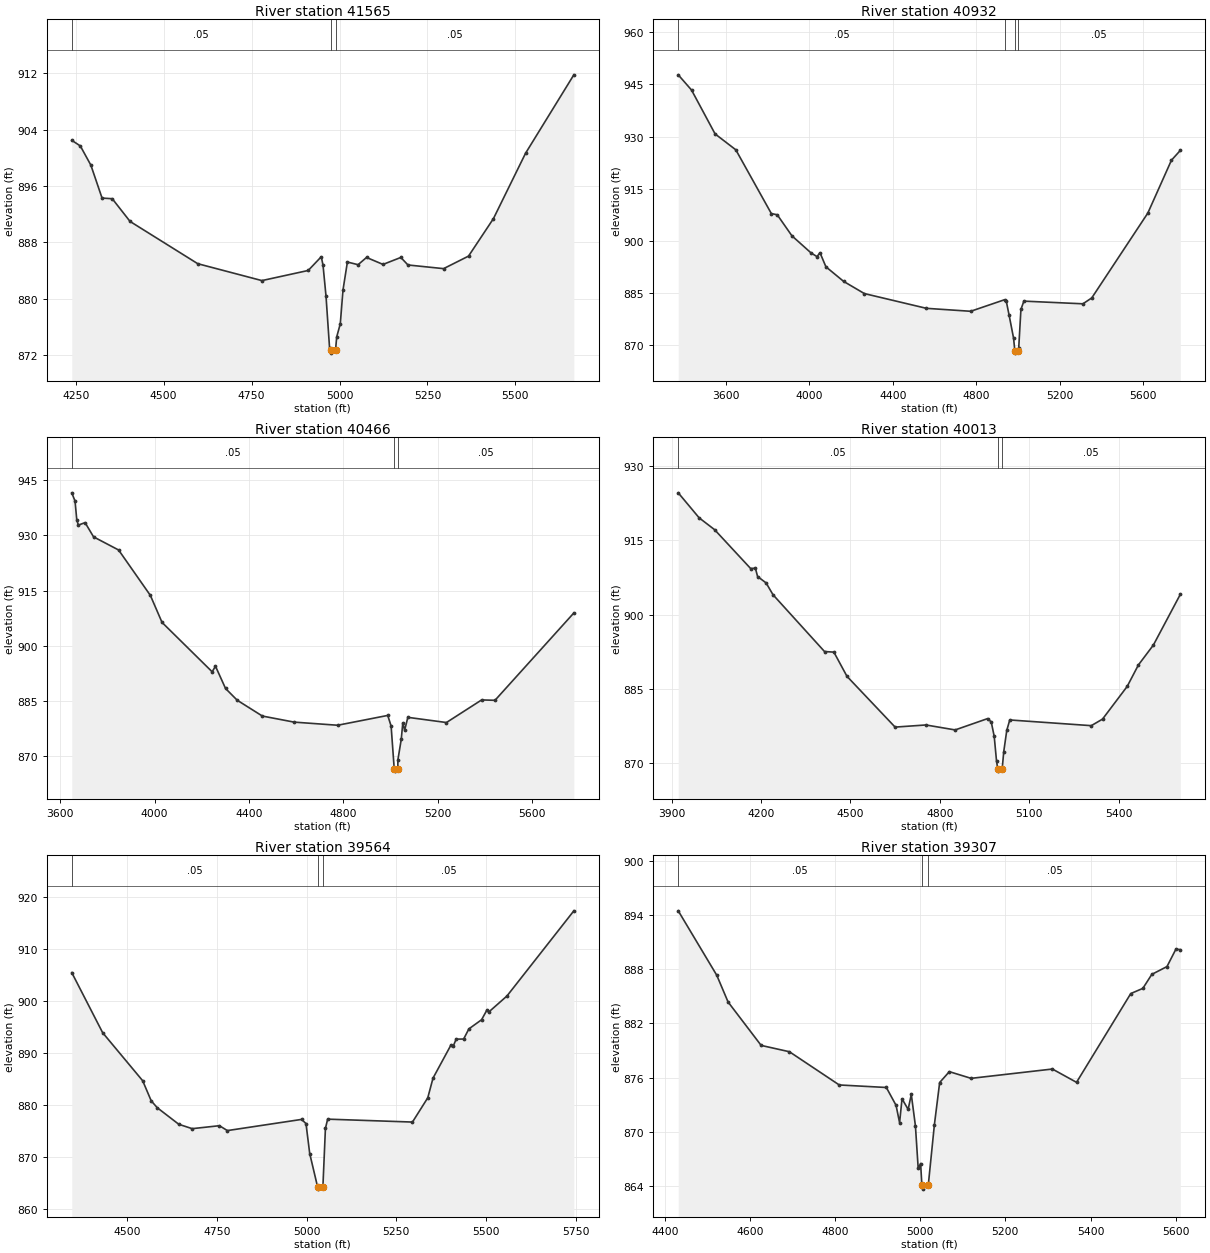
Type RM Length L Ch R = 1,41565,633,633,633
BEGIN DESCRIPTION:
Mapping XS 3e64d05f
END DESCRIPTION:
XS GIS Cut Line= 2
      2255607.11      7171863.63      2255380.00      7170454.41
#Sta/Elev= 30
  4238.8  902.49  4263.1  901.69  4293.1  898.96  4324.9  894.28  4353.9  894.19
  4404.5  890.96  4597.0  884.95  4779.3  882.55  4911.0  883.99  4948.1  885.94
  4953.1  884.75  4961.6  880.35  4971.8  872.91  4975.0  872.74  4976.9  872.24
  4988.8  872.74  4992.0  874.54  5002.2  876.41  5009.9  881.22  5022.4  885.19
  5052.8  884.81  5076.8  885.84  5123.7  884.85  5174.3  885.84  5194.6  884.77
  5295.9  884.25  5366.8  886.03  5437.7  891.37  5528.9  900.65  5666.2  911.80
#Mann=3,-1,0
  4238.8    0.05       0  4975.0    0.04       0  4988.8    0.05       0
Bank Sta=4975,4988.8
Exp/Cntr=0.3,0.1

Type RM Length L Ch R = 1,40932,466,466,466
BEGIN DESCRIPTION:
Black Creek 52.0
END DESCRIPTION:
XS GIS Cut Line= 3
      2257078.98      7172009.98      2255979.00      7170810.00
      2255428.98      7170259.98
#Sta/Elev= 30
  3371.9  947.74  3435.7  943.36  3548.5  930.75  3647.8  926.18  3818.0  907.86
  3846.4  907.50  3916.7  901.45  4009.2  896.49  4036.9  895.48  4051.1  896.60
  4079.5  892.55  4164.5  888.35  4263.8  884.85  4561.0  880.61  4773.2  879.76
  4935.3  883.08  4943.3  882.78  4957.5  878.57  4978.5  872.09  4985.1  868.23
  4987.1  867.73  5000.2  868.23  5003.3  869.16  5013.9  880.29  5028.0  882.68
  5310.9  881.91  5353.3  883.60  5622.0  908.00  5735.1  923.19  5777.6  926.01
#Mann=4,-1,0
  3371.9    0.05       0  4935.3    0.12       0  4985.1    0.07       0
  5000.2    0.05       0
Bank Sta=4985.1,5000.2
Exp/Cntr=0.3,0.1

Type RM Length L Ch R = 1,40466,453,453,453
BEGIN DESCRIPTION:
Black Creek 51.0
END DESCRIPTION:
XS GIS Cut Line= 3
      2257278.98      7171609.98      2256379.00      7170610.00
      2255778.97      7170109.97
#Sta/Elev= 30
  3649.4  941.55  3663.2  939.33  3670.7  934.15  3677.4  932.78  3705.8  933.45
  3741.7  929.58  3847.8  926.01  3982.3  913.67  4031.7  906.33  4243.9  892.91
  4258.1  894.42  4300.7  888.37  4350.1  885.18  4456.6  880.88  4591.1  879.23
  4775.4  878.38  4987.6  881.05  5001.9  878.16  5015.2  866.41  5017.2  865.91
  5030.3  866.41  5030.5  868.93  5044.8  874.53  5051.4  879.04  5059.2  877.05
  5072.8  880.53  5236.2  879.12  5385.2  885.26  5441.9  885.16  5775.8  908.90
#Mann=3,-1,0
  3649.4    0.05       0  5015.2    0.04       0  5030.3    0.05       0
Bank Sta=5015.2,5030.3
Exp/Cntr=0.3,0.1

Type RM Length L Ch R = 1,40013,449,449,449
BEGIN DESCRIPTION:
Black Creek 50.0
END DESCRIPTION:
XS GIS Cut Line= 3
      2257224.38      7171445.74      2256779.00      7170460.00
      2256729.00      7169859.96
#Sta/Elev= 30
  3922.5  924.57  3992.7  919.52  4044.4  917.14  4165.5  909.29  4181.2  909.38
  4188.6  907.69  4217.2  906.40  4240.3  904.02  4413.1  892.56  4444.5  892.44
  4488.4  887.56  4649.8  877.32  4753.2  877.75  4851.2  876.75  4960.3  879.04
  4972.3  878.35  4982.2  875.44  4989.9  870.51  4993.9  868.94  4995.9  868.44
  5009.0  868.94  5014.2  872.39  5024.3  876.65  5034.3  878.76  5307.7  877.61
  5345.4  878.93  5428.1  885.52  5465.8  889.86  5516.0  893.87  5606.3  904.09
#Mann=3,-1,0
  3922.5    0.05       0  4993.9    0.04       0  5009.0    0.05       0
Bank Sta=4993.9,5009
Exp/Cntr=0.3,0.1

Type RM Length L Ch R = 1,39564,257,257,257
BEGIN DESCRIPTION:
Black Creek 49.0
END DESCRIPTION:
XS GIS Cut Line= 3
      2257429.00      7170910.00      2257179.00      7170310.00
      2256729.00      7169710.00
#Sta/Elev= 30
  4345.2  905.52  4431.3  893.96  4542.9  884.72  4566.7  880.86  4583.5  879.53
  4643.7  876.34  4681.0  875.50  4756.9  876.07  4779.1  875.13  4986.0  877.28
  4998.3  876.48  5008.7  870.71  5030.4  864.37  5032.4  863.87  5045.5  864.37
  5052.5  875.55  5058.7  877.33  5295.2  876.77  5337.9  881.44  5352.5  885.22
  5402.5  891.58  5408.7  891.35  5417.1  892.72  5437.9  892.74  5452.5  894.69
  5487.9  896.45  5502.5  898.28  5508.7  897.98  5558.7  901.02  5745.2  917.40
#Mann=3,-1,0
  4345.2    0.05       0  5030.4    0.04       0  5045.5    0.05       0
Bank Sta=5030.4,5045.5
Exp/Cntr=0.3,0.1

Type RM Length L Ch R = 1,39307,184,184,184
BEGIN DESCRIPTION:
Mapping XS 959dd287
END DESCRIPTION:
XS GIS Cut Line= 4
      2257607.01      7170736.82      2257512.03      7170412.59
      2257354.45      7170122.23      2257004.01      7169750.63
#Sta/Elev= 30
  4431.8  894.44  4522.3  887.32  4548.8  884.37  4626.5  879.57  4692.9  878.87
  4809.9  875.20  4920.5  874.92  4943.3  872.95  4951.6  871.03  4957.3  873.67
  4971.7  872.50  4979.1  874.15  4988.8  870.67  4995.3  865.97  5001.0  866.52
  5003.8  864.19  5005.8  863.69  5019.1  864.19  5033.3  870.80  5045.7  875.47
  5068.4  876.67  5119.5  875.93  5310.4  876.96  5367.1  875.49  5494.5  885.30
  5522.8  885.87  5543.9  887.42  5579.5  888.28  5600.5  890.21  5610.8  890.15
#Mann=3,-1,0
  4431.8    0.05       0  5003.8    0.04       0  5019.1    0.05       0
Bank Sta=5003.8,5019.1
Exp/Cntr=0.3,0.1

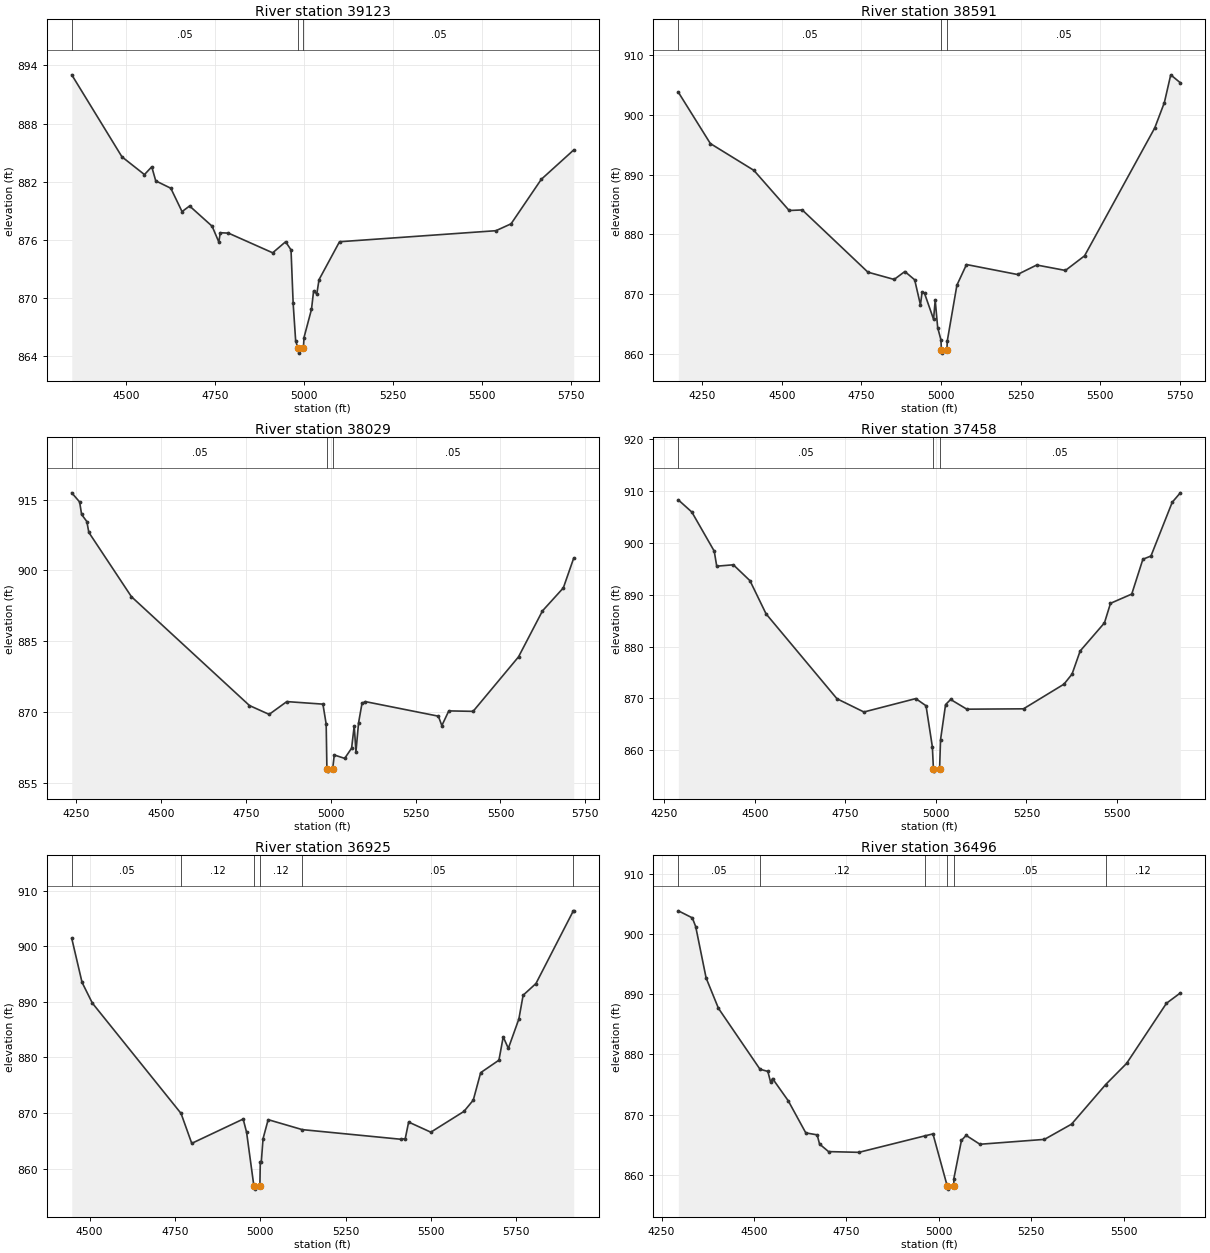
Type RM Length L Ch R = 1,39123,532,532,532
BEGIN DESCRIPTION:
Mapping XS 1426d0b6
END DESCRIPTION:
XS GIS Cut Line= 4
      2257787.64      7170693.42      2257653.25      7170297.22
      2257460.16      7169995.95      2257023.87      7169536.23
#Sta/Elev= 30
  4347.8  893.03  4488.8  884.57  4552.0  882.74  4572.5  883.54  4583.7  882.09
  4626.0  881.33  4657.6  878.92  4678.8  879.50  4742.1  877.41  4760.9  875.78
  4765.0  876.74  4787.9  876.70  4912.2  874.67  4948.5  875.81  4963.7  874.97
  4969.7  869.45  4976.7  865.60  4983.2  864.82  4985.2  864.32  4998.5  864.82
  5000.1  865.92  5021.2  868.84  5027.2  870.75  5036.1  870.42  5042.4  871.90
  5099.9  875.81  5539.3  876.95  5581.8  877.66  5666.7  882.25  5757.8  885.28
#Mann=3,-1,0
  4347.8    0.05       0  4983.2    0.04       0  4998.5    0.05       0
Bank Sta=4983.2,4998.5
Exp/Cntr=0.3,0.1

Type RM Length L Ch R = 1,38591,562,562,562
BEGIN DESCRIPTION:
Black Creek 47.0
END DESCRIPTION:
XS GIS Cut Line= 3
      2258129.00      7170759.98      2257929.00      7169960.00
      2257879.00      7169209.97
#Sta/Elev= 30
  4175.0  903.82  4275.5  895.22  4412.1  890.73  4522.9  884.00  4564.1  884.09
  4770.3  873.66  4852.7  872.44  4886.2  873.77  4917.1  872.38  4935.2  868.18
  4940.3  870.28  4948.1  870.11  4976.4  865.77  4981.6  868.98  4989.3  864.38
  4999.6  862.31  5001.1  860.59  5003.1  860.09  5018.2  860.59  5019.6  862.16
  5049.7  871.48  5079.8  874.94  5240.1  873.27  5300.3  874.86  5390.5  873.95
  5450.6  876.40  5671.1  897.85  5701.2  902.09  5721.2  906.74  5751.3  905.41
#Mann=3,-1,0
  4175.0    0.05       0  5001.1    0.04       0  5018.2    0.05       0
Bank Sta=5001.1,5018.2
Exp/Cntr=0.3,0.1

Type RM Length L Ch R = 1,38029,571,571,571
BEGIN DESCRIPTION:
Black Creek 46.0
END DESCRIPTION:
XS GIS Cut Line= 3
      2258779.02      7170660.03      2258379.00      7170010.00
      2258528.99      7169310.05
#Sta/Elev= 30
  4236.8  916.45  4260.0  914.51  4265.8  911.87  4281.2  910.37  4287.1  908.07
  4412.6  894.45  4760.5  871.39  4818.4  869.52  4870.5  872.23  4976.9  871.69
  4986.5  867.44  4988.6  858.00  4990.6  857.50  5005.7  858.00  5010.3  860.92
  5041.0  860.20  5061.4  862.36  5069.1  867.10  5074.2  861.61  5081.9  867.73
  5092.1  871.87  5102.3  872.22  5317.1  869.14  5327.3  867.14  5347.8  870.26
  5419.4  870.16  5553.2  881.70  5623.9  891.45  5685.3  896.31  5715.9  902.63
#Mann=3,-1,0
  4236.8    0.05       0  4988.6    0.04       0  5005.7    0.05       0
Bank Sta=4988.6,5005.7
Exp/Cntr=0.3,0.1

Type RM Length L Ch R = 1,37458,533,533,533
BEGIN DESCRIPTION:
Black Creek 45.0
END DESCRIPTION:
XS GIS Cut Line= 3
      2259179.00      7170459.99      2258879.00      7169810.00
      2258579.00      7169210.00
#Sta/Elev= 30
  4288.3  908.24  4325.5  905.91  4387.4  898.38  4394.3  895.48  4440.2  895.75
  4486.1  892.69  4530.6  886.30  4726.5  869.95  4800.9  867.40  4944.1  869.98
  4972.5  868.60  4990.0  860.70  4992.9  856.51  4994.9  856.01  5010.0  856.51
  5012.6  862.06  5026.5  868.82  5040.5  869.81  5085.2  867.94  5241.8  868.01
  5353.6  872.76  5375.9  874.70  5398.3  879.15  5465.4  884.56  5482.1  888.33
  5540.8  890.11  5571.6  896.82  5593.9  897.44  5652.6  907.79  5675.0  909.61
#Mann=3,-1,0
  4288.3    0.05       0  4992.9   0.033       0  5010.0    0.05       0
Bank Sta=4992.9,5010
Exp/Cntr=0.3,0.1

Type RM Length L Ch R = 1,36925,429,429,429
BEGIN DESCRIPTION:
Black Creek 44.0
END DESCRIPTION:
XS GIS Cut Line= 3
      2259429.00      7170359.95      2259379.00      7169810.00
      2259829.00      7169010.00
#Sta/Elev= 30
  4447.8  901.40  4477.9  893.50  4508.0  889.78  4767.9  869.93  4799.2  864.55
  4949.8  868.92  4959.9  866.51  4981.3  856.82  4983.3  856.32  4998.7  856.82
  5000.0  861.20  5002.9  861.20  5008.0  865.38  5023.0  868.81  5122.8  867.02
  5412.7  865.28  5424.5  865.40  5434.4  868.38  5499.4  866.56  5596.3  870.29
  5623.7  872.32  5645.4  877.26  5698.9  879.51  5711.4  883.69  5726.4  881.63
  5757.3  886.92  5769.7  891.18  5807.3  893.29  5916.8  906.36  5917.9  906.36
#Mann=6,-1,0
  4447.8    0.05       0  4767.9    0.12       0  4981.3    0.07       0
  4998.7    0.12       0  5122.8    0.05       0  5916.8    0.12       0
Bank Sta=4981.3,4998.7
Exp/Cntr=0.3,0.1

Type RM Length L Ch R = 1,36496,754,754,754
BEGIN DESCRIPTION:
Mapping XS d5c00026
END DESCRIPTION:
XS GIS Cut Line= 2
      2259646.24      7170495.63      2259957.33      7169173.54
#Sta/Elev= 30
  4295.4  903.83  4333.2  902.66  4342.3  901.21  4370.5  892.68  4403.9  887.64
  4516.4  877.52  4537.5  877.17  4545.1  875.36  4550.2  875.98  4592.6  872.30
  4640.2  866.96  4671.0  866.63  4677.4  865.11  4701.8  863.85  4784.0  863.73
  4961.5  866.45  4984.3  866.79  5023.0  858.12  5025.0  857.62  5040.6  858.12
  5040.9  859.38  5061.4  865.72  5074.1  866.54  5111.4  865.07  5286.0  865.88
  5359.3  868.41  5451.7  874.99  5508.2  878.49  5616.1  888.48  5653.6  890.19
#Mann=6,-1,0
  4295.4    0.05       0  4516.4    0.12       0  4961.5    0.05       0
  5023.0   0.033       0  5040.6    0.05       0  5451.7    0.12       0
Bank Sta=5023,5040.6
Exp/Cntr=0.3,0.1

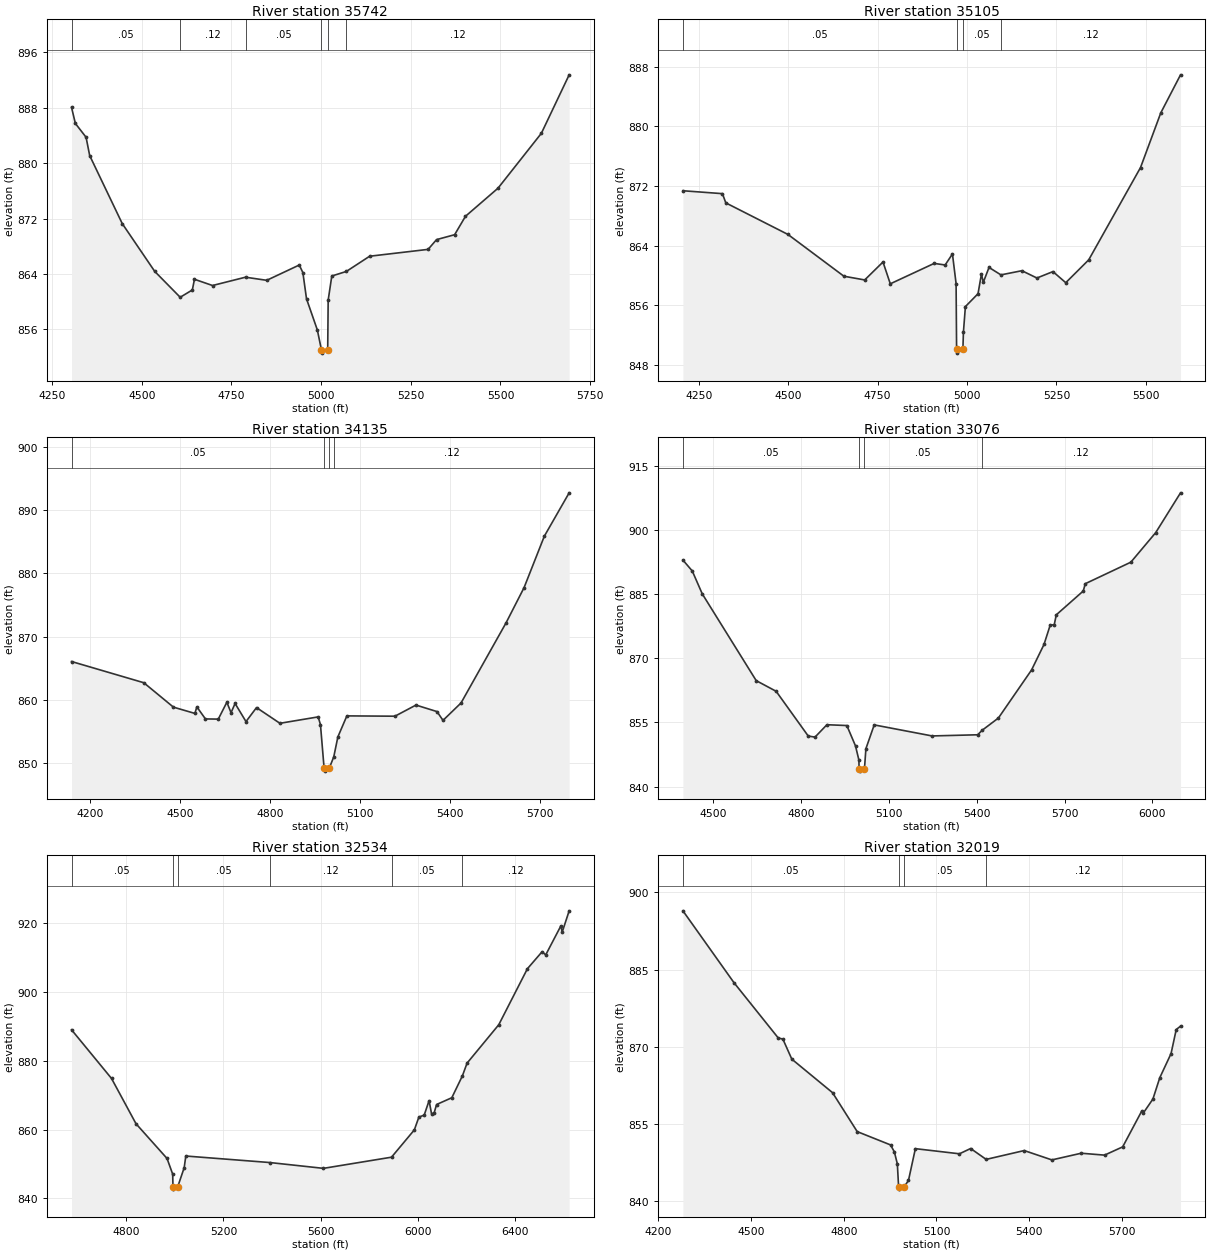
Type RM Length L Ch R = 1,35742,637,637,637
BEGIN DESCRIPTION:
Mapping XS 8018516c
END DESCRIPTION:
XS GIS Cut Line= 2
      2260343.27      7170800.22      2260511.50      7169423.06
#Sta/Elev= 30
  4304.2  888.06  4314.9  885.74  4344.7  883.75  4354.8  881.10  4445.5  871.28
  4536.1  864.37  4607.1  860.63  4641.0  861.69  4646.9  863.23  4697.3  862.33
  4789.2  863.53  4848.4  863.08  4939.1  865.29  4949.2  864.19  4959.3  860.41
  4989.5  855.91  5000.8  853.06  5002.8  852.56  5018.4  853.06  5019.7  860.20
  5029.8  863.70  5070.3  864.36  5135.3  866.56  5298.3  867.55  5321.9  868.96
  5372.3  869.67  5402.5  872.33  5493.2  876.39  5614.1  884.32  5691.6  892.77
#Mann=6,-1,0
  4304.2    0.05       0  4607.1    0.12       0  4789.2    0.05       0
  5000.8   0.033       0  5018.4    0.05       0  5070.3    0.12       0
Bank Sta=5000.8,5018.4
Exp/Cntr=0.3,0.1

Type RM Length L Ch R = 1,35105,970,970,970
BEGIN DESCRIPTION:
Mapping XS 05972e3b
END DESCRIPTION:
XS GIS Cut Line= 2
      2260822.31      7171087.36      2261106.98      7169726.00
#Sta/Elev= 30
  4205.9  871.37  4316.3  870.98  4325.8  869.74  4499.5  865.50  4655.8  859.89
  4714.0  859.39  4765.1  861.80  4785.5  858.87  4908.1  861.61  4938.8  861.40
  4959.2  862.88  4969.4  858.90  4970.8  850.06  4972.8  849.56  4988.4  850.06
  4989.9  852.39  4995.4  855.81  5030.7  857.54  5040.3  860.20  5045.4  859.06
  5061.4  861.07  5094.7  860.07  5153.3  860.63  5195.3  859.65  5240.1  860.51
  5275.9  859.02  5340.1  862.09  5484.9  874.49  5541.5  881.83  5596.7  886.94
#Mann=4,-1,0
  4205.9    0.05       0  4970.8   0.033       0  4988.4    0.05       0
  5094.7    0.12       0
Bank Sta=4970.8,4988.4
Exp/Cntr=0.3,0.1

Type RM Length L Ch R = 1,34135,1059,1059,1059
BEGIN DESCRIPTION:
Black Creek 39.0
END DESCRIPTION:
XS GIS Cut Line= 3
      2261177.42      7171167.63      2261729.00      7170510.00
      2261679.00      7169709.99
#Sta/Elev= 30
  4137.2  866.08  4378.2  862.73  4477.1  858.87  4548.6  857.88  4555.2  858.91
  4583.8  857.01  4626.7  856.98  4655.3  859.65  4669.2  857.99  4682.7  859.45
  4719.1  856.59  4754.2  858.80  4832.3  856.32  4959.8  857.33  4967.5  856.11
  4979.6  849.26  4981.6  848.76  4997.2  849.26  5011.9  851.02  5025.6  854.17
  5055.6  857.49  5216.0  857.44  5286.1  859.20  5356.2  858.17  5376.3  856.78
  5436.4  859.53  5586.7  872.20  5646.8  877.77  5714.4  885.90  5797.1  892.74
#Mann=4,-1,0
  4137.2    0.05       0  4979.6   0.033       0  4997.2    0.05       0
  5011.9    0.12       0
Bank Sta=4979.6,4997.2
Exp/Cntr=0.3,0.1

Type RM Length L Ch R = 1,33076,542,542,542
BEGIN DESCRIPTION:
Black Creek 38.0
END DESCRIPTION:
XS GIS Cut Line= 3
      2263179.04      7170510.02      2262629.00      7170260.00
      2261878.99      7169459.99
#Sta/Elev= 30
  4395.8  892.92  4427.7  890.38  4461.8  885.04  4646.3  864.76  4714.4  862.27
  4824.2  851.81  4847.3  851.57  4888.0  854.46  4956.1  854.27  4985.7  849.50
  4997.3  846.20  4997.9  844.12  4999.9  843.62  5016.3  844.12  5021.2  848.86
  5049.6  854.42  5247.4  851.84  5403.2  852.11  5418.5  853.16  5474.0  856.02
  5587.4  867.25  5629.9  873.20  5650.9  877.68  5665.0  877.84  5671.9  880.13
  5764.2  885.70  5771.0  887.40  5926.8  892.43  6011.8  899.34  6096.6  908.63
#Mann=4,-1,0
  4395.8    0.05       0  4997.9   0.033       0  5016.3    0.05       0
  5418.5    0.12       0
Bank Sta=4997.9,5016.3
Exp/Cntr=0.3,0.1

Type RM Length L Ch R = 1,32534,515,515,515
BEGIN DESCRIPTION:
Black Creek 37.0
END DESCRIPTION:
XS GIS Cut Line= 3
      2263329.01      7170360.01      2263079.00      7170010.00
      2262829.01      7168410.04
#Sta/Elev= 30
  4574.6  888.96  4739.3  874.83  4840.1  861.69  4967.9  851.61  4991.2  847.05
  4992.4  843.21  4994.4  842.71  5011.0  843.21  5038.6  848.94  5045.2  852.32
  5390.9  850.43  5612.0  848.74  5892.4  851.98  5986.5  859.91  6005.2  863.63
  6027.0  864.19  6047.2  868.39  6057.3  864.58  6067.5  864.73  6078.1  867.27
  6140.8  869.24  6184.4  875.59  6203.6  879.28  6334.2  890.43  6452.1  906.68
  6512.8  911.63  6527.5  910.69  6590.2  919.15  6595.3  917.28  6624.1  923.49
#Mann=6,-1,0
  4574.6    0.05       0  4992.4   0.033       0  5011.0    0.05       0
  5390.9    0.12       0  5892.4    0.05       0  6184.4    0.12       0
Bank Sta=4992.4,5011
Exp/Cntr=0.3,0.1

Type RM Length L Ch R = 1,32019,320,320,320
BEGIN DESCRIPTION:
Black Creek 36.0
END DESCRIPTION:
XS GIS Cut Line= 3
      2263729.00      7170360.01      2263429.00      7169710.00
      2263029.01      7168910.02
#Sta/Elev= 30
  4279.5  896.43  4444.7  882.44  4587.9  871.68  4603.0  871.45  4631.9  867.55
  4763.7  861.02  4843.5  853.44  4951.3  850.85  4963.7  849.50  4973.4  847.15
  4977.4  842.74  4979.4  842.24  4996.0  842.74  5009.4  843.93  5031.7  850.12
  5174.3  849.12  5210.6  850.15  5260.8  848.03  5383.9  849.75  5473.4  847.93
  5568.4  849.23  5643.9  848.86  5702.6  850.47  5764.0  857.41  5769.6  857.08
  5800.4  859.78  5822.7  863.94  5859.1  868.63  5875.9  873.32  5889.8  873.97
#Mann=4,-1,0
  4279.5    0.05       0  4977.4   0.033       0  4996.0    0.05       0
  5260.8    0.12       0
Bank Sta=4977.4,4996
Exp/Cntr=0.3,0.1

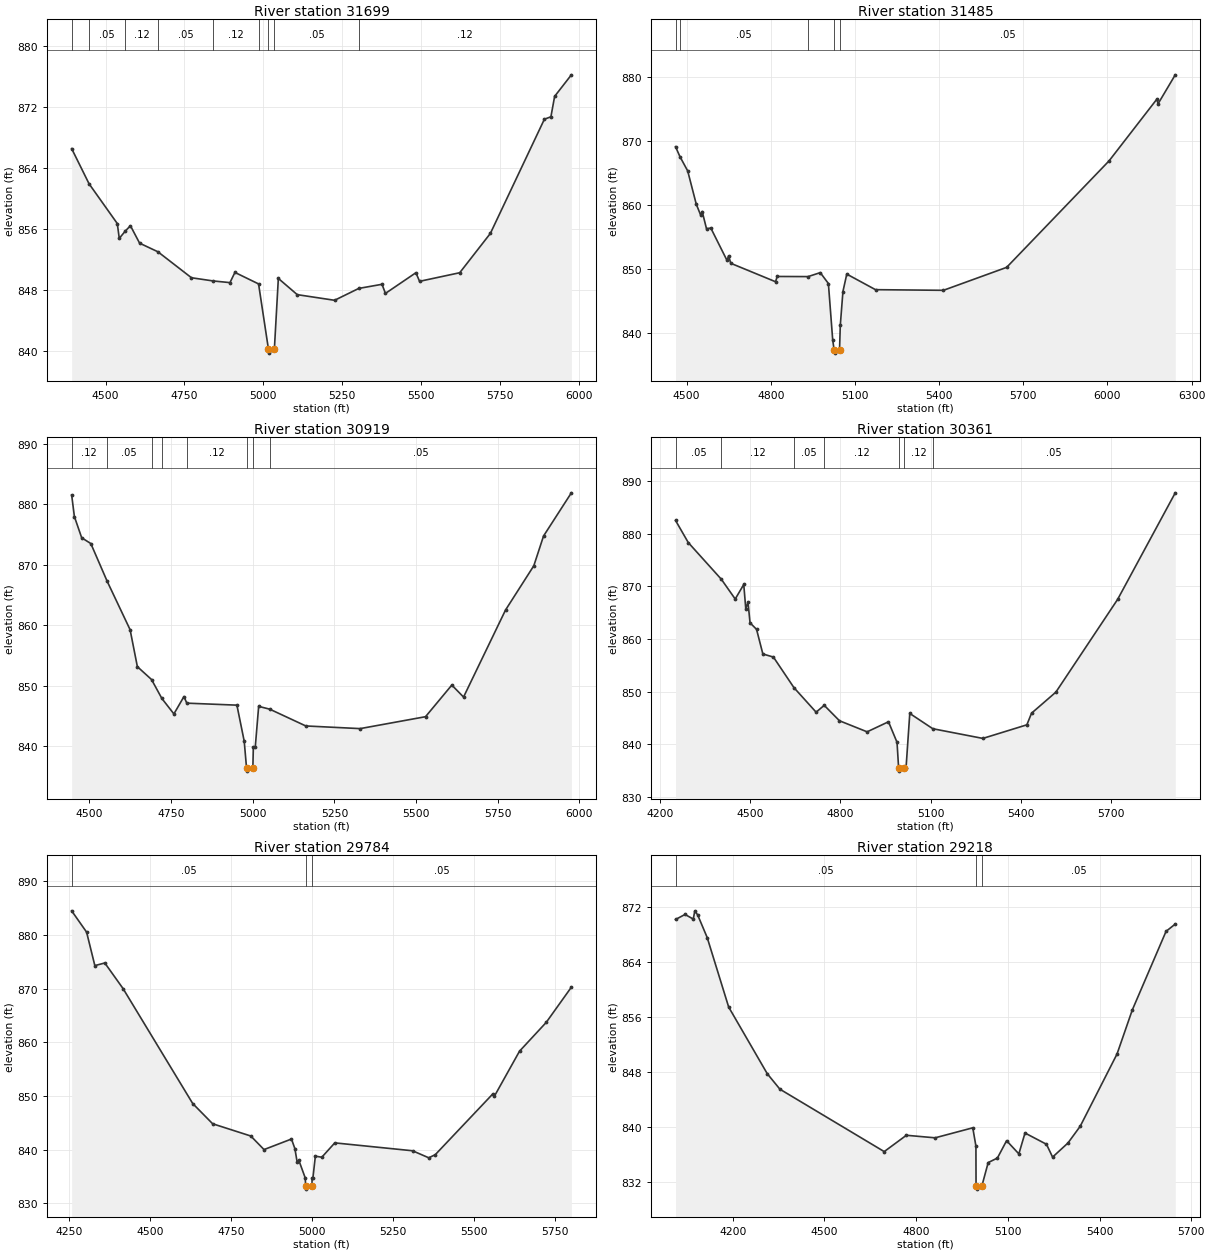
Type RM Length L Ch R = 1,31699,214,214,214
BEGIN DESCRIPTION:
Mapping XS 11ff3232
END DESCRIPTION:
XS GIS Cut Line= 5
      2264044.65      7170055.97      2263754.56      7169672.34
      2263603.08      7169390.43      2263452.53      7169008.11
      2263359.91      7168647.09
#Sta/Elev= 30
  4392.5  866.56  4447.7  861.94  4537.2  856.72  4543.5  854.77  4563.2  855.76
  4578.9  856.43  4608.0  854.14  4666.0  853.01  4772.4  849.60  4841.0  849.18
  4894.5  848.96  4910.2  850.30  4985.2  848.79  5016.6  840.20  5018.6  839.70
  5035.3  840.20  5047.9  849.51  5107.9  847.38  5226.2  846.64  5303.1  848.20
  5376.7  848.74  5387.4  847.54  5484.1  850.26  5495.7  849.13  5623.1  850.26
  5720.2  855.42  5891.5  870.42  5912.2  870.74  5924.0  873.42  5977.1  876.25
#Mann=9,-1,0
  4392.5    0.12       0  4447.7    0.05       0  4563.2    0.12       0
  4666.0    0.05       0  4841.0    0.12       0  4985.2    0.05       0
  5016.6   0.033       0  5035.3    0.05       0  5303.1    0.12       0
Bank Sta=5016.6,5035.3
Exp/Cntr=0.3,0.1

Type RM Length L Ch R = 1,31485,566,566,566
BEGIN DESCRIPTION:
Mapping XS 5884e46e
END DESCRIPTION:
XS GIS Cut Line= 4
      2264164.06      7169966.43      2263813.07      7169409.06
      2263595.77      7168935.22      2263604.93      7168334.26
#Sta/Elev= 30
  4460.6  869.09  4476.4  867.53  4503.9  865.31  4534.5  860.12  4549.8  858.45
  4555.7  858.97  4571.0  856.28  4586.3  856.40  4644.0  851.35  4649.9  852.07
  4657.3  850.90  4817.0  848.02  4823.0  848.84  4933.0  848.82  4976.4  849.44
  5005.4  847.74  5020.7  838.96  5025.8  837.38  5027.8  836.88  5045.1  837.38
  5047.8  841.22  5057.2  846.49  5070.9  849.21  5173.3  846.78  5415.3  846.68
  5640.6  850.26  6005.8  866.88  6175.6  876.48  6180.6  875.80  6241.6  880.30
#Mann=5,-1,0
  4460.6    0.12       0  4476.4    0.05       0  4933.0    0.12       0
  5025.8    0.07       0  5045.1    0.05       0
Bank Sta=5025.8,5045.1
Exp/Cntr=0.3,0.1

Type RM Length L Ch R = 1,30919,558,558,558
BEGIN DESCRIPTION:
Black Creek 35.0
END DESCRIPTION:
XS GIS Cut Line= 3
      2264179.00      7170060.00      2264429.00      7169560.00
      2265228.97      7169010.02
#Sta/Elev= 30
  4445.5  881.58  4453.9  878.00  4476.2  874.50  4504.2  873.54  4554.0  867.33
  4624.4  859.30  4646.7  853.18  4690.0  851.06  4721.6  847.93  4758.5  845.37
  4789.3  848.24  4798.0  847.15  4951.4  846.82  4973.8  840.85  4980.9  836.41
  4982.9  835.91  5000.2  836.41  5001.7  839.84  5007.5  839.84  5018.0  846.62
  5052.1  846.15  5162.3  843.38  5328.6  842.94  5528.8  844.91  5609.3  850.14
  5645.2  848.16  5773.7  862.55  5860.3  869.87  5890.1  874.79  5975.3  881.93
#Mann=8,-1,0
  4445.5    0.12       0  4554.0    0.05       0  4690.0    0.12       0
  4721.6    0.05       0  4798.0    0.12       0  4980.9    0.07       0
  5000.2    0.12       0  5052.1    0.05       0
Bank Sta=4980.9,5000.2
Exp/Cntr=0.3,0.1

Type RM Length L Ch R = 1,30361,577,577,577
BEGIN DESCRIPTION:
Black Creek 34.0
END DESCRIPTION:
XS GIS Cut Line= 3
      2264328.97      7170310.03      2264879.00      7169810.00
      2265328.99      7169010.02
#Sta/Elev= 30
  4251.7  882.53  4294.0  878.33  4404.0  871.36  4450.1  867.61  4478.5  870.37
  4485.2  865.76  4492.6  867.00  4499.4  863.09  4521.0  861.86  4542.0  857.18
  4577.1  856.59  4645.3  850.79  4719.0  846.13  4746.0  847.43  4796.7  844.50
  4888.6  842.40  4959.6  844.31  4988.0  840.41  4993.4  835.44  4995.4  834.94
  5012.7  835.44  5018.0  835.58  5030.4  845.89  5106.9  842.99  5273.3  841.15
  5419.6  843.73  5435.2  845.94  5516.1  849.94  5721.4  867.55  5912.9  887.77
#Mann=7,-1,0
  4251.7    0.05       0  4404.0    0.12       0  4645.3    0.05       0
  4746.0    0.12       0  4993.4    0.07       0  5012.7    0.12       0
  5106.9    0.05       0
Bank Sta=4993.4,5012.7
Exp/Cntr=0.3,0.1

Type RM Length L Ch R = 1,29784,566,566,566
BEGIN DESCRIPTION:
Black Creek 33.0
END DESCRIPTION:
XS GIS Cut Line= 3
      2265078.99      7170710.03      2265329.00      7170010.00
      2265379.00      7169209.99
#Sta/Elev= 30
  4257.1  884.49  4303.3  880.52  4328.8  874.28  4359.6  874.77  4415.9  870.01
  4631.4  848.57  4693.0  844.80  4810.9  842.52  4851.8  839.99  4936.7  841.96
  4947.3  840.15  4954.2  837.67  4959.5  837.98  4979.2  834.71  4980.7  833.12
  4982.7  832.62  5000.0  833.12  5000.4  834.67  5002.9  834.67  5010.5  838.76
  5030.5  838.57  5070.6  841.24  5311.0  839.77  5361.1  838.46  5381.2  839.04
  5559.0  850.36  5564.0  849.94  5641.7  858.33  5724.3  863.70  5802.0  870.26
#Mann=3,-1,0
  4257.1    0.05       0  4980.7   0.035       0  5000.0    0.05       0
Bank Sta=4980.7,5000
Exp/Cntr=0.3,0.1

Type RM Length L Ch R = 1,29218,579,579,579
BEGIN DESCRIPTION:
Black Creek 32.0
END DESCRIPTION:
XS GIS Cut Line= 3
      2265578.99      7170860.05      2265829.00      7169910.00
      2265879.00      7169260.01
#Sta/Elev= 30
  4013.2  870.25  4044.3  870.98  4071.2  870.31  4076.3  871.51  4085.6  870.91
  4116.7  867.62  4187.0  857.48  4313.1  847.77  4354.5  845.51  4695.7  836.41
  4768.1  838.79  4862.2  838.42  4985.3  839.88  4995.6  837.21  4996.0  831.44
  4998.0  830.94  5015.3  831.44  5035.7  834.81  5065.8  835.47  5095.9  838.00
  5136.0  836.08  5156.1  839.12  5226.3  837.48  5246.3  835.61  5296.5  837.66
  5336.6  840.10  5457.0  850.63  5507.1  857.07  5617.4  868.52  5647.5  869.58
#Mann=3,-1,0
  4013.2    0.05       0  4996.0   0.035       0  5015.3    0.05       0
Bank Sta=4996,5015.3
Exp/Cntr=0.3,0.1

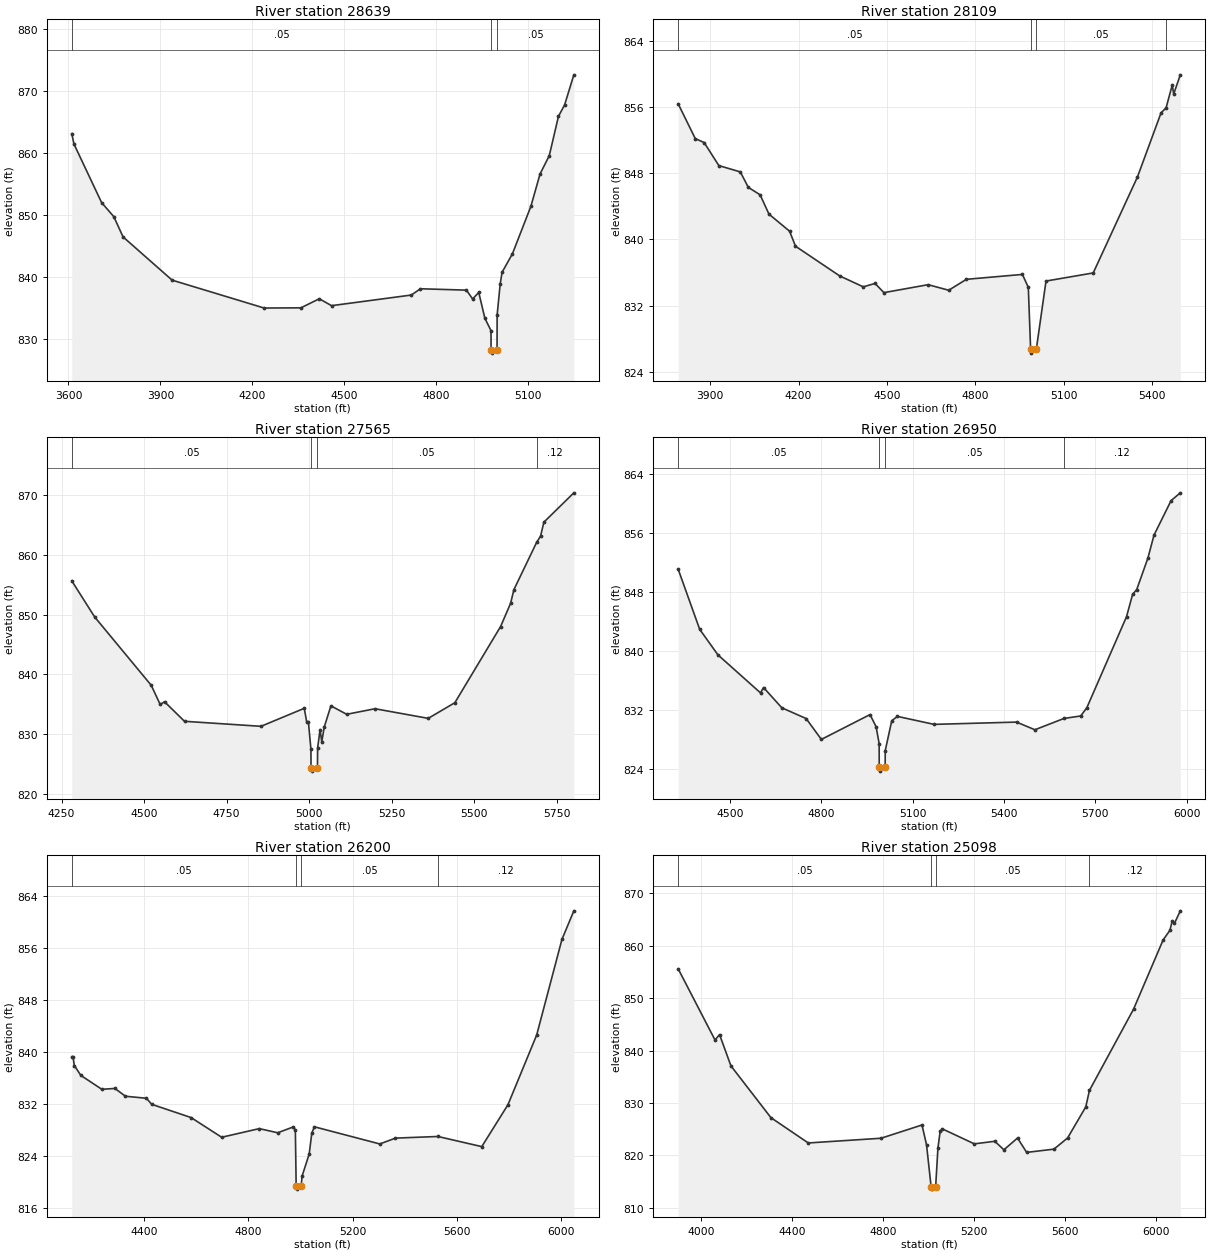
Type RM Length L Ch R = 1,28639,530,530,530
BEGIN DESCRIPTION:
Mapping XS c09dccb5
END DESCRIPTION:
XS GIS Cut Line= 2
      2266216.08      7170997.23      2266283.60      7169359.82
#Sta/Elev= 30
  3610.7  863.13  3617.9  861.46  3708.0  852.04  3748.0  849.76  3778.1  846.51
  3938.2  839.55  4238.5  835.06  4358.6  835.09  4418.6  836.55  4458.6  835.44
  4718.9  837.15  4748.9  838.16  4899.0  837.94  4919.0  836.52  4939.1  837.57
  4959.1  833.41  4979.1  831.42  4979.3  828.30  4981.3  827.80  4998.8  828.30
  4999.1  833.93  5009.1  838.93  5015.3  840.82  5049.2  843.81  5109.2  851.42
  5139.2  856.64  5169.3  859.59  5199.3  865.92  5219.3  867.75  5249.5  872.60
#Mann=3,-1,0
  3610.7    0.05       0  4979.3   0.033       0  4998.8    0.05       0
Bank Sta=4979.3,4998.8
Exp/Cntr=0.3,0.1

Type RM Length L Ch R = 1,28109,544,544,544
BEGIN DESCRIPTION:
Black Creek 30.0
END DESCRIPTION:
XS GIS Cut Line= 3
      2266648.79      7171067.84      2266679.00      7169860.00
      2266705.30      7169364.82
#Sta/Elev= 30
  3791.7  856.36  3849.6  852.17  3879.6  851.70  3929.6  848.91  4002.4  848.15
  4029.6  846.28  4069.6  845.38  4099.6  843.05  4169.7  840.98  4189.7  839.17
  4339.7  835.58  4419.7  834.26  4459.7  834.67  4489.8  833.56  4639.8  834.52
  4709.8  833.85  4769.8  835.17  4959.9  835.76  4979.9  834.19  4987.7  826.75
  4989.7  826.25  5007.2  826.75  5040.0  834.96  5200.2  835.94  5350.4  847.54
  5430.5  855.29  5447.5  855.89  5468.4  858.64  5473.4  857.57  5495.8  859.88
#Mann=4,-1,0
  3791.7    0.05       0  4987.7   0.035       0  5007.2    0.05       0
  5447.5    0.12       0
Bank Sta=4987.7,5007.2
Exp/Cntr=0.3,0.1

Type RM Length L Ch R = 1,27565,615,615,615
BEGIN DESCRIPTION:
Black Creek 29.0
END DESCRIPTION:
XS GIS Cut Line= 3
      2267040.62      7170818.73      2267129.00      7170110.00
      2267028.99      7169309.95
#Sta/Elev= 30
  4281.1  855.63  4350.4  849.59  4521.7  838.17  4548.9  834.96  4562.0  835.42
  4622.5  832.15  4854.2  831.31  4985.2  834.32  4992.8  831.98  4997.8  831.98
  5005.4  827.47  5005.7  824.32  5007.7  823.82  5025.2  824.32  5025.6  827.66
  5033.1  830.76  5038.2  828.72  5045.7  831.19  5065.9  834.73  5113.7  833.32
  5199.4  834.25  5360.6  832.64  5441.3  835.26  5579.8  847.99  5610.1  851.88
  5620.1  854.16  5689.1  862.08  5700.8  863.10  5710.9  865.44  5801.6  870.34
#Mann=4,-1,0
  4281.1    0.05       0  5005.7   0.033       0  5025.2    0.05       0
  5689.1    0.12       0
Bank Sta=5005.7,5025.2
Exp/Cntr=0.3,0.1

Type RM Length L Ch R = 1,26950,750,750,750
BEGIN DESCRIPTION:
Black Creek 28.0
END DESCRIPTION:
XS GIS Cut Line= 3
      2267708.62      7170880.35      2267712.01      7170205.07
      2267796.57      7169233.83
#Sta/Elev= 30
  4329.3  851.06  4399.7  842.94  4459.7  839.47  4599.7  834.31  4609.7  835.04
  4669.7  832.29  4749.7  830.83  4799.7  828.00  4959.7  831.37  4979.7  829.71
  4989.7  827.43  4989.9  824.20  4991.9  823.70  5009.4  824.20  5009.7  826.49
  5031.1  830.54  5049.8  831.12  5170.3  830.04  5441.3  830.35  5501.5  829.31
  5596.9  830.84  5652.1  831.18  5672.2  832.29  5802.7  844.64  5822.7  847.67
  5836.2  848.32  5872.9  852.58  5893.0  855.70  5949.1  860.38  5979.5  861.44
#Mann=4,-1,0
  4329.3    0.05       0  4989.9    0.04       0  5009.4    0.05       0
  5596.9    0.12       0
Bank Sta=4989.9,5009.4
Exp/Cntr=0.3,0.1

Type RM Length L Ch R = 1,26200,1102,1102,1102
BEGIN DESCRIPTION:
Mapping XS 05af503d
END DESCRIPTION:
XS GIS Cut Line= 3
      2268475.06      7170984.49      2268381.51      7170107.43
      2268321.46      7169067.90
#Sta/Elev= 30
  4124.3  839.29  4129.1  839.29  4134.1  837.94  4159.0  836.42  4239.4  834.28
  4289.7  834.41  4330.0  833.21  4410.4  832.90  4430.5  831.97  4581.4  829.93
  4698.5  826.90  4842.8  828.23  4913.2  827.59  4973.6  828.50  4980.8  828.00
  4983.9  819.42  4985.9  818.92  5003.4  819.42  5006.3  820.89  5033.8  824.32
  5043.8  827.54  5053.8  828.51  5304.3  825.87  5364.4  826.77  5526.8  827.02
  5694.9  825.46  5795.1  831.90  5905.3  842.64  6002.0  857.34  6047.6  861.74
#Mann=4,-1,0
  4124.3    0.05       0  4983.9   0.035       0  5003.4    0.05       0
  5526.8    0.12       0
Bank Sta=4983.9,5003.4
Exp/Cntr=0.3,0.1

Type RM Length L Ch R = 1,25098,718,718,718
BEGIN DESCRIPTION:
Mapping XS 5105ae7b
END DESCRIPTION:
XS GIS Cut Line= 3
      2269365.68      7171061.73      2269361.25      7169983.79
      2269350.05      7168854.39
#Sta/Elev= 30
  3898.3  855.57  4060.0  842.01  4080.0  843.04  4130.0  837.07  4305.8  827.19
  4470.0  822.36  4790.0  823.26  4970.0  825.79  4990.0  822.00  5010.0  814.05
  5012.0  813.55  5030.1  814.05  5040.0  821.37  5050.0  824.60  5060.0  825.04
  5200.0  822.19  5290.0  822.68  5330.1  821.06  5390.1  823.30  5430.1  820.56
  5550.1  821.18  5610.1  823.31  5690.1  829.25  5706.2  832.39  5900.1  847.89
  6030.1  861.10  6060.1  862.94  6070.1  864.75  6080.1  864.28  6105.7  866.66
#Mann=4,-1,0
  3898.3    0.05       0  5010.0    0.04       0  5030.1    0.05       0
  5706.2    0.12       0
Bank Sta=5010,5030.1
Exp/Cntr=0.3,0.1