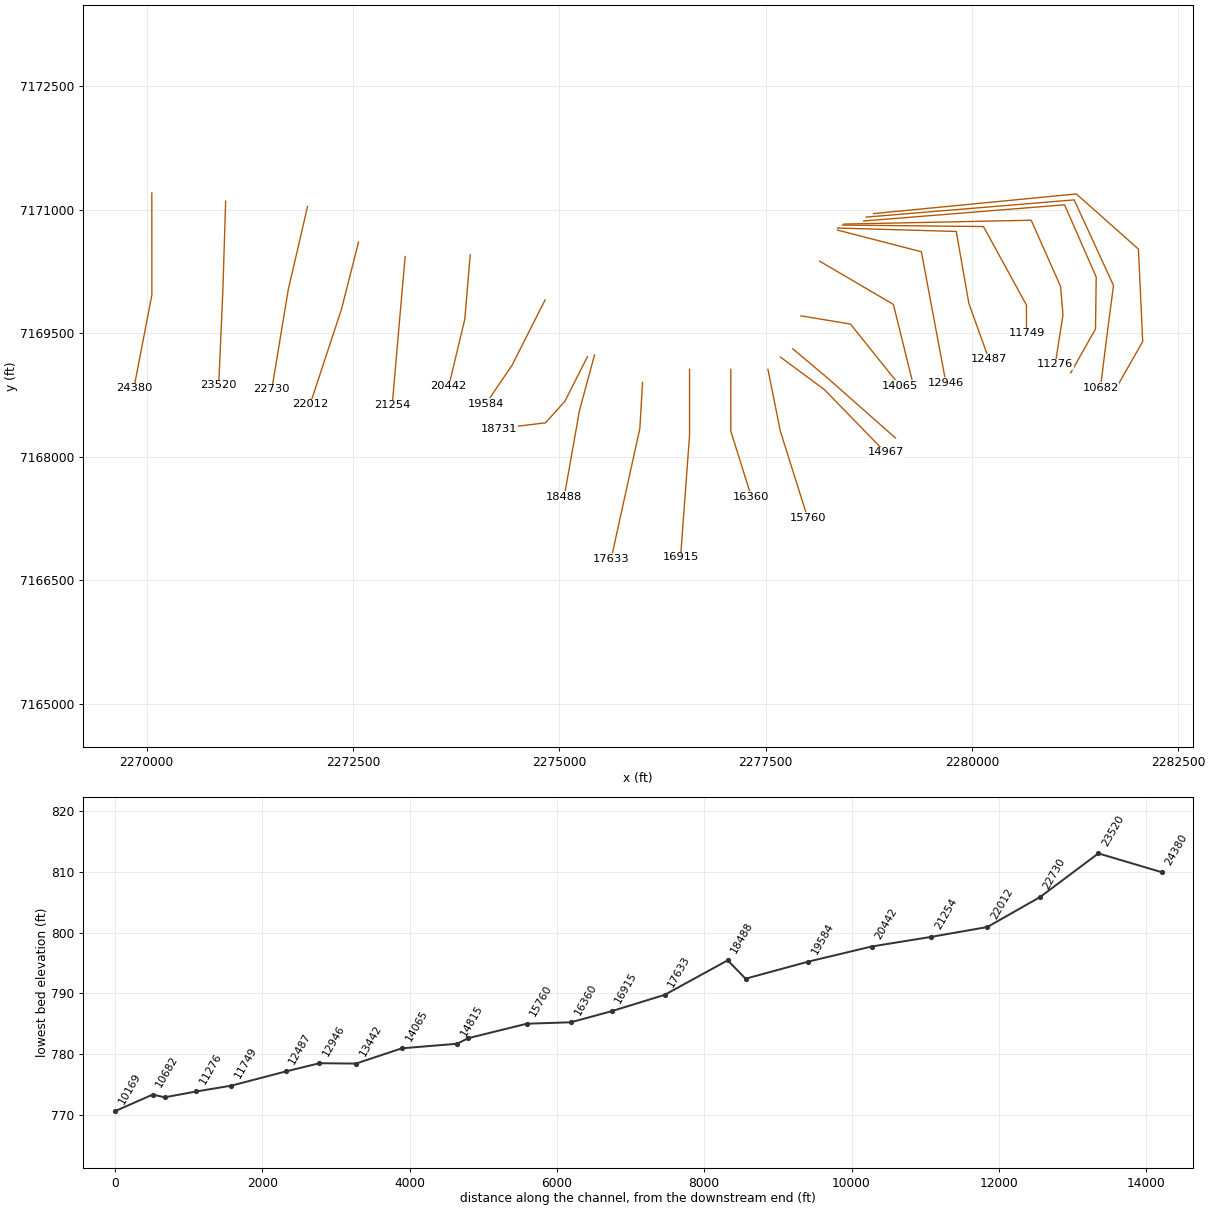
HEC-RAS study Black Creek.prj: Black Creek Base Level Engineering

--- Black Creek.g01 (geometry) --- (continued)

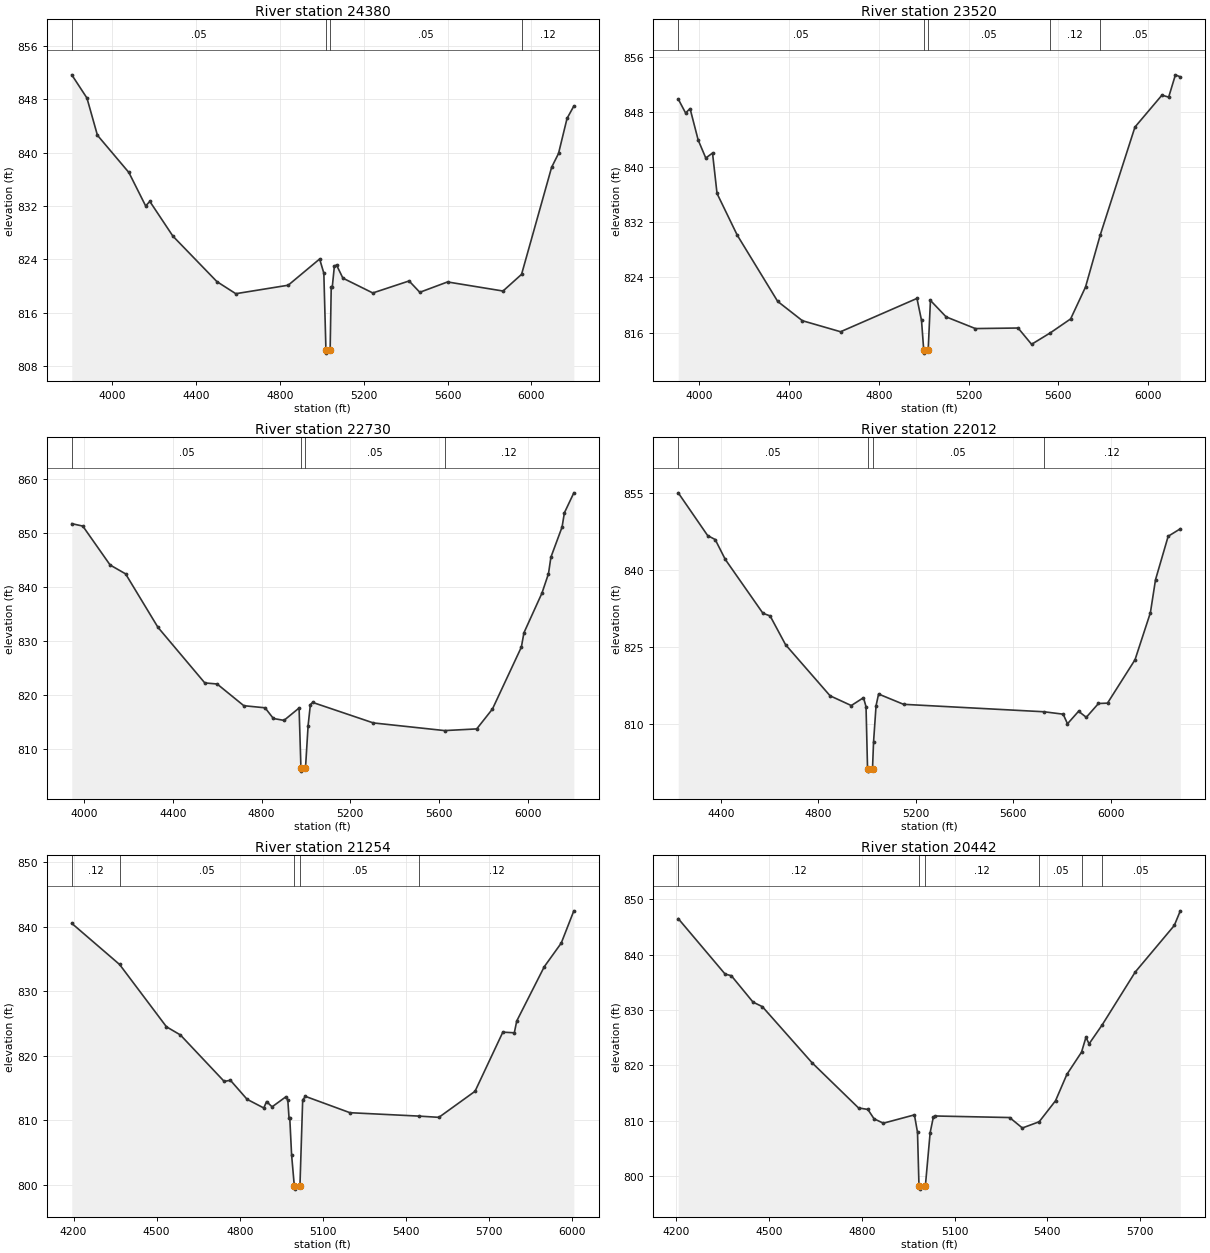
Type RM Length L Ch R = 1,24380,860,860,860
BEGIN DESCRIPTION:
Mapping XS 9e1029b6
END DESCRIPTION:
XS GIS Cut Line= 3
      2270061.99      7171202.41      2270062.73      7169964.40
      2269844.48      7168828.18
#Sta/Elev= 30
  3807.6  851.65  3880.0  848.17  3930.0  842.59  4080.0  837.01  4160.0  832.00
  4180.0  832.67  4290.0  827.47  4500.0  820.65  4590.0  818.84  4840.0  820.11
  4990.0  824.04  5010.0  821.91  5020.0  810.43  5022.0  809.93  5040.1  810.43
  5045.3  819.88  5050.4  819.88  5060.3  822.98  5070.5  823.14  5101.0  821.17
  5243.6  818.95  5416.7  820.75  5467.8  819.05  5600.0  820.60  5864.7  819.24
  5953.2  821.74  6096.5  837.78  6129.5  839.86  6170.2  845.12  6202.6  846.97
#Mann=4,-1,0
  3807.6    0.05       0  5020.0   0.033       0  5040.1    0.05       0
  5953.2    0.12       0
Bank Sta=5020,5040.1
Exp/Cntr=0.3,0.1

Type RM Length L Ch R = 1,23520,790,790,790
BEGIN DESCRIPTION:
Mapping XS b985eca1
END DESCRIPTION:
XS GIS Cut Line= 3
      2270956.78      7171102.67      2270923.34      7170024.45
      2270872.47      7168868.21
#Sta/Elev= 30
  3906.8  849.85  3939.5  847.83  3959.5  848.46  3995.6  843.91  4029.5  841.30
  4059.5  842.02  4079.6  836.16  4169.6  830.12  4349.7  820.52  4459.7  817.72
  4629.8  816.12  4970.0  820.95  4990.3  817.77  5000.0  813.52  5002.0  813.02
  5020.1  813.52  5030.0  820.66  5100.1  818.27  5230.2  816.58  5420.4  816.66
  5480.5  814.30  5564.0  815.96  5654.4  817.98  5720.7  822.60  5786.0  830.11
  5940.9  845.79  6061.0  850.41  6091.1  850.13  6121.1  853.36  6142.9  853.06
#Mann=5,-1,0
  3906.8    0.05       0  5000.0   0.033       0  5020.1    0.05       0
  5564.0    0.12       0  5786.0    0.05       0
Bank Sta=5000,5020.1
Exp/Cntr=0.3,0.1

Type RM Length L Ch R = 1,22730,718,718,718
BEGIN DESCRIPTION:
Mapping XS 8fa72f2c
END DESCRIPTION:
XS GIS Cut Line= 3
      2271949.35      7171038.46      2271715.45      7170027.60
      2271516.13      7168817.98
#Sta/Elev= 30
  3944.6  851.70  3994.3  851.25  4117.5  844.04  4187.2  842.40  4333.1  832.50
  4544.3  822.20  4599.9  822.00  4720.2  817.98  4815.9  817.59  4853.5  815.61
  4901.3  815.26  4969.4  817.55  4977.8  806.36  4979.8  805.86  4998.2  806.36
  5010.1  814.31  5020.3  818.18  5030.4  818.59  5304.1  814.79  5625.5  813.37
  5770.3  813.68  5841.2  817.37  5971.5  828.83  5983.1  831.49  6064.2  838.82
  6093.8  842.44  6104.7  845.49  6155.0  851.07  6165.5  853.71  6208.1  857.41
#Mann=4,-1,0
  3944.6    0.05       0  4977.8   0.035       0  4998.2    0.05       0
  5625.5    0.12       0
Bank Sta=4977.8,4998.2
Exp/Cntr=0.3,0.1

Type RM Length L Ch R = 1,22012,758,758,758
BEGIN DESCRIPTION:
Mapping XS 4e94e4aa
END DESCRIPTION:
XS GIS Cut Line= 3
      2272567.50      7170607.06      2272360.85      7169791.29
      2271979.88      7168633.39
#Sta/Elev= 30
  4225.4  855.07  4346.2  846.75  4377.1  845.98  4418.4  842.12  4573.1  831.63
  4602.5  831.12  4666.0  825.51  4848.5  815.58  4935.6  813.68  4985.7  815.21
  4996.1  813.45  5002.3  801.42  5004.3  800.92  5022.7  801.42  5027.0  806.62
  5037.3  813.66  5047.6  815.92  5150.1  813.92  5726.5  812.47  5805.2  812.00
  5822.9  810.13  5868.4  812.57  5900.0  811.39  5950.0  814.08  5987.1  814.15
  6100.0  822.59  6163.1  831.74  6184.2  838.18  6236.1  846.62  6285.9  848.07
#Mann=4,-1,0
  4225.4    0.05       0  5002.3   0.035       0  5022.7    0.05       0
  5726.5    0.12       0
Bank Sta=5002.3,5022.7
Exp/Cntr=0.3,0.1

Type RM Length L Ch R = 1,21254,812,812,812
BEGIN DESCRIPTION:
Mapping XS 7cedd367
END DESCRIPTION:
XS GIS Cut Line= 3
      2273132.39      7170430.61      2273063.53      7169646.44
      2272975.17      7168624.54
#Sta/Elev= 30
  4193.6  840.52  4366.3  834.14  4535.5  824.48  4585.7  823.22  4744.0  816.01
  4766.4  816.19  4826.6  813.24  4886.9  811.89  4896.9  812.89  4917.0  812.07
  4967.2  813.64  4973.8  813.06  4978.1  810.32  4980.8  810.32  4987.3  804.66
  4997.1  799.81  4999.1  799.31  5017.5  799.81  5027.4  813.15  5037.4  813.69
  5198.0  811.16  5448.4  810.63  5519.2  810.44  5649.7  814.48  5750.1  823.65
  5791.6  823.55  5800.3  825.38  5899.8  833.80  5960.9  837.45  6006.5  842.46
#Mann=5,-1,0
  4193.6    0.12       0  4366.3    0.05       0  4997.1   0.035       0
  5017.5    0.05       0  5448.4    0.12       0
Bank Sta=4997.1,5017.5
Exp/Cntr=0.3,0.1

Type RM Length L Ch R = 1,20442,858,858,858
BEGIN DESCRIPTION:
Mapping XS 5b542128
END DESCRIPTION:
XS GIS Cut Line= 3
      2273920.69      7170451.11      2273855.44      7169671.28
      2273660.19      7168853.11
#Sta/Elev= 30
  4206.2  846.47  4357.8  836.47  4377.9  836.18  4448.1  831.42  4478.3  830.60
  4638.8  820.50  4789.3  812.35  4819.4  812.08  4839.5  810.39  4869.6  809.60
  4970.0  811.10  4980.0  807.96  4984.8  798.22  4986.9  797.72  5005.3  798.22
  5020.9  807.90  5031.2  810.69  5037.2  810.90  5277.9  810.62  5319.1  808.74
  5373.5  809.86  5426.4  813.65  5463.0  818.39  5510.4  822.40  5524.7  825.07
  5534.9  823.90  5577.4  827.33  5684.1  836.84  5810.4  845.23  5829.9  847.87
#Mann=6,-1,0
  4206.2    0.12       0  4984.8    0.07       0  5005.3    0.12       0
  5373.5    0.05       0  5510.4    0.12       0  5577.4    0.05       0
Bank Sta=4984.8,5005.3
Exp/Cntr=0.3,0.1

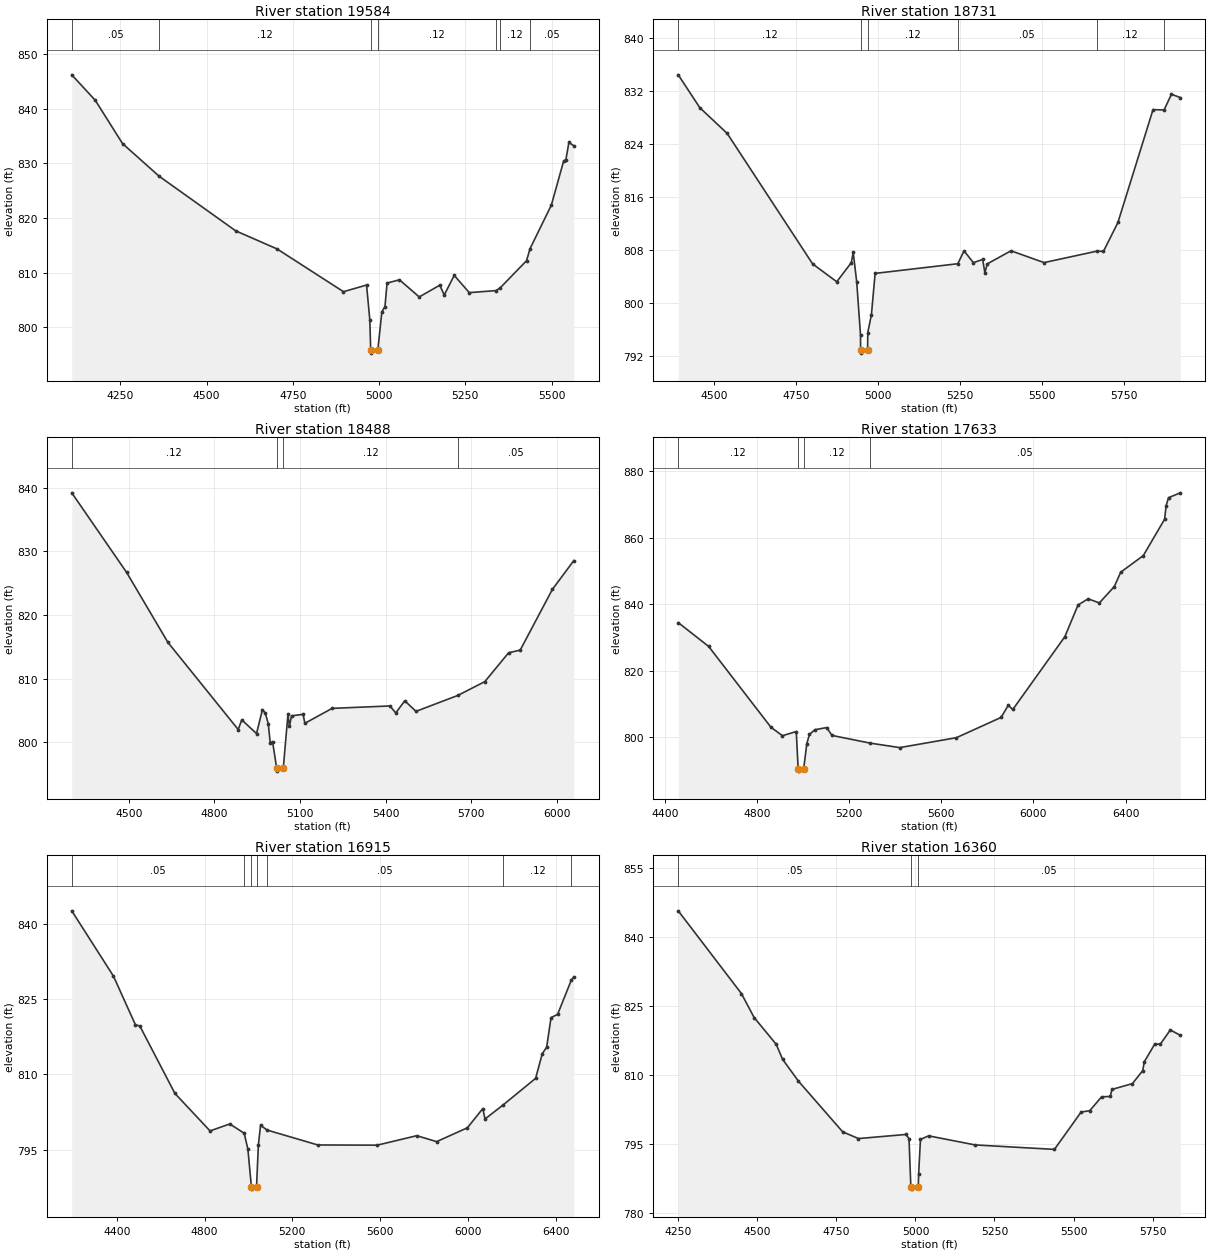
Type RM Length L Ch R = 1,19584,853,853,853
BEGIN DESCRIPTION:
Mapping XS 04f671f5
END DESCRIPTION:
XS GIS Cut Line= 3
      2274827.08      7169901.32      2274427.66      7169109.65
      2274108.72      7168639.07
#Sta/Elev= 30
  4109.4  846.21  4177.7  841.53  4256.5  833.62  4362.6  827.64  4584.7  817.63
  4704.5  814.32  4896.9  806.49  4963.8  807.71  4973.3  801.30  4975.8  795.74
  4977.8  795.24  4996.4  795.74  5008.2  802.85  5017.1  803.72  5023.2  808.07
  5059.1  808.67  5116.5  805.53  5175.9  807.68  5189.0  805.89  5217.9  809.48
  5261.5  806.32  5338.8  806.69  5351.2  807.20  5427.5  812.17  5437.7  814.38
  5499.4  822.35  5535.3  830.48  5541.4  830.62  5550.3  833.83  5564.6  833.21
#Mann=7,-1,0
  4109.4    0.05       0  4362.6    0.12       0  4975.8    0.07       0
  4996.4    0.12       0  5338.8    0.05       0  5351.2    0.12       0
  5437.7    0.05       0
Bank Sta=4975.8,4996.4
Exp/Cntr=0.3,0.1

Type RM Length L Ch R = 1,18731,243,243,243
BEGIN DESCRIPTION:
Mapping XS d950a18b
END DESCRIPTION:
XS GIS Cut Line= 4
      2275342.65      7169215.74      2275066.86      7168670.81
      2274833.31      7168410.84      2274266.41      7168341.84
#Sta/Elev= 30
  4390.0  834.42  4455.8  829.46  4539.3  825.58  4799.9  805.89  4873.5  803.20
  4918.0  806.09  4923.7  807.63  4934.4  803.14  4945.9  795.20  4946.2  792.93
  4948.3  792.43  4967.5  792.93  4968.2  795.54  4979.2  798.24  4990.5  804.46
  5242.7  805.92  5261.7  807.86  5290.1  806.08  5318.5  806.56  5325.2  804.57
  5332.7  805.90  5404.9  807.87  5505.7  806.09  5666.1  807.81  5687.0  807.79
  5731.0  812.14  5838.1  829.17  5871.8  829.12  5894.3  831.49  5921.3  830.99
#Mann=6,-1,0
  4390.0    0.12       0  4946.2    0.07       0  4967.5    0.12       0
  5242.7    0.05       0  5666.1    0.12       0  5871.8    0.05       0
Bank Sta=4946.2,4967.5
Exp/Cntr=0.3,0.1

Type RM Length L Ch R = 1,18488,855,855,855
BEGIN DESCRIPTION:
Black Creek 27.0
END DESCRIPTION:
XS GIS Cut Line= 3
      2275427.53      7169235.60      2275245.01      7168561.98
      2275060.29      7167514.65
#Sta/Elev= 30
  4299.3  839.22  4491.6  826.71  4636.6  815.70  4883.2  801.99  4895.7  803.51
  4947.5  801.36  4968.2  805.13  4978.5  804.55  4988.9  802.85  4995.6  799.85
  5003.7  800.10  5018.0  795.95  5020.3  795.45  5041.4  795.95  5057.8  804.42
  5062.9  802.50  5070.3  804.15  5110.9  804.38  5117.1  802.97  5212.5  805.32
  5415.5  805.70  5435.9  804.60  5467.5  806.51  5506.9  804.85  5653.9  807.36
  5748.5  809.53  5831.9  814.07  5872.5  814.48  5985.5  824.04  6060.7  828.57
#Mann=4,-1,0
  4299.3    0.12       0  5018.0    0.07       0  5041.4    0.12       0
  5653.9    0.05       0
Bank Sta=5018,5041.4
Exp/Cntr=0.3,0.1

Type RM Length L Ch R = 1,17633,718,718,718
BEGIN DESCRIPTION:
Black Creek 26.0
END DESCRIPTION:
XS GIS Cut Line= 3
      2276009.22      7168901.76      2275976.77      7168343.88
      2275629.01      7166760.03
#Sta/Elev= 30
  4457.3  834.48  4589.3  827.32  4859.7  803.00  4909.8  800.44  4969.9  801.70
  4978.2  790.28  4980.6  789.78  5001.7  790.28  5015.6  798.02  5027.1  800.83
  5050.8  802.24  5102.0  802.89  5124.9  800.53  5290.6  798.21  5419.4  796.86
  5665.1  799.84  5859.6  805.95  5890.3  809.58  5910.3  808.34  6136.1  830.22
  6193.6  839.79  6237.4  841.63  6286.3  840.41  6351.1  845.34  6379.0  849.66
  6476.8  854.64  6569.5  865.59  6576.3  869.71  6586.5  872.08  6637.7  873.54
#Mann=4,-1,0
  4457.3    0.12       0  4978.2    0.07       0  5001.7    0.12       0
  5290.6    0.05       0
Bank Sta=4978.2,5001.7
Exp/Cntr=0.3,0.1

Type RM Length L Ch R = 1,16915,555,555,555
BEGIN DESCRIPTION:
Black Creek 25.0
END DESCRIPTION:
XS GIS Cut Line= 3
      2276579.00      7169060.04      2276579.00      7168260.00
      2276469.67      7166776.37
#Sta/Elev= 30
  4194.9  842.61  4384.9  829.58  4484.9  819.88  4504.9  819.64  4664.9  806.19
  4824.9  798.71  4914.9  800.10  4980.7  798.24  4997.4  795.06  5013.3  787.60
  5015.6  787.10  5036.8  787.60  5045.1  795.85  5055.1  799.84  5084.9  798.88
  5315.8  795.91  5586.5  795.87  5767.0  797.76  5857.3  796.57  5997.7  799.34
  6067.8  803.17  6077.9  801.09  6162.0  803.95  6308.5  809.20  6338.6  814.10
  6358.6  815.40  6378.7  821.30  6408.8  821.97  6470.9  828.78  6482.6  829.43
#Mann=7,-1,0
  4194.9    0.05       0  4980.7    0.12       0  5013.3    0.07       0
  5036.8    0.12       0  5084.9    0.05       0  6162.0    0.12       0
  6470.9    0.05       0
Bank Sta=5013.3,5036.8
Exp/Cntr=0.3,0.1

Type RM Length L Ch R = 1,16360,600,600,600
BEGIN DESCRIPTION:
Black Creek 24.0
END DESCRIPTION:
XS GIS Cut Line= 3
      2277079.00      7169060.00      2277079.00      7168310.00
      2277329.01      7167509.96
#Sta/Elev= 30
  4249.6  845.65  4449.6  827.69  4489.6  822.50  4559.6  816.69  4579.6  813.45
  4629.6  808.72  4769.6  797.71  4819.6  796.24  4969.6  797.13  4979.6  796.24
  4985.4  785.77  4987.7  785.27  5008.9  785.77  5010.1  788.59  5015.8  796.05
  5041.5  796.83  5188.7  794.86  5439.6  793.89  5524.0  801.99  5551.2  802.29
  5588.9  805.30  5616.2  805.37  5621.4  806.90  5686.4  808.17  5718.8  810.98
  5724.1  812.92  5756.6  816.71  5774.9  816.76  5806.3  819.81  5837.8  818.63
#Mann=3,-1,0
  4249.6    0.05       0  4985.4   0.033       0  5008.9    0.05       0
Bank Sta=4985.4,5008.9
Exp/Cntr=0.3,0.1

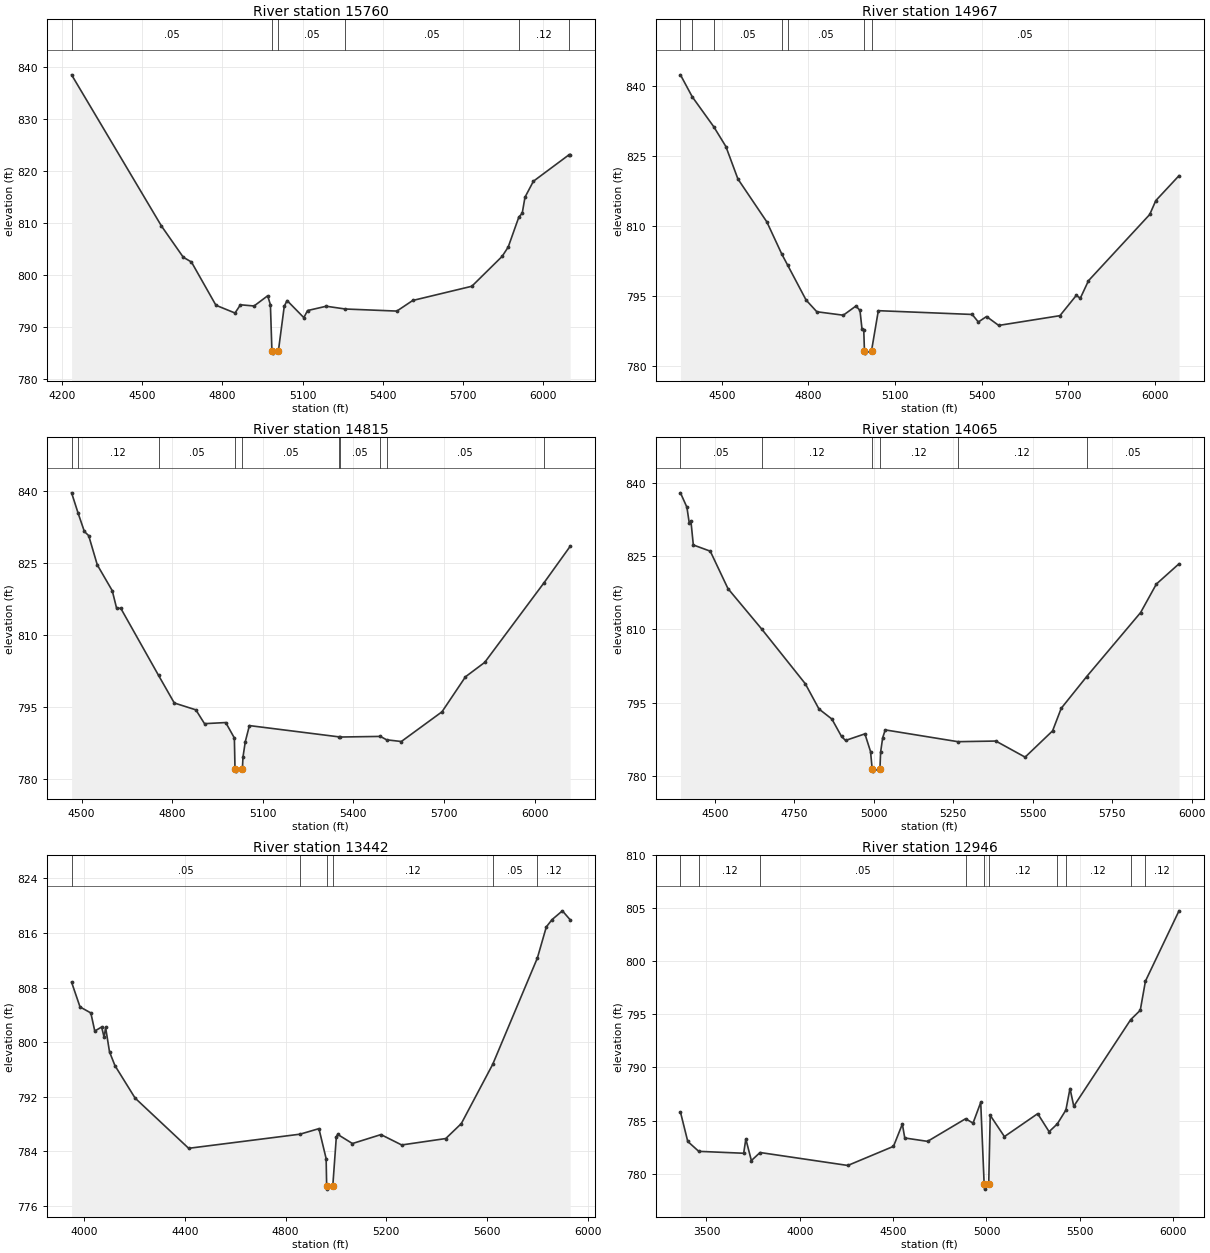
Type RM Length L Ch R = 1,15760,793,793,793
BEGIN DESCRIPTION:
Black Creek 23.0
END DESCRIPTION:
XS GIS Cut Line= 3
      2277528.99      7169060.04      2277679.00      7168310.00
      2278009.48      7167258.72
#Sta/Elev= 30
  4235.0  838.51  4571.6  809.45  4653.2  803.46  4683.8  802.54  4775.5  794.23
  4846.9  792.74  4867.3  794.32  4918.3  794.09  4969.3  796.05  4979.5  794.32
  4985.1  785.53  4987.5  785.03  5009.6  785.53  5031.3  794.01  5041.8  795.14
  5104.7  791.85  5118.5  793.21  5188.6  794.04  5259.7  793.51  5453.0  793.11
  5512.5  795.15  5733.7  797.88  5847.0  803.61  5869.9  805.41  5909.8  811.18
  5922.4  811.90  5932.8  814.99  5964.3  818.06  6096.5  823.10  6101.9  823.19
#Mann=6,-1,0
  4235.0    0.05       0  4985.1   0.033       0  5009.6    0.05       0
  5259.7    0.05       0  5909.8    0.12       0  6096.5    0.05       0
Bank Sta=4985.1,5009.6
Exp/Cntr=0.3,0.1

Type RM Length L Ch R = 1,14967,152,152,152
BEGIN DESCRIPTION:
Black Creek 22.0
END DESCRIPTION:
XS GIS Cut Line= 3
      2277679.02      7169209.98      2278212.51      7168814.72
      2278953.91      7168051.36
#Sta/Elev= 30
  4356.2  842.32  4397.1  837.61  4471.9  831.17  4513.7  826.95  4555.4  819.99
  4655.6  810.80  4707.1  803.94  4728.4  801.45  4791.8  794.03  4828.9  791.53
  4920.7  790.79  4964.5  792.76  4978.5  791.81  4985.4  787.88  4991.6  787.57
  4994.0  783.16  4996.4  782.66  5018.5  783.16  5042.1  791.76  5367.5  790.95
  5388.8  789.33  5417.1  790.51  5459.4  788.60  5671.6  790.69  5728.2  795.03
  5742.3  794.44  5770.6  798.19  5982.8  812.38  6003.9  815.36  6084.3  820.70
#Mann=7,-1,0
  4356.2    0.05       0  4397.1    0.12       0  4471.9    0.05       0
  4707.1    0.12       0  4728.4    0.05       0  4994.0   0.033       0
  5018.5    0.05       0
Bank Sta=4994,5018.5
Exp/Cntr=0.3,0.1

Type RM Length L Ch R = 1,14815,750,750,750
BEGIN DESCRIPTION:
Black Creek 21.0
END DESCRIPTION:
XS GIS Cut Line= 3
      2277829.03      7169309.98      2278247.46      7168957.91
      2279074.88      7168226.49
#Sta/Elev= 30
  4466.6  839.61  4488.3  835.36  4508.9  831.57  4523.2  830.71  4551.8  824.61
  4601.2  819.27  4615.5  815.66  4629.8  815.57  4754.5  801.66  4806.7  795.91
  4878.2  794.48  4906.8  791.61  4977.1  791.84  5005.7  788.63  5007.8  782.24
  5010.2  781.74  5032.3  782.24  5034.2  784.64  5041.8  787.84  5055.5  791.21
  5353.9  788.85  5355.4  788.83  5489.3  788.96  5510.0  788.25  5558.7  787.90
  5693.4  794.08  5771.2  801.36  5834.8  804.35  6030.6  820.85  6117.8  828.48
#Mann=10,-1,0
  4466.6    0.05       0  4488.3    0.12       0  4754.5    0.05       0
  5007.8   0.033       0  5032.3    0.05       0  5353.9    0.12       0
  5355.4    0.05       0  5489.3    0.12       0  5510.0    0.05       0
  6030.6    0.12       0
Bank Sta=5007.8,5032.3
Exp/Cntr=0.3,0.1

Type RM Length L Ch R = 1,14065,623,623,623
BEGIN DESCRIPTION:
Black Creek 20.0
END DESCRIPTION:
XS GIS Cut Line= 3
      2277929.02      7169710.00      2278529.00      7169610.00
      2279128.98      7168860.02
#Sta/Elev= 30
  4391.6  837.89  4411.9  834.95  4419.5  831.63  4424.5  832.16  4432.1  827.23
  4485.4  825.96  4541.1  818.31  4647.4  810.03  4784.4  798.86  4827.5  793.69
  4868.1  791.64  4898.5  788.07  4911.1  787.26  4972.0  788.61  4989.7  785.00
  4994.8  781.49  4997.3  780.99  5019.3  781.49  5021.5  784.91  5027.9  787.80
  5035.9  789.42  5264.7  787.01  5384.0  787.14  5476.1  783.85  5562.5  789.22
  5589.7  793.83  5669.3  800.28  5839.5  813.41  5889.1  819.24  5960.3  823.38
#Mann=6,-1,0
  4391.6    0.05       0  4647.4    0.12       0  4994.8    0.07       0
  5019.3    0.12       0  5264.7    0.12       0  5669.3    0.05       0
Bank Sta=4994.8,5019.3
Exp/Cntr=0.3,0.1

Type RM Length L Ch R = 1,13442,496,496,496
BEGIN DESCRIPTION:
Mapping XS 85983928
END DESCRIPTION:
XS GIS Cut Line= 3
      2278156.97      7170373.09      2279049.18      7169848.75
      2279275.94      7168930.11
#Sta/Elev= 30
  3949.7  808.79  3983.2  805.17  4026.2  804.29  4041.8  801.64  4069.1  802.23
  4079.0  800.71  4084.8  802.18  4100.4  798.59  4121.9  796.58  4202.0  791.82
  4414.9  784.46  4857.5  786.53  4932.5  787.34  4961.2  782.95  4963.2  778.98
  4965.6  778.48  4987.7  778.98  5001.7  786.15  5006.9  786.50  5065.7  785.16
  5179.0  786.47  5261.4  784.95  5436.5  785.89  5498.3  788.08  5622.9  796.75
  5800.5  812.33  5836.2  816.90  5858.8  817.96  5900.0  819.25  5930.8  817.94
#Mann=6,-1,0
  3949.7    0.05       0  4857.5    0.12       0  4963.2    0.07       0
  4987.7    0.12       0  5622.9    0.05       0  5800.5    0.12       0
Bank Sta=4963.2,4987.7
Exp/Cntr=0.3,0.1

Type RM Length L Ch R = 1,12946,459,459,459
BEGIN DESCRIPTION:
Mapping XS 7dc17431
END DESCRIPTION:
XS GIS Cut Line= 3
      2278371.09      7170751.79      2279388.18      7170488.38
      2279685.99      7168896.03
#Sta/Elev= 30
  3360.7  785.80  3399.9  783.03  3458.8  782.10  3699.4  781.92  3710.9  783.26
  3740.7  781.23  3787.1  781.99  4257.2  780.77  4501.9  782.57  4549.4  784.67
  4562.3  783.36  4684.4  783.04  4888.0  785.17  4928.0  784.76  4969.2  786.71
  4987.5  779.04  4990.0  778.54  5012.0  779.04  5020.1  785.49  5096.1  783.49
  5274.4  785.65  5335.5  783.95  5379.2  784.68  5425.4  785.99  5447.4  788.02
  5467.7  786.35  5772.6  794.51  5823.8  795.39  5851.6  798.14  6031.3  804.76
#Mann=10,-1,0
  3360.7    0.05       0  3458.8    0.12       0  3787.1    0.05       0
  4888.0    0.12       0  4987.5    0.07       0  5012.0    0.12       0
  5379.2    0.05       0  5425.4    0.12       0  5772.6    0.05       0
  5851.6    0.12       0
Bank Sta=4987.5,5012
Exp/Cntr=0.3,0.1

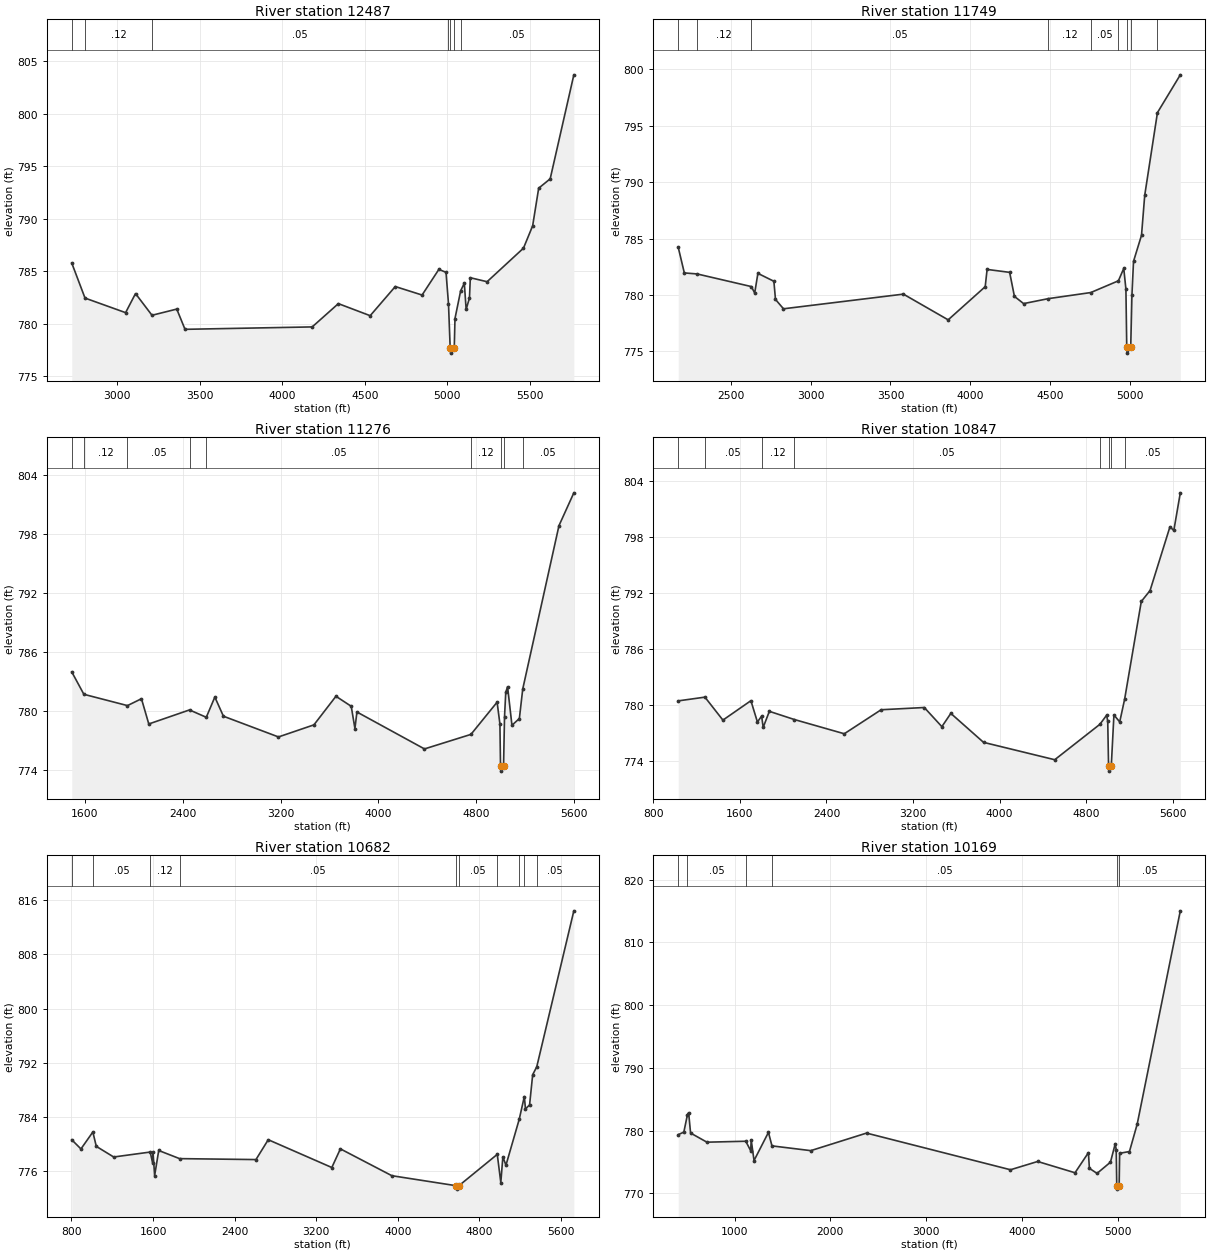
Type RM Length L Ch R = 1,12487,738,738,738
BEGIN DESCRIPTION:
Mapping XS 2327a408
END DESCRIPTION:
XS GIS Cut Line= 4
      2278372.70      7170776.26      2279810.92      7170734.90
      2279964.78      7169857.63      2280206.24      7169184.93
#Sta/Elev= 30
  2723.7  785.77  2804.0  782.43  3050.1  781.04  3110.2  782.86  3210.1  780.79
  3360.3  781.38  3410.3  779.45  4181.5  779.68  4340.1  781.90  4533.0  780.75
  4685.3  783.53  4847.7  782.72  4949.2  785.16  4992.8  784.89  5007.8  781.90
  5018.1  777.68  5020.6  777.18  5042.9  777.68  5047.2  780.48  5081.6  783.12
  5103.8  783.85  5114.9  781.35  5135.0  782.44  5140.3  784.37  5241.9  783.99
  5462.5  787.19  5518.1  789.32  5554.7  792.91  5624.4  793.80  5767.9  803.72
#Mann=7,-1,0
  2723.7    0.05       0  2804.0    0.12       0  3210.1    0.05       0
  5007.8    0.12       0  5018.1    0.04       0  5042.9    0.12       0
  5081.6    0.05       0
Bank Sta=5018.1,5042.9
Exp/Cntr=0.3,0.1

Type RM Length L Ch R = 1,11749,473,473,473
BEGIN DESCRIPTION:
Mapping XS a8af71cc
END DESCRIPTION:
XS GIS Cut Line= 4
      2278430.86      7170812.48      2280141.00      7170794.38
      2280661.89      7169840.17      2280662.31      7169497.43
#Sta/Elev= 30
  2172.5  784.23  2210.6  781.96  2290.3  781.87  2629.6  780.75  2650.7  780.18
  2670.7  781.92  2770.7  781.22  2780.7  779.61  2830.7  778.78  3580.7  780.08
  3860.7  777.80  4092.4  780.74  4104.2  782.27  4245.2  782.01  4275.1  779.88
  4332.5  779.24  4487.0  779.68  4752.5  780.22  4925.4  781.26  4958.9  782.36
  4972.4  780.52  4977.6  775.35  4980.1  774.85  5002.4  775.35  5010.0  779.99
  5020.0  782.99  5070.0  785.30  5090.0  788.84  5169.6  796.17  5312.6  799.52
#Mann=9,-1,0
  2172.5    0.05       0  2290.3    0.12       0  2629.6    0.05       0
  4487.0    0.12       0  4752.5    0.05       0  4925.4    0.12       0
  4977.6    0.07       0  5002.4    0.12       0  5169.6    0.05       0
Bank Sta=4977.6,5002.4
Exp/Cntr=0.3,0.1

Type RM Length L Ch R = 1,11276,429,429,429
BEGIN DESCRIPTION:
Mapping XS ec7b0b7e
END DESCRIPTION:
XS GIS Cut Line= 5
      2278449.31      7170824.42      2280719.16      7170871.18
      2281074.81      7170068.17      2281104.61      7169723.36
      2281010.20      7169119.87
#Sta/Elev= 30
  1492.0  784.00  1591.0  781.72  1947.5  780.57  2061.8  781.27  2121.8  778.70
  2454.7  780.13  2592.0  779.38  2661.9  781.44  2732.0  779.49  3182.1  777.38
  3472.1  778.61  3652.2  781.52  3777.2  780.50  3807.4  778.23  3823.7  779.92
  4376.1  776.16  4756.0  777.64  4970.0  780.92  4992.9  778.71  4997.9  774.40
  5000.4  773.90  5022.7  774.40  5030.6  779.41  5040.7  781.92  5055.6  782.49
  5091.3  778.57  5152.0  779.25  5179.6  782.26  5475.9  798.89  5597.5  802.23
#Mann=9,-1,0
  1492.0    0.05       0  1591.0    0.12       0  1947.5    0.05       0
  2454.7    0.12       0  2592.0    0.05       0  4756.0    0.12       0
  4997.9    0.07       0  5022.7    0.12       0  5179.6    0.05       0
Bank Sta=4997.9,5022.7
Exp/Cntr=0.3,0.1

Type RM Length L Ch R = 1,10847,165,165,165
BEGIN DESCRIPTION:
Mapping XS a3543846
END DESCRIPTION:
XS GIS Cut Line= 5
      2278689.40      7170862.07      2281123.54      7171058.22
      2281507.11      7170182.42      2281498.74      7169550.58
      2281198.69      7169017.79
#Sta/Elev= 30
  1029.7  780.46  1276.5  780.86  1442.7  778.40  1701.5  780.48  1761.7  778.20
  1800.6  778.83  1815.0  777.62  1872.0  779.34  2104.2  778.46  2564.7  776.94
  2905.4  779.51  3304.4  779.75  3466.9  777.70  3549.7  779.12  3852.1  776.02
  4510.3  774.16  4927.6  777.95  4990.3  778.93  5000.3  778.27  5007.9  773.44
  5010.4  772.94  5032.8  773.44  5057.5  778.95  5111.1  778.21  5156.6  780.65
  5310.5  791.10  5391.5  792.27  5575.0  799.08  5611.3  798.71  5671.2  802.73
#Mann=8,-1,0
  1029.7    0.12       0  1276.5    0.05       0  1800.6    0.12       0
  2104.2    0.05       0  4927.6    0.12       0  5007.9    0.07       0
  5032.8    0.12       0  5156.6    0.05       0
Bank Sta=5007.9,5032.8
Exp/Cntr=0.3,0.1

Type RM Length L Ch R = 1,10682,513,513,513
BEGIN DESCRIPTION:
Mapping XS f160ae45
END DESCRIPTION:
XS GIS Cut Line= 5
      2278719.44      7170909.18      2281239.96      7171118.33
      2281716.84      7170078.18      2281650.40      7169574.57
      2281558.73      7168839.48
#Sta/Elev= 30
   803.3  780.66   893.2  779.31  1010.0  781.81  1043.7  779.69  1214.3  778.12
  1572.4  778.85  1594.9  777.30  1599.9  778.84  1615.6  775.37  1655.8  779.08
  1860.2  777.88  2609.0  777.74  2729.5  780.67  3352.7  776.57  3436.7  779.32
  3941.6  775.36  4573.4  773.88  4575.9  773.38  4598.3  773.88  4974.8  778.51
  5009.5  774.35  5029.6  778.14  5059.9  776.91  5190.0  783.68  5240.1  787.04
  5251.3  785.21  5291.6  785.81  5321.9  790.26  5361.9  791.43  5725.5  814.44
#Mann=10,-1,0
   803.3    0.12       0  1010.0    0.05       0  1572.4    0.12       0
  1860.2    0.05       0  4573.4    0.07       0  4598.3    0.05       0
  4974.8    0.12       0  5190.0    0.05       0  5240.1    0.12       0
  5361.9    0.05       0
Bank Sta=4573.4,4598.3
Exp/Cntr=0.3,0.1

Type RM Length L Ch R = 1,10169,0,0,0
BEGIN DESCRIPTION:
Black Creek 19.0
END DESCRIPTION:
XS GIS Cut Line= 5
      2278810.75      7170951.68      2281266.24      7171190.40
      2282019.07      7170520.14      2282070.72      7169398.60
      2281750.79      7168834.70
#Sta/Elev= 30
   409.8  779.34   468.3  779.75   506.2  782.54   518.6  782.84   538.7  779.60
   709.5  778.14  1115.5  778.29  1167.1  776.77  1172.1  778.51  1201.8  775.21
  1352.5  779.71  1389.1  777.55  1794.6  776.79  2377.3  779.59  3881.4  773.74
  4165.3  775.06  4555.7  773.26  4695.8  776.47  4705.8  773.97  4785.9  773.16
  4926.1  774.95  4976.1  777.90  4986.1  776.93  4991.9  771.15  4994.4  770.65
  5016.8  771.15  5022.2  776.37  5124.6  776.65  5205.4  781.02  5655.9  815.05
#Mann=6,-1,0
   409.8    0.12       0   506.2    0.05       0  1115.5    0.12       0
  1389.1    0.05       0  4991.9    0.04       0  5016.8    0.05       0
Bank Sta=4991.9,5016.8
Exp/Cntr=0.3,0.1

Chan Stop Cuts=-1