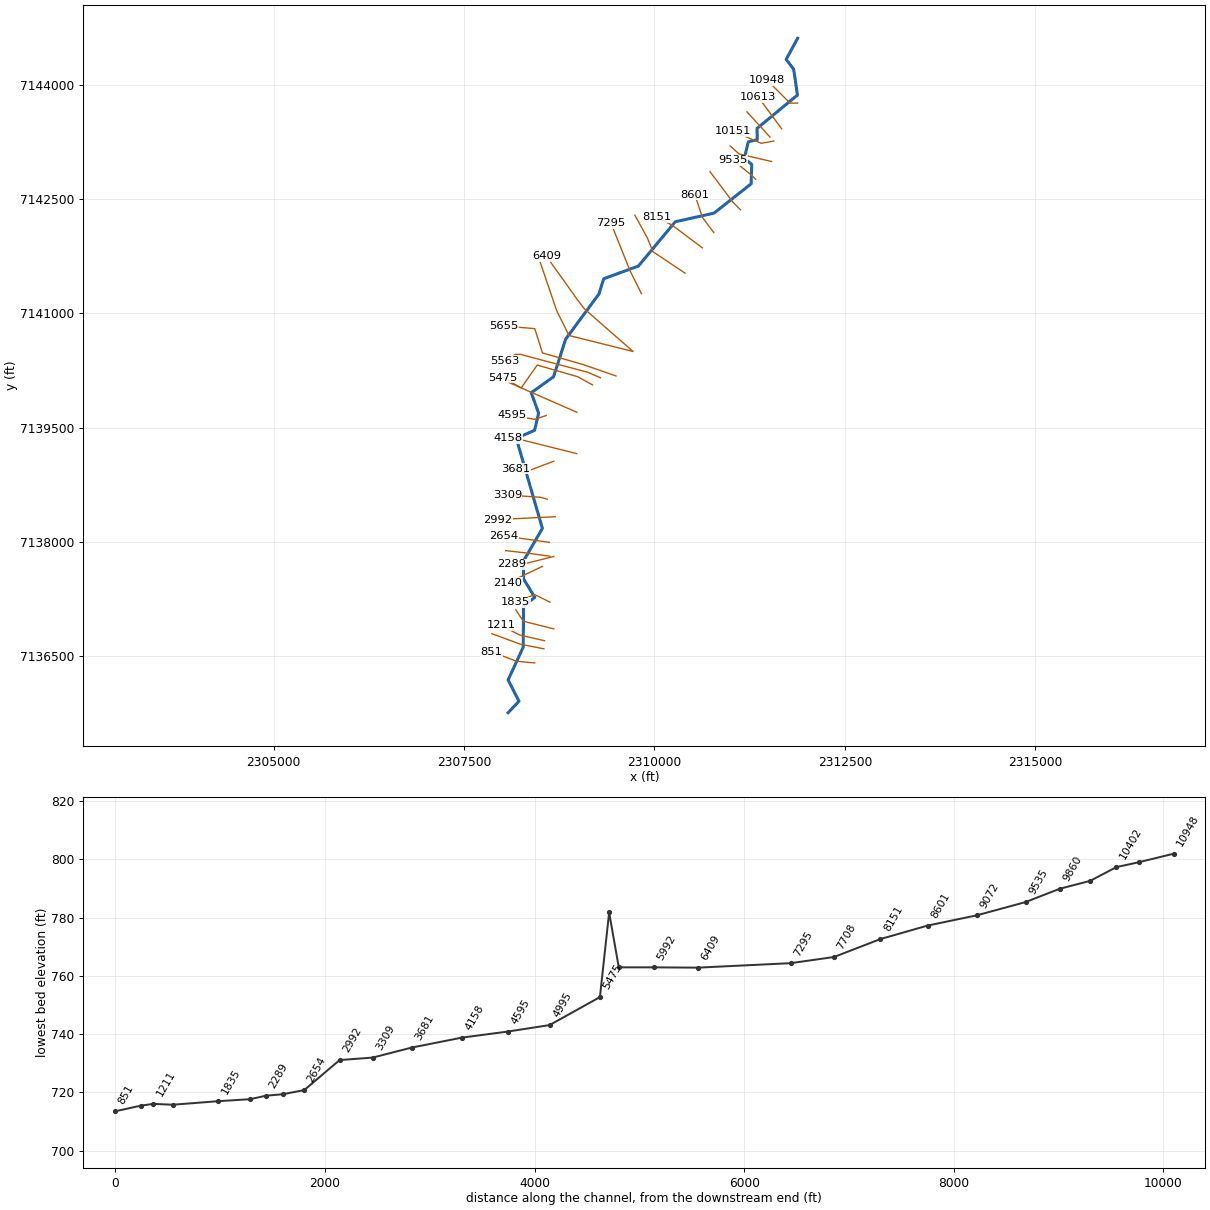
--- Burns Branch.prj (project) ---

Proj Title=Burns Branch Base Level Engineering
Current Plan=p01
Default Exp/Contr=0.3,0.1
English Units
Geom File=g01
Flow File=f01
Plan File=p01
BEGIN DESCRIPTION:
Burns Branch
END DESCRIPTION:

--- Burns Branch.p01 (plan) ---

Plan Title=Multiple Run
Short Identifier=Multiple
Geom File=g01
Flow File=f01
Subcritical Flow
K Sum by GR= 0
Std Step Tol= 0.01
Critical Tol= 0.01
Num of Std Step Trials= 20
Max Error Tol= 0.3
Flow Tol Ratio= 0.001
Split Flow NTrial= 30
Split Flow Tol= 0.02
Split Flow Ratio= 0.02
Log Output Level= 0
Friction Slope Method= 1
Unsteady Friction Slope Method= 2
Unsteady Bridges Friction Slope Method= 1
Parabolic Critical Depth
Global Vel Dist=  1 , 1 , 1
Global Log Level= 0
CheckData=True
Encroach Param= -1, 0, 0, 0
BEGIN DESCRIPTION:
Multiple Run
END DESCRIPTION:

--- Burns Branch.f01 (steady flow) ---

Flow Title=Multiple
Number of Profiles=7
Profile Names=10-year,25-year,50-year,1pct_min,100-year,1pct_plu,500-year
River Rch & RM= Burns Branch,Reach-1,10948
     719     997    1229     753    1502    2997    2248
River Rch & RM= Burns Branch,Reach-1,9072
    1080    1529    1912    1185    2365    4719    3629
Boundary for River Rch & Prof#=Burns Branch,Reach-1,1
Up Type=0
Dn Type=3
Dn Slope=0.005
Boundary for River Rch & Prof#=Burns Branch,Reach-1,2
Up Type=0
Dn Type=3
Dn Slope=0.005
Boundary for River Rch & Prof#=Burns Branch,Reach-1,3
Up Type=0
Dn Type=3
Dn Slope=0.005
Boundary for River Rch & Prof#=Burns Branch,Reach-1,4
Up Type=0
Dn Type=3
Dn Slope=0.005
Boundary for River Rch & Prof#=Burns Branch,Reach-1,5
Up Type=0
Dn Type=3
Dn Slope=0.005
Boundary for River Rch & Prof#=Burns Branch,Reach-1,6
Up Type=0
Dn Type=3
Dn Slope=0.005
Boundary for River Rch & Prof#=Burns Branch,Reach-1,7
Up Type=0
Dn Type=3
Dn Slope=0.005

--- Burns Branch.g01 (geometry) ---

Geom Title=Existing Conditions

River Reach=Burns Branch,Reach-1
Reach XY= 30
      2311879.00      7144610.00      2311728.52      7144332.76
      2311826.81      7144204.55      2311876.83      7143865.45
      2311345.30      7143426.70      2311349.72      7143279.48
      2311232.19      7143252.28      2311178.48      7143034.88
      2311276.88      7142954.73      2311268.52      7142700.20
      2310781.43      7142315.52      2310272.52      7142202.31
      2309788.68      7141620.76      2309334.09      7141454.96
      2309270.86      7141253.94      2308834.54      7140662.42
      2308675.59      7140168.44      2308382.36      7139958.75
      2308479.19      7139691.57      2308426.91      7139465.24
      2308186.21      7139360.35      2308528.91      7138178.22
      2308280.36      7137750.35      2308281.35      7137515.52
      2308429.02      7137273.93      2308281.09      7137154.74
      2308277.78      7136620.50      2308078.72      7136189.82
      2308222.01      7135909.78      2308079.00      7135760.00

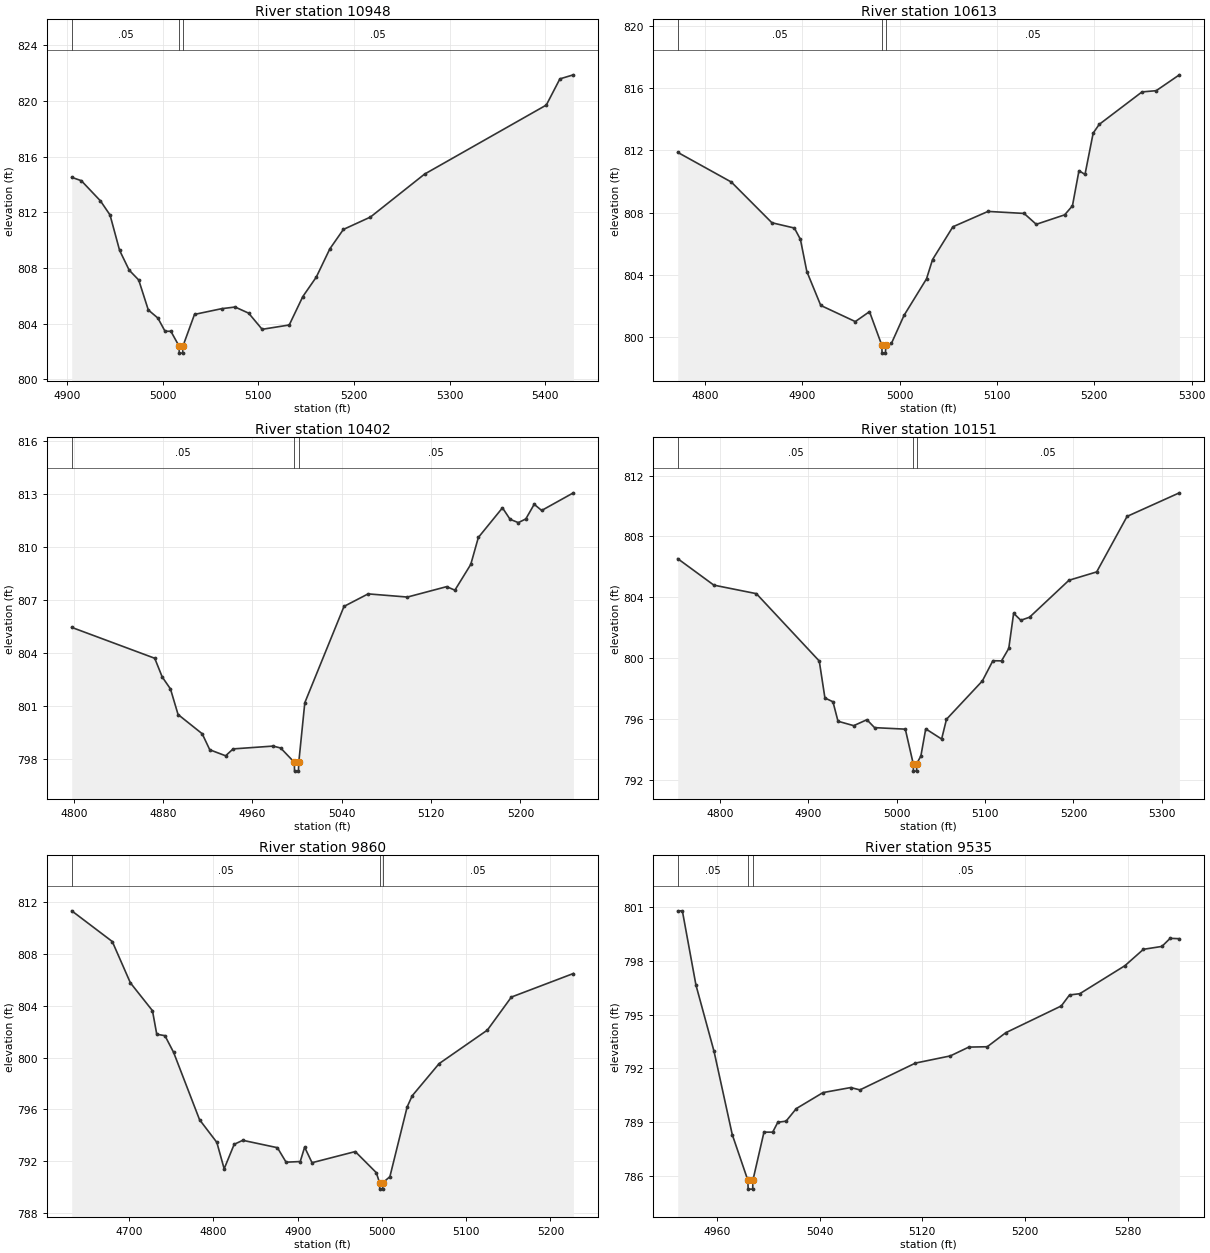
Type RM Length L Ch R = 1,10948,335,335,335
BEGIN DESCRIPTION:
Burns Branch 25.0
END DESCRIPTION:
XS GIS Cut Line= 3
      2311879.04      7143760.00      2311779.00      7143760.00
      2311479.00      7144060.00
#Sta/Elev= 30
  4905.1  814.51  4915.1  814.27  4935.1  812.82  4945.1  811.81  4955.1  809.27
  4965.1  807.85  4975.1  807.14  4985.1  804.99  4995.1  804.41  5002.6  803.46
  5008.7  803.46  5017.3  802.39  5017.5  801.89  5021.0  801.89  5021.3  802.39
  5033.4  804.67  5061.7  805.08  5075.8  805.20  5090.0  804.76  5104.1  803.60
  5132.4  803.91  5146.6  805.95  5160.7  807.35  5174.8  809.37  5189.0  810.77
  5217.3  811.66  5273.8  814.74  5401.1  819.70  5415.3  821.58  5429.4  821.87
#Mann=3,-1,0
  4905.1    0.05       0  5017.3   0.033       0  5021.3    0.05       0
Bank Sta=5017.3,5021.3
Exp/Cntr=0.3,0.1

Type RM Length L Ch R = 1,10613,211,211,211
BEGIN DESCRIPTION:
Mapping XS 36632f3e
END DESCRIPTION:
XS GIS Cut Line= 2
      2311668.52      7143423.10      2311363.11      7143838.51
#Sta/Elev= 30
  4771.8  811.87  4826.9  809.96  4868.6  807.34  4891.7  807.00  4897.9  806.27
  4904.5  804.20  4918.8  802.02  4954.3  800.98  4968.9  801.62  4981.6  799.45
  4981.8  798.95  4985.3  798.95  4985.6  799.45  4991.4  799.57  5004.4  801.38
  5027.5  803.73  5033.7  804.97  5054.6  807.08  5090.7  808.07  5127.8  807.94
  5140.3  807.24  5169.5  807.85  5177.5  808.43  5184.2  810.69  5190.4  810.45
  5198.8  813.11  5205.0  813.67  5249.0  815.76  5263.6  815.84  5287.4  816.86
#Mann=3,-1,0
  4771.8    0.05       0  4981.6   0.033       0  4985.6    0.05       0
Bank Sta=4981.6,4985.6
Exp/Cntr=0.3,0.1

Type RM Length L Ch R = 1,10402,251,251,251
BEGIN DESCRIPTION:
Mapping XS b6351286
END DESCRIPTION:
XS GIS Cut Line= 2
      2311516.92      7143313.29      2311213.92      7143644.91
#Sta/Elev= 30
  4798.2  805.45  4872.5  803.70  4879.2  802.64  4886.6  801.96  4893.4  800.51
  4915.0  799.42  4921.8  798.51  4936.0  798.17  4942.7  798.56  4978.5  798.72
  4985.3  798.61  4997.5  797.80  4997.7  797.30  5001.2  797.30  5001.5  797.80
  5006.9  801.18  5042.0  806.64  5063.6  807.35  5098.8  807.17  5133.9  807.76
  5141.3  807.56  5155.5  809.02  5162.3  810.55  5183.9  812.23  5190.7  811.58
  5198.1  811.39  5204.8  811.60  5212.3  812.43  5219.0  812.08  5247.4  813.08
#Mann=3,-1,0
  4798.2    0.05       0  4997.5   0.033       0  5001.5    0.05       0
Bank Sta=4997.5,5001.5
Exp/Cntr=0.3,0.1

Type RM Length L Ch R = 1,10151,291,291,291
BEGIN DESCRIPTION:
Mapping XS e1ca24ec
END DESCRIPTION:
XS GIS Cut Line= 3
      2311566.60      7143261.87      2311401.42      7143231.96
      2311034.20      7143390.39
#Sta/Elev= 30
  4752.1  806.54  4793.0  804.80  4841.1  804.24  4912.3  799.81  4918.7  797.38
  4927.8  797.13  4933.5  795.85  4951.3  795.56  4966.2  795.95  4974.9  795.43
  5009.7  795.33  5018.6  793.07  5018.9  792.57  5022.4  792.57  5022.6  793.07
  5027.3  793.56  5032.8  795.35  5050.8  794.68  5056.3  795.98  5096.9  798.50
  5108.8  799.83  5118.6  799.82  5126.8  800.64  5132.3  802.95  5140.4  802.49
  5150.3  802.69  5194.9  805.12  5226.3  805.67  5260.7  809.32  5319.9  810.87
#Mann=3,-1,0
  4752.1    0.05       0  5018.6   0.033       0  5022.6    0.05       0
Bank Sta=5018.6,5022.6
Exp/Cntr=0.3,0.1

Type RM Length L Ch R = 1,9860,325,325,325
BEGIN DESCRIPTION:
Mapping XS 37c2e80f
END DESCRIPTION:
XS GIS Cut Line= 3
      2311536.74      7142993.15      2311110.15      7143092.49
      2310992.69      7143197.27
#Sta/Elev= 30
  4631.9  811.34  4680.0  808.97  4701.5  805.78  4727.7  803.63  4732.8  801.81
  4742.5  801.70  4752.8  800.41  4783.6  795.21  4804.1  793.46  4812.8  791.42
  4824.7  793.31  4834.9  793.62  4876.0  793.05  4886.3  791.93  4903.1  791.98
  4908.3  793.09  4917.1  791.89  4968.4  792.75  4993.4  791.12  4997.2  790.35
  4997.5  789.85  5001.0  789.85  5001.2  790.35  5009.5  790.81  5030.0  796.20
  5036.0  797.06  5067.9  799.54  5125.2  802.13  5153.7  804.68  5227.3  806.50
#Mann=3,-1,0
  4631.9    0.05       0  4997.2   0.033       0  5001.2    0.05       0
Bank Sta=4997.2,5001.2
Exp/Cntr=0.3,0.1

Type RM Length L Ch R = 1,9535,463,463,463
BEGIN DESCRIPTION:
Burns Branch 21.0
END DESCRIPTION:
XS GIS Cut Line= 3
      2311329.03      7142759.97      2311279.00      7142810.00
      2311029.01      7143009.99
#Sta/Elev= 30
  4929.4  800.77  4933.0  800.77  4943.6  796.64  4957.7  792.95  4971.9  788.32
  4984.0  785.79  4984.3  785.29  4987.8  785.29  4988.0  785.79  4996.6  788.46
  5003.4  788.46  5007.4  789.01  5013.8  789.07  5021.8  789.77  5042.6  790.66
  5064.2  790.94  5071.4  790.81  5114.6  792.30  5141.8  792.70  5156.2  793.19
  5170.6  793.21  5185.0  793.99  5228.3  795.48  5234.7  796.09  5242.7  796.16
  5277.9  797.72  5292.3  798.63  5306.7  798.79  5313.1  799.24  5320.3  799.22
#Mann=3,-1,0
  4929.4    0.05       0  4984.0   0.033       0  4988.0    0.05       0
Bank Sta=4984,4988
Exp/Cntr=0.3,0.1

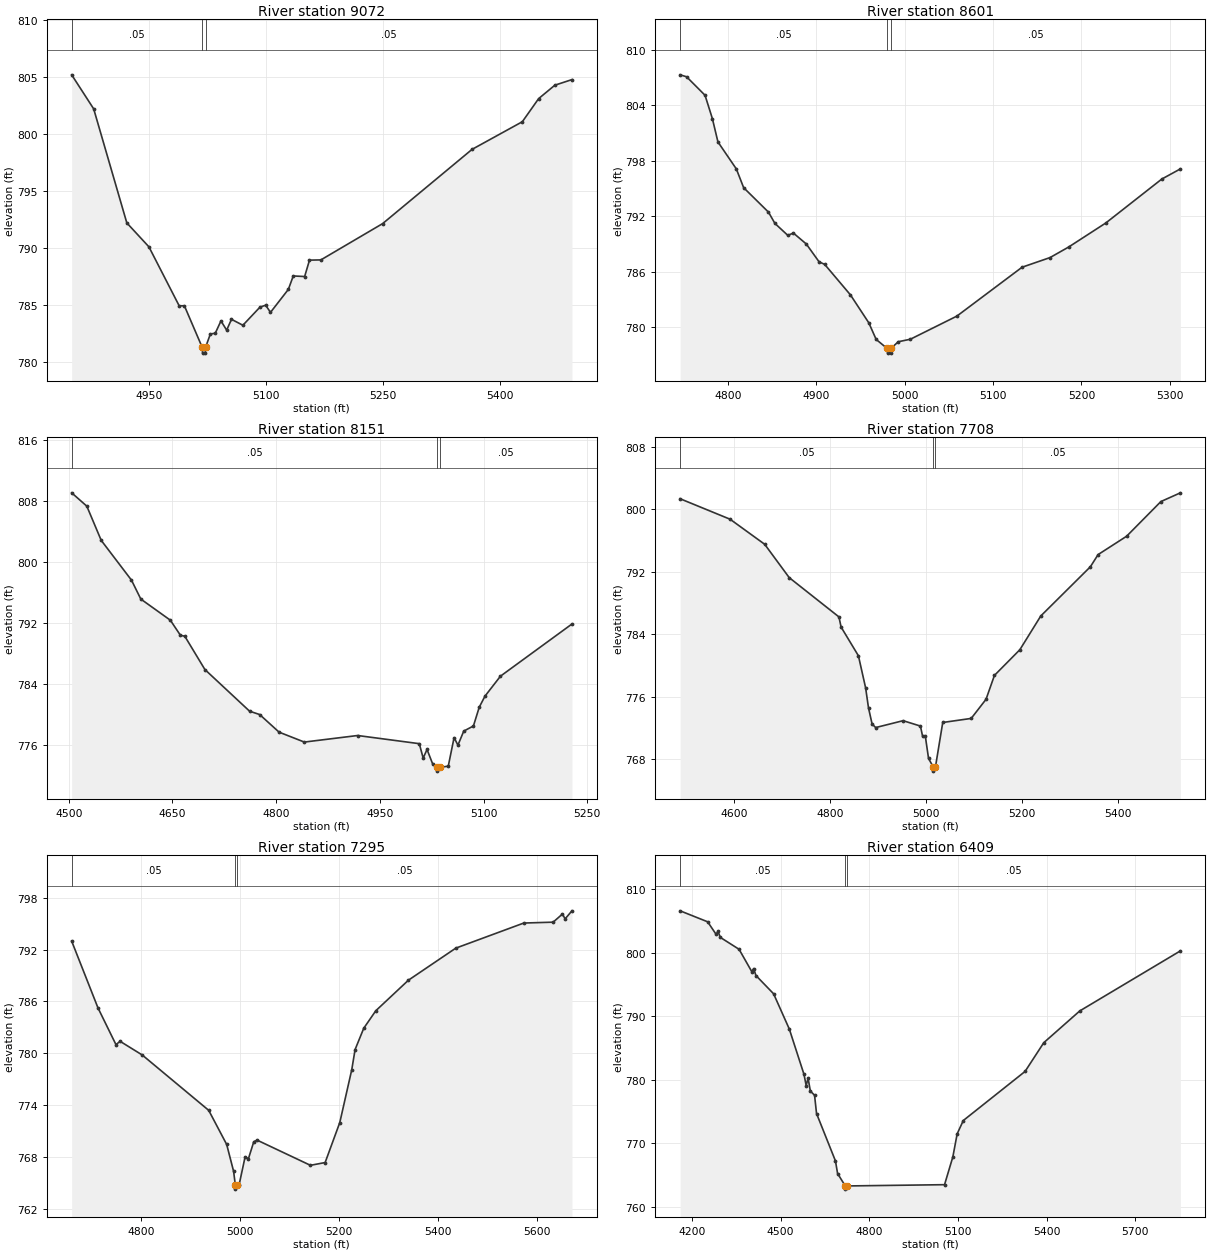
Type RM Length L Ch R = 1,9072,471,471,471
BEGIN DESCRIPTION:
Burns Branch 20.0
END DESCRIPTION:
XS GIS Cut Line= 3
      2311128.97      7142360.03      2311029.00      7142460.00
      2310728.99      7142860.02
#Sta/Elev= 30
  4850.4  805.21  4878.6  802.22  4921.1  792.20  4949.4  790.10  4988.2  784.92
  4994.9  784.92  5017.8  781.26  5018.2  780.76  5021.7  780.76  5022.0  781.26
  5028.2  782.44  5034.5  782.51  5041.8  783.59  5049.1  782.78  5055.3  783.73
  5069.9  783.21  5091.8  784.80  5099.1  784.97  5105.3  784.34  5128.2  786.36
  5134.5  787.54  5149.1  787.49  5155.3  788.93  5169.9  788.95  5249.1  792.14
  5363.7  798.66  5428.2  801.09  5449.1  803.12  5469.9  804.30  5491.8  804.79
#Mann=3,-1,0
  4850.4    0.05       0  5017.8   0.033       0  5022.0    0.05       0
Bank Sta=5017.8,5022
Exp/Cntr=0.3,0.1

Type RM Length L Ch R = 1,8601,450,450,450
BEGIN DESCRIPTION:
Burns Branch 19.0
END DESCRIPTION:
XS GIS Cut Line= 3
      2310779.03      7142059.96      2310629.00      7142260.00
      2310528.99      7142560.03
#Sta/Elev= 30
  4745.7  807.29  4753.0  807.08  4773.9  805.08  4782.2  802.56  4788.5  800.04
  4809.3  797.13  4817.6  795.10  4845.7  792.46  4853.0  791.24  4867.6  789.95
  4873.9  790.20  4888.5  789.02  4903.0  787.09  4909.3  786.82  4938.5  783.52
  4959.3  780.50  4967.6  778.71  4980.1  777.73  4980.5  777.23  4984.0  777.23
  4984.3  777.73  4992.6  778.46  5006.3  778.73  5059.0  781.23  5132.8  786.51
  5164.4  787.55  5185.5  788.69  5227.6  791.29  5290.9  796.03  5312.0  797.13
#Mann=3,-1,0
  4745.7    0.05       0  4980.1   0.033       0  4984.3    0.05       0
Bank Sta=4980.1,4984.3
Exp/Cntr=0.3,0.1

Type RM Length L Ch R = 1,8151,443,443,443
BEGIN DESCRIPTION:
Burns Branch 18.0
END DESCRIPTION:
XS GIS Cut Line= 3
      2310629.01      7141859.99      2310229.00      7142160.00
      2310029.02      7142259.99
#Sta/Elev= 30
  4504.3  809.09  4526.2  807.34  4547.0  802.86  4590.8  797.64  4604.3  795.16
  4647.0  792.39  4661.6  790.41  4667.9  790.29  4697.0  785.92  4761.6  780.46
  4776.2  780.02  4804.3  777.71  4840.8  776.41  4917.9  777.27  5007.1  776.20
  5012.7  774.31  5018.3  775.44  5026.7  773.48  5033.0  773.10  5033.3  772.60
  5037.2  773.10  5049.0  773.25  5057.4  776.99  5063.0  776.01  5071.4  777.85
  5085.4  778.52  5093.8  780.98  5102.1  782.43  5124.5  785.05  5227.9  791.89
#Mann=3,-1,0
  4504.3    0.05       0  5033.0   0.033       0  5037.2    0.05       0
Bank Sta=5033,5037.2
Exp/Cntr=0.3,0.1

Type RM Length L Ch R = 1,7708,413,413,413
BEGIN DESCRIPTION:
Burns Branch 17.0
END DESCRIPTION:
XS GIS Cut Line= 5
      2310401.85      7141528.10      2310129.00      7141710.00
      2309979.00      7141810.00      2309907.81      7141987.96
      2309743.10      7142288.28
#Sta/Elev= 30
  4487.2  801.33  4591.3  798.71  4663.4  795.50  4714.5  791.23  4818.1  786.20
  4822.6  784.90  4858.7  781.22  4873.7  777.11  4879.7  774.55  4887.2  772.48
  4894.7  772.03  4951.8  772.91  4987.9  772.22  4992.4  770.92  4998.1  770.92
  5004.8  768.08  5014.8  766.95  5015.1  766.45  5019.1  766.95  5034.4  772.68
  5093.7  773.20  5124.6  775.65  5142.1  778.71  5195.1  782.00  5238.7  786.32
  5342.0  792.62  5358.1  794.18  5417.5  796.53  5488.9  800.97  5529.6  802.09
#Mann=3,-1,0
  4487.2    0.05       0  5014.8   0.033       0  5019.1    0.05       0
Bank Sta=5014.8,5019.1
Exp/Cntr=0.3,0.1

Type RM Length L Ch R = 1,7295,886,886,886
BEGIN DESCRIPTION:
Burns Branch 16.0
END DESCRIPTION:
XS GIS Cut Line= 4
      2309828.99      7141260.01      2309679.00      7141560.00
      2309579.00      7141810.00      2309428.39      7142186.54
#Sta/Elev= 30
  4660.1  792.97  4713.2  785.26  4749.5  781.02  4757.9  781.40  4802.6  779.82
  4936.8  773.43  4973.1  769.49  4987.1  766.38  4990.5  764.83  4990.9  764.33
  4994.9  764.83  4998.2  764.83  5010.3  768.06  5017.0  767.84  5027.8  769.80
  5034.5  769.99  5142.2  767.08  5171.9  767.40  5201.5  772.02  5225.7  778.13
  5232.4  780.45  5249.9  782.91  5274.2  784.93  5340.1  788.46  5435.7  792.16
  5573.1  795.06  5632.3  795.16  5651.1  796.10  5656.5  795.54  5670.3  796.47
#Mann=3,-1,0
  4660.1    0.05       0  4990.5   0.033       0  4994.9    0.05       0
Bank Sta=4990.5,4994.9
Exp/Cntr=0.3,0.1

Type RM Length L Ch R = 1,6409,417,417,417
BEGIN DESCRIPTION:
Burns Branch 14.0
END DESCRIPTION:
XS GIS Cut Line= 5
      2309714.44      7140503.99      2309479.00      7140710.00
      2309079.00      7141060.00      2308969.78      7141205.62
      2308583.37      7141747.84
#Sta/Elev= 30
  4160.3  806.63  4253.4  804.90  4281.9  802.93  4288.5  803.41  4296.1  802.45
  4359.7  800.57  4402.4  797.07  4409.1  797.53  4416.7  796.44  4476.5  793.56
  4529.6  788.01  4579.4  780.85  4586.6  779.11  4593.2  780.24  4600.8  778.24
  4615.0  777.58  4621.7  774.70  4685.7  767.23  4692.9  765.25  4718.9  763.29
  4719.5  762.79  4723.7  763.29  5054.7  763.49  5082.8  767.87  5097.4  771.50
  5118.2  773.60  5327.1  781.33  5390.4  785.86  5512.1  790.86  5852.5  800.32
#Mann=3,-1,0
  4160.3    0.05       0  4718.9   0.033       0  4723.7    0.05       0
Bank Sta=4718.9,4723.7
Exp/Cntr=0.3,0.1

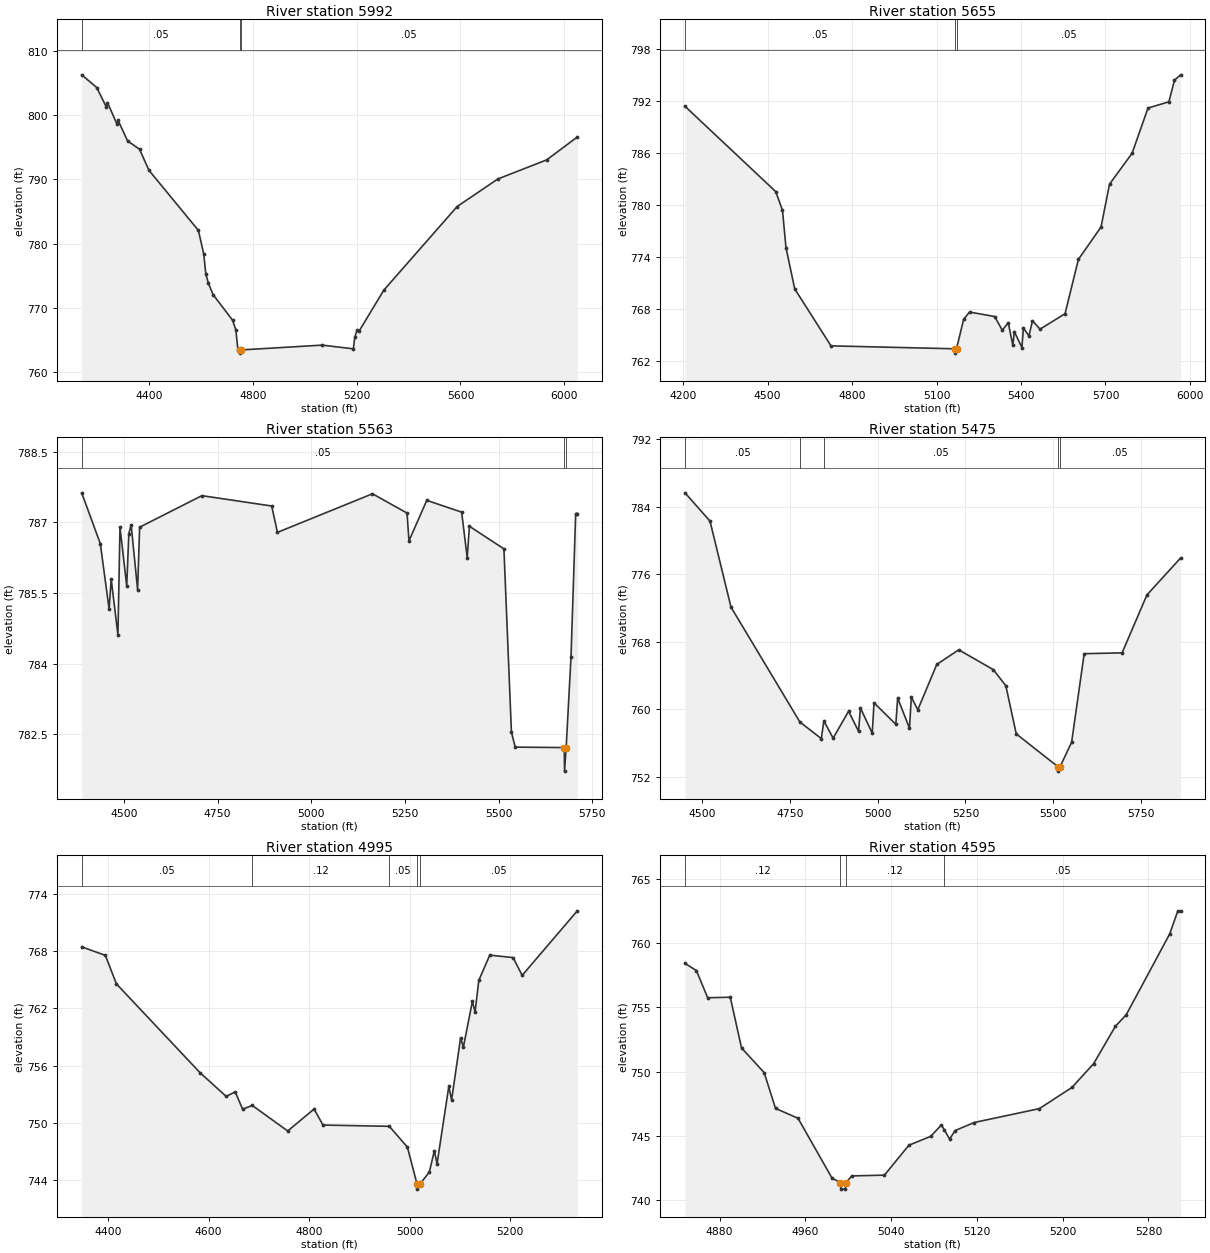
Type RM Length L Ch R = 1,5992,337,337,337
BEGIN DESCRIPTION:
Burns Branch 13.0
END DESCRIPTION:
XS GIS Cut Line= 5
      2309712.82      7140501.55      2309279.00      7140610.00
      2308879.00      7140710.00      2308717.94      7141032.11
      2308495.50      7141685.37
#Sta/Elev= 30
  4140.5  806.34  4198.5  804.36  4234.6  801.37  4239.8  802.00  4275.8  798.71
  4281.0  799.21  4317.1  796.04  4363.5  794.71  4399.5  791.44  4590.2  782.05
  4610.9  778.35  4618.6  775.28  4628.9  773.78  4646.9  772.02  4721.7  768.04
  4734.6  766.51  4742.3  763.44  4750.2  763.39  4750.7  762.89  4755.0  763.39
  5067.1  764.14  5187.2  763.56  5192.8  765.36  5201.2  766.43  5209.6  766.34
  5304.6  772.72  5587.3  785.78  5744.0  790.08  5932.2  793.06  6050.2  796.63
#Mann=3,-1,0
  4140.5    0.05       0  4750.2   0.033       0  4755.0    0.05       0
Bank Sta=4750.2,4755
Exp/Cntr=0.3,0.1

Type RM Length L Ch R = 1,5655,92,92,92
BEGIN DESCRIPTION:
Mapping XS 40f2e878
END DESCRIPTION:
XS GIS Cut Line= 6
      2309495.80      7140178.22      2309263.63      7140259.10
      2309064.67      7140328.41      2308530.22      7140480.75
      2308428.64      7140800.01      2308017.30      7140834.62
#Sta/Elev= 30
  4206.9  791.42  4529.0  781.56  4553.0  779.40  4565.4  775.09  4596.4  770.32
  4725.2  763.73  5166.0  763.39  5166.6  762.89  5171.0  763.39  5196.3  766.79
  5217.2  767.64  5306.6  767.12  5333.6  765.54  5354.8  766.39  5371.1  763.79
  5376.3  765.38  5403.3  763.54  5408.6  765.77  5428.3  764.89  5440.8  766.63
  5467.8  765.66  5556.5  767.45  5604.0  773.73  5684.3  777.47  5714.4  782.42
  5794.7  786.00  5851.1  791.22  5925.2  791.94  5945.2  794.45  5967.0  795.06
#Mann=3,-1,0
  4206.9    0.05       0  5166.0   0.033       0  5171.0    0.05       0
Bank Sta=5166,5171
Exp/Cntr=0.3,0.1

Type RM Length L Ch R = 1,5563,88,88,88
BEGIN DESCRIPTION:
Mapping XS 25f48a0c
END DESCRIPTION:
XS GIS Cut Line= 5
      2309290.16      7140155.50      2309123.93      7140227.32
      2308239.44      7140462.52      2308173.98      7140461.83
      2308036.66      7140378.13
#Sta/Elev= 30
  4387.4  787.63  4437.1  786.55  4460.6  785.16  4466.1  785.80  4484.1  784.61
  4489.6  786.90  4507.6  785.65  4513.1  786.76  4519.4  786.95  4536.6  785.57
  4542.0  786.90  4708.1  787.57  4894.4  787.35  4909.8  786.79  5163.4  787.61
  5255.6  787.20  5260.8  786.61  5308.3  787.47  5401.4  787.22  5416.2  786.25
  5422.1  786.92  5514.2  786.44  5534.2  782.55  5544.2  782.23  5675.2  782.22
  5675.9  781.72  5680.3  782.22  5693.2  784.14  5705.7  787.19  5710.0  787.19
#Mann=3,-1,0
  4387.4    0.05       0  5675.2   0.033       0  5680.3    0.05       0
Bank Sta=5675.2,5680.3
Exp/Cntr=0.3,0.1

Type RM Length L Ch R = 1,5475,480,480,480
BEGIN DESCRIPTION:
Mapping XS 3ff005eb
END DESCRIPTION:
XS GIS Cut Line= 5
      2309187.51      7140061.34      2308989.97      7140169.62
      2308460.98      7140322.02      2308251.21      7140022.09
      2308015.36      7140154.98
#Sta/Elev= 30
  4450.8  785.62  4522.0  782.27  4581.7  772.10  4778.2  758.49  4839.2  756.53
  4846.5  758.62  4872.9  756.58  4916.9  759.77  4945.4  757.39  4950.6  760.16
  4984.3  757.18  4989.5  760.76  5051.6  758.22  5056.8  761.33  5090.5  757.76
  5095.7  761.44  5114.2  759.94  5168.3  765.31  5230.9  767.04  5329.4  764.69
  5365.1  762.79  5394.8  757.09  5514.3  753.18  5515.0  752.68  5519.4  753.18
  5552.6  756.09  5588.4  766.58  5696.5  766.68  5767.3  773.54  5863.3  777.91
#Mann=5,-1,0
  4450.8    0.05       0  4778.2    0.12       0  4846.5    0.05       0
  5514.3   0.033       0  5519.4    0.05       0
Bank Sta=5514.3,5519.4
Exp/Cntr=0.3,0.1

Type RM Length L Ch R = 1,4995,400,400,400
BEGIN DESCRIPTION:
Mapping XS 47adb19e
END DESCRIPTION:
XS GIS Cut Line= 2
      2308982.17      7139702.04      2308079.60      7140097.23
#Sta/Elev= 30
  4347.9  768.46  4395.0  767.56  4416.9  764.58  4582.9  755.29  4635.2  752.79
  4653.0  753.27  4667.9  751.45  4686.9  751.85  4757.5  749.17  4809.9  751.47
  4827.6  749.79  4959.5  749.66  4995.4  747.48  5014.7  743.58  5015.4  743.08
  5019.8  743.58  5039.1  744.87  5049.0  747.10  5054.4  745.73  5077.8  753.86
  5083.3  752.42  5101.2  758.92  5106.7  757.95  5124.6  762.74  5130.0  761.64
  5137.4  764.95  5159.2  767.59  5205.6  767.33  5223.6  765.47  5333.2  772.23
#Mann=5,-1,0
  4347.9    0.05       0  4686.9    0.12       0  4959.5    0.05       0
  5014.7   0.033       0  5019.8    0.05       0
Bank Sta=5014.7,5019.8
Exp/Cntr=0.3,0.1

Type RM Length L Ch R = 1,4595,437,437,437
BEGIN DESCRIPTION:
Burns Branch 10.0
END DESCRIPTION:
XS GIS Cut Line= 3
      2308579.02      7139660.01      2308429.00      7139610.00
      2308128.98      7139660.00
#Sta/Elev= 30
  4847.7  758.43  4858.3  757.88  4868.8  755.76  4889.9  755.80  4900.4  751.85
  4921.5  749.93  4932.1  747.14  4953.1  746.37  4984.8  741.71  4992.7  741.35
  4993.4  740.85  4997.2  740.85  4997.8  741.35  5003.2  741.88  5033.7  741.94
  5056.5  744.27  5076.8  744.96  5086.9  745.85  5089.5  745.47  5094.5  744.75
  5099.6  745.41  5117.4  746.04  5178.2  747.12  5208.6  748.77  5228.9  750.63
  5249.1  753.53  5259.3  754.44  5299.8  760.73  5307.4  762.53  5310.0  762.53
#Mann=4,-1,0
  4847.7    0.12       0  4992.7    0.07       0  4997.8    0.12       0
  5089.5    0.05       0
Bank Sta=4992.7,4997.8
Exp/Cntr=0.3,0.1

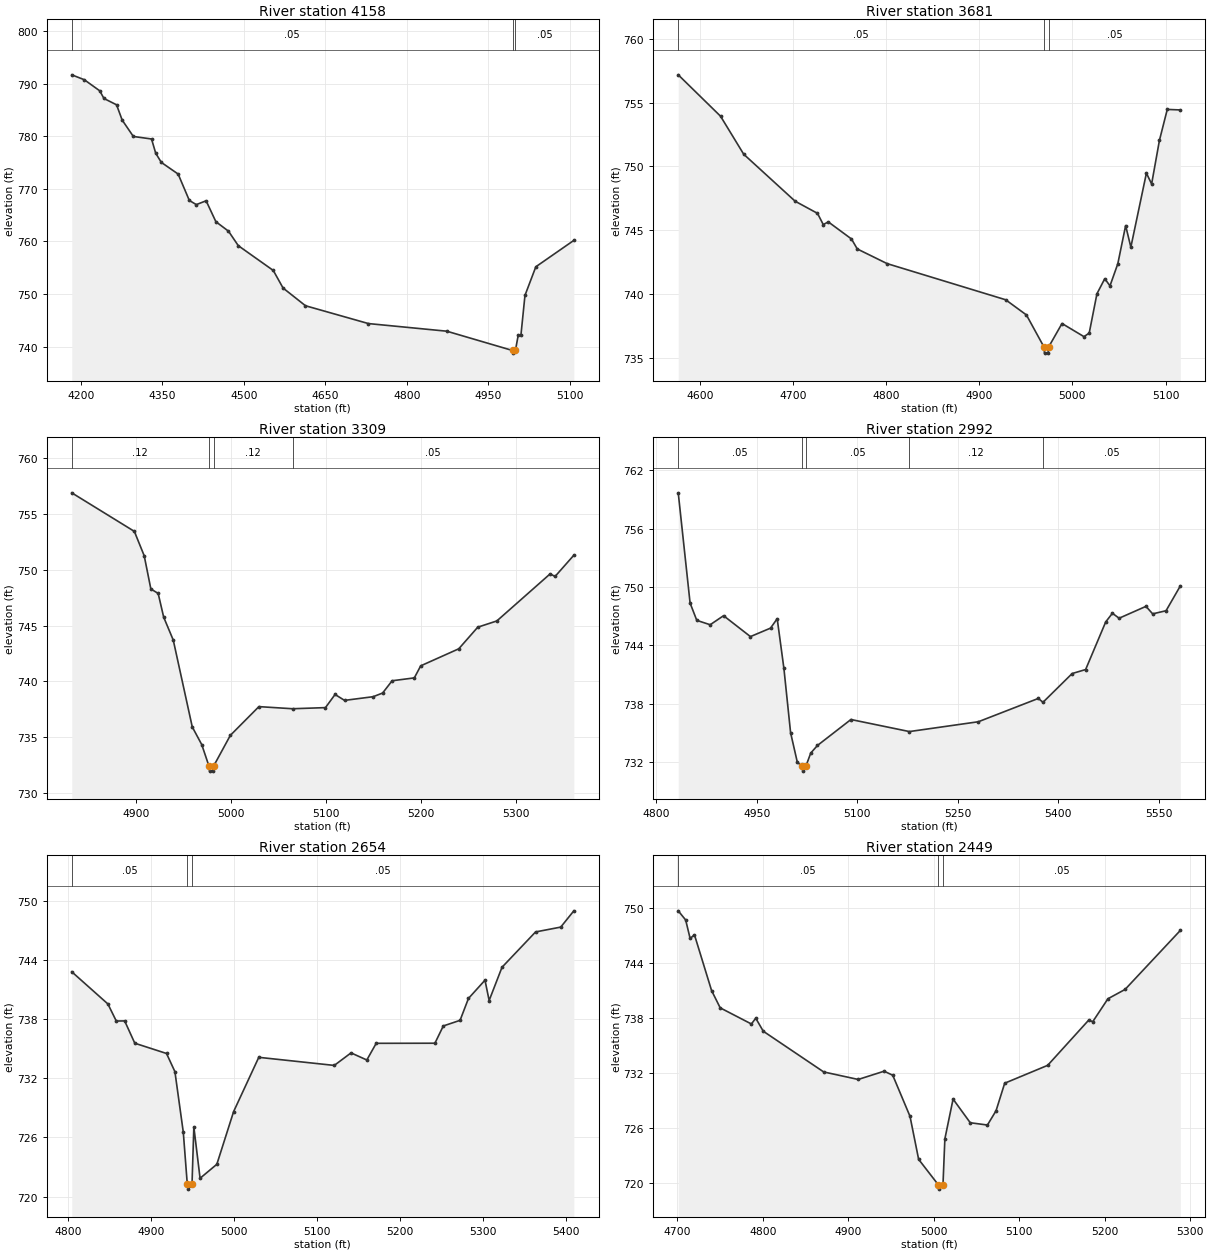
Type RM Length L Ch R = 1,4158,477,477,477
BEGIN DESCRIPTION:
Burns Branch 9.0
END DESCRIPTION:
XS GIS Cut Line= 3
      2308979.01      7139160.00      2308179.00      7139360.00
      2308079.03      7139360.00
#Sta/Elev= 30
  4183.2  791.69  4206.4  790.75  4234.7  788.65  4242.5  787.19  4265.7  785.99
  4276.0  783.09  4296.6  779.97  4330.1  779.49  4337.8  776.78  4348.1  775.04
  4379.1  772.82  4399.7  767.80  4412.6  767.01  4430.6  767.74  4448.6  763.76
  4471.8  761.96  4489.9  759.20  4554.3  754.49  4572.3  751.15  4613.6  747.78
  4729.5  744.39  4873.8  742.94  4994.9  739.27  4995.6  738.77  5000.2  739.27
  5005.3  742.14  5010.3  742.14  5017.8  749.75  5037.8  755.19  5107.8  760.21
#Mann=3,-1,0
  4183.2    0.05       0  4994.9   0.033       0  5000.2    0.05       0
Bank Sta=4994.9,5000.2
Exp/Cntr=0.3,0.1

Type RM Length L Ch R = 1,3681,372,372,372
BEGIN DESCRIPTION:
Burns Branch 8.0
END DESCRIPTION:
XS GIS Cut Line= 3
      2308678.98      7139059.99      2308279.00      7138910.00
      2308178.98      7138960.01
#Sta/Elev= 30
  4576.9  757.17  4622.3  753.93  4647.2  750.95  4702.4  747.27  4726.4  746.32
  4732.6  745.44  4738.0  745.65  4762.9  744.31  4769.1  743.53  4801.2  742.38
  4928.4  739.55  4950.7  738.36  4969.4  735.87  4970.1  735.37  4973.9  735.37
  4974.7  735.87  4988.9  737.69  5012.5  736.66  5018.1  736.94  5026.4  740.02
  5034.8  741.20  5040.4  740.64  5048.8  742.37  5057.2  745.36  5062.8  743.67
  5079.5  749.47  5085.1  748.62  5093.5  752.04  5101.9  754.46  5115.9  754.42
#Mann=3,-1,0
  4576.9    0.05       0  4969.4   0.033       0  4974.7    0.05       0
Bank Sta=4969.4,4974.7
Exp/Cntr=0.3,0.1

Type RM Length L Ch R = 1,3309,317,317,317
BEGIN DESCRIPTION:
Mapping XS 78cca1f1
END DESCRIPTION:
XS GIS Cut Line= 3
      2308592.32      7138561.59      2308504.81      7138586.62
      2308068.06      7138616.63
#Sta/Elev= 30
  4832.6  756.91  4898.5  753.45  4908.9  751.26  4915.9  748.28  4923.6  747.88
  4929.4  745.75  4939.5  743.69  4959.5  735.90  4969.5  734.31  4976.9  732.43
  4977.7  731.93  4981.5  731.93  4982.3  732.43  4999.6  735.14  5029.7  737.72
  5065.1  737.53  5099.8  737.63  5109.9  738.81  5119.9  738.28  5150.0  738.61
  5160.0  738.94  5170.0  740.04  5193.4  740.30  5200.1  741.38  5240.2  742.91
  5260.2  744.85  5280.3  745.41  5336.5  749.64  5341.6  749.40  5361.4  751.31
#Mann=4,-1,0
  4832.6    0.12       0  4976.9    0.07       0  4982.3    0.12       0
  5065.1    0.05       0
Bank Sta=4976.9,4982.3
Exp/Cntr=0.3,0.1

Type RM Length L Ch R = 1,2992,338,338,338
BEGIN DESCRIPTION:
Mapping XS 8bd24372
END DESCRIPTION:
XS GIS Cut Line= 2
      2308696.65      7138331.09      2307947.71      7138295.02
#Sta/Elev= 30
  4832.6  759.70  4850.3  748.36  4860.3  746.58  4880.3  746.13  4900.3  747.06
  4940.4  744.91  4970.4  745.78  4980.4  746.75  4990.4  741.64  5000.4  735.02
  5010.5  731.97  5017.8  731.57  5018.6  731.07  5023.2  731.57  5030.5  732.93
  5040.5  733.71  5090.5  736.38  5177.8  735.14  5280.8  736.15  5370.4  738.55
  5377.3  738.15  5420.9  741.11  5441.0  741.52  5471.0  746.42  5481.0  747.31
  5491.0  746.80  5531.1  748.02  5541.1  747.25  5561.1  747.57  5582.4  750.12
#Mann=5,-1,0
  4832.6    0.05       0  5017.8   0.033       0  5023.2    0.05       0
  5177.8    0.12       0  5377.3    0.05       0
Bank Sta=5017.8,5023.2
Exp/Cntr=0.3,0.1

Type RM Length L Ch R = 1,2654,205,205,205
BEGIN DESCRIPTION:
Mapping XS 1185fa37
END DESCRIPTION:
XS GIS Cut Line= 2
      2308622.03      7137994.81      2308023.36      7138079.29
#Sta/Elev= 30
  4804.9  742.79  4848.4  739.53  4858.5  737.80  4868.6  737.81  4880.8  735.55
  4919.0  734.51  4929.1  732.67  4939.2  726.53  4944.0  721.26  4944.9  720.76
  4949.7  721.26  4951.9  727.06  4959.4  721.86  4979.6  723.28  4999.8  728.62
  5030.1  734.12  5121.0  733.30  5141.2  734.57  5160.2  733.85  5171.5  735.54
  5242.2  735.55  5252.3  737.30  5272.5  737.87  5282.6  740.09  5302.5  741.94
  5307.5  739.88  5323.0  743.25  5363.4  746.83  5393.7  747.32  5409.5  748.97
#Mann=3,-1,0
  4804.9    0.05       0  4944.0   0.033       0  4949.7    0.05       0
Bank Sta=4944,4949.7
Exp/Cntr=0.3,0.1

Type RM Length L Ch R = 1,2449,160,160,160
BEGIN DESCRIPTION:
Mapping XS 7191b8b8
END DESCRIPTION:
XS GIS Cut Line= 3
      2308627.60      7137813.06      2308337.98      7137853.28
      2308044.81      7137886.98
#Sta/Elev= 30
  4701.1  749.69  4709.8  748.69  4715.0  746.68  4720.1  747.07  4740.1  741.00
  4750.2  739.11  4786.7  737.35  4791.8  737.98  4800.6  736.56  4871.3  732.12
  4911.7  731.30  4942.0  732.20  4952.1  731.76  4972.3  727.28  4982.4  722.59
  5005.2  719.84  5006.1  719.34  5010.9  719.84  5013.1  724.82  5022.7  729.16
  5042.8  726.58  5062.9  726.33  5073.0  727.89  5083.1  730.89  5133.4  732.84
  5181.2  737.75  5186.2  737.61  5203.9  740.10  5224.0  741.12  5288.6  747.55
#Mann=3,-1,0
  4701.1    0.05       0  5005.2   0.033       0  5010.9    0.05       0
Bank Sta=5005.2,5010.9
Exp/Cntr=0.3,0.1

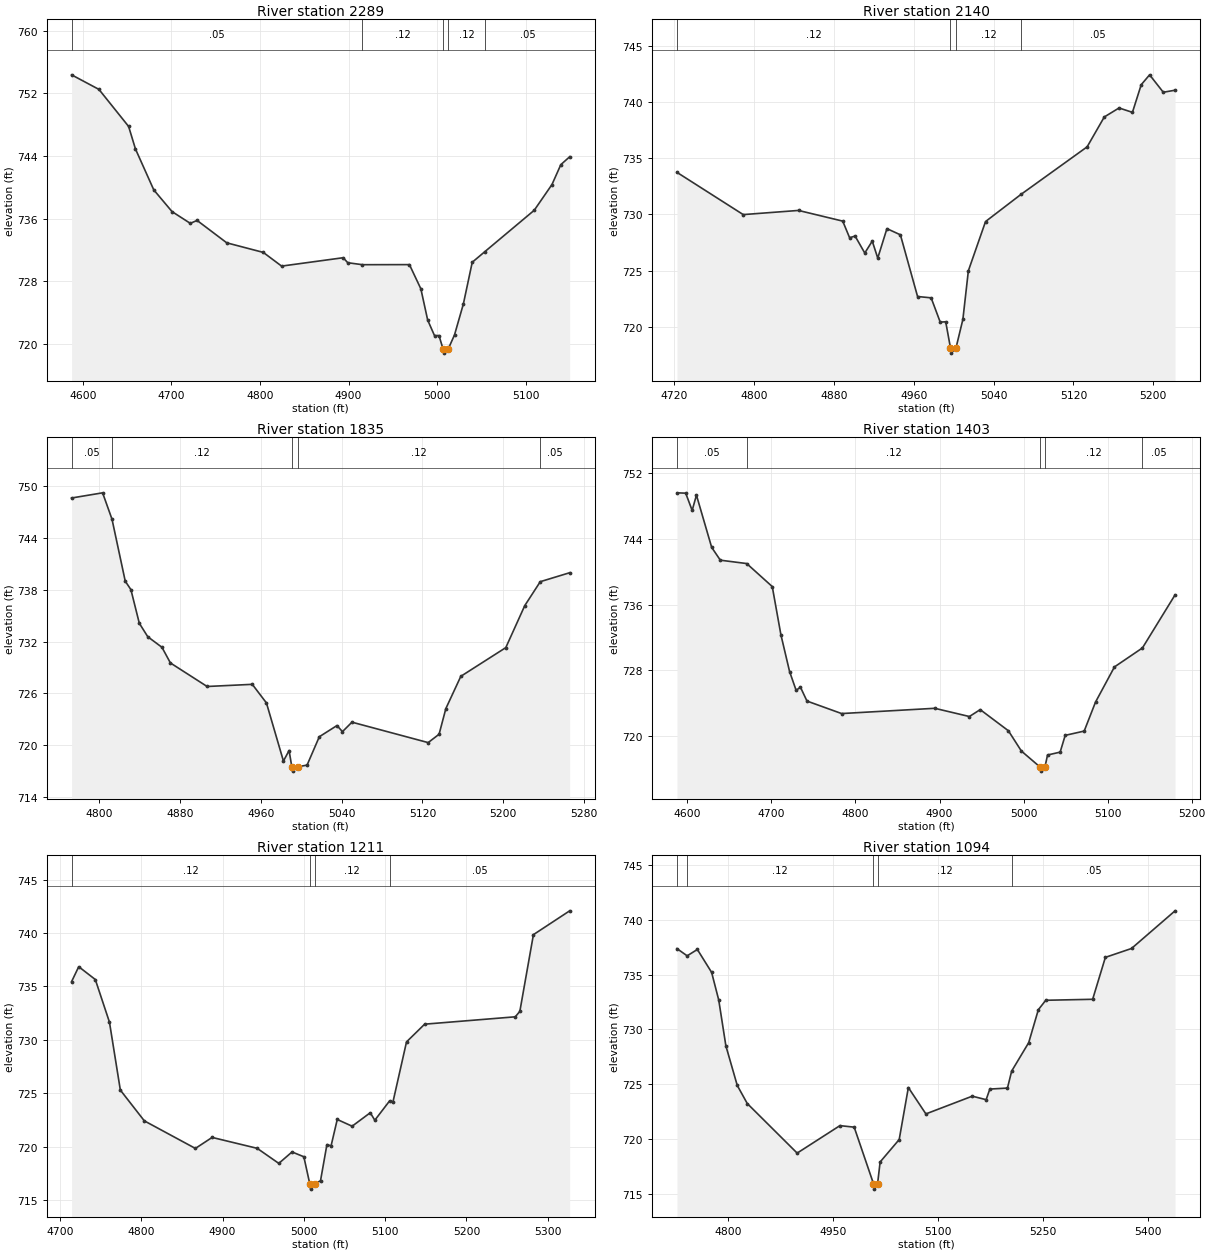
Type RM Length L Ch R = 1,2289,149,149,149
BEGIN DESCRIPTION:
Burns Branch 5.0
END DESCRIPTION:
XS GIS Cut Line= 3
      2308678.98      7137810.00      2308279.00      7137710.00
      2308128.99      7137710.00
#Sta/Elev= 30
  4587.3  754.37  4618.2  752.51  4651.7  747.78  4659.4  744.91  4680.1  739.68
  4700.7  736.91  4721.3  735.41  4729.0  735.78  4762.5  732.92  4803.7  731.70
  4824.4  729.95  4893.9  731.02  4899.1  730.38  4915.7  730.13  4968.7  730.14
  4981.6  727.05  4989.3  723.06  4997.0  721.08  5002.1  721.08  5006.7  719.34
  5007.6  718.84  5012.4  719.34  5019.6  721.17  5029.6  725.12  5039.6  730.44
  5054.0  731.81  5109.6  737.08  5129.6  740.36  5139.6  742.90  5149.6  743.91
#Mann=5,-1,0
  4587.3    0.05       0  4915.7    0.12       0  5006.7    0.07       0
  5012.4    0.12       0  5054.0    0.05       0
Bank Sta=5006.7,5012.4
Exp/Cntr=0.3,0.1

Type RM Length L Ch R = 1,2140,305,305,305
BEGIN DESCRIPTION:
Mapping XS 17179851
END DESCRIPTION:
XS GIS Cut Line= 2
      2308528.93      7137679.97      2308078.37      7137465.27
#Sta/Elev= 30
  4722.7  733.74  4789.1  729.98  4844.5  730.35  4888.8  729.40  4895.7  727.92
  4901.2  728.07  4910.9  726.56  4918.4  727.62  4923.9  726.11  4933.1  728.73
  4946.6  728.18  4963.8  722.69  4977.4  722.57  4986.5  720.41  4992.0  720.44
  4996.7  718.15  4997.6  717.65  5002.4  718.15  5009.2  720.65  5014.7  724.98
  5031.9  729.36  5067.3  731.77  5133.7  736.01  5150.9  738.67  5165.7  739.47
  5179.1  739.08  5187.9  741.54  5196.3  742.42  5210.0  740.87  5221.8  741.05
#Mann=4,-1,0
  4722.7    0.12       0  4996.7    0.07       0  5002.4    0.12       0
  5067.3    0.05       0
Bank Sta=4996.7,5002.4
Exp/Cntr=0.3,0.1

Type RM Length L Ch R = 1,1835,432,432,432
BEGIN DESCRIPTION:
Burns Branch 4.0
END DESCRIPTION:
XS GIS Cut Line= 3
      2308628.97      7137210.02      2308429.00      7137310.00
      2308179.02      7137210.01
#Sta/Elev= 30
  4772.9  748.65  4803.6  749.25  4812.9  746.19  4826.0  739.00  4831.6  738.02
  4839.9  734.12  4848.3  732.55  4862.3  731.33  4870.7  729.51  4907.0  726.78
  4951.7  727.03  4965.7  724.87  4982.5  718.13  4988.1  719.35  4990.8  717.46
  4991.7  716.96  4996.6  717.46  5005.9  717.66  5018.0  720.95  5035.5  722.25
  5040.9  721.54  5050.3  722.64  5125.7  720.27  5136.5  721.24  5143.2  724.22
  5158.0  727.96  5202.5  731.29  5221.3  736.17  5236.6  738.94  5265.7  739.98
#Mann=5,-1,0
  4772.9    0.05       0  4812.9    0.12       0  4990.8    0.07       0
  4996.6    0.12       0  5236.6    0.05       0
Bank Sta=4990.8,4996.6
Exp/Cntr=0.3,0.1

Type RM Length L Ch R = 1,1403,192,192,192
BEGIN DESCRIPTION:
Burns Branch 3.0
END DESCRIPTION:
XS GIS Cut Line= 3
      2308679.05      7136859.99      2308279.00      7136960.00
      2308179.02      7137109.97
#Sta/Elev= 30
  4587.6  749.59  4598.0  749.55  4605.7  747.45  4610.8  749.31  4628.9  742.96
  4639.2  741.40  4670.6  740.99  4701.0  738.19  4711.3  732.32  4721.6  727.86
  4729.4  725.57  4734.5  725.96  4742.3  724.27  4783.5  722.75  4894.3  723.39
  4935.5  722.39  4948.4  723.23  4981.9  720.66  4997.4  718.19  5019.6  716.25
  5020.5  715.75  5025.4  716.25  5028.5  717.71  5043.5  718.06  5049.5  720.10
  5072.1  720.62  5085.6  724.15  5108.1  728.42  5141.4  730.73  5180.2  737.18
#Mann=5,-1,0
  4587.6    0.05       0  4670.6    0.12       0  5019.6    0.07       0
  5025.4    0.12       0  5141.4    0.05       0
Bank Sta=5019.6,5025.4
Exp/Cntr=0.3,0.1

Type RM Length L Ch R = 1,1211,117,117,117
BEGIN DESCRIPTION:
Mapping XS 9aecdfad
END DESCRIPTION:
XS GIS Cut Line= 3
      2308557.48      7136704.14      2308232.95      7136778.62
      2307983.16      7136904.54
#Sta/Elev= 30
  4714.3  735.45  4723.1  736.85  4743.5  735.65  4760.9  731.66  4774.3  725.30
  4803.8  722.42  4866.6  719.84  4887.2  720.87  4942.6  719.85  4969.2  718.44
  4985.5  719.51  5000.0  719.06  5007.3  716.53  5008.3  716.03  5013.2  716.53
  5020.5  716.81  5028.4  720.20  5033.5  720.08  5041.1  722.55  5059.4  721.92
  5081.7  723.18  5087.3  722.48  5105.6  724.30  5109.6  724.18  5126.3  729.81
  5148.6  731.47  5260.1  732.16  5265.7  732.67  5282.4  739.85  5327.0  742.08
#Mann=4,-1,0
  4714.3    0.12       0  5007.3    0.07       0  5013.2    0.12       0
  5105.6    0.05       0
Bank Sta=5007.3,5013.2
Exp/Cntr=0.3,0.1

Type RM Length L Ch R = 1,1094,243,243,243
BEGIN DESCRIPTION:
Mapping XS e4bbbea4
END DESCRIPTION:
XS GIS Cut Line= 3
      2308547.68      7136597.98      2308237.85      7136659.63
      2307865.37      7136796.38
#Sta/Elev= 30
  4726.5  737.38  4741.1  736.72  4755.7  737.30  4776.1  735.21  4786.3  732.68
  4796.5  728.50  4812.8  724.88  4827.1  723.23  4898.5  718.70  4959.7  721.21
  4980.1  721.07  5007.7  715.91  5008.6  715.41  5013.6  715.91  5017.2  717.89
  5044.5  719.94  5057.6  724.69  5082.7  722.28  5149.0  723.90  5168.9  723.58
  5174.2  724.55  5199.4  724.64  5205.4  726.19  5229.8  728.79  5243.6  731.80
  5254.2  732.66  5321.3  732.75  5339.5  736.58  5376.9  737.39  5439.2  740.83
#Mann=5,-1,0
  4726.5    0.05       0  4741.1    0.12       0  5007.7    0.07       0
  5013.6    0.12       0  5205.4    0.05       0
Bank Sta=5007.7,5013.6
Exp/Cntr=0.3,0.1

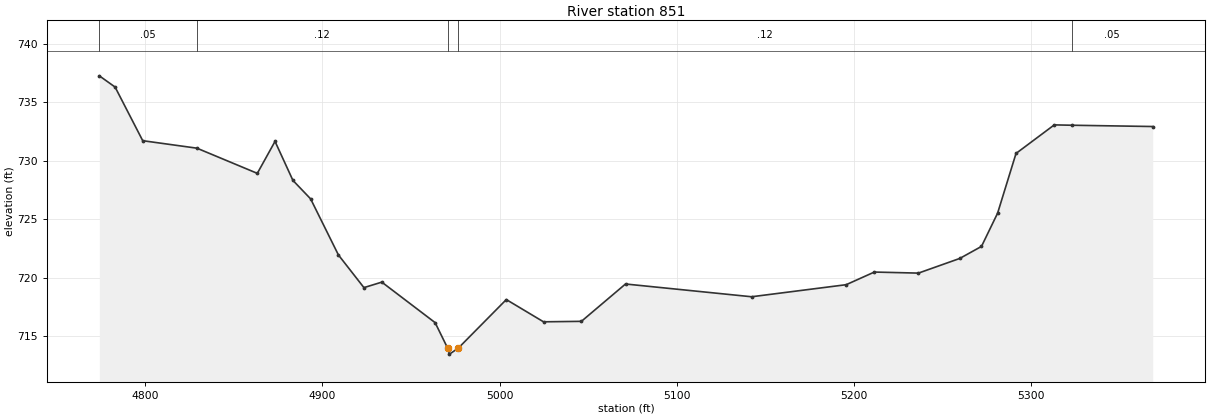
Type RM Length L Ch R = 1,851,0,0,0
BEGIN DESCRIPTION:
Mapping XS 8aaecfb5
END DESCRIPTION:
XS GIS Cut Line= 3
      2308427.83      7136412.73      2308192.94      7136434.06
      2307856.96      7136560.37
#Sta/Elev= 30
  4774.0  737.26  4782.9  736.30  4798.5  731.72  4829.1  731.08  4863.2  728.93
  4873.2  731.66  4883.3  728.33  4893.3  726.75  4909.0  721.96  4923.4  719.17
  4933.5  719.64  4963.6  716.18  4970.7  713.99  4971.7  713.49  4976.6  713.99
  5003.8  718.15  5024.8  716.25  5046.2  716.29  5071.1  719.48  5142.3  718.39
  5195.7  719.42  5211.6  720.50  5236.5  720.41  5259.8  721.66  5272.1  722.69
  5281.2  725.53  5291.6  730.63  5313.2  733.07  5323.0  733.04  5368.8  732.93
#Mann=5,-1,0
  4774.0    0.05       0  4829.1    0.12       0  4970.7    0.07       0
  4976.6    0.12       0  5323.0    0.05       0
Bank Sta=4970.7,4976.6
Exp/Cntr=0.3,0.1

Chan Stop Cuts=-1