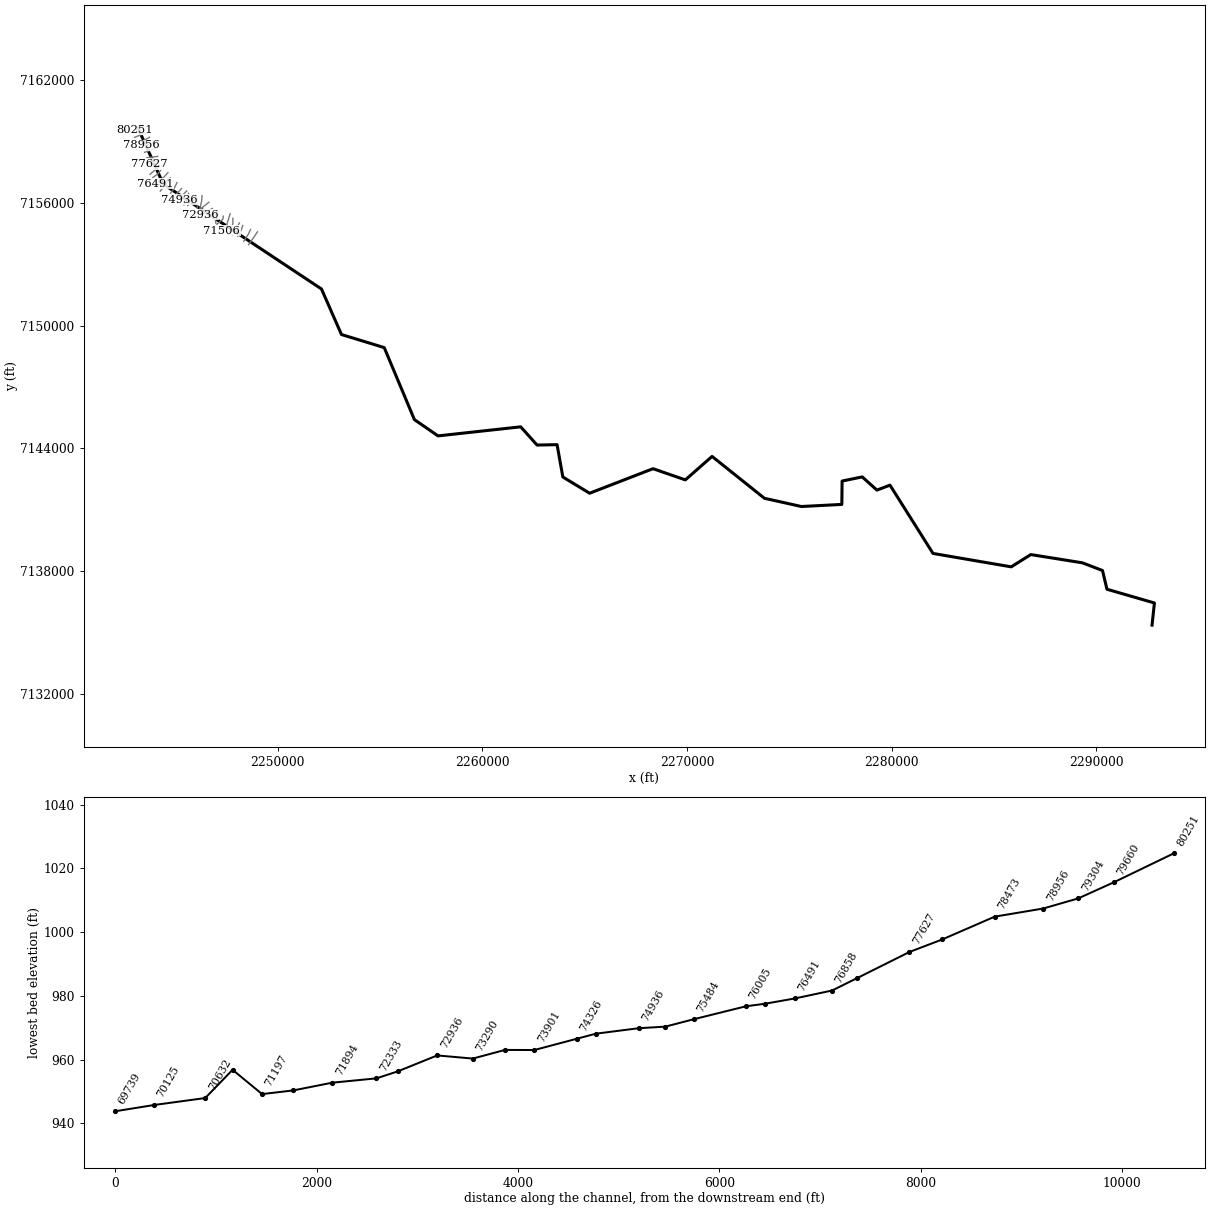
--- Catlett Creek.prj (project) ---

Proj Title=Catlett Creek Base Level Engineering
Current Plan=p01
Default Exp/Contr=0.3,0.1
English Units
Geom File=g01
Flow File=f01
Plan File=p01
BEGIN DESCRIPTION:
Catlett Creek
END DESCRIPTION:

--- Catlett Creek.p01 (plan) ---

Plan Title=Multiple Run
Short Identifier=Multiple
Geom File=g01
Flow File=f01
Subcritical Flow
K Sum by GR= 0
Std Step Tol= 0.01
Critical Tol= 0.01
Num of Std Step Trials= 20
Max Error Tol= 0.3
Flow Tol Ratio= 0.001
Split Flow NTrial= 30
Split Flow Tol= 0.02
Split Flow Ratio= 0.02
Log Output Level= 0
Friction Slope Method= 1
Unsteady Friction Slope Method= 2
Unsteady Bridges Friction Slope Method= 1
Parabolic Critical Depth
Global Vel Dist=  1 , 1 , 1
Global Log Level= 0
CheckData=True
Encroach Param= -1, 0, 0, 0
BEGIN DESCRIPTION:
Multiple Run
END DESCRIPTION:

--- Catlett Creek.f01 (steady flow) ---

Flow Title=Multiple
Number of Profiles=7
Profile Names=10-year,25-year,50-year,1pct_min,100-year,1pct_plu,500-year
River Rch & RM= Catlett Creek,Reach-1,80251
     751    1049    1300     800    1596    3185    2413
River Rch & RM= Catlett Creek,Reach-1,76190
     802    1122    1392     858    1712    3415    2592
River Rch & RM= Catlett Creek,Reach-1,74326
     944    1331    1660    1027    2050    4089    3131
River Rch & RM= Catlett Creek,Reach-1,72333
    1109    1572    1968    1221    2437    4863    3747
River Rch & RM= Catlett Creek,Reach-1,68618
    1204    1714    2150    1337    2667    5321    4116
River Rch & RM= Catlett Creek,Reach-1,67942
    1647    2382    3021    1897    3785    7552    5959
River Rch & RM= Catlett Creek,Reach-1,65248
    1908    2766    3514    2208    4406    8792    6951
River Rch & RM= Catlett Creek,Reach-1,58164
    2121    3089    3936    2480    4949    9875    7850
River Rch & RM= Catlett Creek,Reach-1,53826
    3799    5668    7339    4693    9364   18683   15293
River Rch & RM= Catlett Creek,Reach-1,51757
    3980    5944    7702    4928    9833   19619   16076
River Rch & RM= Catlett Creek,Reach-1,48446
    3957    5894    7625    4869    9716   19385   15825
River Rch & RM= Catlett Creek,Reach-1,43562
    4210    6285    8142    5207   10389   20729   16969
River Rch & RM= Catlett Creek,Reach-1,43083
    4325    6458    8367    5351   10676   21302   17437
River Rch & RM= Catlett Creek,Reach-1,40256
    4460    6662    8634    5522   11019   21985   18002
River Rch & RM= Catlett Creek,Reach-1,38436
    4512    6741    8737    5588   11150   22247   18215
River Rch & RM= Catlett Creek,Reach-1,37087
    5493    8252   10738    6892   13751   27436   22617
River Rch & RM= Catlett Creek,Reach-1,33536
    5809    8740   11383    7312   14590   29110   24037
River Rch & RM= Catlett Creek,Reach-1,32677
    5697    8547   11109    7121   14208   28348   23308
River Rch & RM= Catlett Creek,Reach-1,29439
    5837    8756   11379    7293   14552   29034   23864
River Rch & RM= Catlett Creek,Reach-1,24945
    5931    8897   11564    7411   14787   29504   24248
River Rch & RM= Catlett Creek,Reach-1,19813
    6647    9993   13008    8347   16655   33231   27376
River Rch & RM= Catlett Creek,Reach-1,15677
    6655    9988   12986    8322   16604   33129   27220
River Rch & RM= Catlett Creek,Reach-1,10296
    7095   10656   13863    8888   17734   35383   29095
River Rch & RM= Catlett Creek,Reach-1,4456
    9006   13602   17765   11430   22806   45503   37670
Boundary for River Rch & Prof#=Catlett Creek,Reach-1,1
Up Type=0
Dn Type=1
Dn Known WS=751.7
Boundary for River Rch & Prof#=Catlett Creek,Reach-1,2
Up Type=0
Dn Type=1
Dn Known WS=752.88
Boundary for River Rch & Prof#=Catlett Creek,Reach-1,3
Up Type=0
Dn Type=1
Dn Known WS=753.68
Boundary for River Rch & Prof#=Catlett Creek,Reach-1,4
Up Type=0
Dn Type=1
Dn Known WS=752.38
Boundary for River Rch & Prof#=Catlett Creek,Reach-1,5
Up Type=0
Dn Type=1
Dn Known WS=754.38
Boundary for River Rch & Prof#=Catlett Creek,Reach-1,6
Up Type=0
Dn Type=1
Dn Known WS=756.75
Boundary for River Rch & Prof#=Catlett Creek,Reach-1,7
Up Type=0
Dn Type=1
Dn Known WS=756.02

--- Catlett Creek.g01 (geometry) ---

Geom Title=Existing Conditions

River Reach=Catlett Creek,Reach-1
Reach XY= 30
      2243179.00      7159660.00      2244411.69      7156926.27
      2252142.31      7151796.63      2253118.94      7149570.03
      2255209.37      7148930.15      2256684.03      7145407.69
      2257837.44      7144613.41      2261877.55      7145056.47
      2262676.29      7144165.40      2263655.71      7144183.67
      2263936.93      7142603.60      2265244.77      7141809.89
      2268344.11      7143009.73      2269923.31      7142461.87
      2271229.00      7143610.00      2273787.32      7141562.96
      2275594.16      7141160.36      2277570.53      7141262.58
      2277583.95      7142405.06      2278567.12      7142608.47
      2279285.03      7141961.61      2279923.59      7142204.82
      2282026.30      7138865.36      2285849.03      7138210.07
      2286804.01      7138810.43      2289323.14      7138407.94
      2290309.24      7138030.13      2290526.26      7137115.34
      2292845.77      7136443.57      2292729.00      7135360.00

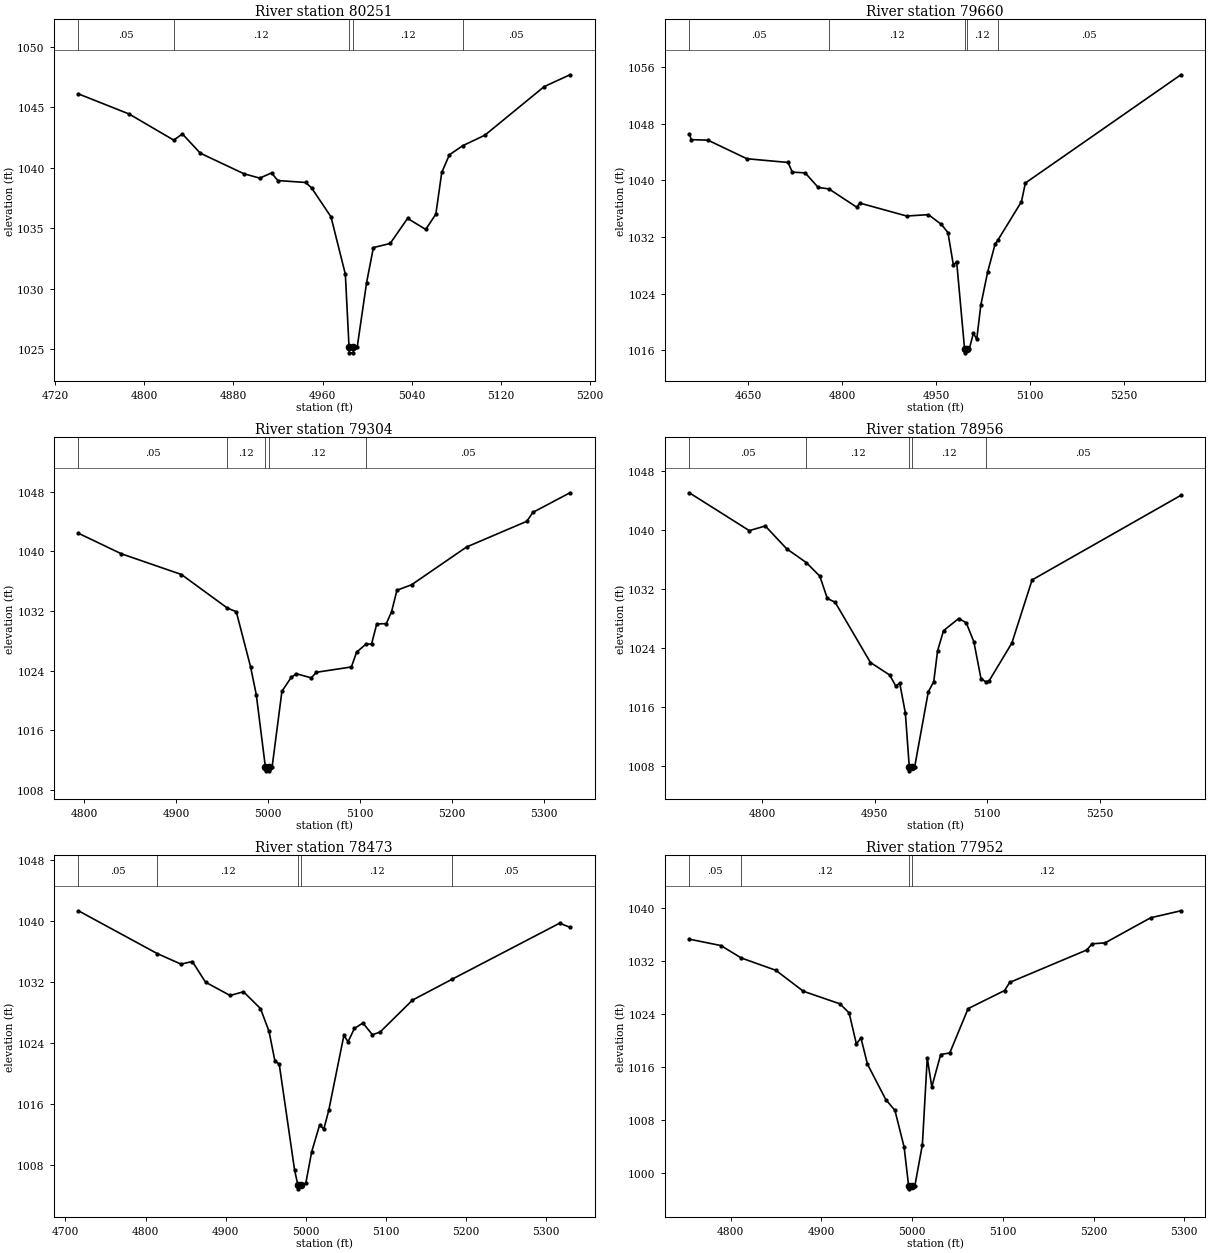
Type RM Length L Ch R = 1,80251,591,591,591
BEGIN DESCRIPTION:
Catlett Creek 105.0
END DESCRIPTION:
XS GIS Cut Line= 3
      2243421.67      7159737.47      2243189.77      7159651.26
      2243007.09      7159585.39
#Sta/Elev= 30
  4740.7 1046.09  4786.2 1044.43  4826.3 1042.27  4834.1 1042.78  4850.2 1041.19
  4889.4 1039.49  4903.6 1039.13  4914.2 1039.56  4919.8 1038.93  4944.8 1038.77
  4950.1 1038.33  4967.6 1035.93  4980.5 1031.19  4983.8 1025.19  4984.1 1024.69
  4987.6 1024.69  4987.8 1025.19  4991.2 1025.19  4999.6 1030.50  5005.7 1033.39
  5020.8 1033.73  5036.4 1035.80  5052.7 1034.89  5061.8 1036.15  5067.1 1039.60
  5074.0 1041.06  5086.0 1041.81  5105.9 1042.68  5159.1 1046.69  5182.3 1047.67
#Mann=5,-1,0
  4740.7    0.05       0  4826.3    0.12       0  4983.8    0.07       0
  4987.8    0.12       0  5086.0    0.05       0
Bank Sta=4983.8,4987.8
Exp/Cntr=0.3,0.1

Type RM Length L Ch R = 1,79660,356,356,356
BEGIN DESCRIPTION:
Catlett Creek 104.0
END DESCRIPTION:
XS GIS Cut Line= 3
      2243757.71      7159455.73      2243328.74      7159340.04
      2243013.14      7159211.95
#Sta/Elev= 30
  4555.7 1046.53  4559.0 1045.74  4585.4 1045.67  4647.6 1043.05  4713.5 1042.52
  4720.1 1041.16  4740.8 1041.05  4761.5 1039.00  4778.7 1038.79  4822.9 1036.22
  4828.1 1036.79  4902.7 1034.97  4937.5 1035.16  4958.3 1033.78  4968.7 1032.63
  4977.4 1028.04  4982.6 1028.54  4995.3 1016.17  4995.5 1015.67  4999.3 1016.17
  5002.6 1016.17  5009.3 1018.43  5014.7 1017.61  5021.3 1022.45  5032.1 1027.06
  5044.1 1031.04  5048.1 1031.52  5086.1 1036.99  5092.3 1039.62  5340.6 1054.89
#Mann=5,-1,0
  4555.7    0.05       0  4778.7    0.12       0  4995.3    0.07       0
  4999.3    0.12       0  5048.1    0.05       0
Bank Sta=4995.3,4999.3
Exp/Cntr=0.3,0.1

Type RM Length L Ch R = 1,79304,348,348,348
BEGIN DESCRIPTION:
Catlett Creek 103.0
END DESCRIPTION:
XS GIS Cut Line= 3
      2243743.15      7159218.47      2243562.06      7159119.01
      2243273.53      7158962.19
#Sta/Elev= 30
  4793.4 1042.44  4840.1 1039.69  4905.5 1036.91  4955.6 1032.40  4965.2 1031.92
  4980.7 1024.56  4987.0 1020.78  4996.9 1011.08  4997.1 1010.58  5000.6 1010.58
  5000.9 1011.08  5004.2 1011.08  5014.9 1021.26  5025.0 1023.11  5030.6 1023.60
  5046.8 1023.05  5052.5 1023.80  5090.5 1024.51  5096.2 1026.50  5106.4 1027.58
  5112.4 1027.58  5118.1 1030.27  5128.5 1030.33  5134.2 1031.91  5140.1 1034.80
  5156.1 1035.54  5215.9 1040.60  5281.5 1044.05  5288.0 1045.24  5328.4 1047.87
#Mann=5,-1,0
  4793.4    0.05       0  4955.6    0.12       0  4996.9    0.07       0
  5000.9    0.12       0  5106.4    0.05       0
Bank Sta=4996.9,5000.9
Exp/Cntr=0.3,0.1

Type RM Length L Ch R = 1,78956,483,483,483
BEGIN DESCRIPTION:
Catlett Creek 102.0
END DESCRIPTION:
XS GIS Cut Line= 3
      2243985.90      7158951.59      2243700.10      7158869.72
      2243346.32      7158814.88
#Sta/Elev= 30
  4702.7 1045.08  4782.7 1039.95  4804.0 1040.58  4832.5 1037.49  4858.7 1035.62
  4876.7 1033.78  4886.7 1030.76  4897.1 1030.25  4944.2 1022.08  4969.9 1020.38
  4978.0 1018.89  4983.2 1019.29  4990.7 1015.26  4996.0 1007.90  4996.2 1007.40
  5000.0 1007.90  5003.1 1007.90  5021.3 1018.10  5028.6 1019.50  5033.7 1023.67
  5041.6 1026.39  5061.8 1028.04  5071.9 1027.47  5082.1 1024.87  5091.6 1019.88
  5098.0 1019.47  5102.3 1019.58  5132.7 1024.71  5159.7 1033.27  5358.0 1044.73
#Mann=5,-1,0
  4702.7    0.05       0  4858.7    0.12       0  4996.0    0.07       0
  5000.0    0.12       0  5098.0    0.05       0
Bank Sta=4996,5000
Exp/Cntr=0.3,0.1

Type RM Length L Ch R = 1,78473,521,521,521
BEGIN DESCRIPTION:
Catlett Creek 101.0
END DESCRIPTION:
XS GIS Cut Line= 3
      2244072.70      7158689.09      2243805.80      7158592.61
      2243496.94      7158477.26
#Sta/Elev= 30
  4716.2 1041.34  4814.6 1035.72  4844.2 1034.34  4858.4 1034.68  4874.8 1031.97
  4905.5 1030.22  4922.2 1030.71  4943.4 1028.51  4954.1 1025.51  4961.5 1021.59
  4966.8 1021.23  4986.0 1007.30  4990.1 1005.34  4990.4 1004.84  4994.1 1005.34
  5000.0 1005.58  5007.3 1009.69  5017.2 1013.21  5022.5 1012.70  5028.6 1015.13
  5047.5 1024.97  5052.8 1024.15  5060.6 1025.89  5071.3 1026.61  5083.1 1025.07
  5092.7 1025.42  5133.1 1029.61  5182.5 1032.35  5316.8 1039.71  5329.7 1039.17
#Mann=5,-1,0
  4716.2    0.05       0  4814.6    0.12       0  4990.1    0.07       0
  4994.1    0.12       0  5182.5    0.05       0
Bank Sta=4990.1,4994.1
Exp/Cntr=0.3,0.1

Type RM Length L Ch R = 1,77952,325,325,325
BEGIN DESCRIPTION:
Catlett Creek 100.0
END DESCRIPTION:
XS GIS Cut Line= 3
      2244143.39      7158281.00      2243900.38      7158246.87
      2243605.97      7158214.34
#Sta/Elev= 30
  4754.6 1035.32  4789.3 1034.36  4811.8 1032.49  4849.9 1030.63  4880.2 1027.47
  4920.6 1025.57  4930.7 1024.20  4938.7 1019.52  4943.7 1020.44  4950.9 1016.47
  4971.1 1011.14  4981.2 1009.50  4991.3 1003.97  4996.2  998.18  4996.4  997.68
  5000.2  998.18  5003.2  998.18  5011.4 1004.33  5016.8 1017.43  5021.8 1013.04
  5031.6 1017.93  5041.6 1018.17  5061.8 1024.85  5102.0 1027.58  5107.6 1028.80
  5192.5 1033.69  5198.4 1034.62  5212.7 1034.76  5263.0 1038.55  5296.2 1039.60
#Mann=4,-1,0
  4754.6    0.05       0  4811.8    0.12       0  4996.2    0.07       0
  5000.2    0.12       0
Bank Sta=4996.2,5000.2
Exp/Cntr=0.3,0.1

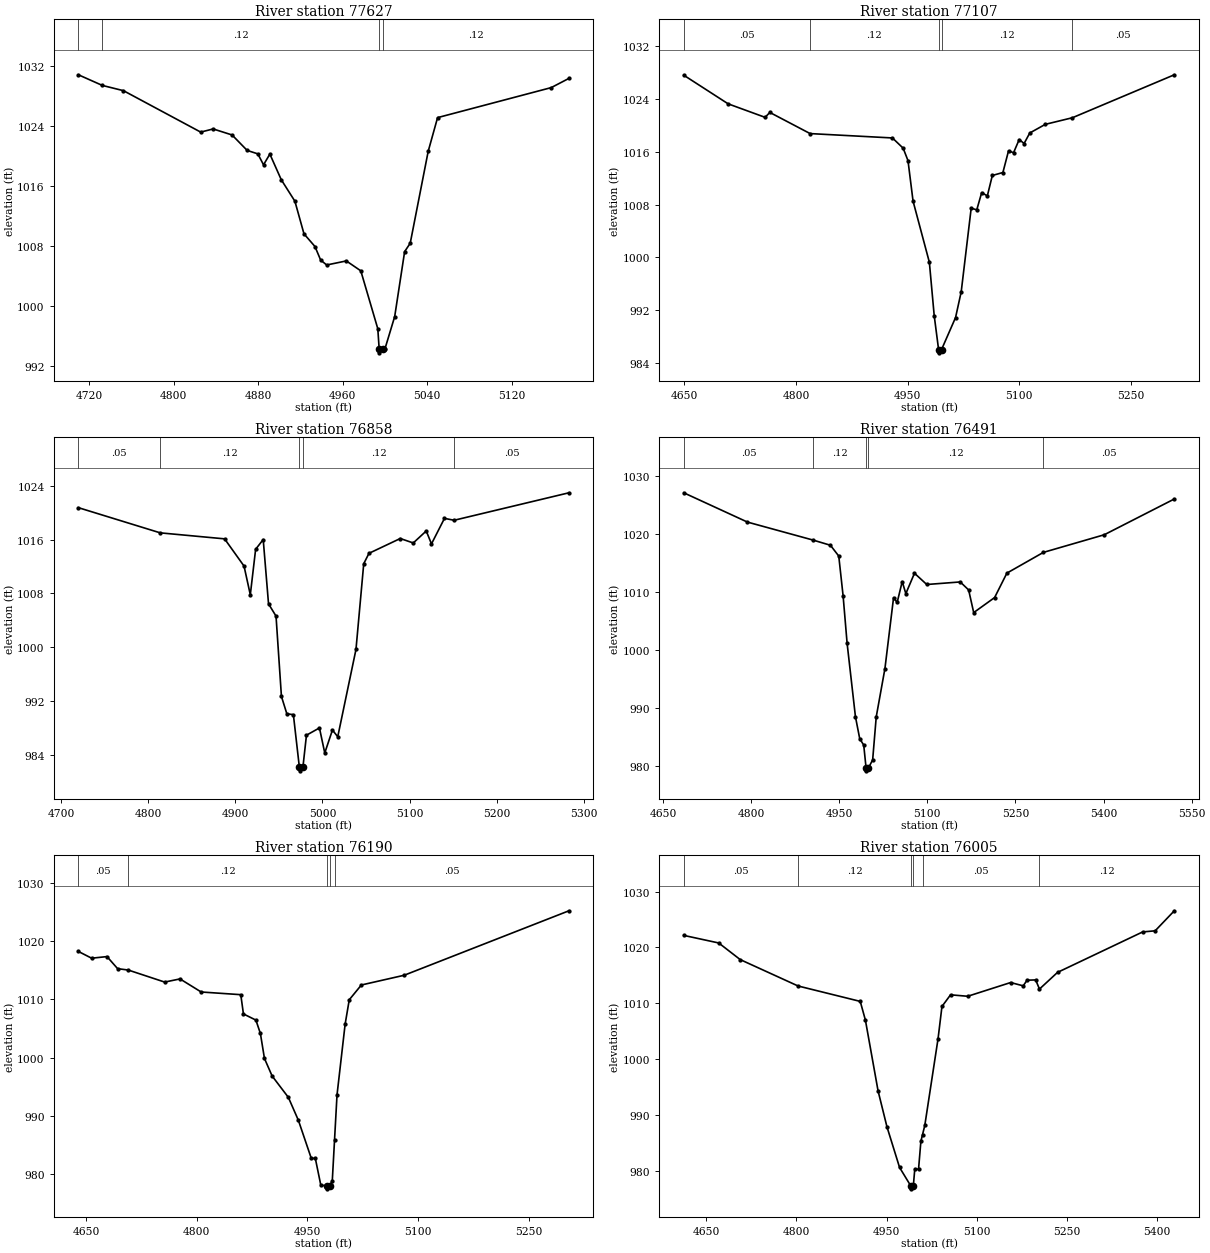
Type RM Length L Ch R = 1,77627,520,520,520
BEGIN DESCRIPTION:
Catlett Creek 99.0
END DESCRIPTION:
XS GIS Cut Line= 3
      2244167.67      7158069.12      2243897.75      7157962.53
      2243733.11      7157905.32
#Sta/Elev= 30
  4709.8 1030.82  4732.5 1029.40  4752.5 1028.70  4825.6 1023.18  4837.4 1023.60
  4855.3 1022.80  4869.6 1020.74  4879.7 1020.28  4885.1 1018.82  4891.1 1020.25
  4901.9 1016.83  4914.8 1013.97  4923.4 1009.62  4933.8 1007.93  4939.2 1006.12
  4944.9 1005.47  4963.5 1006.01  4977.2 1004.69  4993.3  996.97  4994.6  994.26
  4994.9  993.76  4998.6  994.26  5000.0  994.26  5009.3  998.60  5018.7 1007.25
  5024.0 1008.37  5041.0 1020.61  5049.9 1025.11  5157.5 1029.11  5174.3 1030.34
#Mann=4,-1,0
  4709.8    0.05       0  4732.5    0.12       0  4994.6    0.07       0
  4998.6    0.12       0
Bank Sta=4994.6,4998.6
Exp/Cntr=0.3,0.1

Type RM Length L Ch R = 1,77107,249,249,249
BEGIN DESCRIPTION:
Catlett Creek 98.0
END DESCRIPTION:
XS GIS Cut Line= 3
      2244269.01      7157823.62      2243995.64      7157603.62
      2243762.72      7157401.79
#Sta/Elev= 30
  4649.1 1027.58  4708.8 1023.24  4758.4 1021.20  4764.8 1021.94  4818.9 1018.74
  4929.5 1018.08  4943.9 1016.53  4950.4 1014.65  4957.2 1008.52  4979.1  999.27
  4985.6  991.21  4991.5  986.06  4991.8  985.56  4995.5  986.06  5014.3  990.90
  5021.9  994.80  5035.3 1007.45  5042.8 1007.20  5049.4 1009.81  5057.0 1009.31
  5063.7 1012.40  5077.9 1012.85  5085.5 1016.14  5092.2 1015.84  5099.8 1017.84
  5106.4 1017.24  5114.0 1018.83  5134.9 1020.14  5171.3 1021.14  5308.2 1027.64
#Mann=5,-1,0
  4649.1    0.05       0  4818.9    0.12       0  4991.5    0.07       0
  4995.5    0.12       0  5171.3    0.05       0
Bank Sta=4991.5,4995.5
Exp/Cntr=0.3,0.1

Type RM Length L Ch R = 1,76858,367,367,367
BEGIN DESCRIPTION:
Mapping XS 162fba7a
END DESCRIPTION:
XS GIS Cut Line= 3
      2244298.88      7157624.86      2244155.24      7157422.79
      2243895.83      7157244.48
#Sta/Elev= 30
  4720.0 1020.73  4813.9 1016.99  4887.7 1016.10  4910.0 1012.06  4917.2 1007.80
  4923.3 1014.55  4932.0 1016.00  4938.1 1006.45  4946.7 1004.63  4952.9  992.71
  4959.1  990.13  4966.6  990.00  4973.5  982.16  4973.7  981.66  4977.5  982.16
  4981.6  986.95  4996.5  988.03  5002.6  984.31  5011.4  987.72  5017.5  986.72
  5038.4  999.68  5047.3 1012.41  5053.3 1013.95  5089.2 1016.15  5104.1 1015.49
  5119.0 1017.27  5125.0 1015.35  5139.9 1019.14  5151.0 1018.86  5282.7 1022.94
#Mann=5,-1,0
  4720.0    0.05       0  4813.9    0.12       0  4973.5    0.07       0
  4977.5    0.12       0  5151.0    0.05       0
Bank Sta=4973.5,4977.5
Exp/Cntr=0.3,0.1

Type RM Length L Ch R = 1,76491,301,301,301
BEGIN DESCRIPTION:
Catlett Creek 96.0
END DESCRIPTION:
XS GIS Cut Line= 3
      2244639.27      7157482.95      2244425.94      7157251.72
      2244002.66      7156948.81
#Sta/Elev= 30
  4685.4 1027.09  4793.9 1022.04  4906.0 1018.93  4935.1 1018.05  4949.3 1016.19
  4956.7 1009.34  4963.5 1001.17  4977.7  988.51  4985.0  984.72  4991.8  983.63
  4995.8  979.69  4996.0  979.19  4999.8  979.69  5007.0  981.07  5013.1  988.49
  5027.9  996.81  5042.6 1009.03  5048.7 1008.19  5057.3 1011.79  5063.5 1009.72
  5078.2 1013.23  5099.1 1011.29  5156.1 1011.73  5170.4 1010.35  5179.0 1006.45
  5214.6 1009.04  5235.5 1013.25  5297.6 1016.82  5401.3 1019.86  5520.5 1026.02
#Mann=5,-1,0
  4685.4    0.05       0  4906.0    0.12       0  4995.8    0.07       0
  4999.8    0.12       0  5297.6    0.05       0
Bank Sta=4995.8,4999.8
Exp/Cntr=0.3,0.1

Type RM Length L Ch R = 1,76190,185,185,185
BEGIN DESCRIPTION:
Mapping XS 7ad3d1b1
END DESCRIPTION:
XS GIS Cut Line= 3
      2244648.66      7157195.01      2244510.51      7157027.60
      2244103.06      7156841.00
#Sta/Elev= 30
  4639.5 1018.19  4657.5 1017.03  4678.3 1017.31  4692.7 1015.24  4707.2 1015.00
  4756.5 1012.94  4777.3 1013.48  4806.0 1011.24  4859.7 1010.78  4863.3 1007.48
  4880.2 1006.42  4886.3 1004.13  4891.8  999.85  4902.2  996.84  4924.2  993.18
  4937.8  989.25  4955.3  982.73  4960.8  982.71  4968.2  978.14  4976.3  978.00
  4976.5  977.50  4980.3  978.00  4983.8  978.92  4986.8  985.81  4990.2  993.61
  5001.2 1005.73  5006.8 1009.91  5023.2 1012.44  5081.3 1014.11  5304.7 1025.16
#Mann=5,-1,0
  4639.5    0.05       0  4707.2    0.12       0  4976.3   0.033       0
  4980.3    0.12       0  4986.8    0.05       0
Bank Sta=4976.3,4980.3
Exp/Cntr=0.3,0.1

Type RM Length L Ch R = 1,76005,521,521,521
BEGIN DESCRIPTION:
Catlett Creek 95.0
END DESCRIPTION:
XS GIS Cut Line= 3
      2244760.45      7157228.40      2244538.98      7156910.06
      2244262.89      7156581.31
#Sta/Elev= 30
  4612.2 1022.15  4670.5 1020.79  4706.3 1017.81  4802.7 1013.08  4906.2 1010.32
  4914.8 1006.96  4935.9  994.28  4950.7  987.84  4971.7  980.56  4990.5  977.23
  4990.8  976.73  4994.6  977.23  4997.0  980.25  5003.3  980.25  5007.2  985.25
  5009.9  986.43  5013.7  988.09  5035.8 1003.64  5042.3 1009.41  5056.6 1011.50
  5085.2 1011.24  5156.7 1013.70  5177.6 1013.11  5184.1 1014.12  5198.4 1014.17
  5204.7 1012.53  5234.8 1015.52  5376.6 1022.77  5397.4 1022.97  5429.3 1026.56
#Mann=6,-1,0
  4612.2    0.05       0  4802.7    0.12       0  4990.5    0.07       0
  4994.6    0.12       0  5009.9    0.05       0  5204.7    0.12       0
Bank Sta=4990.5,4994.6
Exp/Cntr=0.3,0.1

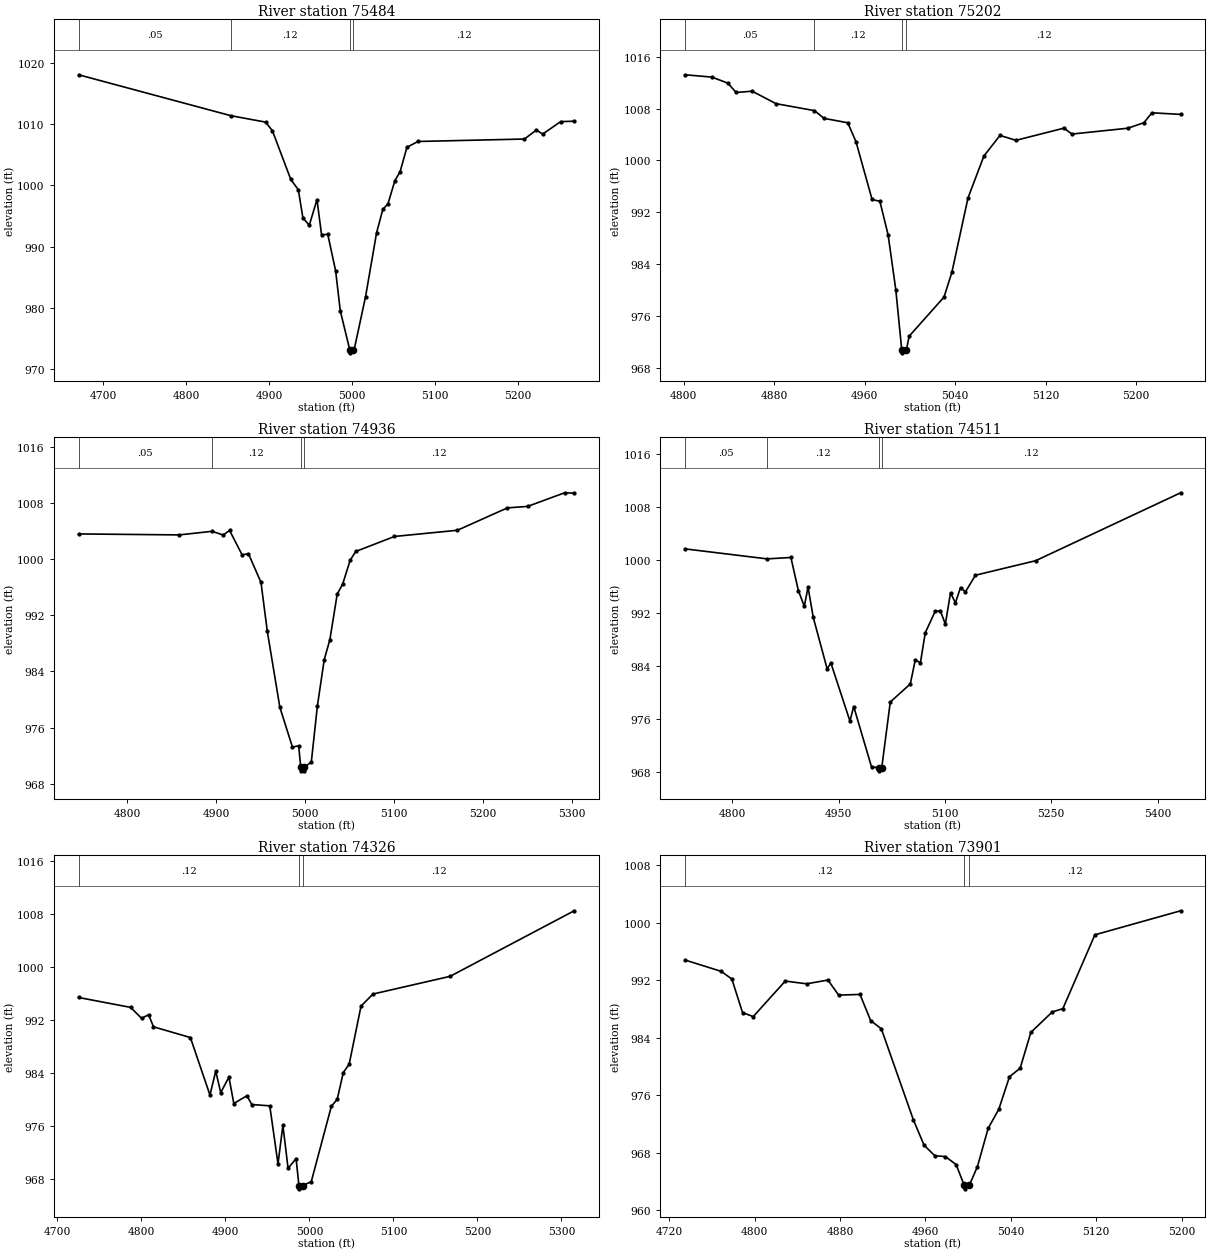
Type RM Length L Ch R = 1,75484,282,282,282
BEGIN DESCRIPTION:
Catlett Creek 94.0
END DESCRIPTION:
XS GIS Cut Line= 3
      2245082.00      7156999.89      2244937.02      7156703.66
      2244776.04      7156489.52
#Sta/Elev= 30
  4670.2 1018.05  4853.8 1011.37  4895.7 1010.32  4903.9 1008.92  4926.1 1000.96
  4935.2  999.28  4940.7  994.69  4948.4  993.48  4957.7  997.67  4963.2  991.93
  4970.7  992.00  4980.2  986.01  4985.8  979.51  4997.2  973.15  4997.5  972.65
  5001.3  973.15  5002.5  973.15  5016.3  981.83  5029.6  992.27  5037.1  996.07
  5043.3  996.99  5051.7 1000.78  5057.9 1002.21  5066.2 1006.22  5079.6 1007.16
  5207.9 1007.56  5222.4 1009.04  5229.8 1008.36  5251.6 1010.40  5267.9 1010.47
#Mann=4,-1,0
  4670.2    0.05       0  4853.8    0.12       0  4997.2    0.07       0
  5001.3    0.12       0
Bank Sta=4997.2,5001.3
Exp/Cntr=0.3,0.1

Type RM Length L Ch R = 1,75202,266,266,266
BEGIN DESCRIPTION:
Catlett Creek 93.0
END DESCRIPTION:
XS GIS Cut Line= 3
      2245309.26      7156713.26      2245173.07      7156568.44
      2245004.41      7156398.69
#Sta/Elev= 30
  4801.2 1013.21  4824.9 1012.85  4839.0 1011.92  4846.3 1010.48  4860.5 1010.68
  4881.5 1008.76  4915.6 1007.68  4924.0 1006.49  4945.0 1005.81  4952.3 1002.88
  4966.5  993.98  4973.4  993.70  4980.7  988.51  4987.5  980.03  4992.7  970.83
  4993.1  970.33  4996.9  970.83  4999.3  972.90  5030.1  978.93  5037.1  982.77
  5051.3  994.22  5065.4 1000.69  5079.6 1003.86  5093.7 1003.10  5136.1 1004.98
  5143.2 1004.07  5192.7 1004.97  5206.9 1005.83  5213.9 1007.35  5239.3 1007.10
#Mann=4,-1,0
  4801.2    0.05       0  4915.6    0.12       0  4992.7    0.07       0
  4996.9    0.12       0
Bank Sta=4992.7,4996.9
Exp/Cntr=0.3,0.1

Type RM Length L Ch R = 1,74936,425,425,425
BEGIN DESCRIPTION:
Catlett Creek 92.0
END DESCRIPTION:
XS GIS Cut Line= 3
      2245557.19      7156591.74      2245377.85      7156410.89
      2245194.71      7156170.25
#Sta/Elev= 30
  4745.3 1003.57  4858.4 1003.43  4895.2 1003.94  4907.9 1003.42  4915.0 1004.07
  4929.1 1000.59  4936.2 1000.76  4950.3  996.67  4957.4  989.71  4971.5  978.89
  4985.7  973.20  4992.7  973.40  4995.0  970.33  4995.4  969.83  4998.9  969.83
  4999.2  970.33  5006.9  971.10  5013.7  979.05  5021.4  985.67  5027.7  988.48
  5036.0  995.00  5042.2  996.45  5050.5  999.80  5056.8 1001.07  5100.4 1003.21
  5171.1 1004.09  5227.3 1007.28  5250.1 1007.49  5291.7 1009.43  5302.4 1009.37
#Mann=4,-1,0
  4745.3    0.05       0  4895.2    0.12       0  4995.0    0.07       0
  4999.2    0.12       0
Bank Sta=4995,4999.2
Exp/Cntr=0.3,0.1

Type RM Length L Ch R = 1,74511,185,185,185
BEGIN DESCRIPTION:
Catlett Creek 91.5
END DESCRIPTION:
XS GIS Cut Line= 3
      2245641.92      7156472.27      2245722.96      7156218.18
      2245423.93      7155905.71
#Sta/Elev= 30
  4733.3 1001.66  4849.0 1000.15  4882.6 1000.36  4893.1  995.36  4901.5  992.99
  4906.8  995.87  4914.1  991.32  4933.7  983.53  4939.0  984.41  4965.9  975.63
  4971.2  977.83  4996.4  968.68  5006.5  968.61  5006.9  968.11  5010.8  968.61
  5022.8  978.51  5051.1  981.25  5058.1  984.90  5065.3  984.43  5072.2  988.99
  5086.4  992.28  5093.6  992.26  5100.5  990.28  5107.8  995.02  5114.7  993.50
  5121.9  995.81  5128.8  995.16  5143.0  997.68  5227.9  999.87  5432.5 1010.14
#Mann=4,-1,0
  4733.3    0.05       0  4849.0    0.12       0  5006.5    0.07       0
  5010.8    0.12       0
Bank Sta=5006.5,5010.8
Exp/Cntr=0.3,0.1

Type RM Length L Ch R = 1,74326,425,425,425
BEGIN DESCRIPTION:
Catlett Creek 91.0
END DESCRIPTION:
XS GIS Cut Line= 3
      2246063.40      7156238.85      2245827.12      7156098.75
      2245606.02      7155874.24
#Sta/Elev= 30
  4725.3  995.41  4787.2  993.92  4800.2  992.27  4808.6  992.81  4814.4  990.99
  4858.3  989.37  4881.6  980.70  4888.5  984.31  4894.4  981.06  4904.2  983.40
  4910.0  979.42  4925.6  980.59  4931.4  979.27  4952.8  979.07  4962.6  970.30
  4968.4  976.13  4974.6  969.64  4984.1  971.12  4987.5  967.05  4988.0  966.55
  4992.3  967.05  5002.2  967.64  5026.1  979.00  5033.1  980.06  5040.3  984.09
  5047.3  985.35  5061.4  994.11  5075.6  995.93  5167.4  998.60  5315.1 1008.49
#Mann=3,-1,0
  4725.3    0.12       0  4987.5    0.07       0  4992.3    0.12       0
Bank Sta=4987.5,4992.3
Exp/Cntr=0.3,0.1

Type RM Length L Ch R = 1,73901,291,291,291
BEGIN DESCRIPTION:
Mapping XS 660be2f5
END DESCRIPTION:
XS GIS Cut Line= 2
      2246073.28      7156223.81      2246071.47      7155759.72
#Sta/Elev= 30
  4735.0  994.79  4768.8  993.22  4778.8  992.15  4788.8  987.49  4798.8  986.93
  4828.8  991.87  4848.8  991.49  4868.8  992.01  4878.8  989.92  4898.8  990.01
  4908.8  986.38  4918.8  985.23  4948.8  972.58  4958.8  969.06  4968.8  967.60
  4978.8  967.47  4988.8  966.37  4996.4  963.49  4997.0  962.99  5001.2  963.49
  5008.8  966.09  5018.8  971.39  5028.8  974.05  5038.8  978.57  5048.8  979.76
  5058.8  984.73  5078.8  987.57  5088.8  988.04  5118.8  998.30  5199.1 1001.64
#Mann=3,-1,0
  4735.0    0.12       0  4996.4    0.07       0  5001.2    0.12       0
Bank Sta=4996.4,5001.2
Exp/Cntr=0.3,0.1

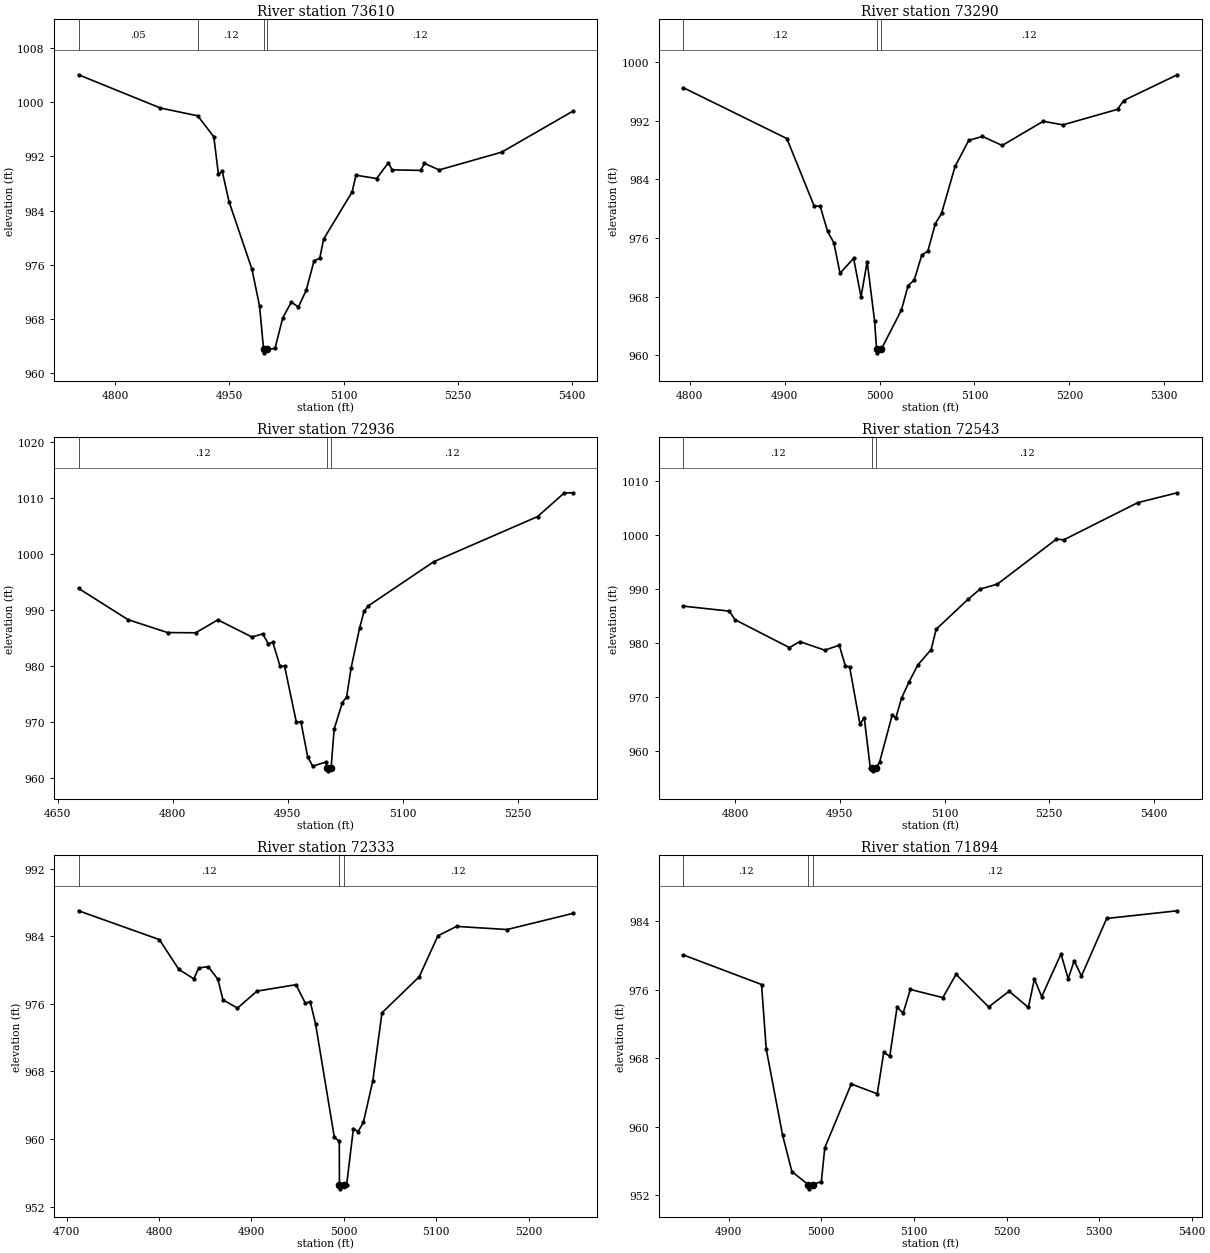
Type RM Length L Ch R = 1,73610,320,320,320
BEGIN DESCRIPTION:
Catlett Creek 90.0
END DESCRIPTION:
XS GIS Cut Line= 3
      2246305.09      7156357.36      2246290.19      7156109.50
      2246198.76      7155719.37
#Sta/Elev= 30
  4751.7 1004.05  4859.2  999.15  4908.3  997.99  4929.4  994.90  4935.4  989.42
  4940.5  989.79  4949.4  985.32  4979.5  975.37  4989.5  969.94  4994.8  963.52
  4995.4  963.02  4999.7  963.52  5009.8  963.67  5020.0  968.20  5031.3  970.49
  5040.6  969.79  5050.8  972.25  5061.1  976.59  5068.6  976.99  5073.7  979.80
  5111.1  986.76  5116.2  989.23  5143.3  988.74  5158.6  991.04  5163.8  990.02
  5201.1  989.94  5206.2  990.97  5225.5  990.01  5307.6  992.63  5400.7  998.65
#Mann=4,-1,0
  4751.7    0.05       0  4908.3    0.12       0  4994.8    0.07       0
  4999.7    0.12       0
Bank Sta=4994.8,4999.7
Exp/Cntr=0.3,0.1

Type RM Length L Ch R = 1,73290,354,354,354
BEGIN DESCRIPTION:
Catlett Creek 89.0
END DESCRIPTION:
XS GIS Cut Line= 3
      2246636.06      7156036.20      2246476.92      7155904.29
      2246233.18      7155706.97
#Sta/Elev= 30
  4793.3  996.52  4902.4  989.57  4931.0  980.40  4937.5  980.32  4945.3  976.89
  4951.9  975.34  4958.4  971.18  4972.7  973.22  4980.5  967.95  4987.0  972.77
  4994.8  964.65  4996.9  960.81  4997.6  960.31  5001.9  960.81  5023.1  966.17
  5030.1  969.50  5036.5  970.24  5044.5  973.66  5050.9  974.21  5058.8  977.96
  5065.3  979.34  5079.6  985.78  5094.0  989.32  5108.4  989.86  5129.2  988.63
  5172.4  991.93  5193.2  991.44  5250.7  993.56  5257.1  994.76  5313.6  998.28
#Mann=3,-1,0
  4793.3    0.12       0  4996.9    0.07       0  5001.9    0.12       0
Bank Sta=4996.9,5001.9
Exp/Cntr=0.3,0.1

Type RM Length L Ch R = 1,72936,393,393,393
BEGIN DESCRIPTION:
Catlett Creek 88.0
END DESCRIPTION:
XS GIS Cut Line= 3
      2246804.00      7155735.00      2246528.63      7155566.38
      2246237.84      7155428.56
#Sta/Elev= 30
  4677.1  993.86  4741.6  988.28  4793.2  985.97  4829.9  985.93  4858.9  988.24
  4903.4  985.18  4917.5  985.74  4924.7  983.99  4930.6  984.23  4940.1  979.97
  4946.0  979.97  4961.4  969.94  4967.3  970.07  4976.1  963.79  4982.7  962.13
  5000.0  962.86  5001.7  961.79  5002.3  961.29  5006.7  961.79  5010.7  968.75
  5021.4  973.47  5026.9  974.46  5032.8  979.63  5043.9  986.79  5049.7  989.74
  5055.2  990.73  5140.6  998.61  5276.2 1006.67  5310.9 1010.88  5321.8 1010.92
#Mann=3,-1,0
  4677.1    0.12       0  5001.7    0.07       0  5006.7    0.12       0
Bank Sta=5001.7,5006.7
Exp/Cntr=0.3,0.1

Type RM Length L Ch R = 1,72543,210,210,210
BEGIN DESCRIPTION:
Catlett Creek 87.5
END DESCRIPTION:
XS GIS Cut Line= 3
      2247039.65      7155531.60      2246815.61      7155373.68
      2246404.96      7155235.42
#Sta/Elev= 30
  4725.9  986.78  4791.7  985.86  4800.1  984.26  4877.9  979.10  4892.7  980.21
  4928.4  978.63  4949.3  979.53  4958.0  975.70  4964.1  975.53  4978.9  964.90
  4985.0  966.13  4993.7  956.80  4996.4  956.77  4997.0  956.27  5001.4  956.77
  5007.0  957.86  5025.0  966.58  5030.3  966.08  5038.6  969.79  5049.2  972.75
  5061.8  975.89  5080.8  978.73  5088.0  982.49  5133.6  988.04  5151.0  989.94
  5175.8  990.86  5260.2  999.19  5270.8  999.06  5376.7 1005.95  5433.3 1007.78
#Mann=3,-1,0
  4725.9    0.12       0  4996.4    0.07       0  5001.4    0.12       0
Bank Sta=4996.4,5001.4
Exp/Cntr=0.3,0.1

Type RM Length L Ch R = 1,72333,439,439,439
BEGIN DESCRIPTION:
Catlett Creek 87.0
END DESCRIPTION:
XS GIS Cut Line= 3
      2247044.04      7155522.82      2246952.19      7155250.91
      2246982.90      7155005.53
#Sta/Elev= 30
  4713.0  987.02  4800.4  983.61  4821.5  980.08  4837.7  978.96  4843.0  980.26
  4853.2  980.40  4863.7  978.92  4869.2  976.48  4884.9  975.50  4906.0  977.51
  4948.2  978.27  4958.3  976.08  4963.6  976.26  4969.3  973.66  4989.7  960.18
  4995.0  959.76  4995.2  954.60  4995.9  954.10  5000.4  954.60  5003.0  954.60
  5010.3  961.24  5015.3  960.86  5021.1  961.98  5031.2  966.84  5041.2  974.94
  5081.5  979.21  5101.7  984.06  5121.9  985.17  5176.5  984.80  5247.3  986.70
#Mann=3,-1,0
  4713.0    0.12       0  4995.2    0.07       0  5000.4    0.12       0
Bank Sta=4995.2,5000.4
Exp/Cntr=0.3,0.1

Type RM Length L Ch R = 1,71894,388,388,388
BEGIN DESCRIPTION:
Catlett Creek 86.0
END DESCRIPTION:
XS GIS Cut Line= 3
      2247346.10      7155356.17      2247325.39      7155208.52
      2247030.10      7154962.41
#Sta/Elev= 30
  4850.9  980.09  4935.4  976.63  4940.5  969.08  4958.1  959.04  4968.2  954.75
  4985.8  953.24  4986.5  952.74  4991.0  953.24  5000.0  953.59  5003.7  957.53
  5032.3  965.00  5060.4  963.85  5067.4  968.70  5073.9  968.24  5081.8  973.99
  5088.3  973.27  5096.1  976.05  5131.2  975.10  5145.5  977.82  5180.7  974.01
  5202.8  975.84  5223.6  973.95  5230.1  977.27  5238.0  975.21  5258.8  980.20
  5266.6  977.30  5273.1  979.40  5280.9  977.62  5308.2  984.35  5384.4  985.25
#Mann=3,-1,0
  4850.9    0.12       0  4985.8    0.07       0  4991.0    0.12       0
Bank Sta=4985.8,4991
Exp/Cntr=0.3,0.1

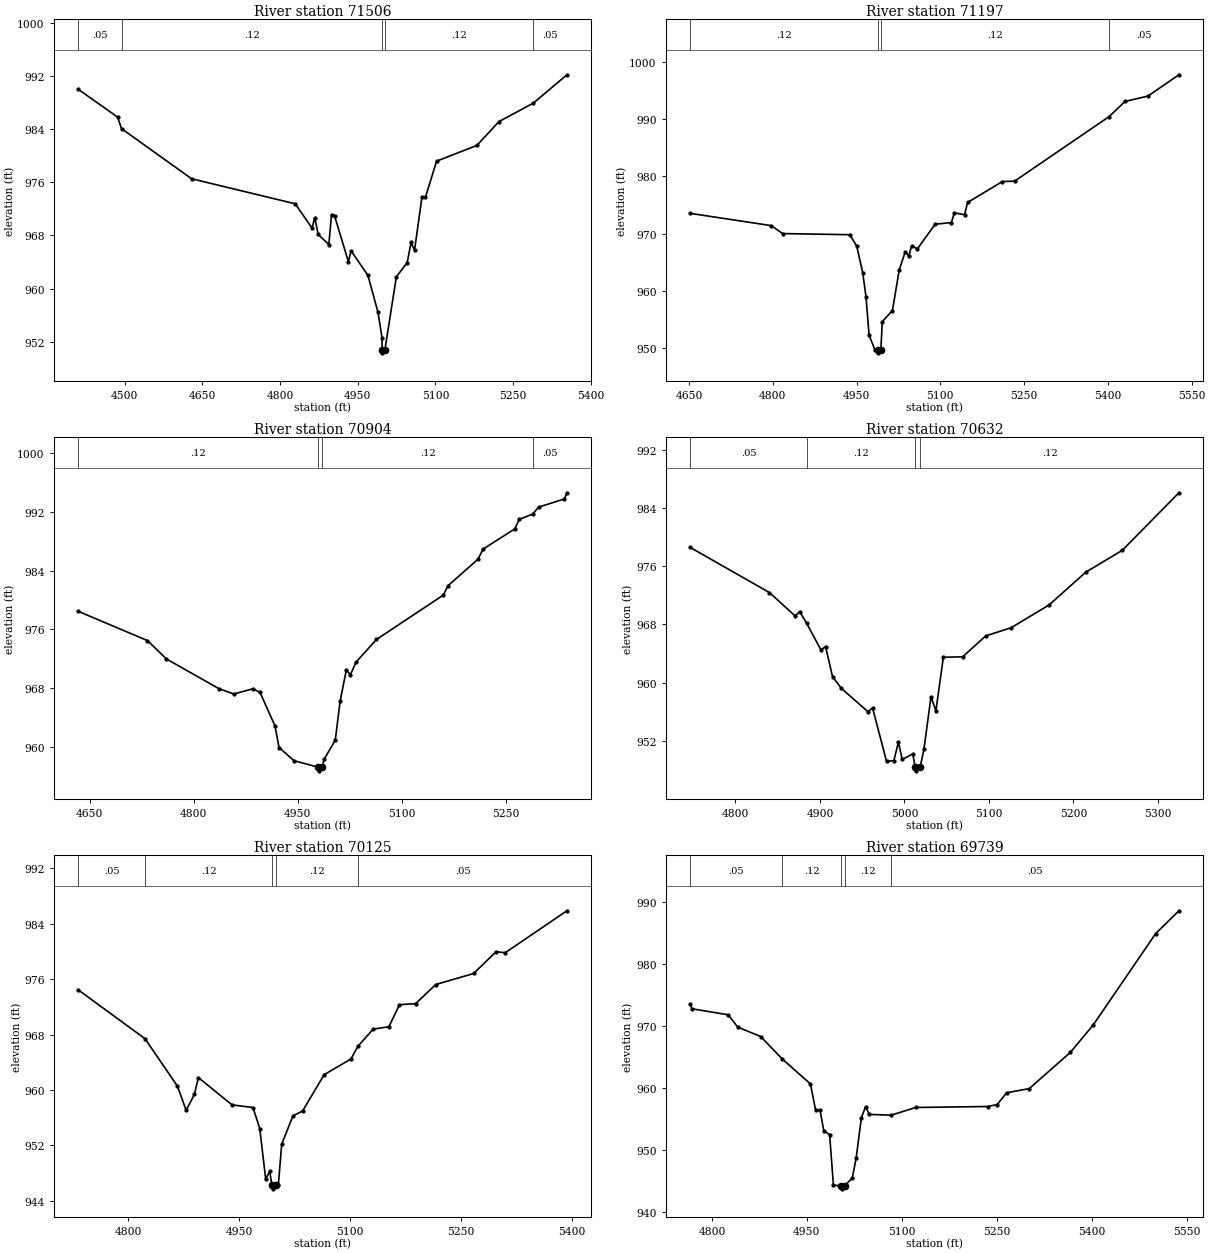
Type RM Length L Ch R = 1,71506,309,309,309
BEGIN DESCRIPTION:
Catlett Creek 85.0
END DESCRIPTION:
XS GIS Cut Line= 3
      2247679.69      7155472.36      2247503.88      7154909.48
      2247267.35      7154645.96
#Sta/Elev= 30
  4410.3  990.00  4486.1  985.82  4493.8  984.08  4629.1  976.53  4829.2  972.76
  4861.7  969.11  4867.0  970.66  4873.7  968.14  4894.2  966.62  4899.4  971.14
  4905.2  970.95  4931.9  964.06  4937.2  965.67  4969.7  961.98  4989.0  956.45
  4996.9  952.62  4997.0  950.81  4997.8  950.31  5002.6  950.81  5024.6  961.76
  5045.5  963.89  5053.0  966.94  5059.7  965.75  5073.9  973.71  5080.7  973.73
  5102.3  979.18  5180.1  981.55  5222.7  985.14  5288.9  987.91  5354.1  992.19
#Mann=5,-1,0
  4410.3    0.05       0  4493.8    0.12       0  4997.0    0.07       0
  5002.6    0.12       0  5288.9    0.05       0
Bank Sta=4997,5002.6
Exp/Cntr=0.3,0.1

Type RM Length L Ch R = 1,71197,293,293,293
BEGIN DESCRIPTION:
Mapping XS 752419cf
END DESCRIPTION:
XS GIS Cut Line= 3
      2247809.14      7155255.34      2247814.34      7154992.21
      2247574.96      7154429.16
#Sta/Elev= 30
  4652.2  973.52  4797.6  971.37  4817.6  969.99  4937.9  969.79  4950.4  967.78
  4961.2  963.07  4967.0  958.89  4972.5  952.20  4983.0  949.68  4987.9  949.66
  4988.7  949.16  4993.5  949.66  4996.1  954.61  5014.3  956.55  5026.4  963.63
  5037.3  966.82  5043.4  966.06  5048.8  967.86  5059.0  967.33  5090.7  971.62
  5119.8  971.91  5125.2  973.61  5143.4  973.28  5148.8  975.42  5211.2  979.08
  5232.9  979.14  5402.2  990.41  5430.7  993.06  5472.0  994.01  5527.2  997.72
#Mann=4,-1,0
  4652.2    0.12       0  4987.9    0.07       0  4993.5    0.12       0
  5402.2    0.05       0
Bank Sta=4987.9,4993.5
Exp/Cntr=0.3,0.1

Type RM Length L Ch R = 1,70904,272,272,272
BEGIN DESCRIPTION:
Mapping XS 94553f19
END DESCRIPTION:
XS GIS Cut Line= 2
      2248133.92      7155029.61      2247790.68      7154414.38
#Sta/Elev= 30
  4633.8  978.45  4733.5  974.48  4760.9  971.98  4836.3  967.96  4858.0  967.22
  4885.5  967.93  4895.7  967.45  4917.4  962.88  4923.2  959.95  4944.9  958.15
  4979.7  957.28  4980.6  956.78  4985.5  957.28  4988.3  958.37  5004.3  960.95
  5011.2  966.21  5020.3  970.53  5026.0  969.81  5034.1  971.54  5063.7  974.63
  5160.1  980.66  5166.6  981.92  5210.0  985.53  5217.4  986.91  5263.2  989.66
  5269.4  990.95  5288.8  991.66  5297.5  992.61  5334.5  993.72  5338.3  994.56
#Mann=4,-1,0
  4633.8    0.12       0  4979.7    0.07       0  4985.5    0.12       0
  5288.8    0.05       0
Bank Sta=4979.7,4985.5
Exp/Cntr=0.3,0.1

Type RM Length L Ch R = 1,70632,507,507,507
BEGIN DESCRIPTION:
Catlett Creek 83.0
END DESCRIPTION:
XS GIS Cut Line= 3
      2248297.93      7154898.26      2248210.91      7154660.05
      2248050.52      7154377.39
#Sta/Elev= 30
  4746.4  978.57  4840.2  972.38  4870.7  969.16  4876.0  969.78  4884.3  968.15
  4901.2  964.51  4906.6  964.97  4914.9  960.84  4925.5  959.22  4957.0  956.02
  4962.3  956.56  4978.8  949.23  4987.5  949.31  4992.9  951.87  4997.4  949.50
  5009.9  950.23  5012.8  948.42  5013.7  947.92  5018.6  948.42  5023.1  950.87
  5031.5  958.09  5037.3  956.15  5046.1  963.50  5069.0  963.57  5096.4  966.44
  5126.5  967.56  5171.4  970.69  5214.7  975.17  5258.0  978.18  5325.0  986.07
#Mann=4,-1,0
  4746.4    0.05       0  4884.3    0.12       0  5012.8    0.07       0
  5018.6    0.12       0
Bank Sta=5012.8,5018.6
Exp/Cntr=0.3,0.1

Type RM Length L Ch R = 1,70125,386,386,386
BEGIN DESCRIPTION:
Catlett Creek 82.0
END DESCRIPTION:
XS GIS Cut Line= 3
      2248673.52      7154701.90      2248559.02      7154460.04
      2248344.77      7154129.97
#Sta/Elev= 30
  4732.4  974.46  4822.7  967.41  4866.6  960.55  4878.3  957.07  4889.4  959.36
  4894.9  961.80  4940.4  957.86  4968.7  957.48  4977.9  954.45  4985.9  947.16
  4991.4  948.27  4994.3  946.24  4995.3  945.74  5000.2  946.24  5003.0  946.24
  5007.6  952.19  5022.8  956.28  5035.8  956.97  5065.0  962.22  5101.2  964.48
  5110.7  966.31  5131.2  968.79  5152.6  969.14  5166.9  972.32  5188.9  972.48
  5215.9  975.23  5267.3  976.83  5297.6  979.97  5310.0  979.83  5393.5  985.88
#Mann=5,-1,0
  4732.4    0.05       0  4822.7    0.12       0  4994.3    0.07       0
  5000.2    0.12       0  5110.7    0.05       0
Bank Sta=4994.3,5000.2
Exp/Cntr=0.3,0.1

Type RM Length L Ch R = 1,69739,300,300,300
BEGIN DESCRIPTION:
Catlett Creek 81.0
END DESCRIPTION:
XS GIS Cut Line= 3
      2249016.04      7154596.20      2248888.81      7154399.57
      2248578.99      7153959.98
#Sta/Elev= 30
  4765.8  973.56  4768.4  972.78  4825.8  971.81  4840.9  969.82  4877.2  968.31
  4911.2  964.69  4955.7  960.68  4963.8  956.50  4970.9  956.42  4976.8  953.14
  4986.0  952.53  4992.0  944.36  5004.0  944.28  5005.0  943.78  5009.9  944.28
  5021.8  945.53  5027.9  948.72  5036.2  955.23  5042.7  956.99  5048.8  955.77
  5083.3  955.64  5121.8  956.88  5236.0  957.04  5250.8  957.36  5265.6  959.25
  5301.3  959.92  5366.5  965.77  5402.3  970.15  5501.1  984.89  5537.8  988.56
#Mann=5,-1,0
  4765.8    0.05       0  4911.2    0.12       0  5004.0    0.07       0
  5009.9    0.12       0  5083.3    0.05       0
Bank Sta=5004,5009.9
Exp/Cntr=0.3,0.1