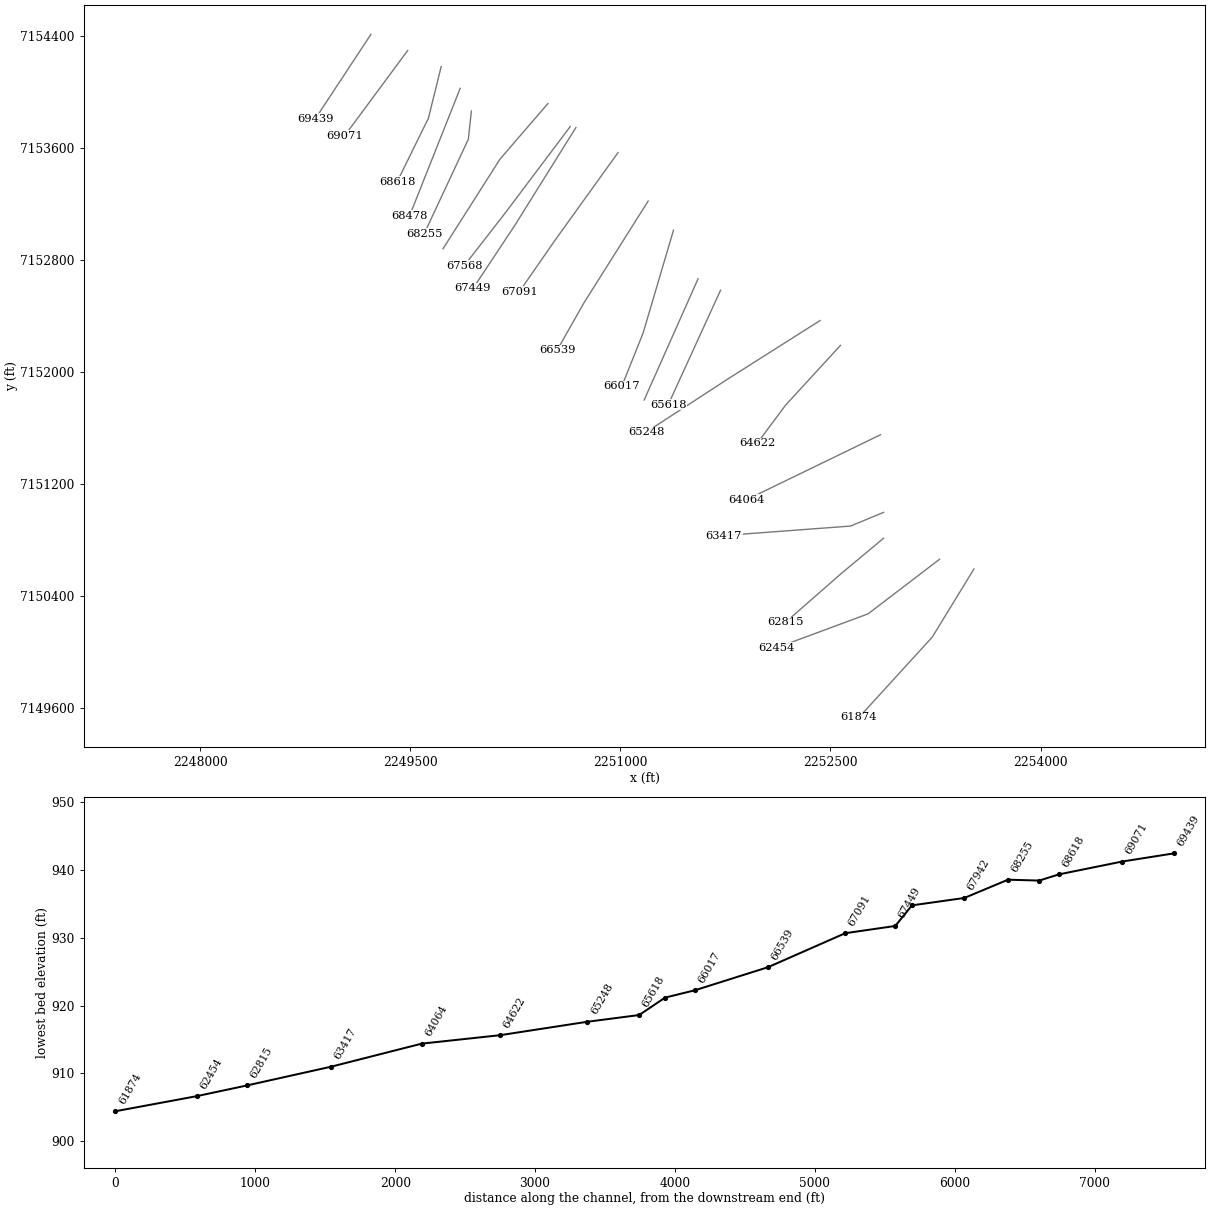
HEC-RAS study Catlett Creek.prj: Catlett Creek Base Level Engineering

--- Catlett Creek.g01 (geometry) --- (continued)

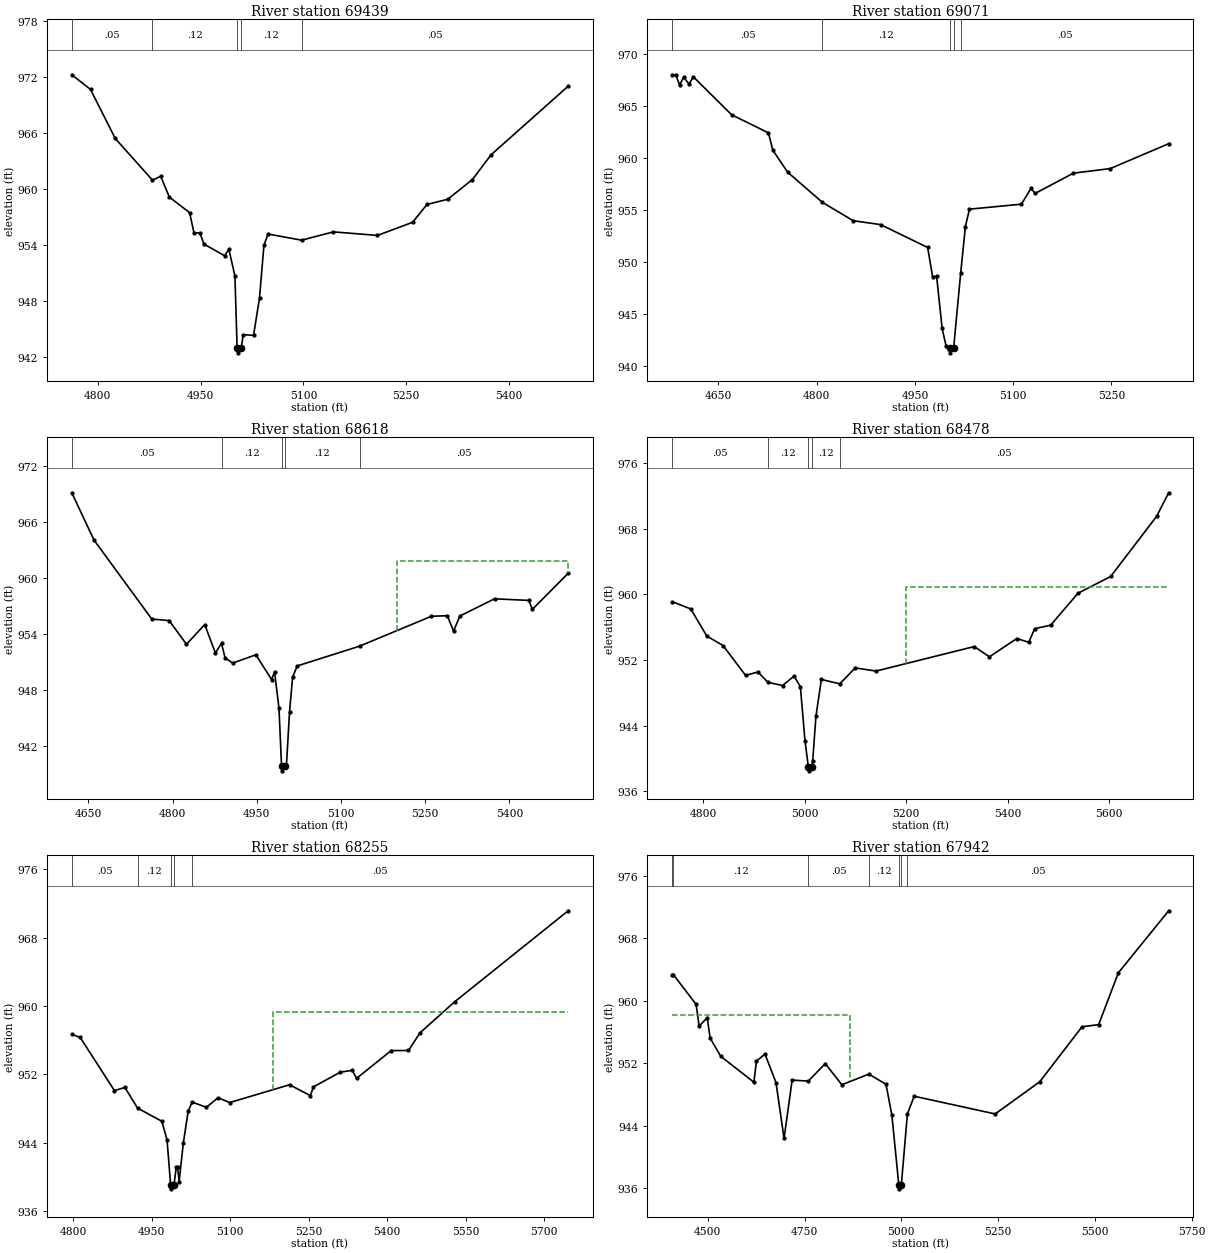
Type RM Length L Ch R = 1,69439,368,368,368
BEGIN DESCRIPTION:
Mapping XS 650d7f36
END DESCRIPTION:
XS GIS Cut Line= 2
      2249218.32      7154408.82      2248820.11      7153803.92
#Sta/Elev= 30
  4762.1  972.20  4789.4  970.63  4825.5  965.39  4879.8  960.94  4891.8  961.35
  4904.4  959.13  4934.0  957.46  4940.3  955.32  4949.0  955.30  4955.0  954.10
  4985.2  952.85  4991.2  953.55  5000.1  950.71  5003.3  942.98  5004.2  942.48
  5009.2  942.98  5012.2  944.42  5027.3  944.35  5036.0  948.37  5042.4  953.96
  5048.4  955.18  5097.4  954.52  5143.8  955.41  5208.0  955.03  5259.3  956.43
  5280.3  958.34  5310.5  958.89  5346.6  961.00  5373.7  963.64  5486.3  970.98
#Mann=5,-1,0
  4762.1    0.05       0  4879.8    0.12       0  5003.3    0.07       0
  5009.2    0.12       0  5097.4    0.05       0
Bank Sta=5003.3,5009.2
Exp/Cntr=0.3,0.1

Type RM Length L Ch R = 1,69071,453,453,453
BEGIN DESCRIPTION:
Mapping XS 6643a5a3
END DESCRIPTION:
XS GIS Cut Line= 2
      2249481.05      7154293.34      2249030.41      7153684.22
#Sta/Elev= 30
  4579.7  967.99  4584.9  967.99  4590.8  967.02  4597.0  967.74  4605.4  967.10
  4611.7  967.80  4670.2  964.15  4726.5  962.41  4733.1  960.75  4755.7  958.64
  4808.9  955.73  4855.9  953.97  4897.6  953.60  4969.5  951.40  4977.0  948.60
  4983.2  948.62  4991.6  943.62  4997.8  941.89  5003.2  941.78  5004.2  941.28
  5009.2  941.78  5019.9  948.93  5027.1  953.41  5033.3  955.08  5112.6  955.56
  5127.3  957.08  5133.5  956.59  5192.0  958.54  5248.3  958.98  5337.4  961.37
#Mann=5,-1,0
  4579.7    0.05       0  4808.9    0.12       0  5003.2    0.07       0
  5009.2    0.12       0  5019.9    0.05       0
Bank Sta=5003.2,5009.2
Exp/Cntr=0.3,0.1

Type RM Length L Ch R = 1,68618,140,140,140
BEGIN DESCRIPTION:
Catlett Creek 78.0
END DESCRIPTION:
XS GIS Cut Line= 3
      2249719.88      7154178.35      2249628.88      7153809.72
      2249406.26      7153356.88
#Sta/Elev= 30
  4620.3  969.17  4659.8  964.11  4762.8  955.64  4793.7  955.48  4824.6  952.94
  4857.1  955.05  4876.1  952.01  4887.0  953.04  4893.4  951.47  4907.0  950.93
  4948.2  951.81  4976.3  949.16  4981.5  949.99  4989.4  946.09  4994.0  939.88
  4995.1  939.38  5000.5  939.88  5002.6  939.88  5008.2  945.69  5013.7  949.43
  5022.0  950.62  5133.0  952.74  5261.0  955.94  5289.4  956.00  5300.4  954.34
  5311.7  955.97  5373.4  957.81  5434.3  957.64  5440.8  956.68  5504.6  960.54
#Mann=5,-1,0
  4620.3    0.05       0  4887.0    0.12       0  4994.0    0.07       0
  5000.5    0.12       0  5133.0    0.05       0
#XS Ineff=2,0
       0                 5199.90    0.00  961.85
Permanent Ineff=
       F       F
Bank Sta=4994,5000.5
Exp/Cntr=0.3,0.1

Type RM Length L Ch R = 1,68478,223,223,223
BEGIN DESCRIPTION:
Mapping XS a9194583
END DESCRIPTION:
XS GIS Cut Line= 2
      2249855.71      7154023.08      2249494.79      7153113.79
#Sta/Elev= 30
  4738.9  959.10  4775.3  958.22  4806.8  954.92  4839.0  953.75  4883.3  950.11
  4907.6  950.53  4927.6  949.26  4956.2  948.88  4978.9  950.03  4991.3  948.73
  5000.4  942.15  5007.0  938.97  5008.0  938.47  5013.5  938.97  5015.6  939.70
  5022.0  945.13  5032.7  949.62  5069.1  949.08  5099.3  951.03  5140.3  950.64
  5334.0  953.63  5363.9  952.38  5417.9  954.61  5441.5  954.15  5453.0  955.81
  5484.6  956.24  5538.4  960.13  5602.9  962.18  5693.3  969.50  5717.2  972.39
#Mann=5,-1,0
  4738.9    0.05       0  4927.6    0.12       0  5007.0    0.07       0
  5013.5    0.12       0  5069.1    0.05       0
#XS Ineff=2,0
       0                 5200.00    0.00  960.89
Permanent Ineff=
       F       F
Bank Sta=5007,5013.5
Exp/Cntr=0.3,0.1

Type RM Length L Ch R = 1,68255,313,313,313
BEGIN DESCRIPTION:
Mapping XS daae628d
END DESCRIPTION:
XS GIS Cut Line= 3
      2249935.66      7153861.06      2249914.15      7153659.96
      2249597.98      7152983.44
#Sta/Elev= 30
  4797.2  956.67  4813.1  956.33  4878.7  950.10  4898.8  950.46  4922.9  948.05
  4969.2  946.51  4979.3  944.34  4986.1  939.10  4987.1  938.60  4992.6  939.10
  4996.9  941.12  4999.4  941.12  5002.4  939.45  5010.4  943.94  5019.7  947.70
  5027.4  948.75  5054.6  948.14  5076.7  949.26  5099.3  948.70  5213.5  950.78
  5253.3  949.51  5259.2  950.53  5310.4  952.25  5333.3  952.47  5341.6  951.52
  5407.8  954.78  5440.9  954.79  5463.0  956.86  5529.2  960.49  5746.2  971.14
#Mann=5,-1,0
  4797.2    0.05       0  4922.9    0.12       0  4986.1    0.07       0
  4992.6    0.12       0  5027.4    0.05       0
#XS Ineff=2,0
       0                 5182.50    0.00  959.25
Permanent Ineff=
       F       F
Bank Sta=4986.1,4992.6
Exp/Cntr=0.3,0.1

Type RM Length L Ch R = 1,67942,374,374,374
BEGIN DESCRIPTION:
Catlett Creek 77.9
END DESCRIPTION:
XS GIS Cut Line= 3
      2250481.98      7153914.31      2250139.35      7153516.49
      2249733.01      7152877.35
#Sta/Elev= 30
  4408.2  963.34  4411.2  963.34  4469.8  959.54  4477.5  956.75  4498.4  957.84
  4506.0  955.21  4533.5  952.88  4619.0  949.57  4625.6  952.27  4647.6  953.18
  4676.1  949.52  4696.9  942.36  4717.8  949.84  4759.5  949.71  4803.4  951.95
  4846.2  949.24  4916.0  950.61  4960.3  949.30  4975.5  945.34  4993.4  936.40
  4994.5  935.90  4999.9  936.40  5015.6  945.51  5033.1  947.77  5242.3  945.50
  5357.4  949.62  5466.7  956.67  5509.7  956.95  5560.7  963.60  5690.6  971.54
#Mann=7,-1,0
  4408.2    0.05       0  4411.2    0.12       0  4759.5    0.05       0
  4916.0    0.12       0  4993.4    0.07       0  4999.9    0.12       0
  5015.6    0.05       0
#XS Ineff=2,0
    0.00 4867.60  958.12               0
Permanent Ineff=
       F       F
Bank Sta=4993.4,4999.9
Exp/Cntr=0.3,0.1

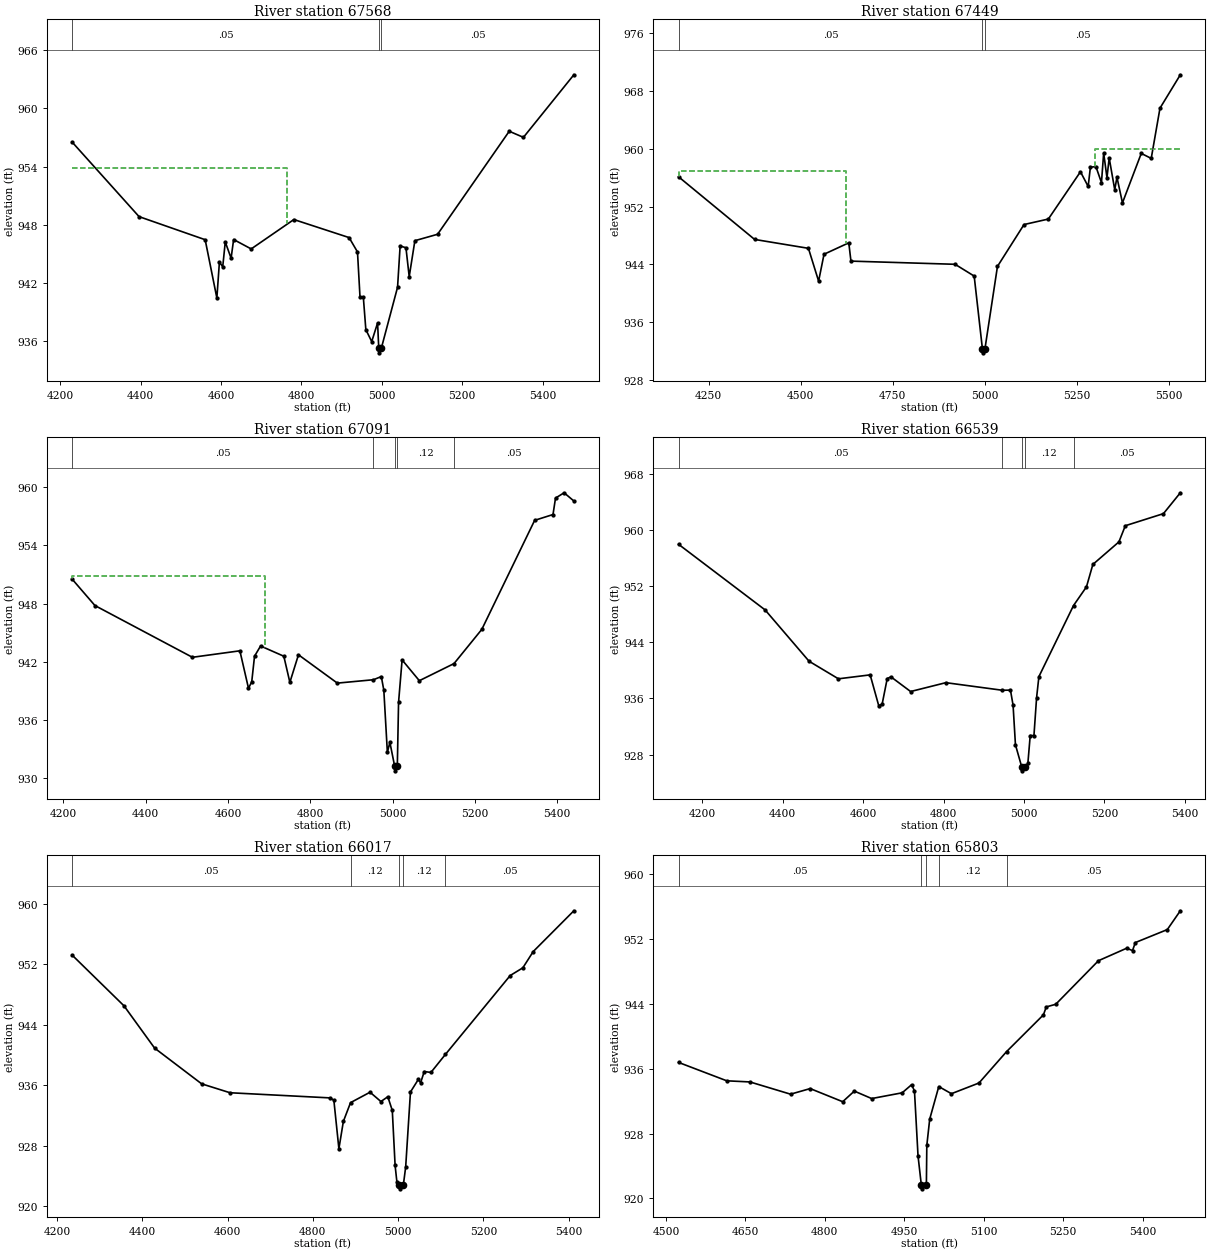
Type RM Length L Ch R = 1,67568,119,119,119
BEGIN DESCRIPTION:
Catlett Creek 77.8
END DESCRIPTION:
XS GIS Cut Line= 3
      2250642.24      7153750.83      2250178.79      7153134.92
      2249885.52      7152757.71
#Sta/Elev= 30
  4229.2  956.54  4395.9  948.85  4560.4  946.47  4589.5  940.46  4595.8  944.15
  4604.1  943.69  4610.4  946.24  4624.9  944.56  4631.2  946.49  4674.9  945.52
  4781.1  948.55  4918.5  946.69  4939.4  945.21  4945.6  940.61  4954.0  940.52
  4960.2  937.20  4974.8  935.97  4989.4  937.89  4992.3  935.31  4993.4  934.81
  4998.9  935.31  5039.1  941.57  5045.5  945.83  5060.0  945.64  5068.1  942.66
  5082.2  946.37  5138.7  947.03  5317.0  957.65  5352.3  957.02  5477.8  963.47
#Mann=3,-1,0
  4229.2    0.05       0  4992.3   0.033       0  4998.9    0.05       0
#XS Ineff=2,0
    0.00 4763.90  953.86               0
Permanent Ineff=
       F       F
Bank Sta=4992.3,4998.9
Exp/Cntr=0.3,0.1

Type RM Length L Ch R = 1,67449,358,358,358
BEGIN DESCRIPTION:
Catlett Creek 77.7
END DESCRIPTION:
XS GIS Cut Line= 3
      2250681.97      7153742.96      2250241.30      7153037.24
      2249947.04      7152593.92
#Sta/Elev= 30
  4168.0  956.13  4374.8  947.46  4521.1  946.23  4548.8  941.69  4563.5  945.41
  4630.8  946.99  4636.7  944.46  4919.8  944.02  4971.7  942.39  4994.2  932.27
  4995.2  931.77  5000.8  932.27  5035.0  943.73  5107.2  949.52  5173.3  950.28
  5260.6  956.82  5281.6  954.79  5287.6  957.45  5302.6  957.54  5317.7  955.32
  5323.7  959.41  5332.7  955.99  5338.7  958.74  5353.8  954.33  5359.8  956.06
  5374.8  952.52  5425.9  959.36  5453.0  958.67  5476.8  965.62  5532.1  970.24
#Mann=3,-1,0
  4168.0    0.05       0  4994.2   0.033       0  5000.8    0.05       0
#XS Ineff=2,0
    0.00 4624.50  956.91 5300.00    0.00  960.00
Permanent Ineff=
       F       F
Bank Sta=4994.2,5000.8
Exp/Cntr=0.3,0.1

Type RM Length L Ch R = 1,67091,552,552,552
BEGIN DESCRIPTION:
Catlett Creek 77.6
END DESCRIPTION:
XS GIS Cut Line= 3
      2250983.23      7153564.59      2250528.68      7152932.08
      2250277.52      7152569.83
#Sta/Elev= 30
  4221.1  950.53  4276.7  947.79  4513.6  942.44  4629.0  943.11  4649.9  939.24
  4657.8  939.90  4664.6  942.55  4679.3  943.61  4735.8  942.55  4750.5  939.85
  4771.4  942.70  4865.9  939.77  4953.7  940.12  4972.8  940.45  4978.9  939.03
  4987.5  932.61  4993.6  933.65  5005.1  931.20  5006.2  930.70  5011.7  931.20
  5014.7  937.78  5023.3  942.17  5065.2  940.02  5149.5  941.79  5217.1  945.33
  5345.5  956.60  5390.1  957.20  5396.2  958.90  5417.1  959.45  5440.8  958.60
#Mann=5,-1,0
  4221.1    0.05       0  4953.7    0.12       0  5005.1    0.07       0
  5011.7    0.12       0  5149.5    0.05       0
#XS Ineff=2,0
    0.00 4690.00  950.88               0
Permanent Ineff=
       F       F
Bank Sta=5005.1,5011.7
Exp/Cntr=0.3,0.1

Type RM Length L Ch R = 1,66539,522,522,522
BEGIN DESCRIPTION:
Catlett Creek 77.5
END DESCRIPTION:
XS GIS Cut Line= 3
      2251198.05      7153218.19      2250739.78      7152491.41
      2250547.96      7152153.45
#Sta/Elev= 30
  4140.8  957.93  4356.0  948.59  4465.4  941.28  4538.4  938.78  4617.3  939.34
  4638.5  934.98  4647.0  935.14  4659.7  938.81  4669.0  939.06  4717.9  936.97
  4805.6  938.23  4946.0  937.15  4966.2  937.17  4972.7  935.02  4978.6  929.39
  4994.5  926.18  4995.6  925.68  5001.2  926.18  5009.5  926.74  5015.3  930.71
  5024.6  930.70  5031.2  936.11  5036.9  939.09  5123.0  949.21  5155.2  951.87
  5171.1  955.06  5235.9  958.27  5251.8  960.57  5346.6  962.29  5388.6  965.26
#Mann=5,-1,0
  4140.8    0.05       0  4946.0    0.12       0  4994.5    0.07       0
  5001.2    0.12       0  5123.0    0.05       0
Bank Sta=4994.5,5001.2
Exp/Cntr=0.3,0.1

Type RM Length L Ch R = 1,66017,214,214,214
BEGIN DESCRIPTION:
Catlett Creek 77.0
END DESCRIPTION:
XS GIS Cut Line= 3
      2251379.00      7153010.01      2251162.40      7152276.83
      2251009.53      7151894.25
#Sta/Elev= 30
  4235.5  953.23  4357.2  946.51  4429.0  940.91  4539.3  936.18  4605.9  935.00
  4840.3  934.32  4849.3  934.01  4861.1  927.59  4871.6  931.21  4888.4  933.69
  4934.1  935.07  4959.6  933.84  4975.8  934.47  4986.3  932.66  4992.9  925.37
  4997.2  923.14  5002.6  922.78  5003.9  922.28  5012.2  922.78  5017.7  925.19
  5028.9  935.10  5047.3  936.76  5052.7  936.32  5061.2  937.81  5076.9  937.69
  5110.9  940.08  5262.8  950.52  5292.4  951.54  5316.7  953.69  5412.0  959.09
#Mann=5,-1,0
  4235.5    0.05       0  4888.4    0.12       0  5002.6    0.07       0
  5012.2    0.12       0  5110.9    0.05       0
Bank Sta=5002.6,5012.2
Exp/Cntr=0.3,0.1

Type RM Length L Ch R = 1,65803,185,185,185
BEGIN DESCRIPTION:
Mapping XS 6edc05ca
END DESCRIPTION:
XS GIS Cut Line= 2
      2251554.56      7152663.22      2251169.51      7151797.48
#Sta/Elev= 30
  4523.9  936.79  4615.0  934.52  4658.8  934.38  4735.4  932.87  4772.5  933.56
  4833.9  931.94  4855.8  933.25  4888.6  932.33  4946.2  933.04  4964.0  934.04
  4969.4  933.27  4976.1  925.27  4982.3  921.69  4983.6  921.19  4991.9  921.69
  4992.7  926.55  4998.2  929.80  5015.3  933.81  5039.2  932.93  5091.2  934.25
  5143.4  938.13  5212.9  942.66  5218.3  943.64  5236.1  943.96  5316.8  949.34
  5370.1  950.88  5381.1  950.59  5386.5  951.58  5446.8  953.18  5471.4  955.50
#Mann=5,-1,0
  4523.9    0.05       0  4982.3   0.033       0  4991.9    0.05       0
  5015.3    0.12       0  5143.4    0.05       0
Bank Sta=4982.3,4991.9
Exp/Cntr=0.3,0.1

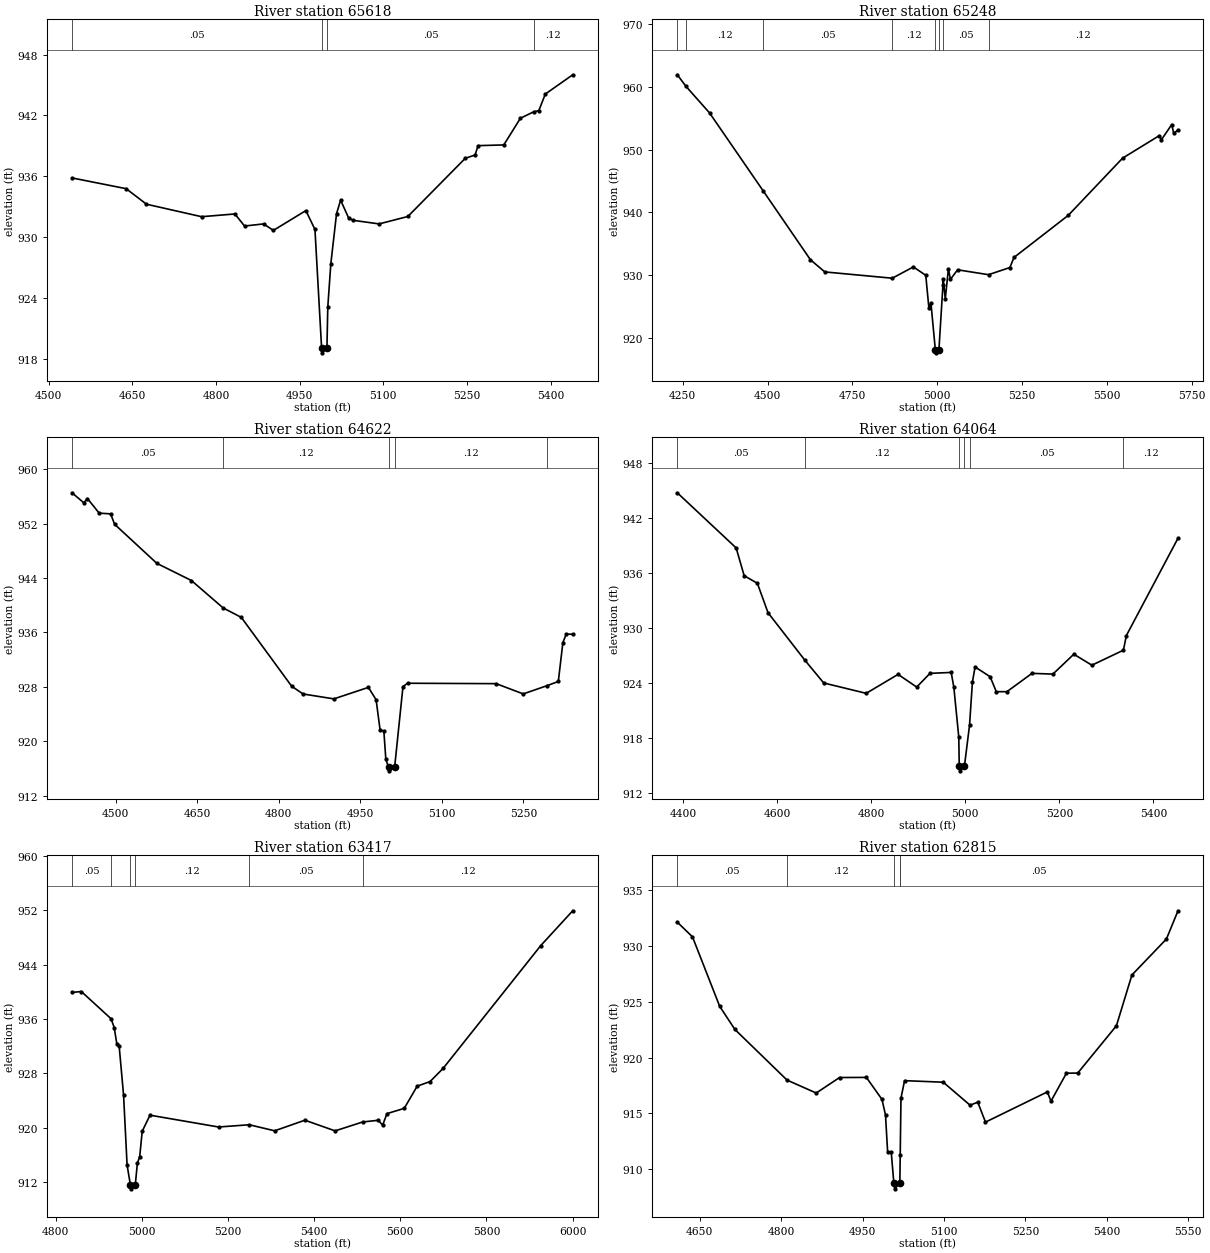
Type RM Length L Ch R = 1,65618,370,370,370
BEGIN DESCRIPTION:
Mapping XS 7361a016
END DESCRIPTION:
XS GIS Cut Line= 2
      2251715.21      7152581.45      2251341.55      7151764.67
#Sta/Elev= 30
  4541.6  935.85  4638.7  934.79  4675.2  933.26  4774.1  932.03  4833.8  932.30
  4851.1  931.11  4885.3  931.32  4902.8  930.68  4961.1  932.63  4977.4  930.77
  4989.3  919.12  4990.6  918.62  4998.9  919.12  5000.4  923.11  5005.9  927.41
  5016.1  932.32  5023.4  933.66  5038.1  931.87  5046.4  931.67  5092.5  931.32
  5144.0  932.05  5247.0  937.78  5264.6  938.11  5270.1  939.03  5316.1  939.10
  5346.0  941.73  5370.1  942.37  5379.0  942.48  5390.6  944.11  5439.8  946.01
#Mann=4,-1,0
  4541.6    0.05       0  4989.3   0.033       0  4998.9    0.05       0
  5370.1    0.12       0
Bank Sta=4989.3,4998.9
Exp/Cntr=0.3,0.1

Type RM Length L Ch R = 1,65248,626,626,626
BEGIN DESCRIPTION:
Catlett Creek 75.0
END DESCRIPTION:
XS GIS Cut Line= 3
      2252425.88      7152364.78      2251778.86      7151954.94
      2251183.81      7151567.98
#Sta/Elev= 30
  4234.1  961.93  4259.8  960.08  4329.1  955.86  4487.2  943.44  4626.5  932.46
  4668.9  930.52  4867.7  929.52  4929.9  931.32  4966.4  929.98  4975.7  924.74
  4981.6  925.59  4994.6  918.13  4996.1  917.63  5005.2  918.13  5017.1  928.49
  5018.0  929.36  5023.9  926.23  5033.1  931.00  5039.1  929.33  5060.2  930.86
  5151.4  930.08  5214.3  931.22  5226.5  932.83  5386.3  939.53  5546.4  948.64
  5655.1  952.25  5661.1  951.59  5691.3  954.00  5697.3  952.58  5709.8  953.16
#Mann=8,-1,0
  4234.1    0.05       0  4259.8    0.12       0  4487.2    0.05       0
  4867.7    0.12       0  4994.6    0.07       0  5005.2    0.12       0
  5017.1    0.05       0  5151.4    0.12       0
Bank Sta=4994.6,5005.2
Exp/Cntr=0.3,0.1

Type RM Length L Ch R = 1,64622,558,558,558
BEGIN DESCRIPTION:
Catlett Creek 74.0
END DESCRIPTION:
XS GIS Cut Line= 3
      2252571.65      7152187.65      2252179.00      7151760.00
      2251975.77      7151487.01
#Sta/Elev= 30
  4419.7  956.56  4441.3  955.09  4448.1  955.71  4469.7  953.56  4490.7  953.46
  4498.0  951.93  4575.8  946.17  4639.3  943.65  4697.7  939.61  4731.1  938.22
  4823.6  928.10  4844.6  926.95  4901.3  926.23  4964.8  927.92  4979.0  926.10
  4986.4  921.60  4993.2  921.52  4996.9  917.31  5002.1  916.14  5003.6  915.64
  5013.0  916.14  5028.4  928.04  5036.8  928.53  5199.7  928.47  5249.6  926.96
  5293.2  928.17  5314.1  928.79  5322.5  934.52  5328.7  935.75  5340.6  935.75
#Mann=5,-1,0
  4419.7    0.05       0  4697.7    0.12       0  5002.1    0.07       0
  5013.0    0.12       0  5293.2    0.05       0
Bank Sta=5002.1,5013
Exp/Cntr=0.3,0.1

Type RM Length L Ch R = 1,64064,647,647,647
BEGIN DESCRIPTION:
Mapping XS 93f405ac
END DESCRIPTION:
XS GIS Cut Line= 2
      2252857.27      7151549.24      2251899.82      7151084.91
#Sta/Elev= 30
  4388.0  944.75  4513.1  938.73  4530.1  935.70  4558.2  934.87  4580.8  931.66
  4658.9  926.49  4699.2  923.99  4789.5  922.86  4857.2  924.93  4896.8  923.54
  4925.0  925.04  4970.1  925.14  4975.7  923.53  4986.2  918.09  4987.2  914.90
  4988.7  914.40  4998.2  914.90  5009.1  919.39  5015.2  924.08  5020.8  925.74
  5052.9  924.67  5065.9  923.04  5088.5  923.04  5141.8  925.04  5186.3  924.96
  5230.7  927.13  5269.1  925.93  5336.1  927.57  5342.4  929.17  5452.1  939.79
#Mann=6,-1,0
  4388.0    0.05       0  4658.9    0.12       0  4987.2    0.07       0
  4998.2    0.12       0  5009.1    0.05       0  5336.1    0.12       0
Bank Sta=4987.2,4998.2
Exp/Cntr=0.3,0.1

Type RM Length L Ch R = 1,63417,602,602,602
BEGIN DESCRIPTION:
Mapping XS 2efc0744
END DESCRIPTION:
XS GIS Cut Line= 3
      2252879.55      7150995.07      2252643.28      7150897.14
      2251738.77      7150829.57
#Sta/Elev= 30
  4837.5  939.90  4859.1  940.04  4928.2  936.03  4935.5  934.73  4941.5  932.35
  4947.0  932.00  4957.2  924.81  4965.4  914.50  4973.3  911.50  4974.8  911.00
  4984.3  911.50  4989.3  914.78  4994.7  915.73  5000.5  919.47  5018.6  921.84
  5177.8  920.10  5249.2  920.43  5308.1  919.54  5378.3  921.10  5448.5  919.53
  5512.5  920.84  5548.8  921.09  5558.8  920.36  5568.9  922.07  5609.0  922.84
  5639.1  926.11  5669.1  926.79  5699.2  928.72  5926.1  946.80  6000.3  951.92
#Mann=6,-1,0
  4837.5    0.05       0  4928.2    0.12       0  4973.3    0.07       0
  4984.3    0.12       0  5249.2    0.05       0  5512.5    0.12       0
Bank Sta=4973.3,4984.3
Exp/Cntr=0.3,0.1

Type RM Length L Ch R = 1,62815,361,361,361
BEGIN DESCRIPTION:
Catlett Creek 71.0
END DESCRIPTION:
XS GIS Cut Line= 3
      2252879.02      7150810.01      2252579.00      7150560.00
      2252179.03      7150210.03
#Sta/Elev= 30
  4608.9  932.14  4636.9  930.82  4687.0  924.59  4715.0  922.52  4811.0  917.98
  4864.7  916.82  4907.7  918.21  4957.1  918.22  4985.8  916.25  4992.3  914.85
  4996.2  911.54  5002.8  911.54  5007.7  908.73  5009.2  908.23  5018.7  908.73
  5019.4  911.27  5020.8  916.36  5027.4  917.93  5098.6  917.79  5148.0  915.73
  5162.2  916.00  5176.4  914.21  5290.3  916.92  5297.0  916.09  5325.5  918.60
  5346.3  918.61  5417.5  922.85  5446.0  927.40  5509.6  930.63  5530.9  933.16
#Mann=5,-1,0
  4608.9    0.05       0  4811.0    0.12       0  5007.7    0.07       0
  5018.7    0.12       0  5019.4    0.05       0
Bank Sta=5007.7,5018.7
Exp/Cntr=0.3,0.1

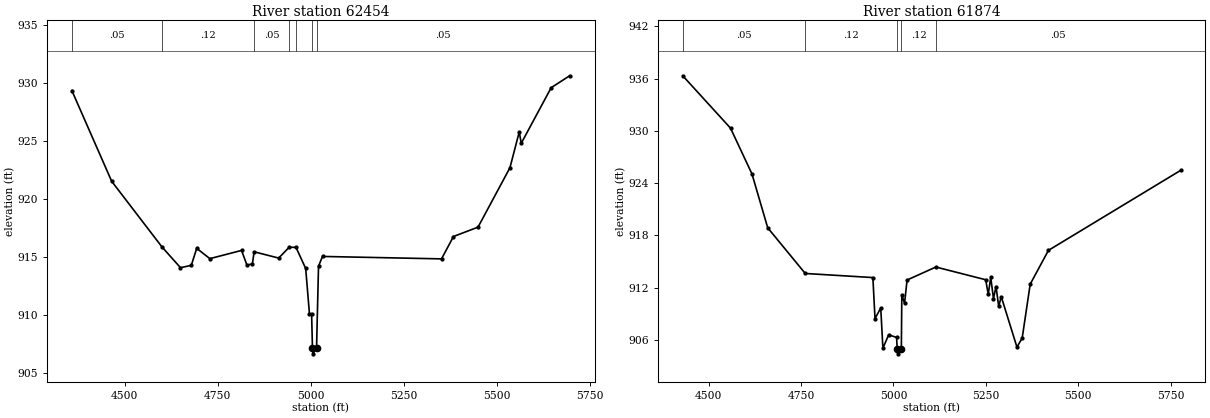
Type RM Length L Ch R = 1,62454,580,580,580
BEGIN DESCRIPTION:
Catlett Creek 70.0
END DESCRIPTION:
XS GIS Cut Line= 3
      2253279.02      7150660.02      2252768.90      7150270.39
      2252116.06      7150028.24
#Sta/Elev= 30
  4358.1  929.37  4465.1  921.54  4600.1  915.88  4650.1  914.08  4679.2  914.28
  4693.7  915.75  4729.1  914.86  4814.3  915.57  4828.8  914.30  4843.4  914.41
  4848.1  915.45  4914.1  914.91  4942.5  915.85  4960.7  915.83  4986.7  914.01
  4996.8  910.11  5002.6  910.11  5004.9  907.14  5006.4  906.64  5015.9  907.14
  5021.2  914.21  5031.9  915.05  5351.9  914.84  5383.9  916.77  5450.0  917.58
  5535.8  922.71  5560.8  925.80  5566.2  924.82  5646.6  929.62  5696.3  930.65
#Mann=7,-1,0
  4358.1    0.05       0  4600.1    0.12       0  4848.1    0.05       0
  4942.5    0.12       0  4960.7    0.05       0  5004.9   0.033       0
  5015.9    0.05       0
Bank Sta=5004.9,5015.9
Exp/Cntr=0.3,0.1

Type RM Length L Ch R = 1,61874,929,929,929
BEGIN DESCRIPTION:
Catlett Creek 69.0
END DESCRIPTION:
XS GIS Cut Line= 3
      2253524.39      7150590.29      2253227.03      7150104.35
      2252703.38      7149530.86
#Sta/Elev= 30
  4430.3  936.32  4559.5  930.31  4617.5  925.06  4660.1  918.88  4761.6  913.64
  4944.5  913.17  4950.3  908.46  4965.8  909.69  4971.6  905.06  4987.1  906.59
  5008.6  906.31  5010.4  904.92  5012.0  904.42  5021.5  904.92  5022.8  911.18
  5030.2  910.22  5037.0  912.89  5114.9  914.38  5249.6  912.92  5256.5  911.26
  5263.3  913.18  5270.7  910.75  5277.5  912.14  5284.9  909.86  5291.7  910.98
  5334.2  905.19  5348.4  906.24  5370.0  912.41  5419.3  916.29  5776.6  925.46
#Mann=5,-1,0
  4430.3    0.05       0  4761.6    0.12       0  5010.4    0.07       0
  5021.5    0.12       0  5114.9    0.05       0
Bank Sta=5010.4,5021.5
Exp/Cntr=0.3,0.1