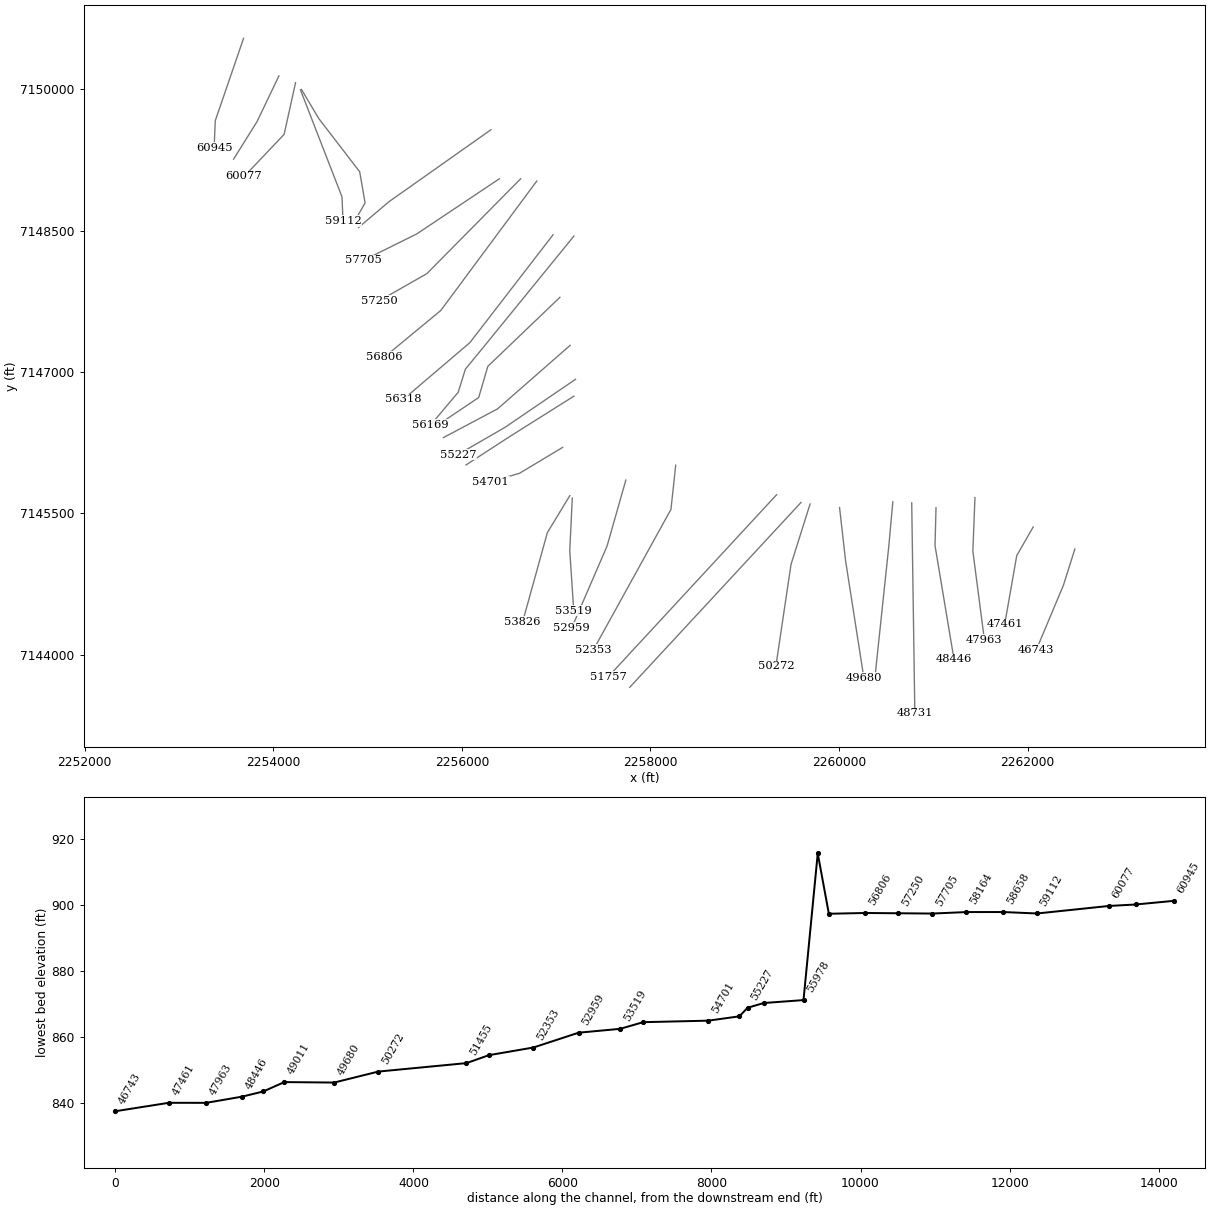
HEC-RAS study Catlett Creek.prj: Catlett Creek Base Level Engineering

--- Catlett Creek.g01 (geometry) --- (continued)

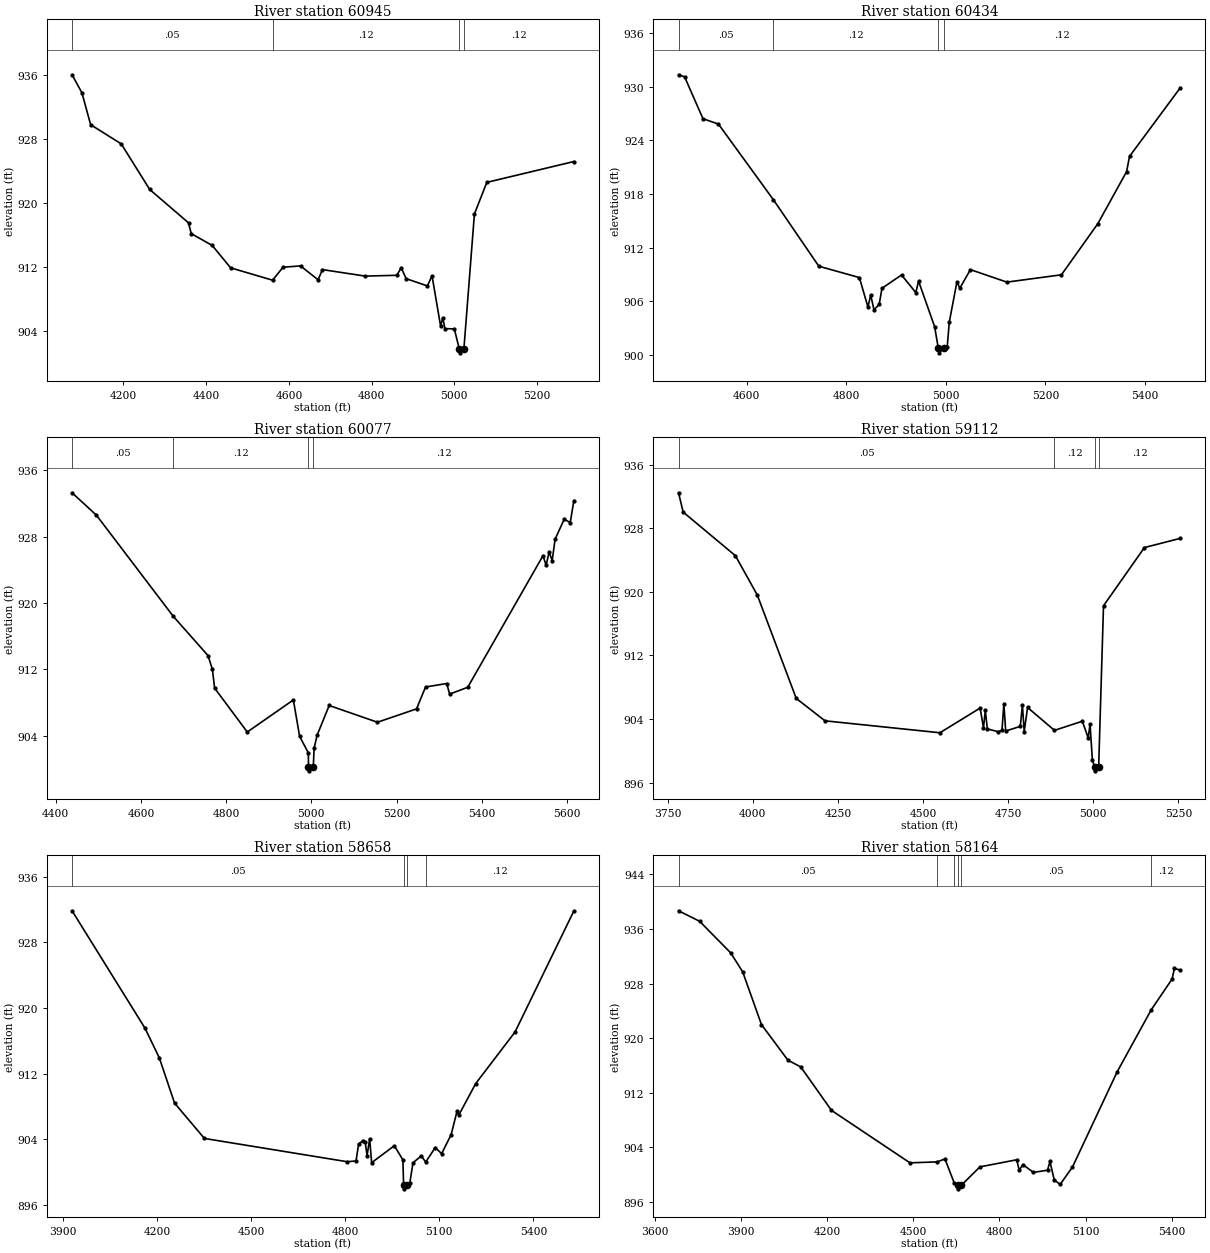
Type RM Length L Ch R = 1,60945,511,511,511
BEGIN DESCRIPTION:
Catlett Creek 68.0
END DESCRIPTION:
XS GIS Cut Line= 3
      2253684.97      7150542.50      2253384.92      7149668.47
      2253372.46      7149379.84
#Sta/Elev= 30
  4075.9  936.02  4099.7  933.77  4120.8  929.79  4194.8  927.39  4263.6  921.70
  4357.4  917.54  4364.0  916.19  4414.6  914.72  4459.2  911.92  4560.5  910.38
  4586.0  912.00  4628.1  912.16  4670.6  910.43  4681.2  911.70  4784.4  910.89
  4860.9  910.99  4871.5  911.93  4883.5  910.57  4934.9  909.66  4946.0  910.94
  4966.7  904.67  4972.0  905.67  4977.3  904.33  5000.0  904.30  5011.8  901.81
  5013.3  901.31  5023.1  901.81  5048.5  918.64  5078.5  922.59  5288.9  925.19
#Mann=4,-1,0
  4075.9    0.05       0  4560.5    0.12       0  5011.8    0.07       0
  5023.1    0.12       0
Bank Sta=5011.8,5023.1
Exp/Cntr=0.3,0.1

Type RM Length L Ch R = 1,60434,357,357,357
BEGIN DESCRIPTION:
Catlett Creek 67.0
END DESCRIPTION:
XS GIS Cut Line= 3
      2254060.10      7150144.29      2253828.36      7149659.65
      2253578.98      7149259.97
#Sta/Elev= 30
  4462.8  931.35  4475.0  931.12  4511.9  926.43  4543.0  925.83  4653.6  917.34
  4744.7  909.91  4826.2  908.64  4843.4  905.34  4848.9  906.69  4855.5  905.03
  4866.0  905.64  4871.6  907.44  4910.9  908.93  4939.6  906.96  4945.1  908.24
  4977.4  903.14  4984.8  900.71  4986.4  900.21  4996.2  900.71  5002.7  900.88
  5006.9  903.67  5022.2  908.16  5028.1  907.45  5049.3  909.53  5122.5  908.13
  5232.2  908.95  5305.3  914.67  5363.1  920.50  5369.0  922.21  5471.1  929.90
#Mann=4,-1,0
  4462.8    0.05       0  4653.6    0.12       0  4984.8    0.07       0
  4996.2    0.12       0
Bank Sta=4984.8,4996.2
Exp/Cntr=0.3,0.1

Type RM Length L Ch R = 1,60077,965,965,965
BEGIN DESCRIPTION:
Catlett Creek 66.0
END DESCRIPTION:
XS GIS Cut Line= 3
      2254236.20      7150071.62      2254115.05      7149523.14
      2253690.74      7149076.16
#Sta/Elev= 30
  4438.3  933.30  4495.6  930.59  4675.9  918.40  4757.4  913.67  4767.7  912.02
  4772.9  909.75  4849.6  904.45  4957.8  908.32  4972.5  903.93  4993.0  901.93
  4993.3  900.27  4994.9  899.77  5004.7  900.27  5006.4  902.47  5013.6  904.07
  5041.9  907.65  5155.2  905.63  5247.0  907.24  5268.1  909.88  5317.8  910.30
  5324.7  909.02  5367.2  909.85  5543.9  925.72  5551.2  924.54  5558.1  926.16
  5565.4  925.13  5572.3  927.71  5593.7  930.11  5607.8  929.71  5616.3  932.36
#Mann=4,-1,0
  4438.3    0.05       0  4675.9    0.12       0  4993.3    0.07       0
  5004.7    0.12       0
Bank Sta=4993.3,5004.7
Exp/Cntr=0.3,0.1

Type RM Length L Ch R = 1,59112,454,454,454
BEGIN DESCRIPTION:
Catlett Creek 65.0
END DESCRIPTION:
XS GIS Cut Line= 3
      2254288.28      7149995.67      2254729.00      7148860.00
      2254739.58      7148604.61
#Sta/Elev= 30
  3781.7  932.46  3795.3  930.03  3948.7  924.55  4013.0  919.60  4127.4  906.60
  4211.8  903.78  4549.4  902.28  4667.4  905.38  4677.4  902.92  4682.7  905.08
  4688.8  902.76  4721.0  902.41  4731.7  902.58  4737.2  905.94  4742.6  902.50
  4785.4  903.08  4791.7  905.71  4797.0  902.43  4806.8  905.46  4885.8  902.58
  4967.7  903.73  4984.9  901.63  4990.3  903.36  4997.2  898.84  5004.1  897.99
  5005.7  897.49  5015.6  897.99  5029.9  918.25  5150.0  925.57  5255.5  926.73
#Mann=4,-1,0
  3781.7    0.05       0  4885.8    0.12       0  5004.1    0.07       0
  5015.6    0.12       0
Bank Sta=5004.1,5015.6
Exp/Cntr=0.3,0.1

Type RM Length L Ch R = 1,58658,494,494,494
BEGIN DESCRIPTION:
Catlett Creek 64.0
END DESCRIPTION:
XS GIS Cut Line= 5
      2254299.15      7149999.98      2254483.59      7149689.68
      2254916.17      7149127.11      2254973.97      7148796.27
      2254877.38      7148626.97
#Sta/Elev= 30
  3927.9  931.86  4160.5  917.54  4206.3  913.92  4255.0  908.39  4350.2  904.08
  4805.7  901.24  4834.1  901.33  4842.3  903.39  4856.1  903.82  4863.1  903.68
  4869.4  901.99  4877.6  904.04  4883.9  901.12  4956.4  903.19  4983.6  901.47
  4986.0  898.43  4987.6  897.93  4997.5  898.43  5005.7  898.63  5015.9  901.11
  5042.7  901.96  5056.4  901.19  5087.0  902.97  5107.3  902.22  5137.7  904.55
  5156.6  907.42  5161.7  906.90  5216.1  910.78  5341.6  917.07  5529.3  931.84
#Mann=4,-1,0
  3927.9    0.05       0  4986.0   0.033       0  4997.5    0.05       0
  5056.4    0.12       0
Bank Sta=4986,4997.5
Exp/Cntr=0.3,0.1

Type RM Length L Ch R = 1,58164,459,459,459
BEGIN DESCRIPTION:
Catlett Creek 63.0
END DESCRIPTION:
XS GIS Cut Line= 3
      2256308.68      7149572.49      2255229.00      7148810.00
      2254904.01      7148535.01
#Sta/Elev= 30
  3682.3  938.67  3755.4  937.14  3864.0  932.50  3905.8  929.71  3971.1  921.99
  4063.4  916.77  4107.8  915.79  4214.9  909.42  4488.2  901.73  4583.0  901.87
  4610.1  902.30  4642.1  898.81  4654.7  898.42  4656.4  897.92  4666.5  898.42
  4732.0  901.14  4860.0  902.18  4868.7  900.66  4881.7  901.46  4918.4  900.33
  4967.3  900.65  4975.8  901.93  4990.6  899.24  5011.2  898.56  5054.1  901.11
  5210.1  915.09  5328.9  924.19  5401.2  928.67  5409.0  930.22  5429.8  929.98
#Mann=6,-1,0
  3682.3    0.05       0  4583.0    0.12       0  4642.1    0.05       0
  4654.7   0.033       0  4666.5    0.05       0  5328.9    0.12       0
Bank Sta=4654.7,4666.5
Exp/Cntr=0.3,0.1

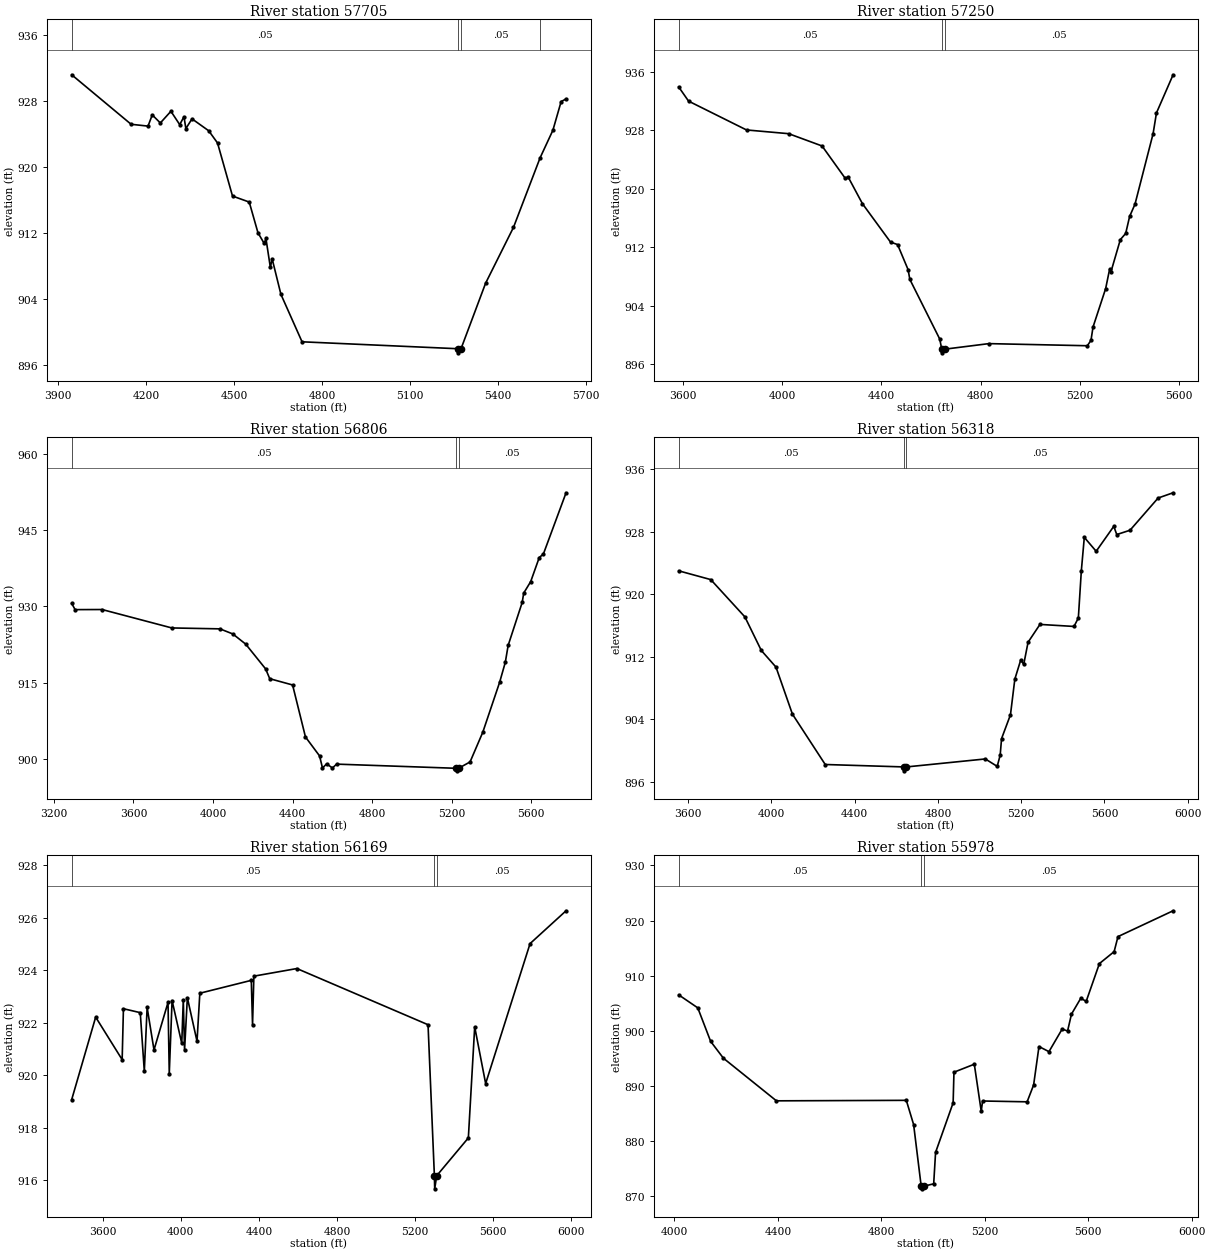
Type RM Length L Ch R = 1,57705,455,455,455
BEGIN DESCRIPTION:
Catlett Creek 62.0
END DESCRIPTION:
XS GIS Cut Line= 3
      2256397.63      7149051.64      2255520.90      7148466.07
      2254953.96      7148184.98
#Sta/Elev= 30
  3945.7  931.22  4148.5  925.21  4206.2  924.99  4220.6  926.35  4248.2  925.37
  4284.3  926.79  4314.3  925.17  4328.9  926.13  4335.3  924.69  4356.3  925.87
  4413.4  924.42  4443.4  922.94  4494.5  916.50  4551.6  915.77  4581.4  912.04
  4602.6  910.75  4608.6  911.35  4623.7  907.83  4629.7  908.89  4659.7  904.57
  4731.8  898.81  5262.5  897.97  5264.2  897.47  5274.4  897.97  5358.2  905.92
  5453.4  912.70  5544.2  921.14  5587.9  924.49  5616.0  927.97  5632.8  928.29
#Mann=4,-1,0
  3945.7    0.05       0  5262.5   0.033       0  5274.4    0.05       0
  5544.2    0.12       0
Bank Sta=5262.5,5274.4
Exp/Cntr=0.3,0.1

Type RM Length L Ch R = 1,57250,444,444,444
BEGIN DESCRIPTION:
Catlett Creek 61.0
END DESCRIPTION:
XS GIS Cut Line= 3
      2256623.36      7149051.67      2255628.46      7148044.78
      2255129.04      7147760.02
#Sta/Elev= 30
  3584.5  933.89  3624.1  931.96  3857.4  928.02  4027.2  927.51  4161.6  925.83
  4253.4  921.48  4267.6  921.53  4324.2  917.94  4437.3  912.69  4465.6  912.36
  4508.0  908.93  4515.0  907.60  4635.3  899.45  4643.5  898.06  4645.1  897.56
  4655.4  898.06  4833.3  898.82  5229.6  898.53  5244.3  899.26  5252.6  901.09
  5303.4  906.34  5319.3  908.98  5325.0  908.66  5362.5  913.03  5384.1  913.88
  5399.9  916.20  5421.5  917.87  5494.4  927.51  5508.0  930.35  5574.9  935.56
#Mann=3,-1,0
  3584.5    0.05       0  4643.5   0.033       0  4655.4    0.05       0
Bank Sta=4643.5,4655.4
Exp/Cntr=0.3,0.1

Type RM Length L Ch R = 1,56806,488,488,488
BEGIN DESCRIPTION:
Catlett Creek 60.0
END DESCRIPTION:
XS GIS Cut Line= 3
      2256794.81      7149027.81      2255776.49      7147653.96
      2255179.03      7147160.02
#Sta/Elev= 30
  3289.9  930.56  3307.0  929.33  3442.6  929.35  3793.2  925.73  4035.2  925.55
  4099.9  924.55  4164.6  922.55  4264.8  917.68  4285.6  915.75  4400.4  914.52
  4465.1  904.30  4536.1  900.57  4550.7  898.19  4571.5  899.02  4600.8  898.20
  4621.6  898.96  5222.8  898.14  5224.5  897.64  5234.7  898.14  5292.6  899.39
  5356.4  905.21  5441.1  915.03  5469.8  918.98  5484.1  922.30  5554.7  930.75
  5562.3  932.58  5597.4  934.84  5640.4  939.57  5661.2  940.26  5775.2  952.30
#Mann=3,-1,0
  3289.9    0.05       0  5222.8   0.033       0  5234.7    0.05       0
Bank Sta=5222.8,5234.7
Exp/Cntr=0.3,0.1

Type RM Length L Ch R = 1,56318,149,149,149
BEGIN DESCRIPTION:
Catlett Creek 59.0
END DESCRIPTION:
XS GIS Cut Line= 3
      2256967.38      7148457.62      2256085.12      7147312.72
      2255377.81      7146709.66
#Sta/Elev= 30
  3554.6  922.98  3708.5  921.86  3872.5  917.09  3951.3  912.80  4021.9  910.67
  4100.8  904.66  4258.4  898.22  4636.6  897.91  4638.2  897.41  4648.5  897.91
  5027.5  898.93  5084.6  897.98  5098.9  899.42  5105.5  901.53  5148.3  904.58
  5169.2  909.13  5197.7  911.59  5212.0  911.02  5232.8  913.85  5290.0  916.13
  5453.6  915.87  5474.4  916.96  5488.7  922.98  5503.0  927.26  5560.0  925.48
  5644.6  928.67  5658.9  927.62  5722.6  928.17  5857.6  932.29  5929.5  932.96
#Mann=3,-1,0
  3554.6    0.05       0  4636.6   0.033       0  4648.5    0.05       0
Bank Sta=4636.6,4648.5
Exp/Cntr=0.3,0.1

Type RM Length L Ch R = 1,56169,191,191,191
BEGIN DESCRIPTION:
Catlett Creek 58.5
END DESCRIPTION:
XS GIS Cut Line= 5
      2257188.63      7148443.77      2256201.85      7147231.42
      2256037.49      7147031.48      2255961.19      7146785.81
      2255669.23      7146439.26
#Sta/Elev= 30
  3440.9  919.07  3563.7  922.21  3699.4  920.59  3705.9  922.53  3792.1  922.38
  3812.9  920.15  3827.3  922.58  3862.5  920.96  3934.3  922.77  3940.7  920.06
  3955.1  922.84  4004.7  921.21  4012.6  922.87  4019.0  920.95  4033.4  922.95
  4082.9  921.29  4097.3  923.12  4360.9  923.61  4367.3  921.91  4374.1  923.77
  4594.3  924.06  5266.3  921.92  5298.8  916.17  5300.4  915.67  5310.7  916.17
  5472.8  917.61  5505.3  921.84  5561.4  919.68  5788.9  925.01  5973.3  926.26
#Mann=3,-1,0
  3440.9    0.05       0  5298.8   0.033       0  5310.7    0.05       0
Bank Sta=5298.8,5310.7
Exp/Cntr=0.3,0.1

Type RM Length L Ch R = 1,55978,533,533,533
BEGIN DESCRIPTION:
Catlett Creek 58.0
END DESCRIPTION:
XS GIS Cut Line= 4
      2257039.70      7147793.63      2256275.50      7147061.15
      2256178.49      7146730.12      2255756.76      7146446.38
#Sta/Elev= 30
  4016.4  906.50  4090.1  904.14  4139.8  898.06  4189.2  895.00  4394.2  887.26
  4896.5  887.35  4924.8  882.95  4954.0  871.78  4955.7  871.28  4965.9  871.78
  5002.4  872.19  5009.7  877.90  5077.6  886.90  5080.8  892.46  5159.5  893.91
  5186.3  885.35  5191.5  887.23  5363.7  887.08  5388.8  890.13  5409.6  897.12
  5448.2  896.19  5499.2  900.29  5520.2  899.94  5535.2  903.00  5571.2  905.88
  5592.2  905.33  5643.2  912.18  5700.2  914.35  5715.1  917.08  5928.2  921.77
#Mann=3,-1,0
  4016.4    0.05       0  4954.0   0.033       0  4965.9    0.05       0
Bank Sta=4954,4965.9
Exp/Cntr=0.3,0.1

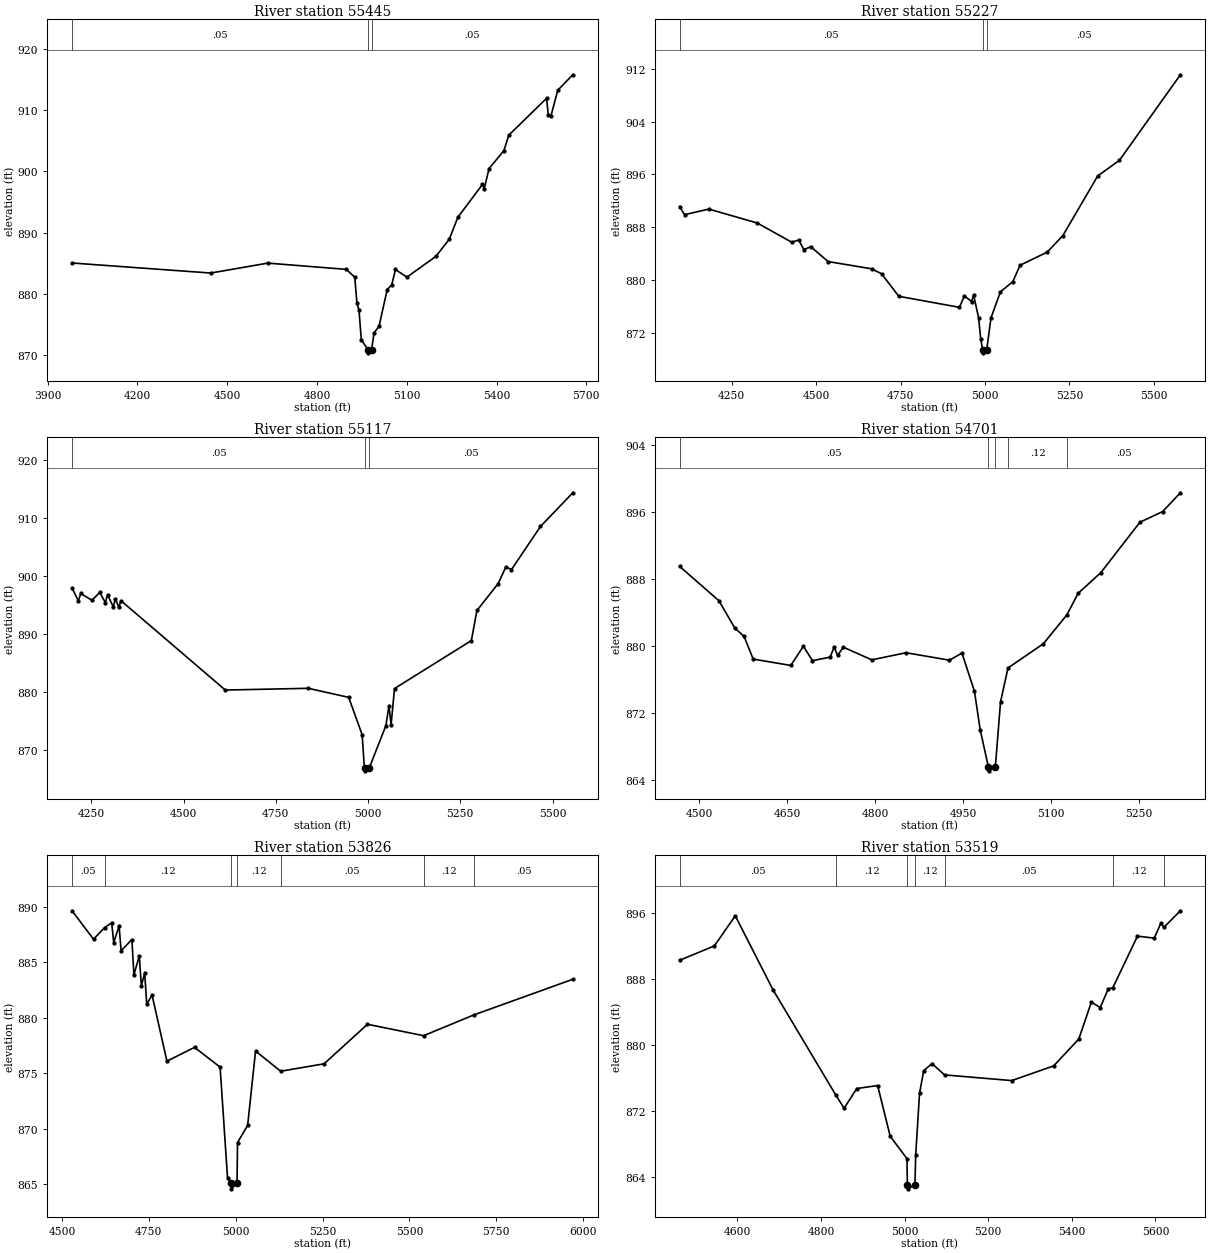
Type RM Length L Ch R = 1,55445,218,218,218
BEGIN DESCRIPTION:
Catlett Creek 57.0
END DESCRIPTION:
XS GIS Cut Line= 3
      2257148.37      7147284.12      2256379.00      7146610.00
      2255804.69      7146304.99
#Sta/Elev= 30
  3981.6  885.06  4445.1  883.42  4635.8  885.04  4898.2  884.02  4926.2  882.74
  4933.8  878.47  4940.5  877.37  4948.1  872.57  4970.6  870.90  4972.2  870.40
  4982.5  870.90  4990.8  873.66  5007.4  874.73  5034.7  880.71  5049.8  881.49
  5062.3  884.00  5100.6  882.75  5197.0  886.12  5242.3  888.95  5270.8  892.52
  5353.1  897.88  5358.7  897.15  5375.1  900.47  5424.7  903.40  5441.0  905.92
  5567.3  911.93  5572.9  909.25  5582.0  909.08  5604.6  913.24  5654.8  915.77
#Mann=3,-1,0
  3981.6    0.05       0  4970.6   0.033       0  4982.5    0.05       0
Bank Sta=4970.6,4982.5
Exp/Cntr=0.3,0.1

Type RM Length L Ch R = 1,55227,110,110,110
BEGIN DESCRIPTION:
Catlett Creek 56.5
END DESCRIPTION:
XS GIS Cut Line= 3
      2257205.50      7146923.61      2256458.74      7146414.31
      2255957.94      7146124.71
#Sta/Elev= 30
  4096.1  891.12  4110.7  889.89  4182.5  890.74  4326.1  888.63  4427.8  885.72
  4448.8  886.05  4463.7  884.61  4484.7  885.03  4535.5  882.79  4664.2  881.69
  4694.0  880.93  4744.9  877.52  4924.4  875.85  4939.2  877.58  4960.3  876.73
  4966.3  877.73  4981.3  874.25  4987.6  870.98  4993.4  869.45  4995.0  868.95
  5005.4  869.45  5017.8  874.25  5045.9  878.20  5082.4  879.74  5104.0  882.23
  5184.5  884.22  5230.7  886.73  5333.6  895.75  5398.2  898.14  5578.5  911.10
#Mann=3,-1,0
  4096.1    0.05       0  4993.4   0.033       0  5005.4    0.05       0
Bank Sta=4993.4,5005.4
Exp/Cntr=0.3,0.1

Type RM Length L Ch R = 1,55117,416,416,416
BEGIN DESCRIPTION:
Catlett Creek 56.0
END DESCRIPTION:
XS GIS Cut Line= 3
      2257188.27      7146744.61      2256509.47      7146317.10
      2256044.25      7146014.83
#Sta/Elev= 30
  4197.8  897.95  4215.2  895.68  4221.2  896.99  4251.7  895.82  4272.9  897.17
  4288.2  895.42  4294.1  896.78  4309.4  894.69  4315.3  896.03  4324.7  894.62
  4330.6  895.74  4613.2  880.32  4838.0  880.62  4947.5  879.06  4984.0  872.61
  4989.9  867.03  4991.3  866.87  4993.0  866.37  5003.3  866.87  5048.3  874.17
  5056.6  877.57  5062.5  874.34  5071.7  880.58  5280.0  888.86  5295.1  894.06
  5352.5  898.69  5373.6  901.58  5388.7  901.12  5467.2  908.56  5554.8  914.38
#Mann=3,-1,0
  4197.8    0.05       0  4991.3   0.033       0  5003.3    0.05       0
Bank Sta=4991.3,5003.3
Exp/Cntr=0.3,0.1

Type RM Length L Ch R = 1,54701,875,875,875
BEGIN DESCRIPTION:
Catlett Creek 55.0
END DESCRIPTION:
XS GIS Cut Line= 3
      2257068.92      7146200.99      2256612.11      7145926.57
      2256305.07      7145836.43
#Sta/Elev= 30
  4467.1  889.49  4534.1  885.38  4561.3  882.10  4576.8  881.13  4592.4  878.41
  4656.5  877.65  4677.9  879.95  4693.4  878.22  4723.6  878.65  4730.3  879.86
  4736.2  878.84  4745.9  879.83  4794.5  878.32  4852.8  879.17  4926.6  878.28
  4948.0  879.13  4969.3  874.56  4979.0  869.99  4992.9  865.56  4994.5  865.06
  5004.9  865.56  5013.7  873.30  5026.4  877.35  5086.6  880.24  5126.9  883.71
  5145.8  886.27  5184.4  888.73  5251.1  894.76  5289.7  896.03  5320.0  898.28
#Mann=5,-1,0
  4467.1    0.05       0  4992.9   0.033       0  5004.9    0.05       0
  5026.4    0.12       0  5126.9    0.05       0
Bank Sta=4992.9,5004.9
Exp/Cntr=0.3,0.1

Type RM Length L Ch R = 1,53826,307,307,307
BEGIN DESCRIPTION:
Catlett Creek 54.5
END DESCRIPTION:
XS GIS Cut Line= 3
      2257145.41      7145689.03      2256907.30      7145297.00
      2256644.90      7144350.26
#Sta/Elev= 30
  4529.0  889.64  4590.9  887.08  4622.5  888.12  4643.2  888.55  4649.0  886.78
  4664.5  888.27  4670.3  886.04  4701.3  887.05  4707.1  883.87  4722.6  885.58
  4728.5  882.88  4738.1  884.05  4744.0  881.24  4759.4  882.04  4802.1  876.10
  4881.6  877.34  4955.2  875.56  4976.5  865.60  4985.9  865.10  4987.9  864.60
  5003.9  865.10  5005.3  868.77  5034.4  870.31  5057.2  877.01  5129.5  875.19
  5254.4  875.86  5379.3  879.42  5540.8  878.39  5686.0  880.27  5970.1  883.47
#Mann=7,-1,0
  4529.0    0.05       0  4622.5    0.12       0  4985.9    0.07       0
  5003.9    0.12       0  5129.5    0.05       0  5540.8    0.12       0
  5686.0    0.05       0
Bank Sta=4985.9,5003.9
Exp/Cntr=0.3,0.1

Type RM Length L Ch R = 1,53519,560,560,560
BEGIN DESCRIPTION:
Catlett Creek 54.0
END DESCRIPTION:
XS GIS Cut Line= 3
      2257171.44      7145662.97      2257144.47      7145103.33
      2257187.07      7144467.65
#Sta/Elev= 30
  4462.1  890.25  4545.2  891.99  4595.2  895.63  4685.3  886.69  4835.3  873.96
  4855.5  872.34  4885.6  874.73  4935.6  875.09  4965.7  868.94  5005.7  866.25
  5006.7  863.09  5008.7  862.59  5024.8  863.09  5026.6  866.67  5035.8  874.16
  5045.8  876.90  5065.8  877.74  5095.5  876.38  5256.2  875.69  5356.5  877.47
  5416.6  880.72  5446.7  885.19  5467.9  884.53  5486.8  886.76  5498.2  886.95
  5556.9  893.17  5597.0  892.93  5612.8  894.73  5620.3  894.25  5659.5  896.24
#Mann=7,-1,0
  4462.1    0.05       0  4835.3    0.12       0  5006.7    0.07       0
  5024.8    0.12       0  5095.5    0.05       0  5498.2    0.12       0
  5620.3    0.05       0
Bank Sta=5006.7,5024.8
Exp/Cntr=0.3,0.1

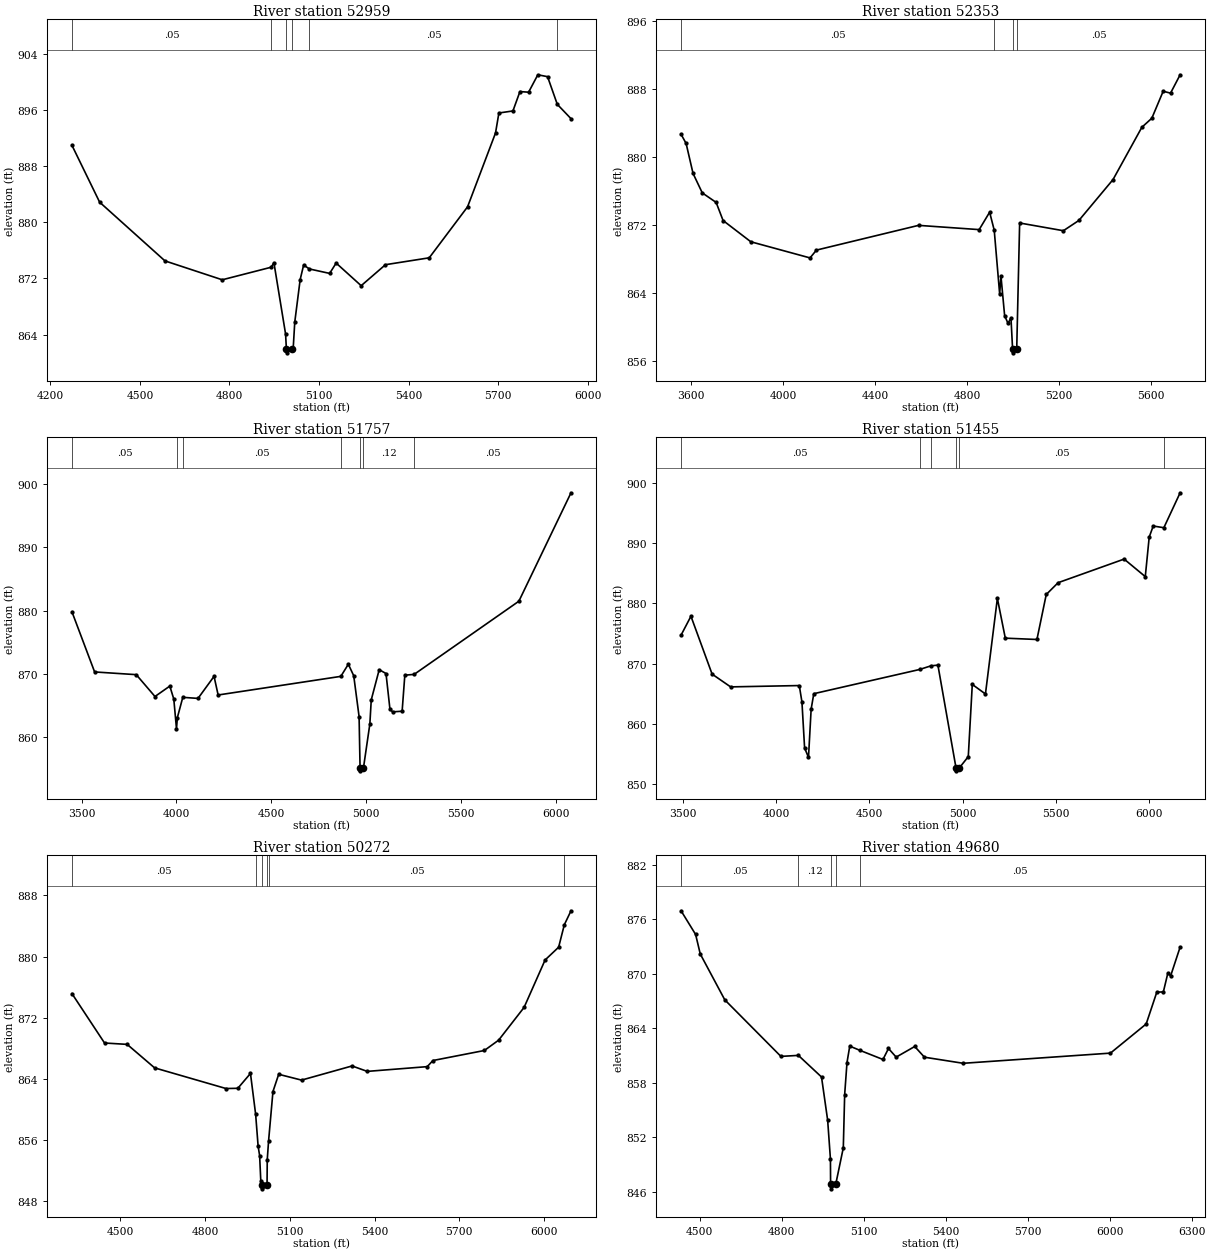
Type RM Length L Ch R = 1,52959,606,606,606
BEGIN DESCRIPTION:
Catlett Creek 53.0
END DESCRIPTION:
XS GIS Cut Line= 3
      2257739.38      7145854.18      2257540.41      7145154.31
      2257166.23      7144287.97
#Sta/Elev= 30
  4272.4  890.96  4365.2  882.86  4584.0  874.50  4775.8  871.81  4939.8  873.60
  4948.8  874.25  4987.9  864.08  4990.6  861.91  4992.6  861.41  5008.7  861.91
  5013.2  861.92  5018.6  865.78  5036.7  871.84  5048.3  873.91  5067.9  873.35
  5135.4  872.72  5157.2  874.19  5241.0  870.97  5322.4  873.96  5468.9  874.94
  5597.3  882.20  5690.9  892.71  5702.2  895.56  5749.2  895.85  5772.7  898.61
  5801.7  898.52  5832.6  901.00  5865.2  900.73  5897.8  896.79  5943.7  894.75
#Mann=6,-1,0
  4272.4    0.05       0  4939.8    0.12       0  4990.6    0.07       0
  5008.7    0.12       0  5067.9    0.05       0  5897.8    0.12       0
Bank Sta=4990.6,5008.7
Exp/Cntr=0.3,0.1

Type RM Length L Ch R = 1,52353,596,596,596
BEGIN DESCRIPTION:
Mapping XS 375727cf
END DESCRIPTION:
XS GIS Cut Line= 3
      2258268.29      7146011.85      2258217.69      7145542.98
      2257396.15      7144054.32
#Sta/Elev= 30
  3555.3  882.65  3577.3  881.57  3607.5  878.04  3647.7  875.75  3708.0  874.63
  3738.2  872.50  3858.9  870.00  4116.6  868.10  4144.5  869.02  4588.8  871.93
  4852.7  871.43  4898.2  873.48  4918.2  871.36  4941.8  863.86  4947.5  865.96
  4963.5  861.29  4978.3  860.40  4991.0  861.06  4998.0  857.43  5000.0  856.93
  5016.1  857.43  5028.8  872.21  5219.1  871.30  5286.7  872.51  5435.2  877.32
  5560.6  883.47  5604.1  884.54  5653.4  887.71  5685.5  887.49  5727.2  889.65
#Mann=4,-1,0
  3555.3    0.05       0  4918.2    0.12       0  4998.0    0.07       0
  5016.1    0.05       0
Bank Sta=4998,5016.1
Exp/Cntr=0.3,0.1

Type RM Length L Ch R = 1,51757,302,302,302
BEGIN DESCRIPTION:
Mapping XS 12f821e5
END DESCRIPTION:
XS GIS Cut Line= 2
      2259338.57      7145698.97      2257553.59      7143767.60
#Sta/Elev= 30
  3449.1  879.81  3568.6  870.28  3788.0  869.85  3886.7  866.39  3964.9  868.04
  3985.9  865.98  4000.1  861.28  4004.7  863.05  4033.3  866.26  4113.5  866.09
  4198.0  869.58  4219.5  866.63  4866.1  869.58  4905.6  871.50  4934.0  869.68
  4962.3  863.21  4967.4  855.12  4969.4  854.62  4985.5  855.12  5019.0  862.04
  5026.4  865.86  5068.3  870.64  5104.1  870.03  5125.0  864.36  5139.2  863.96
  5189.1  864.06  5203.3  869.77  5252.2  869.89  5804.3  881.48  6079.0  898.65
#Mann=7,-1,0
  3449.1    0.05       0  4004.7    0.12       0  4033.3    0.05       0
  4866.1    0.12       0  4967.4    0.07       0  4985.5    0.12       0
  5252.2    0.05       0
Bank Sta=4967.4,4985.5
Exp/Cntr=0.3,0.1

Type RM Length L Ch R = 1,51455,1183,1183,1183
BEGIN DESCRIPTION:
Mapping XS 3c7fdfff
END DESCRIPTION:
XS GIS Cut Line= 2
      2259597.31      7145616.85      2257780.42      7143654.51
#Sta/Elev= 30
  3490.5  874.74  3543.5  877.88  3656.9  868.27  3756.1  866.15  4124.1  866.37
  4138.3  863.64  4152.5  856.01  4173.4  854.44  4187.6  862.46  4201.8  865.02
  4768.9  869.04  4830.1  869.65  4866.9  869.76  4963.8  852.71  4965.8  852.21
  4982.0  852.71  5029.6  854.57  5051.1  866.56  5121.6  864.97  5185.5  880.84
  5228.0  874.24  5397.5  874.02  5447.4  881.49  5510.9  883.45  5864.7  887.37
  5978.1  884.46  5999.1  891.02  6020.6  892.86  6077.6  892.58  6164.8  898.38
#Mann=6,-1,0
  3490.5    0.05       0  4768.9    0.12       0  4830.1    0.05       0
  4963.8   0.033       0  4982.0    0.05       0  6077.6    0.12       0
Bank Sta=4963.8,4982
Exp/Cntr=0.3,0.1

Type RM Length L Ch R = 1,50272,592,592,592
BEGIN DESCRIPTION:
Catlett Creek 49.0
END DESCRIPTION:
XS GIS Cut Line= 3
      2259693.26      7145600.04      2259491.47      7144960.00
      2259330.14      7143876.64
#Sta/Elev= 30
  4328.9  875.17  4444.3  868.71  4524.4  868.53  4621.5  865.46  4874.2  862.76
  4916.1  862.79  4960.8  864.73  4979.1  859.39  4987.9  855.22  4993.2  854.00
  4997.4  850.63  5000.8  850.15  5002.8  849.65  5019.5  850.15  5020.2  853.46
  5024.9  855.91  5040.4  862.37  5060.7  864.62  5141.5  863.86  5320.4  865.71
  5374.1  865.00  5586.4  865.62  5606.6  866.42  5788.6  867.73  5839.1  869.08
  5929.2  873.36  6003.6  879.56  6051.5  881.23  6071.6  884.16  6095.3  885.99
#Mann=6,-1,0
  4328.9    0.05       0  4979.1    0.12       0  5000.8    0.07       0
  5019.5    0.12       0  5024.9    0.05       0  6071.6    0.12       0
Bank Sta=5000.8,5019.5
Exp/Cntr=0.3,0.1

Type RM Length L Ch R = 1,49680,669,669,669
BEGIN DESCRIPTION:
Catlett Creek 48.0
END DESCRIPTION:
XS GIS Cut Line= 3
      2260005.88      7145563.01      2260069.78      7144998.72
      2260263.69      7143755.75
#Sta/Elev= 30
  4432.1  876.96  4485.4  874.35  4502.4  872.20  4592.1  867.15  4797.4  860.92
  4861.3  861.03  4946.0  858.65  4968.5  853.88  4978.6  849.62  4979.2  846.83
  4981.2  846.33  4998.0  846.83  5025.7  850.85  5030.7  856.72  5039.2  860.24
  5049.3  862.05  5085.3  861.60  5170.8  860.58  5191.0  861.79  5219.1  860.84
  5287.0  862.01  5322.6  860.83  5464.3  860.16  6003.1  861.28  6133.8  864.49
  6172.7  868.00  6196.6  868.02  6213.2  870.11  6223.3  869.79  6258.0  872.96
#Mann=5,-1,0
  4432.1    0.05       0  4861.3    0.12       0  4979.2    0.07       0
  4998.0    0.12       0  5085.3    0.05       0
Bank Sta=4979.2,4998
Exp/Cntr=0.3,0.1

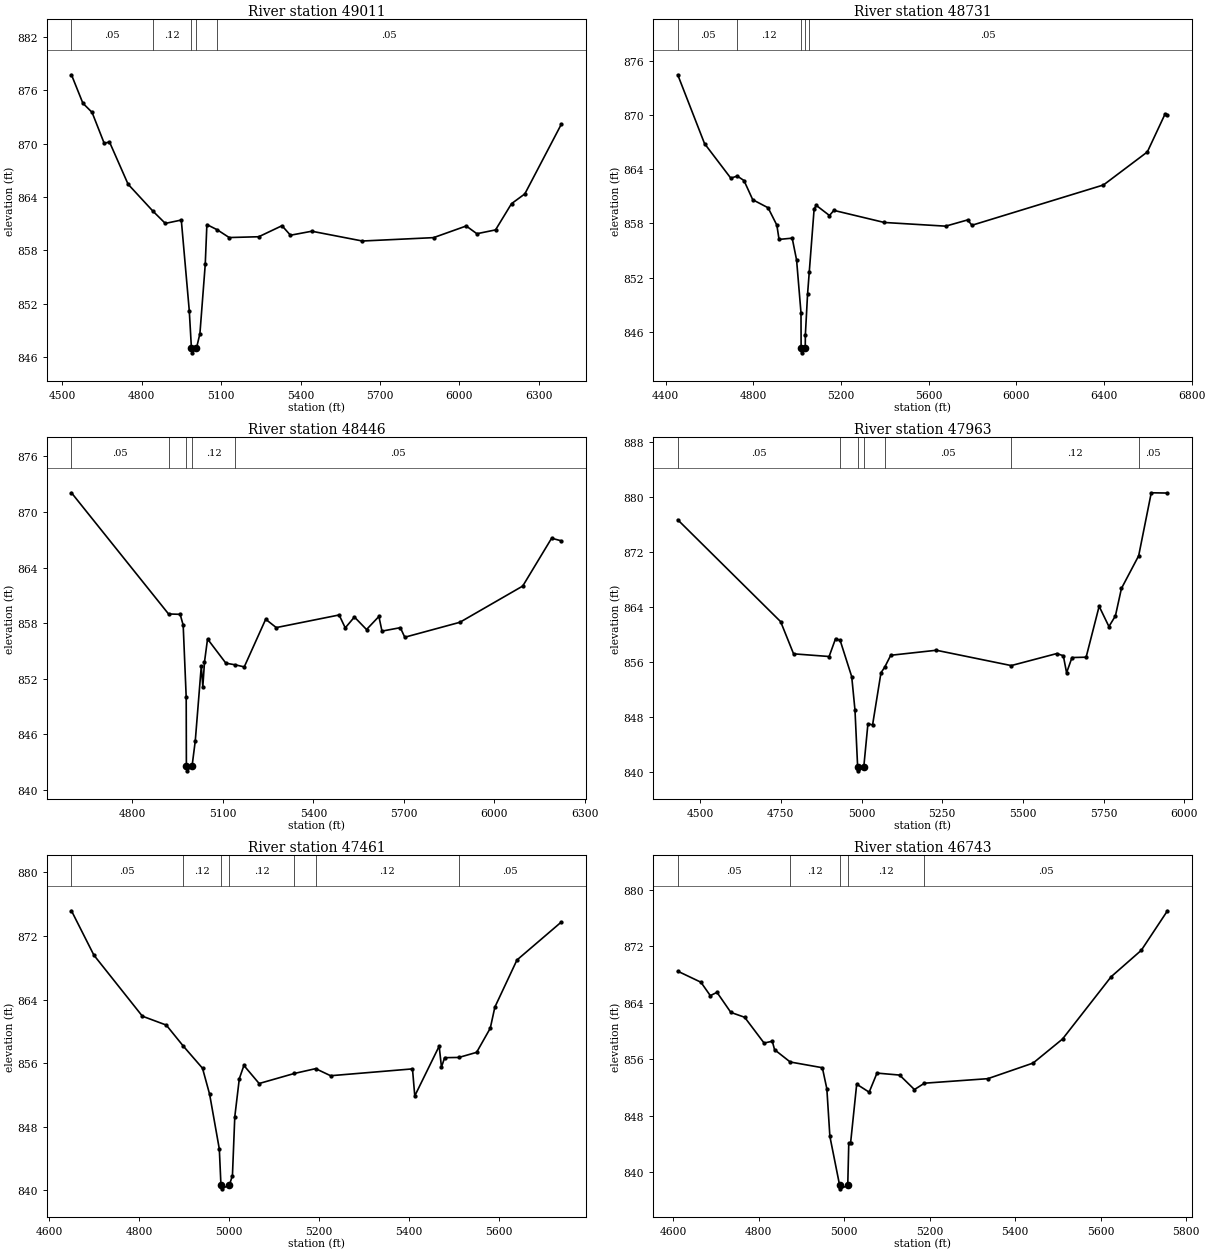
Type RM Length L Ch R = 1,49011,280,280,280
BEGIN DESCRIPTION:
Catlett Creek 47.0
END DESCRIPTION:
XS GIS Cut Line= 3
      2260570.98      7145622.97      2260529.00      7145160.00
      2260383.65      7143783.42
#Sta/Elev= 30
  4535.2  877.75  4578.3  874.55  4613.0  873.52  4658.7  870.05  4678.8  870.19
  4749.0  865.44  4842.8  862.41  4889.6  861.03  4949.9  861.41  4980.0  851.22
  4988.2  846.97  4990.2  846.47  5007.0  846.97  5020.2  848.63  5040.3  856.41
  5046.5  860.90  5085.8  860.31  5130.8  859.44  5242.3  859.53  5330.1  860.77
  5362.1  859.70  5442.5  860.15  5633.6  859.05  5902.4  859.43  6025.7  860.74
  6066.0  859.87  6136.4  860.30  6196.7  863.25  6247.0  864.35  6384.3  872.16
#Mann=5,-1,0
  4535.2    0.05       0  4842.8    0.12       0  4988.2    0.07       0
  5007.0    0.12       0  5085.8    0.05       0
Bank Sta=4988.2,5007
Exp/Cntr=0.3,0.1

Type RM Length L Ch R = 1,48731,285,285,285
BEGIN DESCRIPTION:
Mapping XS 2ac60920
END DESCRIPTION:
XS GIS Cut Line= 2
      2260771.30      7145612.19      2260804.54      7143378.14
#Sta/Elev= 30
  4455.3  874.49  4577.5  866.86  4697.5  863.02  4726.6  863.26  4757.5  862.76
  4797.5  860.63  4867.5  859.74  4907.5  857.81  4917.5  856.23  4977.5  856.37
  4997.5  853.95  5017.6  848.10  5018.2  844.15  5020.2  843.65  5037.0  844.15
  5037.6  845.66  5047.6  850.16  5055.4  852.63  5077.6  859.63  5087.6  860.00
  5147.6  858.88  5167.6  859.45  5397.6  858.11  5677.6  857.70  5777.6  858.39
  5797.6  857.80  6397.7  862.27  6597.7  865.93  6677.7  870.09  6689.6  869.98
#Mann=5,-1,0
  4455.3    0.05       0  4726.6    0.12       0  5018.2    0.07       0
  5037.0    0.12       0  5055.4    0.05       0
Bank Sta=5018.2,5037
Exp/Cntr=0.3,0.1

Type RM Length L Ch R = 1,48446,483,483,483
BEGIN DESCRIPTION:
Catlett Creek 46.0
END DESCRIPTION:
XS GIS Cut Line= 3
      2261029.00      7145559.98      2261018.49      7145158.82
      2261219.31      7143954.34
#Sta/Elev= 30
  4598.7  872.06  4920.3  858.99  4958.8  858.95  4968.8  857.78  4978.8  850.02
  4979.4  842.57  4981.4  842.07  4998.2  842.57  5008.9  845.31  5028.8  853.38
  5033.9  851.15  5039.4  853.81  5049.5  856.29  5110.3  853.68  5142.0  853.50
  5171.1  853.28  5242.1  858.42  5277.2  857.52  5485.4  858.88  5505.7  857.49
  5536.1  858.66  5576.2  857.31  5617.2  858.72  5627.4  857.14  5688.2  857.51
  5702.9  856.48  5885.3  858.09  6093.7  862.00  6189.4  867.16  6221.1  866.88
#Mann=5,-1,0
  4598.7    0.05       0  4920.3    0.12       0  4979.4    0.07       0
  4998.2    0.12       0  5142.0    0.05       0
Bank Sta=4979.4,4998.2
Exp/Cntr=0.3,0.1

Type RM Length L Ch R = 1,47963,502,502,502
BEGIN DESCRIPTION:
Catlett Creek 45.0
END DESCRIPTION:
XS GIS Cut Line= 3
      2261442.14      7145668.43      2261419.70      7145099.57
      2261541.96      7144160.20
#Sta/Elev= 30
  4430.7  876.73  4749.4  861.90  4789.4  857.22  4899.5  856.83  4919.5  859.44
  4933.7  859.17  4969.5  853.89  4979.6  849.02  4987.9  840.69  4989.9  840.19
  5006.7  840.69  5019.7  847.04  5034.1  846.88  5060.1  854.47  5071.7  855.28
  5090.3  857.01  5231.5  857.74  5463.5  855.51  5604.6  857.26  5624.8  856.94
  5634.9  854.46  5651.6  856.68  5695.4  856.73  5735.7  864.14  5766.0  861.19
  5786.1  862.74  5804.7  866.73  5858.1  871.49  5897.1  880.66  5947.3  880.62
#Mann=7,-1,0
  4430.7    0.05       0  4933.7    0.12       0  4987.9    0.07       0
  5006.7    0.12       0  5071.7    0.05       0  5463.5    0.12       0
  5858.1    0.05       0
Bank Sta=4987.9,5006.7
Exp/Cntr=0.3,0.1

Type RM Length L Ch R = 1,47461,718,718,718
BEGIN DESCRIPTION:
Catlett Creek 44.0
END DESCRIPTION:
XS GIS Cut Line= 3
      2262059.69      7145356.76      2261885.21      7145052.20
      2261757.62      7144324.60
#Sta/Elev= 30
  4649.0  875.18  4698.9  869.60  4806.8  861.92  4860.0  860.80  4897.8  858.16
  4940.6  855.37  4956.4  852.10  4978.0  845.21  4981.6  840.70  4983.6  840.20
  5000.5  840.70  5007.2  841.87  5012.4  849.26  5022.5  854.06  5032.7  855.72
  5066.6  853.45  5144.6  854.71  5192.3  855.32  5225.6  854.43  5407.8  855.29
  5412.9  851.89  5467.2  858.15  5472.3  855.52  5479.4  856.70  5511.1  856.73
  5550.5  857.37  5580.9  860.41  5591.1  863.06  5640.3  868.99  5738.7  873.75
#Mann=7,-1,0
  4649.0    0.05       0  4897.8    0.12       0  4981.6    0.07       0
  5000.5    0.12       0  5144.6    0.05       0  5192.3    0.12       0
  5511.1    0.05       0
Bank Sta=4981.6,5000.5
Exp/Cntr=0.3,0.1

Type RM Length L Ch R = 1,46743,776,776,776
BEGIN DESCRIPTION:
Catlett Creek 43.0
END DESCRIPTION:
XS GIS Cut Line= 3
      2262501.57      7145122.68      2262380.00      7144737.14
      2262092.98      7144053.60
#Sta/Elev= 30
  4610.9  868.45  4665.1  866.89  4687.1  864.99  4702.7  865.46  4735.1  862.62
  4767.4  861.93  4812.9  858.28  4832.1  858.54  4837.4  857.34  4874.0  855.60
  4949.2  854.79  4959.7  851.81  4966.8  845.07  4989.6  838.15  4991.6  837.65
  5008.6  838.15  5011.0  844.11  5015.2  844.11  5029.5  852.46  5058.7  851.33
  5077.0  854.03  5129.9  853.75  5164.6  851.70  5188.0  852.60  5336.3  853.24
  5442.2  855.45  5511.0  858.85  5624.8  867.67  5695.3  871.41  5756.5  877.00
#Mann=5,-1,0
  4610.9    0.05       0  4874.0    0.12       0  4989.6    0.07       0
  5008.6    0.12       0  5188.0    0.05       0
Bank Sta=4989.6,5008.6
Exp/Cntr=0.3,0.1