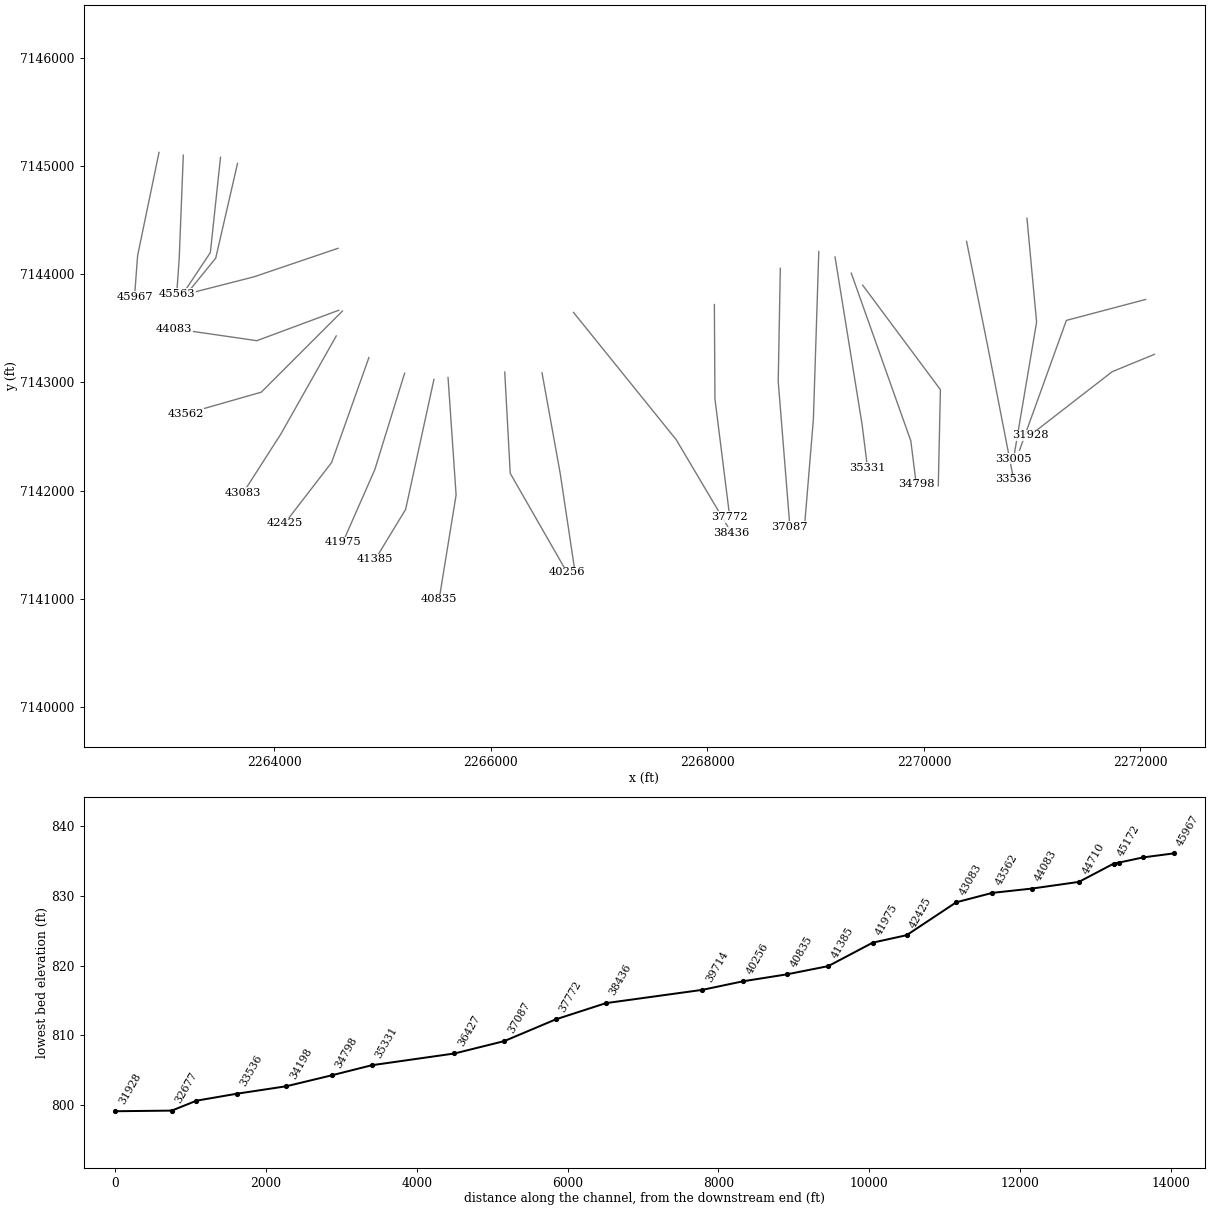
HEC-RAS study Catlett Creek.prj: Catlett Creek Base Level Engineering

--- Catlett Creek.g01 (geometry) --- (continued)

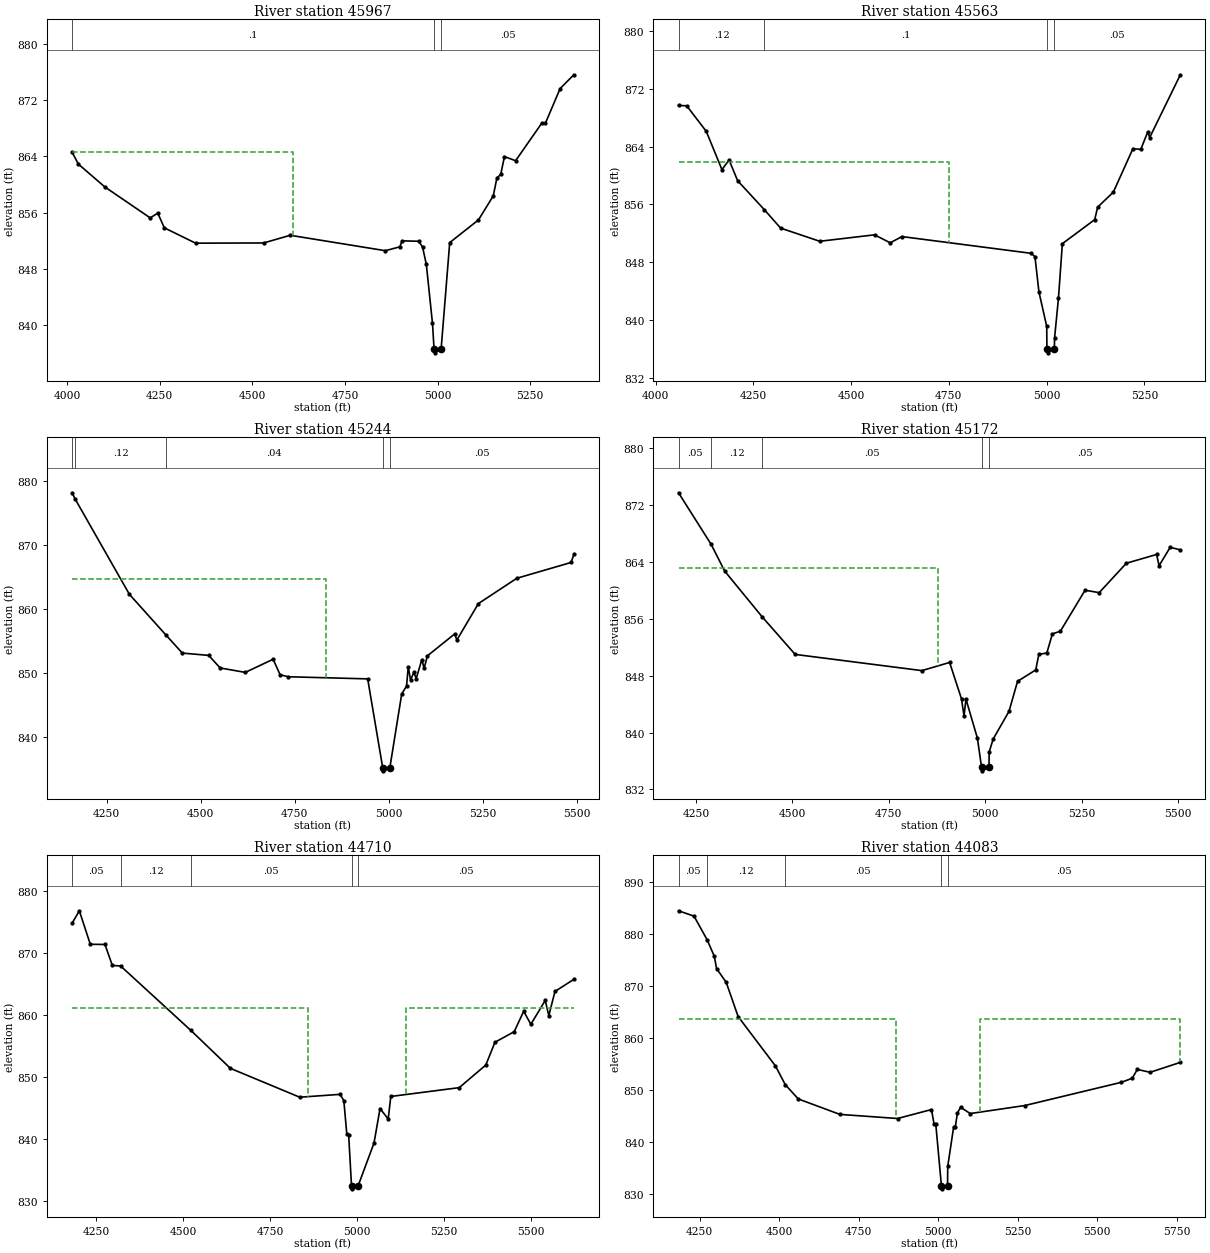
Type RM Length L Ch R = 1,45967,404,404,404
BEGIN DESCRIPTION:
Catlett Creek 42.0
END DESCRIPTION:
XS GIS Cut Line= 3
      2262934.99      7145126.60      2262737.18      7144172.47
      2262708.82      7143793.15
#Sta/Elev= 30
  4013.1  864.58  4030.1  862.88  4101.5  859.64  4224.1  855.24  4244.5  855.92
  4262.1  853.83  4346.6  851.65  4530.5  851.68  4602.0  852.77  4858.9  850.58
  4898.1  851.13  4904.0  851.98  4949.0  851.92  4959.4  851.10  4969.6  848.63
  4986.2  840.25  4990.5  836.57  4992.5  836.07  5009.5  836.57  5032.7  851.73
  5110.3  854.95  5150.4  858.37  5159.9  860.87  5170.5  861.44  5180.5  863.95
  5210.6  863.36  5280.8  868.66  5290.8  868.66  5330.9  873.62  5367.9  875.57
#Mann=3,-1,0
  4013.1     0.1       0  4990.5    0.07       0  5009.5    0.05       0
#XS Ineff=2,0
    0.00 4609.50  864.54               0
Permanent Ineff=
       F       F
Bank Sta=4990.5,5009.5
Exp/Cntr=0.3,0.1

Type RM Length L Ch R = 1,45563,319,319,319
BEGIN DESCRIPTION:
Catlett Creek 41.0
END DESCRIPTION:
XS GIS Cut Line= 3
      2263159.23      7145100.94      2263121.46      7144144.83
      2263098.27      7143819.11
#Sta/Elev= 30
  4058.7  869.68  4079.7  869.62  4129.7  866.09  4169.7  860.81  4188.0  862.14
  4209.8  859.28  4278.4  855.26  4319.8  852.73  4419.9  850.91  4560.0  851.80
  4600.1  850.70  4630.1  851.56  4960.3  849.25  4970.3  848.79  4980.4  843.94
  5000.4  839.14  5000.9  836.00  5002.9  835.50  5019.9  836.00  5020.5  837.57
  5030.4  843.04  5040.4  850.58  5123.1  853.90  5130.7  855.63  5170.8  857.70
  5220.9  863.71  5241.0  863.60  5258.7  866.02  5263.7  865.24  5342.1  873.91
#Mann=4,-1,0
  4058.7    0.12       0  4278.4     0.1       0  5000.9    0.03       0
  5019.9    0.05       0
#XS Ineff=2,0
    0.00 4750.00  861.89               0
Permanent Ineff=
       F       F
Bank Sta=5000.9,5019.9
Exp/Cntr=0.3,0.1

Type RM Length L Ch R = 1,45244,72,72,72
BEGIN DESCRIPTION:
Catlett Creek 40.0
END DESCRIPTION:
XS GIS Cut Line= 3
      2263502.97      7145081.57      2263409.09      7144200.60
      2263161.07      7143827.22
#Sta/Elev= 30
  4158.0  878.09  4166.6  877.07  4310.4  862.27  4407.2  855.95  4451.2  853.11
  4521.2  852.75  4551.8  850.79  4618.6  850.10  4692.6  852.15  4711.1  849.74
  4732.8  849.42  4944.0  849.09  4983.9  835.26  4985.9  834.76  5003.0  835.26
  5034.5  846.75  5047.3  847.96  5051.9  850.98  5057.9  848.93  5067.0  850.10
  5073.0  849.14  5088.0  852.09  5094.0  850.75  5103.0  852.69  5175.2  856.09
  5181.2  855.15  5238.3  860.82  5340.6  864.77  5484.9  867.23  5492.2  868.49
#Mann=5,-1,0
  4158.0    0.05       0  4166.6    0.12       0  4407.2    0.04       0
  4983.9    0.05       0  5003.0    0.05       0
#XS Ineff=2,0
    0.00 4831.90  864.69               0
Permanent Ineff=
       F       F
Bank Sta=4983.9,5003
Exp/Cntr=0.3,0.1

Type RM Length L Ch R = 1,45172,462,462,462
BEGIN DESCRIPTION:
Catlett Creek 39.5
END DESCRIPTION:
XS GIS Cut Line= 3
      2263660.13      7145024.55      2263458.73      7144149.03
      2263205.13      7143837.36
#Sta/Elev= 30
  4205.0  873.73  4289.4  866.48  4324.6  862.71  4421.0  856.32  4507.2  850.99
  4835.6  848.71  4907.4  849.86  4938.2  844.73  4944.7  842.34  4949.8  844.70
  4979.3  839.22  4990.2  835.11  4992.2  834.61  5009.3  835.11  5010.0  837.28
  5020.3  839.09  5061.3  842.98  5083.4  847.20  5130.6  848.81  5138.5  850.99
  5159.3  851.19  5173.7  853.88  5194.5  854.26  5258.4  860.02  5295.0  859.68
  5365.4  863.82  5443.7  865.05  5450.2  863.47  5478.9  866.06  5505.2  865.70
#Mann=5,-1,0
  4205.0    0.05       0  4289.4    0.12       0  4421.0    0.05       0
  4990.2    0.04       0  5009.3    0.05       0
#XS Ineff=2,0
    0.00 4877.30  863.10               0
Permanent Ineff=
       F       F
Bank Sta=4990.2,5009.3
Exp/Cntr=0.3,0.1

Type RM Length L Ch R = 1,44710,627,627,627
BEGIN DESCRIPTION:
Catlett Creek 39.0
END DESCRIPTION:
XS GIS Cut Line= 3
      2264588.58      7144240.08      2263812.41      7143976.52
      2263209.26      7143822.10
#Sta/Elev= 30
  4180.3  874.80  4201.2  876.81  4232.7  871.41  4274.9  871.38  4296.0  868.00
  4319.8  867.91  4521.9  857.52  4635.4  851.41  4834.6  846.76  4950.8  847.22
  4961.4  846.21  4970.1  840.76  4975.4  840.60  4983.5  832.49  4985.5  831.99
  5002.6  832.49  5048.2  839.38  5065.5  844.93  5089.0  843.25  5096.4  846.88
  5293.0  848.30  5369.5  851.94  5395.8  855.62  5451.1  857.32  5478.4  860.61
  5499.0  858.51  5540.3  862.36  5550.6  859.91  5568.3  863.81  5622.6  865.76
#Mann=5,-1,0
  4180.3    0.05       0  4319.8    0.12       0  4521.9    0.05       0
  4983.5    0.04       0  5002.6    0.05       0
#XS Ineff=2,0
    0.00 4859.60  861.19 5140.40    0.00  861.19
Permanent Ineff=
       F       F
Bank Sta=4983.5,5002.6
Exp/Cntr=0.3,0.1

Type RM Length L Ch R = 1,44083,521,521,521
BEGIN DESCRIPTION:
Catlett Creek 38.0
END DESCRIPTION:
XS GIS Cut Line= 3
      2264594.65      7143667.16      2263838.30      7143386.08
      2263075.07      7143496.81
#Sta/Elev= 30
  4183.9  884.40  4232.6  883.37  4273.8  878.84  4296.6  875.63  4303.4  873.32
  4333.8  870.67  4371.3  864.10  4488.6  854.63  4519.6  851.02  4560.6  848.28
  4691.3  845.32  4872.7  844.53  4979.4  846.25  4987.7  843.39  4993.0  843.39
  5010.8  831.53  5012.8  831.03  5029.9  831.53  5030.5  835.33  5049.3  842.97
  5054.3  842.88  5060.8  845.55  5070.9  846.69  5101.2  845.48  5273.0  847.02
  5576.1  851.47  5610.8  852.25  5626.7  853.95  5667.1  853.40  5762.0  855.30
#Mann=5,-1,0
  4183.9    0.05       0  4273.8    0.12       0  4519.6    0.05       0
  5010.8    0.04       0  5029.9    0.05       0
#XS Ineff=2,0
    0.00 4868.00  863.71 5132.00    0.00  863.71
Permanent Ineff=
       F       F
Bank Sta=5010.8,5029.9
Exp/Cntr=0.3,0.1

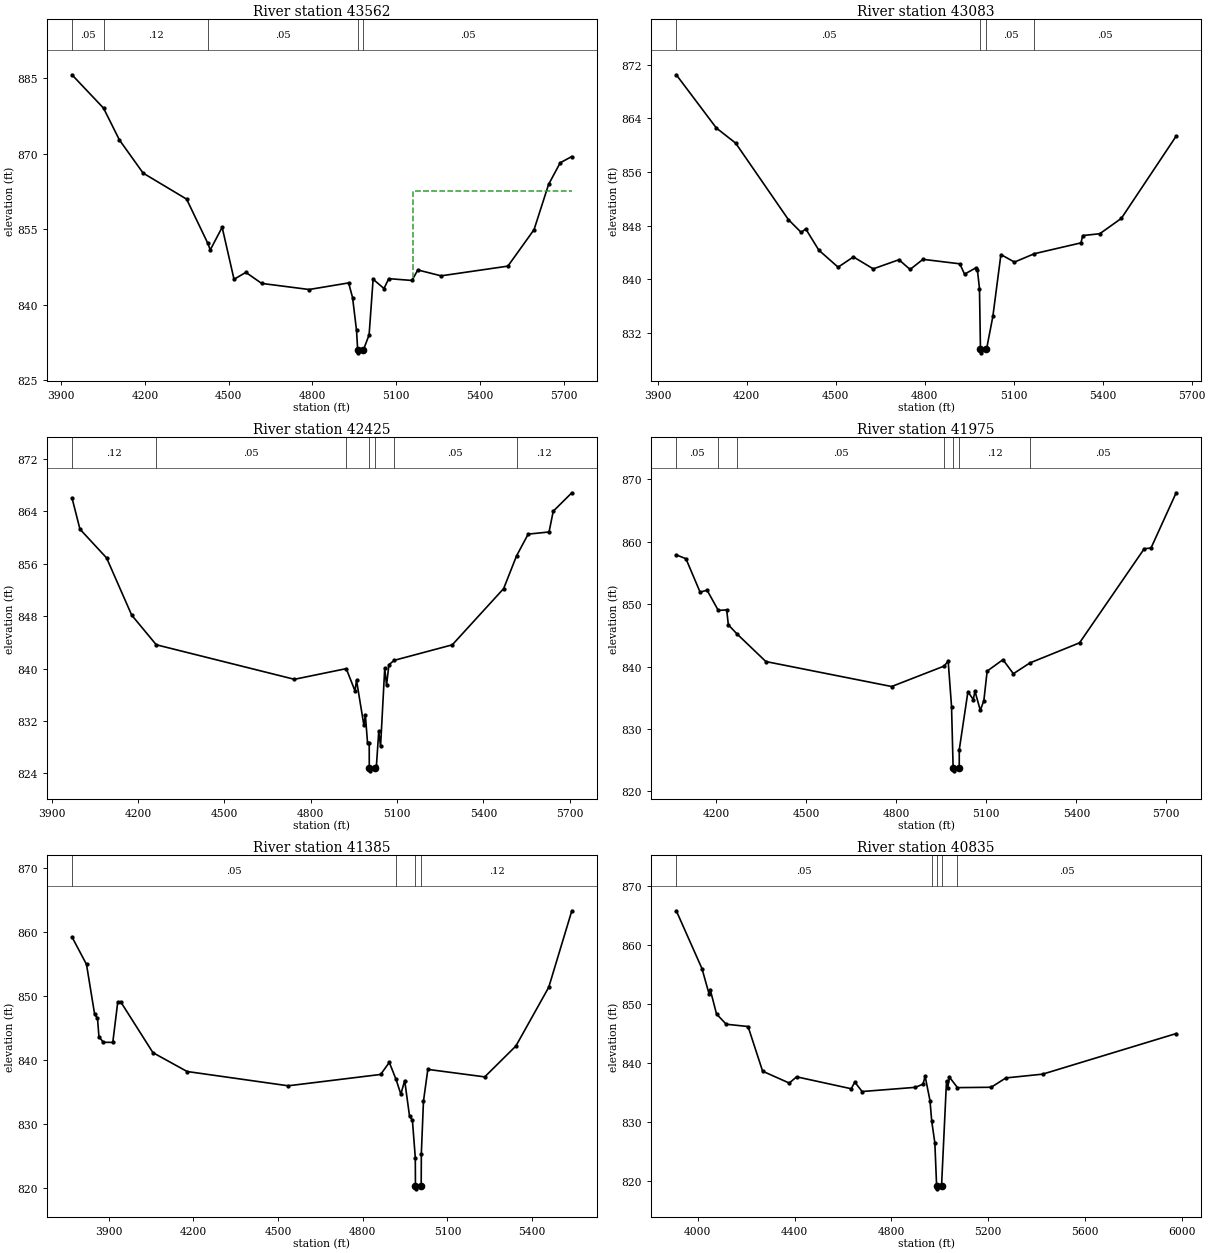
Type RM Length L Ch R = 1,43562,479,479,479
BEGIN DESCRIPTION:
Catlett Creek 37.0
END DESCRIPTION:
XS GIS Cut Line= 3
      2264629.03      7143660.03      2263879.00      7142910.00
      2263179.01      7142710.00
#Sta/Elev= 30
  3939.3  885.74  4052.3  879.10  4109.0  872.78  4193.9  866.18  4349.5  861.00
  4424.5  852.31  4434.3  850.91  4476.7  855.40  4519.2  845.05  4561.6  846.43
  4618.2  844.23  4787.9  843.02  4929.3  844.33  4943.4  841.41  4957.6  834.87
  4961.8  830.92  4963.8  830.42  4981.6  830.92  5002.6  834.01  5016.9  845.06
  5055.9  843.22  5072.8  845.18  5156.0  844.82  5176.8  846.91  5260.0  845.74
  5499.2  847.67  5592.8  854.93  5644.8  863.92  5686.4  868.23  5728.0  869.48
#Mann=5,-1,0
  3939.3    0.05       0  4052.3    0.12       0  4424.5    0.05       0
  4961.8    0.04       0  4981.6    0.05       0
#XS Ineff=2,0
       0                 5160.60    0.00  862.63
Permanent Ineff=
       F       F
Bank Sta=4961.8,4981.6
Exp/Cntr=0.3,0.1

Type RM Length L Ch R = 1,43083,658,658,658
BEGIN DESCRIPTION:
Catlett Creek 36.0
END DESCRIPTION:
XS GIS Cut Line= 3
      2264571.95      7143429.81      2264062.45      7142526.95
      2263713.31      7141981.29
#Sta/Elev= 30
  3963.3  870.49  4098.3  862.56  4163.3  860.31  4341.0  848.92  4384.3  847.00
  4399.4  847.54  4443.5  844.37  4508.5  841.83  4560.2  843.36  4627.0  841.58
  4713.6  842.94  4751.2  841.49  4794.5  843.00  4918.7  842.33  4934.6  840.79
  4972.1  841.71  4977.9  841.47  4985.0  838.63  4988.3  829.57  4990.3  829.07
  5008.6  829.57  5030.1  834.50  5057.2  843.71  5102.9  842.59  5170.2  843.84
  5327.0  845.45  5332.9  846.54  5390.4  846.81  5463.1  849.10  5647.8  861.35
#Mann=4,-1,0
  3963.3    0.05       0  4988.3    0.07       0  5008.6    0.05       0
  5170.2    0.05       0
Bank Sta=4988.3,5008.6
Exp/Cntr=0.3,0.1

Type RM Length L Ch R = 1,42425,450,450,450
BEGIN DESCRIPTION:
Catlett Creek 35.0
END DESCRIPTION:
XS GIS Cut Line= 3
      2264873.60      7143230.15      2264529.00      7142260.00
      2264097.69      7141699.72
#Sta/Elev= 30
  3970.5  866.10  3998.2  861.30  4090.8  856.90  4178.0  848.16  4263.3  843.63
  4743.1  838.35  4923.4  839.98  4953.8  836.58  4959.1  838.21  4984.6  831.34
  4989.9  832.84  4997.4  828.61  5003.2  828.61  5003.4  824.86  5005.4  824.36
  5023.8  824.86  5028.1  825.04  5036.3  830.39  5042.6  828.09  5057.1  840.04
  5063.4  837.44  5071.6  840.58  5090.1  841.25  5291.8  843.62  5470.3  852.22
  5514.9  857.20  5555.4  860.54  5628.0  860.87  5642.5  864.04  5707.1  866.86
#Mann=7,-1,0
  3970.5    0.12       0  4263.3    0.05       0  4923.4    0.12       0
  5003.4    0.07       0  5023.8    0.12       0  5090.1    0.05       0
  5514.9    0.12       0
Bank Sta=5003.4,5023.8
Exp/Cntr=0.3,0.1

Type RM Length L Ch R = 1,41975,590,590,590
BEGIN DESCRIPTION:
Catlett Creek 34.0
END DESCRIPTION:
XS GIS Cut Line= 3
      2265203.45      7143085.80      2264927.98      7142193.98
      2264633.02      7141523.27
#Sta/Elev= 30
  4066.6  857.89  4098.7  857.28  4145.9  851.92  4169.2  852.23  4206.6  848.99
  4234.5  849.08  4240.1  846.68  4268.6  845.24  4365.1  840.80  4784.4  836.80
  4959.1  840.07  4972.8  840.87  4984.0  833.59  4989.3  823.79  4991.3  823.29
  5009.7  823.79  5009.8  826.69  5038.6  835.96  5056.5  834.71  5062.0  836.06
  5079.9  832.98  5091.7  834.54  5102.7  839.27  5155.4  841.10  5190.1  838.85
  5245.3  840.58  5410.7  843.80  5626.2  858.87  5648.9  858.99  5732.7  867.84
#Mann=7,-1,0
  4066.6    0.05       0  4206.6    0.12       0  4268.6    0.05       0
  4959.1    0.12       0  4989.3    0.07       0  5009.7    0.12       0
  5245.3    0.05       0
Bank Sta=4989.3,5009.7
Exp/Cntr=0.3,0.1

Type RM Length L Ch R = 1,41385,550,550,550
BEGIN DESCRIPTION:
Catlett Creek 33.0
END DESCRIPTION:
XS GIS Cut Line= 3
      2265474.27      7143028.46      2265212.71      7141826.59
      2264931.90      7141364.41
#Sta/Elev= 30
  3770.0  859.24  3821.5  854.95  3850.3  847.17  3860.4  846.55  3865.5  843.69
  3881.0  842.80  3914.6  842.78  3932.2  849.09  3942.4  849.13  4056.8  841.18
  4177.8  838.24  4536.0  836.01  4863.5  837.78  4894.2  839.66  4917.8  837.04
  4935.1  834.70  4948.7  836.83  4965.8  831.29  4976.0  830.66  4986.3  824.78
  4986.8  820.43  4988.8  819.93  5007.2  820.43  5007.7  825.44  5015.2  833.60
  5030.7  838.57  5232.3  837.40  5342.7  842.22  5459.0  851.38  5540.8  863.32
#Mann=4,-1,0
  3770.0    0.05       0  4917.8    0.12       0  4986.8    0.07       0
  5007.2    0.12       0
Bank Sta=4986.8,5007.2
Exp/Cntr=0.3,0.1

Type RM Length L Ch R = 1,40835,579,579,579
BEGIN DESCRIPTION:
Catlett Creek 32.0
END DESCRIPTION:
XS GIS Cut Line= 3
      2265604.49      7143045.85      2265679.00      7141960.00
      2265522.20      7140995.47
#Sta/Elev= 30
  3911.5  865.81  4017.6  856.02  4046.6  851.78  4051.6  852.48  4077.7  848.34
  4117.8  846.61  4208.0  846.22  4268.2  838.66  4378.4  836.65  4408.5  837.71
  4634.4  835.69  4649.1  836.82  4679.2  835.22  4899.7  835.93  4930.8  836.47
  4939.8  837.79  4959.8  833.69  4967.1  830.16  4979.9  826.54  4987.2  819.25
  4989.2  818.75  5007.6  819.25  5028.1  837.03  5033.2  835.87  5040.4  837.64
  5073.5  835.88  5212.7  835.94  5273.4  837.52  5425.4  838.16  5977.1  845.03
#Mann=5,-1,0
  3911.5    0.05       0  4967.1    0.12       0  4987.2    0.07       0
  5007.6    0.12       0  5073.5    0.05       0
Bank Sta=4987.2,5007.6
Exp/Cntr=0.3,0.1

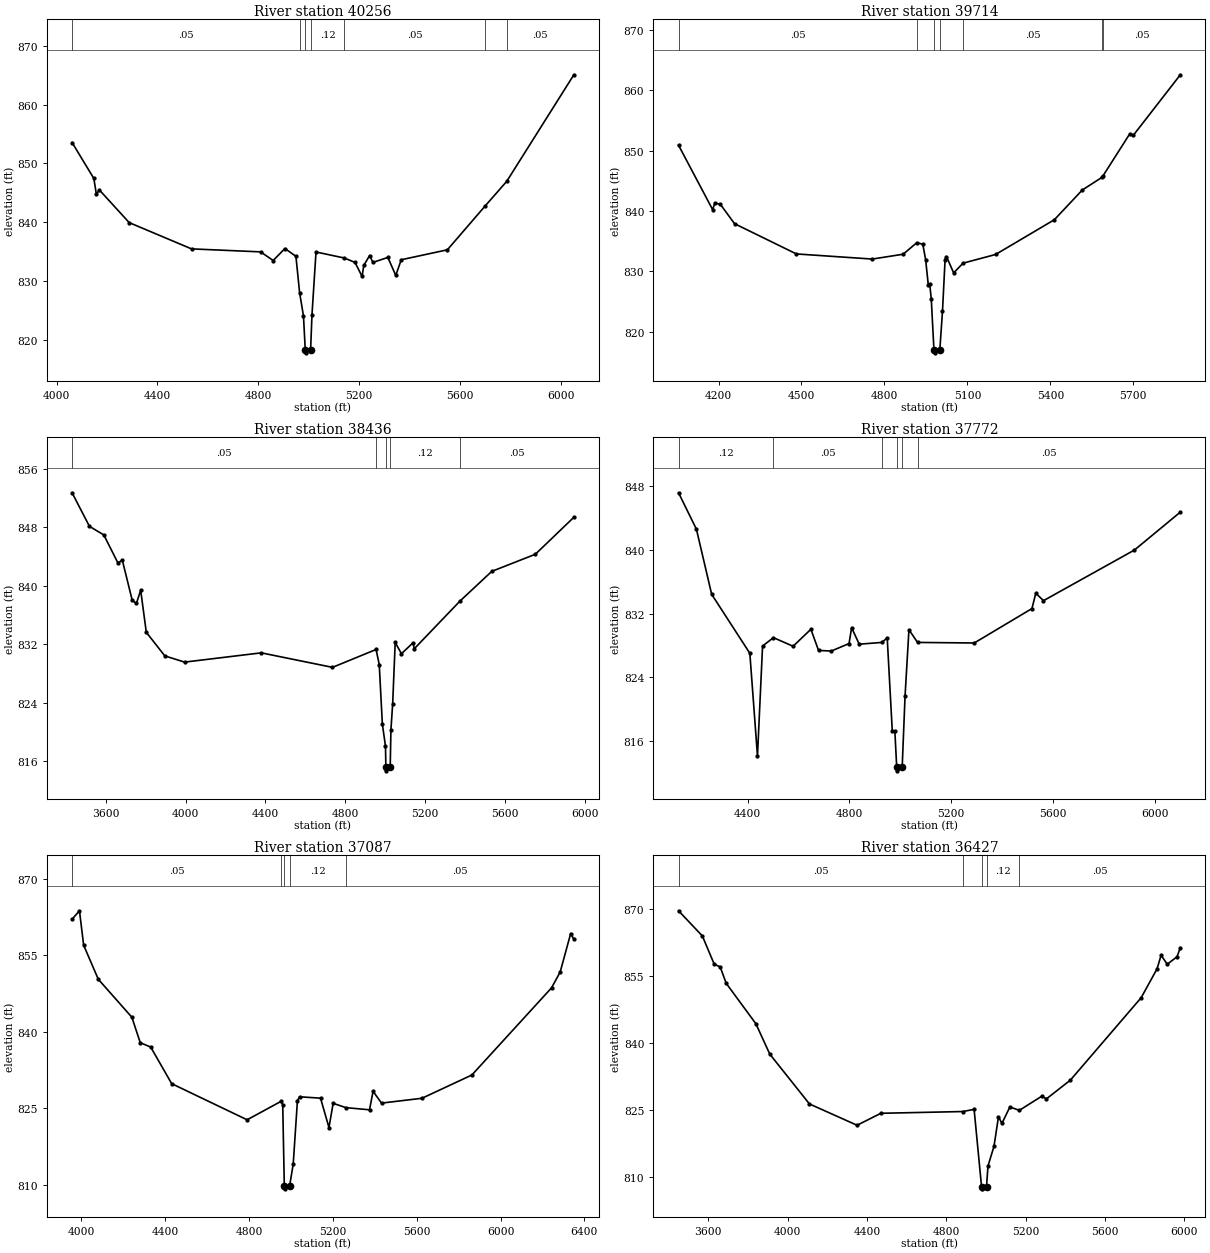
Type RM Length L Ch R = 1,40256,542,542,542
BEGIN DESCRIPTION:
Catlett Creek 31.0
END DESCRIPTION:
XS GIS Cut Line= 3
      2266128.29      7143096.19      2266179.00      7142160.00
      2266701.71      7141247.24
#Sta/Elev= 30
  4061.5  853.57  4147.8  847.45  4157.8  844.77  4170.0  845.48  4288.0  839.93
  4535.1  835.46  4808.8  834.95  4858.9  833.48  4905.3  835.52  4949.0  834.19
  4963.6  828.00  4979.0  824.01  4986.0  818.26  4988.1  817.76  5007.2  818.26
  5012.7  824.27  5028.6  834.93  5141.4  833.90  5183.4  833.15  5211.3  830.76
  5218.0  832.65  5241.1  834.32  5254.5  833.15  5313.5  834.01  5344.8  830.94
  5366.7  833.61  5549.4  835.30  5698.3  842.72  5784.8  846.96  6050.9  865.10
#Mann=7,-1,0
  4061.5    0.05       0  4963.6    0.12       0  4986.0    0.07       0
  5007.2    0.12       0  5141.4    0.05       0  5698.3    0.12       0
  5784.8    0.05       0
Bank Sta=4986,5007.2
Exp/Cntr=0.3,0.1

Type RM Length L Ch R = 1,39714,1278,1278,1278
BEGIN DESCRIPTION:
Catlett Creek 30.0
END DESCRIPTION:
XS GIS Cut Line= 3
      2266472.55      7143089.22      2266640.51      7142159.67
      2266769.64      7141299.51
#Sta/Elev= 30
  4055.4  850.89  4178.8  840.22  4186.7  841.34  4207.0  841.09  4257.8  837.91
  4481.4  832.90  4755.8  832.05  4867.6  832.85  4917.2  834.77  4938.7  834.49
  4948.9  831.94  4958.7  827.68  4963.7  827.88  4969.2  825.49  4978.9  817.03
  4981.0  816.53  5000.2  817.03  5009.8  823.40  5019.2  831.97  5024.2  832.47
  5050.2  829.76  5084.1  831.37  5201.9  832.81  5414.3  838.56  5515.4  843.48
  5586.7  845.58  5590.2  845.82  5687.3  852.80  5699.8  852.53  5869.8  862.55
#Mann=7,-1,0
  4055.4    0.05       0  4917.2    0.12       0  4978.9    0.07       0
  5000.2    0.12       0  5084.1    0.05       0  5586.7    0.12       0
  5590.2    0.05       0
Bank Sta=4978.9,5000.2
Exp/Cntr=0.3,0.1

Type RM Length L Ch R = 1,38436,664,664,664
BEGIN DESCRIPTION:
Catlett Creek 29.0
END DESCRIPTION:
XS GIS Cut Line= 3
      2266763.24      7143647.52      2267712.45      7142470.28
      2268222.36      7141609.29
#Sta/Elev= 30
  3431.5  852.76  3518.5  848.16  3590.5  846.98  3660.9  843.15  3683.2  843.51
  3732.8  838.01  3753.6  837.58  3775.1  839.40  3803.2  833.63  3896.0  830.39
  3995.1  829.54  4379.0  830.81  4735.6  828.82  4953.9  831.27  4969.8  829.21
  4985.4  821.03  5001.0  818.03  5003.0  815.13  5005.2  814.63  5024.7  815.13
  5028.3  820.25  5037.0  823.81  5049.7  832.24  5080.9  830.69  5139.4  832.20
  5145.2  831.37  5374.4  837.92  5533.2  841.98  5751.6  844.33  5944.4  849.40
#Mann=5,-1,0
  3431.5    0.05       0  4953.9    0.12       0  5003.0    0.07       0
  5024.7    0.12       0  5374.4    0.05       0
Bank Sta=5003,5024.7
Exp/Cntr=0.3,0.1

Type RM Length L Ch R = 1,37772,685,685,685
BEGIN DESCRIPTION:
Catlett Creek 28.5
END DESCRIPTION:
XS GIS Cut Line= 3
      2268064.46      7143720.26      2268069.72      7142848.77
      2268206.44      7141756.29
#Sta/Elev= 30
  4128.5  847.13  4198.8  842.57  4258.8  834.41  4408.8  827.03  4438.8  814.17
  4458.8  827.94  4501.6  828.99  4578.8  827.91  4648.8  830.04  4678.8  827.39
  4728.8  827.31  4798.8  828.25  4808.8  830.24  4838.8  828.17  4927.7  828.39
  4948.8  828.95  4968.8  817.27  4978.8  817.32  4986.0  812.81  4988.2  812.31
  5007.7  812.81  5018.9  821.65  5034.2  829.98  5068.2  828.39  5291.0  828.32
  5517.7  832.63  5532.9  834.55  5563.1  833.62  5920.6  839.96  6101.0  844.71
#Mann=6,-1,0
  4128.5    0.12       0  4501.6    0.05       0  4927.7    0.12       0
  4986.0    0.07       0  5007.7    0.12       0  5068.2    0.05       0
Bank Sta=4986,5007.7
Exp/Cntr=0.3,0.1

Type RM Length L Ch R = 1,37087,660,660,660
BEGIN DESCRIPTION:
Catlett Creek 28.0
END DESCRIPTION:
XS GIS Cut Line= 3
      2268673.66      7144055.31      2268654.19      7143010.49
      2268762.19      7141664.82
#Sta/Elev= 30
  3955.0  862.02  3990.3  863.68  4010.3  856.93  4080.3  850.25  4240.4  842.82
  4280.4  837.83  4330.4  836.97  4430.4  829.80  4790.5  822.72  4953.6  826.36
  4960.5  825.61  4968.0  809.69  4970.5  809.19  4993.0  809.69  5010.5  814.04
  5030.6  826.44  5040.6  827.23  5140.9  826.96  5181.1  821.21  5201.1  825.95
  5262.1  825.10  5374.7  824.68  5391.7  828.30  5431.9  825.99  5625.1  826.94
  5863.3  831.50  6243.5  848.58  6284.6  851.67  6334.8  859.22  6350.0  858.10
#Mann=5,-1,0
  3955.0    0.05       0  4953.6    0.12       0  4968.0    0.07       0
  4993.0    0.12       0  5262.1    0.05       0
Bank Sta=4968,4993
Exp/Cntr=0.3,0.1

Type RM Length L Ch R = 1,36427,1096,1096,1096
BEGIN DESCRIPTION:
Catlett Creek 27.0
END DESCRIPTION:
XS GIS Cut Line= 3
      2269029.00      7144210.03      2268979.00      7142660.00
      2268898.25      7141683.27
#Sta/Elev= 30
  3449.5  869.51  3569.6  863.89  3629.6  857.57  3659.6  856.98  3689.7  853.33
  3839.7  844.28  3909.8  837.50  4109.9  826.37  4350.0  821.62  4470.1  824.29
  4883.3  824.68  4940.3  825.17  4977.8  807.92  4980.3  807.42  5002.8  807.92
  5010.4  812.54  5040.5  816.90  5063.3  823.53  5080.6  822.02  5120.7  825.71
  5168.3  824.94  5281.3  828.10  5305.1  827.51  5426.0  831.70  5783.0  850.11
  5863.3  856.57  5883.3  859.57  5914.5  857.58  5963.6  859.23  5980.4  861.27
#Mann=5,-1,0
  3449.5    0.05       0  4883.3    0.12       0  4977.8    0.07       0
  5002.8    0.12       0  5168.3    0.05       0
Bank Sta=4977.8,5002.8
Exp/Cntr=0.3,0.1

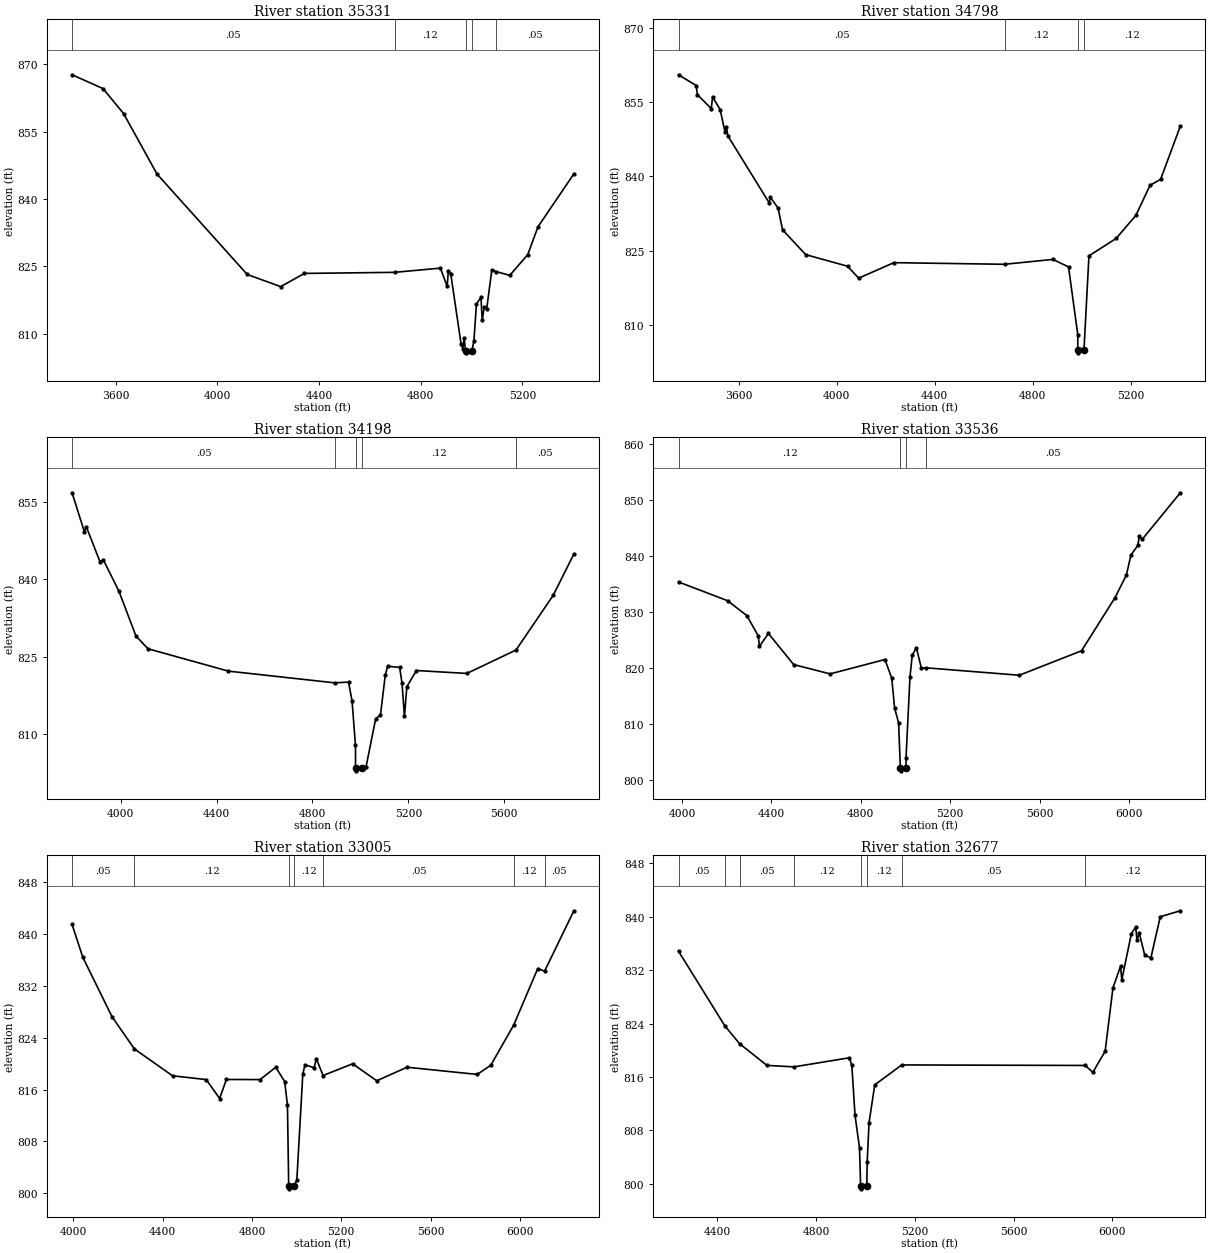
Type RM Length L Ch R = 1,35331,533,533,533
BEGIN DESCRIPTION:
Catlett Creek 26.0
END DESCRIPTION:
XS GIS Cut Line= 3
      2269179.00      7144160.02      2269429.00      7142610.00
      2269479.00      7142209.97
#Sta/Elev= 30
  3429.2  867.67  3550.8  864.60  3631.8  859.03  3763.5  845.54  4118.0  823.19
  4249.7  820.49  4342.9  823.43  4697.6  823.67  4877.7  824.61  4904.0  820.55
  4909.1  824.07  4918.2  823.37  4958.7  807.80  4965.8  806.70  4970.9  808.95
  4976.6  806.24  4979.1  805.74  5001.6  806.24  5009.3  808.36  5019.4  816.64
  5037.0  818.09  5042.1  812.98  5049.6  815.85  5059.7  815.57  5079.9  824.24
  5097.4  823.83  5150.4  822.99  5221.0  827.61  5261.3  833.81  5402.4  845.60
#Mann=5,-1,0
  3429.2    0.05       0  4697.6    0.12       0  4976.6    0.07       0
  5001.6    0.12       0  5097.4    0.05       0
Bank Sta=4976.6,5001.6
Exp/Cntr=0.3,0.1

Type RM Length L Ch R = 1,34798,600,600,600
BEGIN DESCRIPTION:
Catlett Creek 25.0
END DESCRIPTION:
XS GIS Cut Line= 3
      2269329.00      7144010.01      2269879.00      7142460.00
      2269929.00      7142060.01
#Sta/Elev= 30
  3354.4  860.56  3426.3  858.39  3431.6  856.53  3488.0  853.71  3493.3  856.06
  3524.2  853.53  3544.4  848.90  3549.7  850.05  3556.0  848.17  3724.3  834.65
  3729.7  835.73  3760.5  833.60  3778.8  829.19  3873.4  824.16  4044.1  821.82
  4089.5  819.40  4233.2  822.54  4685.1  822.21  4882.4  823.20  4946.0  821.67
  4983.7  807.96  4983.9  804.79  4986.4  804.29  5008.9  804.79  5029.3  823.92
  5140.2  827.43  5220.8  832.11  5278.8  838.21  5321.6  839.38  5402.2  850.17
#Mann=4,-1,0
  3354.4    0.05       0  4685.1    0.12       0  4983.9    0.07       0
  5008.9    0.12       0
Bank Sta=4983.9,5008.9
Exp/Cntr=0.3,0.1

Type RM Length L Ch R = 1,34198,662,662,662
BEGIN DESCRIPTION:
Catlett Creek 24.5
END DESCRIPTION:
XS GIS Cut Line= 3
      2269434.84      7143898.27      2270152.27      7142933.36
      2270132.64      7142043.78
#Sta/Elev= 30
  3797.6  856.89  3849.0  849.27  3857.4  850.23  3913.7  843.48  3928.3  843.80
  3993.0  837.71  4063.9  829.00  4113.9  826.51  4449.7  822.15  4892.6  819.87
  4950.4  820.01  4965.0  816.34  4979.3  807.67  4979.5  803.23  4982.0  802.73
  5004.5  803.23  5023.4  803.52  5063.4  812.86  5083.4  813.60  5103.4  821.33
  5113.4  823.11  5163.4  822.87  5173.4  819.80  5183.4  813.34  5193.4  819.11
  5233.4  822.27  5443.5  821.70  5648.6  826.26  5803.6  836.91  5889.8  844.96
#Mann=5,-1,0
  3797.6    0.05       0  4892.6    0.12       0  4979.5    0.07       0
  5004.5    0.12       0  5648.6    0.05       0
Bank Sta=4979.5,5004.5
Exp/Cntr=0.3,0.1

Type RM Length L Ch R = 1,33536,531,531,531
BEGIN DESCRIPTION:
Catlett Creek 24.0
END DESCRIPTION:
XS GIS Cut Line= 3
      2270393.70      7144304.78      2270594.18      7143309.57
      2270828.63      7142103.14
#Sta/Elev= 30
  3984.8  835.33  4203.9  832.00  4290.4  829.33  4341.2  825.73  4346.7  823.86
  4386.9  826.15  4499.7  820.60  4662.9  818.94  4907.8  821.50  4938.4  818.17
  4951.1  812.85  4969.0  810.23  4976.9  802.15  4979.4  801.65  5001.9  802.15
  5002.3  803.99  5019.9  818.41  5030.1  822.26  5048.5  823.63  5070.9  819.94
  5092.2  820.02  5508.9  818.70  5787.2  823.06  5936.8  832.53  5987.7  836.56
  6008.1  840.13  6038.6  841.85  6045.6  843.46  6059.0  842.96  6229.0  851.24
#Mann=4,-1,0
  3984.8    0.12       0  4976.9    0.07       0  5001.9    0.12       0
  5092.2    0.05       0
Bank Sta=4976.9,5001.9
Exp/Cntr=0.3,0.1

Type RM Length L Ch R = 1,33005,328,328,328
BEGIN DESCRIPTION:
Catlett Creek 23.5
END DESCRIPTION:
XS GIS Cut Line= 3
      2270951.71      7144517.89      2271040.77      7143557.70
      2270827.50      7142293.37
#Sta/Elev= 30
  3995.0  841.49  4043.1  836.42  4173.7  827.25  4273.9  822.27  4444.8  818.12
  4595.5  817.53  4655.7  814.61  4685.8  817.55  4836.5  817.53  4906.8  819.43
  4947.0  817.23  4959.3  813.57  4964.8  801.16  4967.3  800.66  4989.8  801.16
  5001.3  802.04  5028.0  818.40  5038.1  819.82  5078.7  819.36  5088.8  820.75
  5118.7  818.16  5251.1  819.97  5359.1  817.35  5494.5  819.44  5808.8  818.33
  5869.7  819.75  5972.1  825.94  6079.9  834.68  6110.6  834.28  6241.5  843.60
#Mann=7,-1,0
  3995.0    0.05       0  4273.9    0.12       0  4964.8    0.07       0
  4989.8    0.12       0  5118.7    0.05       0  5972.1    0.12       0
  6110.6    0.05       0
Bank Sta=4964.8,4989.8
Exp/Cntr=0.3,0.1

Type RM Length L Ch R = 1,32677,749,749,749
BEGIN DESCRIPTION:
Catlett Creek 23.0
END DESCRIPTION:
XS GIS Cut Line= 3
      2272047.83      7143767.24      2271315.61      7143573.54
      2270883.15      7142373.48
#Sta/Elev= 30
  4242.6  834.83  4430.1  823.66  4490.2  820.97  4600.8  817.73  4710.4  817.51
  4934.4  818.87  4944.8  817.72  4957.7  810.24  4975.8  805.37  4980.3  799.74
  4982.8  799.24  5005.3  799.74  5006.9  803.24  5014.4  809.14  5037.6  814.82
  5147.0  817.80  5890.3  817.72  5921.2  816.69  5971.0  819.85  6002.6  829.33
  6033.3  832.57  6038.6  830.57  6077.3  837.48  6094.7  838.43  6100.0  836.53
  6109.2  837.55  6130.7  834.34  6156.1  833.80  6194.3  840.00  6275.6  840.89
#Mann=8,-1,0
  4242.6    0.05       0  4430.1    0.12       0  4490.2    0.05       0
  4710.4    0.12       0  4980.3    0.07       0  5005.3    0.12       0
  5147.0    0.05       0  5890.3    0.12       0
Bank Sta=4980.3,5005.3
Exp/Cntr=0.3,0.1

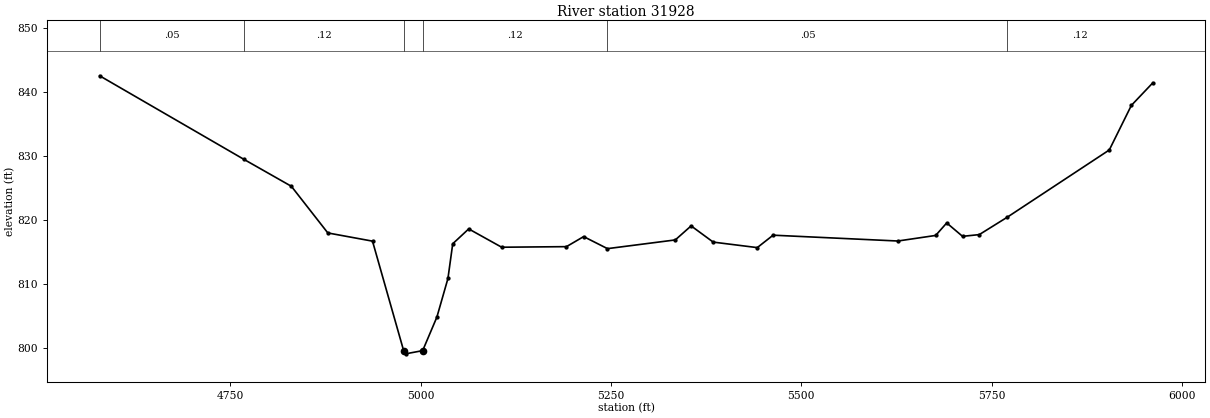
Type RM Length L Ch R = 1,31928,409,409,409
BEGIN DESCRIPTION:
Catlett Creek 22.0
END DESCRIPTION:
XS GIS Cut Line= 3
      2272128.99      7143259.99      2271738.81      7143099.49
      2270978.98      7142509.98
#Sta/Elev= 30
  4578.1  842.55  4767.3  829.53  4830.0  825.30  4877.9  818.02  4936.6  816.74
  4977.5  799.65  4980.0  799.15  5002.5  799.65  5021.2  804.89  5035.7  810.91
  5042.0  816.33  5063.0  818.65  5106.3  815.79  5191.4  815.88  5214.0  817.45
  5245.3  815.57  5334.4  816.93  5355.2  819.12  5384.2  816.59  5442.1  815.73
  5462.9  817.67  5626.8  816.76  5676.5  817.63  5691.0  819.58  5711.8  817.49
  5733.8  817.76  5770.6  820.48  5904.6  830.97  5933.6  837.93  5961.7  841.44
#Mann=6,-1,0
  4578.1    0.05       0  4767.3    0.12       0  4977.5    0.07       0
  5002.5    0.12       0  5245.3    0.05       0  5770.6    0.12       0
Bank Sta=4977.5,5002.5
Exp/Cntr=0.3,0.1