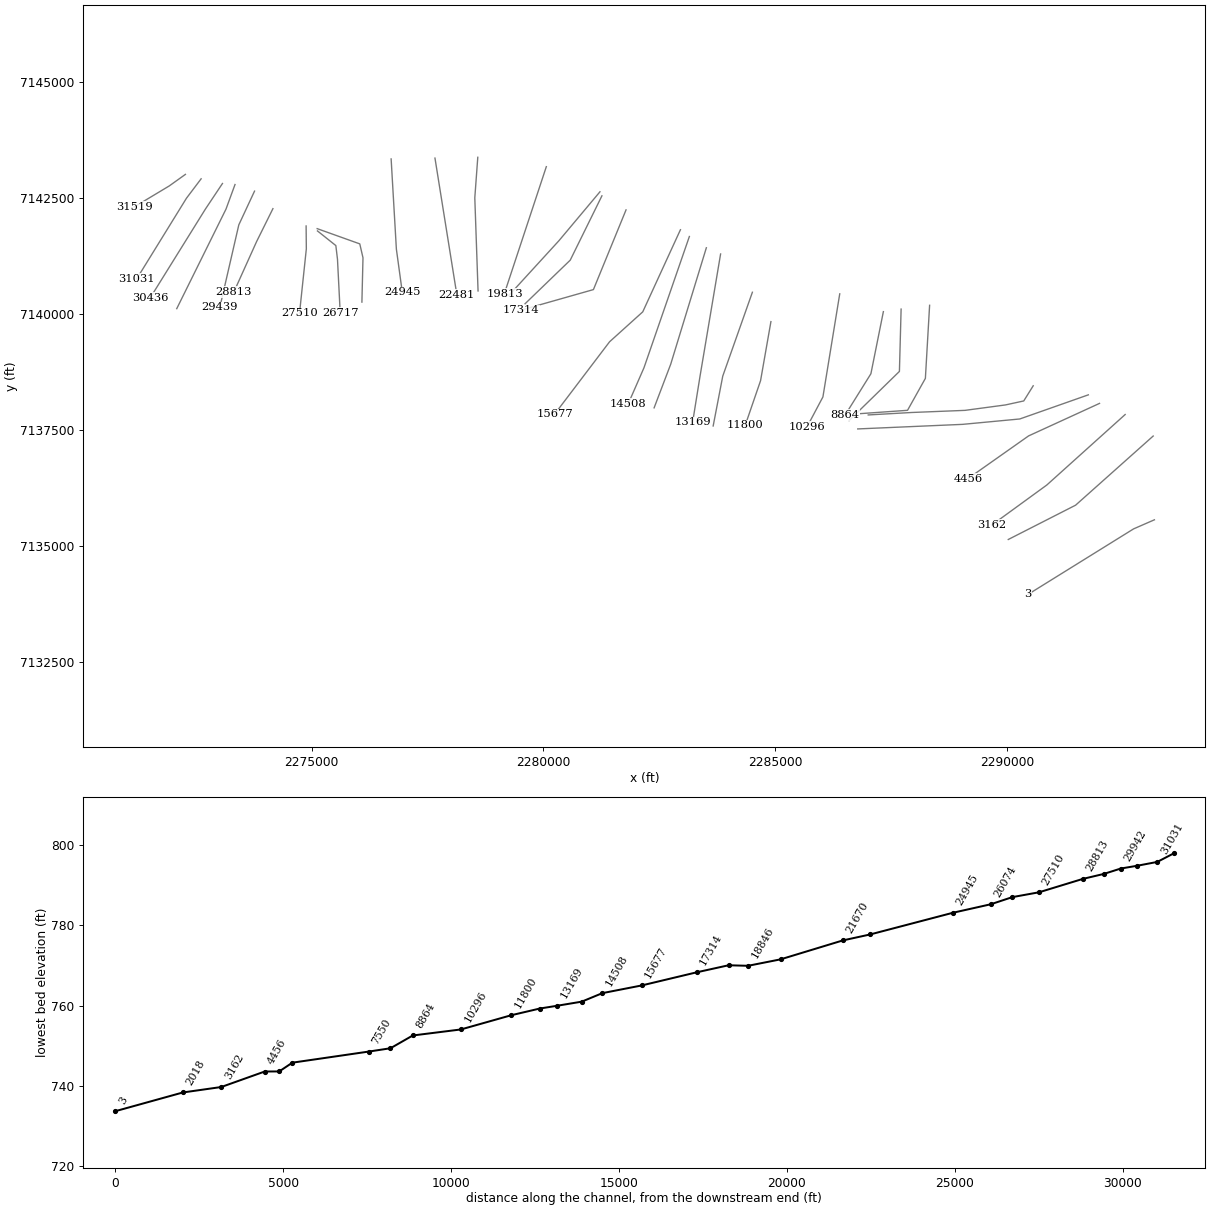
HEC-RAS study Catlett Creek.prj: Catlett Creek Base Level Engineering

--- Catlett Creek.g01 (geometry) --- (continued)

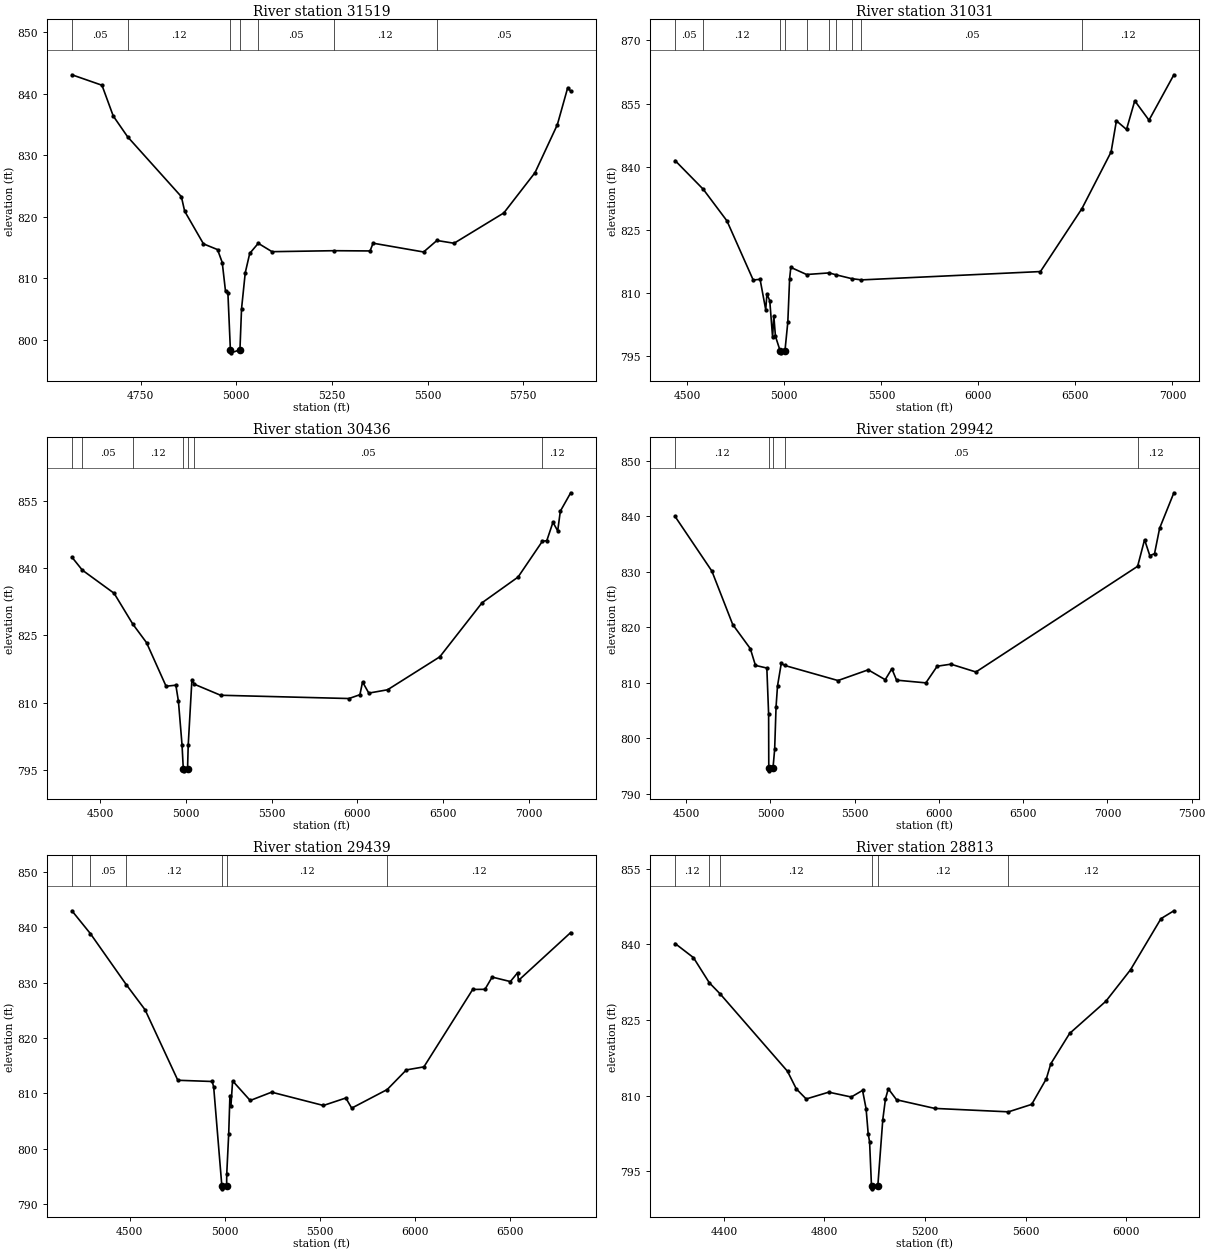
Type RM Length L Ch R = 1,31519,488,488,488
BEGIN DESCRIPTION:
Catlett Creek 21.0
END DESCRIPTION:
XS GIS Cut Line= 3
      2272278.97      7143009.98      2271929.00      7142760.00
      2271179.01      7142310.01
#Sta/Elev= 30
  4569.9  843.08  4648.5  841.38  4678.0  836.38  4715.6  833.00  4856.2  823.27
  4864.8  820.91  4914.0  815.60  4950.8  814.67  4963.1  812.57  4971.7  807.87
  4977.9  807.65  4984.4  798.39  4986.9  797.89  5009.4  798.39  5013.6  805.06
  5023.3  810.91  5035.0  814.05  5057.3  815.69  5093.3  814.33  5254.9  814.49
  5349.8  814.45  5357.6  815.71  5489.8  814.28  5524.6  816.15  5569.5  815.70
  5699.7  820.63  5781.3  827.18  5839.6  834.96  5866.8  840.99  5874.6  840.39
#Mann=7,-1,0
  4569.9    0.05       0  4715.6    0.12       0  4984.4    0.07       0
  5009.4    0.12       0  5057.3    0.05       0  5254.9    0.12       0
  5524.6    0.05       0
Bank Sta=4984.4,5009.4
Exp/Cntr=0.3,0.1

Type RM Length L Ch R = 1,31031,595,595,595
BEGIN DESCRIPTION:
Catlett Creek 20.0
END DESCRIPTION:
XS GIS Cut Line= 3
      2272617.88      7142914.59      2272301.82      7142496.06
      2271227.40      7140754.71
#Sta/Elev= 30
  4436.8  841.45  4582.0  834.63  4704.1  827.12  4839.4  813.07  4874.8  813.24
  4903.9  806.02  4910.2  809.74  4924.7  808.16  4939.3  799.49  4945.6  804.61
  4953.9  799.72  4978.1  796.27  4980.6  795.77  5003.1  796.27  5017.8  803.09
  5027.1  813.42  5033.2  816.07  5114.4  814.38  5231.1  814.76  5265.1  814.32
  5347.8  813.39  5397.2  813.10  6319.7  815.08  6533.7  830.05  6683.9  843.50
  6711.2  850.89  6763.3  848.84  6805.8  855.65  6879.2  851.04  7007.4  861.83
#Mann=10,-1,0
  4436.8    0.05       0  4582.0    0.12       0  4978.1    0.07       0
  5003.1    0.12       0  5114.4    0.05       0  5231.1    0.12       0
  5265.1    0.05       0  5347.8    0.12       0  5397.2    0.05       0
  6533.7    0.12       0
Bank Sta=4978.1,5003.1
Exp/Cntr=0.3,0.1

Type RM Length L Ch R = 1,30436,494,494,494
BEGIN DESCRIPTION:
Catlett Creek 19.0
END DESCRIPTION:
XS GIS Cut Line= 3
      2273078.25      7142813.50      2272708.79      7142259.49
      2271523.00      7140351.91
#Sta/Elev= 30
  4334.1  842.43  4394.8  839.54  4580.4  834.38  4689.6  827.51  4769.7  823.38
  4883.8  813.67  4940.9  813.90  4955.9  810.32  4977.0  800.59  4984.2  795.32
  4986.7  794.82  5009.2  795.32  5013.1  800.58  5034.7  815.14  5048.5  814.12
  5202.0  811.66  5951.7  810.93  6015.4  811.78  6030.8  814.62  6067.4  812.14
  6176.9  812.88  6481.8  820.22  6728.6  832.27  6938.7  837.99  7080.8  845.98
  7106.4  846.09  7142.4  850.19  7170.1  848.29  7185.5  852.67  7246.1  856.77
#Mann=7,-1,0
  4334.1    0.12       0  4394.8    0.05       0  4689.6    0.12       0
  4984.2    0.07       0  5009.2    0.12       0  5048.5    0.05       0
  7080.8    0.12       0
Bank Sta=4984.2,5009.2
Exp/Cntr=0.3,0.1

Type RM Length L Ch R = 1,29942,503,503,503
BEGIN DESCRIPTION:
Catlett Creek 18.0
END DESCRIPTION:
XS GIS Cut Line= 3
      2273348.68      7142791.20      2273154.05      7142260.24
      2272092.04      7140114.14
#Sta/Elev= 30
  4434.5  839.95  4652.8  830.11  4776.6  820.48  4880.9  816.14  4911.4  813.12
  4979.0  812.64  4989.6  804.32  4990.5  794.62  4993.0  794.12  5015.5  794.62
  5025.4  797.99  5033.7  805.66  5042.3  809.41  5064.7  813.49  5084.8  813.11
  5401.2  810.39  5580.5  812.32  5681.5  810.54  5720.8  812.51  5748.8  810.46
  5922.7  809.97  5989.9  812.97  6071.4  813.34  6219.8  811.93  7179.3  830.97
  7220.6  835.76  7251.7  832.89  7279.7  833.25  7309.9  837.83  7394.5  844.22
#Mann=5,-1,0
  4434.5    0.12       0  4990.5    0.07       0  5015.5    0.12       0
  5084.8    0.05       0  7179.3    0.12       0
Bank Sta=4990.5,5015.5
Exp/Cntr=0.3,0.1

Type RM Length L Ch R = 1,29439,626,626,626
BEGIN DESCRIPTION:
Catlett Creek 17.0
END DESCRIPTION:
XS GIS Cut Line= 3
      2273769.64      7142648.51      2273430.43      7141920.45
      2273022.35      7140148.02
#Sta/Elev= 30
  4196.8  842.98  4294.3  838.84  4482.0  829.67  4581.3  825.11  4753.5  812.38
  4934.3  812.16  4942.0  811.16  4985.0  793.28  4987.5  792.78  5010.0  793.28
  5010.7  795.48  5021.0  802.74  5027.4  809.62  5032.5  807.67  5041.5  812.27
  5133.9  808.73  5246.6  810.23  5518.8  807.83  5636.7  809.18  5667.5  807.35
  5854.3  810.71  5954.8  814.25  6047.1  814.80  6303.7  828.78  6368.1  828.80
  6405.7  831.01  6501.6  830.20  6539.3  831.78  6544.4  830.41  6818.8  839.05
#Mann=6,-1,0
  4196.8    0.12       0  4294.3    0.05       0  4482.0    0.12       0
  4985.0   0.033       0  5010.0    0.12       0  5854.3    0.12       0
Bank Sta=4985,5010
Exp/Cntr=0.3,0.1

Type RM Length L Ch R = 1,28813,1303,1303,1303
BEGIN DESCRIPTION:
Catlett Creek 16.5
END DESCRIPTION:
XS GIS Cut Line= 3
      2274166.40      7142270.70      2273813.58      7141559.06
      2273324.63      7140474.37
#Sta/Elev= 30
  4205.7  840.19  4278.8  837.39  4341.6  832.42  4386.0  830.14  4652.9  814.85
  4687.9  811.36  4727.2  809.36  4816.9  810.71  4906.5  809.75  4951.4  811.06
  4965.5  807.42  4973.8  802.47  4979.4  800.85  4987.0  792.04  4989.5  791.54
  5012.0  792.04  5031.9  805.26  5042.5  809.36  5053.8  811.39  5086.7  809.20
  5238.6  807.49  5531.8  806.81  5624.2  808.29  5682.4  813.36  5700.1  816.33
  5775.0  822.35  5919.3  828.74  6017.3  834.98  6138.5  845.12  6189.8  846.68
#Mann=6,-1,0
  4205.7    0.12       0  4341.6    0.05       0  4386.0    0.12       0
  4987.0   0.033       0  5012.0    0.12       0  5531.8    0.12       0
Bank Sta=4987,5012
Exp/Cntr=0.3,0.1

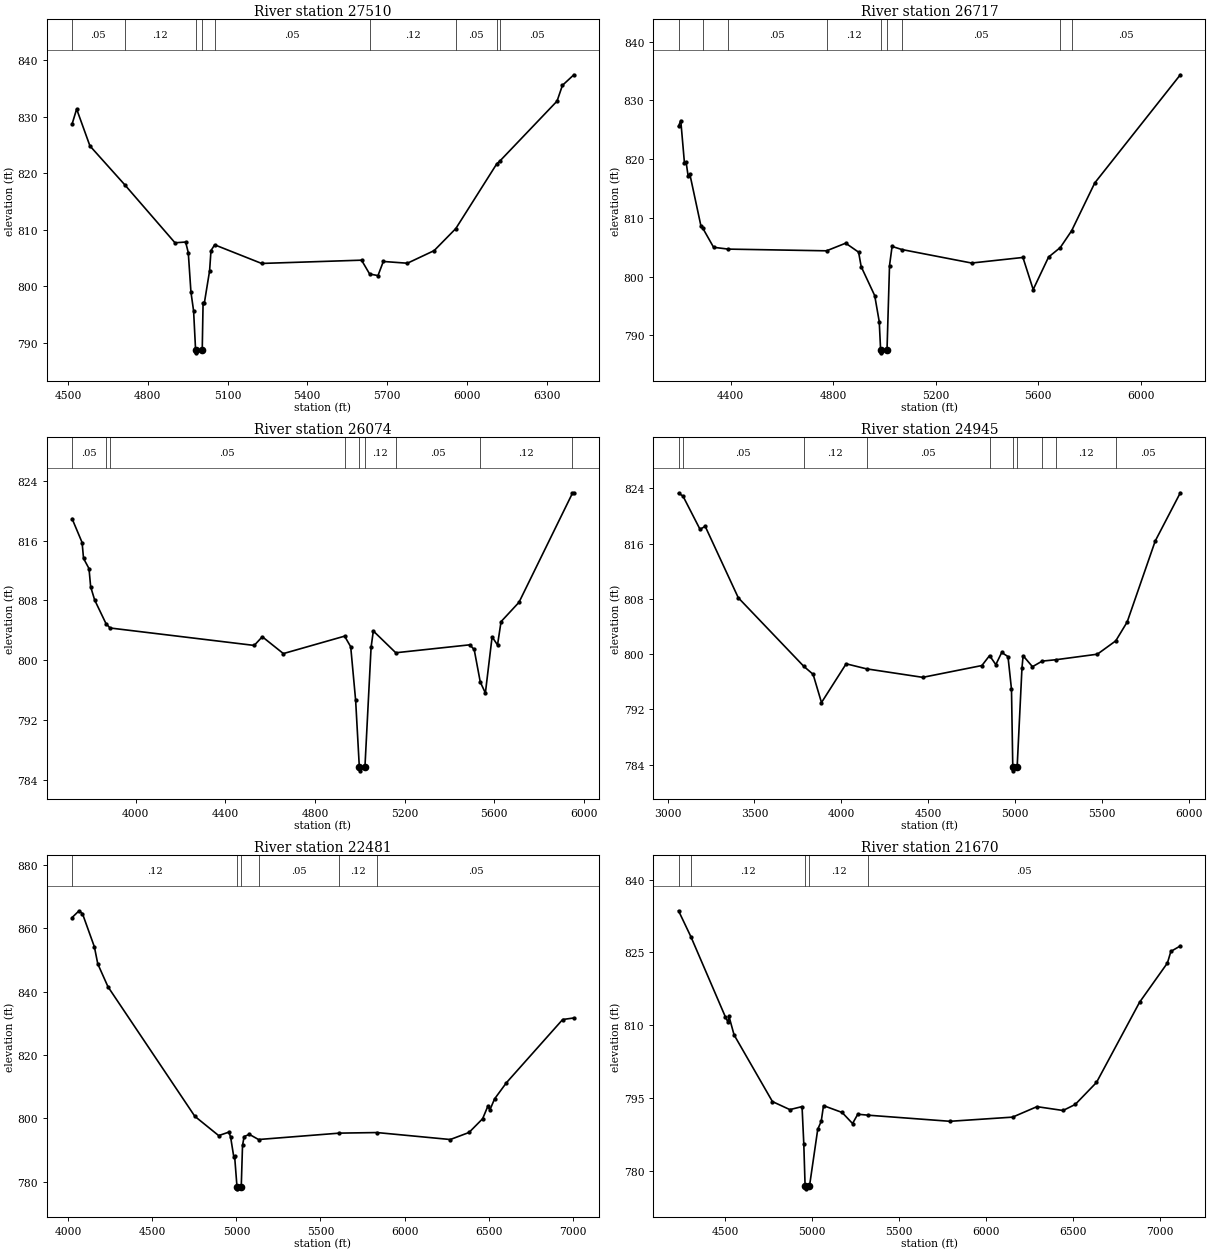
Type RM Length L Ch R = 1,27510,793,793,793
BEGIN DESCRIPTION:
Catlett Creek 16.3
END DESCRIPTION:
XS GIS Cut Line= 3
      2274882.38      7141897.23      2274887.09      7141403.80
      2274740.29      7140017.20
#Sta/Elev= 30
  4515.0  828.71  4532.2  831.38  4582.2  824.85  4712.5  818.01  4902.2  807.70
  4942.2  807.83  4952.2  805.96  4962.2  798.98  4972.2  795.63  4979.7  788.71
  4982.2  788.21  5004.7  788.71  5007.9  797.10  5012.9  797.10  5032.4  802.74
  5037.6  806.31  5051.4  807.34  5228.1  804.04  5604.1  804.62  5634.5  802.17
  5665.9  801.89  5686.0  804.39  5776.5  804.08  5877.1  806.31  5958.7  810.22
  6112.6  821.67  6123.5  822.13  6339.6  832.79  6359.8  835.58  6402.8  837.45
#Mann=9,-1,0
  4515.0    0.05       0  4712.5    0.12       0  4979.7    0.07       0
  5004.7    0.12       0  5051.4    0.05       0  5634.5    0.12       0
  5958.7    0.05       0  6112.6    0.12       0  6123.5    0.05       0
Bank Sta=4979.7,5004.7
Exp/Cntr=0.3,0.1

Type RM Length L Ch R = 1,26717,643,643,643
BEGIN DESCRIPTION:
Catlett Creek 16.2
END DESCRIPTION:
XS GIS Cut Line= 4
      2275127.05      7141790.27      2275523.62      7141474.44
      2275558.84      7141179.60      2275617.37      7140026.49
#Sta/Elev= 30
  4196.1  825.59  4204.8  826.56  4219.2  819.32  4225.6  819.48  4233.6  817.11
  4240.0  817.48  4283.3  808.66  4290.8  808.23  4332.9  804.98  4390.0  804.67
  4773.7  804.38  4848.5  805.68  4898.9  804.15  4909.0  801.68  4961.8  796.75
  4979.5  792.31  4984.8  787.51  4987.3  787.01  5009.8  787.51  5019.6  801.87
  5029.6  805.13  5067.5  804.60  5340.0  802.30  5540.3  803.25  5580.3  797.79
  5640.4  803.32  5686.0  804.93  5730.3  807.79  5820.7  815.94  6154.6  834.35
#Mann=9,-1,0
  4196.1    0.05       0  4290.8    0.12       0  4390.0    0.05       0
  4773.7    0.12       0  4984.8    0.07       0  5009.8    0.12       0
  5067.5    0.05       0  5686.0    0.12       0  5730.3    0.05       0
Bank Sta=4984.8,5009.8
Exp/Cntr=0.3,0.1

Type RM Length L Ch R = 1,26074,1129,1129,1129
BEGIN DESCRIPTION:
Catlett Creek 16.1
END DESCRIPTION:
XS GIS Cut Line= 4
      2275120.81      7141839.73      2276039.85      7141510.99
      2276108.95      7141210.61      2276085.68      7140255.09
#Sta/Elev= 30
  3715.7  818.93  3760.5  815.74  3766.9  813.62  3791.3  812.26  3798.7  809.82
  3816.7  808.05  3866.9  804.92  3885.2  804.32  4528.8  801.99  4564.9  803.15
  4659.0  800.90  4932.4  803.23  4959.6  801.81  4981.6  794.65  4998.1  785.73
  5000.6  785.23  5023.1  785.73  5050.6  801.75  5060.6  803.92  5160.8  801.01
  5490.8  802.07  5510.8  801.45  5538.0  797.10  5560.8  795.63  5590.8  803.14
  5615.0  802.05  5630.8  805.17  5710.8  807.75  5949.3  822.32  5955.8  822.39
#Mann=9,-1,0
  3715.7    0.05       0  3866.9    0.12       0  3885.2    0.05       0
  4932.4    0.12       0  4998.1    0.07       0  5023.1    0.12       0
  5160.8    0.05       0  5538.0    0.12       0  5949.3    0.05       0
Bank Sta=4998.1,5023.1
Exp/Cntr=0.3,0.1

Type RM Length L Ch R = 1,24945,2464,2464,2464
BEGIN DESCRIPTION:
Catlett Creek 16.0
END DESCRIPTION:
XS GIS Cut Line= 3
      2276716.03      7143343.32      2276829.28      7141396.42
      2276956.69      7140466.80
#Sta/Elev= 30
  3063.0  823.27  3088.2  822.89  3186.5  818.07  3216.6  818.49  3406.9  808.16
  3783.8  798.24  3837.6  797.08  3885.9  792.99  4027.9  798.60  4145.3  797.87
  4468.7  796.64  4809.3  798.35  4853.5  799.79  4889.4  798.48  4923.4  800.24
  4959.5  799.64  4979.6  794.92  4987.1  783.61  4989.6  783.11  5012.1  783.61
  5039.9  797.98  5046.5  799.77  5100.4  798.18  5156.3  798.99  5235.5  799.19
  5473.9  799.99  5579.8  801.92  5645.5  804.65  5807.0  816.37  5951.5  823.35
#Mann=10,-1,0
  3063.0    0.12       0  3088.2    0.05       0  3783.8    0.12       0
  4145.3    0.05       0  4853.5    0.12       0  4987.1    0.07       0
  5012.1    0.12       0  5156.3    0.05       0  5235.5    0.12       0
  5579.8    0.05       0
Bank Sta=4987.1,5012.1
Exp/Cntr=0.3,0.1

Type RM Length L Ch R = 1,22481,811,811,811
BEGIN DESCRIPTION:
Mapping XS 02273d79
END DESCRIPTION:
XS GIS Cut Line= 2
      2277661.40      7143361.05      2278133.36      7140414.21
#Sta/Elev= 30
  4022.7  863.41  4064.3  865.55  4084.5  864.65  4155.4  854.16  4175.7  848.76
  4236.4  841.53  4752.9  800.62  4894.7  794.53  4955.5  795.63  4965.6  794.08
  4984.2  787.90  4989.3  788.15  5003.8  778.21  5006.3  777.71  5028.8  778.21
  5036.5  791.47  5046.2  794.23  5077.0  794.92  5131.7  793.29  5613.0  795.31
  5836.0  795.49  6272.1  793.29  6383.7  795.52  6464.5  799.86  6494.9  803.73
  6507.7  802.64  6535.4  806.11  6606.3  811.25  6940.5  831.20  7007.1  831.69
#Mann=6,-1,0
  4022.7    0.12       0  5003.8    0.07       0  5028.8    0.12       0
  5131.7    0.05       0  5613.0    0.12       0  5836.0    0.05       0
Bank Sta=5003.8,5028.8
Exp/Cntr=0.3,0.1

Type RM Length L Ch R = 1,21670,1857,1857,1857
BEGIN DESCRIPTION:
Mapping XS 04824767
END DESCRIPTION:
XS GIS Cut Line= 3
      2278584.95      7143378.60      2278520.66      7142503.56
      2278590.97      7140495.69
#Sta/Elev= 30
  4230.3  833.58  4301.4  828.23  4499.6  811.71  4515.5  810.57  4520.5  811.81
  4549.8  807.98  4770.4  794.23  4870.6  792.57  4940.8  793.19  4950.8  785.55
  4958.4  776.73  4960.9  776.23  4983.4  776.73  5031.1  788.52  5051.1  790.15
  5064.2  793.39  5171.3  791.98  5231.3  789.70  5261.4  791.62  5321.1  791.42
  5791.7  790.16  6151.9  791.02  6292.0  793.18  6442.1  792.39  6512.1  793.63
  6634.5  798.17  6882.3  814.71  7042.4  822.80  7062.5  825.20  7116.8  826.33
#Mann=5,-1,0
  4230.3    0.05       0  4301.4    0.12       0  4958.4    0.07       0
  4983.4    0.12       0  5321.1    0.05       0
Bank Sta=4958.4,4983.4
Exp/Cntr=0.3,0.1

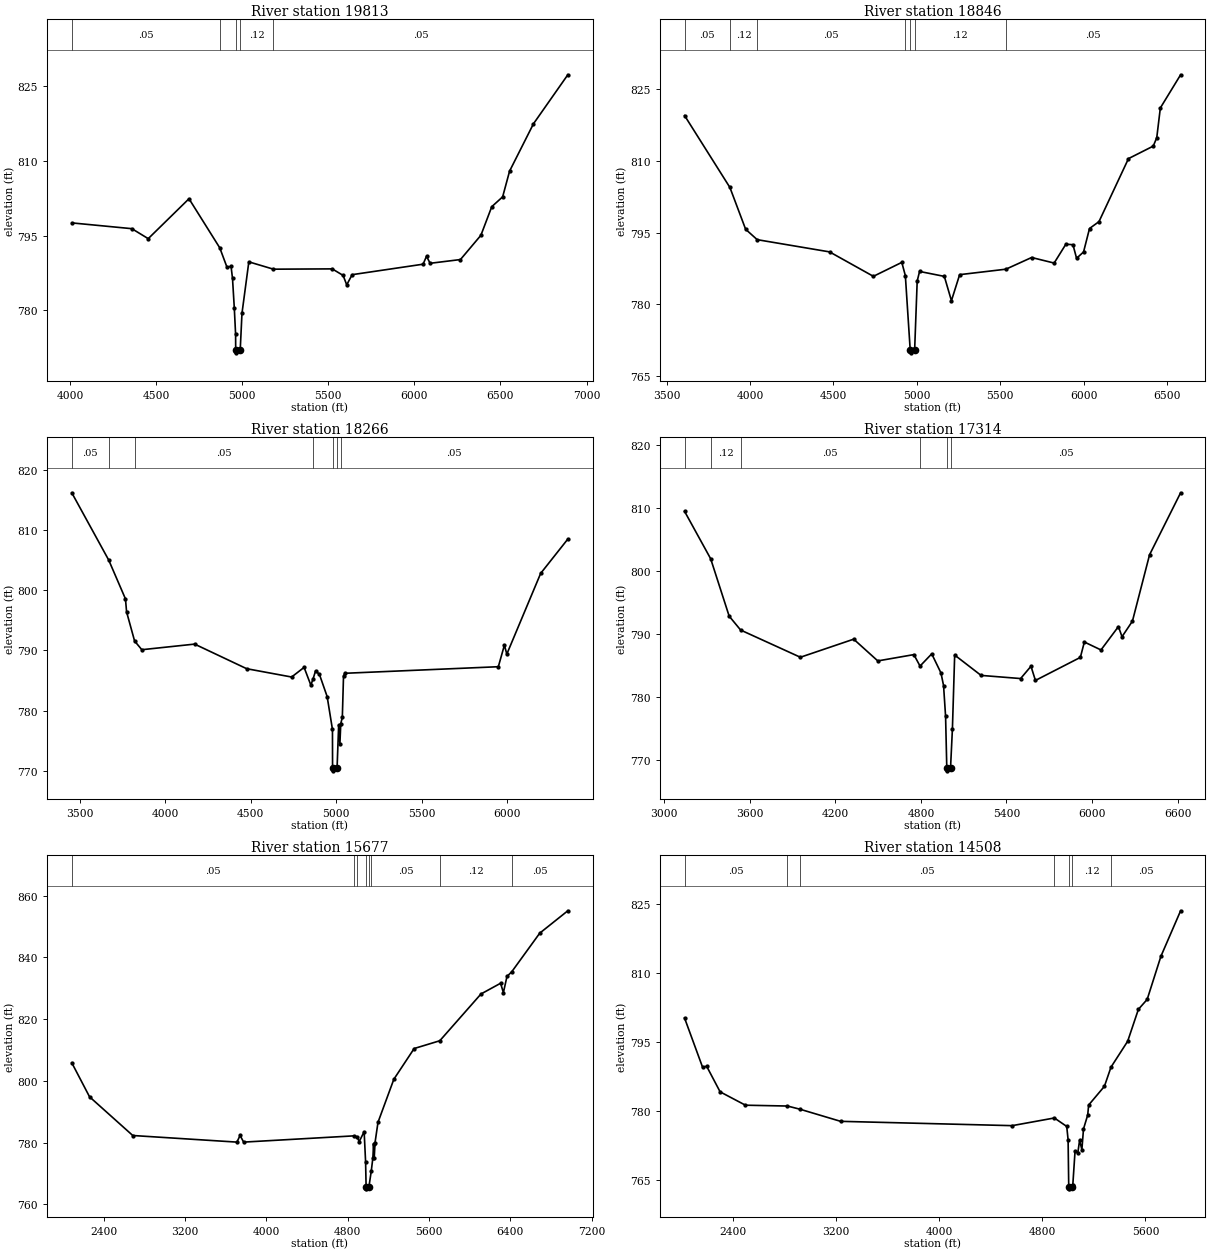
Type RM Length L Ch R = 1,19813,967,967,967
BEGIN DESCRIPTION:
Mapping XS e4dff0af
END DESCRIPTION:
XS GIS Cut Line= 2
      2280063.42      7143176.50      2279158.88      7140440.56
#Sta/Elev= 30
  4009.8  797.56  4358.7  796.40  4453.9  794.40  4690.7  802.40  4869.6  792.55
  4911.9  788.63  4935.0  788.87  4943.5  786.43  4954.0  780.44  4961.5  775.21
  4962.0  772.01  4964.6  771.51  4988.2  772.01  4998.5  779.42  5038.3  789.75
  5181.2  788.28  5522.8  788.34  5586.0  787.03  5607.0  785.14  5638.6  787.18
  6050.7  789.28  6070.5  790.87  6091.5  789.46  6267.6  790.21  6386.4  795.07
  6449.6  800.81  6512.8  802.78  6553.1  807.94  6691.9  817.43  6891.4  827.25
#Mann=5,-1,0
  4009.8    0.05       0  4869.6    0.12       0  4962.0    0.07       0
  4988.2    0.12       0  5181.2    0.05       0
Bank Sta=4962,4988.2
Exp/Cntr=0.3,0.1

Type RM Length L Ch R = 1,18846,580,580,580
BEGIN DESCRIPTION:
Catlett Creek 9.0
END DESCRIPTION:
XS GIS Cut Line= 3
      2281220.06      7142634.65      2280333.51      7141577.43
      2279256.55      7140400.30
#Sta/Elev= 30
  3606.9  819.41  3878.8  804.41  3973.1  795.69  4042.5  793.52  4476.6  790.97
  4739.4  785.87  4909.8  788.78  4931.1  786.02  4960.4  770.41  4963.0  769.91
  4986.7  770.41  5002.1  784.88  5016.3  786.89  5164.9  785.86  5207.5  780.79
  5256.8  786.22  5534.1  787.36  5688.5  789.80  5823.5  788.64  5893.8  792.57
  5936.4  792.47  5958.0  789.64  5999.9  790.95  6035.7  795.85  6092.4  797.28
  6269.4  810.43  6418.0  813.04  6439.0  814.79  6460.5  821.00  6582.1  827.92
#Mann=7,-1,0
  3606.9    0.05       0  3878.8    0.12       0  4042.5    0.05       0
  4931.1    0.12       0  4960.4    0.07       0  4986.7    0.12       0
  5534.1    0.05       0
Bank Sta=4960.4,4986.7
Exp/Cntr=0.3,0.1

Type RM Length L Ch R = 1,18266,952,952,952
BEGIN DESCRIPTION:
Catlett Creek 8.0
END DESCRIPTION:
XS GIS Cut Line= 3
      2281262.37      7142547.42      2280579.00      7141160.00
      2279604.77      7140219.81
#Sta/Elev= 30
  3453.3  816.16  3669.4  804.99  3767.3  798.55  3773.7  796.41  3820.6  791.57
  3862.9  790.13  4171.6  791.06  4476.0  786.98  4738.8  785.60  4811.7  787.20
  4851.1  784.26  4863.3  785.21  4879.1  786.64  4901.6  786.02  4946.5  782.36
  4977.6  776.90  4978.2  770.54  4980.9  770.04  5004.6  770.54  5013.9  777.66
  5021.1  774.55  5026.2  777.88  5035.3  778.91  5042.2  785.73  5049.4  786.22
  5947.5  787.31  5983.0  790.89  5997.1  789.40  6195.0  802.79  6353.8  808.48
#Mann=7,-1,0
  3453.3    0.05       0  3669.4    0.12       0  3820.6    0.05       0
  4863.3    0.12       0  4978.2    0.07       0  5004.6    0.12       0
  5026.2    0.05       0
Bank Sta=4978.2,5004.6
Exp/Cntr=0.3,0.1

Type RM Length L Ch R = 1,17314,1637,1637,1637
BEGIN DESCRIPTION:
Catlett Creek 6.0
END DESCRIPTION:
XS GIS Cut Line= 3
      2281782.56      7142244.00      2281079.13      7140525.06
      2279519.59      7140082.58
#Sta/Elev= 30
  3142.7  809.47  3325.6  801.95  3455.3  792.84  3535.7  790.63  3954.7  786.31
  4328.6  789.18  4497.6  785.73  4750.5  786.73  4793.8  784.91  4875.8  786.85
  4940.6  783.82  4958.8  781.82  4973.0  776.92  4981.4  768.78  4984.0  768.28
  5007.8  768.78  5020.9  774.95  5036.7  786.66  5221.8  783.43  5499.1  782.93
  5571.8  784.88  5603.0  782.63  5918.1  786.29  5946.1  788.73  6062.7  787.47
  6185.1  791.18  6210.2  789.57  6283.2  792.04  6403.4  802.58  6621.1  812.42
#Mann=6,-1,0
  3142.7    0.05       0  3325.6    0.12       0  3535.7    0.05       0
  4793.8    0.12       0  4981.4   0.033       0  5007.8    0.05       0
Bank Sta=4981.4,5007.8
Exp/Cntr=0.3,0.1

Type RM Length L Ch R = 1,15677,1169,1169,1169
BEGIN DESCRIPTION:
Catlett Creek 4.0
END DESCRIPTION:
XS GIS Cut Line= 4
      2282955.91      7141816.20      2282143.42      7140045.39
      2281427.41      7139399.34      2280238.36      7137833.42
#Sta/Elev= 30
  2087.3  805.85  2262.2  794.82  2687.1  782.29  3711.5  780.15  3742.7  782.31
  3777.5  780.15  4865.1  782.18  4895.7  781.86  4913.6  780.26  4962.9  783.54
  4977.1  773.83  4982.3  765.51  4985.0  765.01  5009.2  765.51  5033.0  770.79
  5049.2  775.16  5055.5  779.67  5062.0  774.98  5070.0  779.98  5099.1  786.56
  5255.1  800.52  5454.8  810.47  5707.0  812.99  6112.0  828.14  6305.0  831.62
  6332.5  828.58  6367.8  833.82  6415.2  835.36  6690.1  847.85  6966.2  855.10
#Mann=8,-1,0
  2087.3    0.05       0  4865.1    0.12       0  4895.7    0.05       0
  4982.3    0.07       0  5009.2    0.05       0  5033.0    0.05       0
  5707.0    0.12       0  6415.2    0.05       0
Bank Sta=4982.3,5009.2
Exp/Cntr=0.3,0.1

Type RM Length L Ch R = 1,14508,614,614,614
BEGIN DESCRIPTION:
Catlett Creek 3.0
END DESCRIPTION:
XS GIS Cut Line= 3
      2283148.64      7141670.41      2282170.04      7138840.23
      2281829.00      7138060.00
#Sta/Elev= 30
  2026.3  800.26  2166.2  789.54  2197.4  789.78  2301.8  784.21  2498.5  781.30
  2824.2  781.12  2921.8  780.42  3236.1  777.79  4566.2  776.85  4893.5  778.52
  4989.4  776.68  5000.0  773.80  5004.9  763.60  5007.6  763.10  5031.9  763.60
  5036.7  764.03  5053.9  771.30  5075.7  770.97  5089.0  773.66  5106.9  771.64
  5119.4  776.13  5152.1  779.17  5159.2  781.33  5281.6  785.41  5332.5  789.58
  5461.8  795.21  5545.0  802.16  5613.1  804.32  5719.6  813.70  5872.4  823.61
#Mann=7,-1,0
  2026.3    0.05       0  2824.2    0.12       0  2921.8    0.05       0
  4893.5    0.12       0  5004.9    0.07       0  5031.9    0.12       0
  5332.5    0.05       0
Bank Sta=5004.9,5031.9
Exp/Cntr=0.3,0.1

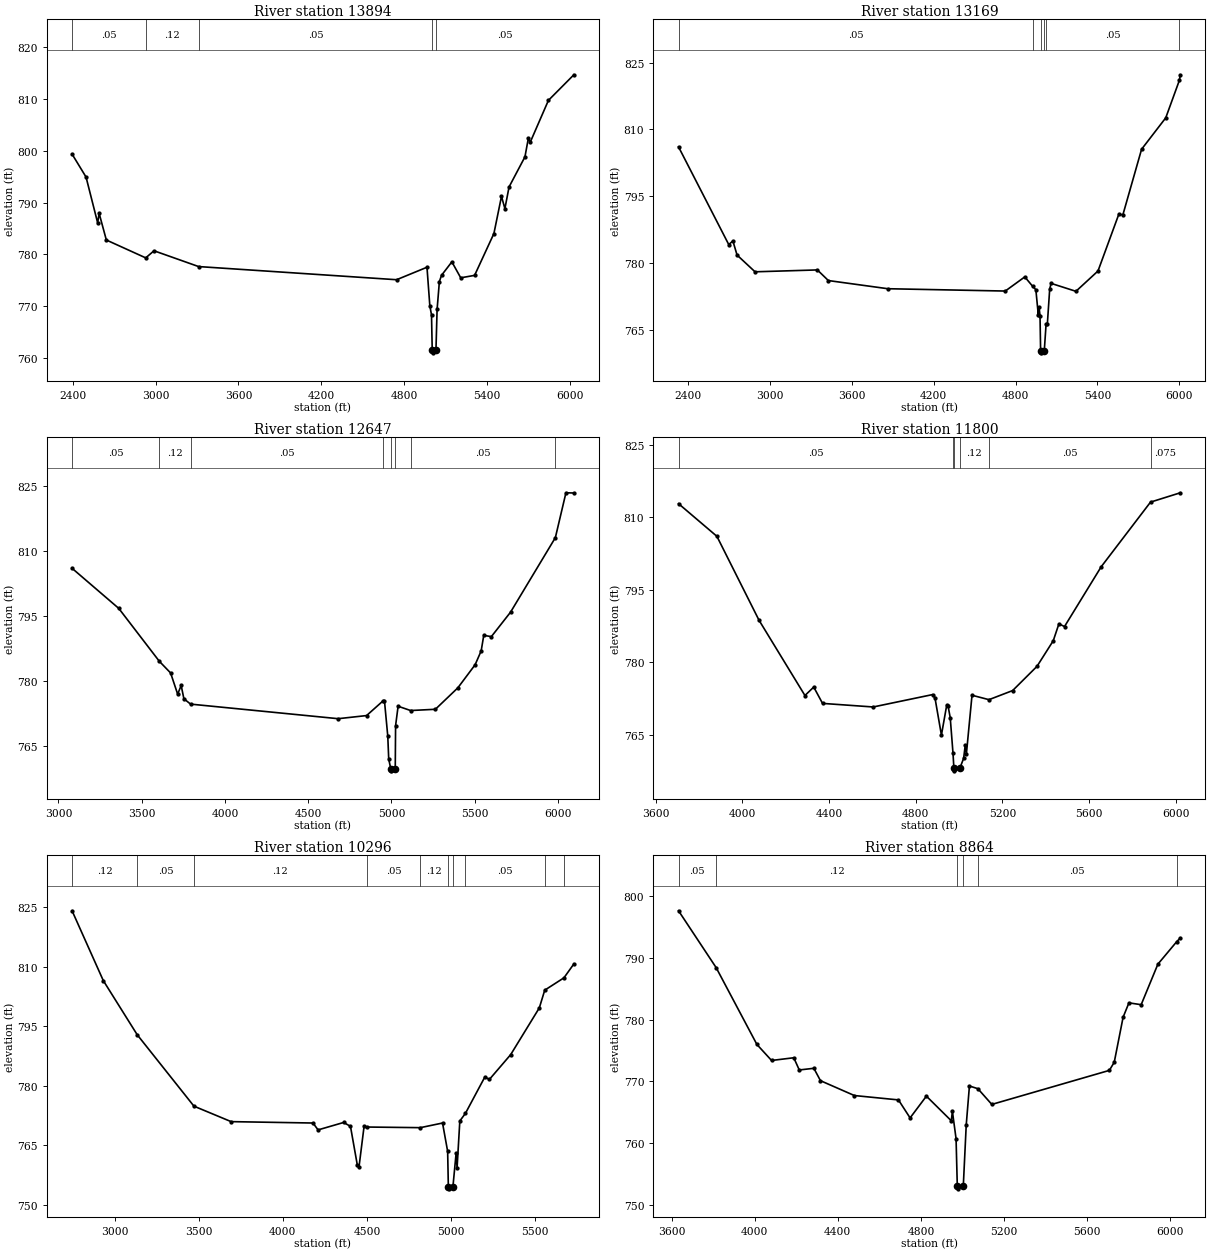
Type RM Length L Ch R = 1,13894,725,725,725
BEGIN DESCRIPTION:
Catlett Creek 2.9
END DESCRIPTION:
XS GIS Cut Line= 3
      2283514.96      7141427.36      2282746.10      7138915.73
      2282388.03      7137974.20
#Sta/Elev= 30
  2395.2  799.36  2496.4  794.93  2580.7  786.06  2591.1  787.93  2643.4  782.77
  2928.7  779.32  2988.5  780.69  3311.8  777.64  4745.5  775.10  4965.5  777.51
  4986.0  770.11  4998.3  768.29  5003.5  761.48  5006.2  760.98  5030.5  761.48
  5038.7  769.35  5055.3  774.75  5070.8  775.95  5145.7  778.55  5209.9  775.47
  5310.3  775.94  5450.2  784.02  5505.1  791.20  5529.8  788.83  5559.9  793.02
  5675.0  798.83  5699.8  802.45  5712.7  801.62  5845.0  809.74  6029.2  814.68
#Mann=5,-1,0
  2395.2    0.05       0  2928.7    0.12       0  3311.8    0.05       0
  5003.5    0.04       0  5030.5    0.05       0
Bank Sta=5003.5,5030.5
Exp/Cntr=0.3,0.1

Type RM Length L Ch R = 1,13169,522,522,522
BEGIN DESCRIPTION:
Catlett Creek 2.8
END DESCRIPTION:
XS GIS Cut Line= 3
      2283822.13      7141293.02      2283379.00      7138659.85
      2283218.90      7137664.54
#Sta/Elev= 30
  2329.8  806.10  2697.9  784.22  2728.3  785.03  2758.8  781.87  2890.6  778.12
  3347.5  778.54  3428.1  776.16  3864.1  774.33  4724.9  773.81  4868.0  776.98
  4924.6  774.91  4949.1  774.11  4967.1  768.44  4972.2  770.26  4979.6  768.31
  4983.9  760.47  4986.6  759.97  5010.9  760.47  5024.2  766.44  5033.4  766.46
  5050.5  774.24  5060.6  775.53  5242.9  773.75  5404.6  778.30  5556.9  790.99
  5587.3  790.91  5724.1  805.57  5901.3  812.61  6001.1  821.00  6008.1  822.25
#Mann=6,-1,0
  2329.8    0.05       0  4924.6    0.12       0  4983.9    0.07       0
  5010.9    0.12       0  5024.2    0.05       0  6001.1   0.075       0
Bank Sta=4983.9,5010.9
Exp/Cntr=0.3,0.1

Type RM Length L Ch R = 1,12647,847,847,847
BEGIN DESCRIPTION:
Catlett Creek 2.7
END DESCRIPTION:
XS GIS Cut Line= 3
      2284507.90      7140467.94      2283868.81      7138659.55
      2283661.85      7137583.27
#Sta/Elev= 30
  3082.0  805.99  3362.3  796.75  3606.1  784.54  3673.8  781.85  3716.2  776.96
  3737.4  778.96  3753.6  775.90  3793.8  774.66  4680.2  771.30  4851.0  772.02
  4948.3  775.35  4958.4  775.43  4978.3  767.26  4984.0  761.96  4996.2  759.77
  4998.9  759.27  5023.2  759.77  5025.2  769.68  5040.3  774.17  5115.6  773.18
  5264.3  773.47  5399.0  778.41  5502.9  783.74  5539.3  786.94  5554.8  790.52
  5600.4  790.23  5715.7  795.87  5984.9  813.06  6048.4  823.41  6096.0  823.36
#Mann=8,-1,0
  3082.0    0.05       0  3606.1    0.12       0  3793.8    0.05       0
  4948.3    0.12       0  4996.2    0.07       0  5023.2    0.12       0
  5115.6    0.05       0  5984.9   0.075       0
Bank Sta=4996.2,5023.2
Exp/Cntr=0.3,0.1

Type RM Length L Ch R = 1,11800,1504,1504,1504
BEGIN DESCRIPTION:
Catlett Creek 2.65
END DESCRIPTION:
XS GIS Cut Line= 3
      2284907.56      7139834.25      2284684.04      7138559.91
      2284352.06      7137594.81
#Sta/Elev= 30
  3706.2  812.79  3883.1  806.05  4077.6  788.70  4289.2  773.17  4329.8  774.91
  4370.4  771.54  4604.0  770.80  4878.1  773.36  4888.9  772.70  4918.7  764.99
  4943.2  771.19  4949.1  771.06  4959.3  768.60  4972.1  761.26  4976.3  758.11
  4978.9  757.61  5003.3  758.11  5021.1  760.18  5028.6  762.90  5033.9  761.12
  5059.8  773.22  5138.0  772.31  5247.2  774.19  5359.5  779.19  5434.6  784.49
  5460.6  787.97  5486.4  787.41  5655.6  799.76  5883.1  813.11  6020.6  815.04
#Mann=6,-1,0
  3706.2    0.05       0  4972.1    0.12       0  4976.3    0.07       0
  5003.3    0.12       0  5138.0    0.05       0  5883.1   0.075       0
Bank Sta=4976.3,5003.3
Exp/Cntr=0.3,0.1

Type RM Length L Ch R = 1,10296,1432,1432,1432
BEGIN DESCRIPTION:
Catlett Creek 2.61
END DESCRIPTION:
XS GIS Cut Line= 3
      2286391.93      7140433.20      2286029.03      7138209.92
      2285687.05      7137565.09
#Sta/Elev= 30
  2747.3  824.15  2932.9  806.55  3134.5  792.90  3471.7  774.90  3692.8  771.00
  4179.2  770.65  4209.6  768.92  4361.6  770.79  4402.1  769.81  4442.6  760.11
  4452.8  759.57  4483.2  769.90  4499.8  769.64  4817.3  769.48  4949.3  770.65
  4979.7  763.51  4983.9  754.56  4986.6  754.06  5011.0  754.56  5030.1  763.05
  5035.8  759.38  5052.1  771.17  5085.3  773.08  5200.4  782.22  5228.1  781.65
  5354.4  787.89  5524.6  799.67  5556.8  804.14  5671.0  807.25  5729.9  810.75
#Mann=10,-1,0
  2747.3    0.12       0  3134.5    0.05       0  3471.7    0.12       0
  4499.8    0.05       0  4817.3    0.12       0  4983.9    0.07       0
  5011.0    0.12       0  5085.3    0.05       0  5556.8   0.075       0
  5671.0    0.05       0
Bank Sta=4983.9,5011
Exp/Cntr=0.3,0.1

Type RM Length L Ch R = 1,8864,664,664,664
BEGIN DESCRIPTION:
Catlett Creek 2.6
END DESCRIPTION:
XS GIS Cut Line= 3
      2287333.02      7140049.80      2287063.99      7138709.94
      2286508.92      7137820.07
#Sta/Elev= 30
  3633.4  797.68  3814.2  788.47  4010.6  775.99  4081.2  773.39  4188.1  773.83
  4214.6  771.85  4284.8  772.12  4316.6  770.11  4479.8  767.70  4692.0  766.99
  4748.0  764.07  4826.5  767.60  4946.5  763.60  4951.6  765.15  4969.3  760.70
  4975.2  753.06  4978.1  752.56  5004.2  753.06  5018.2  762.90  5033.6  769.25
  5074.3  768.81  5141.4  766.26  5707.1  771.78  5730.7  773.10  5773.3  780.40
  5801.4  782.74  5860.3  782.44  5940.8  789.02  6031.7  792.68  6048.8  793.27
#Mann=6,-1,0
  3633.4    0.05       0  3814.2    0.12       0  4975.2    0.07       0
  5004.2    0.12       0  5074.3    0.05       0  6031.7   0.075       0
Bank Sta=4975.2,5004.2
Exp/Cntr=0.3,0.1

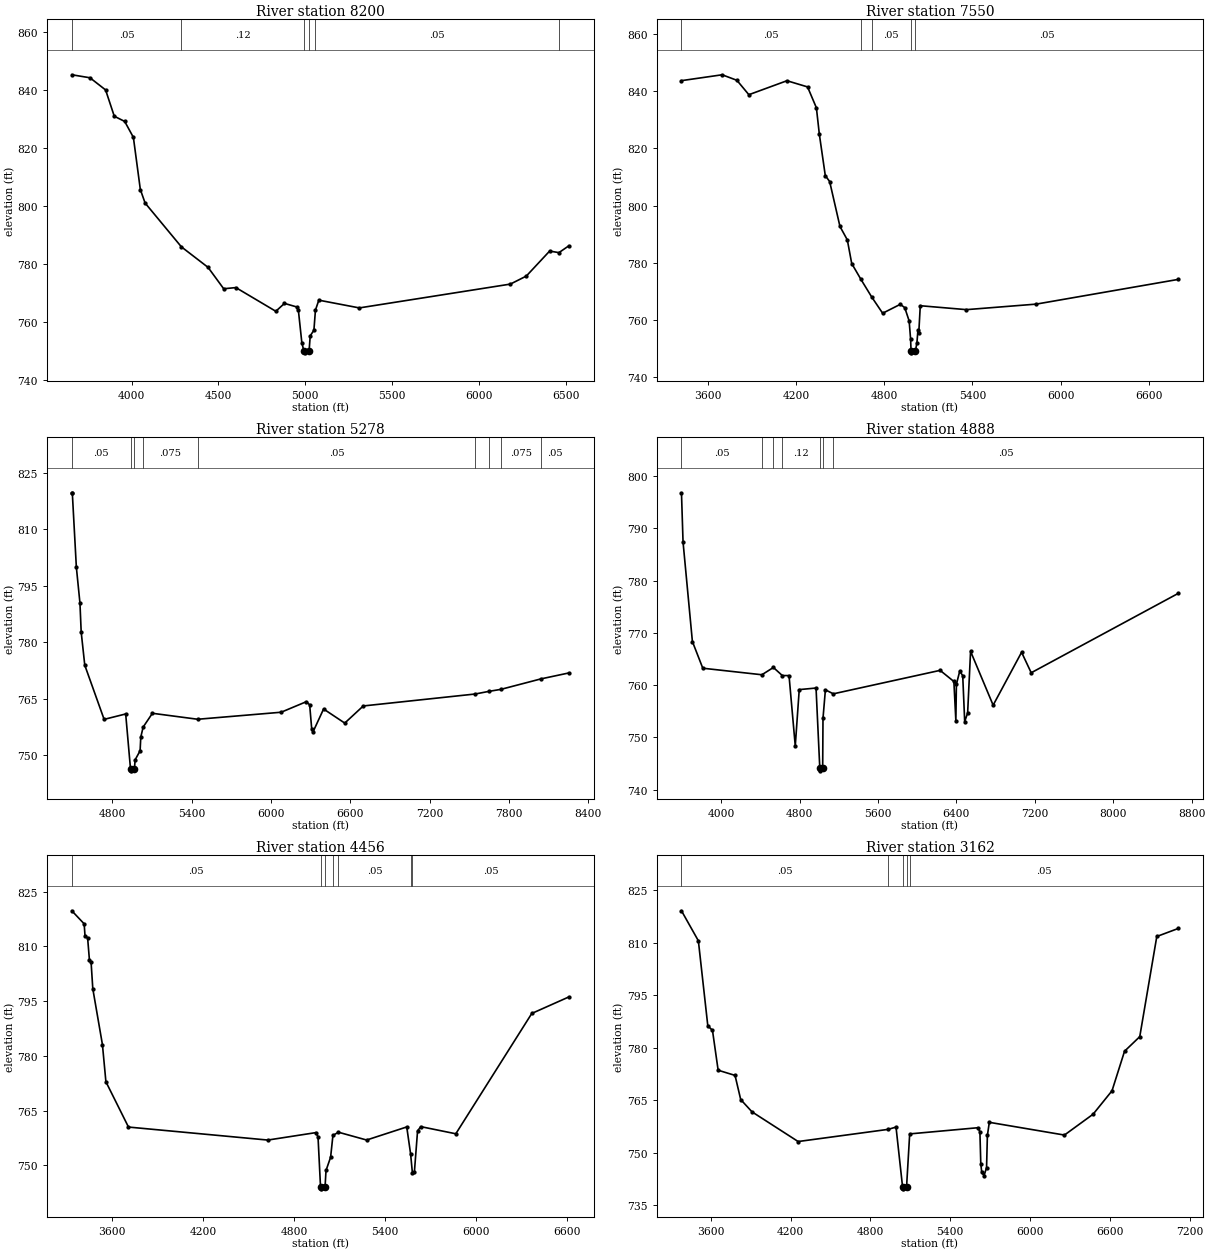
Type RM Length L Ch R = 1,8200,650,650,650
BEGIN DESCRIPTION:
Catlett Creek 2.5
END DESCRIPTION:
XS GIS Cut Line= 3
      2287715.53      7140104.46      2287679.00      7138760.15
      2286592.70      7137699.83
#Sta/Elev= 30
  3655.2  845.25  3759.7  844.22  3849.7  840.02  3899.7  830.96  3959.8  829.16
  4009.8  823.66  4049.8  805.69  4077.3  801.03  4286.3  785.92  4439.9  778.85
  4530.0  771.47  4600.0  771.88  4830.1  763.71  4880.1  766.43  4950.1  765.21
  4960.1  764.07  4980.1  752.85  4992.6  749.88  4995.5  749.38  5021.7  749.88
  5028.3  755.25  5049.6  757.17  5058.4  764.10  5077.9  767.54  5311.2  764.87
  6181.1  773.08  6272.9  775.84  6407.4  784.47  6460.9  783.93  6518.0  786.28
#Mann=6,-1,0
  3655.2    0.05       0  4286.3    0.12       0  4992.6    0.07       0
  5021.7    0.12       0  5058.4    0.05       0  6460.9   0.075       0
Bank Sta=4992.6,5021.7
Exp/Cntr=0.3,0.1

Type RM Length L Ch R = 1,7550,2272,2272,2272
BEGIN DESCRIPTION:
Catlett Creek 2.4
END DESCRIPTION:
XS GIS Cut Line= 4
      2288330.29      7140186.48      2288239.02      7138610.02
      2287854.08      7137921.15      2286843.19      7137850.19
#Sta/Elev= 30
  3420.9  843.64  3697.7  845.69  3798.0  843.76  3879.4  838.73  4138.6  843.61
  4278.8  841.45  4338.9  834.15  4358.9  824.93  4399.4  810.47  4429.1  808.40
  4499.2  792.70  4549.3  788.01  4579.3  779.74  4642.0  774.21  4714.7  768.10
  4789.7  762.38  4909.3  765.49  4939.9  764.36  4970.0  759.69  4980.0  753.23
  4983.0  749.05  4985.8  748.55  5012.1  749.05  5022.9  752.02  5029.7  756.50
  5035.4  755.43  5045.7  765.01  5359.8  763.64  5834.3  765.57  6802.5  774.22
#Mann=5,-1,0
  3420.9    0.05       0  4642.0    0.12       0  4714.7    0.05       0
  4983.0   0.033       0  5012.1    0.05       0
Bank Sta=4983,5012.1
Exp/Cntr=0.3,0.1

Type RM Length L Ch R = 1,5278,390,390,390
BEGIN DESCRIPTION:
Catlett Creek mxs 2
END DESCRIPTION:
XS GIS Cut Line= 6
      2290564.63      7138450.03      2290360.56      7138123.29
      2289964.96      7138037.08      2289093.16      7137920.14
      2287936.95      7137873.99      2287006.29      7137821.46
#Sta/Elev= 30
  4492.9  819.69  4496.5  819.76  4527.1  799.97  4554.3  790.44  4563.7  782.70
  4590.8  773.89  4737.1  759.48  4900.2  760.92  4936.7  746.29  4939.6  745.79
  4966.1  746.29  4971.8  748.73  5009.3  751.13  5014.4  754.77  5032.4  757.44
  5102.3  761.10  5444.9  759.51  6076.0  761.38  6266.9  764.19  6291.7  763.34
  6306.9  757.05  6316.9  756.14  6397.0  762.24  6557.1  758.49  6697.2  763.05
  7544.0  766.23  7645.7  766.92  7738.6  767.47  8039.6  770.24  8251.9  771.83
#Mann=9,-1,0
  4492.9    0.05       0  4936.7   0.033       0  4966.1    0.05       0
  5032.4   0.075       0  5444.9    0.05       0  7544.0   0.075       0
  7645.7    0.05       0  7738.6   0.075       0  8039.6    0.05       0
Bank Sta=4936.7,4966.1
Exp/Cntr=0.3,0.1

Type RM Length L Ch R = 1,4888,432,432,432
BEGIN DESCRIPTION:
Cattlett Creek mapx 1.0
END DESCRIPTION:
XS GIS Cut Line= 4
      2291754.12      7138255.02      2290275.34      7137734.57
      2289042.71      7137618.35      2286779.75      7137519.66
#Sta/Elev= 30
  3595.0  796.80  3611.0  787.39  3706.4  768.35  3812.5  763.24  4415.5  761.99
  4532.9  763.38  4623.8  761.84  4692.4  761.83  4756.0  748.37  4796.5  759.15
  4968.0  759.45  5006.3  744.11  5009.2  743.61  5035.7  744.11  5038.9  753.64
  5063.4  759.11  5144.4  758.34  6233.8  762.83  6374.4  760.70  6394.5  753.19
  6400.1  760.18  6434.5  762.71  6464.6  761.80  6484.6  753.04  6514.6  754.66
  6544.6  766.47  6774.9  756.17  7065.1  766.29  7163.2  762.37  8665.9  777.58
#Mann=7,-1,0
  3595.0    0.05       0  4415.5    0.12       0  4532.9    0.05       0
  4623.8    0.12       0  5006.3    0.07       0  5035.7    0.12       0
  5144.4    0.05       0
Bank Sta=5006.3,5035.7
Exp/Cntr=0.3,0.1

Type RM Length L Ch R = 1,4456,1294,1294,1294
BEGIN DESCRIPTION:
Catlett Creek 2.4a
END DESCRIPTION:
XS GIS Cut Line= 3
      2291994.63      7138070.45      2290465.24      7137369.39
      2289159.16      7136449.03
#Sta/Elev= 30
  3332.7  819.75  3414.1  816.17  3419.6  812.97  3437.1  812.24  3448.9  806.23
  3459.9  805.60  3471.1  798.40  3534.6  783.12  3557.6  772.92  3706.6  760.51
  4626.0  756.95  4945.0  759.00  4957.6  757.77  4974.1  744.09  4977.0  743.59
  5003.9  744.09  5010.3  748.62  5040.6  752.24  5055.9  758.22  5092.1  759.10
  5278.3  756.96  5543.1  760.54  5568.5  753.18  5580.4  747.96  5593.6  748.20
  5614.5  759.44  5635.4  760.63  5866.9  758.67  6368.4  791.63  6612.9  796.15
#Mann=7,-1,0
  3332.7    0.05       0  4974.1   0.033       0  5003.9    0.05       0
  5055.9    0.12       0  5092.1    0.05       0  5568.5    0.12       0
  5580.4    0.05       0
Bank Sta=4974.1,5003.9
Exp/Cntr=0.3,0.1

Type RM Length L Ch R = 1,3162,1144,1144,1144
BEGIN DESCRIPTION:
Catlett Creek 2.4b
END DESCRIPTION:
XS GIS Cut Line= 3
      2292547.98      7137830.41      2290858.01      7136310.04
      2289673.45      7135448.08
#Sta/Elev= 30
  3378.6  819.20  3505.7  810.62  3576.7  786.31  3611.8  785.03  3654.4  773.63
  3781.5  772.15  3824.1  765.25  3909.3  761.73  4256.1  753.25  4933.5  756.73
  4992.3  757.38  5041.7  740.23  5044.6  739.73  5071.5  740.23  5095.1  755.43
  5609.0  757.20  5623.2  756.01  5629.9  746.89  5637.0  744.46  5654.3  743.48
  5673.3  745.79  5679.5  755.00  5694.1  758.74  6259.0  755.10  6474.6  761.06
  6616.8  767.75  6711.1  779.06  6825.5  783.22  6953.7  811.85  7116.8  814.17
#Mann=5,-1,0
  3378.6    0.05       0  4933.5    0.12       0  5041.7    0.07       0
  5071.5    0.12       0  5095.1    0.05       0
Bank Sta=5041.7,5071.5
Exp/Cntr=0.3,0.1

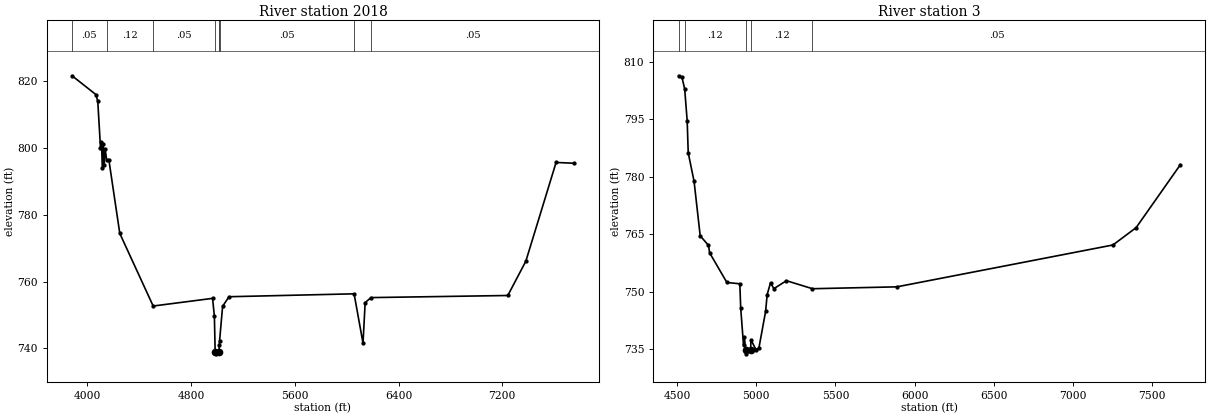
Type RM Length L Ch R = 1,2018,2015,2015,2015
BEGIN DESCRIPTION:
Catlett Creek 2.4c
END DESCRIPTION:
XS GIS Cut Line= 3
      2293152.58      7137366.58      2291479.16      7135875.06
      2290027.04      7135135.16
#Sta/Elev= 30
  3881.2  821.58  4065.4  815.95  4079.6  813.91  4100.5  800.06  4108.0  801.80
  4114.7  793.92  4122.2  801.27  4128.9  794.98  4136.4  799.74  4147.9  796.38
  4164.9  796.48  4249.3  774.41  4506.9  752.68  4965.0  754.97  4979.2  749.66
  4985.2  738.87  4988.1  738.37  5015.0  738.87  5017.6  741.09  5018.8  742.11
  5042.8  752.61  5092.1  755.46  6057.2  756.33  6125.8  741.58  6142.4  753.69
  6187.1  755.20  7243.0  755.83  7382.1  766.09  7615.4  795.64  7752.6  795.41
#Mann=9,-1,0
  3881.2    0.05       0  4147.9    0.12       0  4506.9    0.05       0
  4985.2   0.033       0  5015.0    0.05       0  5017.6    0.12       0
  5018.8    0.05       0  6057.2    0.12       0  6187.1    0.05       0
Bank Sta=4985.2,5015
Exp/Cntr=0.3,0.1

Type RM Length L Ch R = 1,3,0,0,0
BEGIN DESCRIPTION:
Catlett Cr tie in
END DESCRIPTION:
XS GIS Cut Line= 3
      2293179.00      7135560.00      2292728.94      7135363.45
      2290452.70      7133950.35
#Sta/Elev= 30
  4508.9  806.42  4530.7  806.00  4547.8  802.96  4563.5  794.65  4570.1  786.29
  4607.1  778.80  4645.8  764.56  4698.1  762.08  4705.3  760.12  4814.4  752.36
  4896.2  752.02  4901.7  745.64  4919.6  735.92  4925.1  738.12  4932.4  734.70
  4935.7  733.70  4964.5  734.70  4966.4  737.38  4998.1  734.80  5016.8  735.26
  5059.3  744.86  5068.8  749.19  5090.0  752.28  5111.3  750.74  5190.4  752.83
  5355.2  750.73  5888.4  751.22  7253.6  762.17  7400.1  766.71  7679.2  783.15
#Mann=5,-1,0
  4508.9    0.05       0  4547.8    0.12       0  4932.4    0.07       0
  4964.5    0.12       0  5355.2    0.05       0
Bank Sta=4932.4,4964.5
Exp/Cntr=0.3,0.1

Chan Stop Cuts=-1