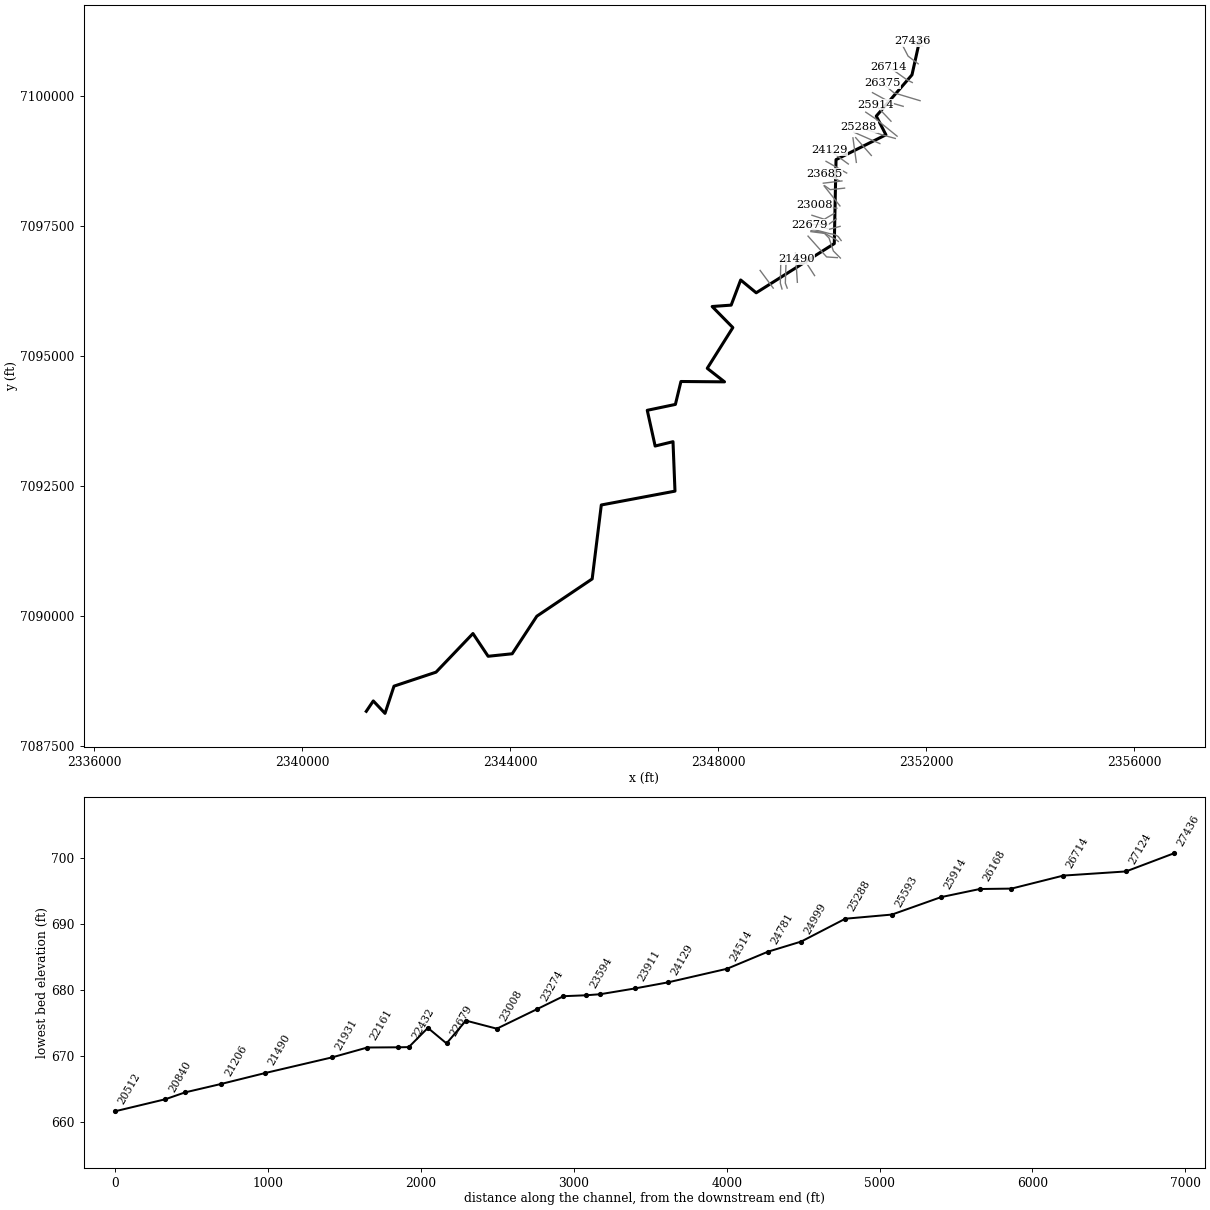
--- Denton Creek Tributary 14.prj (project) ---

Proj Title=Denton Creek Tributary 14 Base Level Engineering
Current Plan=p01
Default Exp/Contr=0.3,0.1
English Units
Geom File=g01
Flow File=f01
Plan File=p01
BEGIN DESCRIPTION:
Denton Creek Tributary 14
END DESCRIPTION:

--- Denton Creek Tributary 14.p01 (plan) ---

Plan Title=Multiple Run
Short Identifier=Multiple
Geom File=g01
Flow File=f01
Subcritical Flow
K Sum by GR= 0
Std Step Tol= 0.01
Critical Tol= 0.01
Num of Std Step Trials= 20
Max Error Tol= 0.3
Flow Tol Ratio= 0.001
Split Flow NTrial= 30
Split Flow Tol= 0.02
Split Flow Ratio= 0.02
Log Output Level= 0
Friction Slope Method= 1
Unsteady Friction Slope Method= 2
Unsteady Bridges Friction Slope Method= 1
Parabolic Critical Depth
Global Vel Dist=  1 , 1 , 1
Global Log Level= 0
CheckData=True
Encroach Param= -1, 0, 0, 0
BEGIN DESCRIPTION:
Multiple Run
END DESCRIPTION:

--- Denton Creek Tributary 14.f01 (steady flow) ---

Flow Title=Multiple
Number of Profiles=7
Profile Names=10-year,25-year,50-year,1pct_min,100-year,1pct_plu,500-year
River Rch & RM= Denton Creek Tri,Reach-1,27436
     491     663     803     483     965    1925    1393
River Rch & RM= Denton Creek Tri,Reach-1,22161
     755    1045    1287     786    1569    3131    2337
River Rch & RM= Denton Creek Tri,Reach-1,19343
    1000    1404    1745    1074    2144    4277    3245
River Rch & RM= Denton Creek Tri,Reach-1,17309
    1168    1646    2050    1264    2521    5030    3828
River Rch & RM= Denton Creek Tri,Reach-1,11461
    1409    2002    2505    1551    3096    6176    4742
River Rch & RM= Denton Creek Tri,Reach-1,5999
    1414    2005    2508    1551    3095    6175    4732
Boundary for River Rch & Prof#=Denton Creek Tri,Reach-1,1
Up Type=0
Dn Type=3
Dn Slope=0.005
Boundary for River Rch & Prof#=Denton Creek Tri,Reach-1,2
Up Type=0
Dn Type=3
Dn Slope=0.005
Boundary for River Rch & Prof#=Denton Creek Tri,Reach-1,3
Up Type=0
Dn Type=3
Dn Slope=0.005
Boundary for River Rch & Prof#=Denton Creek Tri,Reach-1,4
Up Type=0
Dn Type=3
Dn Slope=0.005
Boundary for River Rch & Prof#=Denton Creek Tri,Reach-1,5
Up Type=0
Dn Type=3
Dn Slope=0.005
Boundary for River Rch & Prof#=Denton Creek Tri,Reach-1,6
Up Type=0
Dn Type=3
Dn Slope=0.005
Boundary for River Rch & Prof#=Denton Creek Tri,Reach-1,7
Up Type=0
Dn Type=3
Dn Slope=0.005

--- Denton Creek Tributary 14.g01 (geometry) ---

Geom Title=Existing Conditions

River Reach=Denton Creek Tri,Reach-1
Reach XY= 30
      2351879.00      7101110.00      2351723.48      7100407.57
      2351036.50      7099613.58      2351221.80      7099253.92
      2350262.73      7098775.61      2350229.00      7097160.00
      2348727.51      7096213.45      2348429.00      7096460.00
      2348246.13      7095976.25      2347879.98      7095949.74
      2348278.48      7095544.12      2347786.08      7094759.98
      2348118.41      7094499.95      2347280.29      7094506.63
      2347173.42      7094065.58      2346632.50      7093952.28
      2346784.03      7093264.92      2347127.52      7093348.52
      2347165.61      7092396.67      2345748.72      7092130.54
      2345573.18      7090707.69      2344508.80      7089990.41
      2344035.06      7089267.48      2343572.24      7089219.12
      2343280.43      7089656.99      2342570.52      7088913.51
      2341762.09      7088644.26      2341589.19      7088120.40
      2341363.96      7088359.70      2341229.00      7088160.00

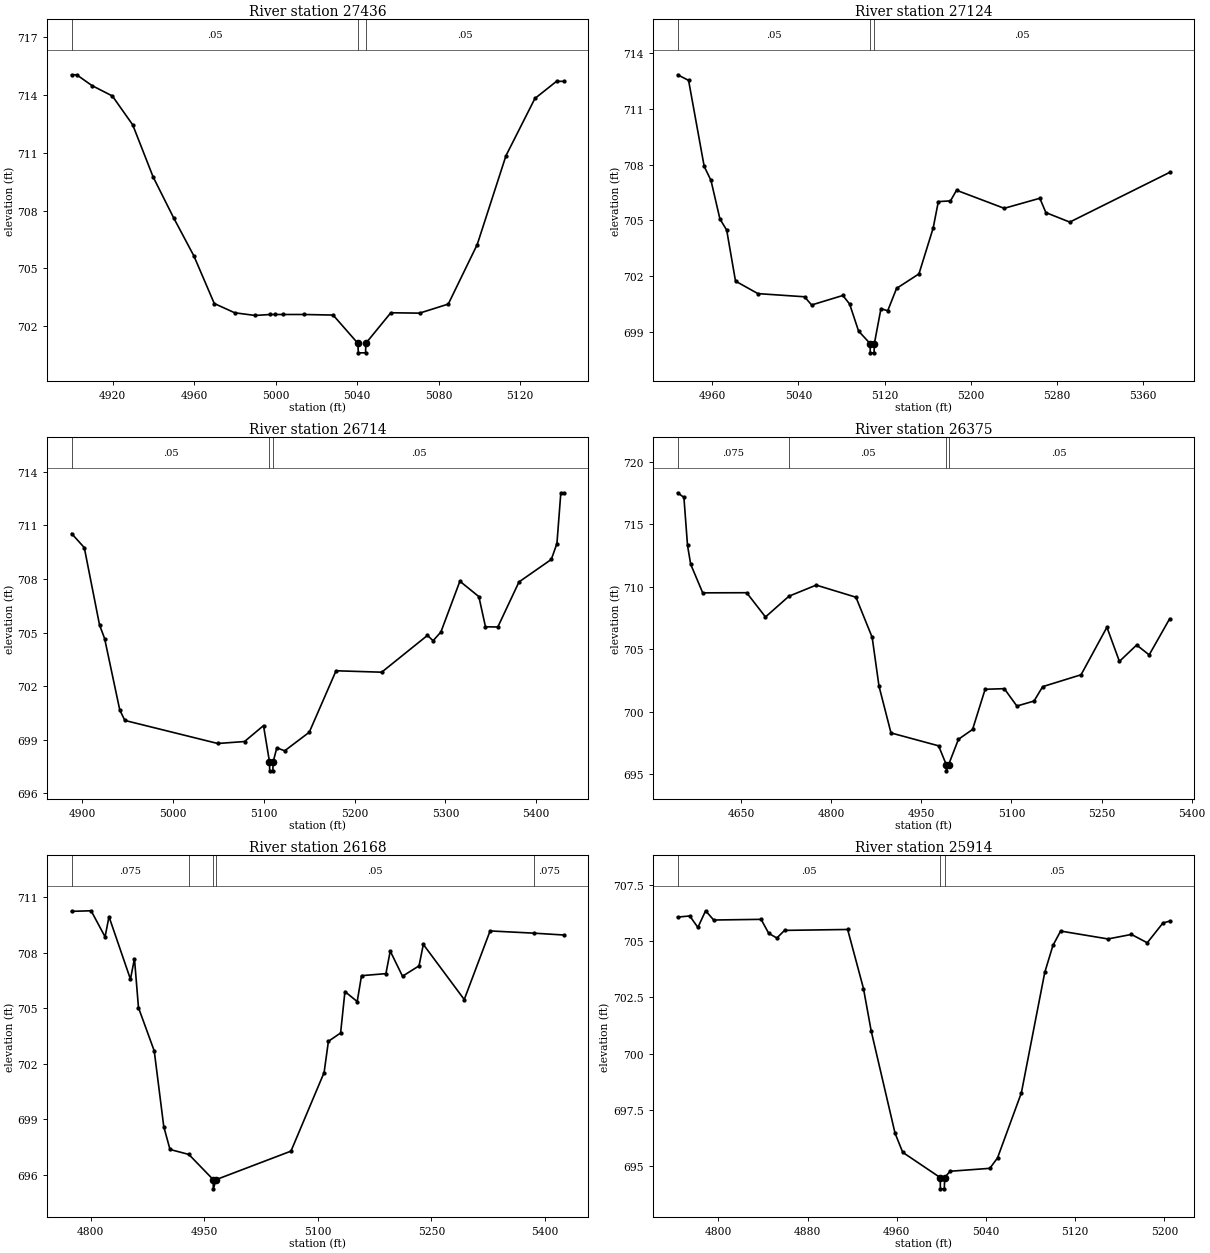
Type RM Length L Ch R = 1,27436,312,312,312
BEGIN DESCRIPTION:
Denton Creek Tributary 14 52.0
END DESCRIPTION:
XS GIS Cut Line= 3
      2351928.99      7100960.00      2351829.00      7100960.00
      2351729.01      7101059.99
#Sta/Elev= 28
  4899.9  715.05  4902.4  715.05  4909.9  714.49  4919.9  713.95  4929.9  712.45
  4939.9  709.75  4949.9  707.64  4959.9  705.65  4969.9  703.18  4979.9  702.70
  4989.9  702.56  4997.4  702.61  4999.9  702.61  5003.4  702.61  5014.0  702.61
  5028.2  702.58  5040.3  701.12  5040.6  700.62  5044.1  700.62  5044.3  701.12
  5056.5  702.70  5070.6  702.68  5084.7  703.15  5098.9  706.24  5113.0  710.85
  5127.2  713.82  5137.8  714.71  5141.3  714.71
#Mann=3,-1,0
  4899.9    0.05       0  5040.3   0.033       0  5044.3    0.05       0
Bank Sta=5040.3,5044.3
Exp/Cntr=0.3,0.1

Type RM Length L Ch R = 1,27124,410,410,410
BEGIN DESCRIPTION:
Denton Creek Tributary 14 51.0
END DESCRIPTION:
XS GIS Cut Line= 3
      2351842.64      7100619.19      2351648.58      7100767.53
      2351551.10      7100956.74
#Sta/Elev= 30
  4927.8  712.82  4938.0  712.52  4952.5  707.90  4958.8  707.15  4967.1  705.08
  4973.4  704.48  4981.6  701.74  5002.4  701.07  5045.7  700.90  5052.3  700.46
  5081.3  700.97  5087.6  700.51  5095.9  699.06  5106.6  698.39  5106.8  697.89
  5110.3  697.89  5110.6  698.39  5116.7  700.26  5123.0  700.15  5131.2  701.35
  5152.0  702.13  5165.2  704.59  5170.0  706.01  5181.3  706.05  5186.9  706.62
  5231.2  705.65  5264.3  706.19  5269.9  705.42  5292.1  704.91  5384.9  707.58
#Mann=3,-1,0
  4927.8    0.05       0  5106.6   0.033       0  5110.6    0.05       0
Bank Sta=5106.6,5110.6
Exp/Cntr=0.3,0.1

Type RM Length L Ch R = 1,26714,339,339,339
BEGIN DESCRIPTION:
Denton Creek Tributary 14 50.0
END DESCRIPTION:
XS GIS Cut Line= 3
      2351729.03      7100259.98      2351629.00      7100310.00
      2351278.96      7100560.03
#Sta/Elev= 30
  4888.2  710.54  4902.2  709.75  4919.0  705.42  4924.6  704.66  4941.3  700.66
  4946.9  700.08  5049.2  698.79  5078.7  698.90  5099.6  699.79  5106.2  697.76
  5106.4  697.26  5109.9  697.26  5110.2  697.76  5114.3  698.55  5122.9  698.38
  5150.0  699.42  5179.5  702.86  5229.8  702.78  5280.2  704.84  5286.4  704.54
  5295.0  705.03  5315.9  707.87  5336.8  707.01  5344.1  705.32  5357.7  705.31
  5381.0  707.83  5416.6  709.09  5422.8  709.98  5427.1  712.82  5430.2  712.82
#Mann=3,-1,0
  4888.2    0.05       0  5106.2   0.033       0  5110.2    0.05       0
Bank Sta=5106.2,5110.2
Exp/Cntr=0.3,0.1

Type RM Length L Ch R = 1,26375,207,207,207
BEGIN DESCRIPTION:
Denton Creek Tributary 14 49.0
END DESCRIPTION:
XS GIS Cut Line= 3
      2351879.01      7099910.00      2351379.00      7100060.00
      2351150.53      7100249.09
#Sta/Elev= 30
  4544.7  717.52  4555.2  717.15  4561.2  713.31  4566.5  711.80  4586.5  709.52
  4659.6  709.53  4690.9  707.59  4729.9  709.25  4775.3  710.14  4841.4  709.17
  4868.4  705.96  4879.7  702.07  4899.7  698.32  4978.9  697.29  4991.6  695.79
  4991.9  695.29  4995.6  695.79  5011.9  697.81  5035.4  698.60  5056.3  701.81
  5088.2  701.86  5109.1  700.47  5137.7  700.87  5152.0  702.02  5215.9  702.97
  5258.9  706.77  5279.7  704.04  5308.4  705.35  5329.2  704.56  5363.3  707.45
#Mann=4,-1,0
  4544.7   0.075       0  4729.9    0.05       0  4991.6   0.033       0
  4995.6    0.05       0
Bank Sta=4991.6,4995.6
Exp/Cntr=0.3,0.1

Type RM Length L Ch R = 1,26168,254,254,254
BEGIN DESCRIPTION:
Mapping XS 5ec90248
END DESCRIPTION:
XS GIS Cut Line= 3
      2351553.77      7099801.93      2351324.25      7099868.47
      2350963.77      7100064.91
#Sta/Elev= 30
  4775.0  710.24  4800.8  710.27  4819.2  708.86  4824.4  709.95  4852.7  706.57
  4858.0  707.68  4863.3  705.03  4884.1  702.69  4896.7  698.59  4904.9  697.36
  4929.8  697.09  4961.9  695.73  4962.1  695.23  4965.9  695.73  5064.6  697.27
  5108.3  701.52  5114.0  703.21  5130.1  703.66  5135.8  705.90  5152.0  705.36
  5157.7  706.76  5189.9  706.87  5195.6  708.09  5211.8  706.73  5233.6  707.29
  5239.3  708.45  5293.3  705.47  5327.4  709.18  5384.9  709.06  5424.5  708.96
#Mann=5,-1,0
  4775.0   0.075       0  4929.8    0.05       0  4961.9   0.033       0
  4965.9    0.05       0  5384.9   0.075       0
Bank Sta=4961.9,4965.9
Exp/Cntr=0.3,0.1

Type RM Length L Ch R = 1,25914,321,321,321
BEGIN DESCRIPTION:
Mapping XS 31e2d48e
END DESCRIPTION:
XS GIS Cut Line= 2
      2351319.74      7099515.16      2351016.79      7099836.05
#Sta/Elev= 30
  4763.4  706.06  4774.3  706.11  4781.6  705.60  4788.5  706.34  4795.8  705.93
  4838.3  705.96  4845.1  705.34  4852.4  705.13  4859.3  705.47  4915.9  705.51
  4930.1  702.89  4937.0  701.01  4958.4  696.47  4965.3  695.62  4998.9  694.50
  4999.1  694.00  5002.6  694.00  5002.9  694.50  5007.8  694.78  5043.4  694.91
  5050.3  695.37  5071.7  698.26  5092.7  703.61  5100.0  704.80  5106.9  705.44
  5149.4  705.09  5170.4  705.29  5184.6  704.92  5198.7  705.80  5204.7  705.88
#Mann=3,-1,0
  4763.4    0.05       0  4998.9    0.05       0  5002.9    0.05       0
Bank Sta=4998.9,5002.9
Exp/Cntr=0.3,0.1

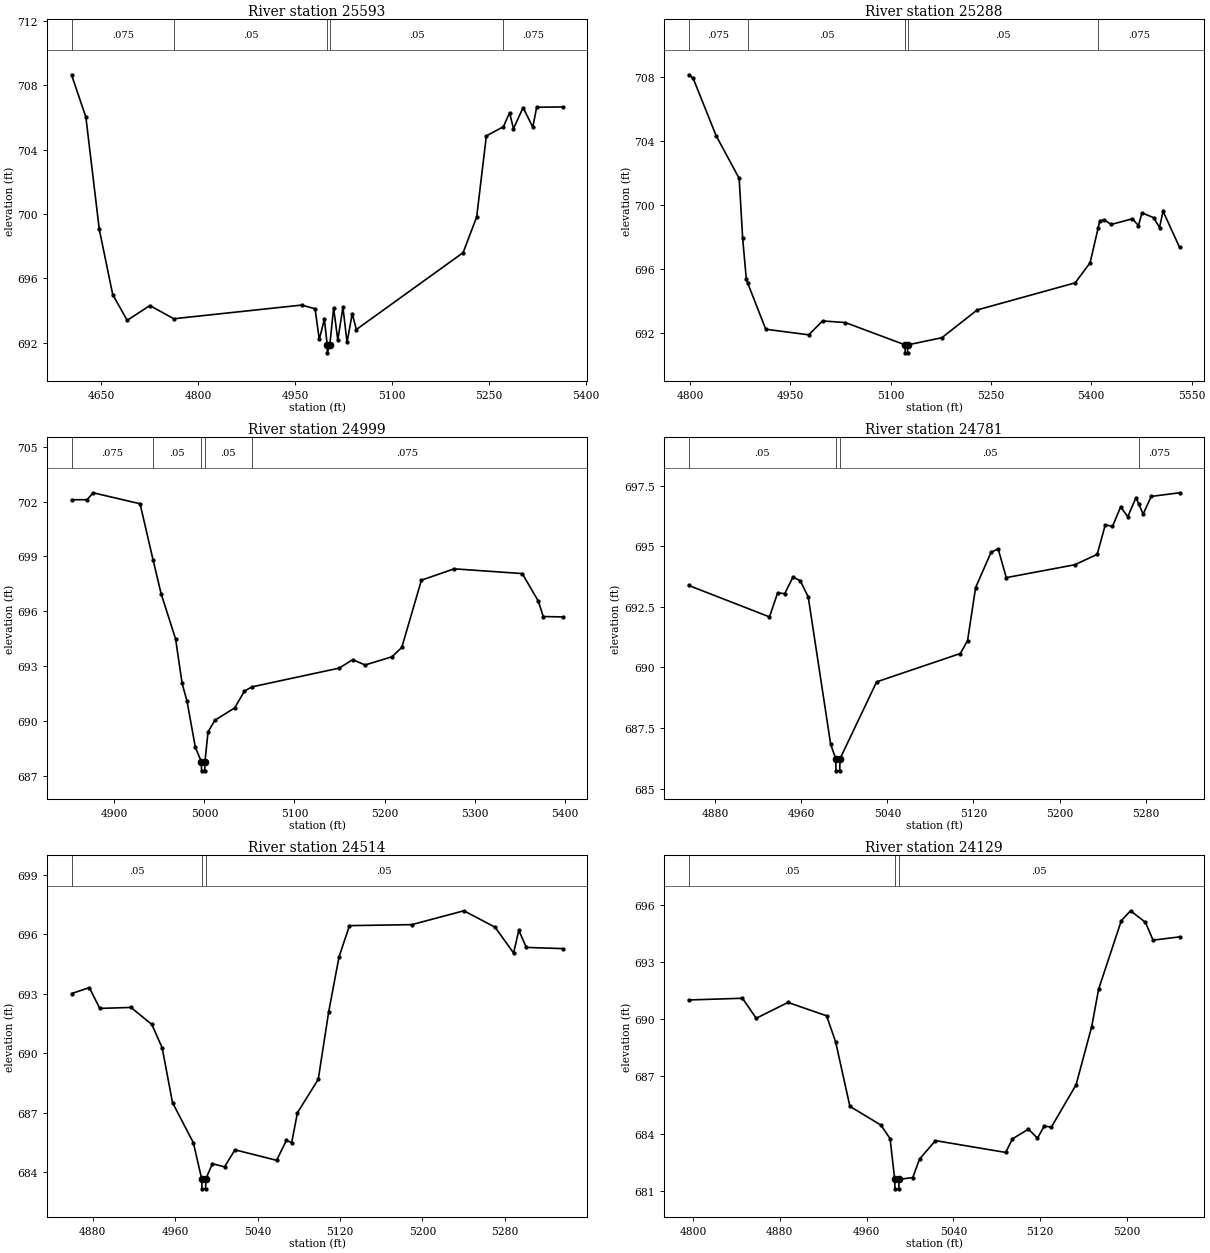
Type RM Length L Ch R = 1,25593,305,305,305
BEGIN DESCRIPTION:
Mapping XS 4ef250ab
END DESCRIPTION:
XS GIS Cut Line= 3
      2351436.80      7099227.39      2351035.20      7099553.35
      2350833.98      7099689.50
#Sta/Elev= 30
  4604.1  708.65  4626.3  706.02  4647.1  699.03  4667.9  694.98  4690.3  693.38
  4725.4  694.30  4762.4  693.48  4960.4  694.33  4981.2  694.10  4987.7  692.19
  4995.6  693.45  5000.0  691.86  5000.2  691.36  5004.0  691.86  5009.9  694.15
  5016.4  692.15  5024.3  694.20  5030.7  692.01  5038.7  693.80  5045.1  692.81
  5210.4  697.59  5231.4  699.81  5246.4  704.85  5272.8  705.42  5282.3  706.29
  5288.4  705.30  5303.3  706.61  5318.3  705.39  5324.3  706.63  5364.3  706.65
#Mann=5,-1,0
  4604.1   0.075       0  4762.4    0.05       0  5000.0   0.033       0
  5004.0    0.05       0  5272.8   0.075       0
Bank Sta=5000,5004
Exp/Cntr=0.3,0.1

Type RM Length L Ch R = 1,25288,289,289,289
BEGIN DESCRIPTION:
Mapping XS 78146dc6
END DESCRIPTION:
XS GIS Cut Line= 3
      2351402.31      7099183.72      2351153.87      7099251.75
      2350702.22      7099403.34
#Sta/Elev= 30
  4797.9  708.17  4804.6  707.97  4839.1  704.35  4873.6  701.67  4878.8  697.91
  4884.3  695.34  4886.4  695.10  4913.3  692.21  4977.6  691.86  4998.3  692.73
  5032.3  692.63  5121.6  691.23  5121.8  690.73  5125.3  690.73  5125.6  691.23
  5176.7  691.68  5229.4  693.42  5375.9  695.12  5398.2  696.38  5410.2  698.55
  5412.7  699.01  5419.3  699.07  5429.8  698.78  5461.5  699.14  5470.5  698.71
  5475.8  699.51  5493.1  699.21  5502.0  698.59  5507.3  699.61  5531.9  697.35
#Mann=5,-1,0
  4797.9   0.075       0  4886.4    0.05       0  5121.6   0.033       0
  5125.6    0.05       0  5410.2   0.075       0
Bank Sta=5121.6,5125.6
Exp/Cntr=0.3,0.1

Type RM Length L Ch R = 1,24999,218,218,218
BEGIN DESCRIPTION:
Mapping XS ffcb6324
END DESCRIPTION:
XS GIS Cut Line= 2
      2351104.87      7099084.94      2350605.54      7099304.09
#Sta/Elev= 30
  4852.4  702.10  4869.7  702.10  4876.3  702.48  4928.5  701.88  4943.0  698.80
  4951.9  696.96  4968.0  694.48  4975.2  692.06  4980.7  691.07  4989.9  688.56
  4996.6  687.77  4996.8  687.27  5000.3  687.27  5000.6  687.77  5004.0  689.40
  5011.7  690.04  5033.5  690.71  5044.5  691.63  5052.5  691.86  5149.7  692.89
  5164.6  693.35  5178.5  693.06  5208.3  693.51  5219.2  694.02  5241.0  697.70
  5277.4  698.32  5353.0  698.06  5370.9  696.55  5376.3  695.71  5397.7  695.69
#Mann=5,-1,0
  4852.4   0.075       0  4943.0    0.05       0  4996.6    0.05       0
  5000.6    0.05       0  5052.5   0.075       0
Bank Sta=4996.6,5000.6
Exp/Cntr=0.3,0.1

Type RM Length L Ch R = 1,24781,267,267,267
BEGIN DESCRIPTION:
Mapping XS 22b45d35
END DESCRIPTION:
XS GIS Cut Line= 2
      2350941.55      7098856.14      2350640.29      7099198.86
#Sta/Elev= 30
  4855.2  693.38  4930.4  692.08  4938.0  693.07  4944.6  693.04  4952.2  693.72
  4958.9  693.58  4966.4  692.91  4987.3  686.82  4992.0  686.23  4992.2  685.73
  4995.7  685.73  4996.0  686.23  5030.0  689.40  5107.8  690.57  5114.5  691.10
  5122.0  693.29  5136.3  694.74  5142.9  694.89  5150.5  693.70  5214.1  694.23
  5235.0  694.66  5242.5  695.88  5249.2  695.81  5256.8  696.62  5263.4  696.21
  5271.0  697.00  5273.7  696.73  5277.7  696.32  5285.2  697.05  5311.5  697.20
#Mann=4,-1,0
  4855.2    0.05       0  4992.0    0.05       0  4996.0    0.05       0
  5273.7   0.075       0
Bank Sta=4992,4996
Exp/Cntr=0.3,0.1

Type RM Length L Ch R = 1,24514,385,385,385
BEGIN DESCRIPTION:
Mapping XS 878f8214
END DESCRIPTION:
XS GIS Cut Line= 2
      2350653.21      7098722.89      2350587.87      7099194.78
#Sta/Elev= 30
  4859.5  693.01  4876.8  693.31  4886.9  692.26  4917.2  692.31  4937.4  691.45
  4947.4  690.28  4957.5  687.50  4977.7  685.48  4985.8  683.65  4986.1  683.15
  4989.6  683.15  4989.8  683.65  4996.2  684.42  5008.0  684.26  5018.1  685.12
  5058.5  684.59  5068.0  685.60  5073.1  685.48  5078.7  686.99  5098.9  688.68
  5109.0  692.08  5119.1  694.87  5129.2  696.44  5189.7  696.49  5240.2  697.19
  5270.5  696.36  5288.4  695.06  5293.5  696.20  5300.8  695.34  5335.9  695.28
#Mann=3,-1,0
  4859.5    0.05       0  4985.8   0.033       0  4989.8    0.05       0
Bank Sta=4985.8,4989.8
Exp/Cntr=0.3,0.1

Type RM Length L Ch R = 1,24129,218,218,218
BEGIN DESCRIPTION:
Mapping XS a79519d6
END DESCRIPTION:
XS GIS Cut Line= 2
      2350499.13      7098691.63      2350133.60      7098958.86
#Sta/Elev= 30
  4795.8  691.01  4845.5  691.10  4858.2  690.05  4887.5  690.88  4923.1  690.18
  4931.5  688.80  4944.6  685.43  4973.3  684.44  4981.7  683.73  4985.9  681.60
  4986.2  681.10  4989.7  681.10  4989.9  681.60  5002.6  681.69  5008.8  682.66
  5023.5  683.63  5088.3  683.01  5094.5  683.72  5109.2  684.23  5117.6  683.76
  5123.8  684.39  5130.4  684.34  5153.2  686.56  5167.6  689.61  5174.0  691.58
  5194.9  695.17  5203.4  695.69  5217.1  695.09  5224.2  694.15  5248.6  694.32
#Mann=3,-1,0
  4795.8    0.05       0  4985.9   0.033       0  4989.9    0.05       0
Bank Sta=4985.9,4989.9
Exp/Cntr=0.3,0.1

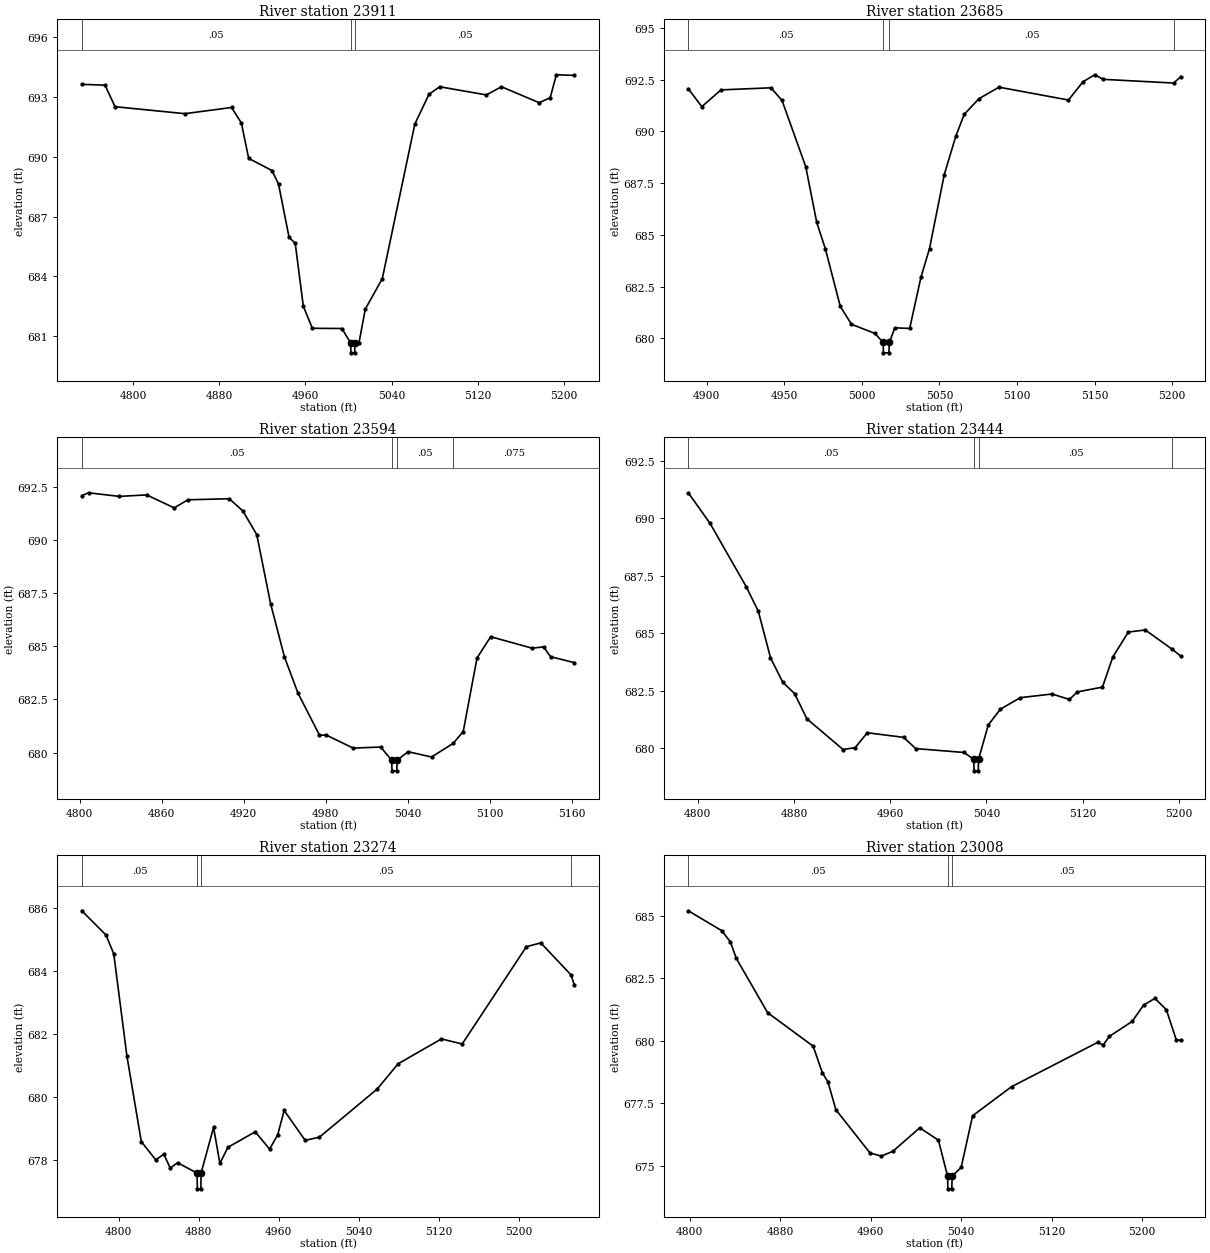
Type RM Length L Ch R = 1,23911,226,226,226
BEGIN DESCRIPTION:
Mapping XS 6b99d18f
END DESCRIPTION:
XS GIS Cut Line= 2
      2350467.70      7098518.09      2350070.25      7098743.66
#Sta/Elev= 30
  4752.6  693.63  4774.1  693.59  4783.4  692.51  4848.2  692.16  4891.5  692.47
  4900.6  691.70  4907.4  689.92  4929.0  689.31  4935.1  688.63  4944.9  685.96
  4950.6  685.66  4958.1  682.51  4966.5  681.40  4993.9  681.39  5002.0  680.67
  5002.3  680.17  5005.8  680.17  5006.0  680.67  5009.8  680.68  5015.6  682.36
  5031.4  683.89  5061.6  691.64  5074.7  693.13  5084.6  693.51  5128.0  693.10
  5142.0  693.51  5177.0  692.71  5187.2  692.96  5192.9  694.11  5209.6  694.08
#Mann=3,-1,0
  4752.6    0.05       0  5002.0   0.033       0  5006.0    0.05       0
Bank Sta=5002,5006
Exp/Cntr=0.3,0.1

Type RM Length L Ch R = 1,23685,91,91,91
BEGIN DESCRIPTION:
Mapping XS 261fc020
END DESCRIPTION:
XS GIS Cut Line= 2
      2350326.76      7098367.49      2350042.45      7098508.82
#Sta/Elev= 30
  4888.1  692.06  4896.8  691.20  4909.2  692.01  4941.4  692.11  4948.5  691.50
  4963.8  688.30  4970.9  685.60  4976.4  684.34  4986.1  681.54  4993.3  680.68
  5008.4  680.24  5013.7  679.80  5013.9  679.30  5017.4  679.30  5017.7  679.80
  5021.2  680.51  5030.8  680.48  5038.1  682.96  5043.6  684.34  5053.1  687.91
  5060.5  689.76  5066.0  690.83  5075.4  691.58  5088.4  692.14  5133.2  691.52
  5142.5  692.40  5150.1  692.74  5155.6  692.52  5201.0  692.34  5205.6  692.65
#Mann=4,-1,0
  4888.1    0.05       0  5013.7    0.05       0  5017.7    0.05       0
  5201.0   0.075       0
Bank Sta=5013.7,5017.7
Exp/Cntr=0.3,0.1

Type RM Length L Ch R = 1,23594,150,150,150
BEGIN DESCRIPTION:
Mapping XS 738d7469
END DESCRIPTION:
XS GIS Cut Line= 2
      2350376.09      7098365.92      2350018.29      7098322.72
#Sta/Elev= 30
  4801.6  692.09  4806.5  692.22  4828.9  692.05  4849.0  692.12  4869.2  691.51
  4879.2  691.89  4909.5  691.94  4919.5  691.36  4929.6  690.25  4939.7  687.01
  4949.8  684.51  4959.8  682.79  4975.5  680.82  4980.6  680.82  5000.1  680.21
  5020.3  680.26  5028.3  679.64  5028.6  679.14  5032.1  679.14  5032.3  679.64
  5040.4  680.04  5057.5  679.79  5073.3  680.43  5080.7  680.99  5090.8  684.45
  5100.8  685.45  5131.1  684.91  5139.5  684.97  5144.6  684.51  5162.0  684.23
#Mann=4,-1,0
  4801.6    0.05       0  5028.3   0.033       0  5032.3    0.05       0
  5073.3   0.075       0
Bank Sta=5028.3,5032.3
Exp/Cntr=0.3,0.1

Type RM Length L Ch R = 1,23444,170,170,170
BEGIN DESCRIPTION:
Mapping XS 72454e38
END DESCRIPTION:
XS GIS Cut Line= 3
      2350426.92      7098227.57      2350150.84      7098198.32
      2350043.46      7098274.53
#Sta/Elev= 30
  4792.2  691.12  4810.2  689.79  4840.4  687.02  4850.4  685.95  4860.5  683.93
  4870.6  682.87  4880.6  682.36  4890.7  681.27  4920.8  679.93  4930.9  680.01
  4940.9  680.66  4971.1  680.46  4981.2  679.97  5021.4  679.80  5029.4  679.50
  5029.7  679.00  5033.2  679.00  5033.4  679.50  5041.5  681.00  5051.6  681.69
  5068.2  682.19  5094.6  682.35  5108.9  682.11  5115.5  682.44  5136.4  682.65
  5145.0  683.96  5157.9  685.05  5172.0  685.14  5194.6  684.29  5201.5  684.00
#Mann=4,-1,0
  4792.2    0.05       0  5029.4   0.033       0  5033.4    0.05       0
  5194.6   0.075       0
Bank Sta=5029.4,5033.4
Exp/Cntr=0.3,0.1

Type RM Length L Ch R = 1,23274,266,266,266
BEGIN DESCRIPTION:
Mapping XS 8b4b1478
END DESCRIPTION:
XS GIS Cut Line= 2
      2350338.11      7097884.97      2350032.99      7098270.93
#Sta/Elev= 30
  4763.3  685.90  4787.4  685.13  4795.2  684.53  4808.3  681.29  4822.7  678.57
  4837.1  677.99  4845.2  678.17  4851.6  677.73  4858.9  677.90  4878.4  677.57
  4878.7  677.07  4882.2  677.07  4882.4  677.57  4894.9  679.02  4901.2  677.88
  4909.3  678.39  4936.5  678.88  4950.9  678.33  4959.0  678.79  4965.4  679.56
  4986.4  678.61  5000.6  678.71  5058.4  680.24  5079.2  681.04  5122.5  681.83
  5143.3  681.67  5207.4  684.76  5221.8  684.88  5252.1  683.86  5255.3  683.54
#Mann=4,-1,0
  4763.3    0.05       0  4878.4   0.033       0  4882.4    0.05       0
  5252.1   0.075       0
Bank Sta=4878.4,4882.4
Exp/Cntr=0.3,0.1

Type RM Length L Ch R = 1,23008,202,202,202
BEGIN DESCRIPTION:
Mapping XS ecbca765
END DESCRIPTION:
XS GIS Cut Line= 2
      2350278.53      7097840.12      2349846.30      7097893.43
#Sta/Elev= 30
  4798.8  685.19  4828.5  684.39  4836.1  683.94  4841.2  683.29  4868.9  681.12
  4909.2  679.78  4917.3  678.72  4922.3  678.35  4929.3  677.24  4959.5  675.51
  4969.6  675.39  4979.7  675.58  5003.5  676.52  5020.0  676.02  5028.1  674.58
  5028.3  674.08  5031.8  674.08  5032.1  674.58  5040.1  674.94  5050.2  677.00
  5084.6  678.16  5160.7  679.93  5165.8  679.83  5171.1  680.17  5191.3  680.77
  5201.4  681.42  5211.4  681.69  5221.5  681.24  5230.4  680.02  5234.3  680.02
#Mann=3,-1,0
  4798.8    0.05       0  5028.1   0.033       0  5032.1    0.05       0
Bank Sta=5028.1,5032.1
Exp/Cntr=0.3,0.1

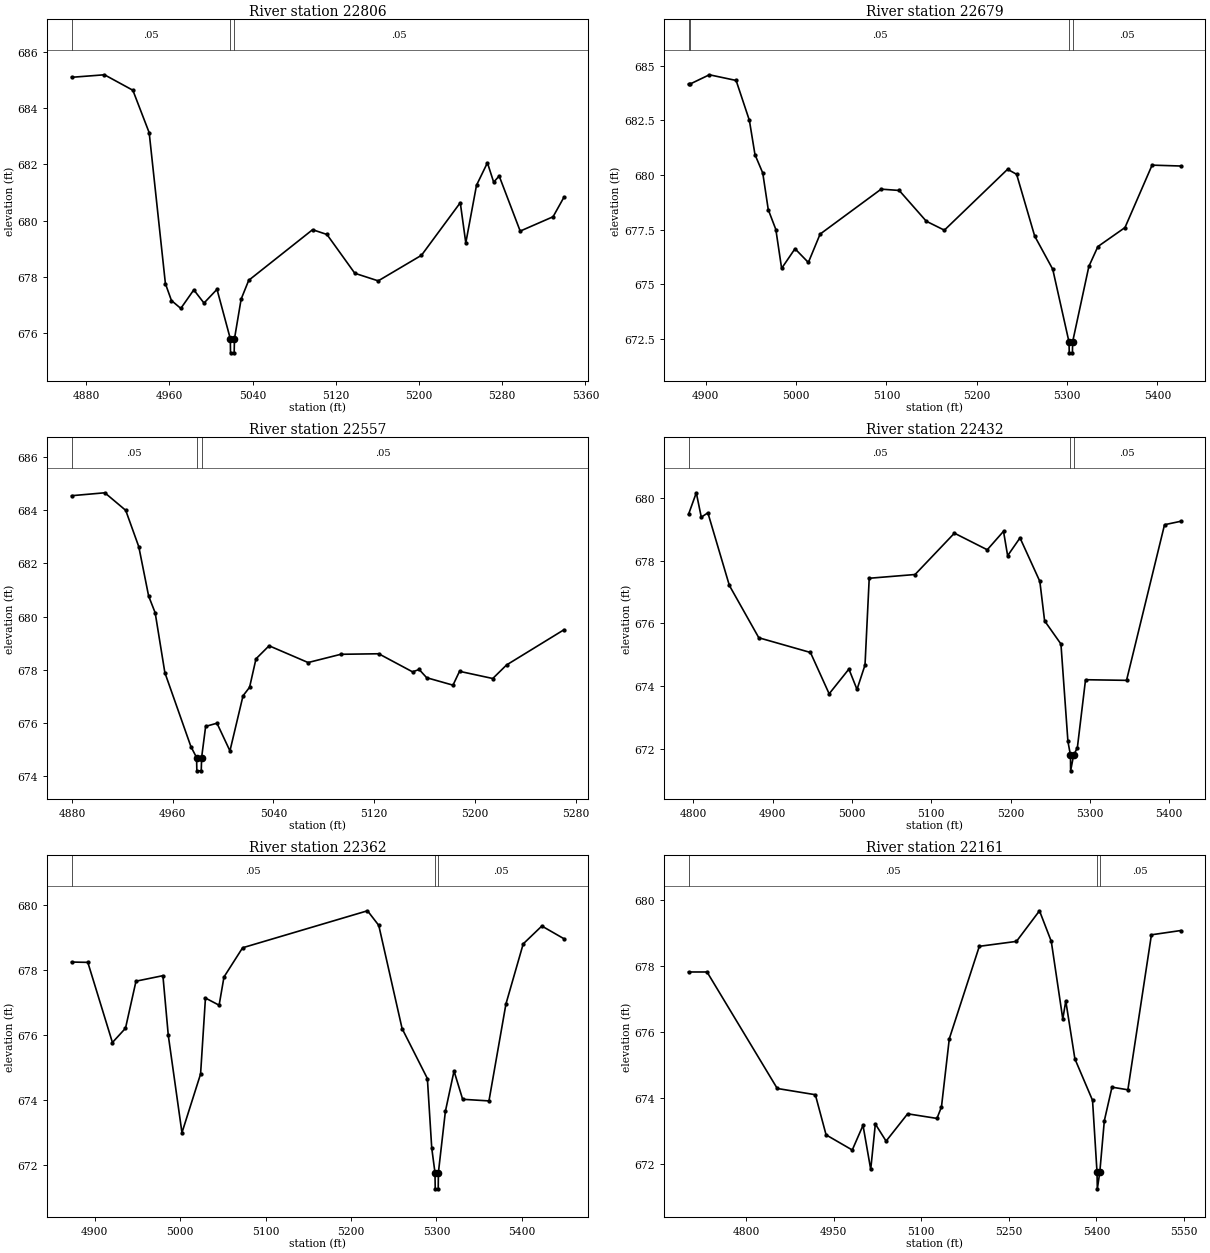
Type RM Length L Ch R = 1,22806,127,127,127
BEGIN DESCRIPTION:
Mapping XS 8fa6e59a
END DESCRIPTION:
XS GIS Cut Line= 3
      2350229.45      7097742.13      2350037.04      7097628.83
      2349799.06      7097705.45
#Sta/Elev= 30
  4866.0  685.10  4897.6  685.19  4924.9  684.64  4940.6  683.13  4956.2  677.76
  4962.0  677.16  4971.0  676.88  4983.5  677.54  4993.3  677.07  5005.8  677.56
  5018.6  675.80  5018.8  675.30  5022.3  675.30  5022.6  675.80  5029.0  677.21
  5036.3  677.88  5097.7  679.68  5111.5  679.51  5138.3  678.13  5160.8  677.86
  5202.4  678.77  5239.7  680.64  5245.0  679.21  5255.3  681.26  5265.8  682.06
  5271.8  681.37  5277.1  681.59  5297.3  679.63  5328.9  680.14  5339.3  680.83
#Mann=3,-1,0
  4866.0    0.05       0  5018.6   0.033       0  5022.6    0.05       0
Bank Sta=5018.6,5022.6
Exp/Cntr=0.3,0.1

Type RM Length L Ch R = 1,22679,122,122,122
BEGIN DESCRIPTION:
Mapping XS 72fcbbe4
END DESCRIPTION:
XS GIS Cut Line= 4
      2350267.87      7097634.80      2350115.13      7097526.55
      2349960.85      7097525.95      2349757.24      7097525.16
#Sta/Elev= 30
  4880.8  684.16  4882.2  684.16  4903.9  684.59  4933.5  684.33  4948.2  682.50
  4954.4  680.93  4963.0  680.09  4969.1  678.41  4977.5  677.50  4983.9  675.72
  4998.7  676.62  5013.5  675.99  5026.5  677.29  5094.1  679.35  5114.1  679.29
  5144.1  677.88  5164.1  677.47  5234.1  680.26  5244.1  680.03  5264.1  677.20
  5284.1  675.68  5302.1  672.35  5302.4  671.85  5305.9  671.85  5306.1  672.35
  5324.1  675.81  5334.1  676.72  5364.1  677.59  5394.1  680.45  5425.9  680.41
#Mann=4,-1,0
  4880.8   0.075       0  4882.2    0.05       0  5302.1   0.033       0
  5306.1    0.05       0
Bank Sta=5302.1,5306.1
Exp/Cntr=0.3,0.1

Type RM Length L Ch R = 1,22557,125,125,125
BEGIN DESCRIPTION:
Mapping XS c88a5861
END DESCRIPTION:
XS GIS Cut Line= 3
      2350340.57      7097491.51      2350133.87      7097436.24
      2349965.19      7097490.34
#Sta/Elev= 30
  4879.6  684.54  4906.0  684.65  4922.6  683.99  4933.0  682.62  4940.8  680.77
  4946.0  680.14  4953.7  677.89  4974.4  675.11  4978.9  674.70  4979.1  674.20
  4982.6  674.20  4982.9  674.70  4986.1  675.87  4995.1  675.99  5005.4  674.95
  5015.8  677.02  5021.0  677.34  5026.1  678.41  5036.5  678.90  5067.5  678.27
  5093.5  678.58  5123.6  678.60  5150.5  677.92  5155.7  678.01  5161.7  677.70
  5182.6  677.42  5187.8  677.94  5214.2  677.67  5225.2  678.18  5270.7  679.50
#Mann=3,-1,0
  4879.6    0.05       0  4978.9   0.033       0  4982.9    0.05       0
Bank Sta=4978.9,4982.9
Exp/Cntr=0.3,0.1

Type RM Length L Ch R = 1,22432,70,70,70
BEGIN DESCRIPTION:
Mapping XS da3cb5eb
END DESCRIPTION:
XS GIS Cut Line= 5
      2350361.32      7097219.05      2350303.58      7097296.28
      2350233.17      7097337.00      2350144.32      7097351.30
      2349802.75      7097439.78
#Sta/Elev= 30
  4794.0  679.48  4803.8  680.17  4810.1  679.39  4818.4  679.53  4845.5  677.21
  4882.6  675.54  4947.7  675.07  4971.3  673.75  4996.2  674.54  5006.4  673.89
  5016.5  674.67  5021.8  677.44  5079.6  677.56  5129.2  678.88  5170.6  678.35
  5191.1  678.94  5196.3  678.16  5211.9  678.73  5236.9  677.34  5242.9  676.08
  5263.5  675.34  5272.3  672.23  5275.5  671.79  5275.7  671.29  5279.5  671.79
  5284.2  672.03  5294.5  674.20  5346.2  674.18  5394.1  679.15  5414.6  679.26
#Mann=3,-1,0
  4794.0    0.05       0  5275.5   0.033       0  5279.5    0.05       0
Bank Sta=5275.5,5279.5
Exp/Cntr=0.3,0.1

Type RM Length L Ch R = 1,22362,201,201,201
BEGIN DESCRIPTION:
Mapping XS 5ca2fd52
END DESCRIPTION:
XS GIS Cut Line= 6
      2350306.90      7097201.52      2350260.56      7097238.63
      2350143.91      7097303.27      2350058.54      7097352.82
      2350035.58      7097368.97      2349782.03      7097409.64
#Sta/Elev= 30
  4872.9  678.25  4891.9  678.24  4920.7  675.77  4936.0  676.21  4948.3  677.66
  4979.8  677.83  4986.1  675.99  5002.1  672.99  5023.9  674.80  5029.6  677.14
  5045.6  676.92  5051.3  677.79  5073.1  678.69  5219.3  679.83  5232.5  679.38
  5259.8  676.20  5289.4  674.66  5294.5  672.52  5298.3  671.76  5298.6  671.26
  5302.1  671.26  5302.3  671.76  5310.5  673.65  5320.6  674.89  5330.7  674.02
  5361.5  673.97  5381.4  676.96  5401.6  678.81  5423.4  679.36  5449.2  678.97
#Mann=3,-1,0
  4872.9    0.05       0  5298.3    0.05       0  5302.3    0.05       0
Bank Sta=5298.3,5302.3
Exp/Cntr=0.3,0.1

Type RM Length L Ch R = 1,22161,230,230,230
BEGIN DESCRIPTION:
Mapping XS dfefcd65
END DESCRIPTION:
XS GIS Cut Line= 5
      2350346.18      7096882.33      2350211.28      7097018.36
      2350127.98      7097267.62      2350040.96      7097356.40
      2349779.17      7097390.47
#Sta/Elev= 30
  4701.7  677.82  4733.4  677.82  4853.6  674.28  4918.8  674.09  4937.2  672.87
  4982.0  672.41  5000.4  673.16  5013.6  671.82  5021.5  673.20  5039.9  672.68
  5076.8  673.51  5127.0  673.37  5134.7  673.72  5148.1  675.79  5199.5  678.60
  5263.1  678.75  5302.5  679.68  5322.7  678.75  5342.4  676.39  5347.5  676.94
  5363.1  675.18  5393.3  673.92  5401.0  671.73  5401.5  671.23  5405.7  671.73
  5413.5  673.30  5426.6  674.32  5453.8  674.24  5494.1  678.95  5544.4  679.08
#Mann=3,-1,0
  4701.7    0.05       0  5401.0    0.05       0  5405.7    0.05       0
Bank Sta=5401,5405.7
Exp/Cntr=0.3,0.1

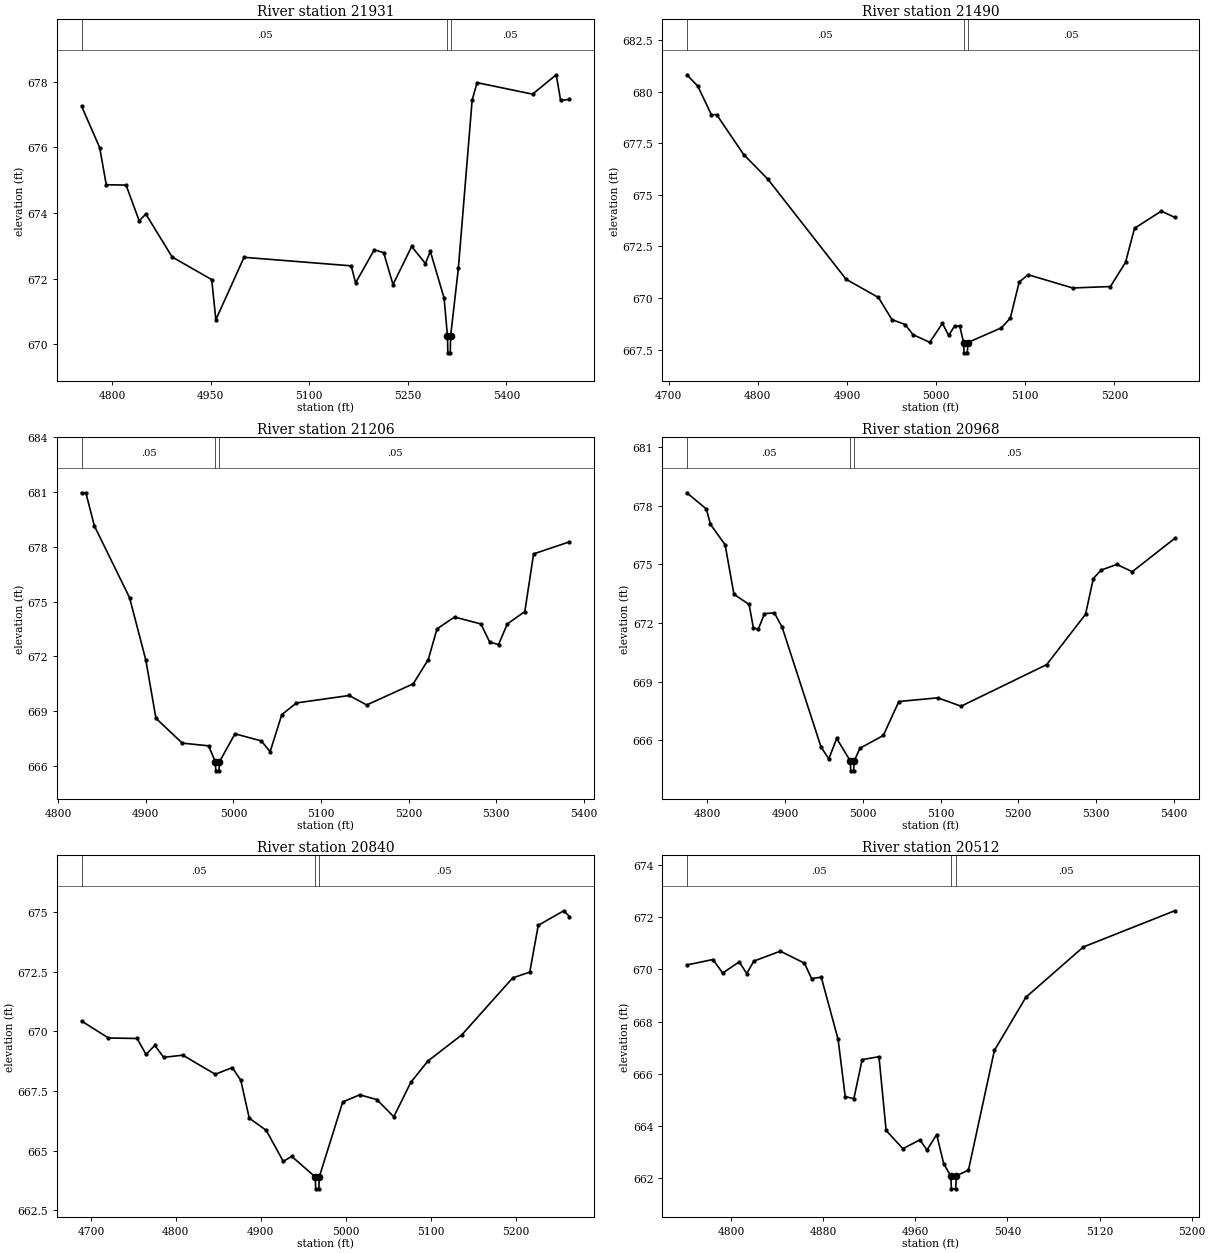
Type RM Length L Ch R = 1,21931,441,441,441
BEGIN DESCRIPTION:
Mapping XS d78ff5f2
END DESCRIPTION:
XS GIS Cut Line= 3
      2350286.42      7096889.83      2350081.43      7096903.62
      2349724.28      7097304.16
#Sta/Elev= 30
  4753.7  677.25  4781.2  675.99  4791.2  674.86  4821.3  674.85  4841.3  673.76
  4851.3  673.97  4891.4  672.66  4951.6  671.97  4957.9  670.75  5000.8  672.65
  5163.8  672.39  5170.5  671.87  5198.9  672.88  5213.2  672.79  5227.4  671.82
  5255.8  672.98  5276.7  672.46  5284.2  672.83  5305.1  671.41  5310.3  670.24
  5310.8  669.74  5314.5  669.74  5315.0  670.24  5326.8  672.31  5347.8  677.44
  5355.3  677.97  5439.7  677.62  5475.7  678.21  5482.4  677.43  5495.8  677.46
#Mann=3,-1,0
  4753.7    0.05       0  5310.3   0.033       0  5315.0    0.05       0
Bank Sta=5310.3,5315
Exp/Cntr=0.3,0.1

Type RM Length L Ch R = 1,21490,284,284,284
BEGIN DESCRIPTION:
Mapping XS 0c00aa88
END DESCRIPTION:
XS GIS Cut Line= 5
      2349850.50      7096544.41      2349711.74      7096759.20
      2349675.63      7096794.27      2349506.65      7096793.13
      2349502.15      7096864.96
#Sta/Elev= 30
  4720.5  680.81  4732.8  680.26  4748.0  678.88  4753.9  678.88  4784.2  676.95
  4811.3  675.76  4899.1  670.91  4935.3  670.03  4950.5  668.96  4965.3  668.72
  4974.1  668.23  4992.9  667.86  5007.1  668.78  5014.1  668.19  5020.7  668.65
  5026.5  668.65  5030.8  667.85  5031.3  667.35  5035.0  667.35  5035.6  667.85
  5073.2  668.56  5083.2  669.03  5093.2  670.78  5103.2  671.13  5153.2  670.49
  5195.5  670.56  5212.4  671.73  5222.5  673.38  5252.5  674.21  5267.5  673.91
#Mann=3,-1,0
  4720.5    0.05       0  5030.8   0.033       0  5035.6    0.05       0
Bank Sta=5030.8,5035.6
Exp/Cntr=0.3,0.1

Type RM Length L Ch R = 1,21206,238,238,238
BEGIN DESCRIPTION:
Mapping XS e9f54988
END DESCRIPTION:
XS GIS Cut Line= 2
      2349519.13      7096415.41      2349481.96      7096970.77
#Sta/Elev= 30
  4826.8  680.96  4831.6  680.96  4841.4  679.14  4881.5  675.21  4900.1  671.78
  4911.6  668.60  4941.6  667.24  4971.7  667.09  4979.3  666.22  4979.9  665.72
  4983.6  665.72  4984.1  666.22  5001.8  667.75  5031.8  667.36  5041.9  666.77
  5055.2  668.80  5071.9  669.44  5132.1  669.85  5152.1  669.33  5205.2  670.49
  5222.3  671.82  5232.3  673.50  5252.3  674.15  5282.4  673.77  5292.4  672.78
  5302.5  672.64  5312.5  673.77  5332.5  674.45  5342.5  677.61  5383.4  678.27
#Mann=3,-1,0
  4826.8    0.05       0  4979.3    0.04       0  4984.1    0.05       0
Bank Sta=4979.3,4984.1
Exp/Cntr=0.3,0.1

Type RM Length L Ch R = 1,20968,128,128,128
BEGIN DESCRIPTION:
Mapping XS 2e30aff3
END DESCRIPTION:
XS GIS Cut Line= 3
      2349323.77      7096303.99      2349287.68      7096399.65
      2349305.50      7096924.50
#Sta/Elev= 30
  4773.7  678.67  4798.8  677.84  4804.1  677.05  4822.9  676.01  4834.3  673.47
  4853.8  672.95  4859.2  671.76  4865.6  671.68  4873.5  672.48  4886.3  672.52
  4896.3  671.78  4946.3  665.65  4956.3  665.04  4966.4  666.09  4984.0  664.93
  4984.5  664.43  4988.2  664.43  4988.8  664.93  4996.4  665.59  5026.4  666.24
  5046.4  667.98  5096.4  668.17  5126.4  667.74  5236.5  669.87  5286.5  672.45
  5296.5  674.28  5306.5  674.71  5326.6  675.00  5346.6  674.63  5401.1  676.33
#Mann=3,-1,0
  4773.7    0.05       0  4984.0   0.033       0  4988.8    0.05       0
Bank Sta=4984,4988.8
Exp/Cntr=0.3,0.1

Type RM Length L Ch R = 1,20840,328,328,328
BEGIN DESCRIPTION:
Mapping XS c074d538
END DESCRIPTION:
XS GIS Cut Line= 3
      2349223.46      7096287.19      2349191.54      7096398.51
      2349201.36      7096856.70
#Sta/Elev= 30
  4689.1  670.43  4720.7  669.72  4754.4  669.70  4764.9  669.03  4775.2  669.41
  4785.7  668.91  4808.2  669.00  4846.4  668.20  4866.4  668.48  4876.4  667.95
  4886.4  666.36  4906.4  665.85  4926.4  664.55  4936.4  664.76  4964.0  663.90
  4964.6  663.40  4968.3  663.40  4968.8  663.90  4996.4  667.04  5016.4  667.34
  5036.5  667.14  5056.5  666.42  5076.5  667.86  5096.5  668.75  5136.5  669.85
  5196.5  672.24  5216.5  672.48  5226.5  674.44  5256.5  675.05  5263.2  674.81
#Mann=3,-1,0
  4689.1    0.05       0  4964.0    0.04       0  4968.8    0.05       0
Bank Sta=4964,4968.8
Exp/Cntr=0.3,0.1

Type RM Length L Ch R = 1,20512,220,220,220
BEGIN DESCRIPTION:
Mapping XS 5e1597b7
END DESCRIPTION:
XS GIS Cut Line= 2
      2349055.00      7096303.38      2348803.23      7096643.91
#Sta/Elev= 30
  4761.7  670.17  4784.4  670.38  4792.8  669.86  4807.2  670.29  4813.7  669.84
  4819.9  670.32  4842.9  670.70  4863.8  670.24  4870.0  669.65  4878.4  669.70
  4893.0  667.32  4899.2  665.12  4906.7  665.04  4913.9  666.54  4928.5  666.65
  4934.7  663.82  4949.3  663.12  4964.0  663.46  4970.2  663.07  4978.6  663.66
  4984.8  662.53  4990.8  662.08  4991.4  661.58  4995.1  661.58  4995.7  662.08
  5006.2  662.30  5028.7  666.89  5056.0  668.93  5105.9  670.86  5185.2  672.25
#Mann=3,-1,0
  4761.7    0.05       0  4990.8    0.04       0  4995.7    0.05       0
Bank Sta=4990.8,4995.7
Exp/Cntr=0.3,0.1