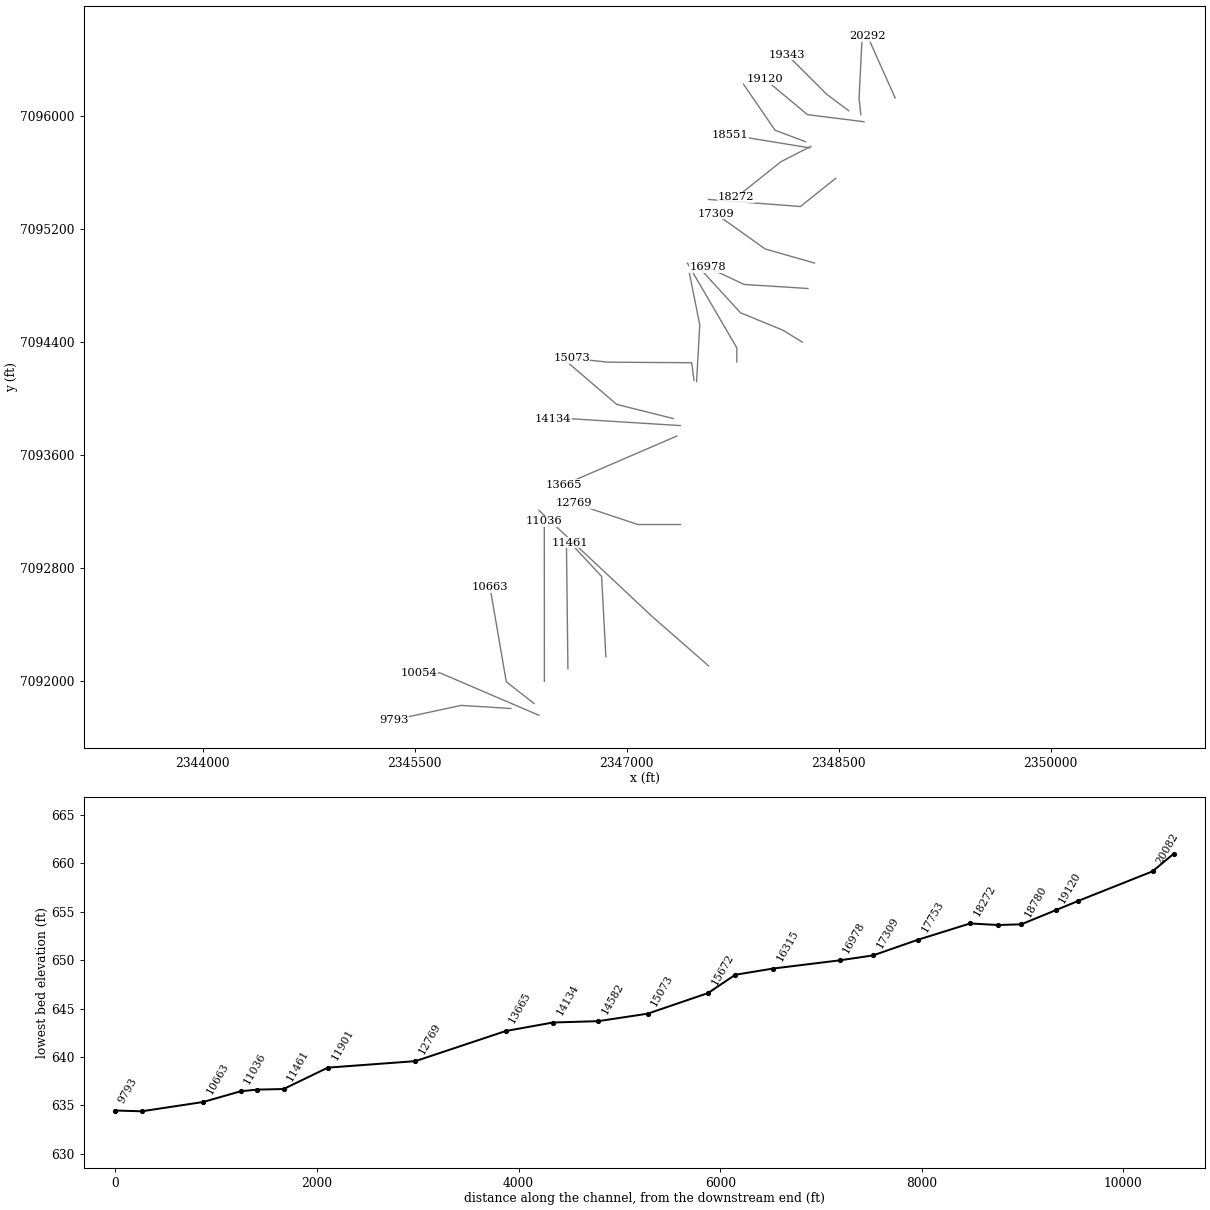
HEC-RAS study Denton Creek Tributary 14.prj: Denton Creek Tributary 14 Base Level Engineering

--- Denton Creek Tributary 14.g01 (geometry) --- (continued)

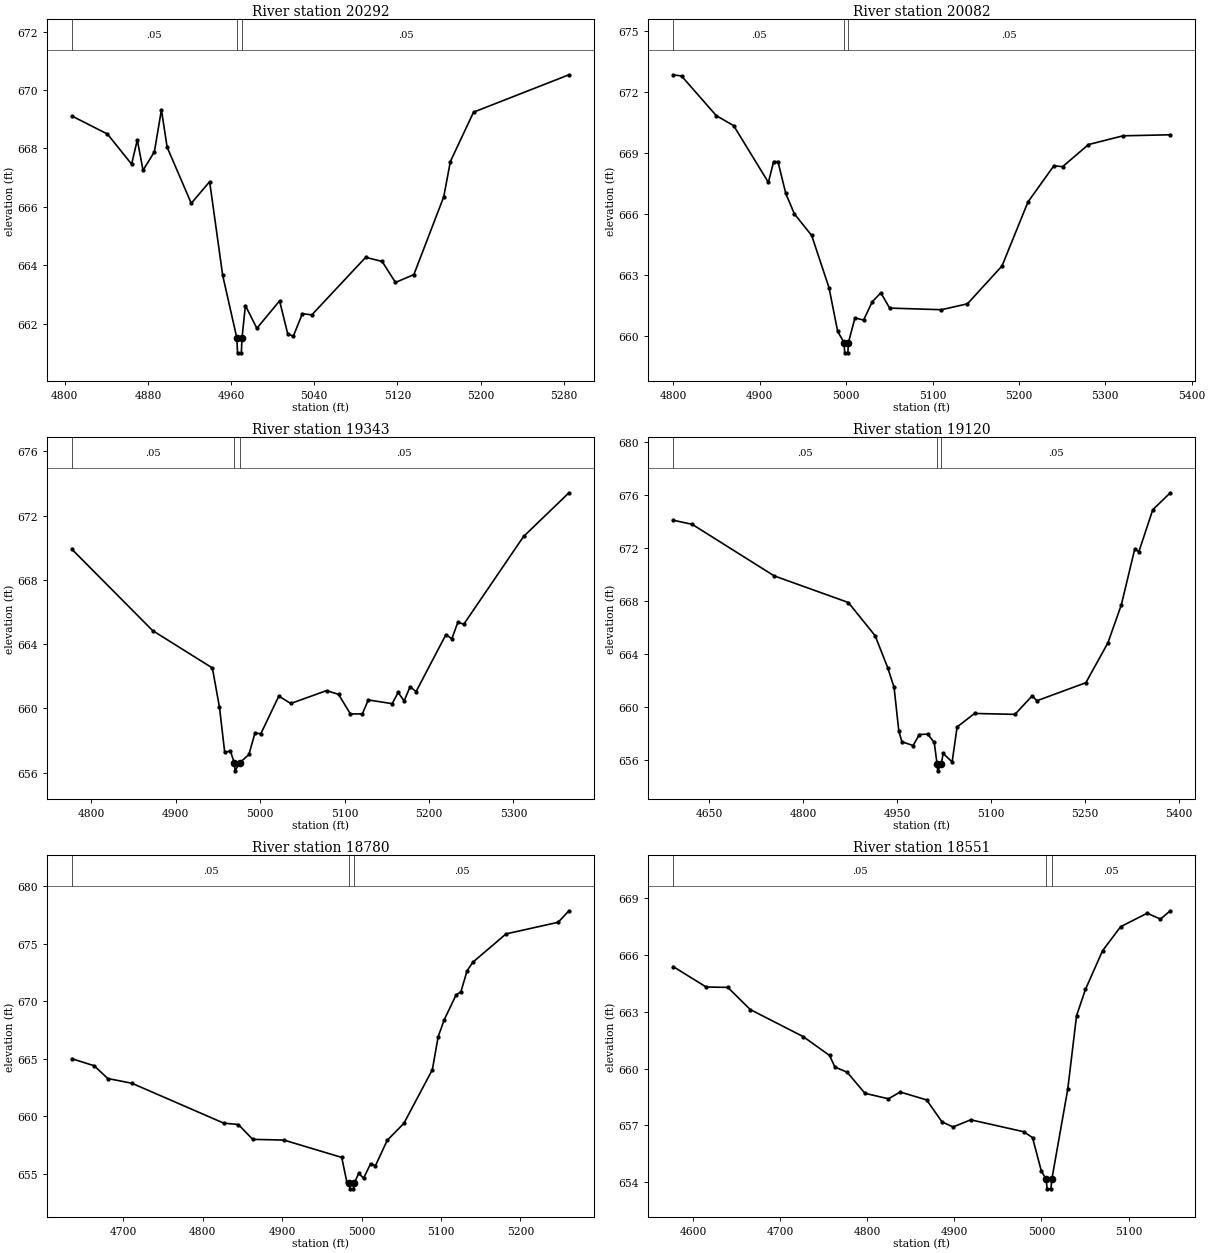
Type RM Length L Ch R = 1,20292,210,210,210
BEGIN DESCRIPTION:
Mapping XS 110f6367
END DESCRIPTION:
XS GIS Cut Line= 2
      2348899.73      7096127.54      2348704.45      7096564.15
#Sta/Elev= 30
  4806.8  669.11  4841.1  668.49  4864.3  667.46  4869.8  668.29  4875.3  667.25
  4886.2  667.88  4893.0  669.32  4898.5  668.04  4921.7  666.12  4939.4  666.86
  4951.9  663.66  4965.6  661.50  4966.2  661.00  4969.9  661.00  4970.5  661.50
  4973.8  662.62  4984.8  661.84  5006.7  662.78  5014.5  661.65  5019.9  661.57
  5028.6  662.34  5037.7  662.30  5089.5  664.27  5105.3  664.13  5118.2  663.41
  5135.9  663.68  5164.6  666.34  5171.0  667.55  5193.3  669.24  5285.1  670.52
#Mann=3,-1,0
  4806.8    0.05       0  4965.6    0.04       0  4970.5    0.05       0
Bank Sta=4965.6,4970.5
Exp/Cntr=0.3,0.1

Type RM Length L Ch R = 1,20082,739,739,739
BEGIN DESCRIPTION:
Mapping XS f59ce027
END DESCRIPTION:
XS GIS Cut Line= 3
      2348656.36      7096010.36      2348644.05      7096127.11
      2348667.05      7096584.53
#Sta/Elev= 30
  4799.8  672.85  4809.5  672.79  4849.7  670.84  4869.8  670.35  4910.0  667.56
  4916.1  668.58  4921.1  668.58  4930.1  667.02  4940.1  666.01  4960.1  664.95
  4980.2  662.38  4990.2  660.23  4997.7  659.68  4998.3  659.18  5002.0  659.18
  5002.6  659.68  5010.2  660.90  5020.2  660.79  5030.2  661.69  5040.2  662.13
  5050.3  661.38  5110.3  661.30  5140.4  661.59  5180.4  663.45  5210.5  666.60
  5240.5  668.38  5250.5  668.33  5280.5  669.42  5320.6  669.85  5375.2  669.90
#Mann=3,-1,0
  4799.8    0.05       0  4997.7   0.033       0  5002.6    0.05       0
Bank Sta=4997.7,5002.6
Exp/Cntr=0.3,0.1

Type RM Length L Ch R = 1,19343,223,223,223
BEGIN DESCRIPTION:
Mapping XS 93a07a1f
END DESCRIPTION:
XS GIS Cut Line= 3
      2348570.78      7096037.95      2348416.47      7096152.99
      2348135.63      7096432.78
#Sta/Elev= 30
  4776.9  669.91  4872.5  664.85  4943.4  662.52  4951.8  660.07  4958.0  657.27
  4964.7  657.36  4969.3  656.62  4970.3  656.12  4975.8  656.62  4986.7  657.14
  4993.8  658.47  5000.8  658.43  5022.1  660.77  5036.2  660.31  5078.6  661.11
  5092.8  660.88  5106.9  659.66  5121.0  659.66  5128.1  660.53  5156.4  660.30
  5163.4  661.00  5170.5  660.47  5177.6  661.35  5184.7  661.05  5220.0  664.59
  5227.1  664.34  5234.2  665.37  5241.2  665.24  5312.0  670.70  5365.8  673.42
#Mann=3,-1,0
  4776.9    0.05       0  4969.3   0.033       0  4975.8    0.05       0
Bank Sta=4969.3,4975.8
Exp/Cntr=0.3,0.1

Type RM Length L Ch R = 1,19120,340,340,340
BEGIN DESCRIPTION:
Denton Creek Tributary 14 34.0
END DESCRIPTION:
XS GIS Cut Line= 3
      2348679.03      7095960.00      2348279.00      7096010.00
      2347978.96      7096260.03
#Sta/Elev= 30
  4592.4  674.07  4622.7  673.76  4753.7  669.87  4872.1  667.86  4914.9  665.35
  4935.1  662.92  4945.1  661.45  4952.7  658.14  4957.7  657.35  4975.4  657.07
  4985.5  657.90  4998.8  657.93  5009.2  657.30  5013.8  655.66  5014.8  655.16
  5020.3  655.66  5023.5  656.47  5037.8  655.83  5045.7  658.47  5073.6  659.49
  5138.1  659.42  5165.4  660.81  5173.2  660.45  5251.3  661.81  5286.5  664.82
  5307.9  667.68  5329.4  671.91  5335.9  671.69  5358.1  674.86  5386.1  676.14
#Mann=3,-1,0
  4592.4    0.05       0  5013.8   0.033       0  5020.3    0.05       0
Bank Sta=5013.8,5020.3
Exp/Cntr=0.3,0.1

Type RM Length L Ch R = 1,18780,229,229,229
BEGIN DESCRIPTION:
Mapping XS 75fb4ab6
END DESCRIPTION:
XS GIS Cut Line= 3
      2348265.28      7095818.75      2348050.14      7095899.33
      2347826.07      7096225.79
#Sta/Elev= 30
  4635.4  665.02  4663.5  664.41  4680.6  663.30  4710.9  662.89  4826.6  659.42
  4845.0  659.30  4863.1  658.01  4902.3  657.95  4975.1  656.44  4981.6  654.28
  4984.4  654.21  4985.5  653.71  4989.9  653.71  4990.9  654.21  4996.5  655.06
  5002.6  654.63  5011.4  655.89  5017.5  655.72  5032.4  657.93  5053.3  659.40
  5089.2  664.07  5096.4  666.91  5104.1  668.41  5119.0  670.56  5125.1  670.84
  5132.8  672.65  5140.0  673.40  5181.9  675.87  5247.5  676.88  5261.1  677.88
#Mann=3,-1,0
  4635.4    0.05       0  4984.4    0.04       0  4990.9    0.05       0
Bank Sta=4984.4,4990.9
Exp/Cntr=0.3,0.1

Type RM Length L Ch R = 1,18551,279,279,279
BEGIN DESCRIPTION:
Mapping XS 674ac3b7
END DESCRIPTION:
XS GIS Cut Line= 2
      2348296.39      7095774.96      2347732.72      7095866.79
#Sta/Elev= 30
  4576.9  665.39  4614.8  664.31  4639.7  664.29  4665.4  663.12  4726.2  661.69
  4756.6  660.69  4762.7  660.08  4776.9  659.80  4797.2  658.69  4824.2  658.40
  4837.7  658.76  4868.1  658.34  4885.7  657.18  4898.5  656.91  4918.7  657.29
  4979.5  656.66  4989.7  656.35  4999.8  654.59  5005.4  654.14  5006.5  653.64
  5010.9  653.64  5011.9  654.14  5030.2  658.91  5040.3  662.79  5050.5  664.18
  5070.2  666.23  5091.0  667.50  5121.4  668.21  5136.7  667.90  5148.0  668.34
#Mann=3,-1,0
  4576.9    0.05       0  5005.4    0.04       0  5011.9    0.05       0
Bank Sta=5005.4,5011.9
Exp/Cntr=0.3,0.1

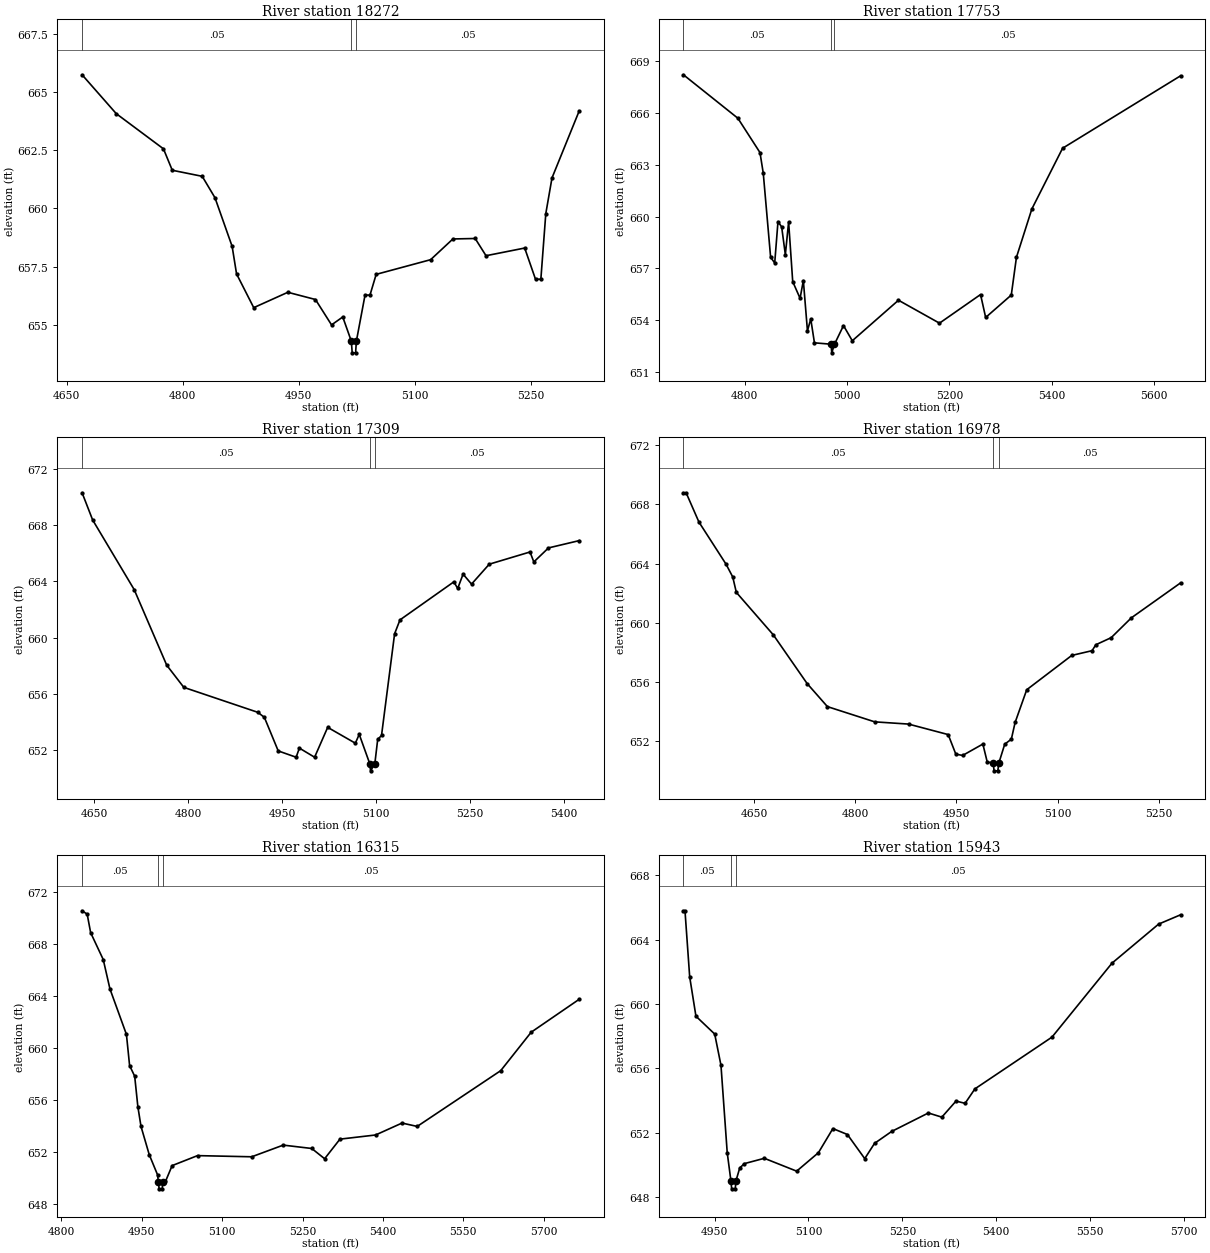
Type RM Length L Ch R = 1,18272,519,519,519
BEGIN DESCRIPTION:
Mapping XS 5729a58d
END DESCRIPTION:
XS GIS Cut Line= 3
      2348302.82      7095785.44      2348089.92      7095676.43
      2347774.93      7095424.23
#Sta/Elev= 30
  4670.0  665.74  4714.2  664.07  4775.2  662.56  4786.6  661.64  4825.3  661.38
  4841.8  660.46  4864.0  658.37  4869.7  657.19  4891.9  655.74  4936.0  656.40
  4971.7  656.09  4992.5  655.00  5007.0  655.34  5018.1  654.30  5019.2  653.80
  5023.6  653.80  5024.6  654.30  5035.8  656.28  5042.2  656.28  5050.2  657.17
  5120.6  657.80  5149.4  658.69  5178.2  658.71  5192.2  657.97  5242.2  658.30
  5256.2  656.96  5263.1  656.96  5269.5  659.78  5277.5  661.31  5312.7  664.19
#Mann=3,-1,0
  4670.0    0.05       0  5018.1   0.033       0  5024.6    0.05       0
Bank Sta=5018.1,5024.6
Exp/Cntr=0.3,0.1

Type RM Length L Ch R = 1,17753,444,444,444
BEGIN DESCRIPTION:
Denton Creek Tributary 14 32.0
END DESCRIPTION:
XS GIS Cut Line= 3
      2348479.02      7095560.02      2348229.00      7095360.00
      2347579.01      7095410.00
#Sta/Elev= 30
  4680.0  668.23  4786.5  665.71  4829.7  663.72  4836.1  662.53  4850.5  657.65
  4858.5  657.32  4864.9  659.72  4872.1  659.41  4879.3  657.80  4885.7  659.70
  4893.7  656.24  4908.1  655.27  4914.5  656.30  4922.5  653.39  4929.0  654.07
  4936.2  652.69  4968.9  652.61  4970.0  652.11  4975.4  652.61  4993.0  653.69
  5010.2  652.81  5100.5  655.16  5180.7  653.83  5261.0  655.49  5271.0  654.16
  5321.1  655.46  5331.2  657.65  5361.3  660.45  5421.4  663.97  5652.1  668.17
#Mann=3,-1,0
  4680.0    0.05       0  4968.9   0.033       0  4975.4    0.05       0
Bank Sta=4968.9,4975.4
Exp/Cntr=0.3,0.1

Type RM Length L Ch R = 1,17309,331,331,331
BEGIN DESCRIPTION:
Denton Creek Tributary 14 31.0
END DESCRIPTION:
XS GIS Cut Line= 3
      2348329.03      7094959.99      2347979.00      7095060.00
      2347629.04      7095309.97
#Sta/Elev= 30
  4630.8  670.32  4647.7  668.38  4714.0  663.42  4766.0  658.03  4793.3  656.45
  4911.6  654.67  4922.0  654.31  4944.1  651.92  4972.7  651.47  4977.9  652.12
  5002.2  651.47  5023.1  653.60  5067.3  652.47  5073.5  653.10  5090.4  651.00
  5091.6  650.50  5098.4  651.00  5103.0  652.74  5109.1  653.02  5130.0  660.27
  5138.6  661.26  5224.6  663.97  5230.8  663.50  5239.4  664.52  5252.9  663.81
  5281.2  665.23  5346.3  666.10  5352.4  665.39  5375.8  666.39  5424.9  666.91
#Mann=3,-1,0
  4630.8    0.05       0  5090.4   0.033       0  5098.4    0.05       0
Bank Sta=5090.4,5098.4
Exp/Cntr=0.3,0.1

Type RM Length L Ch R = 1,16978,663,663,663
BEGIN DESCRIPTION:
Mapping XS 151633e1
END DESCRIPTION:
XS GIS Cut Line= 3
      2348281.94      7094780.04      2347831.36      7094808.49
      2347573.03      7094929.64
#Sta/Elev= 30
  4545.5  668.78  4549.5  668.78  4568.5  666.80  4608.6  663.96  4618.6  663.09
  4623.9  662.05  4678.7  659.18  4728.8  655.89  4758.9  654.33  4829.0  653.30
  4879.1  653.15  4937.9  652.44  4949.2  651.12  4959.3  651.03  4989.3  651.80
  4995.7  650.60  5004.7  650.49  5005.9  649.99  5011.5  649.99  5012.8  650.49
  5021.7  651.79  5031.5  652.13  5037.1  653.26  5054.3  655.47  5121.1  657.79
  5151.2  658.11  5156.7  658.51  5179.5  658.99  5209.4  660.33  5282.3  662.69
#Mann=3,-1,0
  4545.5    0.05       0  5004.7    0.04       0  5012.8    0.05       0
Bank Sta=5004.7,5012.8
Exp/Cntr=0.3,0.1

Type RM Length L Ch R = 1,16315,372,372,372
BEGIN DESCRIPTION:
Mapping XS 71187492
END DESCRIPTION:
XS GIS Cut Line= 4
      2348242.66      7094400.39      2348106.18      7094484.48
      2347805.31      7094608.19      2347506.45      7094934.50
#Sta/Elev= 30
  4838.5  670.57  4848.0  670.31  4854.5  668.88  4878.0  666.81  4890.5  664.55
  4921.3  661.04  4927.2  658.64  4936.7  657.82  4942.6  655.48  4948.5  653.95
  4963.9  651.77  4979.3  650.23  4981.1  649.64  4982.3  649.14  4988.0  649.14
  4989.2  649.64  4994.2  649.71  5006.6  650.93  5054.0  651.70  5155.2  651.61
  5214.0  652.51  5267.3  652.25  5291.3  651.46  5319.9  652.97  5386.4  653.29
  5435.8  654.21  5464.1  653.95  5620.1  658.25  5676.9  661.21  5766.6  663.75
#Mann=3,-1,0
  4838.5    0.05       0  4981.1   0.033       0  4989.2    0.05       0
Bank Sta=4981.1,4989.2
Exp/Cntr=0.3,0.1

Type RM Length L Ch R = 1,15943,271,271,271
BEGIN DESCRIPTION:
Denton Creek Tributary 14 29.0
END DESCRIPTION:
XS GIS Cut Line= 3
      2347779.00      7094260.01      2347779.00      7094360.00
      2347429.01      7094959.99
#Sta/Elev= 30
  4900.1  665.80  4902.6  665.80  4910.1  661.69  4920.1  659.24  4950.1  658.13
  4960.1  656.19  4970.1  650.75  4976.0  649.00  4977.2  648.50  4982.9  648.50
  4984.1  649.00  4990.1  649.80  4997.6  650.07  5029.4  650.40  5081.1  649.60
  5115.9  650.75  5139.0  652.25  5162.2  651.88  5189.9  650.38  5205.6  651.33
  5232.9  652.07  5291.6  653.22  5313.1  652.96  5335.8  653.96  5350.3  653.82
  5366.0  654.72  5489.2  657.94  5585.1  662.54  5659.6  664.97  5694.7  665.55
#Mann=3,-1,0
  4900.1    0.05       0  4976.0    0.04       0  4984.1    0.05       0
Bank Sta=4976,4984.1
Exp/Cntr=0.3,0.1

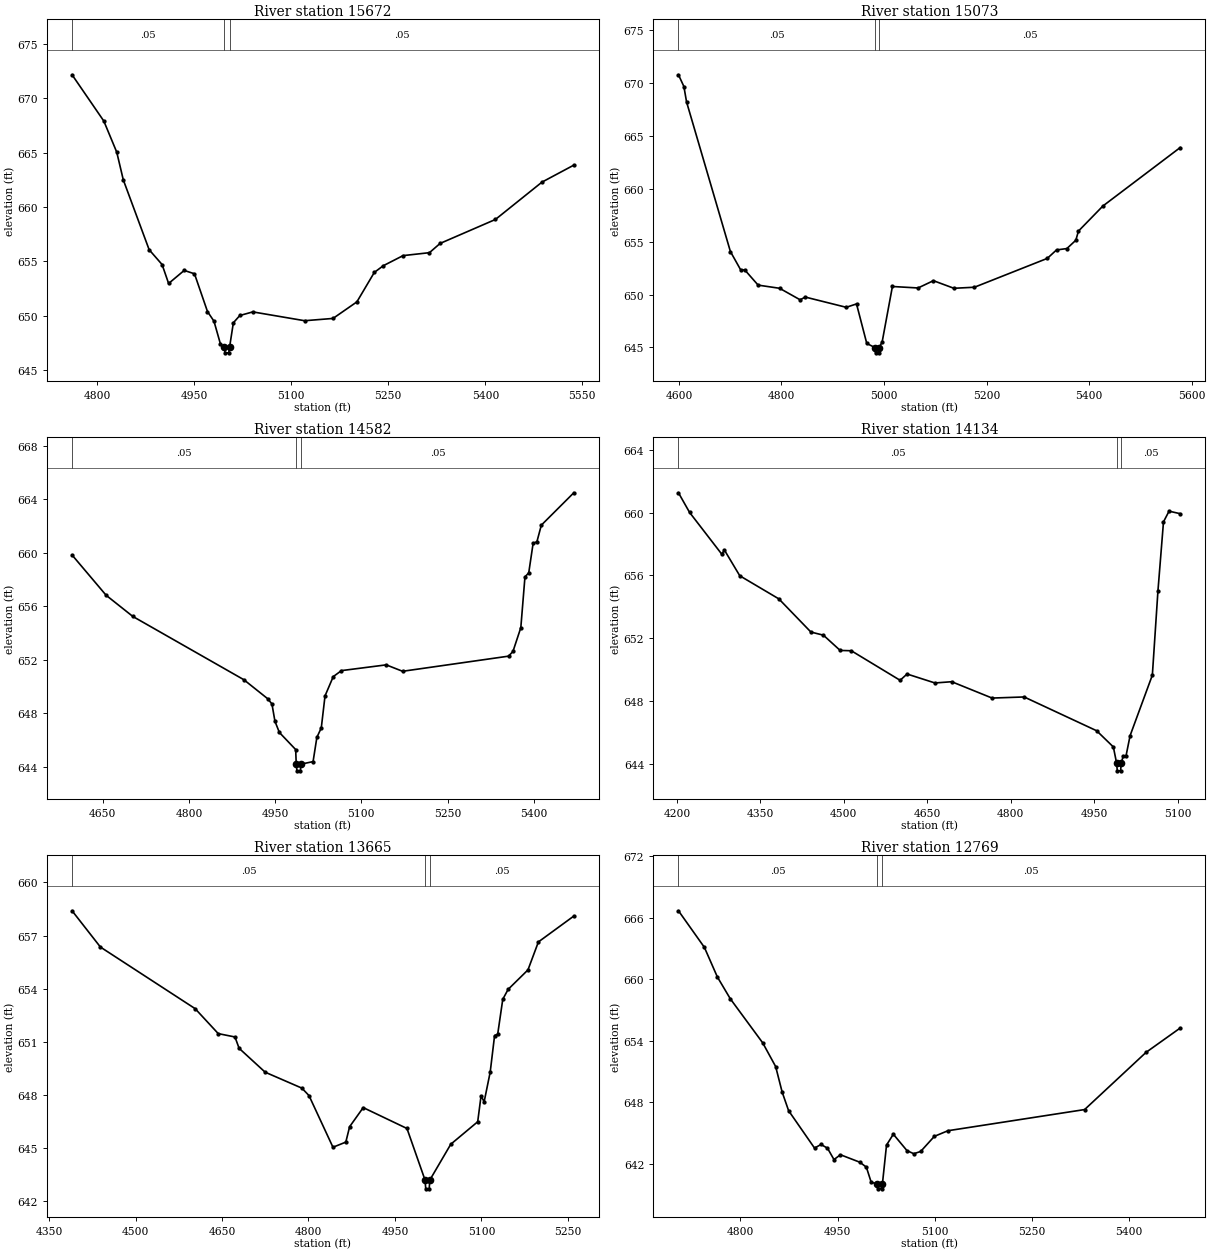
Type RM Length L Ch R = 1,15672,599,599,599
BEGIN DESCRIPTION:
Mapping XS e412bd62
END DESCRIPTION:
XS GIS Cut Line= 3
      2347494.35      7094120.97      2347516.92      7094523.84
      2347443.40      7094888.81
#Sta/Elev= 30
  4761.0  672.15  4810.1  667.90  4830.1  665.04  4840.2  662.50  4880.2  656.08
  4900.2  654.72  4910.3  652.98  4934.4  654.18  4950.3  653.87  4970.4  650.40
  4980.4  649.52  4990.4  647.43  4996.4  647.11  4997.6  646.61  5003.3  646.61
  5004.5  647.11  5010.4  649.37  5020.4  650.04  5040.5  650.37  5120.6  649.56
  5164.5  649.77  5201.4  651.29  5228.4  654.00  5242.2  654.61  5272.8  655.54
  5313.6  655.81  5330.1  656.66  5415.6  658.86  5487.6  662.29  5536.8  663.85
#Mann=3,-1,0
  4761.0    0.05       0  4996.4    0.04       0  5004.5    0.05       0
Bank Sta=4996.4,5004.5
Exp/Cntr=0.3,0.1

Type RM Length L Ch R = 1,15073,491,491,491
BEGIN DESCRIPTION:
Mapping XS 1b06758e
END DESCRIPTION:
XS GIS Cut Line= 4
      2347476.03      7094129.48      2347459.99      7094254.79
      2346869.87      7094258.66      2346609.15      7094285.89
#Sta/Elev= 30
  4599.1  670.80  4609.7  669.69  4614.9  668.23  4700.4  654.07  4720.5  652.33
  4728.4  652.33  4754.5  650.89  4796.4  650.59  4836.4  649.50  4846.4  649.76
  4926.4  648.79  4946.4  649.11  4966.4  645.37  4982.3  644.98  4983.5  644.48
  4989.3  644.48  4990.5  644.98  4996.4  645.51  5016.4  650.76  5066.4  650.62
  5096.4  651.31  5136.4  650.59  5176.4  650.69  5318.5  653.42  5336.5  654.22
  5356.7  654.35  5374.2  655.14  5379.2  656.00  5427.0  658.38  5577.7  663.91
#Mann=3,-1,0
  4599.1    0.05       0  4982.3    0.04       0  4990.5    0.05       0
Bank Sta=4982.3,4990.5
Exp/Cntr=0.3,0.1

Type RM Length L Ch R = 1,14582,448,448,448
BEGIN DESCRIPTION:
Denton Creek Tributary 14 26.0
END DESCRIPTION:
XS GIS Cut Line= 3
      2347329.04      7093859.99      2346929.00      7093960.00
      2346579.03      7094259.98
#Sta/Elev= 30
  4596.5  659.84  4655.8  656.83  4702.2  655.25  4895.5  650.52  4936.7  649.11
  4944.4  648.71  4949.6  647.42  4957.3  646.58  4985.7  645.30  4986.7  644.21
  4987.9  643.71  4993.8  643.71  4995.0  644.21  5016.0  644.40  5022.6  646.21
  5030.3  646.92  5036.8  649.31  5051.1  650.75  5065.4  651.20  5143.3  651.63
  5171.8  651.15  5356.2  652.28  5363.9  652.63  5377.6  654.41  5384.8  658.20
  5391.4  658.51  5399.0  660.71  5405.6  660.83  5413.3  662.07  5469.8  664.49
#Mann=3,-1,0
  4596.5    0.05       0  4986.7    0.04       0  4995.0    0.05       0
Bank Sta=4986.7,4995
Exp/Cntr=0.3,0.1

Type RM Length L Ch R = 1,14134,469,469,469
BEGIN DESCRIPTION:
Denton Creek Tributary 14 25.0
END DESCRIPTION:
XS GIS Cut Line= 3
      2347379.00      7093810.00      2346579.00      7093860.00
      2346478.96      7093860.00
#Sta/Elev= 30
  4202.8  661.26  4222.8  660.01  4280.5  657.36  4285.5  657.61  4313.0  655.98
  4383.2  654.51  4440.8  652.40  4463.3  652.20  4493.4  651.23  4513.4  651.21
  4601.1  649.33  4613.6  649.73  4663.7  649.16  4693.8  649.24  4766.4  648.20
  4824.0  648.27  4954.3  646.12  4984.3  645.09  4990.1  644.07  4991.4  643.57
  4997.3  643.57  4998.5  644.07  5001.9  644.49  5006.9  644.49  5014.4  645.81
  5054.4  649.66  5064.4  655.00  5074.4  659.41  5084.4  660.09  5104.4  659.93
#Mann=3,-1,0
  4202.8    0.05       0  4990.1   0.033       0  4998.5    0.05       0
Bank Sta=4990.1,4998.5
Exp/Cntr=0.3,0.1

Type RM Length L Ch R = 1,13665,896,896,896
BEGIN DESCRIPTION:
Mapping XS 291af3b4
END DESCRIPTION:
XS GIS Cut Line= 2
      2347355.05      7093736.28      2346555.90      7093391.38
#Sta/Elev= 30
  4389.9  658.40  4439.1  656.35  4603.4  652.87  4643.5  651.46  4672.5  651.27
  4679.7  650.63  4724.9  649.28  4788.6  648.38  4800.9  647.96  4842.5  645.04
  4864.8  645.33  4871.4  646.20  4895.0  647.28  4970.9  646.10  5002.2  643.19
  5003.5  642.69  5009.4  642.69  5010.6  643.19  5046.9  645.21  5093.6  646.48
  5099.4  647.94  5104.8  647.61  5115.3  649.29  5122.9  651.35  5128.3  651.43
  5137.1  653.40  5146.4  653.96  5180.8  655.06  5198.9  656.64  5260.3  658.10
#Mann=3,-1,0
  4389.9    0.05       0  5002.2    0.04       0  5010.6    0.05       0
Bank Sta=5002.2,5010.6
Exp/Cntr=0.3,0.1

Type RM Length L Ch R = 1,12769,868,868,868
BEGIN DESCRIPTION:
Denton Creek Tributary 14 23.0
END DESCRIPTION:
XS GIS Cut Line= 3
      2347378.99      7093110.00      2347079.00      7093110.00
      2346629.03      7093259.99
#Sta/Elev= 30
  4704.3  666.66  4744.3  663.10  4764.3  660.22  4784.3  658.09  4834.3  653.80
  4854.3  651.49  4864.3  649.01  4874.3  647.19  4914.3  643.55  4924.3  643.90
  4934.3  643.54  4944.3  642.43  4954.3  642.90  4984.3  642.17  4994.3  641.69
  5001.8  640.21  5010.6  640.08  5011.8  639.58  5017.8  639.58  5019.1  640.08
  5025.4  643.84  5035.9  644.90  5057.0  643.30  5067.5  643.00  5078.1  643.22
  5099.2  644.69  5120.2  645.24  5331.1  647.30  5425.9  652.87  5478.6  655.24
#Mann=3,-1,0
  4704.3    0.05       0  5010.6    0.04       0  5019.1    0.05       0
Bank Sta=5010.6,5019.1
Exp/Cntr=0.3,0.1

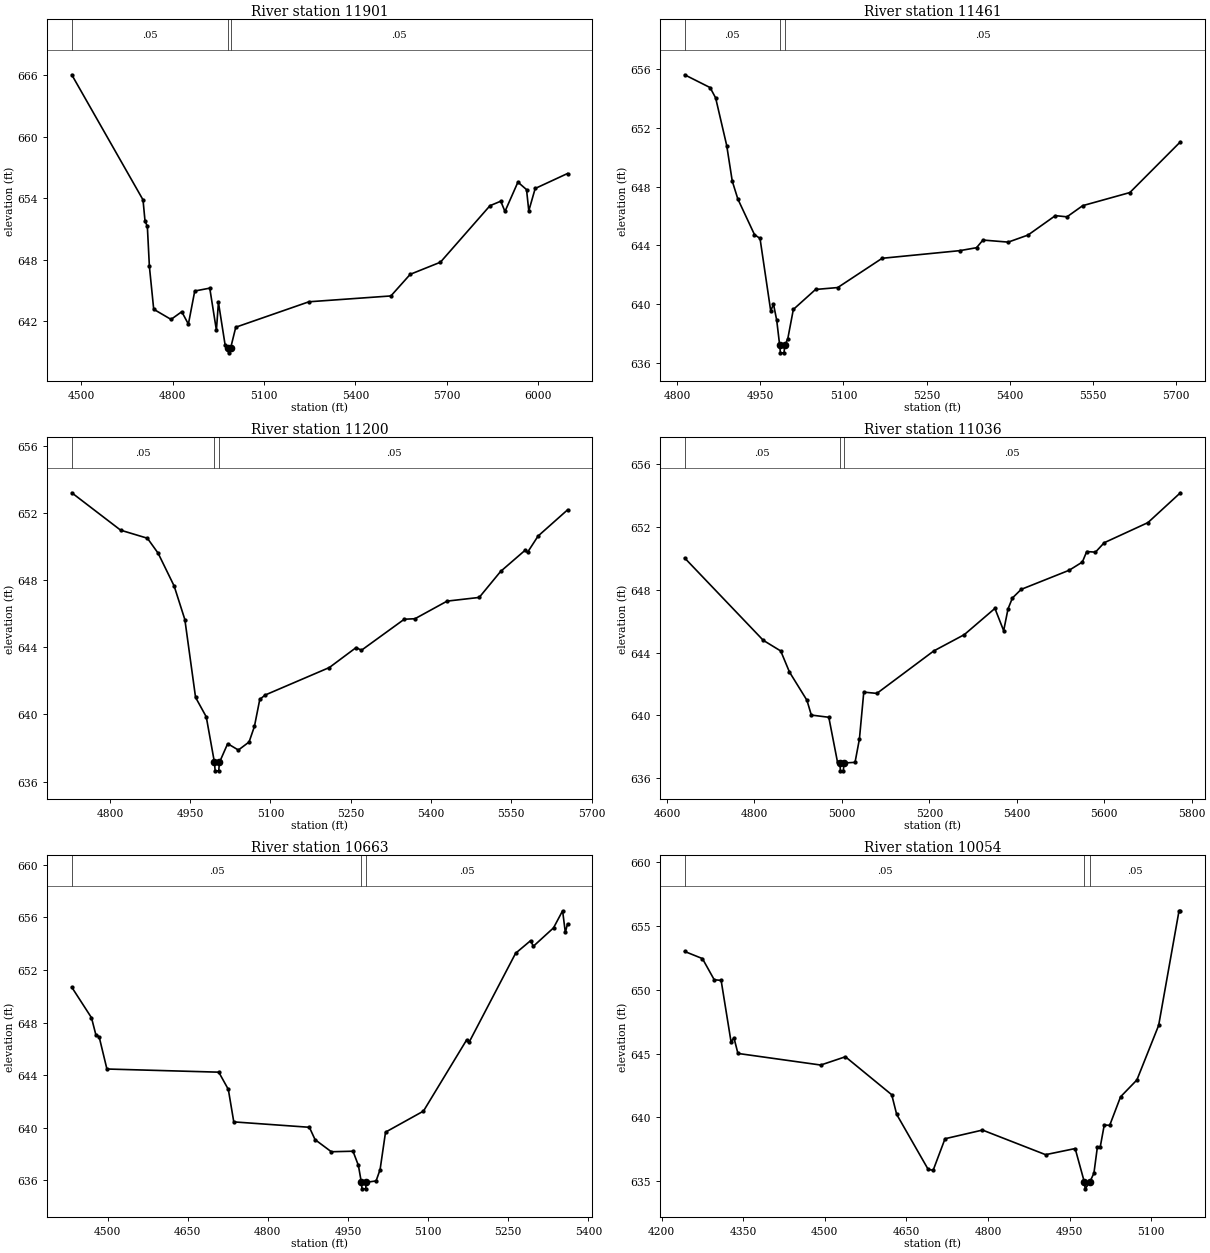
Type RM Length L Ch R = 1,11901,440,440,440
BEGIN DESCRIPTION:
Denton Creek Tributary 14 21.0
END DESCRIPTION:
XS GIS Cut Line= 3
      2347579.01      7092109.99      2347179.00      7092460.00
      2346379.00      7093210.00
#Sta/Elev= 30
  4468.6  666.03  4702.6  653.83  4709.2  651.75  4716.8  651.26  4723.5  647.34
  4737.7  643.16  4794.6  642.17  4829.8  642.92  4851.6  641.71  4872.5  644.94
  4921.8  645.22  4943.6  641.12  4950.3  643.83  4972.1  639.70  4982.1  639.41
  4983.4  638.91  4990.6  639.41  5007.2  641.41  5247.5  643.89  5516.7  644.46
  5580.2  646.57  5679.3  647.75  5842.0  653.26  5877.4  653.70  5891.3  652.70
  5933.8  655.56  5962.1  654.83  5969.5  652.76  5990.5  654.94  6096.7  656.40
#Mann=3,-1,0
  4468.6    0.05       0  4982.1    0.04       0  4990.6    0.05       0
Bank Sta=4982.1,4990.6
Exp/Cntr=0.3,0.1

Type RM Length L Ch R = 1,11461,261,261,261
BEGIN DESCRIPTION:
Mapping XS 03dd9e8f
END DESCRIPTION:
XS GIS Cut Line= 3
      2346852.51      7092174.18      2346822.14      7092743.03
      2346600.80      7092980.66
#Sta/Elev= 30
  4813.5  655.61  4859.4  654.74  4869.4  654.04  4889.4  650.80  4899.4  648.38
  4909.5  647.16  4939.5  644.74  4949.5  644.48  4968.8  639.55  4973.8  640.01
  4979.6  638.92  4985.0  637.20  4986.3  636.70  4992.8  636.70  4994.1  637.20
  4999.6  637.66  5009.6  639.65  5049.7  641.01  5089.7  641.14  5169.8  643.13
  5310.0  643.65  5340.1  643.85  5351.7  644.37  5397.3  644.23  5433.0  644.71
  5482.3  646.03  5503.3  645.95  5531.7  646.71  5616.7  647.60  5707.9  651.05
#Mann=3,-1,0
  4813.5    0.05       0  4985.0    0.04       0  4994.1    0.05       0
Bank Sta=4985,4994.1
Exp/Cntr=0.3,0.1

Type RM Length L Ch R = 1,11200,164,164,164
BEGIN DESCRIPTION:
Mapping XS bb5f9808
END DESCRIPTION:
XS GIS Cut Line= 2
      2346583.96      7092088.73      2346573.07      7093014.97
#Sta/Elev= 30
  4728.7  653.22  4820.0  650.99  4870.0  650.51  4890.0  649.62  4920.0  647.66
  4940.0  645.66  4960.0  641.02  4980.0  639.86  4995.3  637.14  4996.6  636.64
  5003.3  636.64  5004.6  637.14  5020.0  638.26  5040.0  637.88  5060.0  638.36
  5070.0  639.29  5080.0  640.90  5090.0  641.16  5210.0  642.80  5260.0  643.99
  5270.0  643.83  5350.0  645.68  5370.0  645.71  5430.0  646.76  5490.0  646.98
  5530.0  648.53  5575.3  649.78  5580.3  649.67  5600.0  650.64  5655.0  652.20
#Mann=3,-1,0
  4728.7    0.05       0  4995.3   0.033       0  5004.6    0.05       0
Bank Sta=4995.3,5004.6
Exp/Cntr=0.3,0.1

Type RM Length L Ch R = 1,11036,373,373,373
BEGIN DESCRIPTION:
Mapping XS 56e6dfec
END DESCRIPTION:
XS GIS Cut Line= 2
      2346417.43      7092000.24      2346416.85      7093134.34
#Sta/Elev= 30
  4640.2  650.02  4820.0  644.78  4860.0  644.10  4880.0  642.76  4920.0  640.96
  4930.0  640.02  4970.0  639.88  4990.0  637.01  4995.3  636.97  4996.6  636.47
  5003.3  636.47  5004.6  636.97  5030.0  637.01  5040.0  638.49  5050.0  641.48
  5080.0  641.40  5210.0  644.10  5280.0  645.14  5350.0  646.81  5370.0  645.39
  5380.0  646.78  5390.0  647.47  5410.0  648.02  5520.0  649.24  5550.0  649.76
  5560.0  650.43  5580.0  650.39  5600.0  650.99  5700.0  652.27  5774.3  654.17
#Mann=3,-1,0
  4640.2    0.05       0  4995.3   0.033       0  5004.6    0.05       0
Bank Sta=4995.3,5004.6
Exp/Cntr=0.3,0.1

Type RM Length L Ch R = 1,10663,609,609,609
BEGIN DESCRIPTION:
Mapping XS ff15208c
END DESCRIPTION:
XS GIS Cut Line= 3
      2346344.61      7091843.51      2346147.91      7091997.05
      2346032.74      7092665.78
#Sta/Elev= 30
  4432.9  650.69  4469.8  648.37  4477.9  647.09  4484.2  646.91  4498.7  644.47
  4708.1  644.23  4726.0  642.92  4736.2  640.45  4877.7  640.04  4888.4  639.10
  4918.8  638.18  4959.4  638.22  4969.5  637.14  4975.0  635.86  4976.3  635.36
  4983.0  635.36  4984.4  635.86  5002.6  635.96  5010.1  636.82  5020.3  639.67
  5091.3  641.27  5172.1  646.68  5177.2  646.54  5263.8  653.27  5291.9  654.23
  5297.0  653.80  5334.8  655.20  5351.8  656.50  5356.9  654.85  5361.0  655.51
#Mann=3,-1,0
  4432.9    0.05       0  4975.0   0.033       0  4984.4    0.05       0
Bank Sta=4975,4984.4
Exp/Cntr=0.3,0.1

Type RM Length L Ch R = 1,10054,261,261,261
BEGIN DESCRIPTION:
Denton Creek Tributary 14 17.0
END DESCRIPTION:
XS GIS Cut Line= 3
      2346379.04      7091759.98      2345679.00      7092060.00
      2345529.02      7092060.00
#Sta/Elev= 30
  4242.2  653.02  4274.9  652.46  4296.6  650.80  4309.3  650.75  4327.5  645.94
  4332.9  646.24  4340.2  645.02  4492.5  644.11  4537.8  644.76  4623.0  641.78
  4632.1  640.24  4690.1  635.92  4699.2  635.86  4721.0  638.33  4789.9  639.01
  4905.9  637.08  4960.3  637.56  4977.4  634.90  4978.7  634.40  4986.8  634.90
  4994.8  635.63  5001.1  637.66  5006.3  637.66  5013.8  639.41  5023.8  639.38
  5043.8  641.62  5073.8  642.94  5113.8  647.22  5151.3  656.21  5153.8  656.21
#Mann=3,-1,0
  4242.2    0.05       0  4977.4   0.033       0  4986.8    0.05       0
Bank Sta=4977.4,4986.8
Exp/Cntr=0.3,0.1

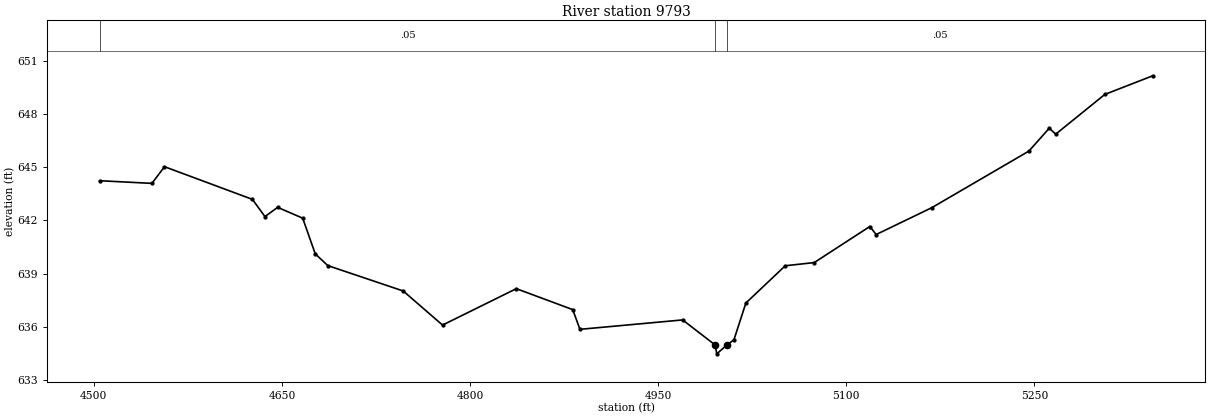
Type RM Length L Ch R = 1,9793,294,294,294
BEGIN DESCRIPTION:
Mapping XS 879df9df
END DESCRIPTION:
XS GIS Cut Line= 3
      2346180.58      7091808.26      2345829.13      7091830.11
      2345352.50      7091727.87
#Sta/Elev= 30
  4504.7  644.23  4546.4  644.08  4556.4  645.02  4626.5  643.18  4636.5  642.21
  4646.6  642.73  4666.6  642.12  4676.6  640.11  4686.6  639.45  4746.7  638.02
  4778.1  636.10  4836.9  638.15  4881.9  636.97  4887.6  635.86  4969.5  636.39
  4995.4  634.98  4996.7  634.48  5004.8  634.98  5010.4  635.27  5019.9  637.34
  5051.3  639.44  5074.4  639.62  5118.7  641.65  5123.8  641.20  5168.1  642.71
  5245.6  645.90  5261.8  647.19  5266.9  646.85  5306.1  649.09  5344.3  650.14
#Mann=3,-1,0
  4504.7    0.05       0  4995.4   0.033       0  5004.8    0.05       0
Bank Sta=4995.4,5004.8
Exp/Cntr=0.3,0.1