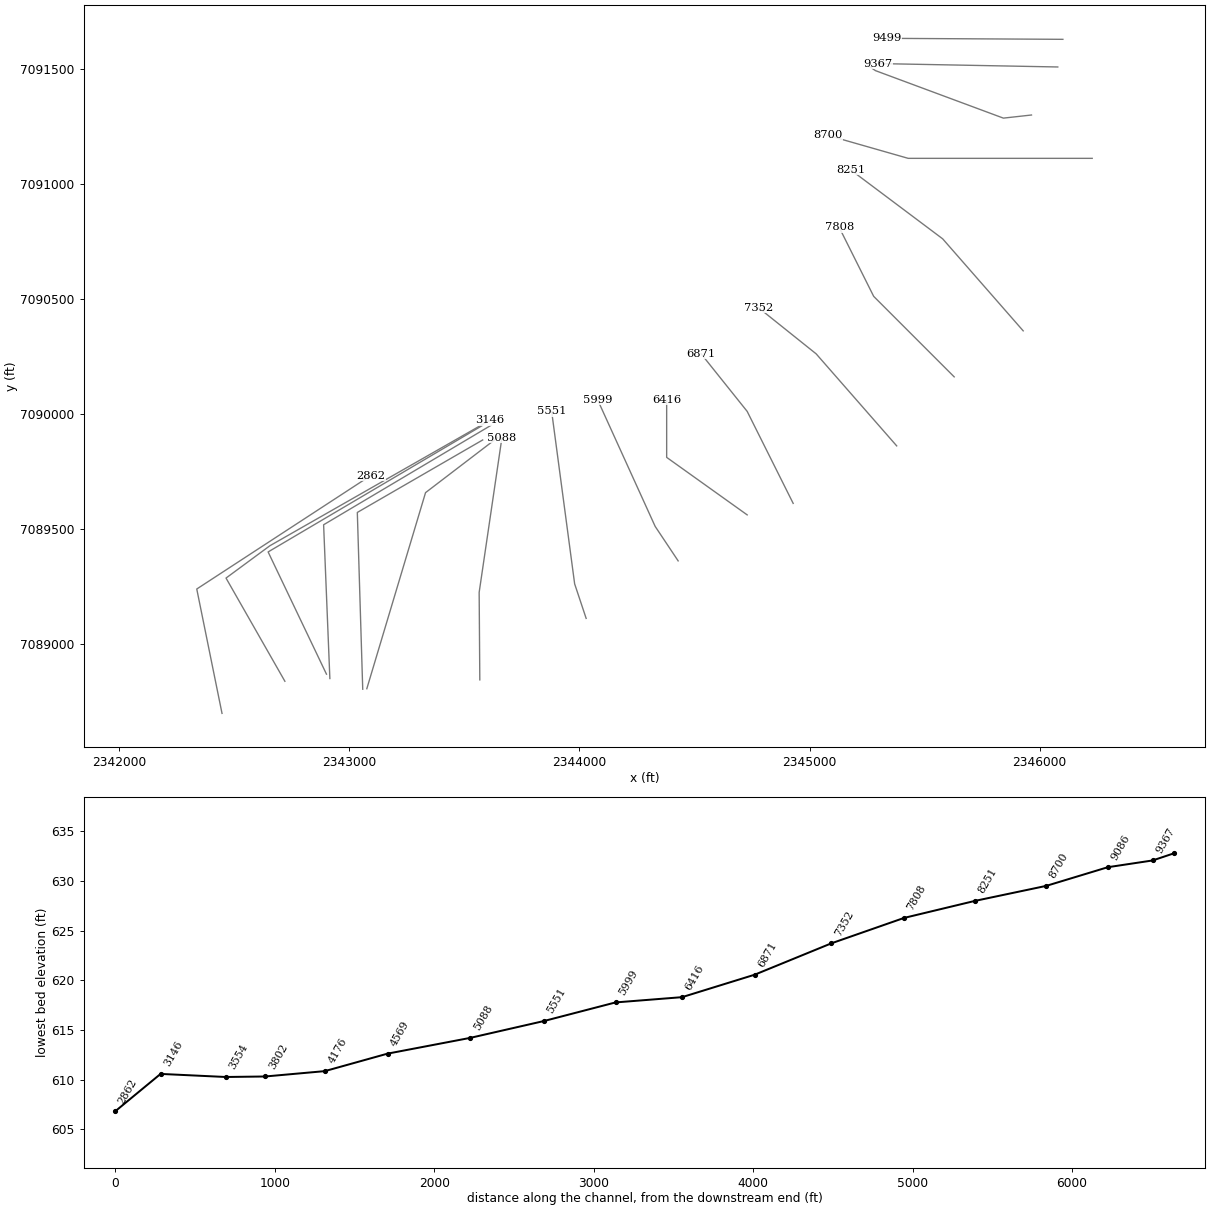
HEC-RAS study Denton Creek Tributary 14.prj: Denton Creek Tributary 14 Base Level Engineering

--- Denton Creek Tributary 14.g01 (geometry) --- (continued)

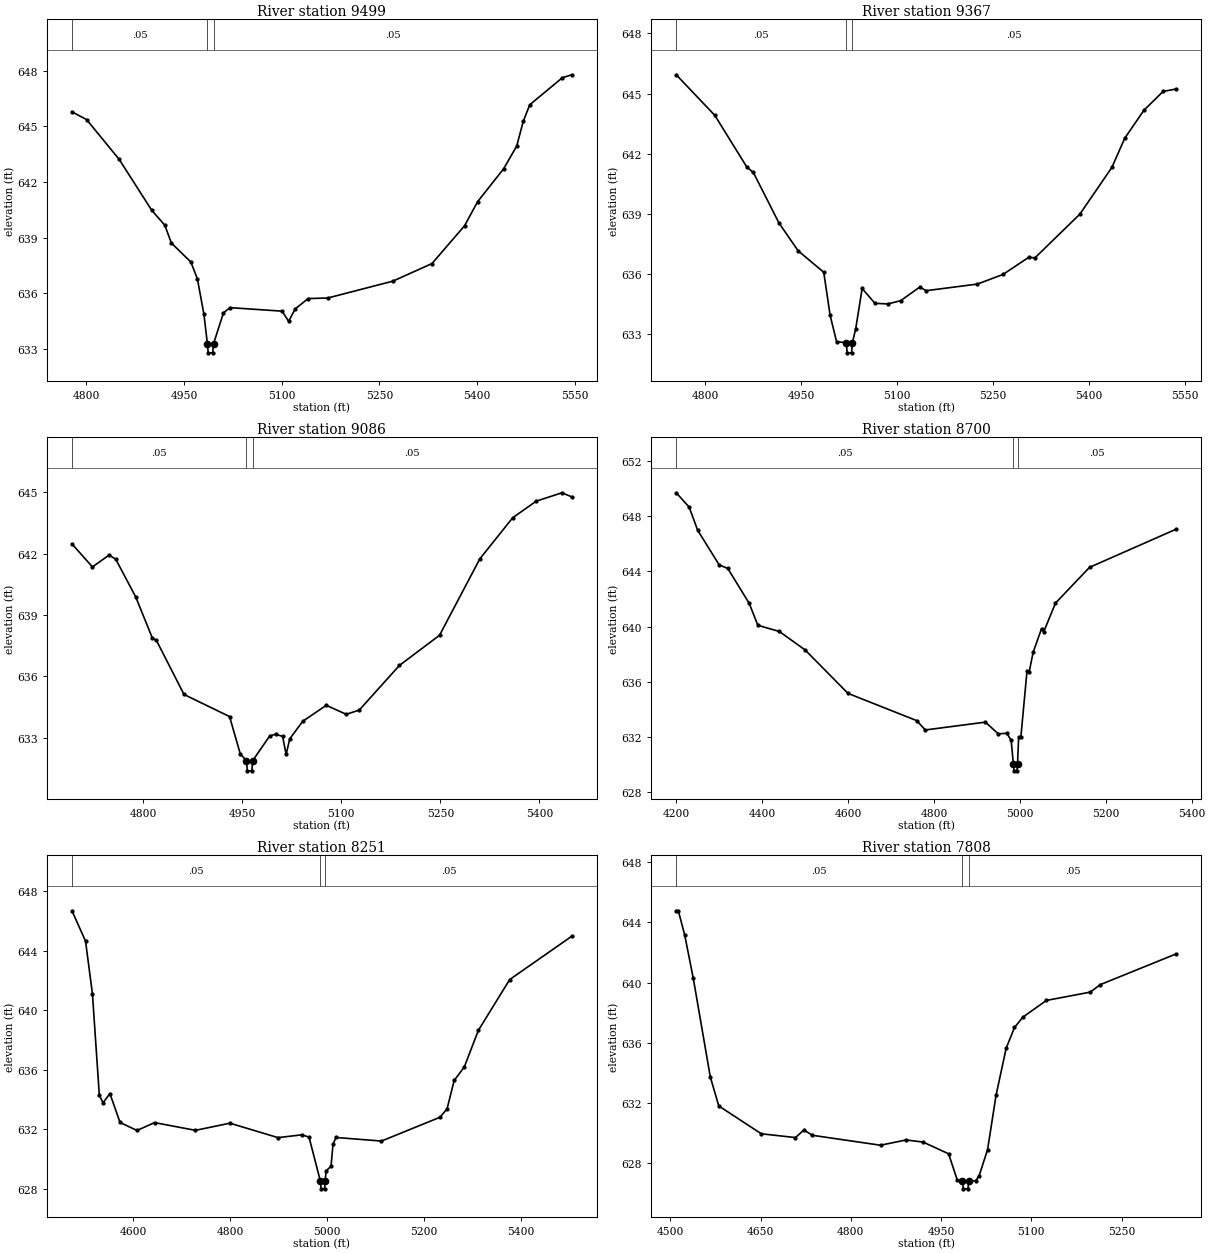
Type RM Length L Ch R = 1,9499,132,132,132
BEGIN DESCRIPTION:
Mapping XS a739a6f2
END DESCRIPTION:
XS GIS Cut Line= 2
      2346101.53      7091627.39      2345334.54      7091631.71
#Sta/Elev= 30
  4778.1  645.79  4800.6  645.37  4850.6  643.22  4900.6  640.47  4920.6  639.67
  4930.6  638.71  4960.6  637.68  4970.6  636.77  4980.6  634.86  4985.9  633.28
  4987.2  632.78  4994.0  632.78  4995.4  633.28  5010.6  634.94  5020.6  635.22
  5100.6  635.03  5110.6  634.48  5120.6  635.15  5140.6  635.71  5170.6  635.74
  5270.6  636.65  5330.6  637.60  5380.6  639.64  5400.6  640.94  5440.6  642.72
  5460.6  643.94  5470.6  645.27  5480.6  646.17  5530.6  647.63  5545.1  647.79
#Mann=3,-1,0
  4778.1    0.05       0  4985.9    0.04       0  4995.4    0.05       0
Bank Sta=4985.9,4995.4
Exp/Cntr=0.3,0.1

Type RM Length L Ch R = 1,9367,281,281,281
BEGIN DESCRIPTION:
Mapping XS e0c68e26
END DESCRIPTION:
XS GIS Cut Line= 2
      2346079.35      7091507.21      2345298.79      7091522.04
#Sta/Elev= 30
  4755.2  645.94  4815.6  643.91  4865.6  641.33  4875.6  641.07  4915.6  638.55
  4945.6  637.16  4985.6  636.09  4995.6  633.94  5005.6  632.63  5020.8  632.57
  5022.2  632.07  5029.0  632.07  5030.3  632.57  5035.6  633.28  5045.6  635.28
  5065.6  634.54  5085.6  634.51  5105.6  634.67  5135.6  635.35  5145.6  635.17
  5225.6  635.50  5265.6  635.98  5305.6  636.83  5315.6  636.81  5385.7  638.99
  5435.7  641.32  5455.7  642.77  5485.7  644.17  5515.7  645.11  5535.9  645.23
#Mann=3,-1,0
  4755.2    0.05       0  5020.8    0.04       0  5030.3    0.05       0
Bank Sta=5020.8,5030.3
Exp/Cntr=0.3,0.1

Type RM Length L Ch R = 1,9086,386,386,386
BEGIN DESCRIPTION:
Mapping XS a02cb2c8
END DESCRIPTION:
XS GIS Cut Line= 4
      2345965.01      7091298.40      2345842.81      7091284.85
      2345286.70      7091491.30      2345252.85      7091514.18
#Sta/Elev= 30
  4692.1  642.47  4723.1  641.35  4748.5  641.93  4758.5  641.72  4788.7  639.88
  4813.8  637.88  4820.0  637.76  4861.8  635.12  4930.8  634.04  4947.1  632.21
  4956.4  631.89  4957.7  631.39  4964.5  631.39  4965.9  631.89  4991.5  633.09
  5000.5  633.18  5011.1  633.07  5016.5  632.19  5021.9  632.95  5041.6  633.81
  5077.3  634.59  5107.6  634.15  5127.3  634.36  5188.1  636.54  5248.8  638.01
  5309.8  641.74  5359.6  643.75  5395.3  644.56  5434.2  644.97  5449.1  644.77
#Mann=3,-1,0
  4692.1    0.05       0  4956.4    0.04       0  4965.9    0.05       0
Bank Sta=4956.4,4965.9
Exp/Cntr=0.3,0.1

Type RM Length L Ch R = 1,8700,449,449,449
BEGIN DESCRIPTION:
Denton Creek Tributary 14 14.0
END DESCRIPTION:
XS GIS Cut Line= 3
      2346228.96      7091110.00      2345429.00      7091110.00
      2345078.97      7091210.01
#Sta/Elev= 30
  4199.5  649.72  4229.5  648.68  4249.5  646.99  4299.5  644.48  4319.5  644.22
  4369.5  641.68  4389.5  640.09  4439.5  639.64  4499.5  638.30  4599.5  635.14
  4759.5  633.16  4779.5  632.48  4919.5  633.05  4949.5  632.20  4969.5  632.24
  4979.5  631.72  4984.7  630.01  4986.1  629.51  4992.9  629.51  4994.3  630.01
  4997.0  631.97  5002.1  631.97  5016.4  636.76  5021.6  636.72  5030.7  638.12
  5050.2  639.84  5055.4  639.62  5082.7  641.70  5162.0  644.30  5363.5  647.07
#Mann=3,-1,0
  4199.5    0.05       0  4984.7    0.04       0  4994.3    0.05       0
Bank Sta=4984.7,4994.3
Exp/Cntr=0.3,0.1

Type RM Length L Ch R = 1,8251,443,443,443
BEGIN DESCRIPTION:
Denton Creek Tributary 14 13.0
END DESCRIPTION:
XS GIS Cut Line= 3
      2345929.00      7090360.01      2345579.00      7090760.00
      2345179.00      7091060.00
#Sta/Elev= 30
  4473.8  646.67  4501.8  644.63  4516.0  641.10  4530.3  634.27  4537.9  633.77
  4552.1  634.39  4573.0  632.45  4608.1  631.91  4644.2  632.44  4728.6  631.92
  4799.8  632.40  4899.0  631.43  4948.8  631.62  4963.1  631.46  4986.6  628.49
  4988.0  627.99  4995.1  627.99  4996.4  628.49  4998.2  629.20  5008.4  629.50
  5012.6  630.99  5018.8  631.44  5112.6  631.20  5233.4  632.80  5248.0  633.37
  5262.6  635.27  5283.4  636.17  5312.6  638.64  5377.2  642.05  5505.3  644.96
#Mann=3,-1,0
  4473.8    0.05       0  4986.6    0.04       0  4996.4    0.05       0
Bank Sta=4986.6,4996.4
Exp/Cntr=0.3,0.1

Type RM Length L Ch R = 1,7808,456,456,456
BEGIN DESCRIPTION:
Denton Creek Tributary 14 12.0
END DESCRIPTION:
XS GIS Cut Line= 3
      2345628.99      7090160.01      2345279.00      7090510.00
      2345128.99      7090810.03
#Sta/Elev= 30
  4510.0  644.77  4513.5  644.77  4524.1  643.15  4538.3  640.28  4566.6  633.72
  4580.7  631.79  4651.4  629.94  4708.0  629.69  4722.1  630.19  4736.3  629.84
  4849.4  629.18  4891.8  629.53  4920.1  629.39  4962.5  628.61  4976.7  626.89
  4985.6  626.78  4987.0  626.28  4994.6  626.28  4996.1  626.78  5007.8  626.83
  5013.3  627.16  5027.3  628.89  5041.3  632.49  5058.1  635.62  5072.0  637.01
  5086.0  637.70  5125.1  638.81  5197.8  639.36  5214.6  639.86  5340.4  641.90
#Mann=3,-1,0
  4510.0    0.05       0  4985.6   0.033       0  4996.1    0.05       0
Bank Sta=4985.6,4996.1
Exp/Cntr=0.3,0.1

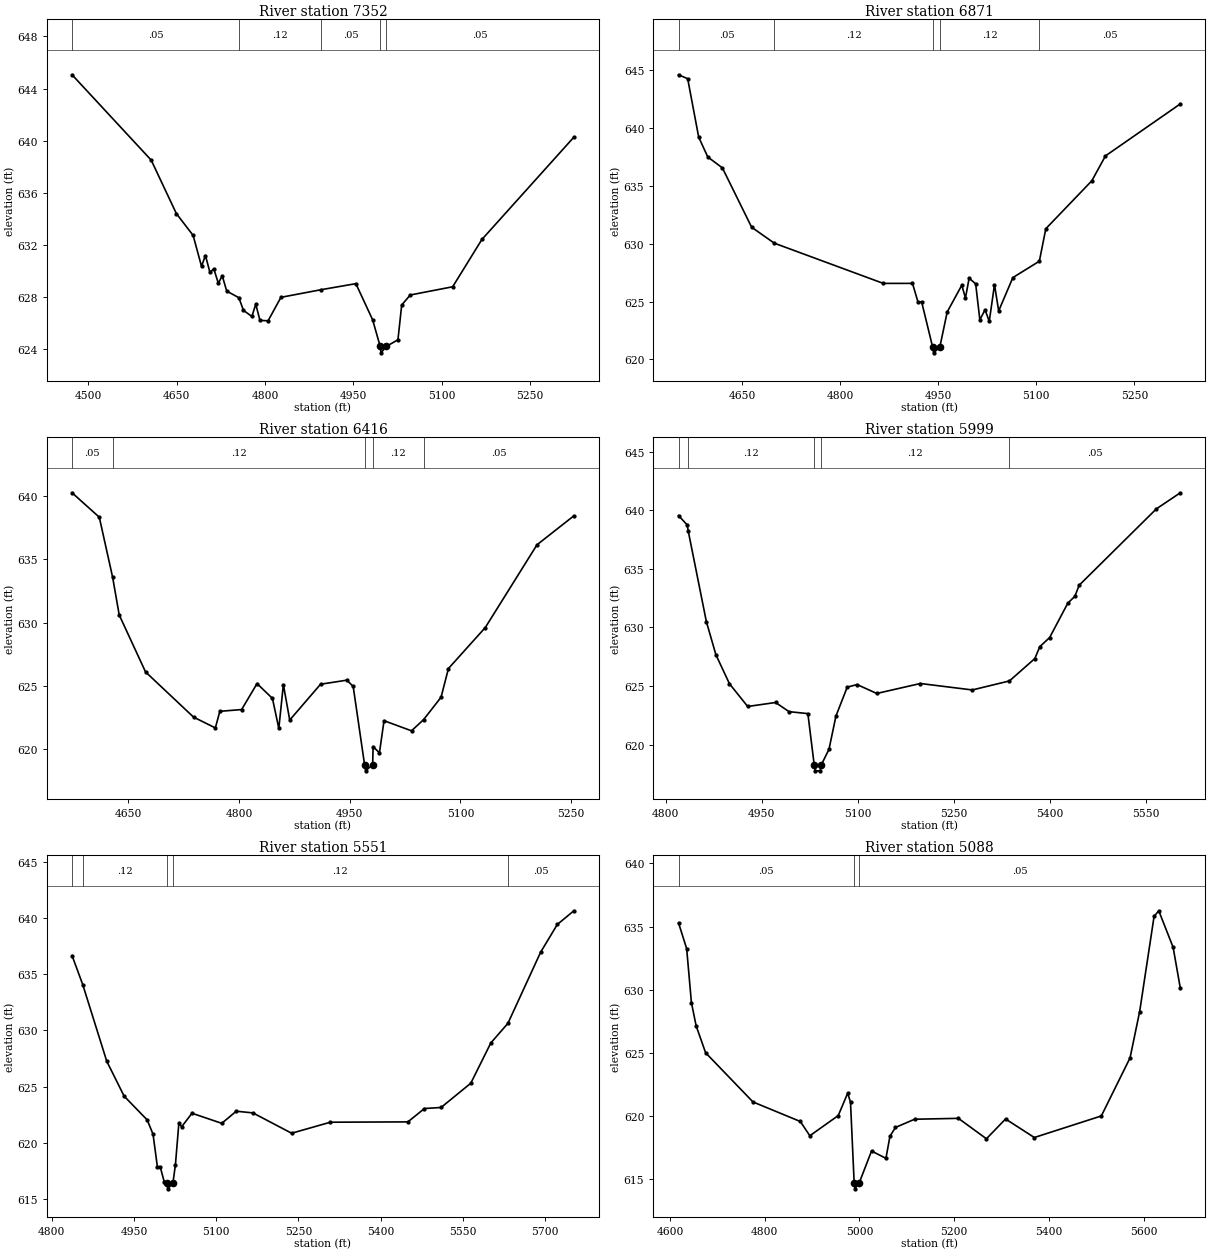
Type RM Length L Ch R = 1,7352,481,481,481
BEGIN DESCRIPTION:
Denton Creek Tributary 14 11.0
END DESCRIPTION:
XS GIS Cut Line= 3
      2345379.02      7089859.98      2345029.00      7090260.00
      2344778.99      7090460.01
#Sta/Elev= 30
  4472.6  645.06  4606.9  638.51  4649.6  634.41  4678.1  632.73  4692.3  630.36
  4699.0  631.19  4706.6  629.89  4713.2  630.17  4720.8  629.06  4727.5  629.63
  4735.1  628.46  4755.7  627.95  4763.5  626.98  4777.8  626.51  4784.4  627.45
  4791.5  626.21  4805.3  626.18  4827.1  627.98  4894.6  628.56  4954.3  629.03
  4982.8  626.25  4995.5  624.22  4996.9  623.72  5006.2  624.22  5025.7  624.72
  5032.1  627.39  5046.6  628.16  5118.6  628.79  5168.2  632.42  5324.3  640.27
#Mann=5,-1,0
  4472.6    0.05       0  4755.7    0.12       0  4894.6    0.05       0
  4995.5   0.033       0  5006.2    0.05       0
Bank Sta=4995.5,5006.2
Exp/Cntr=0.3,0.1

Type RM Length L Ch R = 1,6871,455,455,455
BEGIN DESCRIPTION:
Denton Creek Tributary 14 10.0
END DESCRIPTION:
XS GIS Cut Line= 3
      2344929.00      7089609.99      2344729.00      7090010.00
      2344528.98      7090260.02
#Sta/Elev= 30
  4552.8  644.62  4566.8  644.28  4583.6  639.23  4597.5  637.51  4619.9  636.56
  4664.6  631.43  4699.2  630.05  4865.9  626.57  4910.6  626.57  4919.0  624.96
  4924.6  624.97  4941.4  621.06  4942.9  620.56  4952.4  621.06  4963.7  624.10
  4986.0  626.41  4991.6  625.30  4997.2  627.02  5007.2  626.53  5013.6  623.42
  5021.6  624.29  5028.0  623.28  5036.0  626.46  5042.4  624.19  5064.1  627.07
  5104.6  628.49  5114.5  631.30  5184.9  635.45  5205.7  637.60  5320.2  642.10
#Mann=5,-1,0
  4552.8    0.05       0  4699.2    0.12       0  4941.4    0.07       0
  4952.4    0.12       0  5104.6    0.05       0
Bank Sta=4941.4,4952.4
Exp/Cntr=0.3,0.1

Type RM Length L Ch R = 1,6416,417,417,417
BEGIN DESCRIPTION:
Denton Creek Tributary 14 9.0
END DESCRIPTION:
XS GIS Cut Line= 3
      2344729.03      7089559.98      2344379.00      7089810.00
      2344379.00      7090059.95
#Sta/Elev= 30
  4573.7  640.26  4610.6  638.33  4628.7  633.58  4637.6  630.61  4673.3  626.11
  4738.4  622.54  4767.9  621.69  4774.0  623.00  4803.5  623.14  4824.4  625.19
  4845.3  624.02  4853.9  621.65  4860.1  625.11  4868.7  622.31  4910.5  625.14
  4946.1  625.46  4954.7  624.97  4970.1  618.80  4971.6  618.30  4981.1  618.80
  4981.7  620.21  4990.3  619.72  4996.5  622.26  5033.8  621.46  5050.2  622.35
  5073.8  624.11  5083.8  626.38  5133.8  629.62  5203.8  636.15  5253.8  638.44
#Mann=5,-1,0
  4573.7    0.05       0  4628.7    0.12       0  4970.1    0.07       0
  4981.1    0.12       0  5050.2    0.05       0
Bank Sta=4970.1,4981.1
Exp/Cntr=0.3,0.1

Type RM Length L Ch R = 1,5999,448,448,448
BEGIN DESCRIPTION:
Denton Creek Tributary 14 8.0
END DESCRIPTION:
XS GIS Cut Line= 3
      2344428.98      7089360.03      2344329.00      7089510.00
      2344079.00      7090060.01
#Sta/Elev= 30
  4819.8  639.55  4833.3  638.75  4835.1  638.19  4863.3  630.50  4878.3  627.66
  4899.4  625.20  4927.9  623.26  4971.5  623.60  4992.5  622.82  5022.0  622.65
  5031.9  618.27  5033.4  617.77  5041.4  617.77  5042.9  618.27  5055.0  619.61
  5065.9  622.45  5083.5  624.91  5098.9  625.13  5129.7  624.37  5197.8  625.22
  5279.0  624.67  5337.1  625.44  5376.8  627.35  5384.5  628.36  5399.9  629.14
  5428.4  632.08  5439.4  632.66  5446.0  633.60  5566.8  640.12  5604.2  641.49
#Mann=5,-1,0
  4819.8    0.05       0  4835.1    0.12       0  5031.9    0.07       0
  5042.9    0.12       0  5337.1    0.05       0
Bank Sta=5031.9,5042.9
Exp/Cntr=0.3,0.1

Type RM Length L Ch R = 1,5551,463,463,463
BEGIN DESCRIPTION:
Denton Creek Tributary 14 7.0
END DESCRIPTION:
XS GIS Cut Line= 3
      2344029.00      7089110.01      2343979.00      7089260.00
      2343879.01      7090009.95
#Sta/Elev= 30
  4837.3  636.66  4856.8  634.07  4900.5  627.26  4932.2  624.15  4974.3  622.03
  4984.9  620.76  4992.8  617.87  4997.9  617.87  5005.5  616.49  5010.1  616.40
  5011.6  615.90  5021.1  616.40  5025.7  618.04  5032.0  621.77  5037.0  621.42
  5055.9  622.63  5110.2  621.73  5136.6  622.81  5166.9  622.66  5237.5  620.85
  5308.2  621.83  5449.4  621.86  5479.7  623.05  5509.9  623.14  5564.1  625.30
  5600.7  628.89  5631.8  630.63  5691.5  636.97  5721.8  639.43  5752.0  640.65
#Mann=5,-1,0
  4837.3    0.05       0  4856.8    0.12       0  5010.1    0.07       0
  5021.1    0.12       0  5631.8    0.05       0
Bank Sta=5010.1,5021.1
Exp/Cntr=0.3,0.1

Type RM Length L Ch R = 1,5088,519,519,519
BEGIN DESCRIPTION:
Mapping XS 4f2eeefa
END DESCRIPTION:
XS GIS Cut Line= 3
      2343566.70      7088842.77      2343563.88      7089223.19
      2343662.78      7089895.02
#Sta/Elev= 30
  4618.0  635.29  4635.2  633.24  4645.2  628.97  4655.2  627.12  4675.2  624.99
  4775.2  621.09  4875.2  619.54  4895.2  618.41  4955.2  620.01  4975.2  621.79
  4981.1  621.06  4988.8  614.70  4990.3  614.20  4999.8  614.70  5025.5  617.20
  5055.9  616.62  5064.4  618.37  5076.1  619.07  5116.5  619.72  5208.9  619.79
  5268.1  618.17  5308.5  619.74  5369.2  618.27  5510.7  619.98  5571.3  624.58
  5591.6  628.25  5622.1  635.81  5632.0  636.25  5662.3  633.35  5677.5  630.11
#Mann=3,-1,0
  4618.0    0.05       0  4988.8   0.033       0  4999.8    0.05       0
Bank Sta=4988.8,4999.8
Exp/Cntr=0.3,0.1

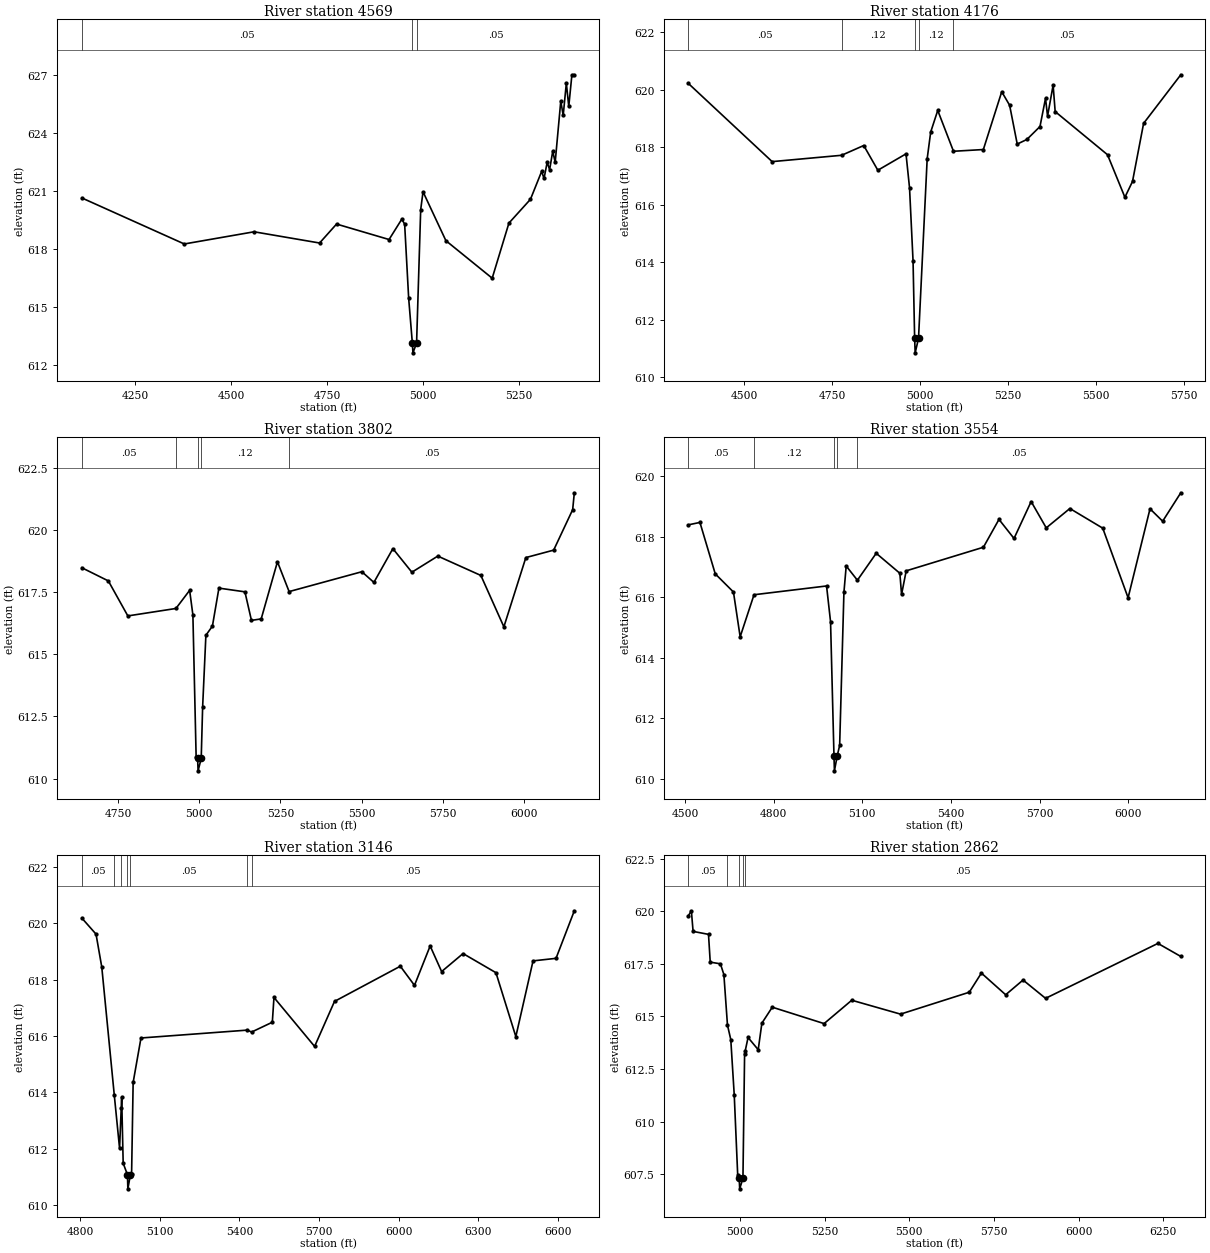
Type RM Length L Ch R = 1,4569,393,393,393
BEGIN DESCRIPTION:
Mapping XS 05e0caf1
END DESCRIPTION:
XS GIS Cut Line= 3
      2343075.49      7088804.35      2343330.79      7089656.71
      2343643.34      7089895.50
#Sta/Elev= 30
  4111.6  620.62  4378.5  618.24  4560.3  618.87  4731.0  618.29  4775.2  619.27
  4912.0  618.47  4945.1  619.52  4952.6  619.27  4963.1  615.43  4972.7  613.11
  4974.2  612.61  4983.7  613.11  4994.4  620.01  5000.5  620.94  5060.1  618.41
  5180.7  616.47  5224.3  619.32  5280.4  620.55  5309.5  621.99  5315.8  621.63
  5324.0  622.47  5330.3  622.08  5338.5  623.04  5344.8  622.46  5359.4  625.63
  5365.7  624.89  5373.9  626.56  5380.2  625.35  5388.4  626.99  5394.7  626.99
#Mann=3,-1,0
  4111.6    0.05       0  4972.7   0.033       0  4983.7    0.05       0
Bank Sta=4972.7,4983.7
Exp/Cntr=0.3,0.1

Type RM Length L Ch R = 1,4176,374,374,374
BEGIN DESCRIPTION:
Mapping XS 65e67f43
END DESCRIPTION:
XS GIS Cut Line= 3
      2343057.72      7088802.15      2343034.21      7089570.62
      2343579.17      7089885.67
#Sta/Elev= 30
  4341.8  620.22  4579.8  617.50  4777.0  617.72  4839.9  618.06  4879.9  617.20
  4959.9  617.77  4969.9  616.59  4979.9  614.04  4984.4  611.35  4985.9  610.85
  4995.4  611.35  5020.0  617.60  5030.0  618.53  5050.0  619.28  5094.7  617.86
  5179.5  617.92  5231.7  619.93  5254.1  619.46  5275.7  618.11  5303.0  618.27
  5340.3  618.72  5356.0  619.70  5361.8  619.08  5377.6  620.16  5383.4  619.24
  5532.0  617.74  5581.4  616.26  5603.0  616.81  5634.5  618.83  5740.1  620.52
#Mann=5,-1,0
  4341.8    0.05       0  4777.0    0.12       0  4984.4    0.07       0
  4995.4    0.12       0  5094.7    0.05       0
Bank Sta=4984.4,4995.4
Exp/Cntr=0.3,0.1

Type RM Length L Ch R = 1,3802,248,248,248
BEGIN DESCRIPTION:
Mapping XS cb49fd54
END DESCRIPTION:
XS GIS Cut Line= 3
      2342914.86      7088848.58      2342887.67      7089517.02
      2343615.43      7089949.37
#Sta/Elev= 30
  4638.8  618.49  4720.3  617.96  4780.3  616.55  4928.3  616.85  4970.5  617.58
  4980.5  616.59  4990.5  610.86  4995.0  610.81  4996.5  610.31  5006.1  610.81
  5010.5  612.89  5020.5  615.77  5040.6  616.14  5060.6  617.67  5140.6  617.52
  5160.7  616.37  5190.7  616.43  5240.7  618.73  5276.6  617.53  5500.5  618.33
  5537.5  617.90  5595.9  619.26  5654.4  618.31  5734.2  618.96  5866.7  618.18
  5937.5  616.11  6005.1  618.90  6090.7  619.20  6149.2  620.83  6154.3  621.51
#Mann=5,-1,0
  4638.8    0.05       0  4928.3    0.12       0  4995.0    0.07       0
  5006.1    0.12       0  5276.6    0.05       0
Bank Sta=4995,5006.1
Exp/Cntr=0.3,0.1

Type RM Length L Ch R = 1,3554,408,408,408
BEGIN DESCRIPTION:
Mapping XS 2c063093
END DESCRIPTION:
XS GIS Cut Line= 3
      2342900.06      7088867.66      2342646.45      7089398.91
      2343575.25      7089947.12
#Sta/Elev= 30
  4510.9  618.39  4550.2  618.47  4602.1  616.77  4663.7  616.17  4686.4  614.69
  4733.3  616.08  4978.9  616.37  4992.4  615.19  5004.0  610.76  5005.5  610.26
  5015.1  610.76  5023.2  611.10  5037.7  616.16  5045.4  617.03  5083.3  616.56
  5147.0  617.45  5227.0  616.79  5232.8  616.09  5248.5  616.87  5509.9  617.65
  5562.6  618.57  5613.5  617.94  5671.5  619.16  5722.6  618.29  5802.6  618.93
  5913.9  618.28  5999.7  615.98  6073.9  618.92  6116.7  618.51  6178.1  619.45
#Mann=5,-1,0
  4510.9    0.05       0  4733.3    0.12       0  5004.0    0.07       0
  5015.1    0.12       0  5083.3    0.05       0
Bank Sta=5004,5015.1
Exp/Cntr=0.3,0.1

Type RM Length L Ch R = 1,3146,284,284,284
BEGIN DESCRIPTION:
Mapping XS 631c675a
END DESCRIPTION:
XS GIS Cut Line= 4
      2342719.32      7088836.66      2342463.40      7089285.32
      2342654.22      7089425.91      2343610.15      7089971.29
#Sta/Elev= 30
  4806.7  620.19  4860.1  619.62  4881.7  618.45  4928.6  613.92  4948.7  612.01
  4955.0  613.45  4956.6  613.82  4962.3  611.48  4978.4  611.07  4979.9  610.57
  4989.5  611.07  4994.0  611.11  4999.8  614.35  5029.3  615.93  5430.2  616.21
  5445.6  616.14  5523.8  616.49  5530.0  617.37  5683.0  615.63  5757.9  617.23
  6005.7  618.48  6059.0  617.80  6118.0  619.20  6161.2  618.29  6241.9  618.93
  6365.7  618.25  6440.6  615.98  6505.4  618.67  6591.9  618.76  6660.8  620.45
#Mann=7,-1,0
  4806.7    0.05       0  4928.6    0.12       0  4955.0    0.05       0
  4978.4   0.033       0  4989.5    0.05       0  5430.2    0.12       0
  5445.6    0.05       0
Bank Sta=4978.4,4989.5
Exp/Cntr=0.3,0.1

Type RM Length L Ch R = 1,2862,0,0,0
BEGIN DESCRIPTION:
Denton Creek Tributary 14 6.0
END DESCRIPTION:
XS GIS Cut Line= 3
      2342445.98      7088697.10      2342336.19      7089237.72
      2343092.15      7089730.77
#Sta/Elev= 30
  4847.8  619.78  4856.8  620.02  4861.9  619.04  4907.4  618.90  4912.5  617.58
  4942.6  617.50  4952.8  616.99  4963.4  614.59  4973.2  613.90  4983.4  611.27
  4993.6  607.47  4998.0  607.31  4999.5  606.81  5009.1  607.31  5014.0  613.23
  5015.9  613.37  5024.2  614.00  5054.2  613.42  5065.0  614.68  5095.7  615.44
  5248.7  614.66  5330.4  615.77  5474.4  615.11  5677.4  616.15  5713.2  617.06
  5784.9  616.03  5836.2  616.73  5902.7  615.86  6234.5  618.47  6302.0  617.85
#Mann=5,-1,0
  4847.8    0.05       0  4963.4    0.12       0  4998.0    0.07       0
  5009.1    0.12       0  5015.9    0.05       0
Bank Sta=4998,5009.1
Exp/Cntr=0.3,0.1

Chan Stop Cuts=-1