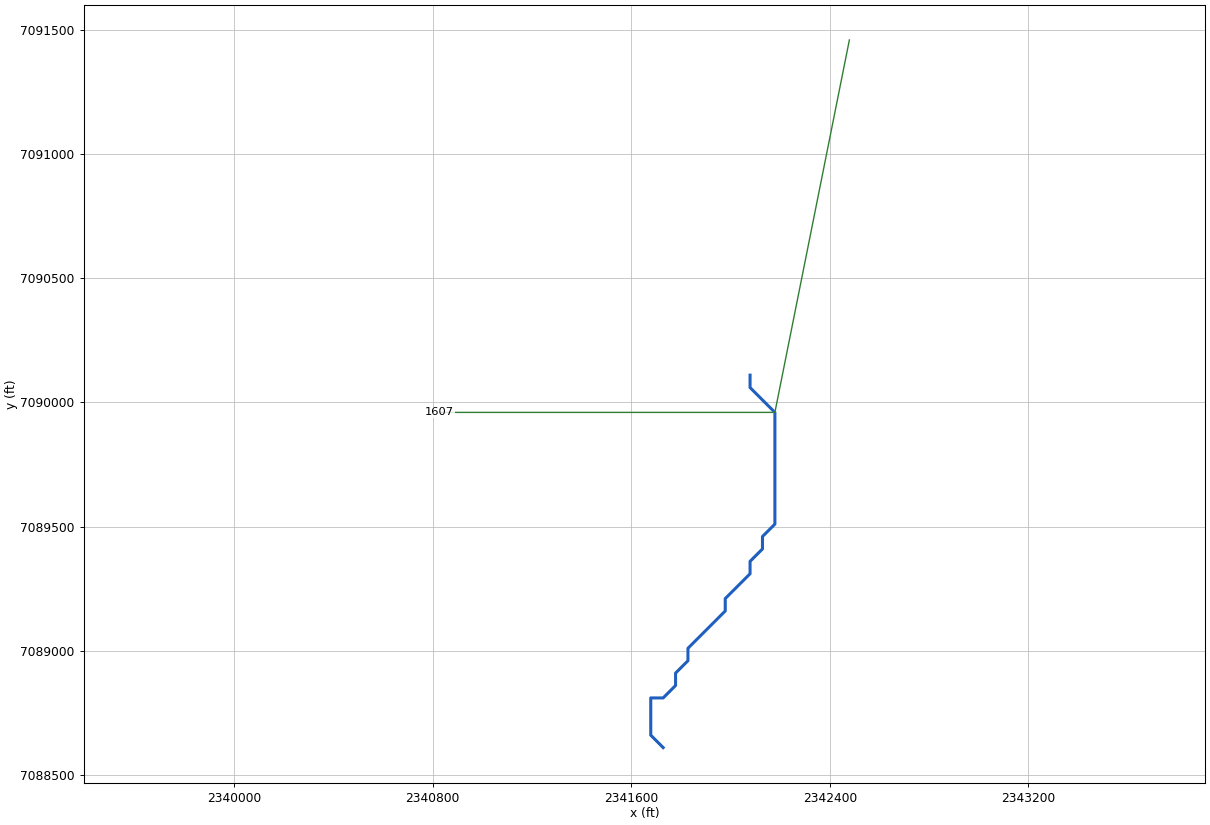
--- Denton Creek Tributary 14_1.prj (project) ---

Proj Title=Denton Creek Tributary 14_1 Base Level Engineering
Current Plan=p01
Default Exp/Contr=0.3,0.1
English Units
Geom File=g01
Flow File=f01
Plan File=p01
BEGIN DESCRIPTION:
Denton Creek Tributary 14_1
END DESCRIPTION:

--- Denton Creek Tributary 14_1.p01 (plan) ---

Plan Title=Multiple Run
Short Identifier=Multiple
Geom File=g01
Flow File=f01
Subcritical Flow
K Sum by GR= 0
Std Step Tol= 0.01
Critical Tol= 0.01
Num of Std Step Trials= 20
Max Error Tol= 0.3
Flow Tol Ratio= 0.001
Split Flow NTrial= 30
Split Flow Tol= 0.02
Split Flow Ratio= 0.02
Log Output Level= 0
Friction Slope Method= 1
Unsteady Friction Slope Method= 2
Unsteady Bridges Friction Slope Method= 1
Parabolic Critical Depth
Global Vel Dist=  1 , 1 , 1
Global Log Level= 0
CheckData=True
Encroach Param= -1, 0, 0, 0
BEGIN DESCRIPTION:
Multiple Run
END DESCRIPTION:

--- Denton Creek Tributary 14_1.f01 (steady flow) ---

Flow Title=Multiple
Number of Profiles=7
Profile Names=10-year,25-year,50-year,1pct_min,100-year,1pct_plu,500-year
River Rch & RM= Denton Creek Tri,Reach-1,1607
     453     608     734     440     878    1752    1259
Boundary for River Rch & Prof#=Denton Creek Tri,Reach-1,1
Up Type=0
Dn Type=3
Dn Slope=0.005
Boundary for River Rch & Prof#=Denton Creek Tri,Reach-1,2
Up Type=0
Dn Type=3
Dn Slope=0.005
Boundary for River Rch & Prof#=Denton Creek Tri,Reach-1,3
Up Type=0
Dn Type=3
Dn Slope=0.005
Boundary for River Rch & Prof#=Denton Creek Tri,Reach-1,4
Up Type=0
Dn Type=3
Dn Slope=0.005
Boundary for River Rch & Prof#=Denton Creek Tri,Reach-1,5
Up Type=0
Dn Type=3
Dn Slope=0.005
Boundary for River Rch & Prof#=Denton Creek Tri,Reach-1,6
Up Type=0
Dn Type=3
Dn Slope=0.005
Boundary for River Rch & Prof#=Denton Creek Tri,Reach-1,7
Up Type=0
Dn Type=3
Dn Slope=0.005

--- Denton Creek Tributary 14_1.g01 (geometry) ---

Geom Title=Existing Conditions

River Reach=Denton Creek Tri,Reach-1
Reach XY= 18
      2342079.00      7090110.00      2342079.00      7090060.00
      2342179.00      7089960.00      2342179.00      7089510.00
      2342129.00      7089460.00      2342129.00      7089410.00
      2342079.00      7089360.00      2342079.00      7089310.00
      2341979.00      7089210.00      2341979.00      7089160.00
      2341829.00      7089010.00      2341829.00      7088960.00
      2341779.00      7088910.00      2341779.00      7088860.00
      2341729.00      7088810.00      2341679.00      7088810.00
      2341679.00      7088660.00      2341729.00      7088610.00

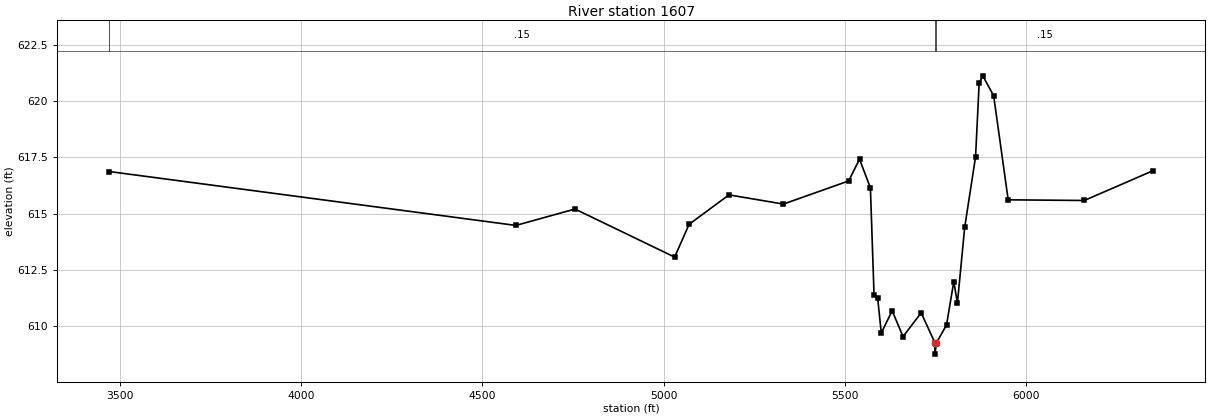
Type RM Length L Ch R = 1,1607,0,0,0
BEGIN DESCRIPTION:
Denton Creek Tributary 14_1 1.0
END DESCRIPTION:
XS GIS Cut Line= 3
      2342479.00      7091459.99      2342179.00      7089960.00
      2340829.00      7089960.00
#Sta/Elev= 30
  3470.3  616.87  4592.1  614.47  4755.2  615.20  5030.0  613.06  5070.0  614.52
  5180.0  615.83  5330.0  615.42  5510.0  616.45  5540.0  617.42  5570.0  616.14
  5580.0  611.39  5590.0  611.24  5600.0  609.68  5630.0  610.67  5660.0  609.52
  5710.0  610.58  5748.0  609.24  5748.2  608.74  5752.0  609.24  5780.0  610.04
  5800.0  611.97  5810.0  611.01  5830.0  614.38  5860.0  617.52  5870.0  620.81
  5880.0  621.13  5910.0  620.24  5950.0  615.61  6160.0  615.58  6350.0  616.91
#Mann=3,-1,0
  3470.3    0.15       0  5748.0    0.05       0  5752.0    0.15       0
Bank Sta=5748,5752
Exp/Cntr=0.3,0.1

Chan Stop Cuts=-1