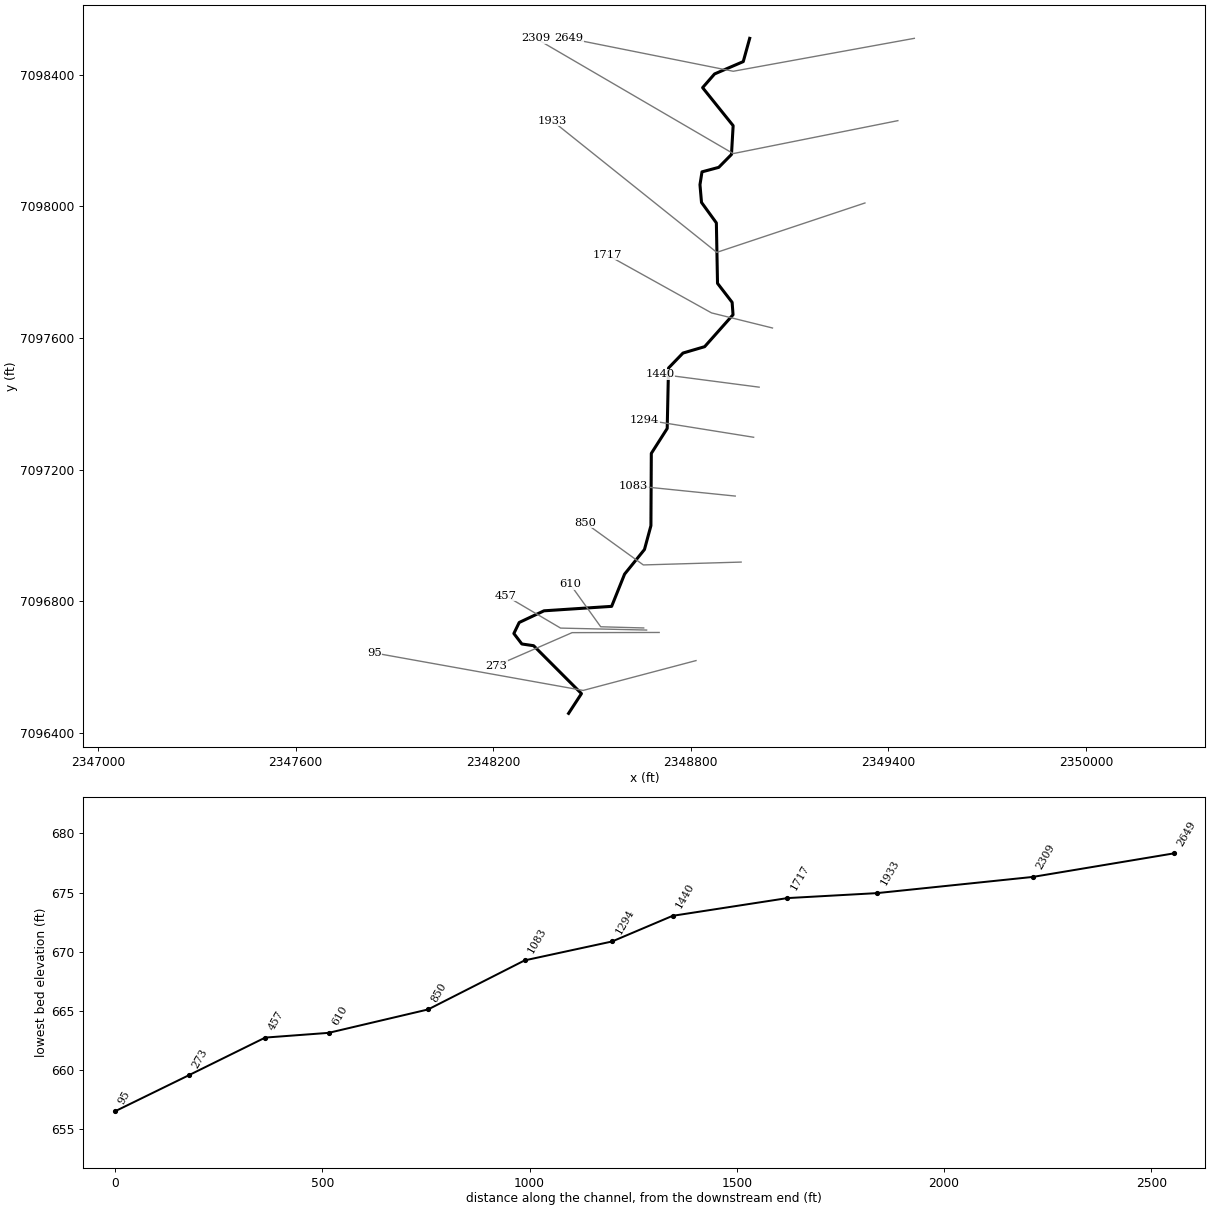
--- Denton Creek Tributary 14_5.prj (project) ---

Proj Title=Denton Creek Tributary 14_5 Base Level Engineering
Current Plan=p01
Default Exp/Contr=0.3,0.1
English Units
Geom File=g01
Flow File=f01
Plan File=p01
BEGIN DESCRIPTION:
Denton Creek Tributary 14_5
END DESCRIPTION:

--- Denton Creek Tributary 14_5.p01 (plan) ---

Plan Title=Multiple Run
Short Identifier=Multiple
Geom File=g01
Flow File=f01
Subcritical Flow
K Sum by GR= 0
Std Step Tol= 0.01
Critical Tol= 0.01
Num of Std Step Trials= 20
Max Error Tol= 0.3
Flow Tol Ratio= 0.001
Split Flow NTrial= 30
Split Flow Tol= 0.02
Split Flow Ratio= 0.02
Log Output Level= 0
Friction Slope Method= 1
Unsteady Friction Slope Method= 2
Unsteady Bridges Friction Slope Method= 1
Parabolic Critical Depth
Global Vel Dist=  1 , 1 , 1
Global Log Level= 0
CheckData=True
Encroach Param= -1, 0, 0, 0
BEGIN DESCRIPTION:
Multiple Run
END DESCRIPTION:

--- Denton Creek Tributary 14_5.f01 (steady flow) ---

Flow Title=Multiple
Number of Profiles=7
Profile Names=10-year,25-year,50-year,1pct_min,100-year,1pct_plu,500-year
River Rch & RM= Denton Creek Tri,Reach-1,2649
     484     656     796     480     959    1913    1392
Boundary for River Rch & Prof#=Denton Creek Tri,Reach-1,1
Up Type=0
Dn Type=3
Dn Slope=0.005
Boundary for River Rch & Prof#=Denton Creek Tri,Reach-1,2
Up Type=0
Dn Type=3
Dn Slope=0.005
Boundary for River Rch & Prof#=Denton Creek Tri,Reach-1,3
Up Type=0
Dn Type=3
Dn Slope=0.005
Boundary for River Rch & Prof#=Denton Creek Tri,Reach-1,4
Up Type=0
Dn Type=3
Dn Slope=0.005
Boundary for River Rch & Prof#=Denton Creek Tri,Reach-1,5
Up Type=0
Dn Type=3
Dn Slope=0.005
Boundary for River Rch & Prof#=Denton Creek Tri,Reach-1,6
Up Type=0
Dn Type=3
Dn Slope=0.005
Boundary for River Rch & Prof#=Denton Creek Tri,Reach-1,7
Up Type=0
Dn Type=3
Dn Slope=0.005

--- Denton Creek Tributary 14_5.g01 (geometry) ---

Geom Title=Existing Conditions

River Reach=Denton Creek Tri,Reach-1
Reach XY= 30
      2348979.00      7098510.00      2348959.44      7098439.36
      2348872.29      7098401.85      2348835.99      7098360.22
      2348928.75      7098244.78      2348923.67      7098157.34
      2348885.03      7098118.17      2348834.14      7098104.52
      2348828.00      7098065.43      2348832.67      7098011.67
      2348877.78      7097949.50      2348881.29      7097765.93
      2348925.66      7097708.25      2348928.41      7097670.61
      2348842.23      7097573.63      2348776.43      7097554.26
      2348732.45      7097508.75      2348728.48      7097325.22
      2348680.22      7097249.50      2348679.04      7097029.98
      2348659.45      7096957.67      2348599.09      7096882.93
      2348559.76      7096785.00      2348354.39      7096771.47
      2348279.03      7096736.04      2348262.82      7096702.53
      2348287.07      7096670.74      2348322.84      7096665.49
      2348468.11      7096520.00      2348429.00      7096460.00

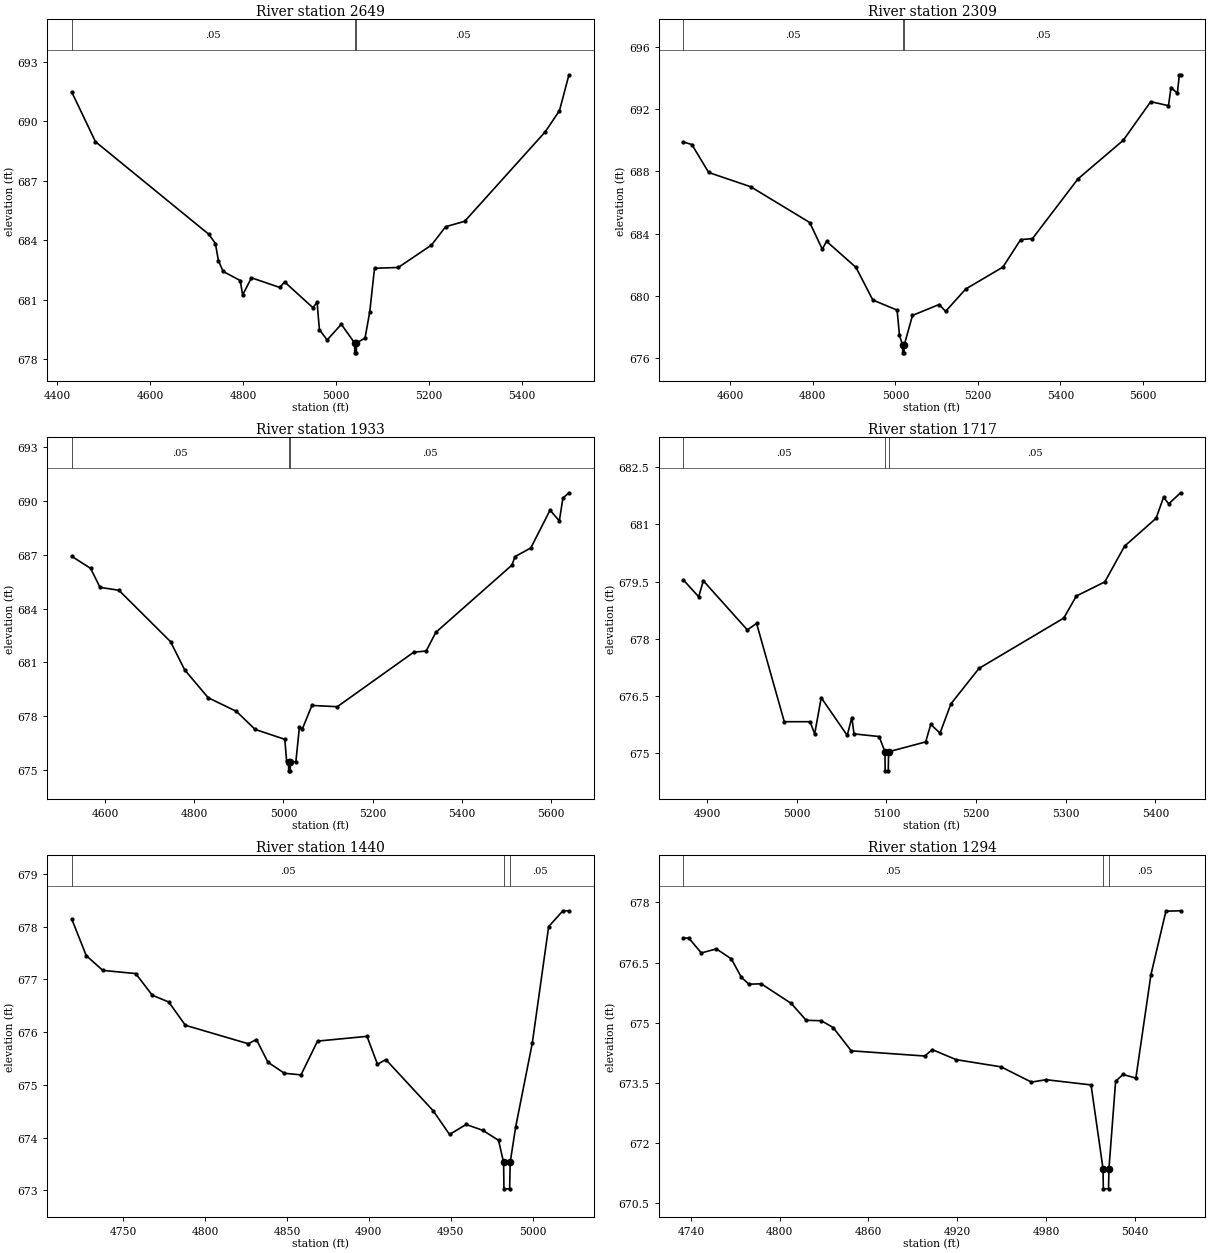
Type RM Length L Ch R = 1,2649,340,340,340
BEGIN DESCRIPTION:
Denton Creek Tributary 14_5 4.0
END DESCRIPTION:
XS GIS Cut Line= 3
      2349479.01      7098510.00      2348929.00      7098410.00
      2348429.03      7098509.99
#Sta/Elev= 30
  4431.7  691.47  4482.5  688.97  4726.5  684.29  4740.4  683.83  4746.8  682.97
  4757.0  682.42  4793.8  681.96  4798.9  681.23  4817.9  682.10  4878.9  681.61
  4889.1  681.89  4950.1  680.59  4959.0  680.87  4964.0  679.48  4980.6  678.96
  5011.1  679.75  5039.7  678.81  5040.0  678.31  5043.5  678.31  5043.7  678.81
  5062.1  679.05  5072.3  680.39  5082.5  682.58  5133.5  682.62  5204.9  683.75
  5235.5  684.68  5276.3  684.95  5449.6  689.47  5480.2  690.54  5500.6  692.35
#Mann=3,-1,0
  4431.7    0.05       0  5039.7   0.033       0  5043.7    0.05       0
Bank Sta=5039.7,5043.7
Exp/Cntr=0.3,0.1

Type RM Length L Ch R = 1,2309,376,376,376
BEGIN DESCRIPTION:
Denton Creek Tributary 14_5 3.0
END DESCRIPTION:
XS GIS Cut Line= 3
      2349428.99      7098260.00      2348929.00      7098160.00
      2348329.01      7098510.00
#Sta/Elev= 30
  4486.4  689.89  4506.8  689.73  4547.6  687.93  4649.6  687.01  4792.3  684.71
  4822.9  682.99  4833.1  683.50  4904.5  681.82  4945.3  679.72  5004.1  679.07
  5009.9  677.44  5017.4  676.82  5017.7  676.32  5021.2  676.32  5021.4  676.82
  5041.4  678.73  5105.9  679.43  5121.6  678.99  5170.4  680.43  5260.5  681.84
  5303.5  683.61  5332.0  683.67  5442.4  687.52  5552.0  690.00  5618.6  692.49
  5661.6  692.23  5667.8  693.40  5683.1  693.03  5688.0  694.22  5690.9  694.22
#Mann=3,-1,0
  4486.4    0.05       0  5017.4   0.033       0  5021.4    0.05       0
Bank Sta=5017.4,5021.4
Exp/Cntr=0.3,0.1

Type RM Length L Ch R = 1,1933,216,216,216
BEGIN DESCRIPTION:
Denton Creek Tributary 14_5 2.0
END DESCRIPTION:
XS GIS Cut Line= 3
      2349328.97      7098009.99      2348879.00      7097860.00
      2348379.01      7098259.99
#Sta/Elev= 30
  4525.7  686.92  4567.8  686.25  4588.9  685.19  4631.1  685.03  4747.0  682.16
  4778.6  680.59  4831.4  679.03  4894.6  678.27  4936.8  677.26  5003.2  676.71
  5007.2  675.50  5011.6  675.45  5011.9  674.95  5015.4  674.95  5015.6  675.45
  5028.0  675.46  5036.0  677.40  5042.4  677.28  5064.0  678.60  5120.9  678.53
  5292.1  681.57  5320.2  681.64  5341.8  682.68  5512.3  686.43  5519.5  686.91
  5554.7  687.39  5597.9  689.50  5618.7  688.90  5626.7  690.17  5640.3  690.47
#Mann=3,-1,0
  4525.7    0.05       0  5011.6   0.033       0  5015.6    0.05       0
Bank Sta=5011.6,5015.6
Exp/Cntr=0.3,0.1

Type RM Length L Ch R = 1,1717,277,277,277
BEGIN DESCRIPTION:
Mapping XS 8b1bbe59
END DESCRIPTION:
XS GIS Cut Line= 3
      2349048.23      7097630.34      2348863.00      7097676.21
      2348545.16      7097852.95
#Sta/Elev= 30
  4873.5  679.54  4890.5  679.10  4895.7  679.52  4944.8  678.23  4955.1  678.40
  4986.0  675.82  5014.7  675.82  5019.9  675.50  5027.2  676.45  5056.2  675.46
  5061.3  675.93  5063.8  675.50  5091.8  675.43  5098.3  675.03  5098.5  674.53
  5102.0  674.53  5102.3  675.03  5143.7  675.29  5149.4  675.75  5159.7  675.52
  5171.9  676.29  5203.2  677.22  5297.7  678.54  5311.8  679.12  5343.5  679.49
  5365.6  680.43  5400.7  681.16  5409.0  681.71  5414.8  681.54  5428.0  681.83
#Mann=3,-1,0
  4873.5    0.05       0  5098.3   0.033       0  5102.3    0.05       0
Bank Sta=5098.3,5102.3
Exp/Cntr=0.3,0.1

Type RM Length L Ch R = 1,1440,146,146,146
BEGIN DESCRIPTION:
Mapping XS 0eb94dbf
END DESCRIPTION:
XS GIS Cut Line= 2
      2349007.70      7097450.66      2348706.75      7097489.96
#Sta/Elev= 30
  4718.7  678.14  4727.5  677.45  4737.6  677.17  4757.7  677.11  4767.8  676.70
  4777.9  676.57  4788.0  676.13  4826.4  675.78  4831.4  675.86  4838.4  675.43
  4848.5  675.22  4858.6  675.19  4868.7  675.83  4898.9  675.92  4905.3  675.39
  4910.4  675.48  4939.3  674.51  4949.3  674.06  4959.4  674.25  4969.5  674.14
  4979.2  673.95  4982.3  673.53  4982.5  673.03  4986.0  673.03  4986.3  673.53
  4989.7  674.21  4999.8  675.79  5009.8  678.00  5018.5  678.30  5022.2  678.30
#Mann=3,-1,0
  4718.7    0.05       0  4982.3   0.033       0  4986.3    0.05       0
Bank Sta=4982.3,4986.3
Exp/Cntr=0.3,0.1

Type RM Length L Ch R = 1,1294,211,211,211
BEGIN DESCRIPTION:
Mapping XS b240ad97
END DESCRIPTION:
XS GIS Cut Line= 2
      2348990.98      7097298.51      2348659.22      7097351.74
#Sta/Elev= 30
  4735.0  677.11  4738.6  677.11  4747.1  676.74  4757.3  676.84  4767.4  676.59
  4774.2  676.13  4779.3  675.96  4787.6  675.97  4807.9  675.48  4818.0  675.06
  4828.2  675.05  4836.2  674.88  4848.4  674.30  4898.1  674.17  4903.2  674.33
  4919.3  674.08  4949.7  673.90  4970.2  673.52  4980.1  673.58  5010.5  673.45
  5018.6  671.36  5018.8  670.86  5022.3  670.86  5022.6  671.36  5027.1  673.54
  5032.1  673.71  5040.8  673.62  5051.0  676.20  5061.1  677.78  5071.0  677.79
#Mann=3,-1,0
  4735.0    0.05       0  5018.6   0.033       0  5022.6    0.05       0
Bank Sta=5018.6,5022.6
Exp/Cntr=0.3,0.1

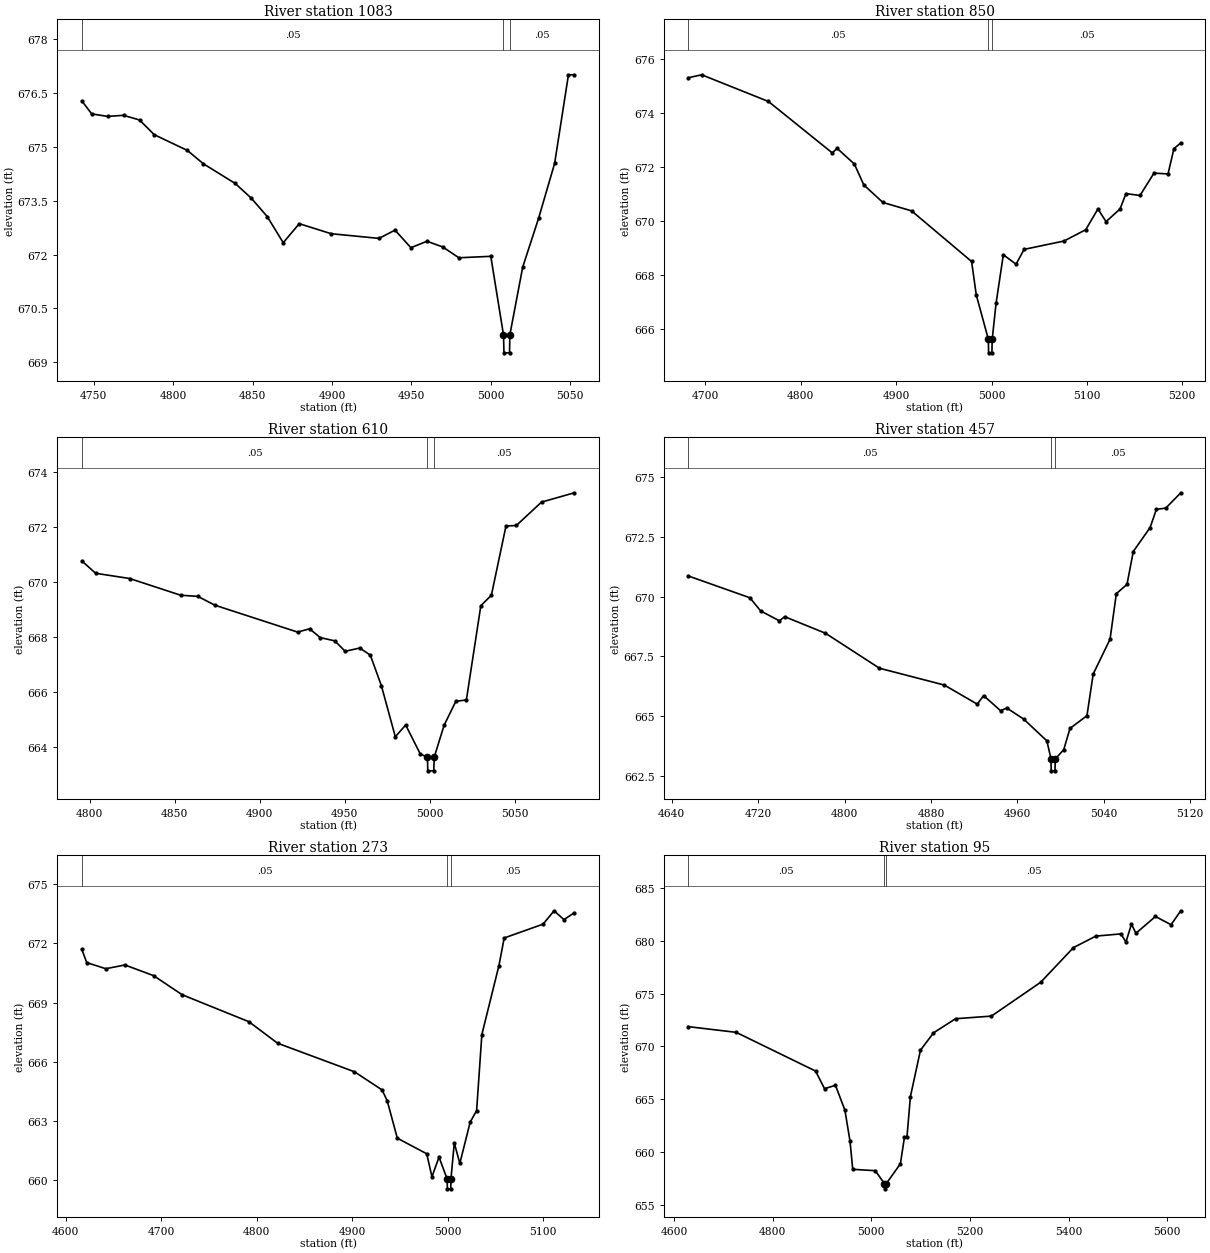
Type RM Length L Ch R = 1,1083,233,233,233
BEGIN DESCRIPTION:
Mapping XS 8336e2da
END DESCRIPTION:
XS GIS Cut Line= 2
      2348935.15      7097119.94      2348626.64      7097151.36
#Sta/Elev= 30
  4742.5  676.28  4748.7  675.92  4758.7  675.85  4768.8  675.88  4778.8  675.75
  4788.1  675.34  4809.0  674.90  4819.0  674.53  4839.1  673.98  4849.2  673.57
  4859.2  673.06  4869.3  672.33  4879.4  672.86  4899.5  672.58  4929.6  672.45
  4939.7  672.68  4949.7  672.19  4959.8  672.37  4969.8  672.21  4979.9  671.91
  5000.0  671.95  5008.0  669.76  5008.3  669.26  5011.8  669.26  5012.0  669.76
  5020.1  671.65  5030.1  673.01  5040.2  674.54  5048.9  677.01  5052.6  677.01
#Mann=3,-1,0
  4742.5    0.05       0  5008.0   0.033       0  5012.0    0.05       0
Bank Sta=5008,5012
Exp/Cntr=0.3,0.1

Type RM Length L Ch R = 1,850,240,240,240
BEGIN DESCRIPTION:
Mapping XS f764865b
END DESCRIPTION:
XS GIS Cut Line= 3
      2348952.99      7096919.47      2348655.98      7096910.78
      2348478.20      7097039.29
#Sta/Elev= 30
  4682.0  675.32  4696.0  675.43  4766.0  674.44  4833.0  672.53  4838.0  672.70
  4856.1  672.12  4866.1  671.34  4886.1  670.69  4916.1  670.38  4979.1  668.50
  4984.0  667.26  4996.7  665.61  4996.9  665.11  5000.4  665.11  5000.7  665.61
  5004.8  666.96  5012.4  668.75  5025.7  668.40  5034.2  668.95  5076.0  669.26
  5098.8  669.68  5111.6  670.45  5120.1  669.98  5134.8  670.45  5141.0  671.02
  5155.7  670.95  5170.4  671.78  5185.1  671.75  5191.3  672.69  5198.5  672.90
#Mann=3,-1,0
  4682.0    0.05       0  4996.7   0.033       0  5000.7    0.05       0
Bank Sta=4996.7,5000.7
Exp/Cntr=0.3,0.1

Type RM Length L Ch R = 1,610,153,153,153
BEGIN DESCRIPTION:
Mapping XS 5415ab8f
END DESCRIPTION:
XS GIS Cut Line= 3
      2348657.14      7096719.39      2348526.53      7096723.01
      2348433.81      7096852.23
#Sta/Elev= 30
  4795.3  670.77  4803.4  670.32  4823.4  670.13  4853.5  669.52  4863.5  669.48
  4873.5  669.16  4922.2  668.18  4929.3  668.30  4935.5  667.98  4944.1  667.86
  4950.2  667.48  4958.8  667.60  4965.0  667.34  4971.5  666.23  4979.7  664.37
  4985.8  664.80  4994.4  663.74  4998.6  663.63  4998.8  663.13  5002.3  663.13
  5002.6  663.63  5008.4  664.79  5015.3  665.66  5021.5  665.71  5030.0  669.14
  5036.2  669.52  5044.8  672.04  5050.9  672.06  5065.7  672.91  5085.0  673.25
#Mann=3,-1,0
  4795.3    0.05       0  4998.6   0.033       0  5002.6    0.05       0
Bank Sta=4998.6,5002.6
Exp/Cntr=0.3,0.1

Type RM Length L Ch R = 1,457,184,184,184
BEGIN DESCRIPTION:
Mapping XS 259123d4
END DESCRIPTION:
XS GIS Cut Line= 3
      2348665.94      7096713.02      2348404.70      7096718.99
      2348237.01      7096817.90
#Sta/Elev= 30
  4655.3  670.86  4712.3  669.95  4722.3  669.40  4739.6  668.99  4744.6  669.16
  4782.3  668.47  4832.3  667.01  4892.3  666.31  4922.9  665.51  4928.7  665.87
  4944.4  665.24  4950.2  665.35  4965.8  664.89  4987.3  663.98  4991.1  663.23
  4991.3  662.73  4994.8  662.73  4995.1  663.23  5002.9  663.61  5008.7  664.50
  5024.4  665.03  5030.2  666.77  5045.8  668.22  5051.6  670.12  5061.5  670.51
  5067.3  671.88  5082.9  672.88  5088.7  673.64  5097.4  673.69  5111.3  674.33
#Mann=3,-1,0
  4655.3    0.05       0  4991.1   0.033       0  4995.1    0.05       0
Bank Sta=4991.1,4995.1
Exp/Cntr=0.3,0.1

Type RM Length L Ch R = 1,273,178,178,178
BEGIN DESCRIPTION:
Mapping XS 2754db6c
END DESCRIPTION:
XS GIS Cut Line= 3
      2348704.10      7096705.71      2348439.69      7096705.18
      2348208.98      7096604.57
#Sta/Elev= 30
  4616.8  671.70  4621.9  671.03  4641.9  670.72  4661.9  670.91  4691.9  670.37
  4721.9  669.40  4791.9  668.03  4821.9  666.94  4902.5  665.49  4931.4  664.57
  4936.8  664.02  4947.4  662.12  4978.2  661.33  4983.7  660.16  4991.1  661.16
  4999.6  660.05  4999.9  659.55  5003.4  659.55  5003.6  660.05  5007.1  661.88
  5012.9  660.84  5023.8  662.94  5030.5  663.52  5036.0  667.38  5053.9  670.88
  5059.4  672.28  5100.1  672.98  5111.7  673.66  5122.0  673.21  5132.9  673.56
#Mann=3,-1,0
  4616.8    0.05       0  4999.6   0.033       0  5003.6    0.05       0
Bank Sta=4999.6,5003.6
Exp/Cntr=0.3,0.1

Type RM Length L Ch R = 1,95,0,0,0
BEGIN DESCRIPTION:
Denton Creek Tributary 14_5 1.0
END DESCRIPTION:
XS GIS Cut Line= 3
      2348815.95      7096620.29      2348473.19      7096529.66
      2347839.56      7096643.39
#Sta/Elev= 30
  4629.2  671.87  4726.2  671.33  4887.2  667.66  4905.3  665.99  4927.5  666.31
  4946.7  663.94  4957.0  661.01  4962.5  658.35  5008.3  658.22  5026.6  657.00
  5026.9  656.50  5030.6  657.00  5059.1  658.87  5067.4  661.42  5072.5  661.45
  5079.4  665.24  5099.8  669.64  5126.2  671.28  5170.9  672.62  5243.7  672.87
  5343.6  676.08  5409.9  679.36  5455.3  680.45  5506.1  680.66  5516.3  679.89
  5527.5  681.58  5536.6  680.72  5576.1  682.31  5607.7  681.53  5627.5  682.85
#Mann=3,-1,0
  4629.2    0.05       0  5026.6   0.033       0  5030.6    0.05       0
Bank Sta=5026.6,5030.6
Exp/Cntr=0.3,0.1

Chan Stop Cuts=-1