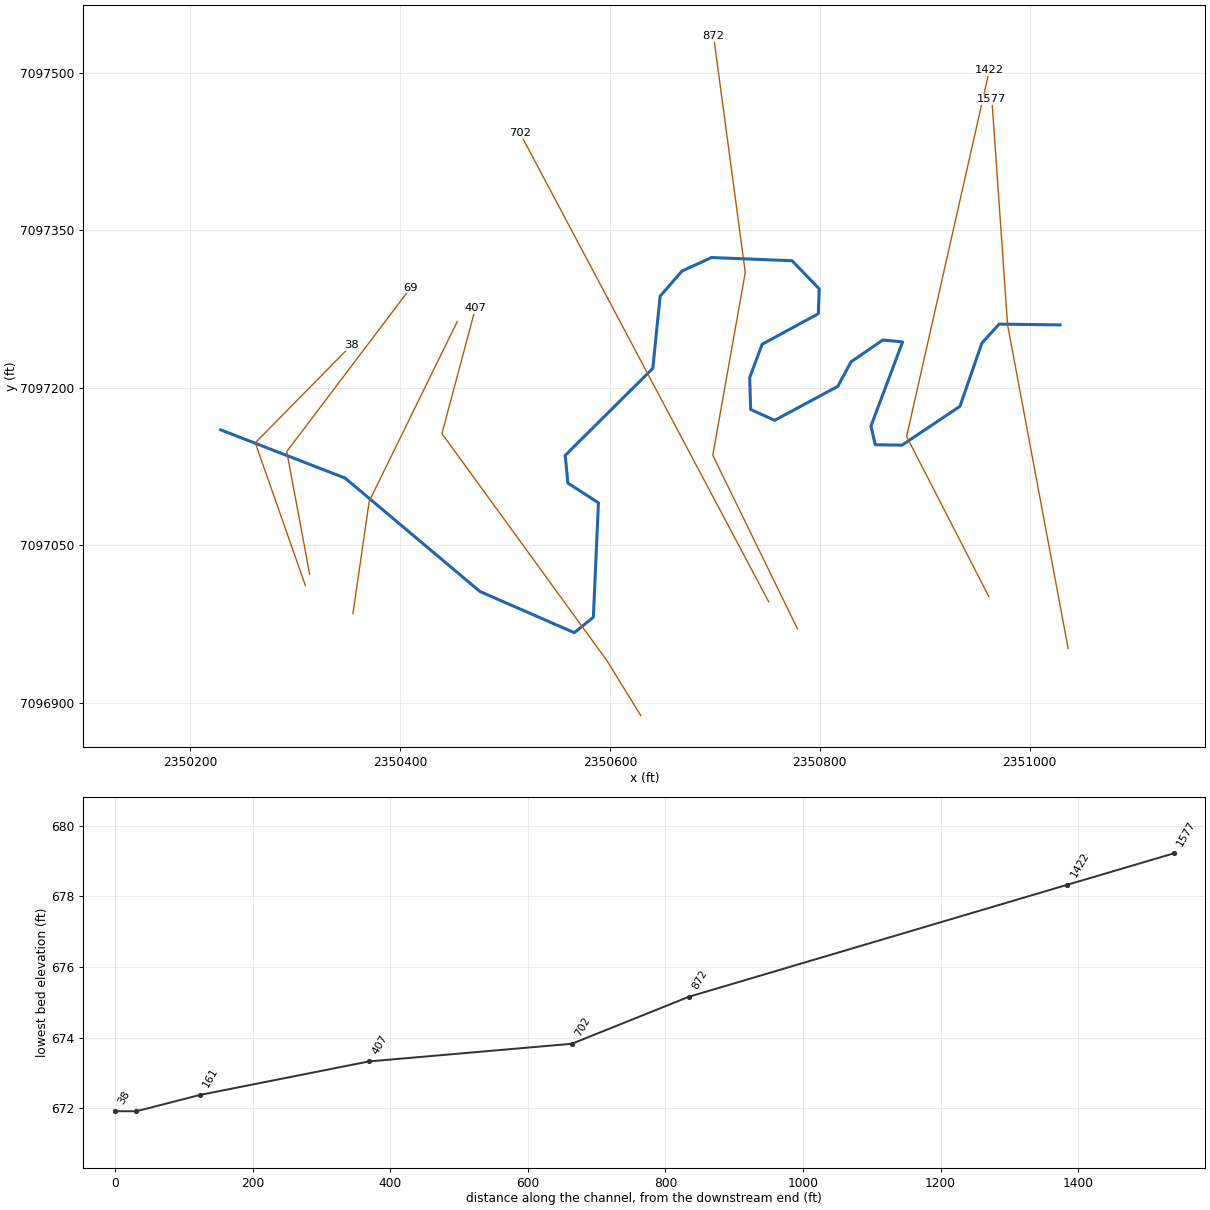
--- Denton Creek Tributary 14_6.prj (project) ---

Proj Title=Denton Creek Tributary 14_6 Base Level Engineering
Current Plan=p01
Default Exp/Contr=0.3,0.1
English Units
Geom File=g01
Flow File=f01
Plan File=p01
BEGIN DESCRIPTION:
Denton Creek Tributary 14_6
END DESCRIPTION:

--- Denton Creek Tributary 14_6.p01 (plan) ---

Plan Title=Multiple Run
Short Identifier=Multiple
Geom File=g01
Flow File=f01
Subcritical Flow
K Sum by GR= 0
Std Step Tol= 0.01
Critical Tol= 0.01
Num of Std Step Trials= 20
Max Error Tol= 0.3
Flow Tol Ratio= 0.001
Split Flow NTrial= 30
Split Flow Tol= 0.02
Split Flow Ratio= 0.02
Log Output Level= 0
Friction Slope Method= 1
Unsteady Friction Slope Method= 2
Unsteady Bridges Friction Slope Method= 1
Parabolic Critical Depth
Global Vel Dist=  1 , 1 , 1
Global Log Level= 0
CheckData=True
Encroach Param= -1, 0, 0, 0
BEGIN DESCRIPTION:
Multiple Run
END DESCRIPTION:

--- Denton Creek Tributary 14_6.f01 (steady flow) ---

Flow Title=Multiple
Number of Profiles=7
Profile Names=10-year,25-year,50-year,1pct_min,100-year,1pct_plu,500-year
River Rch & RM= Denton Creek Tri,Reach-1,1577
     365     485     581     347     691    1380     979
Boundary for River Rch & Prof#=Denton Creek Tri,Reach-1,1
Up Type=0
Dn Type=3
Dn Slope=0.0065
Boundary for River Rch & Prof#=Denton Creek Tri,Reach-1,2
Up Type=0
Dn Type=3
Dn Slope=0.0065
Boundary for River Rch & Prof#=Denton Creek Tri,Reach-1,3
Up Type=0
Dn Type=3
Dn Slope=0.0065
Boundary for River Rch & Prof#=Denton Creek Tri,Reach-1,4
Up Type=0
Dn Type=3
Dn Slope=0.0065
Boundary for River Rch & Prof#=Denton Creek Tri,Reach-1,5
Up Type=0
Dn Type=3
Dn Slope=0.0065
Boundary for River Rch & Prof#=Denton Creek Tri,Reach-1,6
Up Type=0
Dn Type=3
Dn Slope=0.0065
Boundary for River Rch & Prof#=Denton Creek Tri,Reach-1,7
Up Type=0
Dn Type=3
Dn Slope=0.0065

--- Denton Creek Tributary 14_6.g01 (geometry) ---

Geom Title=Existing Conditions

River Reach=Denton Creek Tri,Reach-1
Reach XY= 30
      2351029.00      7097260.00      2350970.99      7097260.77
      2350954.54      7097242.75      2350933.59      7097182.40
      2350878.46      7097145.42      2350852.89      7097145.77
      2350848.79      7097163.56      2350878.95      7097243.83
      2350860.04      7097245.58      2350829.73      7097224.75
      2350817.22      7097201.49      2350757.04      7097169.07
      2350734.13      7097179.36      2350733.22      7097209.73
      2350745.06      7097241.58      2350798.62      7097270.61
      2350799.45      7097294.40      2350773.57      7097321.17
      2350696.85      7097324.22      2350668.66      7097311.34
      2350647.83      7097287.31      2350640.87      7097218.54
      2350557.39      7097135.66      2350559.93      7097109.27
      2350589.05      7097090.46      2350584.23      7096981.43
      2350566.07      7096966.68      2350476.14      7097005.90
      2350347.60      7097114.01      2350229.00      7097160.00

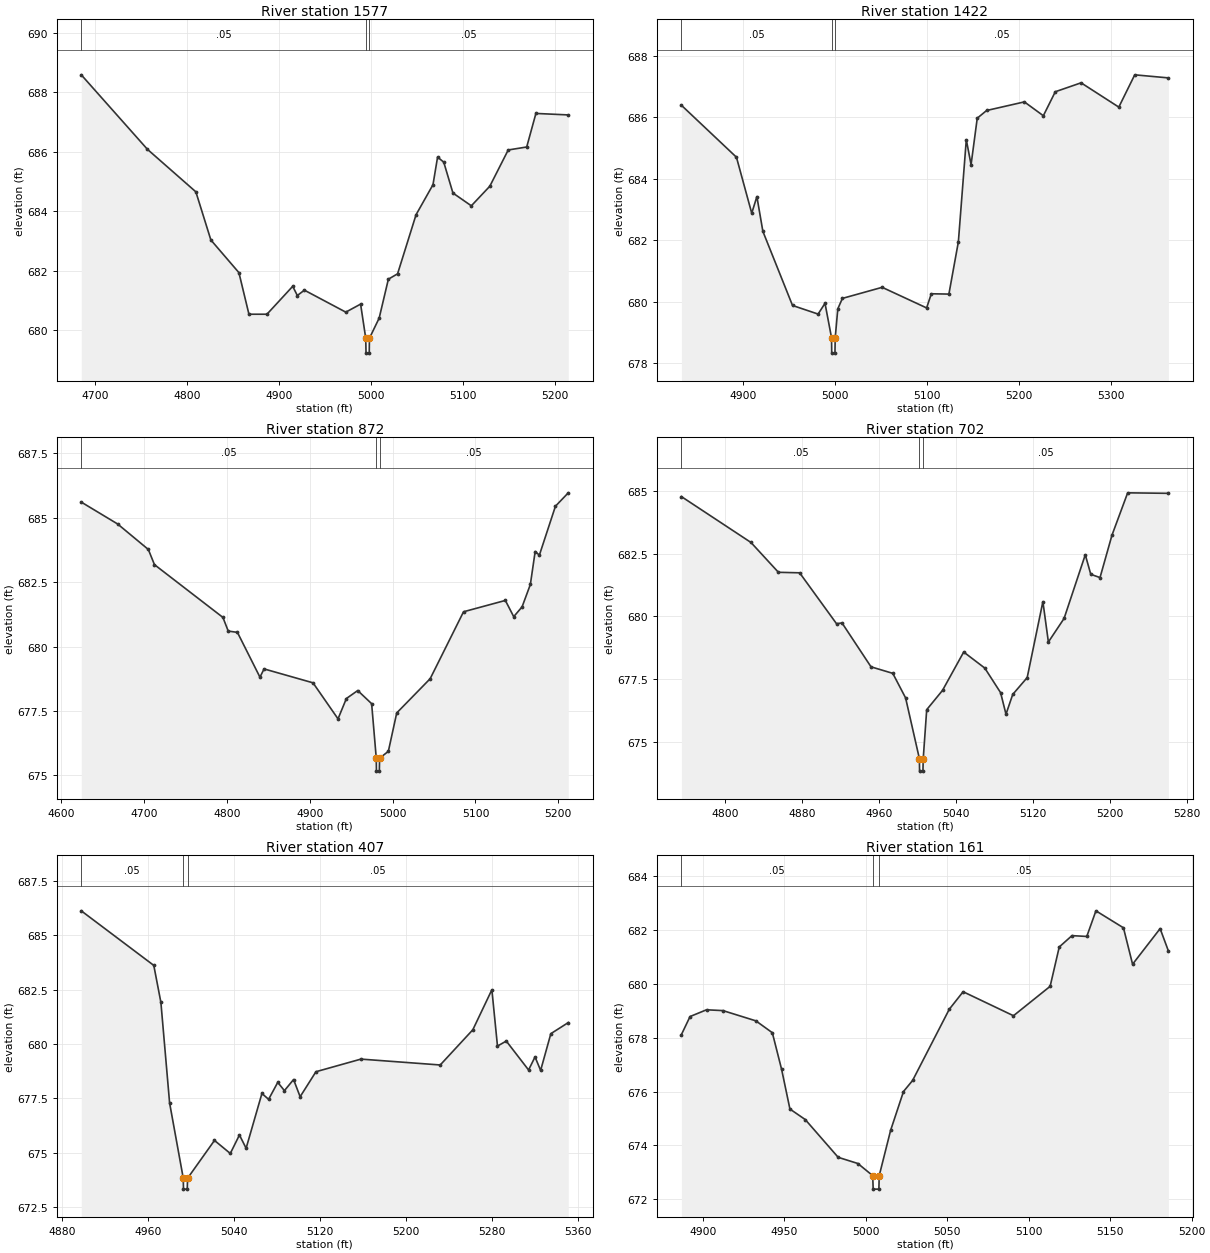
Type RM Length L Ch R = 1,1577,155,155,155
BEGIN DESCRIPTION:
Denton Creek Tributary 14_6 3.0
END DESCRIPTION:
XS GIS Cut Line= 3
      2351036.75      7096951.50      2350979.00      7097260.00
      2350964.01      7097475.12
#Sta/Elev= 30
  4685.0  688.59  4757.0  686.08  4809.6  684.65  4825.9  683.03  4856.4  681.93
  4867.3  680.53  4886.9  680.53  4914.9  681.47  4919.9  681.16  4927.6  681.34
  4972.6  680.60  4988.7  680.87  4994.3  679.72  4994.6  679.22  4998.1  679.22
  4998.3  679.72  5008.9  680.40  5018.9  681.71  5028.9  681.89  5049.0  683.88
  5067.4  684.89  5072.4  685.82  5079.1  685.65  5089.1  684.61  5109.1  684.18
  5129.2  684.84  5149.2  686.06  5169.3  686.16  5179.3  687.29  5214.5  687.24
#Mann=3,-1,0
  4685.0    0.05       0  4994.3   0.033       0  4998.3    0.05       0
Bank Sta=4994.3,4998.3
Exp/Cntr=0.3,0.1

Type RM Length L Ch R = 1,1422,550,550,550
BEGIN DESCRIPTION:
Mapping XS 9e45d6e4
END DESCRIPTION:
XS GIS Cut Line= 3
      2350961.05      7097001.26      2350882.74      7097153.60
      2350961.63      7097502.60
#Sta/Elev= 30
  4833.2  686.39  4893.0  684.70  4909.6  682.88  4915.2  683.42  4921.7  682.29
  4953.9  679.88  4981.7  679.60  4989.2  679.95  4996.3  678.83  4996.5  678.33
  5000.0  678.33  5000.3  678.83  5003.1  679.77  5008.1  680.11  5051.3  680.47
  5099.6  679.80  5104.7  680.26  5123.8  680.25  5134.1  681.95  5142.7  685.27
  5147.9  684.46  5154.6  685.97  5164.8  686.22  5205.8  686.50  5226.4  686.05
  5239.4  686.83  5267.4  687.12  5308.4  686.33  5325.7  687.38  5362.3  687.28
#Mann=3,-1,0
  4833.2    0.05       0  4996.3   0.033       0  5000.3    0.05       0
Bank Sta=4996.3,5000.3
Exp/Cntr=0.3,0.1

Type RM Length L Ch R = 1,872,170,170,170
BEGIN DESCRIPTION:
Denton Creek Tributary 14_6 2.0
END DESCRIPTION:
XS GIS Cut Line= 4
      2350778.65      7096970.51      2350698.03      7097135.75
      2350729.00      7097310.00      2350698.79      7097535.35
#Sta/Elev= 30
  4623.9  685.61  4667.8  684.76  4704.9  683.77  4712.3  683.18  4795.0  681.13
  4801.4  680.60  4812.5  680.55  4839.7  678.81  4844.7  679.13  4903.8  678.59
  4934.0  677.19  4944.1  677.98  4957.8  678.29  4974.6  677.78  4980.2  675.66
  4980.4  675.16  4983.9  675.16  4984.2  675.66  4994.8  675.93  5004.9  677.42
  5045.3  678.75  5085.6  681.35  5136.1  681.79  5146.2  681.16  5156.3  681.54
  5166.3  682.41  5172.1  683.69  5177.2  683.55  5196.6  685.45  5212.1  685.97
#Mann=3,-1,0
  4623.9    0.05       0  4980.2   0.033       0  4984.2    0.05       0
Bank Sta=4980.2,4984.2
Exp/Cntr=0.3,0.1

Type RM Length L Ch R = 1,702,295,295,295
BEGIN DESCRIPTION:
Mapping XS 7e2e1f65
END DESCRIPTION:
XS GIS Cut Line= 2
      2350751.31      7096996.20      2350514.36      7097442.72
#Sta/Elev= 30
  4755.0  684.78  4827.2  682.95  4855.7  681.76  4877.7  681.74  4916.0  679.71
  4921.7  679.74  4951.8  677.99  4974.4  677.73  4987.7  676.75  5002.0  674.33
  5002.2  673.83  5005.7  673.83  5006.0  674.33  5009.6  676.28  5026.0  677.05
  5048.0  678.58  5069.9  677.94  5086.3  676.96  5091.9  676.10  5098.9  676.89
  5113.9  677.56  5130.2  680.59  5135.9  678.98  5152.2  679.92  5174.2  682.46
  5179.9  681.68  5189.5  681.55  5201.9  683.24  5218.2  684.93  5260.5  684.91
#Mann=3,-1,0
  4755.0    0.05       0  5002.0   0.033       0  5006.0    0.05       0
Bank Sta=5002,5006
Exp/Cntr=0.3,0.1

Type RM Length L Ch R = 1,407,246,246,246
BEGIN DESCRIPTION:
Mapping XS e787dea4
END DESCRIPTION:
XS GIS Cut Line= 4
      2350629.51      7096887.54      2350597.01      7096940.19
      2350439.89      7097156.45      2350471.74      7097275.69
#Sta/Elev= 30
  4898.0  686.13  4965.4  683.62  4972.0  681.92  4980.1  677.29  4992.8  673.83
  4993.0  673.33  4996.5  673.33  4996.8  673.83  5021.8  675.57  5036.5  674.97
  5045.0  675.82  5051.2  675.21  5065.9  677.73  5072.1  677.46  5080.6  678.24
  5086.8  677.86  5095.3  678.37  5101.4  677.58  5116.1  678.73  5157.9  679.31
  5231.6  679.04  5261.9  680.66  5279.6  682.50  5284.8  679.91  5293.0  680.14
  5313.7  678.81  5319.7  679.41  5324.9  678.79  5334.4  680.48  5350.6  680.99
#Mann=3,-1,0
  4898.0    0.05       0  4992.8    0.05       0  4996.8    0.05       0
Bank Sta=4992.8,4996.8
Exp/Cntr=0.3,0.1

Type RM Length L Ch R = 1,161,92,92,92
BEGIN DESCRIPTION:
Mapping XS fd59ea84
END DESCRIPTION:
XS GIS Cut Line= 3
      2350355.07      7096984.79      2350370.60      7097091.98
      2350454.47      7097263.13
#Sta/Elev= 30
  4886.8  678.11  4892.1  678.78  4902.2  679.03  4912.3  679.00  4932.5  678.62
  4942.6  678.18  4948.3  676.82  4953.4  675.35  4962.8  674.96  4983.0  673.56
  4995.1  673.33  5004.2  672.88  5004.5  672.38  5008.0  672.38  5008.2  672.88
  5015.2  674.56  5023.1  676.00  5028.7  676.41  5051.2  679.05  5059.7  679.70
  5090.6  678.81  5113.1  679.90  5118.7  681.36  5126.5  681.78  5135.6  681.75
  5141.2  682.70  5158.1  682.07  5163.7  680.72  5180.6  682.04  5185.7  681.21
#Mann=3,-1,0
  4886.8    0.05       0  5004.2    0.05       0  5008.2    0.05       0
Bank Sta=5004.2,5008.2
Exp/Cntr=0.3,0.1

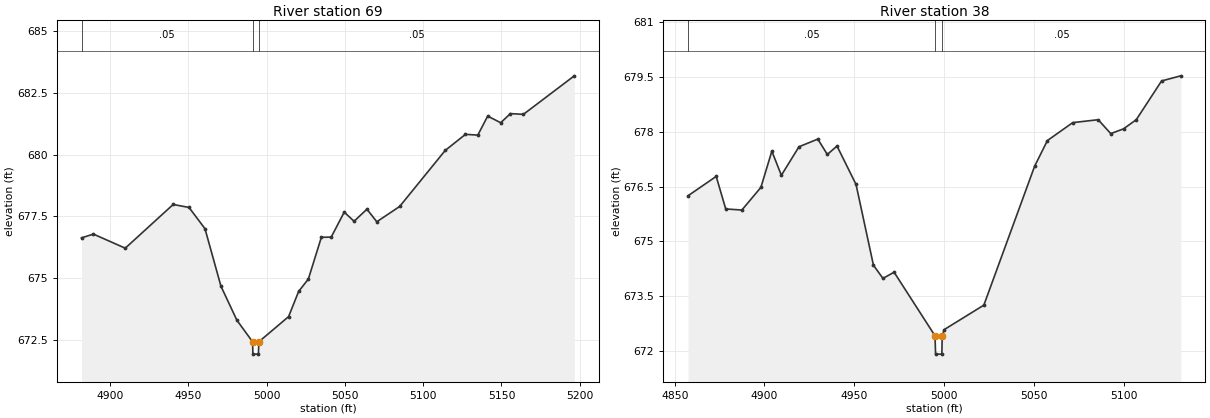
Type RM Length L Ch R = 1,69,31,31,31
BEGIN DESCRIPTION:
Mapping XS 60378228
END DESCRIPTION:
XS GIS Cut Line= 3
      2350313.81      7097022.53      2350292.00      7097139.30
      2350410.16      7097295.44
#Sta/Elev= 30
  4881.9  676.63  4889.5  676.78  4909.8  676.21  4940.4  677.98  4950.5  677.86
  4960.7  677.00  4970.9  674.67  4981.1  673.29  4991.1  672.42  4991.3  671.92
  4994.8  671.92  4995.1  672.42  5014.1  673.44  5020.5  674.46  5026.7  674.96
  5035.0  676.65  5041.3  676.66  5049.6  677.67  5055.9  677.30  5064.1  677.79
  5070.4  677.28  5085.0  677.90  5114.1  680.17  5127.0  680.82  5134.9  680.79
  5141.2  681.56  5149.5  681.29  5155.7  681.66  5164.0  681.63  5196.5  683.19
#Mann=3,-1,0
  4881.9    0.05       0  4991.1    0.05       0  4995.1    0.05       0
Bank Sta=4991.1,4995.1
Exp/Cntr=0.3,0.1

Type RM Length L Ch R = 1,38,0,0,0
BEGIN DESCRIPTION:
Denton Creek Tributary 14_6 1.0
END DESCRIPTION:
XS GIS Cut Line= 3
      2350309.71      7097011.70      2350262.00      7097147.61
      2350353.52      7097240.58
#Sta/Elev= 30
  4857.4  676.25  4873.1  676.78  4878.4  675.89  4887.4  675.86  4898.0  676.48
  4904.1  677.47  4909.4  676.81  4919.2  677.59  4929.7  677.80  4935.0  677.38
  4940.4  677.61  4951.0  676.56  4960.7  674.35  4966.0  673.99  4972.2  674.16
  4995.0  672.42  4995.3  671.92  4998.8  671.92  4999.0  672.42  5000.1  672.59
  5022.2  673.26  5050.5  677.06  5057.6  677.76  5071.7  678.25  5085.9  678.33
  5092.9  677.95  5100.0  678.08  5107.1  678.33  5121.2  679.39  5131.9  679.53
#Mann=3,-1,0
  4857.4    0.05       0  4995.0    0.05       0  4999.0    0.05       0
Bank Sta=4995,4999
Exp/Cntr=0.3,0.1

Chan Stop Cuts=-1