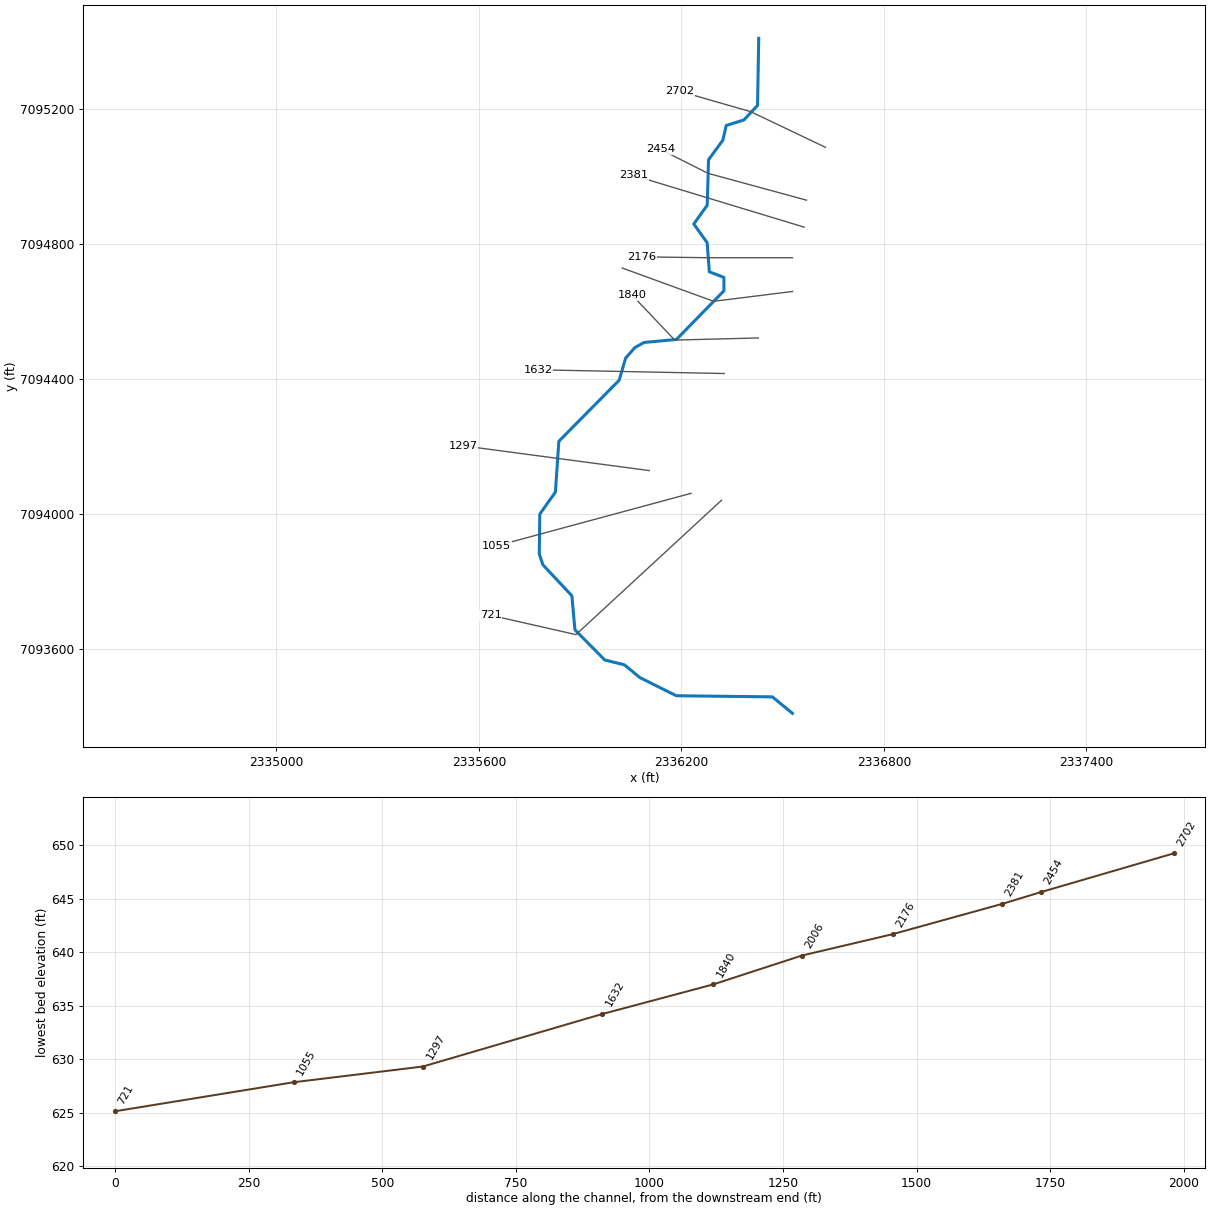
--- Denton Creek Tributary 15.prj (project) ---

Proj Title=Denton Creek Tributary 15 Base Level Engineering
Current Plan=p01
Default Exp/Contr=0.3,0.1
English Units
Geom File=g01
Flow File=f01
Plan File=p01
BEGIN DESCRIPTION:
Denton Creek Tributary 15
END DESCRIPTION:

--- Denton Creek Tributary 15.p01 (plan) ---

Plan Title=Multiple Run
Short Identifier=Multiple
Geom File=g01
Flow File=f01
Subcritical Flow
K Sum by GR= 0
Std Step Tol= 0.01
Critical Tol= 0.01
Num of Std Step Trials= 20
Max Error Tol= 0.3
Flow Tol Ratio= 0.001
Split Flow NTrial= 30
Split Flow Tol= 0.02
Split Flow Ratio= 0.02
Log Output Level= 0
Friction Slope Method= 1
Unsteady Friction Slope Method= 2
Unsteady Bridges Friction Slope Method= 1
Parabolic Critical Depth
Global Vel Dist=  1 , 1 , 1
Global Log Level= 0
CheckData=True
Encroach Param= -1, 0, 0, 0
BEGIN DESCRIPTION:
Multiple Run
END DESCRIPTION:

--- Denton Creek Tributary 15.f01 (steady flow) ---

Flow Title=Multiple
Number of Profiles=7
Profile Names=10-year,25-year,50-year,1pct_min,100-year,1pct_plu,500-year
River Rch & RM= Denton Creek Tri,Reach-1,2702
     277     363     432     256     510    1018     712
Boundary for River Rch & Prof#=Denton Creek Tri,Reach-1,1
Up Type=0
Dn Type=3
Dn Slope=0.00508
Boundary for River Rch & Prof#=Denton Creek Tri,Reach-1,2
Up Type=0
Dn Type=3
Dn Slope=0.00508
Boundary for River Rch & Prof#=Denton Creek Tri,Reach-1,3
Up Type=0
Dn Type=3
Dn Slope=0.00508
Boundary for River Rch & Prof#=Denton Creek Tri,Reach-1,4
Up Type=0
Dn Type=3
Dn Slope=0.00508
Boundary for River Rch & Prof#=Denton Creek Tri,Reach-1,5
Up Type=0
Dn Type=3
Dn Slope=0.00508
Boundary for River Rch & Prof#=Denton Creek Tri,Reach-1,6
Up Type=0
Dn Type=3
Dn Slope=0.00508
Boundary for River Rch & Prof#=Denton Creek Tri,Reach-1,7
Up Type=0
Dn Type=3
Dn Slope=0.00508

--- Denton Creek Tributary 15.g01 (geometry) ---

Geom Title=Existing Conditions

River Reach=Denton Creek Tri,Reach-1
Reach XY= 30
      2336429.00      7095410.00      2336425.53      7095211.26
      2336385.08      7095168.15      2336332.69      7095151.80
      2336322.72      7095108.16      2336280.36      7095050.36
      2336276.41      7094915.45      2336236.56      7094860.00
      2336276.30      7094804.43      2336282.62      7094718.48
      2336325.85      7094701.63      2336325.98      7094661.98
      2336185.17      7094517.86      2336089.33      7094508.90
      2336061.87      7094493.70      2336034.74      7094462.57
      2336015.36      7094396.80      2335836.82      7094216.19
      2335826.61      7094065.53      2335780.37      7094000.33
      2335778.78      7093882.66      2335789.50      7093850.21
      2335875.37      7093758.50      2335884.52      7093657.56
      2335972.93      7093568.13      2336031.18      7093553.90
      2336076.80      7093516.08      2336184.93      7093462.24
      2336469.45      7093458.90      2336529.00      7093410.00

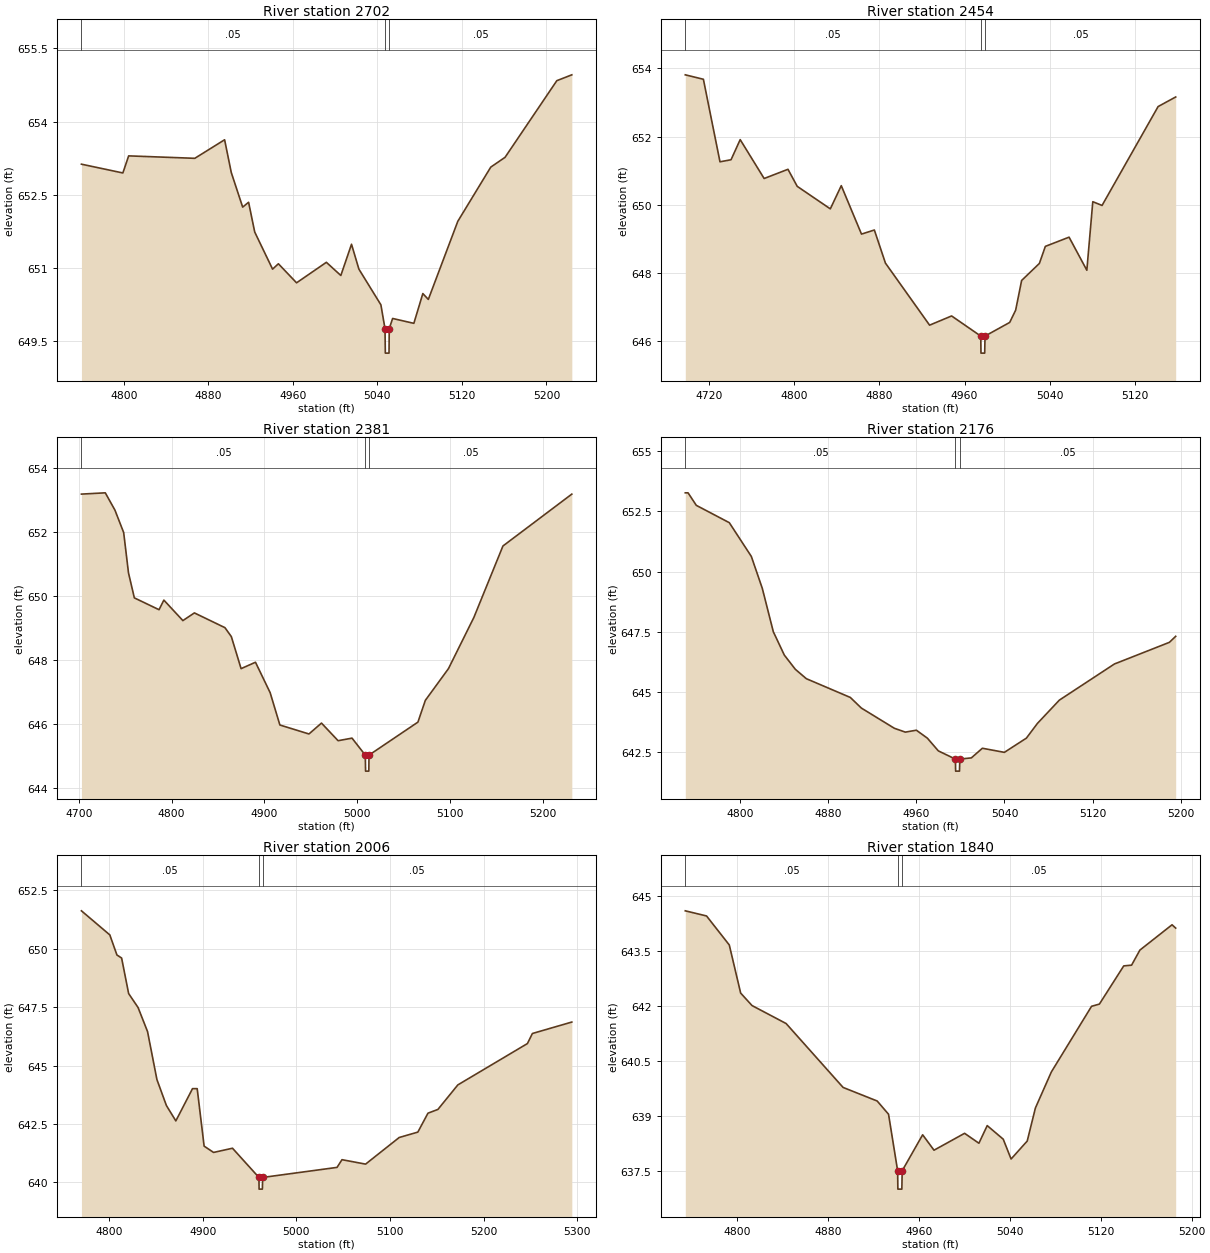
Type RM Length L Ch R = 1,2702,248,248,248
BEGIN DESCRIPTION:
Denton Creek Tributary 15 7.0
END DESCRIPTION:
XS GIS Cut Line= 3
      2336626.99      7095087.00      2336405.43      7095192.68
      2336195.30      7095253.05
#Sta/Elev= 30
  4759.9  653.13  4799.1  652.95  4804.6  653.30  4867.2  653.25  4895.4  653.63
  4901.7  652.96  4912.5  652.25  4918.1  652.35  4923.9  651.74  4940.8  650.98
  4946.3  651.09  4963.5  650.70  4991.7  651.12  5005.4  650.85  5015.5  651.49
  5022.5  650.98  5043.3  650.25  5047.2  649.76  5047.5  649.26  5051.0  649.26
  5051.2  649.76  5054.4  649.97  5074.5  649.87  5083.0  650.48  5088.2  650.36
  5116.1  651.96  5147.3  653.07  5160.8  653.27  5209.8  654.84  5224.0  654.96
#Mann=3,-1,0
  4759.9    0.05       0  5047.2   0.033       0  5051.2    0.05       0
Bank Sta=5047.2,5051.2
Exp/Cntr=0.3,0.1

Type RM Length L Ch R = 1,2454,73,73,73
BEGIN DESCRIPTION:
Denton Creek Tributary 15 6.0
END DESCRIPTION:
XS GIS Cut Line= 3
      2336570.48      7094930.53      2336279.00      7095010.00
      2336137.18      7095081.39
#Sta/Elev= 30
  4697.5  653.81  4714.5  653.68  4730.1  651.26  4740.5  651.32  4749.1  651.91
  4771.6  650.77  4794.0  651.04  4802.7  650.54  4833.8  649.88  4844.1  650.56
  4863.1  649.14  4875.2  649.26  4885.6  648.29  4927.1  646.47  4947.8  646.74
  4975.2  646.15  4975.4  645.65  4978.9  645.65  4979.2  646.15  5002.4  646.55
  5008.0  646.91  5013.6  647.78  5030.3  648.28  5035.9  648.78  5058.2  649.05
  5074.9  648.08  5080.5  650.09  5089.2  649.98  5141.9  652.88  5158.4  653.16
#Mann=3,-1,0
  4697.5    0.05       0  4975.2   0.033       0  4979.2    0.05       0
Bank Sta=4975.2,4979.2
Exp/Cntr=0.3,0.1

Type RM Length L Ch R = 1,2381,205,205,205
BEGIN DESCRIPTION:
Mapping XS 34f25a1d
END DESCRIPTION:
XS GIS Cut Line= 2
      2336563.57      7094850.61      2336058.01      7095003.93
#Sta/Elev= 30
  4702.8  653.19  4728.5  653.23  4738.9  652.69  4748.3  651.99  4753.5  650.73
  4759.8  649.95  4786.4  649.58  4791.6  649.88  4812.1  649.24  4824.5  649.48
  4857.4  649.02  4864.3  648.74  4874.8  647.74  4890.3  647.94  4906.1  646.99
  4916.6  645.98  4947.9  645.70  4961.4  646.04  4979.3  645.49  4994.3  645.57
  5008.6  645.04  5008.9  644.54  5012.4  644.54  5012.6  645.04  5065.3  646.07
  5073.3  646.75  5098.2  647.74  5125.6  649.34  5156.9  651.57  5231.1  653.19
#Mann=3,-1,0
  4702.8    0.05       0  5008.6   0.033       0  5012.6    0.05       0
Bank Sta=5008.6,5012.6
Exp/Cntr=0.3,0.1

Type RM Length L Ch R = 1,2176,170,170,170
BEGIN DESCRIPTION:
Denton Creek Tributary 15 5.0
END DESCRIPTION:
XS GIS Cut Line= 3
      2336528.97      7094760.00      2336279.00      7094760.00
      2336083.29      7094762.60
#Sta/Elev= 30
  4749.9  653.27  4752.4  653.27  4759.9  652.75  4789.9  652.03  4809.9  650.63
  4819.9  649.30  4829.9  647.50  4839.9  646.53  4849.9  645.94  4859.9  645.55
  4899.9  644.77  4909.9  644.33  4939.9  643.49  4949.9  643.33  4959.9  643.41
  4969.9  643.08  4979.9  642.55  4995.4  642.21  4995.6  641.71  4999.1  641.71
  4999.4  642.21  5009.9  642.26  5019.9  642.66  5039.9  642.49  5059.9  643.08
  5069.9  643.69  5089.9  644.66  5139.9  646.16  5189.9  647.06  5195.6  647.31
#Mann=3,-1,0
  4749.9    0.05       0  4995.4    0.04       0  4999.4    0.05       0
Bank Sta=4995.4,4999.4
Exp/Cntr=0.3,0.1

Type RM Length L Ch R = 1,2006,166,166,166
BEGIN DESCRIPTION:
Denton Creek Tributary 15 4.0
END DESCRIPTION:
XS GIS Cut Line= 3
      2336529.02      7094660.00      2336295.30      7094630.85
      2336024.64      7094729.48
#Sta/Elev= 30
  4770.5  651.62  4800.8  650.59  4808.4  649.73  4813.4  649.60  4820.9  648.08
  4831.0  647.48  4841.1  646.45  4851.1  644.40  4861.2  643.29  4871.3  642.63
  4889.1  644.01  4894.1  644.01  4901.5  641.55  4911.6  641.28  4931.8  641.46
  4960.0  640.21  4960.2  639.71  4963.7  639.71  4964.0  640.21  5043.4  640.64
  5048.7  640.97  5073.9  640.78  5109.8  641.92  5129.7  642.15  5140.5  642.96
  5151.1  643.12  5172.4  644.17  5246.7  645.94  5252.0  646.37  5294.1  646.86
#Mann=3,-1,0
  4770.5    0.05       0  4960.0   0.033       0  4964.0    0.05       0
Bank Sta=4960,4964
Exp/Cntr=0.3,0.1

Type RM Length L Ch R = 1,1840,208,208,208
BEGIN DESCRIPTION:
Mapping XS 0830a44c
END DESCRIPTION:
XS GIS Cut Line= 3
      2336427.71      7094522.27      2336180.18      7094516.01
      2336053.73      7094649.39
#Sta/Elev= 30
  4754.5  644.59  4773.2  644.45  4793.2  643.66  4803.2  642.35  4813.2  642.01
  4843.2  641.52  4893.3  639.78  4923.3  639.41  4933.3  639.05  4941.3  637.51
  4941.5  637.01  4945.0  637.01  4945.3  637.51  4963.3  638.49  4973.3  638.07
  5000.2  638.53  5012.8  638.26  5020.1  638.74  5034.2  638.37  5041.1  637.83
  5055.3  638.32  5062.5  639.22  5076.5  640.20  5111.9  641.99  5118.8  642.05
  5140.2  643.09  5147.1  643.11  5154.4  643.52  5182.7  644.21  5185.9  644.12
#Mann=3,-1,0
  4754.5    0.05       0  4941.3   0.033       0  4945.3    0.05       0
Bank Sta=4941.3,4945.3
Exp/Cntr=0.3,0.1

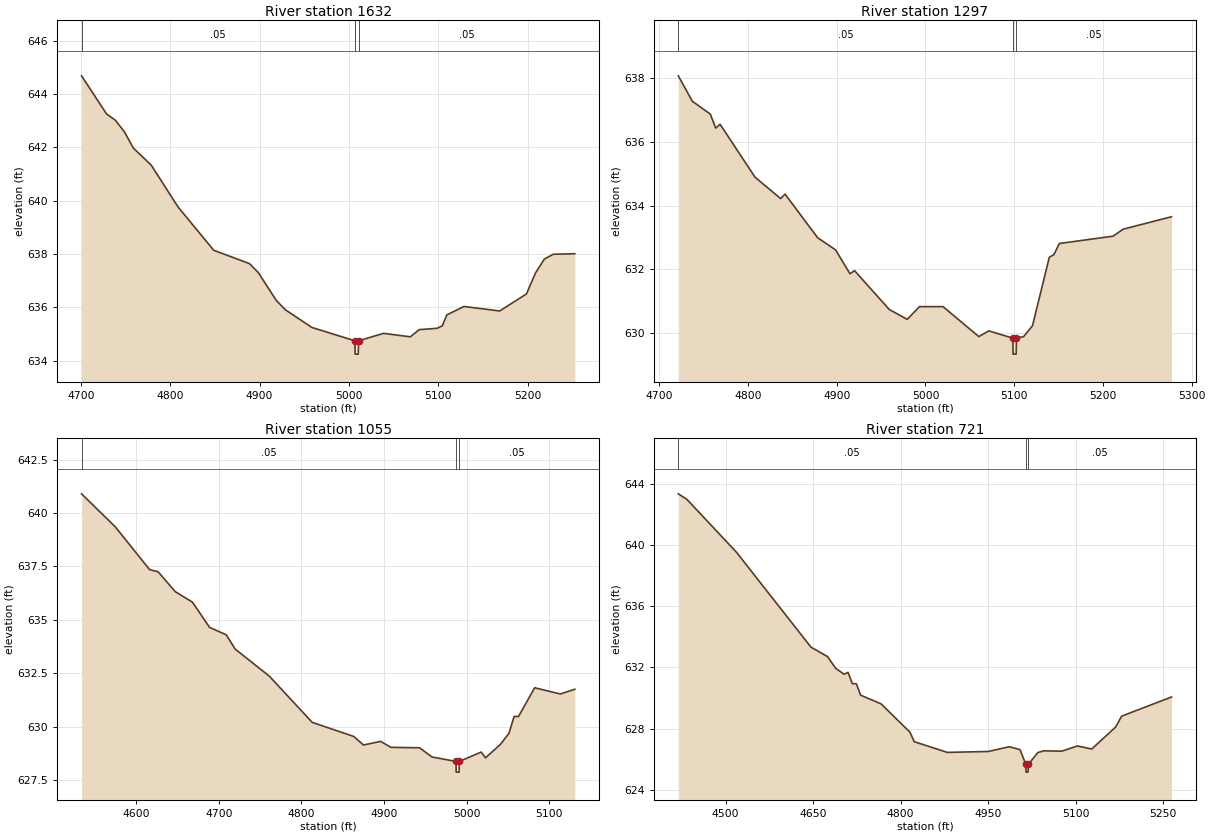
Type RM Length L Ch R = 1,1632,335,335,335
BEGIN DESCRIPTION:
Mapping XS 3596a0f6
END DESCRIPTION:
XS GIS Cut Line= 2
      2336326.89      7094416.93      2335774.90      7094427.94
#Sta/Elev= 30
  4700.8  644.69  4728.7  643.26  4738.7  643.02  4748.7  642.59  4758.7  641.98
  4778.7  641.34  4808.7  639.77  4848.7  638.14  4888.7  637.64  4898.7  637.30
  4918.7  636.26  4928.7  635.91  4958.7  635.24  5006.8  634.74  5007.0  634.24
  5010.5  634.24  5010.8  634.74  5038.8  635.02  5068.8  634.89  5078.8  635.16
  5098.8  635.21  5104.6  635.30  5109.6  635.71  5128.8  636.03  5168.8  635.86
  5198.8  636.50  5208.8  637.28  5218.8  637.81  5228.8  637.99  5252.9  638.01
#Mann=3,-1,0
  4700.8    0.05       0  5006.8    0.04       0  5010.8    0.05       0
Bank Sta=5006.8,5010.8
Exp/Cntr=0.3,0.1

Type RM Length L Ch R = 1,1297,242,242,242
BEGIN DESCRIPTION:
Mapping XS 012205f0
END DESCRIPTION:
XS GIS Cut Line= 2
      2336104.76      7094129.33      2335553.72      7094202.66
#Sta/Elev= 30
  4721.4  638.07  4737.3  637.27  4757.5  636.87  4763.5  636.43  4768.5  636.55
  4807.9  634.89  4836.7  634.22  4841.7  634.36  4878.5  632.99  4898.7  632.61
  4914.9  631.86  4920.0  631.96  4959.2  630.74  4979.4  630.43  4993.2  630.83
  5019.8  630.83  5060.1  629.89  5071.4  630.07  5098.5  629.84  5098.7  629.34
  5102.2  629.34  5102.5  629.84  5110.6  629.89  5120.6  630.23  5139.6  632.38
  5144.7  632.46  5150.9  632.81  5211.4  633.04  5222.9  633.26  5277.3  633.65
#Mann=3,-1,0
  4721.4    0.05       0  5098.5    0.04       0  5102.5    0.05       0
Bank Sta=5098.5,5102.5
Exp/Cntr=0.3,0.1

Type RM Length L Ch R = 1,1055,334,334,334
BEGIN DESCRIPTION:
Mapping XS bf3abaa2
END DESCRIPTION:
XS GIS Cut Line= 2
      2336228.51      7094061.92      2335652.10      7093906.12
#Sta/Elev= 30
  4533.9  640.90  4574.8  639.35  4616.3  637.35  4626.6  637.25  4647.3  636.32
  4668.1  635.83  4688.8  634.65  4709.0  634.30  4719.9  633.63  4761.3  632.36
  4813.1  630.20  4863.4  629.54  4875.2  629.14  4896.0  629.31  4908.4  629.03
  4943.1  629.01  4958.1  628.58  4987.2  628.37  4987.4  627.87  4990.9  627.87
  4991.2  628.37  5017.7  628.81  5022.9  628.54  5041.0  629.17  5051.3  629.69
  5057.6  630.48  5062.8  630.47  5082.4  631.82  5113.5  631.53  5131.0  631.75
#Mann=3,-1,0
  4533.9    0.05       0  4987.2    0.04       0  4991.2    0.05       0
Bank Sta=4987.2,4991.2
Exp/Cntr=0.3,0.1

Type RM Length L Ch R = 1,721,0,0,0
BEGIN DESCRIPTION:
Denton Creek Tributary 15 3.0
END DESCRIPTION:
XS GIS Cut Line= 3
      2336318.69      7094041.35      2335887.57      7093643.34
      2335635.71      7093700.42
#Sta/Elev= 30
  4419.1  643.35  4433.8  642.99  4518.8  639.53  4646.4  633.33  4674.8  632.71
  4688.9  631.94  4703.1  631.56  4709.9  631.68  4717.3  630.94  4724.1  630.94
  4731.5  630.19  4766.6  629.62  4816.0  627.77  4823.3  627.15  4880.0  626.45
  4950.4  626.51  4986.1  626.82  5004.6  626.63  5014.6  625.66  5014.8  625.16
  5018.3  625.16  5018.6  625.66  5035.1  626.44  5045.4  626.55  5076.2  626.53
  5102.8  626.87  5127.4  626.67  5168.4  628.11  5178.7  628.82  5264.1  630.07
#Mann=3,-1,0
  4419.1    0.05       0  5014.6    0.04       0  5018.6    0.05       0
Bank Sta=5014.6,5018.6
Exp/Cntr=0.3,0.1

Chan Stop Cuts=-1