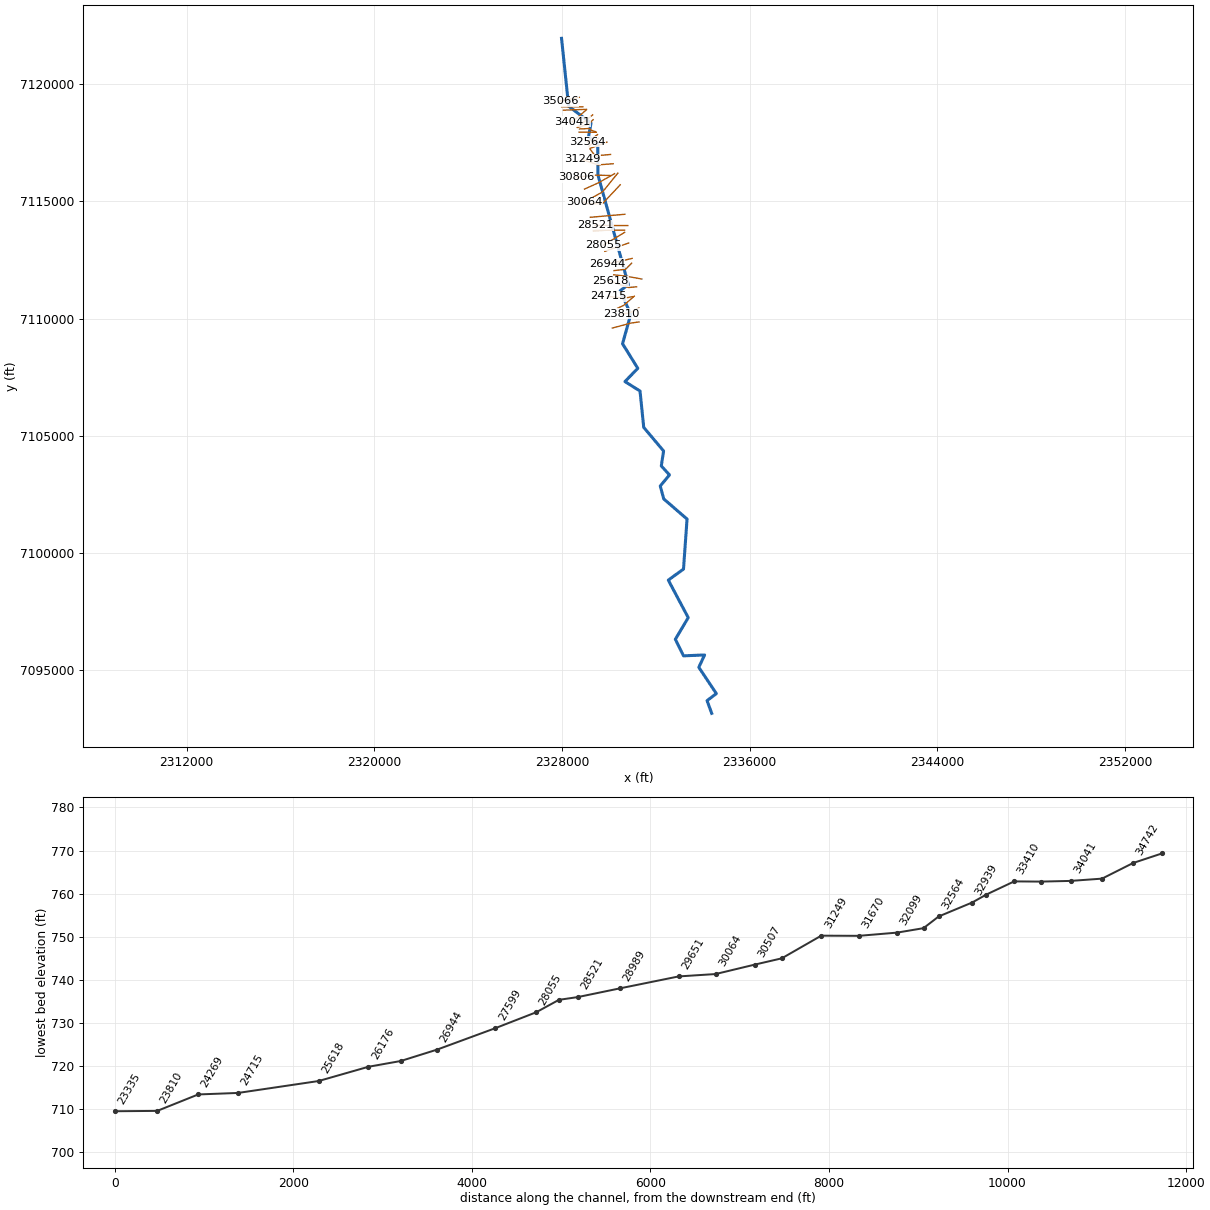
--- Denton Creek Tributary 17.prj (project) ---

Proj Title=Denton Creek Tributary 17 Base Level Engineering
Current Plan=p01
Default Exp/Contr=0.3,0.1
English Units
Geom File=g01
Flow File=f01
Plan File=p01
Y Axis Title=Elevation
X Axis Title(PF)=Main Channel Distance
X Axis Title(XS)=Station
BEGIN DESCRIPTION:
Denton Creek Tributary 17
END DESCRIPTION:
DSS Export Rating Curves= 0
DSS Export Rating Curve Sorted= 0
DSS Export Volume Flow Curves= 0
DXF OffsetX= 0
DXF OffsetY= 0
DXF ScaleX= 1
DXF ScaleY= 10

--- Denton Creek Tributary 17.p01 (plan) ---

Plan Title=Multiple Run
Short Identifier=Multiple
Geom File=g01
Flow File=f01
Subcritical Flow
K Sum by GR= 0
Std Step Tol= 0.01
Critical Tol= 0.01
Num of Std Step Trials= 20
Max Error Tol= 0.3
Flow Tol Ratio= 0.001
Split Flow NTrial= 30
Split Flow Tol= 0.02
Split Flow Ratio= 0.02
Log Output Level= 0
Friction Slope Method= 1
Unsteady Friction Slope Method= 2
Unsteady Bridges Friction Slope Method= 1
Parabolic Critical Depth
Global Vel Dist=  1 , 1 , 1
Global Log Level= 0
CheckData=True
Encroach Param= -1, 0, 0, 0
BEGIN DESCRIPTION:
Multiple Run
END DESCRIPTION:

--- Denton Creek Tributary 17.f01 (steady flow) ---

Flow Title=Multiple
Number of Profiles=7
Profile Names=10-year,25-year,50-year,1pct_min,100-year,1pct_plu,500-year
River Rch & RM= Denton Creek Tri,Reach-1,35066
     503     672     809     483     964    1924    1371
River Rch & RM= Denton Creek Tri,Reach-1,31249
     949    1322    1633     999    1994    3979    2982
River Rch & RM= Denton Creek Tri,Reach-1,26176
    1313    1856    2316    1430    2852    5691    4342
River Rch & RM= Denton Creek Tri,Reach-1,23335
    1693    2421    3044    1892    3776    7534    5831
River Rch & RM= Denton Creek Tri,Reach-1,15895
    1992    2866    3620    2259    4507    8992    7012
River Rch & RM= Denton Creek Tri,Reach-1,7682
    2083    3004    3798    2373    4734    9445    7381
River Rch & RM= Denton Creek Tri,Reach-1,3666
    2180    3148    3985    2492    4971    9919    7766
Boundary for River Rch & Prof#=Denton Creek Tri,Reach-1,1
Up Type=0
Dn Type=3
Dn Slope=0.005
Boundary for River Rch & Prof#=Denton Creek Tri,Reach-1,2
Up Type=0
Dn Type=3
Dn Slope=0.005
Boundary for River Rch & Prof#=Denton Creek Tri,Reach-1,3
Up Type=0
Dn Type=3
Dn Slope=0.005
Boundary for River Rch & Prof#=Denton Creek Tri,Reach-1,4
Up Type=0
Dn Type=3
Dn Slope=0.005
Boundary for River Rch & Prof#=Denton Creek Tri,Reach-1,5
Up Type=0
Dn Type=3
Dn Slope=0.005
Boundary for River Rch & Prof#=Denton Creek Tri,Reach-1,6
Up Type=0
Dn Type=3
Dn Slope=0.005
Boundary for River Rch & Prof#=Denton Creek Tri,Reach-1,7
Up Type=0
Dn Type=3
Dn Slope=0.005

--- Denton Creek Tributary 17.g01 (geometry) ---

Geom Title=Existing Conditions
Program Version=4.10

River Reach=Denton Creek Tri,Reach-1
Reach XY= 30
        2327979.        7121960.      2328280.98      7119065.65
      2329234.16       7118340.2      2329130.62      7117766.04
      2329522.31      7117472.08       2329531.3      7116128.86
      2330827.96      7111449.56       2330479.2      7111194.67
      2330929.33      7110185.22      2330578.88      7108930.27
      2331229.48      7107880.16      2330681.05      7107315.84
      2331323.53      7106912.45      2331482.37      7105361.28
      2332327.35      7104354.58      2332231.24      7103715.93
      2332579.64      7103332.97      2332187.08       7102863.3
      2332332.62       7102311.5      2333327.91      7101450.36
      2333176.82      7099315.45      2332529.33      7098844.97
      2333378.69      7097244.96      2332829.61      7096320.62
      2333176.71      7095615.11      2334075.93       7095651.7
      2333829.36      7095125.16      2334577.43      7094003.96
      2334180.96      7093704.12        2334379.        7093160.

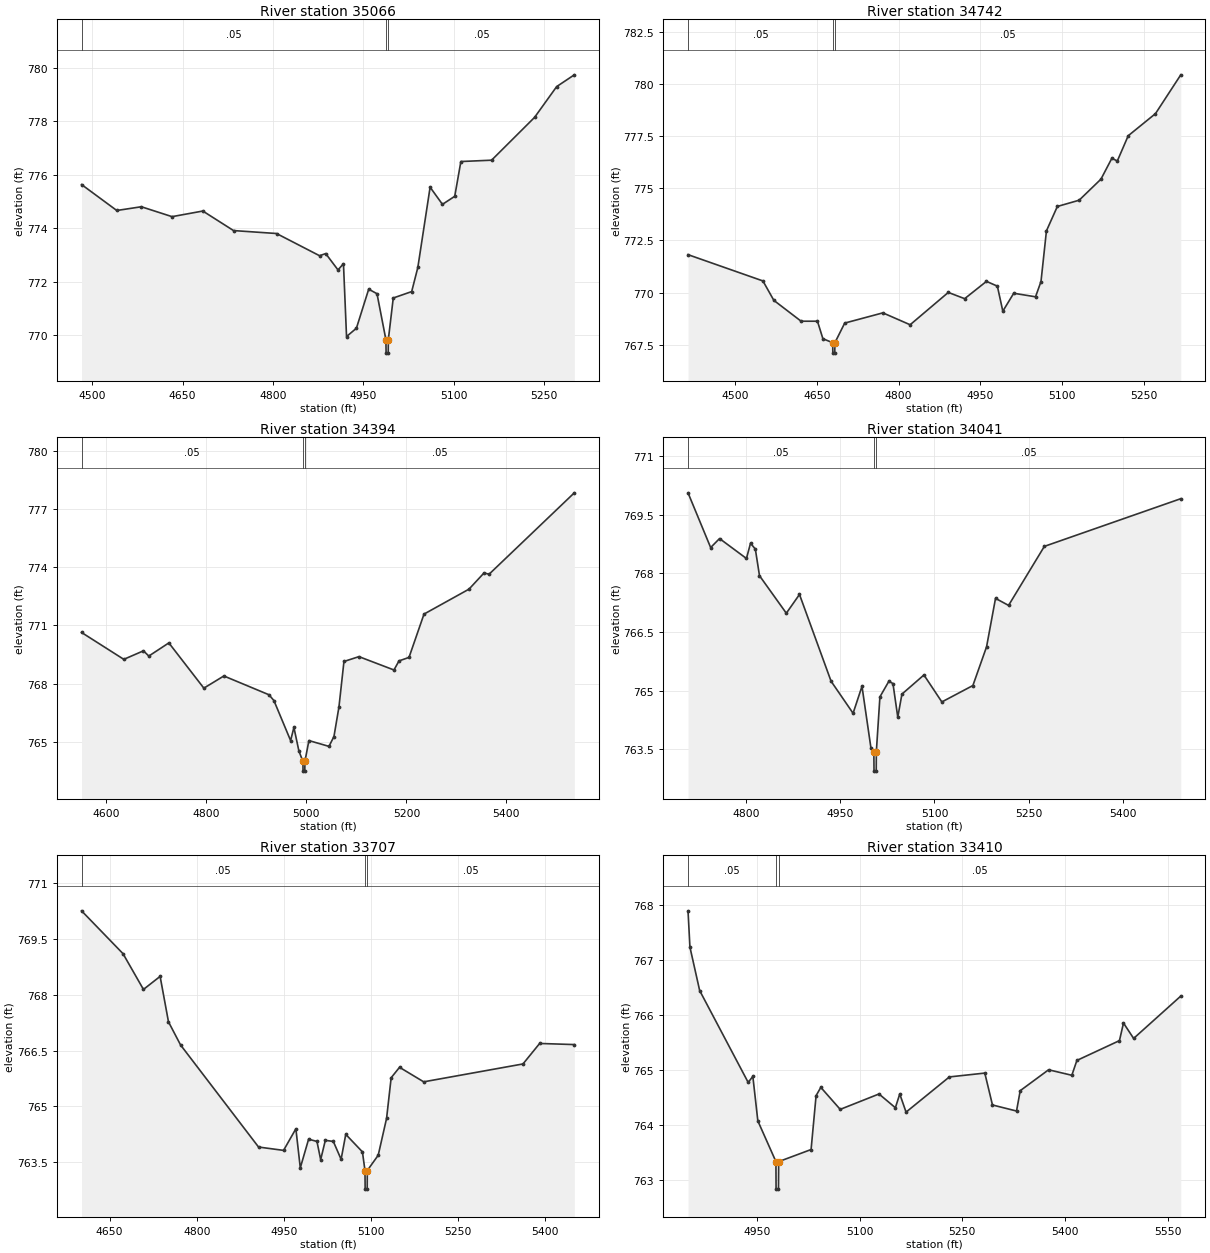
Type RM Length L Ch R = 1 ,35066   ,324,324,324
BEGIN DESCRIPTION:
Mapping XS 0ac4e1bd
END DESCRIPTION:
XS GIS Cut Line= 2
      2328736.32      7119442.53      2327934.35      7119279.35
#Sta/Elev= 30
  4482.1  775.63  4540.6  774.66  4581.4   774.8  4632.4  774.43  4683.5  774.64
  4734.5  773.91  4805.9   773.8  4877.4  772.97  4887.6  773.05    4908  772.44
  4917.1  772.67  4922.2  769.95  4938.6  770.26    4959  771.72  4972.8  771.55
  4987.6  769.83  4987.9  769.33  4991.4  769.33  4991.6  769.83  4999.8  771.39
  5030.4  771.63  5040.6  772.53    5061  775.53  5081.5  774.89  5101.9  775.19
  5112.1  776.49  5163.1  776.54  5234.5  778.14  5271.2  779.29  5300.5  779.73
#Mann= 3 ,-1 , 0
  4482.1     .05       0  4987.6     .04       0  4991.6     .05       0
Bank Sta=4987.6,4991.6
XS Rating Curve= 0 ,0
Exp/Cntr=0.3,0.1

Type RM Length L Ch R = 1 ,34742   ,348,348,348
BEGIN DESCRIPTION:
Mapping XS 10f8d9e2
END DESCRIPTION:
XS GIS Cut Line= 2
      2328886.37      7119038.08      2327982.57      7119037.03
#Sta/Elev= 30
  4413.9  771.82  4551.3  770.56  4571.3  769.63  4621.3  768.63  4651.3  768.63
  4661.3  767.79  4679.3   767.6  4679.5   767.1    4683   767.1  4683.3   767.6
  4701.3  768.54  4771.3  769.03  4821.3  768.46  4891.3  770.01  4921.3  769.71
  4961.3  770.54  4981.3  770.31  4991.3  769.11  5011.3  769.97  5051.3   769.8
  5061.3  770.53  5071.3  772.96  5091.3  774.13  5131.3  774.43  5171.3  775.44
  5191.3  776.44  5201.3  776.31  5221.3  777.52  5271.3  778.58  5317.7  780.44
#Mann= 3 ,-1 , 0
  4413.9     .05       0  4679.3    .033       0  4683.3     .05       0
Bank Sta=4679.3,4683.3
XS Rating Curve= 0 ,0
Exp/Cntr=0.3,0.1

Type RM Length L Ch R = 1 ,34394   ,353,353,353
BEGIN DESCRIPTION:
Mapping XS 62265ab8
END DESCRIPTION:
XS GIS Cut Line= 2
      2329043.47      7118929.44      2328058.56      7118895.27
#Sta/Elev= 30
  4550.3  770.64  4634.8  769.25  4674.1  769.69  4684.8  769.42  4724.9   770.1
  4794.9  767.76  4834.9  768.39    4925  767.42    4935  767.12  4968.4  765.05
    4975  765.73    4985  764.51    4993  763.97  4993.3  763.47  4996.8  763.47
    4997  763.97    5005  765.05  5045.1  764.75  5055.1  765.26  5065.1  766.79
  5075.1  769.14  5105.1  769.39  5175.1   768.7  5185.2  769.17  5205.2  769.35
  5235.2  771.59  5325.2  772.88  5355.3  773.72  5365.3  773.65  5535.8  777.86
#Mann= 3 ,-1 , 0
  4550.3     .05       0    4993    .033       0    4997     .05       0
Bank Sta=4993,4997
XS Rating Curve= 0 ,0
Exp/Cntr=0.3,0.1

Type RM Length L Ch R = 1 ,34041   ,334,334,334
BEGIN DESCRIPTION:
Mapping XS 1682fb86
END DESCRIPTION:
XS GIS Cut Line= 2
      2329034.02      7118906.22      2328437.18      7118394.78
#Sta/Elev= 30
  4706.9  770.06    4743  768.66  4757.2  768.89  4800.1  768.38  4806.6  768.77
  4814.3  768.62  4820.9  767.94  4863.7  766.98  4884.7  767.46  4935.1  765.24
  4970.2  764.42  4984.4  765.11  4998.7  763.53  5003.3  763.44  5003.6  762.94
  5007.1  762.94  5007.3  763.44    5013  764.84  5027.3  765.24  5033.8  765.18
  5041.5  764.32  5048.1  764.91  5083.2   765.4  5111.8  764.71  5161.3  765.13
  5183.1  766.12  5197.4  767.36  5218.2  767.18  5275.3  768.69  5492.9  769.91
#Mann= 3 ,-1 , 0
  4706.9     .05       0  5003.3     .04       0  5007.3     .05       0
Bank Sta=5003.3,5007.3
XS Rating Curve= 0 ,0
Exp/Cntr=0.3,0.1

Type RM Length L Ch R = 1 ,33707   ,297,297,297
BEGIN DESCRIPTION:
Mapping XS f6472d4a
END DESCRIPTION:
XS GIS Cut Line= 2
      2329305.36      7118693.36        2328647.      7118157.92
#Sta/Elev= 30
  4601.6  770.25    4673   769.1  4708.2  768.14  4736.9  768.49  4751.3  767.27
  4772.1  766.65  4906.4  763.91  4949.5  763.82  4970.7   764.4  4978.3  763.35
  4992.6  764.12    5007  764.06  5013.4  763.57  5021.4  764.09  5035.2  764.06
  5048.6  763.58  5056.6  764.25  5085.3  763.78  5089.7  763.28    5090  762.78
  5093.5  762.78  5093.7  763.28  5112.5  763.69  5126.9  764.68  5134.8  765.77
  5149.2  766.05  5190.8  765.66  5361.8  766.14  5390.5  766.69  5450.2  766.66
#Mann= 3 ,-1 , 0
  4601.6     .05       0  5089.7     .04       0  5093.7     .05       0
Bank Sta=5089.7,5093.7
XS Rating Curve= 0 ,0
Exp/Cntr=0.3,0.1

Type RM Length L Ch R = 1 ,33410   ,312,312,312
BEGIN DESCRIPTION:
Mapping XS 378c434c
END DESCRIPTION:
XS GIS Cut Line= 3
      2329325.44       7118487.5       2329105.2      7118279.97
      2328702.44      7118173.91
#Sta/Elev= 30
  4849.7  767.89  4852.5  767.23  4866.7  766.44  4937.5  764.77  4944.3  764.88
  4951.6  764.07    4978  763.33  4978.2  762.83  4981.7  762.83    4982  763.33
  5029.3  763.55  5036.6  764.53  5043.5  764.68  5071.8  764.28  5128.4  764.56
  5152.3  764.31  5158.7  764.56  5167.9  764.23  5231.1  764.87  5282.8  764.94
    5294  764.36  5329.1  764.25  5334.5  764.62  5375.9     765  5409.8   764.9
  5417.2  765.17  5479.3  765.53  5485.2  765.85    5500  765.57  5568.8  766.34
#Mann= 3 ,-1 , 0
  4849.7     .05       0    4978    .033       0    4982     .05       0
Bank Sta=4978,4982
XS Rating Curve= 0 ,0
Exp/Cntr=0.3,0.1

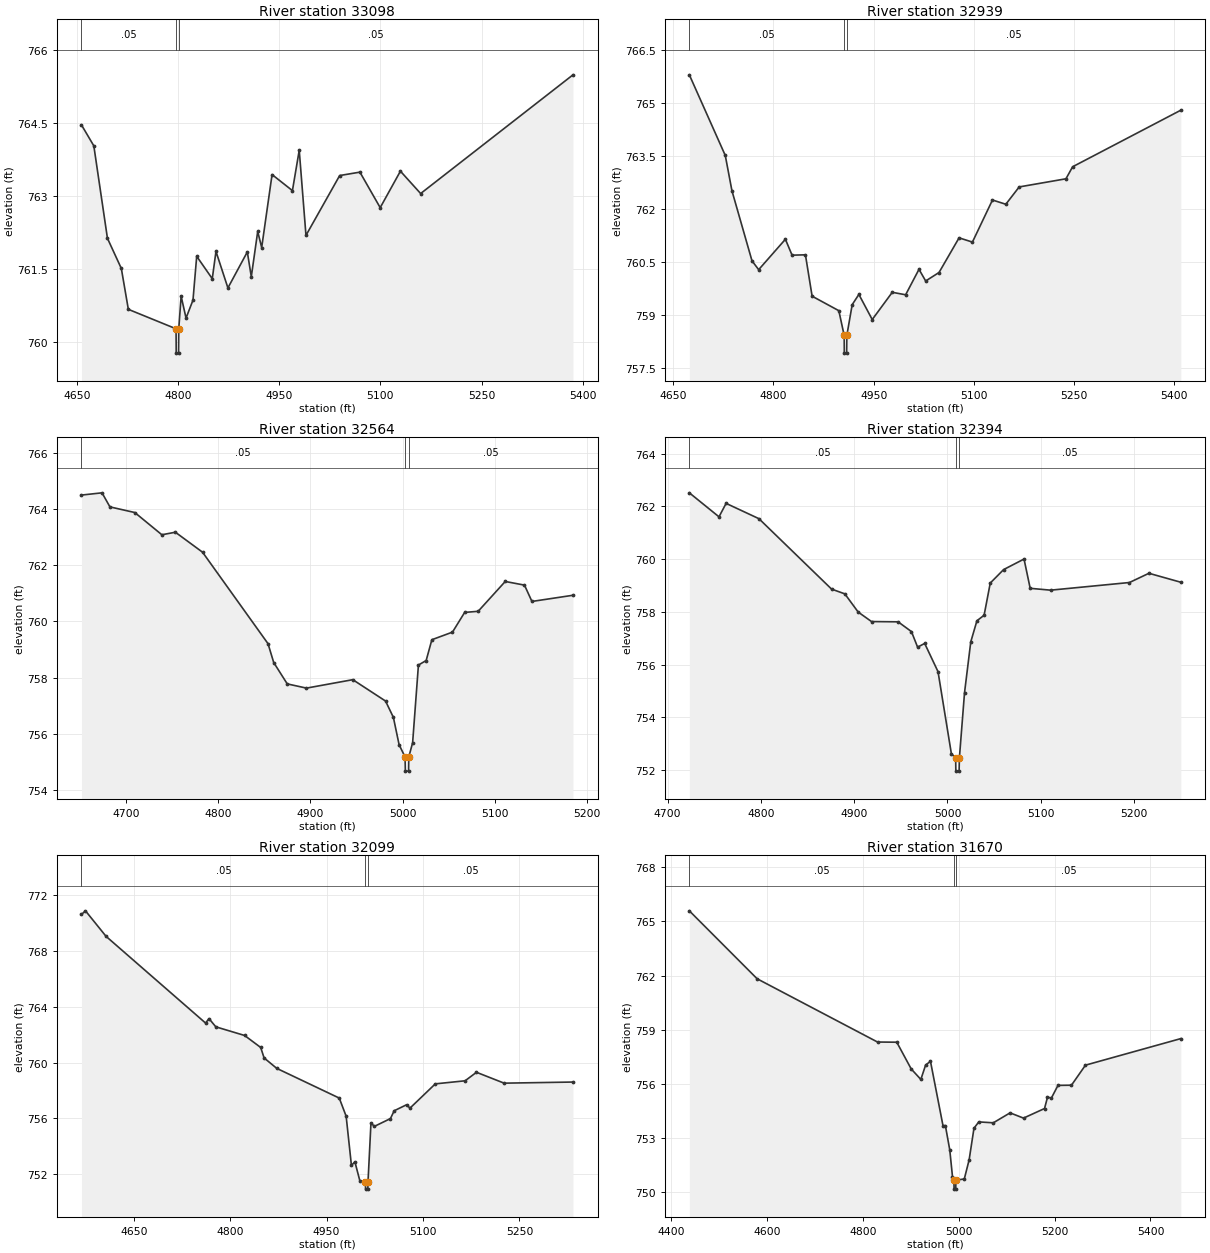
Type RM Length L Ch R = 1 ,33098   ,159,159,159
BEGIN DESCRIPTION:
Mapping XS a219866b
END DESCRIPTION:
XS GIS Cut Line= 5
      2329426.23      7117981.55      2329325.63      7118007.76
      2329215.34      7118057.48      2329180.21      7118114.26
      2328743.27      7118094.47
#Sta/Elev= 30
  4656.6  764.46  4674.9  764.03  4695.1  762.13  4715.7  761.51  4726.1  760.67
  4796.9  760.27  4797.1  759.77  4800.6  759.77  4800.9  760.27  4804.4  760.94
  4811.7  760.49    4822  760.86  4827.5  761.76  4850.6   761.3  4856.1  761.86
  4873.8  761.11  4902.6  761.85  4908.5  761.34    4918  762.27  4923.9  761.94
  4939.3  763.44  4969.5  763.11  4979.6  763.94  4989.6  762.19  5039.6  763.42
  5069.6  763.49  5099.7  762.76  5129.7  763.51  5159.7  763.05  5385.7  765.49
#Mann= 3 ,-1 , 0
  4656.6     .05       0  4796.9     .04       0  4800.9     .05       0
Bank Sta=4796.9,4800.9
XS Rating Curve= 0 ,0
Exp/Cntr=0.3,0.1

Type RM Length L Ch R = 1 ,32939   ,375,375,375
BEGIN DESCRIPTION:
Mapping XS 618bafd2
END DESCRIPTION:
XS GIS Cut Line= 2
      2329462.79       7117951.2      2328727.02      7117958.36
#Sta/Elev= 30
  4674.1  765.79  4727.9  763.51  4737.9  762.51  4767.9  760.53  4777.9  760.28
  4817.9  761.14  4827.9  760.69  4847.9   760.7  4857.9  759.53  4897.9  759.12
  4905.9  758.42  4906.1  757.92  4909.6  757.92  4909.9  758.42  4917.9  759.29
  4927.9  759.58  4947.9  758.87  4977.9  759.64  4997.9  759.57  5017.9  760.29
  5027.9  759.96  5047.9   760.2  5077.9  761.18  5097.9  761.06  5127.9  762.25
  5147.9  762.13  5167.9  762.62  5237.9  762.85  5247.9  763.19  5409.9  764.79
#Mann= 3 ,-1 , 0
  4674.1     .05       0  4905.9     .04       0  4909.9     .05       0
Bank Sta=4905.9,4909.9
XS Rating Curve= 0 ,0
Exp/Cntr=0.3,0.1

Type RM Length L Ch R = 1 ,32564   ,170,170,170
BEGIN DESCRIPTION:
Mapping XS b18e93ea
END DESCRIPTION:
XS GIS Cut Line= 2
      2329515.76      7117855.43      2329082.83      7117542.98
#Sta/Elev= 30
  4651.3  764.49  4673.6  764.57  4682.2  764.07  4709.2  763.87  4738.6  763.08
  4753.3  763.17  4782.8  762.46  4853.9  759.21  4860.1  758.54  4874.8  757.78
  4895.7  757.63    4946  757.93  4981.6  757.17  4990.1  756.59  4996.3  755.62
  5002.8  755.18  5003.1  754.68  5006.6  754.68  5006.8  755.18    5011  755.69
  5017.3  758.45  5025.7  758.61  5031.9  759.35  5054.3  759.62  5067.5  760.32
  5082.2  760.36  5111.6  761.42  5132.5  761.29  5140.6  760.71  5185.2  760.93
#Mann= 3 ,-1 , 0
  4651.3     .05       0  5002.8     .04       0  5006.8     .05       0
Bank Sta=5002.8,5006.8
XS Rating Curve= 0 ,0
Exp/Cntr=0.3,0.1

Type RM Length L Ch R = 1 ,32394   ,295,295,295
BEGIN DESCRIPTION:
Mapping XS 25c2c7ba
END DESCRIPTION:
XS GIS Cut Line= 2
      2329552.92      7117701.54      2329153.01      7117358.48
#Sta/Elev= 30
  4723.3  762.51  4755.1   761.6  4762.7  762.11  4797.9  761.53  4875.8  758.86
    4890  758.68  4904.3  757.99  4918.6  757.63  4947.1  757.62  4961.4  757.25
    4968  756.66  4975.6   756.8  4989.9  755.73  5004.2  752.62  5008.8  752.46
    5009  751.96  5012.5  751.96  5012.8  752.46  5018.3  754.93    5025  756.86
  5031.6  757.66  5039.3  757.87  5045.9  759.09  5060.2   759.6  5082.1     760
  5088.7  758.89  5110.6  758.82  5195.1  759.11    5216  759.46  5250.2  759.12
#Mann= 3 ,-1 , 0
  4723.3     .05       0  5008.8     .04       0  5012.8     .05       0
Bank Sta=5008.8,5012.8
XS Rating Curve= 0 ,0
Exp/Cntr=0.3,0.1

Type RM Length L Ch R = 1 ,32099   ,429,429,429
BEGIN DESCRIPTION:
Mapping XS c27dabc9
END DESCRIPTION:
XS GIS Cut Line= 2
      2329914.81      7117532.26      2329198.29      7117265.96
#Sta/Elev= 30
  4568.8  770.63    4575  770.89    4607  769.06  4761.8  762.84  4767.1  763.16
  4777.7  762.57  4822.5  761.95  4847.5  761.09  4852.8  760.34  4872.5  759.59
  4969.7  757.46  4980.4  756.16  4988.6  752.63    4994  752.89  5001.7  751.53
  5010.4  751.43  5010.6  750.93  5014.1  750.93  5014.4  751.43    5019  755.68
  5024.3  755.43  5049.3  755.99  5055.1  756.55  5074.3  756.98  5079.7  756.74
  5119.1  758.48  5165.4   758.7  5183.1  759.31  5226.1  758.53  5333.2  758.61
#Mann= 3 ,-1 , 0
  4568.8     .05       0  5010.4     .04       0  5014.4     .05       0
Bank Sta=5010.4,5014.4
XS Rating Curve= 0 ,0
Exp/Cntr=0.3,0.1

Type RM Length L Ch R = 1 ,31670   ,421,421,421
BEGIN DESCRIPTION:
Mapping XS 97259d68
END DESCRIPTION:
XS GIS Cut Line= 4
      2330069.79      7117005.91      2329542.04      7116957.57
      2329415.82      7116940.74      2329195.38      7117235.04
#Sta/Elev= 30
  4438.3  765.58  4579.7  761.82  4830.7  758.32  4870.9  758.31    4901  756.83
  4921.1  756.25  4931.1  757.05  4941.2  757.25  4967.3  753.69  4972.3  753.69
  4981.4  752.35  4987.1  750.87  4990.1  750.68  4990.4  750.18  4993.9  750.18
  4994.1  750.68  5011.7  750.74  5021.8   751.8  5031.9  753.55  5041.9   753.9
  5072.2  753.85  5107.2   754.4  5135.2  754.11    5179  754.64  5185.2  755.26
  5193.5  755.23  5207.1  755.92  5235.2  755.93  5264.4  757.04  5463.3  758.51
#Mann= 3 ,-1 , 0
  4438.3     .05       0  4990.1     .04       0  4994.1     .05       0
Bank Sta=4990.1,4994.1
XS Rating Curve= 0 ,0
Exp/Cntr=0.3,0.1

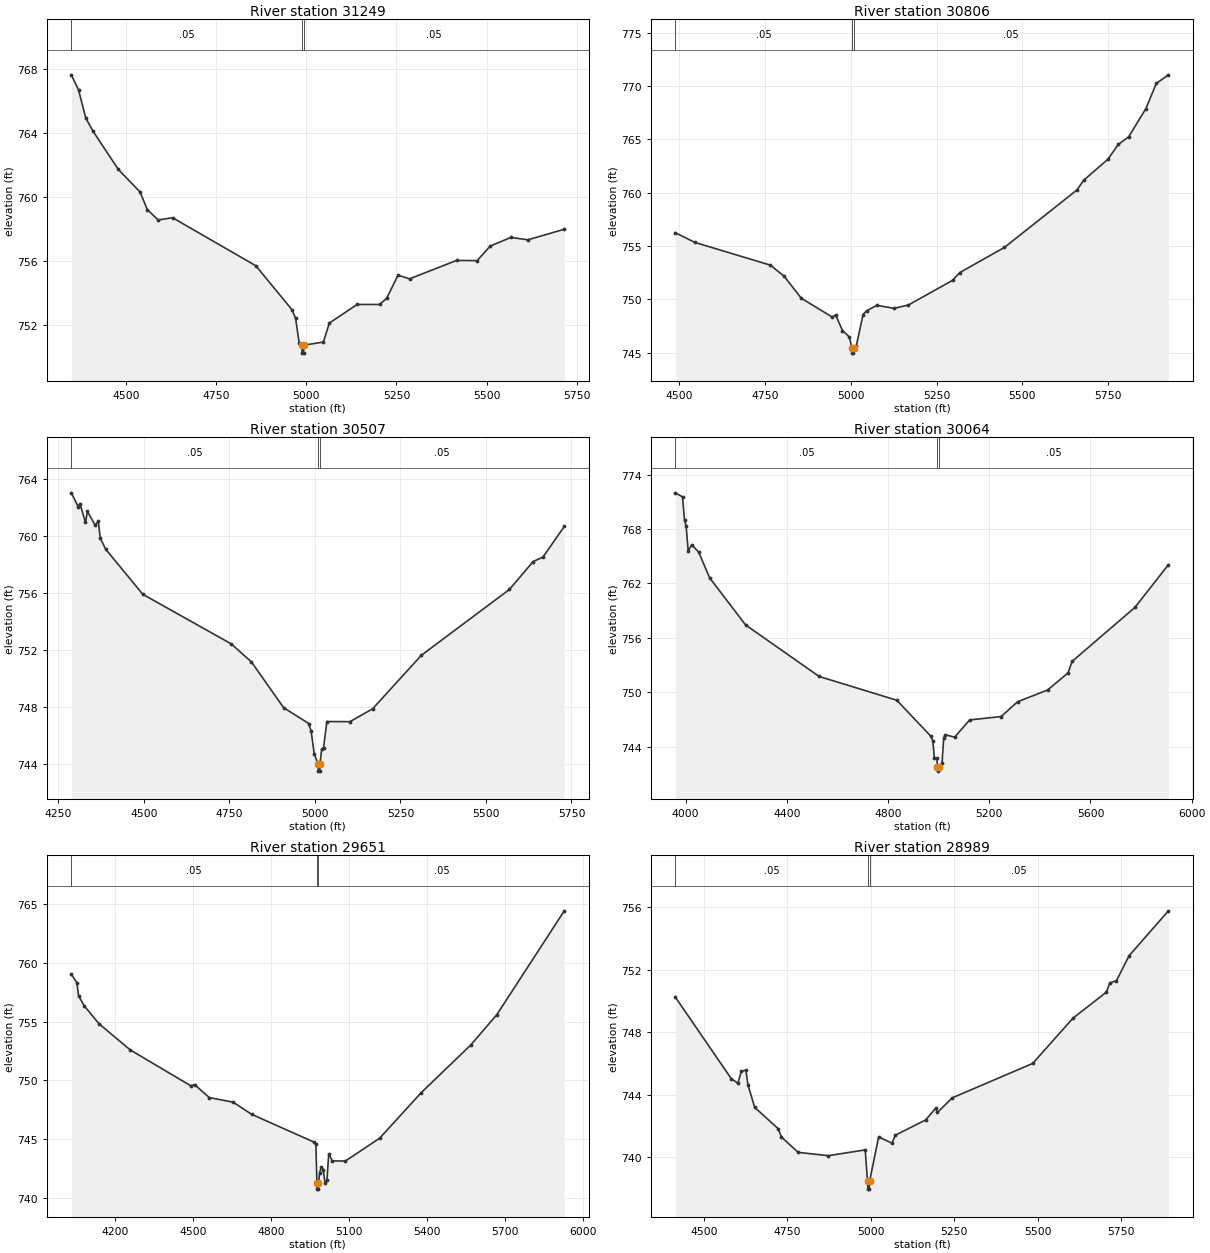
Type RM Length L Ch R = 1 ,31249   ,443,443,443
BEGIN DESCRIPTION:
Denton Creek Tributary 17 54.0
END DESCRIPTION:
XS GIS Cut Line= 3
      2330178.96        7116610.        2329529.        7116560.
      2328853.35      7116793.05
#Sta/Elev= 30
  4348.6  767.61  4368.6  766.67  4388.7  764.91  4408.7  764.09  4478.9   761.7
  4539.1  760.29  4559.2  759.19  4589.3  758.54  4629.4  758.68  4860.1  755.68
  4960.4  752.93  4970.4  752.39  4980.4  750.83  4987.6  750.72  4988.5  750.22
  4992.4  750.22  4993.3  750.72  5047.3  750.91    5064   752.1  5140.9  753.26
  5203.3  753.26  5222.6  753.64  5254.4  755.09  5286.1  754.86  5416.4  756.01
  5473.5     756    5510  756.91  5567.1  757.45    5614   757.3  5715.2  757.96
#Mann= 3 ,-1 , 0
  4348.6     .05       0  4987.6     .04       0  4993.3     .05       0
Bank Sta=4987.6,4993.3
XS Rating Curve= 0 ,0
Exp/Cntr=0.3,0.1

Type RM Length L Ch R = 1 ,30806   ,299,299,299
BEGIN DESCRIPTION:
Denton Creek Tributary 17 53.0
END DESCRIPTION:
XS GIS Cut Line= 3
       2330045.5      7116110.62      2329430.92      7116121.03
      2328613.77      7116039.15
#Sta/Elev= 30
  4489.4  756.23  4545.9  755.33  4765.9   753.2  4805.9  752.16  4855.9   750.1
    4946  748.33    4956  748.53    4976  747.07    4996  746.46  5003.1  745.45
    5004  744.95  5007.9  744.95  5008.9  745.45    5016  745.61    5036  748.57
    5046  748.91    5076  749.43  5126.1  749.15  5167.9  749.46  5296.9  751.78
    5317  752.49  5447.7  754.86  5658.7  760.24  5678.8  761.16  5749.2  763.13
  5779.3  764.51  5809.5  765.23  5859.7  767.87  5889.9  770.23  5925.3  771.04
#Mann= 3 ,-1 , 0
  4489.4     .05       0  5003.1     .04       0  5008.9     .05       0
Bank Sta=5003.1,5008.9
XS Rating Curve= 0 ,0
Exp/Cntr=0.3,0.1

Type RM Length L Ch R = 1 ,30507   ,443,443,443
BEGIN DESCRIPTION:
Denton Creek Tributary 17 52.0
END DESCRIPTION:
XS GIS Cut Line= 3
      2330239.69      7116185.52      2329551.83      7115797.42
      2328958.46      7115528.64
#Sta/Elev= 30
  4287.9  763.04  4307.6  762.08  4313.3  762.27  4329.3  760.97    4335  761.73
  4357.6  760.77  4366.8  761.03  4372.6  759.86  4388.5  759.08  4496.8  755.92
  4755.4  752.44  4814.6  751.17  4908.7  747.96  4982.1  746.85  4989.1   746.3
    4998  744.74  5009.1  744.01    5010  743.51    5014  743.51  5014.9  744.01
  5019.7  745.04  5025.4  745.16    5035  746.99  5102.5  746.98  5168.6  747.88
  5311.3  751.64  5568.8  756.26  5638.1  758.22  5666.7  758.53  5729.1  760.68
#Mann= 3 ,-1 , 0
  4287.9     .05       0  5009.1     .04       0  5014.9     .05       0
Bank Sta=5009.1,5014.9
XS Rating Curve= 0 ,0
Exp/Cntr=0.3,0.1

Type RM Length L Ch R = 1 ,30064   ,413,413,413
BEGIN DESCRIPTION:
Denton Creek Tributary 17 51.0
END DESCRIPTION:
XS GIS Cut Line= 3
      2330378.97      7116209.97        2329729.        7115410.
      2328929.01        7114960.
#Sta/Elev= 30
  3959.5     772  3987.5  771.55  3995.4     769  4001.8  768.33  4009.8   765.6
  4023.9  766.27  4051.4  765.46  4094.5  762.63  4236.7  757.43  4527.6  751.74
  4834.4  749.12  4968.7  745.16  4976.6  744.67    4983  742.79  4993.1  742.72
  4995.2   741.8  4996.2   741.3  5001.1   741.8  5013.2  742.16  5019.9  744.94
  5025.6  745.31  5063.2  745.05  5122.5  746.95  5246.8  747.32  5311.8  748.95
  5430.4  750.25  5511.3  752.13  5527.3   753.4  5775.8  759.36  5908.1  764.07
#Mann= 3 ,-1 , 0
  3959.5     .05       0  4995.2     .04       0  5001.1     .05       0
Bank Sta=4995.2,5001.1
XS Rating Curve= 0 ,0
Exp/Cntr=0.3,0.1

Type RM Length L Ch R = 1 ,29651   ,662,662,662
BEGIN DESCRIPTION:
Denton Creek Tributary 17 50.0
END DESCRIPTION:
XS GIS Cut Line= 3
      2330478.99      7115709.99        2329729.        7114910.
      2328928.98        7114910.
#Sta/Elev= 30
    4032  759.04  4053.2  758.32  4060.1  757.19  4081.6  756.35  4138.2  754.83
  4258.4   752.6  4491.9  749.54    4506  749.65  4562.7  748.54  4654.5  748.15
  4725.4  747.12  4965.7  744.75    4973  744.56  4976.9  741.25  4977.9  740.75
  4981.9  740.75  4982.9  741.25  4987.2  742.15    4994  742.66  5001.3  742.41
  5008.2  741.26  5015.5  741.49  5022.3  743.75  5036.5  743.15  5086.3  743.14
  5218.6  745.09  5378.6  748.97  5568.6  753.01  5668.6  755.58  5928.6  764.43
#Mann= 3 ,-1 , 0
    4032     .05       0  4976.9     .04       0  4982.9     .05       0
Bank Sta=4976.9,4982.9
XS Rating Curve= 0 ,0
Exp/Cntr=0.3,0.1

Type RM Length L Ch R = 1 ,28989   ,468,468,468
BEGIN DESCRIPTION:
Mapping XS c192e643
END DESCRIPTION:
XS GIS Cut Line= 2
      2330675.45      7114453.21      2329203.93      7114325.01
#Sta/Elev= 30
  4414.7  750.23  4581.8  745.03  4601.9  744.73  4611.9  745.49  4625.7  745.57
    4632  744.63  4652.1  743.19  4722.3  741.83  4732.4  741.29  4782.5  740.31
  4872.9   740.1  4983.3  740.47  4990.3  738.46  4991.3  737.96  4995.3  737.96
  4996.4  738.46  5023.5   741.3  5063.6   740.9  5073.6  741.41    5164  742.38
  5194.1  743.12  5199.9  742.87  5244.3   743.8  5485.2     746  5605.6  748.89
    5706  750.56  5716.1  751.15  5736.1  751.29    5774  752.89  5891.8  755.76
#Mann= 3 ,-1 , 0
  4414.7     .05       0  4990.3    .035       0  4996.4     .05       0
Bank Sta=4990.3,4996.4
XS Rating Curve= 0 ,0
Exp/Cntr=0.3,0.1

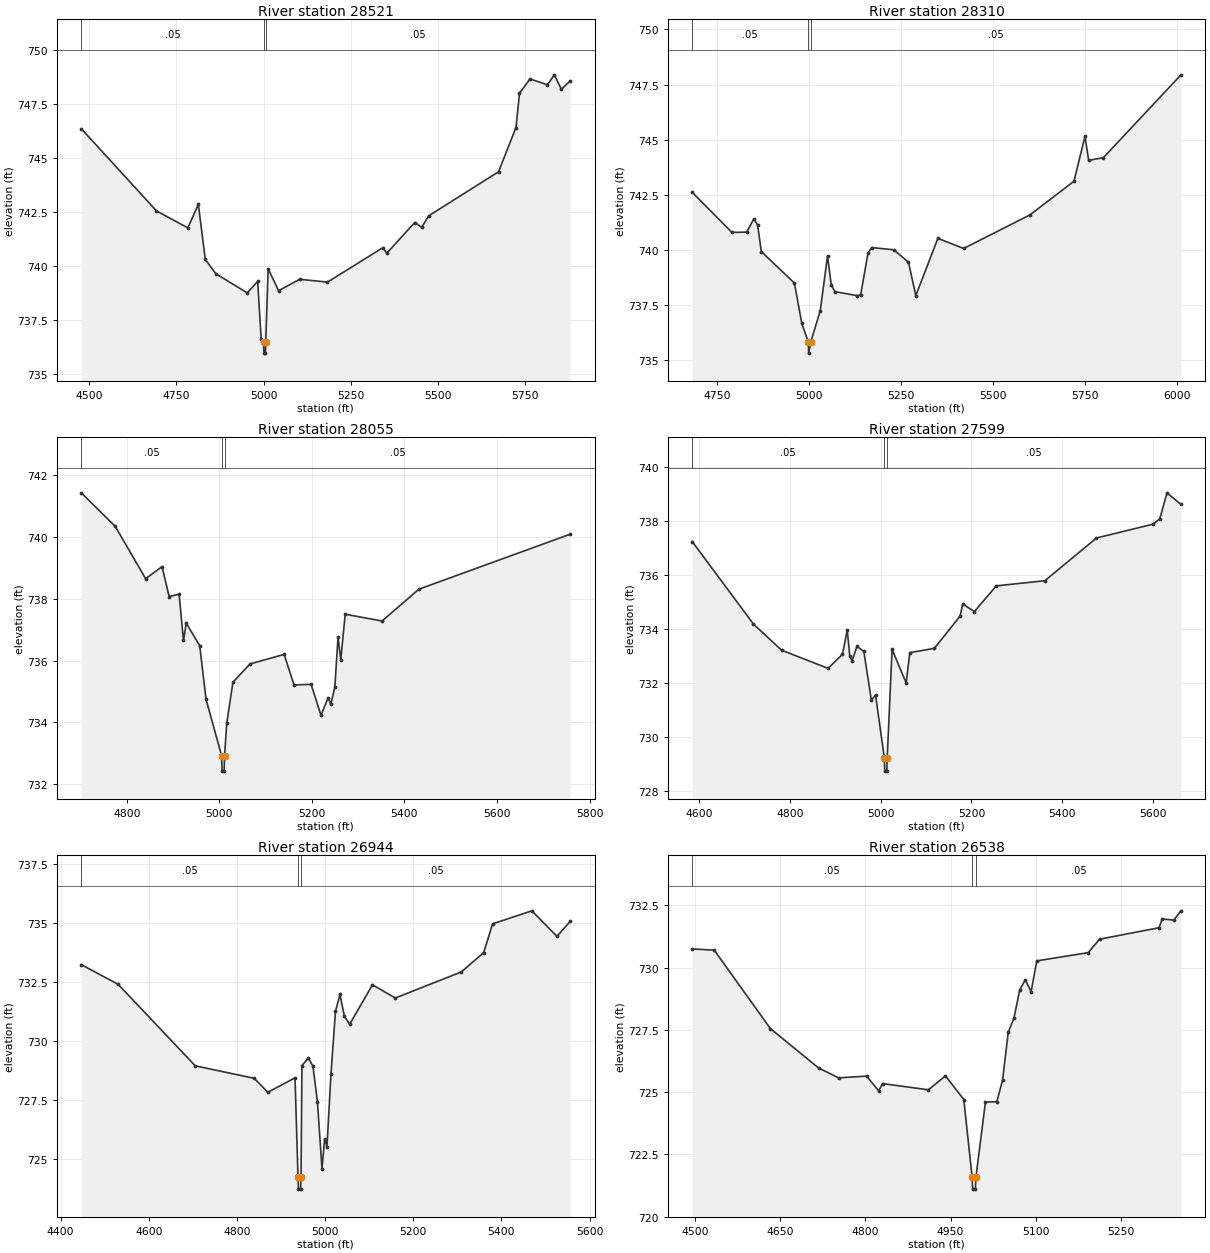
Type RM Length L Ch R = 1 ,28521   ,211,211,211
BEGIN DESCRIPTION:
Mapping XS b12e6d19
END DESCRIPTION:
XS GIS Cut Line= 2
      2330804.07      7113972.82      2329403.88      7113976.34
#Sta/Elev= 30
  4477.9  746.34    4693  742.54    4783  741.75    4813  742.84    4833  740.29
    4863  739.63    4953  738.74    4983  739.27    4993  736.61  4999.8  736.45
  5000.8  735.95  5005.1  735.95  5006.1  736.45    5013  739.86    5043  738.84
    5103  739.37    5183  739.24  5341.3  740.83    5353  740.58    5433     742
    5453  741.78    5473  742.31    5673  744.35    5723   746.4    5733  747.98
    5763  748.65    5813  748.38    5833  748.84    5853  748.17  5878.1  748.56
#Mann= 3 ,-1 , 0
  4477.9     .05       0  4999.8    .035       0  5006.1     .05       0
Bank Sta=4999.8,5006.1
XS Rating Curve= 0 ,0
Exp/Cntr=0.3,0.1

Type RM Length L Ch R = 1 ,28310   ,255,255,255
BEGIN DESCRIPTION:
Mapping XS c37c0ea7
END DESCRIPTION:
XS GIS Cut Line= 2
      2330666.93      7113778.54      2329338.02      7113763.59
#Sta/Elev= 30
    4682  742.61  4789.9  740.79  4829.9   740.8  4849.9  741.41  4859.9  741.12
  4869.9  739.92  4959.9  738.49    4980  736.66  4997.8  735.81  4998.8  735.31
  5004.2  735.81    5030  737.22    5050  739.72    5060  738.41    5070   738.1
    5130  737.92    5140  737.95    5160  739.85    5170   740.1    5230     740
    5270  739.44    5290  737.92    5350  740.52    5420  740.06    5600  741.58
    5720  743.11    5750  745.15    5760  744.06    5800  744.18    6011  747.94
#Mann= 3 ,-1 , 0
    4682     .05       0  4997.8     .04       0  5004.2     .05       0
Bank Sta=4997.8,5004.2
XS Rating Curve= 0 ,0
Exp/Cntr=0.3,0.1

Type RM Length L Ch R = 1 ,28055   ,456,456,456
BEGIN DESCRIPTION:
Mapping XS ccb3d3fb
END DESCRIPTION:
XS GIS Cut Line= 2
        2330668.       7113682.2      2329763.62      7113136.42
#Sta/Elev= 30
  4701.8  741.43  4775.2  740.34  4840.8  738.65  4876.1  739.04  4891.6  738.07
    4913  738.15  4922.5  736.65  4928.5  737.21  4957.6  736.48  4971.2  734.75
  5004.9  732.92  5005.9  732.42  5010.2  732.42  5011.3  732.92    5016  733.97
  5029.4   735.3  5066.3  735.89  5140.1   736.2  5161.4  735.21  5198.3  735.23
  5219.7  734.23  5235.2   734.8    5241  734.58  5249.6  735.14  5256.5  736.76
  5262.4  736.02    5272   737.5  5351.6  737.28  5431.2  738.31  5758.1  740.09
#Mann= 3 ,-1 , 0
  4701.8     .05       0  5004.9    .033       0  5011.3     .05       0
Bank Sta=5004.9,5011.3
XS Rating Curve= 0 ,0
Exp/Cntr=0.3,0.1

Type RM Length L Ch R = 1 ,27599   ,655,655,655
BEGIN DESCRIPTION:
Mapping XS 359a0462
END DESCRIPTION:
XS GIS Cut Line= 2
       2330841.6      7113229.28      2329824.89      7112874.89
#Sta/Elev= 30
  4584.9  737.23  4719.7  734.18  4781.9  733.21  4884.2  732.54  4915.9  733.06
  4926.5  733.96    4932  732.99  4937.3  732.82  4947.7  733.35    4963  733.17
  4979.5  731.37  4988.8  731.55  5008.1  729.24  5009.1  728.74  5013.5  728.74
  5014.5  729.24  5025.2  733.24  5056.3     732  5064.2  733.12  5118.4  733.28
  5175.3  734.48  5180.7  734.92  5206.4  734.64  5254.8  735.59  5361.7  735.78
  5475.5  737.36  5599.8  737.87  5614.9  738.07  5630.8  739.03  5661.6   738.6
#Mann= 3 ,-1 , 0
  4584.9     .05       0  5008.1     .04       0  5014.5     .05       0
Bank Sta=5008.1,5014.5
XS Rating Curve= 0 ,0
Exp/Cntr=0.3,0.1

Type RM Length L Ch R = 1 ,26944   ,406,406,406
BEGIN DESCRIPTION:
Denton Creek Tributary 17 44.0
END DESCRIPTION:
XS GIS Cut Line= 3
      2330990.01      7112572.76        2330529.        7112460.
      2329906.36      7112338.92
#Sta/Elev= 30
    4447  733.24  4530.4  732.41  4705.4  728.96  4839.2  728.43  4870.1  727.84
  4931.8  728.45  4938.5  724.24  4939.6  723.74  4944.3  723.74  4945.4  724.24
  4947.4  728.97  4962.3  729.29  4972.5  728.94  4982.7  727.41  4992.9  724.61
  4999.1  725.87  5004.2  725.53  5013.3  728.61  5023.5  731.26  5033.7  731.98
  5043.8  731.05  5055.8  730.72  5107.5  732.39  5159.2  731.83  5308.7  732.93
  5359.7  733.75    5380  734.97  5469.1  735.52  5525.9  734.44  5555.9  735.07
#Mann= 3 ,-1 , 0
    4447     .05       0  4938.5     .04       0  4945.4     .05       0
Bank Sta=4938.5,4945.4
XS Rating Curve= 0 ,0
Exp/Cntr=0.3,0.1

Type RM Length L Ch R = 1 ,26538   ,362,362,362
BEGIN DESCRIPTION:
Mapping XS 13ace3fe
END DESCRIPTION:
XS GIS Cut Line= 3
      2330967.05      7112367.04      2330710.81      7112107.91
      2330216.37       7112050.4
#Sta/Elev= 30
  4494.3  730.75  4533.2   730.7  4632.2  727.55  4717.1  725.97  4752.5  725.57
  4801.9  725.64  4823.2  725.05  4830.2  725.34  4910.9  725.09  4941.1  725.65
  4973.4   724.7    4988   721.6  4989.1   721.1  4993.8   721.1  4994.9   721.6
  5011.6   724.6  5031.7  724.61  5041.8  725.48  5051.8   727.4    5062  727.98
    5072   729.1    5082  729.51  5092.1  729.03  5102.2  730.27  5192.8   730.6
  5212.9  731.14  5317.6   731.6  5323.6  731.95  5343.8  731.91  5356.5  732.28
#Mann= 3 ,-1 , 0
  4494.3     .05       0    4988     .04       0  4994.9     .05       0
Bank Sta=4988,4994.9
XS Rating Curve= 0 ,0
Exp/Cntr=0.3,0.1

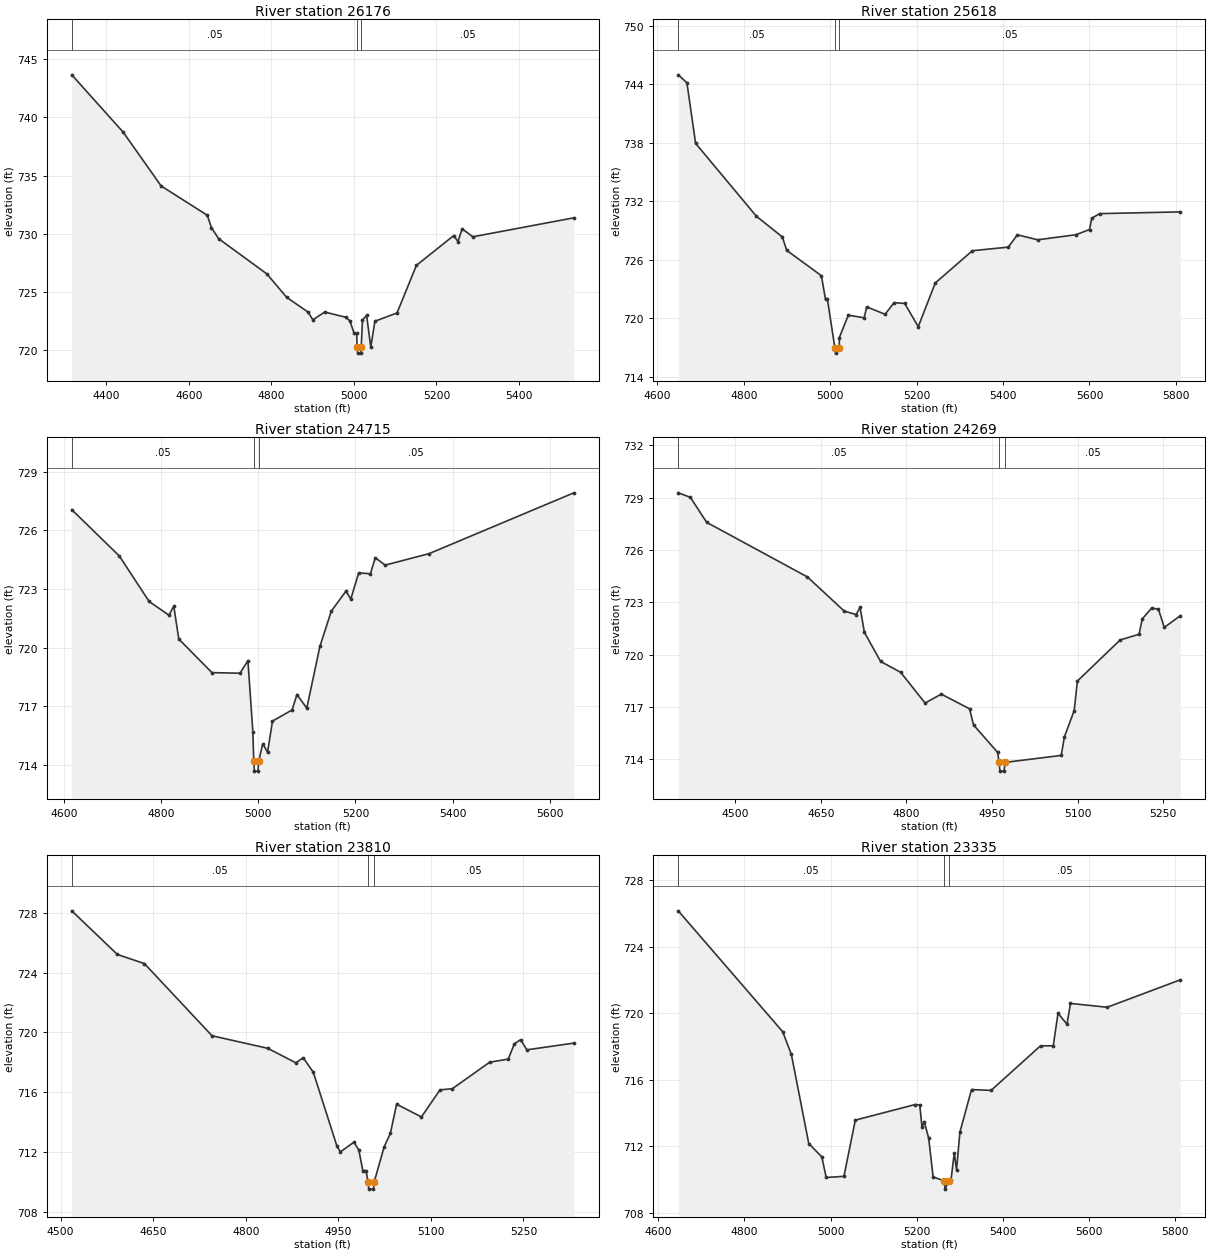
Type RM Length L Ch R = 1 ,26176   ,558,558,558
BEGIN DESCRIPTION:
Denton Creek Tributary 17 43.0
END DESCRIPTION:
XS GIS Cut Line= 3
      2331401.88      7111690.86      2330721.88      7111814.79
      2330199.93      7111871.25
#Sta/Elev= 30
  4316.5  743.66  4441.4  738.72  4532.9  734.12  4644.7   731.6  4654.9  730.53
  4672.2  729.59  4788.9  726.57  4837.1  724.55  4888.7  723.29  4900.6  722.62
  4929.3  723.29  4980.1  722.84  4990.3  722.53  5000.5  721.45  5006.6  721.46
  5007.7  720.26  5009.1  719.76  5016.2  719.76  5017.6  720.26  5020.7   722.6
  5030.7     723  5040.8  720.28  5050.8   722.5  5104.4  723.21  5151.4   727.3
  5241.9  729.86    5252  729.34  5262.1  730.44  5287.9  729.75  5532.7  731.38
#Mann= 3 ,-1 , 0
  4316.5     .05       0  5007.7    .033       0  5017.6     .05       0
Bank Sta=5007.7,5017.6
XS Rating Curve= 0 ,0
Exp/Cntr=0.3,0.1

Type RM Length L Ch R = 1 ,25618   ,903,903,903
BEGIN DESCRIPTION:
Denton Creek Tributary 17 42.0
END DESCRIPTION:
XS GIS Cut Line= 3
        2331179.        7111360.      2330835.13      7111327.78
      2330062.22      7111592.01
#Sta/Elev= 30
  4648.1  744.96  4668.2  744.15  4688.3  737.94  4828.9  730.48  4889.1  728.35
  4899.2  726.98  4979.5  724.38    4989  721.95  4993.5  721.95  5010.8  716.95
  5012.2  716.45  5020.8  716.95  5021.1  718.05  5041.8  720.34  5078.4  720.07
  5084.5  721.19  5126.8  720.43  5147.9  721.62  5172.3  721.54  5203.7  719.16
    5243  723.63  5328.9  726.94  5412.1  727.31  5433.2  728.57  5480.2  728.06
  5568.8  728.58  5600.1  729.11  5605.4  730.27  5623.5  730.74  5810.3  730.92
#Mann= 3 ,-1 , 0
  4648.1     .05       0  5010.8     .04       0  5020.8     .05       0
Bank Sta=5010.8,5020.8
XS Rating Curve= 0 ,0
Exp/Cntr=0.3,0.1

Type RM Length L Ch R = 1 ,24715   ,446,446,446
BEGIN DESCRIPTION:
Denton Creek Tributary 17 41.0
END DESCRIPTION:
XS GIS Cut Line= 3
      2331005.57      7110938.39      2330630.61      7110868.36
      2329983.52      7110951.06
#Sta/Elev= 30
  4615.9  727.06  4714.1  724.68  4775.2  722.36  4815.9  721.66    4826  722.12
  4836.2  720.44  4904.5  718.72  4962.3  718.69  4978.6  719.33  4988.8  715.68
  4990.6  714.18    4992  713.68  4999.3  713.68  5000.7  714.18  5009.1  715.08
  5019.1  714.65  5029.2  716.24  5069.5  716.81  5079.6   717.6  5099.8   716.9
  5126.8  720.06  5150.2  721.86  5180.4  722.89  5190.5  722.49  5206.6  723.82
  5230.8  723.78  5240.9   724.6  5261.1  724.22  5351.8  724.81  5649.7  727.92
#Mann= 3 ,-1 , 0
  4615.9     .05       0  4990.6    .033       0  5000.7     .05       0
Bank Sta=4990.6,5000.7
XS Rating Curve= 0 ,0
Exp/Cntr=0.3,0.1

Type RM Length L Ch R = 1 ,24269   ,459,459,459
BEGIN DESCRIPTION:
Denton Creek Tributary 17 40.0
END DESCRIPTION:
XS GIS Cut Line= 3
      2331078.98      7110959.98      2330628.18      7110567.05
      2330373.64      7110446.62
#Sta/Elev= 30
  4400.2  729.27  4421.5  729.01    4450  727.58  4626.6  724.45  4691.2  722.49
    4712   722.3  4718.7  722.72  4726.3  721.28  4754.8  719.61  4789.9  718.99
  4832.6  717.23  4861.1  717.74  4910.5   716.9  4917.5  715.98  4959.8   714.4
  4962.3  713.83  4963.8  713.33  4971.1  713.33  4972.5  713.83  5071.2  714.23
  5076.7  715.29  5093.9   716.8  5099.5  718.49  5174.3  720.84  5207.5  721.17
  5213.2  722.05  5229.6  722.67  5241.5   722.6  5251.7  721.56  5279.8  722.23
#Mann= 3 ,-1 , 0
  4400.2     .05       0  4962.3    .033       0  4972.5     .05       0
Bank Sta=4962.3,4972.5
XS Rating Curve= 0 ,0
Exp/Cntr=0.3,0.1

Type RM Length L Ch R = 1 ,23810   ,475,475,475
BEGIN DESCRIPTION:
Denton Creek Tributary 17 39.0
END DESCRIPTION:
XS GIS Cut Line= 3
      2331278.97      7110459.98      2330862.69      7110236.68
      2330523.22      7110202.31
#Sta/Elev= 30
  4518.1  728.13    4592  725.21  4635.8   724.6  4745.4  719.77  4835.8  718.93
  4881.2  717.96  4893.2   718.3  4909.5  717.33  4947.7   712.4  4953.3     712
  4975.3  712.65  4983.3  712.12  4989.7  710.75  4994.9  710.75  4998.1  710.01
  4999.5  709.51  5006.9  709.51  5008.3  710.01  5024.4  712.35  5034.4  713.24
  5044.5  715.19  5084.7  714.34  5114.8  716.15  5134.9  716.23  5195.2     718
  5225.4  718.21  5235.4  719.24  5245.5  719.51  5255.5  718.83  5331.7  719.28
#Mann= 3 ,-1 , 0
  4518.1     .05       0  4998.1     .04       0  5008.3     .05       0
Bank Sta=4998.1,5008.3
XS Rating Curve= 0 ,0
Exp/Cntr=0.3,0.1

Type RM Length L Ch R = 1 ,23335   ,487,487,487
BEGIN DESCRIPTION:
Denton Creek Tributary 17 38.0
END DESCRIPTION:
XS GIS Cut Line= 3
      2331278.97        7109860.        2330929.        7109810.
      2330144.91      7109599.78
#Sta/Elev= 30
  4646.5  726.17  4888.9   718.9  4909.1  717.53  4949.5  712.17  4979.8  711.37
  4989.9  710.13  5031.1   710.2  5057.5  713.58  5196.7  714.52  5207.1  714.49
  5212.3  713.15  5217.5  713.49  5227.8  712.49  5238.1  710.16    5264  709.93
  5265.5  709.43  5274.4  709.93  5279.6  709.98  5287.2  711.61  5292.4  710.59
  5300.3  712.86  5327.2  715.42  5372.7  715.37  5487.3  718.05  5516.9  718.05
    5528  720.01  5548.7  719.35  5556.9   720.6  5642.1  720.37  5811.8  722.02
#Mann= 3 ,-1 , 0
  4646.5     .05       0    5264    .033       0  5274.4     .05       0
Bank Sta=5264,5274.4
XS Rating Curve= 0 ,0
Exp/Cntr=0.3,0.1