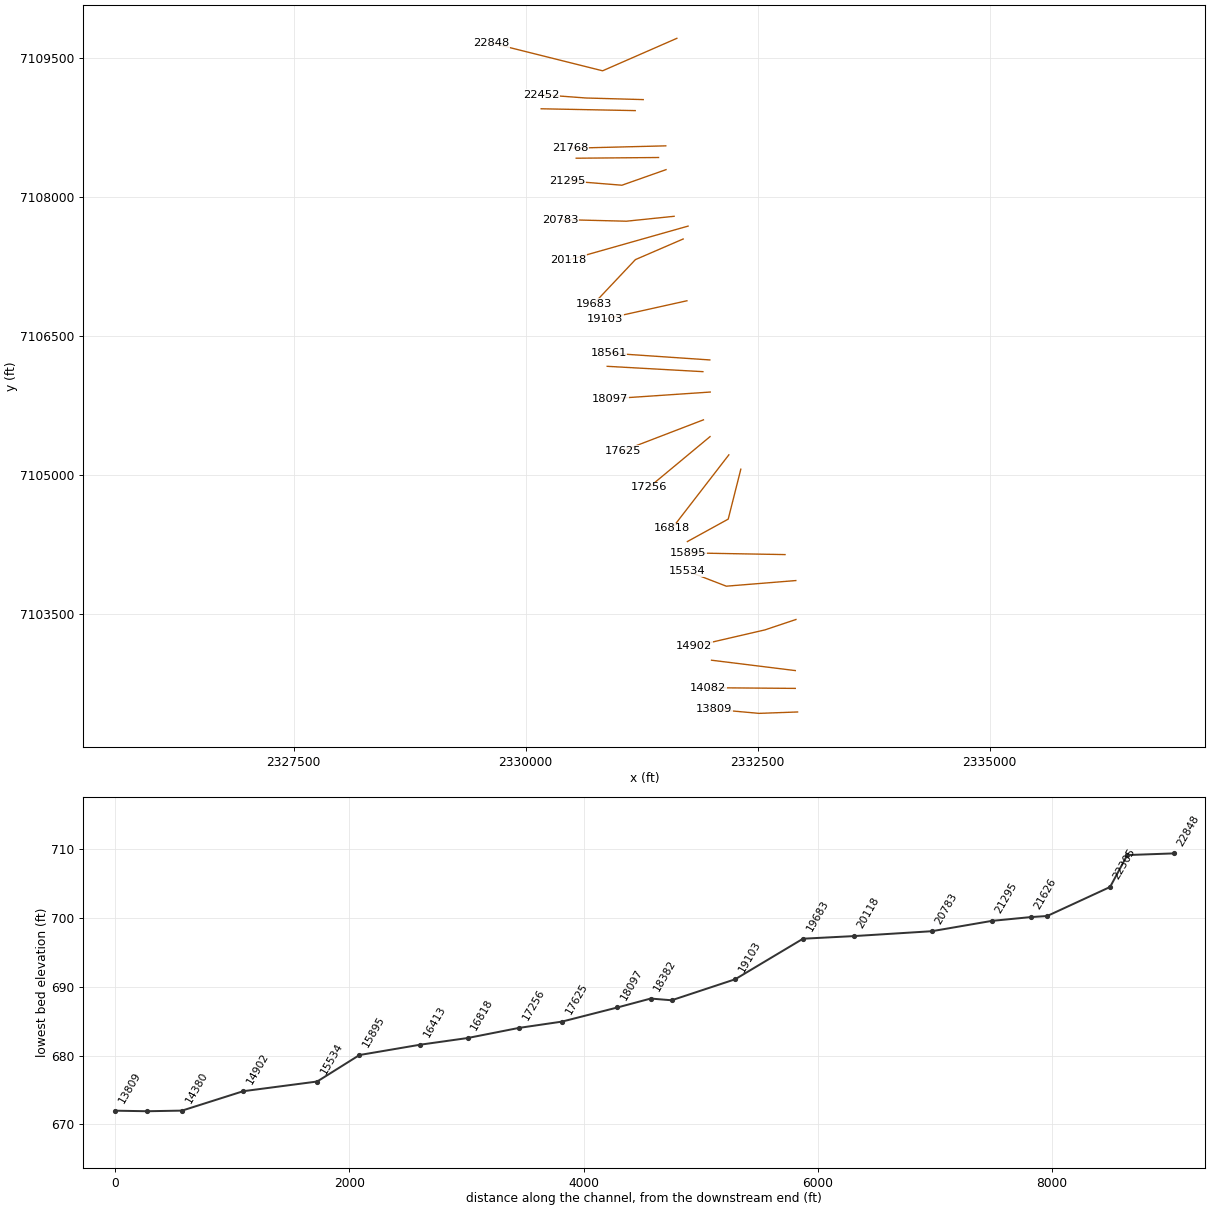
HEC-RAS study Denton Creek Tributary 17.prj: Denton Creek Tributary 17 Base Level Engineering

--- Denton Creek Tributary 17.g01 (geometry) --- (continued)

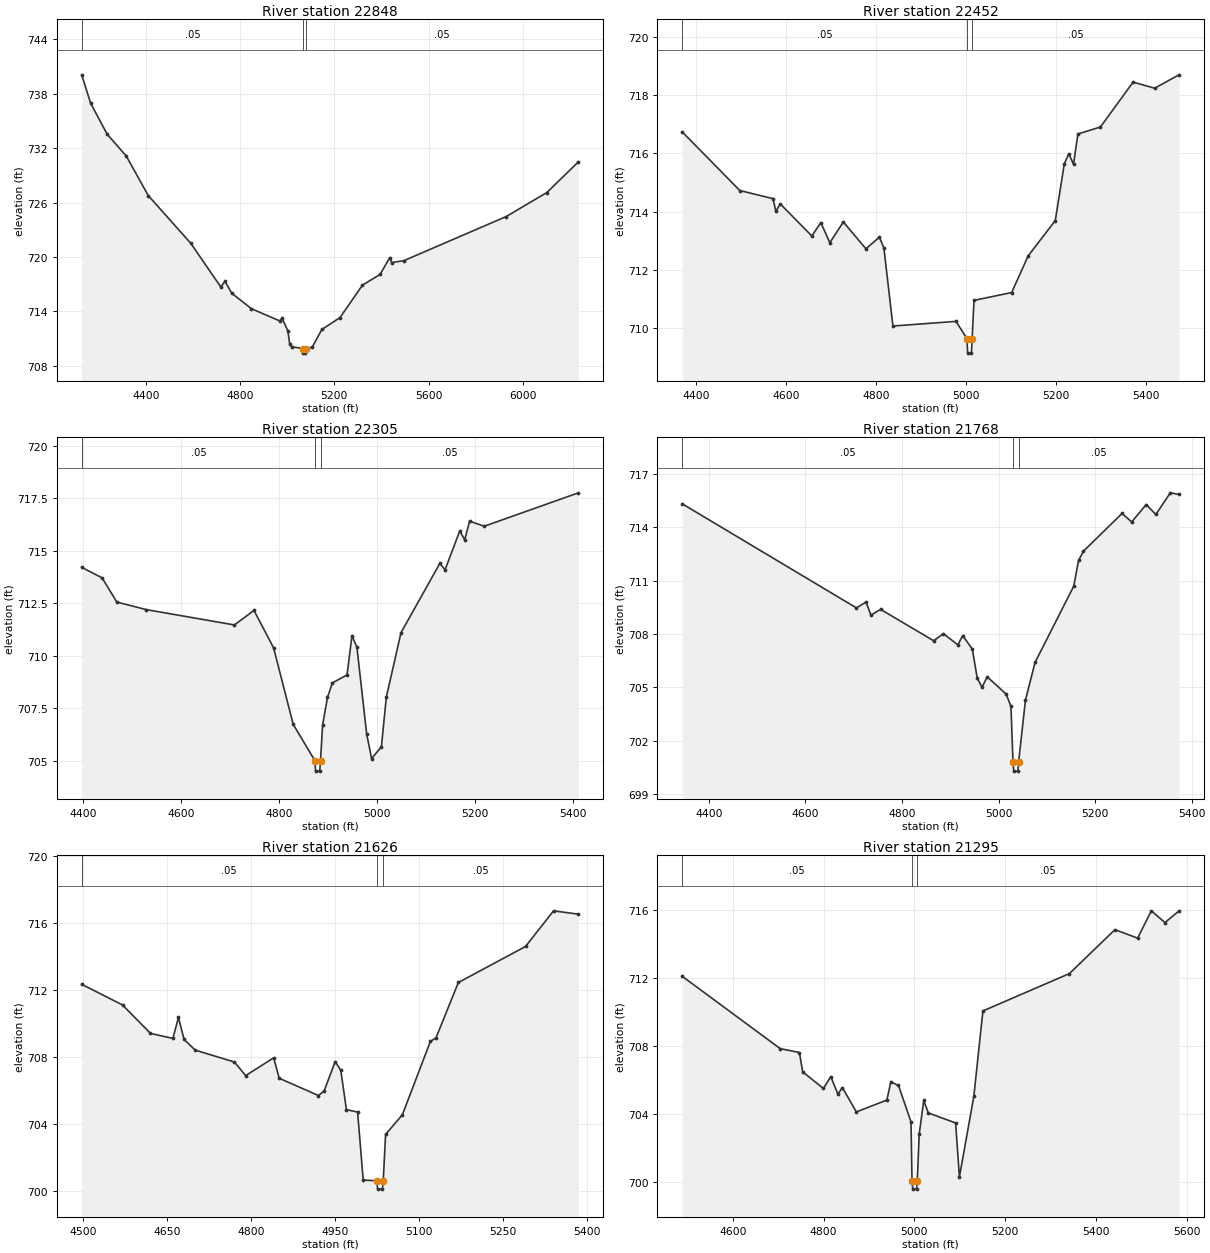
Type RM Length L Ch R = 1 ,22848   ,396,396,396
BEGIN DESCRIPTION:
Denton Creek Tributary 17 37.0
END DESCRIPTION:
XS GIS Cut Line= 3
      2331628.99        7109710.        2330829.        7109360.
      2329629.03      7109659.99
#Sta/Elev= 30
  4126.8   740.1  4164.6  736.96  4234.8  733.54  4315.9  731.14  4409.4  726.77
  4589.5  721.52  4717.4  716.69  4735.3   717.3  4764.2  715.99  4847.2  714.29
  4967.6  712.94  4978.2  713.22  5002.6  711.82  5010.3  710.38    5018  710.09
    5067  709.88  5068.4  709.38  5075.9  709.38  5077.4  709.88  5105.7  710.03
  5146.9  711.99  5224.2  713.31  5319.5  716.89  5394.3  718.07  5435.5  719.93
  5443.2  719.38  5494.8  719.58  5930.3  724.46  6102.9  727.11  6236.9   730.5
#Mann= 3 ,-1 , 0
  4126.8     .05       0    5067    .033       0  5077.4     .05       0
Bank Sta=5067,5077.4
XS Rating Curve= 0 ,0
Exp/Cntr=0.3,0.1

Type RM Length L Ch R = 1 ,22452   ,147,147,147
BEGIN DESCRIPTION:
Mapping XS 276bbecb
END DESCRIPTION:
XS GIS Cut Line= 3
      2331266.61       7109049.4      2330648.96      7109066.67
      2330165.09      7109102.78
#Sta/Elev= 30
  4369.5  716.73  4497.2  714.72  4571.1  714.44  4577.2  714.01  4587.2  714.26
  4657.2  713.16  4677.2  713.62  4697.2  712.93  4727.2  713.64  4777.3  712.72
  4807.3  713.12  4817.3  712.74  4837.3  710.07  4977.3  710.23  5001.7  709.64
  5003.3  709.14  5011.6  709.14  5013.2  709.64  5017.4  710.95    5101  711.22
  5137.8  712.48  5197.9  713.69    5218  715.64    5228  715.98  5238.4  715.62
  5248.1  716.66  5298.2   716.9  5370.7  718.44  5418.5  718.23  5472.6  718.69
#Mann= 3 ,-1 , 0
  4369.5     .05       0  5001.7    .033       0  5013.2     .05       0
Bank Sta=5001.7,5013.2
XS Rating Curve= 0 ,0
Exp/Cntr=0.3,0.1

Type RM Length L Ch R = 1 ,22305   ,537,537,537
BEGIN DESCRIPTION:
Mapping XS f6db2351
END DESCRIPTION:
XS GIS Cut Line= 2
      2331180.54      7108930.68      2330166.84      7108950.42
#Sta/Elev= 30
  4397.5   714.2  4439.1   713.7  4469.1  712.55  4529.1  712.19  4709.1  711.46
  4749.1  712.15  4789.1  710.37  4829.1  706.73  4873.4     705  4874.9   704.5
  4883.3   704.5  4884.9     705  4889.1  706.68  4899.1  708.01  4909.1   708.7
  4939.1  709.08  4949.1  710.95  4959.2   710.4  4979.2  706.25  4989.2   705.1
  5009.2  705.66  5019.2  708.02  5049.2  711.09  5128.5  714.39  5139.2  714.09
  5169.2  715.94  5179.2  715.51  5189.2   716.4  5219.2  716.16  5411.4  717.75
#Mann= 3 ,-1 , 0
  4397.5     .05       0  4873.4    .033       0  4884.9     .05       0
Bank Sta=4873.4,4884.9
XS Rating Curve= 0 ,0
Exp/Cntr=0.3,0.1

Type RM Length L Ch R = 1 ,21768   ,142,142,142
BEGIN DESCRIPTION:
Mapping XS ec1e3616
END DESCRIPTION:
XS GIS Cut Line= 2
      2331509.58      7108550.68       2330481.1      7108524.97
#Sta/Elev= 30
    4345  715.33  4705.7  709.47  4725.7   709.8  4735.7  709.06  4755.7  709.39
  4865.7  707.62  4885.8  708.02  4915.8  707.39  4925.8  707.91  4945.8  707.15
  4955.8  705.53  4965.8     705  4976.6  705.59  5015.8  704.62  5025.8  703.92
    5030  700.78  5031.6  700.28    5040  700.28  5041.6  700.78  5055.8  704.28
  5075.8  706.41  5155.8  710.69  5165.8  712.14  5175.8  712.66  5255.9  714.79
  5275.9  714.31  5305.9  715.29  5325.9  714.73  5355.9  715.95  5373.8  715.86
#Mann= 3 ,-1 , 0
    4345     .05       0    5030     .04       0  5041.6     .05       0
Bank Sta=5030,5041.6
XS Rating Curve= 0 ,0
Exp/Cntr=0.3,0.1

Type RM Length L Ch R = 1 ,21626   ,331,331,331
BEGIN DESCRIPTION:
Mapping XS 6586c7e2
END DESCRIPTION:
XS GIS Cut Line= 2
      2331431.76      7108424.98      2330544.49      7108417.33
#Sta/Elev= 30
  4497.7  712.35  4570.5  711.12  4620.5  709.42  4660.5  709.12  4670.5  710.37
  4680.5  709.06  4700.5  708.42  4770.5  707.71  4790.5   706.9  4840.5  707.96
  4850.5  706.74  4920.5  705.71  4930.5  705.97  4950.5  707.74  4960.5  707.21
  4970.5  704.87  4990.5  704.72  5000.5  700.66  5024.7  700.62  5026.3  700.12
  5034.7  700.12  5036.3  700.62  5040.5  703.39  5070.5  704.56  5120.5  708.94
  5130.5  709.15  5170.5  712.46  5290.5  714.61  5340.5  716.74    5385  716.54
#Mann= 3 ,-1 , 0
  4497.7     .05       0  5024.7     .04       0  5036.3     .05       0
Bank Sta=5024.7,5036.3
XS Rating Curve= 0 ,0
Exp/Cntr=0.3,0.1

Type RM Length L Ch R = 1 ,21295   ,512,512,512
BEGIN DESCRIPTION:
Mapping XS d9db8377
END DESCRIPTION:
XS GIS Cut Line= 3
      2331512.45        7108294.      2331037.02      7108126.15
      2330448.22      7108173.67
#Sta/Elev= 30
  4488.5  712.11  4704.3  707.85  4746.7  707.62  4753.9  706.48  4799.7   705.5
  4815.8   706.2  4831.5  705.17  4841.4  705.55  4872.3  704.12  4939.5  704.82
  4948.2  705.89  4965.1  705.68  4992.7  703.53  4994.9  700.07  4996.5  699.57
  5004.9  699.57  5006.5  700.07  5010.8  702.82  5020.8   704.8  5030.8  704.06
    5091  703.47  5099.4  700.29  5131.2  705.04  5151.2  710.07  5341.8  712.27
  5442.2  714.86  5492.3  714.36  5522.4  715.97  5552.5  715.28  5583.4  715.96
#Mann= 3 ,-1 , 0
  4488.5     .05       0  4994.9    .033       0  5006.5     .05       0
Bank Sta=4994.9,5006.5
XS Rating Curve= 0 ,0
Exp/Cntr=0.3,0.1

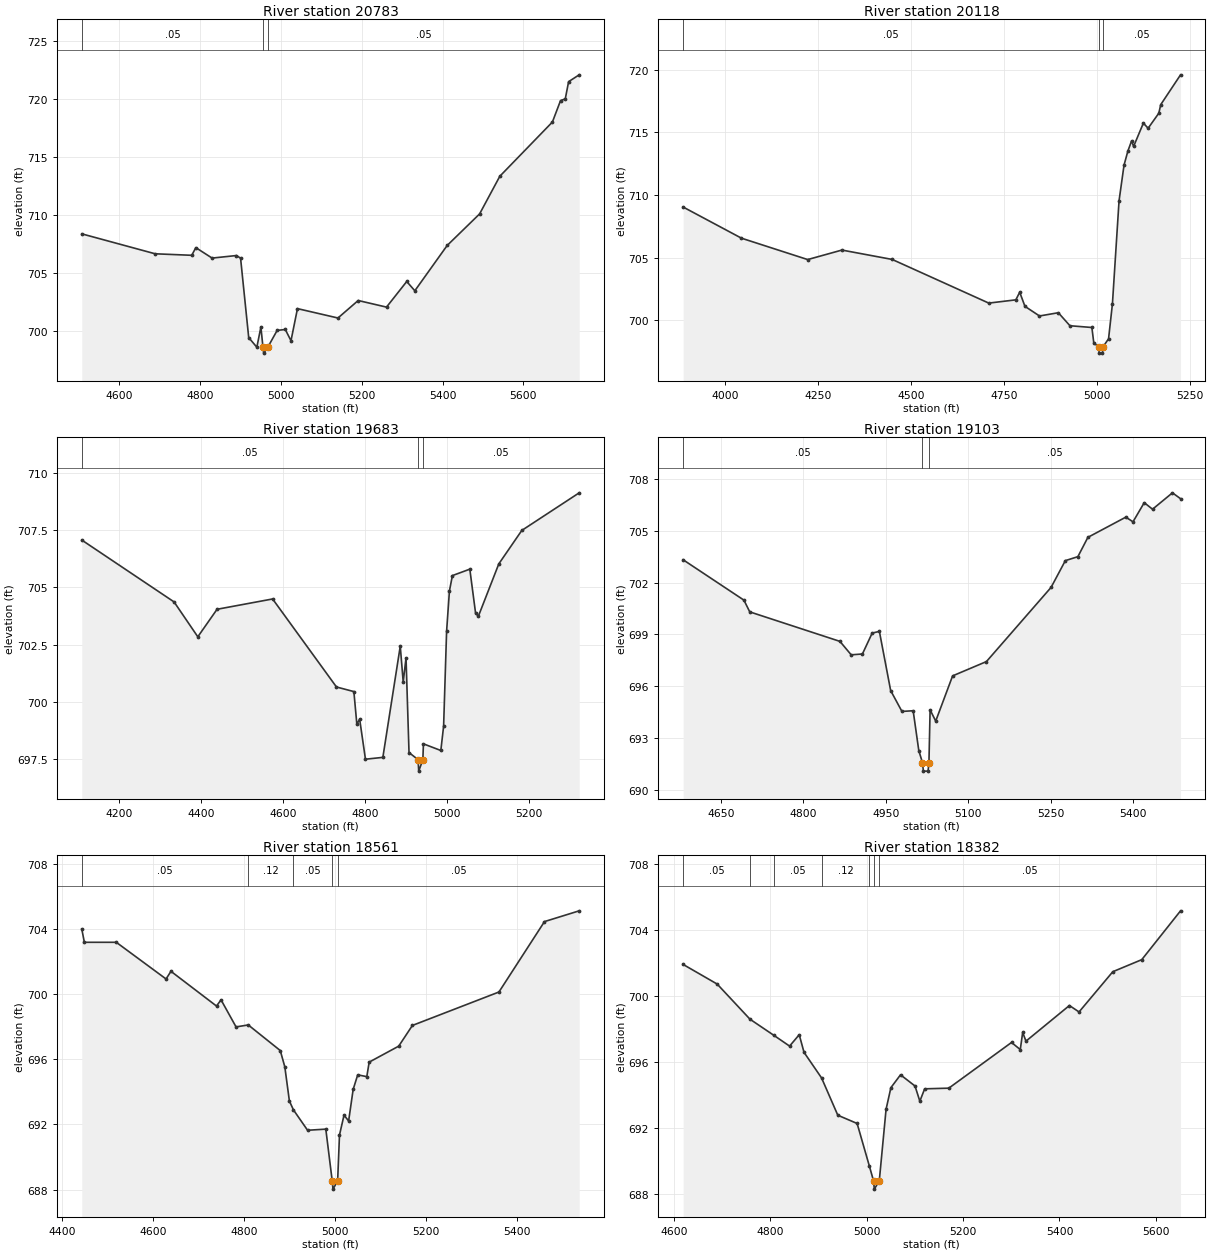
Type RM Length L Ch R = 1 ,20783   ,665,665,665
BEGIN DESCRIPTION:
Mapping XS 12f29107
END DESCRIPTION:
XS GIS Cut Line= 3
       2331599.4      7107791.01      2331084.98       7107738.1
      2330372.84      7107755.94
#Sta/Elev= 30
  4508.4  708.36  4689.8  706.64  4780.2  706.51  4790.3  707.17  4830.5  706.27
  4890.8  706.49  4900.9  706.26    4921  699.41  4941.1  698.58  4951.1  700.32
  4956.3  698.57    4958  698.07    4968  698.57  4991.3  700.03  5011.4  700.11
  5025.5  699.14  5041.5  701.91  5141.6   701.1  5191.6  702.61  5261.6  702.04
  5311.6  704.25  5331.6  703.45  5411.6  707.36  5491.7  710.08  5541.7  713.33
  5671.7  718.01  5691.7  719.85  5703.5  720.01  5711.7  721.49  5737.9  722.08
#Mann= 3 ,-1 , 0
  4508.4     .05       0  4956.3    .033       0    4968     .05       0
Bank Sta=4956.3,4968
XS Rating Curve= 0 ,0
Exp/Cntr=0.3,0.1

Type RM Length L Ch R = 1 ,20118   ,435,435,435
BEGIN DESCRIPTION:
Mapping XS 09b8ca5e
END DESCRIPTION:
XS GIS Cut Line= 2
      2331749.95      7107685.32      2330462.75       7107320.5
#Sta/Elev= 30
  3886.6  709.04  4043.5  706.55  4221.6  704.84  4313.7   705.6  4448.9  704.85
  4708.7  701.36  4781.5  701.62  4791.9  702.23    4806   701.1  4845.1  700.33
  4895.8  700.59    4927  699.55    4986  699.41  4991.2  698.17  5004.3  697.86
  5005.9  697.36  5014.4  697.36    5016  697.86  5030.9  698.51  5041.3   701.3
  5059.1  709.54  5072.5  712.39  5082.9  713.52    5093  714.34  5098.2  713.88
  5124.5  715.75  5137.3  715.34    5166  716.54  5171.3  717.23  5224.5  719.61
#Mann= 3 ,-1 , 0
  3886.6     .05       0  5004.3     .04       0    5016     .05       0
Bank Sta=5004.3,5016
XS Rating Curve= 0 ,0
Exp/Cntr=0.3,0.1

Type RM Length L Ch R = 1 ,19683   ,580,580,580
BEGIN DESCRIPTION:
Mapping XS 07320d84
END DESCRIPTION:
XS GIS Cut Line= 3
      2331696.91      7107546.21      2331182.38      7107323.95
      2330733.33      7106847.76
#Sta/Elev= 30
  4108.5  707.06    4334  704.36  4391.9  702.84  4438.9  704.04  4574.6  704.49
  4730.6  700.65  4773.1  700.45  4780.4  699.02  4787.2  699.25  4801.4   697.5
  4843.9  697.58  4886.4  702.43  4893.6  700.87  4900.5  701.92  4907.8  697.79
  4929.9  697.48  4931.5  696.98  4941.6  697.48    4943  698.17  4985.5  697.88
  4992.3  698.94  4999.6  703.08  5006.5  704.84  5013.8  705.51  5056.3  705.79
  5070.4  703.87  5077.3  703.74  5127.1  706.02  5183.3  707.48  5323.5  709.12
#Mann= 3 ,-1 , 0
  4108.5     .05       0  4929.9     .04       0  4941.6     .05       0
Bank Sta=4929.9,4941.6
XS Rating Curve= 0 ,0
Exp/Cntr=0.3,0.1

Type RM Length L Ch R = 1 ,19103   ,542,542,542
BEGIN DESCRIPTION:
Mapping XS 43e0791d
END DESCRIPTION:
XS GIS Cut Line= 2
      2331737.18      7106880.02      2330854.61      7106683.91
#Sta/Elev= 30
  4581.7  703.33  4692.2  700.99  4702.8  700.31  4866.7   698.6  4887.2  697.82
  4907.6  697.87  4925.3  699.08  4938.4  699.18  4958.9  695.75  4979.4  694.54
  4999.8  694.58  5010.1  692.26  5016.7  691.58  5018.4  691.08  5026.9  691.08
  5028.5  691.58  5030.6  694.63  5040.8  693.98  5071.5   696.6    5133  697.43
  5250.5  701.73  5276.4  703.28  5299.2  703.51  5317.4  704.63  5386.3   705.8
  5399.4  705.53  5419.8  706.64  5434.9  706.26  5471.1  707.21  5485.8  706.87
#Mann= 3 ,-1 , 0
  4581.7     .05       0  5016.7    .033       0  5028.5     .05       0
Bank Sta=5016.7,5028.5
XS Rating Curve= 0 ,0
Exp/Cntr=0.3,0.1

Type RM Length L Ch R = 1 ,18561   ,179,179,179
BEGIN DESCRIPTION:
Mapping XS b5e0e872
END DESCRIPTION:
XS GIS Cut Line= 2
       2331984.7      7106242.15      2330892.82       7106316.3
#Sta/Elev= 30
    4443  703.98  4448.7  703.17  4518.9  703.17  4628.4  700.92  4639.2  701.39
  4739.4  699.26  4749.4  699.64  4782.4  697.98  4809.3   698.1  4879.7  696.53
  4889.7  695.53  4899.8  693.43  4908.7  692.89  4939.8  691.64  4979.9  691.71
    4994  688.53  4995.7  688.03  5005.9  688.53    5010  691.35    5020  692.57
  5030.1  692.21  5040.1  694.15  5050.1  695.04  5070.1  694.93  5075.3  695.82
  5140.3   696.8  5170.4  698.07  5360.8  700.12    5461  704.44  5537.4   705.1
#Mann= 5 ,-1 , 0
    4443     .05       0  4809.3     .12       0  4908.7     .05       0
    4994     .04       0  5005.9     .05       0
Bank Sta=4994,5005.9
XS Rating Curve= 0 ,0
Exp/Cntr=0.3,0.1

Type RM Length L Ch R = 1 ,18382   ,285,285,285
BEGIN DESCRIPTION:
Mapping XS a9a5d149
END DESCRIPTION:
XS GIS Cut Line= 2
      2331909.62      7106115.77      2330878.63      7106173.39
#Sta/Elev= 30
  4618.7   701.9  4689.4  700.71  4757.5  698.58  4806.7  697.61  4839.7  696.95
  4859.7  697.64  4869.7  696.57  4906.1  695.02  4939.8  692.76  4979.9  692.26
  5005.4  689.67    5014  688.78  5015.6  688.28  5025.9  688.78    5040  693.12
    5050  694.43    5070  695.21  5100.1  694.53  5110.1  693.61  5120.1  694.36
  5170.2   694.4  5300.4  697.17  5318.6  696.74  5323.6  697.78  5330.4  697.25
  5420.6  699.41  5440.6  699.02  5510.7  701.46  5570.8  702.19  5651.3  705.15
#Mann= 7 ,-1 , 0
  4618.7     .05       0  4757.5     .12       0  4806.7     .05       0
  4906.1     .12       0  5005.4     .05       0    5014     .07       0
  5025.9     .05       0
Bank Sta=5014,5025.9
XS Rating Curve= 0 ,0
Exp/Cntr=0.3,0.1

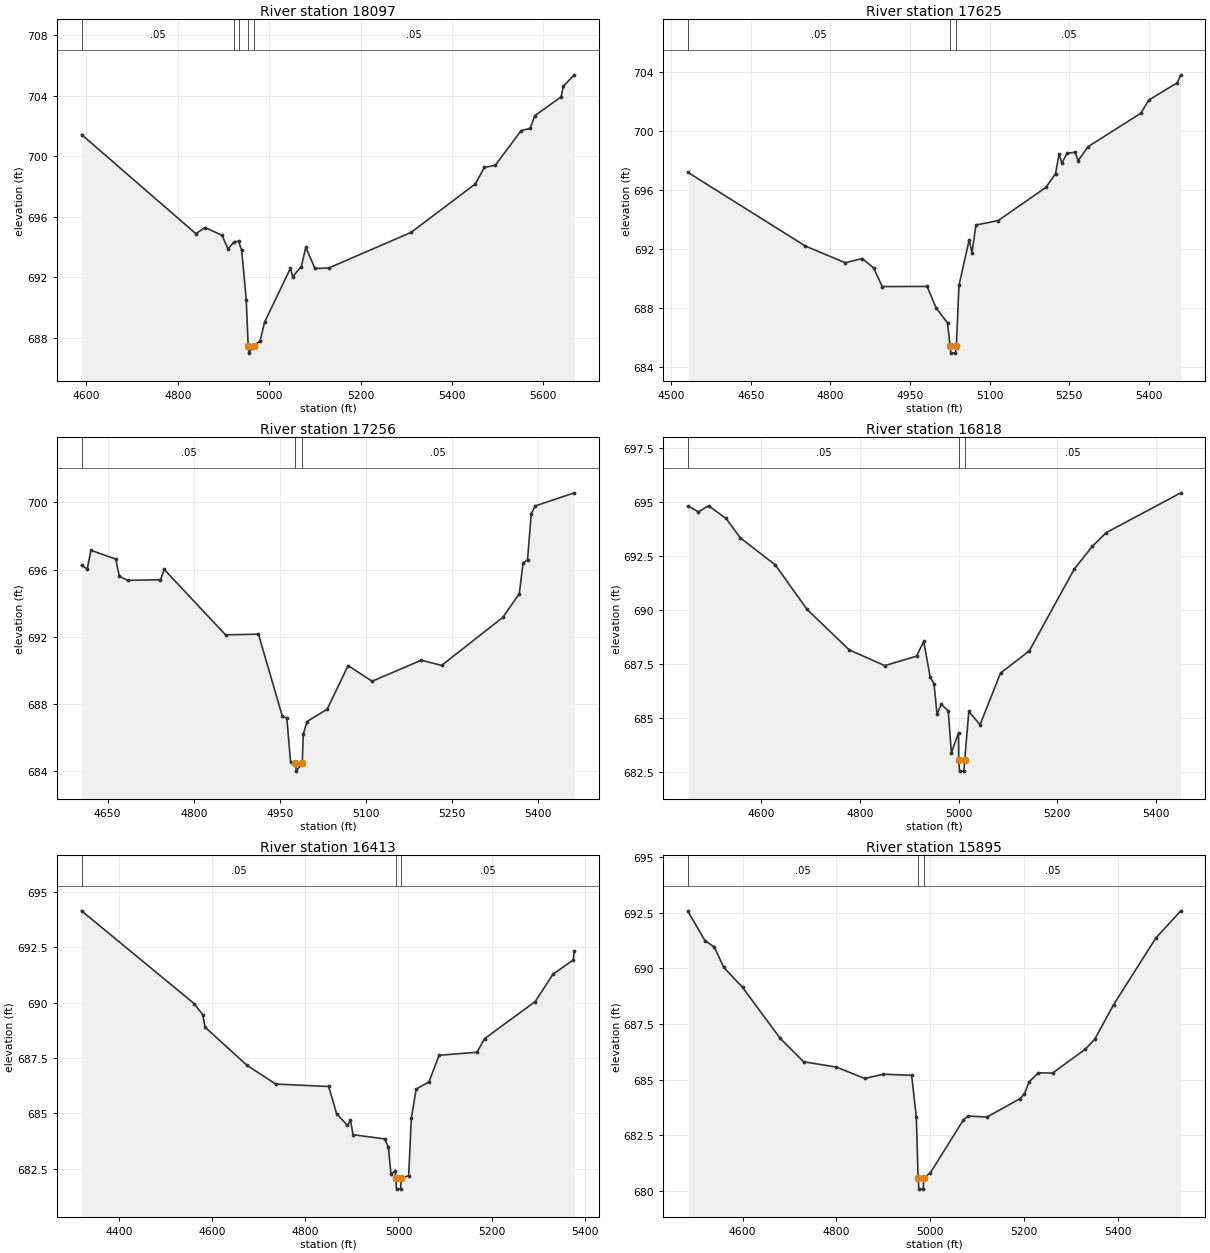
Type RM Length L Ch R = 1 ,18097   ,472,472,472
BEGIN DESCRIPTION:
Mapping XS 28fbedd5
END DESCRIPTION:
XS GIS Cut Line= 2
      2331988.58      7105895.89      2330912.84      7105823.21
#Sta/Elev= 30
  4589.5  701.44  4839.7  694.88  4859.7  695.29  4897.1  694.77  4909.8  693.88
  4923.8  694.35    4933  694.38  4939.9  693.77  4949.9  690.51    4954  687.48
  4955.6  686.98  4965.9  687.48    4980  687.77    4990  689.03  5046.5  692.59
  5051.5  692.04  5070.2   692.7  5080.2  693.98  5100.2  692.58  5130.3  692.61
  5310.7  694.97    5451  698.17  5471.1  699.27  5494.5   699.4  5551.3   701.7
  5571.3  701.85  5581.3  702.69  5638.8  703.93  5643.8  704.64  5667.7  705.39
#Mann= 5 ,-1 , 0
  4589.5     .05       0  4923.8     .12       0    4933     .05       0
    4954    .033       0  4965.9     .05       0
Bank Sta=4954,4965.9
XS Rating Curve= 0 ,0
Exp/Cntr=0.3,0.1

Type RM Length L Ch R = 1 ,17625   ,369,369,369
BEGIN DESCRIPTION:
Mapping XS 50e5a643
END DESCRIPTION:
XS GIS Cut Line= 3
      2331915.54      7105596.39      2331103.45       7105284.2
      2331049.06      7105261.93
#Sta/Elev= 30
  4531.6   697.2  4752.9   692.2  4827.9  691.07    4860  691.35  4881.4  690.72
  4897.6  689.45  4982.3  689.46  4999.3  687.99  5020.7  686.99  5025.5  685.43
  5027.1  684.93  5035.7  684.93  5037.4  685.43  5042.3  689.53  5061.6  692.63
  5066.9  691.75  5074.3  693.63  5116.2  693.93  5206.3  696.19  5224.3  697.11
  5230.9  698.44  5236.3  697.83  5245.7  698.49  5260.9  698.58  5267.1  698.01
  5285.6  698.95    5385  701.22  5400.2  702.12  5453.7  703.29  5460.4  703.83
#Mann= 3 ,-1 , 0
  4531.6     .05       0  5025.5    .033       0  5037.4     .05       0
Bank Sta=5025.5,5037.4
XS Rating Curve= 0 ,0
Exp/Cntr=0.3,0.1

Type RM Length L Ch R = 1 ,17256   ,438,438,438
BEGIN DESCRIPTION:
Mapping XS c22e9798
END DESCRIPTION:
XS GIS Cut Line= 2
      2331986.76      7105415.38      2331326.63      7104866.83
#Sta/Elev= 30
  4604.6  696.25  4614.5  696.04    4621  697.15    4664  696.63  4670.5  695.61
  4684.8  695.36  4742.1   695.4  4748.6  696.01  4855.4  692.12  4912.7  692.16
  4954.3  687.28  4962.2  687.16  4968.7  684.54    4977  684.51  4978.7  684.01
    4989  684.51  4990.8   686.2  4997.3  686.96  5032.5   687.7  5068.9  690.29
  5110.6  689.36  5196.5  690.61  5231.7   690.3  5338.4  693.16  5367.1  694.57
  5373.6  696.39  5381.4  696.58  5387.9  699.33  5394.8  699.79  5462.9  700.57
#Mann= 3 ,-1 , 0
  4604.6     .05       0    4977    .033       0    4989     .05       0
Bank Sta=4977,4989
XS Rating Curve= 0 ,0
Exp/Cntr=0.3,0.1

Type RM Length L Ch R = 1 ,16818   ,405,405,405
BEGIN DESCRIPTION:
Mapping XS 05025829
END DESCRIPTION:
XS GIS Cut Line= 2
      2332189.23      7105218.52       2331579.2      7104428.16
#Sta/Elev= 30
  4451.9  694.83  4472.9  694.56  4493.7  694.84    4529  694.25    4558  693.35
  4628.7   692.1    4693  690.04  4778.5  688.16  4850.6  687.43  4914.9  687.87
  4929.4  688.55  4942.7  686.89  4950.2   686.6  4956.5  685.17  4964.7  685.64
  4979.2  685.33  4985.5  683.39    5000  684.32  5000.4  683.04  5002.1  682.54
  5010.7  682.54  5012.4  683.04  5020.9  685.31  5043.5  684.69  5085.2  687.09
  5143.2  688.11  5234.6  691.91  5271.1  692.96  5298.9  693.59  5450.3  695.44
#Mann= 3 ,-1 , 0
  4451.9     .05       0  5000.4     .04       0  5012.4     .05       0
Bank Sta=5000.4,5012.4
XS Rating Curve= 0 ,0
Exp/Cntr=0.3,0.1

Type RM Length L Ch R = 1 ,16413   ,518,518,518
BEGIN DESCRIPTION:
Mapping XS ba63bced
END DESCRIPTION:
XS GIS Cut Line= 3
      2332318.43      7105064.14      2332182.52      7104525.86
      2331742.48      7104283.58
#Sta/Elev= 30
  4319.9  694.15  4561.4  689.96    4580  689.45  4585.1  688.89  4674.8  687.17
  4736.7  686.32  4850.2  686.21  4867.3  684.98  4890.5  684.45  4896.9  684.69
  4902.6  684.03  4970.4  683.84  4978.3  683.48    4984  682.25  4993.2   682.4
  4994.1  682.07  4995.8  681.57  5004.5  681.57  5006.1  682.07  5021.9  682.18
  5027.6  684.77    5038  686.09  5065.5  686.42  5087.2  687.62  5168.7  687.76
  5184.7  688.37  5293.6  690.05  5331.5  691.28  5375.1  691.93  5377.4  692.34
#Mann= 3 ,-1 , 0
  4319.9     .05       0  4994.1     .04       0  5006.1     .05       0
Bank Sta=4994.1,5006.1
XS Rating Curve= 0 ,0
Exp/Cntr=0.3,0.1

Type RM Length L Ch R = 1 ,15895   ,361,361,361
BEGIN DESCRIPTION:
Mapping XS 4a11c76b
END DESCRIPTION:
XS GIS Cut Line= 2
      2332794.98      7104143.21      2331746.04      7104161.64
#Sta/Elev= 30
    4484  692.56    4520  691.25    4540  690.96    4560  690.05    4600  689.15
    4680  686.86    4730   685.8    4800  685.56    4860  685.05    4900  685.24
  4960.1  685.19  4970.1  683.31  4973.9  680.57  4975.6  680.07  4984.5  680.07
  4986.3  680.57  5000.1  680.81  5070.1  683.18  5080.1  683.36  5120.1  683.31
  5190.1  684.13  5200.1  684.34  5210.1   684.9  5230.1   685.3  5260.1  685.29
  5330.1  686.37  5350.1  686.82  5390.1  688.37  5480.1  691.37  5533.1  692.59
#Mann= 3 ,-1 , 0
    4484     .05       0  4973.9     .04       0  4986.3     .05       0
Bank Sta=4973.9,4986.3
XS Rating Curve= 0 ,0
Exp/Cntr=0.3,0.1

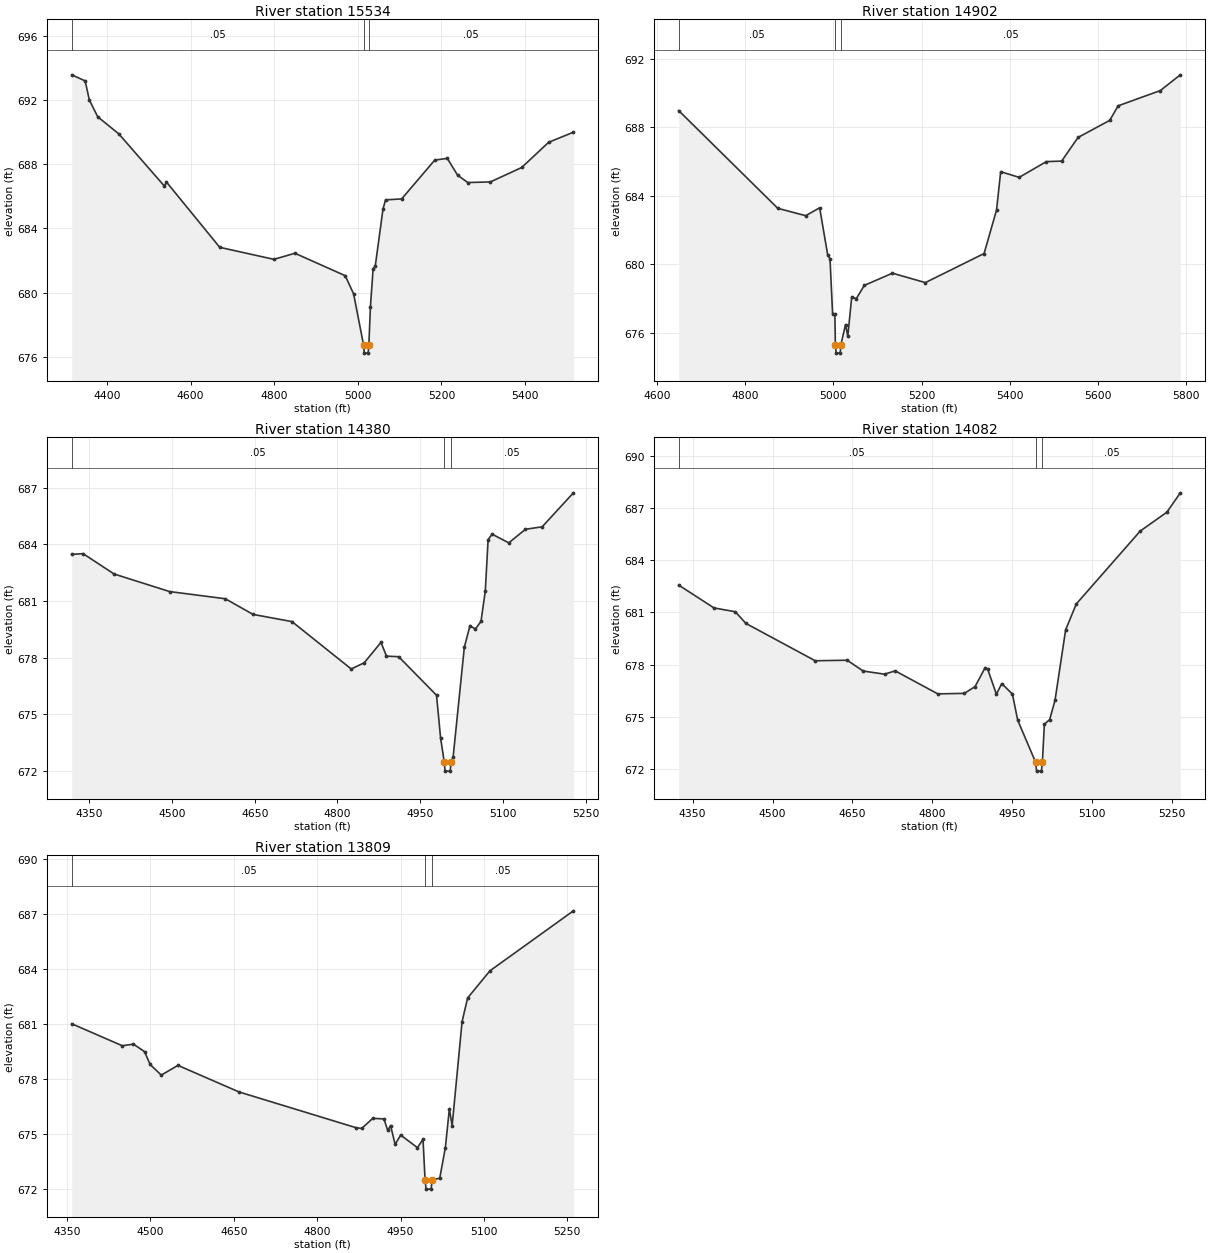
Type RM Length L Ch R = 1 ,15534   ,632,632,632
BEGIN DESCRIPTION:
Mapping XS 4603deea
END DESCRIPTION:
XS GIS Cut Line= 3
      2332910.99      7103863.15      2332161.88      7103802.63
       2331743.7      7103964.05
#Sta/Elev= 30
  4315.7  693.58  4347.8   693.2  4357.8  692.01  4377.9  690.96  4428.1   689.9
  4537.3  686.64  4542.3  686.89  4669.6  682.82  4799.3  682.07  4849.4  682.45
  4969.8  681.05  4989.9  679.91  5013.7  676.72  5015.4  676.22  5024.5  676.22
  5026.3  676.72    5030  679.09  5036.5  681.49  5041.5  681.63  5060.1   685.2
  5066.2  685.78  5104.7  685.84  5183.9  688.26  5213.9  688.37  5238.5  687.32
  5263.1  686.86  5316.9   686.9  5391.9   687.8  5456.2  689.37  5515.5     690
#Mann= 3 ,-1 , 0
  4315.7     .05       0  5013.7    .033       0  5026.3     .05       0
Bank Sta=5013.7,5026.3
XS Rating Curve= 0 ,0
Exp/Cntr=0.3,0.1

Type RM Length L Ch R = 1 ,14902   ,522,522,522
BEGIN DESCRIPTION:
Mapping XS 89bcc9ae
END DESCRIPTION:
XS GIS Cut Line= 3
      2332912.07      7103443.26      2332578.38      7103331.27
      2331813.02      7103154.01
#Sta/Elev= 30
  4649.3  688.98  4874.1  683.27  4937.3  682.84    4969   683.3  4987.2  680.55
  4992.5  680.32  4998.3  677.11  5003.5  677.11  5004.6  675.31  5006.4  674.81
  5015.5  674.81  5017.2  675.31  5027.7  676.48  5032.8   675.8  5041.7  678.09
    5052  677.99  5070.4  678.77  5134.1  679.48  5208.7  678.93  5341.9  680.63
  5370.2  683.18  5379.5  685.41  5421.5  685.08  5483.1     686  5517.8  686.03
  5554.9  687.41  5626.8  688.41  5645.9  689.26  5741.5  690.15  5786.9  691.07
#Mann= 3 ,-1 , 0
  4649.3     .05       0  5004.6     .04       0  5017.2     .05       0
Bank Sta=5004.6,5017.2
XS Rating Curve= 0 ,0
Exp/Cntr=0.3,0.1

Type RM Length L Ch R = 1 ,14380   ,298,298,298
BEGIN DESCRIPTION:
Mapping XS c7b6f1ce
END DESCRIPTION:
XS GIS Cut Line= 2
      2332905.21      7102892.58       2332002.8      7103004.27
#Sta/Elev= 30
  4318.4  683.47  4338.9  683.51  4395.2  682.43  4495.9   681.5  4596.7  681.12
  4647.1  680.29  4717.6  679.91    4825   677.4  4848.6  677.73  4878.9  678.81
  4888.9  678.08    4911  678.05  4979.6  676.01    4987  673.74  4993.5  672.49
  4995.2  671.99  5004.3  671.99  5006.1  672.49  5009.8  672.76    5030  678.55
  5040.1  679.68  5050.2  679.52  5060.2  679.92    5068  681.52  5073.1  684.25
  5080.4  684.54  5110.6  684.08  5140.8   684.8  5171.1  684.93  5227.7  686.73
#Mann= 3 ,-1 , 0
  4318.4     .05       0  4993.5    .033       0  5006.1     .05       0
Bank Sta=4993.5,5006.1
XS Rating Curve= 0 ,0
Exp/Cntr=0.3,0.1

Type RM Length L Ch R = 1 ,14082   ,273,273,273
BEGIN DESCRIPTION:
Mapping XS 76b1435f
END DESCRIPTION:
XS GIS Cut Line= 2
      2332905.24      7102700.38      2331963.77      7102707.89
#Sta/Elev= 30
  4323.8  682.57    4390  681.26    4430  681.04    4450  680.37    4580  678.23
    4640  678.26  4670.1  677.64  4710.1  677.46  4730.1  677.65  4810.1  676.33
  4860.1  676.36  4880.1  676.75  4898.9  677.83  4903.9  677.73  4920.1  676.31
  4930.1  676.92  4950.1  676.32  4960.1  674.82  4993.8   672.4  4995.5   671.9
  5004.6   671.9  5006.4   672.4  5010.1  674.59  5020.1  674.86  5030.1  675.96
  5050.1  680.01  5070.1  681.49  5190.1  685.67  5240.1  686.75  5265.3  687.86
#Mann= 3 ,-1 , 0
  4323.8     .05       0  4993.8     .04       0  5006.4     .05       0
Bank Sta=4993.8,5006.4
XS Rating Curve= 0 ,0
Exp/Cntr=0.3,0.1

Type RM Length L Ch R = 1 ,13809   ,144,144,144
BEGIN DESCRIPTION:
Mapping XS bed8978a
END DESCRIPTION:
XS GIS Cut Line= 3
      2332929.95      7102446.12      2332515.01      7102431.04
       2332029.5      7102474.89
#Sta/Elev= 30
  4358.3     681  4449.3   679.8  4469.3  679.89  4489.3  679.48  4499.3  678.78
  4519.4   678.2  4549.4  678.73  4659.4  677.28  4869.9  675.33    4880  675.29
    4900  675.84  4920.1  675.81  4926.9  675.18    4932  675.45  4940.2  674.42
  4950.2  674.93  4980.4  674.24  4990.4   674.7  4994.1  672.48  4995.9  671.98
    5005  671.98  5006.8  672.48  5020.5  672.58  5030.6  674.24  5037.8  676.36
  5042.8  675.44  5060.7  681.12  5070.7  682.41  5110.9  683.89    5261  687.16
#Mann= 3 ,-1 , 0
  4358.3     .05       0  4994.1    .033       0  5006.8     .05       0
Bank Sta=4994.1,5006.8
XS Rating Curve= 0 ,0
Exp/Cntr=0.3,0.1