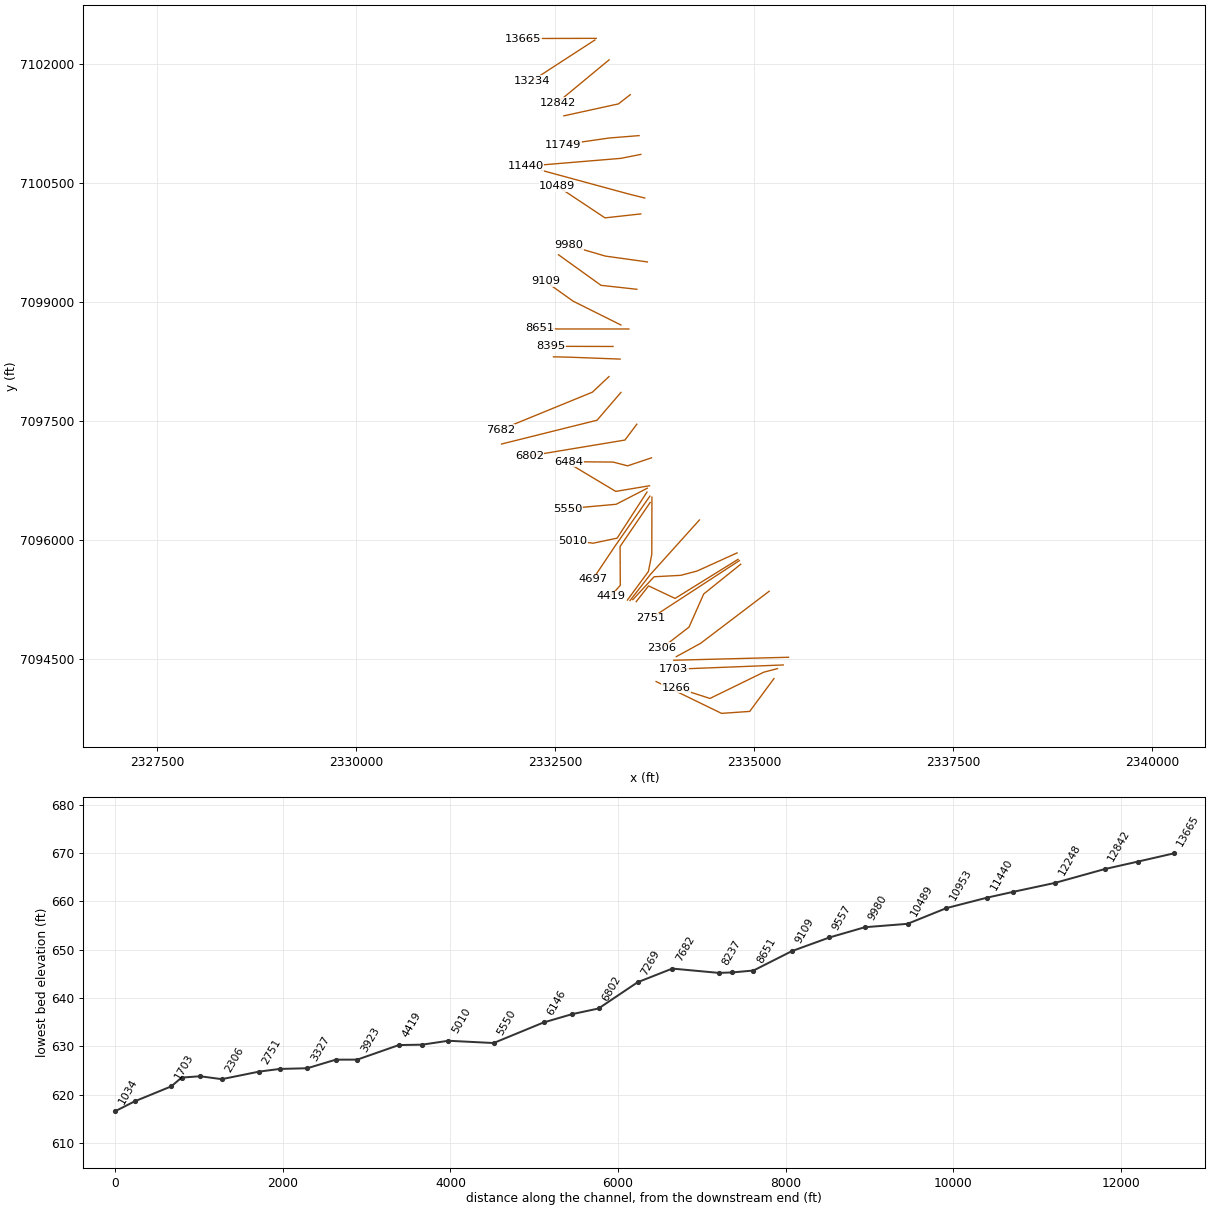
HEC-RAS study Denton Creek Tributary 17.prj: Denton Creek Tributary 17 Base Level Engineering

--- Denton Creek Tributary 17.g01 (geometry) --- (continued)

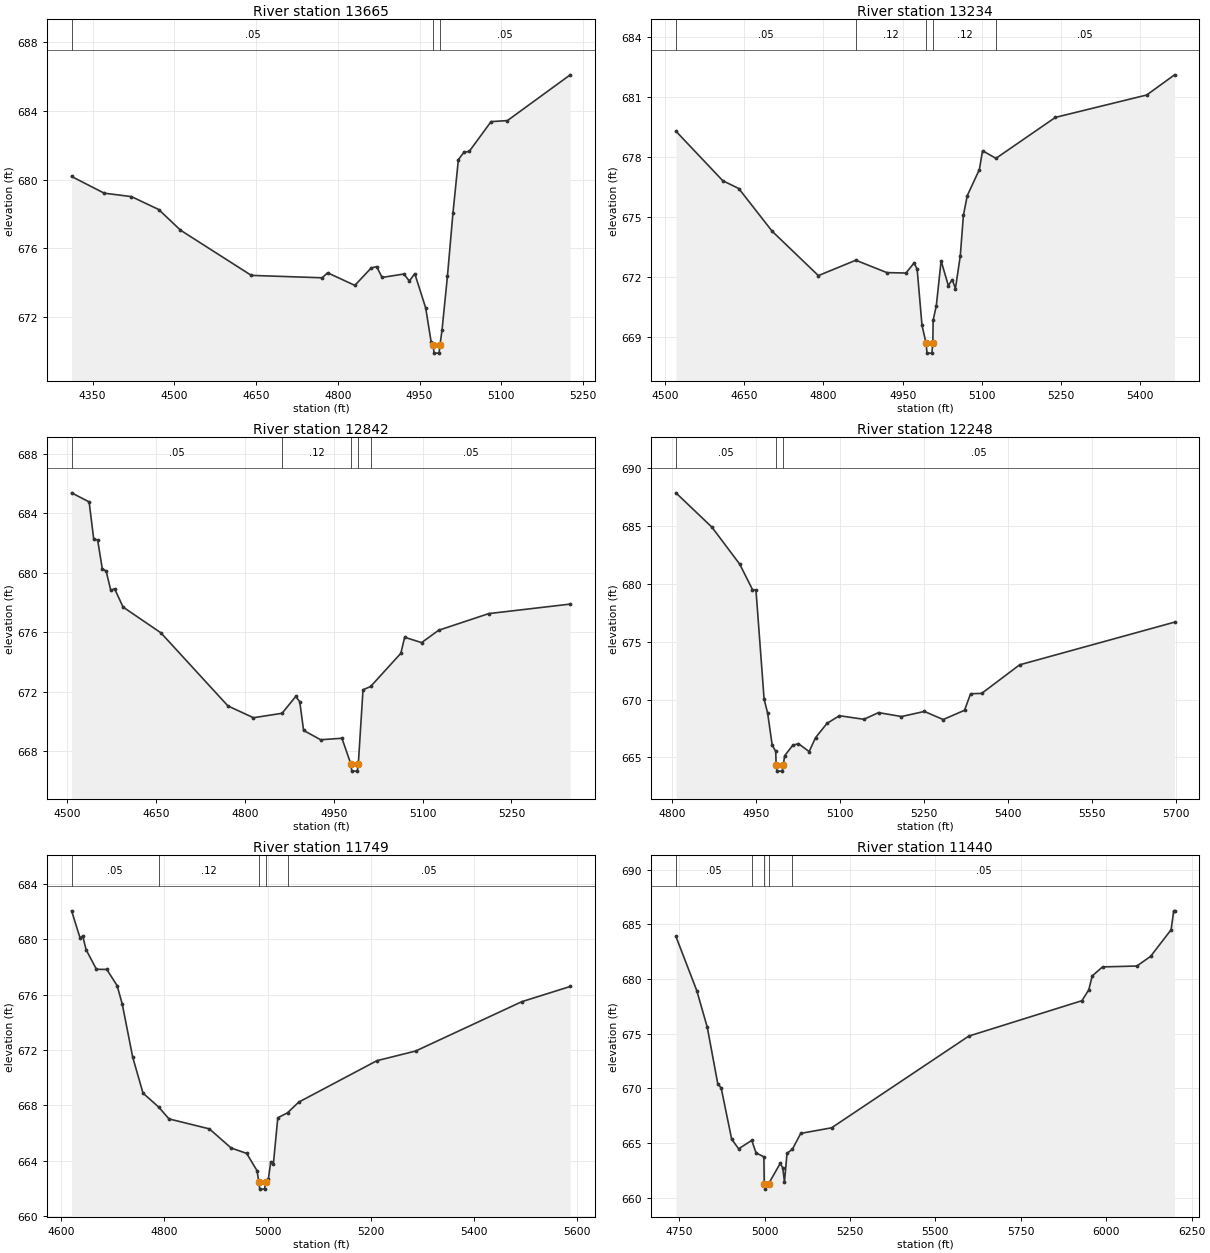
Type RM Length L Ch R = 1 ,13665   ,431,431,431
BEGIN DESCRIPTION:
Mapping XS ead3d30f
END DESCRIPTION:
XS GIS Cut Line= 2
      2333018.76      7102322.46      2332103.66      7102319.89
#Sta/Elev= 30
  4311.4  680.18  4371.2  679.21  4421.2  679.01  4471.2  678.26  4511.2  677.06
  4641.2  674.43  4771.2  674.29  4781.2  674.58  4831.2  673.85  4861.2  674.86
  4871.2  674.94  4881.2  674.31  4921.2  674.51  4931.2   674.1  4941.2  674.53
  4961.2  672.54  4971.2  670.57  4974.8  670.41  4976.6  669.91  4985.8  669.91
  4987.6  670.41  4991.2  671.25  5001.2   674.4  5011.2  678.03  5021.2  681.16
  5031.2  681.58  5041.2  681.64  5081.2  683.37  5111.2  683.43  5226.5  686.09
#Mann= 3 ,-1 , 0
  4311.4     .05       0  4974.8    .033       0  4987.6     .05       0
Bank Sta=4974.8,4987.6
XS Rating Curve= 0 ,0
Exp/Cntr=0.3,0.1

Type RM Length L Ch R = 1 ,13234   ,392,392,392
BEGIN DESCRIPTION:
Mapping XS ae6091e8
END DESCRIPTION:
XS GIS Cut Line= 2
      2333001.49      7102301.46      2332209.89      7101786.07
#Sta/Elev= 30
  4520.5  679.31  4609.3  676.83  4639.6  676.44  4702.9   674.3  4790.4  672.08
  4861.3  672.85  4920.2  672.23  4956.4  672.21  4971.6  672.71  4977.5  672.41
  4986.7  669.59  4994.4   668.7  4996.2   668.2  5005.4   668.2  5007.2   668.7
  5007.8  669.85  5013.8  670.57  5022.9  672.82  5036.6  671.58    5044  671.88
    5050  671.43  5059.2  673.06  5065.1  675.09  5072.4  676.08  5095.4  677.39
  5101.4  678.33  5126.8  677.95  5239.4     680  5412.3  681.12  5465.1  682.13
#Mann= 5 ,-1 , 0
  4520.5     .05       0  4861.3     .12       0  4994.4     .07       0
  5007.2     .12       0  5126.8     .05       0
Bank Sta=4994.4,5007.2
XS Rating Curve= 0 ,0
Exp/Cntr=0.3,0.1

Type RM Length L Ch R = 1 ,12842   ,594,594,594
BEGIN DESCRIPTION:
Mapping XS 0174b8bf
END DESCRIPTION:
XS GIS Cut Line= 2
      2333180.09      7102051.17      2332532.49      7101513.52
#Sta/Elev= 30
  4507.6  685.38  4537.2  684.77    4545  682.25  4551.5  682.22  4559.4  680.28
  4565.9  680.12  4573.7  678.83  4580.2  678.93  4594.5   677.7  4658.3  675.97
  4771.6  671.05  4814.6  670.26  4862.9  670.56  4885.9  671.69  4892.7  671.34
  4899.2  669.41  4927.9  668.78  4963.9  668.88  4978.8  667.17  4980.6  666.67
  4989.8  666.67  4991.6  667.17  4999.5  672.14  5012.4  672.36  5063.3  674.59
  5069.8  675.67  5098.4  675.31  5127.1  676.14  5211.7  677.26  5349.3   677.9
#Mann= 5 ,-1 , 0
  4507.6     .05       0  4862.9     .12       0  4978.8     .07       0
  4991.6     .12       0  5012.4     .05       0
Bank Sta=4978.8,4991.6
XS Rating Curve= 0 ,0
Exp/Cntr=0.3,0.1

Type RM Length L Ch R = 1 ,12248   ,499,499,499
BEGIN DESCRIPTION:
Mapping XS b5ef8ac2
END DESCRIPTION:
XS GIS Cut Line= 3
      2333447.22      7101612.63      2333297.43      7101496.23
      2332612.42      7101345.94
#Sta/Elev= 30
  4806.9  687.87  4871.3   684.9    4921   681.7  4943.7  679.51    4950  679.45
  4964.5  670.04  4970.8  668.83    4979  666.05  4985.3  665.52    4986  664.31
  4987.8  663.81    4997  663.81  4998.8  664.31  5001.2  665.14  5015.5  666.03
  5025.7  666.19    5045   665.5  5056.4   666.7  5076.9  667.94  5099.1   668.6
  5142.9  668.29    5169  668.87    5210  668.53  5250.9  668.97  5284.5  668.27
  5322.6  669.07  5333.5   670.5  5353.3  670.53  5421.1     673  5697.9  676.69
#Mann= 3 ,-1 , 0
  4806.9     .05       0    4986    .033       0  4998.8     .05       0
Bank Sta=4986,4998.8
XS Rating Curve= 0 ,0
Exp/Cntr=0.3,0.1

Type RM Length L Ch R = 1 ,11749   ,309,309,309
BEGIN DESCRIPTION:
Mapping XS f6f9fdaf
END DESCRIPTION:
XS GIS Cut Line= 3
       2333556.9       7101096.6      2333180.31      7101066.35
      2332598.62      7100981.84
#Sta/Elev= 30
  4620.5  682.05    4637  680.08    4642  680.24  4648.5  679.25  4668.6  677.83
  4688.6  677.82  4708.7  676.65  4718.7   675.3  4738.8  671.49  4758.8  668.89
  4789.6  667.87    4809  667.03  4887.3  666.31  4929.4  664.93  4959.5  664.54
  4979.6  663.29  4983.1  662.46  4984.9  661.96  4994.2  661.96    4996  662.46
  5001.5  662.68  5006.2  663.94  5011.2  663.77  5019.8  667.11  5038.6  667.47
  5060.3  668.24  5211.6  671.23  5286.8  671.93  5492.2  675.49  5586.1  676.59
#Mann= 5 ,-1 , 0
  4620.5     .05       0  4789.6     .12       0  4983.1     .07       0
    4996     .12       0  5038.6     .05       0
Bank Sta=4983.1,4996
XS Rating Curve= 0 ,0
Exp/Cntr=0.3,0.1

Type RM Length L Ch R = 1 ,11440   ,487,487,487
BEGIN DESCRIPTION:
Denton Creek Tributary 17 15.0
END DESCRIPTION:
XS GIS Cut Line= 3
      2333578.99        7100860.        2333329.        7100810.
        2332129.        7100710.
#Sta/Elev= 30
  4740.7  683.89  4801.9  678.92  4832.5  675.58  4863.1  670.43  4873.3  670.01
  4903.9  665.34  4924.3  664.46  4962.6  665.23  4975.2  664.09  4998.1  663.72
  4999.2  661.27    5001  660.77  5012.1  661.27  5045.8  663.12  5053.3  662.73
  5058.4  661.43  5065.9  664.06  5081.2   664.4    5106  665.87  5196.3  666.38
  5597.7  674.77  5928.9  678.01  5948.9  679.01    5959  680.28  5989.1   681.1
  6089.4  681.18  6129.6  682.06  6189.8   684.5  6197.3  686.23  6199.8  686.23
#Mann= 5 ,-1 , 0
  4740.7     .05       0  4962.6     .12       0  4999.2     .07       0
  5012.1     .12       0  5081.2     .05       0
Bank Sta=4999.2,5012.1
XS Rating Curve= 0 ,0
Exp/Cntr=0.3,0.1

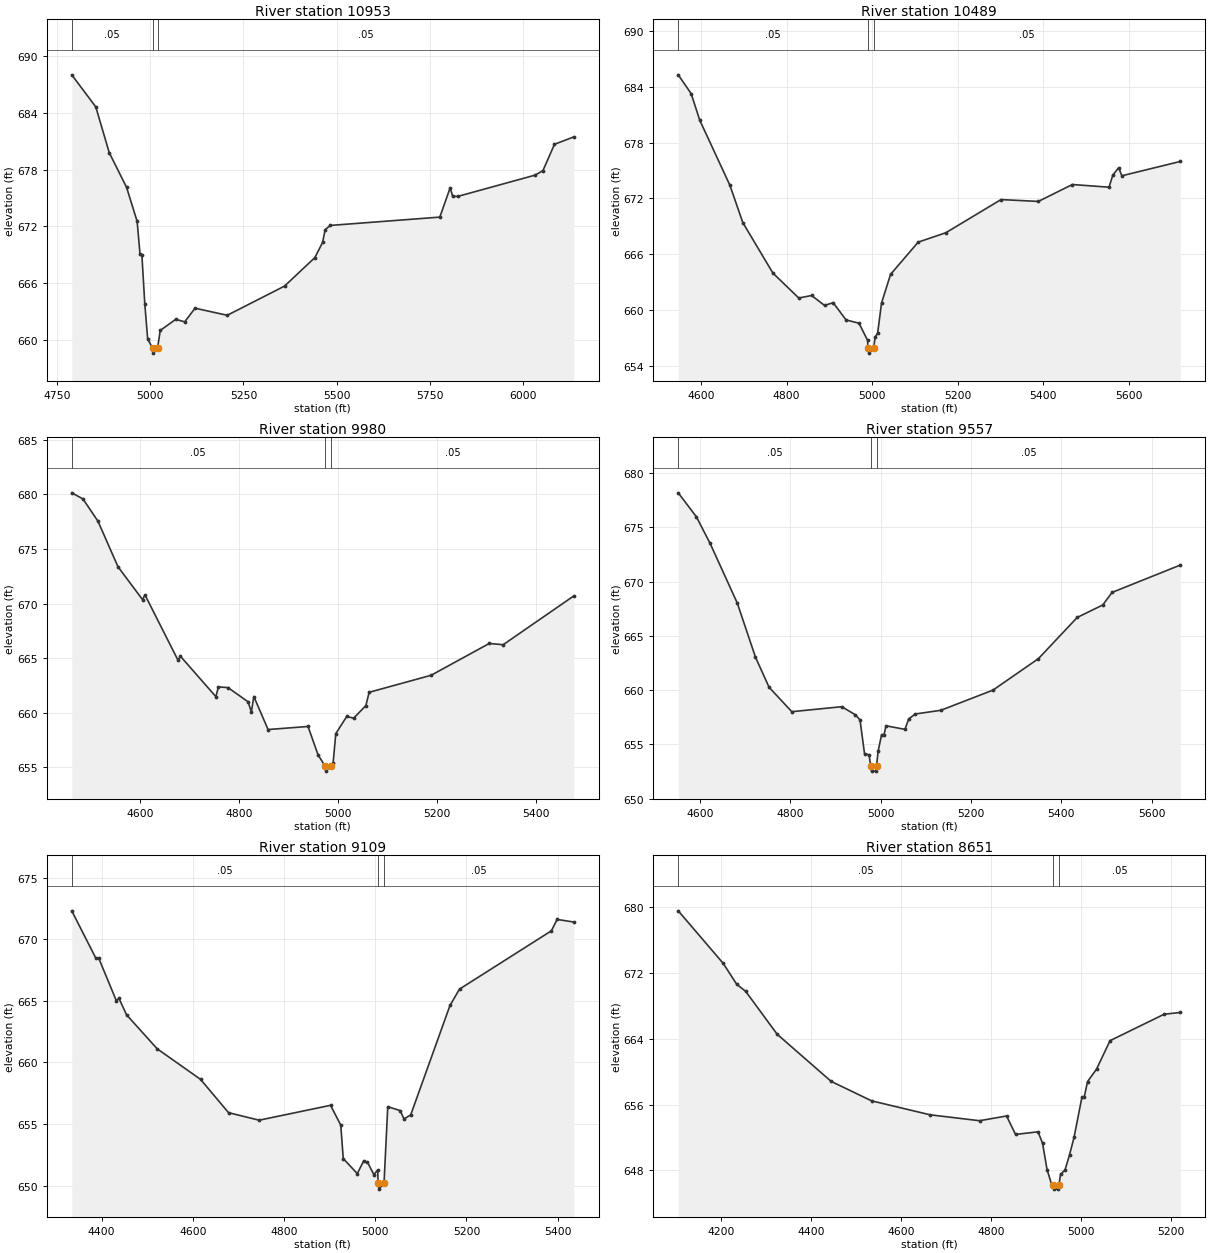
Type RM Length L Ch R = 1 ,10953   ,464,464,464
BEGIN DESCRIPTION:
Denton Creek Tributary 17 14.0
END DESCRIPTION:
XS GIS Cut Line= 3
      2333629.02      7100309.99        2333429.        7100360.
      2332328.95      7100660.01
#Sta/Elev= 30
  4789.7  688.02  4854.1  684.63  4890.2  679.79  4936.6  676.13    4965  672.53
  4972.7  669.08  4977.8  668.93  4985.6  663.76  4993.3  660.09  5006.7   659.1
  5008.5   658.6  5019.6   659.1    5027     661  5068.4  662.17  5092.6  661.91
  5120.3  663.35  5206.6   662.6  5360.4  665.69  5441.6   668.7  5462.3   670.3
  5469.2  671.65    5483   672.1  5776.7  672.98  5804.4  676.08  5811.3  675.17
  5825.1  675.17  6032.4  677.42  6053.1  677.89  6084.2  680.68  6136.1  681.46
#Mann= 3 ,-1 , 0
  4789.7     .05       0  5006.7    .033       0  5019.6     .05       0
Bank Sta=5006.7,5019.6
XS Rating Curve= 0 ,0
Exp/Cntr=0.3,0.1

Type RM Length L Ch R = 1 ,10489   ,509,509,509
BEGIN DESCRIPTION:
Denton Creek Tributary 17 13.0
END DESCRIPTION:
XS GIS Cut Line= 3
      2333579.03        7100110.        2333129.        7100060.
      2332529.01        7100460.
#Sta/Elev= 30
  4546.7  685.29  4576.9  683.27    4597  680.41  4667.5  673.41  4697.7  669.39
  4768.1  663.96  4828.5  661.28  4858.6  661.55  4888.8  660.48  4908.9  660.78
  4939.1  658.92  4969.3  658.57  4989.4  656.73  4990.5  655.85  4992.3  655.35
  5003.5  655.85    5007  657.06    5013  657.52    5022  660.73  5043.1  663.82
  5107.7  667.29  5172.3   668.3  5301.5  671.87  5388.6  671.67  5468.2  673.49
  5553.9   673.2  5562.9  674.51  5576.4  675.29  5583.9  674.43  5720.6  675.97
#Mann= 3 ,-1 , 0
  4546.7     .05       0  4990.5    .033       0  5003.5     .05       0
Bank Sta=4990.5,5003.5
XS Rating Curve= 0 ,0
Exp/Cntr=0.3,0.1

Type RM Length L Ch R = 1 ,9980    ,423,423,423
BEGIN DESCRIPTION:
Denton Creek Tributary 17 12.0
END DESCRIPTION:
XS GIS Cut Line= 3
      2333661.37      7099504.71      2333133.22      7099578.36
      2332672.62      7099713.93
#Sta/Elev= 30
  4462.3  680.14  4484.9  679.58  4515.2  677.54  4555.6  673.37  4605.1  670.36
  4610.1  670.79  4676.6  664.82  4681.7  665.17  4753.2  661.47  4758.3  662.37
  4777.7   662.3  4818.1     661  4824.8  660.08  4829.8  661.48  4858.5  658.46
  4939.2  658.74  4959.4  656.14  4973.1  655.15    4975  654.65  4986.1  655.15
  4989.7  655.35  4995.2  658.08  5017.3  659.66  5031.2   659.5  5055.9  660.65
  5062.5  661.87  5187.6  663.43  5304.9  666.34  5333.1  666.23  5475.7   670.7
#Mann= 3 ,-1 , 0
  4462.3     .05       0  4973.1    .033       0  4986.1     .05       0
Bank Sta=4973.1,4986.1
XS Rating Curve= 0 ,0
Exp/Cntr=0.3,0.1

Type RM Length L Ch R = 1 ,9557    ,448,448,448
BEGIN DESCRIPTION:
Denton Creek Tributary 17 11.0
END DESCRIPTION:
XS GIS Cut Line= 3
        2333529.        7099160.        2333079.        7099210.
      2332544.31      7099595.27
#Sta/Elev= 30
  4551.8  678.19    4592  675.98  4622.2  673.54  4682.6  668.02  4722.8  663.04
    4753  660.26  4803.3  658.01    4914  658.47  4944.2  657.72  4954.3  657.26
  4964.3  654.15  4974.4  654.03  4977.9  653.03  4979.8  652.53  4989.1  652.53
  4990.9  653.03  4994.5  654.38  5002.1  655.89  5007.6  655.89  5011.9  656.71
  5053.9  656.38  5062.2  657.35  5076.9   657.8  5133.4  658.14  5248.8     660
  5349.4   662.9  5435.3   666.7  5491.8  667.85  5512.6  669.01  5663.6  671.53
#Mann= 3 ,-1 , 0
  4551.8     .05       0  4977.9    .033       0  4990.9     .05       0
Bank Sta=4977.9,4990.9
XS Rating Curve= 0 ,0
Exp/Cntr=0.3,0.1

Type RM Length L Ch R = 1 ,9109    ,458,458,458
BEGIN DESCRIPTION:
Denton Creek Tributary 17 10.0
END DESCRIPTION:
XS GIS Cut Line= 3
      2333328.99        7098710.        2332729.        7099010.
      2332379.02      7099259.99
#Sta/Elev= 30
  4334.6  672.32  4387.7  668.45  4393.3  668.51  4432.4  665.01    4438  665.21
  4454.8  663.87  4521.9  661.11  4616.9  658.63  4678.4  655.92  4745.5  655.31
    4902  656.52  4924.4  654.91  4929.9  652.19  4960.7  650.97  4974.7  652.01
    4983   651.9    4997  650.89  5005.4  651.26  5006.3  650.21  5008.1  649.71
  5019.3  650.21  5027.5  656.41  5054.6  656.09  5063.2  655.41  5077.9  655.75
  5163.9  664.63  5184.8  665.96  5386.4   670.7  5398.7  671.62  5435.5  671.41
#Mann= 3 ,-1 , 0
  4334.6     .05       0  5006.3     .04       0  5019.3     .05       0
Bank Sta=5006.3,5019.3
XS Rating Curve= 0 ,0
Exp/Cntr=0.3,0.1

Type RM Length L Ch R = 1 ,8651    ,256,256,256
BEGIN DESCRIPTION:
Denton Creek Tributary 17 9.0
END DESCRIPTION:
XS GIS Cut Line= 3
      2333428.97        7098660.        2332529.        7098660.
      2332313.19      7098674.95
#Sta/Elev= 30
  4104.3  679.59  4204.3  673.19  4234.3  670.65  4254.3  669.78  4324.3  664.56
  4444.3  658.82  4534.3  656.45  4664.3  654.75  4774.3  654.03  4834.3  654.61
  4854.3  652.36  4904.3  652.68  4914.3  651.29  4924.3  648.09  4934.3   646.3
  4937.8   646.2  4939.6   645.7    4949   645.7  4950.8   646.2  4954.3  647.49
  4964.3  648.04  4974.3  649.88  4984.3  651.99  5001.8  656.87  5006.8  656.87
  5014.3  658.79  5034.3  660.31  5064.4  663.78  5184.7     667  5220.6  667.21
#Mann= 3 ,-1 , 0
  4104.3     .05       0  4937.8    .033       0  4950.8     .05       0
Bank Sta=4937.8,4950.8
XS Rating Curve= 0 ,0
Exp/Cntr=0.3,0.1

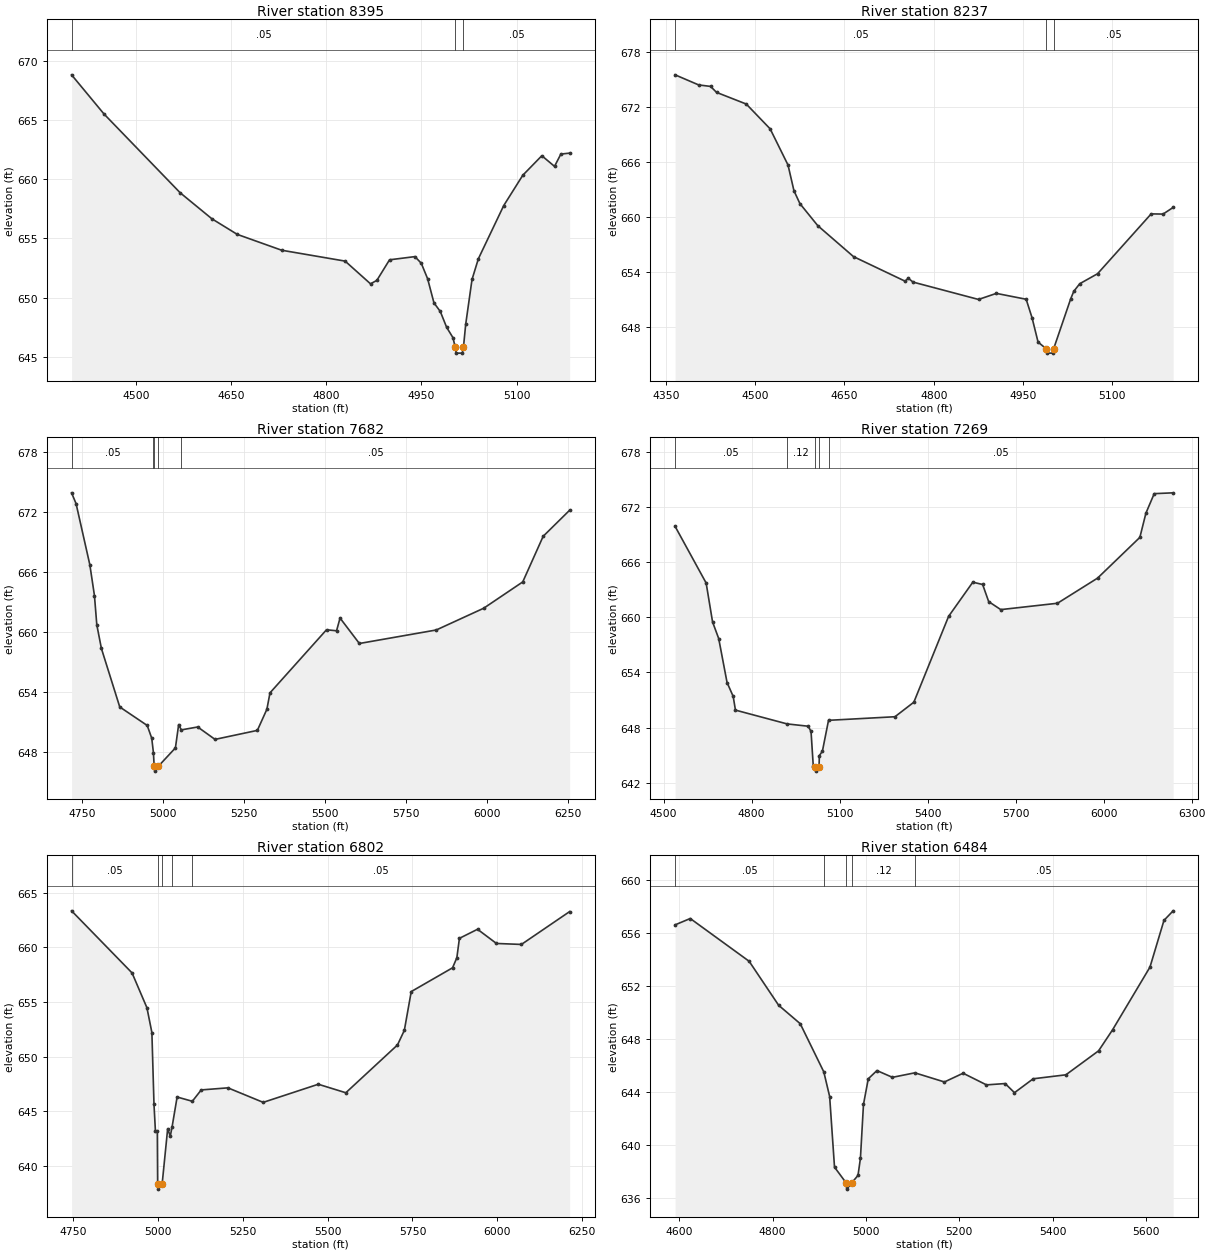
Type RM Length L Ch R = 1 ,8395    ,158,158,158
BEGIN DESCRIPTION:
Mapping XS 946ad61d
END DESCRIPTION:
XS GIS Cut Line= 2
      2333230.13      7098439.35      2332445.24      7098441.28
#Sta/Elev= 30
  4398.7  668.83  4449.8  665.52  4569.8  658.86  4619.8  656.66  4659.8  655.34
  4729.8     654  4829.8  653.08  4869.8  651.16  4879.8  651.45  4899.8  653.19
  4939.8  653.46  4949.8   652.9  4959.8  651.59  4969.8  649.55  4979.8  648.82
  4989.8  647.48  4999.8   646.6  5003.3   645.8  5005.1   645.3  5014.5   645.3
  5016.3   645.8  5019.8  647.73  5029.8  651.53  5039.8  653.28  5079.8  657.78
  5109.8  660.34  5139.8  661.99  5159.8  661.09  5169.8  662.13  5183.6  662.21
#Mann= 3 ,-1 , 0
  4398.7     .05       0  5003.3     .04       0  5016.3     .05       0
Bank Sta=5003.3,5016.3
XS Rating Curve= 0 ,0
Exp/Cntr=0.3,0.1

Type RM Length L Ch R = 1 ,8237    ,555,555,555
BEGIN DESCRIPTION:
Denton Creek Tributary 17 8.0
END DESCRIPTION:
XS GIS Cut Line= 3
      2333318.66      7098280.26       2332684.6      7098304.32
      2332482.06       7098308.9
#Sta/Elev= 30
  4365.3  675.49    4405  674.39    4425  674.23    4435  673.58    4485  672.31
  4525.1  669.61  4555.1  665.68  4565.1  662.88  4575.1  661.48  4605.1  659.08
  4665.2  655.71  4752.1  653.03  4757.1  653.37  4765.2  652.94  4875.3  651.05
  4905.3  651.71  4955.4  651.07  4965.4  649.03  4975.4  646.41  4988.6  645.71
  4990.4  645.21  4999.8  645.21  5001.7  645.71  5030.2  651.11  5035.4  651.93
  5045.4  652.76  5075.4  653.85  5165.5  660.36  5185.5  660.34  5202.4  661.06
#Mann= 3 ,-1 , 0
  4365.3     .05       0  4988.6     .04       0  5001.7     .05       0
Bank Sta=4988.6,5001.7
XS Rating Curve= 0 ,0
Exp/Cntr=0.3,0.1

Type RM Length L Ch R = 1 ,7682    ,413,413,413
BEGIN DESCRIPTION:
Denton Creek Tributary 17 7.0
END DESCRIPTION:
XS GIS Cut Line= 3
        2333179.        7098060.      2332969.96      7097863.23
      2331813.52      7097388.69
#Sta/Elev= 30
  4717.3   673.9  4731.2  672.82  4773.7  666.71  4787.9  663.64  4795.2  660.71
  4809.4  658.35    4866  652.51  4950.8  650.66  4964.7  649.39  4969.9  647.95
  4972.2   646.6  4974.1   646.1  4985.5   646.6  5037.8  648.42  5047.8  650.75
  5055.9  650.22  5106.6  650.51    5160  649.27  5290.7  650.17  5320.1  652.28
  5329.7  653.92  5504.1  660.22  5535.1  660.12  5545.9  661.39  5605.5  658.85
  5842.9   660.2  5989.1  662.37  6109.7     665  6172.8  669.56  6254.4  672.16
#Mann= 5 ,-1 , 0
  4717.3     .05       0  4969.9     .12       0  4972.2     .07       0
  4985.5     .12       0  5055.9     .05       0
Bank Sta=4972.2,4985.5
XS Rating Curve= 0 ,0
Exp/Cntr=0.3,0.1

Type RM Length L Ch R = 1 ,7269    ,467,467,467
BEGIN DESCRIPTION:
Denton Creek Tributary 17 6.0
END DESCRIPTION:
XS GIS Cut Line= 3
      2333328.98      7097859.97        2333029.        7097510.
      2331828.97      7097209.99
#Sta/Elev= 30
    4539  669.88  4644.9  663.72  4666.8  659.49  4687.7  657.69  4716.2  652.91
  4737.1   651.4  4744.8  649.91  4920.9  648.41  4992.8  648.16  5002.5  647.59
  5010.2  643.79  5016.5  643.78  5018.4  643.28  5029.8  643.78  5030.9  644.97
  5041.2  645.44  5062.1   648.8  5288.6  649.19    5353  650.77  5471.5   660.1
    5554  663.81  5587.5  663.56  5608.1   661.7  5649.3  660.83  5842.6  661.52
  5979.2  664.25  6123.5  668.68  6144.1  671.31  6172.4  673.43  6236.9  673.52
#Mann= 5 ,-1 , 0
    4539     .05       0  4920.9     .12       0  5016.5     .07       0
  5029.8     .12       0  5062.1     .05       0
Bank Sta=5016.5,5029.8
XS Rating Curve= 0 ,0
Exp/Cntr=0.3,0.1

Type RM Length L Ch R = 1 ,6802    ,318,318,318
BEGIN DESCRIPTION:
Denton Creek Tributary 17 5.0
END DESCRIPTION:
XS GIS Cut Line= 3
        2333529.        7097460.        2333379.        7097260.
      2332178.96      7097059.99
#Sta/Elev= 30
  4746.2  663.35  4924.3  657.66  4968.1  654.47  4982.7   652.2  4988.9  645.62
  4993.1  643.17  4998.7  643.17  4999.7  638.35  5001.5  637.85    5013  638.35
  5029.2  643.39  5036.8  642.69  5042.3  643.57    5057  646.29  5101.8   645.9
    5128  646.94  5206.6  647.13  5310.5   645.8  5472.7  647.46  5553.8  646.68
  5705.9  651.06  5726.1   652.4  5746.4  655.95  5868.1  658.13  5880.7  659.05
  5888.3  660.83  5941.6  661.66  5997.3  660.36  6070.8  660.27  6212.8  663.28
#Mann= 5 ,-1 , 0
  4746.2     .05       0  4999.7    .033       0    5013     .05       0
  5042.3     .12       0  5101.8     .05       0
Bank Sta=4999.7,5013
XS Rating Curve= 0 ,0
Exp/Cntr=0.3,0.1

Type RM Length L Ch R = 1 ,6484    ,338,338,338
BEGIN DESCRIPTION:
Mapping XS 650e733a
END DESCRIPTION:
XS GIS Cut Line= 4
      2333712.99      7097035.94      2333412.79      7096935.13
      2333230.27      7096982.73      2332669.39      7096987.19
#Sta/Elev= 30
  4591.4  656.62  4623.9   657.1    4750  653.87  4813.1  650.55  4859.3  649.16
  4909.8  645.52  4922.3  643.66  4932.7  638.33    4957  637.17  4958.9  636.67
  4970.3  637.17    4983  637.71  4988.2     639  4994.7  643.06    5005     645
  5023.5  645.62  5056.7  645.11  5104.7  645.45    5168  644.76    5208  645.42
    5258  644.54    5298  644.64    5318  643.95    5358     645    5428   645.3
    5498  647.11    5528   648.7    5608  653.43    5638  656.96  5657.6  657.68
#Mann= 5 ,-1 , 0
  4591.4     .05       0  4909.8     .12       0    4957     .07       0
  4970.3     .12       0  5104.7     .05       0
Bank Sta=4957,4970.3
XS Rating Curve= 0 ,0
Exp/Cntr=0.3,0.1

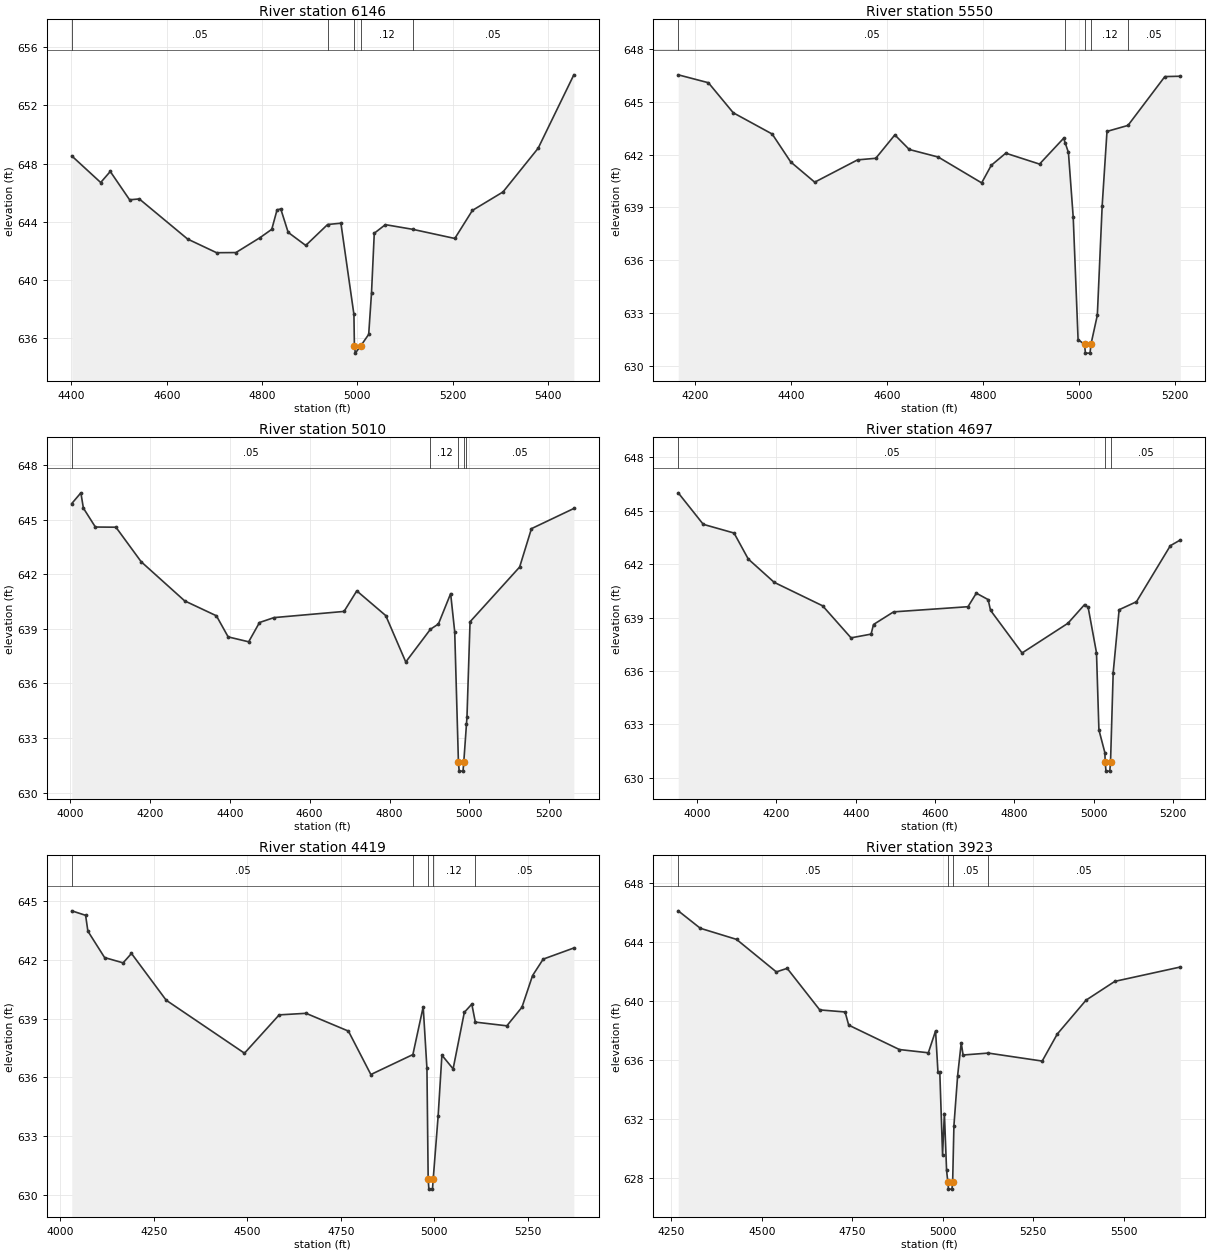
Type RM Length L Ch R = 1 ,6146    ,596,596,596
BEGIN DESCRIPTION:
Mapping XS 11362773
END DESCRIPTION:
XS GIS Cut Line= 3
      2333688.72      7096684.22       2333263.6      7096612.99
      2332730.05      7096933.76
#Sta/Elev= 30
  4400.7  648.53  4461.4   646.7  4481.5  647.46  4522.1  645.51  4542.4  645.57
  4643.8  642.81  4704.6  641.87  4745.2  641.88  4795.9  642.91  4820.4  643.48
  4831.5  644.82  4839.3  644.88  4854.8  643.27  4891.7  642.37  4937.6  643.81
  4965.5   643.9  4992.8  637.62  4993.8  635.46  4995.7  634.96  5007.1  635.46
  5023.8  636.25  5029.7   639.1  5035.5  643.21  5058.8   643.8    5116  643.48
  5204.5  642.85  5241.4  644.78  5305.6  646.05  5379.4  649.06  5454.3  654.11
#Mann= 5 ,-1 , 0
  4400.7     .05       0  4937.6     .12       0  4993.8     .07       0
  5007.1     .12       0    5116     .05       0
Bank Sta=4993.8,5007.1
XS Rating Curve= 0 ,0
Exp/Cntr=0.3,0.1

Type RM Length L Ch R = 1 ,5550    ,540,540,540
BEGIN DESCRIPTION:
Mapping XS fbc4b52c
END DESCRIPTION:
XS GIS Cut Line= 3
      2333660.78      7096653.34      2333269.09      7096450.73
      2332666.94      7096396.29
#Sta/Elev= 30
  4165.2  646.55    4228   646.1  4279.8  644.39  4360.9  643.18  4399.5  641.59
  4449.4  640.44  4538.7  641.71  4576.6   641.8  4616.3  643.13  4646.4   642.3
  4706.7  641.87  4797.1   640.4  4817.1   641.4  4847.3  642.09  4917.6  641.47
  4967.8  642.94  4971.4  642.65  4977.8  642.13  4987.8  638.43  4997.9  631.48
  5011.3  631.21  5013.2  630.71  5022.8  630.71  5024.7  631.21    5038  632.87
  5048.1  639.11  5058.1  643.33  5101.8  643.67  5178.6  646.45  5210.8  646.47
#Mann= 5 ,-1 , 0
  4165.2     .05       0  4971.4     .12       0  5011.3     .07       0
  5024.7     .12       0  5101.8     .05       0
Bank Sta=5011.3,5024.7
XS Rating Curve= 0 ,0
Exp/Cntr=0.3,0.1

Type RM Length L Ch R = 1 ,5010    ,313,313,313
BEGIN DESCRIPTION:
Denton Creek Tributary 17 3.0
END DESCRIPTION:
XS GIS Cut Line= 4
      2333656.21      7096604.41      2333281.47      7096023.87
        2332979.        7095960.      2332723.63       7095992.9
#Sta/Elev= 30
  4004.1  645.89  4026.9  646.48  4033.2  645.64  4063.2   644.6  4114.7  644.59
    4178  642.69  4286.9  640.54  4366.4  639.72  4395.8  638.56  4447.2  638.29
  4474.3  639.35  4510.6  639.62  4686.1  639.96    4718  641.09  4790.6  639.73
  4840.7  637.18  4902.5  638.98  4922.5  639.27  4953.1  640.94  4963.3  638.84
  4972.6  631.68  4974.5  631.18  4984.1  631.18    4986  631.68  4992.7  633.75
    4994  634.15  5001.7  639.39  5125.9   642.4  5155.5  644.51  5261.7  645.62
#Mann= 5 ,-1 , 0
  4004.1     .05       0  4902.5     .12       0  4972.6     .04       0
    4986     .12       0  4992.7     .05       0
Bank Sta=4972.6,4986
XS Rating Curve= 0 ,0
Exp/Cntr=0.3,0.1

Type RM Length L Ch R = 1 ,4697    ,278,278,278
BEGIN DESCRIPTION:
Mapping XS 202bd041
END DESCRIPTION:
XS GIS Cut Line= 3
      2333692.79      7096552.87      2333249.66       7095915.9
      2332977.45      7095508.04
#Sta/Elev= 30
  3952.4  646.01  4015.5  644.24  4093.2  643.75    4129  642.29  4194.4  640.98
  4316.6  639.66  4388.2  637.86  4438.8  638.07  4444.9  638.61  4495.5  639.32
  4683.2  639.61  4704.2  640.37    4734  640.01    4740  639.41  4819.6  637.01
  4935.3  638.68  4977.3  639.73  4986.3  639.57  5007.3  637.02  5013.4  632.69
  5028.4  631.41  5029.3  630.87  5031.2  630.37  5040.8  630.37  5042.7  630.87
  5049.4   635.9  5064.4  639.44  5108.1  639.89  5193.6  643.04  5218.7  643.36
#Mann= 3 ,-1 , 0
  3952.4     .05       0  5029.3     .04       0  5042.7     .05       0
Bank Sta=5029.3,5042.7
XS Rating Curve= 0 ,0
Exp/Cntr=0.3,0.1

Type RM Length L Ch R = 1 ,4419    ,496,496,496
BEGIN DESCRIPTION:
Mapping XS d2e64304
END DESCRIPTION:
XS GIS Cut Line= 4
      2333696.28      7096473.47      2333318.51      7095919.06
      2333321.07      7095429.11      2333199.34      7095293.86
#Sta/Elev= 30
  4030.6  644.52  4067.6  644.29  4073.7  643.48  4118.4  642.13  4167.9  641.86
  4190.3  642.34  4283.1  639.95  4492.5  637.24  4585.3   639.2  4657.1  639.28
  4770.5  638.37  4830.5  636.15  4942.9  637.17  4970.5  639.61  4980.5  636.46
  4983.8  630.79  4985.7  630.29  4995.3  630.29  4997.2  630.79  5010.5  634.04
  5020.5  637.14  5050.5  636.44  5080.5  639.33  5100.5  639.75  5109.9  638.83
  5194.2  638.64  5234.6  639.59    5263  641.21  5291.4  642.05  5373.4  642.62
#Mann= 5 ,-1 , 0
  4030.6     .05       0  4942.9     .12       0  4983.8     .07       0
  4997.2     .12       0  5109.9     .05       0
Bank Sta=4983.8,4997.2
XS Rating Curve= 0 ,0
Exp/Cntr=0.3,0.1

Type RM Length L Ch R = 1 ,3923    ,257,257,257
BEGIN DESCRIPTION:
Mapping XS 94b4aa0d
END DESCRIPTION:
XS GIS Cut Line= 4
      2333718.63      7096540.95      2333716.93      7095821.65
      2333674.58      7095604.43      2333410.78      7095244.08
#Sta/Elev= 30
  4268.9   646.1  4329.9  644.92  4429.9  644.17  4539.9  641.97  4569.9  642.21
  4659.9   639.4  4729.9  639.26  4739.9  638.37  4879.9  636.72  4959.9   636.5
  4979.9  637.98  4986.5  635.18  4991.6  635.18  4999.2  629.61  5004.3  632.39
  5010.3  628.55  5013.7  627.78  5015.6  627.28  5025.2  627.28  5027.1  627.78
  5030.6  631.57  5040.8  634.94  5050.8  637.17  5055.9  636.35  5125.5  636.48
  5274.5  635.94  5316.2  637.77  5395.7  640.06  5475.2  641.33  5656.1   642.3
#Mann= 4 ,-1 , 0
  4268.9     .05       0  5013.7    .033       0  5027.1     .05       0
  5125.5     .05       0
Bank Sta=5013.7,5027.1
XS Rating Curve= 0 ,0
Exp/Cntr=0.3,0.1

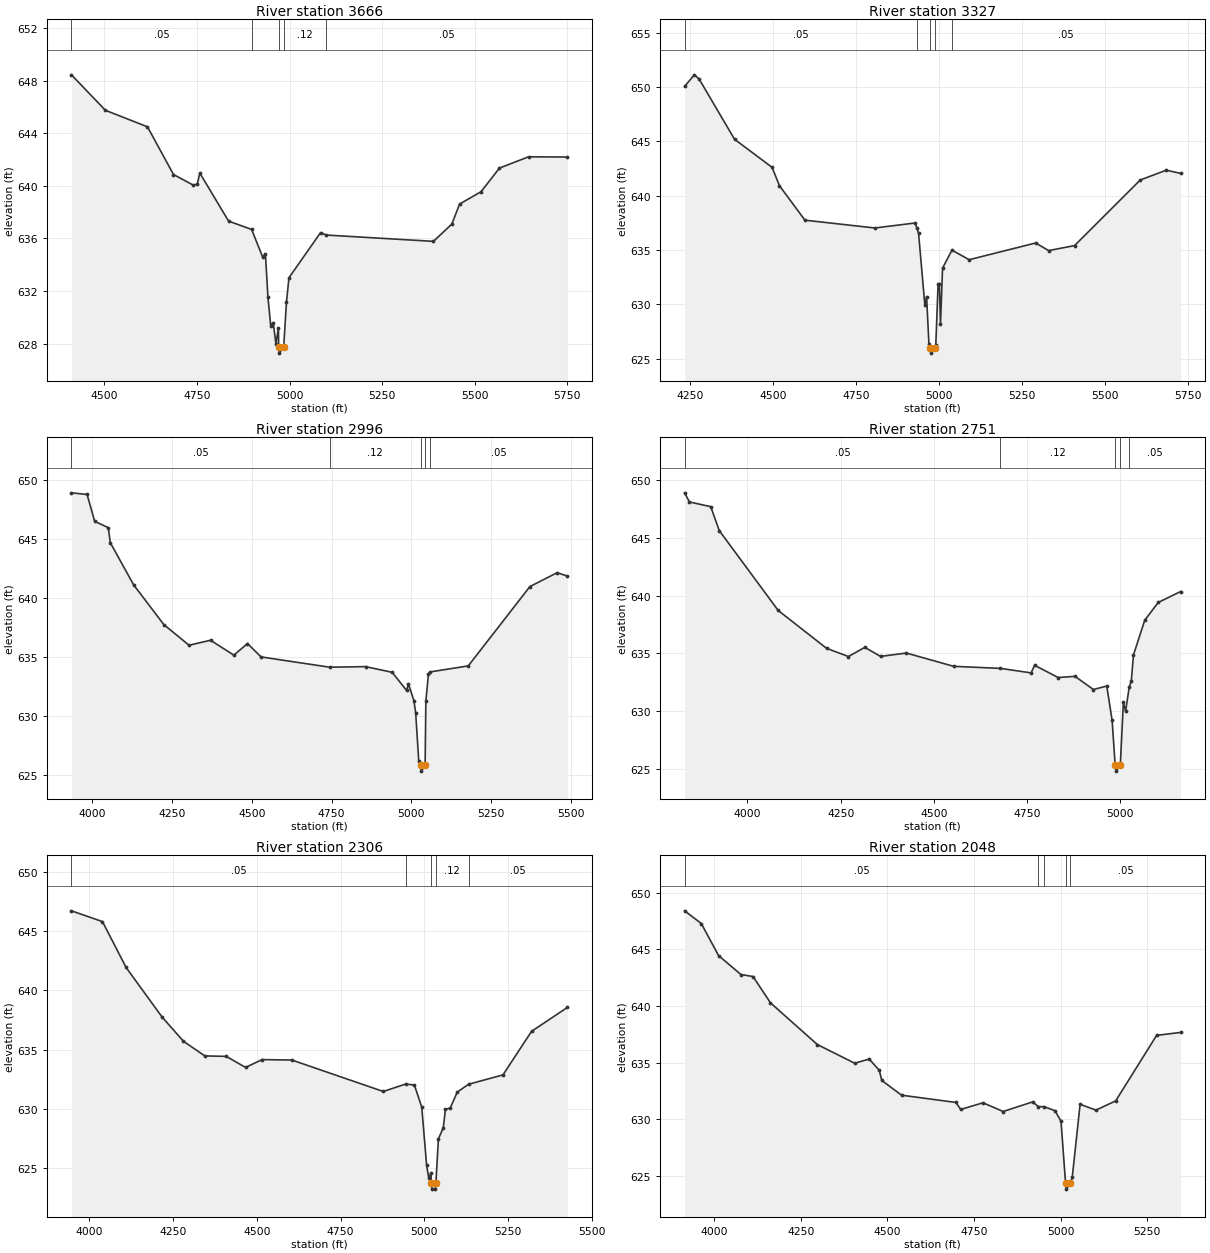
Type RM Length L Ch R = 1 ,3666    ,339,339,339
BEGIN DESCRIPTION:
Mapping XS e7e325fb
END DESCRIPTION:
XS GIS Cut Line= 4
      2334315.29       7096253.1      2334097.22      7096009.94
      2333698.07      7095564.86      2333443.13      7095237.74
#Sta/Elev= 30
    4411  648.46  4502.6  645.76  4616.3   644.5  4686.5  640.87    4740  640.06
  4750.8  640.14  4757.6  640.98  4835.3  637.32  4897.4  636.69  4927.2  634.59
  4934.7  634.84  4941.4  631.58  4948.9  629.37  4955.7   629.6  4963.1  627.98
  4969.9  629.21  4970.5  627.77  4972.5  627.27  4984.1  627.77  4991.6  631.17
  4998.3  633.01  5083.5  636.44  5099.5  636.26  5388.4  635.78  5438.2   637.1
    5459  638.62  5516.9  639.56  5566.7  641.36  5645.4  642.22  5750.2   642.2
#Mann= 5 ,-1 , 0
    4411     .05       0  4897.4     .12       0  4970.5     .07       0
  4984.1     .12       0  5099.5     .05       0
Bank Sta=4970.5,4984.1
XS Rating Curve= 0 ,0
Exp/Cntr=0.3,0.1

Type RM Length L Ch R = 1 ,3327    ,331,331,331
BEGIN DESCRIPTION:
Mapping XS 2abcbd24
END DESCRIPTION:
XS GIS Cut Line= 5
      2334788.62      7095837.98      2334285.71      7095609.51
      2334080.54      7095555.23      2333746.24      7095537.38
       2333478.5      7095249.11
#Sta/Elev= 30
  4234.1  650.06  4263.3  651.12  4277.6  650.74  4384.2  645.19  4497.3   642.6
  4519.3  640.92  4596.1  637.74  4806.5  637.02  4927.9  637.48  4932.8  637.03
  4938.2  636.53  4957.1   629.9  4962.3   630.7  4969.3  626.38  4972.8     626
  4974.7   625.5  4986.5     626    4990  626.23  4996.9  631.83  5000.9  631.83
  5004.1  628.15  5010.3  633.32  5038.6  634.98  5090.4   634.1  5290.7  635.64
  5329.6  634.94  5407.6   635.4  5605.5  641.44  5683.7  642.34  5726.9  642.05
#Mann= 5 ,-1 , 0
  4234.1     .05       0  4932.8     .12       0  4972.8     .07       0
  4986.5     .12       0  5038.6     .05       0
Bank Sta=4972.8,4986.5
XS Rating Curve= 0 ,0
Exp/Cntr=0.3,0.1

Type RM Length L Ch R = 1 ,2996    ,245,245,245
BEGIN DESCRIPTION:
Mapping XS a345e7bd
END DESCRIPTION:
XS GIS Cut Line= 5
      2334800.61      7095756.97      2334267.77      7095425.33
      2334009.18      7095264.39      2333676.79      7095422.18
      2333520.82      7095223.42
#Sta/Elev= 30
  3935.7  648.89  3984.7  648.75  4008.3  646.48  4051.2  645.94  4057.1  644.68
  4130.3  641.11  4224.7  637.75  4303.8     636  4371.1  636.42  4444.1  635.16
  4486.8  636.14  4529.3  635.01  4744.2  634.14  4856.3  634.19  4939.7  633.71
  4985.1  632.17  4990.7  632.73  5007.8  631.32  5013.4  630.29  5023.1  626.17
  5029.3  625.85  5031.2  625.35    5043  625.85  5045.2  631.24  5053.3  633.54
  5058.2  633.74    5178  634.25    5371  640.96    5456  642.13  5488.5  641.85
#Mann= 5 ,-1 , 0
  3935.7     .05       0  4744.2     .12       0  5029.3     .07       0
    5043     .12       0  5058.2     .05       0
Bank Sta=5029.3,5043
XS Rating Curve= 0 ,0
Exp/Cntr=0.3,0.1

Type RM Length L Ch R = 1 ,2751    ,445,445,445
BEGIN DESCRIPTION:
Mapping XS e9694dce
END DESCRIPTION:
XS GIS Cut Line= 3
      2334816.65      7095740.61      2334318.88      7095415.09
      2333703.19      7095012.49
#Sta/Elev= 30
  3831.6  648.91  3844.3  648.12  3901.6  647.71  3924.4  645.64  4082.5  638.72
  4212.2  635.44  4270.9  634.73  4314.8  635.52    4357  634.74  4426.4  635.03
  4553.1  633.88  4678.8   633.7  4761.1  633.31  4770.2  633.97  4833.5  632.91
  4878.8  633.01    4928  631.87  4963.9  632.17  4978.2  629.21  4986.5   625.3
  4988.5   624.8  5000.2   625.3  5008.5  630.79  5014.4  629.99  5024.4  632.13
  5029.6  632.57  5035.6  634.87  5065.7  637.87  5101.9  639.41    5162  640.36
#Mann= 5 ,-1 , 0
  3831.6     .05       0  4678.8     .12       0  4986.5     .07       0
  5000.2     .12       0  5024.4     .05       0
Bank Sta=4986.5,5000.2
XS Rating Curve= 0 ,0
Exp/Cntr=0.3,0.1

Type RM Length L Ch R = 1 ,2306    ,258,258,258
BEGIN DESCRIPTION:
Mapping XS 6e69e6f2
END DESCRIPTION:
XS GIS Cut Line= 4
      2334833.92      7095694.84      2334369.13      7095320.43
      2334184.48      7094902.77      2333846.86      7094641.34
#Sta/Elev= 30
  3946.4   646.7    4039  645.79  4109.4  641.93  4216.5  637.76  4280.5  635.71
  4344.5  634.47  4408.5  634.43  4466.1   633.5  4515.7  634.16  4604.6  634.12
  4877.3  631.47  4944.1   632.1  4970.1  632.01    4992  630.16  5006.5  625.27
  5012.9  624.18  5019.5  624.58  5020.5  623.74  5022.5  623.24  5032.3  623.24
  5034.2  623.74  5041.8  627.47  5056.3  628.42  5062.7  629.96  5077.2  630.08
    5098  631.42  5131.7  632.08  5234.5  632.87  5319.8  636.54  5426.9  638.56
#Mann= 5 ,-1 , 0
  3946.4     .05       0  4944.1     .12       0  5020.5     .07       0
  5034.2     .12       0  5131.7     .05       0
Bank Sta=5020.5,5034.2
XS Rating Curve= 0 ,0
Exp/Cntr=0.3,0.1

Type RM Length L Ch R = 1 ,2048    ,221,221,221
BEGIN DESCRIPTION:
Mapping XS 6bfda98d
END DESCRIPTION:
XS GIS Cut Line= 4
      2335191.49      7095354.66      2334760.38       7095026.2
      2334330.67      7094698.82      2334024.84      7094530.87
#Sta/Elev= 30
  3914.9   648.4  3962.9  647.28  4012.8  644.45  4077.3  642.78  4112.3   642.6
  4162.5  640.28  4297.7   636.6  4405.7  634.95  4447.3  635.32  4476.4  634.33
  4483.8  633.43  4540.8  632.13  4697.5  631.49  4711.4  630.87  4775.8  631.46
  4833.9  630.69  4919.2  631.54    4935  631.13  4952.8  631.11  4983.6  630.76
  5000.9  629.83  5014.1  624.34  5016.1  623.84  5027.8  624.34  5033.2  624.87
    5056  631.33  5101.7  630.81  5158.7  631.63  5276.8  637.41    5346  637.67
#Mann= 5 ,-1 , 0
  3914.9     .05       0    4935     .12       0  4952.8     .05       0
  5014.1    .033       0  5027.8     .05       0
Bank Sta=5014.1,5027.8
XS Rating Curve= 0 ,0
Exp/Cntr=0.3,0.1

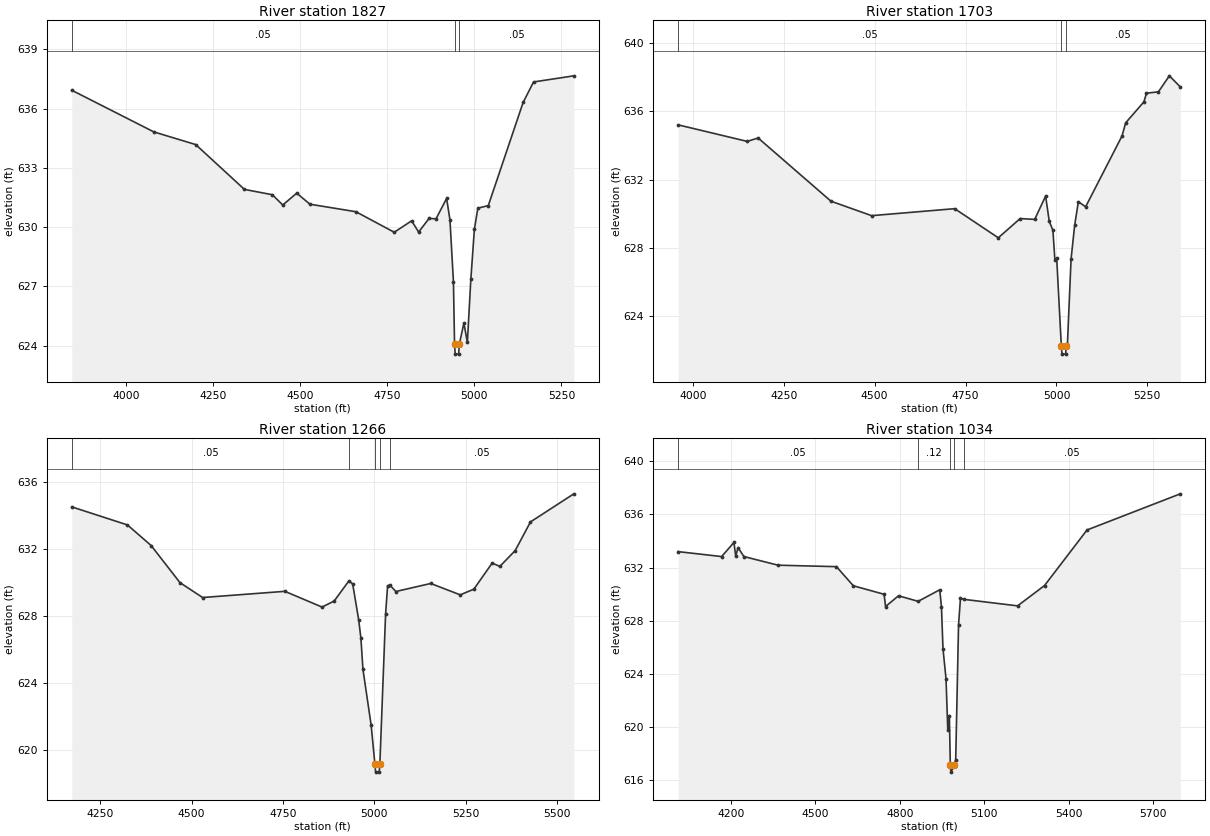
Type RM Length L Ch R = 1 ,1827    ,124,124,124
BEGIN DESCRIPTION:
Mapping XS 15174cd2
END DESCRIPTION:
XS GIS Cut Line= 3
      2335434.76      7094522.86      2335126.83      7094514.85
      2333993.35      7094485.38
#Sta/Elev= 30
  3843.8  636.93  4079.6  634.82  4199.7  634.18  4339.7  631.91  4419.8  631.64
  4449.8  631.12  4489.8  631.72  4527.8  631.16  4659.8  630.78  4769.9  629.74
  4819.9  630.32  4839.9  629.75  4869.9  630.44  4889.9  630.42  4920.3  631.45
  4929.9  630.37  4939.9  627.24  4943.1  624.07    4945  623.57  4954.8  623.57
  4956.8  624.07  4969.9  625.14  4979.9  624.17  4989.9  627.36    5000  629.88
    5010  630.96    5040  631.09    5140  636.31    5170  637.35  5285.7  637.66
#Mann= 3 ,-1 , 0
  3843.8     .05       0  4943.1    .033       0  4956.8     .05       0
Bank Sta=4943.1,4956.8
XS Rating Curve= 0 ,0
Exp/Cntr=0.3,0.1

Type RM Length L Ch R = 1 ,1703    ,437,437,437
BEGIN DESCRIPTION:
Mapping XS 226e60a8
END DESCRIPTION:
XS GIS Cut Line= 3
      2335368.67      7094425.83      2335096.61       7094415.1
      2333988.84      7094371.43
#Sta/Elev= 30
  3959.7  635.21  4149.5  634.24  4179.5  634.44  4379.7  630.73  4491.5  629.88
    4720  630.29    4840  628.58  4900.1  629.71  4940.1  629.66  4970.1  631.03
  4980.2  629.54  4990.2  629.02  4995.6  627.29  5000.6  627.38  5013.3  622.25
  5015.3  621.75  5025.1  621.75    5027  622.25  5030.2  622.37  5040.2  627.35
  5050.2  629.34  5060.2   630.7  5080.2   630.4  5180.3  634.56  5190.3  635.33
  5240.4  636.56  5247.6  637.07  5280.4  637.15  5310.4  638.09  5340.6  637.44
#Mann= 3 ,-1 , 0
  3959.7     .05       0  5013.3    .033       0    5027     .05       0
Bank Sta=5013.3,5027
XS Rating Curve= 0 ,0
Exp/Cntr=0.3,0.1

Type RM Length L Ch R = 1 ,1266    ,232,232,232
BEGIN DESCRIPTION:
Mapping XS 33fc9fa7
END DESCRIPTION:
XS GIS Cut Line= 4
      2335296.39       7094379.9      2335123.66      7094334.64
      2334447.84      7094003.89      2334026.32      7094139.92
#Sta/Elev= 30
  4172.2  634.51  4324.6  633.43  4389.3   632.2  4468.3  629.98  4530.2  629.09
  4755.3  629.46    4857  628.52  4890.3  628.88  4930.7  630.09  4940.9   629.9
  4957.2  627.77  4963.4  626.66    4969  624.79  4991.5  621.45  5001.6  619.15
  5003.6  618.65  5013.4  618.65  5015.3  619.15    5031  628.12  5036.5   629.8
  5043.1  629.82    5059  629.45  5154.5  629.93  5235.2  629.25  5272.5  629.59
  5322.6  631.15  5343.6  630.95  5385.7   631.9  5427.4  633.61  5546.1  635.29
#Mann= 5 ,-1 , 0
  4172.2     .05       0  4930.7     .12       0  5001.6     .07       0
  5015.3     .12       0  5043.1     .05       0
Bank Sta=5001.6,5015.3
XS Rating Curve= 0 ,0
Exp/Cntr=0.3,0.1

Type RM Length L Ch R = 1 ,1034    ,0,0,0
BEGIN DESCRIPTION:
Denton Creek Tributary 17 2.0
END DESCRIPTION:
XS GIS Cut Line= 4
      2335251.48      7094254.04      2334946.97      7093840.49
      2334593.21      7093815.69      2333771.32       7094216.7
#Sta/Elev= 30
  4013.3   633.2  4167.3  632.83  4211.1  633.89  4217.3  632.87  4225.8   633.5
  4246.6  632.83  4367.7  632.18    4575  632.07  4635.1  630.63  4744.4  629.99
  4749.4  629.07  4795.5  629.88  4865.2  629.46  4941.8  630.33  4947.9  629.06
  4953.4  625.88  4964.1  623.64  4970.4  619.77    4976  620.87  4979.4  617.11
  4981.4  616.61  4993.2  617.11  4998.5  617.54  5008.6  627.69  5015.4  629.69
  5027.7  629.61  5218.2  629.12  5313.9  630.65  5464.8  634.83    5796  637.55
#Mann= 5 ,-1 , 0
  4013.3     .05       0  4865.2     .12       0  4979.4     .07       0
  4993.2     .12       0  5027.7     .05       0
Bank Sta=4979.4,4993.2
XS Rating Curve= 0 ,0
Exp/Cntr=0.3,0.1

Chan Stop Cuts=-1
Use User Specified Reach Order=0
Composite Channel Slope=5