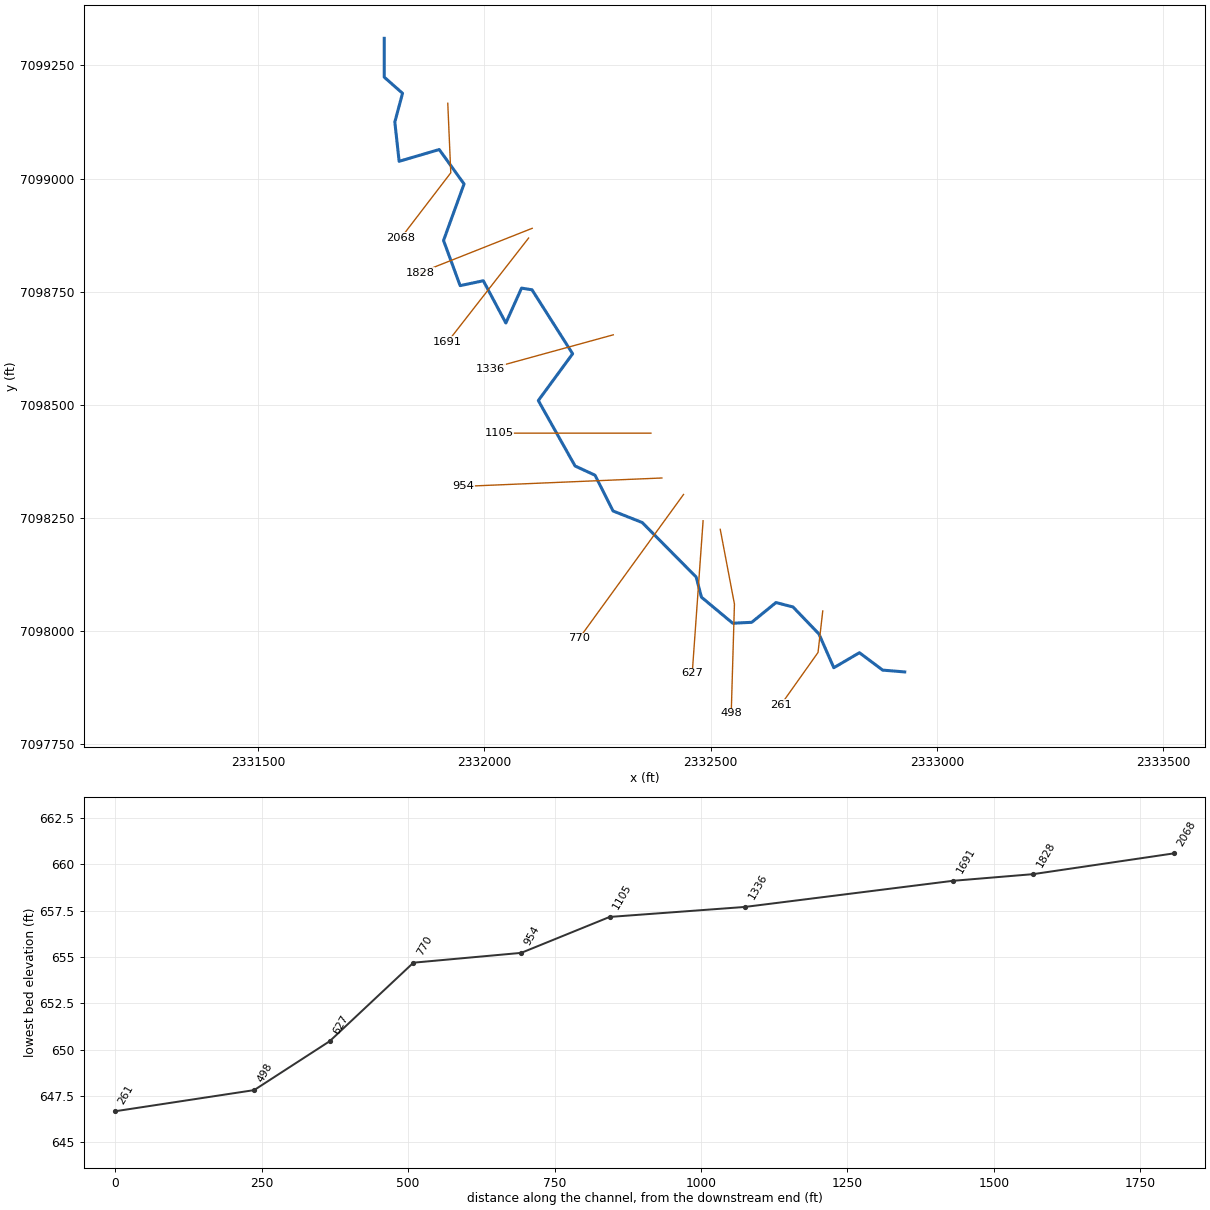
--- Denton Creek Tributary 17_2.prj (project) ---

Proj Title=Denton Creek Tributary 17_2 Base Level Engineering
Current Plan=p01
Default Exp/Contr=0.3,0.1
English Units
Geom File=g01
Flow File=f01
Plan File=p01
BEGIN DESCRIPTION:
Denton Creek Tributary 17_2
END DESCRIPTION:

--- Denton Creek Tributary 17_2.p01 (plan) ---

Plan Title=Multiple Run
Short Identifier=Multiple
Geom File=g01
Flow File=f01
Subcritical Flow
K Sum by GR= 0
Std Step Tol= 0.01
Critical Tol= 0.01
Num of Std Step Trials= 20
Max Error Tol= 0.3
Flow Tol Ratio= 0.001
Split Flow NTrial= 30
Split Flow Tol= 0.02
Split Flow Ratio= 0.02
Log Output Level= 0
Friction Slope Method= 1
Unsteady Friction Slope Method= 2
Unsteady Bridges Friction Slope Method= 1
Parabolic Critical Depth
Global Vel Dist=  1 , 1 , 1
Global Log Level= 0
CheckData=True
Encroach Param= -1, 0, 0, 0
BEGIN DESCRIPTION:
Multiple Run
END DESCRIPTION:

--- Denton Creek Tributary 17_2.f01 (steady flow) ---

Flow Title=Multiple
Number of Profiles=7
Profile Names=10-year,25-year,50-year,1pct_min,100-year,1pct_plu,500-year
River Rch & RM= Denton Creek Tri,Reach-1,2068
     286     375     446     264     526    1050     735
Boundary for River Rch & Prof#=Denton Creek Tri,Reach-1,1
Up Type=0
Dn Type=3
Dn Slope=0.005
Boundary for River Rch & Prof#=Denton Creek Tri,Reach-1,2
Up Type=0
Dn Type=3
Dn Slope=0.005
Boundary for River Rch & Prof#=Denton Creek Tri,Reach-1,3
Up Type=0
Dn Type=3
Dn Slope=0.005
Boundary for River Rch & Prof#=Denton Creek Tri,Reach-1,4
Up Type=0
Dn Type=3
Dn Slope=0.005
Boundary for River Rch & Prof#=Denton Creek Tri,Reach-1,5
Up Type=0
Dn Type=3
Dn Slope=0.005
Boundary for River Rch & Prof#=Denton Creek Tri,Reach-1,6
Up Type=0
Dn Type=3
Dn Slope=0.005
Boundary for River Rch & Prof#=Denton Creek Tri,Reach-1,7
Up Type=0
Dn Type=3
Dn Slope=0.005

--- Denton Creek Tributary 17_2.g01 (geometry) ---

Geom Title=Existing Conditions

River Reach=Denton Creek Tri,Reach-1
Reach XY= 30
      2331779.00      7099310.00      2331778.97      7099224.20
      2331819.39      7099188.59      2331802.34      7099125.01
      2331811.87      7099038.26      2331900.46      7099064.30
      2331955.30      7098988.23      2331909.97      7098863.30
      2331946.65      7098763.56      2331997.88      7098774.31
      2332047.65      7098680.97      2332082.33      7098758.05
      2332105.41      7098754.40      2332195.23      7098612.99
      2332119.37      7098509.63      2332200.67      7098365.00
      2332244.68      7098344.68      2332284.56      7098265.62
      2332348.92      7098240.14      2332468.21      7098119.66
      2332479.83      7098075.17      2332548.92      7098017.59
      2332591.03      7098019.64      2332644.52      7098063.28
      2332682.16      7098053.53      2332739.45      7097993.93
      2332772.33      7097919.28      2332828.93      7097952.42
      2332880.36      7097913.98      2332929.00      7097910.00

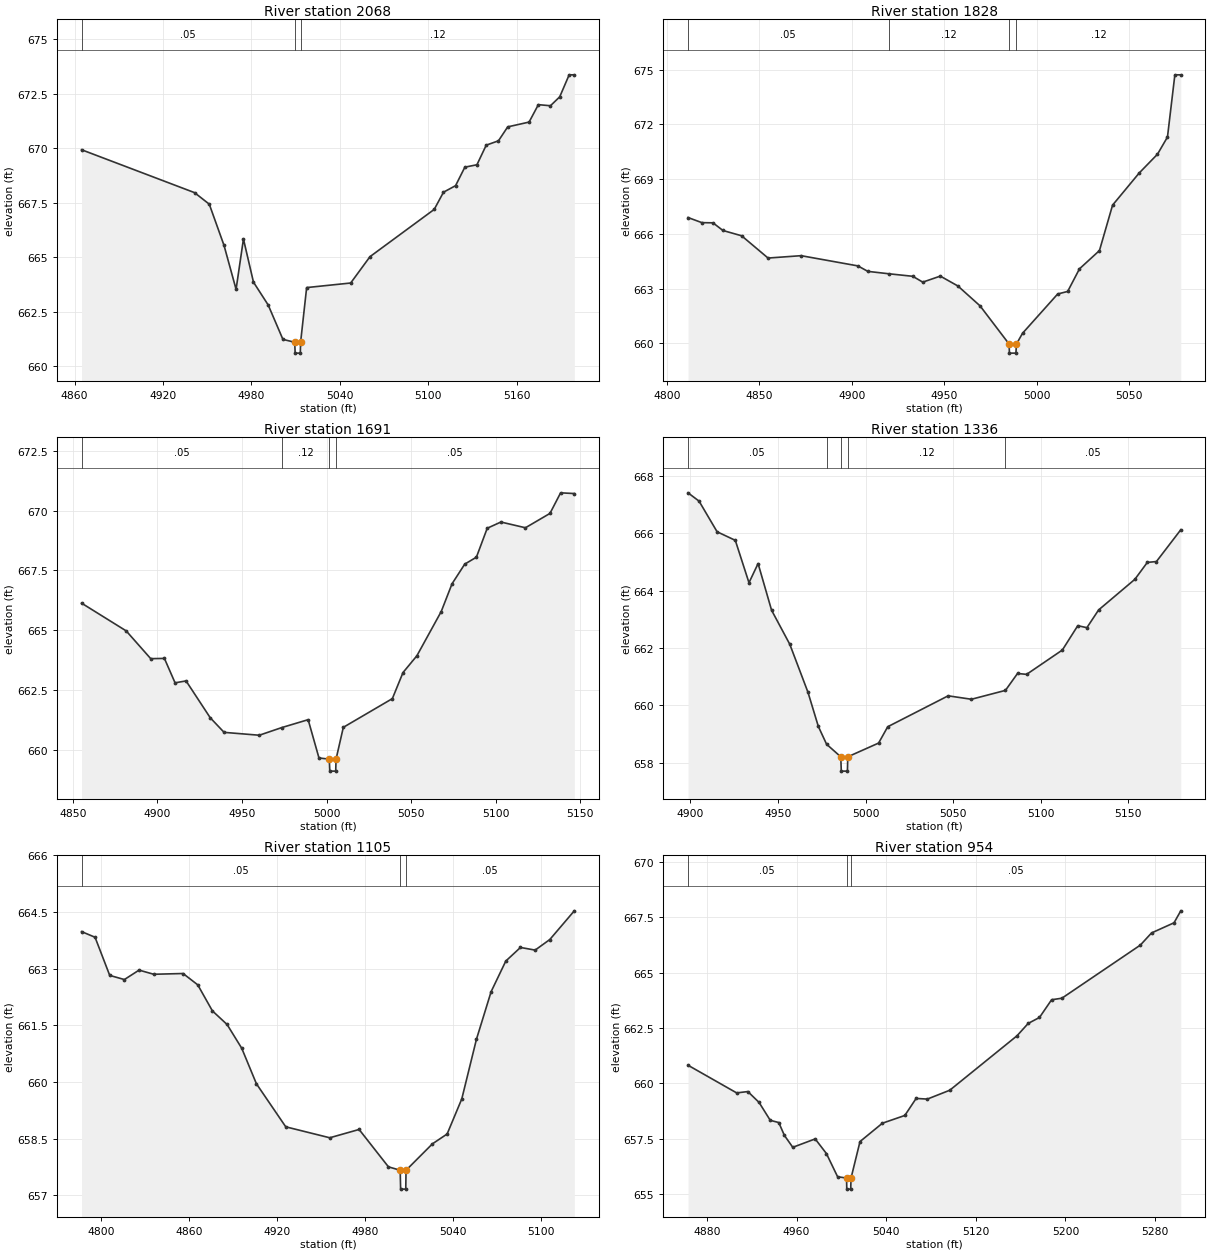
Type RM Length L Ch R = 1,2068,240,240,240
BEGIN DESCRIPTION:
Denton Creek Tributary 17_2 2.0
END DESCRIPTION:
XS GIS Cut Line= 3
      2331919.33      7099166.61      2331925.98      7099012.85
      2331816.20      7098869.46
#Sta/Elev= 30
  4864.7  669.93  4941.4  667.96  4951.4  667.43  4961.4  665.54  4969.6  663.52
  4974.6  665.83  4981.4  663.85  4991.4  662.80  5001.4  661.22  5009.4  661.09
  5009.7  660.59  5013.2  660.59  5013.4  661.09  5017.5  663.60  5047.4  663.81
  5060.5  665.02  5104.1  667.19  5110.4  667.98  5118.6  668.28  5124.9  669.13
  5133.1  669.24  5139.4  670.14  5147.7  670.34  5154.0  670.98  5168.5  671.20
  5174.8  672.00  5183.0  671.95  5189.3  672.36  5195.7  673.37  5199.2  673.37
#Mann=3,-1,0
  4864.7    0.05       0  5009.4   0.033       0  5013.4    0.12       0
Bank Sta=5009.4,5013.4
Exp/Cntr=0.3,0.1

Type RM Length L Ch R = 1,1828,137,137,137
BEGIN DESCRIPTION:
Mapping XS e5915862
END DESCRIPTION:
XS GIS Cut Line= 2
      2332105.93      7098890.25      2331858.07      7098792.05
#Sta/Elev= 30
  4811.4  666.90  4818.9  666.62  4824.9  666.61  4830.3  666.19  4840.4  665.90
  4854.7  664.68  4872.6  664.81  4903.3  664.25  4908.7  663.95  4919.9  663.82
  4933.0  663.68  4938.4  663.36  4947.9  663.69  4957.4  663.15  4969.4  662.06
  4985.1  659.97  4985.3  659.47  4988.8  659.47  4989.1  659.97  4992.4  660.56
  5011.4  662.71  5016.8  662.85  5023.2  664.09  5034.0  665.09  5041.1  667.58
  5055.5  669.34  5065.4  670.37  5070.8  671.31  5074.8  674.72  5078.0  674.72
#Mann=4,-1,0
  4811.4    0.05       0  4919.9    0.12       0  4985.1    0.07       0
  4989.1    0.12       0
Bank Sta=4985.1,4989.1
Exp/Cntr=0.3,0.1

Type RM Length L Ch R = 1,1691,355,355,355
BEGIN DESCRIPTION:
Mapping XS a4e55146
END DESCRIPTION:
XS GIS Cut Line= 2
      2332097.97      7098868.71      2331918.77      7098638.92
#Sta/Elev= 30
  4855.1  666.13  4881.5  664.97  4896.0  663.81  4904.1  663.82  4910.4  662.80
  4916.9  662.88  4931.2  661.34  4939.4  660.73  4960.2  660.61  4973.5  660.93
  4989.1  661.26  4995.5  659.66  5001.6  659.61  5001.9  659.11  5005.4  659.11
  5005.6  659.61  5009.9  660.94  5038.9  662.14  5045.2  663.23  5053.4  663.93
  5067.8  665.78  5074.2  666.94  5081.7  667.76  5088.6  668.05  5095.0  669.26
  5103.1  669.52  5117.6  669.28  5132.1  669.88  5138.4  670.74  5146.5  670.71
#Mann=4,-1,0
  4855.1    0.05       0  4973.5    0.12       0  5001.6    0.07       0
  5005.6    0.05       0
Bank Sta=5001.6,5005.6
Exp/Cntr=0.3,0.1

Type RM Length L Ch R = 1,1336,231,231,231
BEGIN DESCRIPTION:
Mapping XS b50bce4b
END DESCRIPTION:
XS GIS Cut Line= 2
      2332285.04      7098654.89      2332013.77      7098580.43
#Sta/Elev= 30
  4898.6  667.42  4904.9  667.13  4915.2  666.06  4925.6  665.76  4933.4  664.28
  4938.6  664.95  4946.3  663.32  4956.7  662.13  4967.1  660.45  4973.0  659.26
  4977.7  658.64  4985.8  658.20  4986.1  657.70  4989.6  657.70  4989.8  658.20
  5007.4  658.68  5012.6  659.25  5047.1  660.33  5060.4  660.21  5079.8  660.52
  5086.7  661.11  5091.9  661.08  5112.3  661.93  5121.1  662.78  5126.3  662.71
  5133.0  663.33  5153.7  664.40  5160.8  664.99  5166.0  665.02  5179.9  666.13
#Mann=5,-1,0
  4898.6    0.05       0  4977.7    0.12       0  4985.8    0.07       0
  4989.8    0.12       0  5079.8    0.05       0
Bank Sta=4985.8,4989.8
Exp/Cntr=0.3,0.1

Type RM Length L Ch R = 1,1105,151,151,151
BEGIN DESCRIPTION:
Mapping XS 04d14109
END DESCRIPTION:
XS GIS Cut Line= 2
      2332368.25      7098437.56      2332032.35      7098437.64
#Sta/Elev= 30
  4786.9  663.98  4796.1  663.83  4806.1  662.82  4816.1  662.71  4826.1  662.96
  4836.1  662.85  4856.1  662.87  4866.1  662.57  4876.1  661.88  4886.1  661.52
  4896.1  660.89  4906.1  659.95  4926.1  658.81  4956.1  658.52  4976.1  658.74
  4996.1  657.75  5004.1  657.66  5004.4  657.16  5007.9  657.16  5008.1  657.66
  5026.1  658.36  5036.1  658.62  5046.1  659.55  5056.1  661.13  5066.1  662.39
  5076.1  663.20  5086.1  663.56  5096.1  663.49  5106.1  663.77  5122.8  664.53
#Mann=3,-1,0
  4786.9    0.05       0  5004.1   0.033       0  5008.1    0.05       0
Bank Sta=5004.1,5008.1
Exp/Cntr=0.3,0.1

Type RM Length L Ch R = 1,954,184,184,184
BEGIN DESCRIPTION:
Mapping XS b2f38edc
END DESCRIPTION:
XS GIS Cut Line= 2
      2332392.37      7098338.52      2331952.96      7098319.96
#Sta/Elev= 30
  4863.1  660.82  4906.5  659.57  4916.5  659.63  4926.5  659.14  4936.5  658.33
  4944.1  658.23  4949.1  657.65  4956.6  657.11  4976.6  657.49  4986.6  656.83
  4996.6  655.78  5004.6  655.72  5004.8  655.22  5008.3  655.22  5008.6  655.72
  5016.6  657.37  5036.6  658.20  5056.6  658.55  5066.7  659.32  5076.7  659.29
  5096.7  659.69  5156.7  662.15  5166.7  662.71  5176.8  662.98  5187.6  663.78
  5196.8  663.85  5266.8  666.25  5276.8  666.80  5296.9  667.26  5302.9  667.80
#Mann=3,-1,0
  4863.1    0.05       0  5004.6   0.033       0  5008.6    0.05       0
Bank Sta=5004.6,5008.6
Exp/Cntr=0.3,0.1

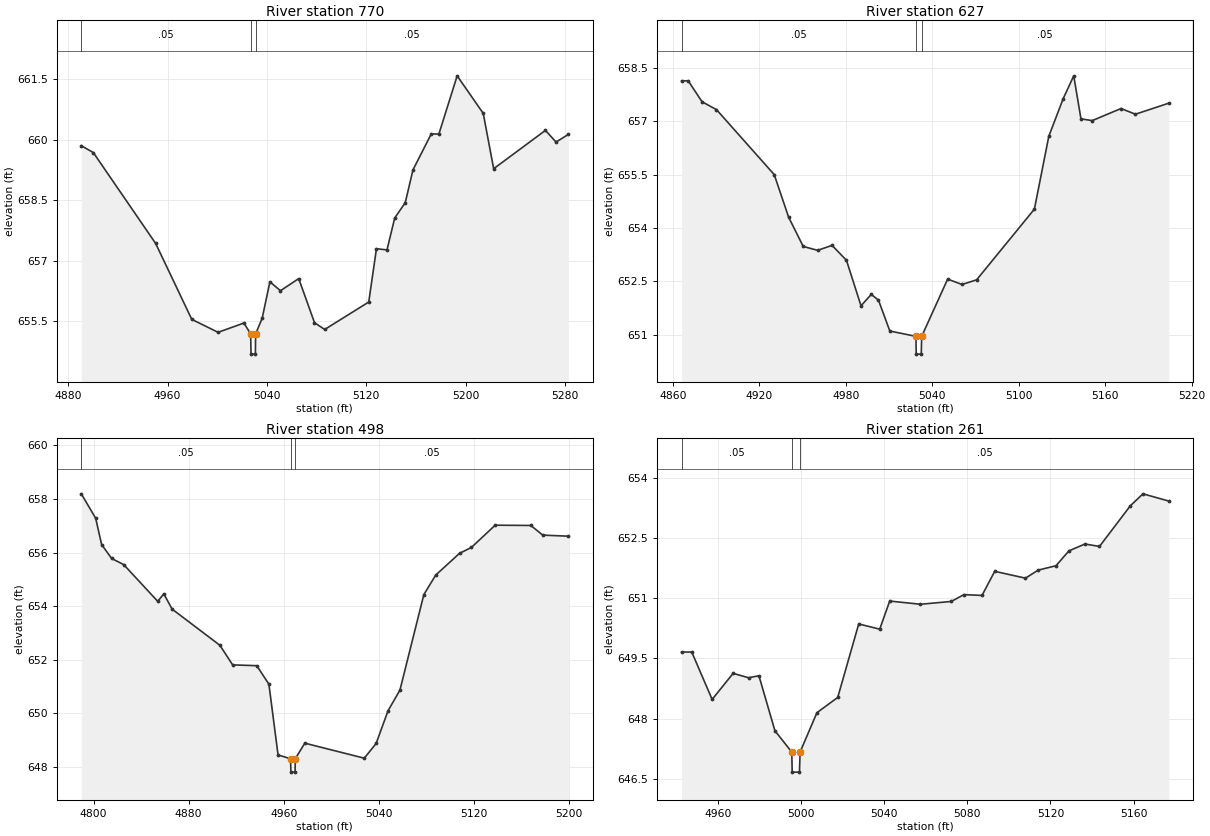
Type RM Length L Ch R = 1,770,143,143,143
BEGIN DESCRIPTION:
Mapping XS d17f0280
END DESCRIPTION:
XS GIS Cut Line= 2
      2332440.23      7098302.04      2332209.91      7097984.47
#Sta/Elev= 30
  4890.5  659.85  4900.2  659.68  4950.4  657.43  4979.5  655.55  5000.7  655.23
  5021.5  655.46  5026.9  655.19  5027.2  654.69  5030.7  654.69  5030.9  655.19
  5036.2  655.58  5042.4  656.48  5050.9  656.26  5065.6  656.56  5078.3  655.47
  5086.5  655.30  5122.0  655.98  5128.2  657.30  5136.7  657.27  5142.9  658.06
  5151.4  658.44  5157.6  659.25  5172.3  660.14  5178.5  660.14  5193.2  661.58
  5214.2  660.65  5222.6  659.28  5264.3  660.23  5272.8  659.94  5282.8  660.13
#Mann=3,-1,0
  4890.5    0.05       0  5026.9   0.033       0  5030.9    0.05       0
Bank Sta=5026.9,5030.9
Exp/Cntr=0.3,0.1

Type RM Length L Ch R = 1,627,129,129,129
BEGIN DESCRIPTION:
Mapping XS 381defd6
END DESCRIPTION:
XS GIS Cut Line= 2
      2332483.51      7098244.15      2332459.47      7097907.01
#Sta/Elev= 30
  4866.0  658.14  4870.6  658.14  4880.2  657.55  4890.2  657.33  4930.3  655.50
  4940.3  654.30  4950.4  653.48  4960.4  653.37  4970.4  653.51  4980.4  653.09
  4990.5  651.81  4997.6  652.13  5002.6  651.97  5010.5  651.10  5028.6  650.95
  5028.8  650.45  5032.3  650.45  5032.6  650.95  5050.6  652.56  5060.6  652.41
  5070.7  652.54  5110.8  654.53  5120.8  656.58  5130.8  657.64  5138.1  658.28
  5143.1  657.07  5150.9  657.02  5170.9  657.36  5180.9  657.20  5204.0  657.51
#Mann=3,-1,0
  4866.0    0.05       0  5028.6   0.033       0  5032.6    0.05       0
Bank Sta=5028.6,5032.6
Exp/Cntr=0.3,0.1

Type RM Length L Ch R = 1,498,237,237,237
BEGIN DESCRIPTION:
Mapping XS d2d2bc05
END DESCRIPTION:
XS GIS Cut Line= 3
      2332521.41      7098225.05      2332552.76      7098059.93
      2332545.67      7097818.41
#Sta/Elev= 30
  4789.7  658.19  4801.8  657.28  4806.8  656.30  4815.2  655.78  4825.4  655.55
  4854.0  654.18  4859.1  654.46  4866.1  653.89  4906.3  652.54  4917.0  651.81
  4937.3  651.78  4947.5  651.09  4955.2  648.45  4965.7  648.31  4966.0  647.81
  4969.5  647.81  4969.7  648.31  4977.7  648.89  5027.7  648.33  5037.7  648.88
  5047.7  650.10  5057.7  650.87  5077.8  654.43  5087.8  655.16  5107.8  655.97
  5117.8  656.19  5137.8  657.02  5167.8  657.01  5177.8  656.65  5199.4  656.61
#Mann=3,-1,0
  4789.7    0.05       0  4965.7   0.033       0  4969.7    0.05       0
Bank Sta=4965.7,4969.7
Exp/Cntr=0.3,0.1

Type RM Length L Ch R = 1,261,0,0,0
BEGIN DESCRIPTION:
Denton Creek Tributary 17_2 1.0
END DESCRIPTION:
XS GIS Cut Line= 3
      2332747.90      7098044.64      2332737.47      7097952.97
      2332655.23      7097837.16
#Sta/Elev= 30
  4942.6  649.66  4947.5  649.66  4957.3  648.48  4967.4  649.13  4974.8  649.02
  4979.8  649.07  4987.5  647.70  4995.6  647.17  4995.8  646.67  4999.3  646.67
  4999.6  647.17  5007.7  648.15  5017.7  648.53  5027.8  650.36  5037.9  650.23
  5042.7  650.93  5057.5  650.85  5072.3  650.92  5078.4  651.09  5087.1  651.07
  5093.2  651.67  5108.0  651.50  5114.1  651.70  5122.7  651.81  5128.9  652.18
  5136.6  652.35  5143.6  652.29  5158.4  653.30  5164.5  653.60  5176.9  653.42
#Mann=3,-1,0
  4942.6    0.05       0  4995.6   0.033       0  4999.6    0.05       0
Bank Sta=4995.6,4999.6
Exp/Cntr=0.3,0.1

Chan Stop Cuts=-1