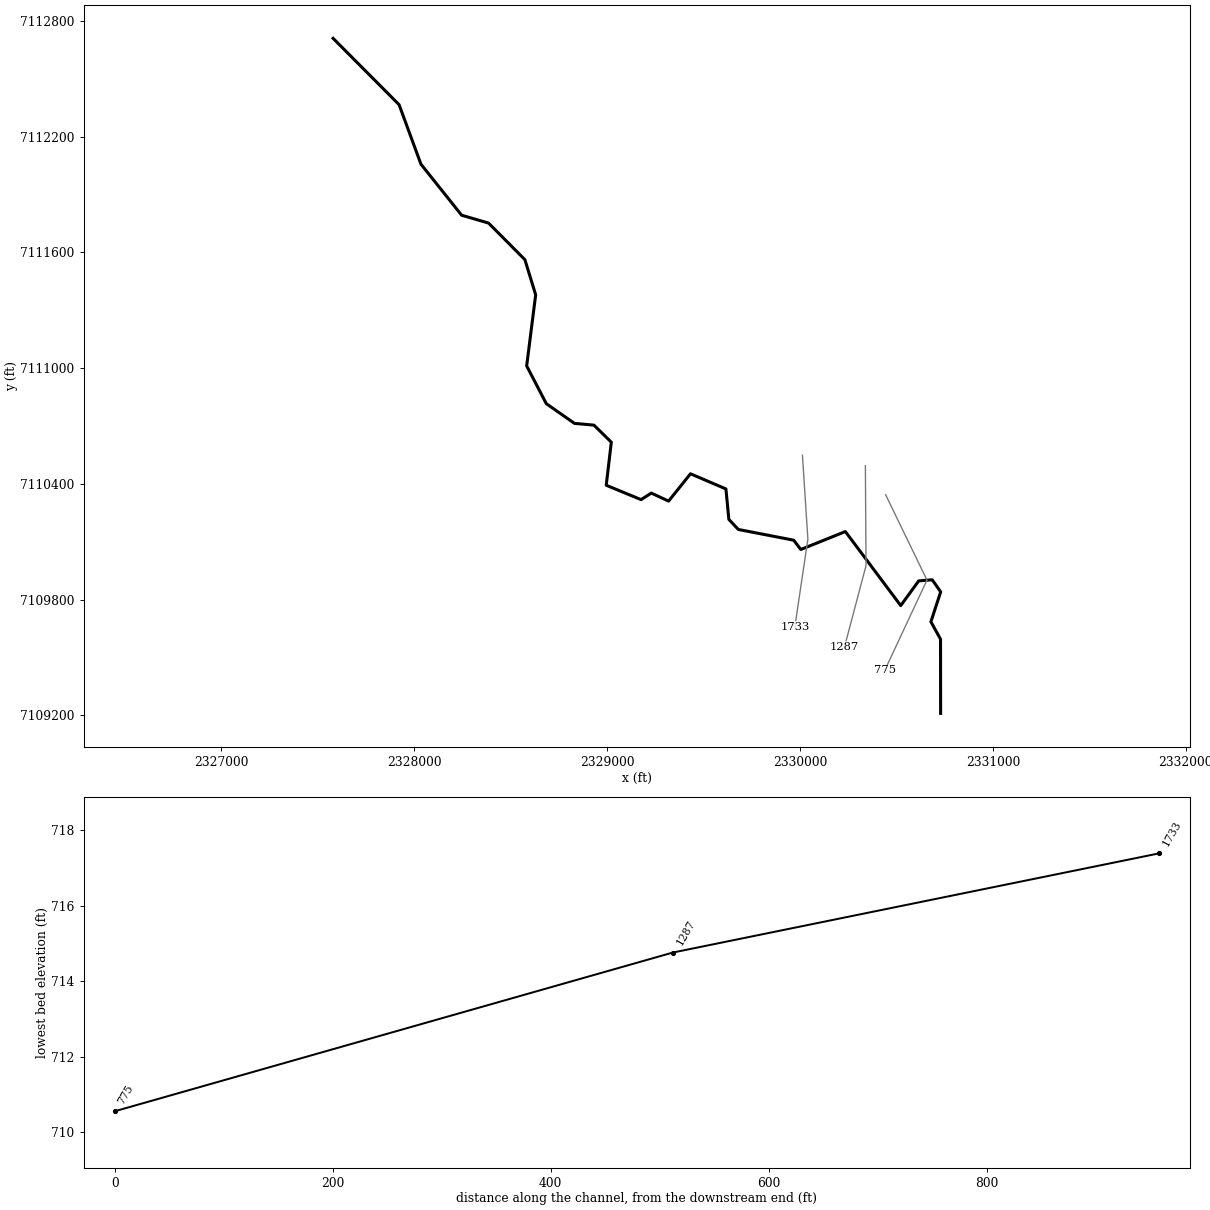
--- Denton Creek Tributary 17_4.prj (project) ---

Proj Title=Denton Creek Tributary 17_4 Base Level Engineering
Current Plan=p01
Default Exp/Contr=0.3,0.1
English Units
Geom File=g01
Flow File=f01
Plan File=p01
BEGIN DESCRIPTION:
Denton Creek Tributary 17_4
END DESCRIPTION:

--- Denton Creek Tributary 17_4.p01 (plan) ---

Plan Title=Multiple Run
Short Identifier=Multiple
Geom File=g01
Flow File=f01
Subcritical Flow
K Sum by GR= 0
Std Step Tol= 0.01
Critical Tol= 0.01
Num of Std Step Trials= 20
Max Error Tol= 0.3
Flow Tol Ratio= 0.001
Split Flow NTrial= 30
Split Flow Tol= 0.02
Split Flow Ratio= 0.02
Log Output Level= 0
Friction Slope Method= 1
Unsteady Friction Slope Method= 2
Unsteady Bridges Friction Slope Method= 1
Parabolic Critical Depth
Global Vel Dist=  1 , 1 , 1
Global Log Level= 0
CheckData=True
Encroach Param= -1, 0, 0, 0
BEGIN DESCRIPTION:
Multiple Run
END DESCRIPTION:

--- Denton Creek Tributary 17_4.f01 (steady flow) ---

Flow Title=Multiple
Number of Profiles=7
Profile Names=10-year,25-year,50-year,1pct_min,100-year,1pct_plu,500-year
River Rch & RM= Denton Creek Tri,Reach-1,1733
     477     642     775     464     926    1848    1328
Boundary for River Rch & Prof#=Denton Creek Tri,Reach-1,1
Up Type=0
Dn Type=3
Dn Slope=0.005
Boundary for River Rch & Prof#=Denton Creek Tri,Reach-1,2
Up Type=0
Dn Type=3
Dn Slope=0.005
Boundary for River Rch & Prof#=Denton Creek Tri,Reach-1,3
Up Type=0
Dn Type=3
Dn Slope=0.005
Boundary for River Rch & Prof#=Denton Creek Tri,Reach-1,4
Up Type=0
Dn Type=3
Dn Slope=0.005
Boundary for River Rch & Prof#=Denton Creek Tri,Reach-1,5
Up Type=0
Dn Type=3
Dn Slope=0.005
Boundary for River Rch & Prof#=Denton Creek Tri,Reach-1,6
Up Type=0
Dn Type=3
Dn Slope=0.005
Boundary for River Rch & Prof#=Denton Creek Tri,Reach-1,7
Up Type=0
Dn Type=3
Dn Slope=0.005

--- Denton Creek Tributary 17_4.g01 (geometry) ---

Geom Title=Existing Conditions

River Reach=Denton Creek Tri,Reach-1
Reach XY= 30
      2327579.00      7112710.00      2327921.12      7112366.13
      2328034.52      7112057.57      2328245.46      7111792.87
      2328385.17      7111752.14      2328573.48      7111562.43
      2328629.36      7111380.15      2328582.67      7111011.58
      2328684.59      7110815.61      2328830.50      7110713.63
      2328931.44      7110704.48      2329021.53      7110616.08
      2328995.21      7110392.79      2329175.78      7110318.27
      2329228.92      7110352.17      2329318.51      7110310.58
      2329432.03      7110452.21      2329615.80      7110373.73
      2329630.98      7110215.65      2329680.25      7110163.51
      2329967.05      7110107.97      2330003.96      7110059.68
      2330235.06      7110152.73      2330522.20      7109768.77
      2330615.45      7109897.04      2330685.37      7109902.68
      2330729.25      7109840.08      2330678.60      7109685.00
      2330728.46      7109594.79      2330729.00      7109210.00

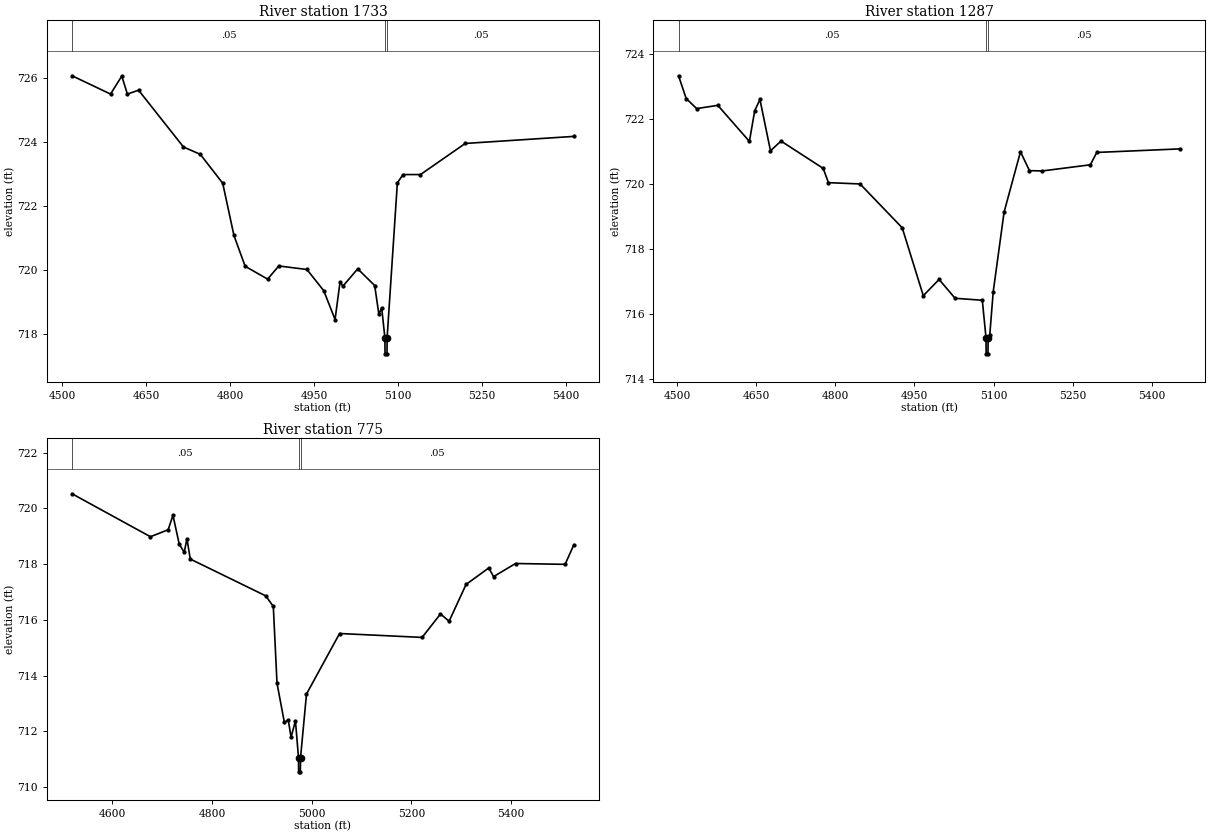
Type RM Length L Ch R = 1,1733,446,446,446
BEGIN DESCRIPTION:
Denton Creek Tributary 17_4 3.0
END DESCRIPTION:
XS GIS Cut Line= 3
      2330012.51      7110548.58      2330040.72      7110112.53
      2329973.02      7109658.10
#Sta/Elev= 30
  4517.3  726.06  4586.0  725.49  4606.1  726.05  4616.1  725.49  4636.1  725.61
  4716.3  723.84  4746.4  723.61  4786.4  722.71  4806.5  721.08  4826.5  720.12
  4866.6  719.72  4886.6  720.13  4936.8  720.02  4966.9  719.36  4987.1  718.46
  4996.0  719.63  5001.1  719.50  5027.6  720.04  5057.9  719.52  5065.4  718.62
  5070.4  718.83  5076.1  717.89  5076.4  717.39  5079.9  717.39  5080.1  717.89
  5098.4  722.72  5108.5  722.98  5139.7  722.98  5219.7  723.95  5413.7  724.17
#Mann=3,-1,0
  4517.3    0.05       0  5076.1    0.04       0  5080.1    0.05       0
Bank Sta=5076.1,5080.1
Exp/Cntr=0.3,0.1

Type RM Length L Ch R = 1,1287,512,512,512
BEGIN DESCRIPTION:
Denton Creek Tributary 17_4 2.0
END DESCRIPTION:
XS GIS Cut Line= 3
      2330338.85      7110494.52      2330342.22      7109976.45
      2330231.25      7109556.65
#Sta/Elev= 30
  4502.2  723.32  4516.7  722.62  4536.7  722.31  4576.7  722.41  4636.7  721.30
  4646.7  722.24  4656.7  722.59  4676.7  721.01  4696.7  721.31  4776.7  720.47
  4786.7  720.03  4846.7  719.99  4926.7  718.64  4966.7  716.55  4996.7  717.05
  5027.0  716.47  5078.7  716.41  5085.7  715.26  5086.0  714.76  5089.5  714.76
  5089.7  715.26  5092.9  715.35  5099.4  716.67  5120.0  719.12  5151.1  720.98
  5168.2  720.40  5192.5  720.39  5283.8  720.58  5295.9  720.96  5454.5  721.07
#Mann=3,-1,0
  4502.2    0.05       0  5085.7    0.04       0  5089.7    0.05       0
Bank Sta=5085.7,5089.7
Exp/Cntr=0.3,0.1

Type RM Length L Ch R = 1,775,0,0,0
BEGIN DESCRIPTION:
Denton Creek Tributary 17_4 1.0
END DESCRIPTION:
XS GIS Cut Line= 3
      2330443.93      7110343.49      2330658.17      7109900.98
      2330439.86      7109434.04
#Sta/Elev= 30
  4519.1  720.52  4676.4  718.98  4711.9  719.23  4721.6  719.75  4734.1  718.72
  4744.2  718.42  4749.7  718.91  4756.3  718.18  4907.8  716.86  4923.0  716.48
  4930.4  713.73  4945.2  712.32  4953.0  712.41  4958.6  711.79  4967.4  712.38
  4973.6  711.05  4973.8  710.55  4977.3  710.55  4977.6  711.05  4989.6  713.34
  5056.0  715.51  5221.6  715.37  5258.5  716.21  5275.8  715.95  5309.9  717.27
  5355.4  717.86  5365.1  717.55  5409.2  718.02  5508.6  717.99  5526.2  718.69
#Mann=3,-1,0
  4519.1    0.05       0  4973.6    0.04       0  4977.6    0.05       0
Bank Sta=4973.6,4977.6
Exp/Cntr=0.3,0.1

Chan Stop Cuts=-1