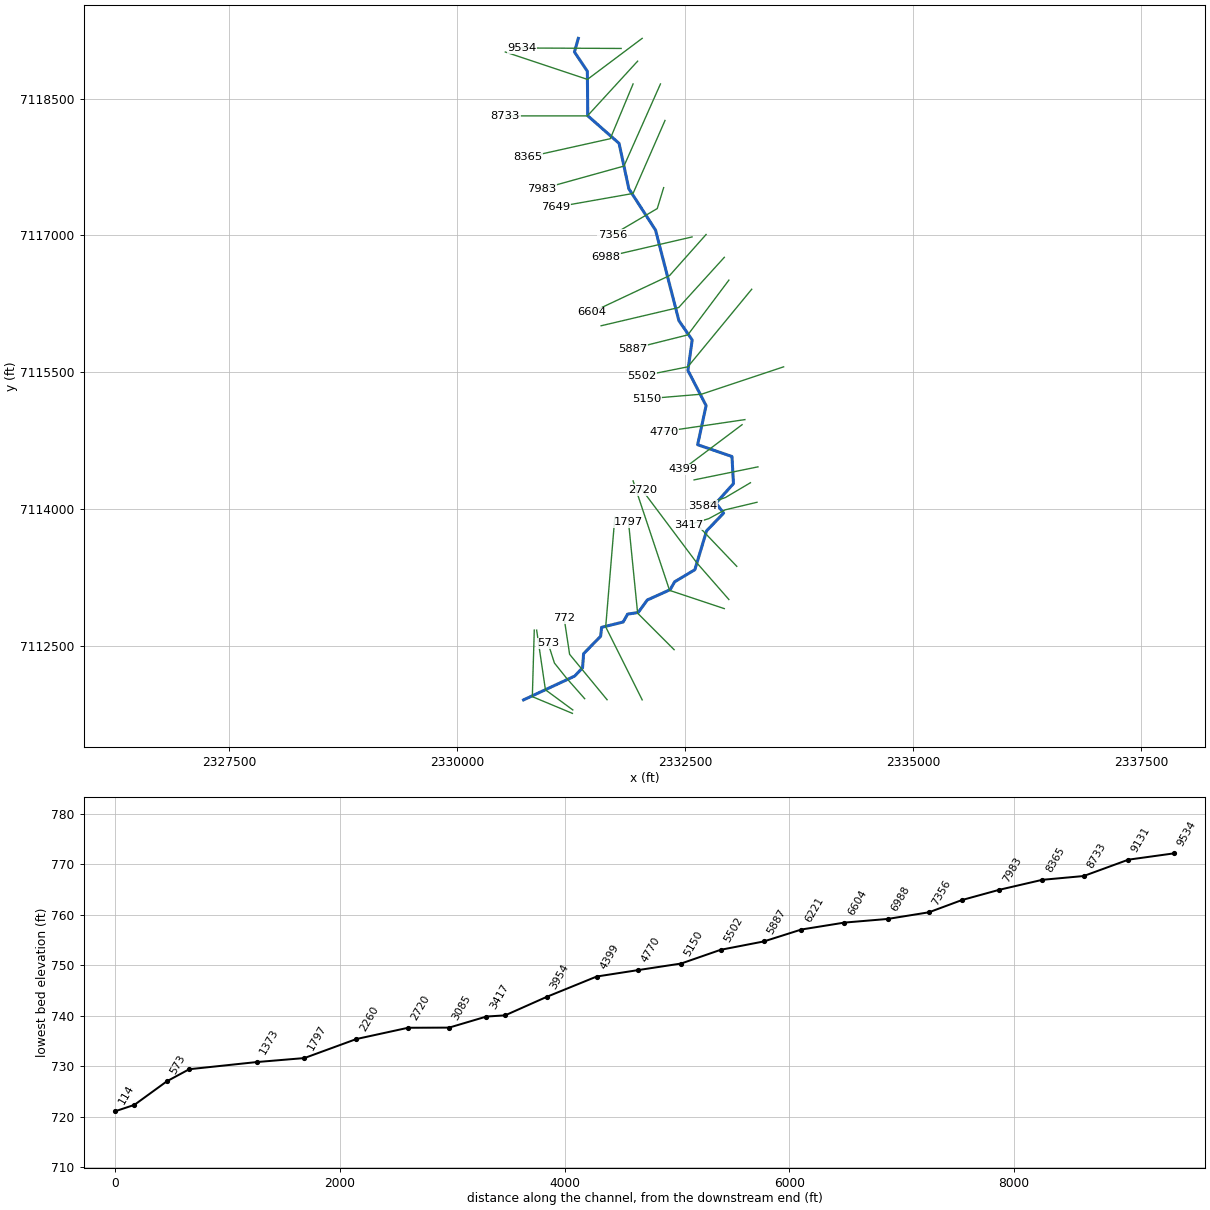
--- Denton Creek Tributary 17_5.prj (project) ---

Proj Title=Denton Creek Tributary 17_5 Base Level Engineering
Current Plan=p01
Default Exp/Contr=0.3,0.1
English Units
Geom File=g01
Flow File=f01
Plan File=p01
BEGIN DESCRIPTION:
Denton Creek Tributary 17_5
END DESCRIPTION:

--- Denton Creek Tributary 17_5.p01 (plan) ---

Plan Title=Multiple Run
Short Identifier=Multiple
Geom File=g01
Flow File=f01
Subcritical Flow
K Sum by GR= 0
Std Step Tol= 0.01
Critical Tol= 0.01
Num of Std Step Trials= 20
Max Error Tol= 0.3
Flow Tol Ratio= 0.001
Split Flow NTrial= 30
Split Flow Tol= 0.02
Split Flow Ratio= 0.02
Log Output Level= 0
Friction Slope Method= 1
Unsteady Friction Slope Method= 2
Unsteady Bridges Friction Slope Method= 1
Parabolic Critical Depth
Global Vel Dist=  1 , 1 , 1
Global Log Level= 0
CheckData=True
Encroach Param= -1, 0, 0, 0
BEGIN DESCRIPTION:
Multiple Run
END DESCRIPTION:

--- Denton Creek Tributary 17_5.f01 (steady flow) ---

Flow Title=Multiple
Number of Profiles=7
Profile Names=10-year,25-year,50-year,1pct_min,100-year,1pct_plu,500-year
River Rch & RM= Denton Creek Tri,Reach-1,9534
     462     617     740     440     879    1753    1243
River Rch & RM= Denton Creek Tri,Reach-1,3085
     552     744     900     540    1078    2151    1549
Boundary for River Rch & Prof#=Denton Creek Tri,Reach-1,1
Up Type=0
Dn Type=3
Dn Slope=0.005
Boundary for River Rch & Prof#=Denton Creek Tri,Reach-1,2
Up Type=0
Dn Type=3
Dn Slope=0.005
Boundary for River Rch & Prof#=Denton Creek Tri,Reach-1,3
Up Type=0
Dn Type=3
Dn Slope=0.005
Boundary for River Rch & Prof#=Denton Creek Tri,Reach-1,4
Up Type=0
Dn Type=3
Dn Slope=0.005
Boundary for River Rch & Prof#=Denton Creek Tri,Reach-1,5
Up Type=0
Dn Type=3
Dn Slope=0.005
Boundary for River Rch & Prof#=Denton Creek Tri,Reach-1,6
Up Type=0
Dn Type=3
Dn Slope=0.005
Boundary for River Rch & Prof#=Denton Creek Tri,Reach-1,7
Up Type=0
Dn Type=3
Dn Slope=0.005

--- Denton Creek Tributary 17_5.g01 (geometry) ---

Geom Title=Existing Conditions

River Reach=Denton Creek Tri,Reach-1
Reach XY= 30
      2331329.00      7119160.00      2331286.48      7119009.99
      2331427.95      7118799.56      2331432.48      7118311.26
      2331775.55      7118008.75      2331882.62      7117511.50
      2332175.24      7117058.44      2332431.25      7116065.93
      2332576.95      7115854.14      2332530.04      7115520.44
      2332729.21      7115135.09      2332636.68      7114706.30
      2333012.76      7114577.23      2333029.04      7114279.98
      2332837.97      7114066.67      2332921.39      7113956.67
      2332734.47      7113762.45      2332606.16      7113336.42
      2332384.62      7113204.37      2332335.44      7113117.79
      2332084.62      7113004.38      2331985.19      7112867.86
      2331868.92      7112849.56      2331820.51      7112763.53
      2331584.08      7112704.96      2331573.52      7112607.41
      2331386.83      7112416.19      2331375.46      7112261.46
      2331288.71      7112170.75      2330729.00      7111910.00

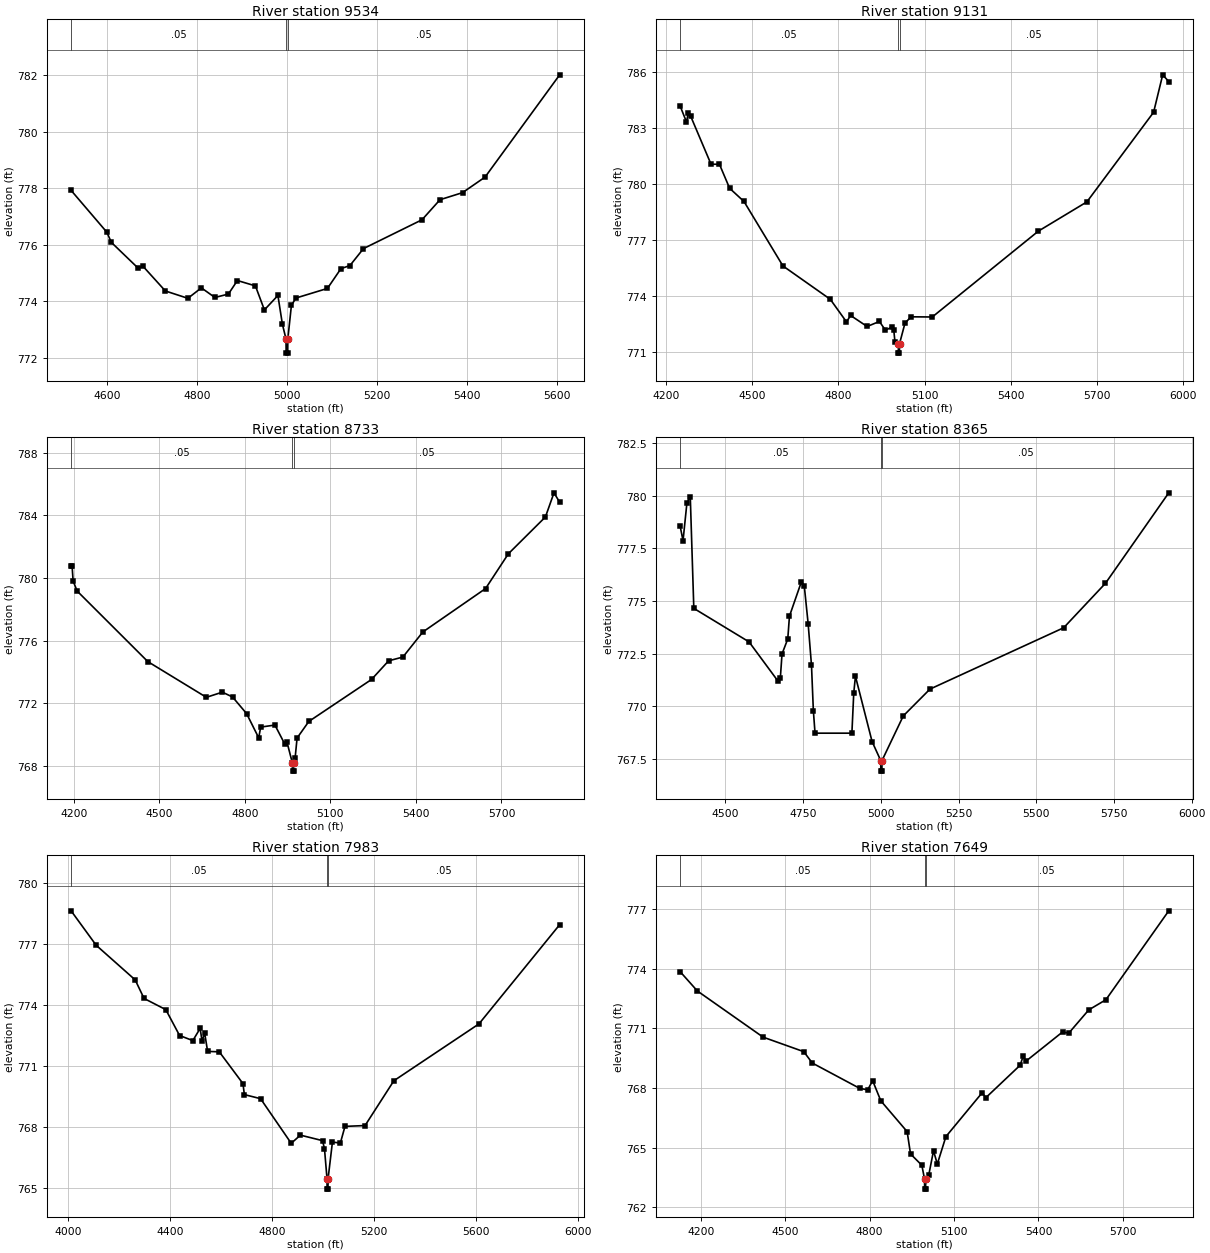
Type RM Length L Ch R = 1,9534,403,403,403
BEGIN DESCRIPTION:
Denton Creek Tributary 17_5 23.0
END DESCRIPTION:
XS GIS Cut Line= 2
      2331798.44      7119049.13      2330713.15      7119054.18
#Sta/Elev= 30
  4520.2  777.92  4599.6  776.44  4609.6  776.08  4669.6  775.16  4679.6  775.24
  4729.6  774.36  4779.6  774.10  4809.6  774.47  4839.6  774.13  4869.6  774.25
  4889.6  774.73  4929.6  774.54  4949.6  773.69  4979.6  774.20  4989.6  773.18
  4997.6  772.66  4997.9  772.16  5001.4  772.16  5001.6  772.66  5009.6  773.85
  5019.6  774.11  5089.6  774.45  5119.6  775.15  5139.6  775.26  5169.7  775.86
  5299.7  776.88  5339.7  777.59  5389.7  777.84  5439.7  778.39  5605.5  782.01
#Mann=3,-1,0
  4520.2    0.05       0  4997.6   0.033       0  5001.6    0.05       0
Bank Sta=4997.6,5001.6
Exp/Cntr=0.3,0.1

Type RM Length L Ch R = 1,9131,398,398,398
BEGIN DESCRIPTION:
Denton Creek Tributary 17_5 22.0
END DESCRIPTION:
XS GIS Cut Line= 3
      2332029.01      7119160.01      2331429.00      7118710.00
      2330529.00      7119010.00
#Sta/Elev= 30
  4250.1  784.18  4272.0  783.33  4278.2  783.79  4286.6  783.64  4357.4  781.06
  4386.6  781.06  4422.0  779.77  4472.0  779.06  4607.4  775.60  4772.0  773.81
  4828.2  772.60  4842.8  772.94  4900.1  772.35  4942.8  772.62  4963.7  772.15
  4986.6  772.32  4992.8  772.15  4997.0  771.50  5008.7  771.42  5008.9  770.92
  5012.4  770.92  5012.7  771.42  5031.7  772.53  5052.8  772.87  5126.6  772.86
  5495.5  777.47  5664.2  779.04  5896.1  783.85  5927.7  785.86  5948.8  785.50
#Mann=3,-1,0
  4250.1    0.05       0  5008.7   0.033       0  5012.7    0.05       0
Bank Sta=5008.7,5012.7
Exp/Cntr=0.3,0.1

Type RM Length L Ch R = 1,8733,368,368,368
BEGIN DESCRIPTION:
Denton Creek Tributary 17_5 21.0
END DESCRIPTION:
XS GIS Cut Line= 3
      2331978.99      7118909.99      2331429.00      7118310.00
      2330529.03      7118310.00
#Sta/Elev= 30
  4190.3  780.80  4193.7  780.80  4197.4  779.81  4211.6  779.17  4459.4  774.67
  4664.8  772.39  4720.9  772.72  4756.7  772.41  4806.0  771.35  4848.5  769.80
  4855.3  770.49  4905.3  770.62  4940.4  769.39  4947.8  769.52  4966.8  768.18
  4967.0  767.68  4970.5  767.68  4970.8  768.18  4976.2  768.52  4983.0  769.79
  5024.2  770.85  5244.2  773.53  5304.2  774.72  5354.2  774.96  5424.2  776.56
  5644.2  779.33  5724.2  781.55  5854.2  783.90  5884.2  785.44  5904.2  784.84
#Mann=3,-1,0
  4190.3    0.05       0  4966.8   0.033       0  4970.8    0.05       0
Bank Sta=4966.8,4970.8
Exp/Cntr=0.3,0.1

Type RM Length L Ch R = 1,8365,382,382,382
BEGIN DESCRIPTION:
Denton Creek Tributary 17_5 20.0
END DESCRIPTION:
XS GIS Cut Line= 3
      2331929.01      7118660.03      2331679.00      7118060.00
      2330778.98      7117860.00
#Sta/Elev= 30
  4354.3  778.54  4363.5  777.86  4376.0  779.65  4386.8  779.95  4398.2  774.65
  4575.9  773.06  4668.5  771.21  4676.6  771.35  4682.0  772.49  4700.5  773.20
  4705.9  774.28  4744.3  775.91  4753.5  775.73  4766.0  773.93  4776.8  771.95
  4782.8  769.80  4788.2  768.73  4906.8  768.73  4912.8  770.64  4918.2  771.43
  4971.8  768.33  4999.6  767.43  4999.9  766.93  5003.4  766.93  5003.6  767.43
  5072.2  769.55  5158.0  770.82  5588.2  773.73  5722.7  775.84  5926.3  780.13
#Mann=3,-1,0
  4354.3    0.05       0  4999.6   0.033       0  5003.6    0.05       0
Bank Sta=4999.6,5003.6
Exp/Cntr=0.3,0.1

Type RM Length L Ch R = 1,7983,334,334,334
BEGIN DESCRIPTION:
Denton Creek Tributary 17_5 19.0
END DESCRIPTION:
XS GIS Cut Line= 3
      2332228.99      7118659.97      2331829.00      7117760.00
      2330929.03      7117510.01
#Sta/Elev= 30
  4010.9  778.62  4109.4  776.93  4262.6  775.23  4297.4  774.32  4382.9  773.77
  4437.0  772.50  4489.0  772.25  4517.7  772.85  4525.2  772.23  4535.5  772.62
  4547.1  771.72  4592.9  771.70  4685.9  770.14  4691.4  769.60  4755.0  769.40
  4875.4  767.21  4911.6  767.61  4998.4  767.34  5006.1  766.94  5016.1  765.46
  5016.3  764.96  5019.8  764.96  5020.1  765.46  5037.3  767.27  5068.4  767.22
  5086.6  768.04  5165.4  768.08  5278.6  770.28  5612.8  773.07  5929.8  777.94
#Mann=3,-1,0
  4010.9    0.05       0  5016.1   0.033       0  5020.1    0.05       0
Bank Sta=5016.1,5020.1
Exp/Cntr=0.3,0.1

Type RM Length L Ch R = 1,7649,293,293,293
BEGIN DESCRIPTION:
Denton Creek Tributary 17_5 18.0
END DESCRIPTION:
XS GIS Cut Line= 3
      2332279.00      7118260.00      2331929.00      7117460.00
      2331079.05      7117310.01
#Sta/Elev= 30
  4126.8  773.85  4188.0  772.88  4421.5  770.56  4566.1  769.83  4596.2  769.26
  4764.2  767.99  4793.0  767.91  4810.9  768.37  4839.8  767.36  4933.4  765.81
  4945.4  764.69  4985.6  764.12  4995.3  763.42  4995.5  762.92  4999.0  762.92
  4999.3  763.42  5010.2  763.63  5027.1  764.85  5040.6  764.18  5071.1  765.56
  5199.7  767.76  5213.3  767.52  5335.1  769.15  5345.3  769.59  5355.4  769.35
  5485.7  770.82  5507.7  770.76  5578.8  771.93  5639.7  772.44  5863.1  776.91
#Mann=3,-1,0
  4126.8    0.05       0  4995.3   0.033       0  4999.3    0.05       0
Bank Sta=4995.3,4999.3
Exp/Cntr=0.3,0.1

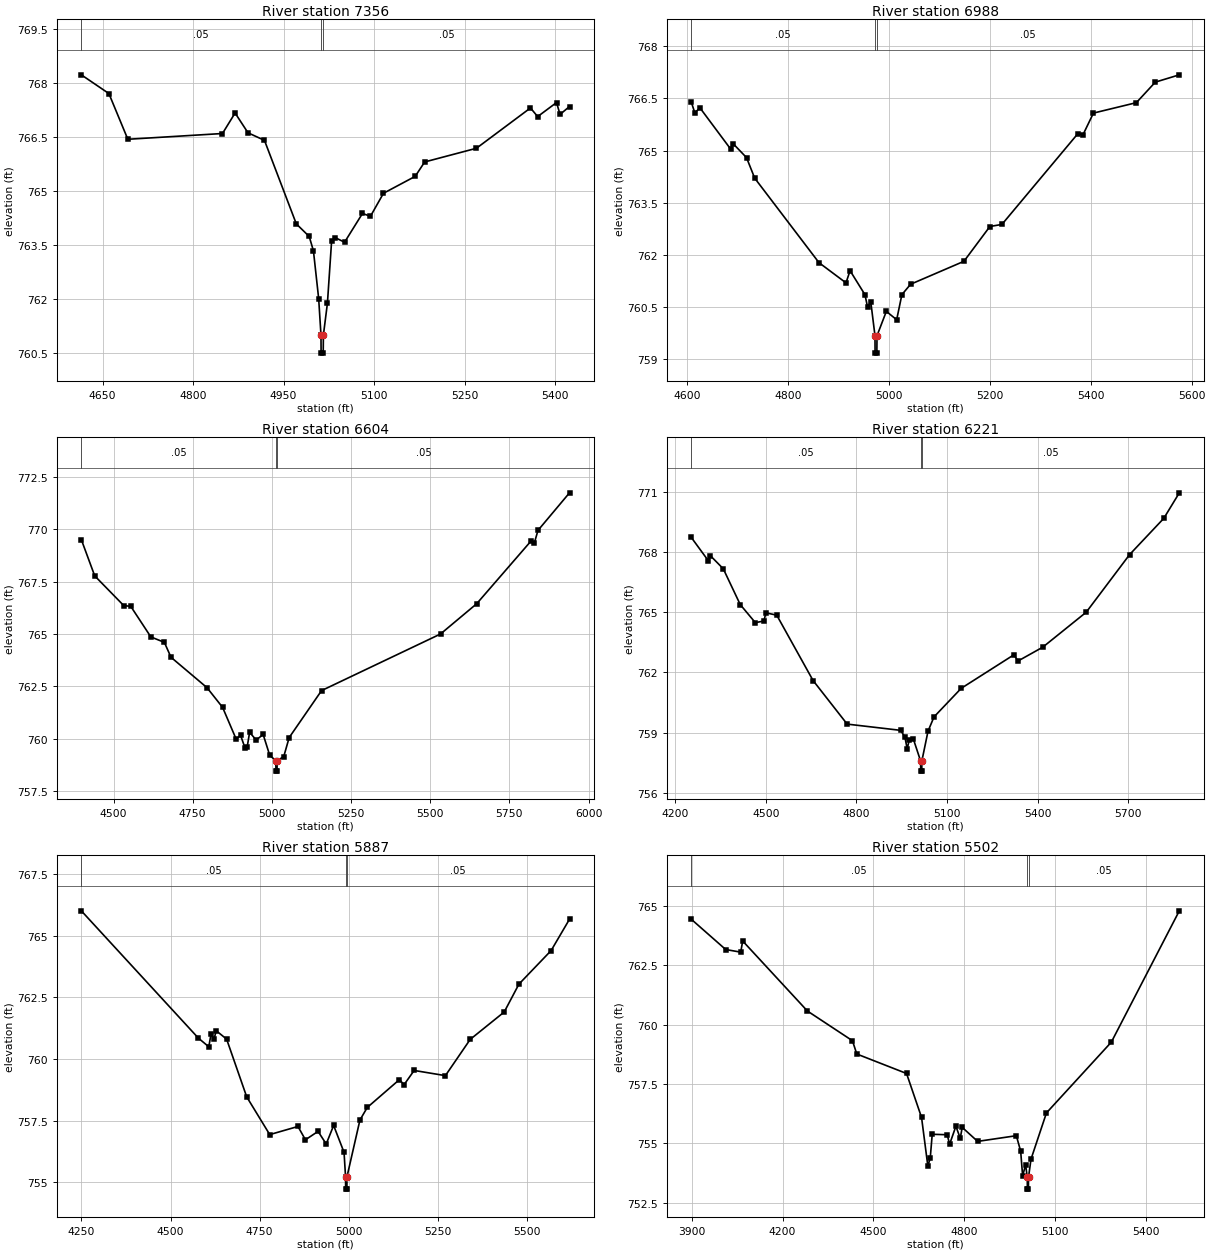
Type RM Length L Ch R = 1,7356,368,368,368
BEGIN DESCRIPTION:
Mapping XS 4b0e8114
END DESCRIPTION:
XS GIS Cut Line= 3
      2332264.13      7117523.73      2332193.93      7117294.37
      2331703.23      7117005.45
#Sta/Elev= 30
  4614.7  768.23  4660.4  767.71  4691.8  766.44  4848.7  766.60  4869.6  767.17
  4891.0  766.62  4918.3  766.41  4971.1  764.09  4992.5  763.74  4999.5  763.34
  5008.2  762.01  5012.0  761.00  5012.2  760.50  5015.7  760.50  5016.0  761.00
  5022.7  761.89  5029.6  763.61  5035.4  763.71  5051.1  763.58  5080.8  764.38
  5094.0  764.30  5115.6  764.94  5168.2  765.41  5183.9  765.81  5269.7  766.19
  5359.3  767.31  5371.2  767.07  5402.5  767.46  5408.3  767.13  5424.0  767.35
#Mann=3,-1,0
  4614.7    0.05       0  5012.0   0.033       0  5016.0    0.05       0
Bank Sta=5012,5016
Exp/Cntr=0.3,0.1

Type RM Length L Ch R = 1,6988,384,384,384
BEGIN DESCRIPTION:
Mapping XS d416ce1d
END DESCRIPTION:
XS GIS Cut Line= 2
      2332576.02      7116983.56      2331633.04      7116765.31
#Sta/Elev= 30
  4607.7  766.41  4614.9  766.09  4625.2  766.23  4685.8  765.05  4691.0  765.20
  4717.5  764.80  4733.7  764.21  4861.2  761.78  4914.7  761.20  4922.8  761.55
  4952.3  760.86  4957.4  760.51  4963.9  760.65  4972.2  759.68  4972.4  759.18
  4975.9  759.18  4976.2  759.68  4994.7  760.38  5015.2  760.14  5025.5  760.86
  5042.8  761.16  5148.6  761.82  5200.0  762.82  5223.9  762.88  5374.5  765.49
  5384.7  765.46  5405.3  766.08  5490.4  766.38  5528.0  766.97  5575.6  767.18
#Mann=3,-1,0
  4607.7    0.05       0  4972.2   0.033       0  4976.2    0.05       0
Bank Sta=4972.2,4976.2
Exp/Cntr=0.3,0.1

Type RM Length L Ch R = 1,6604,383,383,383
BEGIN DESCRIPTION:
Denton Creek Tributary 17_5 15.0
END DESCRIPTION:
XS GIS Cut Line= 3
      2332729.02      7117010.02      2332329.00      7116560.00
      2331479.02      7116160.01
#Sta/Elev= 30
  4398.4  769.50  4440.7  767.77  4532.6  766.35  4554.4  766.32  4617.9  764.86
  4660.6  764.60  4681.5  763.89  4795.2  762.44  4844.5  761.50  4887.2  759.99
  4901.4  760.16  4915.6  759.55  4922.3  759.63  4929.8  760.31  4950.7  759.94
  4972.5  760.21  4993.4  759.21  5012.7  758.96  5012.9  758.46  5016.4  758.46
  5016.7  758.96  5037.5  759.15  5054.7  760.06  5157.0  762.30  5532.7  765.00
  5646.7  766.44  5818.3  769.43  5829.1  769.35  5840.4  769.94  5939.9  771.73
#Mann=3,-1,0
  4398.4    0.05       0  5012.7   0.033       0  5016.7    0.05       0
Bank Sta=5012.7,5016.7
Exp/Cntr=0.3,0.1

Type RM Length L Ch R = 1,6221,334,334,334
BEGIN DESCRIPTION:
Denton Creek Tributary 17_5 14.0
END DESCRIPTION:
XS GIS Cut Line= 3
      2332928.99      7116759.99      2332429.00      7116210.00
      2331579.01      7116010.00
#Sta/Elev= 30
  4252.5  768.73  4308.9  767.57  4316.3  767.81  4358.9  767.16  4415.0  765.38
  4465.0  764.48  4493.4  764.56  4500.1  764.97  4536.0  764.85  4656.2  761.60
  4769.1  759.43  4946.1  759.12  4960.3  758.79  4967.8  758.20  4974.5  758.62
  4988.7  758.67  5012.4  757.59  5012.7  757.09  5016.2  757.09  5016.4  757.59
  5036.9  759.08  5056.8  759.79  5146.7  761.21  5321.3  762.88  5334.8  762.57
  5417.0  763.26  5560.8  765.00  5704.6  767.87  5817.6  769.67  5869.0  770.94
#Mann=3,-1,0
  4252.5    0.05       0  5012.4   0.033       0  5016.4    0.05       0
Bank Sta=5012.4,5016.4
Exp/Cntr=0.3,0.1

Type RM Length L Ch R = 1,5887,385,385,385
BEGIN DESCRIPTION:
Denton Creek Tributary 17_5 13.0
END DESCRIPTION:
XS GIS Cut Line= 3
      2332979.02      7116510.02      2332529.00      7115910.00
      2331928.99      7115760.00
#Sta/Elev= 30
  4250.0  766.01  4578.2  760.85  4607.3  760.50  4613.6  761.01  4621.9  760.81
  4628.2  761.15  4657.3  760.81  4713.6  758.47  4778.2  756.94  4857.3  757.27
  4878.2  756.73  4913.6  757.07  4936.5  756.56  4957.3  757.31  4986.5  756.22
  4990.7  755.23  4991.0  754.73  4994.5  754.73  4994.7  755.23  5031.0  757.53
  5051.6  758.04  5141.8  759.17  5154.6  758.96  5183.0  759.54  5270.6  759.33
  5340.2  760.80  5435.5  761.91  5476.8  763.04  5567.0  764.40  5618.5  765.67
#Mann=3,-1,0
  4250.0    0.05       0  4990.7   0.033       0  4994.7    0.05       0
Bank Sta=4990.7,4994.7
Exp/Cntr=0.3,0.1

Type RM Length L Ch R = 1,5502,352,352,352
BEGIN DESCRIPTION:
Denton Creek Tributary 17_5 12.0
END DESCRIPTION:
XS GIS Cut Line= 3
      2333229.03      7116410.03      2332529.00      7115560.00
      2332028.98      7115460.00
#Sta/Elev= 30
  3898.3  764.44  4012.4  763.16  4061.9  763.05  4068.4  763.52  4282.1  760.57
  4430.6  759.32  4445.0  758.76  4609.2  757.94  4658.7  756.09  4679.5  754.04
  4687.4  754.38  4693.9  755.38  4743.4  755.36  4751.3  754.96  4772.1  755.72
  4786.4  755.21  4792.9  755.67  4843.8  755.08  4971.5  755.32  4985.8  754.67
  4992.3  753.62  5002.0  754.10  5007.7  753.57  5007.9  753.07  5011.4  753.07
  5011.7  753.57  5019.9  754.33  5070.9  756.28  5285.0  759.26  5509.4  764.79
#Mann=3,-1,0
  3898.3    0.05       0  5007.7   0.033       0  5011.7    0.05       0
Bank Sta=5007.7,5011.7
Exp/Cntr=0.3,0.1

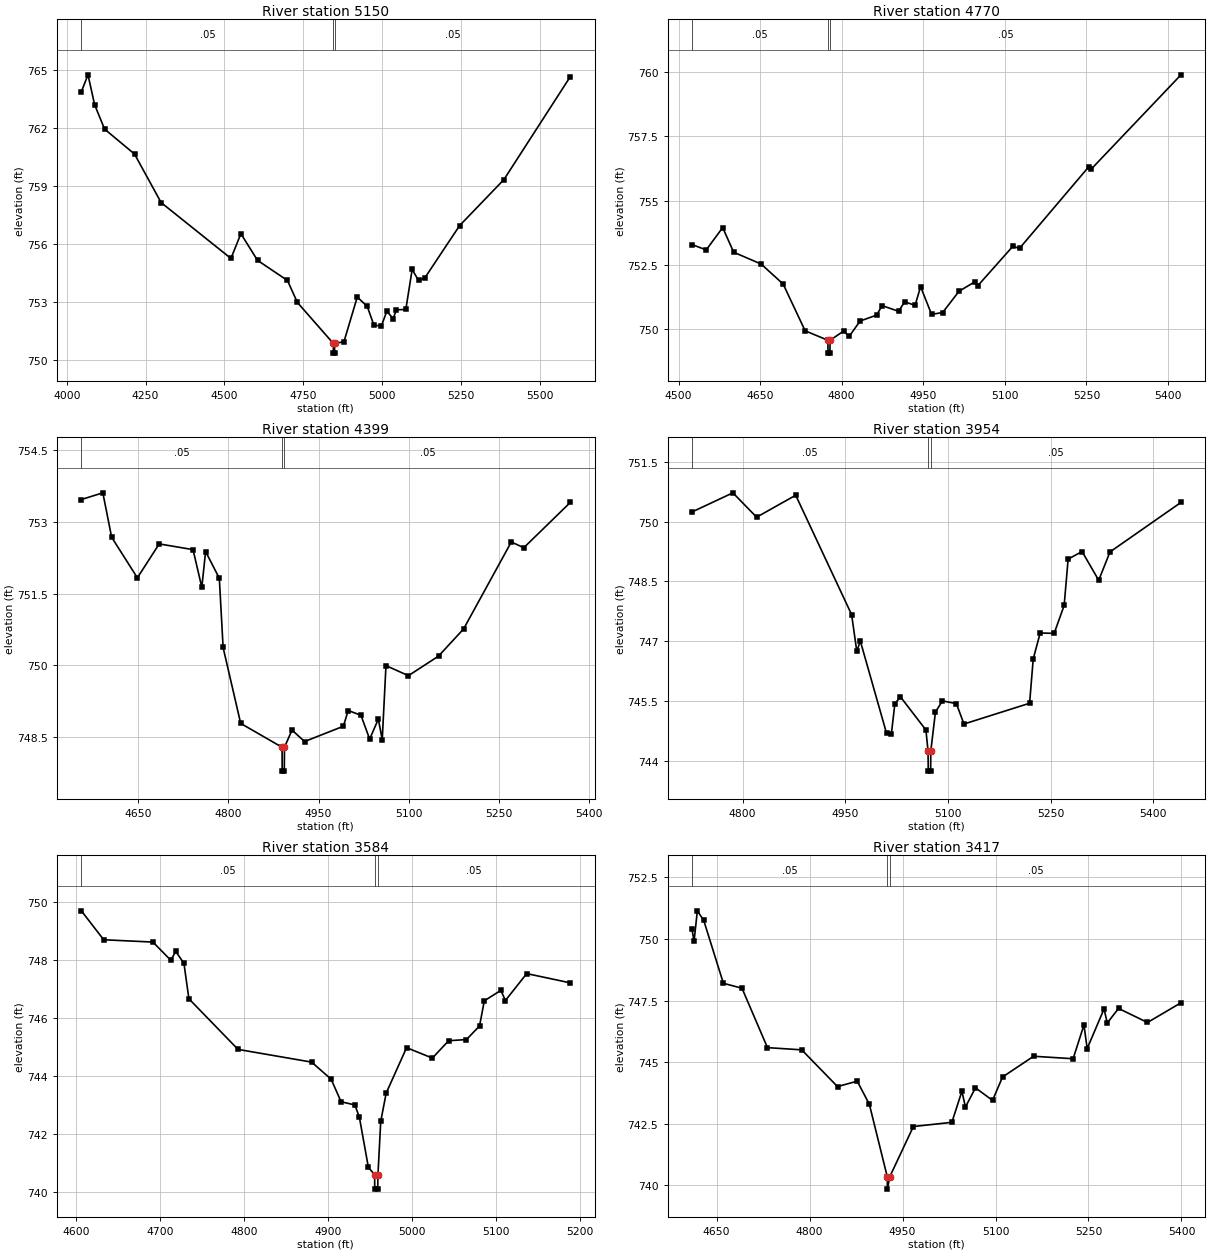
Type RM Length L Ch R = 1,5150,380,380,380
BEGIN DESCRIPTION:
Denton Creek Tributary 17_5 11.0
END DESCRIPTION:
XS GIS Cut Line= 3
      2333578.96      7115559.99      2332679.00      7115260.00
      2332079.02      7115210.00
#Sta/Elev= 30
  4046.5  763.88  4067.5  764.75  4088.6  763.20  4120.2  761.94  4215.1  760.65
  4299.4  758.14  4520.8  755.25  4552.4  756.53  4605.1  755.15  4700.0  754.11
  4731.6  752.97  4845.6  750.85  4845.8  750.35  4849.3  750.35  4849.6  750.85
  4879.2  750.94  4921.4  753.25  4953.0  752.77  4974.1  751.80  4997.7  751.75
  5015.2  752.52  5035.3  752.13  5045.3  752.59  5075.4  752.61  5095.5  754.68
  5115.6  754.11  5135.6  754.24  5246.0  756.95  5386.5  759.33  5597.2  764.66
#Mann=3,-1,0
  4046.5    0.05       0  4845.6   0.033       0  4849.6    0.05       0
Bank Sta=4845.6,4849.6
Exp/Cntr=0.3,0.1

Type RM Length L Ch R = 1,4770,371,371,371
BEGIN DESCRIPTION:
Mapping XS 44becfe7
END DESCRIPTION:
XS GIS Cut Line= 2
      2333154.87      7114981.55      2332265.31      7114850.27
#Sta/Elev= 30
  4524.7  753.29  4550.9  753.08  4581.2  753.95  4601.4  752.99  4651.9  752.53
  4692.4  751.75  4732.8  749.93  4774.7  749.56  4774.9  749.06  4778.4  749.06
  4778.7  749.56  4803.6  749.92  4813.7  749.71  4833.9  750.31  4864.2  750.54
  4874.3  750.91  4904.6  750.69  4915.9  751.06  4935.0  750.92  4945.1  751.65
  4965.3  750.57  4985.6  750.64  5015.8  751.47  5045.1  751.84  5050.1  751.68
  5114.7  753.22  5127.0  753.14  5254.0  756.31  5259.0  756.23  5423.9  759.90
#Mann=3,-1,0
  4524.7    0.05       0  4774.7   0.033       0  4778.7    0.05       0
Bank Sta=4774.7,4778.7
Exp/Cntr=0.3,0.1

Type RM Length L Ch R = 1,4399,445,445,445
BEGIN DESCRIPTION:
Mapping XS 5cd70754
END DESCRIPTION:
XS GIS Cut Line= 2
      2333123.44      7114925.76      2332473.90      7114437.14
#Sta/Elev= 30
  4555.7  753.47  4591.4  753.61  4606.0  752.68  4648.8  751.83  4685.1  752.54
  4741.3  752.42  4755.9  751.63  4762.2  752.38  4785.0  751.82  4791.3  750.37
  4820.5  748.78  4889.3  748.28  4889.5  747.78  4893.0  747.78  4893.3  748.28
  4905.8  748.64  4926.7  748.40  4991.2  748.72  4999.2  749.05  5020.4  748.95
  5034.9  748.45  5049.3  748.87  5055.8  748.44  5062.0  749.99  5099.3  749.78
  5149.4  750.19  5191.1  750.76  5270.3  752.58  5291.1  752.46  5368.5  753.41
#Mann=3,-1,0
  4555.7    0.05       0  4889.3   0.033       0  4893.3    0.05       0
Bank Sta=4889.3,4893.3
Exp/Cntr=0.3,0.1

Type RM Length L Ch R = 1,3954,370,370,370
BEGIN DESCRIPTION:
Mapping XS 83b54eea
END DESCRIPTION:
XS GIS Cut Line= 2
      2333297.57      7114463.71      2332597.43      7114320.72
#Sta/Elev= 30
  4725.9  750.24  4785.7  750.72  4820.4  750.11  4877.5  750.66  4959.2  747.67
  4966.8  746.75  4971.9  747.01  5010.2  744.70  5017.3  744.68  5022.4  745.44
  5030.6  745.61  5067.8  744.78  5070.9  744.25  5071.2  743.75  5074.7  743.75
  5074.9  744.25  5081.7  745.23  5091.9  745.51  5112.3  745.44  5123.4  744.93
  5219.3  745.45  5224.6  746.56  5234.8  747.21  5255.2  747.20  5269.8  747.90
  5275.6  749.06  5296.0  749.25  5320.3  748.53  5336.8  749.24  5440.5  750.48
#Mann=3,-1,0
  4725.9    0.05       0  5070.9   0.033       0  5074.9    0.05       0
Bank Sta=5070.9,5074.9
Exp/Cntr=0.3,0.1

Type RM Length L Ch R = 1,3584,167,167,167
BEGIN DESCRIPTION:
Mapping XS 2102e641
END DESCRIPTION:
XS GIS Cut Line= 3
      2333215.13      7114289.63      2332940.33      7114127.21
      2332692.48      7114038.37
#Sta/Elev= 30
  4606.6  749.71  4633.2  748.71  4691.8  748.63  4713.2  748.00  4719.0  748.31
  4728.8  747.89  4734.7  746.67  4793.2  744.92  4880.9  744.48  4904.1  743.89
  4916.0  743.11  4932.4  743.00  4937.8  742.57  4948.5  740.84  4955.9  740.59
  4956.1  740.09  4959.6  740.09  4959.9  740.59  4963.2  742.43  4969.7  743.41
  4994.0  744.98  5024.7  744.62  5044.1  745.22  5065.3  745.26  5080.9  745.73
  5086.6  746.60  5106.3  746.96  5111.7  746.61  5137.1  747.54  5189.1  747.22
#Mann=3,-1,0
  4606.6    0.05       0  4955.9   0.033       0  4959.9    0.05       0
Bank Sta=4955.9,4959.9
Exp/Cntr=0.3,0.1

Type RM Length L Ch R = 1,3417,332,332,332
BEGIN DESCRIPTION:
Mapping XS bb3084b0
END DESCRIPTION:
XS GIS Cut Line= 4
      2333287.47      7114075.74      2332936.04      7113992.10
      2332759.48      7113896.60      2332542.96      7113828.69
#Sta/Elev= 30
  4610.3  750.39  4613.7  749.91  4619.0  751.14  4629.3  750.75  4661.0  748.20
  4691.0  748.00  4732.1  745.59  4787.4  745.50  4845.1  744.01  4876.9  744.23
  4896.5  743.29  4925.4  740.35  4925.6  739.85  4929.4  740.35  4967.5  742.39
  5029.6  742.56  5045.8  743.82  5051.5  743.18  5067.7  743.96  5095.2  743.45
  5111.4  744.40  5161.5  745.24  5225.2  745.14  5242.7  746.51  5247.9  745.55
  5275.1  747.16  5280.3  746.59  5298.5  747.18  5345.2  746.61  5399.2  747.41
#Mann=3,-1,0
  4610.3    0.05       0  4925.4   0.033       0  4929.4    0.05       0
Bank Sta=4925.4,4929.4
Exp/Cntr=0.3,0.1

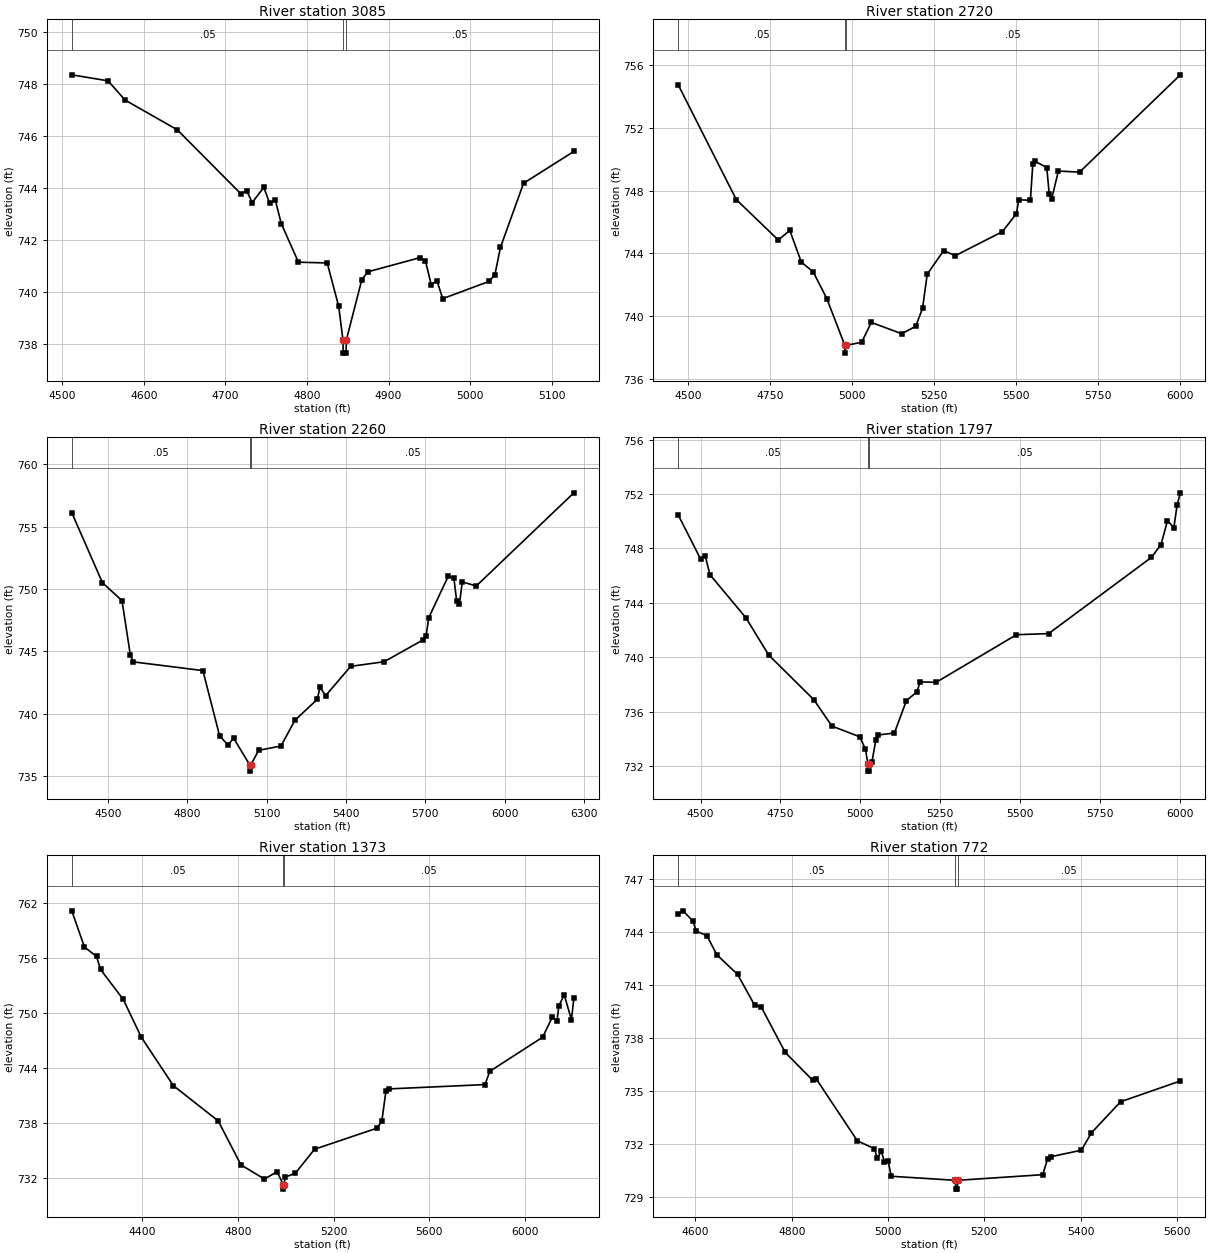
Type RM Length L Ch R = 1,3085,365,365,365
BEGIN DESCRIPTION:
Mapping XS e4fec761
END DESCRIPTION:
XS GIS Cut Line= 2
      2333065.37      7113373.68      2332640.97      7113819.06
#Sta/Elev= 30
  4511.8  748.34  4556.2  748.11  4577.2  747.37  4641.1  746.23  4718.8  743.78
  4726.0  743.90  4732.9  743.44  4747.1  744.02  4754.3  743.41  4761.2  743.53
  4768.5  742.63  4789.5  741.15  4824.8  741.12  4838.9  739.45  4844.1  738.16
  4844.4  737.66  4847.9  737.66  4848.2  738.16  4867.2  740.48  4874.5  740.78
  4938.0  741.32  4945.2  741.20  4952.2  740.29  4959.4  740.43  4966.3  739.75
  5022.9  740.41  5030.2  740.66  5037.1  741.72  5065.4  744.18  5127.0  745.40
#Mann=3,-1,0
  4511.8    0.05       0  4844.1   0.035       0  4848.2    0.05       0
Bank Sta=4844.1,4848.2
Exp/Cntr=0.3,0.1

Type RM Length L Ch R = 1,2720,460,460,460
BEGIN DESCRIPTION:
Denton Creek Tributary 17_5 6.0
END DESCRIPTION:
XS GIS Cut Line= 3
      2332979.01      7113009.99      2332629.00      7113410.00
      2332029.01      7114209.98
#Sta/Elev= 30
  4469.0  754.75  4646.0  747.43  4774.2  744.85  4809.3  745.46  4844.4  743.44
  4880.5  742.82  4922.2  741.11  4977.1  738.13  4977.4  737.63  4981.2  738.13
  5028.6  738.32  5057.8  739.59  5150.5  738.87  5193.2  739.34  5214.1  740.48
  5228.6  742.67  5278.6  744.17  5314.1  743.85  5457.8  745.38  5500.5  746.53
  5507.8  747.42  5543.2  747.38  5550.5  749.69  5557.8  749.87  5593.2  749.47
  5600.5  747.80  5607.8  747.45  5628.6  749.25  5693.2  749.18  6000.5  755.39
#Mann=3,-1,0
  4469.0    0.05       0  4977.1    0.04       0  4981.2    0.05       0
Bank Sta=4977.1,4981.2
Exp/Cntr=0.3,0.1

Type RM Length L Ch R = 1,2260,463,463,463
BEGIN DESCRIPTION:
Denton Creek Tributary 17_5 5.0
END DESCRIPTION:
XS GIS Cut Line= 3
      2332929.05      7112909.98      2332329.00      7113110.00
      2331929.00      7114309.99
#Sta/Elev= 30
  4363.7  756.12  4479.7  750.50  4553.5  749.07  4585.1  744.70  4595.6  744.16
  4859.2  743.46  4922.4  738.23  4954.0  737.49  4975.1  738.05  5036.3  735.90
  5036.6  735.40  5040.4  735.90  5070.0  737.07  5154.3  737.41  5207.0  739.48
  5291.4  741.15  5301.9  742.12  5323.0  741.45  5417.8  743.80  5544.3  744.17
  5691.9  745.93  5702.4  746.21  5713.0  747.71  5786.8  751.04  5807.9  750.85
  5818.4  749.02  5828.9  748.82  5839.5  750.57  5892.2  750.24  6261.1  757.71
#Mann=3,-1,0
  4363.7    0.05       0  5036.3   0.033       0  5040.4    0.05       0
Bank Sta=5036.3,5040.4
Exp/Cntr=0.3,0.1

Type RM Length L Ch R = 1,1797,424,424,424
BEGIN DESCRIPTION:
Denton Creek Tributary 17_5 4.0
END DESCRIPTION:
XS GIS Cut Line= 3
      2332378.97      7112460.03      2331979.00      7112860.00
      2331879.00      7113859.97
#Sta/Elev= 30
  4430.2  750.46  4500.9  747.19  4515.0  747.43  4529.2  746.08  4642.3  742.89
  4713.0  740.17  4854.4  736.88  4911.0  734.94  4998.4  734.15  5015.9  733.23
  5023.9  732.13  5024.2  731.63  5027.8  731.63  5028.1  732.13  5036.0  732.29
  5048.6  733.95  5056.1  734.29  5106.4  734.43  5144.1  736.82  5176.7  737.45
  5186.8  738.19  5237.0  738.16  5488.3  741.66  5588.8  741.74  5910.4  747.34
  5940.5  748.29  5960.6  750.03  5980.7  749.54  5990.8  751.20  6000.8  752.09
#Mann=3,-1,0
  4430.2    0.05       0  5023.9   0.033       0  5028.1    0.05       0
Bank Sta=5023.9,5028.1
Exp/Cntr=0.3,0.1

Type RM Length L Ch R = 1,1373,601,601,601
BEGIN DESCRIPTION:
Denton Creek Tributary 17_5 3.0
END DESCRIPTION:
XS GIS Cut Line= 3
      2332028.99      7111910.01      2331629.00      7112710.00
      2331729.00      7113910.03
#Sta/Elev= 30
  4105.1  761.11  4158.2  757.17  4208.5  756.15  4225.3  754.74  4320.3  751.47
  4395.8  747.36  4529.9  742.09  4717.2  738.26  4812.2  733.48  4910.1  731.94
  4963.2  732.72  4989.0  731.34  4989.3  730.84  4993.3  731.34  4996.7  732.14
  5039.7  732.57  5119.9  735.18  5380.8  737.47  5400.9  738.21  5418.5  741.55
  5431.0  741.74  5832.4  742.21  5852.5  743.66  6073.2  747.36  6113.4  749.53
  6133.4  749.15  6141.0  750.78  6163.5  751.96  6193.6  749.28  6203.7  751.59
#Mann=3,-1,0
  4105.1    0.05       0  4989.0   0.033       0  4993.3    0.05       0
Bank Sta=4989,4993.3
Exp/Cntr=0.3,0.1

Type RM Length L Ch R = 1,772,199,199,199
BEGIN DESCRIPTION:
Denton Creek Tributary 17_5 2.0
END DESCRIPTION:
XS GIS Cut Line= 3
      2331644.01      7111911.75      2331233.56      7112409.28
      2331173.89      7112802.70
#Sta/Elev= 30
  4564.2  745.05  4574.2  745.22  4595.0  744.63  4601.5  744.07  4623.7  743.81
  4644.5  742.72  4687.5  741.61  4722.7  739.87  4737.0  739.74  4786.5  737.18
  4843.9  735.59  4850.3  735.70  4936.4  732.16  4971.5  731.72  4978.0  731.16
  4985.9  731.59  4992.4  730.98  5000.2  731.00  5006.7  730.15  5140.1  729.92
  5140.4  729.42  5144.0  729.42  5144.4  729.92  5321.2  730.24  5331.3  731.13
  5338.0  731.26  5401.7  731.63  5422.3  732.61  5483.0  734.38  5607.1  735.56
#Mann=3,-1,0
  4564.2    0.05       0  5140.1   0.033       0  5144.4    0.05       0
Bank Sta=5140.1,5144.4
Exp/Cntr=0.3,0.1

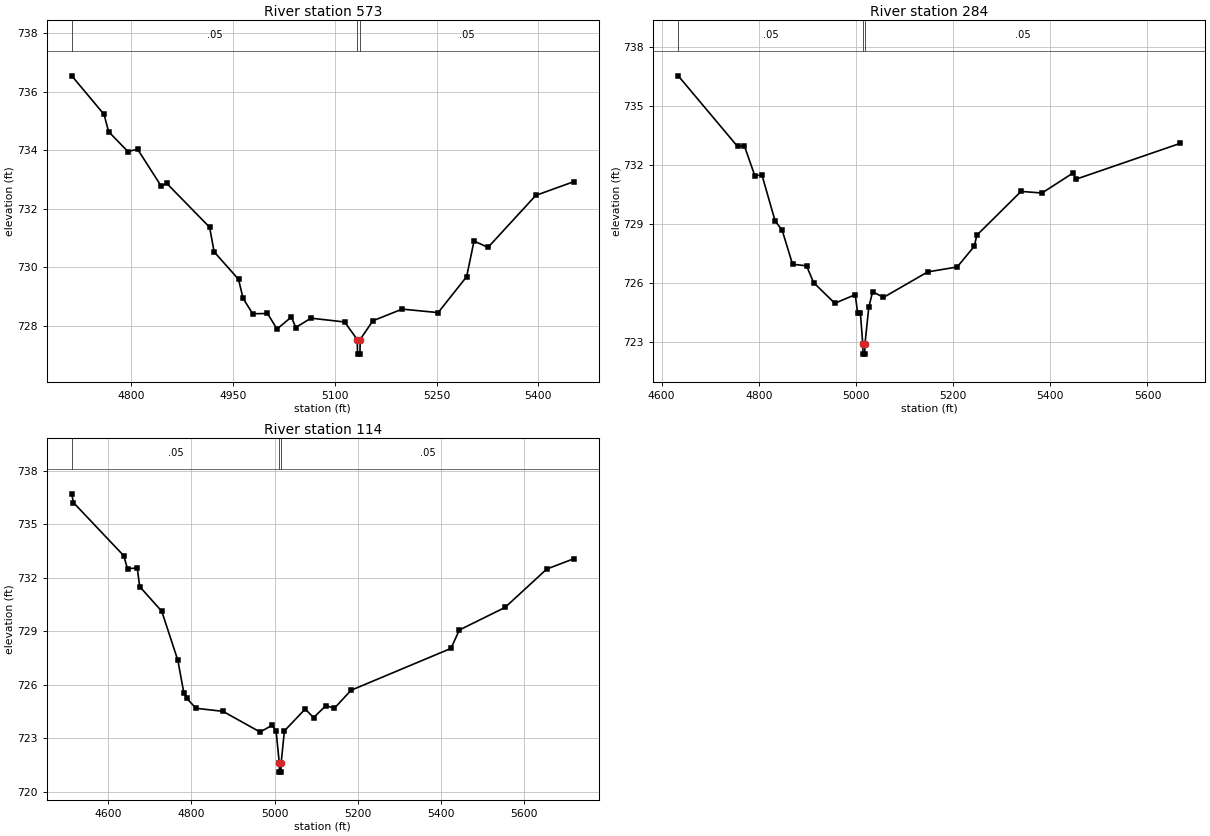
Type RM Length L Ch R = 1,573,289,289,289
BEGIN DESCRIPTION:
Mapping XS e1ed6f7c
END DESCRIPTION:
XS GIS Cut Line= 4
      2331398.62      7111922.80      2331194.23      7112154.90
      2331067.20      7112313.43      2330997.50      7112530.50
#Sta/Elev= 30
  4712.0  736.55  4759.6  735.23  4766.3  734.64  4794.8  733.96  4809.0  734.04
  4844.1  732.77  4851.7  732.88  4915.3  731.37  4921.9  730.53  4957.9  729.59
  4964.6  728.94  4978.8  728.41  5000.6  728.42  5014.7  727.89  5035.9  728.30
  5042.3  727.94  5064.7  728.26  5114.3  728.13  5133.0  727.53  5133.4  727.03
  5137.0  727.03  5137.3  727.53  5156.0  728.17  5199.2  728.57  5252.3  728.45
  5294.3  729.68  5305.2  730.90  5325.8  730.68  5396.3  732.46  5452.4  732.93
#Mann=3,-1,0
  4712.0    0.05       0  5133.0   0.033       0  5137.3    0.05       0
Bank Sta=5133,5137.3
Exp/Cntr=0.3,0.1

Type RM Length L Ch R = 1,284,170,170,170
BEGIN DESCRIPTION:
Mapping XS 1f00b1b1
END DESCRIPTION:
XS GIS Cut Line= 3
      2331268.37      7111799.70      2330968.39      7112020.70
      2330872.22      7112674.26
#Sta/Elev= 30
  4634.4  736.54  4756.5  732.94  4770.2  732.99  4792.0  731.45  4806.6  731.49
  4833.7  729.15  4848.3  728.67  4869.6  726.94  4898.4  726.86  4913.1  726.00
  4956.6  724.95  4998.7  725.39  5003.5  724.46  5009.2  724.46  5014.2  722.86
  5014.6  722.36  5018.2  722.36  5018.6  722.86  5026.5  724.74  5034.4  725.54
  5056.8  725.25  5147.8  726.55  5208.4  726.80  5243.5  727.85  5248.9  728.42
  5339.8  730.65  5383.0  730.57  5447.6  731.60  5452.7  731.27  5667.6  733.10
#Mann=3,-1,0
  4634.4    0.05       0  5014.2   0.033       0  5018.6    0.05       0
Bank Sta=5014.2,5018.6
Exp/Cntr=0.3,0.1

Type RM Length L Ch R = 1,114,0,0,0
BEGIN DESCRIPTION:
Denton Creek Tributary 17_5 1.0
END DESCRIPTION:
XS GIS Cut Line= 3
      2331264.15      7111762.05      2330824.95      7111945.17
      2330846.15      7112675.03
#Sta/Elev= 30
  4513.0  736.71  4516.9  736.22  4637.8  733.24  4646.9  732.51  4670.3  732.55
  4676.1  731.51  4729.2  730.12  4767.8  727.37  4782.3  725.53  4789.4  725.23
  4811.5  724.68  4876.1  724.51  4965.3  723.35  4993.8  723.72  5003.7  723.43
  5011.5  721.60  5011.9  721.10  5015.5  721.10  5015.9  721.60  5023.7  723.41
  5073.7  724.64  5093.7  724.16  5123.7  724.83  5143.7  724.68  5183.7  725.69
  5423.9  728.04  5443.9  729.07  5553.9  730.34  5653.9  732.49  5719.0  733.07
#Mann=3,-1,0
  4513.0    0.05       0  5011.5   0.033       0  5015.9    0.05       0
Bank Sta=5011.5,5015.9
Exp/Cntr=0.3,0.1

Chan Stop Cuts=-1