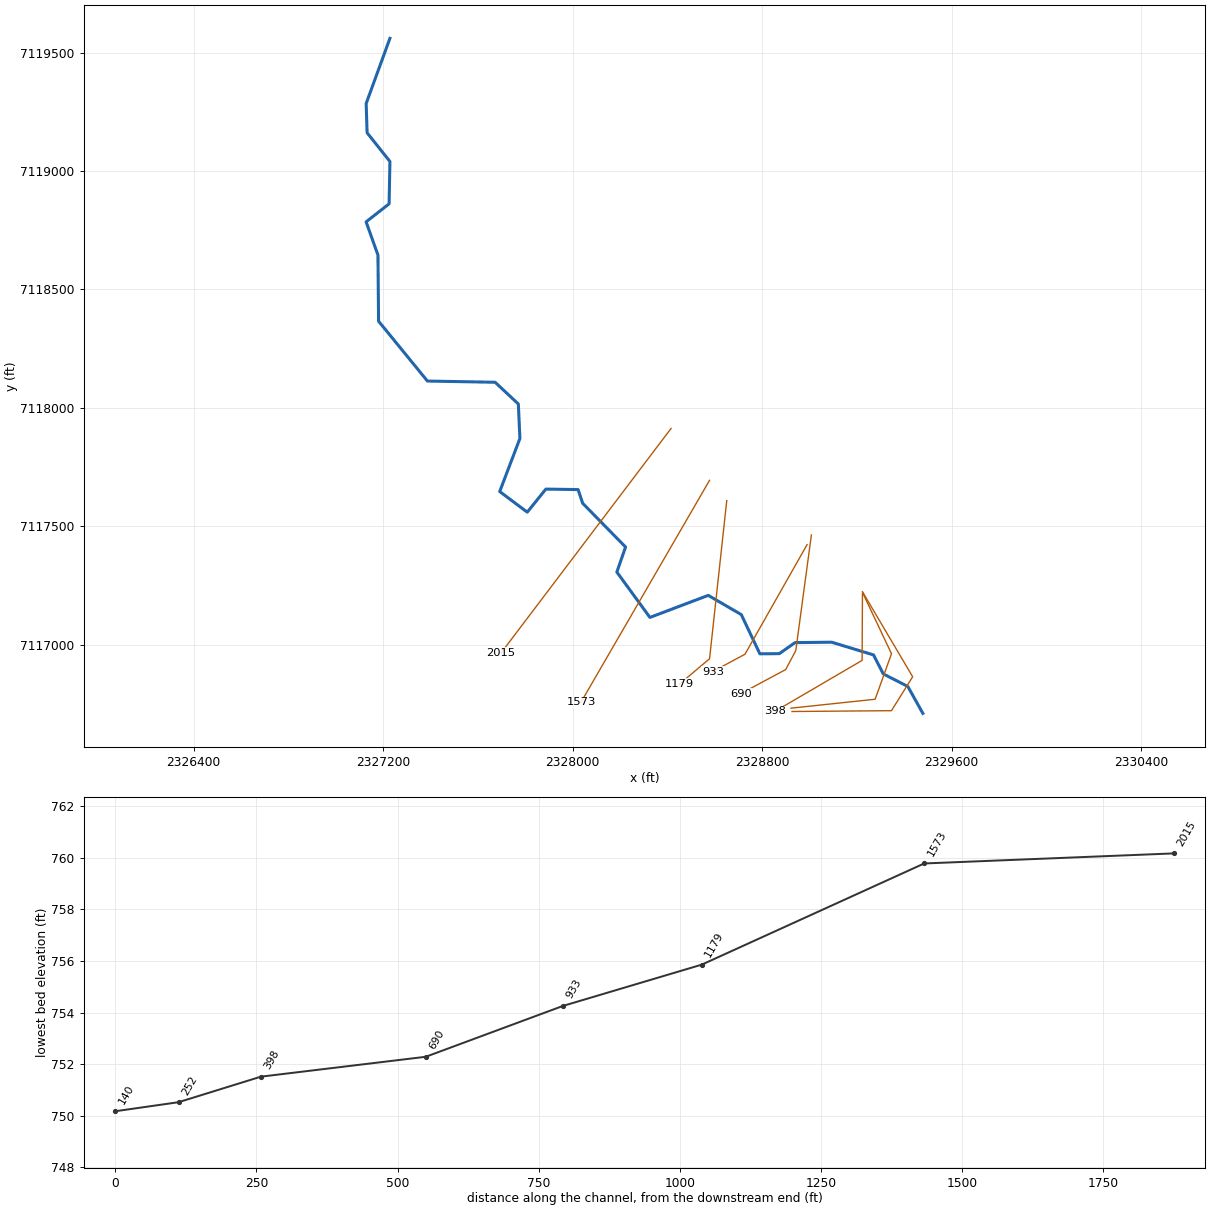
--- Denton Creek Tributary 17_6.prj (project) ---

Proj Title=Denton Creek Tributary 17_6 Base Level Engineering
Current Plan=p01
Default Exp/Contr=0.3,0.1
English Units
Geom File=g01
Flow File=f01
Plan File=p01
BEGIN DESCRIPTION:
Denton Creek Tributary 17_6
END DESCRIPTION:

--- Denton Creek Tributary 17_6.p01 (plan) ---

Plan Title=Multiple Run
Short Identifier=Multiple
Geom File=g01
Flow File=f01
Subcritical Flow
K Sum by GR= 0
Std Step Tol= 0.01
Critical Tol= 0.01
Num of Std Step Trials= 20
Max Error Tol= 0.3
Flow Tol Ratio= 0.001
Split Flow NTrial= 30
Split Flow Tol= 0.02
Split Flow Ratio= 0.02
Log Output Level= 0
Friction Slope Method= 1
Unsteady Friction Slope Method= 2
Unsteady Bridges Friction Slope Method= 1
Parabolic Critical Depth
Global Vel Dist=  1 , 1 , 1
Global Log Level= 0
CheckData=True
Encroach Param= -1, 0, 0, 0
BEGIN DESCRIPTION:
Multiple Run
END DESCRIPTION:

--- Denton Creek Tributary 17_6.f01 (steady flow) ---

Flow Title=Multiple
Number of Profiles=7
Profile Names=10-year,25-year,50-year,1pct_min,100-year,1pct_plu,500-year
River Rch & RM= Denton Creek Tri,Reach-1,2015
     460     613     737     440     877    1750    1245
Boundary for River Rch & Prof#=Denton Creek Tri,Reach-1,1
Up Type=0
Dn Type=3
Dn Slope=0.005
Boundary for River Rch & Prof#=Denton Creek Tri,Reach-1,2
Up Type=0
Dn Type=3
Dn Slope=0.005
Boundary for River Rch & Prof#=Denton Creek Tri,Reach-1,3
Up Type=0
Dn Type=3
Dn Slope=0.005
Boundary for River Rch & Prof#=Denton Creek Tri,Reach-1,4
Up Type=0
Dn Type=3
Dn Slope=0.005
Boundary for River Rch & Prof#=Denton Creek Tri,Reach-1,5
Up Type=0
Dn Type=3
Dn Slope=0.005
Boundary for River Rch & Prof#=Denton Creek Tri,Reach-1,6
Up Type=0
Dn Type=3
Dn Slope=0.005
Boundary for River Rch & Prof#=Denton Creek Tri,Reach-1,7
Up Type=0
Dn Type=3
Dn Slope=0.005

--- Denton Creek Tributary 17_6.g01 (geometry) ---

Geom Title=Existing Conditions

River Reach=Denton Creek Tri,Reach-1
Reach XY= 30
      2327229.00      7119560.00      2327128.77      7119285.07
      2327132.54      7119161.47      2327229.04      7119040.01
      2327225.52      7118861.26      2327128.48      7118785.12
      2327178.48      7118644.79      2327181.06      7118365.85
      2327387.30      7118113.07      2327673.16      7118107.95
      2327771.20      7118016.21      2327777.80      7117870.51
      2327692.52      7117646.58      2327808.93      7117559.49
      2327887.32      7117656.92      2328023.55      7117654.83
      2328042.74      7117597.05      2328223.89      7117412.29
      2328187.07      7117306.69      2328326.69      7117115.08
      2328572.89      7117208.21      2328712.51      7117127.05
      2328790.85      7116961.50      2328872.94      7116962.13
      2328939.50      7117008.78      2329094.18      7117010.43
      2329270.65      7116956.81      2329312.00      7116876.59
      2329415.58      7116823.60      2329479.00      7116710.00

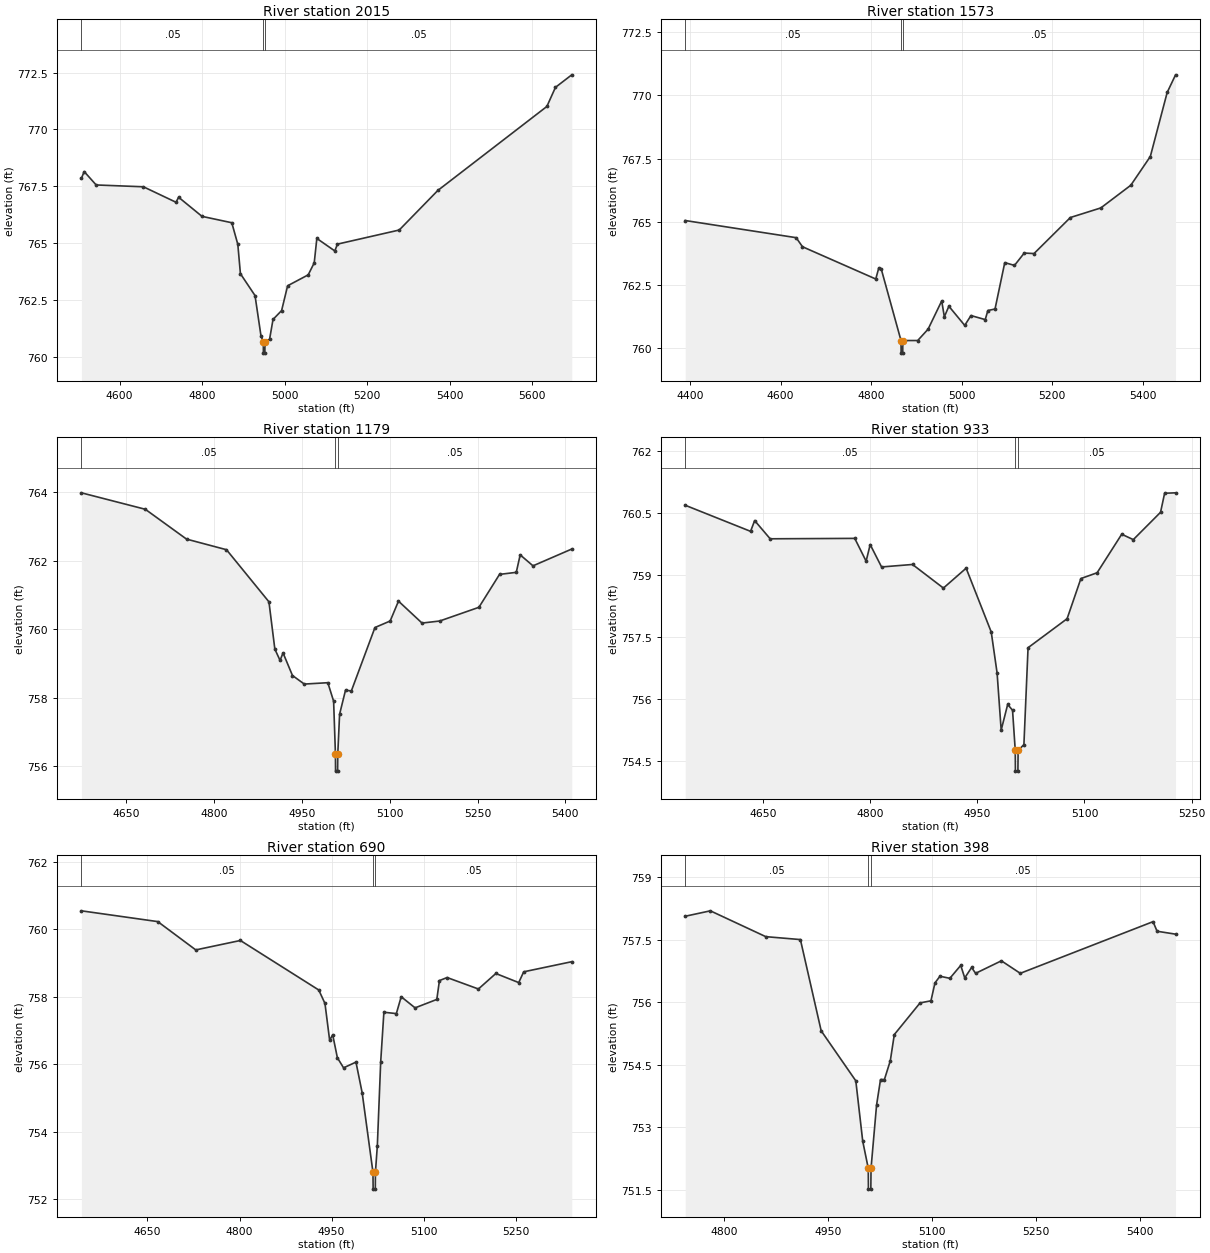
Type RM Length L Ch R = 1,2015,442,442,442
BEGIN DESCRIPTION:
Mapping XS a9b2bf3e
END DESCRIPTION:
XS GIS Cut Line= 2
      2328415.95      7117912.98      2327698.61      7116965.62
#Sta/Elev= 30
  4507.5  767.85  4514.1  768.15  4543.2  767.56  4657.7  767.48  4736.7  766.80
  4743.0  767.02  4799.7  766.18  4871.9  765.90  4886.5  764.95  4892.8  763.66
  4928.2  762.70  4942.7  760.92  4948.3  760.67  4948.5  760.17  4952.0  760.17
  4952.3  760.67  4963.5  760.78  4971.8  761.65  4992.6  762.04  5007.2  763.13
  5057.1  763.61  5071.7  764.14  5078.0  765.21  5121.6  764.66  5127.9  764.96
  5277.7  765.58  5371.3  767.32  5635.5  771.01  5656.3  771.85  5695.8  772.40
#Mann=3,-1,0
  4507.5    0.05       0  4948.3    0.04       0  4952.3    0.05       0
Bank Sta=4948.3,4952.3
Exp/Cntr=0.3,0.1

Type RM Length L Ch R = 1,1573,394,394,394
BEGIN DESCRIPTION:
Mapping XS d0217467
END DESCRIPTION:
XS GIS Cut Line= 2
      2328578.51      7117693.98      2328035.78      7116757.25
#Sta/Elev= 30
  4389.6  765.04  4634.5  764.36  4648.5  764.00  4810.3  762.72  4816.8  763.15
  4822.5  763.11  4866.0  760.28  4866.3  759.78  4869.8  759.78  4870.0  760.28
  4902.9  760.28  4925.8  760.73  4955.9  761.85  4961.7  761.22  4971.7  761.64
  5006.7  760.88  5020.5  761.27  5052.0  761.11  5057.8  761.47  5073.6  761.53
  5095.1  763.37  5116.6  763.26  5138.1  763.75  5159.7  763.73  5240.0  765.16
  5307.2  765.54  5373.4  766.44  5416.5  767.58  5453.7  770.12  5472.2  770.82
#Mann=3,-1,0
  4389.6    0.05       0  4866.0    0.04       0  4870.0    0.05       0
Bank Sta=4866,4870
Exp/Cntr=0.3,0.1

Type RM Length L Ch R = 1,1179,246,246,246
BEGIN DESCRIPTION:
Mapping XS c89dd9c1
END DESCRIPTION:
XS GIS Cut Line= 3
      2328651.12      7117608.42      2328578.48      7116940.57
      2328451.60      7116833.82
#Sta/Elev= 30
  4573.4  763.98  4682.5  763.50  4752.9  762.63  4821.2  762.32  4893.7  760.80
  4903.8  759.42  4912.7  759.09  4917.8  759.31  4933.9  758.65  4954.1  758.40
  4994.3  758.44  5004.2  757.90  5007.3  756.36  5007.5  755.86  5011.0  755.86
  5011.3  756.36  5014.4  757.52  5024.5  758.22  5034.5  758.20  5074.8  760.05
  5100.8  760.24  5115.0  760.82  5155.2  760.18  5185.4  760.24  5252.4  760.64
  5287.6  761.60  5316.2  761.66  5322.9  762.17  5344.8  761.85  5411.0  762.34
#Mann=3,-1,0
  4573.4    0.05       0  5007.3    0.04       0  5011.3    0.05       0
Bank Sta=5007.3,5011.3
Exp/Cntr=0.3,0.1

Type RM Length L Ch R = 1,933,243,243,243
BEGIN DESCRIPTION:
Mapping XS 74607c2a
END DESCRIPTION:
XS GIS Cut Line= 3
      2328990.27      7117422.37      2328728.05      7116959.72
      2328592.44      7116886.74
#Sta/Elev= 30
  4541.6  760.68  4633.0  760.05  4638.7  760.31  4660.4  759.87  4778.7  759.88
  4794.6  759.33  4800.3  759.73  4816.2  759.19  4859.5  759.25  4902.7  758.68
  4934.5  759.16  4969.6  757.62  4977.8  756.63  4983.5  755.25  4992.6  755.87
  4999.4  755.73  5003.2  754.76  5003.4  754.26  5006.9  754.26  5007.2  754.76
  5015.3  754.90  5021.1  757.24  5075.7  757.94  5095.0  758.91  5117.7  759.05
  5152.1  759.98  5168.3  759.85  5206.4  760.51  5212.1  760.97  5227.4  760.98
#Mann=3,-1,0
  4541.6    0.05       0  5003.2    0.04       0  5007.2    0.05       0
Bank Sta=5003.2,5007.2
Exp/Cntr=0.3,0.1

Type RM Length L Ch R = 1,690,292,292,292
BEGIN DESCRIPTION:
Mapping XS a477eb77
END DESCRIPTION:
XS GIS Cut Line= 4
      2329008.46      7117463.24      2328942.49      7116974.83
      2328899.90      7116894.93      2328709.99      7116793.05
#Sta/Elev= 30
  4542.4  760.55  4666.8  760.23  4728.7  759.39  4801.4  759.67  4929.1  758.20
  4939.2  757.80  4946.8  756.71  4951.8  756.87  4959.4  756.19  4969.5  755.89
  4989.7  756.06  4999.8  755.15  5017.4  752.79  5017.7  752.29  5021.2  752.29
  5021.4  752.79  5024.5  753.57  5030.0  756.07  5035.2  757.54  5055.5  757.50
  5063.4  758.00  5086.0  757.67  5121.4  757.92  5125.7  758.48  5138.2  758.57
  5189.2  758.23  5217.6  758.69  5254.9  758.42  5263.0  758.74  5341.3  759.04
#Mann=3,-1,0
  4542.4    0.05       0  5017.4    0.04       0  5021.4    0.05       0
Bank Sta=5017.4,5021.4
Exp/Cntr=0.3,0.1

Type RM Length L Ch R = 1,398,146,146,146
BEGIN DESCRIPTION:
Mapping XS 001070b2
END DESCRIPTION:
XS GIS Cut Line= 3
      2329224.01      7117216.27      2329222.53      7116933.64
      2328855.31      7116718.96
#Sta/Elev= 30
  4743.8  758.07  4780.1  758.20  4860.1  757.58  4910.1  757.51  4940.1  755.32
  4990.1  754.12  5000.1  752.67  5008.1  752.02  5008.3  751.52  5011.8  751.52
  5012.1  752.02  5020.1  753.54  5025.8  754.15  5031.4  754.15  5039.9  754.60
  5045.7  755.23  5082.9  755.99  5098.6  756.04  5104.4  756.47  5111.6  756.63
  5125.9  756.58  5141.6  756.89  5147.4  756.59  5157.3  756.84  5163.1  756.70
  5200.3  757.00  5227.6  756.70  5419.3  757.94  5425.1  757.71  5451.8  757.64
#Mann=3,-1,0
  4743.8    0.05       0  5008.1    0.04       0  5012.1    0.05       0
Bank Sta=5008.1,5012.1
Exp/Cntr=0.3,0.1

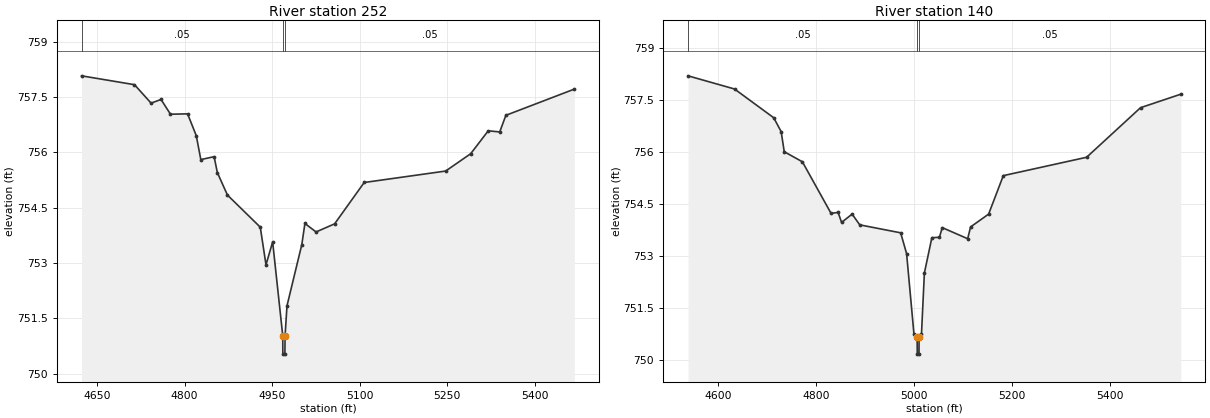
Type RM Length L Ch R = 1,252,112,112,112
BEGIN DESCRIPTION:
Mapping XS ccd87671
END DESCRIPTION:
XS GIS Cut Line= 4
      2329225.63      7117217.75      2329346.65      7116961.79
      2329277.62      7116769.69      2328922.37      7116732.00
#Sta/Elev= 30
  4623.5  758.07  4714.2  757.83  4742.7  757.33  4759.7  757.43  4775.9  757.03
  4805.2  757.04  4820.1  756.45  4827.9  755.80  4850.7  755.88  4856.2  755.45
  4873.5  754.84  4929.8  753.97  4939.6  752.95  4951.0  753.57  4968.3  751.03
  4968.5  750.53  4972.0  750.53  4972.3  751.03  4975.6  751.84  5001.0  753.50
  5006.3  754.07  5025.4  753.84  5057.2  754.06  5107.9  755.18  5247.5  755.49
  5290.4  755.96  5320.5  756.58  5340.2  756.55  5350.7  757.00  5468.0  757.71
#Mann=3,-1,0
  4623.5    0.05       0  4968.3    0.04       0  4972.3    0.05       0
Bank Sta=4968.3,4972.3
Exp/Cntr=0.3,0.1

Type RM Length L Ch R = 1,140,0,0,0
BEGIN DESCRIPTION:
Denton Creek Tributary 17_6 1.0
END DESCRIPTION:
XS GIS Cut Line= 4
      2329223.92      7117223.69      2329436.01      7116864.59
      2329346.50      7116721.36      2328926.77      7116717.90
#Sta/Elev= 30
  4538.7  758.21  4633.6  757.83  4713.6  757.00  4728.8  756.60  4735.1  756.02
  4772.1  755.73  4830.7  754.24  4845.0  754.27  4852.1  753.98  4873.6  754.22
  4889.2  753.91  4972.7  753.68  4984.8  753.08  4999.9  750.75  5006.3  750.68
  5006.6  750.18  5010.1  750.18  5010.3  750.68  5015.2  750.76  5021.1  752.52
  5036.4  753.54  5051.8  753.55  5057.6  753.83  5109.5  753.51  5115.4  753.85
  5152.2  754.22  5182.2  755.33  5352.2  755.86  5462.2  757.29  5544.4  757.68
#Mann=3,-1,0
  4538.7    0.05       0  5006.3    0.04       0  5010.3    0.05       0
Bank Sta=5006.3,5010.3
Exp/Cntr=0.3,0.1

Chan Stop Cuts=-1