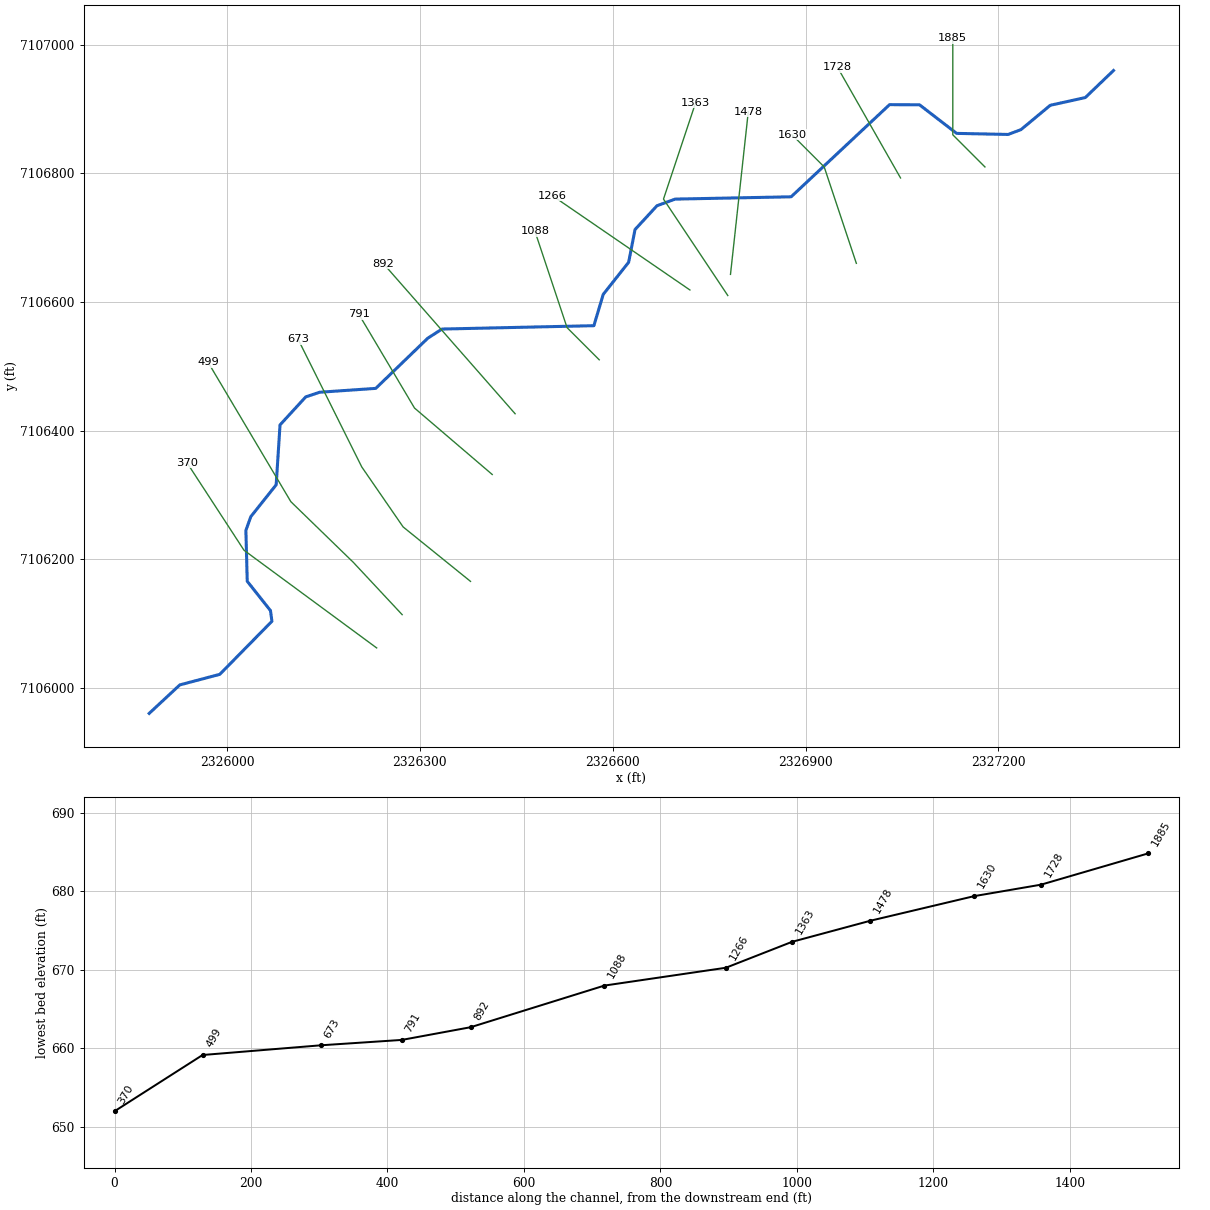
--- Denton Creek Tributary 21.prj (project) ---

Proj Title=Denton Creek Tributary 21 Base Level Engineering
Current Plan=p01
Default Exp/Contr=0.3,0.1
English Units
Geom File=g01
Flow File=f01
Plan File=p01
Y Axis Title=Elevation
X Axis Title(PF)=Main Channel Distance
X Axis Title(XS)=Station
BEGIN DESCRIPTION:
Denton Creek Tributary 21
END DESCRIPTION:
DSS Export Rating Curves= 0
DSS Export Rating Curve Sorted= 0
DSS Export Volume Flow Curves= 0
DXF OffsetX= 0
DXF OffsetY= 0
DXF ScaleX= 1
DXF ScaleY= 10

--- Denton Creek Tributary 21.p01 (plan) ---

Plan Title=Multiple Run
Short Identifier=Multiple
Geom File=g01
Flow File=f01
Subcritical Flow
K Sum by GR= 0
Std Step Tol= 0.01
Critical Tol= 0.01
Num of Std Step Trials= 20
Max Error Tol= 0.3
Flow Tol Ratio= 0.001
Split Flow NTrial= 30
Split Flow Tol= 0.02
Split Flow Ratio= 0.02
Log Output Level= 0
Friction Slope Method= 1
Unsteady Friction Slope Method= 2
Unsteady Bridges Friction Slope Method= 1
Parabolic Critical Depth
Global Vel Dist=  1 , 1 , 1
Global Log Level= 0
CheckData=True
Encroach Param= -1, 0, 0, 0
BEGIN DESCRIPTION:
Multiple Run
END DESCRIPTION:

--- Denton Creek Tributary 21.f01 (steady flow) ---

Flow Title=Multiple
Number of Profiles=7
Profile Names=10-year,25-year,50-year,1pct_min,100-year,1pct_plu,500-year
River Rch & RM= Denton Creek Tri,Reach-1,1885
     262     344     410     244     487     971     685
Boundary for River Rch & Prof#=Denton Creek Tri,Reach-1,1
Up Type=0
Dn Type=3
Dn Slope=0.005
Boundary for River Rch & Prof#=Denton Creek Tri,Reach-1,2
Up Type=0
Dn Type=3
Dn Slope=0.005
Boundary for River Rch & Prof#=Denton Creek Tri,Reach-1,3
Up Type=0
Dn Type=3
Dn Slope=0.005
Boundary for River Rch & Prof#=Denton Creek Tri,Reach-1,4
Up Type=0
Dn Type=3
Dn Slope=0.005
Boundary for River Rch & Prof#=Denton Creek Tri,Reach-1,5
Up Type=0
Dn Type=3
Dn Slope=0.005
Boundary for River Rch & Prof#=Denton Creek Tri,Reach-1,6
Up Type=0
Dn Type=3
Dn Slope=0.005
Boundary for River Rch & Prof#=Denton Creek Tri,Reach-1,7
Up Type=0
Dn Type=3
Dn Slope=0.005

--- Denton Creek Tributary 21.g01 (geometry) ---

Geom Title=Existing Conditions
Program Version=4.10

River Reach=Denton Creek Tri,Reach-1
Reach XY= 30
        2327379.        7106960.      2327335.15      7106917.91
      2327280.69      7106905.92      2327235.06      7106868.03
      2327215.03      7106860.53      2327134.97      7106862.19
      2327077.25      7106906.66      2327030.63      7106906.87
      2326877.54      7106763.54      2326697.11      7106759.96
      2326668.88      7106749.66      2326634.71      7106712.58
      2326624.81      7106661.74      2326585.27      7106611.79
      2326570.72      7106563.06      2326334.45      7106557.82
      2326312.25      7106543.53      2326231.42      7106465.54
      2326144.08      7106459.53       2326122.5      7106452.27
      2326082.51      7106408.75      2326076.52      7106315.57
      2326037.09      7106266.04      2326029.39      7106244.72
       2326031.5      7106165.48      2326067.67      7106119.84
      2326069.88      7106103.24      2325988.76       7106020.7
      2325926.65      7106004.29        2325879.        7105960.

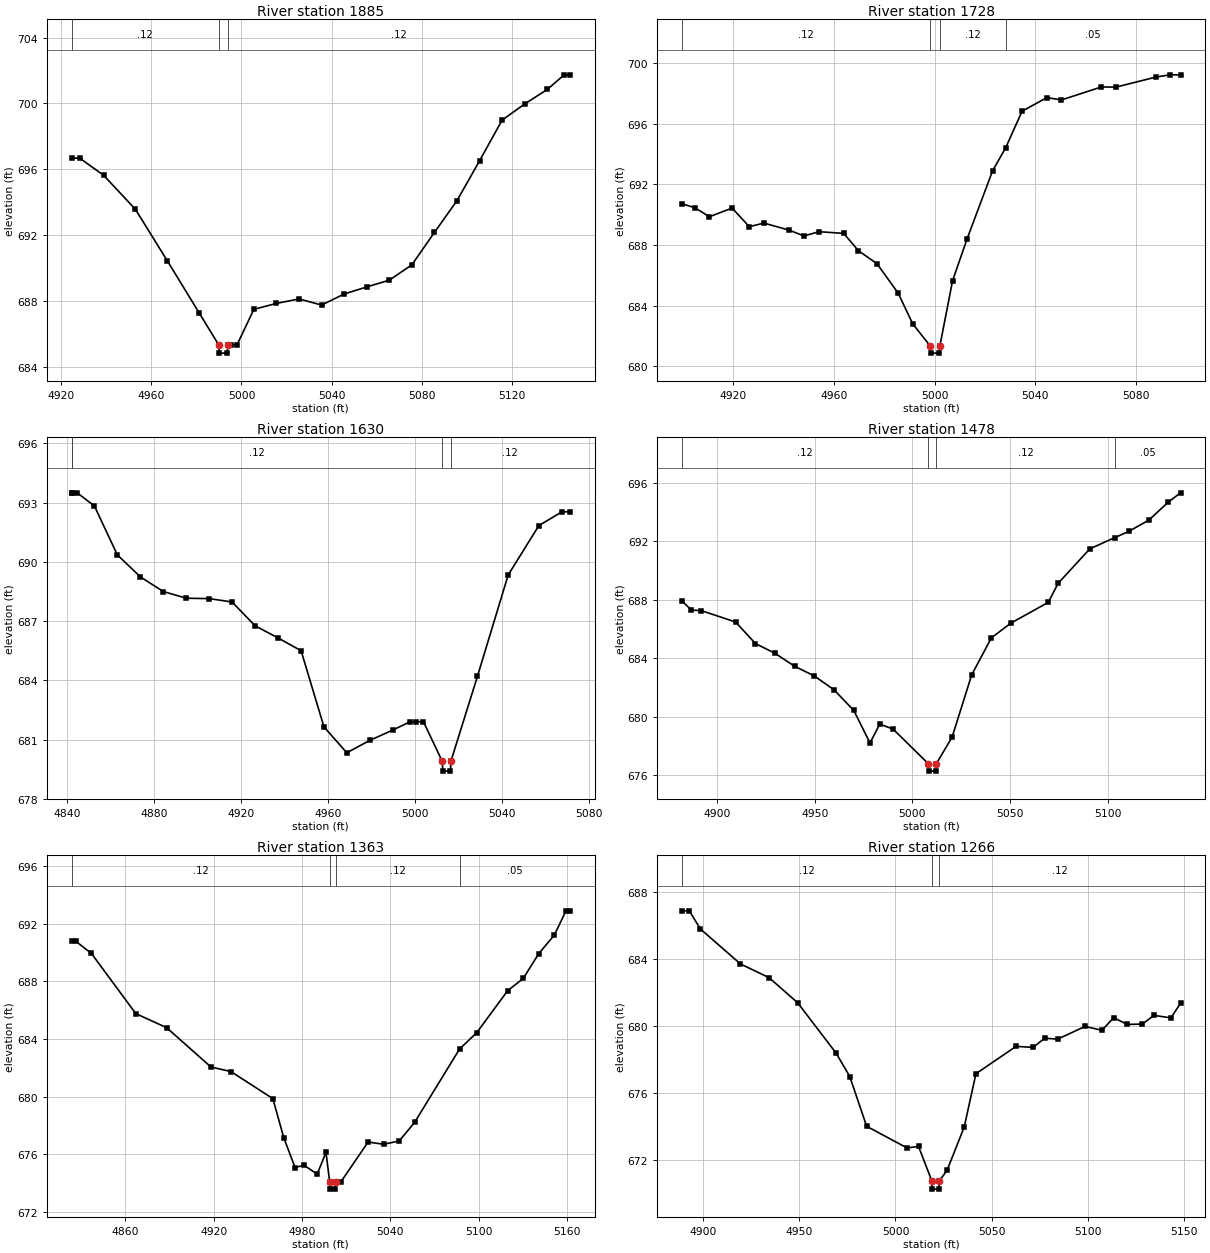
Type RM Length L Ch R = 1 ,1885    ,157,157,157
BEGIN DESCRIPTION:
Denton Creek Tributary 21 6.0
END DESCRIPTION:
XS GIS Cut Line= 3
      2327179.03      7106809.97        2327129.        7106860.
        2327129.      7107010.04
#Sta/Elev= 28
  4924.7  696.68  4928.3  696.68  4938.9  695.64    4953  693.57  4967.2  690.43
  4981.3  687.27  4989.9  685.34  4990.2  684.84  4993.7  684.84  4993.9  685.34
  4995.5  685.34    4998  685.34  5005.5   687.5  5015.5  687.86  5025.5  688.13
  5035.5  687.76  5045.5  688.43  5055.5  688.86  5065.5  689.27  5075.5   690.2
  5085.5  692.17  5095.5   694.1  5105.5  696.52  5115.5  698.99  5125.5  699.97
  5135.5  700.85    5143  701.74  5145.5  701.74
#Mann= 3 ,-1 , 0
  4924.7     .12       0  4989.9     .07       0  4993.9     .12       0
Bank Sta=4989.9,4993.9
XS Rating Curve= 0 ,0
Exp/Cntr=0.3,0.1

Type RM Length L Ch R = 1 ,1728    ,98,98,98
BEGIN DESCRIPTION:
Mapping XS 56a3428d
END DESCRIPTION:
XS GIS Cut Line= 2
      2327047.74      7106792.82      2326949.83      7106964.69
#Sta/Elev= 30
  4899.8  690.71  4904.8  690.45  4910.6  689.86  4919.6  690.43  4926.4   689.2
  4932.2  689.44  4942.3  688.97  4948.1  688.59  4954.1  688.87  4963.9  688.76
  4969.7  687.62  4977.1  686.76  4985.5  684.82  4991.3  682.79  4998.1  681.36
  4998.4  680.86  5001.9  680.86  5002.1  681.36  5007.1  685.63  5012.9  688.41
    5023  692.89  5028.2  694.41  5034.7  696.82  5044.6  697.72  5050.3  697.56
  5066.2  698.42    5072  698.41  5087.8  699.07  5093.4  699.22  5097.6  699.22
#Mann= 4 ,-1 , 0
  4899.8     .12       0  4998.1     .07       0  5002.1     .12       0
  5028.2     .05       0
Bank Sta=4998.1,5002.1
XS Rating Curve= 0 ,0
Exp/Cntr=0.3,0.1

Type RM Length L Ch R = 1 ,1630    ,152,152,152
BEGIN DESCRIPTION:
Denton Creek Tributary 21 5.0
END DESCRIPTION:
XS GIS Cut Line= 3
      2326978.99      7106660.04        2326929.        7106810.
      2326878.98      7106860.02
#Sta/Elev= 29
  4842.2   693.5  4842.6   693.5  4844.8   693.5  4852.7  692.83  4863.2  690.36
  4873.8  689.24  4884.3   688.5  4894.9  688.16  4905.4  688.14  4915.9  687.97
  4926.5  686.76    4937  686.15  4947.6   685.5  4958.1  681.64  4968.6  680.33
  4979.2  680.96  4989.7  681.48  4997.6   681.9  5000.3   681.9  5003.8   681.9
  5012.4   679.9  5012.7   679.4  5016.2   679.4  5016.4   679.9  5028.6  684.21
  5042.7  689.34  5056.8  691.84  5067.4  692.54    5071  692.54
#Mann= 4 ,-1 , 0
  4842.2     .05       0  4842.6     .12       0  5012.4     .07       0
  5016.4     .12       0
Bank Sta=5012.4,5016.4
XS Rating Curve= 0 ,0
Exp/Cntr=0.3,0.1

Type RM Length L Ch R = 1 ,1478    ,115,115,115
BEGIN DESCRIPTION:
Mapping XS 71e725cc
END DESCRIPTION:
XS GIS Cut Line= 2
      2326783.21      7106642.85      2326810.92      7106896.14
#Sta/Elev= 29
  4882.3   687.9    4887   687.3  4892.1  687.26  4909.6  686.48  4919.7  685.01
  4929.7  684.34  4939.8  683.45  4949.8  682.79  4959.9  681.84    4970  680.43
  4978.3   678.2  4983.3  679.49  4990.1  679.15  5008.2  676.77  5008.5  676.27
    5012  676.27  5012.2  676.77  5020.3   678.6  5030.3  682.86  5040.4   685.4
  5050.4  686.41  5069.5  687.83  5074.5  689.13  5090.7  691.49  5103.6  692.27
  5110.8   692.7  5120.9  693.46  5130.9   694.7  5137.1  695.33
#Mann= 4 ,-1 , 0
  4882.3     .12       0  5008.2     .07       0  5012.2     .12       0
  5103.6     .05       0
Bank Sta=5008.2,5012.2
XS Rating Curve= 0 ,0
Exp/Cntr=0.3,0.1

Type RM Length L Ch R = 1 ,1363    ,97,97,97
BEGIN DESCRIPTION:
Denton Creek Tributary 21 4.0
END DESCRIPTION:
XS GIS Cut Line= 3
      2326779.01      7106609.98        2326679.        7106760.
        2326729.      7106909.99
#Sta/Elev= 30
  4823.5  690.77  4826.5  690.77    4837  689.93  4867.1  685.76  4888.1  684.78
  4918.2  682.05  4931.7  681.74  4960.2  679.86  4967.7  677.12  4975.3  675.08
  4981.3  675.24  4990.3  674.62  4996.3  676.13  4998.8  674.08    4999  673.58
  5002.5  673.58  5002.8  674.08  5006.4  674.08  5024.9  676.85  5035.4  676.69
    5046  676.92  5056.5  678.21    5087   683.3  5098.7  684.44  5119.7  687.35
  5130.3   688.2  5140.8  689.92  5151.4  691.21  5159.3  692.89  5161.9  692.89
#Mann= 4 ,-1 , 0
  4823.5     .12       0  4998.8     .07       0  5002.8     .12       0
    5087     .05       0
Bank Sta=4998.8,5002.8
XS Rating Curve= 0 ,0
Exp/Cntr=0.3,0.1

Type RM Length L Ch R = 1 ,1266    ,178,178,178
BEGIN DESCRIPTION:
Mapping XS 62fd06d3
END DESCRIPTION:
XS GIS Cut Line= 2
      2326720.11      7106618.59      2326506.18       7106765.3
#Sta/Elev= 30
    4889  686.89  4892.7  686.89  4898.4  685.81  4919.3  683.72  4934.2   682.9
  4949.1   681.4  4969.2  678.38  4976.2     677    4985  674.03    5006  672.74
    5012  672.83  5018.9  670.78  5019.1  670.28  5022.6  670.28  5022.9  670.78
  5026.9  671.41  5035.8  673.99  5041.9  677.17  5062.8   678.8  5071.7  678.74
  5077.7  679.29  5084.4  679.23  5098.7  679.99  5107.5  679.76  5113.6  680.51
  5120.7  680.11  5128.5  680.13  5134.6  680.65  5143.4   680.5  5148.4  681.37
#Mann= 3 ,-1 , 0
    4889     .12       0  5018.9     .07       0  5022.9     .12       0
Bank Sta=5018.9,5022.9
XS Rating Curve= 0 ,0
Exp/Cntr=0.3,0.1

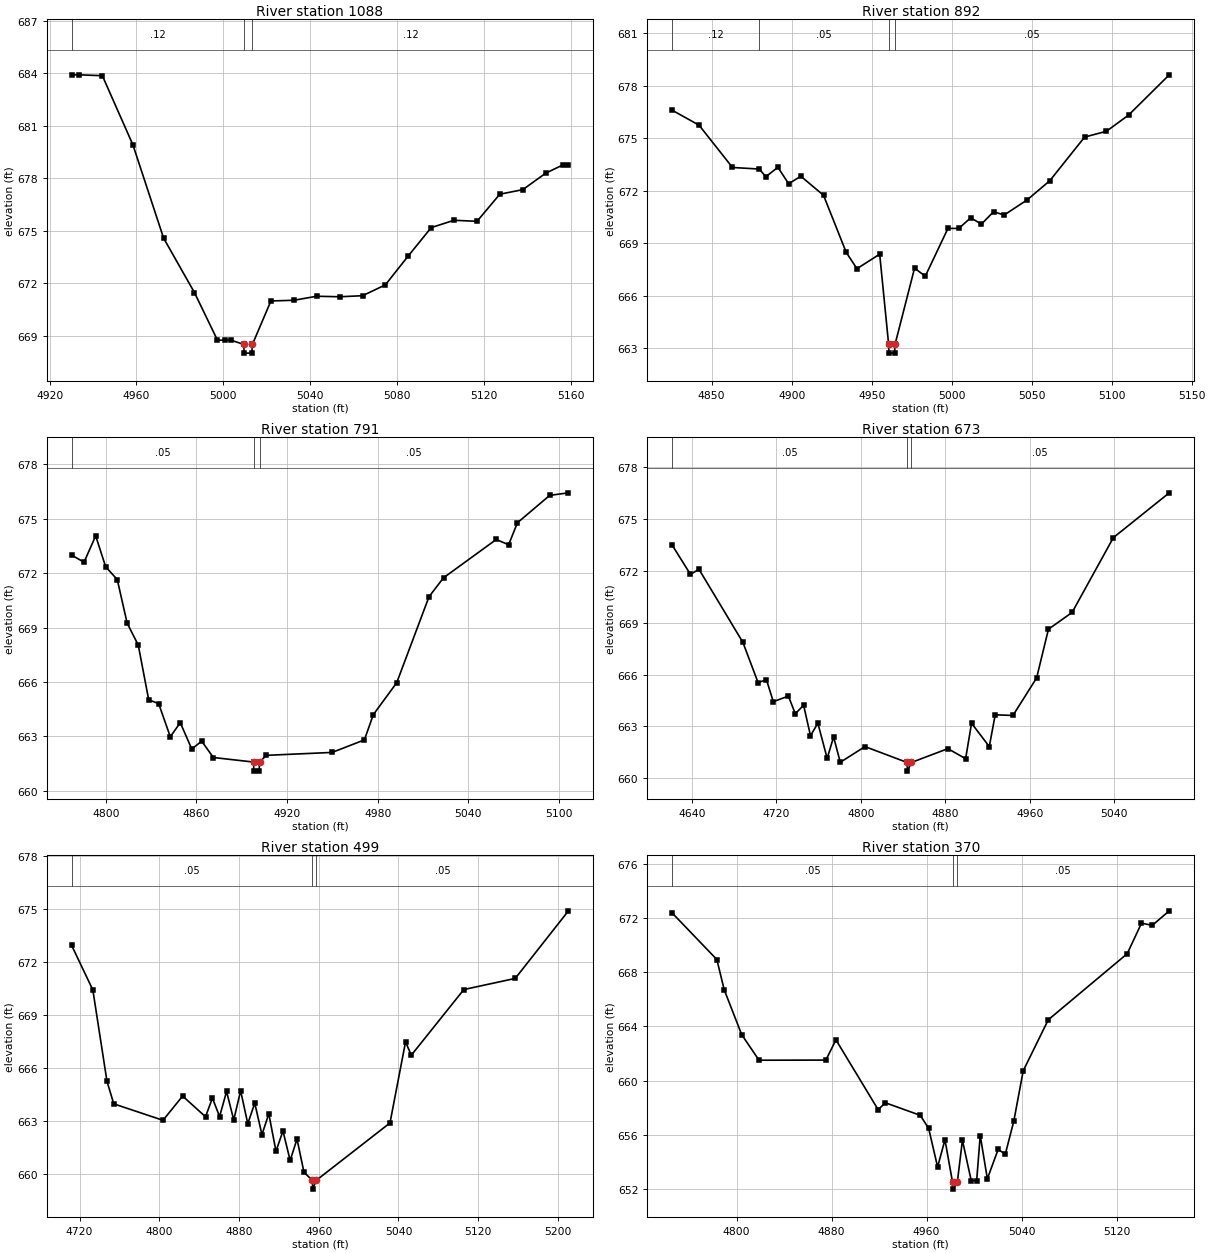
Type RM Length L Ch R = 1 ,1088    ,196,196,196
BEGIN DESCRIPTION:
Denton Creek Tributary 21 3.0
END DESCRIPTION:
XS GIS Cut Line= 3
      2326579.01      7106509.99        2326529.        7106560.
      2326479.01      7106709.96
#Sta/Elev= 28
  4930.1  683.91  4933.7  683.91  4944.3  683.86  4958.4   679.9  4972.5  674.58
  4986.7  671.47  4997.3  668.75  5000.8  668.75  5003.5  668.75  5009.4  668.51
  5009.6  668.01  5013.1  668.01  5013.4  668.51  5021.9  670.99  5032.5  671.03
    5043  671.26  5053.5  671.23  5064.1  671.29  5074.6  671.91  5085.2  673.57
  5095.7  675.18  5106.2   675.6  5116.8  675.54  5127.3  677.09  5137.9  677.35
  5148.4  678.29  5156.3  678.76  5158.9  678.76
#Mann= 3 ,-1 , 0
  4930.1     .12       0  5009.4     .05       0  5013.4     .12       0
Bank Sta=5009.4,5013.4
XS Rating Curve= 0 ,0
Exp/Cntr=0.3,0.1

Type RM Length L Ch R = 1 ,892     ,101,101,101
BEGIN DESCRIPTION:
Mapping XS 918fa806
END DESCRIPTION:
XS GIS Cut Line= 2
      2326448.18      7106426.09      2326243.34      7106659.56
#Sta/Elev= 30
  4825.4   676.6  4842.1  675.75    4863  673.33  4879.8  673.24  4883.8   672.8
  4891.4  673.34  4898.1   672.4  4905.7  672.83  4919.9  671.74  4934.1  668.47
  4940.8  667.54    4955  668.37  4960.6  663.21  4960.8  662.71  4964.3  662.71
  4964.6  663.21  4976.8  667.57  4983.5  667.11  4997.7  669.85  5004.4  669.84
  5011.9  670.45  5018.6  670.09  5026.2   670.8  5032.8  670.61  5047.1  671.47
  5061.3  672.57  5083.1  675.07  5096.7   675.4  5110.6  676.33    5136  678.63
#Mann= 4 ,-1 , 0
  4825.4     .12       0  4879.8     .05       0  4960.6    .033       0
  4964.6     .05       0
Bank Sta=4960.6,4964.6
XS Rating Curve= 0 ,0
Exp/Cntr=0.3,0.1

Type RM Length L Ch R = 1 ,791     ,118,118,118
BEGIN DESCRIPTION:
Mapping XS 4ad0c2b9
END DESCRIPTION:
XS GIS Cut Line= 3
       2326412.6      7106331.58      2326291.69      7106434.96
      2326204.96      7106581.08
#Sta/Elev= 30
  4777.3  672.99  4785.6   672.6  4793.3  674.05  4799.9  672.35  4807.6  671.64
  4814.1  669.25  4821.5  668.03  4828.4  665.02    4835  664.81  4842.7  662.98
  4849.3  663.76  4856.9  662.31  4863.5  662.74  4871.2  661.84  4897.8  661.59
    4898  661.09  4901.5  661.09  4901.8  661.59  4906.3  661.96  4949.8  662.12
  4971.2  662.81  4977.1   664.2  4992.6  665.96    5014   670.7  5023.6  671.74
  5058.5  673.85  5066.7  673.56  5072.5  674.77  5093.9  676.28  5106.3  676.42
#Mann= 3 ,-1 , 0
  4777.3     .05       0  4897.8    .033       0  4901.8     .05       0
Bank Sta=4897.8,4901.8
XS Rating Curve= 0 ,0
Exp/Cntr=0.3,0.1

Type RM Length L Ch R = 1 ,673     ,174,174,174
BEGIN DESCRIPTION:
Mapping XS 8314f058
END DESCRIPTION:
XS GIS Cut Line= 4
      2326378.81      7106165.33      2326273.96      7106250.05
      2326209.58      7106343.45       2326110.4      7106542.35
#Sta/Elev= 30
  4621.5  673.47  4638.7  671.79  4646.7  672.09  4688.3  667.86  4702.7  665.53
  4710.6   665.7  4717.1  664.43  4731.4  664.75  4737.9  663.73  4745.8  664.22
  4752.3  662.46  4759.3  663.18  4768.1  661.15  4774.2  662.39  4780.5  660.92
  4803.9  661.83  4843.8  660.91  4844.1  660.41  4847.8  660.91  4882.4  661.71
  4899.2  661.13  4904.8  663.18  4921.6  661.83  4927.2  663.67    4944  663.63
  4966.4   665.8  4977.6  668.62    5000  669.59  5039.1  673.92    5092  676.51
#Mann= 3 ,-1 , 0
  4621.5     .05       0  4843.8    .033       0  4847.8     .05       0
Bank Sta=4843.8,4847.8
XS Rating Curve= 0 ,0
Exp/Cntr=0.3,0.1

Type RM Length L Ch R = 1 ,499     ,129,129,129
BEGIN DESCRIPTION:
Mapping XS b3763078
END DESCRIPTION:
XS GIS Cut Line= 4
      2326272.51      7106113.54      2326196.39      7106195.06
      2326099.35      7106289.28      2325970.74      7106505.88
#Sta/Elev= 30
  4711.9  672.96  4733.3  670.43  4747.5  665.26  4754.3  663.99  4803.7  663.06
  4823.4  664.43  4846.4  663.26  4853.3  664.32  4860.5  663.27  4867.5  664.69
  4874.7  663.08  4881.6  664.73  4888.8  662.87  4895.8  664.03    4903  662.25
  4909.9  663.43  4917.1  661.31  4924.1  662.46  4931.3  660.79  4938.2     662
  4945.2  660.12  4953.6  659.67  4953.9  659.17  4957.6  659.67  5031.5  662.91
  5047.1  667.49  5052.9  666.74  5105.6  670.45  5157.2  671.08  5210.6   674.9
#Mann= 3 ,-1 , 0
  4711.9     .05       0  4953.6    .033       0  4957.6     .05       0
Bank Sta=4953.6,4957.6
XS Rating Curve= 0 ,0
Exp/Cntr=0.3,0.1

Type RM Length L Ch R = 1 ,370     ,0,0,0
BEGIN DESCRIPTION:
Denton Creek Tributary 21 1.0
END DESCRIPTION:
XS GIS Cut Line= 3
      2326232.86      7106061.77      2326026.45      7106213.78
      2325937.94      7106349.65
#Sta/Elev= 30
  4745.9  672.35  4783.4  668.93  4789.6   666.7  4804.3   663.4  4818.9  661.51
  4875.2  661.52  4883.7  663.01  4919.2  657.87  4925.4  658.37  4954.7  657.45
  4961.8  656.48  4969.3  653.64  4975.5  655.65  4981.9  652.51  4982.2  652.01
  4985.9  652.51  4990.2  655.61  4997.6  652.64  5002.2  652.64  5005.2  655.96
  5011.2  652.77  5020.3  654.94  5026.3  654.58  5033.5  657.03  5041.4  660.73
  5062.5  664.49    5129  669.36    5141  671.61  5150.1  671.45  5164.4  672.52
#Mann= 3 ,-1 , 0
  4745.9     .05       0  4981.9    .033       0  4985.9     .05       0
Bank Sta=4981.9,4985.9
XS Rating Curve= 0 ,0
Exp/Cntr=0.3,0.1

Chan Stop Cuts=-1
Use User Specified Reach Order=0
Composite Channel Slope=5