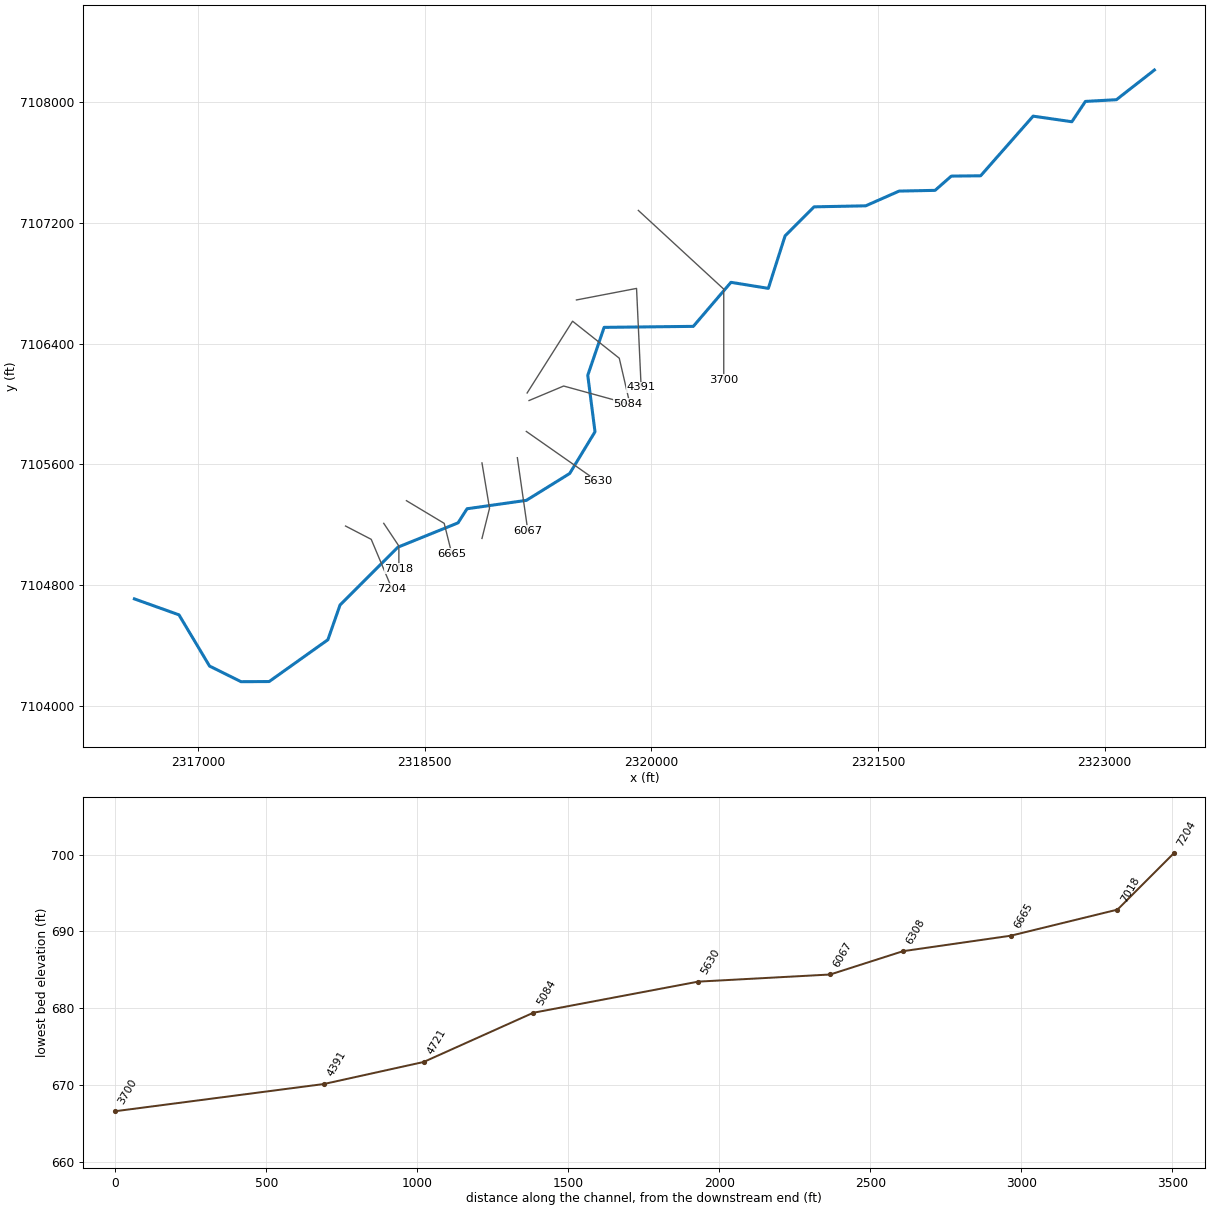
--- Denton Creek Tributary 23.prj (project) ---

Proj Title=Denton Creek Tributary 23 Base Level Engineering
Current Plan=p01
Default Exp/Contr=0.3,0.1
English Units
Geom File=g01
Flow File=f01
Plan File=p01
BEGIN DESCRIPTION:
Denton Creek Tributary 23
END DESCRIPTION:

--- Denton Creek Tributary 23.p01 (plan) ---

Plan Title=Multiple Run
Short Identifier=Multiple
Geom File=g01
Flow File=f01
Subcritical Flow
K Sum by GR= 0
Std Step Tol= 0.01
Critical Tol= 0.01
Num of Std Step Trials= 20
Max Error Tol= 0.3
Flow Tol Ratio= 0.001
Split Flow NTrial= 30
Split Flow Tol= 0.02
Split Flow Ratio= 0.02
Log Output Level= 0
Friction Slope Method= 1
Unsteady Friction Slope Method= 2
Unsteady Bridges Friction Slope Method= 1
Parabolic Critical Depth
Global Vel Dist=  1 , 1 , 1
Global Log Level= 0
CheckData=True
Encroach Param= -1, 0, 0, 0
BEGIN DESCRIPTION:
Multiple Run
END DESCRIPTION:

--- Denton Creek Tributary 23.f01 (steady flow) ---

Flow Title=Multiple
Number of Profiles=7
Profile Names=10-year,25-year,50-year,1pct_min,100-year,1pct_plu,500-year
River Rch & RM= Denton Creek Tri,Reach-1,7204
     650     898    1105     675    1347    2687    2006
Boundary for River Rch & Prof#=Denton Creek Tri,Reach-1,1
Up Type=0
Dn Type=3
Dn Slope=0.005
Boundary for River Rch & Prof#=Denton Creek Tri,Reach-1,2
Up Type=0
Dn Type=3
Dn Slope=0.005
Boundary for River Rch & Prof#=Denton Creek Tri,Reach-1,3
Up Type=0
Dn Type=3
Dn Slope=0.005
Boundary for River Rch & Prof#=Denton Creek Tri,Reach-1,4
Up Type=0
Dn Type=3
Dn Slope=0.005
Boundary for River Rch & Prof#=Denton Creek Tri,Reach-1,5
Up Type=0
Dn Type=3
Dn Slope=0.005
Boundary for River Rch & Prof#=Denton Creek Tri,Reach-1,6
Up Type=0
Dn Type=3
Dn Slope=0.005
Boundary for River Rch & Prof#=Denton Creek Tri,Reach-1,7
Up Type=0
Dn Type=3
Dn Slope=0.005

--- Denton Creek Tributary 23.g01 (geometry) ---

Geom Title=Existing Conditions

River Reach=Denton Creek Tri,Reach-1
Reach XY= 30
      2316579.00      7104710.00      2316873.75      7104604.56
      2317076.33      7104265.42      2317284.86      7104162.06
      2317470.69      7104163.09      2317859.39      7104439.80
      2317939.76      7104669.68      2318322.55      7105052.26
      2318720.65      7105213.19      2318780.26      7105306.52
      2319173.07      7105362.25      2319459.39      7105539.80
      2319626.95      7105815.86      2319579.07      7106189.97
      2319687.28      7106506.94      2320277.55      7106513.53
      2320526.70      7106804.91      2320773.99      7106765.00
      2320884.83      7107112.30      2321076.55      7107304.54
      2321418.50      7107311.22      2321639.50      7107408.78
      2321877.53      7107413.55      2321984.85      7107507.94
      2322179.00      7107510.00      2322526.30      7107904.64
      2322782.67      7107867.69      2322872.52      7108002.30
      2323077.54      7108013.54      2323329.00      7108210.00

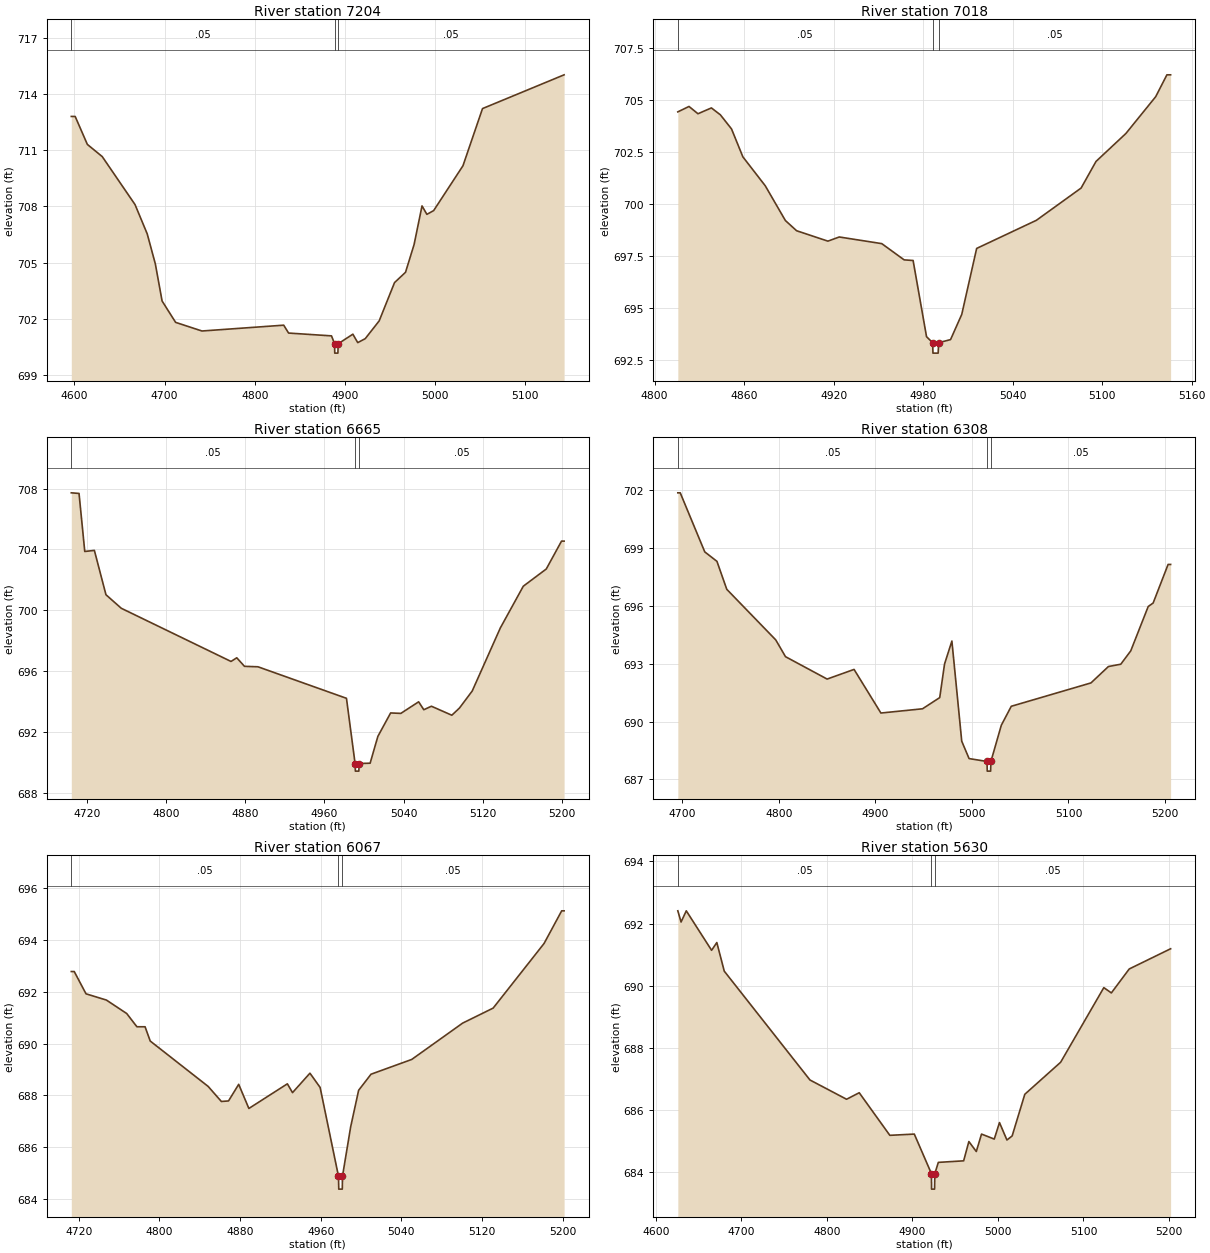
Type RM Length L Ch R = 1,7204,186,186,186
BEGIN DESCRIPTION:
Mapping XS 87e1c92b
END DESCRIPTION:
XS GIS Cut Line= 3
      2317976.28      7105192.24      2318146.15      7105104.06
      2318283.71      7104776.57
#Sta/Elev= 30
  4596.6  712.80  4600.9  712.80  4614.4  711.31  4630.9  710.66  4667.3  708.10
  4680.8  706.54  4689.8  704.94  4697.3  702.96  4712.3  701.82  4741.5  701.36
  4832.2  701.67  4837.6  701.25  4885.2  701.10  4888.6  700.68  4888.8  700.18
  4892.3  700.18  4892.6  700.68  4908.9  701.19  4914.3  700.74  4922.6  700.95
  4938.1  701.90  4955.1  703.94  4967.3  704.49  4976.8  705.97  4985.6  708.03
  4991.0  707.58  4998.5  707.78  5031.0  710.17  5052.7  713.22  5143.2  715.02
#Mann=3,-1,0
  4596.6    0.05       0  4888.6    0.04       0  4892.6    0.05       0
Bank Sta=4888.6,4892.6
Exp/Cntr=0.3,0.1

Type RM Length L Ch R = 1,7018,353,353,353
BEGIN DESCRIPTION:
Denton Creek Tributary 23 13.0
END DESCRIPTION:
XS GIS Cut Line= 3
      2318229.01      7105209.99      2318329.00      7105060.00
      2318329.00      7104909.96
#Sta/Elev= 30
  4815.6  704.44  4823.1  704.70  4829.1  704.35  4838.1  704.63  4844.1  704.30
  4851.6  703.62  4859.2  702.28  4874.2  700.89  4887.7  699.22  4895.2  698.73
  4916.2  698.23  4923.8  698.43  4952.3  698.11  4967.3  697.33  4973.3  697.30
  4982.3  693.64  4986.4  693.35  4986.6  692.85  4990.1  692.85  4990.4  693.35
  4998.4  693.50  5005.9  694.71  5015.9  697.88  5055.9  699.23  5085.9  700.78
  5095.9  702.06  5115.9  703.40  5135.9  705.17  5143.4  706.22  5145.9  706.22
#Mann=3,-1,0
  4815.6    0.05       0  4986.4    0.04       0  4990.4    0.05       0
Bank Sta=4986.4,4990.4
Exp/Cntr=0.3,0.1

Type RM Length L Ch R = 1,6665,357,357,357
BEGIN DESCRIPTION:
Denton Creek Tributary 23 12.0
END DESCRIPTION:
XS GIS Cut Line= 3
      2318379.01      7105360.00      2318629.00      7105210.00
      2318679.00      7105009.99
#Sta/Elev= 30
  4704.4  707.72  4712.2  707.68  4718.0  703.87  4727.7  703.94  4739.4  701.03
  4754.9  700.14  4865.7  696.65  4871.5  696.89  4879.3  696.33  4892.9  696.30
  4982.3  694.23  4991.0  689.95  4991.3  689.45  4994.8  689.45  4995.0  689.95
  5006.2  689.97  5014.0  691.73  5026.9  693.27  5037.2  693.24  5055.2  694.00
  5060.4  693.48  5068.1  693.71  5088.7  693.12  5096.4  693.59  5109.3  694.71
  5137.7  698.85  5160.9  701.59  5184.1  702.72  5199.5  704.55  5202.1  704.55
#Mann=3,-1,0
  4704.4    0.05       0  4991.0    0.04       0  4995.0    0.05       0
Bank Sta=4991,4995
Exp/Cntr=0.3,0.1

Type RM Length L Ch R = 1,6308,241,241,241
BEGIN DESCRIPTION:
Denton Creek Tributary 23 11.0
END DESCRIPTION:
XS GIS Cut Line= 3
      2318879.00      7105609.98      2318929.00      7105310.00
      2318878.99      7105109.97
#Sta/Elev= 30
  4695.5  701.85  4698.0  701.85  4723.4  698.79  4736.0  698.30  4746.2  696.85
  4796.9  694.23  4807.0  693.36  4850.1  692.20  4878.0  692.70  4905.8  690.44
  4948.9  690.66  4966.7  691.24  4971.7  692.98  4979.3  694.17  4989.5  688.98
  4997.1  688.08  5015.7  687.93  5015.9  687.43  5019.4  687.43  5019.7  687.93
  5030.5  689.81  5040.8  690.79  5123.3  692.00  5141.4  692.85  5154.2  692.97
  5164.5  693.66  5182.6  695.96  5187.7  696.14  5203.2  698.14  5205.8  698.14
#Mann=3,-1,0
  4695.5    0.05       0  5015.7    0.04       0  5019.7    0.05       0
Bank Sta=5015.7,5019.7
Exp/Cntr=0.3,0.1

Type RM Length L Ch R = 1,6067,437,437,437
BEGIN DESCRIPTION:
Mapping XS f4824fb4
END DESCRIPTION:
XS GIS Cut Line= 2
      2319113.17      7105644.40      2319182.53      7105160.35
#Sta/Elev= 30
  4712.5  692.78  4715.4  692.78  4727.1  691.92  4747.3  691.68  4767.5  691.16
  4777.6  690.65  4785.7  690.65  4790.8  690.10  4848.3  688.35  4861.4  687.77
  4868.5  687.79  4878.6  688.43  4888.7  687.50  4926.9  688.45  4932.0  688.11
  4949.3  688.86  4959.4  688.31  4977.6  684.89  4977.9  684.39  4981.4  684.39
  4981.6  684.89  4989.7  686.79  4997.6  688.20  5009.9  688.82  5050.3  689.39
  5100.8  690.79  5131.1  691.37  5181.6  693.86  5199.1  695.12  5201.5  695.12
#Mann=3,-1,0
  4712.5    0.05       0  4977.6    0.04       0  4981.6    0.05       0
Bank Sta=4977.6,4981.6
Exp/Cntr=0.3,0.1

Type RM Length L Ch R = 1,5630,546,546,546
BEGIN DESCRIPTION:
Mapping XS 8a261569
END DESCRIPTION:
XS GIS Cut Line= 2
      2319172.45      7105818.22      2319644.52      7105487.83
#Sta/Elev= 30
  4625.7  692.41  4629.5  692.05  4635.6  692.41  4665.2  691.14  4671.3  691.39
  4680.0  690.47  4780.2  686.97  4823.0  686.35  4837.8  686.56  4873.6  685.19
  4902.2  685.23  4922.2  683.96  4922.4  683.46  4925.9  683.46  4926.2  683.96
  4930.3  684.32  4959.9  684.37  4966.0  684.99  4974.7  684.67  4980.8  685.23
  4995.7  685.07  5001.8  685.60  5010.5  685.04  5016.6  685.17  5031.4  686.51
  5073.3  687.54  5123.8  689.94  5132.6  689.77  5153.5  690.54  5201.9  691.19
#Mann=3,-1,0
  4625.7    0.05       0  4922.2    0.04       0  4926.2    0.05       0
Bank Sta=4922.2,4926.2
Exp/Cntr=0.3,0.1

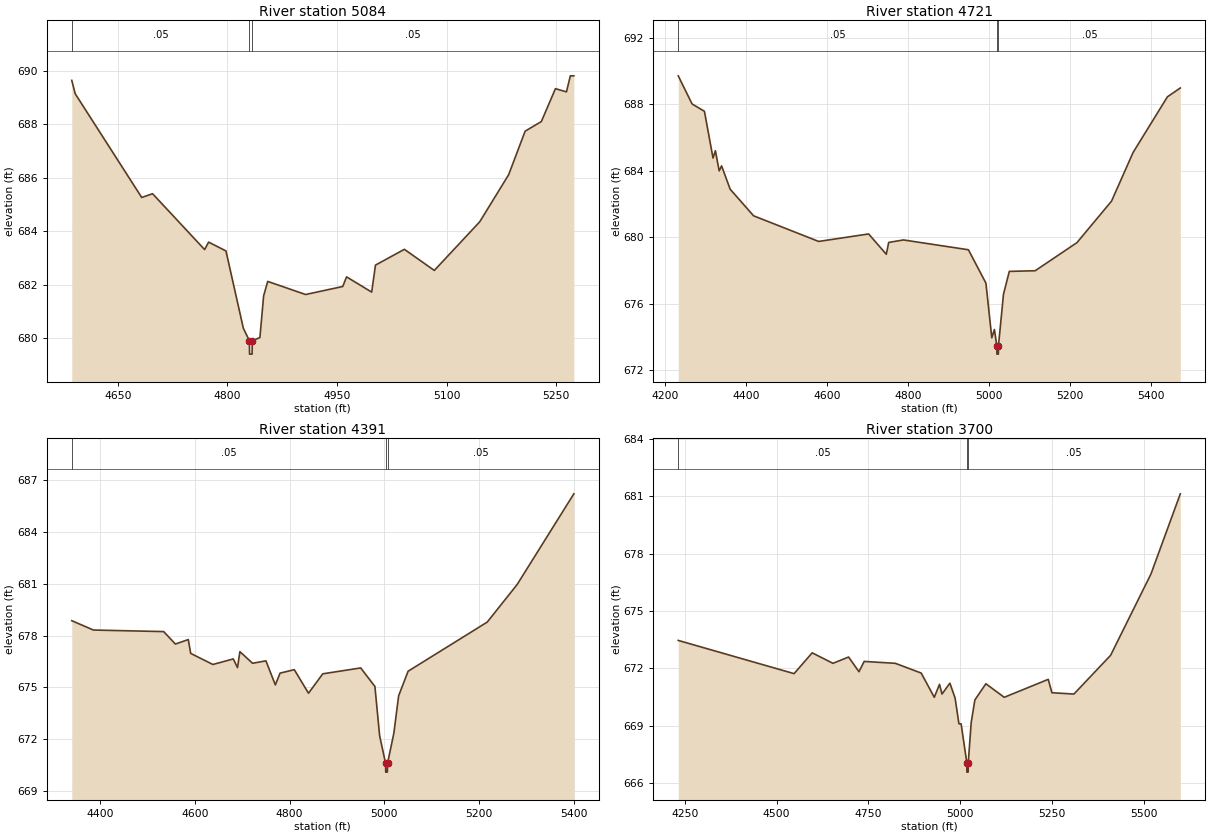
Type RM Length L Ch R = 1,5084,363,363,363
BEGIN DESCRIPTION:
Mapping XS 3139f3ef
END DESCRIPTION:
XS GIS Cut Line= 3
      2319190.62      7106022.76      2319419.66      7106118.75
      2319843.27      7106002.18
#Sta/Elev= 30
  4586.7  689.64  4591.4  689.14  4682.5  685.26  4697.4  685.40  4768.7  683.31
  4774.1  683.59  4797.9  683.26  4821.7  680.37  4830.0  679.90  4830.2  679.40
  4833.7  679.40  4834.0  679.90  4844.4  680.02  4849.5  681.58  4855.1  682.12
  4907.0  681.63  4957.9  681.93  4963.1  682.29  4997.5  681.72  5002.7  682.73
  5042.3  683.32  5083.3  682.53  5145.5  684.35  5185.1  686.11  5207.7  687.74
  5229.9  688.10  5249.2  689.33  5264.3  689.21  5269.6  689.81  5274.4  689.81
#Mann=3,-1,0
  4586.7    0.05       0  4830.0    0.04       0  4834.0    0.05       0
Bank Sta=4830,4834
Exp/Cntr=0.3,0.1

Type RM Length L Ch R = 1,4721,330,330,330
BEGIN DESCRIPTION:
Mapping XS 58314b4e
END DESCRIPTION:
XS GIS Cut Line= 4
      2319177.87      7106072.73      2319478.57      7106547.65
      2319787.58      7106302.84      2319851.76      7106026.53
#Sta/Elev= 30
  4232.1  689.70  4266.3  688.01  4296.8  687.57  4318.0  684.76  4323.9  685.20
  4333.2  683.99  4339.2  684.29  4360.3  682.89  4418.2  681.29  4579.0  679.75
  4702.3  680.20  4746.0  678.98  4751.9  679.69  4788.4  679.84  4948.8  679.25
  4992.1  677.24  5006.5  673.96  5012.9  674.46  5019.0  673.48  5019.2  672.98
  5022.7  672.98  5023.0  673.48  5035.4  676.58  5049.8  677.95  5113.7  677.99
  5216.9  679.68  5302.2  682.17  5355.6  685.10  5440.3  688.44  5472.1  688.97
#Mann=3,-1,0
  4232.1    0.05       0  5019.0    0.04       0  5023.0    0.05       0
Bank Sta=5019,5023
Exp/Cntr=0.3,0.1

Type RM Length L Ch R = 1,4391,691,691,691
BEGIN DESCRIPTION:
Mapping XS 8a1ff398
END DESCRIPTION:
XS GIS Cut Line= 3
      2319504.15      7106688.28      2319901.95      7106764.68
      2319932.41      7106110.45
#Sta/Elev= 30
  4340.0  678.86  4385.7  678.32  4534.0  678.23  4558.8  677.51  4586.0  677.77
  4591.1  676.97  4637.9  676.33  4681.0  676.65  4689.9  676.15  4695.0  677.07
  4721.7  676.40  4749.9  676.54  4769.8  675.15  4779.8  675.83  4809.8  676.03
  4839.8  674.67  4869.9  675.79  4950.0  676.13  4980.0  675.06  4990.0  672.21
  5002.6  670.61  5002.8  670.11  5006.3  670.11  5006.6  670.61  5020.0  672.36
  5030.1  674.52  5050.1  675.94  5217.2  678.78  5280.3  680.95  5400.0  686.19
#Mann=3,-1,0
  4340.0    0.05       0  5002.6   0.033       0  5006.6    0.05       0
Bank Sta=5002.6,5006.6
Exp/Cntr=0.3,0.1

Type RM Length L Ch R = 1,3700,0,0,0
BEGIN DESCRIPTION:
Denton Creek Tributary 23 5.0
END DESCRIPTION:
XS GIS Cut Line= 3
      2319913.77      7107280.81      2320479.00      7106760.00
      2320479.00      7106159.98
#Sta/Elev= 30
  4231.7  673.46  4547.5  671.72  4596.8  672.81  4653.5  672.26  4696.0  672.59
  4724.4  671.82  4738.6  672.36  4823.5  672.26  4894.0  671.75  4929.7  670.48
  4943.9  671.16  4950.7  670.65  4972.2  671.22  4986.4  670.44  4996.9  669.09
  5002.8  669.09  5018.3  667.06  5018.5  666.56  5022.0  666.56  5022.3  667.06
  5030.3  669.16  5040.3  670.34  5070.3  671.19  5120.3  670.48  5240.3  671.42
  5250.3  670.72  5310.3  670.65  5410.3  672.68  5520.3  676.94  5600.3  681.14
#Mann=3,-1,0
  4231.7    0.05       0  5018.3   0.033       0  5022.3    0.05       0
Bank Sta=5018.3,5022.3
Exp/Cntr=0.3,0.1

Chan Stop Cuts=-1