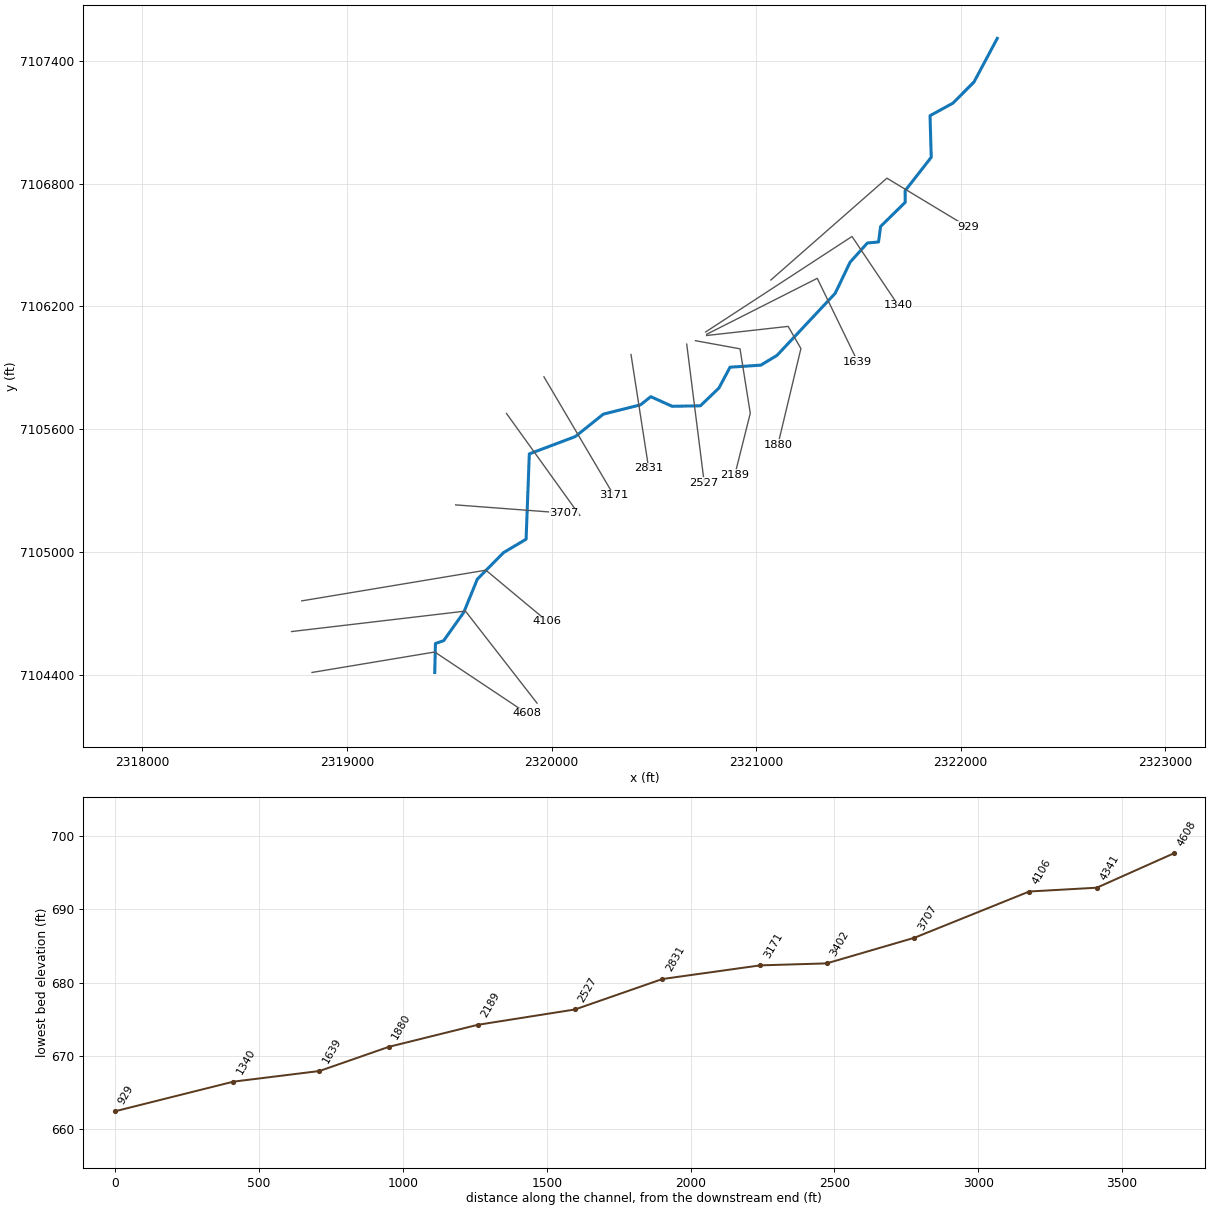
--- Denton Creek Tributary 23_2.prj (project) ---

Proj Title=Denton Creek Tributary 23_2 Base Level Engineering
Current Plan=p01
Default Exp/Contr=0.3,0.1
English Units
Geom File=g01
Flow File=f01
Plan File=p01
BEGIN DESCRIPTION:
Denton Creek Tributary 23_2
END DESCRIPTION:

--- Denton Creek Tributary 23_2.p01 (plan) ---

Plan Title=Multiple Run
Short Identifier=Multiple
Geom File=g01
Flow File=f01
Subcritical Flow
K Sum by GR= 0
Std Step Tol= 0.01
Critical Tol= 0.01
Num of Std Step Trials= 20
Max Error Tol= 0.3
Flow Tol Ratio= 0.001
Split Flow NTrial= 30
Split Flow Tol= 0.02
Split Flow Ratio= 0.02
Log Output Level= 0
Friction Slope Method= 1
Unsteady Friction Slope Method= 2
Unsteady Bridges Friction Slope Method= 1
Parabolic Critical Depth
Global Vel Dist=  1 , 1 , 1
Global Log Level= 0
CheckData=True
Encroach Param= -1, 0, 0, 0
BEGIN DESCRIPTION:
Multiple Run
END DESCRIPTION:

--- Denton Creek Tributary 23_2.f01 (steady flow) ---

Flow Title=Multiple
Number of Profiles=7
Profile Names=10-year,25-year,50-year,1pct_min,100-year,1pct_plu,500-year
River Rch & RM= Denton Creek Tri,Reach-1,4608
     373     498     599     358     715    1426    1019
Boundary for River Rch & Prof#=Denton Creek Tri,Reach-1,1
Up Type=0
Dn Type=3
Dn Slope=0.005
Boundary for River Rch & Prof#=Denton Creek Tri,Reach-1,2
Up Type=0
Dn Type=3
Dn Slope=0.005
Boundary for River Rch & Prof#=Denton Creek Tri,Reach-1,3
Up Type=0
Dn Type=3
Dn Slope=0.005
Boundary for River Rch & Prof#=Denton Creek Tri,Reach-1,4
Up Type=0
Dn Type=3
Dn Slope=0.005
Boundary for River Rch & Prof#=Denton Creek Tri,Reach-1,5
Up Type=0
Dn Type=3
Dn Slope=0.005
Boundary for River Rch & Prof#=Denton Creek Tri,Reach-1,6
Up Type=0
Dn Type=3
Dn Slope=0.005
Boundary for River Rch & Prof#=Denton Creek Tri,Reach-1,7
Up Type=0
Dn Type=3
Dn Slope=0.005

--- Denton Creek Tributary 23_2.g01 (geometry) ---

Geom Title=Existing Conditions

River Reach=Denton Creek Tri,Reach-1
Reach XY= 30
      2319429.00      7104410.00      2319432.35      7104551.61
      2319472.95      7104565.79      2319570.84      7104703.95
      2319637.14      7104866.06      2319765.80      7104996.36
      2319875.55      7105061.25      2319891.32      7105478.50
      2320116.15      7105563.20      2320253.31      7105672.92
      2320435.41      7105718.57      2320485.12      7105758.18
      2320589.50      7105711.23      2320727.54      7105713.52
      2320818.22      7105800.32      2320872.53      7105902.30
      2321023.06      7105912.27      2321102.25      7105960.11
      2321386.48      7106263.23      2321459.45      7106415.54
      2321543.98      7106509.54      2321598.54      7106514.47
      2321608.63      7106590.33      2321728.92      7106708.26
      2321728.54      7106765.02      2321856.14      7106928.53
      2321850.26      7107131.92      2321962.06      7107193.06
      2322065.38      7107296.78      2322179.00      7107510.00

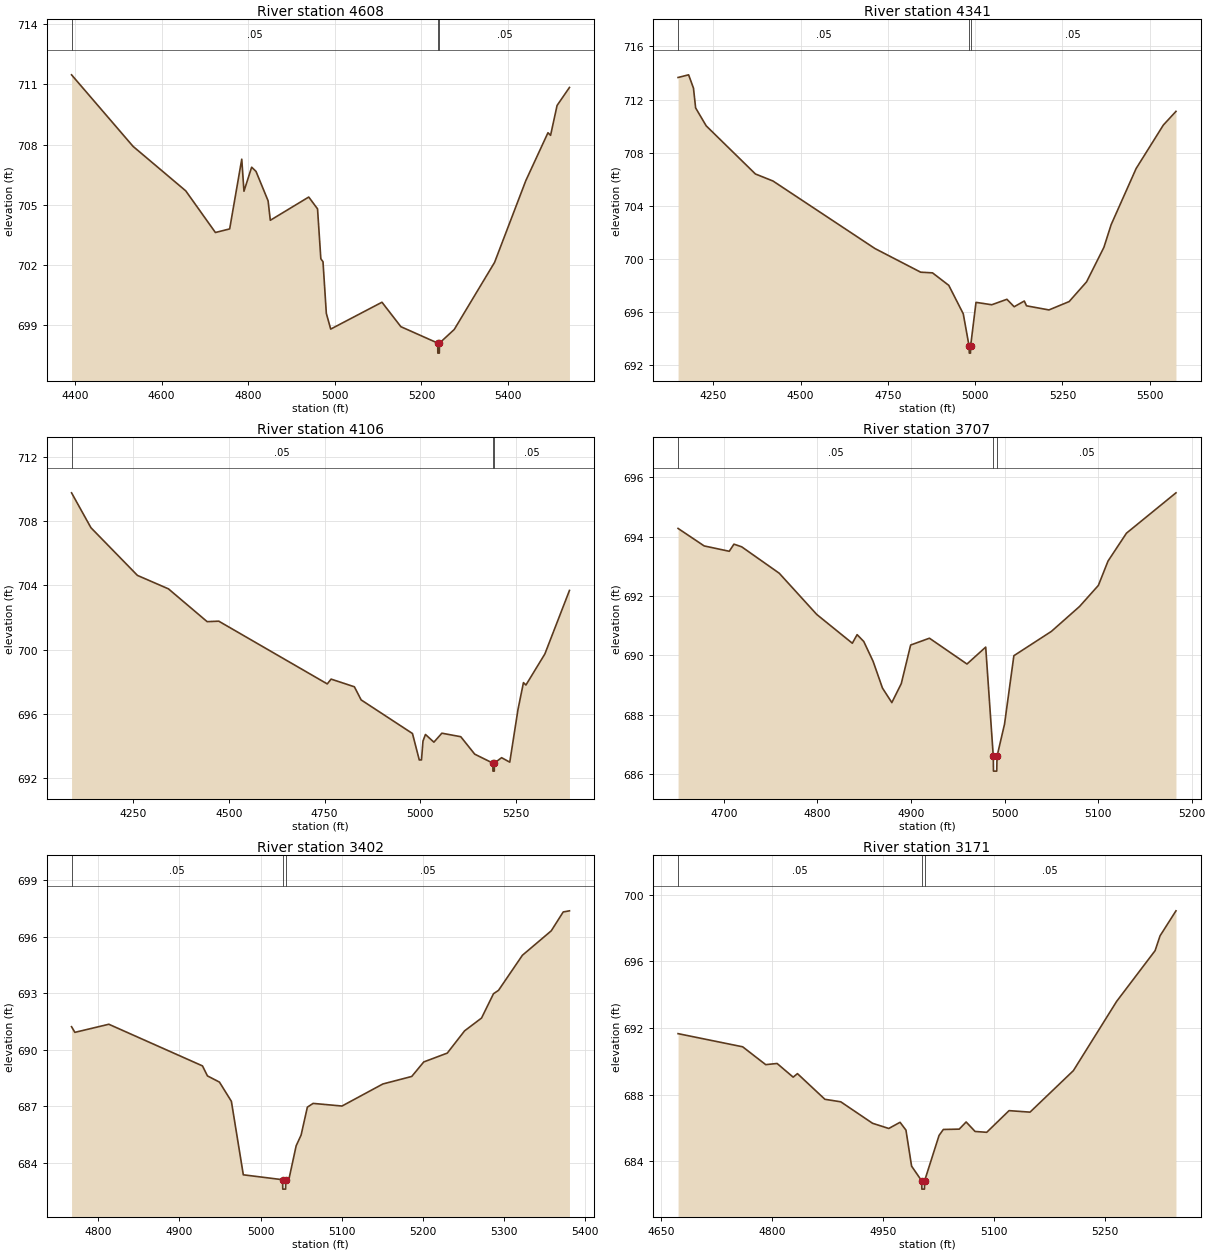
Type RM Length L Ch R = 1,4608,267,267,267
BEGIN DESCRIPTION:
Denton Creek Tributary 23_2 5.0
END DESCRIPTION:
XS GIS Cut Line= 3
      2318829.05      7104410.01      2319429.00      7104510.00
      2319879.03      7104209.98
#Sta/Elev= 30
  4392.4  711.48  4534.3  707.91  4655.9  705.69  4724.4  703.61  4757.3  703.79
  4785.2  707.27  4790.3  705.67  4808.0  706.87  4818.1  706.66  4846.0  705.19
  4851.1  704.22  4939.8  705.38  4960.1  704.79  4967.7  702.30  4972.7  702.15
  4980.4  699.57  4990.5  698.79  5108.8  700.13  5152.4  698.91  5237.5  698.09
  5237.7  697.59  5241.2  697.59  5241.5  698.09  5275.6  698.77  5368.7  702.12
  5440.8  706.20  5491.9  708.59  5497.9  708.46  5512.9  709.95  5541.5  710.85
#Mann=3,-1,0
  4392.4    0.05       0  5237.5    0.04       0  5241.5    0.05       0
Bank Sta=5237.5,5241.5
Exp/Cntr=0.3,0.1

Type RM Length L Ch R = 1,4341,235,235,235
BEGIN DESCRIPTION:
Denton Creek Tributary 23_2 4.0
END DESCRIPTION:
XS GIS Cut Line= 3
      2318729.00      7104610.00      2319579.00      7104710.00
      2319929.03      7104259.96
#Sta/Elev= 30
  4149.2  713.66  4179.4  713.86  4193.3  712.86  4199.5  711.37  4229.8  710.02
  4370.7  706.40  4421.1  705.87  4713.1  700.79  4844.0  699.01  4877.9  698.96
  4924.5  698.02  4966.0  695.88  4982.9  693.42  4983.2  692.92  4986.7  692.92
  4986.9  693.42  5002.5  696.74  5047.6  696.56  5091.0  696.97  5111.8  696.41
  5140.8  696.84  5147.1  696.48  5211.4  696.17  5269.3  696.80  5319.1  698.28
  5368.8  700.88  5389.6  702.59  5461.1  706.81  5539.0  710.08  5575.2  711.11
#Mann=3,-1,0
  4149.2    0.05       0  4982.9    0.04       0  4986.9    0.05       0
Bank Sta=4982.9,4986.9
Exp/Cntr=0.3,0.1

Type RM Length L Ch R = 1,4106,399,399,399
BEGIN DESCRIPTION:
Denton Creek Tributary 23_2 3.0
END DESCRIPTION:
XS GIS Cut Line= 3
      2318778.99      7104760.00      2319679.00      7104910.00
      2319978.97      7104660.02
#Sta/Elev= 30
  4088.0  709.79  4138.7  707.61  4260.4  704.63  4341.5  703.79  4442.8  701.74
  4473.2  701.77  4757.1  697.85  4767.2  698.15  4828.1  697.67  4845.8  696.85
  4980.1  694.75  4997.9  693.10  5003.7  693.10  5007.6  694.28  5014.1  694.69
  5036.2  694.21  5057.0  694.77  5106.5  694.55  5143.0  693.46  5190.4  692.90
  5190.7  692.40  5194.2  692.40  5194.4  692.90  5213.3  693.24  5234.7  692.96
  5256.2  696.25  5270.5  697.93  5277.0  697.78  5326.5  699.72  5390.9  703.69
#Mann=3,-1,0
  4088.0    0.05       0  5190.4    0.04       0  5194.4    0.05       0
Bank Sta=5190.4,5194.4
Exp/Cntr=0.3,0.1

Type RM Length L Ch R = 1,3707,305,305,305
BEGIN DESCRIPTION:
Mapping XS 038c4ad6
END DESCRIPTION:
XS GIS Cut Line= 2
      2319531.21      7105229.25      2320061.70      7105189.18
#Sta/Elev= 30
  4651.2  694.28  4679.1  693.69  4705.9  693.51  4710.9  693.75  4719.2  693.66
  4759.3  692.77  4799.4  691.38  4837.4  690.41  4842.5  690.70  4849.6  690.47
  4859.6  689.80  4869.6  688.90  4879.6  688.41  4889.7  689.05  4899.7  690.35
  4919.8  690.58  4959.9  689.71  4979.9  690.28  4988.0  686.60  4988.2  686.10
  4991.7  686.10  4992.0  686.60  5000.0  687.68  5010.0  689.99  5050.1  690.81
  5080.2  691.65  5100.3  692.36  5110.6  693.18  5130.3  694.12  5183.2  695.48
#Mann=3,-1,0
  4651.2    0.05       0  4988.0    0.04       0  4992.0    0.05       0
Bank Sta=4988,4992
Exp/Cntr=0.3,0.1

Type RM Length L Ch R = 1,3402,231,231,231
BEGIN DESCRIPTION:
Mapping XS 21c2f8e2
END DESCRIPTION:
XS GIS Cut Line= 2
      2319779.87      7105675.95      2320137.74      7105177.77
#Sta/Elev= 30
  4767.2  691.23  4771.3  690.93  4813.1  691.36  4928.5  689.15  4934.6  688.62
  4949.4  688.29  4964.1  687.27  4978.8  683.37  5027.2  683.11  5027.4  682.61
  5030.9  682.61  5031.2  683.11  5035.3  683.20  5043.9  684.91  5050.0  685.48
  5057.7  686.96  5064.8  687.16  5100.4  687.02  5150.7  688.19  5186.3  688.59
  5201.1  689.36  5230.1  689.83  5251.4  691.01  5272.3  691.69  5287.0  692.98
  5293.2  693.16  5322.6  695.02  5358.2  696.32  5372.9  697.32  5380.6  697.38
#Mann=3,-1,0
  4767.2    0.05       0  5027.2    0.04       0  5031.2    0.05       0
Bank Sta=5027.2,5031.2
Exp/Cntr=0.3,0.1

Type RM Length L Ch R = 1,3171,340,340,340
BEGIN DESCRIPTION:
Mapping XS fcbd41ae
END DESCRIPTION:
XS GIS Cut Line= 2
      2319962.85      7105855.24      2320304.48      7105275.75
#Sta/Elev= 30
  4672.9  691.67  4760.2  690.88  4791.3  689.81  4806.7  689.88  4828.4  689.06
  4834.2  689.27  4871.3  687.73  4892.7  687.58  4935.7  686.29  4957.6  685.98
  4972.8  686.35  4980.8  685.88  4988.4  683.72  5002.0  682.84  5002.3  682.34
  5005.8  682.34  5006.0  682.84  5025.5  685.56  5031.3  685.92  5052.8  685.94
  5062.1  686.37  5074.2  685.80  5089.9  685.75  5120.1  687.05  5148.4  686.96
  5207.0  689.45  5265.5  693.61  5317.4  696.65  5324.1  697.54  5345.6  699.04
#Mann=3,-1,0
  4672.9    0.05       0  5002.0    0.04       0  5006.0    0.05       0
Bank Sta=5002,5006
Exp/Cntr=0.3,0.1

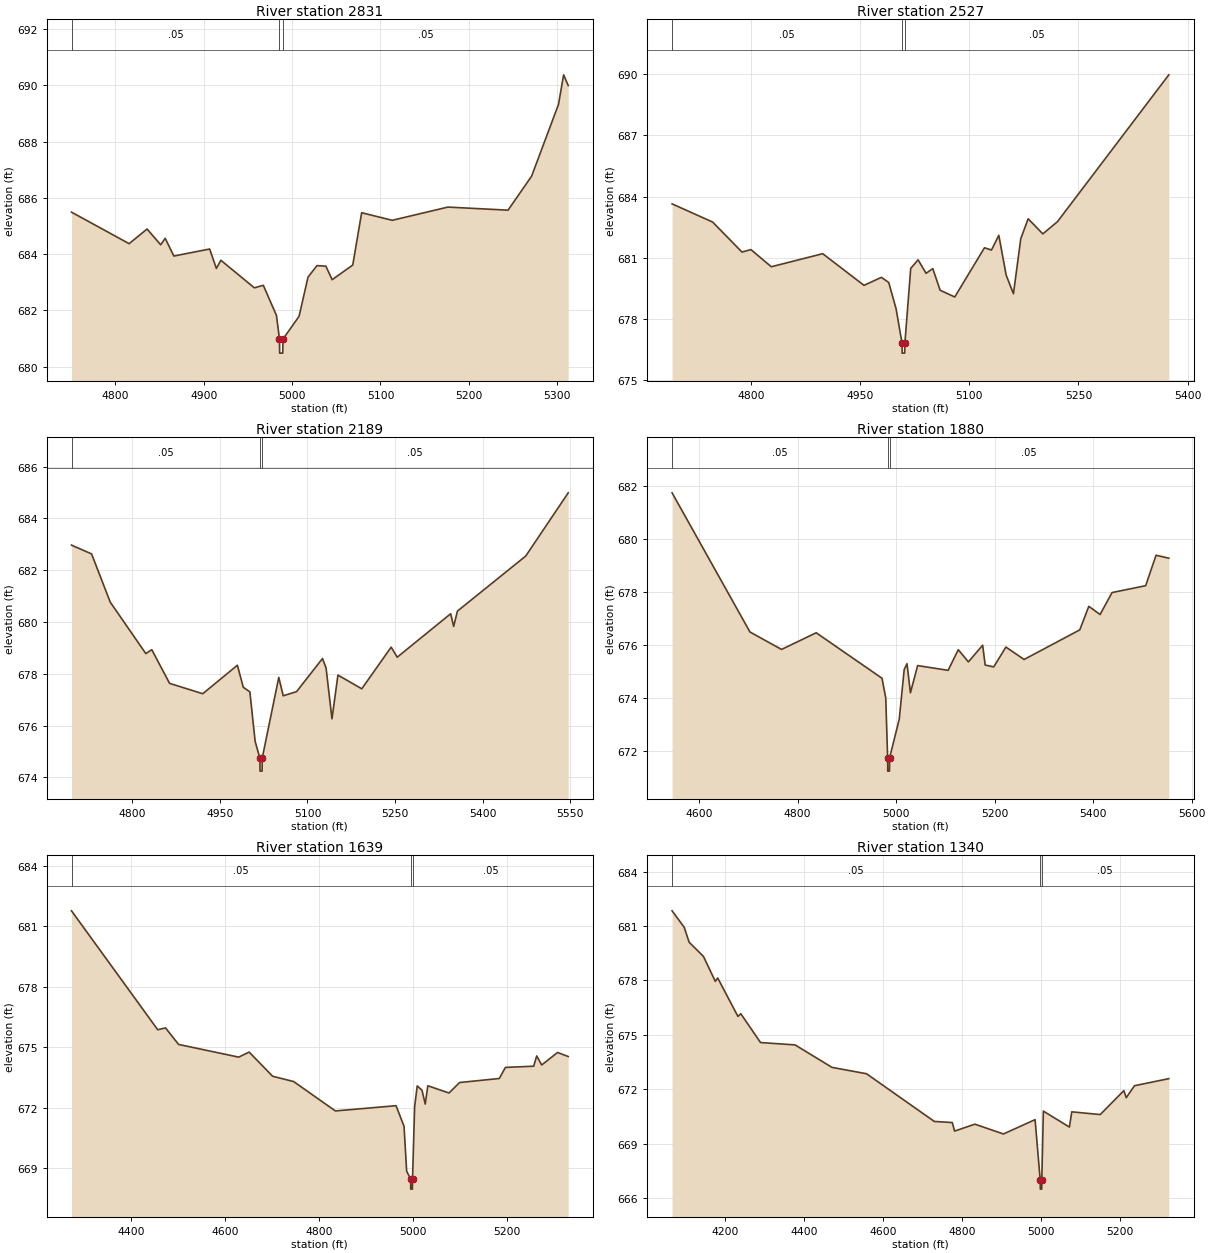
Type RM Length L Ch R = 1,2831,304,304,304
BEGIN DESCRIPTION:
Mapping XS bf388588
END DESCRIPTION:
XS GIS Cut Line= 2
      2320388.47      7105964.44      2320474.66      7105409.09
#Sta/Elev= 30
  4750.4  685.49  4815.6  684.37  4835.9  684.89  4851.3  684.33  4856.4  684.56
  4866.2  683.93  4906.7  684.18  4914.3  683.49  4919.4  683.78  4957.3  682.80
  4967.4  682.89  4982.3  681.82  4985.7  680.98  4985.9  680.48  4989.4  680.48
  4989.7  680.98  5007.9  681.79  5018.0  683.18  5028.1  683.59  5038.2  683.57
  5045.3  683.09  5068.6  683.61  5078.7  685.47  5113.3  685.20  5176.3  685.67
  5244.3  685.56  5271.0  686.77  5301.4  689.32  5307.2  690.37  5312.4  689.99
#Mann=3,-1,0
  4750.4    0.05       0  4985.7    0.04       0  4989.7    0.05       0
Bank Sta=4985.7,4989.7
Exp/Cntr=0.3,0.1

Type RM Length L Ch R = 1,2527,338,338,338
BEGIN DESCRIPTION:
Mapping XS fdacd219
END DESCRIPTION:
XS GIS Cut Line= 2
      2320660.79      7106015.25      2320746.30      7105338.33
#Sta/Elev= 30
  4691.9  683.64  4747.6  682.75  4787.9  681.28  4800.2  681.40  4828.2  680.56
  4898.8  681.20  4955.5  679.65  4979.4  680.04  4989.5  679.79  4999.6  678.50
  5007.7  676.83  5007.9  676.33  5011.4  676.33  5011.7  676.83  5019.7  680.48
  5029.8  680.90  5040.8  680.24  5050.0  680.47  5060.1  679.41  5080.2  679.08
  5121.0  681.49  5130.6  681.38  5140.7  682.10  5150.8  680.15  5160.8  679.24
  5170.9  681.94  5181.0  682.91  5201.2  682.17  5221.3  682.77  5374.2  689.96
#Mann=3,-1,0
  4691.9    0.05       0  5007.7    0.04       0  5011.7    0.05       0
Bank Sta=5007.7,5011.7
Exp/Cntr=0.3,0.1

Type RM Length L Ch R = 1,2189,309,309,309
BEGIN DESCRIPTION:
Mapping XS aba6376f
END DESCRIPTION:
XS GIS Cut Line= 4
      2320703.78      7106031.82      2320921.39      7105992.13
      2320971.50      7105677.05      2320895.97      7105375.92
#Sta/Elev= 30
  4695.9  682.97  4730.3  682.63  4762.2  680.77  4823.2  678.78  4833.4  678.93
  4863.9  677.63  4920.7  677.23  4980.0  678.33  4990.1  677.48  5001.4  677.30
  5010.4  675.39  5018.5  674.74  5018.8  674.24  5022.3  674.24  5022.5  674.74
  5050.9  677.86  5058.5  677.15  5081.3  677.31  5125.8  678.59  5131.9  678.22
  5142.0  676.26  5152.2  677.95  5193.0  677.42  5243.4  679.03  5253.7  678.64
  5345.3  680.32  5350.4  679.83  5356.8  680.42  5473.9  682.55  5546.6  684.99
#Mann=3,-1,0
  4695.9    0.05       0  5018.5    0.04       0  5022.5    0.05       0
Bank Sta=5018.5,5022.5
Exp/Cntr=0.3,0.1

Type RM Length L Ch R = 1,1880,241,241,241
BEGIN DESCRIPTION:
Mapping XS 022e1775
END DESCRIPTION:
XS GIS Cut Line= 4
      2320758.19      7106057.30      2321156.70      7106101.83
      2321219.03      7105993.48      2321106.90      7105524.30
#Sta/Elev= 30
  4545.2  681.76  4703.3  676.50  4767.4  675.84  4837.8  676.47  4971.4  674.75
  4979.0  674.00  4982.8  671.74  4983.0  671.24  4986.5  671.24  4986.8  671.74
  5006.4  673.21  5016.4  675.08  5022.1  675.30  5029.1  674.20  5043.7  675.23
  5105.6  675.05  5126.2  675.83  5146.8  675.37  5175.7  676.00  5180.8  675.25
  5198.2  675.18  5222.9  675.93  5259.8  675.46  5372.9  676.58  5391.2  677.47
  5414.1  677.16  5438.4  677.99  5506.6  678.25  5527.7  679.40  5553.6  679.29
#Mann=3,-1,0
  4545.2    0.05       0  4982.8    0.04       0  4986.8    0.05       0
Bank Sta=4982.8,4986.8
Exp/Cntr=0.3,0.1

Type RM Length L Ch R = 1,1639,299,299,299
BEGIN DESCRIPTION:
Mapping XS 0a0b5414
END DESCRIPTION:
XS GIS Cut Line= 3
      2320758.07      7106063.01      2321298.93      7106336.77
      2321496.49      7105929.56
#Sta/Elev= 30
  4272.6  681.76  4456.4  675.86  4473.0  675.95  4500.9  675.13  4629.0  674.50
  4651.3  674.75  4701.4  673.55  4746.0  673.29  4835.1  671.83  4964.4  672.09
  4981.4  671.07  4987.0  668.84  4995.5  668.45  4995.7  667.95  4999.2  667.95
  4999.5  668.45  5004.0  672.03  5009.5  673.07  5019.7  672.86  5026.6  672.17
  5032.1  673.08  5077.3  672.72  5099.8  673.24  5184.5  673.44  5197.5  673.99
  5257.8  674.05  5264.2  674.56  5274.8  674.11  5308.7  674.73  5331.4  674.53
#Mann=3,-1,0
  4272.6    0.05       0  4995.5    0.04       0  4999.5    0.05       0
Bank Sta=4995.5,4999.5
Exp/Cntr=0.3,0.1

Type RM Length L Ch R = 1,1340,411,411,411
BEGIN DESCRIPTION:
Mapping XS fec52ada
END DESCRIPTION:
XS GIS Cut Line= 3
      2320753.18      7106074.47      2321468.85      7106541.40
      2321694.30      7106205.70
#Sta/Elev= 30
  4065.9  681.84  4096.7  680.93  4109.1  680.11  4145.3  679.33  4175.5  677.95
  4181.5  678.14  4232.8  676.02  4240.0  676.17  4290.1  674.58  4377.6  674.45
  4471.2  673.21  4558.7  672.86  4730.6  670.23  4776.0  670.17  4781.9  669.70
  4833.3  670.08  4905.7  669.54  4985.9  670.33  4998.9  667.00  4999.2  666.50
  5002.7  666.50  5002.9  667.00  5006.9  670.80  5072.9  669.92  5078.9  670.76
  5151.0  670.61  5210.9  671.93  5216.9  671.54  5237.9  672.20  5324.8  672.59
#Mann=3,-1,0
  4065.9    0.05       0  4998.9    0.04       0  5002.9    0.05       0
Bank Sta=4998.9,5002.9
Exp/Cntr=0.3,0.1

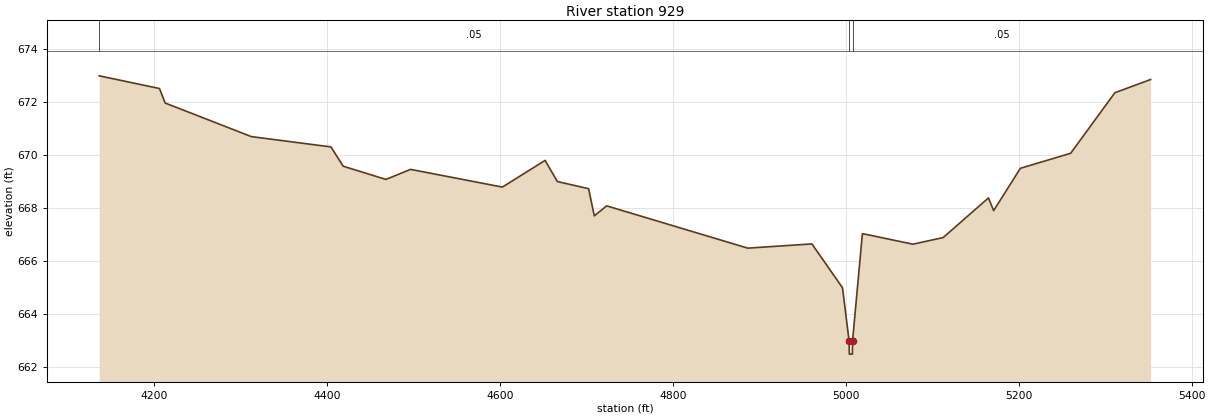
Type RM Length L Ch R = 1,929,0,0,0
BEGIN DESCRIPTION:
Mapping XS dd847050
END DESCRIPTION:
XS GIS Cut Line= 3
      2321072.18      7106328.56      2321639.48      7106826.38
      2322034.34      7106588.00
#Sta/Elev= 30
  4136.5  673.00  4206.2  672.52  4212.8  671.97  4312.5  670.70  4404.5  670.31
  4418.7  669.58  4468.1  669.08  4496.6  669.46  4602.8  668.79  4652.2  669.80
  4666.4  669.00  4702.5  668.73  4709.1  667.70  4723.4  668.08  4886.6  666.48
  4960.8  666.64  4996.2  664.98  5003.8  662.97  5004.1  662.47  5007.6  662.47
  5007.8  662.97  5019.2  667.03  5077.6  666.63  5112.6  666.88  5165.0  668.38
  5171.0  667.90  5201.9  669.50  5260.1  670.07  5311.2  672.36  5352.5  672.86
#Mann=3,-1,0
  4136.5    0.05       0  5003.8   0.033       0  5007.8    0.05       0
Bank Sta=5003.8,5007.8
Exp/Cntr=0.3,0.1

Chan Stop Cuts=-1