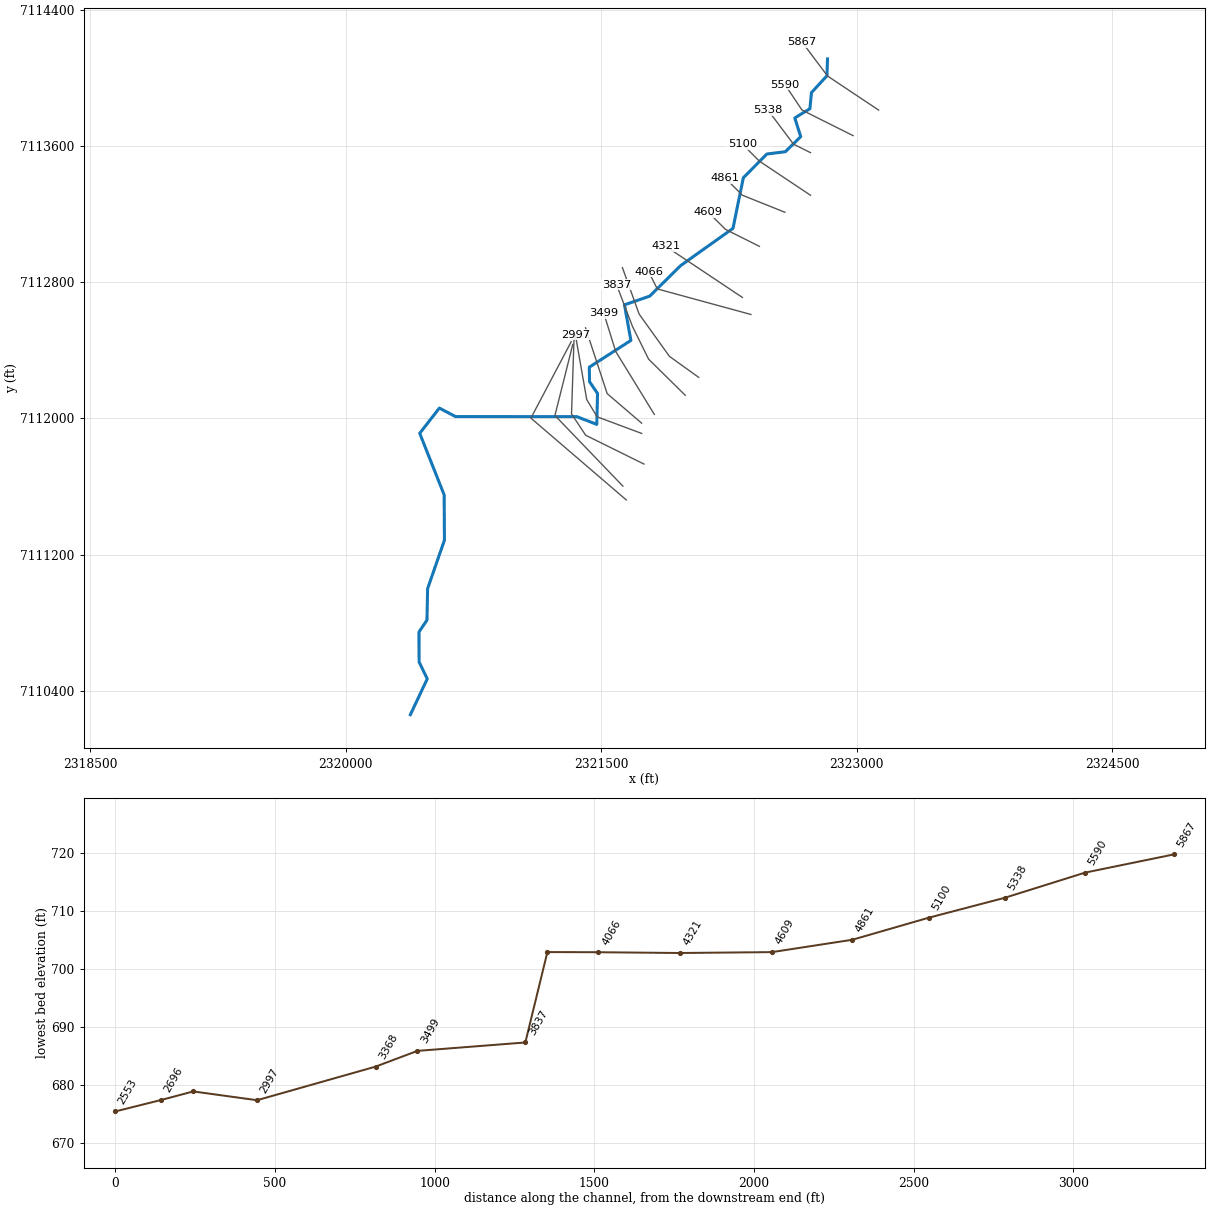
--- Denton Creek Tributary 25.prj (project) ---

Proj Title=Denton Creek Tributary 25 Base Level Engineering
Current Plan=p01
Default Exp/Contr=0.3,0.1
English Units
Geom File=g01
Flow File=f01
Plan File=p01
BEGIN DESCRIPTION:
Denton Creek Tributary 25
END DESCRIPTION:

--- Denton Creek Tributary 25.p01 (plan) ---

Plan Title=Multiple Run
Short Identifier=Multiple
Geom File=g01
Flow File=f01
Subcritical Flow
K Sum by GR= 0
Std Step Tol= 0.01
Critical Tol= 0.01
Num of Std Step Trials= 20
Max Error Tol= 0.3
Flow Tol Ratio= 0.001
Split Flow NTrial= 30
Split Flow Tol= 0.02
Split Flow Ratio= 0.02
Log Output Level= 0
Friction Slope Method= 1
Unsteady Friction Slope Method= 2
Unsteady Bridges Friction Slope Method= 1
Parabolic Critical Depth
Global Vel Dist=  1 , 1 , 1
Global Log Level= 0
CheckData=True
Encroach Param= -1, 0, 0, 0
BEGIN DESCRIPTION:
Multiple Run
END DESCRIPTION:

--- Denton Creek Tributary 25.f01 (steady flow) ---

Flow Title=Multiple
Number of Profiles=7
Profile Names=10-year,25-year,50-year,1pct_min,100-year,1pct_plu,500-year
River Rch & RM= Denton Creek Tri,Reach-1,5867
     307     406     486     290     578    1153     819
Boundary for River Rch & Prof#=Denton Creek Tri,Reach-1,1
Up Type=0
Dn Type=3
Dn Slope=0.005
Boundary for River Rch & Prof#=Denton Creek Tri,Reach-1,2
Up Type=0
Dn Type=3
Dn Slope=0.005
Boundary for River Rch & Prof#=Denton Creek Tri,Reach-1,3
Up Type=0
Dn Type=3
Dn Slope=0.005
Boundary for River Rch & Prof#=Denton Creek Tri,Reach-1,4
Up Type=0
Dn Type=3
Dn Slope=0.005
Boundary for River Rch & Prof#=Denton Creek Tri,Reach-1,5
Up Type=0
Dn Type=3
Dn Slope=0.005
Boundary for River Rch & Prof#=Denton Creek Tri,Reach-1,6
Up Type=0
Dn Type=3
Dn Slope=0.005
Boundary for River Rch & Prof#=Denton Creek Tri,Reach-1,7
Up Type=0
Dn Type=3
Dn Slope=0.005

--- Denton Creek Tributary 25.g01 (geometry) ---

Geom Title=Existing Conditions

River Reach=Denton Creek Tri,Reach-1
Reach XY= 30
      2322829.00      7114110.00      2322825.61      7114011.41
      2322734.56      7113912.36      2322725.62      7113818.05
      2322636.76      7113763.64      2322671.51      7113653.93
      2322581.44      7113565.52      2322472.83      7113552.14
      2322334.47      7113412.45      2322273.74      7113115.47
      2321965.79      7112896.37      2321785.17      7112717.86
      2321636.62      7112666.50      2321674.01      7112457.45
      2321430.03      7112300.52      2321431.28      7112215.57
      2321478.32      7112146.08      2321473.83      7111964.59
      2321356.33      7112010.08      2320644.20      7112010.54
      2320549.34      7112060.31      2320434.10      7111912.29
      2320577.62      7111550.34      2320579.20      7111284.92
      2320480.38      7111000.34      2320476.62      7110815.53
      2320429.68      7110746.08      2320430.40      7110569.65
      2320478.25      7110470.68      2320379.00      7110260.00

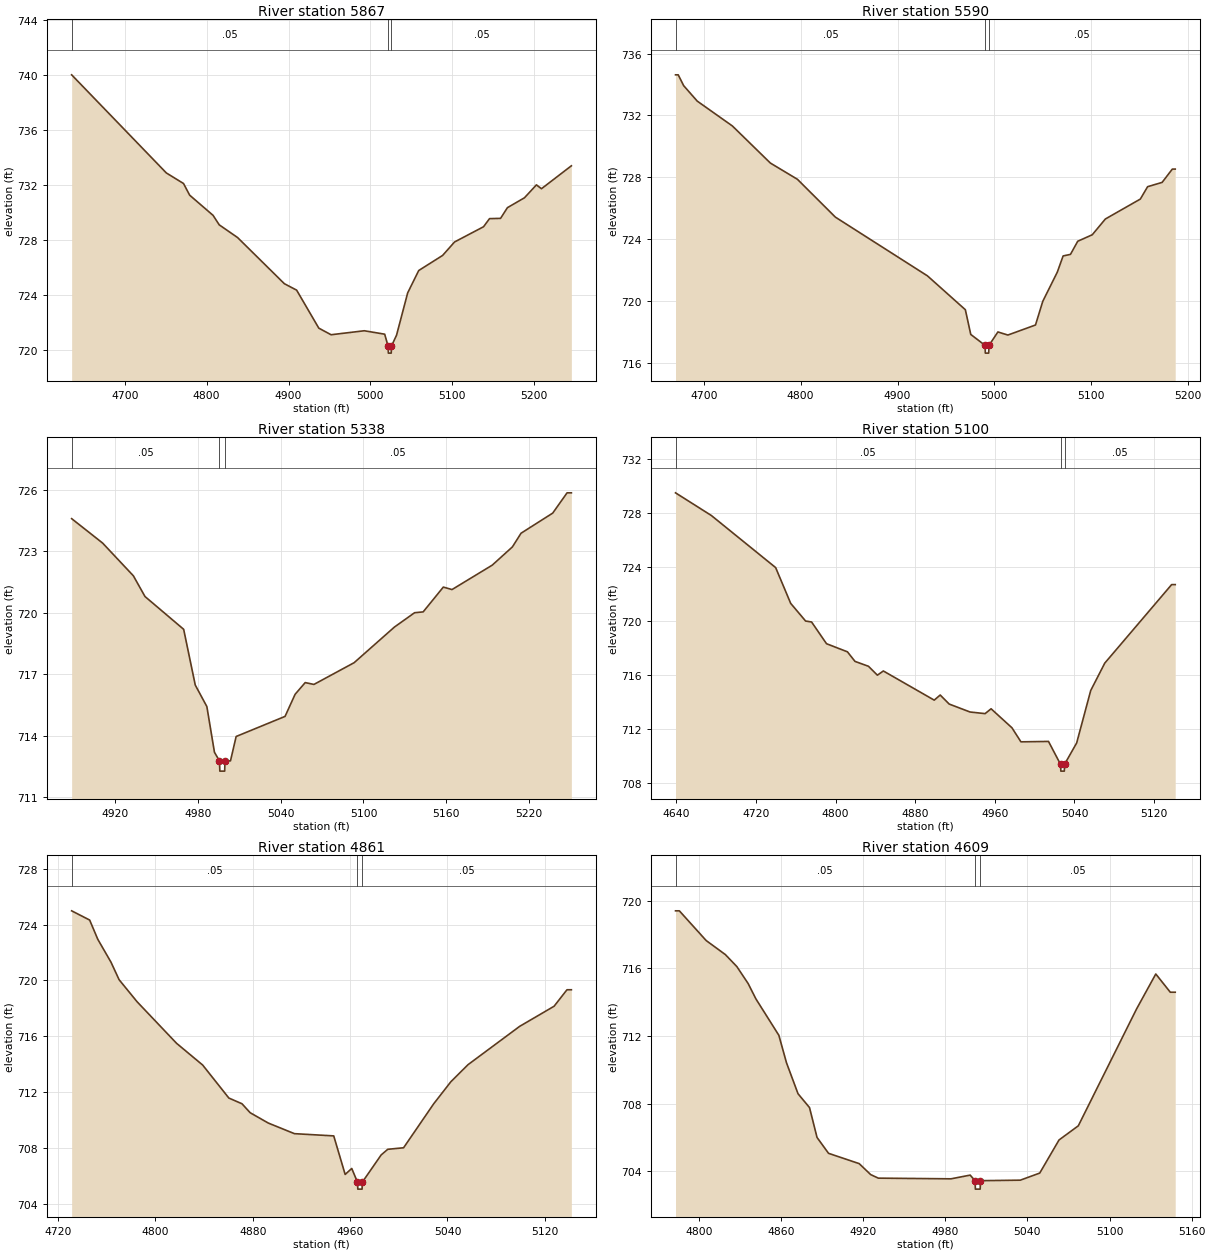
Type RM Length L Ch R = 1,5867,277,277,277
BEGIN DESCRIPTION:
Denton Creek Tributary 25 16.0
END DESCRIPTION:
XS GIS Cut Line= 3
      2323129.02      7113809.99      2322829.00      7114010.00
      2322678.99      7114210.02
#Sta/Elev= 30
  4635.0  740.02  4750.7  732.87  4771.7  732.10  4779.2  731.25  4807.8  729.78
  4815.3  729.09  4837.8  728.16  4894.9  724.80  4909.9  724.33  4937.0  721.56
  4952.0  721.08  4992.6  721.37  5017.5  721.12  5021.7  720.24  5022.0  719.74
  5025.5  719.74  5025.7  720.24  5032.0  721.05  5045.6  724.13  5059.1  725.76
  5088.3  726.86  5102.9  727.84  5138.3  728.95  5145.6  729.54  5159.1  729.56
  5167.5  730.34  5188.3  731.06  5202.9  732.00  5209.1  731.72  5245.6  733.39
#Mann=3,-1,0
  4635.0    0.05       0  5021.7   0.033       0  5025.7    0.05       0
Bank Sta=5021.7,5025.7
Exp/Cntr=0.3,0.1

Type RM Length L Ch R = 1,5590,252,252,252
BEGIN DESCRIPTION:
Denton Creek Tributary 25 15.0
END DESCRIPTION:
XS GIS Cut Line= 3
      2322979.04      7113659.98      2322679.00      7113810.00
      2322579.02      7113959.98
#Sta/Elev= 30
  4670.9  734.63  4673.7  734.63  4679.3  733.93  4693.3  732.93  4729.6  731.32
  4768.8  728.92  4796.7  727.87  4835.9  725.42  4930.9  721.62  4970.0  719.43
  4975.6  717.83  4990.4  717.12  4990.6  716.62  4994.1  716.62  4994.4  717.12
  5003.6  717.99  5013.9  717.79  5042.4  718.44  5049.9  719.97  5064.9  721.86
  5070.9  722.91  5078.5  723.01  5086.0  723.86  5101.0  724.28  5114.5  725.30
  5150.6  726.59  5158.1  727.39  5173.1  727.67  5183.6  728.53  5186.6  728.53
#Mann=3,-1,0
  4670.9    0.05       0  4990.4   0.033       0  4994.4    0.05       0
Bank Sta=4990.4,4994.4
Exp/Cntr=0.3,0.1

Type RM Length L Ch R = 1,5338,238,238,238
BEGIN DESCRIPTION:
Denton Creek Tributary 25 14.0
END DESCRIPTION:
XS GIS Cut Line= 3
      2322729.02      7113559.99      2322629.00      7113610.00
      2322479.02      7113809.98
#Sta/Elev= 30
  4888.7  724.60  4911.1  723.41  4933.4  721.81  4941.8  720.80  4969.8  719.20
  4978.2  716.48  4986.6  715.43  4992.1  713.20  4995.7  712.78  4996.0  712.28
  4999.5  712.28  4999.7  712.78  5003.7  712.78  5007.8  713.97  5043.2  714.95
  5050.5  716.03  5057.8  716.60  5064.1  716.51  5093.2  717.57  5122.4  719.31
  5137.0  720.01  5143.2  720.05  5157.8  721.26  5164.1  721.14  5193.2  722.33
  5207.8  723.22  5214.1  723.89  5237.0  724.87  5247.4  725.86  5250.5  725.86
#Mann=3,-1,0
  4888.7    0.05       0  4995.7    0.04       0  4999.7    0.05       0
Bank Sta=4995.7,4999.7
Exp/Cntr=0.3,0.1

Type RM Length L Ch R = 1,5100,239,239,239
BEGIN DESCRIPTION:
Denton Creek Tributary 25 13.0
END DESCRIPTION:
XS GIS Cut Line= 3
      2322728.98      7113310.01      2322429.00      7113510.00
      2322328.97      7113610.03
#Sta/Elev= 30
  4639.2  729.47  4675.2  727.79  4739.8  723.93  4754.9  721.28  4769.9  719.97
  4775.9  719.90  4790.9  718.29  4811.9  717.69  4819.5  716.98  4833.0  716.62
  4842.0  715.96  4848.0  716.27  4899.1  714.11  4905.1  714.49  4914.1  713.82
  4935.1  713.23  4950.2  713.11  4956.2  713.47  4977.2  712.06  4986.2  711.02
  5013.9  711.05  5026.0  709.35  5026.3  708.85  5029.8  708.85  5030.0  709.35
  5042.2  710.94  5056.3  714.82  5070.4  716.85  5137.6  722.67  5141.2  722.67
#Mann=3,-1,0
  4639.2    0.05       0  5026.0    0.04       0  5030.0    0.05       0
Bank Sta=5026,5030
Exp/Cntr=0.3,0.1

Type RM Length L Ch R = 1,4861,252,252,252
BEGIN DESCRIPTION:
Denton Creek Tributary 25 12.0
END DESCRIPTION:
XS GIS Cut Line= 3
      2322579.00      7113210.00      2322329.00      7113310.00
      2322228.98      7113410.02
#Sta/Elev= 30
  4731.1  724.98  4745.9  724.32  4752.6  722.94  4763.4  721.31  4770.1  720.05
  4784.9  718.47  4817.3  715.50  4838.8  713.94  4860.3  711.58  4871.1  711.17
  4877.8  710.53  4892.7  709.79  4914.2  709.03  4946.5  708.87  4955.9  706.11
  4961.3  706.54  4966.0  705.56  4966.3  705.06  4969.8  705.06  4970.0  705.56
  4985.5  707.51  4990.9  707.91  5003.9  708.02  5028.6  711.16  5042.8  712.75
  5056.9  713.97  5099.3  716.71  5127.6  718.15  5138.2  719.33  5141.8  719.33
#Mann=3,-1,0
  4731.1    0.05       0  4966.0    0.04       0  4970.0    0.05       0
Bank Sta=4966,4970
Exp/Cntr=0.3,0.1

Type RM Length L Ch R = 1,4609,288,288,288
BEGIN DESCRIPTION:
Denton Creek Tributary 25 11.0
END DESCRIPTION:
XS GIS Cut Line= 3
      2322429.03      7113009.99      2322229.00      7113110.00
      2322128.97      7113210.03
#Sta/Elev= 30
  4782.9  719.41  4785.7  719.41  4805.3  717.65  4819.3  716.82  4827.7  716.11
  4836.0  715.10  4841.6  714.20  4858.4  712.04  4864.0  710.41  4872.4  708.58
  4880.8  707.76  4886.3  705.99  4894.7  705.05  4917.1  704.44  4925.5  703.79
  4931.1  703.58  4984.2  703.54  4998.2  703.76  5001.7  703.43  5002.0  702.93
  5005.5  702.93  5005.7  703.43  5034.8  703.46  5049.0  703.88  5063.1  705.84
  5077.2  706.68  5119.7  713.59  5133.8  715.67  5144.4  714.59  5148.0  714.59
#Mann=3,-1,0
  4782.9    0.05       0  5001.7   0.033       0  5005.7    0.05       0
Bank Sta=5001.7,5005.7
Exp/Cntr=0.3,0.1

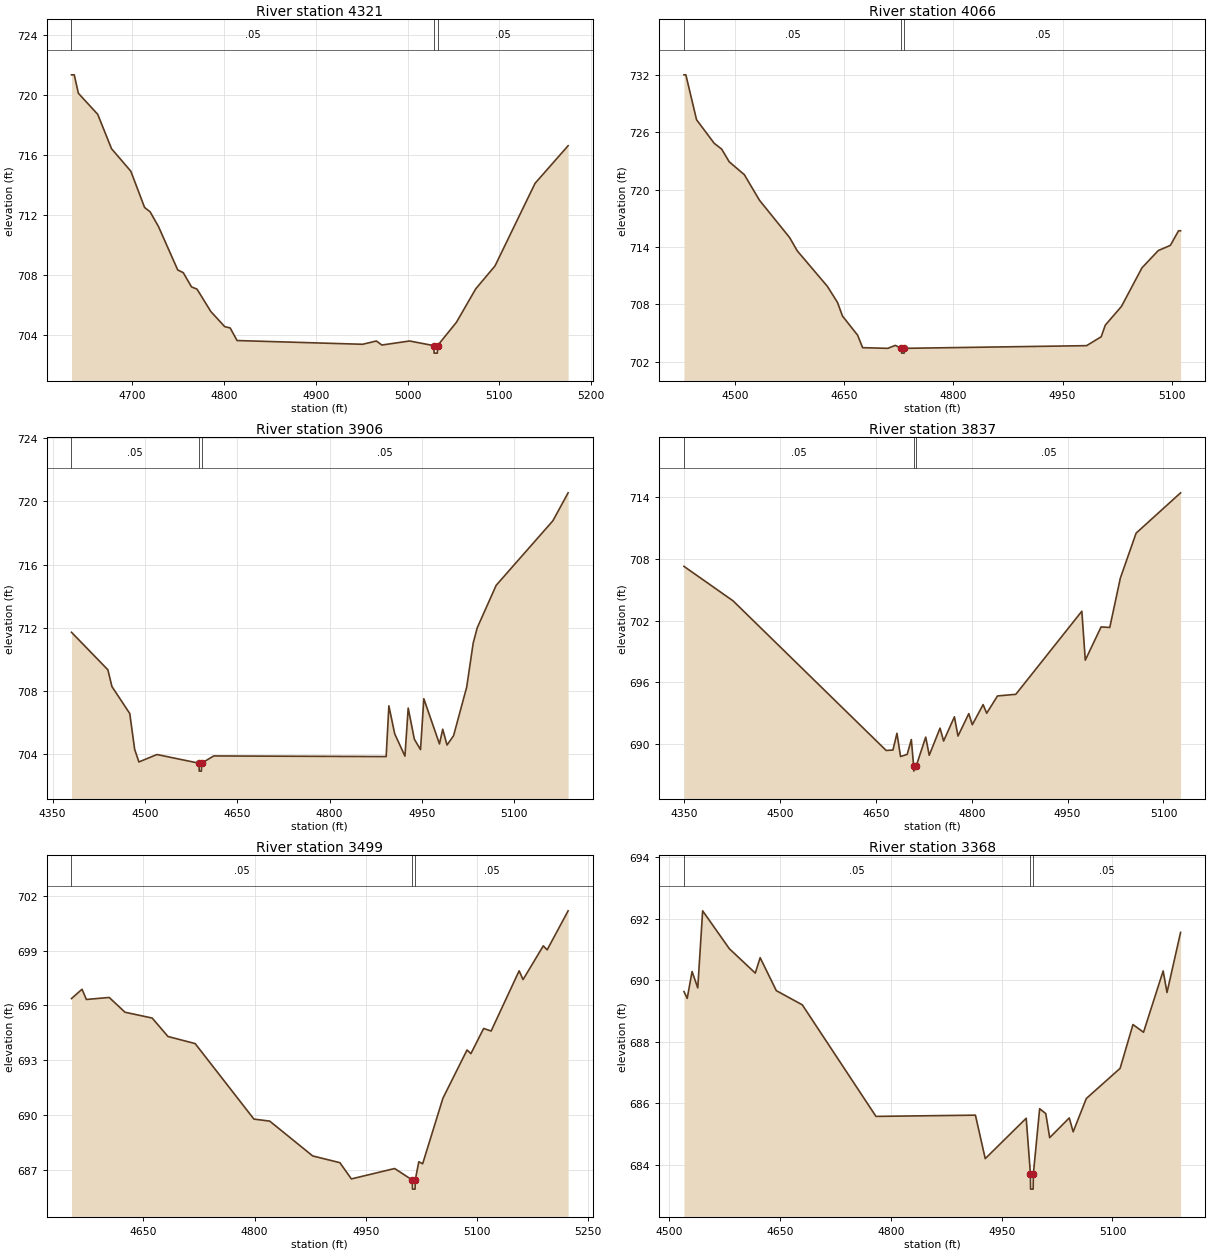
Type RM Length L Ch R = 1,4321,255,255,255
BEGIN DESCRIPTION:
Denton Creek Tributary 25 10.0
END DESCRIPTION:
XS GIS Cut Line= 3
      2322329.01      7112710.00      2322029.00      7112910.00
      2321879.03      7113009.98
#Sta/Elev= 30
  4634.0  721.35  4637.0  721.35  4641.5  720.12  4662.6  718.71  4677.6  716.42
  4698.6  714.92  4713.6  712.50  4719.6  712.21  4728.7  711.23  4749.7  708.33
  4755.7  708.15  4764.7  707.20  4770.7  707.05  4785.7  705.56  4800.8  704.55
  4806.8  704.46  4814.3  703.62  4951.0  703.37  4966.0  703.59  4972.0  703.32
  5002.1  703.59  5028.6  703.28  5028.9  702.78  5032.4  702.78  5032.6  703.28
  5053.2  704.84  5074.2  707.07  5095.2  708.60  5138.8  714.11  5174.8  716.62
#Mann=3,-1,0
  4634.0    0.05       0  5028.6    0.04       0  5032.6    0.05       0
Bank Sta=5028.6,5032.6
Exp/Cntr=0.3,0.1

Type RM Length L Ch R = 1,4066,160,160,160
BEGIN DESCRIPTION:
Denton Creek Tributary 25 9.0
END DESCRIPTION:
XS GIS Cut Line= 3
      2322379.01      7112610.00      2321829.00      7112760.00
      2321779.00      7112860.00
#Sta/Elev= 30
  4430.2  731.98  4432.8  731.98  4447.5  727.29  4471.7  724.83  4482.0  724.22
  4492.4  722.89  4513.1  721.55  4533.9  718.88  4575.3  714.98  4585.7  713.60
  4627.1  709.89  4641.0  708.21  4647.9  706.78  4668.6  704.79  4675.5  703.48
  4710.1  703.41  4720.4  703.72  4728.8  703.41  4729.1  702.91  4732.6  702.91
  4732.8  703.41  4983.0  703.69  5003.1  704.62  5008.7  705.83  5031.0  707.80
  5059.0  711.81  5081.4  713.62  5098.1  714.17  5109.3  715.69  5112.1  715.69
#Mann=3,-1,0
  4430.2    0.05       0  4728.8   0.033       0  4732.8    0.05       0
Bank Sta=4728.8,4732.8
Exp/Cntr=0.3,0.1

Type RM Length L Ch R = 1,3906,69,69,69
BEGIN DESCRIPTION:
Mapping XS 3182ef96
END DESCRIPTION:
XS GIS Cut Line= 4
      2322072.35      7112240.75      2321900.68      7112363.95
      2321722.61      7112612.20      2321624.46      7112885.07
#Sta/Elev= 30
  4380.7  711.72  4439.8  709.35  4446.4  708.29  4475.4  706.58  4483.3  704.32
  4490.2  703.52  4519.6  703.99  4588.0  703.44  4588.2  702.94  4591.7  702.94
  4592.0  703.44  4611.8  703.90  4891.9  703.86  4896.3  707.07  4905.8  705.30
  4922.4  703.89  4927.7  706.93  4937.7  704.96  4947.7  704.30  4953.1  707.52
  4978.5  704.66  4983.8  705.59  4990.8  704.59  5001.4  705.18  5022.7  708.25
  5033.3  711.04  5039.9  712.01  5070.6  714.69  5162.7  718.77  5187.5  720.54
#Mann=3,-1,0
  4380.7    0.05       0  4588.0    0.04       0  4592.0    0.05       0
Bank Sta=4588,4592
Exp/Cntr=0.3,0.1

Type RM Length L Ch R = 1,3837,338,338,338
BEGIN DESCRIPTION:
Mapping XS 15a8bd81
END DESCRIPTION:
XS GIS Cut Line= 4
      2321993.34      7112135.64      2321778.12      7112347.71
      2321683.32      7112540.28      2321590.49      7112783.48
#Sta/Elev= 30
  4349.7  707.29  4426.5  703.94  4666.1  689.39  4676.7  689.43  4683.0  691.06
  4688.6  688.80  4699.0  689.01  4705.5  690.45  4709.1  687.88  4709.3  687.38
  4713.1  687.88  4728.0  690.69  4733.5  688.92  4750.4  691.56  4756.0  690.31
  4772.9  692.66  4778.5  690.79  4795.4  692.97  4800.9  691.89  4817.8  693.85
  4823.4  693.01  4840.3  694.69  4869.0  694.85  4972.3  702.93  4977.7  698.17
  5002.4  701.40  5016.0  701.35  5032.5  706.14  5057.2  710.52  5126.8  714.44
#Mann=3,-1,0
  4349.7    0.05       0  4709.1    0.04       0  4713.1    0.05       0
Bank Sta=4709.1,4713.1
Exp/Cntr=0.3,0.1

Type RM Length L Ch R = 1,3499,131,131,131
BEGIN DESCRIPTION:
Mapping XS 2e636e51
END DESCRIPTION:
XS GIS Cut Line= 3
      2321811.74      7112023.42      2321584.74      7112393.25
      2321514.63      7112618.87
#Sta/Elev= 30
  4552.9  696.38  4567.1  696.89  4573.0  696.33  4603.8  696.44  4625.1  695.63
  4661.8  695.31  4683.1  694.30  4719.8  693.91  4799.1  689.77  4820.4  689.66
  4878.4  687.75  4915.1  687.38  4930.6  686.49  4989.0  687.06  5012.8  686.43
  5013.1  685.93  5016.6  685.93  5016.8  686.43  5021.6  687.43  5026.8  687.32
  5054.1  690.91  5086.7  693.56  5091.9  693.36  5109.1  694.74  5119.2  694.60
  5157.0  697.90  5162.3  697.42  5189.6  699.27  5194.8  699.05  5223.1  701.19
#Mann=3,-1,0
  4552.9    0.05       0  5012.8   0.033       0  5016.8    0.05       0
Bank Sta=5012.8,5016.8
Exp/Cntr=0.3,0.1

Type RM Length L Ch R = 1,3368,371,371,371
BEGIN DESCRIPTION:
Mapping XS db0f0ecb
END DESCRIPTION:
XS GIS Cut Line= 3
      2321737.15      7111971.97      2321534.86      7112145.47
      2321407.88      7112531.31
#Sta/Elev= 30
  4519.6  689.63  4524.0  689.41  4530.6  690.28  4538.3  689.75  4544.9  692.25
  4581.1  691.02  4616.2  690.23  4622.8  690.73  4644.7  689.66  4679.9  689.20
  4779.7  685.58  4914.4  685.62  4927.7  684.21  4983.2  685.52  4988.9  683.72
  4989.1  683.22  4992.6  683.22  4992.9  683.72  5001.4  685.83  5009.7  685.67
  5015.0  684.89  5041.5  685.53  5046.8  685.08  5064.6  686.16  5110.4  687.14
  5127.8  688.56  5142.1  688.31  5168.7  690.30  5173.9  689.60  5192.3  691.55
#Mann=3,-1,0
  4519.6    0.05       0  4988.9   0.033       0  4992.9    0.05       0
Bank Sta=4988.9,4992.9
Exp/Cntr=0.3,0.1

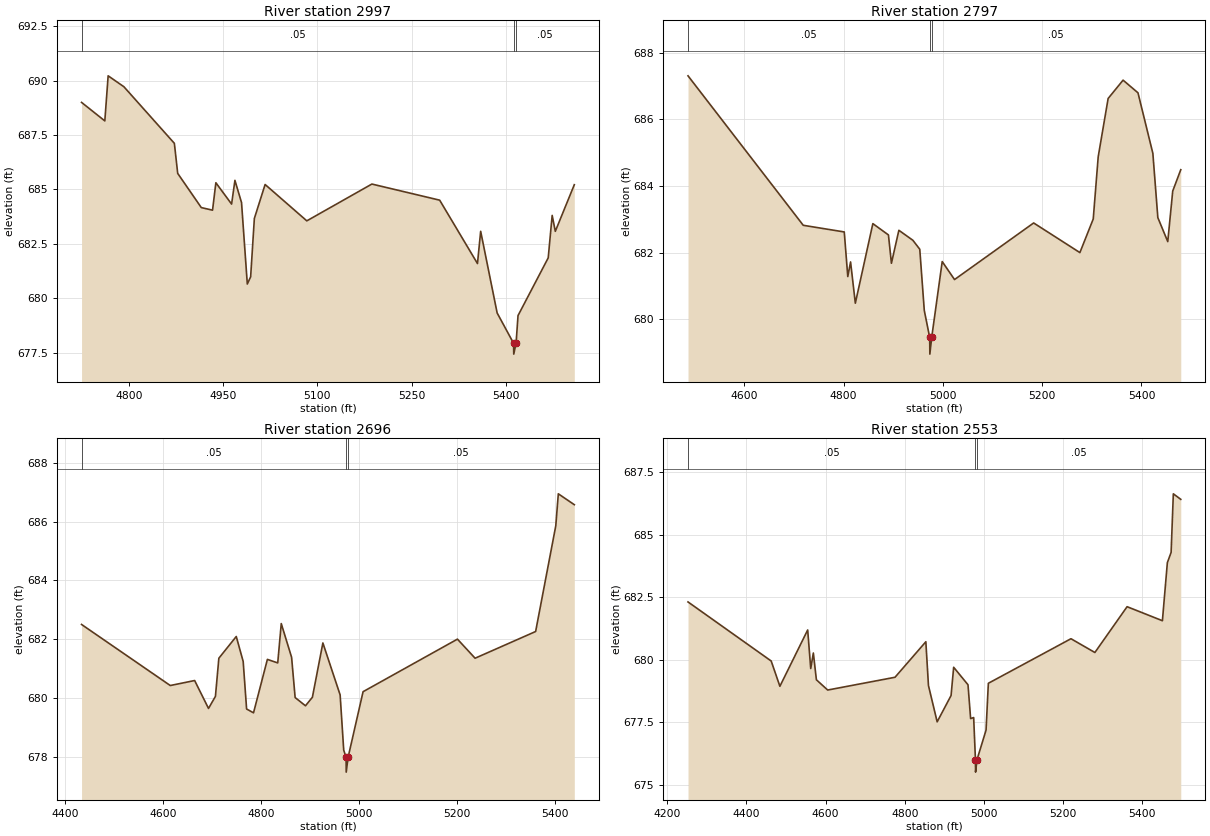
Type RM Length L Ch R = 1,2997,200,200,200
BEGIN DESCRIPTION:
Mapping XS 344b9967
END DESCRIPTION:
XS GIS Cut Line= 4
      2321737.38      7111911.61      2321475.71      7112009.15
      2321414.89      7112110.64      2321348.10      7112490.84
#Sta/Elev= 30
  4724.9  689.00  4761.9  688.15  4767.2  690.22  4792.2  689.72  4872.5  687.12
  4877.8  685.74  4915.3  684.17  4933.2  684.05  4938.5  685.31  4963.5  684.33
  4968.8  685.42  4979.3  684.40  4988.5  680.66  4993.8  680.99  4999.7  683.67
  5016.8  685.23  5083.1  683.56  5186.6  685.25  5294.4  684.51  5354.5  681.60
  5359.6  683.08  5385.8  679.33  5411.9  677.94  5412.2  677.44  5415.9  677.94
  5419.0  679.21  5467.0  681.86  5473.3  683.81  5478.3  683.08  5508.5  685.22
#Mann=3,-1,0
  4724.9    0.05       0  5411.9   0.033       0  5415.9    0.05       0
Bank Sta=5411.9,5415.9
Exp/Cntr=0.3,0.1

Type RM Length L Ch R = 1,2797,101,101,101
BEGIN DESCRIPTION:
Mapping XS ca9aa72d
END DESCRIPTION:
XS GIS Cut Line= 4
      2321751.07      7111731.66      2321408.45      7111901.06
      2321325.53      7112026.55      2321340.82      7112486.17
#Sta/Elev= 30
  4486.7  687.31  4718.8  682.82  4801.4  682.62  4808.5  681.28  4814.1  681.72
  4823.7  680.48  4859.0  682.87  4890.4  682.53  4896.4  681.68  4911.4  682.67
  4939.6  682.37  4953.5  682.10  4962.6  680.26  4973.5  679.45  4973.8  678.95
  4977.5  679.45  4998.7  681.73  5023.5  681.19  5182.9  682.89  5276.0  682.00
  5302.9  683.01  5312.9  684.88  5332.9  686.63  5363.0  687.18  5393.0  686.80
  5423.0  684.98  5433.0  683.05  5453.0  682.33  5463.0  683.85  5479.2  684.49
#Mann=3,-1,0
  4486.7    0.05       0  4973.5   0.033       0  4977.5    0.05       0
Bank Sta=4973.5,4977.5
Exp/Cntr=0.3,0.1

Type RM Length L Ch R = 1,2696,143,143,143
BEGIN DESCRIPTION:
Mapping XS 769ef960
END DESCRIPTION:
XS GIS Cut Line= 3
      2321627.23      7111602.20      2321228.08      7112016.82
      2321332.72      7112433.56
#Sta/Elev= 30
  4433.9  682.50  4614.9  680.42  4664.6  680.59  4692.9  679.64  4707.0  680.05
  4714.0  681.35  4749.5  682.09  4763.6  681.24  4770.6  679.62  4784.7  679.49
  4813.0  681.31  4834.1  681.19  4841.3  682.53  4862.4  681.38  4869.6  680.01
  4890.7  679.73  4904.8  680.02  4926.2  681.87  4961.4  680.10  4968.7  678.22
  4973.6  677.97  4973.8  677.47  4977.6  677.97  5008.2  680.21  5200.7  682.00
  5236.7  681.35  5360.2  682.26  5401.3  685.86  5406.5  686.95  5439.1  686.58
#Mann=3,-1,0
  4433.9    0.05       0  4973.6   0.033       0  4977.6    0.05       0
Bank Sta=4973.6,4977.6
Exp/Cntr=0.3,0.1

Type RM Length L Ch R = 1,2553,0,0,0
BEGIN DESCRIPTION:
Denton Creek Tributary 25 7.0
END DESCRIPTION:
XS GIS Cut Line= 3
      2321646.95      7111521.18      2321087.00      7112001.42
      2321323.61      7112449.95
#Sta/Elev= 30
  4252.6  682.31  4462.7  679.95  4484.7  678.94  4554.9  681.19  4562.6  679.65
  4569.2  680.27  4576.9  679.20  4605.4  678.79  4775.5  679.30  4853.4  680.72
  4860.0  678.97  4882.0  677.52  4917.1  678.57  4923.7  679.70  4959.9  679.00
  4966.5  677.65  4974.2  677.69  4978.7  676.01  4979.0  675.51  4982.7  676.01
  5005.5  677.19  5011.3  679.06  5220.0  680.84  5280.4  680.29  5361.8  682.12
  5451.0  681.56  5463.5  683.88  5473.0  684.29  5478.6  686.63  5497.4  686.41
#Mann=3,-1,0
  4252.6    0.05       0  4978.7   0.033       0  4982.7    0.05       0
Bank Sta=4978.7,4982.7
Exp/Cntr=0.3,0.1

Chan Stop Cuts=-1