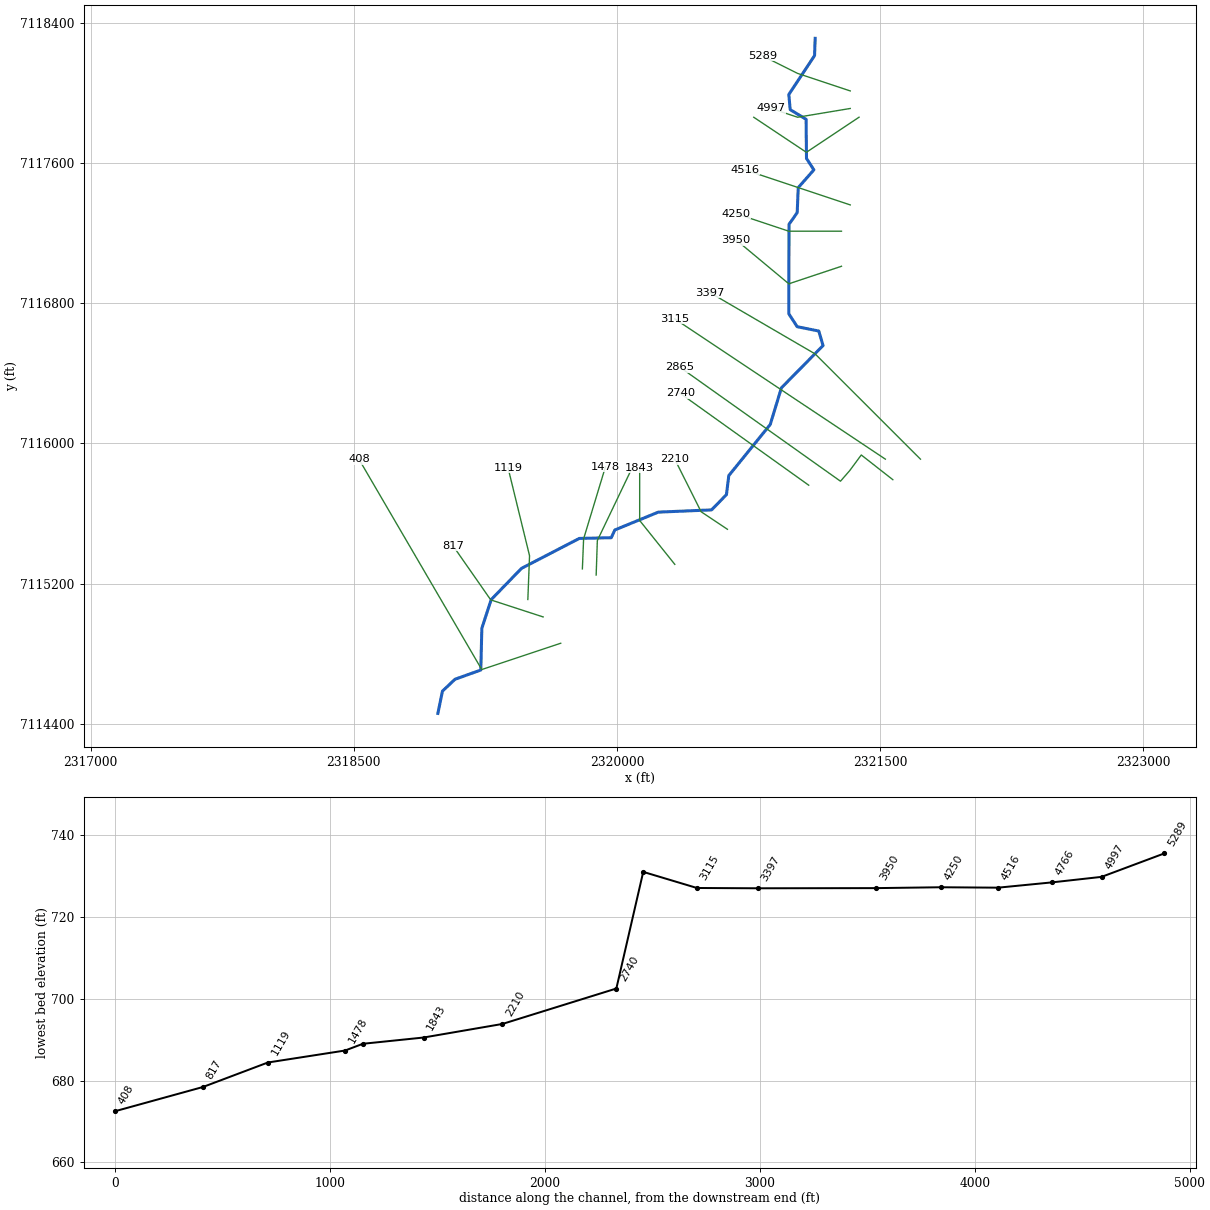
--- Denton Creek Tributary 27.prj (project) ---

Proj Title=Denton Creek Tributary 27 Base Level Engineering
Current Plan=p01
Default Exp/Contr=0.3,0.1
English Units
Geom File=g01
Flow File=f01
Plan File=p01
BEGIN DESCRIPTION:
Denton Creek Tributary 27
END DESCRIPTION:

--- Denton Creek Tributary 27.p01 (plan) ---

Plan Title=Multiple Run
Short Identifier=Multiple
Geom File=g01
Flow File=f01
Subcritical Flow
K Sum by GR= 0
Std Step Tol= 0.01
Critical Tol= 0.01
Num of Std Step Trials= 20
Max Error Tol= 0.3
Flow Tol Ratio= 0.001
Split Flow NTrial= 30
Split Flow Tol= 0.02
Split Flow Ratio= 0.02
Log Output Level= 0
Friction Slope Method= 1
Unsteady Friction Slope Method= 2
Unsteady Bridges Friction Slope Method= 1
Parabolic Critical Depth
Global Vel Dist=  1 , 1 , 1
Global Log Level= 0
CheckData=True
Encroach Param= -1, 0, 0, 0
BEGIN DESCRIPTION:
Multiple Run
END DESCRIPTION:

--- Denton Creek Tributary 27.f01 (steady flow) ---

Flow Title=Multiple
Number of Profiles=7
Profile Names=10-year,25-year,50-year,1pct_min,100-year,1pct_plu,500-year
River Rch & RM= Denton Creek Tri,Reach-1,5289
     285     376     448     266     531    1059     746
River Rch & RM= Denton Creek Tri,Reach-1,3950
     489     669     817     497     991    1977    1460
Boundary for River Rch & Prof#=Denton Creek Tri,Reach-1,1
Up Type=0
Dn Type=3
Dn Slope=0.005
Boundary for River Rch & Prof#=Denton Creek Tri,Reach-1,2
Up Type=0
Dn Type=3
Dn Slope=0.005
Boundary for River Rch & Prof#=Denton Creek Tri,Reach-1,3
Up Type=0
Dn Type=3
Dn Slope=0.005
Boundary for River Rch & Prof#=Denton Creek Tri,Reach-1,4
Up Type=0
Dn Type=3
Dn Slope=0.005
Boundary for River Rch & Prof#=Denton Creek Tri,Reach-1,5
Up Type=0
Dn Type=3
Dn Slope=0.005
Boundary for River Rch & Prof#=Denton Creek Tri,Reach-1,6
Up Type=0
Dn Type=3
Dn Slope=0.005
Boundary for River Rch & Prof#=Denton Creek Tri,Reach-1,7
Up Type=0
Dn Type=3
Dn Slope=0.005

--- Denton Creek Tributary 27.g01 (geometry) ---

Geom Title=Existing Conditions

River Reach=Denton Creek Tri,Reach-1
Reach XY= 30
      2321129.00      7118310.00      2321125.61      7118211.41
      2320978.88      7117989.90      2320986.69      7117903.57
      2321077.36      7117848.17      2321079.66      7117625.16
      2321121.67      7117559.90      2321032.57      7117458.53
      2321026.73      7117315.94      2320980.22      7117249.50
      2320978.54      7116739.74      2321026.29      7116665.41
      2321149.75      7116640.53      2321173.95      7116557.74
      2320936.50      7116316.32      2320873.16      7116107.71
      2320636.88      7115816.17      2320623.48      7115707.56
      2320538.83      7115620.47      2320234.94      7115607.74
      2319987.65      7115506.10      2319967.05      7115461.92
      2319784.93      7115457.76      2319455.53      7115286.99
      2319282.61      7115108.50      2319229.52      7114944.78
      2319223.66      7114707.26      2319076.56      7114654.48
      2319005.16      7114586.93      2318979.00      7114460.00

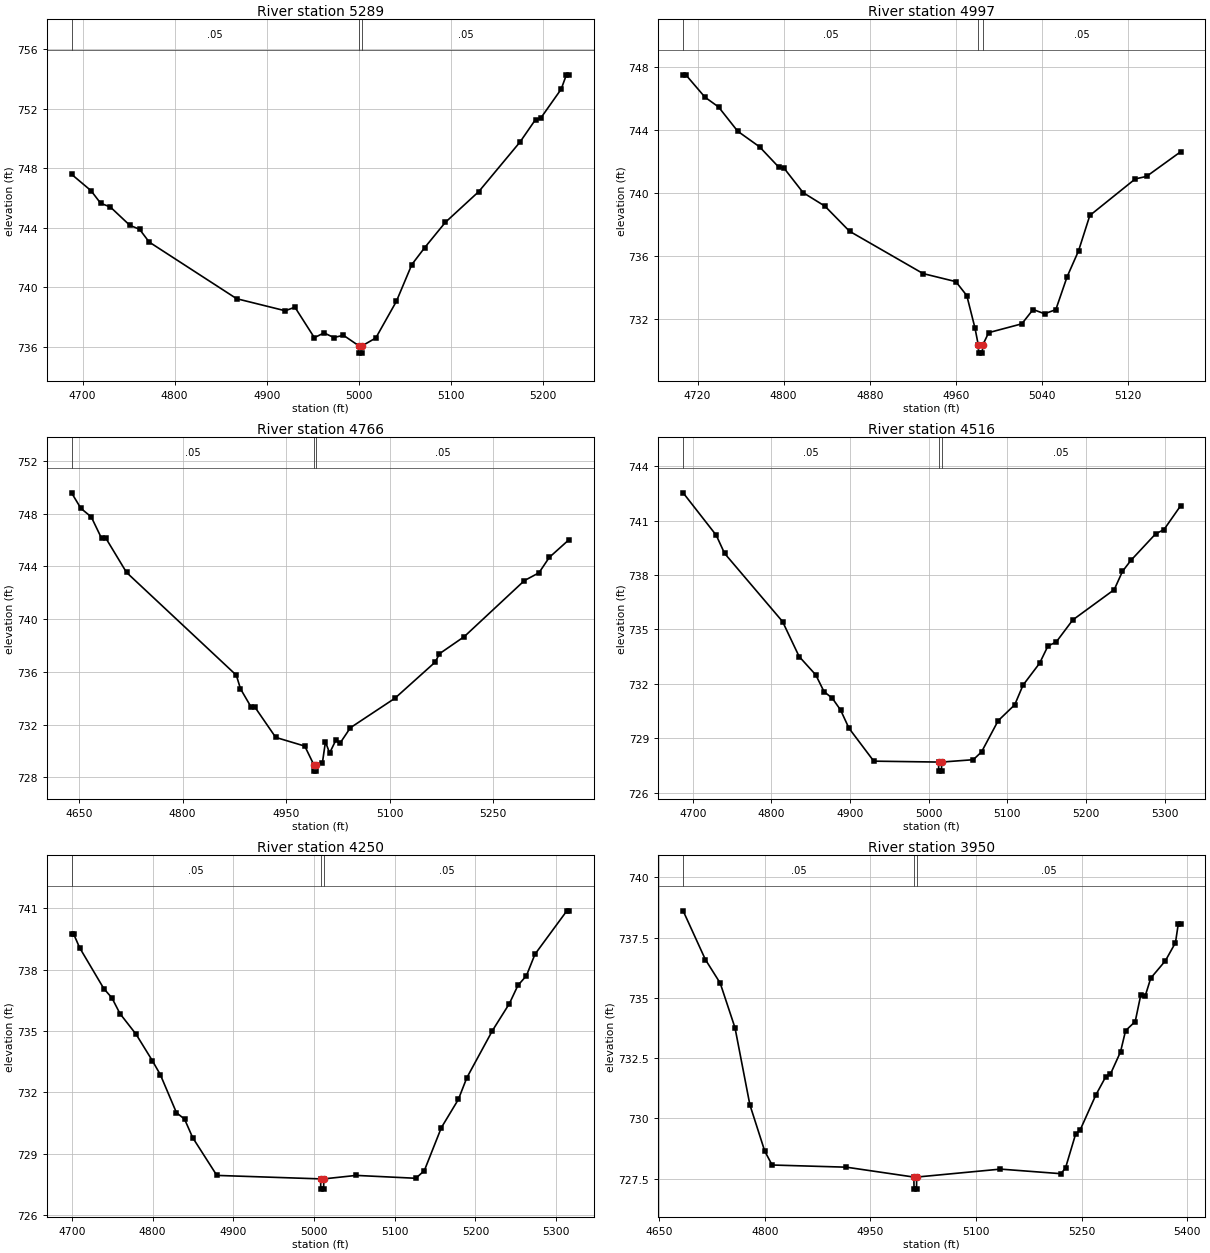
Type RM Length L Ch R = 1,5289,292,292,292
BEGIN DESCRIPTION:
Denton Creek Tributary 27 16.0
END DESCRIPTION:
XS GIS Cut Line= 3
      2321328.98      7118010.01      2321029.00      7118110.00
      2320829.01      7118209.99
#Sta/Elev= 30
  4688.1  747.59  4709.2  746.49  4719.7  745.64  4730.2  745.39  4751.3  744.16
  4761.9  743.89  4772.4  743.03  4867.3  739.22  4920.0  738.41  4930.5  738.65
  4951.6  736.60  4962.1  736.92  4972.7  736.61  4983.2  736.76  4999.7  736.06
  4999.9  735.56  5003.4  735.56  5003.7  736.06  5018.3  736.58  5040.6  739.04
  5057.4  741.52  5071.4  742.66  5093.8  744.36  5130.1  746.43  5174.8  749.76
  5191.6  751.27  5197.2  751.36  5219.5  753.32  5225.1  754.28  5227.9  754.28
#Mann=3,-1,0
  4688.1    0.05       0  4999.7   0.033       0  5003.7    0.05       0
Bank Sta=4999.7,5003.7
Exp/Cntr=0.3,0.1

Type RM Length L Ch R = 1,4997,231,231,231
BEGIN DESCRIPTION:
Denton Creek Tributary 27 15.0
END DESCRIPTION:
XS GIS Cut Line= 3
      2321328.99      7117910.00      2321029.00      7117860.00
      2320879.04      7117909.99
#Sta/Elev= 30
  4706.6  747.49  4709.1  747.49  4726.9  746.07  4739.5  745.45  4757.3  743.91
  4777.6  742.92  4795.3  741.64  4800.4  741.56  4818.1  740.01  4838.4  739.15
  4861.2  737.56  4929.6  734.87  4960.0  734.36  4970.2  733.47  4977.8  731.41
  4980.9  730.32  4981.1  729.82  4984.6  729.82  4984.9  730.32  4990.5  731.12
  5021.3  731.68  5031.8  732.59  5042.4  732.32  5052.9  732.58  5063.4  734.67
  5074.0  736.31  5084.5  738.56  5126.7  740.88  5137.2  741.04  5168.8  742.60
#Mann=3,-1,0
  4706.6    0.05       0  4980.9   0.033       0  4984.9    0.05       0
Bank Sta=4980.9,4984.9
Exp/Cntr=0.3,0.1

Type RM Length L Ch R = 1,4766,250,250,250
BEGIN DESCRIPTION:
Denton Creek Tributary 27 14.0
END DESCRIPTION:
XS GIS Cut Line= 3
      2321379.03      7117860.02      2321079.00      7117660.00
      2320779.04      7117859.97
#Sta/Elev= 30
  4639.0  749.59  4652.6  748.41  4667.6  747.76  4682.6  746.13  4688.6  746.16
  4718.7  743.55  4877.9  735.75  4883.9  734.72  4898.9  733.37  4904.9  733.32
  4935.0  731.03  4977.1  730.37  4990.1  728.97  4990.3  728.47  4993.8  728.47
  4994.1  728.97  5002.6  729.07  5007.1  730.70  5013.1  729.84  5022.1  730.81
  5028.1  730.58  5043.2  731.76  5107.8  734.00  5166.3  736.75  5172.4  737.38
  5208.4  738.68  5295.5  742.93  5316.6  743.52  5331.6  744.69  5360.1  746.03
#Mann=3,-1,0
  4639.0    0.05       0  4990.1   0.033       0  4994.1    0.05       0
Bank Sta=4990.1,4994.1
Exp/Cntr=0.3,0.1

Type RM Length L Ch R = 1,4516,266,266,266
BEGIN DESCRIPTION:
Denton Creek Tributary 27 13.0
END DESCRIPTION:
XS GIS Cut Line= 3
      2321328.96      7117360.01      2321029.00      7117460.00
      2320729.01      7117560.00
#Sta/Elev= 30
  4687.7  742.53  4729.8  740.19  4740.4  739.19  4814.1  735.43  4835.2  733.50
  4856.3  732.49  4866.9  731.56  4877.4  731.20  4887.9  730.55  4898.5  729.55
  4930.1  727.73  5012.4  727.68  5012.7  727.18  5016.2  727.18  5016.4  727.68
  5056.6  727.81  5067.1  728.24  5088.2  729.96  5109.3  730.84  5119.8  731.92
  5140.9  733.13  5151.5  734.08  5162.0  734.30  5183.1  735.52  5235.8  737.19
  5246.3  738.20  5256.9  738.80  5288.5  740.27  5299.0  740.50  5320.1  741.81
#Mann=3,-1,0
  4687.7    0.05       0  5012.4   0.033       0  5016.4    0.05       0
Bank Sta=5012.4,5016.4
Exp/Cntr=0.3,0.1

Type RM Length L Ch R = 1,4250,300,300,300
BEGIN DESCRIPTION:
Denton Creek Tributary 27 12.0
END DESCRIPTION:
XS GIS Cut Line= 3
      2321278.99      7117210.00      2320979.00      7117210.00
      2320679.02      7117309.99
#Sta/Elev= 30
  4699.6  739.75  4702.1  739.75  4709.6  739.07  4739.6  737.07  4749.6  736.62
  4759.6  735.85  4779.6  734.84  4799.6  733.56  4809.6  732.87  4829.6  731.01
  4839.6  730.70  4849.6  729.80  4879.6  727.95  5008.1  727.78  5008.4  727.28
  5011.9  727.28  5012.1  727.78  5052.3  727.95  5126.1  727.81  5136.6  728.18
  5157.7  730.28  5178.8  731.66  5189.3  732.72  5221.0  735.02  5242.0  736.34
  5252.6  737.23  5263.1  737.70  5273.7  738.75  5313.2  740.87  5315.8  740.87
#Mann=3,-1,0
  4699.6    0.05       0  5008.1   0.033       0  5012.1    0.05       0
Bank Sta=5008.1,5012.1
Exp/Cntr=0.3,0.1

Type RM Length L Ch R = 1,3950,553,553,553
BEGIN DESCRIPTION:
Denton Creek Tributary 27 11.0
END DESCRIPTION:
XS GIS Cut Line= 3
      2321278.95      7117009.98      2320979.00      7116910.00
      2320678.99      7117160.01
#Sta/Elev= 30
  4683.8  738.61  4715.4  736.59  4736.5  735.61  4757.5  733.76  4778.6  730.57
  4799.7  728.65  4810.2  728.07  4915.7  727.98  5011.6  727.57  5011.9  727.07
  5015.4  727.07  5015.6  727.57  5134.7  727.90  5220.6  727.71  5227.1  727.95
  5241.4  729.35  5248.0  729.53  5270.1  730.97  5284.4  731.74  5290.9  731.84
  5305.2  732.76  5312.4  733.64  5326.1  734.02  5333.9  735.11  5340.4  735.09
  5348.2  735.82  5369.0  736.54  5383.3  737.29  5387.2  738.05  5390.5  738.05
#Mann=3,-1,0
  4683.8    0.05       0  5011.6   0.033       0  5015.6    0.05       0
Bank Sta=5011.6,5015.6
Exp/Cntr=0.3,0.1

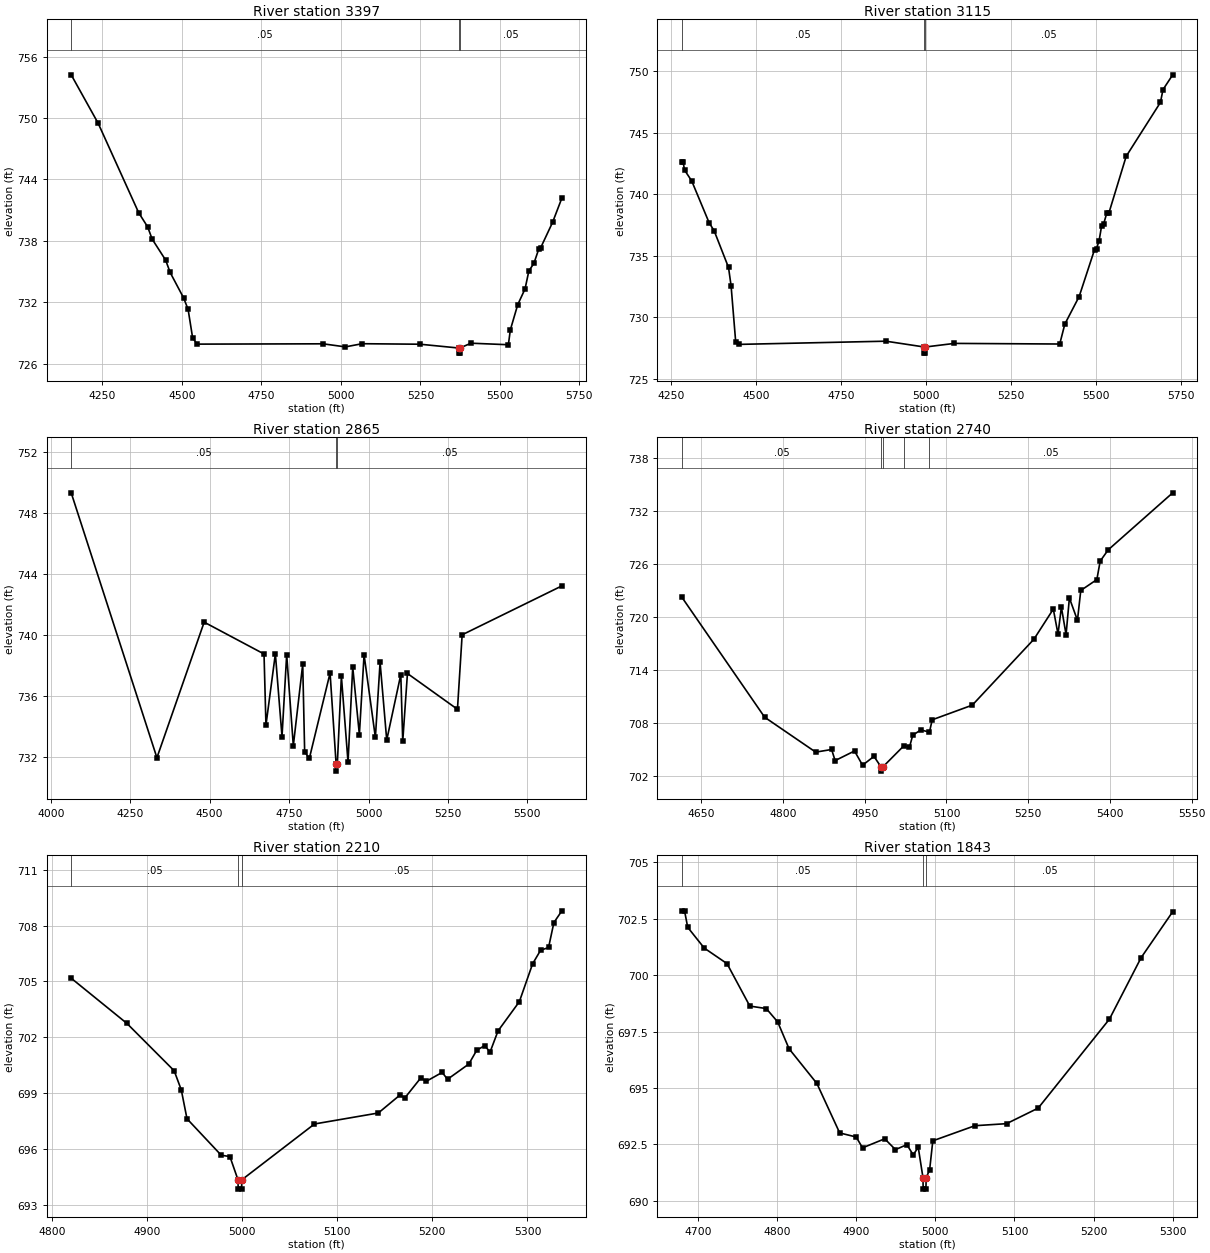
Type RM Length L Ch R = 1,3397,282,282,282
BEGIN DESCRIPTION:
Denton Creek Tributary 27 10.0
END DESCRIPTION:
XS GIS Cut Line= 3
      2321729.03      7115909.97      2321129.00      7116510.00
      2320528.99      7116860.01
#Sta/Elev= 30
  4151.7  754.22  4236.6  749.48  4363.9  740.75  4392.2  739.36  4406.3  738.17
  4448.7  736.12  4462.9  734.91  4505.3  732.42  4519.4  731.30  4533.6  728.52
  4547.7  727.91  4943.7  727.94  5013.9  727.64  5066.8  727.95  5248.8  727.90
  5370.0  727.53  5370.2  727.03  5373.7  727.03  5374.0  727.53  5409.2  728.00
  5526.6  727.85  5532.8  729.30  5556.0  731.76  5579.1  733.31  5591.1  735.07
  5606.8  735.79  5622.5  737.23  5628.3  737.33  5665.5  739.80  5694.9  742.18
#Mann=3,-1,0
  4151.7    0.05       0  5370.0   0.033       0  5374.0    0.05       0
Bank Sta=5370,5374
Exp/Cntr=0.3,0.1

Type RM Length L Ch R = 1,3115,250,250,250
BEGIN DESCRIPTION:
Denton Creek Tributary 27 9.0
END DESCRIPTION:
XS GIS Cut Line= 3
      2321529.00      7115910.00      2320929.00      7116310.00
      2320329.02      7116709.99
#Sta/Elev= 30
  4282.7  742.66  4285.7  742.66  4290.2  741.97  4311.2  741.09  4362.3  737.70
  4377.3  737.03  4419.4  734.06  4426.9  732.58  4440.4  728.04  4449.5  727.81
  4882.1  728.07  4994.3  727.60  4994.5  727.10  4998.0  727.10  4998.3  727.60
  5083.4  727.89  5392.9  727.84  5407.9  729.46  5450.0  731.70  5495.1  735.50
  5501.1  735.59  5508.6  736.24  5516.1  737.46  5522.1  737.61  5531.1  738.47
  5537.1  738.46  5588.2  743.09  5688.9  747.47  5696.4  748.51  5724.9  749.71
#Mann=3,-1,0
  4282.7    0.05       0  4994.3   0.033       0  4998.3    0.05       0
Bank Sta=4994.3,4998.3
Exp/Cntr=0.3,0.1

Type RM Length L Ch R = 1,2865,125,125,125
BEGIN DESCRIPTION:
Mapping XS 123b2d6d
END DESCRIPTION:
XS GIS Cut Line= 5
      2321571.69      7115792.75      2321391.86      7115933.77
      2321325.66      7115844.27      2321273.35      7115784.10
      2320356.46      7116435.66
#Sta/Elev= 30
  4064.2  749.31  4334.0  731.92  4482.7  740.82  4671.1  738.73  4677.2  734.06
  4706.8  738.74  4727.7  733.31  4742.4  738.69  4763.3  732.71  4792.9  738.06
  4799.0  732.30  4813.8  731.88  4879.0  737.48  4897.9  731.54  4898.1  731.04
  4901.9  731.54  4914.6  737.26  4935.5  731.63  4950.3  737.87  4971.2  733.44
  4986.0  738.68  5021.6  733.25  5036.4  738.18  5057.3  733.08  5101.6  737.38
  5107.7  733.00  5122.5  737.45  5279.9  735.10  5294.7  739.99  5608.6  743.20
#Mann=3,-1,0
  4064.2    0.05       0  4897.9   0.033       0  4901.9    0.05       0
Bank Sta=4897.9,4901.9
Exp/Cntr=0.3,0.1

Type RM Length L Ch R = 1,2740,530,530,530
BEGIN DESCRIPTION:
Mapping XS 51cbbc54
END DESCRIPTION:
XS GIS Cut Line= 2
      2321092.34      7115761.33      2320359.88      7116285.35
#Sta/Elev= 30
  4614.6  722.17  4766.3  708.61  4860.0  704.66  4889.2  704.96  4895.6  703.70
  4931.2  704.79  4946.0  703.18  4966.9  704.18  4979.6  703.01  4979.9  702.51
  4983.6  703.01  5021.8  705.38  5032.0  705.20  5038.1  706.58  5052.9  707.17
  5068.8  706.93  5073.8  708.32  5147.4  709.98  5260.5  717.44  5296.1  720.85
  5304.7  718.02  5310.9  721.06  5319.5  717.96  5325.6  722.11  5340.4  719.58
  5346.5  722.96  5376.0  724.19  5382.1  726.28  5396.9  727.56  5515.2  734.01
#Mann=5,-1,0
  4614.6    0.05       0  4979.6   0.033       0  4983.6    0.05       0
  5021.8    0.12       0  5068.8    0.05       0
Bank Sta=4979.6,4983.6
Exp/Cntr=0.3,0.1

Type RM Length L Ch R = 1,2210,367,367,367
BEGIN DESCRIPTION:
Denton Creek Tributary 27 6.0
END DESCRIPTION:
XS GIS Cut Line= 3
      2320629.00      7115510.00      2320479.00      7115610.00
      2320328.99      7115910.01
#Sta/Elev= 30
  4820.5  705.17  4879.1  702.74  4928.7  700.20  4936.2  699.17  4942.2  697.62
  4978.2  695.66  4987.3  695.59  4995.8  694.34  4996.0  693.84  4999.5  693.84
  4999.8  694.34  5076.2  697.34  5143.3  697.93  5165.7  698.88  5171.3  698.75
  5188.0  699.82  5193.6  699.63  5210.4  700.11  5216.0  699.74  5238.4  700.56
  5246.7  701.30  5255.1  701.55  5260.7  701.20  5269.1  702.34  5291.5  703.91
  5305.4  705.94  5313.8  706.67  5322.2  706.82  5327.8  708.16  5336.2  708.79
#Mann=3,-1,0
  4820.5    0.05       0  4995.8    0.04       0  4999.8    0.05       0
Bank Sta=4995.8,4999.8
Exp/Cntr=0.3,0.1

Type RM Length L Ch R = 1,1843,282,282,282
BEGIN DESCRIPTION:
Denton Creek Tributary 27 5.0
END DESCRIPTION:
XS GIS Cut Line= 3
      2320329.02      7115309.97      2320129.00      7115560.00
      2320129.00      7115860.00
#Sta/Elev= 30
  4679.8  702.85  4683.0  702.85  4687.0  702.12  4707.9  701.20  4736.7  700.51
  4765.5  698.63  4786.3  698.52  4800.7  697.93  4815.1  696.74  4850.3  695.20
  4879.1  693.01  4899.9  692.83  4908.0  692.35  4936.0  692.75  4949.6  692.27
  4964.0  692.49  4972.0  692.04  4978.4  692.37  4984.4  691.02  4984.6  690.52
  4988.1  690.52  4988.4  691.02  4992.8  691.38  4996.8  692.66  5050.0  693.33
  5090.0  693.42  5130.0  694.11  5220.0  698.05  5260.0  700.77  5300.0  702.81
#Mann=3,-1,0
  4679.8    0.05       0  4984.4    0.04       0  4988.4    0.05       0
Bank Sta=4984.4,4988.4
Exp/Cntr=0.3,0.1

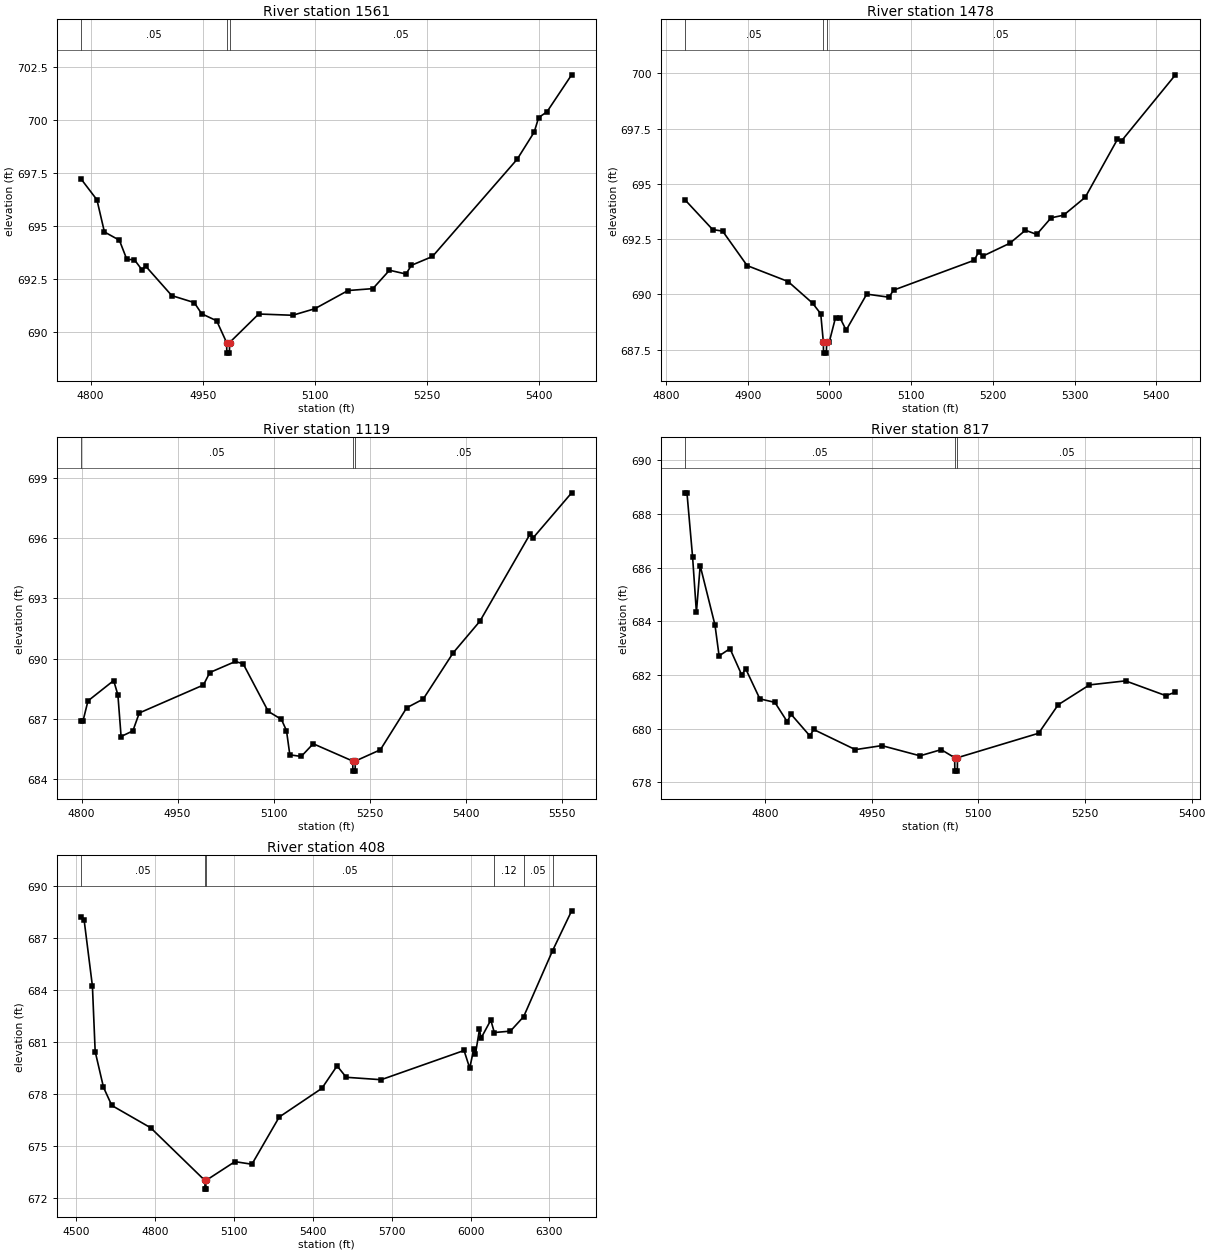
Type RM Length L Ch R = 1,1561,83,83,83
BEGIN DESCRIPTION:
Mapping XS ff4a44cc
END DESCRIPTION:
XS GIS Cut Line= 3
      2319881.06      7115249.11      2319887.79      7115445.63
      2320085.79      7115859.80
#Sta/Elev= 30
  4787.6  697.21  4808.5  696.24  4818.5  694.72  4838.5  694.33  4848.5  693.42
  4858.5  693.41  4868.5  692.94  4873.5  693.11  4908.6  691.71  4938.6  691.38
  4948.6  690.85  4968.6  690.52  4981.9  689.49  4982.2  688.99  4985.7  688.99
  4985.9  689.49  5024.8  690.84  5070.2  690.78  5099.9  691.09  5144.3  691.95
  5177.5  692.04  5199.7  692.91  5221.8  692.73  5228.9  693.14  5257.2  693.56
  5370.5  698.16  5393.2  699.44  5399.2  700.13  5410.3  700.40  5443.3  702.15
#Mann=3,-1,0
  4787.6    0.05       0  4981.9    0.04       0  4985.9    0.05       0
Bank Sta=4981.9,4985.9
Exp/Cntr=0.3,0.1

Type RM Length L Ch R = 1,1478,359,359,359
BEGIN DESCRIPTION:
Mapping XS b075d2b4
END DESCRIPTION:
XS GIS Cut Line= 3
      2319802.50      7115284.14      2319809.51      7115455.34
      2319933.77      7115865.70
#Sta/Elev= 30
  4823.4  694.27  4857.1  692.93  4869.3  692.86  4899.3  691.30  4949.4  690.58
  4979.4  689.60  4989.4  689.12  4992.6  687.84  4992.8  687.34  4996.3  687.34
  4996.6  687.84  4999.8  687.84  5007.5  688.95  5012.8  688.95  5020.5  688.38
  5045.7  690.01  5072.8  689.87  5078.6  690.19  5177.2  691.54  5182.6  691.91
  5187.8  691.73  5220.8  692.31  5239.9  692.90  5253.7  692.71  5271.3  693.46
  5286.6  693.58  5313.1  694.39  5352.5  697.01  5357.7  696.95  5423.5  699.93
#Mann=3,-1,0
  4823.4    0.05       0  4992.6    0.04       0  4996.6    0.05       0
Bank Sta=4992.6,4996.6
Exp/Cntr=0.3,0.1

Type RM Length L Ch R = 1,1119,302,302,302
BEGIN DESCRIPTION:
Denton Creek Tributary 27 3.0
END DESCRIPTION:
XS GIS Cut Line= 3
      2319491.72      7115109.56      2319501.43      7115359.01
      2319378.99      7115860.03
#Sta/Elev= 30
  4799.7  686.91  4802.4  686.91  4810.1  687.90  4850.2  688.91  4856.8  688.20
  4861.8  686.13  4880.2  686.41  4890.2  687.30  4990.3  688.69  5000.3  689.31
  5040.3  689.86  5052.4  689.74  5091.5  687.38  5112.1  686.98  5120.0  686.42
  5125.2  685.22  5143.0  685.14  5161.7  685.77  5223.4  684.91  5223.6  684.41
  5227.1  684.41  5227.4  684.91  5266.5  685.47  5307.7  687.56  5333.4  687.99
  5380.2  690.29  5421.9  691.86  5500.0  696.18  5505.2  696.01  5565.1  698.24
#Mann=3,-1,0
  4799.7    0.05       0  5223.4    0.04       0  5227.4    0.05       0
Bank Sta=5223.4,5227.4
Exp/Cntr=0.3,0.1

Type RM Length L Ch R = 1,817,409,409,409
BEGIN DESCRIPTION:
Denton Creek Tributary 27 2.0
END DESCRIPTION:
XS GIS Cut Line= 3
      2319578.97      7115010.01      2319280.32      7115107.28
      2319065.70      7115415.29
#Sta/Elev= 30
  4687.7  688.78  4690.3  688.78  4698.2  686.40  4703.6  684.33  4708.9  686.07
  4729.7  683.86  4735.5  682.71  4750.8  682.98  4767.5  681.99  4772.7  682.24
  4792.8  681.11  4813.9  680.98  4831.3  680.26  4836.6  680.54  4863.2  679.73
  4868.5  679.97  4927.1  679.22  4964.3  679.37  5018.1  678.99  5047.8  679.22
  5066.7  678.92  5067.0  678.42  5070.5  678.42  5070.7  678.92  5184.8  679.83
  5212.3  680.89  5256.3  681.63  5307.0  681.78  5363.7  681.23  5377.2  681.36
#Mann=3,-1,0
  4687.7    0.05       0  5066.7   0.035       0  5070.7    0.05       0
Bank Sta=5066.7,5070.7
Exp/Cntr=0.3,0.1

Type RM Length L Ch R = 1,408,0,0,0
BEGIN DESCRIPTION:
Denton Creek Tributary 27 1.0
END DESCRIPTION:
XS GIS Cut Line= 3
      2319679.00      7114860.00      2319229.00      7114710.00
      2318528.99      7115910.02
#Sta/Elev= 30
  4520.8  688.25  4531.3  688.08  4563.0  684.24  4573.5  680.45  4605.1  678.38
  4636.7  677.33  4784.3  676.04  4990.5  672.99  4990.8  672.49  4994.3  672.49
  4994.5  672.99  5104.7  674.08  5169.2  673.93  5273.0  676.66  5435.1  678.32
  5492.9  679.62  5527.7  678.96  5660.4  678.82  5975.5  680.51  5997.0  679.49
  6012.7  680.62  6018.5  680.28  6034.2  681.74  6040.0  681.22  6077.2  682.27
  6090.5  681.55  6151.6  681.63  6202.1  682.47  6312.1  686.29  6384.4  688.59
#Mann=6,-1,0
  4520.8    0.05       0  4990.5   0.035       0  4994.5    0.05       0
  6090.5    0.12       0  6202.1    0.05       0  6312.1    0.12       0
Bank Sta=4990.5,4994.5
Exp/Cntr=0.3,0.1

Chan Stop Cuts=-1