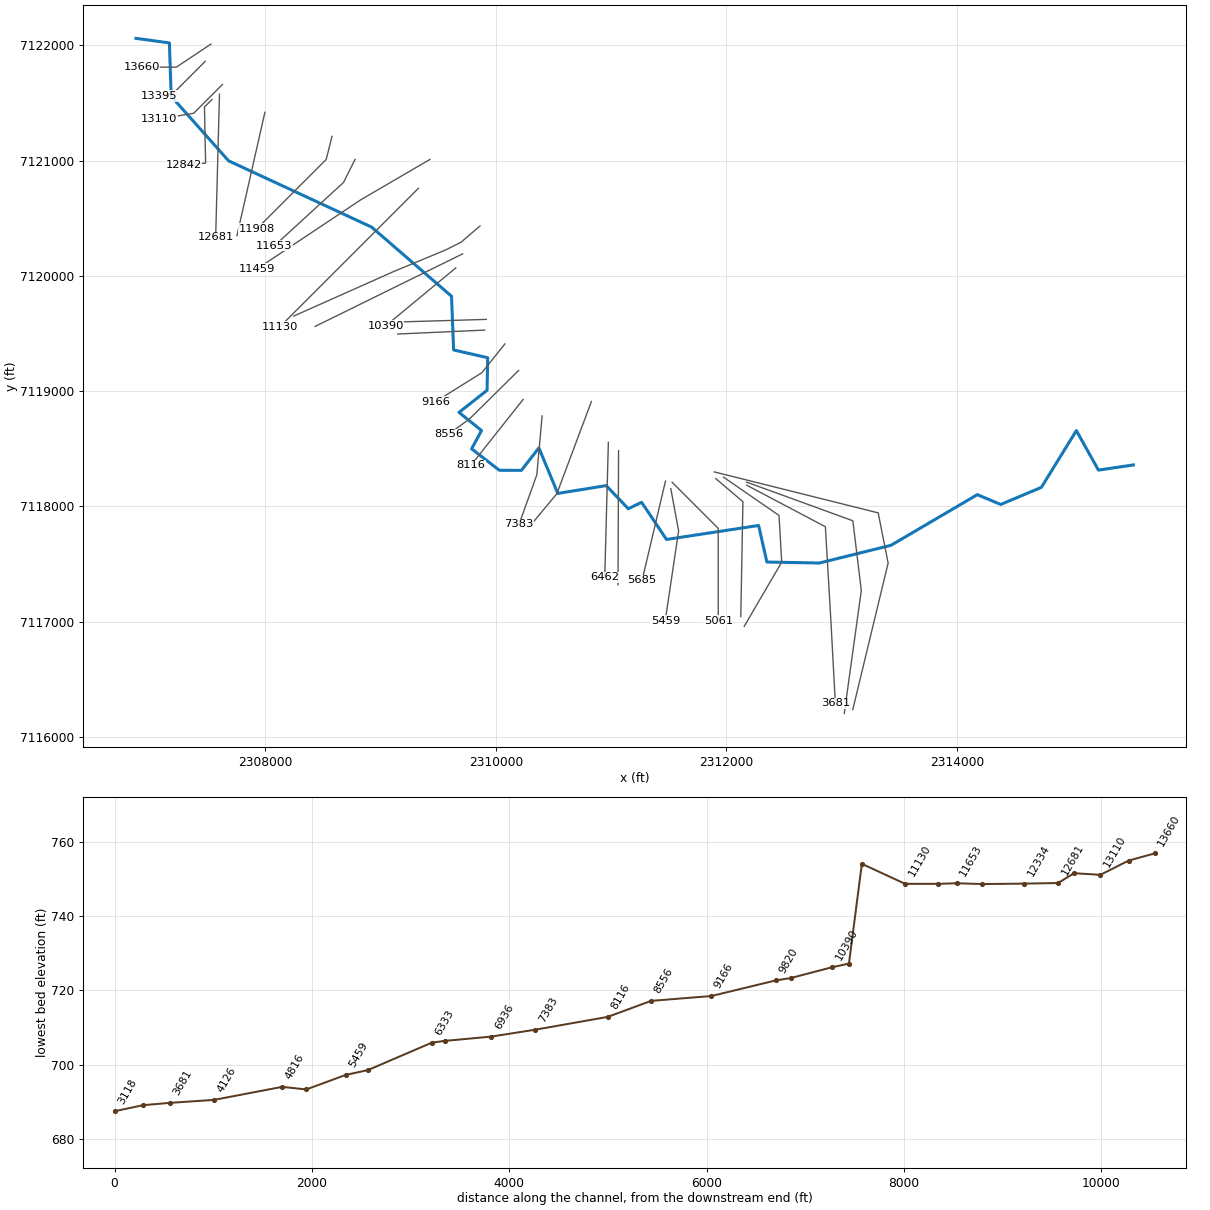
--- Denton Creek Tributary 29.prj (project) ---

Proj Title=Denton Creek Tributary 29 Base Level Engineering
Current Plan=p01
Default Exp/Contr=0.3,0.1
English Units
Geom File=g01
Flow File=f01
Plan File=p01
BEGIN DESCRIPTION:
Denton Creek Tributary 29
END DESCRIPTION:

--- Denton Creek Tributary 29.p01 (plan) ---

Plan Title=Multiple Run
Short Identifier=Multiple
Geom File=g01
Flow File=f01
Subcritical Flow
K Sum by GR= 0
Std Step Tol= 0.01
Critical Tol= 0.01
Num of Std Step Trials= 20
Max Error Tol= 0.3
Flow Tol Ratio= 0.001
Split Flow NTrial= 30
Split Flow Tol= 0.02
Split Flow Ratio= 0.02
Log Output Level= 0
Friction Slope Method= 1
Unsteady Friction Slope Method= 2
Unsteady Bridges Friction Slope Method= 1
Parabolic Critical Depth
Global Vel Dist=  1 , 1 , 1
Global Log Level= 0
CheckData=True
Encroach Param= -1, 0, 0, 0
BEGIN DESCRIPTION:
Multiple Run
END DESCRIPTION:

--- Denton Creek Tributary 29.f01 (steady flow) ---

Flow Title=Multiple
Number of Profiles=7
Profile Names=10-year,25-year,50-year,1pct_min,100-year,1pct_plu,500-year
River Rch & RM= Denton Creek Tri,Reach-1,13660
     634     875    1077     658    1312    2619    1955
River Rch & RM= Denton Creek Tri,Reach-1,10561
     661     912    1122     685    1367    2727    2034
River Rch & RM= Denton Creek Tri,Reach-1,9970
     807    1126    1394     856    1709    3409    2574
River Rch & RM= Denton Creek Tri,Reach-1,3681
     968    1363    1697    1048    2091    4172    3184
Boundary for River Rch & Prof#=Denton Creek Tri,Reach-1,1
Up Type=0
Dn Type=3
Dn Slope=0.005
Boundary for River Rch & Prof#=Denton Creek Tri,Reach-1,2
Up Type=0
Dn Type=3
Dn Slope=0.005
Boundary for River Rch & Prof#=Denton Creek Tri,Reach-1,3
Up Type=0
Dn Type=3
Dn Slope=0.005
Boundary for River Rch & Prof#=Denton Creek Tri,Reach-1,4
Up Type=0
Dn Type=3
Dn Slope=0.005
Boundary for River Rch & Prof#=Denton Creek Tri,Reach-1,5
Up Type=0
Dn Type=3
Dn Slope=0.005
Boundary for River Rch & Prof#=Denton Creek Tri,Reach-1,6
Up Type=0
Dn Type=3
Dn Slope=0.005
Boundary for River Rch & Prof#=Denton Creek Tri,Reach-1,7
Up Type=0
Dn Type=3
Dn Slope=0.005

--- Denton Creek Tributary 29.g01 (geometry) ---

Geom Title=Existing Conditions

River Reach=Denton Creek Tri,Reach-1
Reach XY= 30
      2306879.00      7122060.00      2307168.95      7122020.05
      2307184.28      7121557.29      2307682.38      7120997.60
      2308922.94      7120422.79      2309615.68      7119823.33
      2309633.97      7119357.42      2309929.42      7119289.91
      2309924.01      7119007.45      2309680.67      7118815.67
      2309875.99      7118658.57      2309789.96      7118500.00
      2310030.55      7118313.75      2310221.38      7118313.07
      2310373.52      7118507.93      2310537.28      7118113.06
      2310957.34      7118180.77      2311149.12      7117980.07
      2311264.24      7118036.34      2311480.55      7117713.75
      2312278.91      7117835.18      2312350.97      7117517.95
      2312806.24      7117509.52      2313427.37      7117663.13
      2314175.67      7118102.38      2314379.00      7118017.54
      2314731.54      7118165.70      2315035.05      7118657.90
      2315226.29      7118315.28      2315529.00      7118360.00

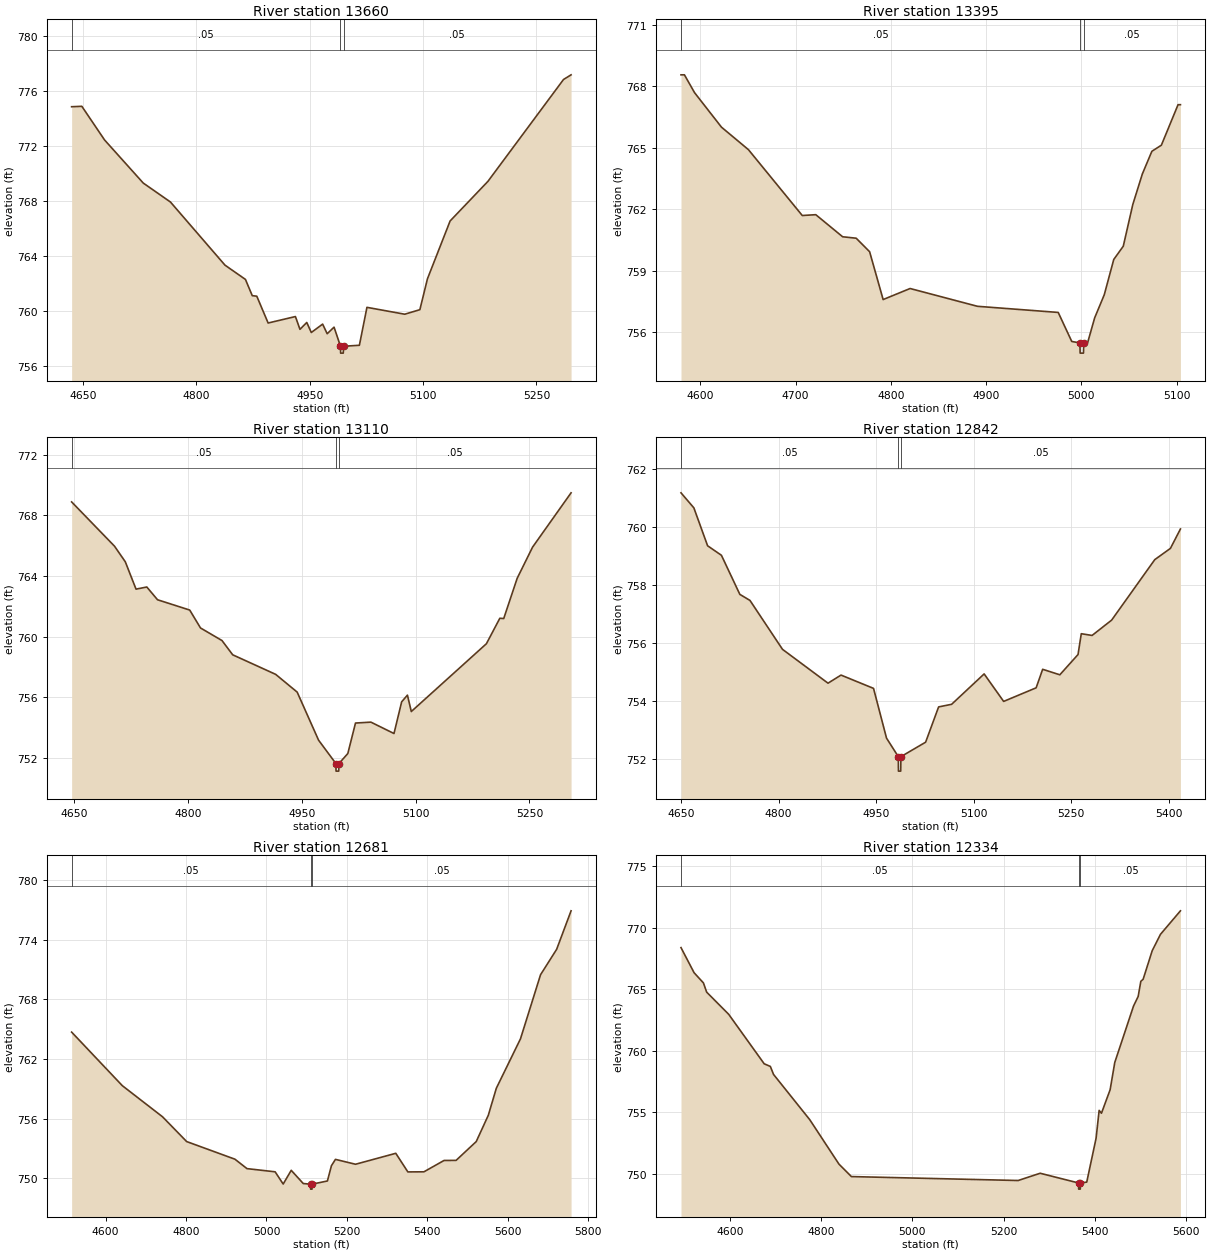
Type RM Length L Ch R = 1,13660,265,265,265
BEGIN DESCRIPTION:
Denton Creek Tributary 29 29.0
END DESCRIPTION:
XS GIS Cut Line= 3
      2307529.02      7122010.01      2307229.00      7121810.00
      2306928.97      7121810.00
#Sta/Elev= 30
  4635.2  774.82  4648.7  774.85  4678.8  772.40  4729.9  769.27  4765.9  767.89
  4838.0  763.30  4865.1  762.26  4874.1  761.08  4880.1  761.04  4895.1  759.09
  4931.2  759.56  4937.2  758.63  4946.2  759.13  4952.2  758.40  4967.2  759.01
  4973.2  758.31  4982.3  758.79  4990.8  757.40  4991.0  756.90  4994.5  756.90
  4994.8  757.40  5015.8  757.47  5025.8  760.23  5075.8  759.73  5095.8  760.06
  5105.8  762.30  5135.8  766.51  5185.8  769.39  5285.8  776.80  5295.8  777.14
#Mann=3,-1,0
  4635.2    0.05       0  4990.8   0.033       0  4994.8    0.05       0
Bank Sta=4990.8,4994.8
Exp/Cntr=0.3,0.1

Type RM Length L Ch R = 1,13395,285,285,285
BEGIN DESCRIPTION:
Denton Creek Tributary 29 28.0
END DESCRIPTION:
XS GIS Cut Line= 3
      2307479.03      7121860.03      2307179.00      7121560.00
      2307079.01      7121560.00
#Sta/Elev= 30
  4579.7  768.57  4583.3  768.57  4593.9  767.70  4622.2  766.01  4650.5  764.91
  4707.0  761.69  4721.2  761.73  4749.4  760.65  4763.6  760.58  4777.7  759.92
  4791.9  757.58  4820.2  758.12  4890.9  757.25  4975.7  756.95  4989.9  755.53
  4998.5  755.46  4998.7  754.96  5002.2  754.96  5002.5  755.46  5006.5  755.46
  5014.0  756.69  5024.0  757.81  5034.0  759.54  5044.0  760.19  5054.0  762.23
  5064.0  763.72  5074.0  764.83  5084.0  765.13  5101.5  767.11  5104.0  767.11
#Mann=3,-1,0
  4579.7    0.05       0  4998.5   0.033       0  5002.5    0.05       0
Bank Sta=4998.5,5002.5
Exp/Cntr=0.3,0.1

Type RM Length L Ch R = 1,13110,268,268,268
BEGIN DESCRIPTION:
Denton Creek Tributary 29 27.0
END DESCRIPTION:
XS GIS Cut Line= 3
      2307628.99      7121659.99      2307379.00      7121410.00
      2307078.97      7121360.00
#Sta/Elev= 30
  4647.1  768.88  4703.6  765.96  4717.8  764.93  4731.9  763.13  4746.1  763.27
  4760.2  762.43  4802.6  761.75  4816.8  760.57  4845.1  759.74  4859.2  758.80
  4915.8  757.51  4944.1  756.34  4972.3  753.17  4995.1  751.63  4995.3  751.13
  4998.8  751.13  4999.1  751.63  5010.8  752.29  5020.9  754.30  5041.2  754.36
  5071.6  753.61  5081.7  755.70  5089.3  756.14  5094.4  755.06  5193.3  759.53
  5211.0  761.21  5216.1  761.19  5233.8  763.84  5254.1  765.90  5304.8  769.48
#Mann=3,-1,0
  4647.1    0.05       0  4995.1   0.033       0  4999.1    0.05       0
Bank Sta=4995.1,4999.1
Exp/Cntr=0.3,0.1

Type RM Length L Ch R = 1,12842,161,161,161
BEGIN DESCRIPTION:
Mapping XS aeaa928e
END DESCRIPTION:
XS GIS Cut Line= 4
      2307537.98      7121528.96      2307472.92      7121464.56
      2307482.92      7120978.11      2307293.62      7120961.67
#Sta/Elev= 30
  4649.8  761.19  4669.6  760.67  4690.7  759.36  4712.0  759.03  4740.3  757.68
  4755.9  757.47  4805.9  755.78  4875.9  754.61  4895.9  754.89  4945.9  754.43
  4965.9  752.71  4984.0  752.07  4984.2  751.57  4987.7  751.57  4988.0  752.07
  5026.0  752.57  5046.0  753.79  5066.0  753.88  5116.0  754.93  5146.0  753.98
  5196.0  754.45  5206.0  755.09  5232.4  754.90  5260.4  755.60  5265.4  756.32
  5282.0  756.26  5312.1  756.79  5378.4  758.88  5402.5  759.27  5417.9  759.94
#Mann=3,-1,0
  4649.8    0.05       0  4984.0   0.033       0  4988.0    0.05       0
Bank Sta=4984,4988
Exp/Cntr=0.3,0.1

Type RM Length L Ch R = 1,12681,347,347,347
BEGIN DESCRIPTION:
Mapping XS 7e474a56
END DESCRIPTION:
XS GIS Cut Line= 2
      2307603.23      7121576.00      2307570.11      7120334.14
#Sta/Elev= 30
  4515.4  764.70  4641.4  759.32  4741.5  756.19  4801.5  753.70  4921.5  751.93
  4951.6  750.98  5021.6  750.66  5041.6  749.43  5061.6  750.81  5091.6  749.48
  5109.6  749.42  5109.9  748.92  5113.4  748.92  5113.6  749.42  5151.6  749.74
  5161.6  751.27  5171.6  751.91  5221.6  751.42  5321.7  752.52  5351.7  750.65
  5391.7  750.66  5441.7  751.80  5471.7  751.81  5521.8  753.70  5551.8  756.34
  5571.8  759.06  5631.8  764.02  5681.8  770.47  5721.8  773.02  5757.7  776.89
#Mann=3,-1,0
  4515.4    0.05       0  5109.6   0.033       0  5113.6    0.05       0
Bank Sta=5109.6,5113.6
Exp/Cntr=0.3,0.1

Type RM Length L Ch R = 1,12334,426,426,426
BEGIN DESCRIPTION:
Mapping XS fb8085e6
END DESCRIPTION:
XS GIS Cut Line= 2
      2307996.90      7121417.94      2307754.95      7120349.60
#Sta/Elev= 30
  4492.6  768.39  4521.3  766.35  4541.8  765.52  4548.9  764.77  4597.2  762.97
  4675.0  758.95  4688.6  758.73  4695.6  758.08  4774.9  754.41  4839.1  750.79
  4866.3  749.78  5232.0  749.46  5280.3  750.05  5364.5  749.26  5364.8  748.76
  5368.3  748.76  5368.5  749.26  5382.5  749.33  5403.0  752.90  5409.7  755.16
  5414.8  754.93  5433.8  756.84  5444.0  759.06  5485.1  763.64  5495.3  764.42
  5501.1  765.65  5506.2  765.82  5526.1  768.14  5544.2  769.47  5588.0  771.38
#Mann=3,-1,0
  4492.6    0.05       0  5364.5   0.033       0  5368.5    0.05       0
Bank Sta=5364.5,5368.5
Exp/Cntr=0.3,0.1

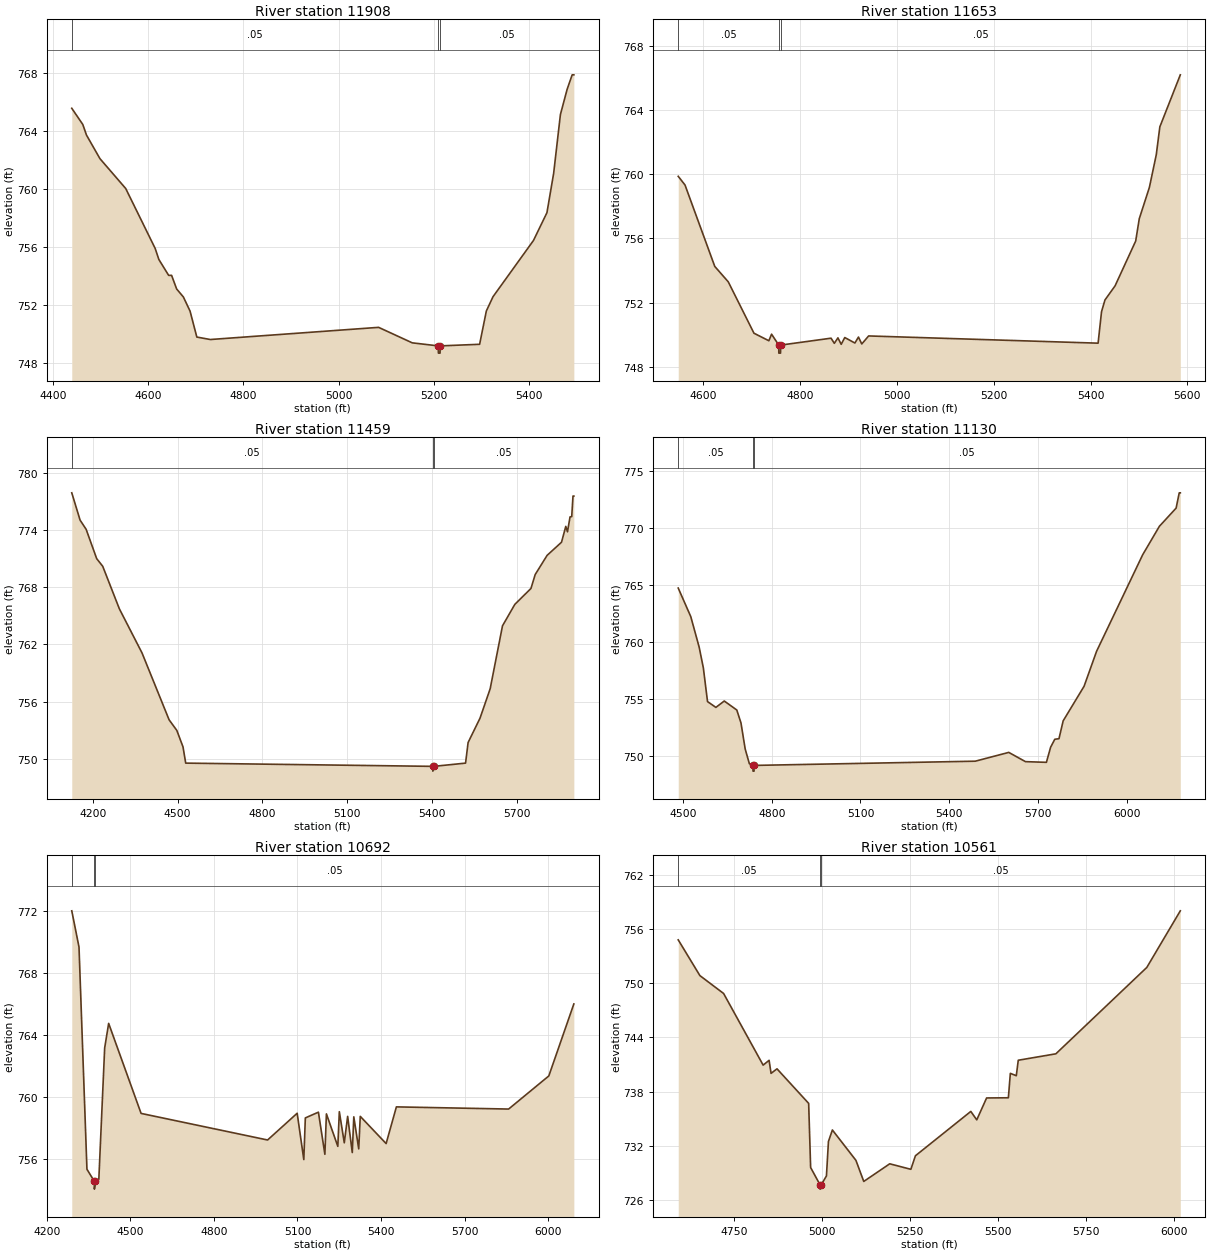
Type RM Length L Ch R = 1,11908,255,255,255
BEGIN DESCRIPTION:
Denton Creek Tributary 29 22.0
END DESCRIPTION:
XS GIS Cut Line= 3
      2308578.99      7121209.96      2308529.00      7121010.00
      2307929.03      7120410.03
#Sta/Elev= 30
  4439.3  765.56  4462.5  764.44  4470.2  763.71  4498.5  762.08  4552.6  760.02
  4614.5  755.88  4622.2  755.12  4642.8  754.02  4649.0  754.02  4659.6  753.08
  4673.7  752.53  4687.8  751.55  4702.0  749.76  4730.3  749.59  5083.8  750.43
  5154.5  749.36  5209.1  749.15  5209.4  748.65  5212.9  748.65  5213.1  749.15
  5296.0  749.26  5310.1  751.56  5324.2  752.55  5409.1  756.43  5437.4  758.35
  5451.5  761.07  5465.7  765.13  5479.8  766.87  5490.4  767.87  5493.9  767.87
#Mann=3,-1,0
  4439.3    0.05       0  5209.1   0.033       0  5213.1    0.05       0
Bank Sta=5209.1,5213.1
Exp/Cntr=0.3,0.1

Type RM Length L Ch R = 1,11653,194,194,194
BEGIN DESCRIPTION:
Denton Creek Tributary 29 21.0
END DESCRIPTION:
XS GIS Cut Line= 3
      2308779.01      7121010.02      2308679.00      7120810.00
      2308078.98      7120259.98
#Sta/Elev= 30
  4547.9  759.87  4561.9  759.33  4623.4  754.26  4651.3  753.30  4704.4  750.10
  4735.2  749.63  4740.8  750.04  4755.6  749.36  4755.8  748.86  4759.3  748.86
  4759.6  749.36  4863.7  749.79  4870.5  749.47  4877.9  749.81  4884.7  749.41
  4892.1  749.83  4913.0  749.49  4920.4  749.86  4927.2  749.43  4941.4  749.93
  5415.6  749.48  5422.7  751.44  5429.8  752.17  5450.7  753.05  5493.3  755.84
  5500.7  757.23  5521.6  759.18  5535.8  761.21  5543.2  762.95  5585.5  766.19
#Mann=3,-1,0
  4547.9    0.05       0  4755.6   0.033       0  4759.6    0.05       0
Bank Sta=4755.6,4759.6
Exp/Cntr=0.3,0.1

Type RM Length L Ch R = 1,11459,329,329,329
BEGIN DESCRIPTION:
Denton Creek Tributary 29 20.0
END DESCRIPTION:
XS GIS Cut Line= 3
      2309429.01      7121010.01      2308829.00      7120660.00
      2307929.00      7120060.00
#Sta/Elev= 30
  4125.6  777.89  4155.0  775.03  4176.5  774.06  4213.7  770.99  4235.2  770.18
  4293.9  765.73  4374.1  761.10  4470.0  754.08  4497.3  752.97  4519.2  751.24
  4528.7  749.54  5402.6  749.20  5402.9  748.70  5406.6  749.20  5518.8  749.54
  5527.8  751.70  5569.9  754.25  5605.9  757.34  5649.5  763.94  5693.1  766.19
  5750.2  767.86  5765.2  769.32  5807.3  771.33  5858.3  772.71  5873.4  774.37
  5879.4  773.80  5888.4  775.36  5894.4  775.40  5898.9  777.55  5901.9  777.55
#Mann=3,-1,0
  4125.6    0.05       0  5402.6   0.033       0  5406.6    0.05       0
Bank Sta=5402.6,5406.6
Exp/Cntr=0.3,0.1

Type RM Length L Ch R = 1,11130,438,438,438
BEGIN DESCRIPTION:
Denton Creek Tributary 29 19.0
END DESCRIPTION:
XS GIS Cut Line= 3
      2309329.01      7120760.01      2309029.00      7120460.00
      2308128.98      7119559.98
#Sta/Elev= 30
  4484.0  764.74  4526.4  762.24  4554.7  759.57  4568.9  757.75  4583.0  754.80
  4611.3  754.29  4639.6  754.85  4682.0  754.06  4696.1  752.93  4710.3  750.65
  4724.4  749.36  4736.6  749.21  4736.8  748.71  4740.3  748.71  4740.6  749.21
  5488.1  749.58  5601.2  750.35  5657.8  749.54  5728.5  749.48  5742.7  750.80
  5756.8  751.50  5771.0  751.55  5785.1  753.11  5855.8  756.14  5898.2  759.21
  6053.8  767.65  6110.4  770.15  6166.9  771.74  6177.5  773.08  6181.1  773.08
#Mann=3,-1,0
  4484.0    0.05       0  4736.6   0.033       0  4740.6    0.05       0
Bank Sta=4736.6,4740.6
Exp/Cntr=0.3,0.1

Type RM Length L Ch R = 1,10692,131,131,131
BEGIN DESCRIPTION:
Mapping XS dd077b50
END DESCRIPTION:
XS GIS Cut Line= 5
      2309862.74      7120432.79      2309698.64      7120292.01
      2309563.00      7120223.95      2309112.09      7120036.71
      2308246.86      7119651.04
#Sta/Elev= 30
  4289.2  771.99  4315.2  769.66  4343.7  755.37  4370.3  754.59  4370.5  754.09
  4374.3  754.59  4386.4  754.72  4407.4  763.17  4421.7  764.75  4538.2  758.96
  4992.6  757.25  5098.9  758.97  5122.7  755.99  5128.2  758.67  5175.2  759.04
  5198.4  756.33  5203.9  758.93  5244.9  756.84  5250.3  759.07  5268.1  757.07
  5280.2  758.77  5296.8  756.44  5302.3  758.74  5320.0  756.68  5325.5  758.77
  5418.4  757.02  5455.3  759.38  5858.4  759.24  6002.8  761.37  6092.7  766.00
#Mann=3,-1,0
  4289.2    0.05       0  4370.3   0.033       0  4374.3    0.05       0
Bank Sta=4370.3,4374.3
Exp/Cntr=0.3,0.1

Type RM Length L Ch R = 1,10561,171,171,171
BEGIN DESCRIPTION:
Mapping XS a00c4392
END DESCRIPTION:
XS GIS Cut Line= 2
      2309711.91      7120190.79      2308432.21      7119561.17
#Sta/Elev= 30
  4592.4  754.78  4653.9  750.83  4721.3  748.85  4833.6  740.93  4850.5  741.46
  4856.1  740.02  4873.0  740.52  4962.9  736.70  4968.5  729.61  4994.9  727.72
  4995.1  727.22  4998.9  727.72  5013.4  728.68  5019.1  732.49  5030.3  733.76
  5097.2  730.40  5119.4  728.07  5193.2  730.02  5253.2  729.41  5266.2  730.91
  5423.5  735.81  5440.4  734.88  5468.4  737.30  5530.2  737.32  5535.8  740.02
  5552.7  739.76  5558.3  741.47  5665.1  742.18  5923.4  751.73  6018.6  757.99
#Mann=3,-1,0
  4592.4    0.05       0  4994.9   0.033       0  4998.9    0.05       0
Bank Sta=4994.9,4998.9
Exp/Cntr=0.3,0.1

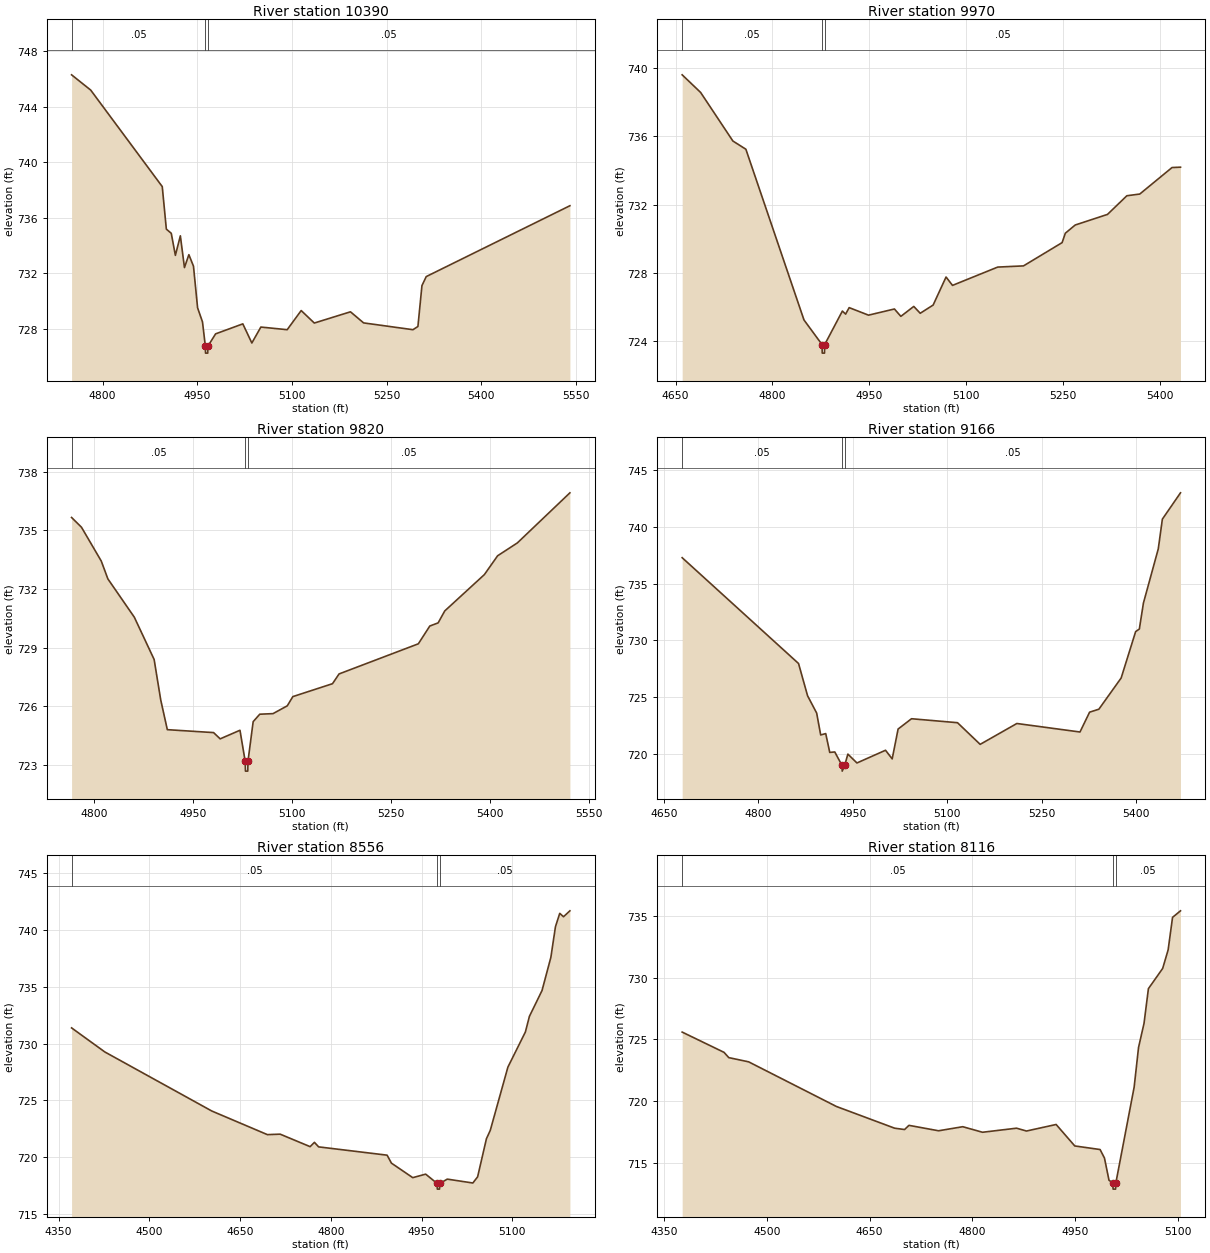
Type RM Length L Ch R = 1,10390,420,420,420
BEGIN DESCRIPTION:
Mapping XS d0bee553
END DESCRIPTION:
XS GIS Cut Line= 2
      2309652.34      7120068.54      2309043.50      7119565.45
#Sta/Elev= 30
  4750.8  746.31  4781.1  745.21  4894.5  738.25  4901.0  735.18  4908.8  734.88
  4915.3  733.29  4923.2  734.70  4929.7  732.41  4936.7  733.34  4944.0  732.51
  4950.5  729.51  4958.3  728.49  4962.8  726.74  4963.1  726.24  4966.6  726.24
  4966.8  726.74  4979.1  727.63  5022.2  728.35  5036.5  726.97  5050.8  728.12
  5092.5  727.93  5114.7  729.31  5135.5  728.41  5192.8  729.22  5213.6  728.42
  5291.8  727.93  5299.7  728.16  5306.1  731.11  5312.9  731.76  5540.6  736.87
#Mann=3,-1,0
  4750.8    0.05       0  4962.8   0.033       0  4966.8    0.05       0
Bank Sta=4962.8,4966.8
Exp/Cntr=0.3,0.1

Type RM Length L Ch R = 1,9970,150,150,150
BEGIN DESCRIPTION:
Mapping XS e336fdf6
END DESCRIPTION:
XS GIS Cut Line= 2
      2309917.61      7119622.42      2309145.94      7119599.75
#Sta/Elev= 30
  4660.3  739.59  4688.9  738.56  4738.9  735.72  4759.0  735.24  4849.0  725.26
  4877.0  723.82  4877.3  723.32  4880.8  723.32  4881.1  723.82  4908.5  725.78
  4913.5  725.60  4919.0  725.98  4949.0  725.54  4989.1  725.90  4999.1  725.47
  5019.1  726.05  5029.1  725.65  5049.1  726.13  5069.1  727.77  5079.1  727.28
  5149.1  728.35  5189.1  728.42  5248.9  729.78  5253.9  730.33  5269.2  730.81
  5319.2  731.43  5349.2  732.52  5369.2  732.62  5419.2  734.17  5432.3  734.19
#Mann=3,-1,0
  4660.3    0.05       0  4877.0   0.033       0  4881.1    0.05       0
Bank Sta=4877,4881.1
Exp/Cntr=0.3,0.1

Type RM Length L Ch R = 1,9820,654,654,654
BEGIN DESCRIPTION:
Mapping XS ccd44be6
END DESCRIPTION:
XS GIS Cut Line= 2
      2309903.95      7119529.60      2309149.52      7119495.53
#Sta/Elev= 30
  4765.4  735.66  4780.4  735.16  4810.4  733.43  4820.4  732.52  4860.5  730.56
  4890.5  728.40  4900.5  726.33  4910.5  724.81  4980.6  724.66  4990.6  724.34
  5020.6  724.78  5028.5  723.19  5028.9  722.69  5032.4  722.69  5032.7  723.19
  5040.6  725.22  5050.6  725.60  5070.7  725.63  5092.3  726.03  5100.7  726.50
  5160.8  727.16  5170.8  727.66  5290.9  729.20  5308.3  730.11  5320.9  730.27
  5330.9  730.88  5391.0  732.74  5411.0  733.70  5441.0  734.36  5520.6  736.92
#Mann=3,-1,0
  4765.4    0.05       0  5028.5   0.033       0  5032.7    0.05       0
Bank Sta=5028.5,5032.7
Exp/Cntr=0.3,0.1

Type RM Length L Ch R = 1,9166,610,610,610
BEGIN DESCRIPTION:
Denton Creek Tributary 29 14.0
END DESCRIPTION:
XS GIS Cut Line= 3
      2310079.00      7119409.99      2309879.00      7119160.00
      2309479.04      7118910.03
#Sta/Elev= 30
  4678.9  737.30  4863.8  727.97  4878.2  725.12  4892.6  723.60  4899.0  721.67
  4907.0  721.79  4913.4  720.13  4921.4  720.17  4932.9  718.98  4933.2  718.48
  4937.1  718.98  4942.2  719.98  4956.6  719.20  5002.0  720.32  5012.6  719.56
  5022.0  722.19  5043.3  723.10  5116.4  722.75  5152.4  720.84  5210.7  722.68
  5311.0  721.93  5326.3  723.68  5341.0  723.94  5376.4  726.69  5399.4  730.78
  5405.3  731.01  5411.8  733.30  5435.4  738.08  5441.9  740.70  5470.7  743.02
#Mann=3,-1,0
  4678.9    0.05       0  4932.9   0.033       0  4937.1    0.05       0
Bank Sta=4932.9,4937.1
Exp/Cntr=0.3,0.1

Type RM Length L Ch R = 1,8556,440,440,440
BEGIN DESCRIPTION:
Mapping XS 69aab10d
END DESCRIPTION:
XS GIS Cut Line= 3
      2310197.42      7119179.35      2309773.34      7118760.73
      2309589.72      7118625.56
#Sta/Elev= 30
  4371.4  731.38  4426.4  729.26  4603.2  724.06  4695.1  721.98  4716.3  722.02
  4765.8  720.92  4772.9  721.30  4779.9  720.90  4893.1  720.17  4900.2  719.47
  4935.5  718.19  4956.8  718.50  4975.8  717.68  4976.1  717.18  4979.7  717.18
  4980.1  717.68  4992.6  718.06  5034.8  717.72  5042.7  718.26  5057.3  721.62
  5063.6  722.35  5092.8  727.93  5121.7  731.02  5128.3  732.39  5149.2  734.67
  5163.8  737.59  5171.4  740.29  5178.5  741.47  5184.7  741.17  5195.3  741.69
#Mann=3,-1,0
  4371.4    0.05       0  4975.8   0.033       0  4980.1    0.05       0
Bank Sta=4975.8,4980.1
Exp/Cntr=0.3,0.1

Type RM Length L Ch R = 1,8116,733,733,733
BEGIN DESCRIPTION:
Mapping XS a4c9f3b5
END DESCRIPTION:
XS GIS Cut Line= 2
      2310236.63      7118927.81      2309784.92      7118358.30
#Sta/Elev= 30
  4376.7  725.59  4437.7  723.95  4444.7  723.52  4473.6  723.18  4601.7  719.56
  4686.6  717.80  4701.1  717.69  4707.5  718.03  4750.7  717.59  4786.0  717.92
  4814.8  717.47  4864.5  717.80  4878.9  717.57  4922.2  718.10  4949.4  716.36
  4986.3  716.07  4992.7  715.38  4999.3  713.58  5005.0  713.36  5005.3  712.86
  5008.9  712.86  5009.3  713.36  5036.0  721.13  5042.4  724.34  5050.4  726.30
  5056.8  729.11  5077.6  730.75  5085.6  732.26  5092.0  734.89  5103.6  735.42
#Mann=3,-1,0
  4376.7    0.05       0  5005.0   0.033       0  5009.3    0.05       0
Bank Sta=5005,5009.3
Exp/Cntr=0.3,0.1

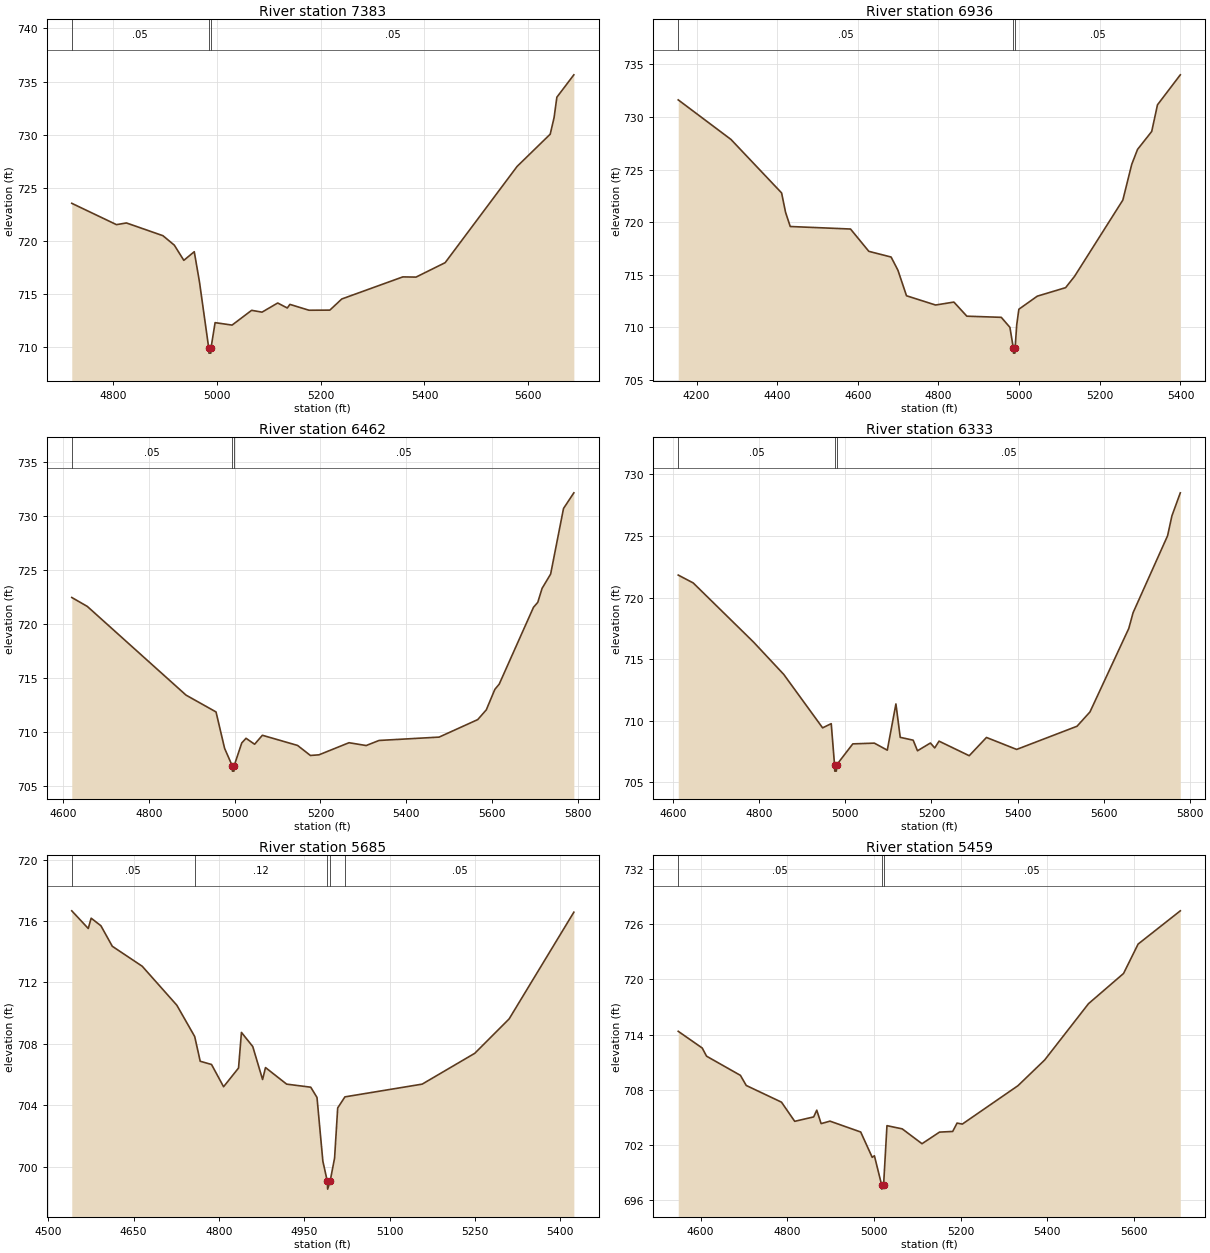
Type RM Length L Ch R = 1,7383,447,447,447
BEGIN DESCRIPTION:
Mapping XS 821a2fd0
END DESCRIPTION:
XS GIS Cut Line= 3
      2310401.32      7118784.81      2310355.61      7118274.57
      2310201.86      7117847.17
#Sta/Elev= 30
  4721.0  723.53  4807.1  721.52  4826.2  721.68  4896.5  720.48  4918.4  719.59
  4936.7  718.16  4956.8  718.97  4966.8  716.14  4984.6  709.92  4985.1  709.42
  4988.7  709.42  4989.1  709.92  4996.9  712.29  5029.6  712.06  5067.2  713.45
  5087.3  713.28  5117.4  714.14  5135.9  713.67  5140.9  714.01  5177.6  713.46
  5217.8  713.47  5240.8  714.52  5358.3  716.60  5383.7  716.58  5439.8  717.94
  5578.2  727.00  5642.0  730.04  5649.5  731.61  5654.8  733.52  5687.5  735.63
#Mann=3,-1,0
  4721.0    0.05       0  4984.6   0.033       0  4989.1    0.05       0
Bank Sta=4984.6,4989.1
Exp/Cntr=0.3,0.1

Type RM Length L Ch R = 1,6936,474,474,474
BEGIN DESCRIPTION:
Denton Creek Tributary 29 9.0
END DESCRIPTION:
XS GIS Cut Line= 3
      2310829.00      7118910.00      2310529.00      7118110.00
      2310279.01      7117810.01
#Sta/Elev= 30
  4154.7  731.62  4285.5  727.86  4411.0  722.78  4420.8  720.94  4432.4  719.59
  4581.9  719.35  4627.3  717.23  4682.5  716.69  4699.4  715.44  4720.7  713.01
  4792.8  712.13  4838.2  712.41  4870.3  711.07  4955.7  710.96  4977.1  710.01
  4985.5  708.06  4985.9  707.56  4989.5  707.56  4990.0  708.06  4994.0  710.25
  4999.3  711.73  5044.9  712.97  5115.2  713.78  5137.3  714.85  5257.1  722.10
  5279.2  725.50  5293.5  726.91  5328.7  728.62  5343.0  731.15  5399.6  734.00
#Mann=3,-1,0
  4154.7    0.05       0  4985.5    0.04       0  4990.0    0.05       0
Bank Sta=4985.5,4990
Exp/Cntr=0.3,0.1

Type RM Length L Ch R = 1,6462,129,129,129
BEGIN DESCRIPTION:
Mapping XS e0f9f19a
END DESCRIPTION:
XS GIS Cut Line= 2
      2310975.99      7118556.30      2310944.63      7117385.92
#Sta/Elev= 30
  4620.0  722.47  4656.3  721.64  4886.4  713.43  4956.4  711.87  4976.4  708.50
  4994.1  706.89  4994.6  706.39  4998.2  706.39  4998.7  706.89  5016.4  709.00
  5026.4  709.43  5046.4  708.88  5064.5  709.71  5146.5  708.77  5176.5  707.84
  5196.5  707.90  5266.5  709.02  5306.5  708.76  5336.6  709.23  5476.6  709.54
  5566.6  711.16  5586.6  712.06  5606.6  713.96  5616.7  714.44  5696.7  721.56
  5706.7  722.02  5716.7  723.31  5736.7  724.64  5766.7  730.71  5790.8  732.16
#Mann=3,-1,0
  4620.0    0.05       0  4994.1    0.04       0  4998.7    0.05       0
Bank Sta=4994.1,4998.7
Exp/Cntr=0.3,0.1

Type RM Length L Ch R = 1,6333,648,648,648
BEGIN DESCRIPTION:
Mapping XS d414c1a7
END DESCRIPTION:
XS GIS Cut Line= 2
      2311064.41      7118484.80      2311059.78      7117320.51
#Sta/Elev= 30
  4612.7  721.82  4647.5  721.18  4787.5  716.38  4857.5  713.76  4947.5  709.43
  4967.5  709.77  4975.2  706.42  4975.7  705.92  4979.4  705.92  4979.9  706.42
  5017.5  708.13  5067.5  708.19  5097.5  707.62  5117.5  711.37  5127.5  708.66
  5157.5  708.43  5167.5  707.57  5197.5  708.20  5207.5  707.80  5217.5  708.35
  5287.5  707.17  5327.5  708.65  5397.5  707.68  5537.5  709.56  5567.5  710.72
  5657.5  717.49  5667.5  718.77  5747.5  725.01  5757.5  726.62  5777.0  728.49
#Mann=3,-1,0
  4612.7    0.05       0  4975.2    0.04       0  4979.9    0.05       0
Bank Sta=4975.2,4979.9
Exp/Cntr=0.3,0.1

Type RM Length L Ch R = 1,5685,226,226,226
BEGIN DESCRIPTION:
Mapping XS aca805cd
END DESCRIPTION:
XS GIS Cut Line= 2
      2311471.46      7118219.83      2311268.77      7117360.41
#Sta/Elev= 30
  4541.2  716.66  4570.2  715.51  4575.3  716.18  4592.4  715.69  4612.5  714.35
  4665.1  713.05  4726.0  710.51  4757.4  708.47  4767.1  706.86  4787.0  706.65
  4808.2  705.20  4834.5  706.42  4839.6  708.74  4859.5  707.82  4876.8  705.67
  4881.9  706.45  4919.1  705.37  4961.5  705.17  4972.5  704.50  4982.8  700.35
  4990.7  699.03  4991.2  698.53  4995.5  699.03  5003.4  700.55  5008.9  703.82
  5021.6  704.54  5157.5  705.37  5250.0  707.38  5310.4  709.62  5424.2  716.57
#Mann=5,-1,0
  4541.2    0.05       0  4757.4    0.12       0  4990.7    0.07       0
  4995.5    0.12       0  5021.6    0.05       0
Bank Sta=4990.7,4995.5
Exp/Cntr=0.3,0.1

Type RM Length L Ch R = 1,5459,398,398,398
BEGIN DESCRIPTION:
Mapping XS bac1d7ac
END DESCRIPTION:
XS GIS Cut Line= 3
      2311517.67      7118154.35      2311585.25      7117787.83
      2311469.39      7117010.42
#Sta/Elev= 30
  4548.5  714.35  4603.8  712.54  4613.9  711.65  4692.0  709.57  4705.5  708.47
  4786.8  706.66  4817.3  704.58  4861.1  705.06  4868.2  705.79  4878.3  704.33
  4898.7  704.60  4969.6  703.42  4996.2  700.67  5001.2  700.84  5017.7  697.72
  5018.3  697.22  5022.5  697.72  5030.2  704.11  5065.5  703.76  5111.1  702.15
  5151.5  703.41  5181.9  703.48  5192.0  704.39  5204.1  704.28  5332.6  708.45
  5394.2  711.24  5495.3  717.35  5576.2  720.63  5609.8  723.82  5707.2  727.43
#Mann=3,-1,0
  4548.5    0.05       0  5017.7   0.033       0  5022.5    0.05       0
Bank Sta=5017.7,5022.5
Exp/Cntr=0.3,0.1

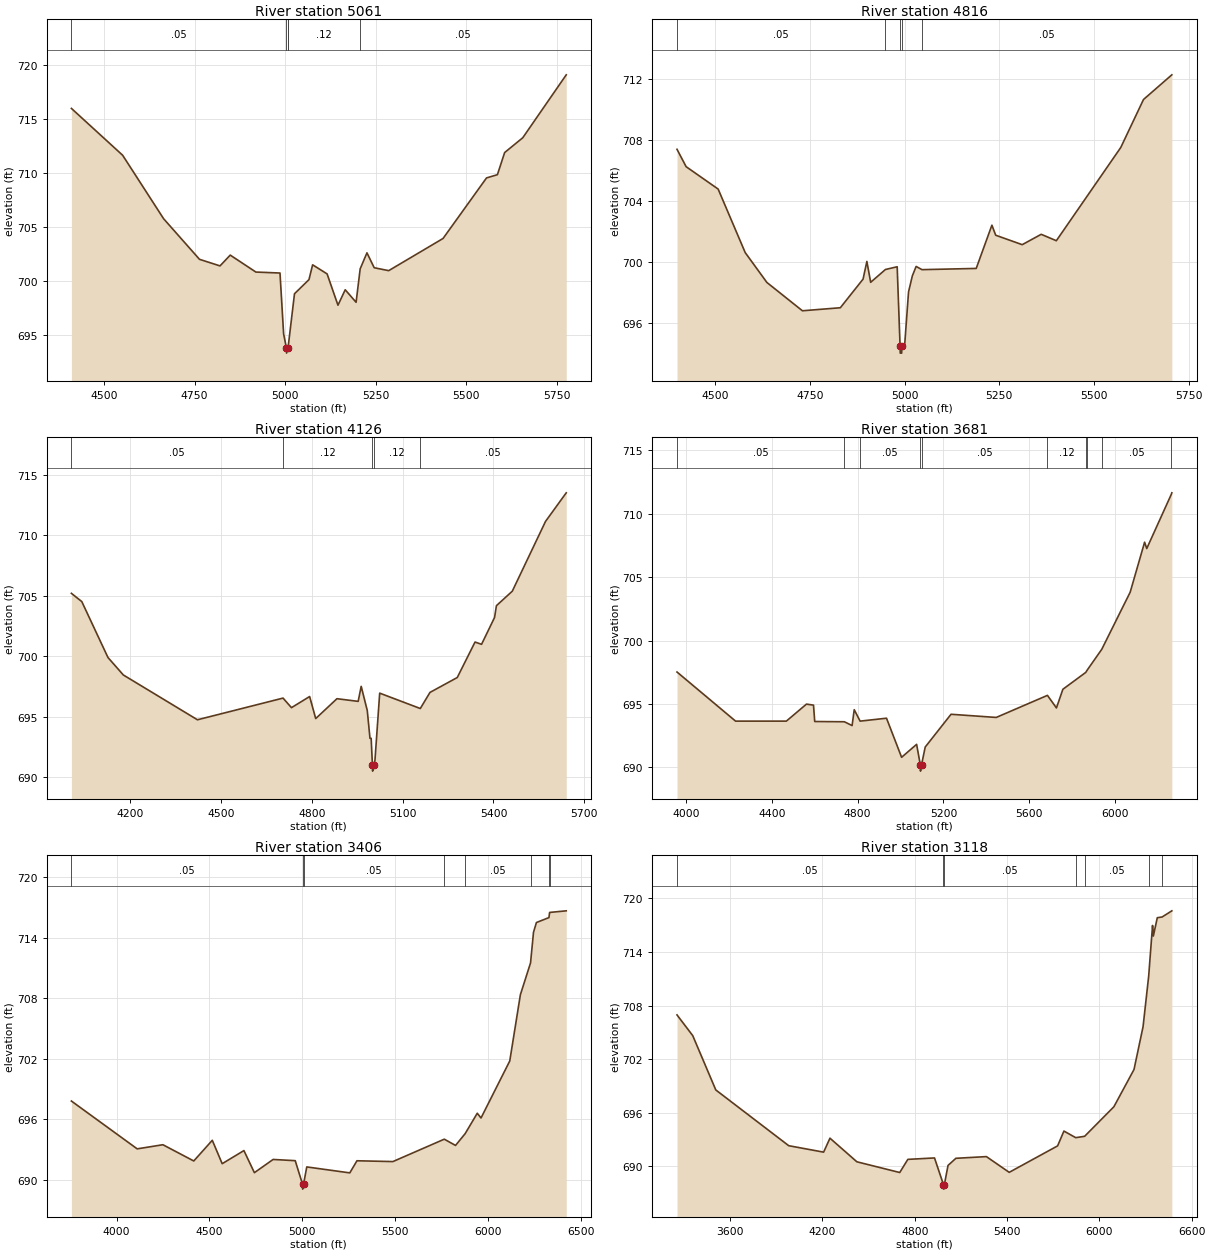
Type RM Length L Ch R = 1,5061,245,245,245
BEGIN DESCRIPTION:
Denton Creek Tributary 29 5.0
END DESCRIPTION:
XS GIS Cut Line= 3
      2311529.02      7118209.98      2311929.00      7117810.00
      2311929.00      7117009.96
#Sta/Elev= 30
  4410.1  715.99  4551.5  711.65  4664.6  705.77  4763.6  702.01  4820.2  701.40
  4848.5  702.40  4919.2  700.83  4985.8  700.74  4995.8  695.10  5003.4  693.82
  5003.9  693.32  5008.2  693.82  5009.1  694.11  5025.8  698.82  5065.8  700.13
  5075.8  701.50  5115.8  700.66  5145.8  697.76  5165.8  699.19  5195.8  698.03
  5207.1  701.13  5225.8  702.61  5245.8  701.23  5285.8  700.96  5435.8  703.94
  5555.8  709.55  5585.8  709.85  5605.8  711.90  5655.8  713.27  5775.8  719.10
#Mann=5,-1,0
  4410.1    0.05       0  5003.4   0.033       0  5008.2    0.05       0
  5009.1    0.12       0  5207.1    0.05       0
Bank Sta=5003.4,5008.2
Exp/Cntr=0.3,0.1

Type RM Length L Ch R = 1,4816,690,690,690
BEGIN DESCRIPTION:
Mapping XS 1038c03a
END DESCRIPTION:
XS GIS Cut Line= 3
      2311907.14      7118241.85      2312143.01      7118041.67
      2312124.45      7117045.21
#Sta/Elev= 30
  4399.2  707.39  4423.3  706.25  4507.8  704.78  4579.2  700.61  4636.4  698.65
  4730.2  696.79  4830.3  696.99  4890.3  698.87  4900.3  700.03  4910.3  698.66
  4949.3  699.50  4980.3  699.68  4987.9  694.51  4988.4  694.01  4992.1  694.01
  4992.7  694.51  5000.3  694.63  5010.3  698.03  5020.3  699.08  5030.3  699.70
  5045.8  699.49  5188.9  699.57  5230.3  702.41  5240.3  701.75  5310.3  701.13
  5360.4  701.81  5400.4  701.39  5570.4  707.51  5630.4  710.66  5705.2  712.28
#Mann=5,-1,0
  4399.2    0.05       0  4949.3    0.12       0  4987.9    0.07       0
  4992.7    0.12       0  5045.8    0.05       0
Bank Sta=4987.9,4992.7
Exp/Cntr=0.3,0.1

Type RM Length L Ch R = 1,4126,445,445,445
BEGIN DESCRIPTION:
Mapping XS c27be859
END DESCRIPTION:
XS GIS Cut Line= 4
      2311974.99      7118253.92      2312456.06      7117922.08
      2312479.50      7117517.22      2312154.35      7116960.93
#Sta/Elev= 30
  4006.0  705.19  4040.3  704.51  4126.8  699.89  4177.5  698.45  4422.3  694.75
  4705.0  696.54  4732.8  695.75  4792.8  696.67  4812.9  694.85  4883.0  696.49
  4953.1  696.27  4963.1  697.51  4983.2  695.51  4992.1  693.22  4996.0  693.22
  5000.2  691.01  5000.8  690.51  5005.1  691.01  5008.5  691.39  5024.2  696.95
  5158.3  695.68  5190.3  697.01  5280.4  698.24  5339.1  701.17  5360.6  700.98
  5403.6  703.20  5409.7  704.17  5462.2  705.37  5571.9  711.13  5640.3  713.49
#Mann=5,-1,0
  4006.0    0.05       0  4705.0    0.12       0  5000.2    0.07       0
  5005.1    0.12       0  5158.3    0.05       0
Bank Sta=5000.2,5005.1
Exp/Cntr=0.3,0.1

Type RM Length L Ch R = 1,3681,275,275,275
BEGIN DESCRIPTION:
Mapping XS 8ade2b50
END DESCRIPTION:
XS GIS Cut Line= 4
      2312176.32      7118184.11      2312858.22      7117824.16
      2312904.98      7117025.79      2312944.59      7116293.37
#Sta/Elev= 30
  3959.1  697.52  4231.8  693.65  4468.3  693.65  4562.0  694.99  4594.8  694.91
  4600.4  693.62  4738.5  693.60  4774.4  693.30  4784.4  694.55  4811.8  693.65
  4934.7  693.88  5005.0  690.80  5074.9  691.82  5092.1  690.21  5093.0  689.71
  5097.8  690.21  5115.0  691.61  5235.2  694.19  5445.6  693.94  5684.1  695.68
  5726.0  694.69  5756.0  696.16  5862.6  697.49  5869.6  697.68  5937.1  699.31
  6069.4  703.81  6136.6  707.75  6146.6  707.25  6261.4  711.54  6263.4  711.64
#Mann=10,-1,0
  3959.1    0.05       0  4738.5    0.12       0  4811.8    0.05       0
  5092.1   0.033       0  5097.8    0.05       0  5684.1    0.12       0
  5862.6    0.05       0  5869.6    0.12       0  5937.1    0.05       0
  6261.4    0.12       0
Bank Sta=5092.1,5097.8
Exp/Cntr=0.3,0.1

Type RM Length L Ch R = 1,3406,288,288,288
BEGIN DESCRIPTION:
Mapping XS fcdc0ab4
END DESCRIPTION:
XS GIS Cut Line= 4
      2312176.02      7118210.62      2313096.42      7117875.94
      2313169.76      7117270.94      2313022.00      7116205.42
#Sta/Elev= 30
  3756.9  697.81  4111.2  693.07  4249.5  693.48  4415.8  691.87  4515.5  693.92
  4568.8  691.60  4685.8  692.90  4742.2  690.71  4843.0  692.02  4962.1  691.90
  5001.3  689.58  5002.2  689.08  5007.0  689.58  5024.3  691.28  5256.0  690.69
  5294.5  691.89  5488.0  691.81  5764.7  694.03  5825.3  693.41  5877.2  694.58
  5942.3  696.60  5962.5  696.13  6117.3  701.78  6174.5  708.35  6229.2  711.50
  6245.1  714.53  6260.8  715.50  6328.3  715.99  6331.9  716.50  6421.4  716.66
#Mann=8,-1,0
  3756.9    0.05       0  5001.3    0.04       0  5007.0    0.05       0
  5764.7    0.12       0  5877.2    0.05       0  6229.2    0.12       0
  6328.3    0.05       0  6331.9    0.12       0
Bank Sta=5001.3,5007
Exp/Cntr=0.3,0.1

Type RM Length L Ch R = 1,3118,0,0,0
BEGIN DESCRIPTION:
Mapping XS 500018f9
END DESCRIPTION:
XS GIS Cut Line= 4
      2311894.30      7118299.67      2313316.26      7117944.30
      2313402.46      7117508.88      2313095.79      7116238.12
#Sta/Elev= 30
  3254.4  706.95  3356.7  704.63  3506.6  698.55  3980.8  692.31  4207.5  691.59
  4248.8  693.15  4423.7  690.51  4702.3  689.31  4755.0  690.78  4928.4  690.94
  4986.7  687.95  4987.6  687.45  4992.4  687.95  5016.2  690.10  5067.4  690.90
  5265.7  691.09  5414.0  689.33  5728.6  692.29  5769.7  693.95  5846.4  693.21
  5904.1  693.36  6094.5  696.67  6225.3  700.84  6284.1  705.63  6320.7  711.30
  6345.8  716.96  6351.0  715.78  6376.7  717.83  6408.0  717.91  6471.2  718.60
#Mann=7,-1,0
  3254.4    0.05       0  4986.7    0.04       0  4992.4    0.05       0
  5846.4    0.12       0  5904.1    0.05       0  6320.7    0.12       0
  6408.0    0.05       0
Bank Sta=4986.7,4992.4
Exp/Cntr=0.3,0.1

Chan Stop Cuts=-1