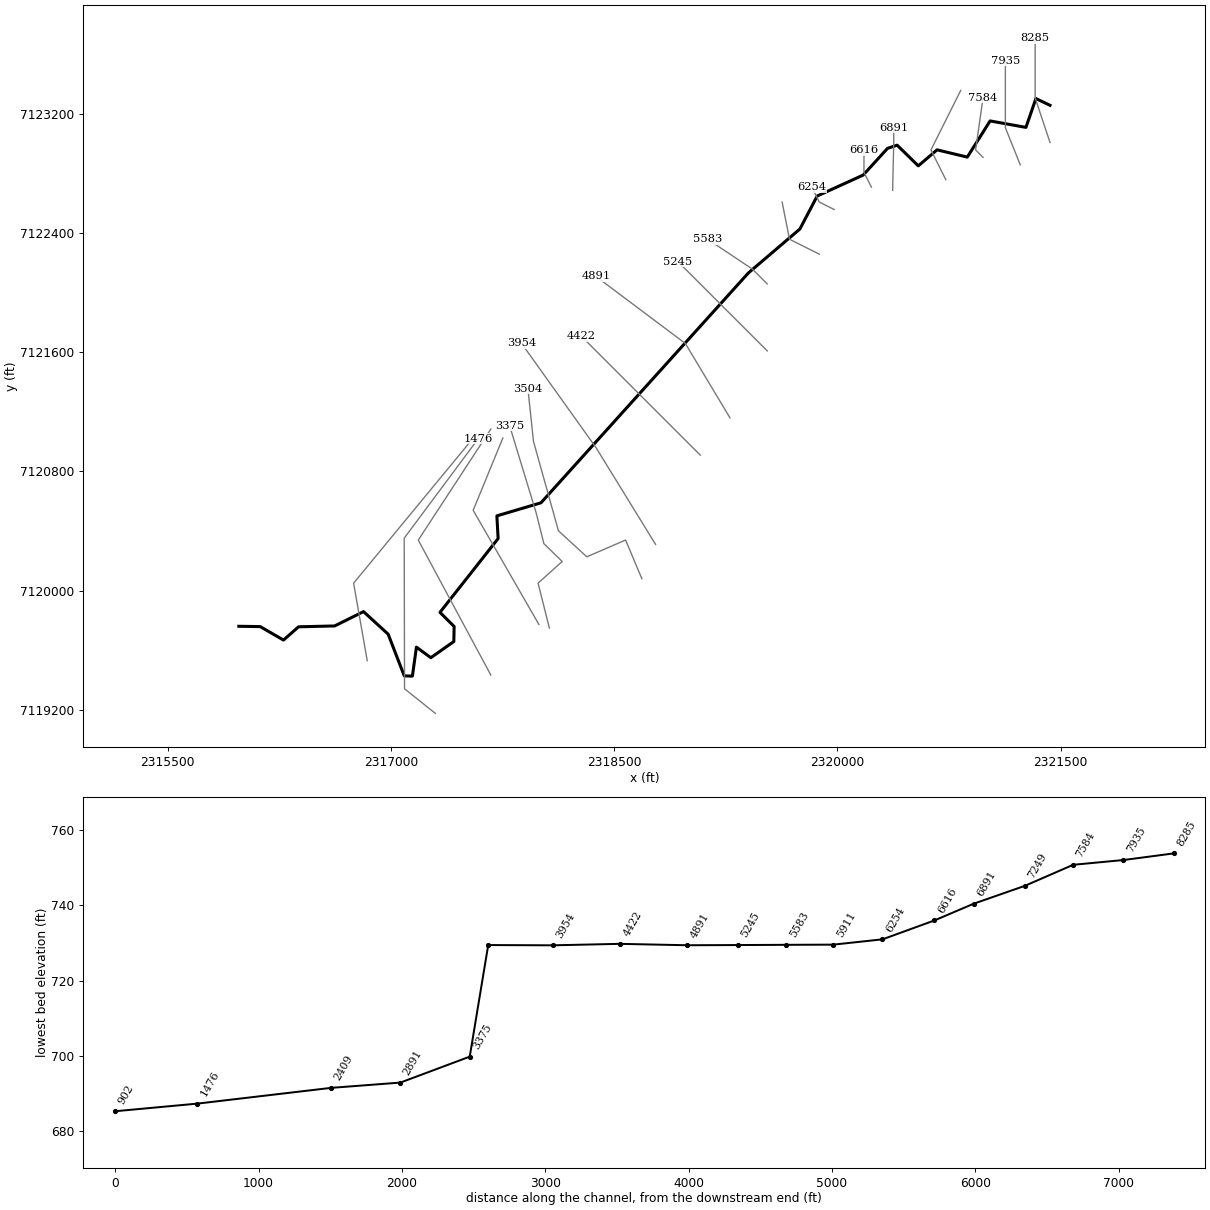
--- Denton Creek Tributary 30.prj (project) ---

Proj Title=Denton Creek Tributary 30 Base Level Engineering
Current Plan=p01
Default Exp/Contr=0.3,0.1
English Units
Geom File=g01
Flow File=f01
Plan File=p01
BEGIN DESCRIPTION:
Denton Creek Tributary 30
END DESCRIPTION:

--- Denton Creek Tributary 30.p01 (plan) ---

Plan Title=Multiple Run
Short Identifier=Multiple
Geom File=g01
Flow File=f01
Subcritical Flow
K Sum by GR= 0
Std Step Tol= 0.01
Critical Tol= 0.01
Num of Std Step Trials= 20
Max Error Tol= 0.3
Flow Tol Ratio= 0.001
Split Flow NTrial= 30
Split Flow Tol= 0.02
Split Flow Ratio= 0.02
Log Output Level= 0
Friction Slope Method= 1
Unsteady Friction Slope Method= 2
Unsteady Bridges Friction Slope Method= 1
Parabolic Critical Depth
Global Vel Dist=  1 , 1 , 1
Global Log Level= 0
CheckData=True
Encroach Param= -1, 0, 0, 0
BEGIN DESCRIPTION:
Multiple Run
END DESCRIPTION:

--- Denton Creek Tributary 30.f01 (steady flow) ---

Flow Title=Multiple
Number of Profiles=7
Profile Names=10-year,25-year,50-year,1pct_min,100-year,1pct_plu,500-year
River Rch & RM= Denton Creek Tri,Reach-1,8285
     468     633     767     463     923    1841    1337
River Rch & RM= Denton Creek Tri,Reach-1,5583
     863    1214    1511     933    1861    3714    2834
Boundary for River Rch & Prof#=Denton Creek Tri,Reach-1,1
Up Type=0
Dn Type=3
Dn Slope=0.00508
Boundary for River Rch & Prof#=Denton Creek Tri,Reach-1,2
Up Type=0
Dn Type=3
Dn Slope=0.00508
Boundary for River Rch & Prof#=Denton Creek Tri,Reach-1,3
Up Type=0
Dn Type=3
Dn Slope=0.00508
Boundary for River Rch & Prof#=Denton Creek Tri,Reach-1,4
Up Type=0
Dn Type=3
Dn Slope=0.00508
Boundary for River Rch & Prof#=Denton Creek Tri,Reach-1,5
Up Type=0
Dn Type=3
Dn Slope=0.00508
Boundary for River Rch & Prof#=Denton Creek Tri,Reach-1,6
Up Type=0
Dn Type=3
Dn Slope=0.00508
Boundary for River Rch & Prof#=Denton Creek Tri,Reach-1,7
Up Type=0
Dn Type=3
Dn Slope=0.00508

--- Denton Creek Tributary 30.g01 (geometry) ---

Geom Title=Existing Conditions

River Reach=Denton Creek Tri,Reach-1
Reach XY= 30
      2321429.00      7123260.00      2321334.10      7123305.47
      2321267.19      7123111.60      2321026.42      7123155.03
      2320873.12      7122911.96      2320669.98      7122960.94
      2320543.99      7122853.10      2320401.99      7122992.20
      2320337.54      7122971.06      2320173.76      7122791.34
      2319865.03      7122650.92      2319748.49      7122428.98
      2319402.04      7122133.38      2318009.16      7120589.62
      2317712.87      7120501.79      2317721.14      7120349.28
      2317330.42      7119853.57      2317425.60      7119758.70
      2317423.61      7119657.56      2317268.98      7119548.91
      2317172.37      7119619.92      2317145.11      7119424.99
      2317090.54      7119426.89      2316982.41      7119707.04
      2316816.86      7119858.54      2316623.07      7119762.24
      2316380.46      7119756.44      2316279.08      7119667.30
      2316123.09      7119757.80      2315979.00      7119760.00

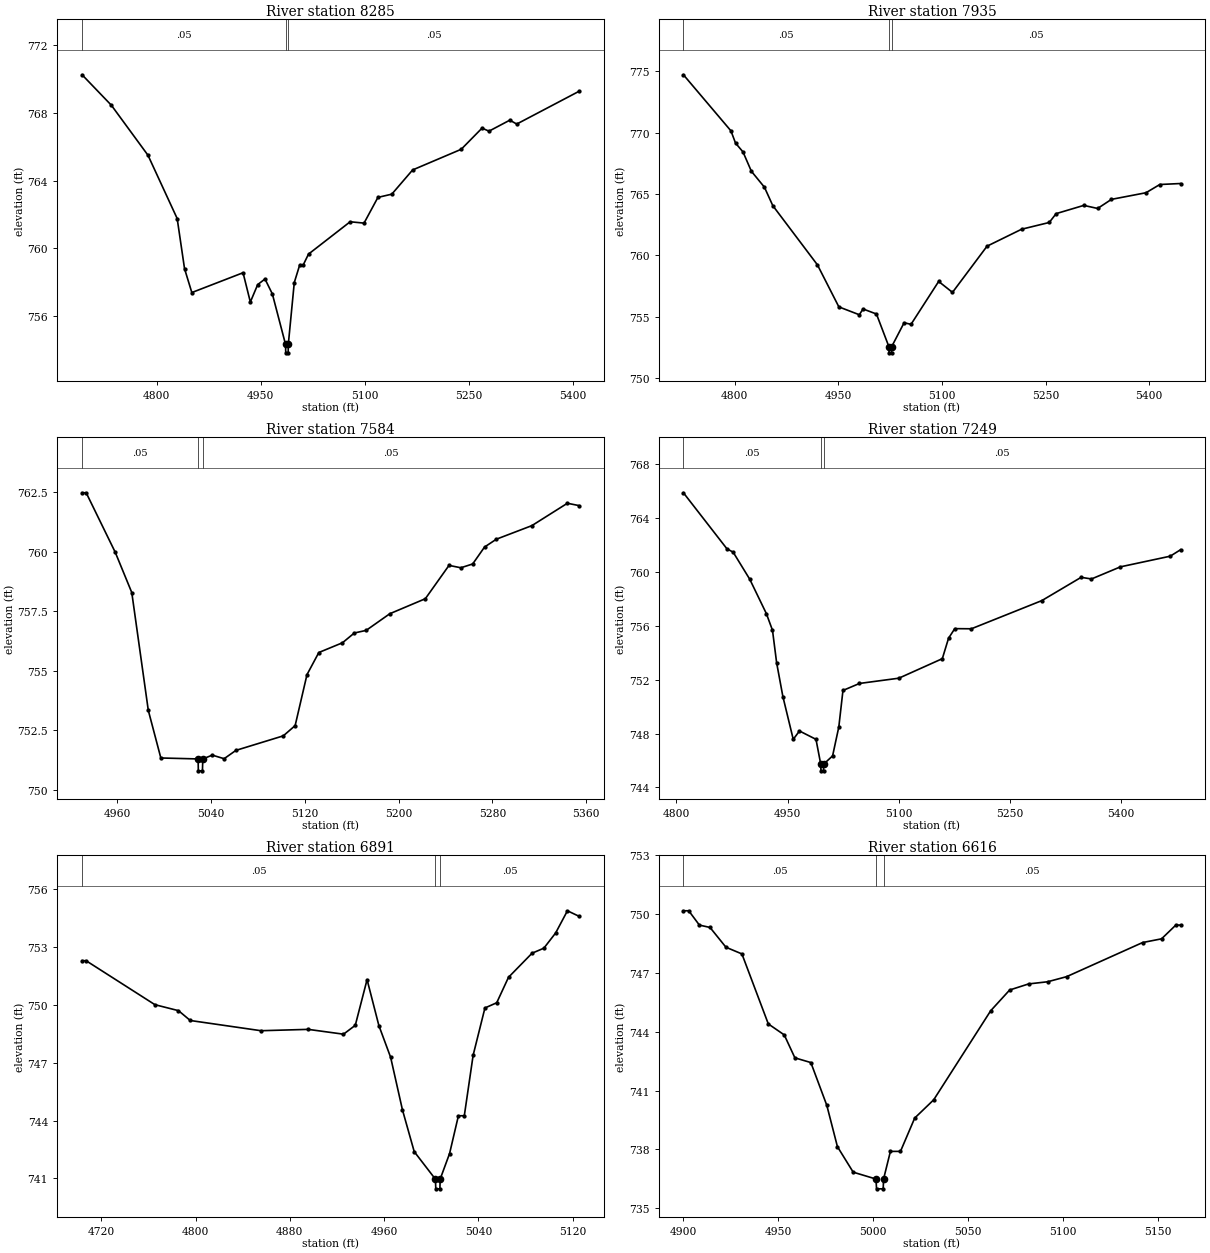
Type RM Length L Ch R = 1,8285,350,350,350
BEGIN DESCRIPTION:
Denton Creek Tributary 30 16.0
END DESCRIPTION:
XS GIS Cut Line= 3
      2321429.00      7123010.00      2321329.00      7123310.00
      2321329.00      7123709.97
#Sta/Elev= 30
  4692.5  770.25  4734.7  768.45  4787.4  765.50  4829.5  761.76  4840.1  758.80
  4850.6  757.39  4924.4  758.56  4934.9  756.83  4945.5  757.86  4956.0  758.19
  4966.6  757.31  4985.6  754.33  4985.9  753.83  4989.4  753.83  4989.6  754.33
  4998.2  757.98  5006.1  759.03  5011.2  759.03  5018.7  759.66  5078.7  761.57
  5098.7  761.49  5118.7  763.01  5138.7  763.20  5168.7  764.63  5238.7  765.85
  5268.7  767.10  5278.7  766.92  5308.7  767.57  5318.7  767.34  5408.7  769.28
#Mann=3,-1,0
  4692.5    0.05       0  4985.6    0.04       0  4989.6    0.05       0
Bank Sta=4985.6,4989.6
Exp/Cntr=0.3,0.1

Type RM Length L Ch R = 1,7935,351,351,351
BEGIN DESCRIPTION:
Denton Creek Tributary 30 15.0
END DESCRIPTION:
XS GIS Cut Line= 3
      2321229.02      7122859.95      2321129.00      7123110.00
      2321129.00      7123559.99
#Sta/Elev= 30
  4726.1  774.70  4794.8  770.14  4801.5  769.14  4812.3  768.42  4824.4  766.85
  4843.3  765.55  4855.4  764.05  4920.0  759.23  4951.0  755.81  4980.6  755.17
  4986.0  755.64  5005.4  755.23  5023.4  752.57  5023.7  752.07  5027.2  752.07
  5027.4  752.57  5045.4  754.52  5055.4  754.39  5095.4  757.88  5115.4  756.99
  5165.4  760.75  5215.4  762.13  5255.4  762.68  5265.4  763.40  5305.4  764.07
  5325.4  763.82  5345.4  764.56  5395.4  765.10  5415.4  765.77  5445.4  765.85
#Mann=3,-1,0
  4726.1    0.05       0  5023.4   0.033       0  5027.4    0.05       0
Bank Sta=5023.4,5027.4
Exp/Cntr=0.3,0.1

Type RM Length L Ch R = 1,7584,335,335,335
BEGIN DESCRIPTION:
Denton Creek Tributary 30 14.0
END DESCRIPTION:
XS GIS Cut Line= 3
      2320978.98      7122910.02      2320929.00      7122960.00
      2320978.99      7123309.96
#Sta/Elev= 30
  4929.8  762.48  4933.3  762.48  4958.1  759.98  4972.2  758.29  4986.3  753.34
  4997.0  751.34  5028.8  751.30  5029.0  750.80  5032.5  750.80  5032.8  751.30
  5040.9  751.46  5051.0  751.31  5061.1  751.66  5101.5  752.27  5111.6  752.70
  5121.7  754.84  5131.8  755.77  5152.0  756.18  5162.1  756.59  5172.2  756.70
  5192.4  757.40  5222.7  758.03  5242.9  759.43  5253.0  759.33  5263.1  759.49
  5273.2  760.20  5283.3  760.53  5313.6  761.10  5343.9  762.04  5354.0  761.94
#Mann=3,-1,0
  4929.8    0.05       0  5028.8   0.033       0  5032.8    0.05       0
Bank Sta=5028.8,5032.8
Exp/Cntr=0.3,0.1

Type RM Length L Ch R = 1,7249,358,358,358
BEGIN DESCRIPTION:
Denton Creek Tributary 30 13.0
END DESCRIPTION:
XS GIS Cut Line= 3
      2320729.02      7122759.96      2320629.00      7122960.00
      2320829.01      7123360.03
#Sta/Elev= 30
  4809.4  765.88  4868.1  761.72  4876.5  761.47  4898.9  759.46  4921.3  756.91
  4929.6  755.67  4935.2  753.25  4943.6  750.75  4957.6  747.57  4966.0  748.19
  4988.3  747.57  4994.7  745.73  4995.0  745.23  4998.5  745.23  4998.7  745.73
  5010.7  746.34  5019.1  748.49  5024.7  751.20  5047.0  751.72  5100.1  752.11
  5158.8  753.56  5167.2  755.08  5175.6  755.79  5198.0  755.78  5293.0  757.87
  5346.1  759.60  5360.1  759.48  5399.2  760.38  5466.3  761.17  5480.3  761.65
#Mann=3,-1,0
  4809.4    0.05       0  4994.7   0.033       0  4998.7    0.05       0
Bank Sta=4994.7,4998.7
Exp/Cntr=0.3,0.1

Type RM Length L Ch R = 1,6891,275,275,275
BEGIN DESCRIPTION:
Denton Creek Tributary 30 12.0
END DESCRIPTION:
XS GIS Cut Line= 3
      2320371.52      7122688.25      2320379.00      7123010.00
      2320379.00      7123109.96
#Sta/Elev= 30
  4703.7  752.29  4707.1  752.29  4765.5  750.01  4785.5  749.70  4795.5  749.19
  4855.5  748.66  4895.5  748.73  4925.5  748.48  4935.5  748.94  4945.5  751.31
  4955.5  748.93  4965.5  747.28  4975.5  744.56  4985.5  742.39  5003.5  740.96
  5003.8  740.46  5007.3  740.46  5007.5  740.96  5015.5  742.29  5023.0  744.25
  5028.0  744.25  5035.5  747.39  5045.5  749.84  5055.5  750.11  5065.5  751.43
  5085.5  752.68  5095.5  752.94  5105.5  753.73  5115.5  754.88  5125.5  754.59
#Mann=3,-1,0
  4703.7    0.05       0  5003.5   0.033       0  5007.5    0.05       0
Bank Sta=5003.5,5007.5
Exp/Cntr=0.3,0.1

Type RM Length L Ch R = 1,6616,362,362,362
BEGIN DESCRIPTION:
Denton Creek Tributary 30 11.0
END DESCRIPTION:
XS GIS Cut Line= 3
      2320229.00      7122710.00      2320179.00      7122810.00
      2320179.00      7122959.99
#Sta/Elev= 30
  4900.0  750.17  4902.8  750.17  4908.4  749.44  4914.0  749.32  4922.4  748.31
  4930.8  747.97  4944.7  744.40  4953.1  743.84  4958.7  742.67  4967.1  742.43
  4975.5  740.25  4981.1  738.14  4989.4  736.84  5001.4  736.49  5001.7  735.99
  5005.2  735.99  5005.4  736.49  5009.0  737.90  5014.3  737.90  5021.8  739.60
  5031.8  740.53  5061.8  745.07  5071.8  746.13  5081.8  746.44  5091.8  746.55
  5101.8  746.81  5141.8  748.55  5151.8  748.74  5159.3  749.44  5161.8  749.44
#Mann=3,-1,0
  4900.0    0.05       0  5001.4   0.033       0  5005.4    0.05       0
Bank Sta=5001.4,5005.4
Exp/Cntr=0.3,0.1

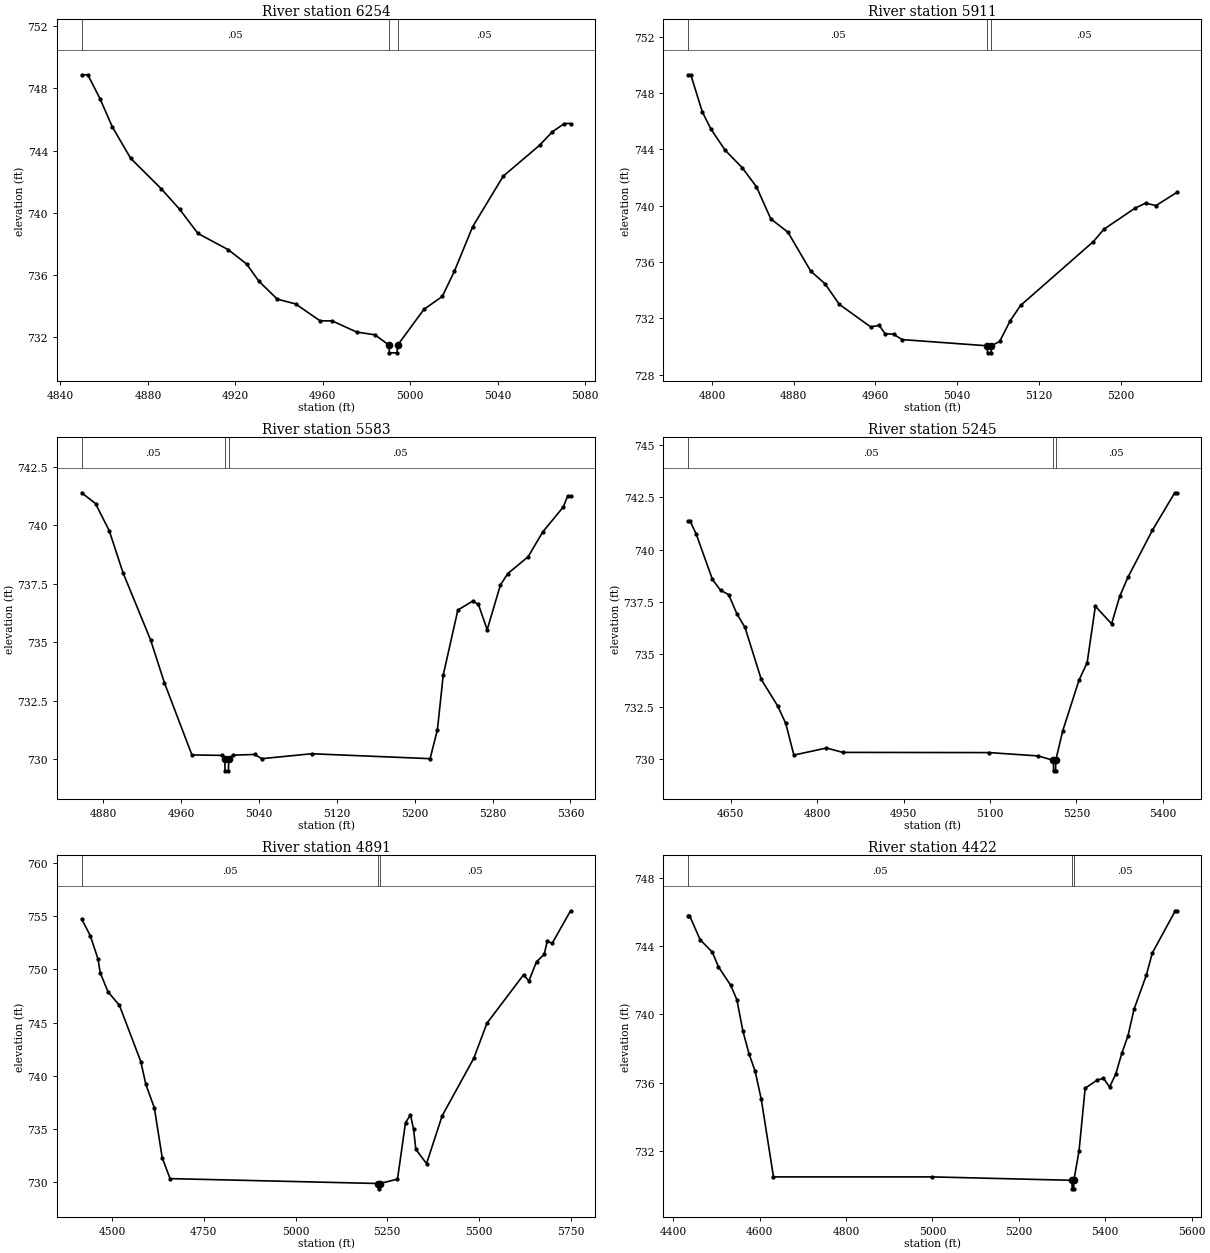
Type RM Length L Ch R = 1,6254,343,343,343
BEGIN DESCRIPTION:
Denton Creek Tributary 30 10.0
END DESCRIPTION:
XS GIS Cut Line= 3
      2319979.04      7122559.98      2319879.00      7122610.00
      2319828.98      7122710.04
#Sta/Elev= 30
  4849.7  748.88  4852.5  748.88  4858.1  747.34  4863.7  745.53  4872.1  743.50
  4886.1  741.54  4894.5  740.22  4902.9  738.66  4916.8  737.61  4925.2  736.69
  4930.8  735.58  4939.2  734.43  4947.6  734.12  4958.8  733.03  4964.3  733.03
  4975.5  732.31  4983.9  732.13  4990.3  731.47  4990.5  730.97  4994.0  730.97
  4994.3  731.47  5006.3  733.77  5014.7  734.60  5020.2  736.21  5028.6  739.09
  5042.6  742.35  5059.4  744.36  5065.0  745.20  5070.6  745.74  5073.4  745.74
#Mann=3,-1,0
  4849.7    0.05       0  4990.3   0.033       0  4994.3    0.05       0
Bank Sta=4990.3,4994.3
Exp/Cntr=0.3,0.1

Type RM Length L Ch R = 1,5911,328,328,328
BEGIN DESCRIPTION:
Denton Creek Tributary 30 9.0
END DESCRIPTION:
XS GIS Cut Line= 3
      2319879.02      7122259.99      2319679.00      7122360.00
      2319629.00      7122610.02
#Sta/Elev= 30
  4776.4  749.29  4779.2  749.29  4790.4  746.67  4798.8  745.45  4812.8  743.94
  4829.5  742.70  4843.5  741.34  4857.5  739.07  4874.3  738.12  4896.6  735.36
  4910.6  734.46  4924.6  733.00  4955.3  731.40  4963.7  731.51  4969.3  730.92
  4977.7  730.88  4986.1  730.50  5069.4  730.06  5069.7  729.56  5073.2  729.56
  5073.4  730.06  5081.6  730.37  5091.8  731.82  5102.0  732.92  5173.4  737.46
  5183.6  738.33  5214.2  739.83  5224.4  740.18  5234.6  740.01  5255.0  740.94
#Mann=3,-1,0
  4776.4    0.05       0  5069.4   0.033       0  5073.4    0.05       0
Bank Sta=5069.4,5073.4
Exp/Cntr=0.3,0.1

Type RM Length L Ch R = 1,5583,338,338,338
BEGIN DESCRIPTION:
Denton Creek Tributary 30 8.0
END DESCRIPTION:
XS GIS Cut Line= 3
      2319529.03      7122059.97      2319429.00      7122160.00
      2319129.02      7122359.99
#Sta/Elev= 30
  4858.1  741.39  4872.3  740.93  4886.4  739.77  4900.6  737.97  4928.9  735.10
  4943.0  733.28  4971.3  730.19  5002.6  730.17  5005.1  730.01  5005.3  729.51
  5008.8  729.51  5009.1  730.01  5013.1  730.18  5035.6  730.21  5043.1  730.03
  5094.2  730.24  5215.9  730.03  5223.4  731.27  5229.4  733.61  5244.4  736.38
  5259.5  736.76  5265.5  736.62  5274.5  735.54  5288.0  737.44  5295.5  737.93
  5316.6  738.66  5331.6  739.72  5352.6  740.78  5357.1  741.25  5360.1  741.25
#Mann=3,-1,0
  4858.1    0.05       0  5005.1   0.033       0  5009.1    0.05       0
Bank Sta=5005.1,5009.1
Exp/Cntr=0.3,0.1

Type RM Length L Ch R = 1,5245,354,354,354
BEGIN DESCRIPTION:
Denton Creek Tributary 30 7.0
END DESCRIPTION:
XS GIS Cut Line= 3
      2319529.03      7121609.97      2319229.00      7121910.00
      2318928.98      7122210.02
#Sta/Elev= 30
  4575.7  741.37  4579.3  741.37  4589.9  740.75  4618.2  738.58  4632.3  738.06
  4646.5  737.85  4660.6  736.94  4674.7  736.29  4703.0  733.81  4731.3  732.55
  4745.5  731.71  4759.6  730.20  4816.2  730.54  4844.4  730.33  5099.0  730.32
  5183.9  730.16  5210.1  729.95  5210.4  729.45  5213.9  729.45  5214.1  729.95
  5226.3  731.36  5254.6  733.78  5268.7  734.61  5282.9  737.30  5311.1  736.46
  5325.3  737.78  5339.4  738.68  5381.9  740.92  5420.7  742.71  5424.3  742.71
#Mann=3,-1,0
  4575.7    0.05       0  5210.1   0.033       0  5214.1    0.05       0
Bank Sta=5210.1,5214.1
Exp/Cntr=0.3,0.1

Type RM Length L Ch R = 1,4891,469,469,469
BEGIN DESCRIPTION:
Denton Creek Tributary 30 6.0
END DESCRIPTION:
XS GIS Cut Line= 3
      2319279.00      7121160.00      2318979.00      7121660.00
      2318378.99      7122110.01
#Sta/Elev= 30
  4416.9  754.73  4440.2  753.17  4461.6  750.96  4467.4  749.68  4488.8  747.89
  4519.9  746.62  4578.2  741.34  4591.8  739.21  4615.1  737.00  4636.5  732.32
  4657.9  730.36  5226.1  729.90  5226.4  729.40  5230.1  729.90  5278.1  730.31
  5300.0  735.62  5313.5  736.34  5321.9  735.02  5328.1  733.11  5357.3  731.77
  5400.0  736.26  5486.4  741.67  5521.9  744.94  5621.9  749.49  5636.4  748.91
  5657.3  750.73  5678.1  751.40  5686.4  752.63  5700.0  752.45  5750.0  755.50
#Mann=3,-1,0
  4416.9    0.05       0  5226.1   0.033       0  5230.1    0.05       0
Bank Sta=5226.1,5230.1
Exp/Cntr=0.3,0.1

Type RM Length L Ch R = 1,4422,468,468,468
BEGIN DESCRIPTION:
Denton Creek Tributary 30 5.0
END DESCRIPTION:
XS GIS Cut Line= 3
      2319079.02      7120909.98      2318679.00      7121310.00
      2318278.99      7121710.01
#Sta/Elev= 30
  4434.3  745.79  4437.9  745.79  4462.6  744.37  4490.9  743.64  4505.0  742.78
  4533.3  741.70  4547.5  740.86  4561.6  739.01  4575.7  737.68  4589.9  736.66
  4604.0  735.02  4632.3  730.47  5000.0  730.47  5323.0  730.27  5323.5  729.77
  5327.1  729.77  5327.5  730.27  5339.4  731.99  5353.6  735.67  5381.8  736.15
  5396.0  736.25  5410.1  735.74  5424.3  736.49  5438.4  737.71  5452.6  738.73
  5466.7  740.30  5495.0  742.28  5509.1  743.60  5562.2  746.07  5565.7  746.07
#Mann=3,-1,0
  4434.3    0.05       0  5323.0   0.033       0  5327.5    0.05       0
Bank Sta=5323,5327.5
Exp/Cntr=0.3,0.1

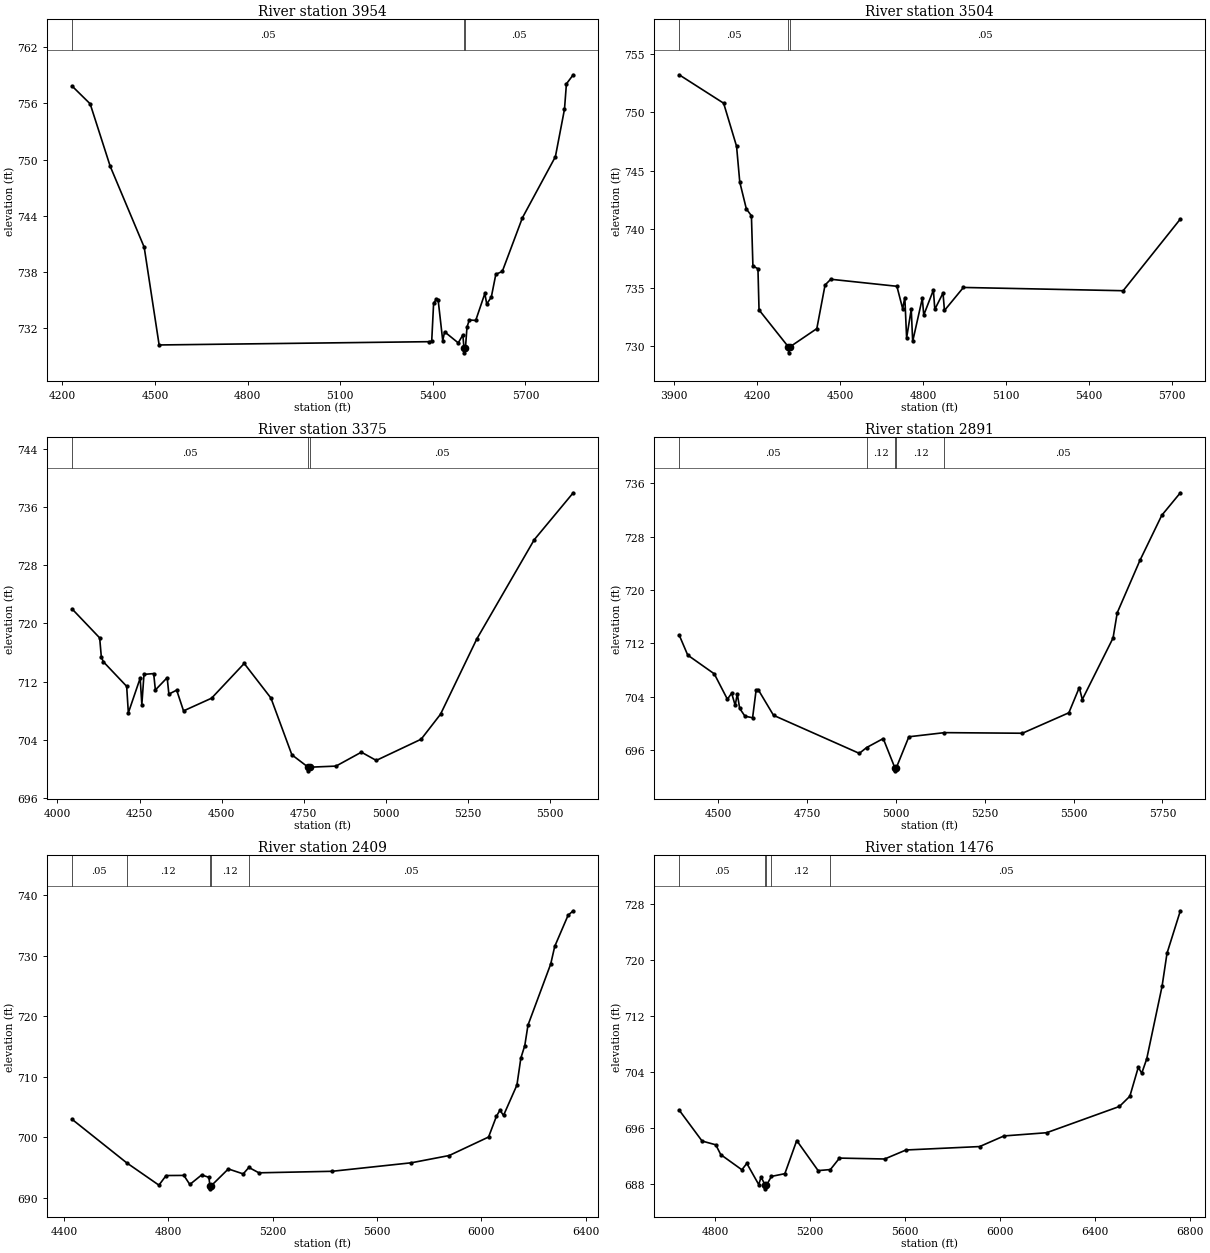
Type RM Length L Ch R = 1,3954,450,450,450
BEGIN DESCRIPTION:
Denton Creek Tributary 30 4.0
END DESCRIPTION:
XS GIS Cut Line= 3
      2318778.98      7120310.04      2318379.00      7120960.00
      2317879.00      7121660.00
#Sta/Elev= 30
  4231.5  757.84  4290.2  755.94  4355.1  749.28  4465.2  740.65  4513.6  730.22
  5387.9  730.57  5396.5  730.62  5402.7  734.69  5411.3  735.08  5417.4  735.00
  5432.2  730.68  5438.3  731.62  5482.5  730.44  5497.3  731.29  5501.1  729.88
  5501.6  729.38  5505.7  729.88  5510.8  732.12  5518.2  732.88  5539.1  732.84
  5568.6  735.71  5574.7  734.59  5589.5  735.32  5604.2  737.76  5625.1  738.06
  5690.2  743.78  5797.1  750.30  5826.6  755.37  5832.8  758.07  5854.9  759.04
#Mann=3,-1,0
  4231.5    0.05       0  5501.1   0.033       0  5505.7    0.05       0
Bank Sta=5501.1,5505.7
Exp/Cntr=0.3,0.1

Type RM Length L Ch R = 1,3504,129,129,129
BEGIN DESCRIPTION:
Mapping XS 168b9928
END DESCRIPTION:
XS GIS Cut Line= 6
      2318687.18      7120078.83      2318577.50      7120339.27
      2318316.89      7120226.80      2318126.47      7120401.62
      2317958.64      7121002.73      2317921.35      7121355.51
#Sta/Elev= 30
  3918.3  753.22  4079.0  750.79  4125.7  747.11  4137.3  744.05  4161.1  741.75
  4179.4  741.17  4184.8  736.87  4203.0  736.64  4206.9  733.12  4313.3  729.95
  4313.8  729.45  4317.9  729.95  4415.7  731.52  4445.5  735.25  4466.1  735.74
  4705.1  735.14  4725.9  733.22  4733.7  734.18  4740.2  730.73  4756.9  733.17
  4762.1  730.43  4796.9  734.11  4802.1  732.68  4836.9  734.81  4842.1  733.17
  4871.7  734.56  4876.9  733.07  4945.4  735.04  5522.6  734.76  5729.3  740.89
#Mann=3,-1,0
  3918.3    0.05       0  4313.3   0.033       0  4317.9    0.05       0
Bank Sta=4313.3,4317.9
Exp/Cntr=0.3,0.1

Type RM Length L Ch R = 1,3375,484,484,484
BEGIN DESCRIPTION:
Mapping XS 9acde0eb
END DESCRIPTION:
XS GIS Cut Line= 6
      2318065.58      7119747.64      2317989.51      7120049.82
      2318151.76      7120195.11      2318028.65      7120314.91
      2317977.40      7120519.63      2317798.79      7121106.54
#Sta/Elev= 30
  4044.5  721.99  4128.6  718.01  4133.7  715.37  4139.7  714.74  4210.8  711.36
  4215.9  707.72  4251.9  712.48  4257.0  708.86  4263.5  713.00  4293.0  713.11
  4298.2  710.86  4334.1  712.55  4339.3  710.29  4363.0  710.84  4383.9  707.99
  4469.2  709.73  4568.6  714.50  4650.0  709.75  4713.7  701.96  4763.3  700.26
  4763.8  699.76  4767.9  700.26  4848.0  700.41  4925.3  702.32  4970.6  701.19
  5107.2  704.10  5166.2  707.53  5276.7  717.87  5451.4  731.48  5570.2  737.93
#Mann=3,-1,0
  4044.5    0.05       0  4763.3   0.033       0  4767.9    0.05       0
Bank Sta=4763.3,4767.9
Exp/Cntr=0.3,0.1

Type RM Length L Ch R = 1,2891,482,482,482
BEGIN DESCRIPTION:
Mapping XS 235fcd67
END DESCRIPTION:
XS GIS Cut Line= 3
      2317995.05      7119772.38      2317553.61      7120539.11
      2317753.12      7121025.24
#Sta/Elev= 30
  4390.2  713.24  4414.3  710.22  4489.0  707.41  4525.9  703.60  4537.9  704.51
  4547.9  702.67  4553.7  704.42  4560.5  702.22  4575.3  701.06  4596.8  700.82
  4606.7  704.97  4612.6  705.04  4655.7  701.19  4897.1  695.48  4917.5  696.35
  4964.4  697.70  4996.8  693.36  4997.3  692.86  5001.5  693.36  5036.5  697.97
  5136.7  698.59  5356.0  698.50  5486.7  701.57  5516.0  705.35  5524.5  703.56
  5611.0  712.78  5622.8  716.57  5686.6  724.42  5748.1  731.19  5800.4  734.57
#Mann=5,-1,0
  4390.2    0.05       0  4917.5    0.12       0  4996.8    0.07       0
  5001.5    0.12       0  5136.7    0.05       0
Bank Sta=4996.8,5001.5
Exp/Cntr=0.3,0.1

Type RM Length L Ch R = 1,2409,933,933,933
BEGIN DESCRIPTION:
Mapping XS 9792b411
END DESCRIPTION:
XS GIS Cut Line= 3
      2317672.00      7119432.45      2317184.72      7120339.05
      2317672.44      7121085.13
#Sta/Elev= 30
  4431.0  702.96  4640.2  695.77  4763.9  692.07  4791.5  693.66  4859.6  693.68
  4882.3  692.18  4927.7  693.76  4955.5  693.36  4959.4  691.96  4960.0  691.46
  4964.2  691.96  5029.9  694.75  5087.0  693.93  5108.5  695.00  5147.0  694.11
  5427.3  694.36  5731.6  695.77  5876.4  696.97  6027.2  700.03  6057.4  703.47
  6070.7  704.46  6084.5  703.60  6135.8  708.62  6150.9  713.08  6166.0  715.16
  6178.2  718.53  6265.4  728.65  6280.6  731.54  6331.9  736.70  6351.6  737.44
#Mann=5,-1,0
  4431.0    0.05       0  4640.2    0.12       0  4959.4    0.07       0
  4964.2    0.12       0  5108.5    0.05       0
Bank Sta=4959.4,4964.2
Exp/Cntr=0.3,0.1

Type RM Length L Ch R = 1,1476,574,574,574
BEGIN DESCRIPTION:
Mapping XS ca2d9a45
END DESCRIPTION:
XS GIS Cut Line= 4
      2317299.52      7119174.86      2317092.41      7119340.06
      2317090.23      7120351.85      2317587.48      7121020.13
#Sta/Elev= 30
  4648.3  698.54  4744.8  694.11  4802.5  693.57  4823.3  692.17  4912.2  690.00
  4933.2  690.91  4983.2  687.88  4993.2  688.95  5010.8  687.77  5011.3  687.27
  5015.6  687.77  5036.7  689.05  5093.2  689.44  5143.2  694.18  5233.2  689.88
  5284.9  690.03  5323.2  691.67  5513.2  691.54  5603.2  692.83  5913.2  693.32
  6015.6  694.84  6195.0  695.30  6501.6  699.06  6545.4  700.52  6580.9  704.66
  6595.5  703.82  6616.3  705.85  6681.0  716.25  6701.8  720.98  6758.0  727.06
#Mann=5,-1,0
  4648.3    0.05       0  5010.8   0.033       0  5015.6    0.05       0
  5036.7    0.12       0  5284.9    0.05       0
Bank Sta=5010.8,5015.6
Exp/Cntr=0.3,0.1

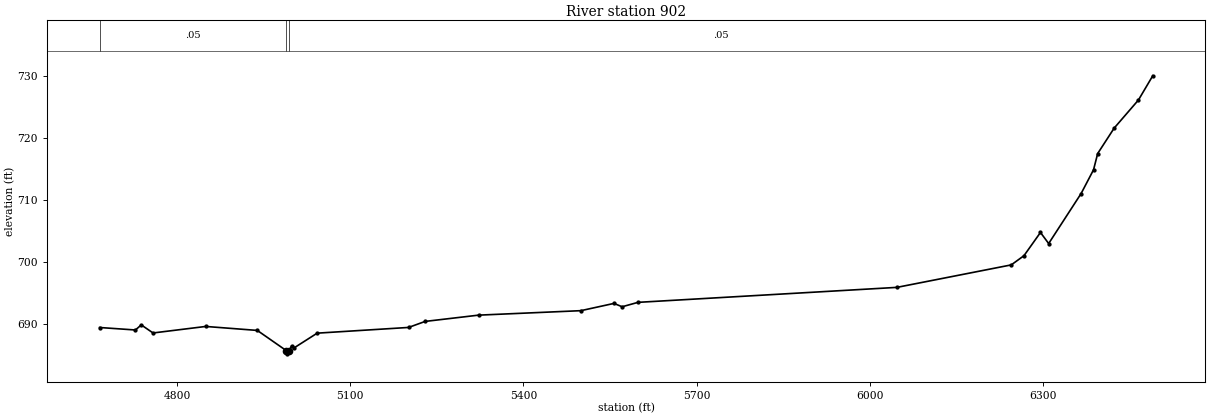
Type RM Length L Ch R = 1,902,0,0,0
BEGIN DESCRIPTION:
Mapping XS b2f56b01
END DESCRIPTION:
XS GIS Cut Line= 3
      2316841.89      7119528.95      2316750.22      7120049.52
      2317574.30      7121049.15
#Sta/Elev= 30
  4666.1  689.48  4728.1  689.08  4738.2  689.90  4758.6  688.60  4849.9  689.65
  4939.2  689.01  4989.7  685.74  4990.2  685.24  4994.5  685.74  4998.5  686.52
  5003.6  686.24  5042.9  688.57  5201.2  689.49  5229.9  690.46  5322.4  691.47
  5499.6  692.19  5557.0  693.36  5571.1  692.82  5598.6  693.53  6046.9  695.94
  6245.1  699.56  6267.1  701.04  6295.7  704.78  6309.9  703.00  6366.1  711.05
  6387.6  714.87  6394.8  717.49  6423.4  721.59  6465.4  726.11  6490.2  730.01
#Mann=3,-1,0
  4666.1    0.05       0  4989.7   0.033       0  4994.5    0.05       0
Bank Sta=4989.7,4994.5
Exp/Cntr=0.3,0.1

Chan Stop Cuts=-1