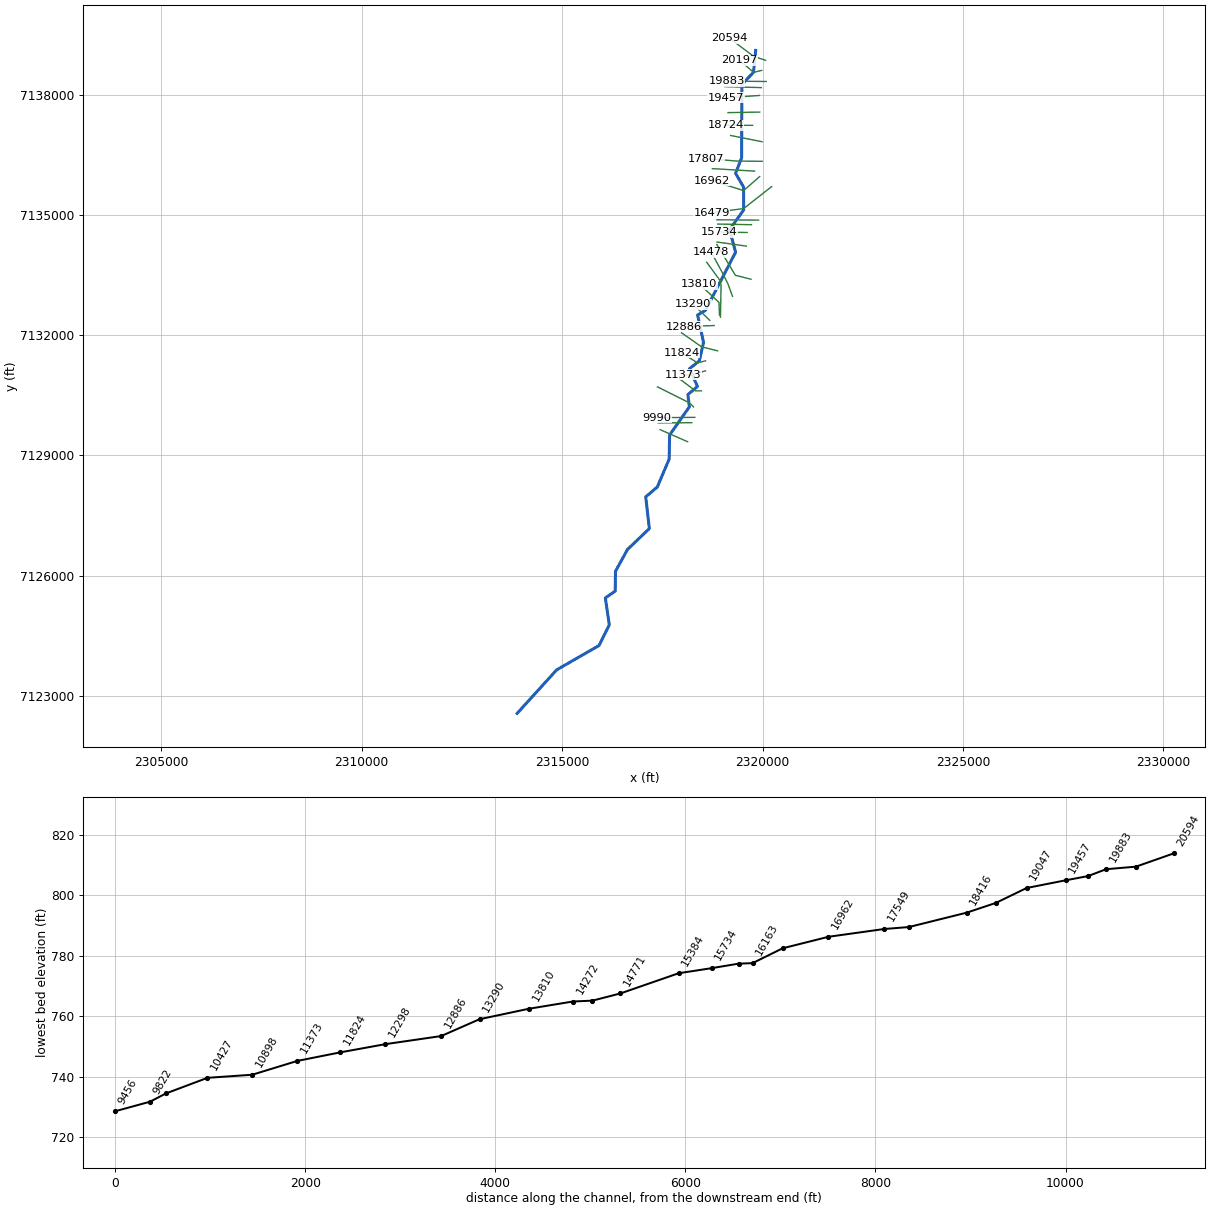
--- Denton Creek Tributary 31.prj (project) ---

Proj Title=Denton Creek Tributary 31 Base Level Engineering
Current Plan=p01
Default Exp/Contr=0.3,0.1
English Units
Geom File=g01
Flow File=f01
Plan File=p01
BEGIN DESCRIPTION:
Denton Creek Tributary 31
END DESCRIPTION:

--- Denton Creek Tributary 31.p01 (plan) ---

Plan Title=Multiple Run
Short Identifier=Multiple
Geom File=g01
Flow File=f01
Subcritical Flow
K Sum by GR= 0
Std Step Tol= 0.01
Critical Tol= 0.01
Num of Std Step Trials= 20
Max Error Tol= 0.3
Flow Tol Ratio= 0.001
Split Flow NTrial= 30
Split Flow Tol= 0.02
Split Flow Ratio= 0.02
Log Output Level= 0
Friction Slope Method= 1
Unsteady Friction Slope Method= 2
Unsteady Bridges Friction Slope Method= 1
Parabolic Critical Depth
Global Vel Dist=  1 , 1 , 1
Global Log Level= 0
CheckData=True
Encroach Param= -1, 0, 0, 0
BEGIN DESCRIPTION:
Multiple Run
END DESCRIPTION:

--- Denton Creek Tributary 31.f01 (steady flow) ---

Flow Title=Multiple
Number of Profiles=7
Profile Names=10-year,25-year,50-year,1pct_min,100-year,1pct_plu,500-year
River Rch & RM= Denton Creek Tri,Reach-1,20594
     514     697     846     511    1020    2035    1482
River Rch & RM= Denton Creek Tri,Reach-1,17807
     774    1075    1327     813    1622    3236    2428
River Rch & RM= Denton Creek Tri,Reach-1,14771
    1110    1572    1965    1218    2431    4850    3728
River Rch & RM= Denton Creek Tri,Reach-1,13290
    1258    1790    2245    1395    2784    5555    4293
River Rch & RM= Denton Creek Tri,Reach-1,7649
    1910    2768    3516    2209    4407    8794    6949
Boundary for River Rch & Prof#=Denton Creek Tri,Reach-1,1
Up Type=0
Dn Type=3
Dn Slope=0.00508
Boundary for River Rch & Prof#=Denton Creek Tri,Reach-1,2
Up Type=0
Dn Type=3
Dn Slope=0.00508
Boundary for River Rch & Prof#=Denton Creek Tri,Reach-1,3
Up Type=0
Dn Type=3
Dn Slope=0.00508
Boundary for River Rch & Prof#=Denton Creek Tri,Reach-1,4
Up Type=0
Dn Type=3
Dn Slope=0.00508
Boundary for River Rch & Prof#=Denton Creek Tri,Reach-1,5
Up Type=0
Dn Type=3
Dn Slope=0.00508
Boundary for River Rch & Prof#=Denton Creek Tri,Reach-1,6
Up Type=0
Dn Type=3
Dn Slope=0.00508
Boundary for River Rch & Prof#=Denton Creek Tri,Reach-1,7
Up Type=0
Dn Type=3
Dn Slope=0.00508

--- Denton Creek Tributary 31.g01 (geometry) ---

Geom Title=Existing Conditions

River Reach=Denton Creek Tri,Reach-1
Reach XY= 30
      2319829.00      7139110.00      2319775.46      7138561.46
      2319486.32      7138260.10      2319479.04      7136429.98
      2319328.57      7136039.82      2319527.78      7135699.50
      2319528.91      7135125.39      2319178.64      7134635.20
      2319328.26      7134070.69      2318575.50      7132618.46
      2318380.98      7132504.33      2318528.30      7131820.70
      2318423.61      7131357.56      2318178.13      7131165.08
      2318377.80      7130720.51      2318137.99      7130517.07
      2318175.25      7130211.55      2317682.76      7129508.44
      2317670.96      7128906.68      2317375.45      7128211.29
      2317086.61      7127963.33      2317177.07      7127171.95
      2316634.44      7126654.75      2316332.48      7126108.73
      2316325.48      7125611.46      2316079.21      7125441.43
      2316177.90      7124769.64      2315921.25      7124253.55
      2314865.67      7123646.60      2313879.00      7122560.00

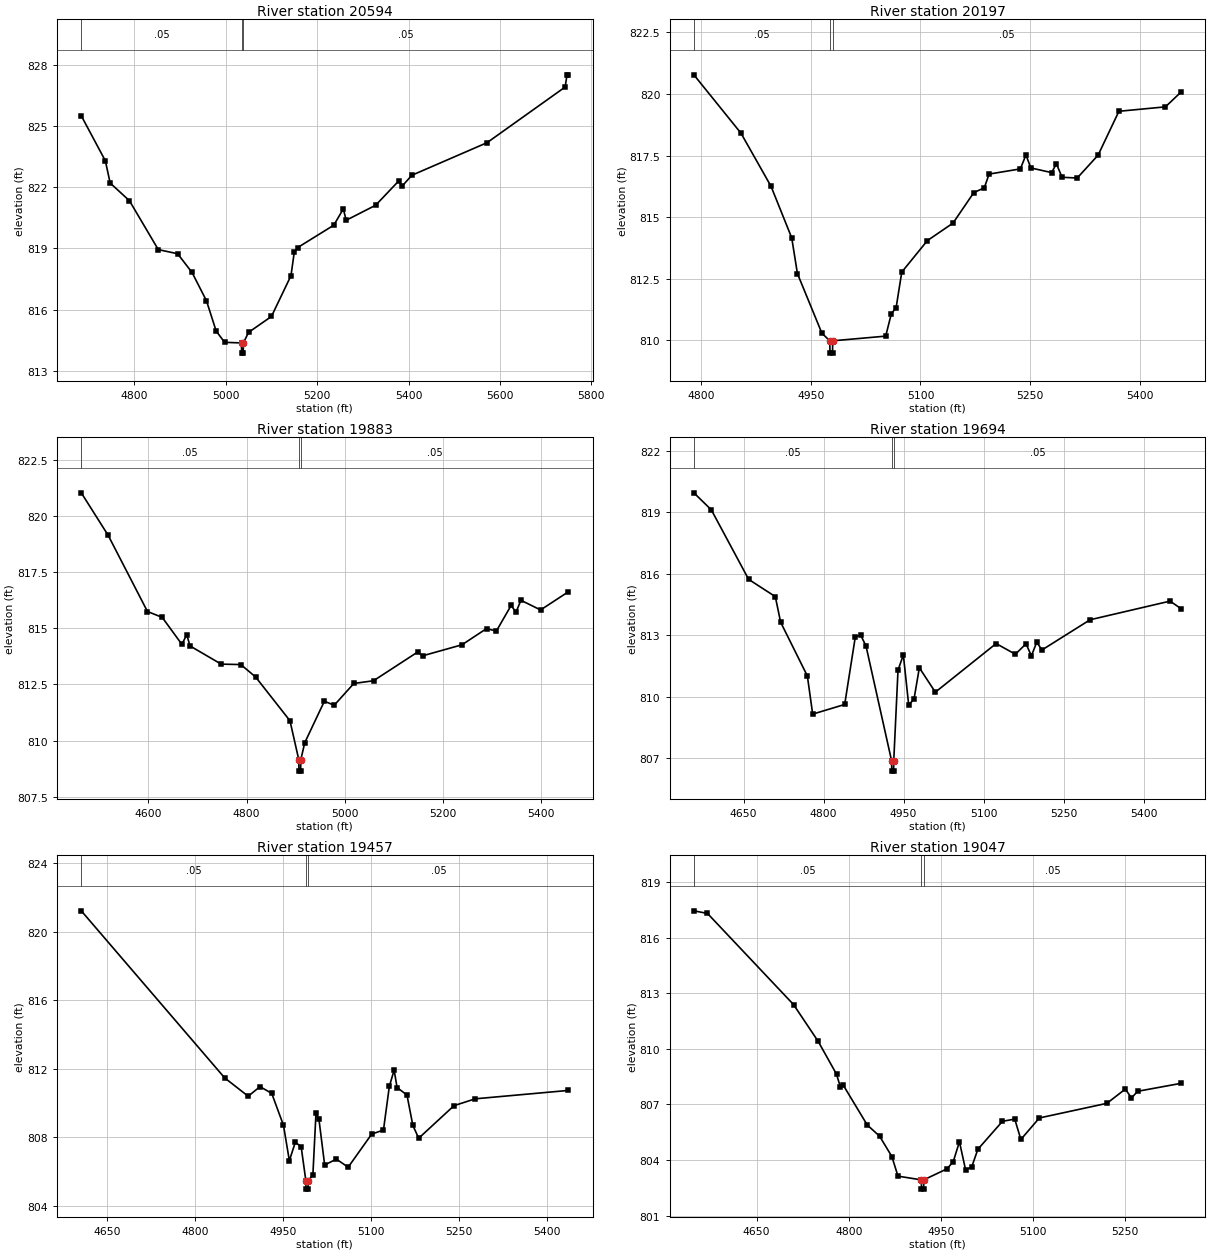
Type RM Length L Ch R = 1,20594,397,397,397
BEGIN DESCRIPTION:
Denton Creek Tributary 31 46.0
END DESCRIPTION:
XS GIS Cut Line= 3
      2320078.97      7138860.01      2319779.00      7138960.00
      2319179.00      7139410.00
#Sta/Elev= 30
  4683.7  825.51  4736.4  823.30  4746.9  822.21  4789.1  821.34  4852.3  818.94
  4894.5  818.74  4926.1  817.82  4957.7  816.43  4978.8  814.95  4997.3  814.39
  5034.4  814.36  5034.6  813.86  5038.1  813.86  5038.4  814.36  5049.9  814.88
  5099.9  815.66  5142.6  817.66  5149.9  818.82  5157.2  819.04  5236.4  820.14
  5257.2  820.94  5263.4  820.38  5328.0  821.12  5378.0  822.30  5386.4  822.07
  5407.2  822.59  5571.8  824.19  5742.6  826.92  5746.8  827.52  5749.9  827.52
#Mann=3,-1,0
  4683.7    0.05       0  5034.4   0.033       0  5038.4    0.05       0
Bank Sta=5034.4,5038.4
Exp/Cntr=0.3,0.1

Type RM Length L Ch R = 1,20197,314,314,314
BEGIN DESCRIPTION:
Denton Creek Tributary 31 45.0
END DESCRIPTION:
XS GIS Cut Line= 3
      2319979.03      7138610.01      2319779.00      7138560.00
      2319428.97      7138860.03
#Sta/Elev= 30
  4789.7  820.78  4854.2  818.41  4895.4  816.25  4923.7  814.16  4931.5  812.71
  4965.0  810.29  4975.8  809.98  4976.1  809.48  4979.6  809.48  4979.8  809.98
  5052.4  810.17  5060.1  811.08  5066.7  811.33  5074.4  812.77  5109.5  814.05
  5144.6  814.76  5173.1  816.00  5187.4  816.19  5194.0  816.75  5236.8  816.96
  5244.5  817.53  5251.1  817.00  5279.6  816.81  5286.2  817.17  5293.9  816.62
  5314.7  816.59  5343.3  817.52  5371.8  819.30  5435.5  819.48  5456.9  820.08
#Mann=3,-1,0
  4789.7    0.05       0  4975.8   0.033       0  4979.8    0.05       0
Bank Sta=4975.8,4979.8
Exp/Cntr=0.3,0.1

Type RM Length L Ch R = 1,19883,189,189,189
BEGIN DESCRIPTION:
Mapping XS de423554
END DESCRIPTION:
XS GIS Cut Line= 2
      2320093.67      7138332.58      2319102.33      7138343.35
#Sta/Elev= 30
  4463.6  821.02  4518.3  819.13  4598.3  815.74  4628.3  815.48  4668.3  814.28
  4678.3  814.71  4684.8  814.21  4748.3  813.40  4788.3  813.38  4818.3  812.83
  4888.3  810.88  4906.3  809.14  4906.5  808.64  4910.0  808.64  4910.3  809.14
  4918.3  809.90  4958.3  811.75  4978.3  811.57  5018.3  812.54  5058.3  812.66
  5148.3  813.94  5158.3  813.77  5238.3  814.26  5288.3  814.98  5308.3  814.87
  5338.3  816.01  5348.3  815.71  5358.3  816.24  5398.3  815.81  5455.0  816.62
#Mann=3,-1,0
  4463.6    0.05       0  4906.3   0.033       0  4910.3    0.05       0
Bank Sta=4906.3,4910.3
Exp/Cntr=0.3,0.1

Type RM Length L Ch R = 1,19694,237,237,237
BEGIN DESCRIPTION:
Mapping XS 75f7f012
END DESCRIPTION:
XS GIS Cut Line= 2
      2319971.68      7138179.74      2319058.42      7138204.39
#Sta/Elev= 30
  4556.8  819.94  4589.5  819.11  4659.5  815.72  4709.5  814.88  4719.5  813.63
  4769.6  811.01  4779.6  809.15  4839.6  809.62  4859.6  812.93  4869.6  813.00
  4879.6  812.47  4927.6  806.87  4927.9  806.37  4931.4  806.37  4931.6  806.87
  4939.6  811.29  4949.6  812.04  4959.6  809.60  4969.6  809.88  4979.6  811.41
  5009.6  810.22  5123.6  812.59  5159.7  812.07  5179.7  812.58  5189.7  811.99
  5199.7  812.65  5209.7  812.28  5299.8  813.75  5449.8  814.66  5470.4  814.29
#Mann=3,-1,0
  4556.8    0.05       0  4927.6   0.033       0  4931.6    0.05       0
Bank Sta=4927.6,4931.6
Exp/Cntr=0.3,0.1

Type RM Length L Ch R = 1,19457,410,410,410
BEGIN DESCRIPTION:
Mapping XS 5c422332
END DESCRIPTION:
XS GIS Cut Line= 2
      2319922.97      7137984.41      2319094.31      7137923.40
#Sta/Elev= 30
  4605.4  821.21  4850.0  811.46  4890.1  810.39  4910.2  810.95  4930.2  810.56
  4950.3  808.69  4960.3  806.63  4970.4  807.70  4980.4  807.45  4988.4  805.47
  4988.7  804.97  4992.2  804.97  4992.4  805.47  5000.4  805.79  5005.7  809.40
  5010.7  809.06  5020.5  806.38  5040.5  806.72  5060.6  806.25  5100.7  808.18
  5120.8  808.42  5130.8  810.96  5139.0  811.92  5144.0  810.90  5160.9  810.46
  5170.9  808.69  5180.9  807.94  5241.1  809.84  5277.3  810.24  5436.3  810.73
#Mann=3,-1,0
  4605.4    0.05       0  4988.4   0.033       0  4992.4    0.05       0
Bank Sta=4988.4,4992.4
Exp/Cntr=0.3,0.1

Type RM Length L Ch R = 1,19047,323,323,323
BEGIN DESCRIPTION:
Mapping XS 78153170
END DESCRIPTION:
XS GIS Cut Line= 2
      2319931.13      7137568.93      2319138.34      7137555.93
#Sta/Elev= 30
  4547.8  817.45  4569.9  817.31  4710.0  812.39  4750.0  810.41  4780.0  808.63
  4786.1  807.95  4791.1  808.03  4830.0  805.89  4850.0  805.29  4870.0  804.19
  4880.0  803.13  4918.0  802.93  4918.2  802.43  4921.7  802.43  4922.0  802.93
  4960.0  803.53  4970.0  803.92  4980.0  804.99  4990.0  803.47  5000.0  803.63
  5010.0  804.58  5050.0  806.09  5070.0  806.21  5080.0  805.11  5110.0  806.27
  5220.0  807.06  5250.0  807.83  5260.0  807.35  5270.0  807.71  5340.7  808.14
#Mann=3,-1,0
  4547.8    0.05       0  4918.0   0.033       0  4922.0    0.05       0
Bank Sta=4918,4922
Exp/Cntr=0.3,0.1

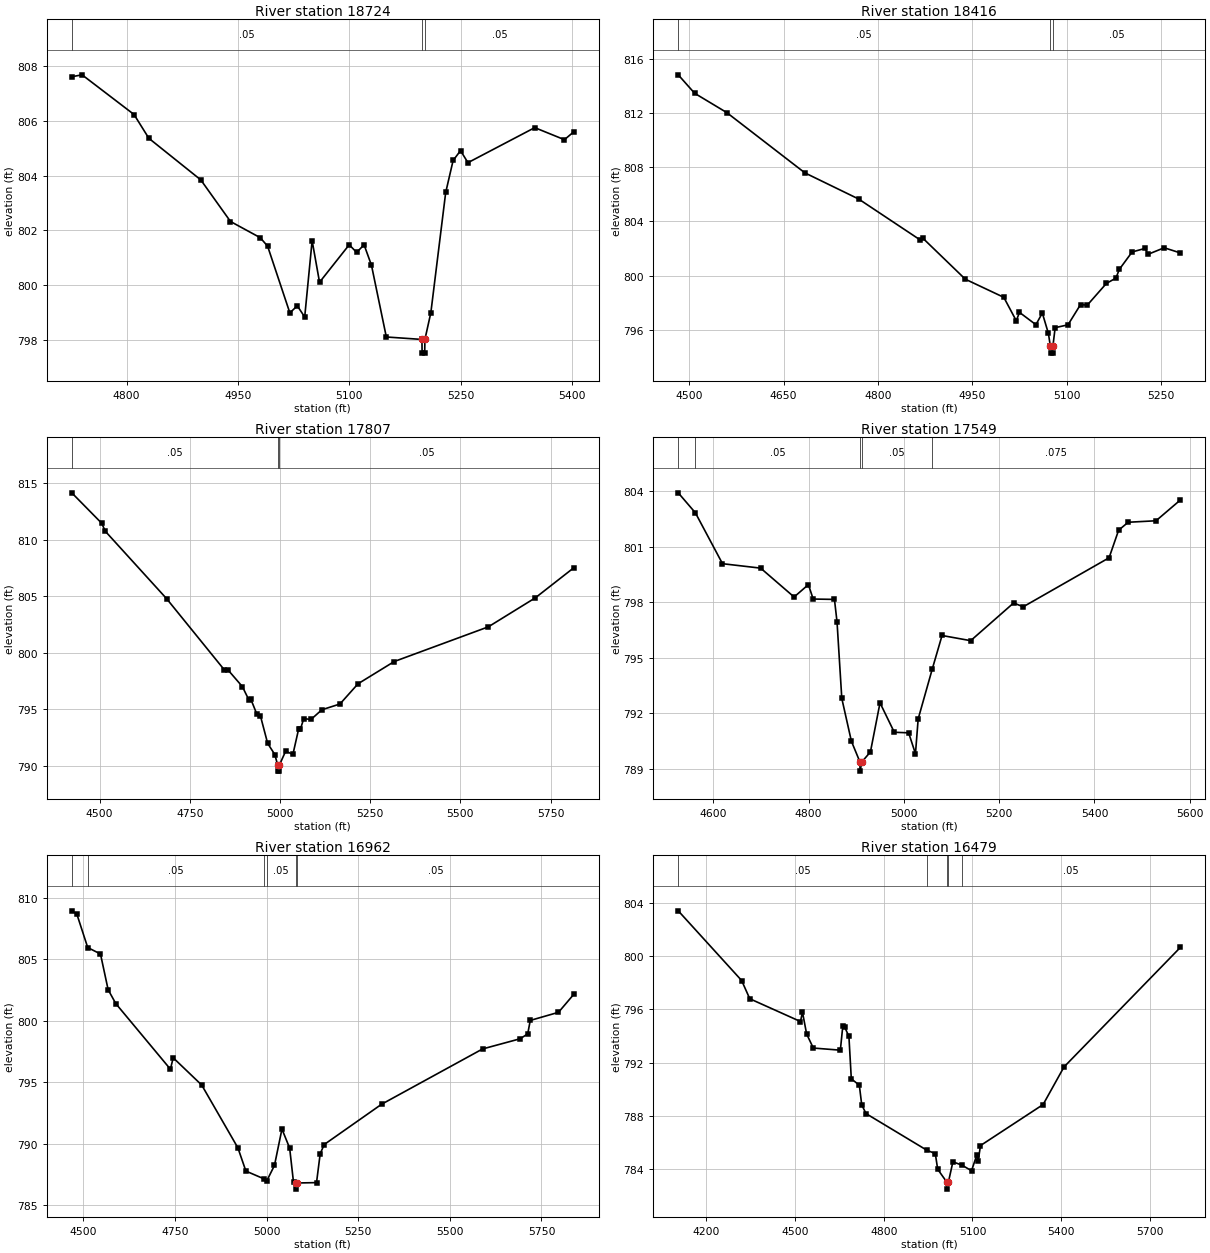
Type RM Length L Ch R = 1,18724,308,308,308
BEGIN DESCRIPTION:
Mapping XS 1ffe82b7
END DESCRIPTION:
XS GIS Cut Line= 2
      2319752.90      7137237.98      2319076.30      7137239.25
#Sta/Elev= 30
  4726.1  807.61  4740.0  807.68  4810.0  806.23  4830.0  805.36  4900.0  803.84
  4940.0  802.32  4980.0  801.73  4990.0  801.42  5020.0  798.98  5030.0  799.24
  5040.0  798.83  5050.0  801.62  5060.0  800.10  5100.0  801.47  5110.0  801.19
  5120.0  801.47  5130.0  800.72  5150.0  798.10  5198.0  798.01  5198.2  797.51
  5201.7  797.51  5202.0  798.01  5210.0  798.99  5230.0  803.38  5240.0  804.55
  5250.0  804.91  5260.0  804.47  5350.0  805.75  5390.0  805.31  5402.7  805.60
#Mann=3,-1,0
  4726.1    0.05       0  5198.0   0.033       0  5202.0    0.05       0
Bank Sta=5198,5202
Exp/Cntr=0.3,0.1

Type RM Length L Ch R = 1,18416,609,609,609
BEGIN DESCRIPTION:
Mapping XS 77b57a4f
END DESCRIPTION:
XS GIS Cut Line= 2
      2319986.46      7136829.31      2319203.90      7136984.99
#Sta/Elev= 30
  4482.6  814.83  4508.6  813.47  4559.8  812.04  4683.9  807.59  4769.3  805.66
  4866.4  802.66  4871.5  802.76  4938.8  799.74  5000.0  798.40  5019.8  796.67
  5024.9  797.29  5051.0  796.38  5061.2  797.24  5070.9  795.73  5074.0  794.78
  5074.3  794.28  5077.8  794.28  5078.0  794.78  5081.6  796.16  5102.0  796.37
  5122.0  797.87  5132.6  797.82  5163.1  799.43  5178.2  799.82  5183.5  800.46
  5203.9  801.75  5224.3  802.01  5229.4  801.58  5254.9  802.06  5280.5  801.68
#Mann=3,-1,0
  4482.6    0.05       0  5074.0   0.033       0  5078.0    0.05       0
Bank Sta=5074,5078
Exp/Cntr=0.3,0.1

Type RM Length L Ch R = 1,17807,258,258,258
BEGIN DESCRIPTION:
Mapping XS 1c6e2dc3
END DESCRIPTION:
XS GIS Cut Line= 3
      2319991.89      7136340.20      2319362.48      7136346.30
      2318602.76      7136407.16
#Sta/Elev= 30
  4423.1  814.15  4506.0  811.46  4516.0  810.75  4686.0  804.78  4846.0  798.48
  4856.0  798.48  4896.0  797.00  4914.6  795.78  4919.6  795.87  4936.0  794.57
  4946.0  794.41  4966.0  791.98  4986.0  790.98  4994.0  790.02  4994.3  789.52
  4997.8  789.52  4998.0  790.02  5016.0  791.29  5036.0  791.00  5051.8  793.23
  5056.8  793.23  5066.1  794.17  5086.1  794.09  5116.2  794.95  5166.4  795.46
  5216.5  797.25  5316.9  799.22  5577.7  802.29  5708.1  804.86  5814.7  807.52
#Mann=3,-1,0
  4423.1    0.05       0  4994.0   0.033       0  4998.0    0.05       0
Bank Sta=4994,4998
Exp/Cntr=0.3,0.1

Type RM Length L Ch R = 1,17549,587,587,587
BEGIN DESCRIPTION:
Mapping XS a01054b0
END DESCRIPTION:
XS GIS Cut Line= 2
      2319801.73      7136095.70      2318749.76      7136157.81
#Sta/Elev= 30
  4526.4  803.92  4562.4  802.84  4619.3  800.09  4699.4  799.85  4769.6  798.29
  4799.6  798.96  4809.6  798.18  4854.3  798.16  4859.7  796.94  4869.7  792.81
  4889.8  790.50  4907.7  789.38  4908.0  788.88  4911.9  789.38  4929.8  789.92
  4949.9  792.57  4979.9  790.98  5010.0  790.95  5024.3  789.82  5030.0  791.70
  5059.5  794.39  5080.1  796.21  5140.2  795.93  5230.4  797.97  5250.4  797.76
  5430.7  800.41  5450.7  801.90  5470.8  802.33  5529.2  802.41  5580.2  803.53
#Mann=5,-1,0
  4526.4   0.075       0  4562.4    0.05       0  4907.7    0.05       0
  4911.9    0.05       0  5059.5   0.075       0
Bank Sta=4907.7,4911.9
Exp/Cntr=0.3,0.1

Type RM Length L Ch R = 1,16962,483,483,483
BEGIN DESCRIPTION:
Denton Creek Tributary 31 37.0
END DESCRIPTION:
XS GIS Cut Line= 3
      2319929.01      7135960.01      2319529.00      7135610.00
      2318728.97      7135860.01
#Sta/Elev= 30
  4468.6  808.96  4482.4  808.70  4512.1  805.97  4546.9  805.45  4567.8  802.54
  4588.7  801.41  4737.7  796.07  4745.3  797.00  4823.1  794.78  4921.8  789.67
  4943.6  787.78  4991.9  787.16  5001.0  787.01  5021.6  788.24  5042.0  791.20
  5063.0  789.65  5073.5  786.87  5079.2  786.81  5079.5  786.31  5083.5  786.81
  5136.3  786.84  5146.3  789.19  5157.3  789.94  5313.9  793.22  5589.4  797.72
  5692.1  798.55  5712.5  798.95  5719.4  800.04  5796.4  800.70  5838.3  802.17
#Mann=6,-1,0
  4468.6   0.075       0  4512.1    0.05       0  4991.9    0.12       0
  5001.0    0.05       0  5079.2    0.07       0  5083.5    0.05       0
Bank Sta=5079.2,5083.5
Exp/Cntr=0.3,0.1

Type RM Length L Ch R = 1,16479,316,316,316
BEGIN DESCRIPTION:
Denton Creek Tributary 31 36.0
END DESCRIPTION:
XS GIS Cut Line= 3
      2320229.03      7135710.02      2319529.00      7135160.00
      2318728.99      7135060.00
#Sta/Elev= 30
  4105.7  803.39  4319.9  798.16  4347.4  796.79  4518.8  795.08  4525.4  795.79
  4539.6  794.14  4562.1  793.09  4653.5  792.93  4661.6  794.71  4667.9  794.67
  4682.4  793.97  4690.5  790.78  4717.6  790.30  4725.7  788.83  4740.2  788.17
  4946.5  785.41  4974.3  785.17  4982.4  783.99  5014.0  783.00  5014.3  782.50
  5018.3  783.00  5033.8  784.55  5064.4  784.30  5096.7  783.88  5114.4  785.05
  5119.4  784.64  5127.0  785.77  5338.6  788.85  5409.2  791.67  5802.2  800.64
#Mann=5,-1,0
  4105.7    0.05       0  4946.5    0.12       0  5014.0    0.07       0
  5018.3    0.12       0  5064.4    0.05       0
Bank Sta=5014,5018.3
Exp/Cntr=0.3,0.1

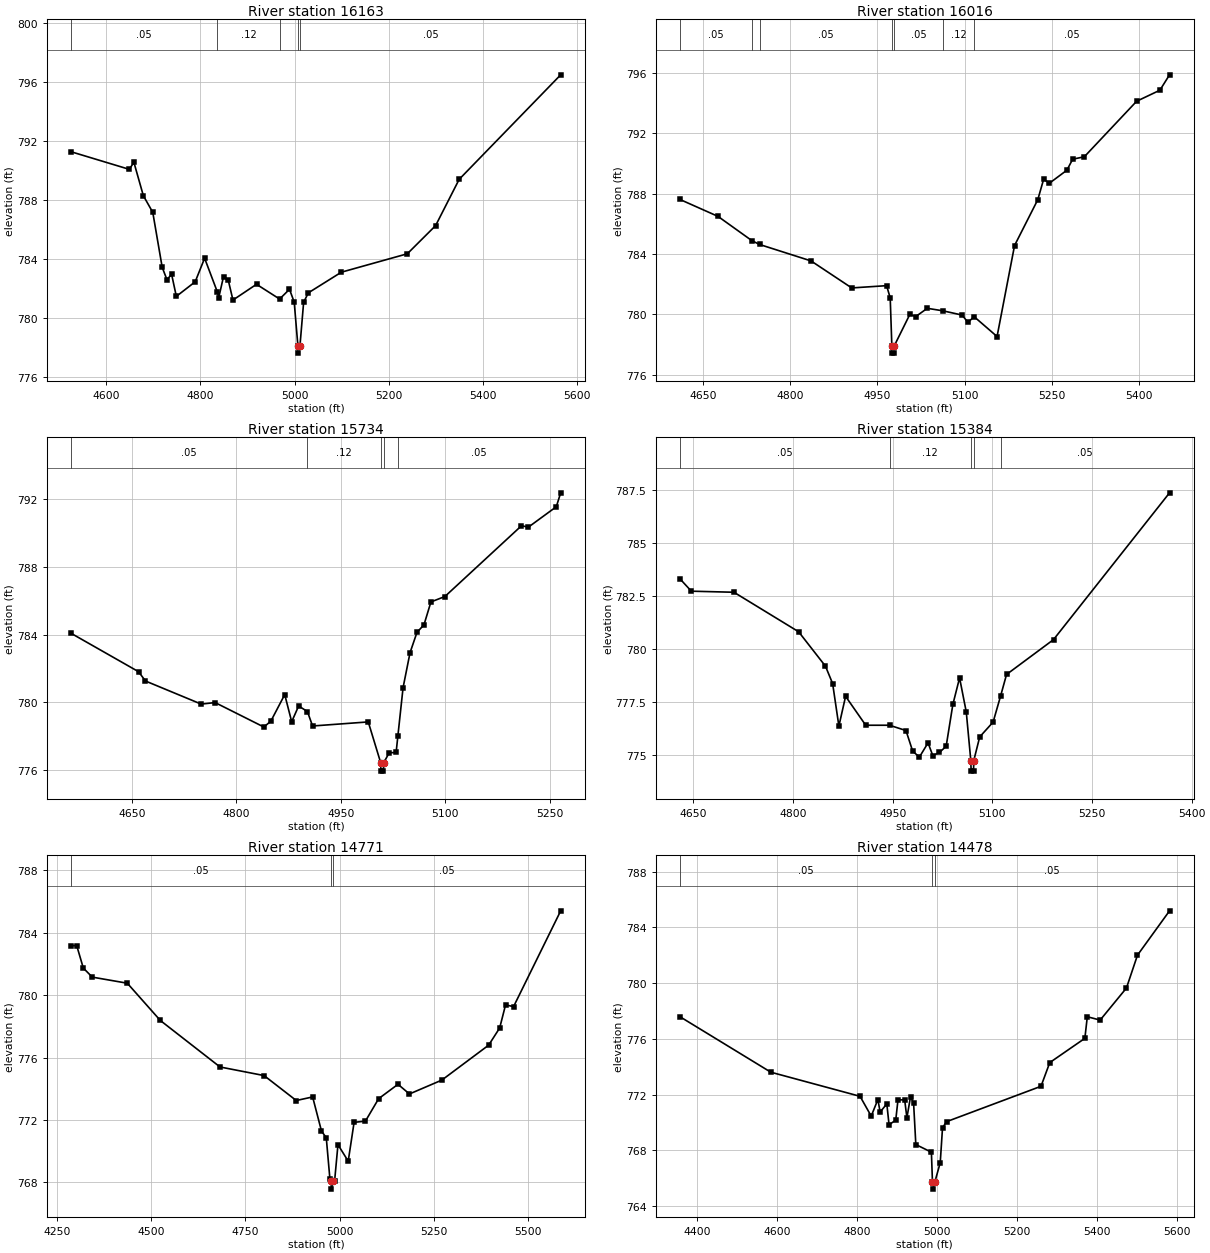
Type RM Length L Ch R = 1,16163,147,147,147
BEGIN DESCRIPTION:
Mapping XS 8f5f23cd
END DESCRIPTION:
XS GIS Cut Line= 2
      2319902.24      7134872.19      2318863.57      7134880.46
#Sta/Elev= 30
  4526.0  791.26  4649.2  790.07  4659.2  790.54  4679.2  788.28  4699.2  787.15
  4719.2  783.42  4729.2  782.59  4739.2  782.94  4749.2  781.45  4789.2  782.44
  4809.2  784.04  4836.1  781.76  4839.2  781.37  4849.3  782.79  4859.3  782.56
  4869.3  781.20  4919.3  782.27  4968.3  781.27  4989.3  781.93  4999.3  781.06
  5007.1  778.10  5007.5  777.60  5011.5  778.10  5019.3  781.05  5029.3  781.69
  5099.3  783.09  5239.3  784.34  5299.3  786.25  5349.3  789.39  5564.7  796.48
#Mann=5,-1,0
  4526.0    0.05       0  4836.1    0.12       0  4968.3    0.05       0
  5007.1   0.033       0  5011.5    0.05       0
Bank Sta=5007.1,5011.5
Exp/Cntr=0.3,0.1

Type RM Length L Ch R = 1,16016,282,282,282
BEGIN DESCRIPTION:
Mapping XS 11905780
END DESCRIPTION:
XS GIS Cut Line= 2
      2319724.35      7134758.11      2318882.40      7134774.10
#Sta/Elev= 30
  4610.4  787.61  4675.8  786.49  4733.8  784.89  4747.2  784.63  4835.8  783.54
  4905.8  781.75  4965.8  781.90  4972.0  781.09  4974.8  777.93  4975.2  777.43
  4978.8  777.43  4979.2  777.93  5005.8  780.00  5015.8  779.85  5035.8  780.40
  5063.1  780.23  5095.8  779.95  5105.8  779.46  5116.2  779.85  5155.8  778.53
  5185.9  784.56  5225.9  787.60  5235.9  788.95  5245.9  788.69  5275.9  789.55
  5285.9  790.28  5305.9  790.44  5395.9  794.12  5435.9  794.85  5452.5  795.87
#Mann=7,-1,0
  4610.4    0.05       0  4733.8    0.12       0  4747.2    0.05       0
  4974.8   0.033       0  4979.2    0.05       0  5063.1    0.12       0
  5116.2    0.05       0
Bank Sta=4974.8,4979.2
Exp/Cntr=0.3,0.1

Type RM Length L Ch R = 1,15734,350,350,350
BEGIN DESCRIPTION:
Mapping XS fed97c5c
END DESCRIPTION:
XS GIS Cut Line= 2
      2319615.77      7134563.49      2318912.68      7134575.39
#Sta/Elev= 30
  4562.7  784.07  4659.5  781.81  4669.5  781.26  4749.5  779.90  4769.5  779.99
  4839.5  778.55  4849.5  778.89  4869.5  780.46  4879.5  778.86  4889.5  779.79
  4902.1  779.46  4909.5  778.61  4989.5  778.85  5007.3  776.45  5007.7  775.95
  5011.3  775.95  5011.8  776.45  5019.5  777.03  5029.5  777.05  5032.0  778.01
  5039.5  780.87  5049.5  782.93  5059.5  784.13  5069.5  784.57  5079.5  785.92
  5099.6  786.24  5209.6  790.41  5219.6  790.33  5259.6  791.53  5265.9  792.35
#Mann=5,-1,0
  4562.7    0.05       0  4902.1    0.12       0  5007.3    0.07       0
  5011.8    0.12       0  5032.0    0.05       0
Bank Sta=5007.3,5011.8
Exp/Cntr=0.3,0.1

Type RM Length L Ch R = 1,15384,613,613,613
BEGIN DESCRIPTION:
Mapping XS c80f1932
END DESCRIPTION:
XS GIS Cut Line= 2
      2319595.95      7134224.05      2318865.93      7134325.20
#Sta/Elev= 30
  4629.7  783.30  4646.8  782.72  4710.9  782.67  4808.3  780.81  4848.7  779.19
  4859.5  778.37  4868.9  776.37  4879.0  777.77  4909.3  776.41  4945.1  776.41
  4969.9  776.16  4980.0  775.19  4990.1  774.91  5003.1  775.58  5010.3  774.98
  5020.3  775.13  5030.4  775.42  5040.5  777.39  5050.6  778.64  5060.7  777.03
  5067.5  774.75  5068.0  774.25  5071.6  774.25  5072.0  774.75  5080.9  775.86
  5101.1  776.56  5112.3  777.78  5121.3  778.80  5192.0  780.44  5366.7  787.35
#Mann=5,-1,0
  4629.7    0.05       0  4945.1    0.12       0  5067.5    0.07       0
  5072.0    0.12       0  5112.3    0.05       0
Bank Sta=5067.5,5072
Exp/Cntr=0.3,0.1

Type RM Length L Ch R = 1,14771,293,293,293
BEGIN DESCRIPTION:
Mapping XS 215254ad
END DESCRIPTION:
XS GIS Cut Line= 3
      2319713.34      7133396.52      2319323.23      7133495.95
      2318860.47      7134263.68
#Sta/Elev= 30
  4287.9  783.18  4302.7  783.18  4320.2  781.74  4344.0  781.16  4436.9  780.77
  4524.6  778.38  4683.0  775.40  4799.8  774.85  4885.3  773.25  4928.7  773.48
  4952.1  771.30  4964.9  770.86  4974.6  768.20  4977.5  768.07  4978.5  767.57
  4983.3  768.07  4987.1  768.12  4995.9  770.42  5023.1  769.36  5038.7  771.85
  5068.8  771.93  5103.9  773.37  5155.2  774.29  5185.6  773.67  5271.6  774.56
  5395.8  776.80  5425.0  777.90  5440.6  779.38  5461.9  779.27  5586.9  785.41
#Mann=3,-1,0
  4287.9    0.05       0  4977.5   0.033       0  4983.3    0.05       0
Bank Sta=4977.5,4983.3
Exp/Cntr=0.3,0.1

Type RM Length L Ch R = 1,14478,206,206,206
BEGIN DESCRIPTION:
Mapping XS 85632d1e
END DESCRIPTION:
XS GIS Cut Line= 4
      2319251.53      7132969.99      2319132.56      7133293.86
      2319000.12      7133555.94      2318723.79      7134071.14
#Sta/Elev= 30
  4357.7  777.58  4584.7  773.60  4807.6  771.87  4835.5  770.45  4852.2  771.64
  4857.8  770.74  4874.5  771.33  4880.1  769.83  4896.8  770.16  4902.4  771.61
  4919.1  771.62  4924.7  770.33  4933.7  771.83  4941.4  771.40  4947.0  768.41
  4985.9  767.86  4988.6  765.71  4989.5  765.21  4994.4  765.71  5008.0  767.11
  5013.7  769.61  5023.7  770.05  5259.8  772.59  5281.7  774.29  5369.4  776.03
  5375.5  777.58  5407.6  777.34  5473.3  779.64  5500.9  782.00  5581.0  785.18
#Mann=3,-1,0
  4357.7    0.05       0  4988.6   0.033       0  4994.4    0.05       0
Bank Sta=4988.6,4994.4
Exp/Cntr=0.3,0.1

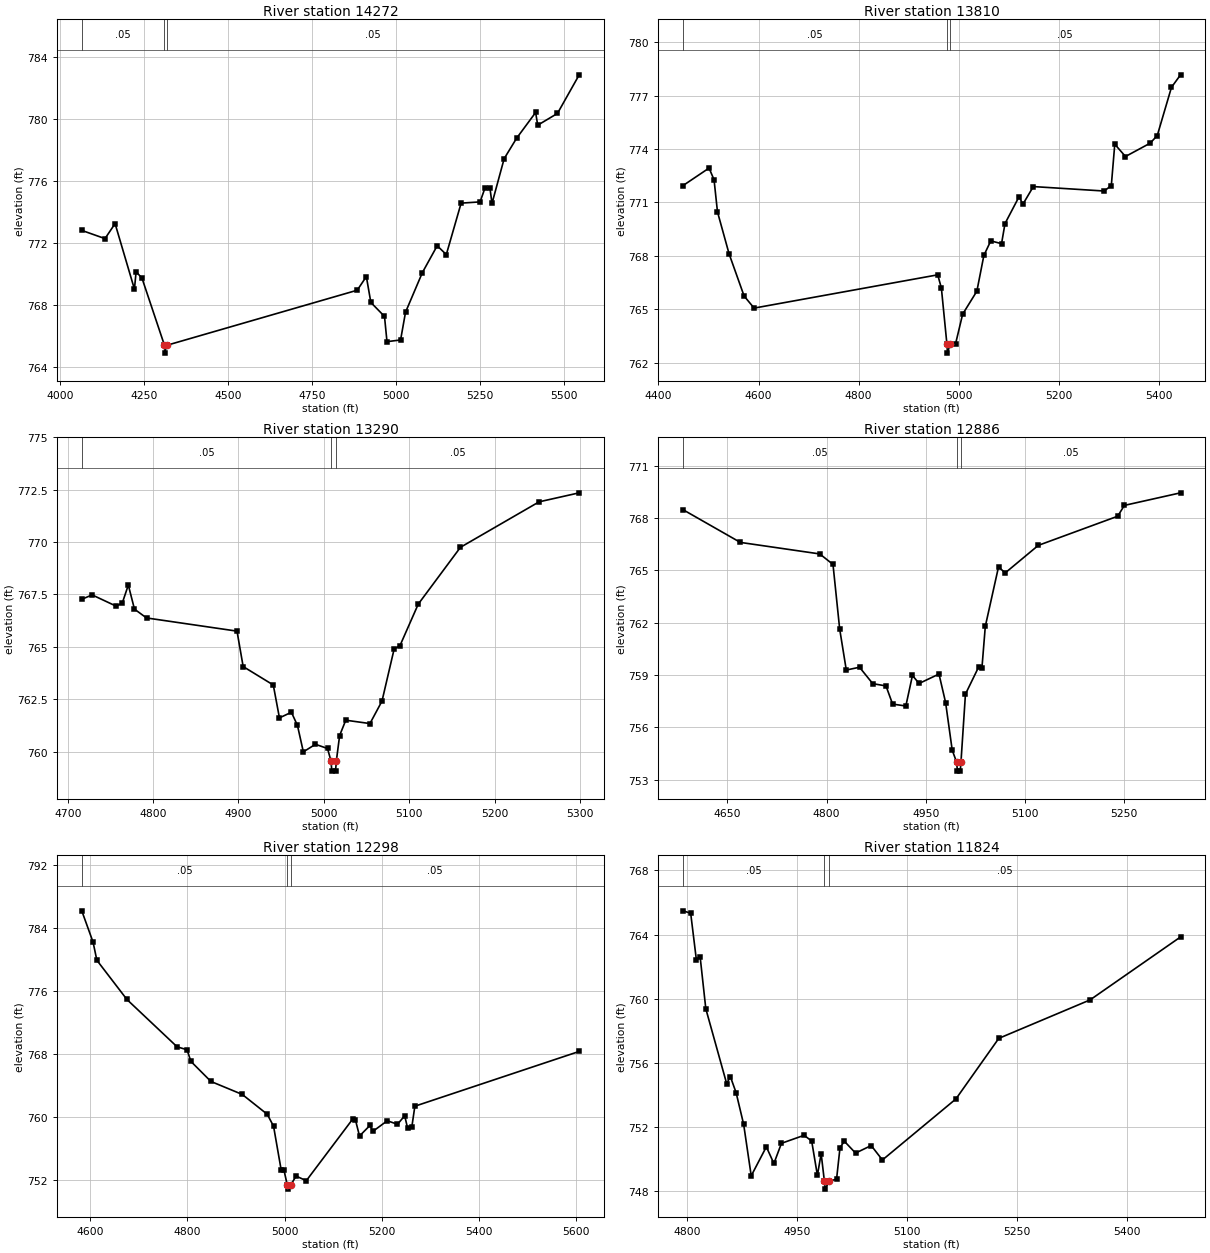
Type RM Length L Ch R = 1,14272,462,462,462
BEGIN DESCRIPTION:
Mapping XS 84824e7a
END DESCRIPTION:
XS GIS Cut Line= 4
      2318950.92      7132450.88      2318965.98      7133230.37
      2318943.37      7133359.08      2318608.49      7133820.81
#Sta/Elev= 30
  4064.7  772.84  4133.8  772.31  4163.8  773.28  4221.4  769.05  4226.4  770.17
  4243.9  769.76  4310.9  765.42  4311.9  764.92  4316.9  765.42  4884.6  768.98
  4911.8  769.86  4925.2  768.19  4965.8  767.29  4973.2  765.66  5013.7  765.77
  5028.4  767.56  5078.6  770.12  5122.7  771.85  5149.8  771.28  5193.9  774.60
  5250.3  774.68  5265.0  775.58  5279.7  775.57  5285.8  774.58  5322.0  777.47
  5359.1  778.79  5415.7  780.45  5421.9  779.63  5480.7  780.39  5545.4  782.88
#Mann=3,-1,0
  4064.7    0.05       0  4310.9    0.04       0  4316.9    0.05       0
Bank Sta=4310.9,4316.9
Exp/Cntr=0.3,0.1

Type RM Length L Ch R = 1,13810,520,520,520
BEGIN DESCRIPTION:
Mapping XS 13fdb313
END DESCRIPTION:
XS GIS Cut Line= 3
      2318926.84      7132498.28      2318913.94      7132817.69
      2318422.63      7133279.14
#Sta/Elev= 30
  4449.3  771.95  4501.1  772.93  4511.1  772.27  4517.9  770.47  4541.1  768.11
  4571.1  765.74  4591.1  765.06  4957.9  766.93  4965.2  766.19  4976.3  763.03
  4977.4  762.53  4982.5  763.03  4993.6  763.06  5007.7  764.72  5036.1  766.01
  5050.1  768.02  5063.9  768.84  5085.4  768.68  5092.3  769.81  5120.6  771.33
  5127.9  770.89  5148.9  771.89  5290.5  771.64  5304.7  771.95  5311.6  774.27
  5333.0  773.58  5382.4  774.33  5396.5  774.76  5424.9  777.47  5443.0  778.17
#Mann=3,-1,0
  4449.3    0.05       0  4976.3    0.04       0  4982.5    0.05       0
Bank Sta=4976.3,4982.5
Exp/Cntr=0.3,0.1

Type RM Length L Ch R = 1,13290,404,404,404
BEGIN DESCRIPTION:
Mapping XS bc48dc93
END DESCRIPTION:
XS GIS Cut Line= 2
      2318685.59      7132369.44      2318266.52      7132774.17
#Sta/Elev= 30
  4716.5  767.27  4728.6  767.48  4756.9  766.94  4764.0  767.10  4771.0  767.95
  4778.2  766.80  4792.3  766.38  4898.3  765.75  4905.5  764.06  4940.8  763.18
  4948.0  761.61  4962.0  761.88  4969.1  761.25  4976.0  759.99  4990.2  760.35
  5004.3  760.15  5008.3  759.57  5009.4  759.07  5013.7  759.07  5014.7  759.57
  5018.5  760.77  5025.7  761.50  5054.0  761.34  5068.1  762.41  5082.3  764.89
  5089.2  765.06  5110.6  767.04  5160.0  769.75  5252.1  771.92  5299.1  772.35
#Mann=3,-1,0
  4716.5    0.05       0  5008.3   0.033       0  5014.7    0.05       0
Bank Sta=5008.3,5014.7
Exp/Cntr=0.3,0.1

Type RM Length L Ch R = 1,12886,588,588,588
BEGIN DESCRIPTION:
Mapping XS 4bcd6890
END DESCRIPTION:
XS GIS Cut Line= 2
      2318795.39      7132241.70      2318044.11      7132213.89
#Sta/Elev= 30
  4583.3  768.47  4669.8  766.60  4789.8  765.94  4809.8  765.34  4819.9  761.64
  4829.9  759.29  4849.9  759.45  4869.9  758.51  4889.9  758.38  4899.9  757.34
  4919.9  757.23  4929.9  758.98  4939.9  758.52  4970.0  759.06  4980.0  757.43
  4990.0  754.70  4996.8  754.00  4997.8  753.50  5002.1  753.50  5003.2  754.00
  5010.0  757.91  5029.9  759.46  5034.9  759.40  5040.0  761.79  5060.0  765.20
  5070.0  764.85  5120.1  766.43  5240.1  768.10  5250.2  768.72  5335.1  769.44
#Mann=3,-1,0
  4583.3    0.05       0  4996.8    0.04       0  5003.2    0.05       0
Bank Sta=4996.8,5003.2
Exp/Cntr=0.3,0.1

Type RM Length L Ch R = 1,12298,474,474,474
BEGIN DESCRIPTION:
Denton Creek Tributary 31 27.0
END DESCRIPTION:
XS GIS Cut Line= 3
      2318879.03      7131609.99      2318479.00      7131710.00
      2317978.98      7132060.02
#Sta/Elev= 30
  4583.2  786.23  4606.4  782.24  4614.2  779.94  4676.0  774.95  4779.1  768.93
  4799.7  768.55  4807.4  767.08  4848.7  764.52  4913.1  762.87  4964.6  760.34
  4977.5  758.82  4993.0  753.31  4998.6  753.31  5005.8  751.32  5006.8  750.82
  5012.4  751.32  5023.9  752.48  5044.8  751.89  5139.8  759.70  5145.9  759.61
  5154.2  757.58  5175.6  758.92  5181.7  758.17  5211.3  759.52  5232.3  759.07
  5247.1  760.16  5253.2  758.54  5261.9  758.78  5268.0  761.37  5605.9  768.34
#Mann=3,-1,0
  4583.2    0.05       0  5005.8   0.033       0  5012.4    0.05       0
Bank Sta=5005.8,5012.4
Exp/Cntr=0.3,0.1

Type RM Length L Ch R = 1,11824,451,451,451
BEGIN DESCRIPTION:
Denton Creek Tributary 31 26.0
END DESCRIPTION:
XS GIS Cut Line= 3
      2318579.00      7131360.00      2318379.00      7131310.00
      2317978.96      7131560.02
#Sta/Elev= 30
  4794.8  765.48  4805.1  765.33  4812.8  762.44  4818.0  762.60  4825.7  759.37
  4854.1  754.70  4859.2  755.13  4867.0  754.13  4877.3  752.15  4887.6  748.94
  4908.2  750.75  4918.5  749.71  4928.8  750.97  4959.7  751.47  4970.0  751.11
  4977.8  748.97  4982.9  750.33  4987.3  748.61  4988.4  748.11  4993.9  748.61
  5003.9  748.73  5008.6  750.70  5014.5  751.10  5029.8  750.36  5051.1  750.83
  5066.4  749.93  5166.6  753.74  5225.0  757.52  5349.4  759.92  5472.7  763.85
#Mann=3,-1,0
  4794.8    0.05       0  4987.3   0.033       0  4993.9    0.05       0
Bank Sta=4987.3,4993.9
Exp/Cntr=0.3,0.1

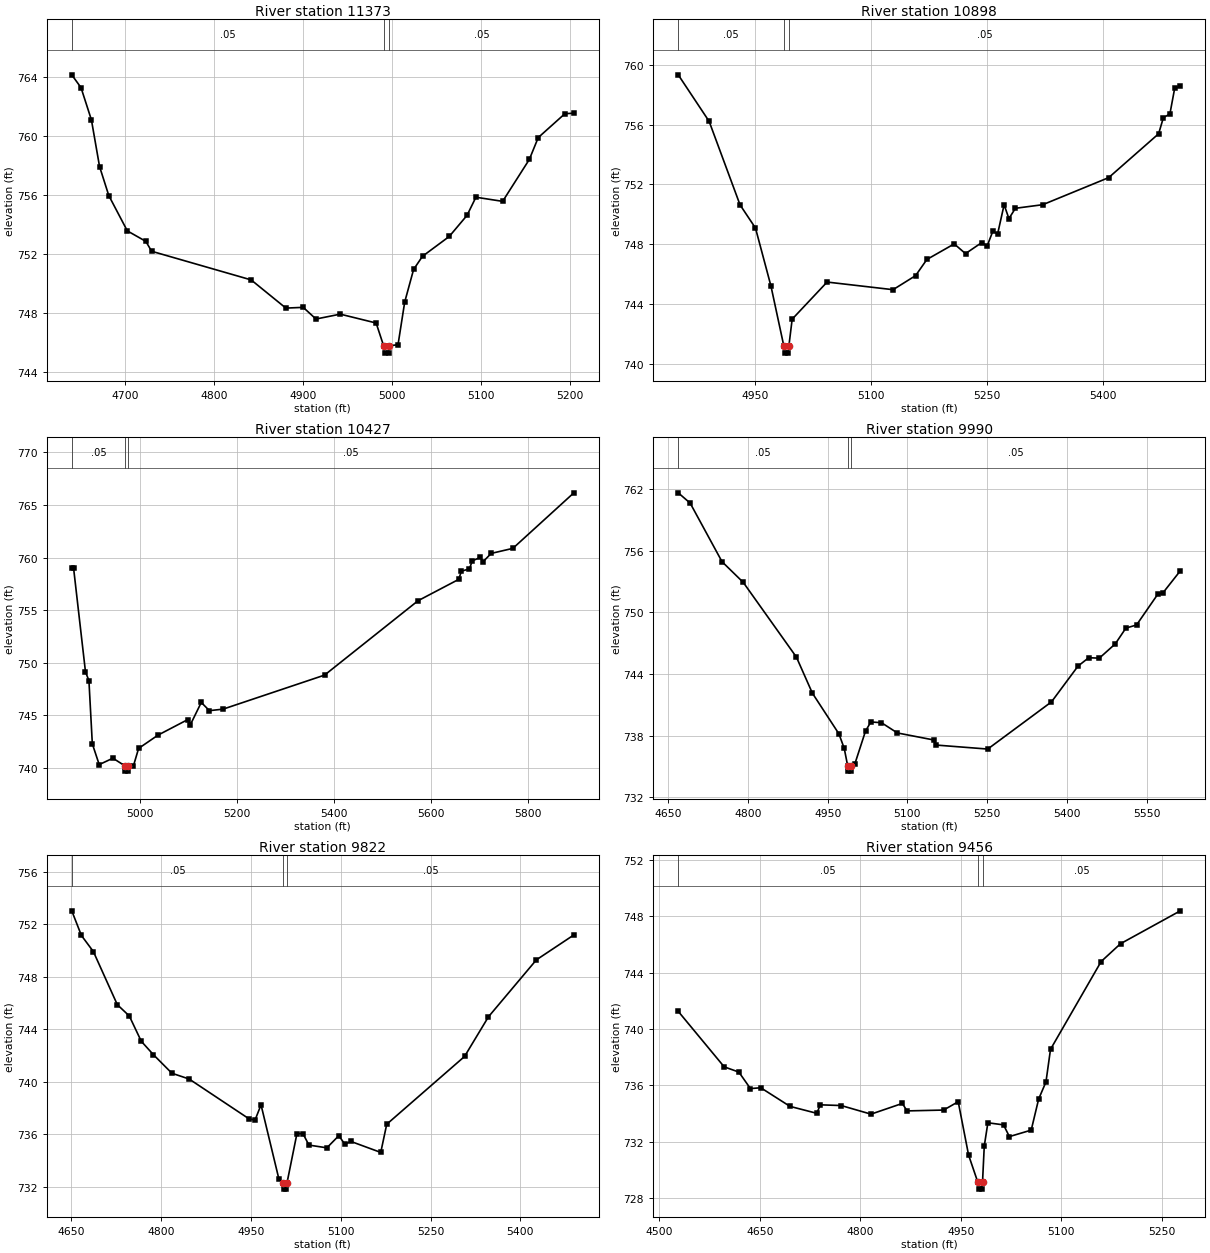
Type RM Length L Ch R = 1,11373,475,475,475
BEGIN DESCRIPTION:
Denton Creek Tributary 31 25.0
END DESCRIPTION:
XS GIS Cut Line= 3
      2318579.02      7131110.01      2318229.00      7131010.00
      2318029.02      7131010.00
#Sta/Elev= 30
  4640.3  764.14  4650.7  763.27  4662.4  761.08  4671.5  757.93  4681.9  755.96
  4702.7  753.57  4723.5  752.86  4730.0  752.19  4841.8  750.25  4880.8  748.34
  4900.3  748.39  4914.6  747.60  4941.9  747.93  4982.2  747.33  4990.6  745.79
  4991.7  745.29  4996.2  745.29  4997.2  745.79  5006.8  745.86  5014.3  748.75
  5024.3  750.96  5034.3  751.85  5064.3  753.19  5084.3  754.62  5094.3  755.85
  5124.3  755.57  5154.3  758.41  5164.3  759.89  5194.3  761.51  5204.3  761.54
#Mann=3,-1,0
  4640.3    0.05       0  4990.6   0.033       0  4997.2    0.05       0
Bank Sta=4990.6,4997.2
Exp/Cntr=0.3,0.1

Type RM Length L Ch R = 1,10898,471,471,471
BEGIN DESCRIPTION:
Denton Creek Tributary 31 24.0
END DESCRIPTION:
XS GIS Cut Line= 3
      2318479.00      7130610.00      2318329.00      7130610.00
      2317929.00      7130910.00
#Sta/Elev= 30
  4850.2  759.32  4890.2  756.21  4930.2  750.63  4950.2  749.08  4970.2  745.21
  4986.8  741.22  4987.9  740.72  4992.5  740.72  4993.5  741.22  4997.7  742.99
  5042.9  745.47  5128.3  744.96  5157.5  745.90  5172.1  746.98  5207.5  748.02
  5222.1  747.37  5242.9  748.10  5250.2  747.89  5257.5  748.87  5263.7  748.69
  5272.1  750.64  5278.3  749.71  5286.7  750.40  5322.1  750.64  5407.5  752.45
  5472.1  755.38  5478.3  756.46  5486.7  756.70  5492.9  758.42  5500.2  758.54
#Mann=3,-1,0
  4850.2    0.05       0  4986.8   0.033       0  4993.5    0.05       0
Bank Sta=4986.8,4993.5
Exp/Cntr=0.3,0.1

Type RM Length L Ch R = 1,10427,437,437,437
BEGIN DESCRIPTION:
Denton Creek Tributary 31 23.0
END DESCRIPTION:
XS GIS Cut Line= 3
      2318279.01      7130209.99      2318179.00      7130310.00
      2317378.97      7130710.01
#Sta/Elev= 30
  4858.7  759.06  4862.3  759.06  4887.0  749.13  4894.1  748.31  4901.1  742.30
  4915.3  740.32  4943.6  740.93  4968.4  740.20  4969.5  739.70  4974.3  739.70
  4975.4  740.20  4986.0  740.21  4996.6  741.86  5036.5  743.12  5098.0  744.60
  5103.6  744.13  5125.9  746.23  5142.7  745.45  5170.6  745.59  5380.3  748.83
  5573.1  755.90  5657.0  757.93  5662.6  758.71  5679.3  758.93  5684.9  759.69
  5701.7  760.02  5707.3  759.61  5724.1  760.40  5768.8  760.88  5894.6  766.16
#Mann=3,-1,0
  4858.7    0.05       0  4968.4   0.033       0  4975.4    0.05       0
Bank Sta=4968.4,4975.4
Exp/Cntr=0.3,0.1

Type RM Length L Ch R = 1,9990,168,168,168
BEGIN DESCRIPTION:
Mapping XS bfe9e37b
END DESCRIPTION:
XS GIS Cut Line= 2
      2318311.38      7129948.82      2317366.61      7129941.35
#Sta/Elev= 30
  4668.7  761.66  4691.1  760.66  4751.1  754.95  4791.1  752.93  4891.1  745.65
  4921.1  742.14  4971.1  738.17  4981.1  736.75  4987.6  735.04  4988.7  734.54
  4993.5  734.54  4994.6  735.04  5001.1  735.25  5021.1  738.44  5031.1  739.33
  5051.1  739.26  5081.1  738.26  5149.1  737.58  5154.1  737.08  5251.1  736.69
  5371.1  741.29  5421.1  744.78  5441.1  745.59  5461.1  745.55  5491.1  746.94
  5511.1  748.48  5531.1  748.78  5571.1  751.78  5581.1  751.93  5613.5  754.06
#Mann=3,-1,0
  4668.7    0.05       0  4987.6   0.033       0  4994.6    0.05       0
Bank Sta=4987.6,4994.6
Exp/Cntr=0.3,0.1

Type RM Length L Ch R = 1,9822,366,366,366
BEGIN DESCRIPTION:
Mapping XS bedccda3
END DESCRIPTION:
XS GIS Cut Line= 2
      2318235.14      7129816.23      2317396.37      7129809.91
#Sta/Elev= 30
  4650.5  753.03  4666.6  751.15  4686.6  749.92  4726.6  745.87  4746.6  745.01
  4766.6  743.08  4786.6  742.07  4817.8  740.64  4846.6  740.20  4946.7  737.16
  4956.7  737.07  4966.7  738.23  4996.7  732.54  5003.2  732.30  5004.3  731.80
  5009.1  731.80  5010.2  732.30  5026.7  736.04  5036.7  736.04  5046.7  735.16
  5076.7  734.95  5096.7  735.88  5106.7  735.22  5116.7  735.44  5166.7  734.60
  5176.7  736.75  5306.7  741.92  5346.7  744.95  5426.7  749.29  5489.3  751.19
#Mann=3,-1,0
  4650.5    0.05       0  5003.2   0.033       0  5010.2    0.05       0
Bank Sta=5003.2,5010.2
Exp/Cntr=0.3,0.1

Type RM Length L Ch R = 1,9456,371,371,371
BEGIN DESCRIPTION:
Mapping XS 4fcfa2e2
END DESCRIPTION:
XS GIS Cut Line= 2
      2318131.85      7129341.34      2317445.30      7129642.23
#Sta/Elev= 30
  4528.2  741.25  4596.8  737.32  4618.7  736.95  4636.0  735.78  4651.4  735.84
  4695.1  734.52  4735.0  734.03  4740.4  734.63  4771.5  734.58  4816.0  733.97
  4862.8  734.73  4869.8  734.20  4924.4  734.26  4946.2  734.85  4961.7  731.07
  4975.4  729.16  4976.5  728.66  4981.4  728.66  4982.5  729.16  4985.1  731.71
  4990.5  733.36  5013.9  733.21  5022.6  732.38  5055.2  732.84  5066.3  735.04
  5077.2  736.25  5084.0  738.56  5159.6  744.78  5188.5  746.04  5277.8  748.37
#Mann=3,-1,0
  4528.2    0.05       0  4975.4   0.033       0  4982.5    0.05       0
Bank Sta=4975.4,4982.5
Exp/Cntr=0.3,0.1