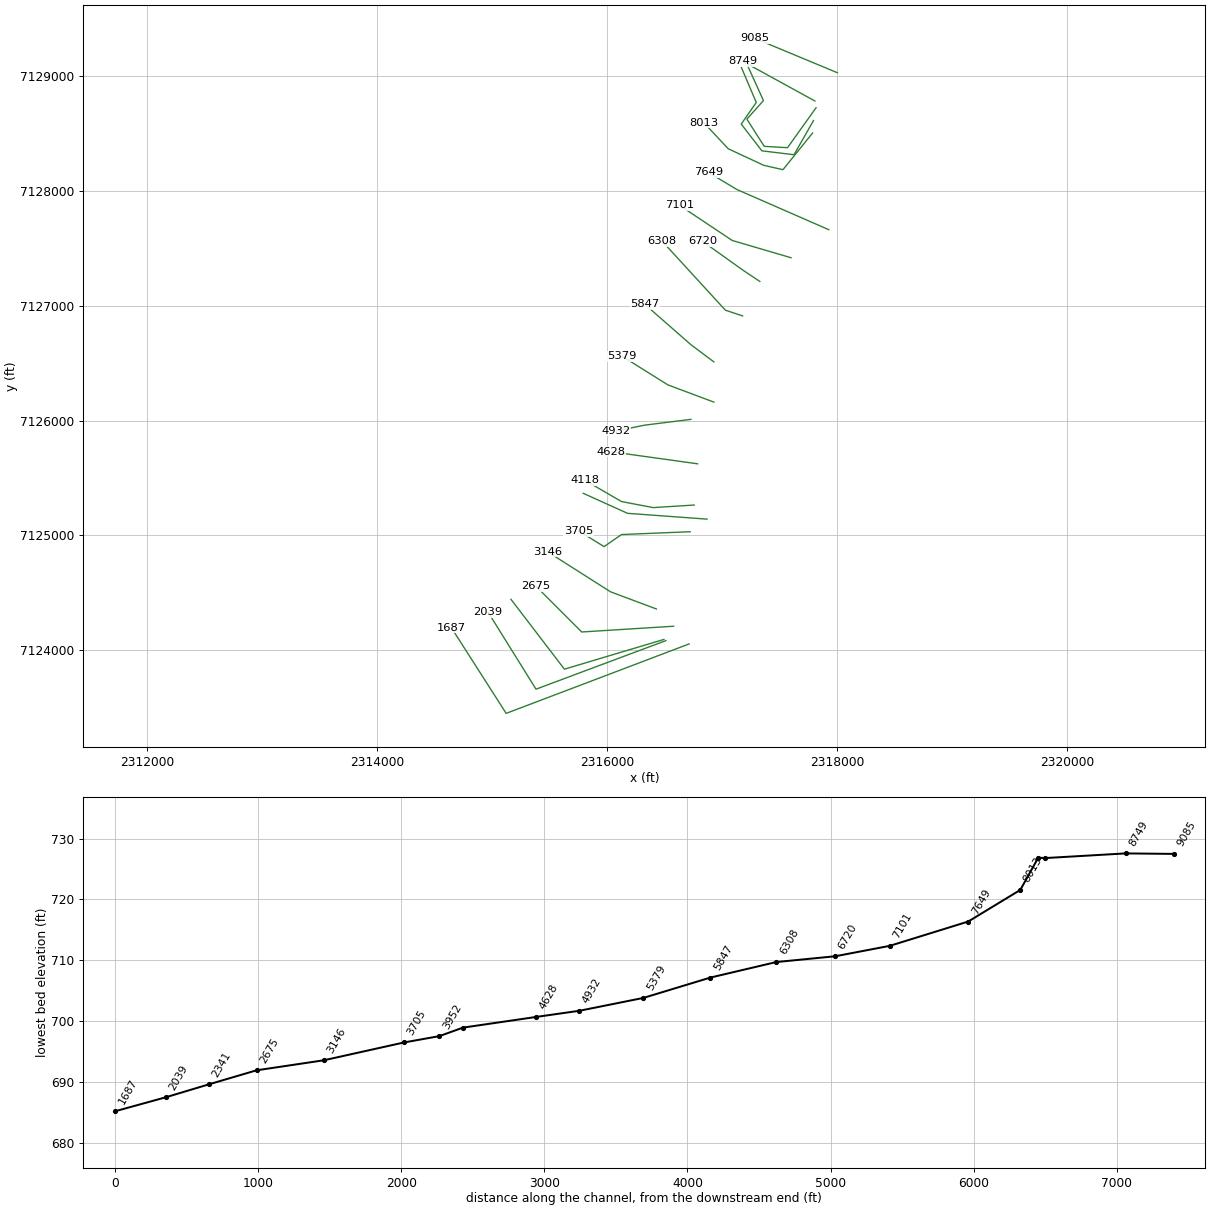
HEC-RAS study Denton Creek Tributary 31.prj: Denton Creek Tributary 31 Base Level Engineering

--- Denton Creek Tributary 31.g01 (geometry) --- (continued)

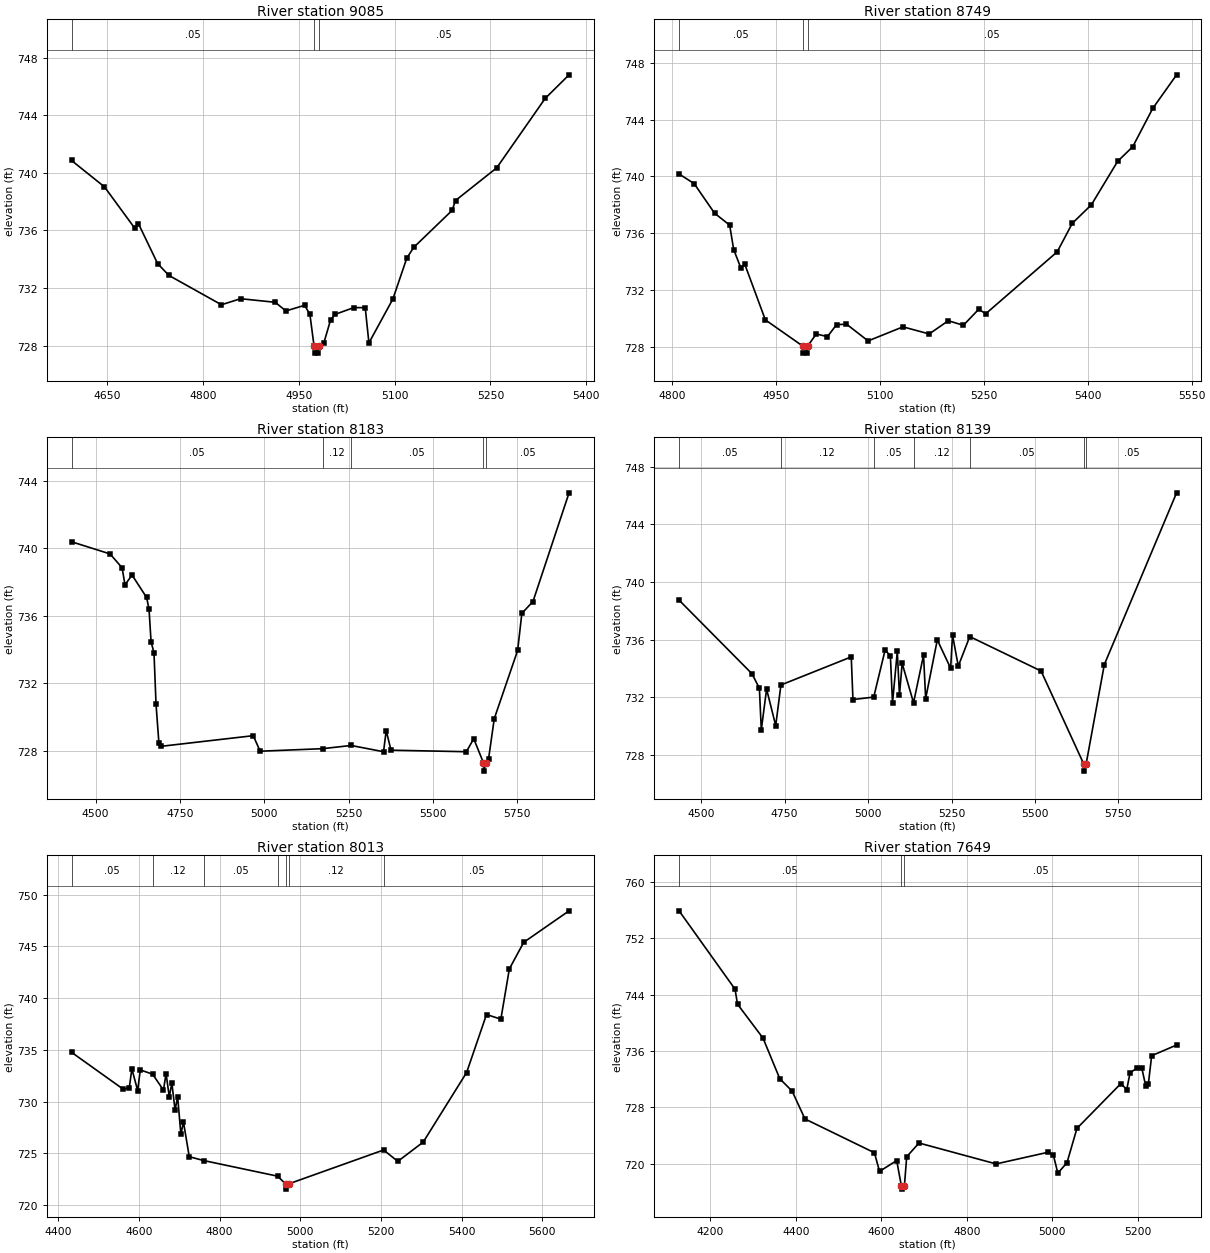
Type RM Length L Ch R = 1,9085,336,336,336
BEGIN DESCRIPTION:
Mapping XS 7eead419
END DESCRIPTION:
XS GIS Cut Line= 2
      2318003.32      7129025.96      2317284.51      7129325.19
#Sta/Elev= 30
  4594.5  740.86  4646.0  739.03  4693.7  736.14  4699.1  736.48  4729.2  733.70
  4746.8  732.88  4829.1  730.84  4859.1  731.26  4913.3  731.01  4929.9  730.41
  4959.2  730.80  4967.5  730.18  4974.0  727.98  4975.1  727.48  4980.1  727.48
  4981.2  727.98  4989.1  728.15  5000.0  729.80  5006.8  730.17  5036.1  730.64
  5054.1  730.64  5059.9  728.19  5097.4  731.24  5119.1  734.07  5129.9  734.82
  5190.0  737.39  5195.4  738.08  5259.9  740.35  5335.7  745.17  5373.1  746.81
#Mann=3,-1,0
  4594.5    0.05       0  4974.0   0.033       0  4981.2    0.05       0
Bank Sta=4974,4981.2
Exp/Cntr=0.3,0.1

Type RM Length L Ch R = 1,8749,566,566,566
BEGIN DESCRIPTION:
Mapping XS 6652942d
END DESCRIPTION:
XS GIS Cut Line= 2
      2317808.09      7128779.93      2317178.79      7129125.63
#Sta/Elev= 30
  4810.3  740.17  4832.1  739.49  4861.5  737.41  4883.3  736.57  4889.1  734.85
  4899.4  733.56  4905.1  733.82  4934.8  729.90  4988.7  728.06  4989.8  727.56
  4994.8  727.56  4995.9  728.06  5008.3  728.91  5024.4  728.72  5037.5  729.56
  5051.9  729.60  5083.1  728.42  5133.4  729.41  5171.3  728.91  5198.8  729.84
  5220.6  729.52  5242.8  730.65  5252.8  730.33  5356.0  734.69  5377.8  736.70
  5405.3  738.00  5443.2  741.06  5465.0  742.09  5493.8  744.78  5528.3  747.15
#Mann=3,-1,0
  4810.3    0.05       0  4988.7   0.033       0  4995.9    0.05       0
Bank Sta=4988.7,4995.9
Exp/Cntr=0.3,0.1

Type RM Length L Ch R = 1,8183,44,44,44
BEGIN DESCRIPTION:
Mapping XS 09f85ae7
END DESCRIPTION:
XS GIS Cut Line= 6
      2317818.15      7128721.14      2317569.81      7128373.64
      2317367.04      7128385.46      2317216.02      7128622.11
      2317360.36      7128783.47      2317222.76      7129087.51
#Sta/Elev= 30
  4428.5  740.38  4542.7  739.66  4578.4  738.84  4587.0  737.83  4607.9  738.41
  4651.1  737.08  4658.3  736.39  4664.4  734.44  4673.0  733.81  4679.1  730.74
  4687.7  728.43  4693.9  728.26  4967.3  728.89  4987.9  727.97  5172.8  728.12
  5257.7  728.31  5353.8  727.94  5361.7  729.19  5375.9  728.03  5599.4  727.94
  5621.3  728.71  5650.0  727.29  5651.1  726.79  5657.3  727.29  5665.3  727.52
  5682.2  729.90  5751.5  733.94  5764.0  736.14  5797.0  736.84  5904.0  743.28
#Mann=5,-1,0
  4428.5    0.05       0  5172.8    0.12       0  5257.7    0.05       0
  5650.0   0.033       0  5657.3    0.05       0
Bank Sta=5650,5657.3
Exp/Cntr=0.3,0.1

Type RM Length L Ch R = 1,8139,126,126,126
BEGIN DESCRIPTION:
Mapping XS e4df14fa
END DESCRIPTION:
XS GIS Cut Line= 6
      2317795.71      7128609.63      2317626.14      7128312.58
      2317346.66      7128346.44      2317166.93      7128579.04
      2317297.79      7128767.57      2317168.21      7129071.90
#Sta/Elev= 30
  4433.8  738.74  4652.2  733.63  4674.4  732.62  4680.1  729.74  4696.0  732.56
  4723.3  730.03  4738.9  732.85  4949.6  734.80  4954.7  731.84  5016.9  732.01
  5050.9  735.26  5066.8  734.89  5073.2  731.61  5087.6  735.18  5094.0  732.14
  5102.1  734.35  5136.2  731.62  5166.2  734.92  5172.5  731.91  5207.4  735.98
  5247.4  734.01  5253.0  736.32  5270.2  734.16  5304.7  736.21  5518.3  733.82
  5646.0  727.37  5647.2  726.87  5653.3  727.37  5707.8  734.27  5924.3  746.19
#Mann=7,-1,0
  4433.8    0.05       0  4738.9    0.12       0  5016.9    0.05       0
  5136.2    0.12       0  5304.7    0.05       0  5646.0    0.07       0
  5653.3    0.05       0
Bank Sta=5646,5653.3
Exp/Cntr=0.3,0.1

Type RM Length L Ch R = 1,8013,364,364,364
BEGIN DESCRIPTION:
Mapping XS 81e77b4c
END DESCRIPTION:
XS GIS Cut Line= 5
      2317787.98      7128501.43      2317530.09      7128182.41
      2317363.54      7128220.13      2317054.07      7128364.35
      2316841.18      7128591.32
#Sta/Elev= 30
  4433.0  734.77  4561.8  731.19  4576.2  731.37  4582.6  733.17  4597.0  731.07
  4603.4  733.07  4634.0  732.66  4660.9  731.12  4667.4  732.72  4675.3  730.48
  4681.8  731.80  4689.7  729.18  4696.1  730.48  4704.1  726.85  4710.5  728.04
  4724.9  724.69  4760.5  724.32  4944.0  722.81  4963.7  722.06  4964.9  721.56
  4971.0  722.06  5206.8  725.34  5241.9  724.24  5305.0  726.10  5412.6  732.82
  5461.9  738.42  5497.5  737.97  5518.6  742.83  5554.2  745.39  5666.6  748.43
#Mann=7,-1,0
  4433.0    0.05       0  4634.0    0.12       0  4760.5    0.05       0
  4944.0    0.12       0  4963.7    0.07       0  4971.0    0.12       0
  5206.8    0.05       0
Bank Sta=4963.7,4971
Exp/Cntr=0.3,0.1

Type RM Length L Ch R = 1,7649,548,548,548
BEGIN DESCRIPTION:
Denton Creek Tributary 31 17.0
END DESCRIPTION:
XS GIS Cut Line= 3
      2317929.00      7127660.00      2317129.00      7128010.00
      2316878.96      7128160.02
#Sta/Elev= 30
  4126.6  755.90  4257.6  744.77  4263.4  742.64  4323.1  737.82  4362.4  732.05
  4391.3  730.29  4421.3  726.34  4583.9  721.54  4595.9  718.89  4636.1  720.43
  4646.9  716.87  4648.0  716.37  4654.2  716.87  4659.5  720.97  4688.3  722.92
  4868.8  719.95  4990.8  721.61  5002.7  721.24  5013.4  718.64  5034.8  720.13
  5058.1  725.00  5161.1  731.37  5174.7  730.51  5182.5  732.91  5198.1  733.53
  5209.7  733.63  5219.4  730.95  5225.3  731.31  5233.0  735.32  5291.4  736.84
#Mann=3,-1,0
  4126.6    0.05       0  4646.9   0.033       0  4654.2    0.05       0
Bank Sta=4646.9,4654.2
Exp/Cntr=0.3,0.1

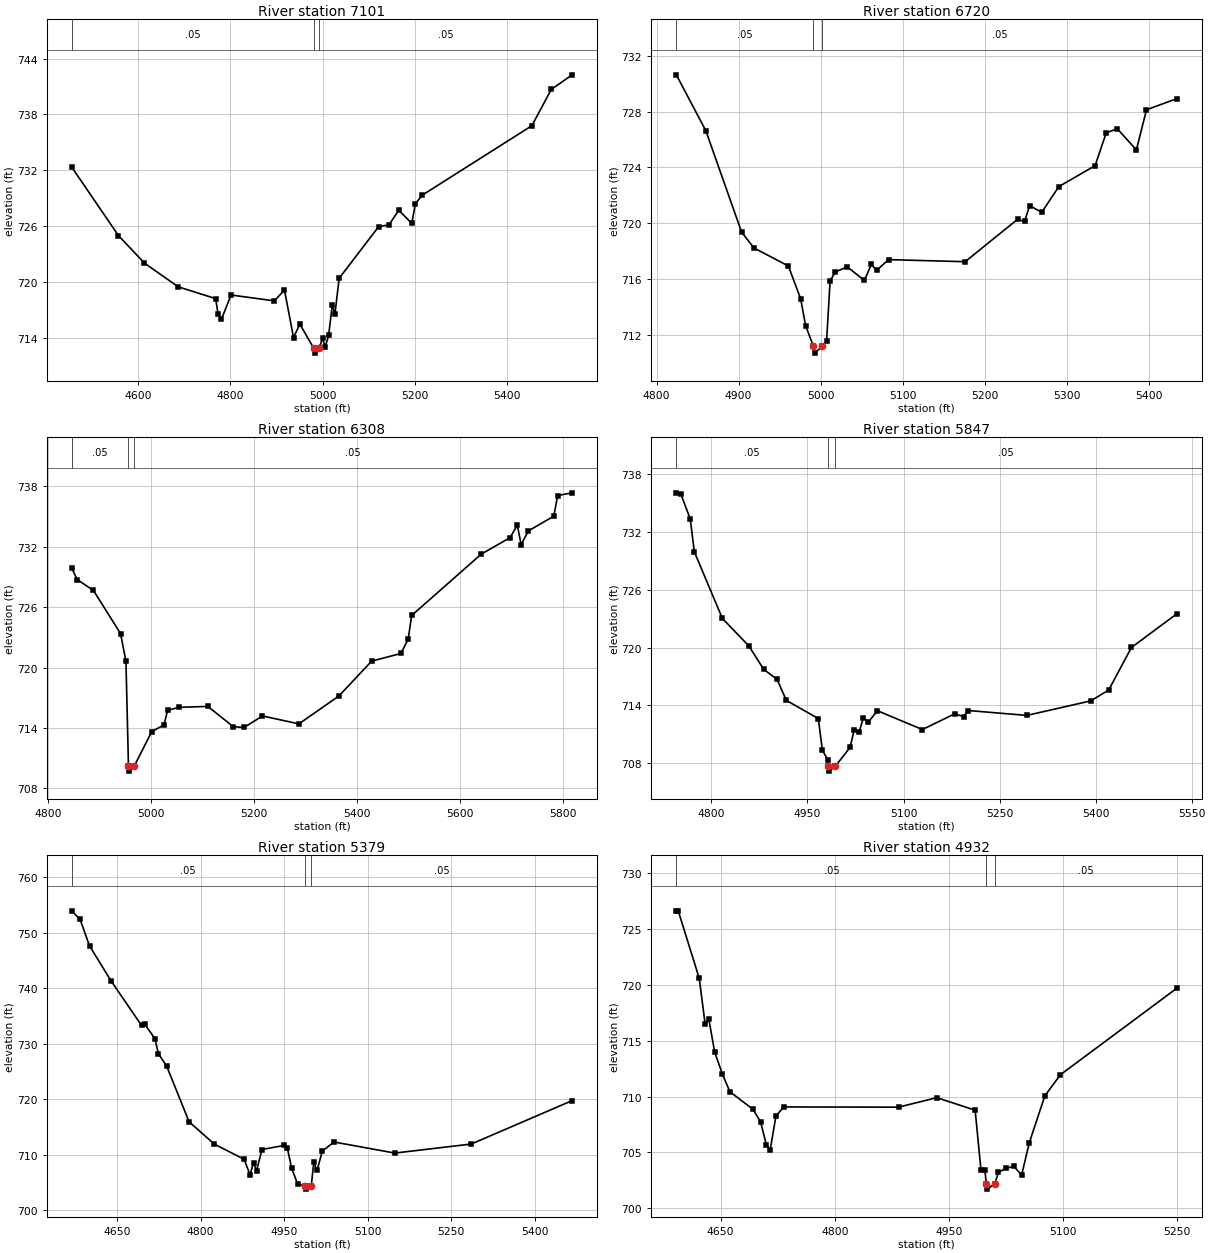
Type RM Length L Ch R = 1,7101,381,381,381
BEGIN DESCRIPTION:
Mapping XS 03504f9f
END DESCRIPTION:
XS GIS Cut Line= 3
      2317600.44      7127416.27      2317089.32      7127566.21
      2316629.70      7127872.18
#Sta/Elev= 30
  4455.9  732.35  4557.2  725.00  4613.7  722.04  4686.7  719.50  4768.0  718.23
  4773.2  716.58  4780.5  716.00  4801.3  718.62  4895.1  717.99  4917.2  719.15
  4936.8  714.05  4950.6  715.49  4980.9  712.88  4982.4  712.38  4992.0  712.88
  4999.7  713.96  5005.7  713.08  5013.0  714.30  5020.7  717.53  5026.7  716.62
  5035.7  720.41  5121.1  725.94  5143.9  726.15  5165.0  727.73  5193.2  726.30
  5201.0  728.43  5216.1  729.34  5453.5  736.79  5495.6  740.68  5540.7  742.25
#Mann=3,-1,0
  4455.9    0.05       0  4980.9   0.033       0  4992.0    0.05       0
Bank Sta=4980.9,4992
Exp/Cntr=0.3,0.1

Type RM Length L Ch R = 1,6720,412,412,412
BEGIN DESCRIPTION:
Denton Creek Tributary 31 15.0
END DESCRIPTION:
XS GIS Cut Line= 3
      2317328.99      7127210.01      2317179.00      7127310.00
      2316828.98      7127560.01
#Sta/Elev= 30
  4824.0  730.64  4860.0  726.63  4903.6  719.36  4918.6  718.22  4960.7  716.92
  4975.7  714.56  4981.7  712.64  4991.2  711.17  4992.7  710.67  5002.3  711.17
  5007.3  711.54  5011.6  715.85  5017.8  716.49  5032.5  716.86  5053.4  715.89
  5062.0  717.05  5068.2  716.60  5082.9  717.38  5176.3  717.23  5240.2  720.27
  5248.8  720.12  5255.0  721.26  5269.7  720.77  5290.6  722.62  5334.8  724.12
  5348.4  726.48  5361.9  726.77  5385.2  725.25  5397.5  728.13  5434.4  728.93
#Mann=3,-1,0
  4824.0    0.05       0  4991.2   0.033       0  5002.3    0.05       0
Bank Sta=4991.2,5002.3
Exp/Cntr=0.3,0.1

Type RM Length L Ch R = 1,6308,461,461,461
BEGIN DESCRIPTION:
Denton Creek Tributary 31 14.0
END DESCRIPTION:
XS GIS Cut Line= 3
      2317179.02      7126909.99      2317029.00      7126960.00
      2316478.99      7127560.02
#Sta/Elev= 30
  4846.4  729.89  4857.0  728.73  4888.6  727.65  4941.3  723.37  4951.8  720.62
  4956.7  710.22  4958.3  709.72  4968.0  710.22  5001.9  713.64  5025.8  714.31
  5032.6  715.74  5054.2  716.05  5110.9  716.14  5160.2  714.13  5181.2  714.05
  5217.0  715.19  5287.9  714.41  5365.6  717.18  5429.1  720.63  5485.8  721.39
  5500.0  722.79  5506.8  725.16  5641.8  731.24  5697.9  732.88  5712.1  734.11
  5719.5  732.19  5733.7  733.56  5783.0  735.01  5790.4  737.06  5818.5  737.33
#Mann=3,-1,0
  4846.4    0.05       0  4956.7   0.033       0  4968.0    0.05       0
Bank Sta=4956.7,4968
Exp/Cntr=0.3,0.1

Type RM Length L Ch R = 1,5847,468,468,468
BEGIN DESCRIPTION:
Denton Creek Tributary 31 13.0
END DESCRIPTION:
XS GIS Cut Line= 3
      2316928.97      7126510.02      2316729.00      7126660.00
      2316328.98      7127010.02
#Sta/Elev= 30
  4745.2  736.09  4752.5  735.92  4767.0  733.36  4773.3  729.97  4817.0  723.05
  4858.7  720.16  4881.6  717.75  4902.5  716.71  4917.0  714.52  4967.0  712.63
  4973.3  709.34  4981.6  708.37  4982.2  707.67  4983.8  707.17  4993.5  707.67
  5016.5  709.63  5023.2  711.49  5030.8  711.26  5037.4  712.72  5045.0  712.25
  5059.2  713.45  5129.5  711.49  5179.8  713.12  5194.0  712.84  5200.6  713.47
  5292.7  712.96  5392.4  714.47  5420.4  715.59  5456.0  720.02  5526.7  723.51
#Mann=3,-1,0
  4745.2    0.05       0  4982.2   0.033       0  4993.5    0.05       0
Bank Sta=4982.2,4993.5
Exp/Cntr=0.3,0.1

Type RM Length L Ch R = 1,5379,447,447,447
BEGIN DESCRIPTION:
Denton Creek Tributary 31 12.0
END DESCRIPTION:
XS GIS Cut Line= 3
      2316929.01      7126160.00      2316529.00      7126310.00
      2316129.01      7126560.00
#Sta/Elev= 30
  4568.4  753.93  4583.5  752.38  4600.4  747.63  4638.7  741.38  4693.9  733.29
  4699.2  733.57  4717.9  730.92  4724.2  728.21  4739.3  725.91  4779.3  715.95
  4824.7  711.93  4878.1  709.21  4888.8  706.40  4895.0  708.62  4900.4  707.11
  4910.2  710.96  4950.2  711.70  4955.6  711.27  4963.6  707.56  4974.2  704.78
  4987.3  704.33  4988.8  703.83  4998.6  704.33  5003.3  708.64  5009.2  707.20
  5018.6  710.68  5039.8  712.31  5148.9  710.32  5286.3  711.95  5467.3  719.76
#Mann=3,-1,0
  4568.4    0.05       0  4987.3   0.033       0  4998.6    0.05       0
Bank Sta=4987.3,4998.6
Exp/Cntr=0.3,0.1

Type RM Length L Ch R = 1,4932,304,304,304
BEGIN DESCRIPTION:
Denton Creek Tributary 31 11.0
END DESCRIPTION:
XS GIS Cut Line= 3
      2316728.99      7126010.00      2316329.00      7125960.00
      2316078.96      7125909.99
#Sta/Elev= 30
  4591.7  726.61  4594.2  726.61  4621.9  720.56  4629.5  716.53  4634.5  716.90
  4642.1  713.99  4652.2  712.02  4662.2  710.43  4692.5  708.86  4702.5  707.74
  4710.1  705.69  4715.1  705.21  4722.7  708.25  4732.8  709.07  4883.9  709.05
  4934.3  709.90  4984.7  708.78  4992.3  703.46  4997.4  703.46  4999.4  702.22
  5000.9  701.72  5010.7  702.22  5015.2  703.22  5025.4  703.58  5035.6  703.76
  5045.8  702.97  5056.0  705.89  5076.4  710.07  5096.8  711.95  5249.8  719.68
#Mann=3,-1,0
  4591.7    0.05       0  4999.4   0.033       0  5010.7    0.05       0
Bank Sta=4999.4,5010.7
Exp/Cntr=0.3,0.1

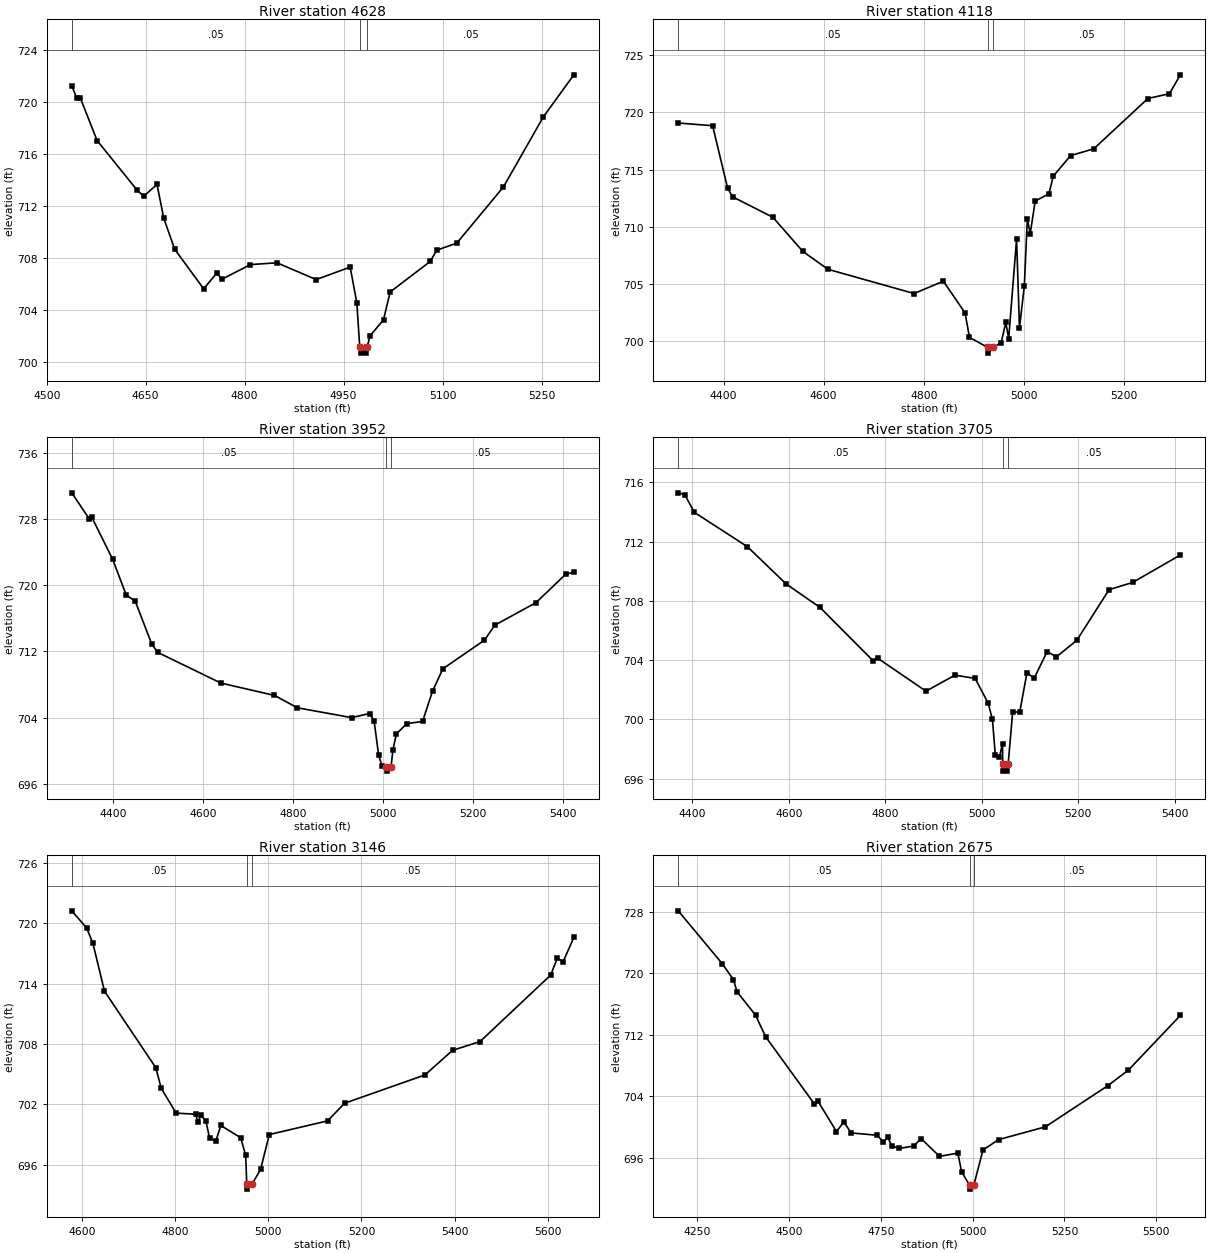
Type RM Length L Ch R = 1,4628,510,510,510
BEGIN DESCRIPTION:
Mapping XS f382d586
END DESCRIPTION:
XS GIS Cut Line= 2
      2316786.99      7125623.28      2316033.28      7125728.35
#Sta/Elev= 30
  4538.0  721.25  4545.7  720.27  4550.8  720.32  4576.4  717.03  4636.9  713.23
  4647.0  712.75  4667.2  713.66  4677.3  711.09  4693.9  708.69  4737.9  705.64
  4758.1  706.87  4765.4  706.37  4808.6  707.50  4849.0  707.64  4908.5  706.35
  4960.0  707.31  4970.1  704.55  4974.4  701.20  4976.0  700.70  4984.2  700.70
  4985.7  701.20  4990.3  702.04  5010.5  703.26  5020.6  705.40  5081.2  707.74
  5091.3  708.61  5121.6  709.15  5192.3  713.47  5252.8  718.85  5299.0  722.08
#Mann=3,-1,0
  4538.0    0.05       0  4974.4   0.033       0  4985.7    0.05       0
Bank Sta=4974.4,4985.7
Exp/Cntr=0.3,0.1

Type RM Length L Ch R = 1,4118,166,166,166
BEGIN DESCRIPTION:
Mapping XS 321c7c0d
END DESCRIPTION:
XS GIS Cut Line= 4
      2316757.61      7125264.56      2316401.20      7125242.25
      2316125.93      7125294.61      2315809.38      7125478.30
#Sta/Elev= 30
  4309.5  719.07  4378.2  718.83  4408.3  713.35  4418.3  712.61  4498.5  710.83
  4558.6  707.84  4608.7  706.28  4780.8  704.16  4839.3  705.24  4882.6  702.47
  4891.5  700.33  4927.9  699.45  4929.4  698.95  4939.2  699.45  4954.8  699.87
  4964.1  701.63  4969.8  700.21  4985.6  708.91  4991.4  701.17  5001.1  704.83
  5007.1  710.70  5012.9  709.40  5022.8  712.24  5050.2  712.88  5058.9  714.42
  5093.6  716.22  5139.8  716.81  5248.1  721.21  5291.1  721.63  5312.8  723.28
#Mann=3,-1,0
  4309.5    0.05       0  4927.9    0.04       0  4939.2    0.05       0
Bank Sta=4927.9,4939.2
Exp/Cntr=0.3,0.1

Type RM Length L Ch R = 1,3952,247,247,247
BEGIN DESCRIPTION:
Mapping XS cfc3c1b9
END DESCRIPTION:
XS GIS Cut Line= 3
      2316869.74      7125141.91      2316177.99      7125192.40
      2315792.32      7125366.65
#Sta/Elev= 30
  4307.7  731.14  4346.9  727.97  4351.9  728.23  4398.7  723.11  4428.8  718.81
  4448.8  718.07  4485.7  712.87  4499.0  711.88  4639.3  708.18  4758.5  706.69
  4809.8  705.19  4930.1  704.01  4970.2  704.50  4980.2  703.63  4990.3  699.46
  4998.3  698.11  5006.4  698.05  5008.0  697.55  5017.8  698.05  5022.1  700.14
  5029.8  702.05  5052.9  703.28  5088.0  703.55  5110.1  707.19  5133.2  709.90
  5225.7  713.36  5248.8  715.17  5340.4  717.89  5406.2  721.31  5424.5  721.57
#Mann=3,-1,0
  4307.7    0.05       0  5006.4    0.04       0  5017.8    0.05       0
Bank Sta=5006.4,5017.8
Exp/Cntr=0.3,0.1

Type RM Length L Ch R = 1,3705,559,559,559
BEGIN DESCRIPTION:
Mapping XS 3ac4e0be
END DESCRIPTION:
XS GIS Cut Line= 4
      2316722.52      7125032.26      2316125.66      7125007.99
      2315973.49      7124902.73      2315753.34      7125039.21
#Sta/Elev= 30
  4370.5  715.30  4384.0  715.18  4404.0  713.98  4514.1  711.66  4594.2  709.15
  4664.3  707.57  4774.4  703.97  4784.4  704.13  4884.4  701.91  4944.5  702.99
  4986.4  702.77  5013.4  701.09  5022.2  700.00  5028.3  697.57  5036.7  697.44
  5043.1  698.37  5043.5  697.01  5045.1  696.51  5053.3  696.51  5054.9  697.01
  5064.1  700.48  5078.9  700.51  5093.8  703.15  5108.7  702.78  5135.7  704.58
  5155.0  704.23  5197.2  705.34  5264.1  708.76  5313.0  709.25  5411.9  711.10
#Mann=3,-1,0
  4370.5    0.05       0  5043.5    0.04       0  5054.9    0.05       0
Bank Sta=5043.5,5054.9
Exp/Cntr=0.3,0.1

Type RM Length L Ch R = 1,3146,471,471,471
BEGIN DESCRIPTION:
Denton Creek Tributary 31 7.0
END DESCRIPTION:
XS GIS Cut Line= 3
      2316428.98      7124360.01      2316029.00      7124510.00
      2315479.00      7124860.00
#Sta/Elev= 30
  4577.4  721.23  4609.4  719.53  4622.8  718.01  4647.7  713.25  4758.0  705.65
  4769.6  703.61  4801.7  701.14  4843.5  701.03  4848.8  700.25  4855.1  700.93
  4865.7  700.35  4873.7  698.63  4887.1  698.37  4897.8  699.91  4940.5  698.69
  4951.2  696.93  4953.5  694.09  4955.0  693.59  4964.9  694.09  4983.2  695.54
  5001.9  699.01  5127.3  700.37  5163.7  702.12  5336.5  704.93  5395.7  707.37
  5455.0  708.25  5606.5  714.84  5620.9  716.50  5633.6  716.19  5656.5  718.59
#Mann=3,-1,0
  4577.4    0.05       0  4953.5    0.04       0  4964.9    0.05       0
Bank Sta=4953.5,4964.9
Exp/Cntr=0.3,0.1

Type RM Length L Ch R = 1,2675,334,334,334
BEGIN DESCRIPTION:
Denton Creek Tributary 31 6.0
END DESCRIPTION:
XS GIS Cut Line= 3
      2316579.00      7124210.00      2315779.00      7124160.00
      2315379.03      7124559.97
#Sta/Elev= 30
  4198.4  728.14  4318.6  721.24  4348.7  719.19  4358.7  717.59  4408.8  714.58
  4436.4  711.76  4569.1  703.02  4579.1  703.37  4629.2  699.43  4649.3  700.68
  4669.3  699.25  4739.5  698.95  4757.0  698.09  4769.5  698.67  4779.5  697.58
  4799.6  697.23  4839.7  697.54  4859.7  698.52  4909.8  696.20  4959.9  696.63
  4969.9  694.22  4991.7  692.44  4993.3  691.94  5003.2  692.44  5028.2  697.03
  5070.7  698.38  5198.0  700.04  5367.7  705.38  5424.2  707.42  5565.6  714.53
#Mann=3,-1,0
  4198.4    0.05       0  4991.7    0.04       0  5003.2    0.05       0
Bank Sta=4991.7,5003.2
Exp/Cntr=0.3,0.1

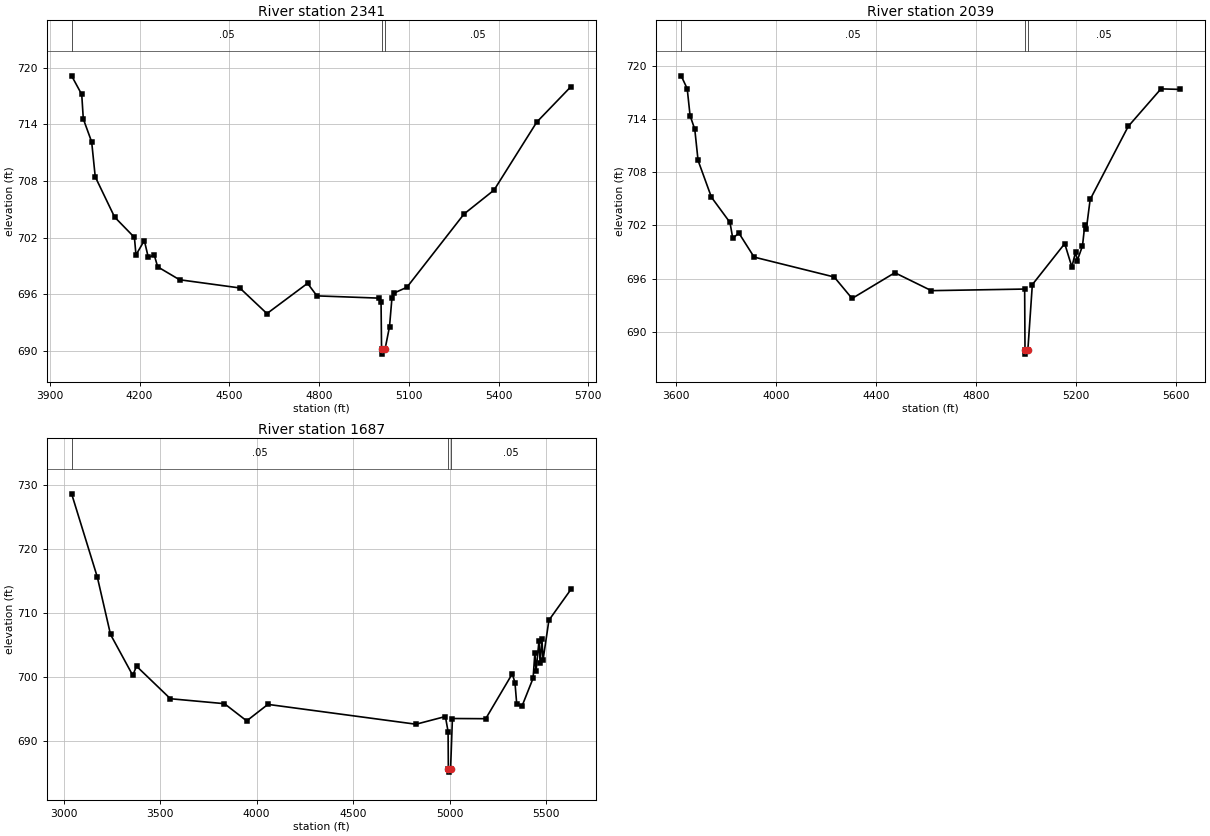
Type RM Length L Ch R = 1,2341,302,302,302
BEGIN DESCRIPTION:
Mapping XS a9b87e4b
END DESCRIPTION:
XS GIS Cut Line= 3
      2316494.61      7124095.22      2315628.45      7123836.52
      2315163.68      7124444.06
#Sta/Elev= 30
  3973.0  719.15  4006.8  717.17  4012.0  714.58  4040.0  712.14  4051.9  708.44
  4116.6  704.17  4182.9  702.01  4188.1  700.15  4216.0  701.68  4229.3  699.89
  4249.1  700.15  4260.6  698.89  4333.7  697.52  4535.0  696.65  4625.9  693.93
  4761.6  697.14  4792.9  695.81  5000.2  695.57  5007.3  695.16  5009.0  690.13
  5010.6  689.63  5020.5  690.13  5035.6  692.55  5043.8  695.62  5050.1  696.10
  5093.7  696.72  5284.9  704.50  5385.0  707.03  5528.0  714.25  5641.9  718.00
#Mann=3,-1,0
  3973.0    0.05       0  5009.0    0.04       0  5020.5    0.05       0
Bank Sta=5009,5020.5
Exp/Cntr=0.3,0.1

Type RM Length L Ch R = 1,2039,352,352,352
BEGIN DESCRIPTION:
Mapping XS 95d8eb04
END DESCRIPTION:
XS GIS Cut Line= 3
      2316512.23      7124085.03      2315381.43      7123662.43
      2314963.87      7124332.96
#Sta/Elev= 30
  3620.8  718.85  3644.9  717.40  3656.3  714.38  3675.2  712.82  3688.3  709.32
  3741.7  705.18  3816.0  702.33  3827.1  700.54  3851.6  701.14  3912.5  698.43
  4232.8  696.19  4304.3  693.77  4475.4  696.67  4621.5  694.65  4994.7  694.83
  4996.1  688.00  4997.7  687.50  5007.6  688.00  5025.4  695.33  5155.0  699.95
  5183.5  697.32  5198.8  699.06  5204.7  698.02  5226.0  699.68  5235.4  702.10
  5241.3  701.56  5256.7  704.92  5408.9  713.15  5539.9  717.38  5617.9  717.32
#Mann=3,-1,0
  3620.8    0.05       0  4996.1    0.04       0  5007.6    0.05       0
Bank Sta=4996.1,5007.6
Exp/Cntr=0.3,0.1

Type RM Length L Ch R = 1,1687,0,0,0
BEGIN DESCRIPTION:
Denton Creek Tributary 31 5.0
END DESCRIPTION:
XS GIS Cut Line= 3
      2316713.43      7124056.05      2315121.69      7123451.84
      2314645.91      7124195.87
#Sta/Elev= 30
  3041.6  728.56  3174.7  715.59  3243.0  706.66  3358.2  700.29  3377.6  701.72
  3553.1  696.65  3833.0  695.88  3948.2  693.20  4058.1  695.77  4825.1  692.68
  4977.3  693.88  4991.2  691.54  4992.7  685.72  4994.3  685.22  5004.2  685.72
  5013.7  693.57  5186.2  693.54  5323.6  700.53  5337.6  699.17  5346.9  695.79
  5374.0  695.49  5431.5  699.84  5440.8  703.80  5446.7  700.96  5461.9  705.63
  5467.9  702.23  5477.2  705.96  5483.1  702.72  5513.5  708.88  5627.3  713.67
#Mann=3,-1,0
  3041.6    0.05       0  4992.7    0.04       0  5004.2    0.05       0
Bank Sta=4992.7,5004.2
Exp/Cntr=0.3,0.1

Chan Stop Cuts=-1