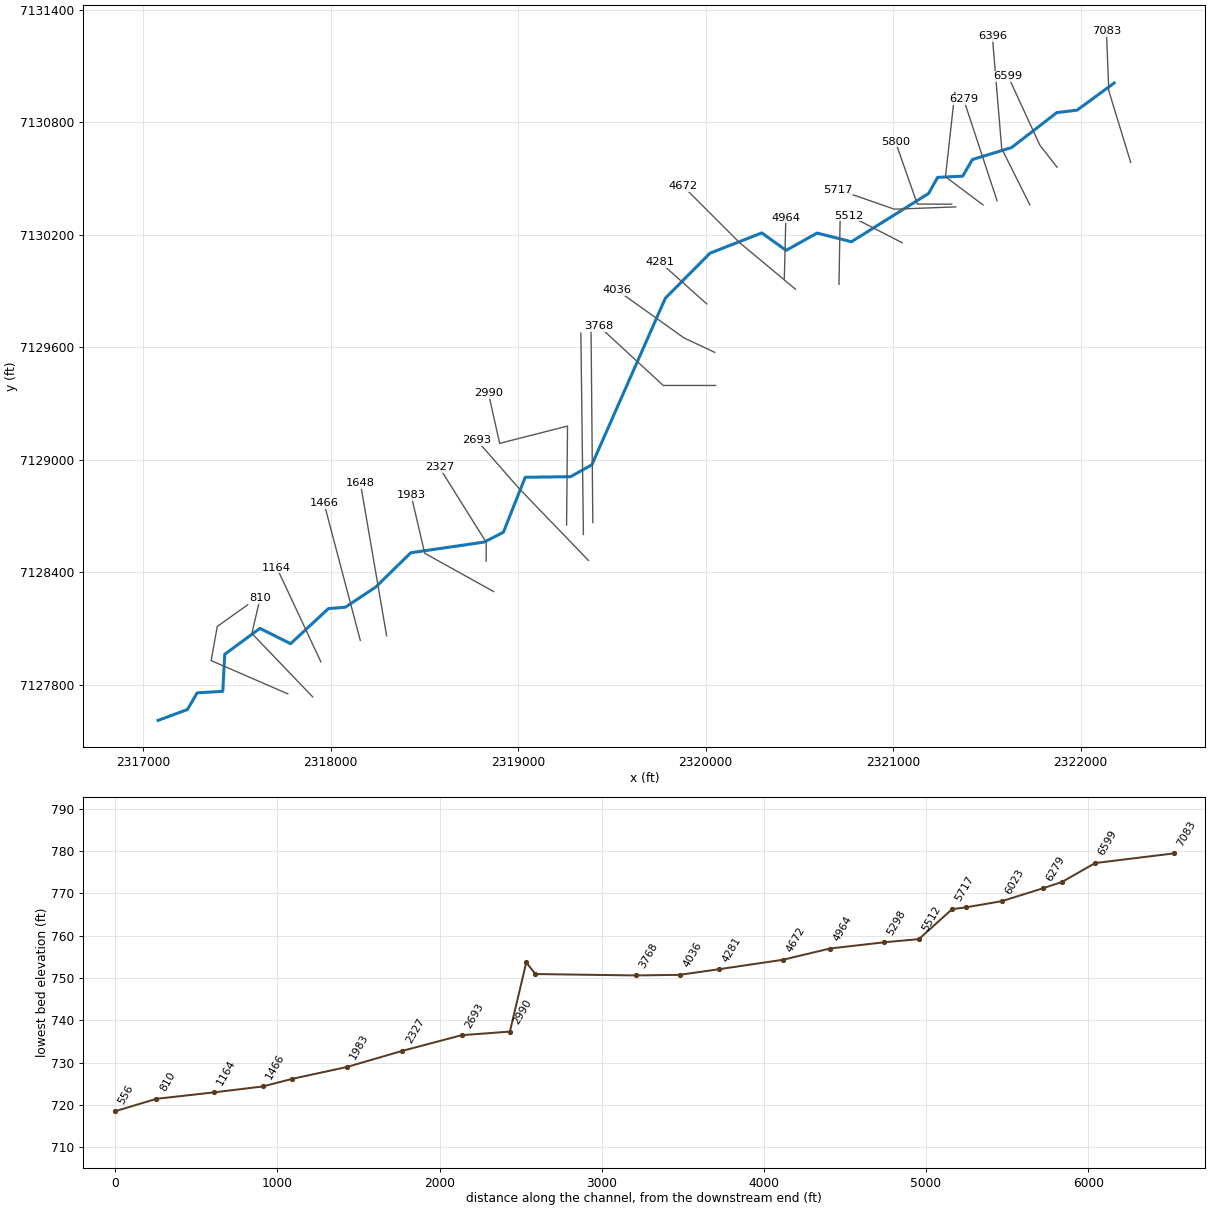
--- Denton Creek Tributary 31_1.prj (project) ---

Proj Title=Denton Creek Tributary 31_1 Base Level Engineering
Current Plan=p01
Default Exp/Contr=0.3,0.1
English Units
Geom File=g01
Flow File=f01
Plan File=p01
BEGIN DESCRIPTION:
Denton Creek Tributary 31_1
END DESCRIPTION:

--- Denton Creek Tributary 31_1.p01 (plan) ---

Plan Title=Multiple Run
Short Identifier=Multiple
Geom File=g01
Flow File=f01
Subcritical Flow
K Sum by GR= 0
Std Step Tol= 0.01
Critical Tol= 0.01
Num of Std Step Trials= 20
Max Error Tol= 0.3
Flow Tol Ratio= 0.001
Split Flow NTrial= 30
Split Flow Tol= 0.02
Split Flow Ratio= 0.02
Log Output Level= 0
Friction Slope Method= 1
Unsteady Friction Slope Method= 2
Unsteady Bridges Friction Slope Method= 1
Parabolic Critical Depth
Global Vel Dist=  1 , 1 , 1
Global Log Level= 0
CheckData=True
Encroach Param= -1, 0, 0, 0
BEGIN DESCRIPTION:
Multiple Run
END DESCRIPTION:

--- Denton Creek Tributary 31_1.f01 (steady flow) ---

Flow Title=Multiple
Number of Profiles=7
Profile Names=10-year,25-year,50-year,1pct_min,100-year,1pct_plu,500-year
River Rch & RM= Denton Creek Tri,Reach-1,7083
     543     738     898     543    1084    2162    1579
River Rch & RM= Denton Creek Tri,Reach-1,3147
     864    1208    1498     922    1839    3669    2778
River Rch & RM= Denton Creek Tri,Reach-1,1648
     934    1311    1629    1005    2005    4000    3042
Boundary for River Rch & Prof#=Denton Creek Tri,Reach-1,1
Up Type=0
Dn Type=3
Dn Slope=0.005
Boundary for River Rch & Prof#=Denton Creek Tri,Reach-1,2
Up Type=0
Dn Type=3
Dn Slope=0.005
Boundary for River Rch & Prof#=Denton Creek Tri,Reach-1,3
Up Type=0
Dn Type=3
Dn Slope=0.005
Boundary for River Rch & Prof#=Denton Creek Tri,Reach-1,4
Up Type=0
Dn Type=3
Dn Slope=0.005
Boundary for River Rch & Prof#=Denton Creek Tri,Reach-1,5
Up Type=0
Dn Type=3
Dn Slope=0.005
Boundary for River Rch & Prof#=Denton Creek Tri,Reach-1,6
Up Type=0
Dn Type=3
Dn Slope=0.005
Boundary for River Rch & Prof#=Denton Creek Tri,Reach-1,7
Up Type=0
Dn Type=3
Dn Slope=0.005

--- Denton Creek Tributary 31_1.g01 (geometry) ---

Geom Title=Existing Conditions

River Reach=Denton Creek Tri,Reach-1
Reach XY= 30
      2322179.00      7131010.00      2321981.42      7130865.54
      2321872.84      7130852.12      2321631.42      7130665.54
      2321422.68      7130601.93      2321370.68      7130513.11
      2321237.32      7130506.89      2321188.97      7130420.71
      2320777.28      7130163.34      2320594.27      7130209.63
      2320428.92      7130117.30      2320299.20      7130210.37
      2320022.83      7130102.14      2319784.83      7129862.30
      2319392.61      7128973.42      2319279.00      7128910.00
      2319037.27      7128906.94      2318920.54      7128613.50
      2318818.52      7128561.19      2318426.64      7128504.25
      2318238.79      7128320.50      2318077.43      7128213.65
      2317987.48      7128206.50      2317785.73      7128019.11
      2317622.28      7128100.87      2317434.36      7127962.70
      2317423.99      7127765.01      2317287.32      7127756.89
      2317235.33      7127668.06      2317079.00      7127610.00

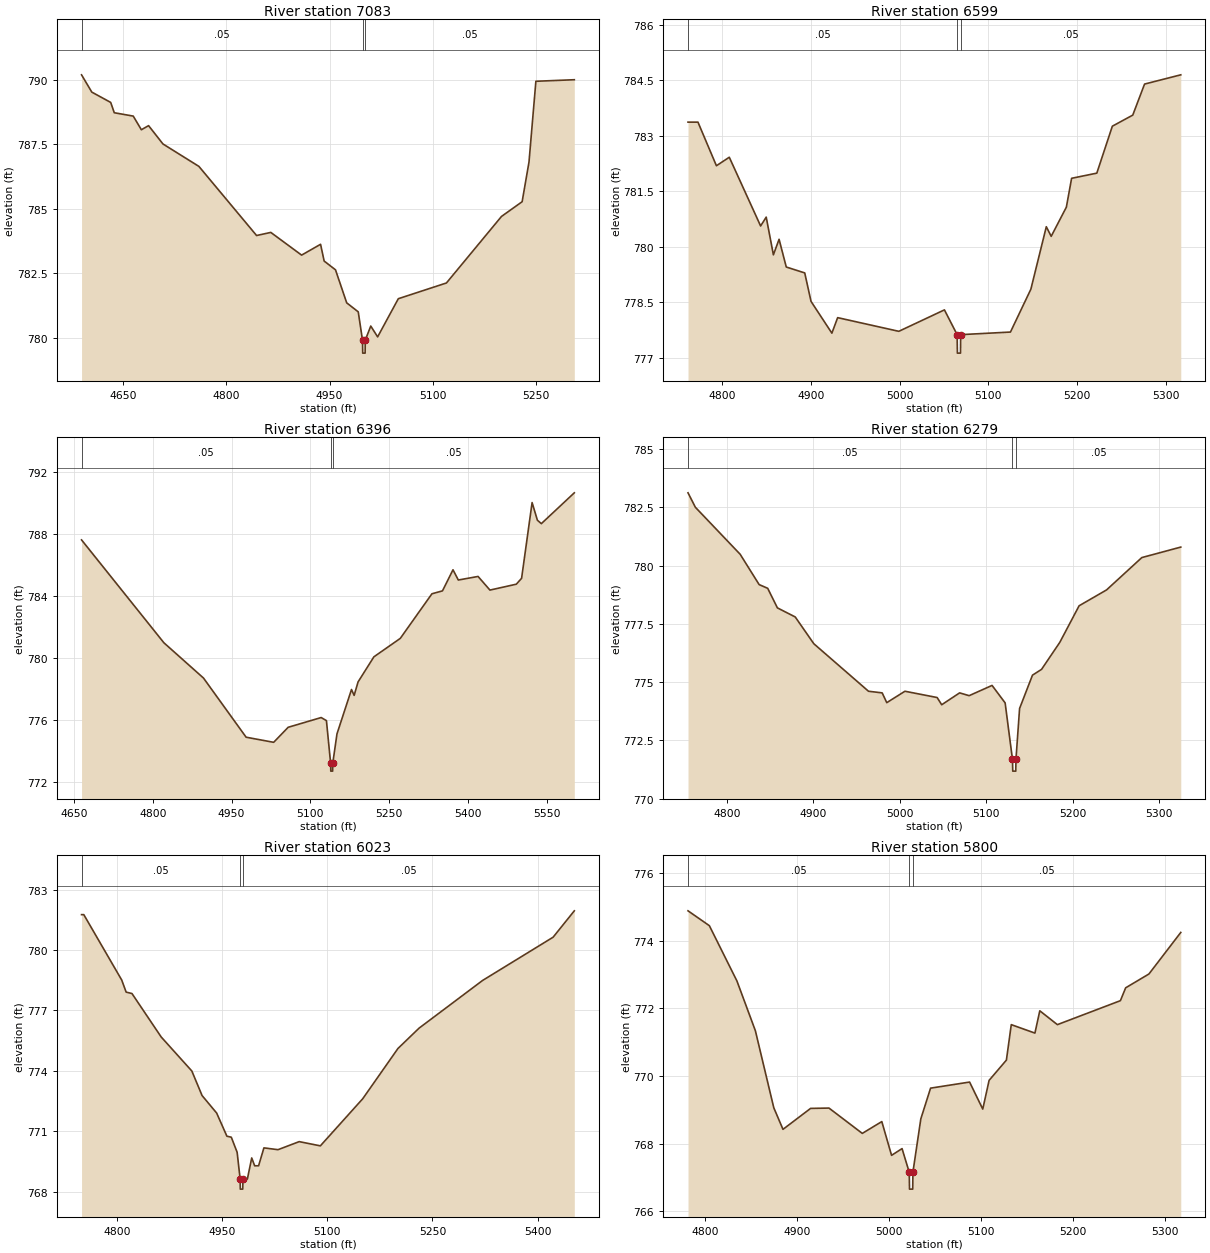
Type RM Length L Ch R = 1,7083,484,484,484
BEGIN DESCRIPTION:
Denton Creek Tributary 31_1 15.0
END DESCRIPTION:
XS GIS Cut Line= 3
      2322267.15      7130586.80      2322150.17      7130968.57
      2322137.60      7131285.83
#Sta/Elev= 30
  4589.3  790.19  4604.2  789.52  4631.7  789.12  4636.9  788.72  4664.5  788.59
  4676.3  788.06  4686.8  788.22  4707.7  787.51  4760.0  786.64  4843.9  783.96
  4864.6  784.08  4909.4  783.20  4937.0  783.62  4942.2  782.97  4958.7  782.63
  4975.0  781.35  4991.8  781.00  4998.0  779.90  4998.3  779.40  5001.8  779.40
  5002.0  779.90  5010.0  780.45  5020.0  780.03  5050.1  781.51  5120.1  782.12
  5200.2  784.70  5230.2  785.27  5240.2  786.81  5250.2  789.94  5306.1  790.00
#Mann=3,-1,0
  4589.3    0.05       0  4998.0   0.033       0  5002.0    0.05       0
Bank Sta=4998,5002
Exp/Cntr=0.3,0.1

Type RM Length L Ch R = 1,6599,203,203,203
BEGIN DESCRIPTION:
Mapping XS 3795b0df
END DESCRIPTION:
XS GIS Cut Line= 3
      2321874.51      7130560.79      2321782.26      7130678.82
      2321612.68      7131047.05
#Sta/Elev= 30
  4761.7  783.37  4772.9  783.37  4793.7  782.19  4808.2  782.42  4843.5  780.56
  4849.8  780.80  4857.9  779.78  4864.3  780.20  4872.4  779.45  4893.2  779.29
  4900.3  778.52  4923.8  777.66  4930.3  778.08  4999.2  777.71  5050.6  778.29
  5064.9  777.62  5065.2  777.12  5068.7  777.12  5068.9  777.62  5125.0  777.69
  5148.0  778.85  5165.4  780.54  5170.9  780.28  5188.0  781.07  5193.9  781.85
  5222.3  781.99  5239.8  783.26  5262.8  783.56  5276.1  784.40  5316.9  784.65
#Mann=3,-1,0
  4761.7    0.05       0  5064.9   0.033       0  5068.9    0.05       0
Bank Sta=5064.9,5068.9
Exp/Cntr=0.3,0.1

Type RM Length L Ch R = 1,6396,117,117,117
BEGIN DESCRIPTION:
Denton Creek Tributary 31_1 14.0
END DESCRIPTION:
XS GIS Cut Line= 3
      2321729.01      7130359.98      2321579.00      7130660.00
      2321529.00      7131259.98
#Sta/Elev= 30
  4664.6  787.62  4821.2  780.98  4896.6  778.70  4977.7  774.88  5030.1  774.55
  5057.7  775.52  5120.5  776.15  5130.5  775.95  5138.5  773.19  5138.8  772.69
  5142.3  772.69  5142.5  773.19  5150.6  775.10  5178.2  777.96  5183.2  777.58
  5190.7  778.45  5220.8  780.07  5271.0  781.26  5331.2  784.14  5351.3  784.33
  5371.3  785.69  5381.4  785.03  5419.0  785.26  5441.6  784.38  5491.7  784.76
  5501.8  785.14  5521.8  790.03  5531.9  788.89  5539.4  788.67  5602.1  790.66
#Mann=3,-1,0
  4664.6    0.05       0  5138.5   0.033       0  5142.5    0.05       0
Bank Sta=5138.5,5142.5
Exp/Cntr=0.3,0.1

Type RM Length L Ch R = 1,6279,256,256,256
BEGIN DESCRIPTION:
Mapping XS 580b1f78
END DESCRIPTION:
XS GIS Cut Line= 2
      2321554.30      7130381.94      2321375.92      7130922.78
#Sta/Elev= 30
  4755.2  783.13  4763.7  782.51  4815.5  780.49  4837.4  779.19  4847.3  779.03
  4858.5  778.19  4879.1  777.80  4900.6  776.65  4963.8  774.61  4979.6  774.54
  4984.9  774.12  5005.9  774.61  5043.1  774.34  5048.4  774.03  5069.1  774.54
  5080.1  774.42  5106.6  774.86  5121.7  774.11  5130.2  771.68  5130.5  771.18
  5134.0  771.18  5134.2  771.68  5138.4  773.87  5153.3  775.30  5163.8  775.55
  5184.9  776.71  5207.2  778.28  5238.9  778.96  5279.7  780.35  5324.7  780.80
#Mann=3,-1,0
  4755.2    0.05       0  5130.2   0.033       0  5134.2    0.05       0
Bank Sta=5130.2,5134.2
Exp/Cntr=0.3,0.1

Type RM Length L Ch R = 1,6023,223,223,223
BEGIN DESCRIPTION:
Denton Creek Tributary 31_1 13.0
END DESCRIPTION:
XS GIS Cut Line= 3
      2321479.02      7130359.98      2321279.00      7130510.00
      2321329.00      7130960.00
#Sta/Elev= 30
  4749.5  781.76  4752.7  781.76  4806.8  778.51  4813.1  777.91  4821.4  777.84
  4863.1  775.68  4906.8  773.99  4921.4  772.77  4942.2  771.90  4956.8  770.75
  4963.1  770.70  4971.4  769.95  4975.7  768.62  4975.9  768.12  4979.4  768.12
  4979.7  768.62  4986.0  768.62  4992.2  769.67  4996.4  769.28  5002.0  769.28
  5009.6  770.17  5029.7  770.08  5059.9  770.48  5090.1  770.27  5150.5  772.61
  5200.8  775.11  5230.9  776.12  5321.5  778.49  5422.1  780.64  5452.3  781.95
#Mann=3,-1,0
  4749.5    0.05       0  4975.7   0.033       0  4979.7    0.05       0
Bank Sta=4975.7,4979.7
Exp/Cntr=0.3,0.1

Type RM Length L Ch R = 1,5800,83,83,83
BEGIN DESCRIPTION:
Mapping XS deda728e
END DESCRIPTION:
XS GIS Cut Line= 3
      2321312.16      7130363.69      2321128.82      7130364.27
      2321012.17      7130696.54
#Sta/Elev= 30
  4781.5  774.89  4804.7  774.45  4834.7  772.81  4854.7  771.34  4874.7  769.06
  4884.7  768.42  4914.7  769.04  4934.7  769.05  4970.9  768.30  4992.1  768.65
  5002.7  767.65  5014.1  767.85  5021.9  767.15  5022.2  766.65  5025.7  766.65
  5025.9  767.15  5034.5  768.73  5045.1  769.64  5087.5  769.82  5101.8  769.02
  5108.7  769.87  5127.5  770.47  5132.8  771.52  5158.5  771.27  5163.8  771.93
  5182.9  771.52  5251.4  772.23  5257.1  772.61  5282.4  773.02  5317.0  774.25
#Mann=3,-1,0
  4781.5    0.05       0  5021.9   0.033       0  5025.9    0.05       0
Bank Sta=5021.9,5025.9
Exp/Cntr=0.3,0.1

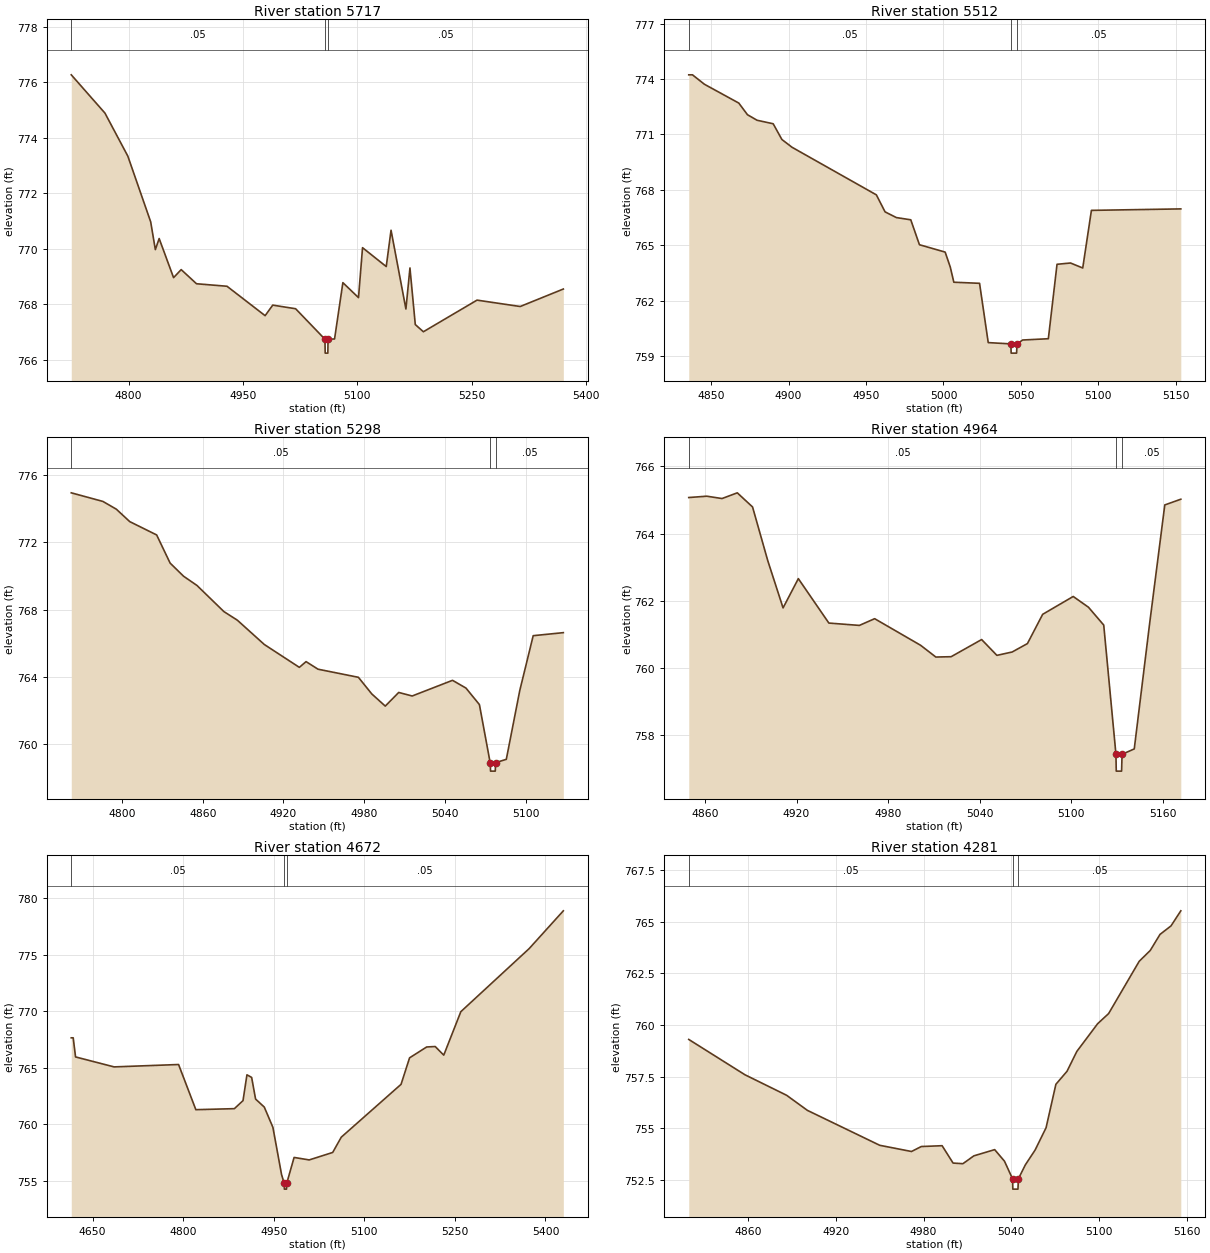
Type RM Length L Ch R = 1,5717,205,205,205
BEGIN DESCRIPTION:
Mapping XS a4faee6a
END DESCRIPTION:
XS GIS Cut Line= 3
      2321333.14      7130349.19      2321006.82      7130336.90
      2320705.54      7130441.60
#Sta/Elev= 30
  4724.8  776.27  4769.0  774.89  4799.0  773.34  4829.0  770.97  4835.1  769.97
  4840.1  770.37  4859.0  768.96  4869.0  769.25  4889.1  768.74  4929.1  768.65
  4979.1  767.59  4989.1  767.97  5019.1  767.84  5057.6  766.74  5057.9  766.24
  5061.4  766.24  5061.6  766.74  5070.2  766.75  5081.1  768.78  5101.6  768.24
  5106.9  770.04  5138.0  769.36  5144.3  770.67  5163.8  767.83  5169.1  769.31
  5176.1  767.27  5186.7  767.01  5257.1  768.15  5313.7  767.92  5370.3  768.55
#Mann=3,-1,0
  4724.8    0.05       0  5057.6   0.033       0  5061.6    0.05       0
Bank Sta=5057.6,5061.6
Exp/Cntr=0.3,0.1

Type RM Length L Ch R = 1,5512,214,214,214
BEGIN DESCRIPTION:
Mapping XS 111652cd
END DESCRIPTION:
XS GIS Cut Line= 2
      2321048.27      7130157.96      2320765.67      7130302.89
#Sta/Elev= 30
  4835.6  774.23  4838.0  774.23  4845.7  773.72  4867.9  772.70  4873.5  772.07
  4879.7  771.77  4890.1  771.58  4895.7  770.73  4902.2  770.31  4956.7  767.73
  4962.3  766.81  4969.6  766.50  4978.9  766.38  4984.5  765.03  5001.1  764.63
  5004.4  763.82  5006.7  763.00  5023.3  762.94  5028.9  759.73  5043.5  759.66
  5043.7  759.16  5047.2  759.16  5047.5  759.66  5051.1  759.87  5067.7  759.94
  5073.3  763.97  5082.0  764.04  5089.9  763.77  5095.5  766.89  5153.2  766.97
#Mann=3,-1,0
  4835.6    0.05       0  5043.5    0.04       0  5047.5    0.05       0
Bank Sta=5043.5,5047.5
Exp/Cntr=0.3,0.1

Type RM Length L Ch R = 1,5298,334,334,334
BEGIN DESCRIPTION:
Mapping XS 64943699
END DESCRIPTION:
XS GIS Cut Line= 2
      2320711.09      7129936.53      2320717.33      7130302.37
#Sta/Elev= 30
  4762.2  774.93  4785.7  774.42  4795.7  773.96  4805.7  773.22  4825.7  772.43
  4835.7  770.76  4845.7  769.98  4855.7  769.43  4875.7  767.88  4885.7  767.37
  4905.7  765.93  4931.8  764.57  4936.8  764.91  4945.7  764.46  4975.7  763.98
  4985.7  762.99  4995.7  762.27  5005.7  763.08  5015.7  762.87  5045.7  763.80
  5055.7  763.34  5065.7  762.36  5073.7  758.91  5074.0  758.41  5077.5  758.41
  5077.7  758.91  5085.7  759.11  5095.7  763.19  5105.7  766.45  5128.1  766.63
#Mann=3,-1,0
  4762.2    0.05       0  5073.7    0.04       0  5077.7    0.05       0
Bank Sta=5073.7,5077.7
Exp/Cntr=0.3,0.1

Type RM Length L Ch R = 1,4964,292,292,292
BEGIN DESCRIPTION:
Mapping XS a9a99afa
END DESCRIPTION:
XS GIS Cut Line= 2
      2320419.41      7129968.19      2320427.59      7130290.49
#Sta/Elev= 30
  4849.4  765.07  4861.2  765.11  4871.2  765.04  4881.2  765.21  4891.2  764.79
  4901.2  763.19  4911.2  761.79  4921.2  762.66  4941.2  761.34  4961.2  761.27
  4971.2  761.47  5001.3  760.68  5011.3  760.33  5021.3  760.34  5041.3  760.85
  5051.3  760.38  5061.3  760.48  5071.3  760.73  5081.3  761.60  5101.3  762.13
  5111.3  761.81  5121.3  761.28  5129.3  757.44  5129.5  756.94  5133.0  756.94
  5133.3  757.44  5141.3  757.60  5151.3  761.30  5161.3  764.85  5171.8  765.02
#Mann=3,-1,0
  4849.4    0.05       0  5129.3    0.04       0  5133.3    0.05       0
Bank Sta=5129.3,5133.3
Exp/Cntr=0.3,0.1

Type RM Length L Ch R = 1,4672,391,391,391
BEGIN DESCRIPTION:
Denton Creek Tributary 31_1 9.0
END DESCRIPTION:
XS GIS Cut Line= 3
      2320478.99      7129910.01      2320179.00      7130160.00
      2319878.97      7130460.03
#Sta/Elev= 30
  4614.8  767.64  4618.0  767.64  4621.9  765.95  4685.7  765.07  4792.5  765.28
  4821.1  761.29  4884.9  761.38  4899.2  762.09  4905.7  764.37  4913.5  764.14
  4920.0  762.23  4934.4  761.52  4948.7  759.73  4963.0  755.56  4967.5  754.77
  4967.7  754.27  4971.2  754.27  4971.5  754.77  4983.8  757.07  5008.8  756.85
  5047.7  757.51  5061.9  758.86  5160.9  763.53  5175.0  765.87  5203.3  766.83
  5217.4  766.87  5231.6  766.11  5259.9  769.95  5373.0  775.52  5429.6  778.86
#Mann=3,-1,0
  4614.8    0.05       0  4967.5    0.04       0  4971.5    0.05       0
Bank Sta=4967.5,4971.5
Exp/Cntr=0.3,0.1

Type RM Length L Ch R = 1,4281,245,245,245
BEGIN DESCRIPTION:
Mapping XS a51e0988
END DESCRIPTION:
XS GIS Cut Line= 2
      2320005.47      7129831.97      2319754.73      7130055.63
#Sta/Elev= 30
  4819.7  759.30  4858.1  757.59  4886.5  756.60  4900.7  755.87  4950.1  754.18
  4971.8  753.88  4978.5  754.12  4992.7  754.16  5000.2  753.32  5006.9  753.29
  5014.4  753.67  5028.6  753.97  5035.3  753.41  5040.8  752.56  5041.0  752.06
  5044.5  752.06  5044.8  752.56  5049.5  753.23  5056.2  753.95  5063.7  755.03
  5070.4  757.13  5078.0  757.76  5084.7  758.72  5098.9  760.06  5106.4  760.55
  5127.3  763.08  5134.8  763.60  5141.5  764.38  5149.0  764.79  5155.7  765.52
#Mann=3,-1,0
  4819.7    0.05       0  5040.8    0.04       0  5044.8    0.05       0
Bank Sta=5040.8,5044.8
Exp/Cntr=0.3,0.1

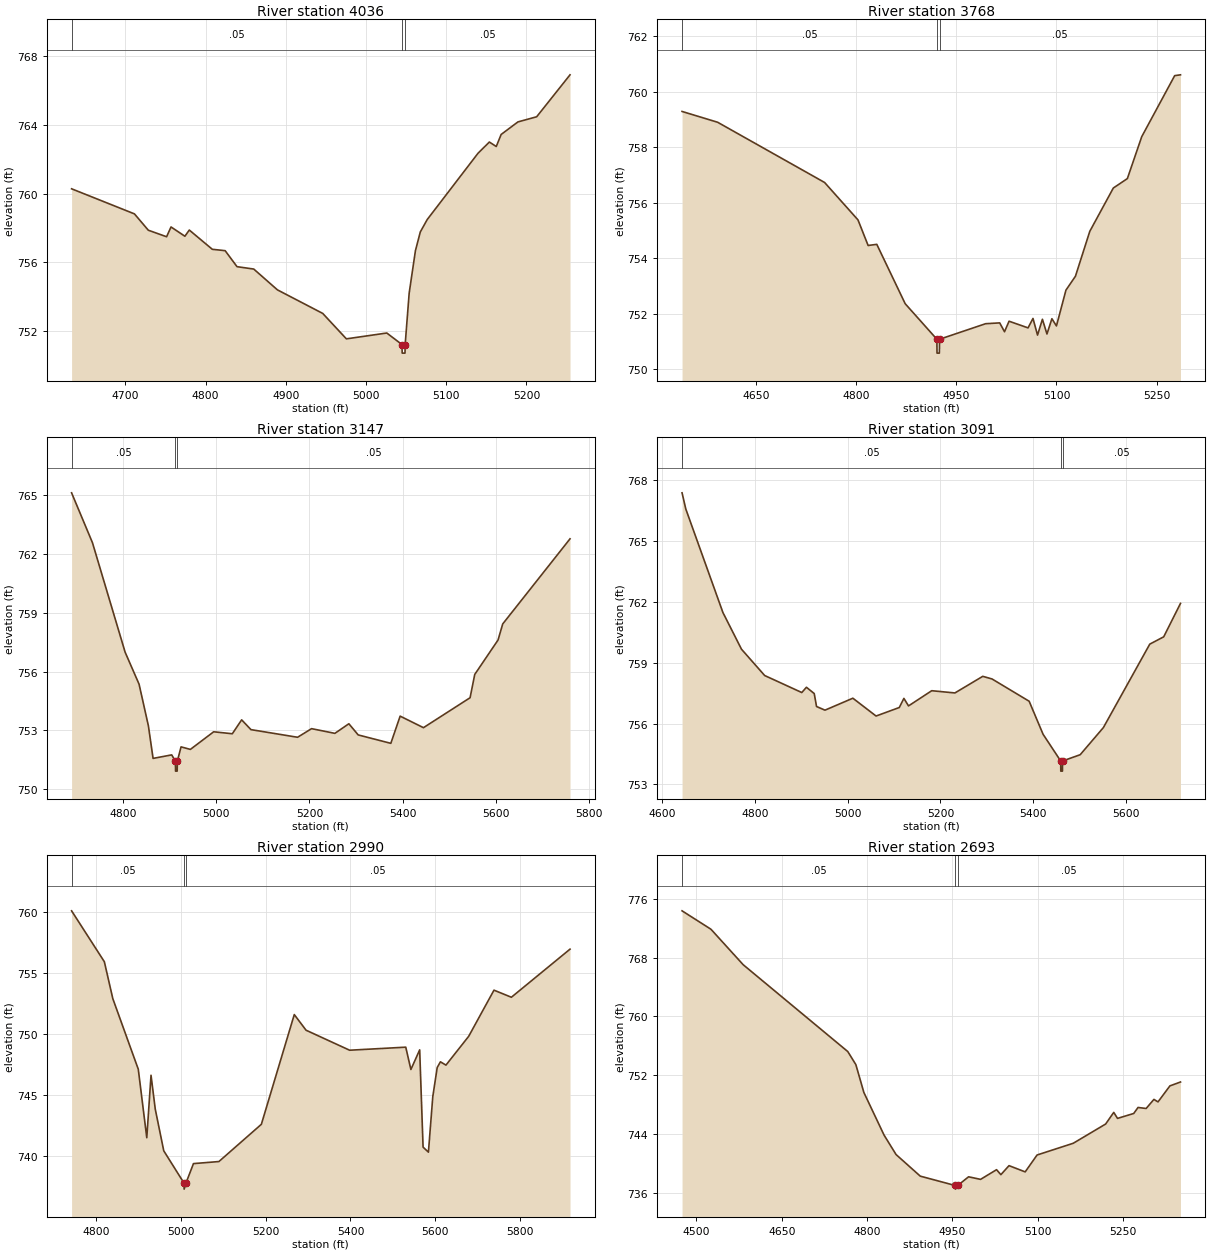
Type RM Length L Ch R = 1,4036,268,268,268
BEGIN DESCRIPTION:
Mapping XS 87ead999
END DESCRIPTION:
XS GIS Cut Line= 3
      2320048.21      7129573.22      2319884.77      7129649.98
      2319525.60      7129905.93
#Sta/Elev= 30
  4632.8  760.28  4711.2  758.82  4728.5  757.87  4751.3  757.49  4756.8  758.06
  4774.1  757.52  4779.6  757.88  4808.3  756.76  4824.3  756.68  4839.1  755.75
  4860.0  755.61  4889.5  754.40  4946.0  753.03  4975.5  751.55  5025.9  751.89
  5044.8  751.22  5045.1  750.72  5048.6  750.72  5048.8  751.22  5053.8  754.21
  5061.6  756.68  5067.7  757.77  5076.3  758.49  5139.7  762.35  5153.8  763.00
  5162.4  762.74  5168.5  763.44  5189.4  764.17  5212.8  764.47  5254.4  766.91
#Mann=3,-1,0
  4632.8    0.05       0  5044.8   0.033       0  5048.8    0.05       0
Bank Sta=5044.8,5048.8
Exp/Cntr=0.3,0.1

Type RM Length L Ch R = 1,3768,621,621,621
BEGIN DESCRIPTION:
Mapping XS 1e0a48bc
END DESCRIPTION:
XS GIS Cut Line= 3
      2320052.30      7129396.67      2319773.72      7129396.56
      2319430.09      7129713.13
#Sta/Elev= 30
  4539.8  759.29  4593.1  758.90  4753.1  756.73  4803.1  755.38  4818.2  754.46
  4831.2  754.50  4873.7  752.36  4921.1  751.08  4921.3  750.58  4924.8  750.58
  4925.1  751.08  4994.0  751.64  5015.1  751.67  5022.3  751.35  5029.1  751.73
  5057.5  751.49  5064.9  751.83  5071.7  751.23  5079.0  751.80  5085.8  751.27
  5093.2  751.82  5100.0  751.56  5114.2  752.85  5128.4  753.35  5149.9  754.97
  5185.1  756.53  5206.1  756.87  5227.6  758.38  5276.9  760.58  5285.6  760.61
#Mann=3,-1,0
  4539.8    0.05       0  4921.1   0.033       0  4925.1    0.05       0
Bank Sta=4921.1,4925.1
Exp/Cntr=0.3,0.1

Type RM Length L Ch R = 1,3147,56,56,56
BEGIN DESCRIPTION:
Mapping XS feeb0cc7
END DESCRIPTION:
XS GIS Cut Line= 2
      2319397.86      7128665.21      2319388.00      7129734.37
#Sta/Elev= 30
  4689.7  765.13  4734.5  762.58  4804.5  756.99  4834.5  755.35  4854.5  753.22
  4864.5  751.56  4904.5  751.74  4912.5  751.41  4912.7  750.91  4916.2  750.91
  4916.5  751.41  4924.5  752.15  4944.5  752.02  4994.5  752.92  5034.5  752.82
  5054.5  753.53  5074.5  753.03  5174.5  752.64  5204.5  753.08  5254.5  752.84
  5284.5  753.33  5304.5  752.76  5374.5  752.33  5394.5  753.72  5444.5  753.13
  5544.5  754.66  5554.5  755.85  5604.5  757.61  5614.5  758.43  5758.9  762.78
#Mann=3,-1,0
  4689.7    0.05       0  4912.5   0.033       0  4916.5    0.05       0
Bank Sta=4912.5,4916.5
Exp/Cntr=0.3,0.1

Type RM Length L Ch R = 1,3091,101,101,101
BEGIN DESCRIPTION:
Mapping XS 835a297f
END DESCRIPTION:
XS GIS Cut Line= 2
      2319347.62      7128601.88      2319334.07      7129676.19
#Sta/Elev= 30
  4643.1  767.39  4651.2  766.59  4731.2  761.48  4771.2  759.67  4821.2  758.37
  4901.2  757.53  4911.2  757.79  4928.0  757.48  4933.0  756.84  4951.2  756.66
  5011.3  757.25  5061.3  756.37  5111.3  756.79  5121.3  757.24  5131.3  756.87
  5181.3  757.62  5231.3  757.51  5291.3  758.33  5311.3  758.20  5391.3  757.10
  5421.3  755.47  5459.3  754.15  5459.5  753.65  5463.0  753.65  5463.3  754.15
  5501.3  754.46  5551.3  755.80  5651.3  759.92  5681.3  760.28  5717.5  761.93
#Mann=3,-1,0
  4643.1    0.05       0  5459.3   0.033       0  5463.3    0.05       0
Bank Sta=5459.3,5463.3
Exp/Cntr=0.3,0.1

Type RM Length L Ch R = 1,2990,297,297,297
BEGIN DESCRIPTION:
Mapping XS 44bec4a7
END DESCRIPTION:
XS GIS Cut Line= 4
      2319257.92      7128652.82      2319262.89      7129180.11
      2318900.88      7129087.77      2318841.17      7129354.87
#Sta/Elev= 30
  4742.8  760.12  4820.0  755.95  4840.0  752.92  4900.0  747.14  4920.0  741.53
  4930.0  746.65  4940.0  743.87  4960.0  740.46  5007.6  737.82  5008.1  737.32
  5012.4  737.82  5030.0  739.41  5090.0  739.58  5190.0  742.63  5267.6  751.62
  5295.3  750.34  5398.0  748.70  5530.3  748.95  5542.4  747.12  5563.1  748.73
  5571.1  740.76  5583.7  740.35  5594.0  744.90  5604.4  747.28  5612.0  747.75
  5625.0  747.48  5678.6  749.84  5738.2  753.62  5779.2  753.04  5917.4  756.98
#Mann=3,-1,0
  4742.8    0.05       0  5007.6   0.033       0  5012.4    0.05       0
Bank Sta=5007.6,5012.4
Exp/Cntr=0.3,0.1

Type RM Length L Ch R = 1,2693,366,366,366
BEGIN DESCRIPTION:
Denton Creek Tributary 31_1 4.0
END DESCRIPTION:
XS GIS Cut Line= 3
      2319374.42      7128463.41      2319004.76      7128846.77
      2318778.30      7129105.11
#Sta/Elev= 30
  4474.7  774.40  4525.5  771.89  4582.1  767.06  4766.0  755.22  4780.2  753.44
  4794.3  749.64  4829.8  743.83  4850.9  741.18  4893.4  738.24  4954.5  736.97
  4955.1  736.47  4959.3  736.97  4978.3  738.15  4999.4  737.80  5027.5  739.12
  5035.1  738.44  5049.4  739.67  5077.8  738.82  5098.7  741.12  5162.3  742.72
  5219.2  745.34  5233.5  746.93  5240.1  746.11  5268.6  746.78  5276.2  747.60
  5290.4  747.46  5304.1  748.70  5311.3  748.36  5332.2  750.54  5350.8  751.07
#Mann=3,-1,0
  4474.7    0.05       0  4954.5   0.033       0  4959.3    0.05       0
Bank Sta=4954.5,4959.3
Exp/Cntr=0.3,0.1

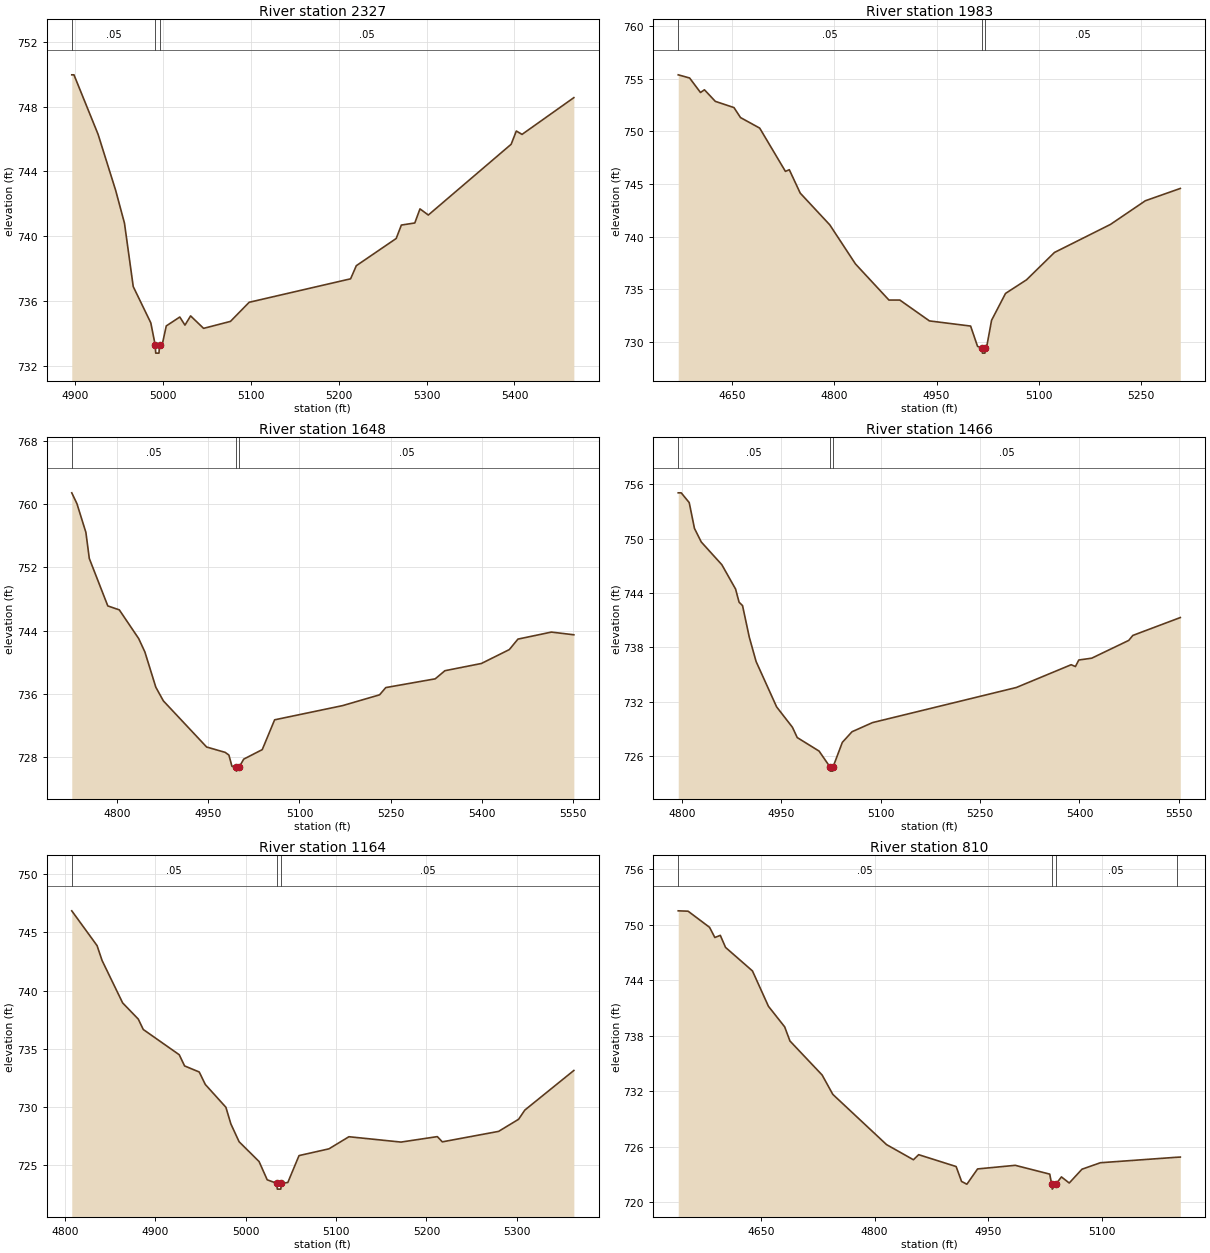
Type RM Length L Ch R = 1,2327,344,344,344
BEGIN DESCRIPTION:
Denton Creek Tributary 31_1 3.0
END DESCRIPTION:
XS GIS Cut Line= 3
      2318829.00      7128460.04      2318829.00      7128560.00
      2318578.98      7128960.03
#Sta/Elev= 30
  4895.9  749.96  4898.4  749.96  4925.9  746.28  4945.9  742.82  4955.9  740.80
  4965.9  736.88  4985.9  734.64  4990.9  733.27  4991.5  732.77  4995.2  732.77
  4995.8  733.27  4998.8  733.27  5003.5  734.45  5018.9  735.00  5024.8  734.50
  5031.2  735.07  5046.0  734.30  5076.6  734.73  5097.9  735.91  5213.4  737.36
  5219.9  738.17  5265.3  739.85  5271.2  740.68  5286.5  740.81  5292.4  741.68
  5301.9  741.30  5396.2  745.67  5402.1  746.49  5408.6  746.28  5467.6  748.55
#Mann=3,-1,0
  4895.9    0.05       0  4990.9   0.033       0  4995.8    0.05       0
Bank Sta=4990.9,4995.8
Exp/Cntr=0.3,0.1

Type RM Length L Ch R = 1,1983,335,335,335
BEGIN DESCRIPTION:
Denton Creek Tributary 31_1 2.0
END DESCRIPTION:
XS GIS Cut Line= 3
      2318869.03      7128297.11      2318501.27      7128501.31
      2318429.00      7128810.02
#Sta/Elev= 30
  4570.5  755.37  4587.2  755.07  4603.2  753.69  4609.0  753.95  4625.0  752.85
  4652.4  752.26  4662.0  751.31  4690.2  750.31  4728.0  746.20  4733.7  746.36
  4749.7  744.14  4793.2  741.12  4830.9  737.41  4880.1  733.98  4896.1  733.98
  4939.6  732.00  5000.1  731.51  5010.3  729.58  5016.8  729.44  5017.4  728.94
  5021.1  728.94  5021.7  729.44  5024.4  729.78  5030.9  732.06  5051.4  734.61
  5082.2  735.90  5123.3  738.50  5205.5  741.16  5256.8  743.41  5308.2  744.58
#Mann=3,-1,0
  4570.5    0.05       0  5016.8   0.033       0  5021.7    0.05       0
Bank Sta=5016.8,5021.7
Exp/Cntr=0.3,0.1

Type RM Length L Ch R = 1,1648,182,182,182
BEGIN DESCRIPTION:
Mapping XS 668c1780
END DESCRIPTION:
XS GIS Cut Line= 2
      2318297.83      7128061.65      2318158.29      7128874.46
#Sta/Elev= 30
  4726.0  761.47  4734.5  760.09  4749.2  756.45  4754.8  753.14  4785.2  747.12
  4804.1  746.62  4835.9  742.98  4846.1  741.28  4864.1  736.80  4876.5  735.07
  4947.5  729.22  4978.0  728.54  4984.1  728.20  4989.1  726.78  4995.7  726.66
  4996.4  726.16  5000.9  726.66  5008.4  727.68  5038.9  728.89  5059.2  732.67
  5170.8  734.47  5231.6  735.84  5241.8  736.76  5323.0  737.87  5338.9  738.90
  5398.9  739.82  5444.7  741.58  5458.9  742.91  5513.8  743.80  5550.7  743.46
#Mann=3,-1,0
  4726.0    0.05       0  4995.7   0.033       0  5000.9    0.05       0
Bank Sta=4995.7,5000.9
Exp/Cntr=0.3,0.1

Type RM Length L Ch R = 1,1466,302,302,302
BEGIN DESCRIPTION:
Mapping XS 7e259ae9
END DESCRIPTION:
XS GIS Cut Line= 2
      2318157.54      7128036.31      2317963.83      7128769.34
#Sta/Elev= 30
  4794.1  755.04  4798.6  755.04  4810.7  753.96  4818.6  751.12  4828.9  749.62
  4860.0  747.11  4880.7  744.43  4886.0  742.98  4891.2  742.61  4901.4  739.13
  4911.7  736.44  4942.7  731.44  4966.6  729.19  4973.8  728.06  5006.8  726.57
  5022.9  724.86  5023.6  724.36  5027.4  724.36  5028.1  724.86  5041.9  727.53
  5056.5  728.70  5087.5  729.71  5304.7  733.58  5387.5  736.09  5393.9  735.89
  5399.0  736.61  5418.5  736.81  5474.4  738.77  5480.6  739.32  5552.3  741.29
#Mann=3,-1,0
  4794.1    0.05       0  5022.9   0.033       0  5028.1    0.05       0
Bank Sta=5022.9,5028.1
Exp/Cntr=0.3,0.1

Type RM Length L Ch R = 1,1164,354,354,354
BEGIN DESCRIPTION:
Mapping XS bdf45700
END DESCRIPTION:
XS GIS Cut Line= 2
      2317947.09      7127922.33      2317711.66      7128425.36
#Sta/Elev= 30
  4807.6  746.86  4835.6  743.87  4841.1  742.60  4863.9  738.95  4881.2  737.56
  4886.7  736.67  4926.5  734.50  4932.4  733.54  4948.6  733.02  4955.3  731.95
  4978.1  729.99  4983.6  728.56  4992.7  727.03  5014.8  725.33  5023.8  723.76
  5034.3  723.46  5035.0  722.96  5038.8  722.96  5039.5  723.46  5046.6  723.53
  5059.0  725.84  5092.1  726.42  5114.2  727.46  5171.8  727.00  5212.0  727.47
  5217.5  727.02  5279.8  727.92  5301.9  728.96  5308.8  729.75  5363.0  733.15
#Mann=3,-1,0
  4807.6    0.05       0  5034.3   0.033       0  5039.5    0.05       0
Bank Sta=5034.3,5039.5
Exp/Cntr=0.3,0.1

Type RM Length L Ch R = 1,810,254,254,254
BEGIN DESCRIPTION:
Mapping XS 50112f5b
END DESCRIPTION:
XS GIS Cut Line= 3
      2317903.10      7127735.70      2317579.11      7128073.84
      2317623.08      7128262.68
#Sta/Elev= 30
  4541.1  751.49  4554.1  751.45  4582.4  749.71  4589.4  748.61  4596.6  748.84
  4603.5  747.54  4639.0  745.00  4660.1  741.18  4681.5  738.96  4688.4  737.44
  4730.9  733.76  4745.0  731.67  4815.8  726.25  4851.3  724.61  4858.2  725.16
  4907.6  723.88  4914.8  722.27  4921.8  721.97  4935.9  723.62  4985.6  724.01
  5031.1  723.06  5033.7  721.94  5034.4  721.44  5038.9  721.94  5046.5  722.76
  5056.8  722.10  5073.6  723.59  5097.9  724.29  5198.4  724.88  5203.3  724.90
#Mann=4,-1,0
  4541.1    0.05       0  5033.7   0.033       0  5038.9    0.05       0
  5198.4    0.12       0
Bank Sta=5033.7,5038.9
Exp/Cntr=0.3,0.1

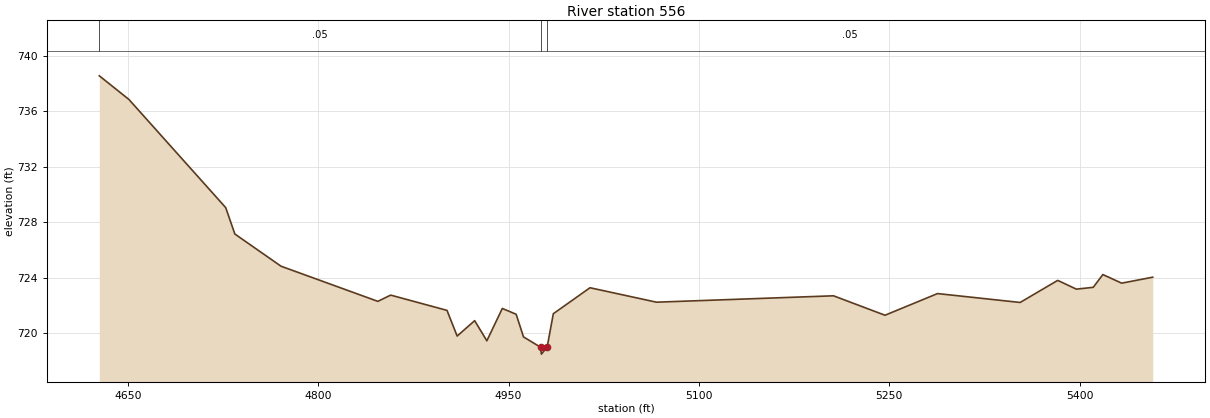
Type RM Length L Ch R = 1,556,0,0,0
BEGIN DESCRIPTION:
Denton Creek Tributary 31_1 1.0
END DESCRIPTION:
XS GIS Cut Line= 4
      2317770.38      7127751.79      2317361.62      7127929.12
      2317394.62      7128111.26      2317557.20      7128226.91
#Sta/Elev= 30
  4627.5  738.55  4650.8  736.85  4727.1  729.06  4734.3  727.16  4770.7  724.84
  4847.0  722.31  4857.1  722.76  4901.5  721.66  4909.5  719.81  4923.3  720.92
  4932.9  719.47  4945.1  721.80  4956.0  721.38  4961.8  719.75  4975.2  719.01
  4975.9  718.51  4980.4  719.01  4985.3  721.42  5014.2  723.29  5066.6  722.25
  5206.1  722.71  5246.7  721.31  5288.1  722.87  5353.2  722.23  5382.8  723.82
  5397.5  723.19  5410.8  723.32  5418.4  724.24  5433.2  723.62  5457.7  724.05
#Mann=3,-1,0
  4627.5    0.05       0  4975.2   0.033       0  4980.4    0.05       0
Bank Sta=4975.2,4980.4
Exp/Cntr=0.3,0.1

Chan Stop Cuts=-1