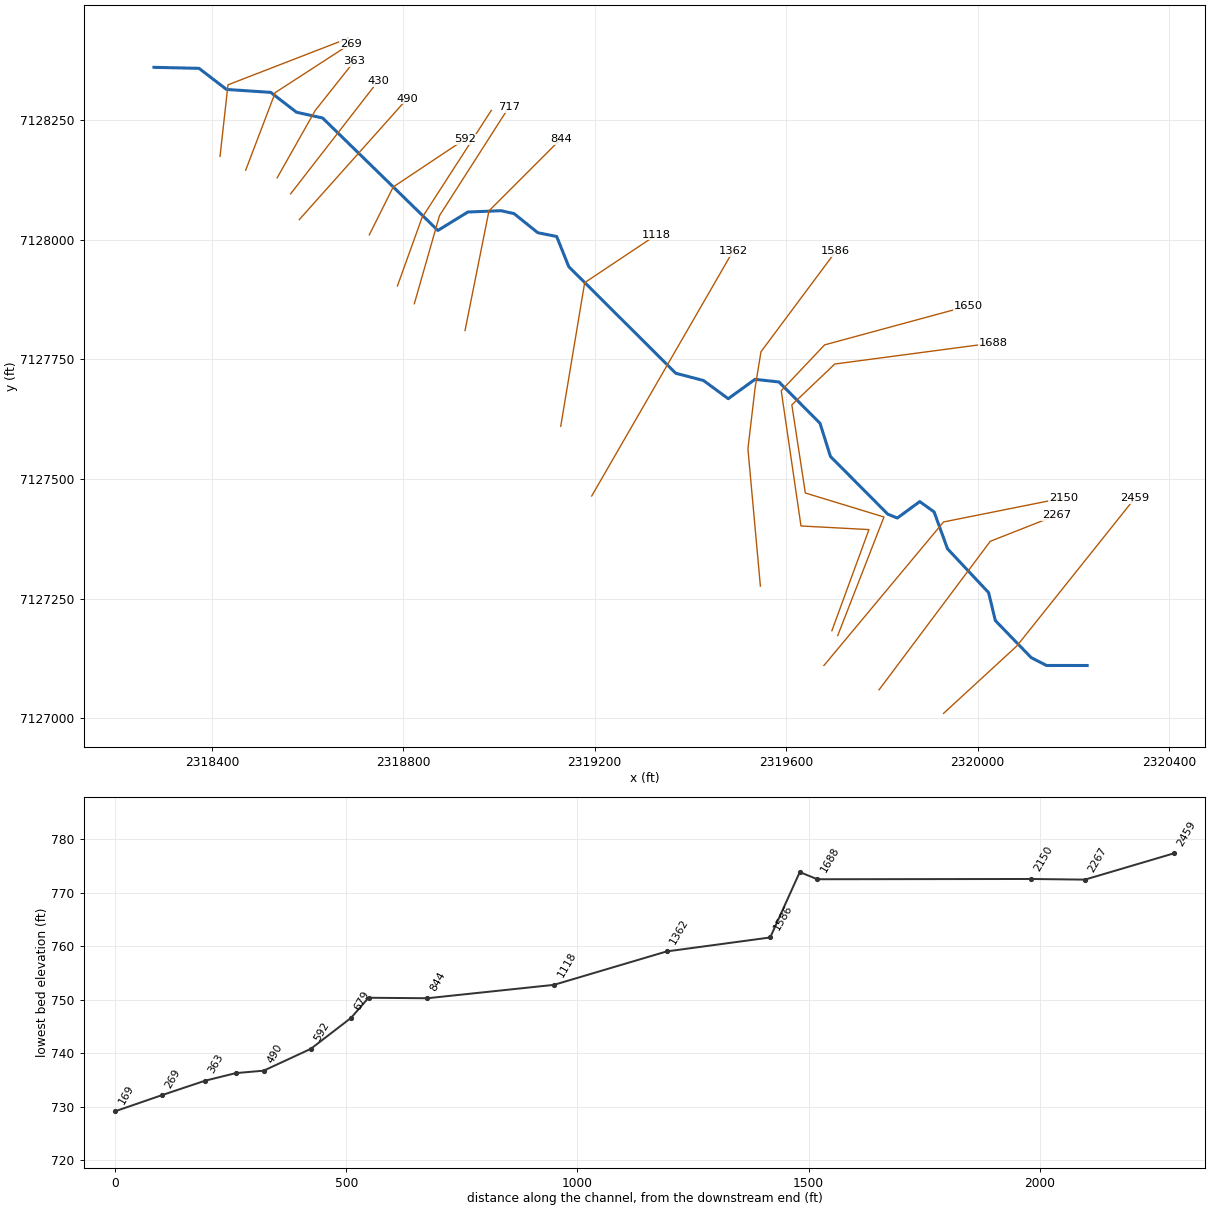
--- Denton Creek Tributary 31_1_1.prj (project) ---

Proj Title=Denton Creek Tributary 31_1_1 Base Level Engineering
Current Plan=p01
Default Exp/Contr=0.3,0.1
English Units
Geom File=g01
Flow File=f01
Plan File=p01
BEGIN DESCRIPTION:
Denton Creek Tributary 31_1_1
END DESCRIPTION:

--- Denton Creek Tributary 31_1_1.p01 (plan) ---

Plan Title=Multiple Run
Short Identifier=Multiple
Geom File=g01
Flow File=f01
Subcritical Flow
K Sum by GR= 0
Std Step Tol= 0.01
Critical Tol= 0.01
Num of Std Step Trials= 20
Max Error Tol= 0.3
Flow Tol Ratio= 0.001
Split Flow NTrial= 30
Split Flow Tol= 0.02
Split Flow Ratio= 0.02
Log Output Level= 0
Friction Slope Method= 1
Unsteady Friction Slope Method= 2
Unsteady Bridges Friction Slope Method= 1
Parabolic Critical Depth
Global Vel Dist=  1 , 1 , 1
Global Log Level= 0
CheckData=True
Encroach Param= -1, 0, 0, 0
BEGIN DESCRIPTION:
Multiple Run
END DESCRIPTION:

--- Denton Creek Tributary 31_1_1.f01 (steady flow) ---

Flow Title=Multiple
Number of Profiles=7
Profile Names=10-year,25-year,50-year,1pct_min,100-year,1pct_plu,500-year
River Rch & RM= Denton Creek Tri,Reach-1,2459
     169     214     248     144     287     572     382
Boundary for River Rch & Prof#=Denton Creek Tri,Reach-1,1
Up Type=0
Dn Type=3
Dn Slope=0.005
Boundary for River Rch & Prof#=Denton Creek Tri,Reach-1,2
Up Type=0
Dn Type=3
Dn Slope=0.005
Boundary for River Rch & Prof#=Denton Creek Tri,Reach-1,3
Up Type=0
Dn Type=3
Dn Slope=0.005
Boundary for River Rch & Prof#=Denton Creek Tri,Reach-1,4
Up Type=0
Dn Type=3
Dn Slope=0.005
Boundary for River Rch & Prof#=Denton Creek Tri,Reach-1,5
Up Type=0
Dn Type=3
Dn Slope=0.005
Boundary for River Rch & Prof#=Denton Creek Tri,Reach-1,6
Up Type=0
Dn Type=3
Dn Slope=0.005
Boundary for River Rch & Prof#=Denton Creek Tri,Reach-1,7
Up Type=0
Dn Type=3
Dn Slope=0.005

--- Denton Creek Tributary 31_1_1.g01 (geometry) ---

Geom Title=Existing Conditions

River Reach=Denton Creek Tri,Reach-1
Reach XY= 30
      2320229.00      7127110.00      2320144.04      7127110.11
      2320112.20      7127126.42      2320037.15      7127203.93
      2320023.13      7127262.28      2319937.18      7127354.00
      2319909.21      7127430.98      2319879.21      7127452.53
      2319832.35      7127418.17      2319812.34      7127426.39
      2319692.63      7127546.79      2319670.85      7127616.07
      2319585.07      7127702.51      2319535.05      7127708.02
      2319479.00      7127667.56      2319427.35      7127705.55
      2319369.32      7127720.75      2319145.73      7127943.52
      2319120.52      7128006.49      2319081.11      7128014.37
      2319031.36      7128054.37      2319004.01      7128060.41
      2318934.89      7128057.63      2318872.26      7128019.13
      2318631.30      7128254.17      2318576.83      7128266.14
      2318523.04      7128307.67      2318430.58      7128313.83
      2318373.13      7128357.90      2318279.00      7128360.00

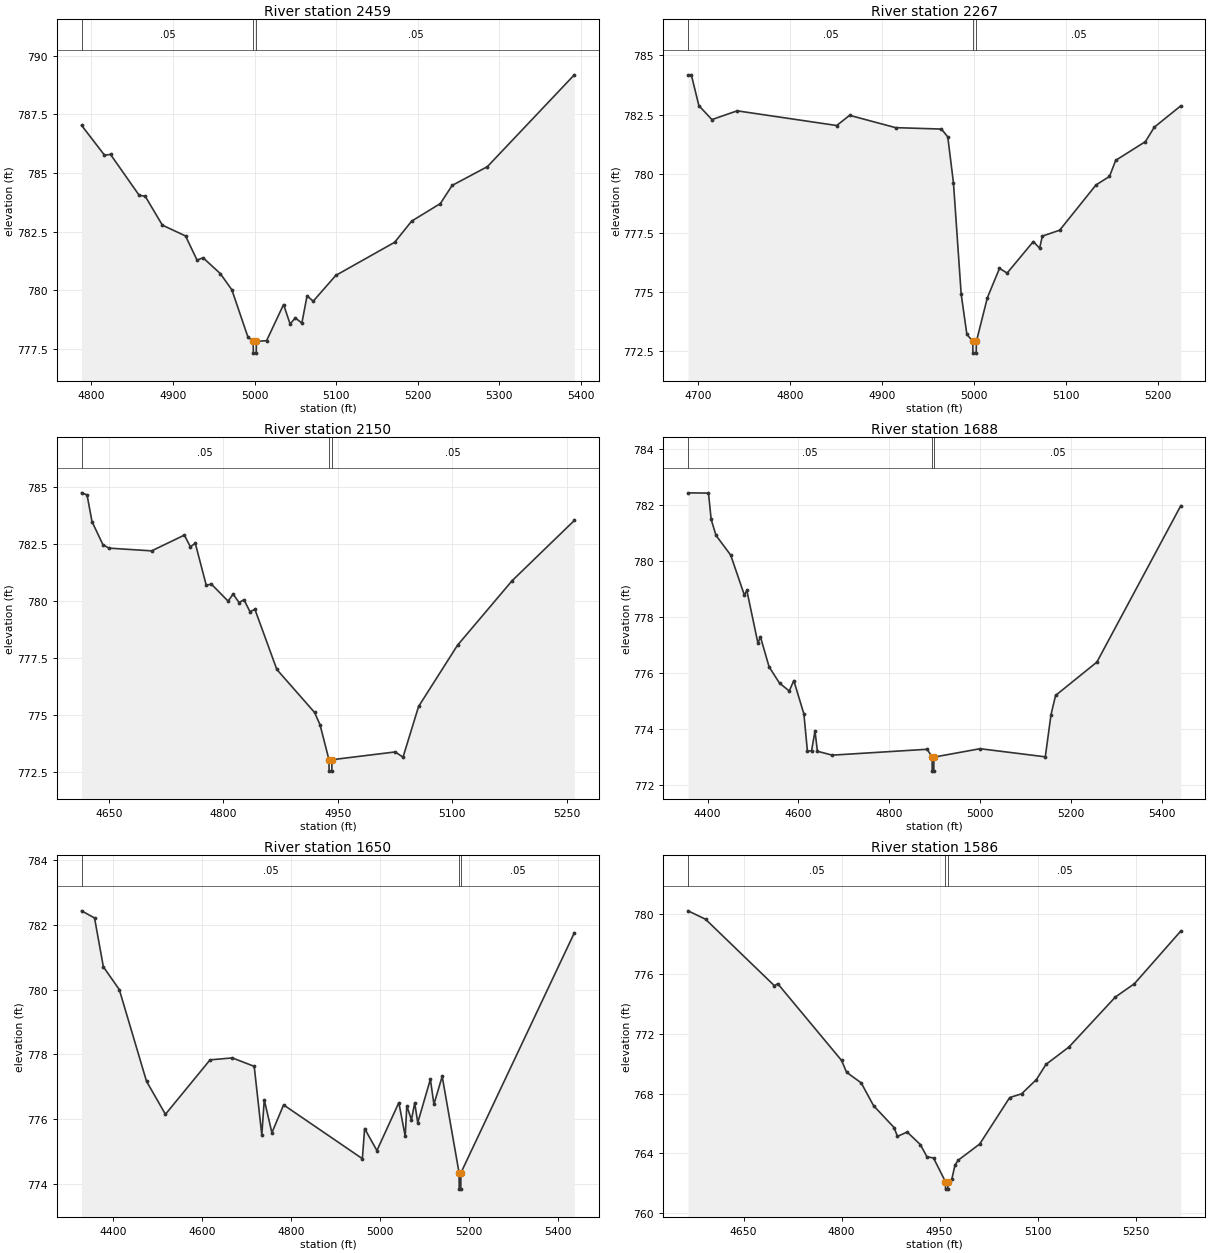
Type RM Length L Ch R = 1,2459,192,192,192
BEGIN DESCRIPTION:
Denton Creek Tributary 31_1_1 9.0
END DESCRIPTION:
XS GIS Cut Line= 3
      2319928.97      7127009.98      2320082.13      7127150.81
      2320328.99      7127459.98
#Sta/Elev= 30
  4788.1  787.03  4816.2  785.76  4823.6  785.79  4858.7  784.05  4866.1  784.01
  4887.1  782.78  4915.5  782.32  4929.6  781.29  4937.0  781.39  4958.0  780.72
  4972.2  780.03  4991.9  778.02  4998.3  777.83  4998.6  777.33  5002.1  777.33
  5002.3  777.83  5014.8  777.86  5035.6  779.40  5043.6  778.57  5050.0  778.83
  5058.0  778.61  5064.4  779.77  5071.9  779.54  5099.6  780.64  5171.7  782.05
  5192.5  782.95  5227.7  783.70  5242.1  784.47  5285.3  785.27  5391.8  789.18
#Mann=3,-1,0
  4788.1    0.05       0  4998.3   0.033       0  5002.3    0.05       0
Bank Sta=4998.3,5002.3
Exp/Cntr=0.3,0.1

Type RM Length L Ch R = 1,2267,117,117,117
BEGIN DESCRIPTION:
Mapping XS 3294ef1e
END DESCRIPTION:
XS GIS Cut Line= 3
      2319794.18      7127059.21      2320026.58      7127369.54
      2320164.84      7127423.97
#Sta/Elev= 30
  4688.8  784.18  4692.4  784.18  4700.6  782.88  4714.8  782.29  4742.3  782.66
  4850.6  782.04  4864.7  782.47  4914.7  781.95  4964.6  781.89  4971.5  781.56
  4977.7  779.62  4986.1  774.92  4992.3  773.22  4998.7  772.93  4998.9  772.43
  5002.4  772.43  5002.7  772.93  5014.6  774.77  5027.8  776.01  5036.1  775.81
  5064.6  777.14  5071.5  776.86  5074.4  777.37  5093.3  777.62  5132.8  779.53
  5147.5  779.89  5154.3  780.57  5186.6  781.36  5196.3  781.97  5225.1  782.87
#Mann=3,-1,0
  4688.8    0.05       0  4998.7   0.033       0  5002.7    0.05       0
Bank Sta=4998.7,5002.7
Exp/Cntr=0.3,0.1

Type RM Length L Ch R = 1,2150,462,462,462
BEGIN DESCRIPTION:
Denton Creek Tributary 31_1_1 8.0
END DESCRIPTION:
XS GIS Cut Line= 3
      2319679.00      7127110.00      2319929.00      7127410.00
      2320179.04      7127460.01
#Sta/Elev= 30
  4614.4  784.73  4621.6  784.64  4628.1  783.47  4642.4  782.46  4650.2  782.31
  4706.2  782.19  4749.1  782.88  4756.9  782.37  4763.4  782.52  4777.8  780.68
  4784.3  780.74  4806.4  779.99  4812.9  780.30  4820.7  779.93  4827.2  780.05
  4835.0  779.53  4841.5  779.63  4870.2  777.00  4919.6  775.12  4926.8  774.58
  4938.5  773.05  4938.7  772.55  4942.2  772.55  4942.5  773.05  5025.3  773.39
  5035.5  773.16  5055.9  775.38  5106.9  778.06  5178.3  780.88  5259.9  783.52
#Mann=3,-1,0
  4614.4    0.05       0  4938.5   0.033       0  4942.5    0.05       0
Bank Sta=4938.5,4942.5
Exp/Cntr=0.3,0.1

Type RM Length L Ch R = 1,1688,38,38,38
BEGIN DESCRIPTION:
Mapping XS f65afc1d
END DESCRIPTION:
XS GIS Cut Line= 6
      2319707.81      7127172.58      2319804.43      7127420.36
      2319640.14      7127470.51      2319611.93      7127654.61
      2319701.60      7127740.00      2320031.89      7127783.87
#Sta/Elev= 30
  4357.1  782.43  4402.1  782.42  4408.0  781.48  4418.7  780.91  4450.9  780.21
  4481.0  778.78  4486.4  778.95  4510.9  777.06  4516.2  777.30  4535.4  776.22
  4558.3  775.64  4579.7  775.36  4589.7  775.73  4611.9  774.54  4619.6  773.22
  4628.7  773.22  4636.3  773.93  4641.6  773.21  4674.1  773.07  4883.1  773.28
  4893.8  773.00  4894.0  772.50  4897.5  772.50  4897.8  773.00  4999.4  773.30
  5142.7  773.01  5155.2  774.51  5165.3  775.20  5256.1  776.39  5440.6  781.97
#Mann=3,-1,0
  4357.1    0.05       0  4893.8   0.033       0  4897.8    0.05       0
Bank Sta=4893.8,4897.8
Exp/Cntr=0.3,0.1

Type RM Length L Ch R = 1,1650,64,64,64
BEGIN DESCRIPTION:
Mapping XS 82a9ebc8
END DESCRIPTION:
XS GIS Cut Line= 6
      2319695.68      7127182.79      2319773.06      7127394.04
      2319631.07      7127401.58      2319589.78      7127684.23
      2319680.42      7127780.02      2319979.74      7127861.22
#Sta/Elev= 30
  4328.4  782.43  4357.6  782.21  4377.5  780.70  4413.3  780.00  4474.5  777.17
  4517.1  776.15  4617.5  777.83  4667.6  777.89  4716.8  777.63  4733.9  775.51
  4739.4  776.60  4756.6  775.58  4782.9  776.44  4960.1  774.78  4965.2  775.71
  4992.8  775.03  5042.2  776.51  5056.5  775.47  5060.1  776.41  5070.5  775.98
  5077.9  776.50  5084.7  775.89  5113.1  777.23  5121.1  776.46  5139.7  777.32
  5177.7  774.34  5178.0  773.84  5181.5  773.84  5181.7  774.34  5436.9  781.75
#Mann=3,-1,0
  4328.4    0.05       0  5177.7   0.033       0  5181.7    0.05       0
Bank Sta=5177.7,5181.7
Exp/Cntr=0.3,0.1

Type RM Length L Ch R = 1,1586,224,224,224
BEGIN DESCRIPTION:
Mapping XS 838e9404
END DESCRIPTION:
XS GIS Cut Line= 5
      2319546.21      7127275.97      2319520.16      7127562.70
      2319535.14      7127690.13      2319547.41      7127765.58
      2319703.73      7127975.38
#Sta/Elev= 30
  4564.9  780.19  4591.7  779.63  4697.2  775.19  4702.2  775.33  4799.9  770.21
  4807.6  769.42  4830.0  768.71  4848.9  767.19  4880.3  765.73  4885.5  765.14
  4900.4  765.43  4920.6  764.59  4930.6  763.78  4940.7  763.70  4958.9  762.12
  4959.1  761.62  4962.6  761.62  4962.9  762.12  4968.6  762.27  4973.7  763.24
  4978.5  763.55  5011.4  764.63  5057.3  767.73  5075.5  767.98  5098.2  768.93
  5112.8  769.94  5148.2  771.11  5219.1  774.44  5248.3  775.33  5319.2  778.84
#Mann=3,-1,0
  4564.9    0.05       0  4958.9   0.033       0  4962.9    0.05       0
Bank Sta=4958.9,4962.9
Exp/Cntr=0.3,0.1

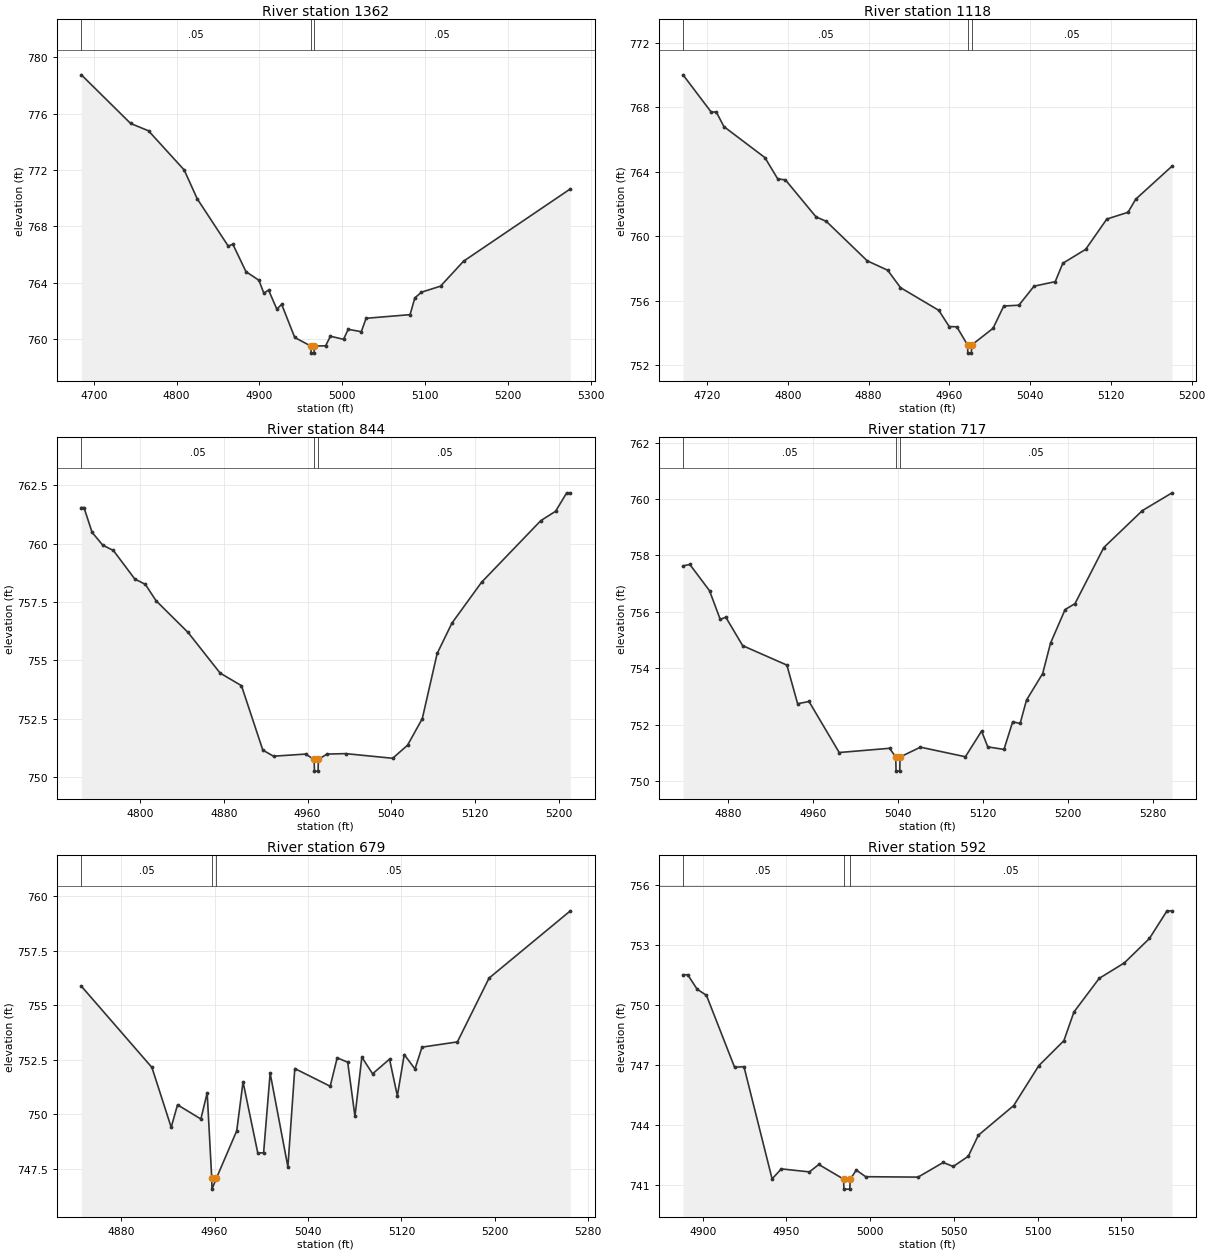
Type RM Length L Ch R = 1,1362,244,244,244
BEGIN DESCRIPTION:
Mapping XS 586c3e14
END DESCRIPTION:
XS GIS Cut Line= 2
      2319193.75      7127464.31      2319488.97      7127975.83
#Sta/Elev= 30
  4684.9  778.75  4744.4  775.30  4766.0  774.78  4809.1  772.00  4824.8  769.96
  4862.2  766.61  4867.9  766.73  4883.7  764.79  4899.3  764.18  4905.3  763.26
  4911.0  763.48  4921.0  762.13  4926.8  762.47  4942.6  760.12  4962.1  759.51
  4962.4  759.01  4965.9  759.01  4966.1  759.51  4979.9  759.53  4985.7  760.21
  5001.5  759.99  5007.2  760.70  5023.0  760.53  5028.8  761.48  5081.9  761.74
  5087.7  762.93  5095.6  763.33  5118.7  763.76  5146.5  765.53  5275.5  770.66
#Mann=3,-1,0
  4684.9    0.05       0  4962.1   0.033       0  4966.1    0.05       0
Bank Sta=4962.1,4966.1
Exp/Cntr=0.3,0.1

Type RM Length L Ch R = 1,1118,274,274,274
BEGIN DESCRIPTION:
Denton Creek Tributary 31_1_1 4.0
END DESCRIPTION:
XS GIS Cut Line= 3
      2319129.00      7127610.01      2319179.00      7127910.00
      2319328.99      7128010.00
#Sta/Elev= 30
  4696.1  770.01  4724.0  767.70  4729.0  767.71  4736.6  766.80  4777.2  764.88
  4789.9  763.56  4797.5  763.50  4827.9  761.20  4838.0  760.93  4878.6  758.48
  4898.8  757.90  4911.5  756.82  4949.5  755.41  4959.7  754.41  4967.3  754.39
  4978.0  753.26  4978.2  752.76  4981.7  752.76  4982.0  753.26  5003.2  754.30
  5013.8  755.68  5028.8  755.73  5043.8  756.91  5064.8  757.19  5072.3  758.33
  5094.9  759.19  5115.9  761.07  5136.9  761.49  5144.5  762.30  5180.5  764.35
#Mann=3,-1,0
  4696.1    0.05       0  4978.0   0.033       0  4982.0    0.05       0
Bank Sta=4978,4982
Exp/Cntr=0.3,0.1

Type RM Length L Ch R = 1,844,127,127,127
BEGIN DESCRIPTION:
Denton Creek Tributary 31_1_1 3.0
END DESCRIPTION:
XS GIS Cut Line= 3
      2318929.01      7127810.04      2318979.00      7128060.00
      2319128.97      7128209.97
#Sta/Elev= 30
  4744.0  761.55  4746.5  761.55  4754.2  760.49  4764.4  759.94  4774.6  759.71
  4795.0  758.49  4805.1  758.26  4815.3  757.56  4845.9  756.20  4876.5  754.46
  4896.9  753.92  4917.3  751.16  4927.5  750.90  4958.1  750.99  4966.3  750.76
  4966.6  750.26  4970.1  750.26  4970.3  750.76  4978.5  750.99  4996.4  751.01
  5041.3  750.81  5055.5  751.37  5069.6  752.51  5083.8  755.30  5097.9  756.60
  5126.2  758.35  5182.8  760.99  5196.9  761.39  5207.5  762.18  5211.0  762.18
#Mann=3,-1,0
  4744.0    0.05       0  4966.3   0.033       0  4970.3    0.05       0
Bank Sta=4966.3,4970.3
Exp/Cntr=0.3,0.1

Type RM Length L Ch R = 1,717,38,38,38
BEGIN DESCRIPTION:
Mapping XS d60a3386
END DESCRIPTION:
XS GIS Cut Line= 3
      2318823.06      7127866.01      2318875.57      7128050.00
      2319020.45      7128276.25
#Sta/Elev= 30
  4837.7  757.63  4844.1  757.68  4862.6  756.75  4872.7  755.73  4877.9  755.81
  4893.8  754.80  4935.4  754.11  4945.5  752.74  4956.2  752.82  4984.6  751.01
  5032.0  751.16  5037.8  750.85  5038.1  750.35  5041.6  750.35  5041.8  750.85
  5061.0  751.20  5103.3  750.86  5118.5  751.77  5124.4  751.21  5139.6  751.12
  5147.8  752.10  5154.8  752.04  5160.8  752.87  5176.0  753.81  5183.4  754.89
  5197.1  756.08  5206.4  756.29  5233.5  758.28  5269.8  759.59  5297.7  760.22
#Mann=3,-1,0
  4837.7    0.05       0  5037.8   0.033       0  5041.8    0.05       0
Bank Sta=5037.8,5041.8
Exp/Cntr=0.3,0.1

Type RM Length L Ch R = 1,679,87,87,87
BEGIN DESCRIPTION:
Mapping XS f94e426c
END DESCRIPTION:
XS GIS Cut Line= 3
      2318787.75      7127903.15      2318838.99      7128045.55
      2318983.92      7128270.10
#Sta/Elev= 30
  4846.0  755.87  4906.4  752.15  4922.9  749.41  4928.3  750.44  4948.3  749.79
  4953.7  750.99  4957.6  747.08  4957.8  746.58  4961.6  747.08  4979.0  749.25
  4984.4  751.49  4997.0  748.24  5002.0  748.24  5007.6  751.89  5022.8  747.60
  5028.7  752.10  5059.0  751.29  5065.0  752.59  5074.0  752.39  5080.2  749.91
  5086.1  752.62  5095.3  751.86  5109.8  752.53  5116.5  750.85  5122.4  752.74
  5131.6  752.08  5137.6  753.08  5167.9  753.32  5195.0  756.24  5264.6  759.32
#Mann=3,-1,0
  4846.0    0.05       0  4957.6   0.033       0  4961.6    0.05       0
Bank Sta=4957.6,4961.6
Exp/Cntr=0.3,0.1

Type RM Length L Ch R = 1,592,102,102,102
BEGIN DESCRIPTION:
Denton Creek Tributary 31_1_1 2.0
END DESCRIPTION:
XS GIS Cut Line= 3
      2318728.98      7128009.96      2318779.00      7128110.00
      2318928.98      7128209.98
#Sta/Elev= 30
  4888.2  751.50  4891.0  751.50  4896.6  750.78  4902.2  750.47  4919.0  746.88
  4924.6  746.91  4941.4  741.31  4946.9  741.81  4963.7  741.66  4969.3  742.03
  4984.1  741.30  4984.3  740.80  4987.8  740.80  4988.1  741.30  4991.7  741.75
  4997.3  741.42  5028.6  741.40  5043.6  742.13  5049.6  741.93  5058.6  742.44
  5064.6  743.49  5085.7  744.97  5100.7  746.96  5115.7  748.21  5121.7  749.64
  5136.8  751.32  5151.8  752.09  5166.8  753.31  5177.3  754.69  5180.3  754.69
#Mann=3,-1,0
  4888.2    0.05       0  4984.1   0.033       0  4988.1    0.05       0
Bank Sta=4984.1,4988.1
Exp/Cntr=0.3,0.1

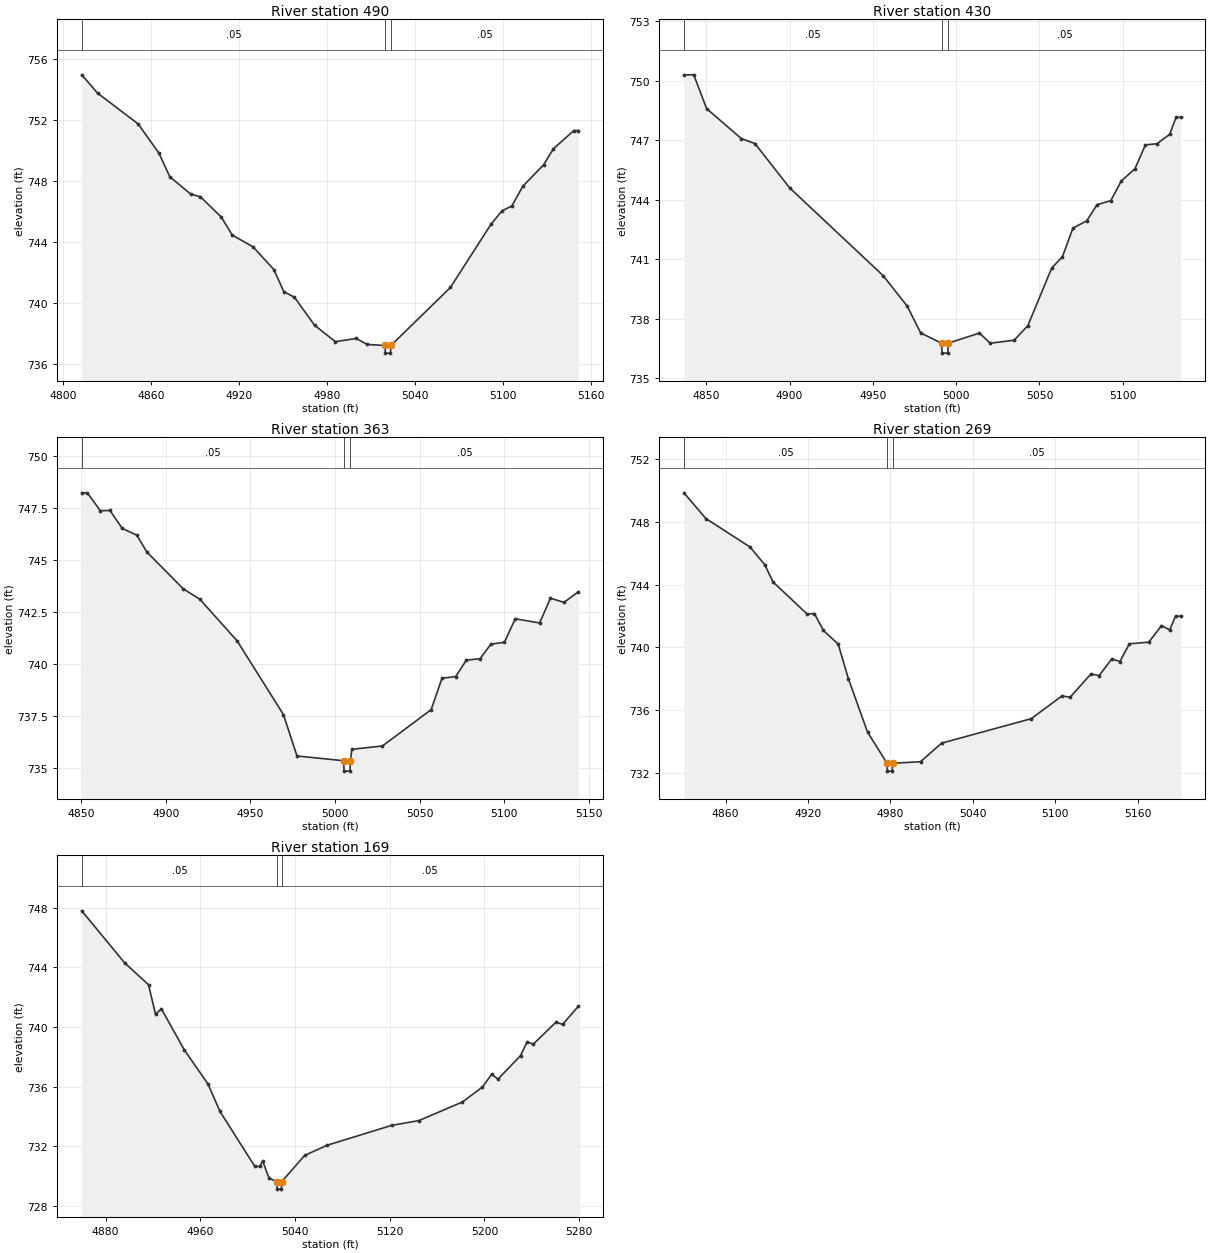
Type RM Length L Ch R = 1,490,60,60,60
BEGIN DESCRIPTION:
Mapping XS 3acd5fb3
END DESCRIPTION:
XS GIS Cut Line= 2
      2318582.62      7128041.71      2318808.18      7128294.51
#Sta/Elev= 30
  4812.5  754.95  4823.3  753.75  4850.9  751.74  4865.1  749.83  4872.6  748.27
  4886.8  747.14  4893.5  746.96  4907.7  745.63  4915.2  744.45  4929.4  743.68
  4943.6  742.19  4950.3  740.75  4957.6  740.38  4971.3  738.55  4985.5  737.47
  4999.7  737.68  5007.2  737.29  5019.4  737.22  5019.6  736.72  5023.1  736.72
  5023.4  737.22  5064.0  741.02  5091.6  745.15  5099.2  746.04  5105.9  746.36
  5113.4  747.65  5127.6  749.06  5134.3  750.11  5148.2  751.30  5151.3  751.30
#Mann=3,-1,0
  4812.5    0.05       0  5019.4   0.033       0  5023.4    0.05       0
Bank Sta=5019.4,5023.4
Exp/Cntr=0.3,0.1

Type RM Length L Ch R = 1,430,67,67,67
BEGIN DESCRIPTION:
Mapping XS 1c1f049b
END DESCRIPTION:
XS GIS Cut Line= 2
      2318564.57      7128095.67      2318747.33      7128331.17
#Sta/Elev= 30
  4836.6  750.29  4842.5  750.29  4850.2  748.59  4871.0  747.08  4879.2  746.83
  4900.0  744.60  4956.1  740.18  4970.6  738.64  4978.7  737.29  4991.2  736.77
  4991.5  736.27  4995.0  736.27  4995.2  736.77  5014.0  737.28  5020.4  736.77
  5034.8  736.92  5043.0  737.65  5057.3  740.55  5063.8  741.13  5070.1  742.57
  5078.3  742.93  5084.6  743.75  5092.8  743.95  5099.1  744.94  5107.3  745.56
  5113.6  746.76  5120.6  746.82  5128.1  747.29  5132.0  748.15  5134.7  748.15
#Mann=3,-1,0
  4836.6    0.05       0  4991.2   0.033       0  4995.2    0.05       0
Bank Sta=4991.2,4995.2
Exp/Cntr=0.3,0.1

Type RM Length L Ch R = 1,363,94,94,94
BEGIN DESCRIPTION:
Mapping XS 739f2a5e
END DESCRIPTION:
XS GIS Cut Line= 3
      2318536.47      7128129.22      2318615.93      7128269.85
      2318698.01      7128373.20
#Sta/Elev= 30
  4850.3  748.23  4853.6  748.23  4861.3  747.37  4867.0  747.38  4874.2  746.52
  4882.9  746.19  4888.7  745.39  4910.3  743.61  4920.1  743.11  4942.1  741.11
  4969.5  737.56  4977.5  735.57  5005.1  735.34  5005.3  734.84  5008.8  734.84
  5009.1  735.34  5009.9  735.89  5028.0  736.05  5056.8  737.80  5063.2  739.31
  5071.3  739.39  5077.6  740.18  5085.7  740.25  5092.1  740.95  5100.1  741.04
  5106.5  742.17  5120.9  741.97  5127.3  743.16  5135.3  742.96  5143.8  743.47
#Mann=3,-1,0
  4850.3    0.05       0  5005.1   0.033       0  5009.1    0.05       0
Bank Sta=5005.1,5009.1
Exp/Cntr=0.3,0.1

Type RM Length L Ch R = 1,269,100,100,100
BEGIN DESCRIPTION:
Mapping XS 4c401bc4
END DESCRIPTION:
XS GIS Cut Line= 3
      2318470.63      7128145.02      2318532.33      7128307.14
      2318690.27      7128409.55
#Sta/Elev= 30
  4829.6  749.85  4845.6  748.21  4877.7  746.40  4888.4  745.28  4894.5  744.17
  4919.3  742.13  4924.6  742.16  4931.2  741.08  4941.9  740.22  4949.4  738.00
  4963.3  734.61  4977.5  732.62  4977.8  732.12  4981.3  732.12  4981.5  732.62
  5001.9  732.72  5017.2  733.90  5082.5  735.46  5104.9  736.91  5110.9  736.83
  5126.0  738.31  5132.0  738.21  5141.2  739.27  5147.1  739.10  5154.0  740.23
  5168.2  740.34  5177.4  741.39  5183.4  741.12  5187.6  741.99  5191.3  741.99
#Mann=3,-1,0
  4829.6    0.05       0  4977.5   0.033       0  4981.5    0.05       0
Bank Sta=4977.5,4981.5
Exp/Cntr=0.3,0.1

Type RM Length L Ch R = 1,169,0,0,0
BEGIN DESCRIPTION:
Denton Creek Tributary 31_1_1 1.0
END DESCRIPTION:
XS GIS Cut Line= 3
      2318417.03      7128173.93      2318433.64      7128323.42
      2318684.56      7128420.60
#Sta/Elev= 30
  4859.9  747.78  4896.2  744.29  4916.3  742.83  4922.2  740.86  4927.2  741.21
  4946.5  738.47  4966.6  736.17  4976.7  734.34  5006.1  730.66  5010.3  730.66
  5012.7  731.03  5018.1  729.87  5024.8  729.64  5025.0  729.14  5028.5  729.14
  5028.8  729.64  5048.2  731.40  5067.2  732.08  5121.7  733.41  5144.7  733.73
  5181.5  734.98  5198.4  735.98  5206.1  736.83  5211.5  736.51  5230.5  738.08
  5236.0  738.99  5241.4  738.86  5260.6  740.33  5266.0  740.17  5279.4  741.39
#Mann=3,-1,0
  4859.9    0.05       0  5024.8   0.033       0  5028.8    0.05       0
Bank Sta=5024.8,5028.8
Exp/Cntr=0.3,0.1

Chan Stop Cuts=-1