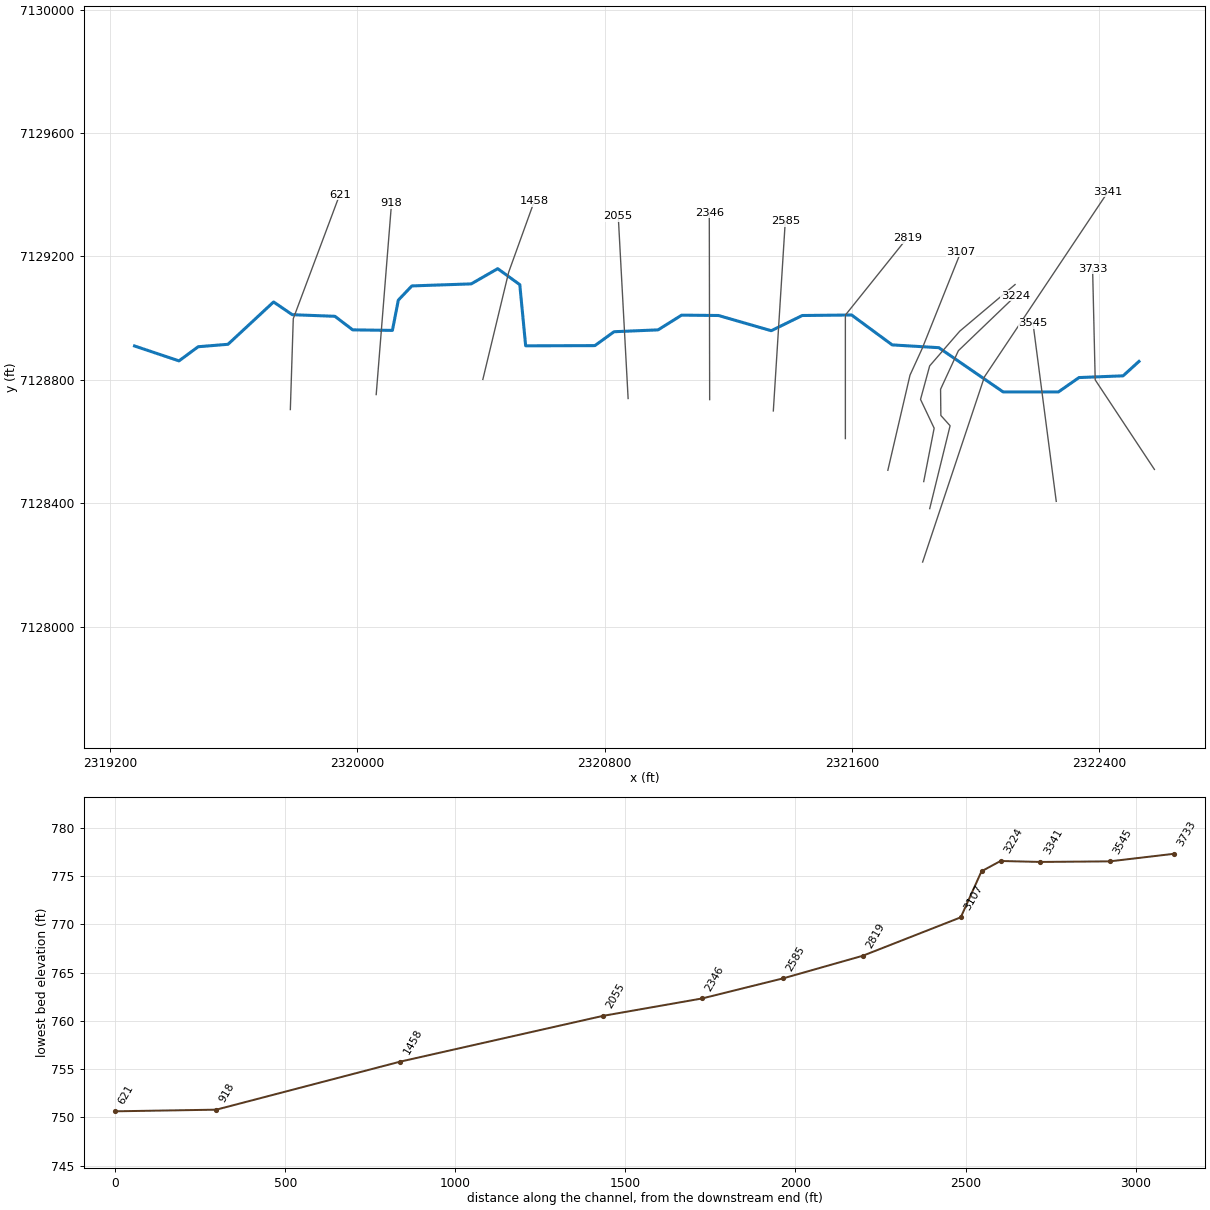
--- Denton Creek Tributary 31_1_2.prj (project) ---

Proj Title=Denton Creek Tributary 31_1_2 Base Level Engineering
Current Plan=p01
Default Exp/Contr=0.3,0.1
English Units
Geom File=g01
Flow File=f01
Plan File=p01
BEGIN DESCRIPTION:
Denton Creek Tributary 31_1_2
END DESCRIPTION:

--- Denton Creek Tributary 31_1_2.p01 (plan) ---

Plan Title=Multiple Run
Short Identifier=Multiple
Geom File=g01
Flow File=f01
Subcritical Flow
K Sum by GR= 0
Std Step Tol= 0.01
Critical Tol= 0.01
Num of Std Step Trials= 20
Max Error Tol= 0.3
Flow Tol Ratio= 0.001
Split Flow NTrial= 30
Split Flow Tol= 0.02
Split Flow Ratio= 0.02
Log Output Level= 0
Friction Slope Method= 1
Unsteady Friction Slope Method= 2
Unsteady Bridges Friction Slope Method= 1
Parabolic Critical Depth
Global Vel Dist=  1 , 1 , 1
Global Log Level= 0
CheckData=True
Encroach Param= -1, 0, 0, 0
BEGIN DESCRIPTION:
Multiple Run
END DESCRIPTION:

--- Denton Creek Tributary 31_1_2.f01 (steady flow) ---

Flow Title=Multiple
Number of Profiles=7
Profile Names=10-year,25-year,50-year,1pct_min,100-year,1pct_plu,500-year
River Rch & RM= Denton Creek Tri,Reach-1,3733
     445     599     724     435     869    1734    1252
Boundary for River Rch & Prof#=Denton Creek Tri,Reach-1,1
Up Type=0
Dn Type=3
Dn Slope=0.005
Boundary for River Rch & Prof#=Denton Creek Tri,Reach-1,2
Up Type=0
Dn Type=3
Dn Slope=0.005
Boundary for River Rch & Prof#=Denton Creek Tri,Reach-1,3
Up Type=0
Dn Type=3
Dn Slope=0.005
Boundary for River Rch & Prof#=Denton Creek Tri,Reach-1,4
Up Type=0
Dn Type=3
Dn Slope=0.005
Boundary for River Rch & Prof#=Denton Creek Tri,Reach-1,5
Up Type=0
Dn Type=3
Dn Slope=0.005
Boundary for River Rch & Prof#=Denton Creek Tri,Reach-1,6
Up Type=0
Dn Type=3
Dn Slope=0.005
Boundary for River Rch & Prof#=Denton Creek Tri,Reach-1,7
Up Type=0
Dn Type=3
Dn Slope=0.005

--- Denton Creek Tributary 31_1_2.g01 (geometry) ---

Geom Title=Existing Conditions

River Reach=Denton Creek Tri,Reach-1
Reach XY= 30
      2322529.00      7128860.00      2322477.63      7128813.30
      2322334.94      7128807.73      2322268.49      7128761.22
      2322089.50      7128761.20      2321881.44      7128904.52
      2321730.47      7128913.56      2321599.18      7129010.43
      2321439.51      7129008.78      2321339.17      7128959.50
      2321168.49      7129008.79      2321049.04      7129009.95
      2320973.06      7128962.27      2320830.57      7128956.21
      2320768.50      7128911.22      2320544.54      7128910.54
      2320525.55      7129108.81      2320454.13      7129160.54
      2320368.50      7129111.24      2320176.27      7129104.65
      2320132.55      7129058.67      2320113.41      7128960.54
      2319984.95      7128962.25      2319927.43      7129006.21
      2319789.44      7129011.40      2319728.90      7129052.68
      2319581.43      7128915.52      2319484.97      7128907.62
      2319422.89      7128861.80      2319279.00      7128910.00

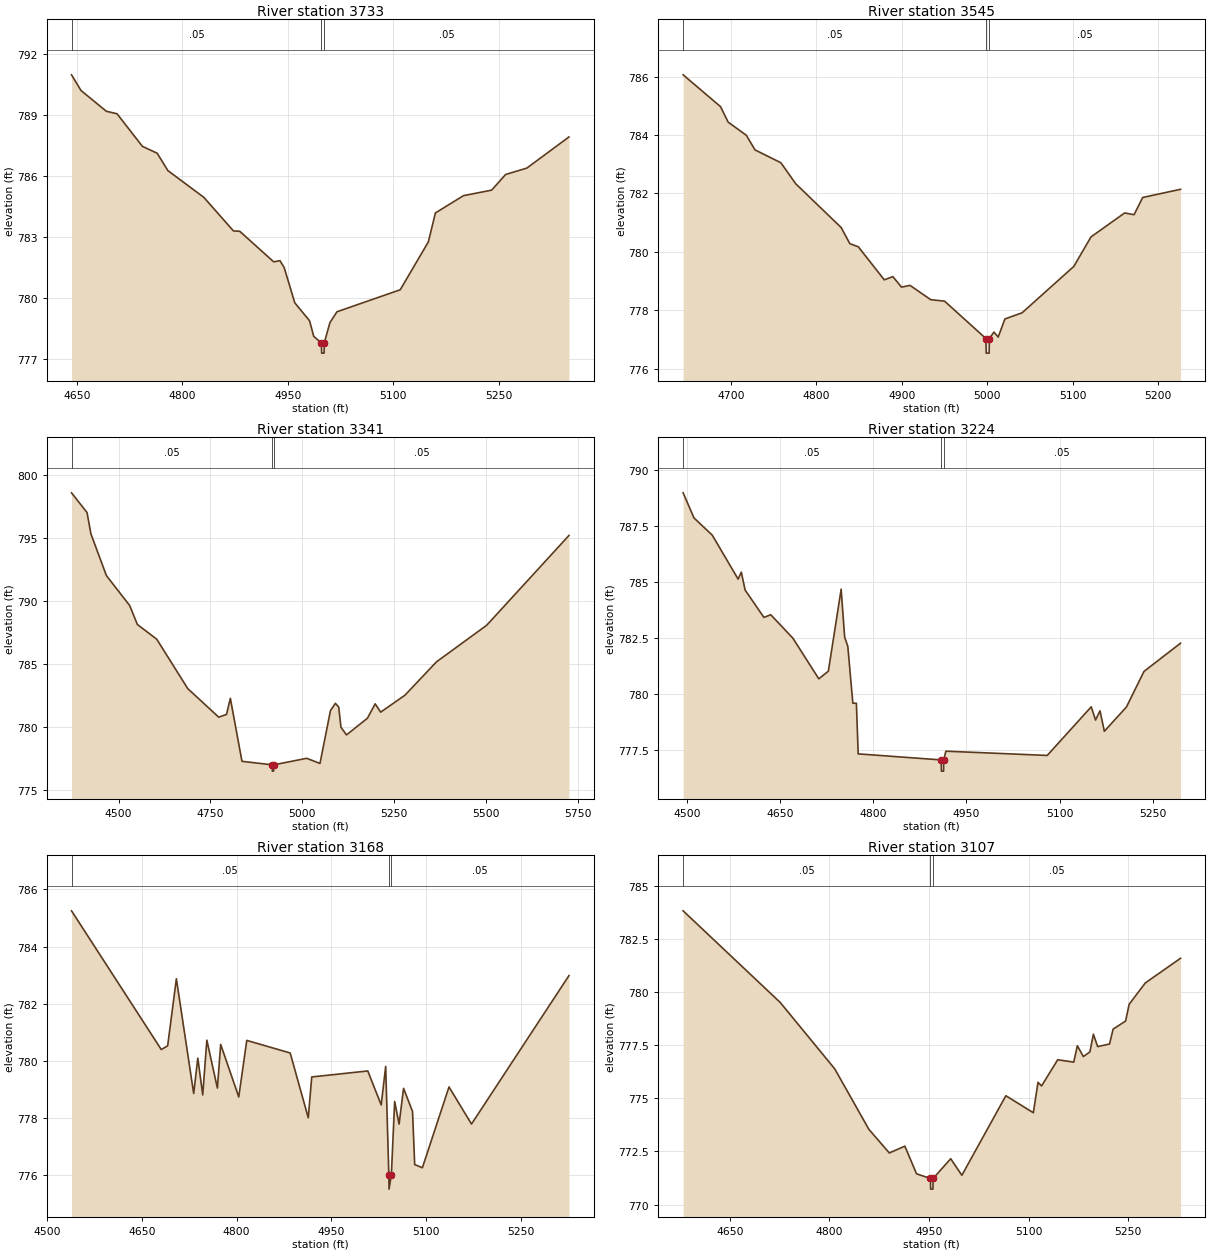
Type RM Length L Ch R = 1,3733,188,188,188
BEGIN DESCRIPTION:
Denton Creek Tributary 31_1_2 9.0
END DESCRIPTION:
XS GIS Cut Line= 3
      2322579.00      7128510.01      2322387.38      7128800.21
      2322379.00      7129159.96
#Sta/Elev= 30
  4642.2  790.97  4655.7  790.20  4691.8  789.18  4706.9  789.06  4743.0  787.46
  4764.1  787.12  4779.2  786.27  4830.3  784.96  4872.5  783.31  4881.5  783.29
  4929.8  781.79  4938.7  781.85  4944.7  781.51  4959.8  779.78  4980.8  778.90
  4986.8  778.13  4997.7  777.81  4998.0  777.31  5001.5  777.31  5001.7  777.81
  5009.8  778.81  5019.8  779.34  5109.8  780.42  5149.8  782.77  5159.8  784.19
  5199.8  785.04  5239.8  785.31  5259.8  786.08  5289.8  786.39  5349.8  787.92
#Mann=3,-1,0
  4642.2    0.05       0  4997.7    0.04       0  5001.7    0.05       0
Bank Sta=4997.7,5001.7
Exp/Cntr=0.3,0.1

Type RM Length L Ch R = 1,3545,204,204,204
BEGIN DESCRIPTION:
Mapping XS 0bad6f0c
END DESCRIPTION:
XS GIS Cut Line= 2
      2322261.32      7128406.58      2322186.07      7128983.90
#Sta/Elev= 30
  4643.9  786.06  4687.7  784.97  4696.6  784.44  4717.9  783.99  4728.0  783.49
  4758.3  783.05  4775.7  782.33  4828.9  780.83  4839.0  780.28  4849.0  780.17
  4879.3  779.04  4889.4  779.15  4899.5  778.79  4909.5  778.85  4933.7  778.36
  4949.9  778.31  4998.3  777.03  4998.6  776.53  5002.1  776.53  5002.3  777.03
  5007.7  777.25  5012.7  777.08  5020.5  777.70  5040.6  777.91  5101.2  779.50
  5121.3  780.51  5160.7  781.33  5171.7  781.27  5181.8  781.86  5226.1  782.14
#Mann=3,-1,0
  4643.9    0.05       0  4998.3    0.04       0  5002.3    0.05       0
Bank Sta=4998.3,5002.3
Exp/Cntr=0.3,0.1

Type RM Length L Ch R = 1,3341,117,117,117
BEGIN DESCRIPTION:
Denton Creek Tributary 31_1_2 8.0
END DESCRIPTION:
XS GIS Cut Line= 3
      2321828.99      7128209.96      2322029.00      7128810.00
      2322428.99      7129409.99
#Sta/Elev= 30
  4372.1  798.60  4414.3  797.03  4424.8  795.34  4467.0  792.02  4530.3  789.64
  4551.3  788.13  4604.0  786.96  4688.4  783.03  4772.7  780.76  4793.8  780.98
  4804.3  782.26  4835.9  777.25  4918.3  776.97  4918.5  776.47  4922.0  776.47
  4922.3  776.97  5012.1  777.49  5048.2  777.08  5076.7  781.28  5090.2  781.86
  5099.2  781.56  5105.3  779.96  5120.3  779.35  5177.4  780.68  5198.4  781.82
  5213.4  781.16  5279.5  782.51  5365.2  785.16  5501.9  788.07  5725.7  795.21
#Mann=3,-1,0
  4372.1    0.05       0  4918.3    0.04       0  4922.3    0.05       0
Bank Sta=4918.3,4922.3
Exp/Cntr=0.3,0.1

Type RM Length L Ch R = 1,3224,56,56,56
BEGIN DESCRIPTION:
Mapping XS a6e593ee
END DESCRIPTION:
XS GIS Cut Line= 6
      2321851.94      7128383.05      2321917.87      7128651.61
      2321887.98      7128684.94      2321887.05      7128769.82
      2321944.72      7128894.86      2322129.75      7129072.52
#Sta/Elev= 30
  4494.2  788.99  4511.7  787.87  4541.1  787.10  4582.7  785.14  4587.8  785.45
  4594.0  784.65  4624.2  783.43  4635.2  783.55  4670.9  782.50  4712.5  780.69
  4727.9  781.03  4748.5  784.69  4754.1  782.55  4759.2  782.14  4767.3  779.60
  4773.0  779.60  4775.9  777.34  4909.5  777.07  4909.8  776.57  4913.3  776.57
  4913.5  777.07  4917.0  777.46  5080.1  777.27  5150.9  779.44  5157.8  778.85
  5165.0  779.26  5172.0  778.35  5207.5  779.43  5235.8  781.02  5294.6  782.28
#Mann=3,-1,0
  4494.2    0.05       0  4909.5    0.04       0  4913.5    0.05       0
Bank Sta=4909.5,4913.5
Exp/Cntr=0.3,0.1

Type RM Length L Ch R = 1,3168,61,61,61
BEGIN DESCRIPTION:
Mapping XS e0415a7c
END DESCRIPTION:
XS GIS Cut Line= 6
      2321832.53      7128470.68      2321866.29      7128643.72
      2321822.21      7128736.91      2321851.77      7128845.54
      2321948.95      7128957.83      2322128.09      7129109.06
#Sta/Elev= 30
  4538.7  785.25  4680.7  780.39  4690.8  780.52  4704.6  782.87  4732.0  778.85
  4738.5  780.09  4746.3  778.80  4752.8  780.72  4769.5  779.04  4774.7  780.57
  4803.3  778.73  4816.0  780.71  4884.7  780.27  4913.3  778.00  4918.8  779.43
  5007.5  779.64  5028.7  778.45  5035.8  779.80  5040.8  776.00  5041.1  775.50
  5044.8  776.00  5050.0  778.57  5057.0  777.78  5064.1  779.03  5078.3  778.22
  5081.7  776.36  5093.9  776.25  5136.0  779.08  5171.6  777.78  5325.8  782.98
#Mann=3,-1,0
  4538.7    0.05       0  5040.8    0.04       0  5044.8    0.05       0
Bank Sta=5040.8,5044.8
Exp/Cntr=0.3,0.1

Type RM Length L Ch R = 1,3107,288,288,288
BEGIN DESCRIPTION:
Mapping XS ee8449a1
END DESCRIPTION:
XS GIS Cut Line= 4
      2321716.48      7128507.40      2321788.14      7128815.56
      2321827.78      7128902.35      2321953.08      7129215.94
#Sta/Elev= 30
  4579.6  783.81  4726.0  779.50  4808.1  776.38  4859.5  773.54  4890.3  772.43
  4913.7  772.75  4931.3  771.45  4952.3  771.23  4952.5  770.73  4956.0  770.73
  4956.3  771.23  4982.8  772.16  4999.6  771.38  5065.9  775.12  5107.3  774.32
  5114.3  775.75  5119.7  775.58  5144.0  776.81  5168.2  776.70  5173.6  777.47
  5182.7  776.96  5192.5  777.18  5197.8  778.01  5204.2  777.43  5222.1  777.55
  5227.5  778.25  5246.3  778.63  5251.7  779.42  5276.0  780.42  5329.1  781.58
#Mann=3,-1,0
  4579.6    0.05       0  4952.3    0.04       0  4956.3    0.05       0
Bank Sta=4952.3,4956.3
Exp/Cntr=0.3,0.1

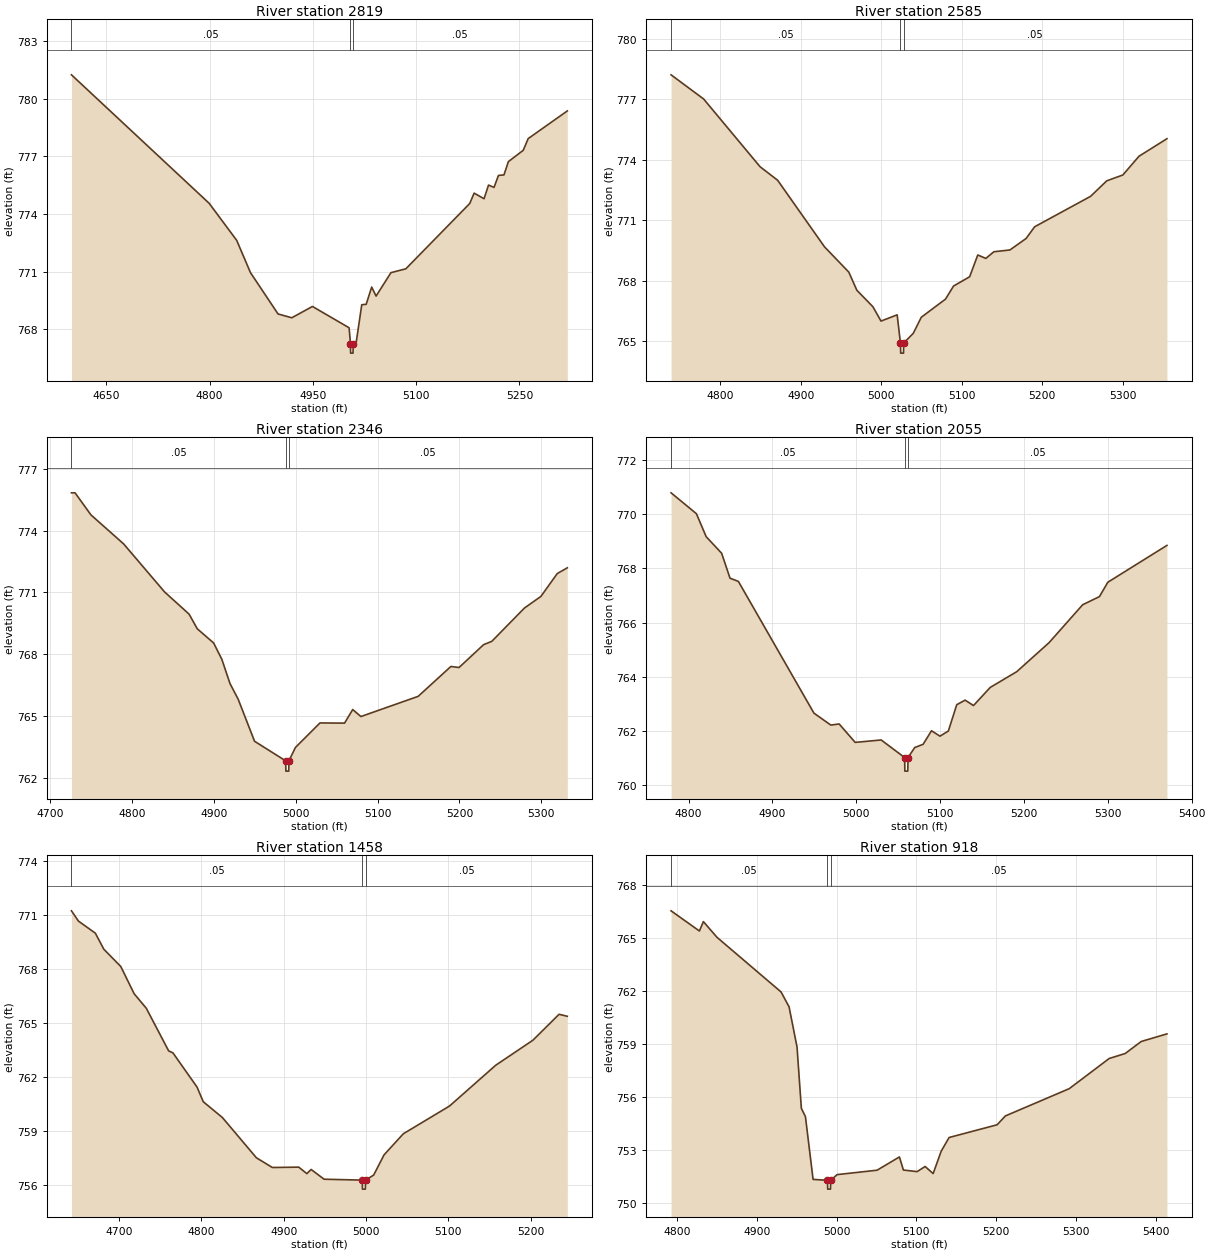
Type RM Length L Ch R = 1,2819,234,234,234
BEGIN DESCRIPTION:
Denton Creek Tributary 31_1_2 6.0
END DESCRIPTION:
XS GIS Cut Line= 3
      2321579.00      7128610.05      2321579.00      7129010.00
      2321779.00      7129259.99
#Sta/Elev= 30
  4599.5  781.24  4799.5  774.55  4839.5  772.62  4859.5  770.94  4899.5  768.79
  4919.5  768.59  4949.5  769.18  5002.7  768.07  5004.7  767.25  5004.9  766.75
  5008.4  766.75  5008.7  767.25  5013.1  767.33  5021.1  769.27  5027.5  769.29
  5035.5  770.19  5041.9  769.72  5063.5  770.94  5085.1  771.14  5177.9  774.54
  5184.3  775.08  5198.7  774.79  5205.2  775.50  5213.2  775.38  5219.6  776.00
  5227.6  776.03  5234.0  776.72  5255.6  777.31  5262.8  777.92  5319.6  779.36
#Mann=3,-1,0
  4599.5    0.05       0  5004.7    0.04       0  5008.7    0.05       0
Bank Sta=5004.7,5008.7
Exp/Cntr=0.3,0.1

Type RM Length L Ch R = 1,2585,239,239,239
BEGIN DESCRIPTION:
Mapping XS d9692e68
END DESCRIPTION:
XS GIS Cut Line= 2
      2321345.89      7128699.58      2321384.61      7129314.67
#Sta/Elev= 30
  4738.7  778.22  4779.2  777.02  4849.3  773.66  4871.1  772.99  4929.5  769.68
  4959.6  768.43  4969.6  767.53  4989.6  766.71  4999.6  766.00  5019.7  766.31
  5023.8  764.91  5024.1  764.41  5027.6  764.41  5027.8  764.91  5039.7  765.39
  5049.7  766.19  5079.8  767.09  5089.8  767.74  5109.8  768.20  5119.9  769.28
  5129.9  769.11  5139.9  769.44  5159.9  769.53  5180.0  770.10  5190.6  770.68
  5260.1  772.19  5280.2  772.96  5300.2  773.25  5320.3  774.18  5355.0  775.05
#Mann=3,-1,0
  4738.7    0.05       0  5023.8    0.04       0  5027.8    0.05       0
Bank Sta=5023.8,5027.8
Exp/Cntr=0.3,0.1

Type RM Length L Ch R = 1,2346,291,291,291
BEGIN DESCRIPTION:
Mapping XS f91f40ed
END DESCRIPTION:
XS GIS Cut Line= 2
      2321139.91      7128736.20      2321138.71      7129342.30
#Sta/Elev= 30
  4725.7  775.83  4730.1  775.83  4749.5  774.76  4789.5  773.35  4839.5  771.02
  4869.5  769.94  4879.5  769.23  4899.5  768.54  4909.5  767.75  4919.5  766.57
  4929.5  765.81  4949.5  763.77  4987.5  762.82  4987.8  762.32  4991.3  762.32
  4991.5  762.82  4999.5  763.47  5029.5  764.66  5059.5  764.65  5069.5  765.31
  5079.5  764.97  5149.5  765.95  5189.5  767.40  5199.5  767.35  5229.5  768.46
  5239.5  768.62  5279.5  770.24  5299.5  770.80  5319.5  771.91  5331.8  772.19
#Mann=3,-1,0
  4725.7    0.05       0  4987.5    0.04       0  4991.5    0.05       0
Bank Sta=4987.5,4991.5
Exp/Cntr=0.3,0.1

Type RM Length L Ch R = 1,2055,597,597,597
BEGIN DESCRIPTION:
Mapping XS ac784039
END DESCRIPTION:
XS GIS Cut Line= 2
      2320876.08      7128739.81      2320844.13      7129330.35
#Sta/Elev= 30
  4779.1  770.79  4809.3  770.02  4821.0  769.17  4839.4  768.56  4849.4  767.64
  4859.4  767.52  4949.5  762.66  4969.6  762.22  4979.6  762.26  4998.7  761.58
  5029.7  761.67  5057.7  761.02  5057.9  760.52  5061.4  760.52  5061.7  761.02
  5069.7  761.39  5079.7  761.51  5089.7  762.01  5099.8  761.81  5109.8  762.00
  5119.8  762.97  5129.8  763.14  5139.8  762.94  5159.8  763.61  5191.4  764.19
  5229.9  765.26  5270.0  766.66  5290.0  766.96  5300.0  767.49  5370.5  768.85
#Mann=3,-1,0
  4779.1    0.05       0  5057.7    0.04       0  5061.7    0.05       0
Bank Sta=5057.7,5061.7
Exp/Cntr=0.3,0.1

Type RM Length L Ch R = 1,1458,540,540,540
BEGIN DESCRIPTION:
Denton Creek Tributary 31_1_2 2.0
END DESCRIPTION:
XS GIS Cut Line= 3
      2320406.04      7128801.77      2320489.56      7129149.00
      2320572.55      7129379.37
#Sta/Elev= 30
  4642.4  771.21  4650.9  770.64  4671.4  769.97  4681.7  769.08  4702.3  768.12
  4718.5  766.61  4733.2  765.81  4760.4  763.44  4765.6  763.33  4794.9  761.43
  4802.4  760.62  4825.7  759.74  4866.9  757.51  4886.3  756.97  4918.3  756.99
  4928.2  756.63  4933.4  756.86  4949.1  756.32  4995.5  756.27  4995.7  755.77
  4999.2  755.77  4999.5  756.27  5009.3  756.55  5021.9  757.67  5045.3  758.84
  5101.4  760.38  5157.4  762.64  5202.6  764.03  5234.4  765.47  5244.4  765.36
#Mann=3,-1,0
  4642.4    0.05       0  4995.5    0.04       0  4999.5    0.05       0
Bank Sta=4995.5,4999.5
Exp/Cntr=0.3,0.1

Type RM Length L Ch R = 1,918,297,297,297
BEGIN DESCRIPTION:
Mapping XS f814394d
END DESCRIPTION:
XS GIS Cut Line= 2
      2320060.93      7128752.58      2320110.54      7129372.10
#Sta/Elev= 30
  4792.6  766.54  4828.1  765.40  4833.1  765.93  4850.2  765.04  4930.5  761.95
  4940.5  761.11  4950.5  758.83  4955.9  755.37  4961.0  754.90  4970.6  751.35
  4988.6  751.30  4988.9  750.80  4992.4  750.80  4992.6  751.30  5000.7  751.62
  5050.8  751.87  5078.8  752.62  5083.8  751.88  5101.0  751.79  5111.0  752.08
  5121.1  751.68  5131.1  752.94  5141.1  753.72  5201.3  754.44  5211.6  754.94
  5291.6  756.48  5341.8  758.19  5361.8  758.47  5381.9  759.15  5414.1  759.58
#Mann=3,-1,0
  4792.6    0.05       0  4988.6    0.04       0  4992.6    0.05       0
Bank Sta=4988.6,4992.6
Exp/Cntr=0.3,0.1

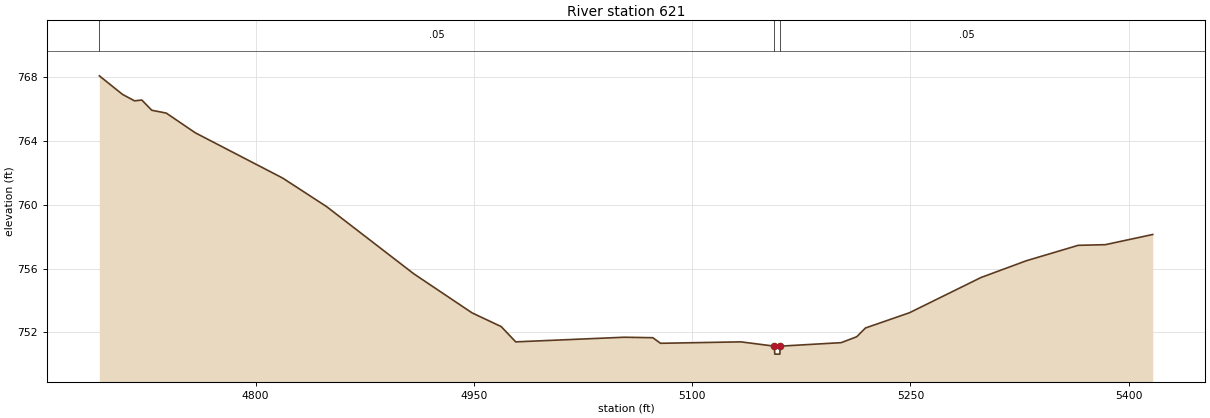
Type RM Length L Ch R = 1,621,0,0,0
BEGIN DESCRIPTION:
Denton Creek Tributary 31_1_2 1.0
END DESCRIPTION:
XS GIS Cut Line= 3
      2319783.12      7128704.05      2319792.63      7128998.52
      2319942.85      7129400.55
#Sta/Elev= 30
  4692.7  768.10  4708.7  766.93  4716.9  766.53  4721.9  766.58  4728.7  765.94
  4738.7  765.76  4758.7  764.52  4818.7  761.68  4848.7  759.90  4908.8  755.67
  4948.8  753.22  4968.8  752.36  4978.8  751.40  5053.3  751.69  5073.0  751.66
  5078.3  751.31  5133.5  751.40  5156.5  751.13  5156.8  750.63  5160.3  750.63
  5160.5  751.13  5202.4  751.35  5213.1  751.72  5219.1  752.27  5249.4  753.23
  5298.5  755.44  5329.6  756.49  5365.3  757.46  5383.9  757.50  5416.5  758.14
#Mann=3,-1,0
  4692.7    0.05       0  5156.5   0.033       0  5160.5    0.05       0
Bank Sta=5156.5,5160.5
Exp/Cntr=0.3,0.1

Chan Stop Cuts=-1