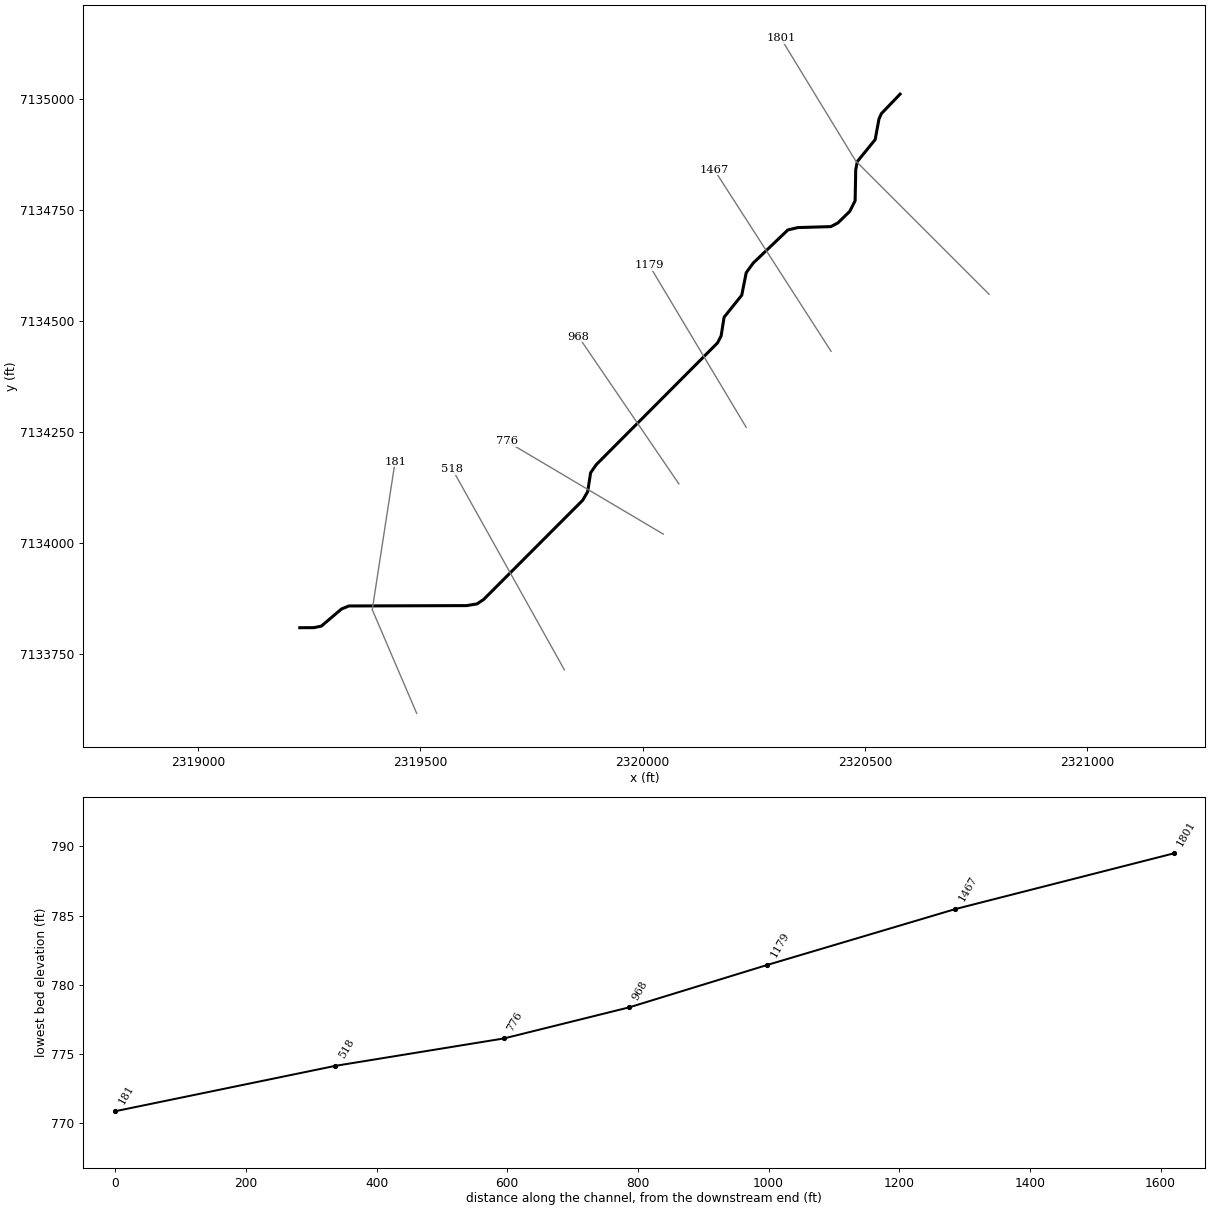
--- Denton Creek Tributary 31_2.prj (project) ---

Proj Title=Denton Creek Tributary 31_2 Base Level Engineering
Current Plan=p01
Default Exp/Contr=0.3,0.1
English Units
Geom File=g01
Flow File=f01
Plan File=p01
BEGIN DESCRIPTION:
Denton Creek Tributary 31_2
END DESCRIPTION:

--- Denton Creek Tributary 31_2.p01 (plan) ---

Plan Title=Multiple Run
Short Identifier=Multiple
Geom File=g01
Flow File=f01
Subcritical Flow
K Sum by GR= 0
Std Step Tol= 0.01
Critical Tol= 0.01
Num of Std Step Trials= 20
Max Error Tol= 0.3
Flow Tol Ratio= 0.001
Split Flow NTrial= 30
Split Flow Tol= 0.02
Split Flow Ratio= 0.02
Log Output Level= 0
Friction Slope Method= 1
Unsteady Friction Slope Method= 2
Unsteady Bridges Friction Slope Method= 1
Parabolic Critical Depth
Global Vel Dist=  1 , 1 , 1
Global Log Level= 0
CheckData=True
Encroach Param= -1, 0, 0, 0
BEGIN DESCRIPTION:
Multiple Run
END DESCRIPTION:

--- Denton Creek Tributary 31_2.f01 (steady flow) ---

Flow Title=Multiple
Number of Profiles=7
Profile Names=10-year,25-year,50-year,1pct_min,100-year,1pct_plu,500-year
River Rch & RM= Denton Creek Tri,Reach-1,1801
     425     568     684     409     817    1630    1167
Boundary for River Rch & Prof#=Denton Creek Tri,Reach-1,1
Up Type=0
Dn Type=3
Dn Slope=0.005
Boundary for River Rch & Prof#=Denton Creek Tri,Reach-1,2
Up Type=0
Dn Type=3
Dn Slope=0.005
Boundary for River Rch & Prof#=Denton Creek Tri,Reach-1,3
Up Type=0
Dn Type=3
Dn Slope=0.005
Boundary for River Rch & Prof#=Denton Creek Tri,Reach-1,4
Up Type=0
Dn Type=3
Dn Slope=0.005
Boundary for River Rch & Prof#=Denton Creek Tri,Reach-1,5
Up Type=0
Dn Type=3
Dn Slope=0.005
Boundary for River Rch & Prof#=Denton Creek Tri,Reach-1,6
Up Type=0
Dn Type=3
Dn Slope=0.005
Boundary for River Rch & Prof#=Denton Creek Tri,Reach-1,7
Up Type=0
Dn Type=3
Dn Slope=0.005

--- Denton Creek Tributary 31_2.g01 (geometry) ---

Geom Title=Existing Conditions

River Reach=Denton Creek Tri,Reach-1
Reach XY= 30
      2320579.00      7135010.00      2320536.91      7134966.15
      2320531.51      7134953.96      2320522.97      7134907.78
      2320482.82      7134858.42      2320479.24      7134839.90
      2320477.91      7134770.31      2320465.77      7134746.28
      2320439.16      7134720.36      2320423.31      7134712.07
      2320349.06      7134709.87      2320326.56      7134704.48
      2320248.77      7134630.13      2320232.94      7134608.38
      2320222.90      7134557.81      2320183.19      7134508.26
      2320176.50      7134466.04      2320168.24      7134450.32
      2319895.65      7134176.67      2319882.98      7134158.35
      2319876.47      7134116.05      2319865.37      7134096.79
      2319642.32      7133873.37      2319627.54      7133863.54
      2319604.12      7133859.70      2319339.46      7133858.88
      2319322.84      7133852.11      2319277.49      7133813.65
      2319260.80      7133810.12      2319229.00      7133810.00

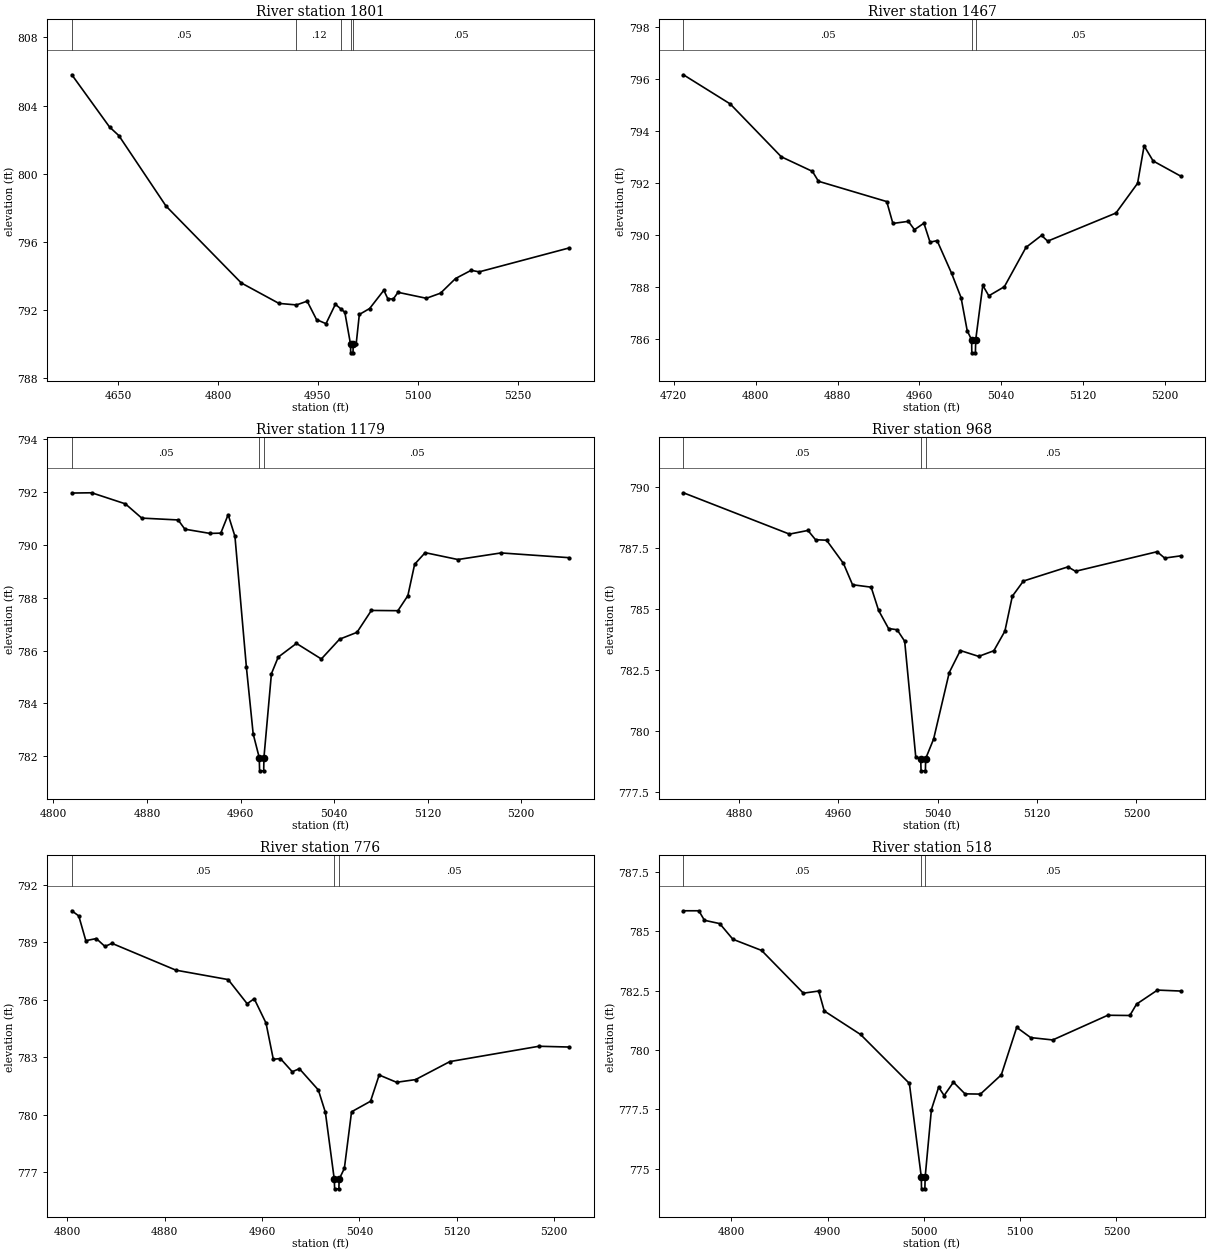
Type RM Length L Ch R = 1,1801,334,334,334
BEGIN DESCRIPTION:
Denton Creek Tributary 31_2 2.0
END DESCRIPTION:
XS GIS Cut Line= 3
      2320779.03      7134559.97      2320479.00      7134860.00
      2320310.89      7135135.46
#Sta/Elev= 30
  4580.3  805.81  4636.9  802.75  4651.0  802.24  4721.8  798.11  4834.9  793.60
  4891.5  792.40  4917.8  792.31  4933.9  792.53  4948.0  791.45  4962.2  791.21
  4976.3  792.35  4984.7  792.07  4990.5  791.88  4999.1  790.00  4999.3  789.50
  5002.8  789.50  5003.1  790.00  5007.5  790.00  5012.3  791.75  5027.8  792.10
  5049.1  793.17  5055.0  792.68  5063.2  792.65  5070.4  793.05  5113.0  792.70
  5134.3  793.00  5156.9  793.86  5180.3  794.34  5192.4  794.25  5327.3  795.65
#Mann=5,-1,0
  4580.3    0.05       0  4917.8    0.12       0  4984.7    0.05       0
  4999.1   0.033       0  5003.1    0.05       0
Bank Sta=4999.1,5003.1
Exp/Cntr=0.3,0.1

Type RM Length L Ch R = 1,1467,288,288,288
BEGIN DESCRIPTION:
Mapping XS 5c294059
END DESCRIPTION:
XS GIS Cut Line= 2
      2320423.80      7134431.60      2320161.04      7134839.97
#Sta/Elev= 30
  4729.5  796.16  4775.2  795.04  4825.1  793.01  4855.5  792.45  4861.4  792.07
  4928.1  791.29  4934.1  790.45  4949.2  790.53  4955.2  790.21  4964.4  790.46
  4970.4  789.73  4977.3  789.79  4991.5  788.53  5000.7  787.60  5006.7  786.33
  5011.0  785.98  5011.2  785.48  5014.7  785.48  5015.0  785.98  5021.9  788.07
  5027.8  787.67  5043.0  788.02  5064.1  789.53  5079.3  789.99  5085.3  789.77
  5152.0  790.85  5173.1  791.99  5179.5  793.43  5188.3  792.85  5215.1  792.27
#Mann=3,-1,0
  4729.5    0.05       0  5011.0   0.033       0  5015.0    0.05       0
Bank Sta=5011,5015
Exp/Cntr=0.3,0.1

Type RM Length L Ch R = 1,1179,211,211,211
BEGIN DESCRIPTION:
Mapping XS b35e1ac4
END DESCRIPTION:
XS GIS Cut Line= 2
      2320232.88      7134260.67      2320014.63      7134625.59
#Sta/Elev= 30
  4815.7  791.97  4832.7  791.98  4861.5  791.56  4875.5  791.02  4906.6  790.95
  4912.4  790.60  4933.8  790.44  4943.1  790.45  4949.4  791.15  4955.2  790.33
  4965.0  785.37  4970.8  782.84  4976.0  781.94  4976.3  781.44  4979.8  781.44
  4980.0  781.94  4986.4  785.12  4992.2  785.75  5007.8  786.27  5029.1  785.68
  5044.7  786.43  5059.6  786.69  5071.9  787.52  5094.6  787.51  5103.1  788.08
  5108.9  789.27  5117.9  789.71  5145.9  789.45  5182.8  789.70  5240.9  789.52
#Mann=3,-1,0
  4815.7    0.05       0  4976.0   0.033       0  4980.0    0.05       0
Bank Sta=4976,4980
Exp/Cntr=0.3,0.1

Type RM Length L Ch R = 1,968,192,192,192
BEGIN DESCRIPTION:
Mapping XS 17430777
END DESCRIPTION:
XS GIS Cut Line= 2
      2320081.47      7134133.49      2319855.94      7134464.34
#Sta/Elev= 30
  4835.2  789.75  4920.6  788.06  4935.5  788.21  4941.6  787.83  4950.5  787.81
  4964.1  786.86  4971.4  785.99  4986.4  785.89  4992.4  784.94  5000.4  784.20
  5007.3  784.15  5013.4  783.68  5022.3  778.96  5026.3  778.88  5026.6  778.38
  5030.1  778.38  5030.3  778.88  5036.7  779.68  5049.3  782.40  5058.2  783.30
  5073.0  783.06  5085.2  783.29  5094.1  784.09  5100.1  785.52  5109.0  786.14
  5144.9  786.72  5151.0  786.54  5216.7  787.34  5222.8  787.08  5235.6  787.17
#Mann=3,-1,0
  4835.2    0.05       0  5026.3   0.033       0  5030.3    0.05       0
Bank Sta=5026.3,5030.3
Exp/Cntr=0.3,0.1

Type RM Length L Ch R = 1,776,258,258,258
BEGIN DESCRIPTION:
Mapping XS 777e8718
END DESCRIPTION:
XS GIS Cut Line= 2
      2320046.33      7134020.54      2319694.80      7134228.82
#Sta/Elev= 30
  4803.7  790.64  4809.4  790.37  4815.2  789.08  4823.8  789.19  4830.9  788.78
  4836.7  788.94  4889.3  787.54  4932.2  787.05  4947.8  785.79  4953.6  786.05
  4963.3  784.78  4969.3  782.89  4975.1  782.93  4984.9  782.24  4990.7  782.40
  5006.3  781.29  5012.1  780.12  5019.4  776.63  5019.7  776.13  5023.2  776.13
  5023.4  776.63  5027.7  777.20  5033.6  780.15  5049.2  780.70  5056.3  782.07
  5070.6  781.69  5086.2  781.83  5114.4  782.77  5187.6  783.57  5212.3  783.53
#Mann=3,-1,0
  4803.7    0.05       0  5019.4   0.033       0  5023.4    0.05       0
Bank Sta=5019.4,5023.4
Exp/Cntr=0.3,0.1

Type RM Length L Ch R = 1,518,337,337,337
BEGIN DESCRIPTION:
Mapping XS ff9f71f1
END DESCRIPTION:
XS GIS Cut Line= 2
      2319824.11      7133715.12      2319572.31      7134165.97
#Sta/Elev= 30
  4750.2  785.86  4766.2  785.86  4772.0  785.46  4787.9  785.32  4801.6  784.66
  4831.4  784.19  4874.8  782.39  4890.7  782.48  4896.5  781.64  4934.2  780.65
  4984.9  778.59  4997.3  774.65  4997.5  774.15  5001.0  774.15  5001.3  774.65
  5007.8  777.49  5015.3  778.43  5021.0  778.08  5030.7  778.64  5042.7  778.15
  5058.7  778.14  5080.4  778.95  5096.4  780.95  5110.9  780.52  5133.8  780.42
  5191.0  781.46  5213.9  781.45  5220.9  781.93  5242.6  782.52  5266.6  782.48
#Mann=3,-1,0
  4750.2    0.05       0  4997.3   0.033       0  5001.3    0.05       0
Bank Sta=4997.3,5001.3
Exp/Cntr=0.3,0.1

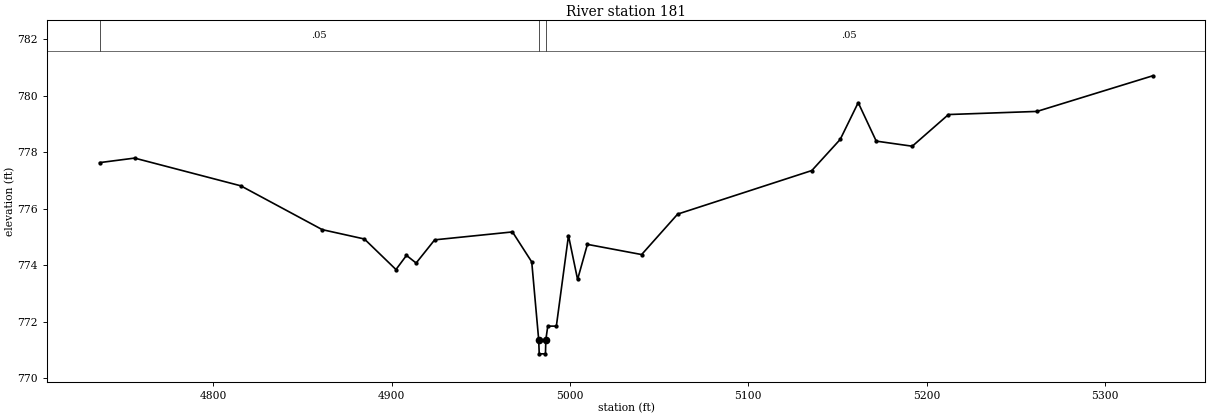
Type RM Length L Ch R = 1,181,0,0,0
BEGIN DESCRIPTION:
Denton Creek Tributary 31_2 1.0
END DESCRIPTION:
XS GIS Cut Line= 3
      2319491.87      7133617.33      2319391.92      7133850.67
      2319443.27      7134183.19
#Sta/Elev= 30
  4736.4  777.63  4756.0  777.79  4815.5  776.81  4861.2  775.26  4884.8  774.93
  4902.5  773.85  4908.4  774.35  4913.8  774.08  4924.2  774.90  4967.8  775.18
  4978.6  774.12  4982.5  771.37  4982.8  770.87  4986.3  770.87  4986.5  771.37
  4987.6  771.85  4992.4  771.85  4999.2  775.05  5004.3  773.50  5009.8  774.74
  5040.2  774.38  5060.4  775.81  5135.6  777.35  5151.5  778.45  5161.6  779.75
  5171.7  778.39  5191.9  778.21  5212.2  779.33  5261.8  779.44  5326.7  780.70
#Mann=3,-1,0
  4736.4    0.05       0  4982.5   0.033       0  4986.5    0.05       0
Bank Sta=4982.5,4986.5
Exp/Cntr=0.3,0.1

Chan Stop Cuts=-1