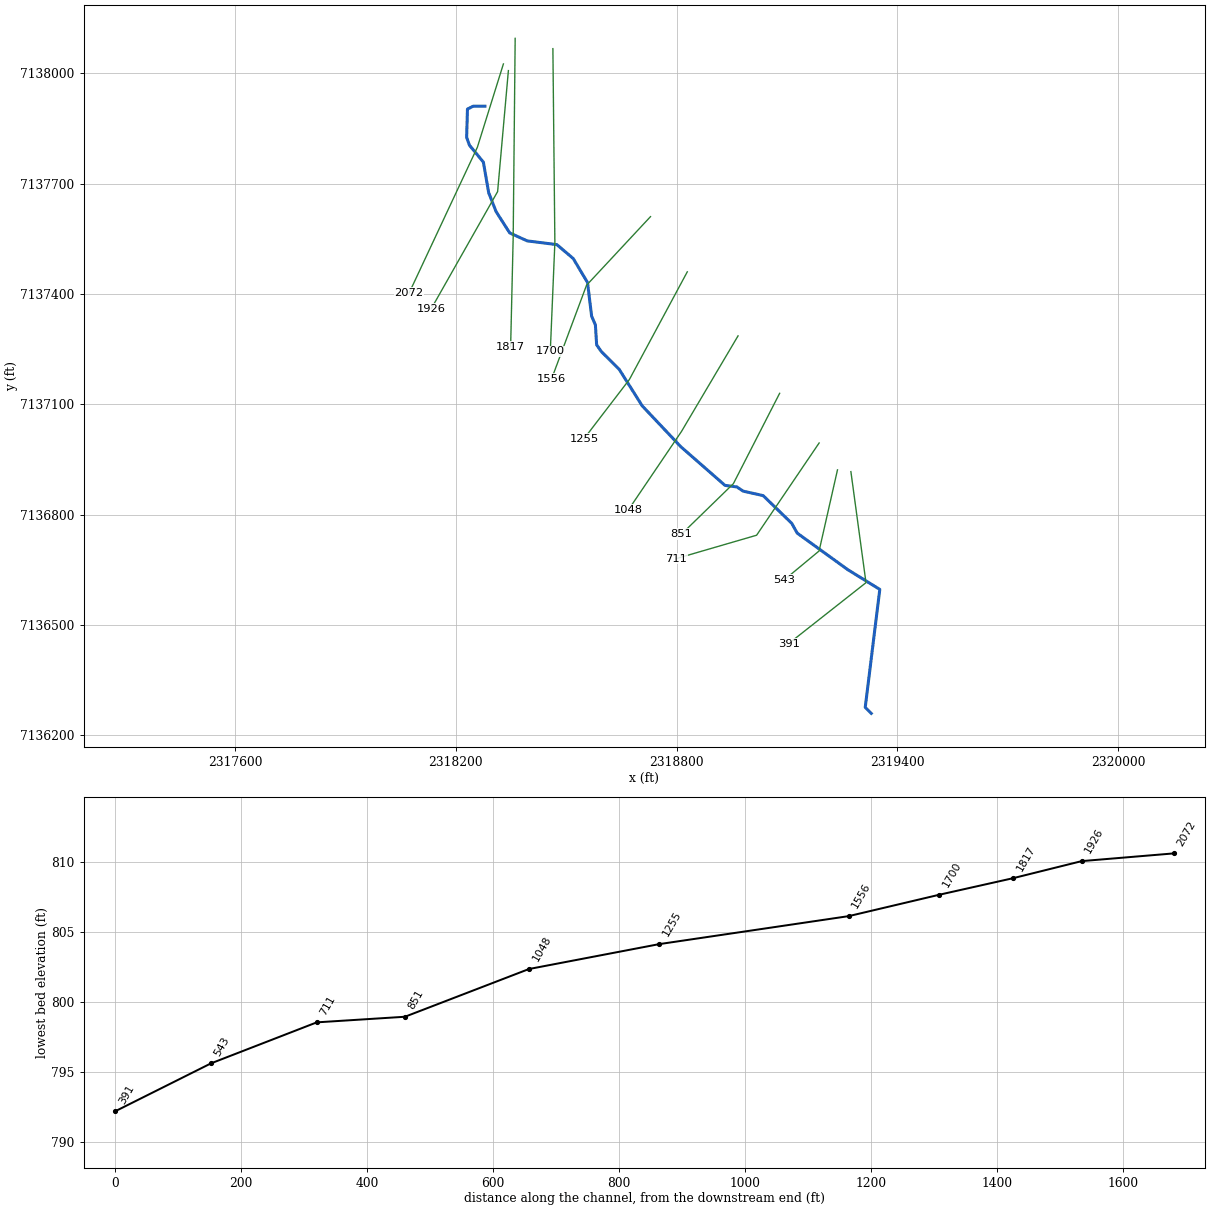
--- Denton Creek Tributary 31_3.prj (project) ---

Proj Title=Denton Creek Tributary 31_3 Base Level Engineering
Current Plan=p01
Default Exp/Contr=0.3,0.1
English Units
Geom File=g01
Flow File=f01
Plan File=p01
BEGIN DESCRIPTION:
Denton Creek Tributary 31_3
END DESCRIPTION:

--- Denton Creek Tributary 31_3.p01 (plan) ---

Plan Title=Multiple Run
Short Identifier=Multiple
Geom File=g01
Flow File=f01
Subcritical Flow
K Sum by GR= 0
Std Step Tol= 0.01
Critical Tol= 0.01
Num of Std Step Trials= 20
Max Error Tol= 0.3
Flow Tol Ratio= 0.001
Split Flow NTrial= 30
Split Flow Tol= 0.02
Split Flow Ratio= 0.02
Log Output Level= 0
Friction Slope Method= 1
Unsteady Friction Slope Method= 2
Unsteady Bridges Friction Slope Method= 1
Parabolic Critical Depth
Global Vel Dist=  1 , 1 , 1
Global Log Level= 0
CheckData=True
Encroach Param= -1, 0, 0, 0
BEGIN DESCRIPTION:
Multiple Run
END DESCRIPTION:

--- Denton Creek Tributary 31_3.f01 (steady flow) ---

Flow Title=Multiple
Number of Profiles=7
Profile Names=10-year,25-year,50-year,1pct_min,100-year,1pct_plu,500-year
River Rch & RM= Denton Creek Tri,Reach-1,2072
     279     364     430     253     505    1008     697
Boundary for River Rch & Prof#=Denton Creek Tri,Reach-1,1
Up Type=0
Dn Type=3
Dn Slope=0.005
Boundary for River Rch & Prof#=Denton Creek Tri,Reach-1,2
Up Type=0
Dn Type=3
Dn Slope=0.005
Boundary for River Rch & Prof#=Denton Creek Tri,Reach-1,3
Up Type=0
Dn Type=3
Dn Slope=0.005
Boundary for River Rch & Prof#=Denton Creek Tri,Reach-1,4
Up Type=0
Dn Type=3
Dn Slope=0.005
Boundary for River Rch & Prof#=Denton Creek Tri,Reach-1,5
Up Type=0
Dn Type=3
Dn Slope=0.005
Boundary for River Rch & Prof#=Denton Creek Tri,Reach-1,6
Up Type=0
Dn Type=3
Dn Slope=0.005
Boundary for River Rch & Prof#=Denton Creek Tri,Reach-1,7
Up Type=0
Dn Type=3
Dn Slope=0.005

--- Denton Creek Tributary 31_3.g01 (geometry) ---

Geom Title=Existing Conditions

River Reach=Denton Creek Tri,Reach-1
Reach XY= 30
      2318279.00      7137910.00      2318246.99      7137910.08
      2318231.56      7137902.24      2318229.31      7137825.32
      2318237.03      7137803.97      2318274.77      7137758.23
      2318289.23      7137675.00      2318309.28      7137623.80
      2318346.33      7137565.74      2318394.01      7137544.08
      2318474.59      7137533.87      2318519.05      7137496.04
      2318557.88      7137430.94      2318569.04      7137339.33
      2318579.20      7137315.86      2318582.64      7137261.57
      2318595.47      7137243.27      2318644.08      7137194.76
      2318706.39      7137095.86      2318810.94      7136985.10
      2318931.53      7136879.55      2318963.76      7136875.40
      2318980.65      7136863.98      2319035.07      7136851.85
      2319112.58      7136776.80      2319127.93      7136749.70
      2319265.22      7136650.54      2319352.14      7136596.91
      2319312.61      7136276.39      2319329.00      7136260.00

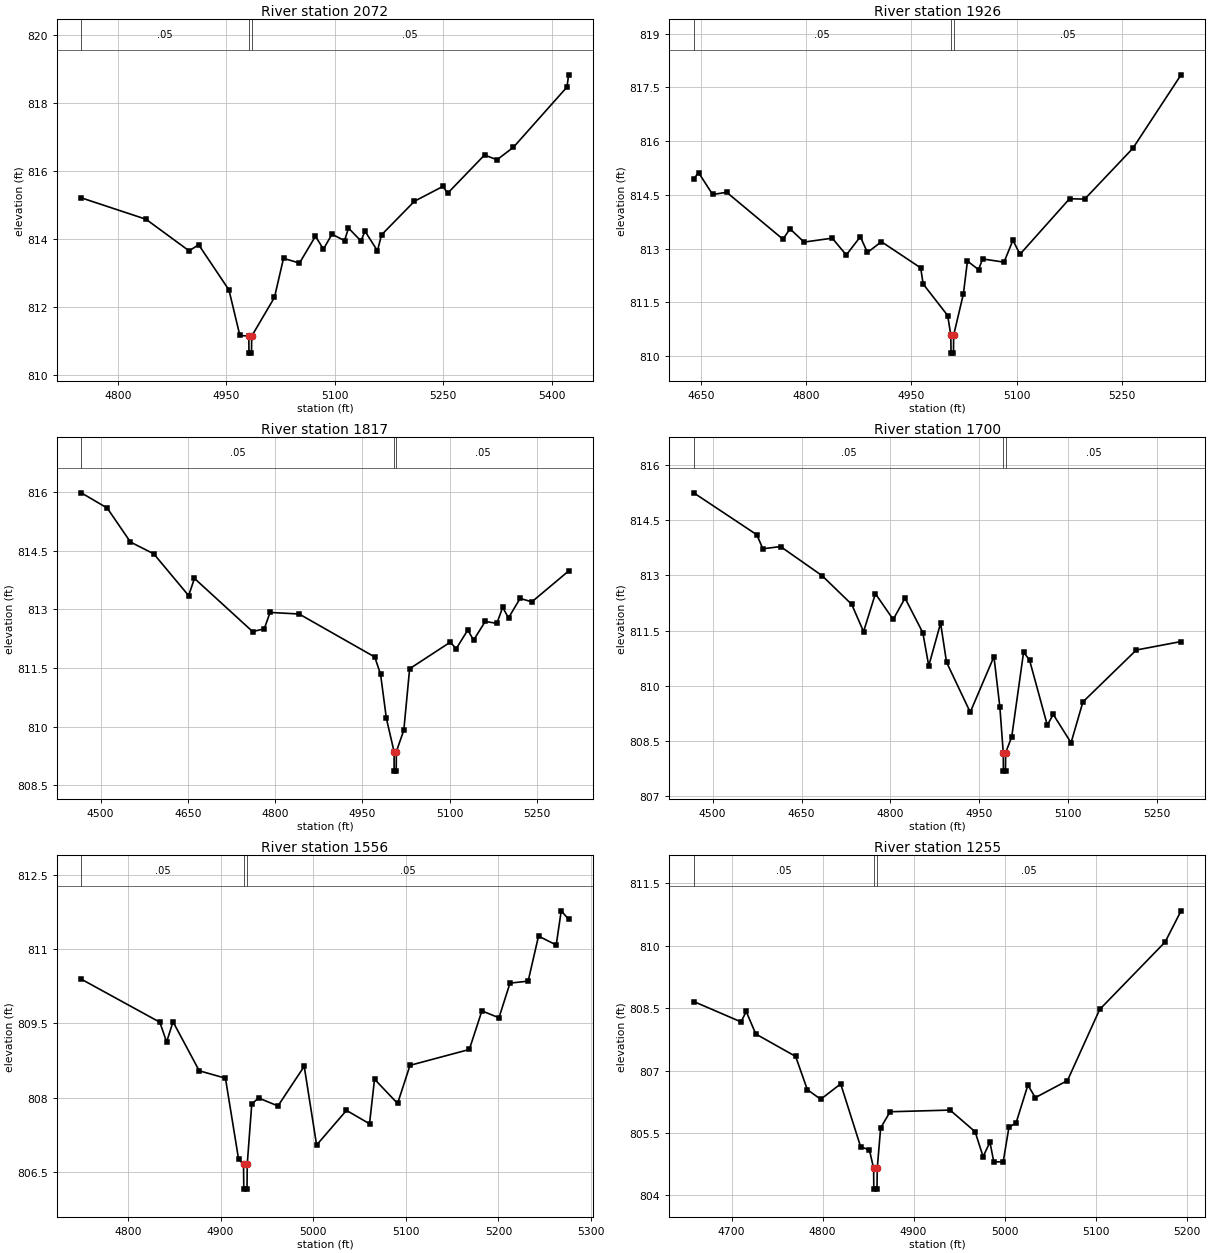
Type RM Length L Ch R = 1,2072,146,146,146
BEGIN DESCRIPTION:
Denton Creek Tributary 31_3 10.0
END DESCRIPTION:
XS GIS Cut Line= 3
      2318329.25      7138025.00      2318258.54      7137798.69
      2318073.15      7137402.74
#Sta/Elev= 30
  4749.1  815.20  4838.6  814.57  4898.3  813.64  4911.5  813.82  4953.4  812.49
  4968.5  811.15  4980.9  811.13  4981.1  810.63  4984.6  810.63  4984.9  811.13
  5016.4  812.27  5028.9  813.42  5051.0  813.28  5073.1  814.07  5084.1  813.69
  5096.0  814.13  5113.3  813.94  5118.8  814.31  5136.1  813.93  5141.6  814.22
  5158.9  813.64  5164.5  814.11  5210.1  815.10  5249.8  815.54  5255.8  815.33
  5307.0  816.46  5324.3  816.32  5347.1  816.69  5421.1  818.46  5423.4  818.82
#Mann=3,-1,0
  4749.1    0.05       0  4980.9   0.033       0  4984.9    0.05       0
Bank Sta=4980.9,4984.9
Exp/Cntr=0.3,0.1

Type RM Length L Ch R = 1,1926,109,109,109
BEGIN DESCRIPTION:
Mapping XS 0f904d07
END DESCRIPTION:
XS GIS Cut Line= 3
      2318342.80      7138006.89      2318313.52      7137678.06
      2318133.48      7137360.24
#Sta/Elev= 30
  4639.3  814.94  4646.2  815.12  4666.3  814.51  4686.4  814.57  4766.7  813.26
  4776.7  813.55  4796.8  813.18  4837.0  813.29  4857.0  812.82  4877.1  813.33
  4887.2  812.89  4907.2  813.19  4963.2  812.46  4966.7  812.01  5001.7  811.13
  5006.2  810.58  5006.5  810.08  5010.0  810.08  5010.2  810.58  5024.1  811.73
  5029.9  812.65  5045.8  812.41  5051.5  812.71  5082.1  812.62  5094.8  813.23
  5104.9  812.84  5175.6  814.39  5197.2  814.38  5266.0  815.80  5334.7  817.85
#Mann=3,-1,0
  4639.3    0.05       0  5006.2   0.033       0  5010.2    0.05       0
Bank Sta=5006.2,5010.2
Exp/Cntr=0.3,0.1

Type RM Length L Ch R = 1,1817,117,117,117
BEGIN DESCRIPTION:
Denton Creek Tributary 31_3 9.0
END DESCRIPTION:
XS GIS Cut Line= 3
      2318361.22      7138094.56      2318355.83      7137554.60
      2318348.89      7137256.67
#Sta/Elev= 30
  4466.8  815.98  4511.4  815.59  4551.4  814.72  4591.4  814.42  4651.4  813.35
  4661.4  813.79  4761.4  812.43  4781.4  812.50  4791.4  812.92  4841.4  812.88
  4971.4  811.78  4981.4  811.34  4991.4  810.21  5004.6  809.36  5004.8  808.86
  5008.3  808.86  5008.6  809.36  5021.4  809.91  5031.4  811.48  5101.4  812.16
  5111.4  811.99  5131.4  812.47  5141.4  812.21  5161.4  812.69  5181.4  812.64
  5191.4  813.05  5201.4  812.78  5221.4  813.28  5241.5  813.19  5304.8  813.98
#Mann=3,-1,0
  4466.8    0.05       0  5004.6   0.033       0  5008.6    0.05       0
Bank Sta=5004.6,5008.6
Exp/Cntr=0.3,0.1

Type RM Length L Ch R = 1,1700,144,144,144
BEGIN DESCRIPTION:
Denton Creek Tributary 31_3 8.0
END DESCRIPTION:
XS GIS Cut Line= 3
      2318463.74      7138066.56      2318469.12      7137539.50
      2318456.72      7137244.54
#Sta/Elev= 30
  4468.0  815.24  4574.6  814.10  4584.6  813.72  4614.6  813.78  4684.6  812.99
  4734.6  812.21  4754.6  811.47  4774.6  812.50  4804.6  811.80  4824.6  812.38
  4854.6  811.44  4864.6  810.54  4884.6  811.70  4894.6  810.64  4934.6  809.28
  4974.6  810.79  4984.6  809.42  4990.3  808.18  4990.6  807.68  4994.1  807.68
  4994.3  808.18  5004.6  808.61  5024.6  810.91  5034.6  810.70  5064.6  808.93
  5074.7  809.22  5104.7  808.45  5124.7  809.56  5214.8  810.97  5290.3  811.20
#Mann=3,-1,0
  4468.0    0.05       0  4990.3   0.033       0  4994.3    0.05       0
Bank Sta=4990.3,4994.3
Exp/Cntr=0.3,0.1

Type RM Length L Ch R = 1,1556,301,301,301
BEGIN DESCRIPTION:
Denton Creek Tributary 31_3 7.0
END DESCRIPTION:
XS GIS Cut Line= 3
      2318729.02      7137610.02      2318555.14      7137423.45
      2318460.41      7137169.58
#Sta/Elev= 30
  4749.7  810.39  4834.5  809.52  4841.8  809.12  4848.7  809.53  4877.0  808.54
  4905.3  808.39  4919.5  806.75  4924.8  806.65  4925.1  806.15  4928.6  806.15
  4928.8  806.65  4933.7  807.87  4941.0  807.99  4962.0  807.83  4990.3  808.63
  5003.7  807.04  5035.9  807.74  5060.8  807.47  5066.2  808.37  5091.1  807.88
  5104.5  808.65  5168.5  808.97  5182.1  809.75  5200.5  809.61  5212.4  810.31
  5232.0  810.35  5243.2  811.26  5262.3  811.08  5267.7  811.77  5275.7  811.60
#Mann=3,-1,0
  4749.7    0.05       0  4924.8   0.033       0  4928.8    0.05       0
Bank Sta=4924.8,4928.8
Exp/Cntr=0.3,0.1

Type RM Length L Ch R = 1,1255,207,207,207
BEGIN DESCRIPTION:
Denton Creek Tributary 31_3 6.0
END DESCRIPTION:
XS GIS Cut Line= 3
      2318829.02      7137460.03      2318671.63      7137167.34
      2318548.05      7137006.07
#Sta/Elev= 30
  4658.4  808.66  4710.4  808.17  4716.1  808.42  4726.6  807.88  4770.4  807.34
  4783.3  806.54  4798.0  806.31  4819.9  806.68  4841.8  805.17  4851.5  805.09
  4856.1  804.65  4856.3  804.15  4859.8  804.15  4860.1  804.65  4863.8  805.62
  4874.2  806.01  4940.1  806.05  4967.6  805.53  4976.4  804.93  4983.9  805.28
  4988.2  804.80  4998.5  804.81  5004.8  805.64  5012.6  805.74  5025.6  806.65
  5033.8  806.35  5069.1  806.76  5104.5  808.47  5176.4  810.09  5193.9  810.84
#Mann=3,-1,0
  4658.4    0.05       0  4856.1   0.033       0  4860.1    0.05       0
Bank Sta=4856.1,4860.1
Exp/Cntr=0.3,0.1

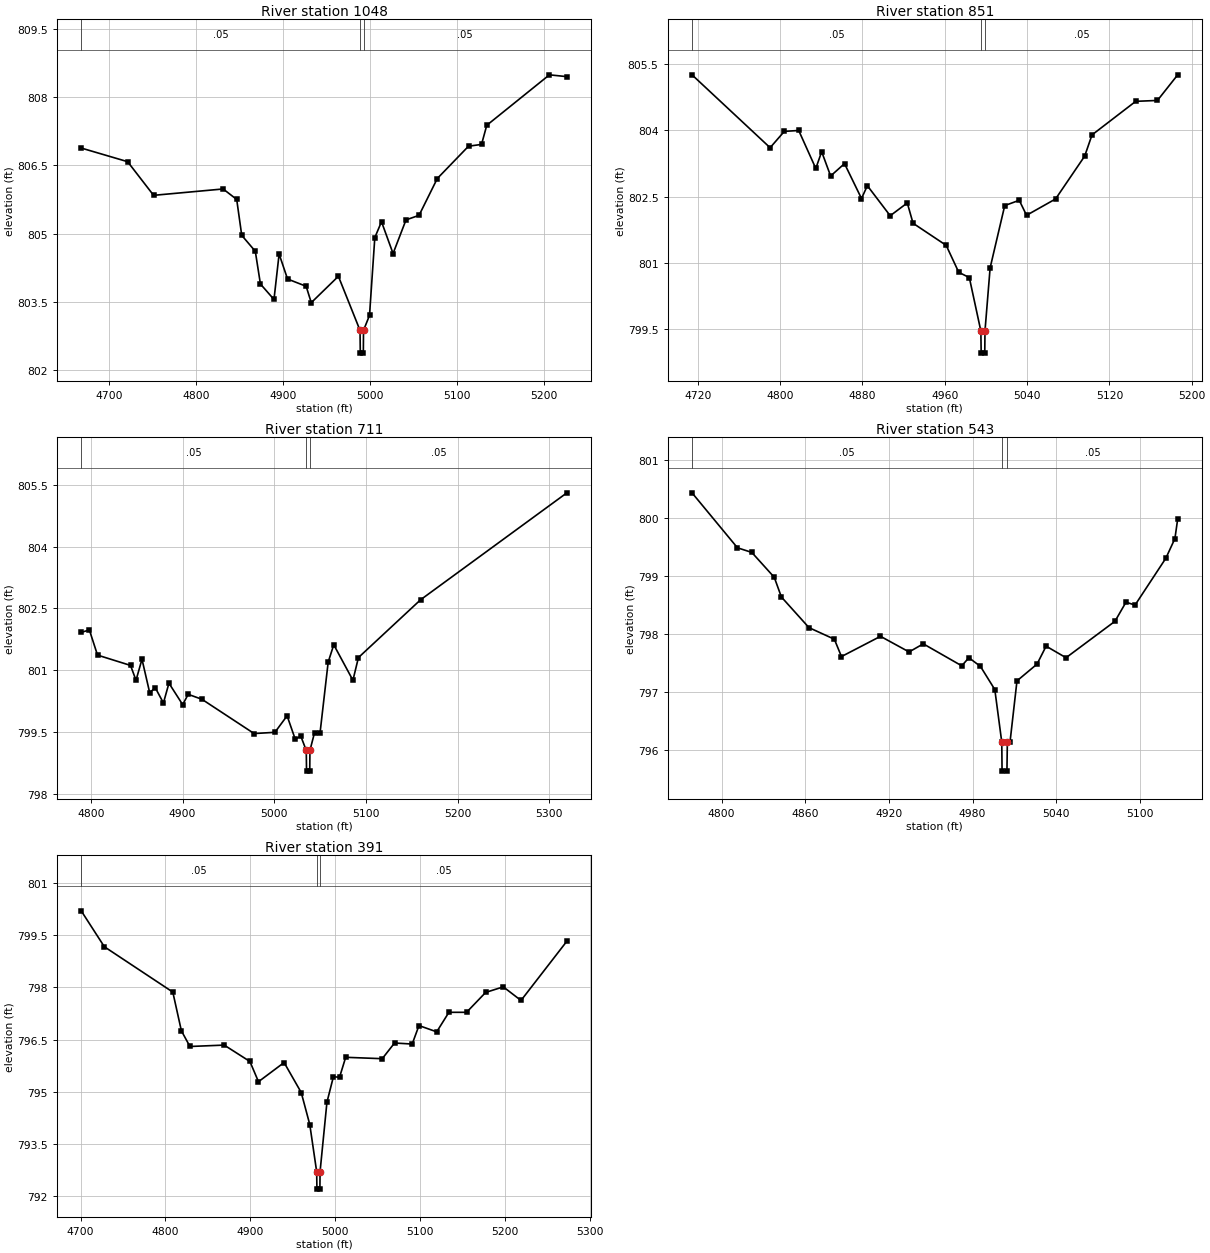
Type RM Length L Ch R = 1,1048,197,197,197
BEGIN DESCRIPTION:
Denton Creek Tributary 31_3 5.0
END DESCRIPTION:
XS GIS Cut Line= 3
      2318966.93      7137285.92      2318813.05      7137025.92
      2318669.15      7136813.37
#Sta/Elev= 30
  4667.6  806.88  4721.0  806.58  4750.9  805.84  4830.9  805.98  4846.5  805.75
  4852.3  804.96  4867.9  804.61  4873.8  803.89  4889.4  803.55  4895.3  804.55
  4905.0  804.00  4926.4  803.84  4932.3  803.48  4963.5  804.06  4988.4  802.87
  4988.7  802.37  4992.2  802.37  4992.4  802.87  4999.3  803.20  5005.4  804.91
  5013.1  805.26  5026.4  804.56  5041.3  805.30  5056.3  805.40  5077.3  806.21
  5113.2  806.92  5128.2  806.96  5134.2  807.38  5206.3  808.49  5226.4  808.45
#Mann=3,-1,0
  4667.6    0.05       0  4988.4   0.033       0  4992.4    0.05       0
Bank Sta=4988.4,4992.4
Exp/Cntr=0.3,0.1

Type RM Length L Ch R = 1,851,140,140,140
BEGIN DESCRIPTION:
Denton Creek Tributary 31_3 4.0
END DESCRIPTION:
XS GIS Cut Line= 3
      2319079.98      7137129.88      2318954.25      7136884.28
      2318813.72      7136747.52
#Sta/Elev= 30
  4714.4  805.26  4790.3  803.61  4804.1  803.98  4818.1  804.00  4834.7  803.14
  4840.4  803.52  4849.1  802.97  4862.6  803.25  4879.1  802.46  4884.8  802.75
  4907.0  802.07  4923.6  802.36  4929.2  801.90  4961.4  801.40  4973.6  800.79
  4983.9  800.67  4995.1  799.46  4995.4  798.96  4998.9  798.96  4999.1  799.46
  5004.1  800.89  5018.3  802.30  5032.4  802.42  5039.5  802.08  5067.7  802.45
  5096.0  803.42  5103.1  803.90  5145.6  804.66  5166.7  804.68  5186.4  805.26
#Mann=3,-1,0
  4714.4    0.05       0  4995.1   0.033       0  4999.1    0.05       0
Bank Sta=4995.1,4999.1
Exp/Cntr=0.3,0.1

Type RM Length L Ch R = 1,711,168,168,168
BEGIN DESCRIPTION:
Mapping XS 83086de7
END DESCRIPTION:
XS GIS Cut Line= 3
      2319187.29      7136994.87      2319017.34      7136744.15
      2318799.47      7136680.77
#Sta/Elev= 30
  4789.4  801.92  4798.3  801.98  4807.2  801.37  4843.2  801.12  4849.2  800.76
  4855.7  801.27  4864.1  800.46  4870.2  800.58  4879.1  800.21  4885.1  800.69
  4900.1  800.17  4906.1  800.42  4921.1  800.30  4978.0  799.47  5000.7  799.50
  5014.0  799.90  5022.9  799.33  5028.9  799.41  5034.9  799.06  5035.2  798.56
  5038.7  798.56  5038.9  799.06  5043.9  799.49  5049.9  799.48  5058.8  801.20
  5064.9  801.62  5085.8  800.76  5091.8  801.31  5159.6  802.71  5319.2  805.30
#Mann=3,-1,0
  4789.4    0.05       0  5034.9   0.033       0  5038.9    0.05       0
Bank Sta=5034.9,5038.9
Exp/Cntr=0.3,0.1

Type RM Length L Ch R = 1,543,152,152,152
BEGIN DESCRIPTION:
Mapping XS d55ef2e8
END DESCRIPTION:
XS GIS Cut Line= 3
      2319237.19      7136921.83      2319187.21      7136701.36
      2319093.06      7136623.25
#Sta/Elev= 30
  4778.8  800.44  4811.4  799.49  4821.7  799.41  4837.8  798.98  4842.9  798.64
  4862.7  798.11  4880.9  797.91  4886.0  797.61  4914.0  797.96  4934.5  797.69
  4944.7  797.83  4972.3  797.45  4977.4  797.59  4985.7  797.44  4996.0  797.04
  5001.0  796.13  5001.2  795.63  5004.7  795.63  5005.0  796.13  5006.9  796.13
  5011.9  797.19  5026.3  797.48  5032.8  797.79  5047.1  797.59  5082.2  798.22
  5090.1  798.55  5096.6  798.50  5118.7  799.31  5125.2  799.65  5127.2  799.99
#Mann=3,-1,0
  4778.8    0.05       0  5001.0   0.033       0  5005.0    0.05       0
Bank Sta=5001,5005
Exp/Cntr=0.3,0.1

Type RM Length L Ch R = 1,391,0,0,0
BEGIN DESCRIPTION:
Denton Creek Tributary 31_3 3.0
END DESCRIPTION:
XS GIS Cut Line= 3
      2319273.61      7136917.06      2319314.65      7136615.21
      2319104.13      7136449.39
#Sta/Elev= 30
  4700.7  800.19  4728.0  799.16  4808.7  797.86  4818.8  796.75  4828.9  796.30
  4869.3  796.34  4899.6  795.87  4909.7  795.29  4939.9  795.84  4960.1  794.98
  4970.2  794.06  4978.3  792.71  4978.6  792.21  4982.1  792.21  4982.3  792.71
  4990.4  794.70  4998.0  795.43  5005.3  795.42  5012.5  795.99  5055.6  795.95
  5070.1  796.40  5090.9  796.37  5098.9  796.90  5119.8  796.72  5134.2  797.28
  5155.0  797.28  5177.5  797.85  5198.3  798.01  5219.2  797.62  5273.3  799.32
#Mann=3,-1,0
  4700.7    0.05       0  4978.3   0.033       0  4982.3    0.05       0
Bank Sta=4978.3,4982.3
Exp/Cntr=0.3,0.1

Chan Stop Cuts=-1