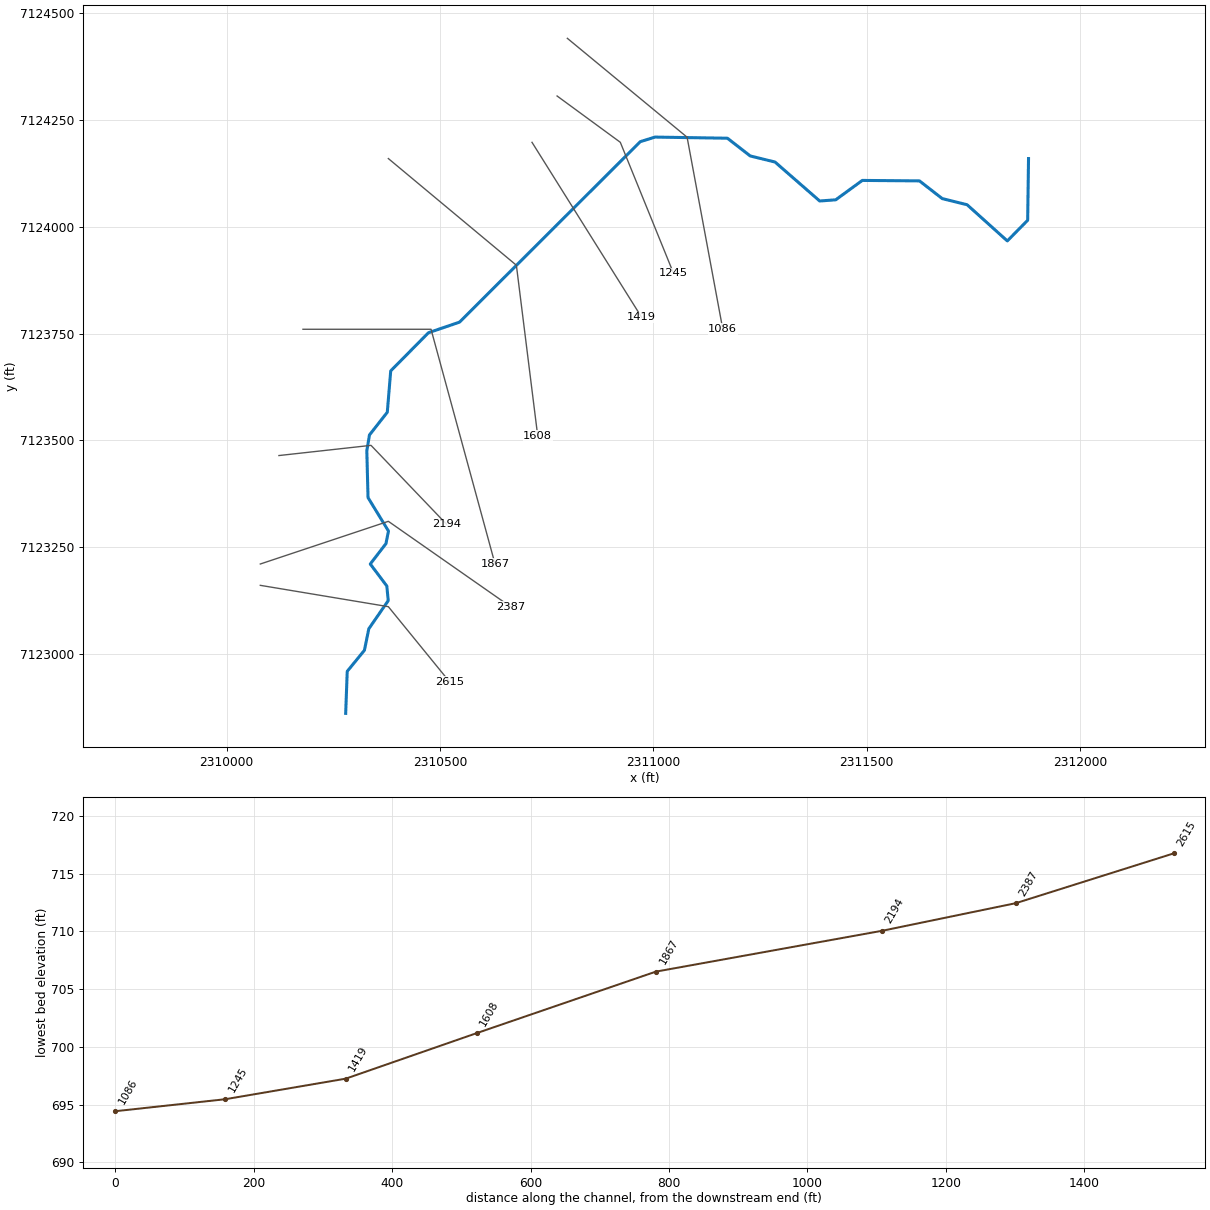
--- Denton Creek Tributary 34.prj (project) ---

Proj Title=Denton Creek Tributary 34 Base Level Engineering
Current Plan=p01
Default Exp/Contr=0.3,0.1
English Units
Geom File=g01
Flow File=f01
Plan File=p01
BEGIN DESCRIPTION:
Denton Creek Tributary 34
END DESCRIPTION:

--- Denton Creek Tributary 34.p01 (plan) ---

Plan Title=Multiple Run
Short Identifier=Multiple
Geom File=g01
Flow File=f01
Subcritical Flow
K Sum by GR= 0
Std Step Tol= 0.01
Critical Tol= 0.01
Num of Std Step Trials= 20
Max Error Tol= 0.3
Flow Tol Ratio= 0.001
Split Flow NTrial= 30
Split Flow Tol= 0.02
Split Flow Ratio= 0.02
Log Output Level= 0
Friction Slope Method= 1
Unsteady Friction Slope Method= 2
Unsteady Bridges Friction Slope Method= 1
Parabolic Critical Depth
Global Vel Dist=  1 , 1 , 1
Global Log Level= 0
CheckData=True
Encroach Param= -1, 0, 0, 0
BEGIN DESCRIPTION:
Multiple Run
END DESCRIPTION:

--- Denton Creek Tributary 34.f01 (steady flow) ---

Flow Title=Multiple
Number of Profiles=7
Profile Names=10-year,25-year,50-year,1pct_min,100-year,1pct_plu,500-year
River Rch & RM= Denton Creek Tri,Reach-1,2615
     240     313     371     220     438     875     611
Boundary for River Rch & Prof#=Denton Creek Tri,Reach-1,1
Up Type=0
Dn Type=3
Dn Slope=0.005
Boundary for River Rch & Prof#=Denton Creek Tri,Reach-1,2
Up Type=0
Dn Type=3
Dn Slope=0.005
Boundary for River Rch & Prof#=Denton Creek Tri,Reach-1,3
Up Type=0
Dn Type=3
Dn Slope=0.005
Boundary for River Rch & Prof#=Denton Creek Tri,Reach-1,4
Up Type=0
Dn Type=3
Dn Slope=0.005
Boundary for River Rch & Prof#=Denton Creek Tri,Reach-1,5
Up Type=0
Dn Type=3
Dn Slope=0.005
Boundary for River Rch & Prof#=Denton Creek Tri,Reach-1,6
Up Type=0
Dn Type=3
Dn Slope=0.005
Boundary for River Rch & Prof#=Denton Creek Tri,Reach-1,7
Up Type=0
Dn Type=3
Dn Slope=0.005

--- Denton Creek Tributary 34.g01 (geometry) ---

Geom Title=Existing Conditions

River Reach=Denton Creek Tri,Reach-1
Reach XY= 30
      2310279.00      7122860.00      2310282.63      7122958.50
      2310322.92      7123007.81      2310333.22      7123058.28
      2310378.72      7123124.12      2310375.40      7123158.36
      2310336.62      7123210.00      2310373.35      7123257.71
      2310379.30      7123287.16      2310331.39      7123365.52
      2310328.53      7123475.16      2310334.74      7123512.33
      2310376.53      7123565.57      2310384.52      7123662.44
      2310472.93      7123751.85      2310545.67      7123776.65
      2310969.20      7124199.52      2311003.88      7124210.30
      2311173.48      7124207.65      2311226.83      7124166.14
      2311285.05      7124151.84      2311389.62      7124060.60
      2311427.25      7124063.34      2311489.50      7124108.77
      2311623.48      7124107.66      2311676.83      7124066.14
      2311735.06      7124051.82      2311829.25      7123966.98
      2311876.99      7124015.40      2311879.00      7124160.00

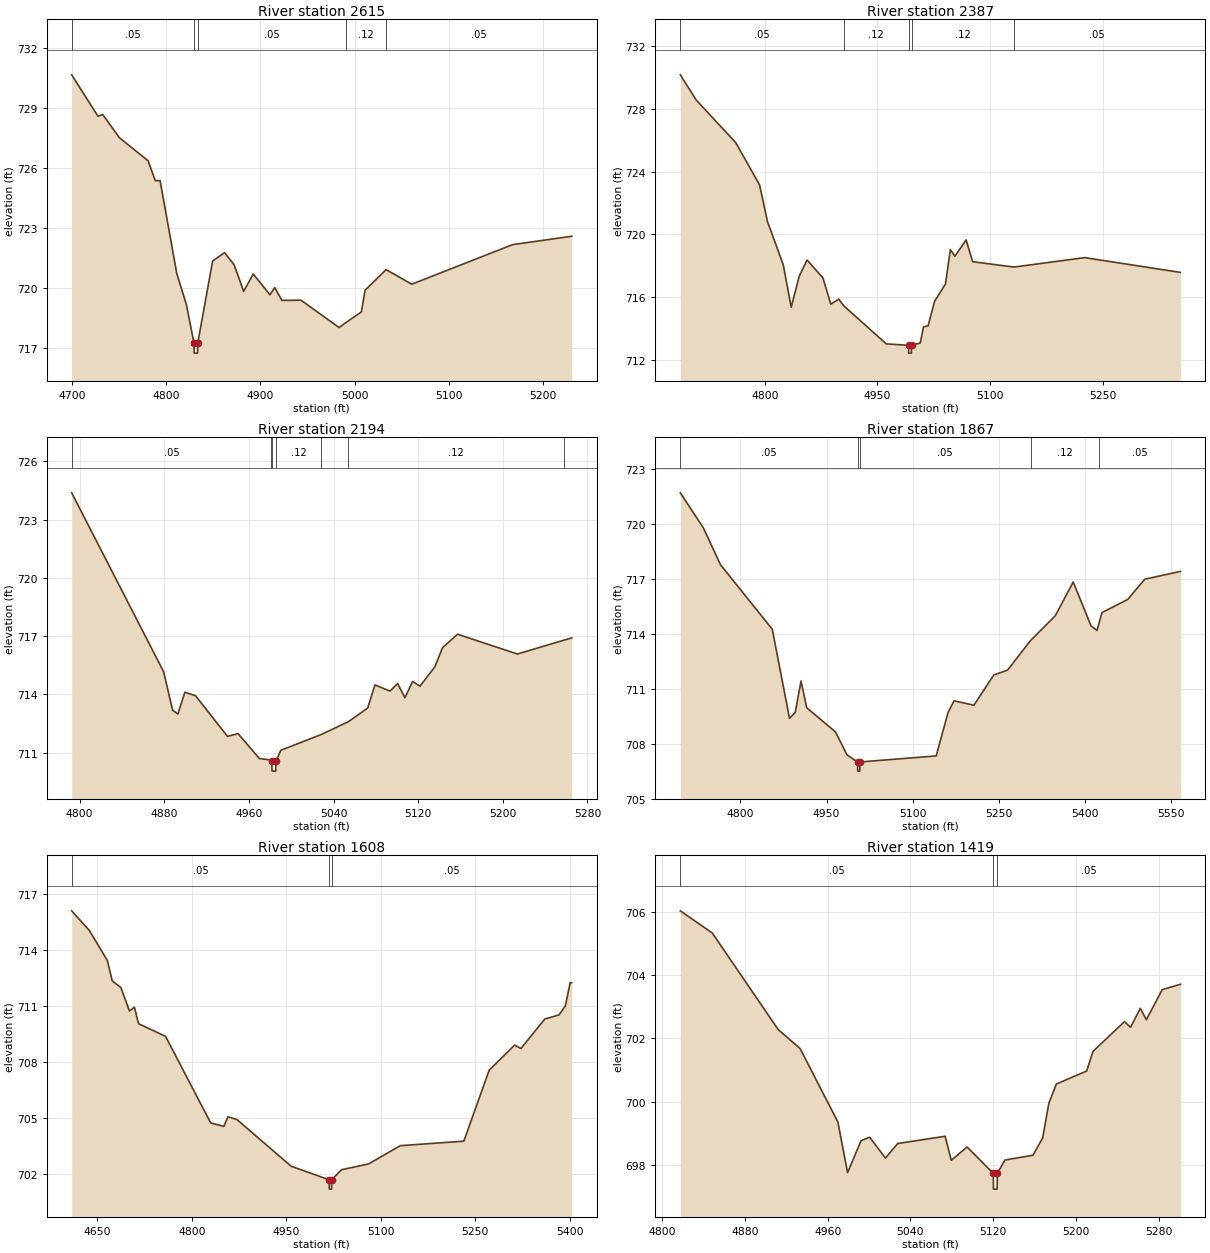
Type RM Length L Ch R = 1,2615,228,228,228
BEGIN DESCRIPTION:
Denton Creek Tributary 34 9.0
END DESCRIPTION:
XS GIS Cut Line= 3
      2310078.96      7123160.01      2310379.00      7123110.00
      2310522.08      7122934.38
#Sta/Elev= 30
  4699.8  730.68  4727.7  728.61  4732.8  728.69  4750.5  727.53  4780.9  726.38
  4788.5  725.38  4793.6  725.39  4811.4  720.72  4821.5  719.19  4829.6  717.25
  4829.9  716.75  4833.4  716.75  4833.6  717.25  4849.4  721.36  4862.0  721.78
  4872.2  721.17  4882.3  719.84  4892.5  720.71  4910.2  719.67  4915.3  720.03
  4922.9  719.39  4943.1  719.40  4983.7  718.03  4991.2  718.29  5007.2  718.81
  5011.2  719.90  5033.5  720.93  5060.7  720.20  5167.7  722.18  5230.5  722.60
#Mann=5,-1,0
  4699.8    0.05       0  4829.6    0.07       0  4833.6    0.05       0
  4991.2    0.12       0  5033.5    0.05       0
Bank Sta=4829.6,4833.6
Exp/Cntr=0.3,0.1

Type RM Length L Ch R = 1,2387,193,193,193
BEGIN DESCRIPTION:
Denton Creek Tributary 34 8.0
END DESCRIPTION:
XS GIS Cut Line= 3
      2310078.96      7123209.99      2310379.00      7123310.00
      2310665.35      7123109.91
#Sta/Elev= 30
  4687.6  730.16  4708.7  728.56  4761.4  725.84  4793.1  723.15  4803.6  720.82
  4824.7  718.05  4835.2  715.36  4845.8  717.33  4856.3  718.37  4877.4  717.23
  4887.9  715.56  4898.5  715.88  4905.2  715.45  4961.7  713.03  4991.3  712.94
  4991.6  712.44  4995.1  712.44  4995.3  712.94  5006.9  713.08  5011.3  714.11
  5017.4  714.18  5026.1  715.75  5040.5  716.84  5047.0  719.03  5053.1  718.61
  5068.0  719.65  5076.7  718.26  5131.8  717.92  5225.8  718.52  5353.2  717.58
#Mann=5,-1,0
  4687.6    0.05       0  4905.2    0.12       0  4991.3    0.07       0
  4995.3    0.12       0  5131.8    0.05       0
Bank Sta=4991.3,4995.3
Exp/Cntr=0.3,0.1

Type RM Length L Ch R = 1,2194,327,327,327
BEGIN DESCRIPTION:
Mapping XS d763e319
END DESCRIPTION:
XS GIS Cut Line= 3
      2310122.64      7123464.12      2310338.36      7123488.00
      2310515.17      7123303.34
#Sta/Elev= 30
  4792.5  724.38  4879.4  715.17  4887.9  713.19  4892.9  712.99  4899.5  714.11
  4909.6  713.93  4939.8  711.84  4949.8  711.98  4969.9  710.70  4980.9  710.62
  4981.6  710.55  4981.9  710.05  4985.4  710.05  4985.6  710.55  4990.1  711.12
  5028.2  711.93  5053.9  712.59  5072.3  713.30  5079.2  714.49  5093.4  714.17
  5100.6  714.56  5107.5  713.83  5114.8  714.67  5121.7  714.42  5135.8  715.42
  5143.1  716.41  5157.2  717.10  5213.8  716.08  5257.6  716.79  5265.2  716.91
#Mann=7,-1,0
  4792.5    0.05       0  4980.9    0.12       0  4981.6    0.07       0
  4985.6    0.12       0  5028.2    0.05       0  5053.9    0.12       0
  5257.6    0.05       0
Bank Sta=4981.6,4985.6
Exp/Cntr=0.3,0.1

Type RM Length L Ch R = 1,1867,259,259,259
BEGIN DESCRIPTION:
Denton Creek Tributary 34 7.0
END DESCRIPTION:
XS GIS Cut Line= 3
      2310178.96      7123760.00      2310479.00      7123760.00
      2310628.99      7123210.03
#Sta/Elev= 30
  4695.6  721.71  4735.6  719.80  4765.6  717.78  4855.6  714.26  4885.6  709.39
  4895.6  709.72  4905.6  711.43  4915.6  709.97  4965.6  708.65  4985.6  707.40
  5004.0  707.01  5004.3  706.51  5007.8  706.51  5008.0  707.01  5140.8  707.34
  5161.5  709.72  5171.9  710.35  5206.4  710.11  5241.0  711.76  5265.1  712.03
  5304.9  713.64  5348.1  715.00  5379.2  716.84  5410.3  714.44  5420.6  714.19
  5423.7  714.54  5429.3  715.17  5474.2  715.89  5503.5  716.99  5565.7  717.42
#Mann=5,-1,0
  4695.6    0.05       0  5004.0   0.033       0  5008.0    0.05       0
  5304.9    0.12       0  5423.7    0.05       0
Bank Sta=5004,5008
Exp/Cntr=0.3,0.1

Type RM Length L Ch R = 1,1608,189,189,189
BEGIN DESCRIPTION:
Denton Creek Tributary 34 6.0
END DESCRIPTION:
XS GIS Cut Line= 3
      2310379.02      7124159.98      2310679.00      7123910.00
      2310729.00      7123510.00
#Sta/Elev= 30
  4609.5  716.10  4637.5  715.05  4666.1  713.44  4673.9  712.34  4687.6  711.99
  4701.2  710.73  4709.1  710.93  4715.6  710.05  4758.5  709.37  4830.1  704.73
  4850.9  704.54  4857.5  705.06  4871.8  704.91  4957.7  702.41  5018.1  701.68
  5018.4  701.18  5021.9  701.18  5022.1  701.68  5037.8  702.22  5080.6  702.53
  5131.0  703.51  5231.8  703.75  5272.1  707.56  5312.4  708.90  5322.5  708.72
  5360.3  710.30  5382.9  710.52  5393.0  711.01  5400.6  712.25  5403.1  712.25
#Mann=3,-1,0
  4609.5    0.05       0  5018.1   0.033       0  5022.1    0.05       0
Bank Sta=5018.1,5022.1
Exp/Cntr=0.3,0.1

Type RM Length L Ch R = 1,1419,174,174,174
BEGIN DESCRIPTION:
Mapping XS 8630318d
END DESCRIPTION:
XS GIS Cut Line= 2
      2310715.60      7124198.02      2310972.25      7123788.38
#Sta/Elev= 30
  4817.6  706.03  4848.5  705.33  4912.2  702.28  4933.4  701.68  4969.9  699.36
  4979.3  697.76  4992.3  698.77  5000.6  698.88  5015.9  698.22  5027.7  698.68
  5073.6  698.91  5079.5  698.15  5094.8  698.57  5120.1  697.74  5120.3  697.24
  5123.8  697.24  5124.1  697.74  5131.4  698.16  5158.5  698.31  5167.9  698.86
  5173.8  699.95  5181.1  700.56  5210.4  700.97  5216.5  701.59  5246.9  702.53
  5252.8  702.35  5262.2  702.95  5268.1  702.59  5283.4  703.54  5301.0  703.71
#Mann=3,-1,0
  4817.6    0.05       0  5120.1   0.033       0  5124.1    0.05       0
Bank Sta=5120.1,5124.1
Exp/Cntr=0.3,0.1

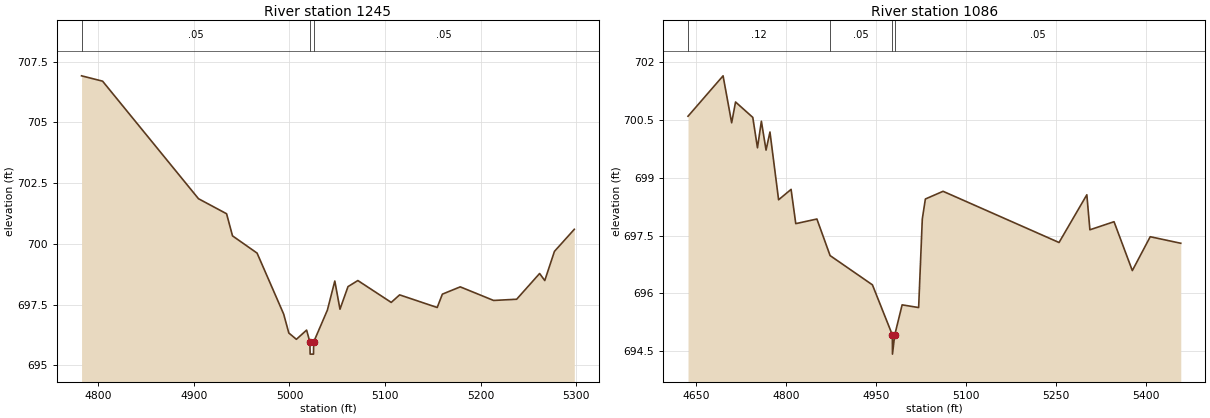
Type RM Length L Ch R = 1,1245,159,159,159
BEGIN DESCRIPTION:
Mapping XS eca4be56
END DESCRIPTION:
XS GIS Cut Line= 3
      2310774.36      7124306.60      2310922.50      7124198.09
      2311047.37      7123890.71
#Sta/Elev= 30
  4782.5  706.92  4804.5  706.70  4904.8  701.86  4934.2  701.24  4940.4  700.33
  4966.1  699.62  4993.9  697.11  4999.3  696.33  5007.2  696.07  5017.9  696.45
  5021.3  695.96  5021.6  695.46  5025.1  695.46  5025.3  695.96  5039.6  697.27
  5047.4  698.47  5052.8  697.31  5061.2  698.24  5071.5  698.49  5106.4  697.59
  5115.2  697.90  5154.5  697.38  5159.9  697.93  5178.6  698.23  5213.5  697.67
  5237.6  697.72  5261.6  698.78  5267.0  698.49  5277.1  699.69  5297.9  700.60
#Mann=3,-1,0
  4782.5    0.05       0  5021.3   0.033       0  5025.3    0.05       0
Bank Sta=5021.3,5025.3
Exp/Cntr=0.3,0.1

Type RM Length L Ch R = 1,1086,0,0,0
BEGIN DESCRIPTION:
Denton Creek Tributary 34 4.0
END DESCRIPTION:
XS GIS Cut Line= 3
      2310798.43      7124441.69      2311079.00      7124210.00
      2311162.50      7123760.66
#Sta/Elev= 30
  4636.4  700.60  4694.8  701.65  4709.1  700.43  4715.6  700.97  4744.3  700.57
  4752.1  699.78  4758.6  700.47  4766.4  699.72  4772.9  700.19  4787.3  698.43
  4808.1  698.70  4815.9  697.81  4851.1  697.93  4873.1  696.98  4943.6  696.22
  4976.8  694.92  4977.0  694.42  4980.8  694.92  4993.1  695.70  5020.6  695.63
  5026.7  697.93  5031.8  698.45  5061.3  698.65  5254.5  697.32  5300.8  698.56
  5305.9  697.65  5346.1  697.86  5376.6  696.59  5406.4  697.47  5457.3  697.30
#Mann=4,-1,0
  4636.4    0.12       0  4873.1    0.05       0  4976.8   0.033       0
  4980.8    0.05       0
Bank Sta=4976.8,4980.8
Exp/Cntr=0.3,0.1

Chan Stop Cuts=-1