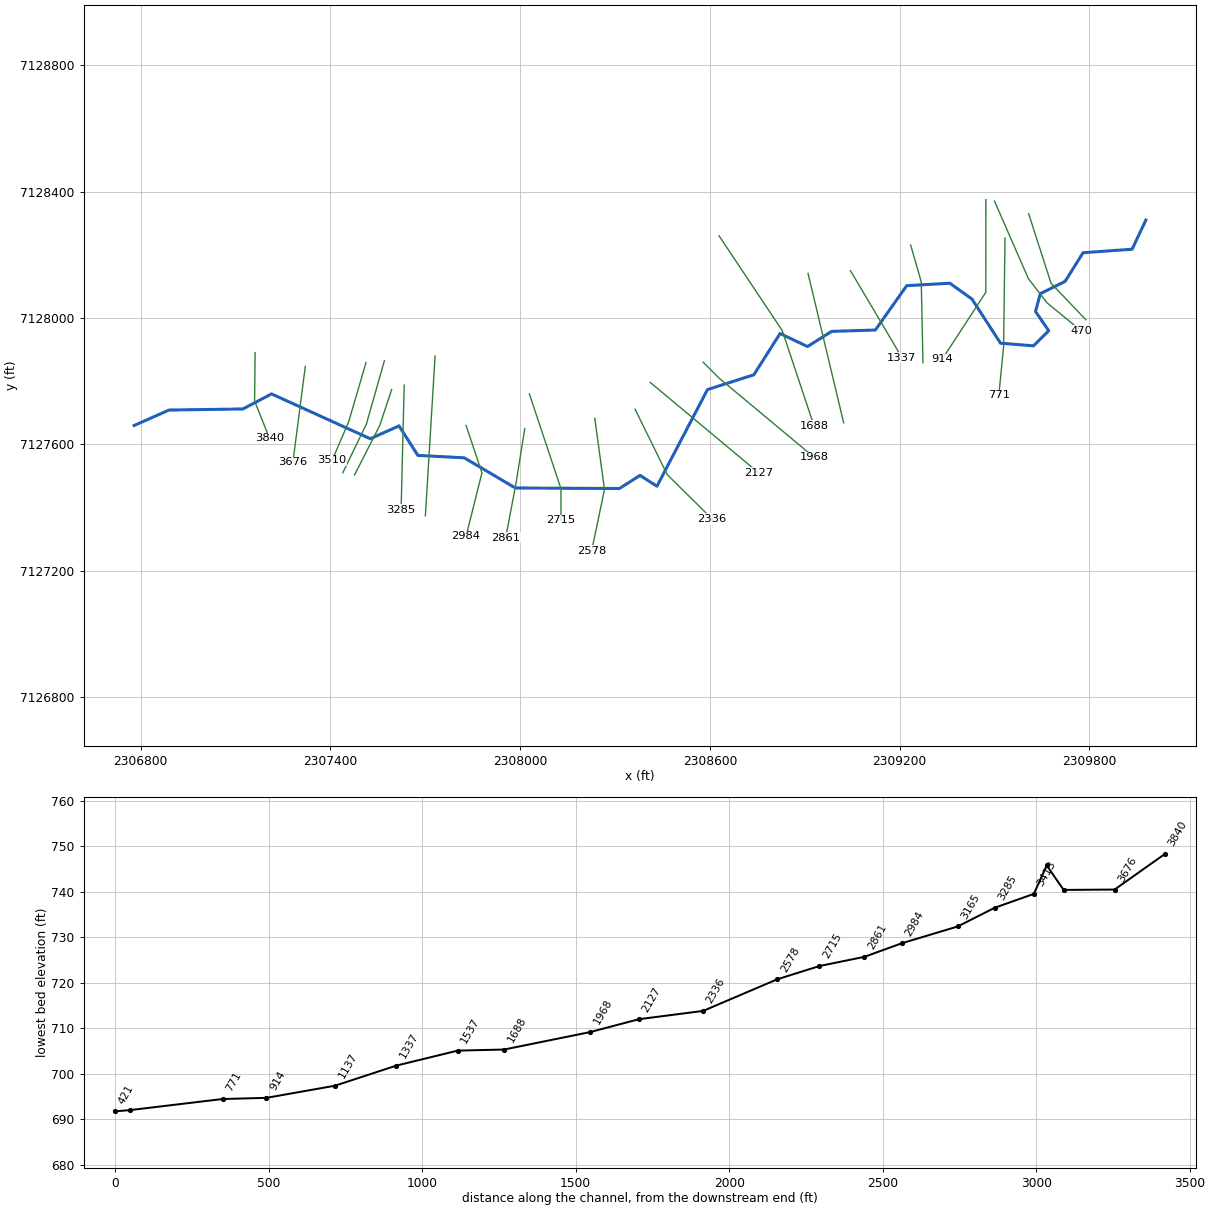
--- Denton Creek Tributary 35.prj (project) ---

Proj Title=Denton Creek Tributary 35 Base Level Engineering
Current Plan=p01
Default Exp/Contr=0.3,0.1
English Units
Geom File=g01
Flow File=f01
Plan File=p01
BEGIN DESCRIPTION:
Denton Creek Tributary 35
END DESCRIPTION:

--- Denton Creek Tributary 35.p01 (plan) ---

Plan Title=Multiple Run
Short Identifier=Multiple
Geom File=g01
Flow File=f01
Subcritical Flow
K Sum by GR= 0
Std Step Tol= 0.01
Critical Tol= 0.01
Num of Std Step Trials= 20
Max Error Tol= 0.3
Flow Tol Ratio= 0.001
Split Flow NTrial= 30
Split Flow Tol= 0.02
Split Flow Ratio= 0.02
Log Output Level= 0
Friction Slope Method= 1
Unsteady Friction Slope Method= 2
Unsteady Bridges Friction Slope Method= 1
Parabolic Critical Depth
Global Vel Dist=  1 , 1 , 1
Global Log Level= 0
CheckData=True
Encroach Param= -1, 0, 0, 0
BEGIN DESCRIPTION:
Multiple Run
END DESCRIPTION:

--- Denton Creek Tributary 35.f01 (steady flow) ---

Flow Title=Multiple
Number of Profiles=7
Profile Names=10-year,25-year,50-year,1pct_min,100-year,1pct_plu,500-year
River Rch & RM= Denton Creek Tri,Reach-1,3840
     205     264     310     182     363     724     497
River Rch & RM= Denton Creek Tri,Reach-1,2336
     373     503     610     369     736    1468    1069
River Rch & RM= Denton Creek Tri,Reach-1,914
     655     907    1118     685    1366    2725    2043
Boundary for River Rch & Prof#=Denton Creek Tri,Reach-1,1
Up Type=0
Dn Type=3
Dn Slope=0.005
Boundary for River Rch & Prof#=Denton Creek Tri,Reach-1,2
Up Type=0
Dn Type=3
Dn Slope=0.005
Boundary for River Rch & Prof#=Denton Creek Tri,Reach-1,3
Up Type=0
Dn Type=3
Dn Slope=0.005
Boundary for River Rch & Prof#=Denton Creek Tri,Reach-1,4
Up Type=0
Dn Type=3
Dn Slope=0.005
Boundary for River Rch & Prof#=Denton Creek Tri,Reach-1,5
Up Type=0
Dn Type=3
Dn Slope=0.005
Boundary for River Rch & Prof#=Denton Creek Tri,Reach-1,6
Up Type=0
Dn Type=3
Dn Slope=0.005
Boundary for River Rch & Prof#=Denton Creek Tri,Reach-1,7
Up Type=0
Dn Type=3
Dn Slope=0.005

--- Denton Creek Tributary 35.g01 (geometry) ---

Geom Title=Existing Conditions

River Reach=Denton Creek Tri,Reach-1
Reach XY= 30
      2306779.00      7127660.00      2306889.46      7127708.88
      2307123.07      7127712.29      2307213.61      7127759.92
      2307525.73      7127618.11      2307616.96      7127658.76
      2307676.32      7127565.41      2307823.07      7127557.75
      2307984.93      7127462.24      2308313.84      7127460.65
      2308379.11      7127502.19      2308432.62      7127467.88
      2308592.46      7127773.63      2308739.10      7127820.39
      2308821.99      7127950.97      2308908.79      7127909.79
      2308984.93      7127957.70      2309123.32      7127961.99
      2309222.53      7128102.31      2309359.00      7128110.04
      2309429.00      7128060.00      2309519.19      7127920.41
      2309623.51      7127911.96      2309671.75      7127959.66
      2309629.88      7128020.68      2309645.15      7128077.01
      2309723.33      7128115.67      2309780.27      7128206.52
      2309935.47      7128217.59      2309979.00      7128310.00

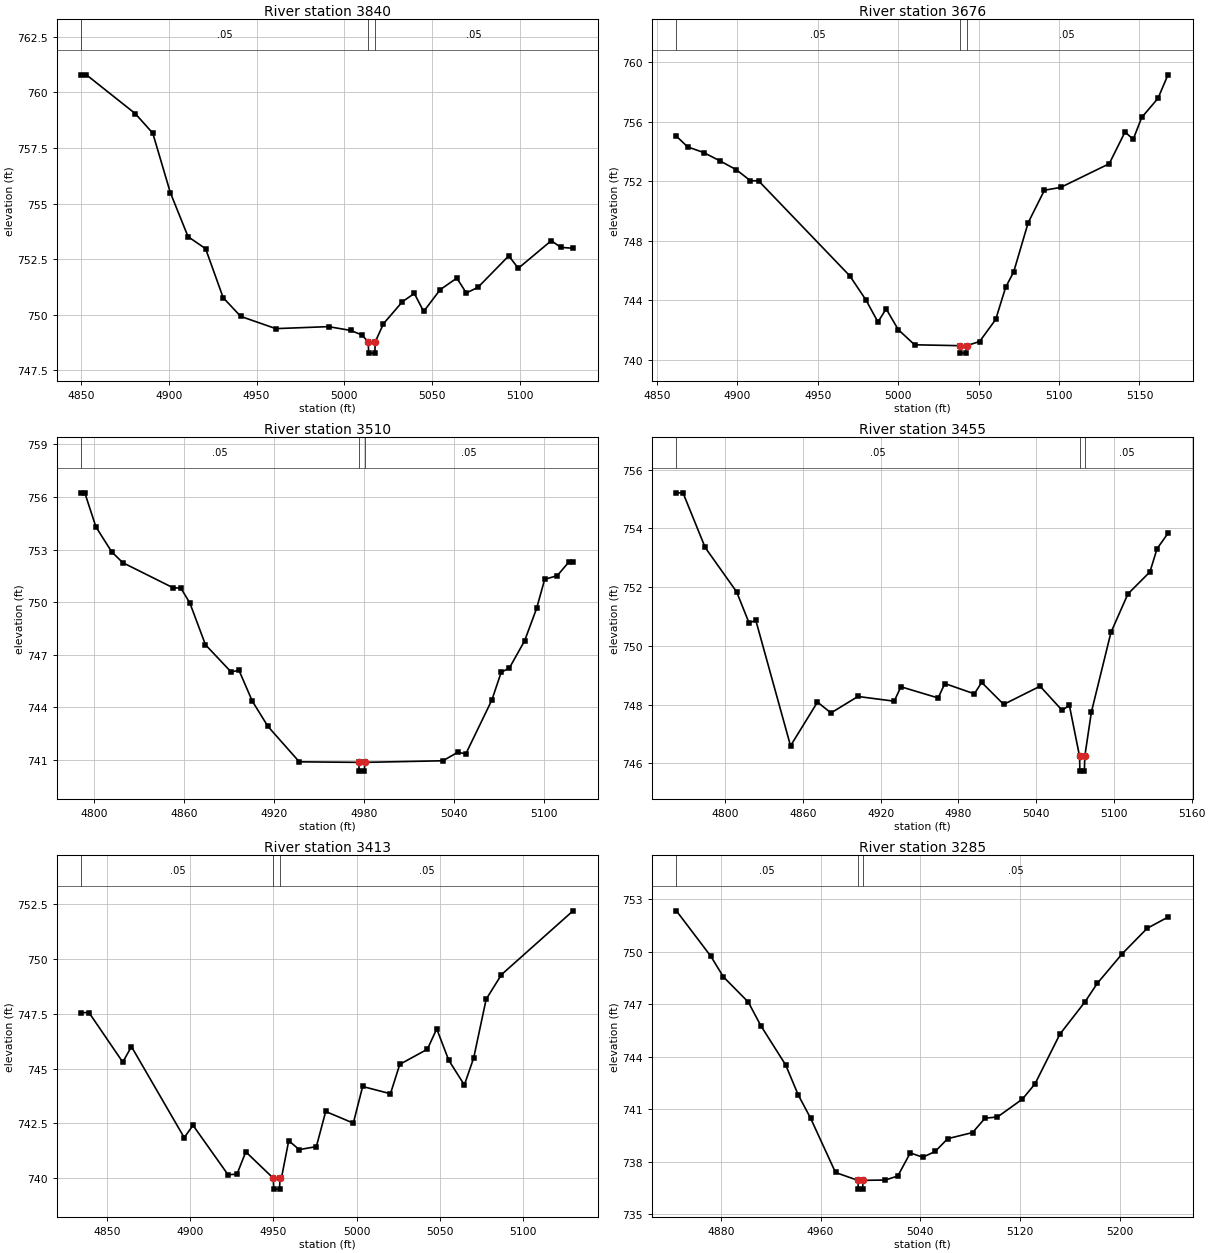
Type RM Length L Ch R = 1,3840,164,164,164
BEGIN DESCRIPTION:
Denton Creek Tributary 35 12.0
END DESCRIPTION:
XS GIS Cut Line= 3
      2307161.65      7127890.65      2307159.99      7127737.40
      2307207.08      7127619.73
#Sta/Elev= 30
  4850.3  760.78  4853.1  760.78  4880.9  759.04  4890.9  758.16  4900.9  755.49
  4911.0  753.51  4921.0  752.97  4931.0  750.77  4941.0  749.93  4961.0  749.38
  4991.0  749.47  5003.6  749.30  5010.2  749.09  5013.6  748.78  5013.9  748.28
  5017.4  748.28  5017.6  748.78  5022.3  749.60  5033.1  750.59  5039.9  750.96
  5045.2  750.15  5054.6  751.13  5064.1  751.65  5069.5  750.98  5076.2  751.24
  5093.7  752.65  5099.1  752.09  5117.9  753.33  5123.3  753.03  5130.3  752.99
#Mann=3,-1,0
  4850.3    0.05       0  5013.6    0.04       0  5017.6    0.05       0
Bank Sta=5013.6,5017.6
Exp/Cntr=0.3,0.1

Type RM Length L Ch R = 1,3676,166,166,166
BEGIN DESCRIPTION:
Mapping XS 7eadb43d
END DESCRIPTION:
XS GIS Cut Line= 2
      2307320.39      7127846.90      2307281.19      7127543.83
#Sta/Elev= 30
  4862.1  755.02  4869.1  754.30  4879.1  753.92  4889.2  753.36  4899.3  752.77
  4908.1  752.03  4913.2  752.02  4969.9  745.64  4980.0  744.01  4987.4  742.54
  4992.5  743.42  5000.1  742.02  5010.2  741.01  5038.5  740.95  5038.7  740.45
  5042.2  740.45  5042.5  740.95  5050.6  741.23  5060.6  742.71  5066.8  744.87
  5071.8  745.91  5080.8  749.21  5090.9  751.39  5101.0  751.58  5131.2  753.17
  5141.0  755.30  5146.1  754.81  5151.4  756.28  5161.5  757.56  5167.7  759.14
#Mann=3,-1,0
  4862.1    0.05       0  5038.5    0.04       0  5042.5    0.05       0
Bank Sta=5038.5,5042.5
Exp/Cntr=0.3,0.1

Type RM Length L Ch R = 1,3510,55,55,55
BEGIN DESCRIPTION:
Mapping XS a37d05b1
END DESCRIPTION:
XS GIS Cut Line= 3
      2307512.36      7127859.26      2307457.59      7127671.71
      2307405.37      7127550.35
#Sta/Elev= 30
  4791.8  756.23  4794.0  756.23  4801.4  754.29  4811.9  752.87  4819.3  752.25
  4852.8  750.82  4858.0  750.80  4864.0  749.95  4874.4  747.57  4891.5  746.02
  4896.7  746.12  4905.6  744.36  4916.0  742.92  4936.9  740.90  4976.5  740.87
  4976.8  740.37  4980.3  740.37  4980.5  740.87  5032.6  740.96  5042.4  741.44
  5047.9  741.36  5065.2  744.42  5071.4  746.00  5076.9  746.25  5087.0  747.79
  5095.0  749.64  5100.4  751.30  5108.8  751.51  5116.7  752.31  5119.3  752.31
#Mann=3,-1,0
  4791.8    0.05       0  4976.5   0.033       0  4980.5    0.05       0
Bank Sta=4976.5,4980.5
Exp/Cntr=0.3,0.1

Type RM Length L Ch R = 1,3455,42,42,42
BEGIN DESCRIPTION:
Mapping XS aaa2dfd6
END DESCRIPTION:
XS GIS Cut Line= 3
      2307570.52      7127864.73      2307513.65      7127664.62
      2307438.94      7127510.40
#Sta/Elev= 30
  4762.3  755.21  4767.4  755.21  4784.5  753.35  4808.8  751.84  4818.4  750.78
  4823.6  750.87  4850.4  746.60  4871.2  748.09  4881.6  747.72  4902.4  748.28
  4930.4  748.12  4935.6  748.61  4964.3  748.23  4969.5  748.72  4992.3  748.37
  4997.9  748.76  5014.9  748.01  5043.0  748.63  5060.0  747.81  5065.6  747.98
  5073.5  746.24  5073.7  745.74  5077.2  745.74  5077.5  746.24  5082.6  747.75
  5097.7  750.46  5110.8  751.77  5127.8  752.52  5133.3  753.31  5141.7  753.83
#Mann=3,-1,0
  4762.3    0.05       0  5073.5    0.05       0  5077.5    0.05       0
Bank Sta=5073.5,5077.5
Exp/Cntr=0.3,0.1

Type RM Length L Ch R = 1,3413,128,128,128
BEGIN DESCRIPTION:
Mapping XS 056cf21d
END DESCRIPTION:
XS GIS Cut Line= 3
      2307593.44      7127773.56      2307555.64      7127659.55
      2307476.07      7127503.48
#Sta/Elev= 30
  4834.7  747.55  4839.2  747.55  4859.5  745.29  4864.7  746.00  4896.4  741.85
  4901.7  742.41  4922.7  740.16  4928.1  740.18  4933.4  741.20  4949.9  740.00
  4950.2  739.50  4953.7  739.50  4953.9  740.00  4954.8  740.00  4959.2  741.71
  4965.5  741.30  4975.8  741.44  4981.4  743.04  4998.0  742.51  5003.6  744.18
  5020.3  743.85  5025.9  745.19  5042.5  745.88  5048.1  746.81  5055.3  745.38
  5064.7  744.25  5070.3  745.48  5077.8  748.16  5087.0  749.28  5130.0  752.19
#Mann=3,-1,0
  4834.7    0.05       0  4949.9    0.05       0  4953.9    0.05       0
Bank Sta=4949.9,4953.9
Exp/Cntr=0.3,0.1

Type RM Length L Ch R = 1,3285,120,120,120
BEGIN DESCRIPTION:
Mapping XS fddc3680
END DESCRIPTION:
XS GIS Cut Line= 2
      2307633.18      7127787.66      2307623.41      7127393.29
#Sta/Elev= 30
  4844.3  752.33  4872.0  749.73  4882.0  748.56  4902.0  747.12  4912.0  745.78
  4932.0  743.53  4942.0  741.83  4952.0  740.49  4972.0  737.39  4990.0  736.94
  4990.3  736.44  4993.8  736.44  4994.0  736.94  5012.0  736.96  5022.0  737.19
  5032.0  738.51  5042.0  738.26  5052.0  738.59  5062.0  739.32  5082.0  739.67
  5092.0  740.49  5102.0  740.56  5122.0  741.58  5132.1  742.45  5152.1  745.29
  5172.1  747.12  5182.1  748.19  5202.1  749.88  5222.1  751.33  5238.8  751.97
#Mann=3,-1,0
  4844.3    0.05       0  4990.0    0.05       0  4994.0    0.05       0
Bank Sta=4990,4994
Exp/Cntr=0.3,0.1

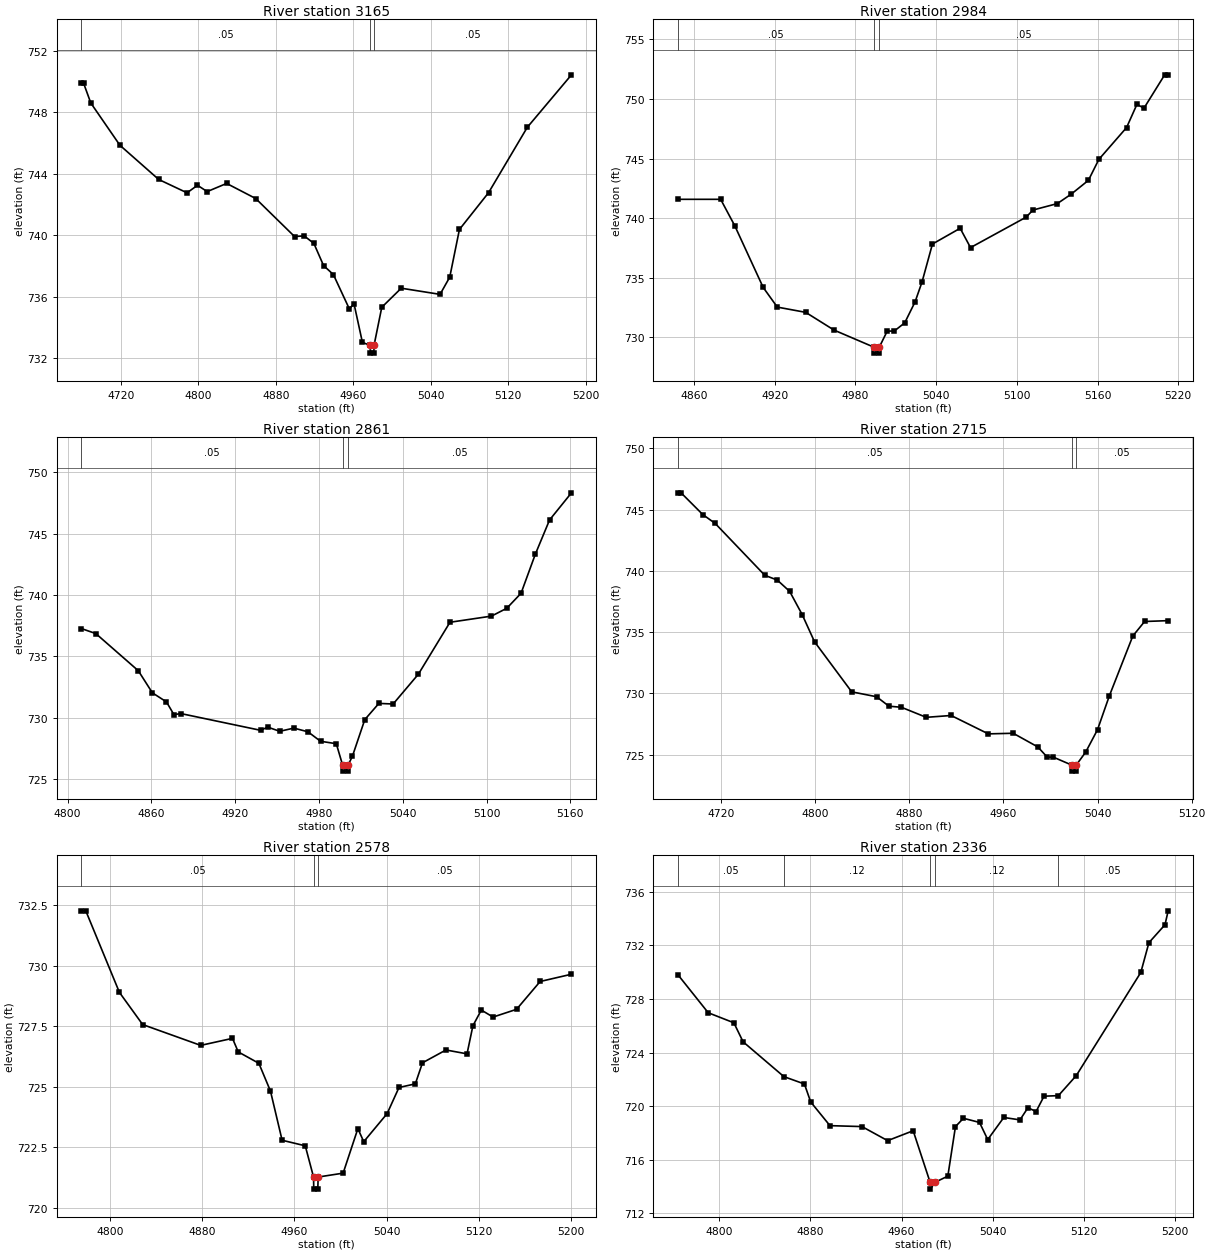
Type RM Length L Ch R = 1,3165,181,181,181
BEGIN DESCRIPTION:
Mapping XS b6576eaa
END DESCRIPTION:
XS GIS Cut Line= 2
      2307730.88      7127879.78      2307700.17      7127374.51
#Sta/Elev= 30
  4679.2  749.88  4681.6  749.88  4689.0  748.60  4719.1  745.85  4759.1  743.63
  4788.4  742.76  4799.2  743.25  4809.2  742.84  4829.3  743.37  4859.3  742.39
  4899.4  739.92  4909.4  739.96  4919.4  739.47  4929.4  738.03  4939.5  737.45
  4955.9  735.23  4960.9  735.53  4969.5  733.04  4977.5  732.84  4977.8  732.34
  4981.3  732.34  4981.5  732.84  4989.5  735.32  5009.6  736.56  5049.7  736.16
  5059.7  737.28  5069.7  740.38  5099.8  742.77  5139.8  747.02  5185.4  750.43
#Mann=3,-1,0
  4679.2    0.05       0  4977.5    0.05       0  4981.5    0.05       0
Bank Sta=4977.5,4981.5
Exp/Cntr=0.3,0.1

Type RM Length L Ch R = 1,2984,123,123,123
BEGIN DESCRIPTION:
Denton Creek Tributary 35 10.0
END DESCRIPTION:
XS GIS Cut Line= 3
      2307828.99      7127660.04      2307879.00      7127510.00
      2307829.00      7127310.01
#Sta/Elev= 30
  4848.2  741.58  4879.9  741.58  4890.4  739.36  4911.5  734.19  4922.0  732.54
  4943.1  732.10  4964.2  730.61  4993.8  729.18  4994.1  728.68  4997.6  728.68
  4997.8  729.18  5003.7  730.53  5008.9  730.53  5016.7  731.22  5024.4  732.98
  5029.6  734.66  5037.3  737.83  5057.9  739.15  5065.6  737.53  5106.9  740.08
  5112.0  740.68  5130.1  741.22  5140.4  742.01  5153.2  743.17  5161.0  744.93
  5181.6  747.60  5189.3  749.55  5194.5  749.22  5209.9  752.02  5212.5  752.02
#Mann=3,-1,0
  4848.2    0.05       0  4993.8   0.033       0  4997.8    0.05       0
Bank Sta=4993.8,4997.8
Exp/Cntr=0.3,0.1

Type RM Length L Ch R = 1,2861,146,146,146
BEGIN DESCRIPTION:
Mapping XS 6a7d6530
END DESCRIPTION:
XS GIS Cut Line= 3
      2308014.51      7127650.28      2307986.87      7127477.31
      2307954.09      7127304.55
#Sta/Elev= 30
  4809.8  737.27  4820.2  736.86  4850.6  733.84  4860.7  732.04  4870.8  731.30
  4876.1  730.27  4881.2  730.35  4938.2  728.99  4943.3  729.25  4951.9  728.91
  4962.0  729.17  4972.1  728.87  4981.1  728.10  4992.4  727.90  4996.9  726.17
  4997.2  725.67  5000.7  725.67  5000.9  726.17  5004.0  726.90  5012.8  729.86
  5022.9  731.18  5033.1  731.13  5051.2  733.56  5073.8  737.78  5103.5  738.28
  5114.5  738.92  5124.7  740.14  5134.9  743.31  5145.1  746.10  5160.8  748.31
#Mann=3,-1,0
  4809.8    0.05       0  4996.9   0.033       0  5000.9    0.05       0
Bank Sta=4996.9,5000.9
Exp/Cntr=0.3,0.1

Type RM Length L Ch R = 1,2715,137,137,137
BEGIN DESCRIPTION:
Denton Creek Tributary 35 9.0
END DESCRIPTION:
XS GIS Cut Line= 3
      2308029.02      7127759.95      2308129.00      7127460.00
      2308129.00      7127359.98
#Sta/Elev= 30
  4683.8  746.37  4686.4  746.37  4704.8  744.60  4715.4  743.87  4757.5  739.64
  4768.1  739.25  4778.6  738.33  4789.2  736.44  4799.7  734.22  4831.3  730.13
  4852.4  729.73  4862.9  728.96  4873.5  728.87  4894.6  728.05  4915.7  728.20
  4947.3  726.70  4968.4  726.75  4989.4  725.63  4997.3  724.80  5002.5  724.80
  5018.0  724.16  5018.2  723.66  5021.7  723.66  5022.0  724.16  5030.0  725.22
  5040.0  727.04  5050.0  729.79  5070.0  734.69  5080.0  735.87  5100.0  735.94
#Mann=3,-1,0
  4683.8    0.05       0  5018.0   0.033       0  5022.0    0.05       0
Bank Sta=5018,5022
Exp/Cntr=0.3,0.1

Type RM Length L Ch R = 1,2578,242,242,242
BEGIN DESCRIPTION:
Mapping XS d5096fcb
END DESCRIPTION:
XS GIS Cut Line= 3
      2308236.01      7127682.77      2308266.64      7127457.43
      2308226.00      7127263.35
#Sta/Elev= 30
  4774.9  732.26  4778.8  732.26  4808.0  728.89  4828.2  727.56  4878.6  726.70
  4906.2  726.99  4911.2  726.43  4929.1  725.96  4939.2  724.81  4949.3  722.78
  4969.4  722.55  4976.6  721.26  4976.8  720.76  4980.3  720.76  4980.6  721.26
  5002.3  721.42  5015.1  723.26  5020.2  722.72  5040.5  723.88  5050.8  724.96
  5065.0  725.11  5071.2  725.98  5091.6  726.51  5109.9  726.35  5115.0  727.51
  5122.3  728.16  5132.5  727.87  5152.9  728.19  5173.4  729.34  5200.6  729.64
#Mann=3,-1,0
  4774.9    0.05       0  4976.6   0.033       0  4980.6    0.05       0
Bank Sta=4976.6,4980.6
Exp/Cntr=0.3,0.1

Type RM Length L Ch R = 1,2336,209,209,209
BEGIN DESCRIPTION:
Mapping XS 966b9c2c
END DESCRIPTION:
XS GIS Cut Line= 3
      2308363.51      7127711.26      2308465.22      7127504.33
      2308607.14      7127364.22
#Sta/Elev= 30
  4763.9  729.80  4790.4  726.97  4812.9  726.22  4821.0  724.80  4856.8  722.20
  4874.8  721.65  4880.3  720.31  4897.2  718.54  4925.3  718.47  4947.8  717.42
  4970.2  718.16  4985.1  714.30  4985.4  713.80  4989.1  714.30  5000.6  714.77
  5007.3  718.47  5014.3  719.09  5028.4  718.78  5035.6  717.50  5049.7  719.15
  5063.9  718.97  5070.9  719.88  5078.0  719.59  5085.0  720.74  5097.6  720.78
  5113.3  722.28  5169.9  729.98  5177.0  732.20  5191.1  733.54  5193.9  734.58
#Mann=5,-1,0
  4763.9    0.05       0  4856.8    0.12       0  4985.1    0.07       0
  4989.1    0.12       0  5097.6    0.05       0
Bank Sta=4985.1,4989.1
Exp/Cntr=0.3,0.1

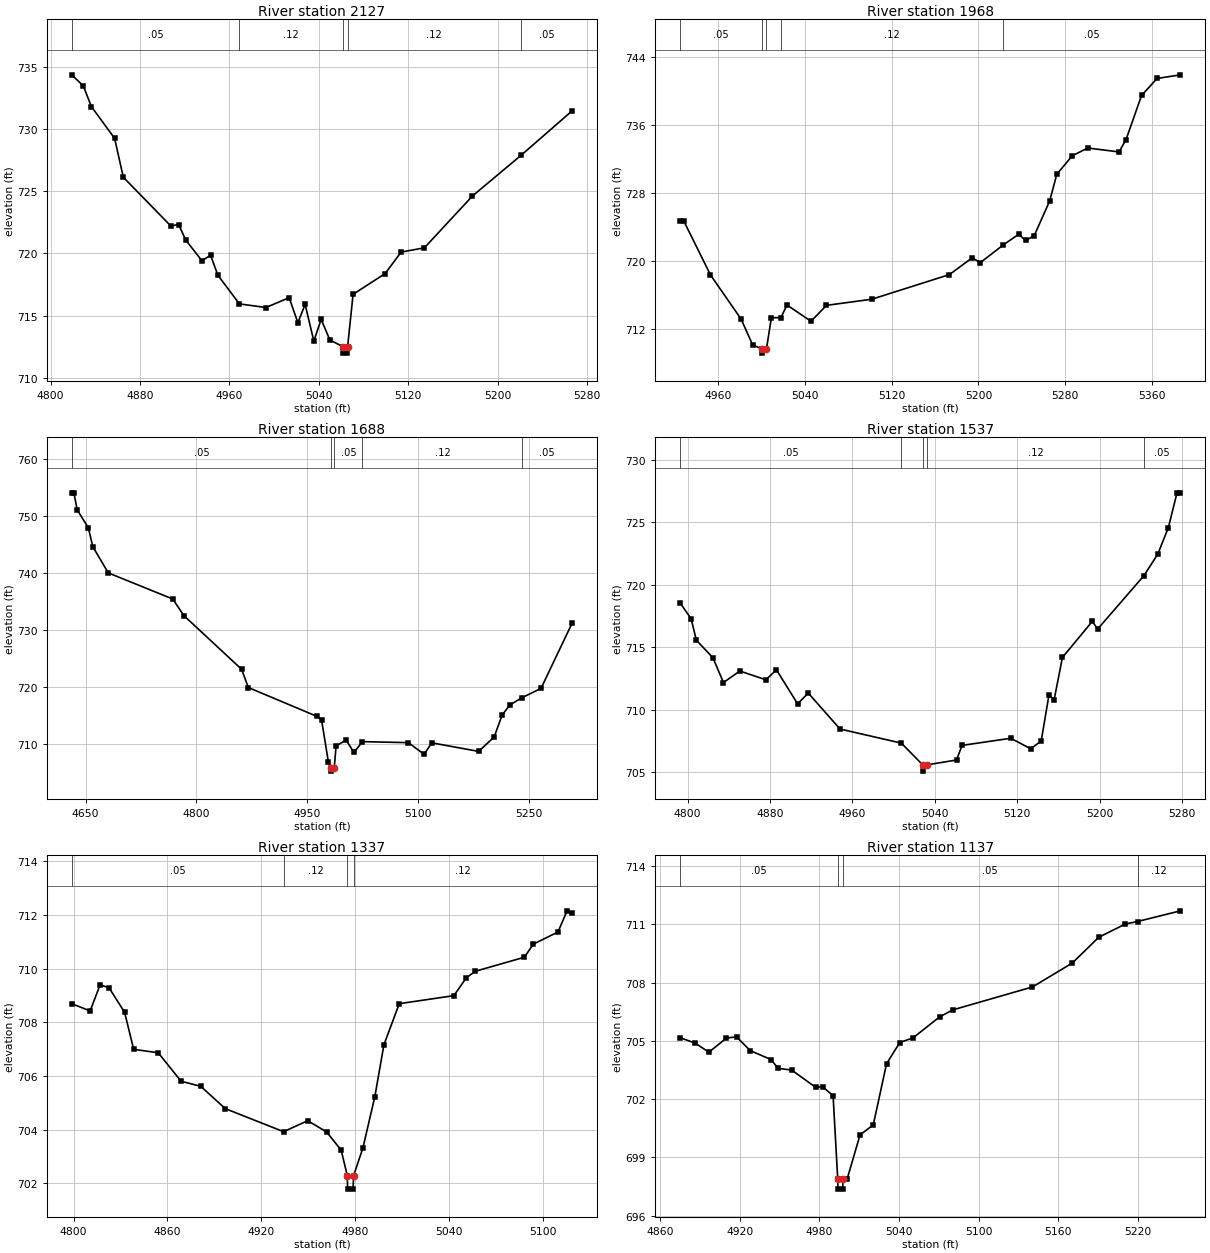
Type RM Length L Ch R = 1,2127,159,159,159
BEGIN DESCRIPTION:
Mapping XS 9feadf67
END DESCRIPTION:
XS GIS Cut Line= 2
      2308410.98      7127796.64      2308754.89      7127509.69
#Sta/Elev= 30
  4818.9  734.37  4829.3  733.48  4836.5  731.82  4857.3  729.26  4865.1  726.13
  4907.5  722.22  4914.6  722.32  4921.1  721.06  4935.4  719.42  4943.2  719.85
  4949.7  718.25  4969.0  715.94  4992.7  715.65  5013.5  716.44  5021.3  714.43
  5027.8  715.90  5035.6  712.94  5042.1  714.70  5049.9  713.05  5061.8  712.48
  5062.0  711.98  5065.5  711.98  5065.8  712.48  5070.7  716.71  5099.4  718.38
  5113.7  720.11  5134.5  720.45  5177.5  724.62  5221.1  727.90  5266.8  731.48
#Mann=5,-1,0
  4818.9    0.05       0  4969.0    0.12       0  5061.8    0.07       0
  5065.8    0.12       0  5221.1    0.05       0
Bank Sta=5061.8,5065.8
Exp/Cntr=0.3,0.1

Type RM Length L Ch R = 1,1968,280,280,280
BEGIN DESCRIPTION:
Denton Creek Tributary 35 6.0
END DESCRIPTION:
XS GIS Cut Line= 3
      2308579.03      7127859.97      2308629.00      7127810.00
      2308929.01      7127559.99
#Sta/Elev= 30
  4924.9  724.72  4928.4  724.72  4953.1  718.35  4981.4  713.14  4992.0  710.10
  5000.7  709.65  5001.0  709.15  5004.7  709.65  5009.2  713.31  5018.0  713.33
  5023.6  714.81  5045.7  712.90  5060.0  714.77  5101.7  715.49  5173.3  718.39
  5194.1  720.35  5201.9  719.81  5222.3  721.82  5237.0  723.13  5243.5  722.40
  5251.4  722.96  5265.7  727.07  5272.2  730.19  5286.5  732.37  5300.8  733.28
  5329.5  732.82  5336.0  734.26  5350.3  739.46  5364.6  741.46  5386.1  741.89
#Mann=5,-1,0
  4924.9    0.05       0  5000.7   0.033       0  5004.7    0.05       0
  5018.0    0.12       0  5222.3    0.05       0
Bank Sta=5000.7,5004.7
Exp/Cntr=0.3,0.1

Type RM Length L Ch R = 1,1688,151,151,151
BEGIN DESCRIPTION:
Denton Creek Tributary 35 5.0
END DESCRIPTION:
XS GIS Cut Line= 3
      2308629.02      7128259.97      2308829.00      7127960.00
      2308929.02      7127659.95
#Sta/Elev= 30
  4631.3  754.01  4634.3  754.01  4638.8  751.02  4653.8  747.90  4659.8  744.60
  4680.8  740.00  4768.0  735.43  4783.0  732.53  4861.1  723.13  4870.1  719.95
  4963.3  714.88  4969.3  714.19  4978.3  707.00  4982.3  705.82  4982.6  705.32
  4986.3  705.82  4988.8  709.72  5002.4  710.76  5012.9  708.59  5024.5  710.48
  5086.7  710.30  5107.8  708.26  5118.3  710.27  5181.6  708.77  5202.6  711.30
  5213.2  715.09  5223.7  716.90  5240.7  718.20  5265.9  719.79  5308.1  731.24
#Mann=5,-1,0
  4631.3    0.05       0  4982.3   0.033       0  4986.3    0.05       0
  5024.5    0.12       0  5240.7    0.05       0
Bank Sta=4982.3,4986.3
Exp/Cntr=0.3,0.1

Type RM Length L Ch R = 1,1537,200,200,200
BEGIN DESCRIPTION:
Mapping XS 1532eaaa
END DESCRIPTION:
XS GIS Cut Line= 2
      2308910.42      7128141.19      2309023.05      7127668.63
#Sta/Elev= 30
  4792.5  718.57  4803.4  717.27  4808.5  715.56  4824.6  714.15  4834.8  712.17
  4850.7  713.09  4876.0  712.39  4886.2  713.19  4906.8  710.46  4917.1  711.33
  4947.9  708.45  5007.5  707.32  5028.2  705.58  5028.4  705.08  5032.2  705.58
  5061.0  705.97  5066.4  707.14  5113.7  707.71  5133.0  706.87  5143.2  707.49
  5150.7  711.15  5155.8  710.81  5163.8  714.18  5192.8  717.06  5198.0  716.45
  5243.0  720.73  5256.3  722.44  5266.6  724.56  5275.0  727.35  5278.3  727.35
#Mann=5,-1,0
  4792.5    0.05       0  5007.5    0.12       0  5028.2   0.033       0
  5032.2    0.12       0  5243.0    0.05       0
Bank Sta=5028.2,5032.2
Exp/Cntr=0.3,0.1

Type RM Length L Ch R = 1,1337,200,200,200
BEGIN DESCRIPTION:
Mapping XS 380f67c6
END DESCRIPTION:
XS GIS Cut Line= 2
      2309044.44      7128150.16      2309207.37      7127874.98
#Sta/Elev= 30
  4798.8  708.70  4810.6  708.43  4817.0  709.41  4822.8  709.28  4832.6  708.38
  4838.4  707.00  4854.1  706.87  4868.7  705.81  4881.3  705.62  4896.9  704.79
  4934.2  703.93  4949.6  704.34  4961.7  703.92  4971.0  703.24  4974.9  702.29
  4975.1  701.79  4978.6  701.79  4978.9  702.29  4984.9  703.33  4992.5  705.24
  4998.3  707.17  5008.1  708.70  5043.0  709.00  5051.0  709.67  5056.8  709.91
  5088.0  710.43  5093.8  710.92  5109.5  711.37  5115.3  712.16  5118.6  712.07
#Mann=4,-1,0
  4798.8    0.05       0  4934.2    0.12       0  4974.9    0.07       0
  4978.9    0.12       0
Bank Sta=4974.9,4978.9
Exp/Cntr=0.3,0.1

Type RM Length L Ch R = 1,1137,223,223,223
BEGIN DESCRIPTION:
Mapping XS b5d44d3d
END DESCRIPTION:
XS GIS Cut Line= 3
      2309234.97      7128231.04      2309268.50      7128114.55
      2309273.91      7127858.53
#Sta/Elev= 30
  4874.8  705.17  4886.3  704.89  4896.7  704.42  4909.9  705.15  4917.5  705.21
  4927.9  704.50  4943.6  704.04  4948.8  703.59  4959.1  703.50  4977.2  702.61
  4982.4  702.64  4990.3  702.18  4993.8  697.87  4994.0  697.37  4997.5  697.37
  4997.8  697.87  5000.8  697.87  5010.6  700.16  5020.6  700.68  5030.6  703.83
  5040.6  704.92  5050.6  705.16  5070.6  706.24  5080.6  706.60  5140.6  707.78
  5170.6  709.01  5190.6  710.34  5210.6  711.02  5219.8  711.15  5252.1  711.70
#Mann=4,-1,0
  4874.8    0.05       0  4993.8   0.033       0  4997.8    0.05       0
  5219.8    0.12       0
Bank Sta=4993.8,4997.8
Exp/Cntr=0.3,0.1

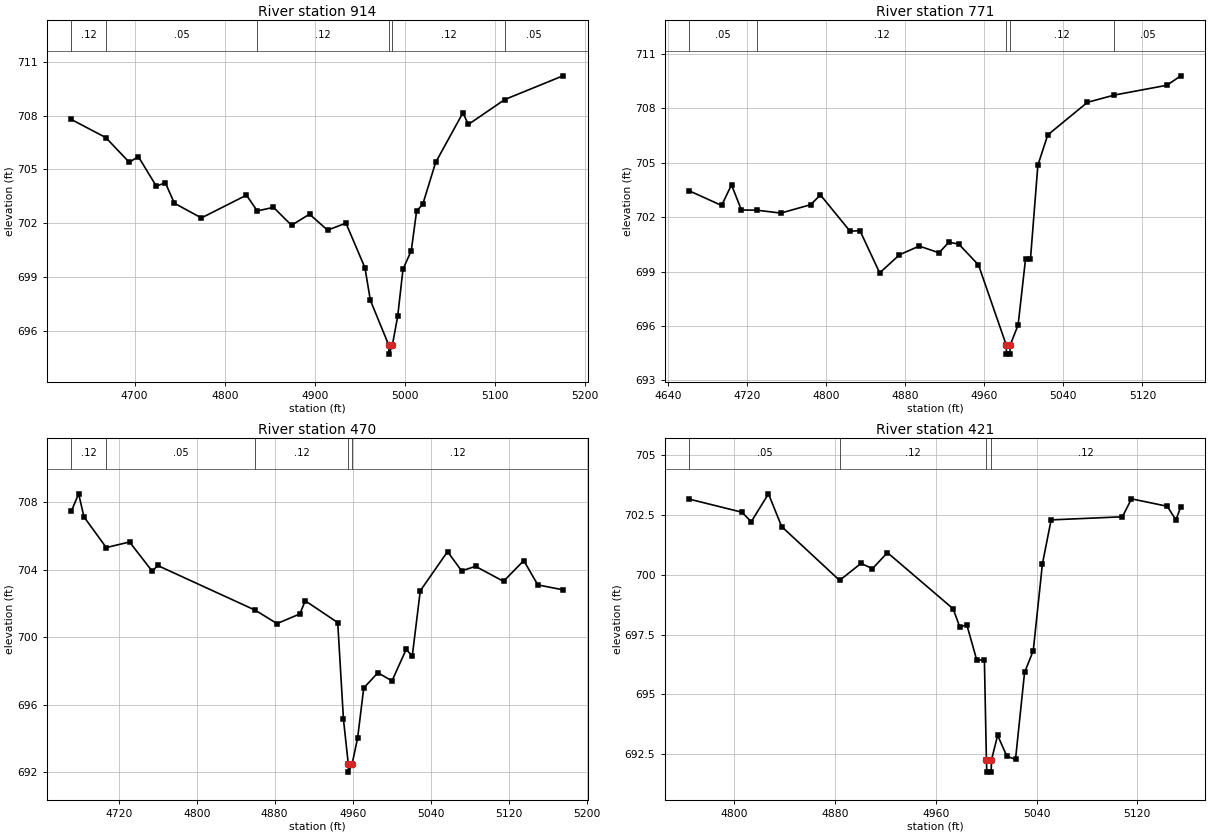
Type RM Length L Ch R = 1,914,143,143,143
BEGIN DESCRIPTION:
Mapping XS 7a19ad9a
END DESCRIPTION:
XS GIS Cut Line= 3
      2309472.98      7128374.38      2309472.67      7128081.15
      2309334.84      7127869.75
#Sta/Elev= 30
  4629.7  707.79  4668.0  706.78  4694.1  705.40  4704.1  705.72  4724.1  704.07
  4734.1  704.26  4744.1  703.12  4774.1  702.30  4824.1  703.57  4836.1  702.69
  4854.1  702.89  4874.1  701.89  4894.1  702.51  4914.1  701.62  4934.5  702.01
  4955.6  699.52  4961.6  697.71  4982.0  695.21  4982.2  694.71  4986.0  695.21
  4991.9  696.81  4997.8  699.44  5007.0  700.48  5012.9  702.68  5019.8  703.07
  5034.0  705.39  5064.3  708.16  5070.3  707.51  5110.8  708.90  5175.3  710.22
#Mann=6,-1,0
  4629.7    0.12       0  4668.0    0.05       0  4836.1    0.12       0
  4982.0    0.07       0  4986.0    0.12       0  5110.8    0.05       0
Bank Sta=4982,4986
Exp/Cntr=0.3,0.1

Type RM Length L Ch R = 1,771,301,301,301
BEGIN DESCRIPTION:
Denton Creek Tributary 35 2.0
END DESCRIPTION:
XS GIS Cut Line= 3
      2309533.39      7128252.92      2309529.00      7127910.00
      2309513.95      7127755.99
#Sta/Elev= 30
  4661.2  703.46  4694.1  702.65  4704.1  703.79  4714.1  702.40  4729.4  702.39
  4754.1  702.23  4784.1  702.69  4794.1  703.23  4824.1  701.23  4834.1  701.26
  4854.1  698.93  4874.1  699.93  4894.1  700.41  4914.1  700.04  4924.1  700.62
  4934.1  700.52  4954.1  699.37  4982.2  694.95  4982.4  694.45  4985.9  694.45
  4986.2  694.95  4994.2  696.06  5001.7  699.69  5006.7  699.69  5014.2  704.87
  5024.2  706.54  5064.4  708.34  5091.7  708.74  5144.8  709.28  5158.9  709.80
#Mann=5,-1,0
  4661.2    0.05       0  4729.4    0.12       0  4982.2    0.07       0
  4986.2    0.12       0  5091.7    0.05       0
Bank Sta=4982.2,4986.2
Exp/Cntr=0.3,0.1

Type RM Length L Ch R = 1,470,49,49,49
BEGIN DESCRIPTION:
Mapping XS 8dfd056e
END DESCRIPTION:
XS GIS Cut Line= 4
      2309500.12      7128369.96      2309607.53      7128124.32
      2309666.19      7128048.32      2309774.58      7127959.09
#Sta/Elev= 30
  4671.3  707.45  4678.9  708.49  4684.3  707.13  4707.2  705.31  4731.1  705.64
  4754.5  703.90  4759.9  704.25  4860.2  701.60  4882.4  700.81  4905.8  701.38
  4911.4  702.16  4944.7  700.87  4950.6  695.14  4955.5  692.52  4955.7  692.02
  4959.5  692.52  4965.1  694.03  4971.4  697.00  4985.9  697.90  5000.4  697.42
  5014.9  699.28  5021.2  698.89  5029.4  702.75  5057.4  705.07  5071.8  703.93
  5086.1  704.20  5114.8  703.31  5135.6  704.54  5150.0  703.10  5175.8  702.81
#Mann=5,-1,0
  4671.3    0.12       0  4707.2    0.05       0  4860.2    0.12       0
  4955.5    0.07       0  4959.5    0.12       0
Bank Sta=4955.5,4959.5
Exp/Cntr=0.3,0.1

Type RM Length L Ch R = 1,421,0,0,0
BEGIN DESCRIPTION:
Denton Creek Tributary 35 1.0
END DESCRIPTION:
XS GIS Cut Line= 3
      2309608.26      7128329.94      2309679.00      7128110.00
      2309789.03      7127994.59
#Sta/Elev= 30
  4764.1  703.17  4806.1  702.62  4813.4  702.22  4827.1  703.39  4837.6  702.02
  4883.6  699.77  4900.6  700.48  4909.7  700.26  4921.6  700.93  4973.8  698.58
  4979.1  697.81  4984.6  697.92  4992.5  696.44  4998.6  696.44  5000.2  692.25
  5000.5  691.75  5004.0  691.75  5004.2  692.25  5009.1  693.29  5016.4  692.42
  5023.3  692.28  5030.5  695.92  5037.4  696.83  5044.7  700.47  5051.6  702.30
  5108.2  702.43  5115.4  703.18  5143.8  702.87  5150.7  702.30  5154.6  702.85
#Mann=4,-1,0
  4764.1    0.05       0  4883.6    0.12       0  5000.2    0.07       0
  5004.2    0.12       0
Bank Sta=5000.2,5004.2
Exp/Cntr=0.3,0.1

Chan Stop Cuts=-1