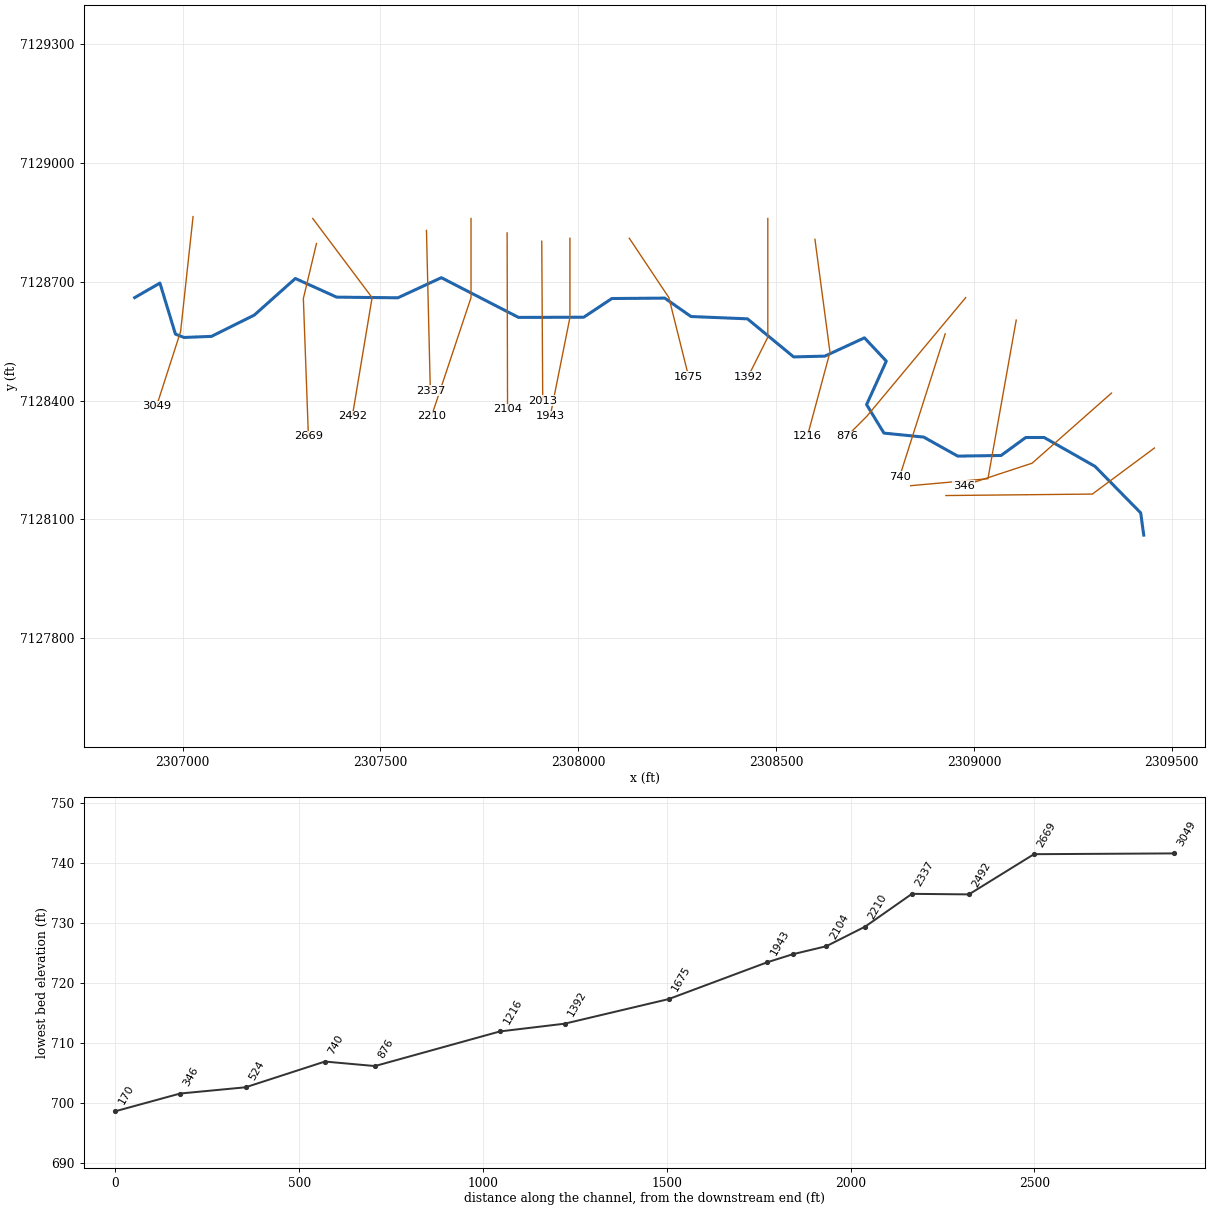
--- Denton Creek Tributary 35_1.prj (project) ---

Proj Title=Denton Creek Tributary 35_1 Base Level Engineering
Current Plan=p01
Default Exp/Contr=0.3,0.1
English Units
Geom File=g01
Flow File=f01
Plan File=p01
BEGIN DESCRIPTION:
Denton Creek Tributary 35_1
END DESCRIPTION:

--- Denton Creek Tributary 35_1.p01 (plan) ---

Plan Title=Multiple Run
Short Identifier=Multiple
Geom File=g01
Flow File=f01
Subcritical Flow
K Sum by GR= 0
Std Step Tol= 0.01
Critical Tol= 0.01
Num of Std Step Trials= 20
Max Error Tol= 0.3
Flow Tol Ratio= 0.001
Split Flow NTrial= 30
Split Flow Tol= 0.02
Split Flow Ratio= 0.02
Log Output Level= 0
Friction Slope Method= 1
Unsteady Friction Slope Method= 2
Unsteady Bridges Friction Slope Method= 1
Parabolic Critical Depth
Global Vel Dist=  1 , 1 , 1
Global Log Level= 0
CheckData=True
Encroach Param= -1, 0, 0, 0
BEGIN DESCRIPTION:
Multiple Run
END DESCRIPTION:

--- Denton Creek Tributary 35_1.f01 (steady flow) ---

Flow Title=Multiple
Number of Profiles=7
Profile Names=10-year,25-year,50-year,1pct_min,100-year,1pct_plu,500-year
River Rch & RM= Denton Creek Tri,Reach-1,3049
     425     572     691     416     830    1657    1199
Boundary for River Rch & Prof#=Denton Creek Tri,Reach-1,1
Up Type=0
Dn Type=3
Dn Slope=0.005
Boundary for River Rch & Prof#=Denton Creek Tri,Reach-1,2
Up Type=0
Dn Type=3
Dn Slope=0.005
Boundary for River Rch & Prof#=Denton Creek Tri,Reach-1,3
Up Type=0
Dn Type=3
Dn Slope=0.005
Boundary for River Rch & Prof#=Denton Creek Tri,Reach-1,4
Up Type=0
Dn Type=3
Dn Slope=0.005
Boundary for River Rch & Prof#=Denton Creek Tri,Reach-1,5
Up Type=0
Dn Type=3
Dn Slope=0.005
Boundary for River Rch & Prof#=Denton Creek Tri,Reach-1,6
Up Type=0
Dn Type=3
Dn Slope=0.005
Boundary for River Rch & Prof#=Denton Creek Tri,Reach-1,7
Up Type=0
Dn Type=3
Dn Slope=0.005

--- Denton Creek Tributary 35_1.g01 (geometry) ---

Geom Title=Existing Conditions

River Reach=Denton Creek Tri,Reach-1
Reach XY= 30
      2306879.00      7128660.00      2306942.85      7128696.77
      2306982.03      7128567.89      2307003.69      7128559.39
      2307072.94      7128562.10      2307181.29      7128615.85
      2307285.04      7128708.37      2307389.50      7128661.24
      2307544.18      7128659.57      2307654.00      7128710.41
      2307849.03      7128610.06      2308013.78      7128610.52
      2308084.94      7128657.75      2308218.49      7128658.79
      2308284.94      7128612.27      2308427.53      7128606.44
      2308544.22      7128510.25      2308623.03      7128512.19
      2308723.20      7128558.46      2308778.46      7128499.57
      2308728.62      7128389.72      2308772.45      7128317.74
      2308873.02      7128307.64      2308958.87      7128259.61
      2309068.50      7128261.23      2309130.74      7128306.63
      2309177.28      7128306.66      2309305.82      7128233.71
      2309421.24      7128116.21      2309429.00      7128060.00

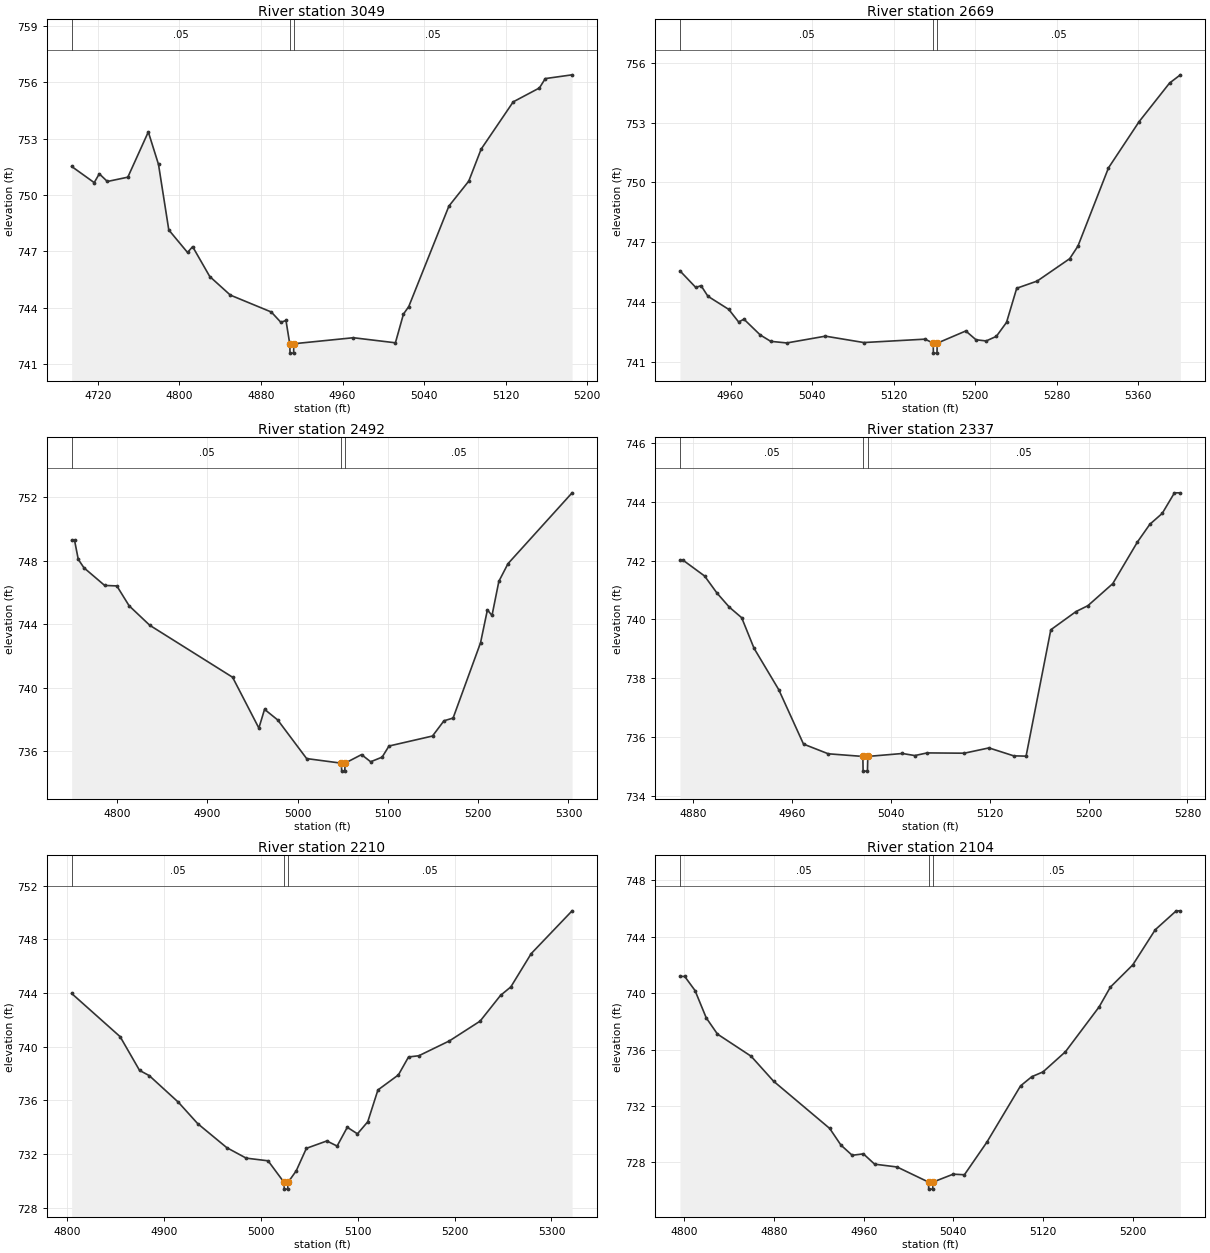
Type RM Length L Ch R = 1,3049,380,380,380
BEGIN DESCRIPTION:
Denton Creek Tributary 35_1 9.0
END DESCRIPTION:
XS GIS Cut Line= 3
      2307026.62      7128864.75      2306995.12      7128574.40
      2306934.00      7128384.97
#Sta/Elev= 30
  4694.2  751.52  4716.3  750.66  4721.3  751.13  4729.2  750.72  4749.3  750.95
  4769.4  753.36  4779.4  751.63  4789.5  748.14  4807.9  746.94  4812.9  747.25
  4829.7  745.66  4849.9  744.67  4890.1  743.77  4899.5  743.22  4904.5  743.32
  4908.2  742.08  4908.5  741.58  4912.0  741.58  4912.2  742.08  4970.6  742.40
  5011.9  742.13  5019.8  743.66  5025.0  744.06  5064.4  749.41  5083.9  750.74
  5096.0  752.44  5127.5  754.96  5153.2  755.70  5159.0  756.20  5185.3  756.40
#Mann=3,-1,0
  4694.2    0.05       0  4908.2   0.033       0  4912.2    0.05       0
Bank Sta=4908.2,4912.2
Exp/Cntr=0.3,0.1

Type RM Length L Ch R = 1,2669,177,177,177
BEGIN DESCRIPTION:
Mapping XS b92d2a02
END DESCRIPTION:
XS GIS Cut Line= 3
      2307338.42      7128796.63      2307305.32      7128657.76
      2307318.09      7128309.46
#Sta/Elev= 30
  4910.3  745.57  4925.8  744.74  4931.0  744.83  4937.7  744.30  4958.2  743.64
  4967.9  743.01  4973.1  743.15  4989.1  742.36  4999.4  742.04  5015.2  741.96
  5053.1  742.30  5090.8  741.98  5150.9  742.15  5158.9  741.95  5159.1  741.45
  5162.6  741.45  5162.9  741.95  5190.9  742.56  5200.9  742.12  5210.9  742.06
  5220.9  742.29  5230.9  742.99  5240.9  744.70  5261.0  745.06  5292.9  746.18
  5301.0  746.81  5331.0  750.73  5361.0  753.04  5391.0  754.98  5401.6  755.39
#Mann=3,-1,0
  4910.3    0.05       0  5158.9   0.033       0  5162.9    0.05       0
Bank Sta=5158.9,5162.9
Exp/Cntr=0.3,0.1

Type RM Length L Ch R = 1,2492,155,155,155
BEGIN DESCRIPTION:
Denton Creek Tributary 35_1 8.0
END DESCRIPTION:
XS GIS Cut Line= 3
      2307328.97      7128860.04      2307479.00      7128660.00
      2307429.00      7128359.98
#Sta/Elev= 30
  4749.8  749.27  4753.0  749.27  4757.1  748.08  4763.4  747.55  4786.3  746.44
  4799.8  746.41  4813.4  745.16  4836.3  743.93  4928.0  740.66  4957.1  737.46
  4963.4  738.64  4978.0  737.97  5010.0  735.54  5048.5  735.25  5048.8  734.75
  5052.3  734.75  5052.5  735.25  5070.8  735.79  5080.9  735.34  5093.6  735.63
  5101.2  736.33  5149.4  736.96  5162.1  737.92  5172.2  738.09  5202.6  742.83
  5210.2  744.90  5215.3  744.55  5222.9  746.70  5233.0  747.81  5304.0  752.27
#Mann=3,-1,0
  4749.8    0.05       0  5048.5   0.033       0  5052.5    0.05       0
Bank Sta=5048.5,5052.5
Exp/Cntr=0.3,0.1

Type RM Length L Ch R = 1,2337,127,127,127
BEGIN DESCRIPTION:
Mapping XS c3f69b5b
END DESCRIPTION:
XS GIS Cut Line= 2
      2307616.41      7128829.85      2307626.14      7128425.27
#Sta/Elev= 30
  4869.6  742.02  4872.0  742.02  4889.5  741.48  4899.5  740.90  4909.5  740.42
  4919.5  740.06  4929.5  739.02  4949.5  737.61  4969.5  735.76  4989.5  735.43
  5017.5  735.34  5017.7  734.84  5021.2  734.84  5021.5  735.34  5049.5  735.44
  5059.5  735.37  5069.5  735.46  5099.5  735.45  5119.5  735.63  5139.5  735.36
  5149.5  735.35  5169.5  739.65  5189.9  740.27  5199.5  740.47  5219.6  741.22
  5239.6  742.64  5249.6  743.24  5259.6  743.61  5269.5  744.31  5274.3  744.31
#Mann=3,-1,0
  4869.6    0.05       0  5017.5   0.033       0  5021.5    0.05       0
Bank Sta=5017.5,5021.5
Exp/Cntr=0.3,0.1

Type RM Length L Ch R = 1,2210,106,106,106
BEGIN DESCRIPTION:
Denton Creek Tributary 35_1 7.0
END DESCRIPTION:
XS GIS Cut Line= 3
      2307729.00      7128859.97      2307729.00      7128660.00
      2307629.00      7128360.00
#Sta/Elev= 30
  4805.1  743.97  4855.1  740.75  4875.1  738.24  4885.1  737.85  4915.1  735.87
  4935.1  734.27  4965.1  732.48  4985.1  731.70  5007.7  731.50  5024.2  729.89
  5024.4  729.39  5027.9  729.39  5028.2  729.89  5036.7  730.75  5047.2  732.43
  5068.3  732.98  5078.9  732.60  5089.4  734.00  5099.9  733.51  5110.5  734.41
  5121.0  736.78  5142.1  737.90  5152.6  739.24  5163.2  739.33  5194.8  740.44
  5226.4  741.91  5247.5  743.83  5258.1  744.46  5279.1  746.94  5321.3  750.13
#Mann=3,-1,0
  4805.1    0.05       0  5024.2   0.033       0  5028.2    0.05       0
Bank Sta=5024.2,5028.2
Exp/Cntr=0.3,0.1

Type RM Length L Ch R = 1,2104,91,91,91
BEGIN DESCRIPTION:
Mapping XS f0ce0923
END DESCRIPTION:
XS GIS Cut Line= 2
      2307820.23      7128823.35      2307821.30      7128377.55
#Sta/Elev= 30
  4796.4  741.19  4800.6  741.19  4809.8  740.19  4819.8  738.25  4829.8  737.10
  4859.8  735.53  4879.8  733.76  4929.8  730.41  4939.8  729.23  4949.8  728.51
  4959.8  728.61  4969.8  727.88  4989.8  727.68  5017.8  726.61  5018.0  726.11
  5021.5  726.11  5021.8  726.61  5039.8  727.17  5049.8  727.13  5069.8  729.44
  5099.8  733.43  5109.8  734.08  5119.8  734.42  5139.8  735.85  5169.8  739.03
  5179.8  740.43  5199.8  742.01  5219.8  744.50  5238.5  745.84  5242.2  745.84
#Mann=3,-1,0
  4796.4    0.05       0  5017.8   0.033       0  5021.8    0.05       0
Bank Sta=5017.8,5021.8
Exp/Cntr=0.3,0.1

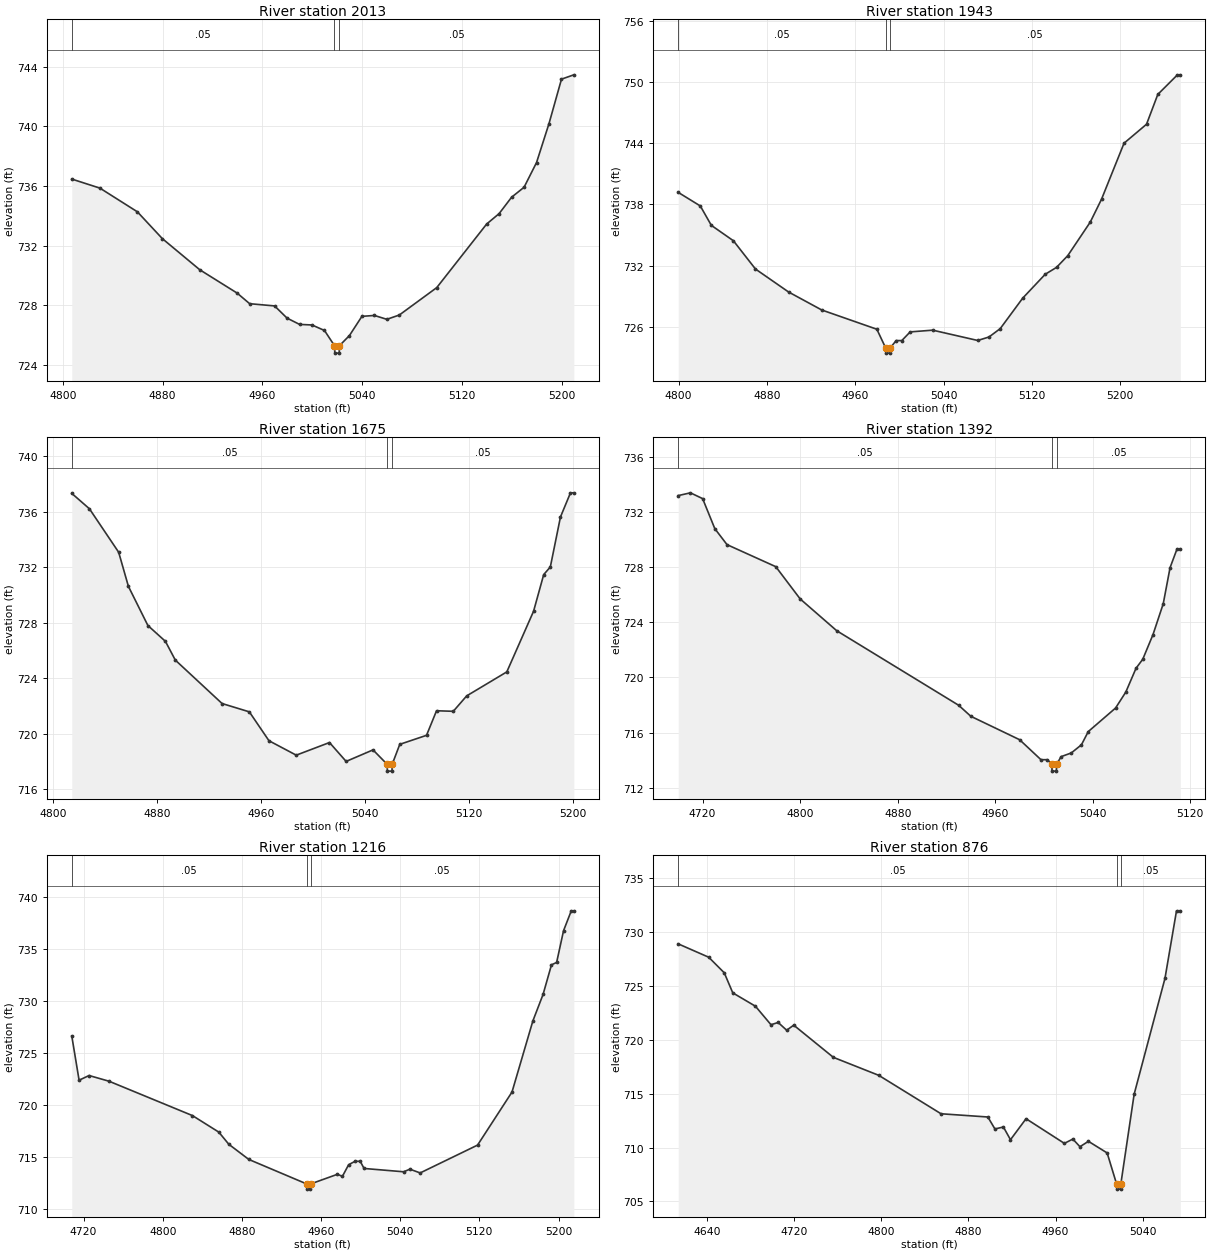
Type RM Length L Ch R = 1,2013,70,70,70
BEGIN DESCRIPTION:
Mapping XS f0085d42
END DESCRIPTION:
XS GIS Cut Line= 2
      2307907.77      7128802.60      2307910.21      7128400.10
#Sta/Elev= 30
  4807.2  736.47  4829.8  735.86  4859.8  734.27  4879.8  732.47  4909.8  730.38
  4939.8  728.81  4949.8  728.10  4969.8  727.95  4979.8  727.13  4989.8  726.71
  4999.8  726.67  5009.8  726.30  5017.8  725.28  5018.1  724.78  5021.6  724.78
  5021.8  725.28  5029.8  725.96  5039.8  727.25  5049.8  727.31  5059.8  727.05
  5069.8  727.34  5099.8  729.18  5139.8  733.45  5149.8  734.15  5159.8  735.25
  5169.8  735.92  5179.8  737.58  5189.8  740.20  5199.8  743.18  5209.7  743.47
#Mann=3,-1,0
  4807.2    0.05       0  5017.8   0.033       0  5021.8    0.05       0
Bank Sta=5017.8,5021.8
Exp/Cntr=0.3,0.1

Type RM Length L Ch R = 1,1943,268,268,268
BEGIN DESCRIPTION:
Denton Creek Tributary 35_1 6.0
END DESCRIPTION:
XS GIS Cut Line= 3
      2307979.00      7128810.00      2307979.00      7128610.00
      2307928.99      7128359.95
#Sta/Elev= 30
  4799.6  739.18  4819.6  737.85  4829.6  735.95  4849.6  734.44  4869.6  731.67
  4899.6  729.42  4929.6  727.66  4979.6  725.77  4987.6  723.93  4987.9  723.43
  4991.4  723.43  4991.6  723.93  4997.1  724.66  5002.2  724.66  5009.8  725.51
  5030.2  725.68  5071.0  724.67  5081.2  725.01  5091.4  725.83  5111.8  728.82
  5132.2  731.16  5142.4  731.83  5152.6  732.98  5173.0  736.27  5183.2  738.51
  5203.6  744.00  5224.0  745.86  5234.2  748.78  5252.0  750.70  5254.6  750.70
#Mann=3,-1,0
  4799.6    0.05       0  4987.6   0.033       0  4991.6    0.05       0
Bank Sta=4987.6,4991.6
Exp/Cntr=0.3,0.1

Type RM Length L Ch R = 1,1675,283,283,283
BEGIN DESCRIPTION:
Denton Creek Tributary 35_1 5.0
END DESCRIPTION:
XS GIS Cut Line= 3
      2308128.98      7128810.03      2308229.00      7128660.00
      2308279.01      7128459.97
#Sta/Elev= 30
  4814.3  737.31  4827.9  736.20  4850.4  733.07  4857.9  730.61  4872.9  727.79
  4886.4  726.65  4894.0  725.30  4930.0  722.17  4951.0  721.57  4966.1  719.49
  4987.1  718.45  5012.7  719.36  5025.5  718.00  5046.2  718.83  5057.0  717.80
  5057.3  717.30  5060.8  717.30  5061.0  717.80  5066.8  719.23  5087.4  719.88
  5095.1  721.65  5108.0  721.61  5118.3  722.72  5149.2  724.45  5169.8  728.82
  5177.6  731.46  5182.7  732.01  5190.5  735.61  5198.2  737.35  5200.8  737.35
#Mann=3,-1,0
  4814.3    0.05       0  5057.0   0.033       0  5061.0    0.05       0
Bank Sta=5057,5061
Exp/Cntr=0.3,0.1

Type RM Length L Ch R = 1,1392,176,176,176
BEGIN DESCRIPTION:
Denton Creek Tributary 35_1 4.0
END DESCRIPTION:
XS GIS Cut Line= 3
      2308479.00      7128859.99      2308479.00      7128560.00
      2308429.00      7128460.00
#Sta/Elev= 30
  4700.0  733.20  4710.0  733.40  4720.0  732.98  4730.0  730.80  4740.0  729.64
  4780.0  728.04  4800.0  725.70  4830.0  723.39  4930.0  717.98  4940.0  717.18
  4980.0  715.48  4997.5  714.03  5002.8  714.03  5006.4  713.70  5006.6  713.20
  5010.1  713.20  5010.4  713.70  5014.0  714.25  5022.4  714.52  5030.7  715.11
  5036.3  716.07  5058.7  717.78  5067.1  718.94  5075.5  720.67  5081.0  721.32
  5089.4  723.11  5097.8  725.35  5103.4  727.97  5109.0  729.30  5111.8  729.30
#Mann=3,-1,0
  4700.0    0.05       0  5006.4   0.033       0  5010.4    0.05       0
Bank Sta=5006.4,5010.4
Exp/Cntr=0.3,0.1

Type RM Length L Ch R = 1,1216,340,340,340
BEGIN DESCRIPTION:
Denton Creek Tributary 35_1 3.0
END DESCRIPTION:
XS GIS Cut Line= 3
      2308598.10      7128807.34      2308636.05      7128522.04
      2308579.00      7128310.00
#Sta/Elev= 30
  4708.1  726.66  4715.5  722.40  4725.6  722.85  4745.8  722.30  4830.1  718.99
  4856.7  717.40  4866.8  716.23  4887.0  714.77  4945.5  712.41  4945.8  711.91
  4949.3  711.91  4949.5  712.41  4976.6  713.34  4981.6  713.14  4987.9  714.26
  4994.4  714.59  4999.6  714.59  5003.5  713.90  5043.5  713.58  5049.8  713.83
  5060.2  713.47  5118.2  716.15  5153.0  721.26  5174.1  728.11  5184.4  730.66
  5192.9  733.51  5198.1  733.74  5205.1  736.80  5212.9  738.71  5215.5  738.71
#Mann=3,-1,0
  4708.1    0.05       0  4945.5   0.033       0  4949.5    0.05       0
Bank Sta=4945.5,4949.5
Exp/Cntr=0.3,0.1

Type RM Length L Ch R = 1,876,136,136,136
BEGIN DESCRIPTION:
Denton Creek Tributary 35_1 2.0
END DESCRIPTION:
XS GIS Cut Line= 3
      2308978.99      7128659.98      2308729.00      7128360.00
      2308679.00      7128310.00
#Sta/Elev= 30
  4613.4  728.92  4641.4  727.68  4655.7  726.23  4663.5  724.37  4684.3  723.13
  4698.6  721.41  4705.2  721.62  4713.0  720.90  4719.5  721.37  4755.9  718.38
  4797.6  716.71  4854.8  713.14  4897.8  712.84  4904.3  711.73  4912.1  711.91
  4918.6  710.73  4932.9  712.68  4968.1  710.39  4975.9  710.79  4982.4  710.08
  4990.2  710.58  5007.4  709.50  5016.0  706.64  5016.3  706.14  5019.8  706.14
  5020.0  706.64  5032.2  714.96  5060.5  725.71  5071.1  731.99  5074.6  731.99
#Mann=3,-1,0
  4613.4    0.05       0  5016.0   0.033       0  5020.0    0.05       0
Bank Sta=5016,5020
Exp/Cntr=0.3,0.1

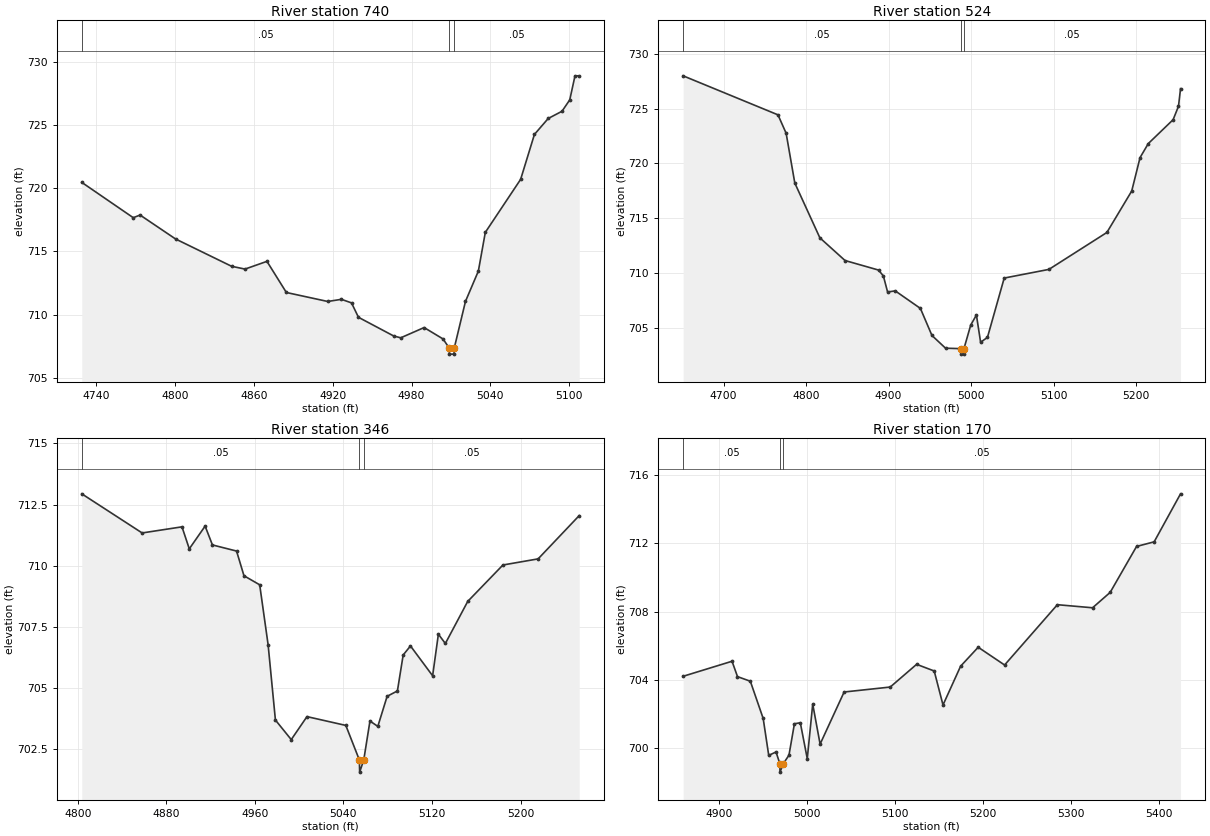
Type RM Length L Ch R = 1,740,216,216,216
BEGIN DESCRIPTION:
Mapping XS 912dcbb7
END DESCRIPTION:
XS GIS Cut Line= 2
      2308927.17      7128568.39      2308812.04      7128207.51
#Sta/Elev= 30
  4728.9  720.46  4768.1  717.67  4773.3  717.88  4800.3  715.99  4843.0  713.83
  4853.2  713.61  4869.9  714.22  4884.7  711.76  4916.2  711.05  4926.6  711.22
  4934.3  710.94  4939.6  709.80  4966.5  708.32  4971.8  708.18  4989.6  708.99
  5004.0  708.09  5008.6  707.39  5008.9  706.89  5012.4  706.89  5012.6  707.39
  5021.1  711.06  5030.9  713.45  5036.2  716.51  5063.1  720.70  5073.6  724.25
  5084.1  725.51  5094.6  726.08  5100.5  726.98  5104.5  728.88  5107.7  728.88
#Mann=3,-1,0
  4728.9    0.05       0  5008.6   0.033       0  5012.6    0.05       0
Bank Sta=5008.6,5012.6
Exp/Cntr=0.3,0.1

Type RM Length L Ch R = 1,524,178,178,178
BEGIN DESCRIPTION:
Mapping XS 8d06d6c0
END DESCRIPTION:
XS GIS Cut Line= 3
      2309106.74      7128603.25      2309035.30      7128202.48
      2308840.08      7128184.91
#Sta/Elev= 30
  4650.9  727.99  4765.9  724.43  4775.8  722.75  4786.3  718.21  4816.7  713.21
  4847.2  711.14  4887.8  710.27  4893.7  709.73  4898.8  708.27  4908.1  708.37
  4938.6  706.77  4952.6  704.30  4969.1  703.14  4987.4  703.10  4987.7  702.60
  4991.2  702.60  4991.4  703.10  4999.6  705.25  5006.5  706.17  5011.6  703.68
  5019.9  704.13  5040.2  709.54  5094.4  710.33  5164.7  713.70  5194.8  717.48
  5204.9  720.53  5214.9  721.81  5245.0  723.99  5251.5  725.21  5254.0  726.82
#Mann=3,-1,0
  4650.9    0.05       0  4987.4   0.033       0  4991.4    0.05       0
Bank Sta=4987.4,4991.4
Exp/Cntr=0.3,0.1

Type RM Length L Ch R = 1,346,176,176,176
BEGIN DESCRIPTION:
Mapping XS d83181f6
END DESCRIPTION:
XS GIS Cut Line= 3
      2309347.40      7128418.79      2309146.95      7128241.76
      2308974.20      7128184.92
#Sta/Elev= 30
  4803.7  712.94  4858.2  711.34  4894.2  711.59  4900.8  710.69  4915.1  711.62
  4921.7  710.85  4943.5  710.60  4950.2  709.59  4964.4  709.22  4972.0  706.77
  4978.6  703.69  4992.9  702.89  5007.1  703.83  5042.2  703.47  5054.4  702.06
  5054.7  701.56  5058.4  702.06  5064.0  703.65  5071.1  703.43  5079.5  704.66
  5088.8  704.88  5094.0  706.35  5100.6  706.72  5120.6  705.50  5125.8  707.20
  5132.1  706.82  5152.3  708.54  5184.1  710.03  5215.9  710.28  5253.0  712.05
#Mann=3,-1,0
  4803.7    0.05       0  5054.4   0.033       0  5058.4    0.05       0
Bank Sta=5054.4,5058.4
Exp/Cntr=0.3,0.1

Type RM Length L Ch R = 1,170,0,0,0
BEGIN DESCRIPTION:
Denton Creek Tributary 35_1 1.0
END DESCRIPTION:
XS GIS Cut Line= 3
      2309455.98      7128280.08      2309299.14      7128163.72
      2308929.04      7128160.00
#Sta/Elev= 30
  4859.3  704.22  4914.9  705.10  4921.1  704.20  4935.7  703.93  4950.3  701.75
  4956.6  699.59  4964.9  699.79  4969.2  699.11  4969.4  698.61  4973.2  699.11
  4979.6  699.60  4985.8  701.44  4992.5  701.50  5000.4  699.40  5006.6  702.59
  5015.0  700.25  5042.3  703.30  5094.7  703.59  5124.7  704.92  5144.7  704.53
  5154.7  702.54  5174.7  704.81  5194.7  705.92  5224.7  704.88  5284.7  708.41
  5324.7  708.23  5344.7  709.13  5374.7  711.82  5394.7  712.09  5424.7  714.90
#Mann=3,-1,0
  4859.3    0.05       0  4969.2   0.033       0  4973.2    0.05       0
Bank Sta=4969.2,4973.2
Exp/Cntr=0.3,0.1

Chan Stop Cuts=-1