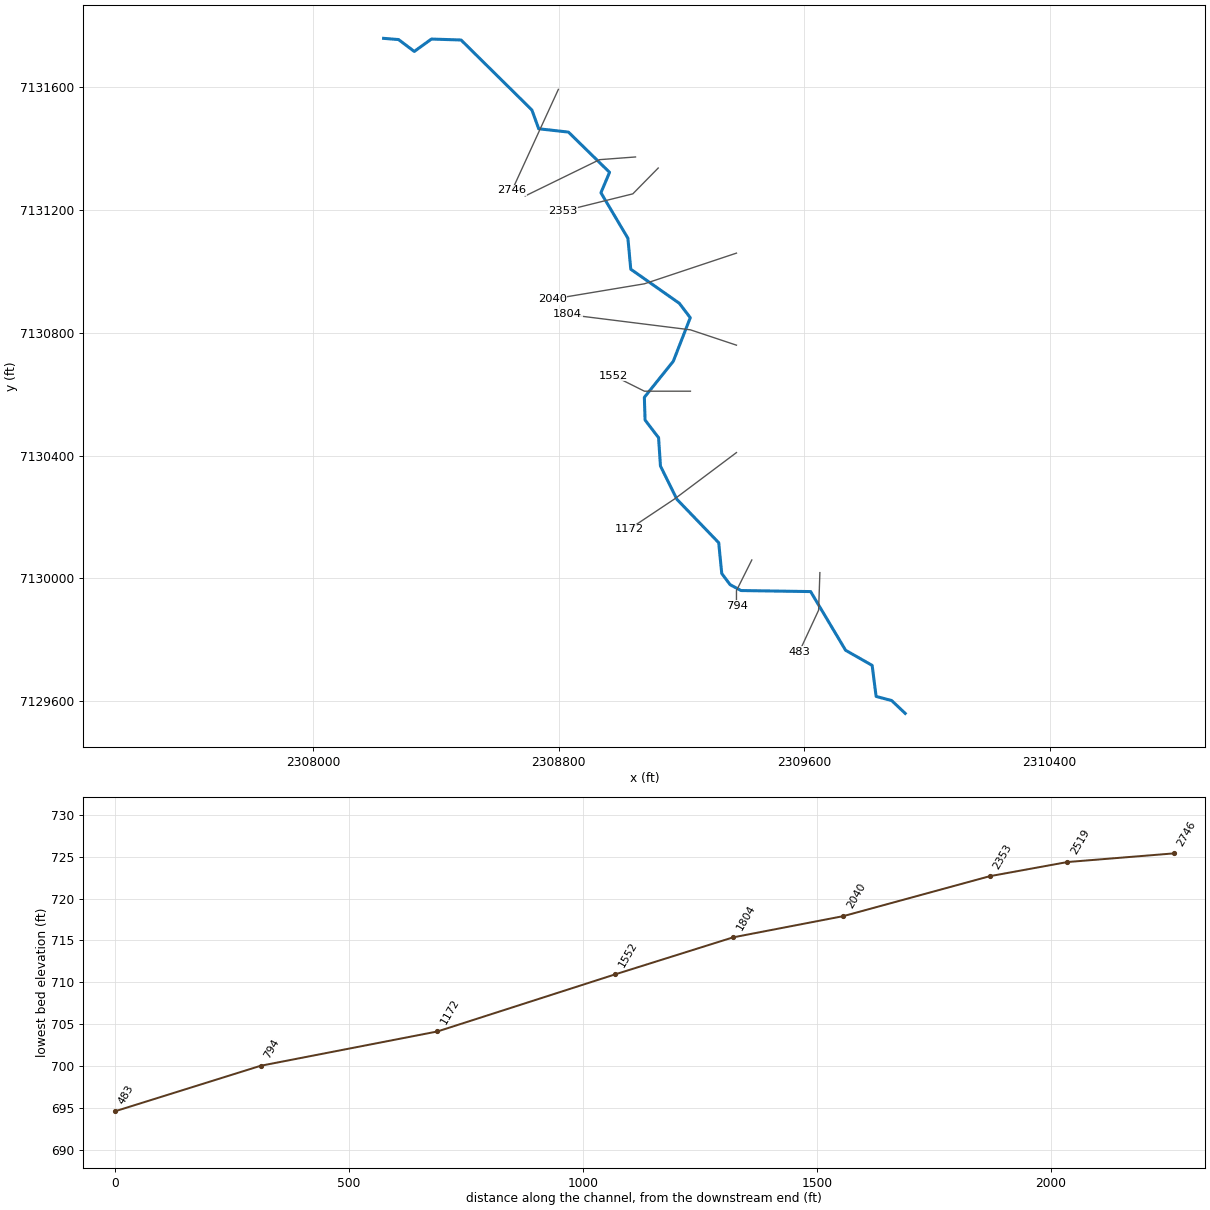
--- Denton Creek Tributary 36.prj (project) ---

Proj Title=Denton Creek Tributary 36 Base Level Engineering
Current Plan=p01
Default Exp/Contr=0.3,0.1
English Units
Geom File=g01
Flow File=f01
Plan File=p01
BEGIN DESCRIPTION:
Denton Creek Tributary 36
END DESCRIPTION:

--- Denton Creek Tributary 36.p01 (plan) ---

Plan Title=Multiple Run
Short Identifier=Multiple
Geom File=g01
Flow File=f01
Subcritical Flow
K Sum by GR= 0
Std Step Tol= 0.01
Critical Tol= 0.01
Num of Std Step Trials= 20
Max Error Tol= 0.3
Flow Tol Ratio= 0.001
Split Flow NTrial= 30
Split Flow Tol= 0.02
Split Flow Ratio= 0.02
Log Output Level= 0
Friction Slope Method= 1
Unsteady Friction Slope Method= 2
Unsteady Bridges Friction Slope Method= 1
Parabolic Critical Depth
Global Vel Dist=  1 , 1 , 1
Global Log Level= 0
CheckData=True
Encroach Param= -1, 0, 0, 0
BEGIN DESCRIPTION:
Multiple Run
END DESCRIPTION:

--- Denton Creek Tributary 36.f01 (steady flow) ---

Flow Title=Multiple
Number of Profiles=7
Profile Names=10-year,25-year,50-year,1pct_min,100-year,1pct_plu,500-year
River Rch & RM= Denton Creek Tri,Reach-1,2746
     179     224     258     148     296     590     388
River Rch & RM= Denton Creek Tri,Reach-1,2040
     375     497     594     353     705    1407     995
Boundary for River Rch & Prof#=Denton Creek Tri,Reach-1,1
Up Type=0
Dn Type=3
Dn Slope=0.005
Boundary for River Rch & Prof#=Denton Creek Tri,Reach-1,2
Up Type=0
Dn Type=3
Dn Slope=0.005
Boundary for River Rch & Prof#=Denton Creek Tri,Reach-1,3
Up Type=0
Dn Type=3
Dn Slope=0.005
Boundary for River Rch & Prof#=Denton Creek Tri,Reach-1,4
Up Type=0
Dn Type=3
Dn Slope=0.005
Boundary for River Rch & Prof#=Denton Creek Tri,Reach-1,5
Up Type=0
Dn Type=3
Dn Slope=0.005
Boundary for River Rch & Prof#=Denton Creek Tri,Reach-1,6
Up Type=0
Dn Type=3
Dn Slope=0.005
Boundary for River Rch & Prof#=Denton Creek Tri,Reach-1,7
Up Type=0
Dn Type=3
Dn Slope=0.005

--- Denton Creek Tributary 36.g01 (geometry) ---

Geom Title=Existing Conditions

River Reach=Denton Creek Tri,Reach-1
Reach XY= 30
      2308229.00      7131760.00      2308277.64      7131756.00
      2308328.96      7131717.32      2308384.89      7131757.65
      2308481.43      7131754.60      2308712.26      7131526.45
      2308734.47      7131465.26      2308831.37      7131454.45
      2308965.36      7131323.34      2308937.25      7131256.77
      2309025.17      7131108.41      2309034.52      7131007.56
      2309192.70      7130896.51      2309228.47      7130849.53
      2309173.16      7130707.71      2309078.79      7130589.95
      2309081.16      7130515.98      2309125.14      7130458.40
      2309131.33      7130365.97      2309184.83      7130257.70
      2309321.14      7130116.17      2309331.07      7130015.69
      2309358.35      7129979.40      2309394.02      7129960.32
      2309620.70      7129956.93      2309734.65      7129765.63
      2309821.19      7129716.39      2309834.11      7129615.27
      2309884.64      7129601.85      2309929.00      7129560.00

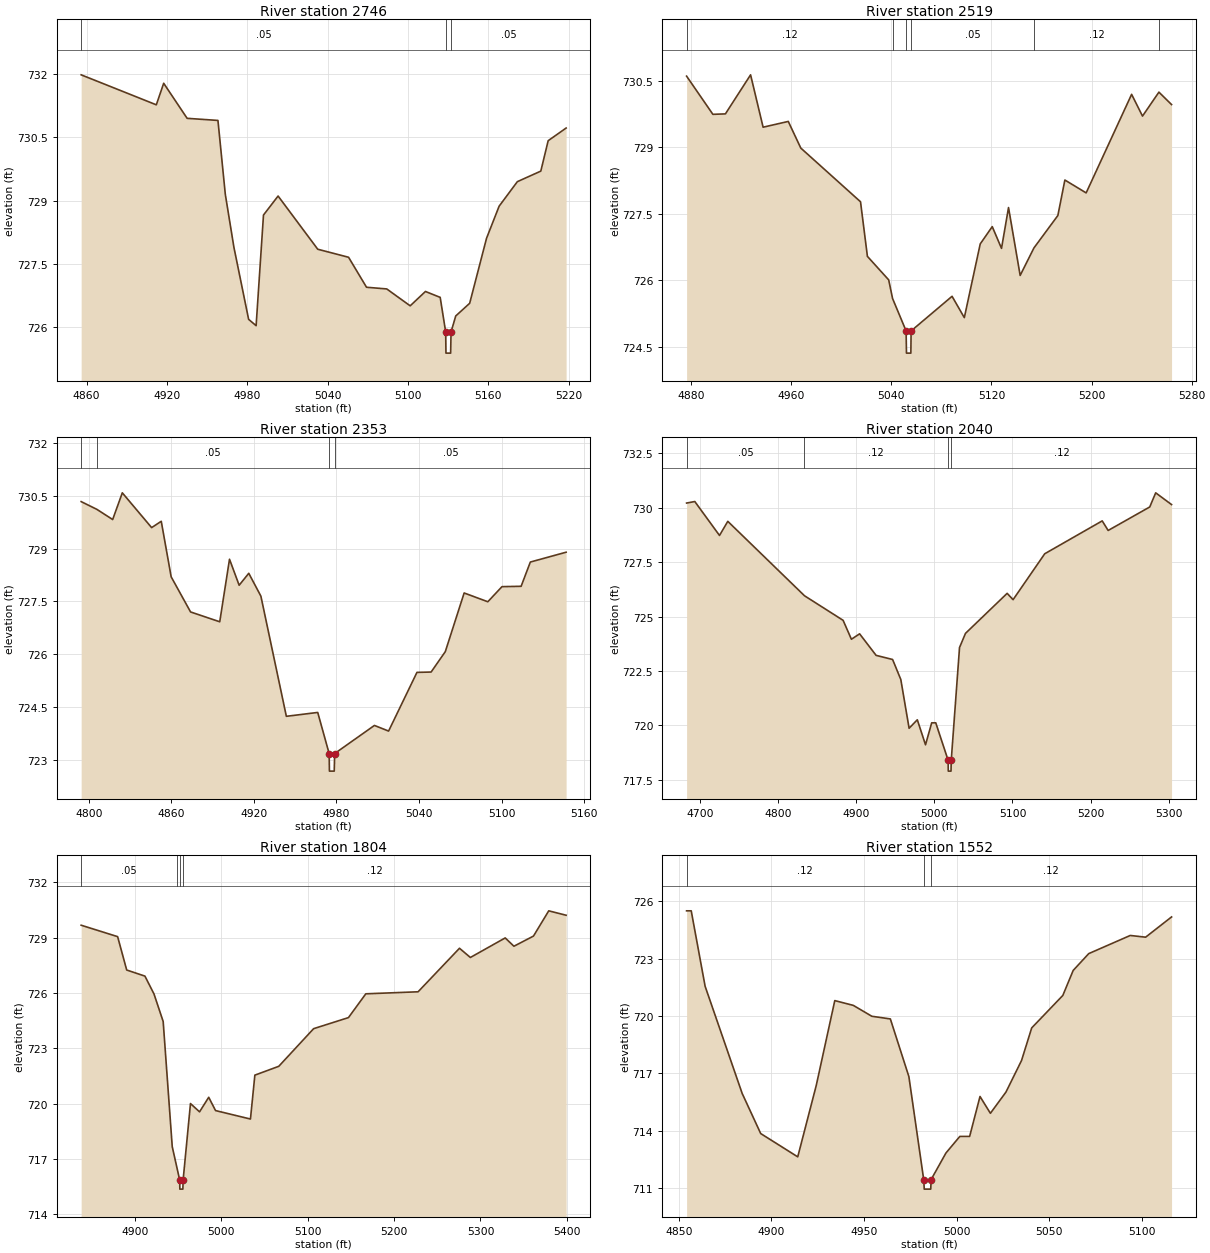
Type RM Length L Ch R = 1,2746,227,227,227
BEGIN DESCRIPTION:
Mapping XS cf953f9a
END DESCRIPTION:
XS GIS Cut Line= 2
      2308798.50      7131593.60      2308647.58      7131264.56
#Sta/Elev= 30
  4856.0  731.98  4912.1  731.27  4917.6  731.78  4935.1  730.95  4958.1  730.90
  4963.6  729.15  4970.0  727.90  4981.0  726.19  4986.6  726.04  4992.1  728.66
  5003.0  729.11  5032.6  727.85  5055.6  727.66  5069.0  726.95  5084.1  726.91
  5101.6  726.51  5113.0  726.85  5124.0  726.71  5128.1  725.89  5128.3  725.39
  5131.8  725.39  5132.1  725.89  5135.6  726.27  5146.0  726.57  5158.6  728.11
  5168.0  728.87  5181.6  729.45  5199.1  729.70  5204.6  730.42  5218.0  730.72
#Mann=3,-1,0
  4856.0    0.05       0  5128.1   0.033       0  5132.1    0.05       0
Bank Sta=5128.1,5132.1
Exp/Cntr=0.3,0.1

Type RM Length L Ch R = 1,2519,166,166,166
BEGIN DESCRIPTION:
Mapping XS 238eb5f5
END DESCRIPTION:
XS GIS Cut Line= 3
      2309049.94      7131373.39      2308932.78      7131364.58
      2308690.31      7131246.23
#Sta/Elev= 30
  4876.6  730.60  4897.6  729.74  4907.6  729.75  4927.7  730.63  4937.7  729.45
  4957.8  729.58  4967.8  728.98  5015.5  727.77  5021.0  726.54  5038.0  726.01
  5041.1  725.59  5051.9  724.86  5052.2  724.36  5055.7  724.36  5055.9  724.86
  5088.6  725.64  5098.4  725.16  5111.1  726.82  5120.7  727.21  5128.1  726.72
  5133.7  727.64  5143.0  726.11  5154.0  726.73  5173.1  727.46  5178.7  728.26
  5195.7  727.97  5232.0  730.19  5240.7  729.70  5253.8  730.24  5263.9  729.96
#Mann=6,-1,0
  4876.6    0.12       0  5041.1    0.05       0  5051.9    0.07       0
  5055.9    0.05       0  5154.0    0.12       0  5253.8    0.05       0
Bank Sta=5051.9,5055.9
Exp/Cntr=0.3,0.1

Type RM Length L Ch R = 1,2353,313,313,313
BEGIN DESCRIPTION:
Mapping XS 0ab5b829
END DESCRIPTION:
XS GIS Cut Line= 3
      2309123.99      7131337.37      2309041.26      7131253.21
      2308813.78      7131196.74
#Sta/Elev= 30
  4794.5  730.34  4805.9  730.12  4817.4  729.83  4824.4  730.59  4845.7  729.60
  4852.7  729.78  4859.9  728.20  4874.0  727.20  4895.2  726.92  4902.3  728.70
  4909.3  727.96  4916.3  728.30  4925.1  727.65  4943.6  724.23  4966.4  724.34
  4974.7  723.17  4974.9  722.67  4978.4  722.67  4978.7  723.17  5007.6  723.97
  5017.9  723.81  5038.5  725.48  5048.8  725.49  5059.1  726.07  5072.8  727.74
  5090.0  727.49  5100.3  727.92  5114.2  727.93  5120.9  728.62  5146.9  728.90
#Mann=4,-1,0
  4794.5    0.12       0  4805.9    0.05       0  4974.7   0.033       0
  4978.7    0.05       0
Bank Sta=4974.7,4978.7
Exp/Cntr=0.3,0.1

Type RM Length L Ch R = 1,2040,236,236,236
BEGIN DESCRIPTION:
Denton Creek Tributary 36 6.0
END DESCRIPTION:
XS GIS Cut Line= 3
      2309378.96      7131059.99      2309079.00      7130960.00
      2308779.02      7130910.00
#Sta/Elev= 30
  4683.2  730.22  4693.7  730.29  4725.3  728.73  4735.9  729.38  4834.0  725.96
  4883.4  724.83  4894.0  723.96  4904.5  724.21  4925.6  723.22  4946.7  723.03
  4957.2  722.11  4967.8  719.87  4978.3  720.26  4988.8  719.11  4996.7  720.12
  5001.9  720.12  5017.7  718.40  5017.9  717.90  5021.4  717.90  5021.7  718.40
  5032.3  723.58  5039.9  724.23  5093.2  726.07  5100.8  725.78  5141.3  727.89
  5214.8  729.40  5222.4  728.96  5275.6  730.04  5283.2  730.69  5303.5  730.15
#Mann=4,-1,0
  4683.2    0.05       0  4834.0    0.12       0  5017.7    0.07       0
  5021.7    0.12       0
Bank Sta=5017.7,5021.7
Exp/Cntr=0.3,0.1

Type RM Length L Ch R = 1,1804,252,252,252
BEGIN DESCRIPTION:
Denton Creek Tributary 36 5.0
END DESCRIPTION:
XS GIS Cut Line= 3
      2309379.01      7130760.00      2309229.00      7130810.00
      2308829.04      7130860.00
#Sta/Elev= 30
  4837.9  729.67  4880.1  729.05  4890.6  727.24  4911.7  726.91  4922.2  725.94
  4932.8  724.45  4943.3  717.66  4948.5  716.57  4951.9  715.86  4952.1  715.36
  4955.6  715.36  4955.9  715.86  4964.4  720.00  4974.9  719.55  4985.5  720.34
  4993.4  719.62  5033.8  719.16  5038.9  721.54  5066.6  722.02  5106.9  724.06
  5147.2  724.66  5167.3  725.95  5227.8  726.06  5275.7  728.42  5288.3  727.92
  5328.6  728.98  5338.7  728.53  5361.3  729.08  5379.0  730.45  5399.1  730.21
#Mann=4,-1,0
  4837.9    0.05       0  4948.5    0.12       0  4951.9    0.07       0
  4955.9    0.12       0
Bank Sta=4951.9,4955.9
Exp/Cntr=0.3,0.1

Type RM Length L Ch R = 1,1552,380,380,380
BEGIN DESCRIPTION:
Denton Creek Tributary 36 4.0
END DESCRIPTION:
XS GIS Cut Line= 3
      2309229.01      7130610.00      2309079.00      7130610.00
      2308979.02      7130659.99
#Sta/Elev= 30
  4854.2  725.51  4856.7  725.51  4864.2  721.56  4884.2  715.95  4894.2  713.85
  4914.2  712.63  4924.2  716.37  4934.2  720.81  4944.2  720.56  4954.2  719.99
  4964.2  719.85  4974.2  716.83  4982.2  711.44  4982.5  710.94  4986.0  710.94
  4986.2  711.44  4994.2  712.83  5001.7  713.70  5007.0  713.70  5012.6  715.79
  5018.2  714.91  5026.6  716.02  5035.0  717.67  5040.5  719.38  5057.3  721.08
  5062.9  722.39  5071.3  723.27  5093.7  724.22  5102.0  724.13  5116.0  725.19
#Mann=3,-1,0
  4854.2    0.12       0  4982.2    0.07       0  4986.2    0.12       0
Bank Sta=4982.2,4986.2
Exp/Cntr=0.3,0.1

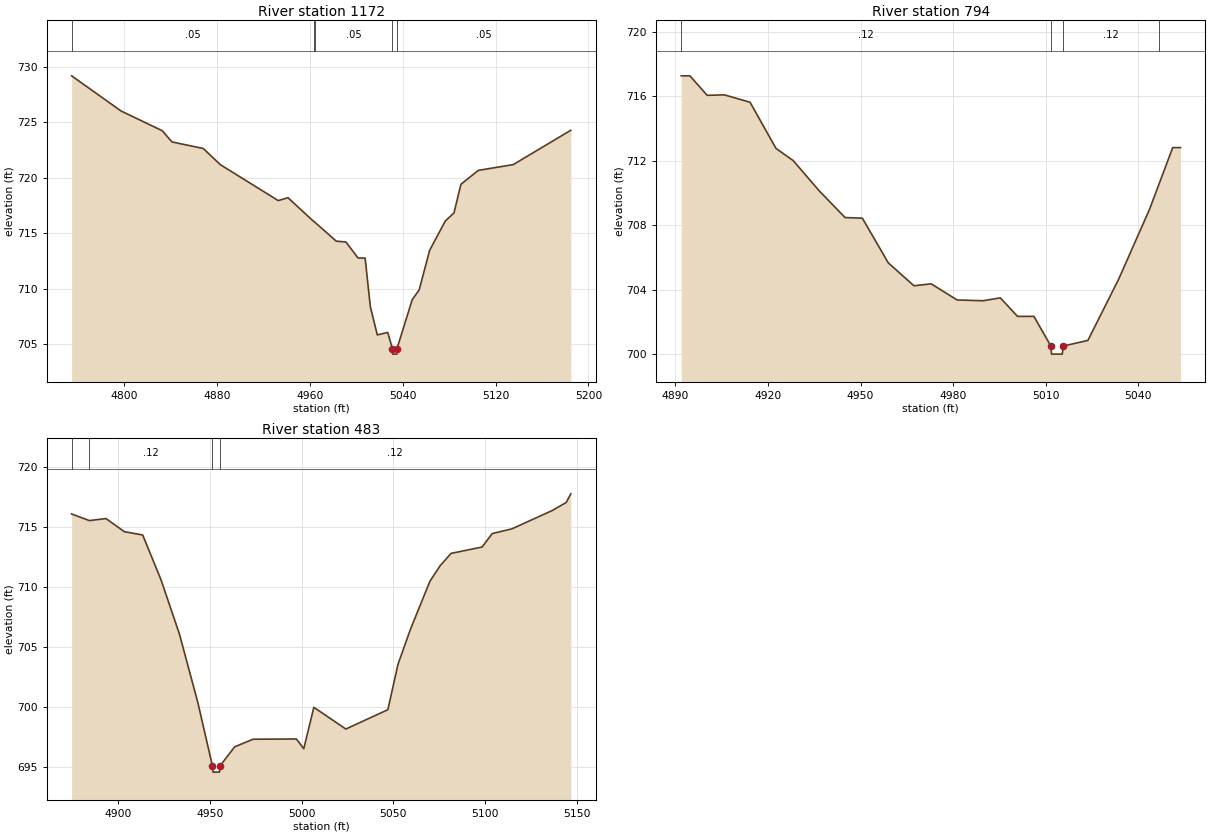
Type RM Length L Ch R = 1,1172,378,378,378
BEGIN DESCRIPTION:
Denton Creek Tributary 36 3.0
END DESCRIPTION:
XS GIS Cut Line= 3
      2309378.99      7130410.00      2309179.00      7130260.00
      2309028.98      7130159.98
#Sta/Elev= 30
  4754.5  729.17  4797.2  726.00  4832.6  724.23  4841.0  723.22  4868.0  722.63
  4882.6  721.18  4932.6  717.94  4941.0  718.20  4963.2  716.06  4964.4  715.97
  4982.6  714.29  4991.0  714.21  5001.4  712.77  5007.5  712.77  5012.0  708.39
  5018.0  705.85  5027.0  706.07  5031.0  704.62  5031.3  704.12  5034.8  704.12
  5035.0  704.62  5048.1  709.02  5054.1  709.90  5063.1  713.46  5076.6  716.10
  5084.1  716.83  5090.1  719.41  5105.1  720.66  5135.2  721.18  5184.8  724.27
#Mann=5,-1,0
  4754.5    0.05       0  4963.2    0.12       0  4964.4    0.05       0
  5031.0   0.033       0  5035.0    0.05       0
Bank Sta=5031,5035
Exp/Cntr=0.3,0.1

Type RM Length L Ch R = 1,794,311,311,311
BEGIN DESCRIPTION:
Denton Creek Tributary 36 2.0
END DESCRIPTION:
XS GIS Cut Line= 3
      2309428.99      7130059.98      2309379.00      7129960.00
      2309379.00      7129909.98
#Sta/Elev= 29
  4891.9  717.28  4894.7  717.28  4900.3  716.07  4905.9  716.10  4914.2  715.64
  4922.6  712.78  4928.2  712.02  4936.6  710.15  4945.0  708.49  4950.6  708.45
  4959.0  705.68  4967.3  704.26  4972.9  704.38  4981.3  703.38  4989.7  703.33
  4995.3  703.51  5000.9  702.36  5003.7  702.36  5006.2  702.36  5011.7  700.52
  5011.9  700.02  5015.4  700.02  5015.7  700.52  5023.7  700.87  5033.7  704.68
  5043.7  709.01  5046.6  710.49  5051.2  712.83  5053.7  712.83
#Mann=4,-1,0
  4891.9    0.12       0  5011.7    0.07       0  5015.7    0.12       0
  5046.6    0.05       0
Bank Sta=5011.7,5015.7
Exp/Cntr=0.3,0.1

Type RM Length L Ch R = 1,483,0,0,0
BEGIN DESCRIPTION:
Mapping XS d9e10e67
END DESCRIPTION:
XS GIS Cut Line= 3
      2309650.88      7130018.70      2309646.72      7129896.38
      2309583.79      7129760.87
#Sta/Elev= 30
  4874.8  716.09  4884.5  715.54  4893.5  715.71  4903.5  714.62  4913.5  714.34
  4923.5  710.60  4933.5  706.09  4943.5  700.40  4951.5  695.09  4951.8  694.59
  4955.3  694.59  4955.5  695.09  4963.6  696.70  4973.6  697.33  4997.2  697.35
  5001.2  696.54  5006.7  699.99  5024.1  698.18  5047.0  699.79  5052.5  703.57
  5059.4  706.53  5069.9  710.49  5075.4  711.77  5081.4  712.81  5098.3  713.34
  5103.8  714.46  5114.5  714.85  5136.5  716.38  5144.1  717.05  5146.6  717.77
#Mann=4,-1,0
  4874.8    0.05       0  4884.5    0.12       0  4951.5    0.07       0
  4955.5    0.12       0
Bank Sta=4951.5,4955.5
Exp/Cntr=0.3,0.1

Chan Stop Cuts=-1