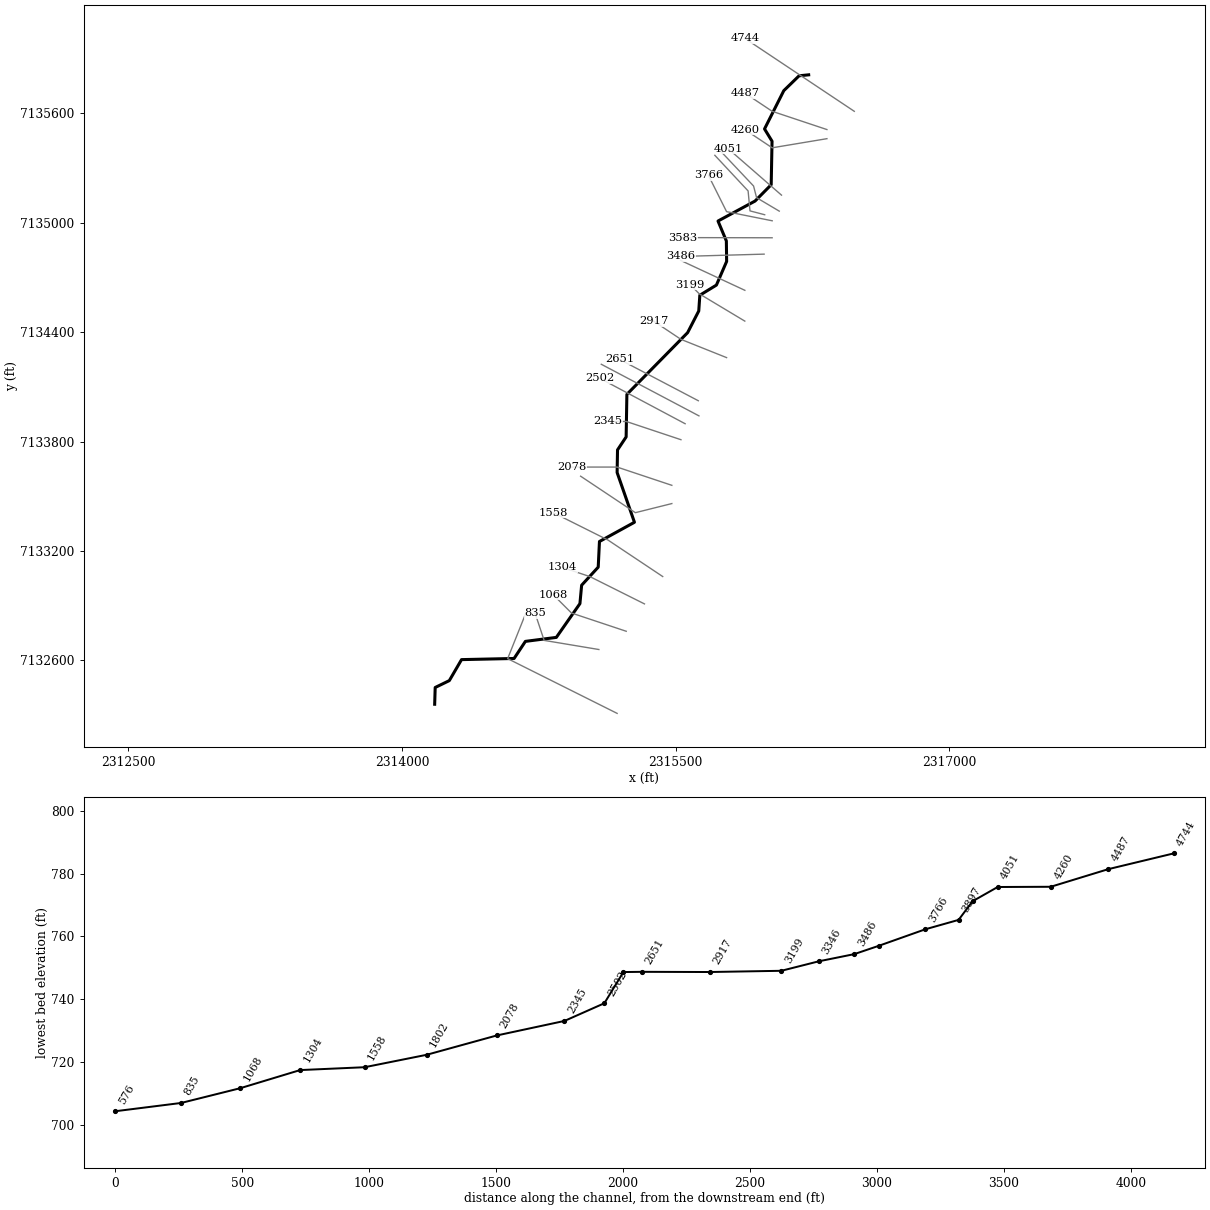
--- Denton Creek Tributary 38.prj (project) ---

Proj Title=Denton Creek Tributary 38 Base Level Engineering
Current Plan=p01
Default Exp/Contr=0.3,0.1
English Units
Geom File=g01
Flow File=f01
Plan File=p01
BEGIN DESCRIPTION:
Denton Creek Tributary 38
END DESCRIPTION:

--- Denton Creek Tributary 38.p01 (plan) ---

Plan Title=Multiple Run
Short Identifier=Multiple
Geom File=g01
Flow File=f01
Subcritical Flow
K Sum by GR= 0
Std Step Tol= 0.01
Critical Tol= 0.01
Num of Std Step Trials= 20
Max Error Tol= 0.3
Flow Tol Ratio= 0.001
Split Flow NTrial= 30
Split Flow Tol= 0.02
Split Flow Ratio= 0.02
Log Output Level= 0
Friction Slope Method= 1
Unsteady Friction Slope Method= 2
Unsteady Bridges Friction Slope Method= 1
Parabolic Critical Depth
Global Vel Dist=  1 , 1 , 1
Global Log Level= 0
CheckData=True
Encroach Param= -1, 0, 0, 0
BEGIN DESCRIPTION:
Multiple Run
END DESCRIPTION:

--- Denton Creek Tributary 38.f01 (steady flow) ---

Flow Title=Multiple
Number of Profiles=7
Profile Names=10-year,25-year,50-year,1pct_min,100-year,1pct_plu,500-year
River Rch & RM= Denton Creek Tri,Reach-1,4744
     474     646     787     478     954    1903    1400
Boundary for River Rch & Prof#=Denton Creek Tri,Reach-1,1
Up Type=0
Dn Type=3
Dn Slope=0.005
Boundary for River Rch & Prof#=Denton Creek Tri,Reach-1,2
Up Type=0
Dn Type=3
Dn Slope=0.005
Boundary for River Rch & Prof#=Denton Creek Tri,Reach-1,3
Up Type=0
Dn Type=3
Dn Slope=0.005
Boundary for River Rch & Prof#=Denton Creek Tri,Reach-1,4
Up Type=0
Dn Type=3
Dn Slope=0.005
Boundary for River Rch & Prof#=Denton Creek Tri,Reach-1,5
Up Type=0
Dn Type=3
Dn Slope=0.005
Boundary for River Rch & Prof#=Denton Creek Tri,Reach-1,6
Up Type=0
Dn Type=3
Dn Slope=0.005
Boundary for River Rch & Prof#=Denton Creek Tri,Reach-1,7
Up Type=0
Dn Type=3
Dn Slope=0.005

--- Denton Creek Tributary 38.g01 (geometry) ---

Geom Title=Existing Conditions

River Reach=Denton Creek Tri,Reach-1
Reach XY= 30
      2316229.00      7135810.00      2316176.46      7135804.70
      2316092.60      7135723.24      2315987.04      7135513.32
      2316028.17      7135446.14      2316023.55      7135207.53
      2315935.07      7135118.13      2315732.04      7135008.58
      2315777.77      7134899.50      2315779.32      7134787.16
      2315723.23      7134657.47      2315632.35      7134601.94
      2315626.52      7134515.64      2315565.38      7134396.78
      2315232.54      7134058.54      2315228.48      7133825.22
      2315181.25      7133754.06      2315179.05      7133630.04
      2315274.01      7133357.45      2315082.23      7133252.01
      2315075.44      7133111.48      2314984.54      7133012.42
      2314975.17      7132911.59      2314845.80      7132726.42
      2314676.32      7132704.60      2314614.29      7132610.90
      2314326.30      7132604.64      2314259.27      7132489.57
      2314181.85      7132451.88      2314179.00      7132360.00

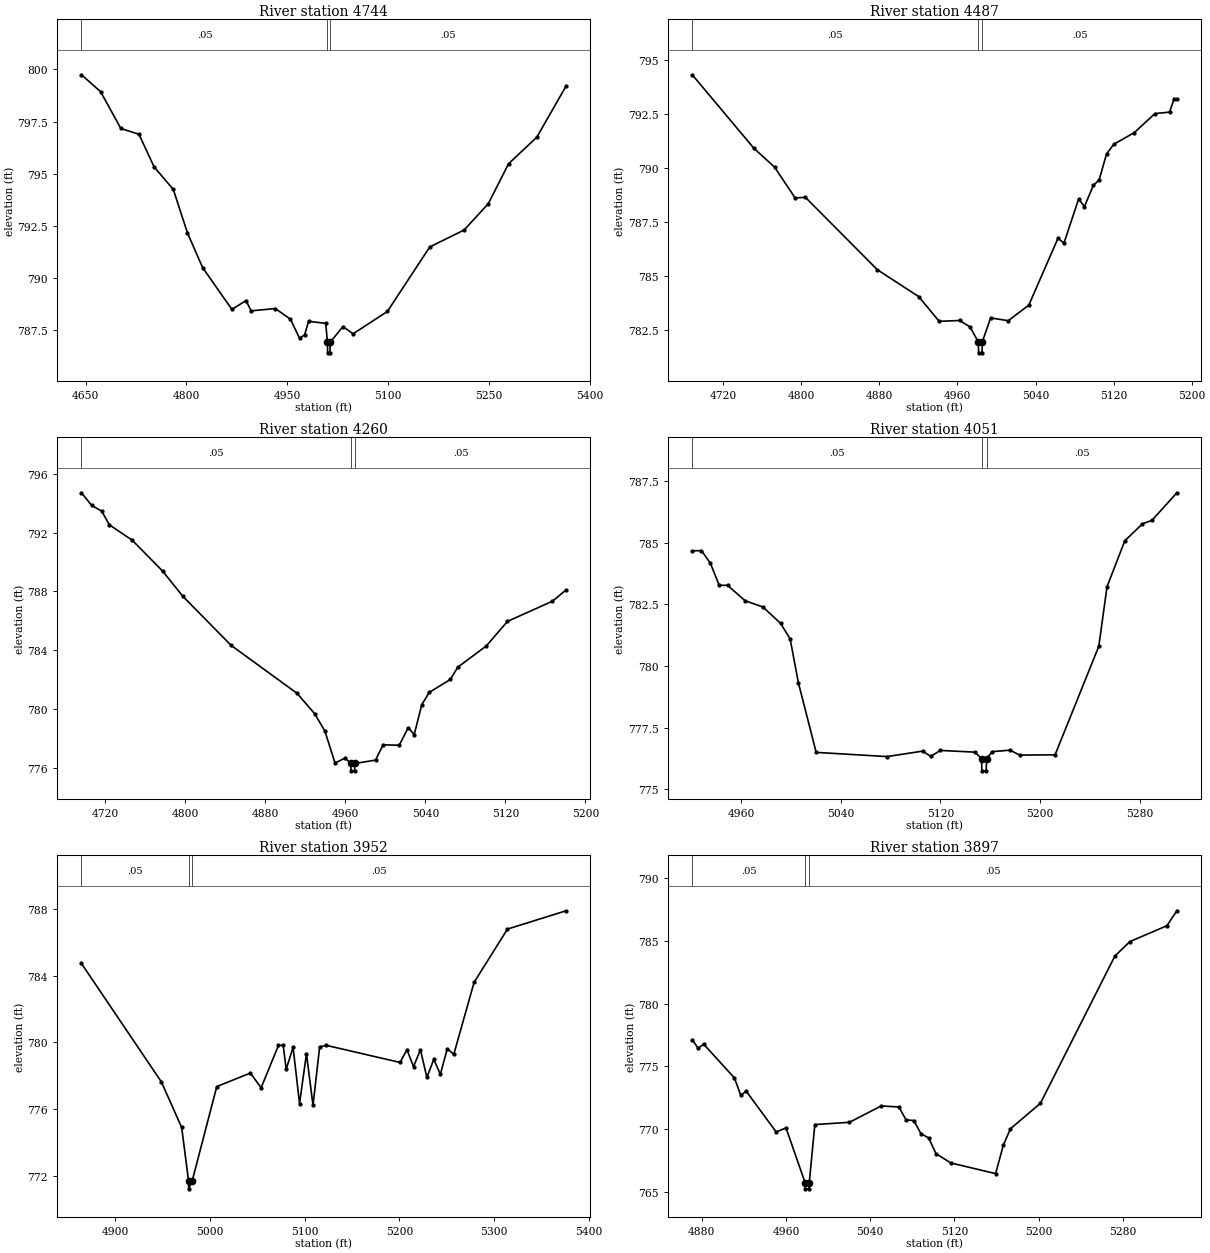
Type RM Length L Ch R = 1,4744,257,257,257
BEGIN DESCRIPTION:
Denton Creek Tributary 38 18.0
END DESCRIPTION:
XS GIS Cut Line= 3
      2316478.99      7135610.01      2316179.00      7135810.00
      2315878.99      7136010.00
#Sta/Elev= 30
  4643.9  799.74  4672.4  798.93  4702.5  797.17  4729.5  796.89  4752.0  795.33
  4780.6  794.25  4801.6  792.17  4824.2  790.51  4867.7  788.51  4888.8  788.93
  4896.3  788.44  4932.3  788.55  4954.9  788.04  4968.4  787.13  4975.9  787.29
  4981.9  787.94  5007.4  787.84  5009.9  786.93  5010.2  786.43  5013.7  786.43
  5013.9  786.93  5033.0  787.69  5048.0  787.34  5099.1  788.41  5162.2  791.50
  5213.3  792.31  5249.3  793.57  5279.4  795.48  5321.4  796.75  5365.0  799.20
#Mann=3,-1,0
  4643.9    0.05       0  5009.9   0.033       0  5013.9    0.05       0
Bank Sta=5009.9,5013.9
Exp/Cntr=0.3,0.1

Type RM Length L Ch R = 1,4487,227,227,227
BEGIN DESCRIPTION:
Denton Creek Tributary 38 17.0
END DESCRIPTION:
XS GIS Cut Line= 3
      2316328.98      7135510.01      2316029.00      7135610.00
      2315878.99      7135710.01
#Sta/Elev= 30
  4688.3  794.32  4751.5  790.91  4772.6  790.04  4793.7  788.61  4804.2  788.64
  4878.0  785.28  4920.2  784.04  4941.3  782.89  4962.3  782.93  4972.9  782.63
  4981.4  781.93  4981.7  781.43  4985.2  781.43  4985.4  781.93  4994.0  783.05
  5012.0  782.92  5033.1  783.64  5063.1  786.75  5069.1  786.51  5084.1  788.56
  5090.1  788.21  5099.2  789.19  5105.2  789.45  5112.7  790.65  5120.2  791.10
  5141.2  791.64  5162.3  792.52  5177.3  792.59  5181.8  793.18  5184.8  793.18
#Mann=3,-1,0
  4688.3    0.05       0  4981.4   0.033       0  4985.4    0.05       0
Bank Sta=4981.4,4985.4
Exp/Cntr=0.3,0.1

Type RM Length L Ch R = 1,4260,209,209,209
BEGIN DESCRIPTION:
Denton Creek Tributary 38 16.0
END DESCRIPTION:
XS GIS Cut Line= 3
      2316329.04      7135460.01      2316029.00      7135410.00
      2315878.97      7135510.02
#Sta/Elev= 30
  4696.2  794.71  4706.4  793.85  4716.5  793.46  4724.1  792.53  4746.9  791.49
  4777.3  789.39  4797.6  787.67  4845.8  784.34  4911.7  781.08  4929.4  779.69
  4939.6  778.51  4949.7  776.34  4959.8  776.68  4965.4  776.31  4965.7  775.81
  4969.2  775.81  4969.4  776.31  4990.2  776.54  4997.8  777.58  5013.9  777.55
  5022.9  778.74  5028.9  778.28  5036.4  780.30  5043.9  781.14  5065.0  782.02
  5072.5  782.86  5101.0  784.30  5122.1  785.97  5167.1  787.34  5180.7  788.11
#Mann=3,-1,0
  4696.2    0.05       0  4965.4   0.033       0  4969.4    0.05       0
Bank Sta=4965.4,4969.4
Exp/Cntr=0.3,0.1

Type RM Length L Ch R = 1,4051,99,99,99
BEGIN DESCRIPTION:
Mapping XS bc094d25
END DESCRIPTION:
XS GIS Cut Line= 2
      2316080.03      7135150.56      2315786.56      7135406.05
#Sta/Elev= 30
  4920.8  784.68  4928.2  784.69  4935.4  784.17  4942.4  783.28  4949.1  783.28
  4963.3  782.65  4977.5  782.40  4991.8  781.73  4999.4  781.10  5006.0  779.32
  5020.3  776.49  5077.2  776.32  5105.7  776.54  5112.4  776.33  5120.0  776.57
  5147.6  776.50  5153.1  776.24  5153.3  775.74  5156.8  775.74  5157.1  776.24
  5161.7  776.52  5176.0  776.58  5183.6  776.38  5212.1  776.39  5247.2  780.80
  5253.8  783.22  5268.1  785.09  5282.3  785.78  5289.9  785.92  5309.9  787.04
#Mann=3,-1,0
  4920.8    0.05       0  5153.1   0.033       0  5157.1    0.05       0
Bank Sta=5153.1,5157.1
Exp/Cntr=0.3,0.1

Type RM Length L Ch R = 1,3952,55,55,55
BEGIN DESCRIPTION:
Mapping XS c6543a76
END DESCRIPTION:
XS GIS Cut Line= 4
      2316067.79      7135062.81      2315943.40      7135136.57
      2315926.93      7135200.55      2315720.70      7135419.00
#Sta/Elev= 30
  4864.6  784.75  4948.9  777.63  4970.3  774.89  4977.5  771.70  4977.7  771.20
  4981.5  771.70  5007.3  777.35  5042.7  778.16  5054.1  777.28  5072.4  779.83
  5077.4  779.83  5080.5  778.39  5087.8  779.71  5094.6  776.33  5101.9  779.32
  5108.8  776.22  5115.8  779.73  5122.7  779.83  5200.6  778.80  5207.9  779.57
  5214.8  778.55  5222.1  779.56  5228.9  777.90  5236.2  778.99  5243.1  778.08
  5250.4  779.62  5257.3  779.29  5278.7  783.62  5313.9  786.82  5375.7  787.92
#Mann=3,-1,0
  4864.6    0.05       0  4977.5   0.033       0  4981.5    0.05       0
Bank Sta=4977.5,4981.5
Exp/Cntr=0.3,0.1

Type RM Length L Ch R = 1,3897,131,131,131
BEGIN DESCRIPTION:
Mapping XS 7701eb25
END DESCRIPTION:
XS GIS Cut Line= 4
      2315987.82      7135043.15      2315907.36      7135064.20
      2315896.97      7135173.63      2315714.67      7135368.86
#Sta/Elev= 30
  4871.0  777.13  4876.6  776.44  4881.8  776.78  4911.1  774.08  4917.1  772.70
  4922.2  773.04  4950.7  769.79  4960.0  770.12  4978.1  765.77  4978.3  765.27
  4981.8  765.27  4982.1  765.77  4987.4  770.38  5020.3  770.56  5050.4  771.86
  5067.2  771.78  5074.0  770.76  5081.4  770.70  5088.2  769.65  5095.5  769.32
  5102.4  768.07  5116.5  767.33  5159.1  766.48  5166.4  768.75  5173.2  770.05
  5201.6  772.07  5272.4  783.79  5286.6  784.93  5321.7  786.19  5331.2  787.38
#Mann=3,-1,0
  4871.0    0.05       0  4978.1   0.033       0  4982.1    0.05       0
Bank Sta=4978.1,4982.1
Exp/Cntr=0.3,0.1

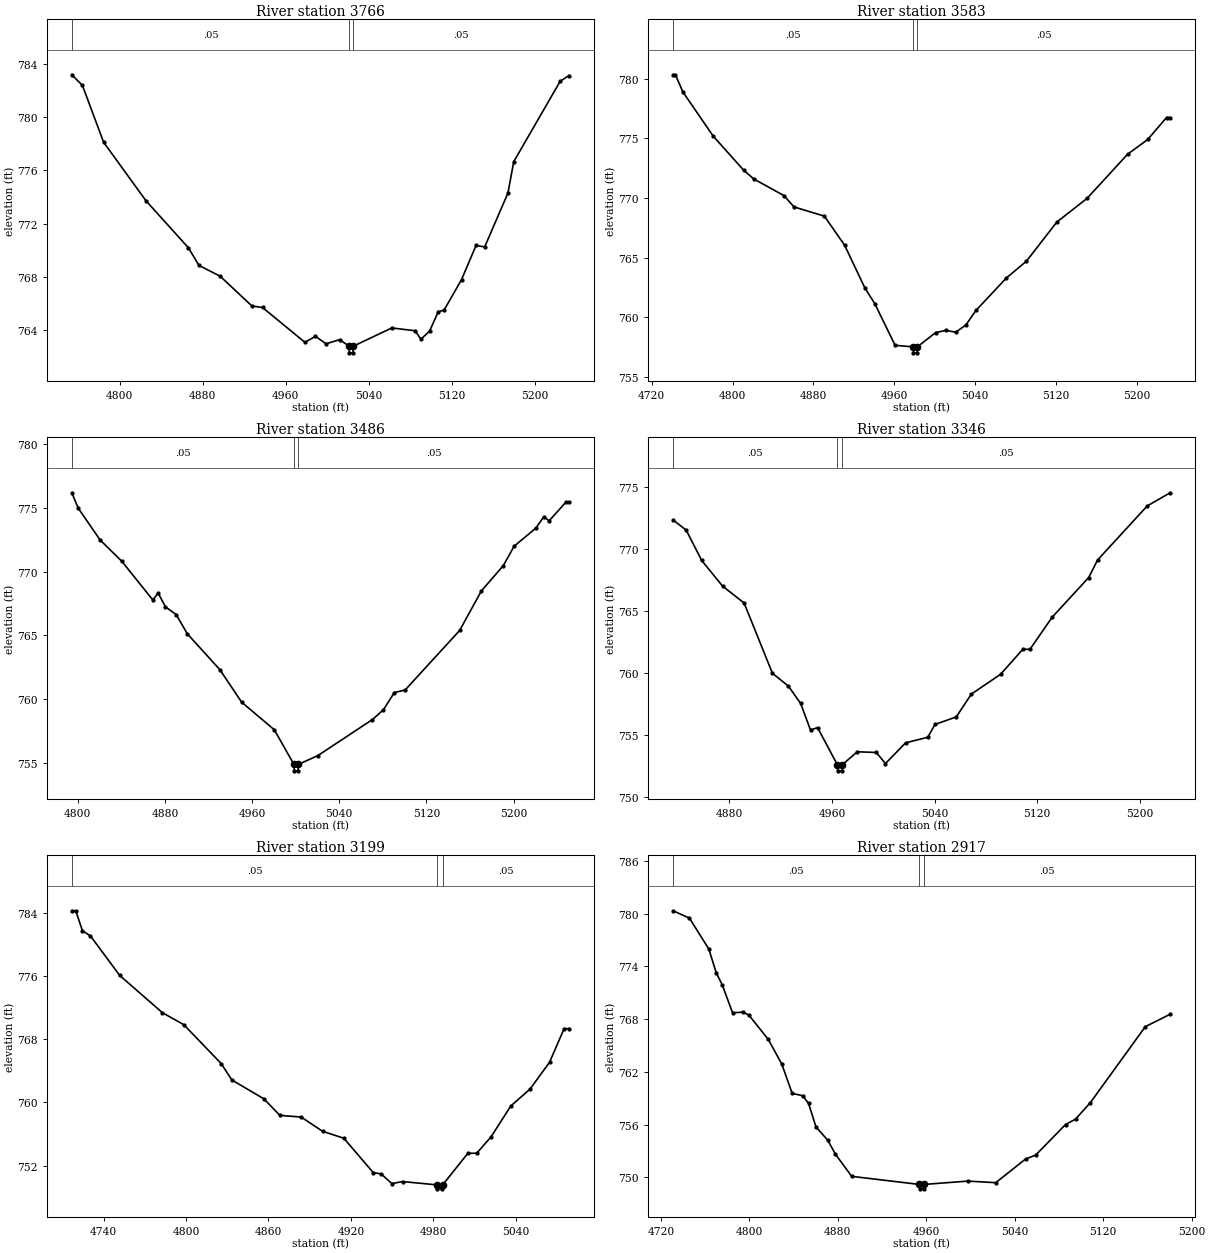
Type RM Length L Ch R = 1,3766,183,183,183
BEGIN DESCRIPTION:
Denton Creek Tributary 38 14.0
END DESCRIPTION:
XS GIS Cut Line= 3
      2316029.04      7135009.99      2315779.00      7135060.00
      2315679.00      7135260.00
#Sta/Elev= 30
  4754.0  783.18  4764.2  782.38  4784.6  778.11  4825.4  773.71  4866.2  770.18
  4876.4  768.85  4896.8  768.04  4927.4  765.80  4937.6  765.69  4978.4  763.07
  4988.6  763.52  4998.8  762.96  5011.8  763.27  5021.0  762.78  5021.2  762.28
  5024.7  762.28  5025.0  762.78  5062.1  764.15  5084.5  763.94  5090.1  763.31
  5098.4  763.90  5106.8  765.37  5112.4  765.49  5129.2  767.78  5143.2  770.35
  5151.5  770.24  5173.9  774.29  5179.5  776.65  5224.2  782.69  5232.6  783.12
#Mann=3,-1,0
  4754.0    0.05       0  5021.0   0.033       0  5025.0    0.05       0
Bank Sta=5021,5025
Exp/Cntr=0.3,0.1

Type RM Length L Ch R = 1,3583,97,97,97
BEGIN DESCRIPTION:
Mapping XS 8ba09ee2
END DESCRIPTION:
XS GIS Cut Line= 2
      2316028.66      7134916.84      2315536.76      7134917.78
#Sta/Elev= 30
  4741.2  780.32  4743.5  780.32  4750.9  778.88  4780.9  775.18  4810.9  772.34
  4820.9  771.60  4850.9  770.20  4860.9  769.25  4890.9  768.48  4910.9  766.05
  4930.9  762.48  4940.9  761.13  4960.9  757.66  4978.9  757.53  4979.1  757.03
  4982.6  757.03  4982.9  757.53  5000.9  758.72  5010.9  758.91  5020.9  758.76
  5030.9  759.36  5040.9  760.58  5070.9  763.29  5090.9  764.71  5120.9  767.98
  5150.9  769.97  5190.9  773.66  5210.9  774.90  5229.5  776.74  5233.1  776.74
#Mann=3,-1,0
  4741.2    0.05       0  4978.9   0.033       0  4982.9    0.05       0
Bank Sta=4978.9,4982.9
Exp/Cntr=0.3,0.1

Type RM Length L Ch R = 1,3486,140,140,140
BEGIN DESCRIPTION:
Mapping XS ce1626a4
END DESCRIPTION:
XS GIS Cut Line= 2
      2315984.86      7134827.17      2315528.74      7134814.42
#Sta/Elev= 30
  4794.5  776.20  4800.4  774.99  4820.4  772.50  4840.4  770.82  4868.8  767.79
  4873.8  768.32  4880.4  767.25  4890.4  766.63  4900.4  765.14  4930.4  762.31
  4950.4  759.76  4980.4  757.59  4998.4  754.87  4998.7  754.37  5002.2  754.37
  5002.4  754.87  5020.4  755.57  5070.5  758.40  5080.5  759.16  5090.5  760.51
  5100.5  760.72  5150.5  765.39  5170.5  768.50  5190.5  770.47  5200.5  772.00
  5220.5  773.43  5227.7  774.31  5232.7  774.00  5248.2  775.48  5250.8  775.48
#Mann=3,-1,0
  4794.5    0.05       0  4998.4   0.033       0  5002.4    0.05       0
Bank Sta=4998.4,5002.4
Exp/Cntr=0.3,0.1

Type RM Length L Ch R = 1,3346,147,147,147
BEGIN DESCRIPTION:
Mapping XS 2ea1b6c9
END DESCRIPTION:
XS GIS Cut Line= 2
      2315879.24      7134628.83      2315527.66      7134792.48
#Sta/Elev= 30
  4836.0  772.31  4846.2  771.50  4858.3  769.05  4874.6  766.98  4891.4  765.62
  4913.5  759.95  4925.9  758.92  4935.5  757.52  4943.2  755.37  4948.7  755.57
  4964.1  752.58  4964.4  752.08  4967.9  752.08  4968.1  752.58  4979.7  753.62
  4994.5  753.56  5001.7  752.67  5017.4  754.34  5034.7  754.79  5040.3  755.82
  5056.9  756.43  5068.7  758.27  5091.5  759.87  5108.9  761.89  5114.4  761.88
  5131.8  764.48  5160.2  767.67  5167.2  769.09  5205.9  773.45  5223.8  774.51
#Mann=3,-1,0
  4836.0    0.05       0  4964.1   0.033       0  4968.1    0.05       0
Bank Sta=4964.1,4968.1
Exp/Cntr=0.3,0.1

Type RM Length L Ch R = 1,3199,282,282,282
BEGIN DESCRIPTION:
Denton Creek Tributary 38 12.0
END DESCRIPTION:
XS GIS Cut Line= 3
      2315878.96      7134460.02      2315629.00      7134610.00
      2315579.01      7134659.99
#Sta/Elev= 30
  4716.7  784.24  4719.6  784.24  4724.4  781.72  4730.3  781.05  4751.6  776.06
  4782.7  771.35  4798.3  769.83  4825.5  764.92  4833.3  762.84  4856.6  760.46
  4868.3  758.36  4883.8  758.15  4899.4  756.35  4914.9  755.47  4936.3  751.13
  4942.1  750.96  4949.9  749.73  4957.7  749.99  4982.9  749.57  4983.1  749.07
  4986.6  749.07  4986.9  749.57  5005.3  753.57  5011.7  753.57  5022.3  755.67
  5036.5  759.54  5050.6  761.69  5064.8  765.08  5075.4  769.33  5078.9  769.33
#Mann=3,-1,0
  4716.7    0.05       0  4982.9   0.033       0  4986.9    0.05       0
Bank Sta=4982.9,4986.9
Exp/Cntr=0.3,0.1

Type RM Length L Ch R = 1,2917,266,266,266
BEGIN DESCRIPTION:
Denton Creek Tributary 38 11.0
END DESCRIPTION:
XS GIS Cut Line= 3
      2315778.98      7134260.01      2315529.00      7134360.00
      2315379.01      7134459.99
#Sta/Elev= 30
  4731.0  780.32  4745.8  779.48  4763.3  775.97  4770.0  773.27  4775.4  771.90
  4784.8  768.71  4794.3  768.79  4799.6  768.44  4817.1  765.68  4829.3  762.87
  4838.7  759.54  4848.1  759.28  4853.5  758.40  4860.2  755.73  4871.0  754.19
  4877.7  752.64  4892.5  750.10  4953.8  749.18  4954.1  748.68  4957.6  748.68
  4957.8  749.18  4997.5  749.56  5022.8  749.38  5049.8  752.08  5058.8  752.51
  5085.9  756.00  5094.9  756.61  5108.4  758.50  5158.0  767.13  5180.5  768.55
#Mann=3,-1,0
  4731.0    0.05       0  4953.8   0.033       0  4957.8    0.05       0
Bank Sta=4953.8,4957.8
Exp/Cntr=0.3,0.1

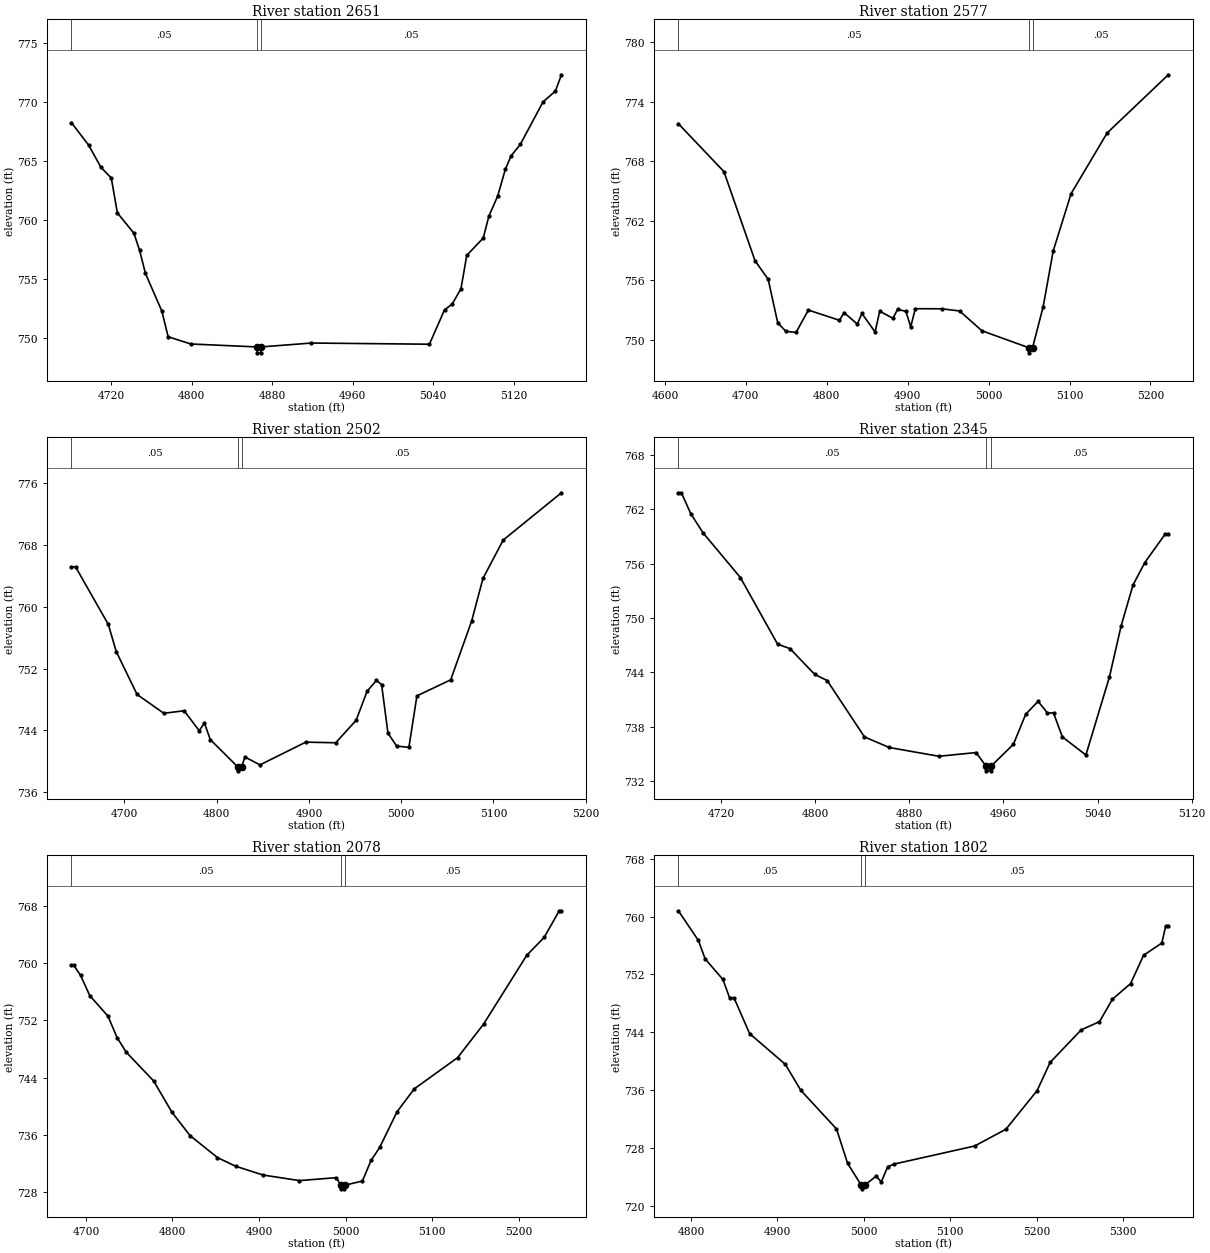
Type RM Length L Ch R = 1,2651,74,74,74
BEGIN DESCRIPTION:
Mapping XS aede0d05
END DESCRIPTION:
XS GIS Cut Line= 2
      2315624.06      7134023.60      2315192.82      7134249.88
#Sta/Elev= 30
  4680.4  768.22  4697.4  766.33  4709.6  764.46  4720.0  763.53  4726.0  760.59
  4742.5  758.86  4748.1  757.42  4753.9  755.47  4770.2  752.28  4776.5  750.10
  4799.0  749.49  4864.8  749.24  4865.0  748.74  4868.5  748.74  4868.8  749.24
  4918.9  749.57  5036.2  749.47  5051.2  752.38  5058.8  752.86  5067.6  754.18
  5073.3  756.99  5089.7  758.46  5095.3  760.31  5104.0  762.00  5111.7  764.29
  5117.4  765.42  5126.5  766.38  5149.1  769.98  5161.5  770.91  5167.4  772.28
#Mann=3,-1,0
  4680.4    0.05       0  4864.8   0.033       0  4868.8    0.05       0
Bank Sta=4864.8,4868.8
Exp/Cntr=0.3,0.1

Type RM Length L Ch R = 1,2577,75,75,75
BEGIN DESCRIPTION:
Mapping XS 40f73259
END DESCRIPTION:
XS GIS Cut Line= 2
      2315627.57      7133940.70      2315092.29      7134223.50
#Sta/Elev= 30
  4616.6  771.77  4672.9  766.94  4711.3  757.96  4727.6  756.08  4739.4  751.69
  4749.6  750.83  4762.0  750.73  4777.3  752.98  4815.7  751.95  4821.3  752.73
  4837.7  751.57  4843.4  752.64  4859.7  750.77  4865.4  752.87  4881.7  752.15
  4887.4  753.04  4897.7  752.86  4903.7  751.29  4909.4  753.12  4942.1  753.11
  4964.1  752.89  4991.8  750.89  5050.2  749.17  5050.4  748.67  5054.2  749.17
  5067.4  753.33  5079.8  758.95  5101.9  764.72  5146.5  770.84  5222.0  776.70
#Mann=3,-1,0
  4616.6    0.05       0  5050.2   0.033       0  5054.2    0.05       0
Bank Sta=5050.2,5054.2
Exp/Cntr=0.3,0.1

Type RM Length L Ch R = 1,2502,157,157,157
BEGIN DESCRIPTION:
Mapping XS 7da1da03
END DESCRIPTION:
XS GIS Cut Line= 2
      2315551.78      7133897.62      2315083.08      7134147.17
#Sta/Elev= 30
  4642.7  765.19  4647.1  765.19  4682.6  757.73  4691.2  754.21  4713.8  748.64
  4742.8  746.20  4764.8  746.53  4781.1  743.94  4786.8  744.94  4793.1  742.80
  4823.0  739.24  4823.3  738.74  4827.0  739.24  4830.7  740.53  4847.0  739.51
  4896.6  742.46  4929.1  742.38  4951.2  745.29  4963.1  749.06  4973.2  750.46
  4978.8  749.93  4985.7  743.63  4995.1  741.95  5008.4  741.79  5017.1  748.46
  5053.7  750.54  5076.4  758.16  5088.7  763.69  5110.6  768.66  5173.7  774.79
#Mann=3,-1,0
  4642.7    0.05       0  4823.0   0.033       0  4827.0    0.05       0
Bank Sta=4823,4827
Exp/Cntr=0.3,0.1

Type RM Length L Ch R = 1,2345,267,267,267
BEGIN DESCRIPTION:
Denton Creek Tributary 38 9.0
END DESCRIPTION:
XS GIS Cut Line= 3
      2315528.95      7133810.02      2315229.00      7133910.00
      2315128.98      7133910.00
#Sta/Elev= 30
  4683.9  763.84  4686.5  763.84  4694.4  761.54  4704.9  759.41  4736.6  754.47
  4768.2  747.11  4778.7  746.62  4799.8  743.76  4810.3  743.09  4842.0  736.86
  4863.0  735.69  4905.2  734.72  4936.8  735.13  4945.4  733.61  4945.6  733.11
  4949.1  733.11  4949.4  733.61  4968.5  736.04  4979.0  739.37  4989.5  740.79
  4997.4  739.51  5002.6  739.51  5010.1  736.86  5030.1  734.86  5050.1  743.49
  5060.1  749.17  5070.1  753.64  5080.1  756.12  5097.6  759.30  5100.1  759.30
#Mann=3,-1,0
  4683.9    0.05       0  4945.4   0.033       0  4949.4    0.05       0
Bank Sta=4945.4,4949.4
Exp/Cntr=0.3,0.1

Type RM Length L Ch R = 1,2078,276,276,276
BEGIN DESCRIPTION:
Denton Creek Tributary 38 8.0
END DESCRIPTION:
XS GIS Cut Line= 3
      2315479.00      7133560.00      2315179.00      7133660.00
      2314929.03      7133660.00
#Sta/Elev= 30
  4683.3  759.70  4685.9  759.70  4693.8  758.30  4704.4  755.48  4725.5  752.60
  4736.0  749.61  4746.5  747.58  4778.2  743.56  4799.3  739.20  4820.3  735.92
  4852.0  732.85  4873.0  731.64  4904.7  730.41  4946.8  729.63  4989.0  730.04
  4994.9  728.98  4995.1  728.48  4998.6  728.48  4998.9  728.98  5019.5  729.57
  5029.5  732.44  5039.5  734.27  5059.5  739.24  5079.5  742.45  5129.5  746.80
  5159.5  751.48  5209.5  761.11  5229.5  763.59  5247.0  767.32  5249.5  767.32
#Mann=3,-1,0
  4683.3    0.05       0  4994.9   0.033       0  4998.9    0.05       0
Bank Sta=4994.9,4998.9
Exp/Cntr=0.3,0.1

Type RM Length L Ch R = 1,1802,244,244,244
BEGIN DESCRIPTION:
Denton Creek Tributary 38 7.0
END DESCRIPTION:
XS GIS Cut Line= 3
      2315478.98      7133459.99      2315279.00      7133410.00
      2314978.99      7133610.01
#Sta/Elev= 30
  4785.5  760.80  4808.7  756.69  4816.4  754.16  4837.0  751.30  4844.7  748.78
  4849.9  748.75  4867.9  743.81  4909.2  739.56  4927.2  735.95  4968.4  730.62
  4981.3  725.84  4997.1  722.83  4997.4  722.33  5001.1  722.83  5014.2  724.09
  5020.2  723.29  5027.7  725.40  5035.2  725.76  5128.3  728.26  5164.4  730.58
  5200.5  735.93  5215.5  739.82  5251.5  744.33  5272.6  745.46  5287.6  748.57
  5308.6  750.73  5323.6  754.64  5344.7  756.34  5349.2  758.68  5352.2  758.68
#Mann=3,-1,0
  4785.5    0.05       0  4997.1   0.033       0  5001.1    0.05       0
Bank Sta=4997.1,5001.1
Exp/Cntr=0.3,0.1

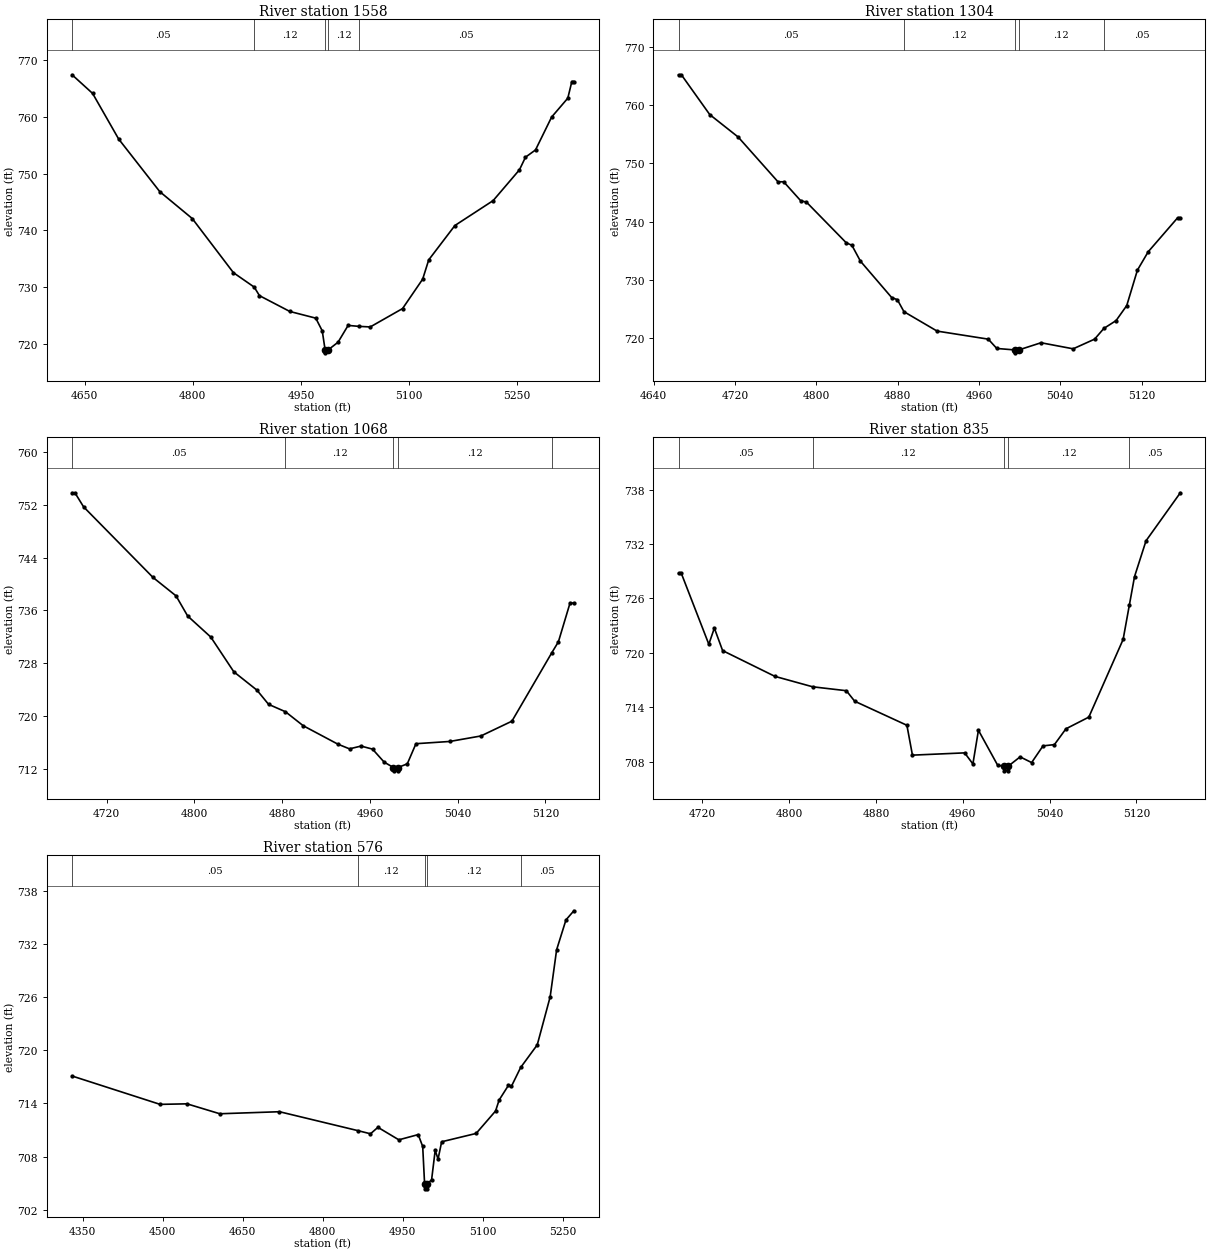
Type RM Length L Ch R = 1,1558,254,254,254
BEGIN DESCRIPTION:
Denton Creek Tributary 38 6.0
END DESCRIPTION:
XS GIS Cut Line= 3
      2315428.99      7133060.01      2315129.00      7133260.00
      2314828.96      7133410.02
#Sta/Elev= 30
  4632.6  767.43  4661.1  764.14  4697.2  756.10  4754.3  746.81  4799.3  742.07
  4856.4  732.52  4885.3  729.97  4892.5  728.47  4934.6  725.68  4970.6  724.50
  4979.6  722.26  4983.6  718.88  4983.9  718.38  4987.6  718.88  5001.5  720.25
  5015.5  723.22  5030.4  723.05  5046.2  722.95  5091.0  726.19  5118.9  731.38
  5127.3  734.78  5163.6  740.84  5216.7  745.24  5253.1  750.66  5261.5  752.89
  5275.4  754.17  5297.8  759.98  5320.2  763.30  5325.8  766.24  5328.6  766.24
#Mann=5,-1,0
  4632.6    0.05       0  4885.3    0.12       0  4983.6    0.07       0
  4987.6    0.12       0  5030.4    0.05       0
Bank Sta=4983.6,4987.6
Exp/Cntr=0.3,0.1

Type RM Length L Ch R = 1,1304,236,236,236
BEGIN DESCRIPTION:
Denton Creek Tributary 38 5.0
END DESCRIPTION:
XS GIS Cut Line= 3
      2315328.98      7132910.01      2315029.00      7133060.00
      2314879.01      7133110.00
#Sta/Elev= 30
  4664.6  765.18  4667.4  765.18  4695.3  758.35  4723.3  754.49  4762.4  746.82
  4768.0  746.82  4784.8  743.56  4790.4  743.33  4829.5  736.36  4835.1  735.92
  4843.5  733.20  4874.2  726.96  4879.8  726.59  4886.3  724.53  4918.9  721.20
  4969.2  719.82  4977.6  718.22  4995.2  717.97  4995.4  717.47  4999.2  717.97
  5021.1  719.20  5052.7  718.16  5073.8  719.82  5082.9  721.66  5094.9  723.00
  5105.4  725.58  5115.9  731.66  5126.5  734.81  5155.5  740.65  5158.1  740.65
#Mann=5,-1,0
  4664.6    0.05       0  4886.3    0.12       0  4995.2    0.07       0
  4999.2    0.12       0  5082.9    0.05       0
Bank Sta=4995.2,4999.2
Exp/Cntr=0.3,0.1

Type RM Length L Ch R = 1,1068,233,233,233
BEGIN DESCRIPTION:
Denton Creek Tributary 38 4.0
END DESCRIPTION:
XS GIS Cut Line= 3
      2315228.97      7132760.01      2314929.00      7132860.00
      2314829.01      7132959.99
#Sta/Elev= 30
  4688.4  753.81  4691.0  753.81  4698.9  751.68  4762.2  740.99  4783.2  738.20
  4793.8  735.15  4814.9  731.96  4835.9  726.70  4857.0  723.92  4867.6  721.77
  4883.0  720.65  4899.2  718.53  4930.8  715.74  4941.4  715.03  4951.9  715.45
  4962.4  714.99  4973.0  713.02  4981.5  712.20  4981.8  711.70  4985.3  711.70
  4985.5  712.20  4994.1  712.76  5002.0  715.81  5032.9  716.15  5061.2  716.98
  5089.5  719.22  5125.9  729.59  5131.9  731.24  5142.5  737.11  5146.0  737.11
#Mann=5,-1,0
  4688.4    0.05       0  4883.0    0.12       0  4981.5    0.07       0
  4985.5    0.12       0  5125.9    0.05       0
Bank Sta=4981.5,4985.5
Exp/Cntr=0.3,0.1

Type RM Length L Ch R = 1,835,259,259,259
BEGIN DESCRIPTION:
Denton Creek Tributary 38 3.0
END DESCRIPTION:
XS GIS Cut Line= 3
      2315079.04      7132659.99      2314779.00      7132710.00
      2314729.00      7132860.00
#Sta/Elev= 30
  4698.1  728.75  4700.7  728.75  4726.0  720.95  4731.1  722.73  4738.7  720.25
  4786.9  717.41  4821.7  716.26  4852.7  715.83  4860.4  714.67  4908.5  712.02
  4913.6  708.73  4961.7  708.98  4969.3  707.76  4974.4  711.47  4992.1  707.62
  4997.7  707.50  4998.0  707.00  5001.5  707.00  5001.7  707.50  5012.8  708.54
  5023.4  707.91  5033.9  709.75  5044.4  709.89  5055.0  711.63  5076.1  712.92
  5107.7  721.48  5113.4  725.24  5118.2  728.40  5128.8  732.35  5160.4  737.64
#Mann=5,-1,0
  4698.1    0.05       0  4821.7    0.12       0  4997.7    0.07       0
  5001.7    0.12       0  5113.4    0.05       0
Bank Sta=4997.7,5001.7
Exp/Cntr=0.3,0.1

Type RM Length L Ch R = 1,576,0,0,0
BEGIN DESCRIPTION:
Denton Creek Tributary 38 2.0
END DESCRIPTION:
XS GIS Cut Line= 3
      2315179.03      7132309.98      2314579.00      7132610.00
      2314678.99      7132859.98
#Sta/Elev= 30
  4330.4  717.10  4495.3  713.90  4545.7  713.96  4607.2  712.84  4719.0  713.07
  4865.6  710.94  4889.5  710.58  4903.4  711.31  4942.6  709.90  4978.9  710.49
  4987.3  709.15  4990.9  704.87  4991.1  704.37  4994.6  704.37  4994.9  704.87
  5004.0  705.40  5010.7  708.71  5016.1  707.73  5022.8  709.68  5087.4  710.62
  5123.8  713.15  5130.5  714.39  5148.0  716.05  5153.4  715.92  5170.8  718.06
  5201.9  720.61  5226.1  726.03  5238.2  731.34  5255.7  734.71  5270.5  735.74
#Mann=5,-1,0
  4330.4    0.05       0  4865.6    0.12       0  4990.9    0.07       0
  4994.9    0.12       0  5170.8    0.05       0
Bank Sta=4990.9,4994.9
Exp/Cntr=0.3,0.1

Chan Stop Cuts=-1