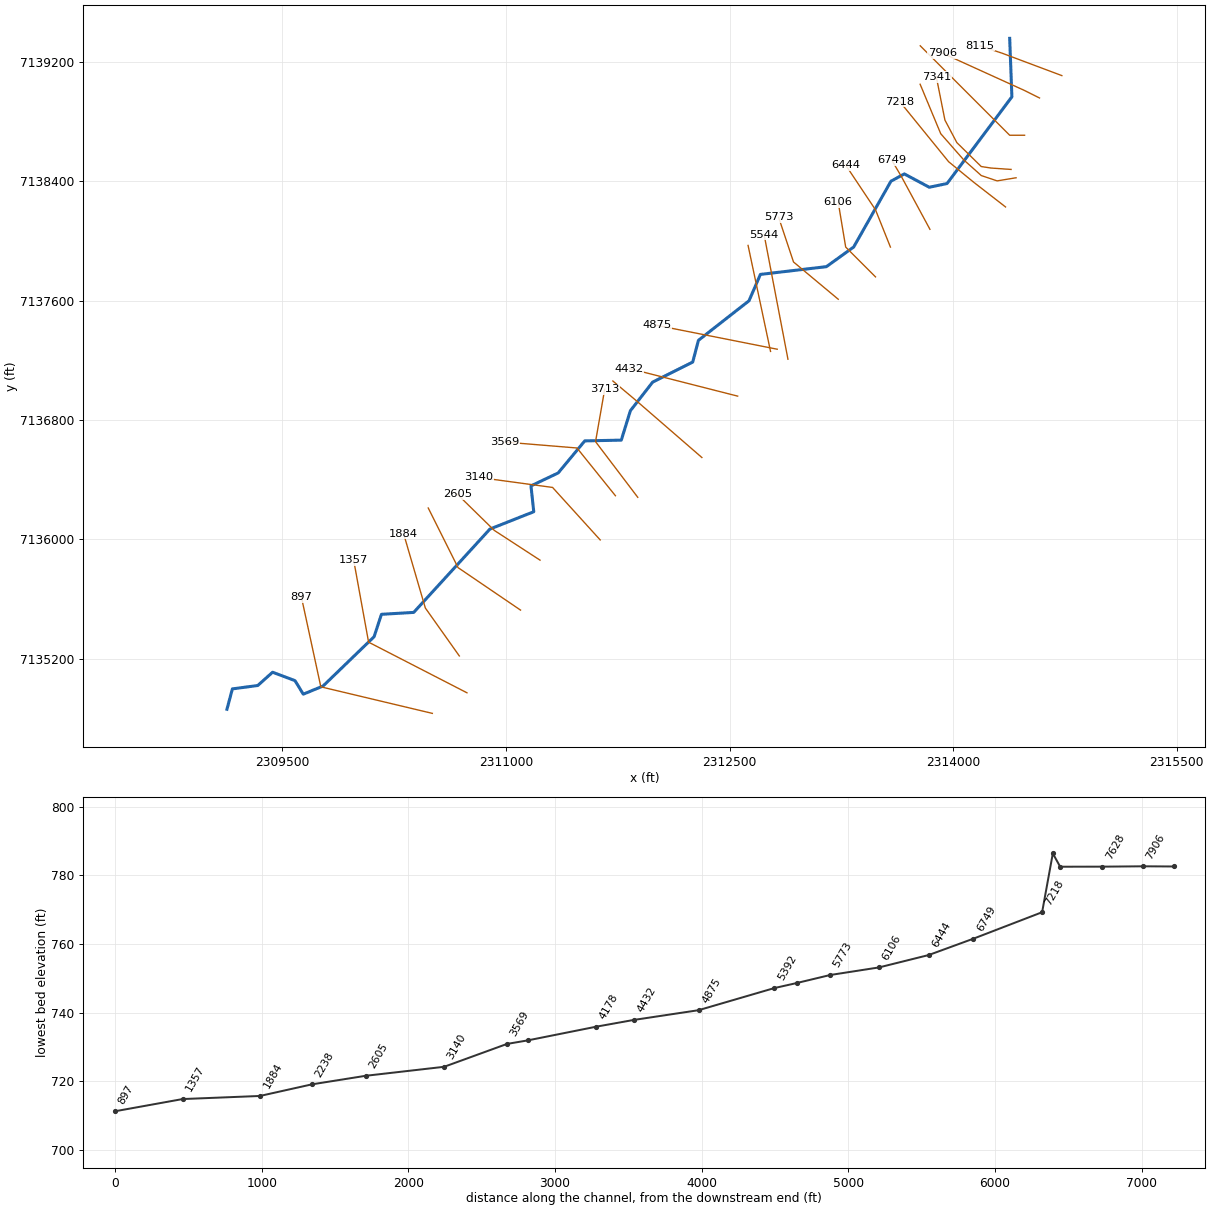
--- Denton Creek Tributary 40.prj (project) ---

Proj Title=Denton Creek Tributary 40 Base Level Engineering
Current Plan=p01
Default Exp/Contr=0.3,0.1
English Units
Geom File=g01
Flow File=f01
Plan File=p01
BEGIN DESCRIPTION:
Denton Creek Tributary 40
END DESCRIPTION:

--- Denton Creek Tributary 40.p01 (plan) ---

Plan Title=Multiple Run
Short Identifier=Multiple
Geom File=g01
Flow File=f01
Subcritical Flow
K Sum by GR= 0
Std Step Tol= 0.01
Critical Tol= 0.01
Num of Std Step Trials= 20
Max Error Tol= 0.3
Flow Tol Ratio= 0.001
Split Flow NTrial= 30
Split Flow Tol= 0.02
Split Flow Ratio= 0.02
Log Output Level= 0
Friction Slope Method= 1
Unsteady Friction Slope Method= 2
Unsteady Bridges Friction Slope Method= 1
Parabolic Critical Depth
Global Vel Dist=  1 , 1 , 1
Global Log Level= 0
CheckData=True
Encroach Param= -1, 0, 0, 0
BEGIN DESCRIPTION:
Multiple Run
END DESCRIPTION:

--- Denton Creek Tributary 40.f01 (steady flow) ---

Flow Title=Multiple
Number of Profiles=7
Profile Names=10-year,25-year,50-year,1pct_min,100-year,1pct_plu,500-year
River Rch & RM= Denton Creek Tri,Reach-1,8115
     655     904    1111     679    1354    2702    2014
River Rch & RM= Denton Creek Tri,Reach-1,4875
     792    1105    1369     842    1679    3350    2532
River Rch & RM= Denton Creek Tri,Reach-1,3569
     907    1274    1585     978    1952    3894    2967
River Rch & RM= Denton Creek Tri,Reach-1,897
     987    1393    1738    1076    2147    4284    3283
Boundary for River Rch & Prof#=Denton Creek Tri,Reach-1,1
Up Type=0
Dn Type=3
Dn Slope=0.005
Boundary for River Rch & Prof#=Denton Creek Tri,Reach-1,2
Up Type=0
Dn Type=3
Dn Slope=0.005
Boundary for River Rch & Prof#=Denton Creek Tri,Reach-1,3
Up Type=0
Dn Type=3
Dn Slope=0.005
Boundary for River Rch & Prof#=Denton Creek Tri,Reach-1,4
Up Type=0
Dn Type=3
Dn Slope=0.005
Boundary for River Rch & Prof#=Denton Creek Tri,Reach-1,5
Up Type=0
Dn Type=3
Dn Slope=0.005
Boundary for River Rch & Prof#=Denton Creek Tri,Reach-1,6
Up Type=0
Dn Type=3
Dn Slope=0.005
Boundary for River Rch & Prof#=Denton Creek Tri,Reach-1,7
Up Type=0
Dn Type=3
Dn Slope=0.005

--- Denton Creek Tributary 40.g01 (geometry) ---

Geom Title=Existing Conditions

River Reach=Denton Creek Tri,Reach-1
Reach XY= 30
      2314379.00      7139360.00      2314393.71      7138967.76
      2313958.71      7138386.00      2313839.50      7138361.21
      2313672.34      7138450.63      2313582.51      7138401.57
      2313332.61      7137960.33      2313149.58      7137828.55
      2312706.88      7137776.60      2312630.42      7137599.63
      2312291.17      7137334.32      2312253.06      7137188.76
      2311984.61      7137054.41      2311834.83      7136862.30
      2311773.92      7136665.03      2311529.00      7136660.00
      2311350.67      7136445.07      2311168.14      7136358.16
      2311186.85      7136184.88      2310892.57      7136068.45
      2310381.54      7135509.54      2310165.27      7135496.80
      2310115.76      7135346.34      2309773.39      7135015.59
      2309641.03      7134961.19      2309585.32      7135051.93
      2309435.04      7135108.37      2309335.66      7135019.32
      2309165.38      7134996.59      2309129.00      7134860.00

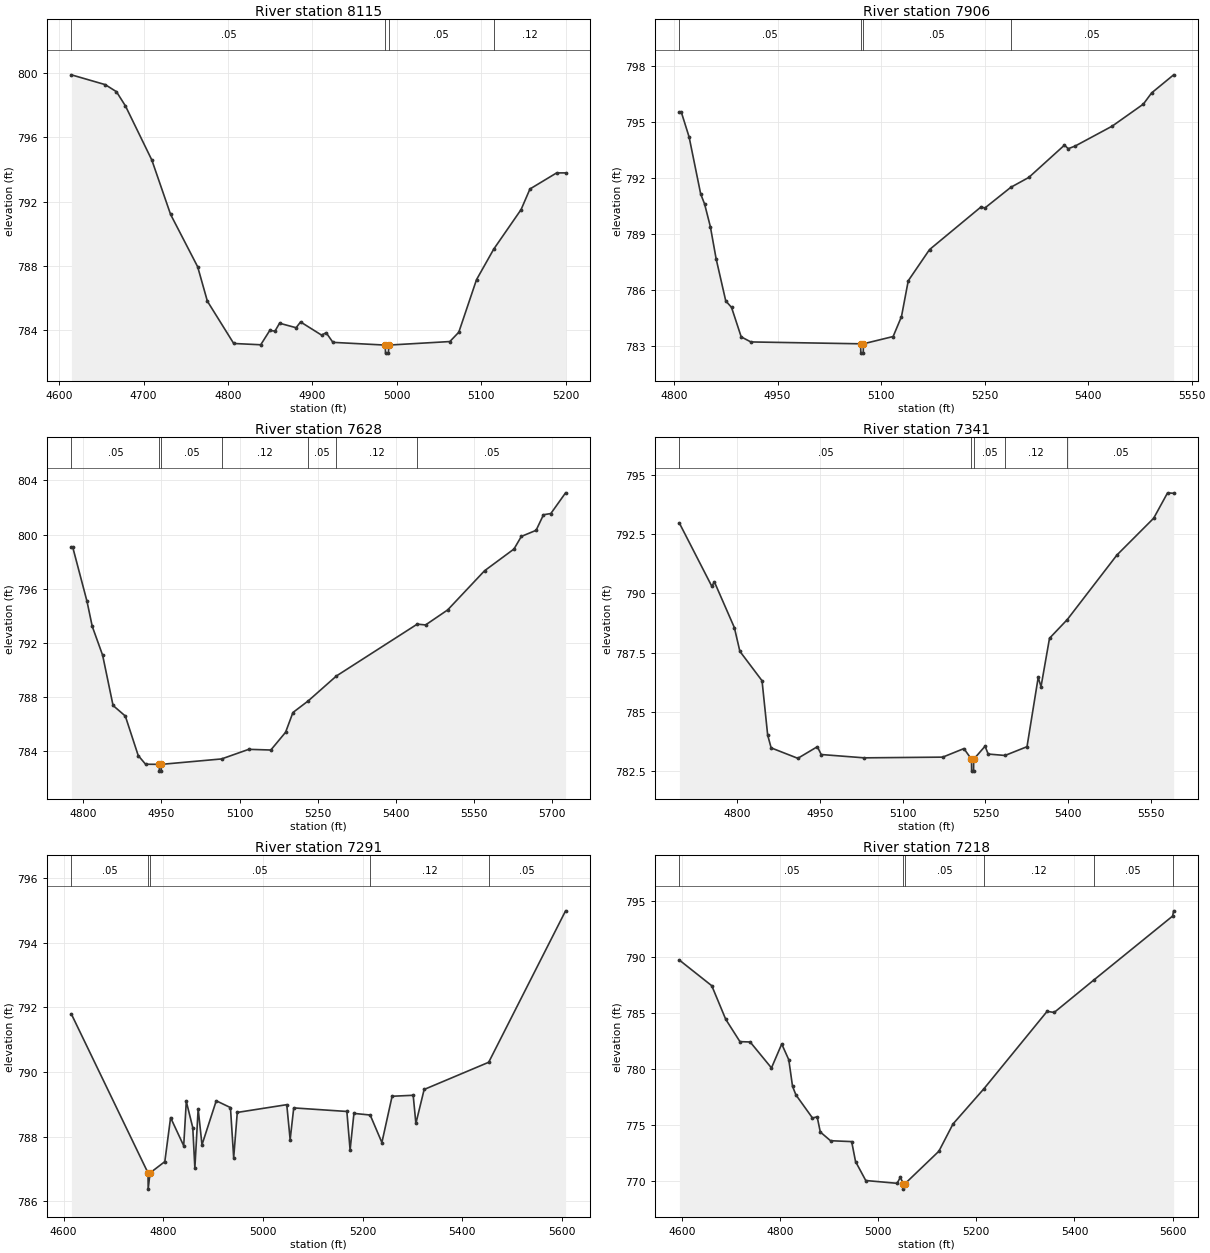
Type RM Length L Ch R = 1,8115,209,209,209
BEGIN DESCRIPTION:
Denton Creek Tributary 40 21.0
END DESCRIPTION:
XS GIS Cut Line= 3
      2314729.04      7139109.98      2314329.00      7139260.00
      2314178.96      7139310.01
#Sta/Elev= 30
  4614.5  799.88  4654.6  799.27  4667.9  798.83  4678.6  797.94  4709.8  794.58
  4732.0  791.20  4764.1  787.94  4775.6  785.80  4806.8  783.17  4838.8  783.09
  4849.5  783.98  4855.7  783.94  4861.1  784.43  4880.7  784.15  4886.0  784.51
  4910.9  783.69  4916.3  783.84  4924.3  783.24  4986.3  783.07  4986.6  782.57
  4990.1  782.57  4990.3  783.07  5062.8  783.29  5073.4  783.87  5094.4  787.14
  5114.8  789.04  5147.2  791.50  5157.7  792.78  5189.3  793.78  5199.9  793.78
#Mann=4,-1,0
  4614.5    0.05       0  4986.3   0.033       0  4990.3    0.05       0
  5114.8    0.12       0
Bank Sta=4986.3,4990.3
Exp/Cntr=0.3,0.1

Type RM Length L Ch R = 1,7906,278,278,278
BEGIN DESCRIPTION:
Denton Creek Tributary 40 20.0
END DESCRIPTION:
XS GIS Cut Line= 3
      2314579.04      7138959.98      2314479.00      7139010.00
      2313929.00      7139260.00
#Sta/Elev= 30
  4807.9  795.53  4810.7  795.53  4821.9  794.21  4838.7  791.15  4844.3  790.62
  4852.7  789.40  4861.1  787.67  4875.0  785.42  4883.4  785.07  4897.4  783.49
  4911.4  783.22  5070.4  783.12  5070.7  782.62  5074.2  782.62  5074.4  783.12
  5117.5  783.51  5129.6  784.58  5139.4  786.50  5170.2  788.17  5244.9  790.46
  5250.4  790.40  5288.0  791.51  5314.1  792.04  5365.7  793.77  5371.2  793.58
  5381.1  793.72  5434.9  794.79  5480.0  795.97  5492.0  796.57  5523.9  797.54
#Mann=4,-1,0
  4807.9    0.05       0  5070.4   0.033       0  5074.4    0.05       0
  5288.0    0.05       0
Bank Sta=5070.4,5074.4
Exp/Cntr=0.3,0.1

Type RM Length L Ch R = 1,7628,287,287,287
BEGIN DESCRIPTION:
Denton Creek Tributary 40 19.0
END DESCRIPTION:
XS GIS Cut Line= 3
      2314478.97      7138710.00      2314379.00      7138710.00
      2313779.00      7139310.00
#Sta/Elev= 30
  4777.3  799.08  4779.8  799.08  4807.3  795.06  4817.3  793.22  4837.3  791.08
  4857.3  787.37  4880.8  786.59  4905.6  783.67  4919.7  783.03  4946.0  783.02
  4946.2  782.52  4949.7  782.52  4950.0  783.02  5065.5  783.42  5117.7  784.13
  5160.1  784.08  5188.4  785.39  5202.5  786.85  5231.6  787.70  5286.0  789.55
  5441.1  793.38  5457.1  793.32  5499.5  794.43  5570.2  797.32  5626.8  798.93
  5640.9  799.86  5669.2  800.31  5683.4  801.46  5697.5  801.55  5725.8  803.08
#Mann=7,-1,0
  4777.3    0.05       0  4946.0   0.033       0  4950.0    0.05       0
  5065.5    0.12       0  5231.6    0.05       0  5286.0    0.12       0
  5441.1    0.05       0
Bank Sta=4946,4950
Exp/Cntr=0.3,0.1

Type RM Length L Ch R = 1,7341,50,50,50
BEGIN DESCRIPTION:
Mapping XS 234beb19
END DESCRIPTION:
XS GIS Cut Line= 6
      2314388.34      7138480.66      2314253.66      7138490.03
      2314188.08      7138500.14      2314024.49      7138660.72
      2313944.66      7138811.37      2313886.99      7139100.79
#Sta/Elev= 30
  4695.0  792.95  4753.5  790.30  4758.5  790.47  4794.6  788.55  4804.6  787.55
  4844.8  786.31  4855.0  784.02  4861.3  783.48  4909.7  783.04  4945.1  783.53
  4952.1  783.20  5030.0  783.06  5172.5  783.09  5210.9  783.45  5224.6  783.00
  5224.9  782.50  5228.4  782.50  5228.6  783.00  5249.2  783.55  5254.9  783.22
  5285.4  783.16  5325.3  783.53  5345.6  786.45  5350.7  786.06  5366.1  788.10
  5398.4  788.89  5488.4  791.61  5555.0  793.16  5580.2  794.23  5591.2  794.21
#Mann=5,-1,0
  4695.0    0.05       0  5224.6   0.033       0  5228.6    0.05       0
  5285.4    0.12       0  5398.4    0.05       0
Bank Sta=5224.6,5228.6
Exp/Cntr=0.3,0.1

Type RM Length L Ch R = 1,7291,73,73,73
BEGIN DESCRIPTION:
Mapping XS b60f781f
END DESCRIPTION:
XS GIS Cut Line= 6
      2314421.72      7138424.75      2314294.59      7138403.89
      2314188.73      7138439.55      2314071.20      7138544.34
      2313916.55      7138720.16      2313778.39      7139052.01
#Sta/Elev= 30
  4615.7  791.79  4769.5  786.88  4769.8  786.38  4773.5  786.88  4803.2  787.23
  4814.8  788.59  4841.1  787.72  4846.3  789.09  4859.3  788.28  4863.5  787.03
  4870.1  788.86  4877.8  787.75  4906.4  789.11  4934.9  788.90  4941.4  787.35
  4948.6  788.75  5047.9  788.99  5054.7  787.91  5061.9  788.89  5168.5  788.78
  5175.0  787.59  5182.7  788.72  5215.3  788.67  5238.8  787.82  5259.3  789.25
  5301.6  789.28  5307.0  788.41  5323.6  789.46  5453.1  790.30  5607.4  794.98
#Mann=5,-1,0
  4615.7    0.05       0  4769.5   0.033       0  4773.5    0.05       0
  5215.3    0.12       0  5453.1    0.05       0
Bank Sta=4769.5,4773.5
Exp/Cntr=0.3,0.1

Type RM Length L Ch R = 1,7218,469,469,469
BEGIN DESCRIPTION:
Mapping XS 0f1b0505
END DESCRIPTION:
XS GIS Cut Line= 4
      2314351.06      7138229.16      2314136.46      7138395.70
      2313969.49      7138532.42      2313641.74      7138935.43
#Sta/Elev= 30
  4595.2  789.72  4661.1  787.43  4689.5  784.43  4718.5  782.43  4739.3  782.40
  4782.7  780.08  4803.6  782.22  4818.0  780.81  4825.6  778.44  4832.5  777.67
  4866.3  775.60  4875.8  775.71  4882.2  774.35  4903.0  773.57  4946.1  773.49
  4954.0  771.71  4974.8  770.01  5038.7  769.76  5045.2  770.30  5051.1  769.74
  5051.3  769.24  5055.1  769.74  5123.8  772.63  5152.6  775.07  5215.6  778.22
  5344.3  785.14  5358.7  785.04  5439.7  787.95  5600.0  793.66  5602.1  794.13
#Mann=6,-1,0
  4595.2    0.05       0  5051.1   0.033       0  5055.1    0.05       0
  5215.6    0.12       0  5439.7    0.05       0  5600.0    0.12       0
Bank Sta=5051.1,5055.1
Exp/Cntr=0.3,0.1

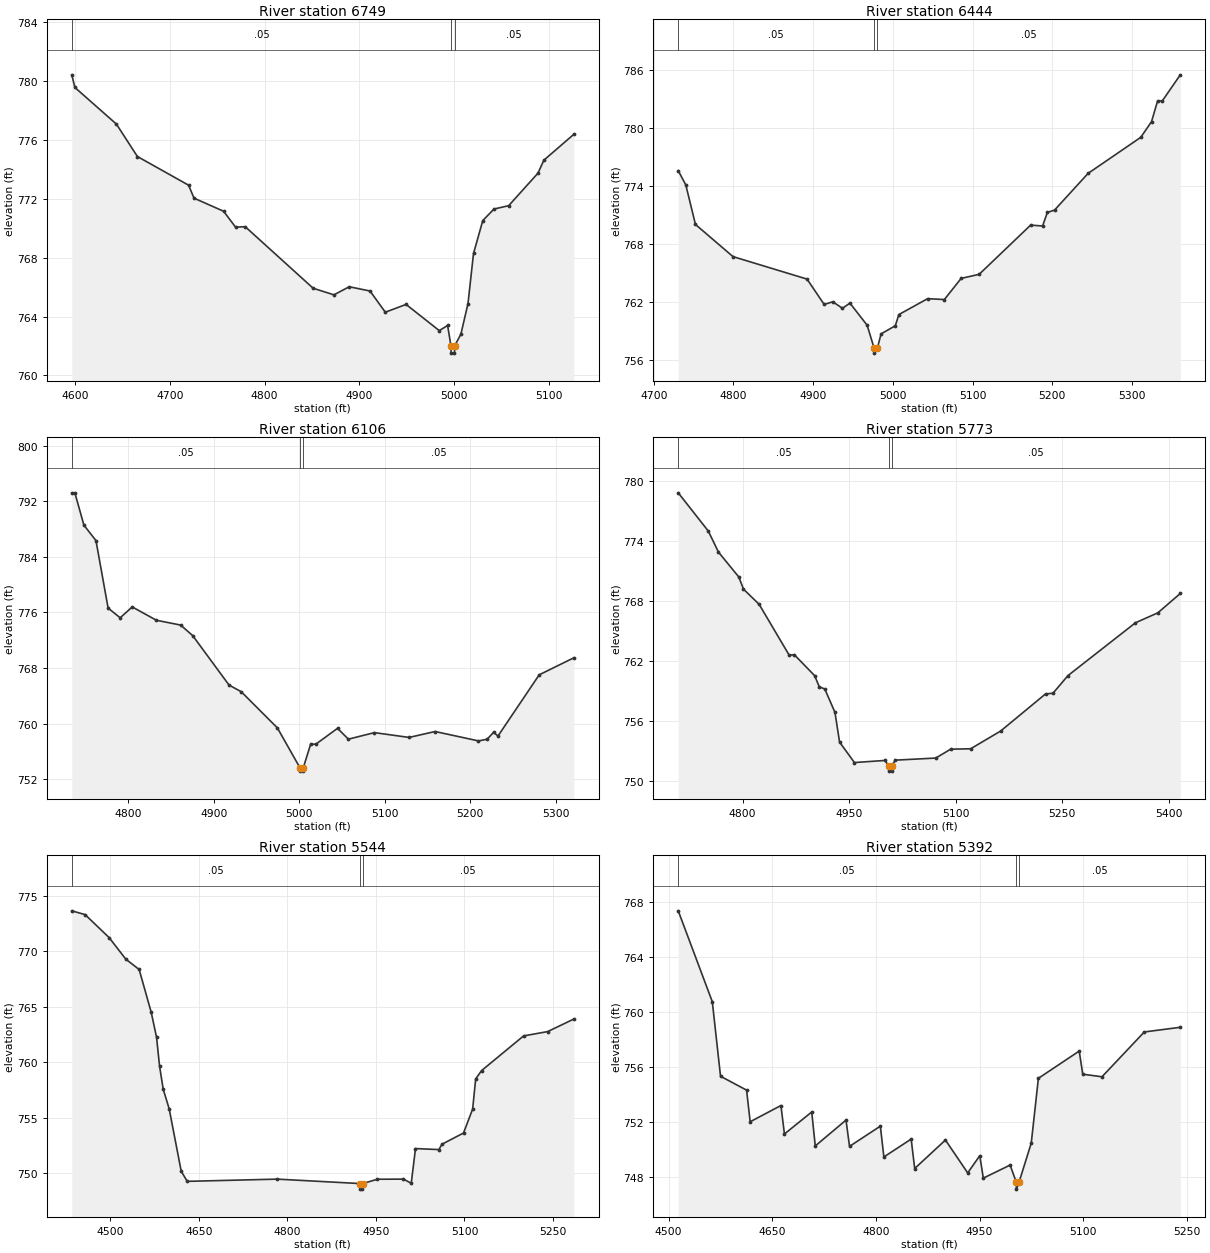
Type RM Length L Ch R = 1,6749,305,305,305
BEGIN DESCRIPTION:
Denton Creek Tributary 40 16.0
END DESCRIPTION:
XS GIS Cut Line= 3
      2313843.98      7138079.16      2313651.78      7138434.63
      2313588.12      7138542.55
#Sta/Elev= 30
  4596.7  780.43  4600.0  779.57  4643.8  777.08  4665.9  774.88  4719.9  772.93
  4725.6  772.05  4756.8  771.16  4769.4  770.08  4779.6  770.11  4851.2  765.93
  4873.1  765.48  4889.3  766.03  4911.2  765.74  4927.3  764.30  4949.2  764.83
  4984.2  763.05  4993.0  763.40  4996.5  762.02  4996.7  761.52  5000.2  761.52
  5000.5  762.02  5007.0  762.81  5014.5  764.89  5020.3  768.29  5030.1  770.53
  5041.9  771.31  5057.4  771.54  5088.3  773.75  5094.5  774.63  5126.1  776.39
#Mann=3,-1,0
  4596.7    0.05       0  4996.5   0.033       0  5000.5    0.05       0
Bank Sta=4996.5,5000.5
Exp/Cntr=0.3,0.1

Type RM Length L Ch R = 1,6444,338,338,338
BEGIN DESCRIPTION:
Denton Creek Tributary 40 15.0
END DESCRIPTION:
XS GIS Cut Line= 3
      2313579.02      7137959.96      2313479.00      7138210.00
      2313278.97      7138510.04
#Sta/Elev= 30
  4730.7  775.58  4740.2  774.11  4752.3  770.03  4799.4  766.71  4892.3  764.39
  4913.8  761.77  4924.6  762.05  4936.7  761.38  4946.1  761.91  4967.7  759.63
  4976.5  757.25  4976.7  756.75  4980.5  757.25  4985.2  758.74  5003.0  759.57
  5007.5  760.73  5043.6  762.37  5064.6  762.28  5085.6  764.46  5108.2  764.88
  5172.8  769.96  5187.8  769.87  5193.8  771.27  5202.8  771.51  5244.9  775.30
  5311.0  779.02  5324.5  780.64  5332.0  782.75  5338.0  782.78  5360.6  785.47
#Mann=3,-1,0
  4730.7    0.05       0  4976.5   0.033       0  4980.5    0.05       0
Bank Sta=4976.5,4980.5
Exp/Cntr=0.3,0.1

Type RM Length L Ch R = 1,6106,333,333,333
BEGIN DESCRIPTION:
Denton Creek Tributary 40 14.0
END DESCRIPTION:
XS GIS Cut Line= 3
      2313479.02      7137759.98      2313279.00      7137960.00
      2313229.00      7138259.99
#Sta/Elev= 30
  4734.1  793.20  4737.7  793.20  4748.3  788.55  4762.4  786.32  4776.6  776.61
  4790.7  775.22  4804.8  776.78  4833.1  774.86  4861.4  774.17  4875.5  772.65
  4918.0  765.53  4932.1  764.59  4974.5  759.37  5000.8  753.65  5001.1  753.15
  5004.6  753.15  5004.8  753.65  5013.4  757.03  5019.5  757.03  5044.8  759.31
  5057.5  757.75  5087.9  758.69  5128.5  758.00  5158.9  758.85  5209.6  757.50
  5219.7  757.74  5227.3  758.74  5232.4  758.20  5280.6  767.01  5321.1  769.46
#Mann=3,-1,0
  4734.1    0.05       0  5000.8   0.033       0  5004.8    0.05       0
Bank Sta=5000.8,5004.8
Exp/Cntr=0.3,0.1

Type RM Length L Ch R = 1,5773,229,229,229
BEGIN DESCRIPTION:
Denton Creek Tributary 40 13.0
END DESCRIPTION:
XS GIS Cut Line= 3
      2313229.00      7137610.00      2312929.00      7137860.00
      2312829.01      7138159.96
#Sta/Elev= 30
  4709.4  778.84  4751.7  775.01  4766.0  772.90  4794.7  770.40  4801.2  769.19
  4823.3  767.66  4865.6  762.56  4872.8  762.61  4901.4  760.51  4907.9  759.40
  4915.7  759.17  4930.0  756.83  4936.5  753.85  4957.4  751.80  5000.3  752.01
  5006.1  751.44  5006.4  750.94  5009.9  750.94  5010.1  751.44  5014.7  752.04
  5071.9  752.25  5092.8  753.14  5121.0  753.18  5163.2  754.96  5226.4  758.68
  5236.9  758.75  5258.0  760.52  5352.9  765.81  5384.5  766.81  5416.1  768.75
#Mann=3,-1,0
  4709.4    0.05       0  5006.1   0.033       0  5010.1    0.05       0
Bank Sta=5006.1,5010.1
Exp/Cntr=0.3,0.1

Type RM Length L Ch R = 1,5544,152,152,152
BEGIN DESCRIPTION:
Mapping XS fc96bc10
END DESCRIPTION:
XS GIS Cut Line= 2
      2312891.76      7137207.81      2312731.79      7138043.64
#Sta/Elev= 30
  4434.4  773.64  4457.0  773.30  4497.7  771.23  4526.0  769.29  4548.6  768.36
  4569.0  764.52  4578.1  762.26  4583.2  759.66  4589.4  757.58  4599.5  755.82
  4619.9  750.20  4630.1  749.29  4782.8  749.49  4923.3  749.09  4923.6  748.59
  4927.1  748.59  4927.3  749.09  4952.6  749.48  4996.6  749.49  5009.8  749.12
  5017.0  752.24  5056.7  752.15  5061.8  752.63  5098.4  753.64  5113.9  755.80
  5119.0  758.51  5129.0  759.26  5200.2  762.38  5241.0  762.77  5285.4  763.90
#Mann=3,-1,0
  4434.4    0.05       0  4923.3   0.033       0  4927.3    0.05       0
Bank Sta=4923.3,4927.3
Exp/Cntr=0.3,0.1

Type RM Length L Ch R = 1,5392,517,517,517
BEGIN DESCRIPTION:
Mapping XS 91d939cb
END DESCRIPTION:
XS GIS Cut Line= 2
      2312774.94      7137260.17      2312624.25      7137970.97
#Sta/Elev= 30
  4514.0  767.37  4563.3  760.76  4575.2  755.34  4612.9  754.33  4618.1  752.03
  4662.6  753.21  4667.7  751.14  4707.2  752.74  4712.3  750.27  4756.8  752.15
  4761.9  750.24  4806.5  751.71  4811.6  749.47  4851.1  750.77  4856.2  748.63
  4900.7  750.70  4932.9  748.31  4950.4  749.56  4955.5  747.93  4994.3  748.88
  5003.2  747.63  5003.4  747.13  5007.2  747.63  5024.9  750.48  5035.2  755.19
  5094.3  757.17  5099.4  755.49  5127.2  755.30  5188.5  758.56  5240.6  758.90
#Mann=3,-1,0
  4514.0    0.05       0  5003.2   0.033       0  5007.2    0.05       0
Bank Sta=5003.2,5007.2
Exp/Cntr=0.3,0.1

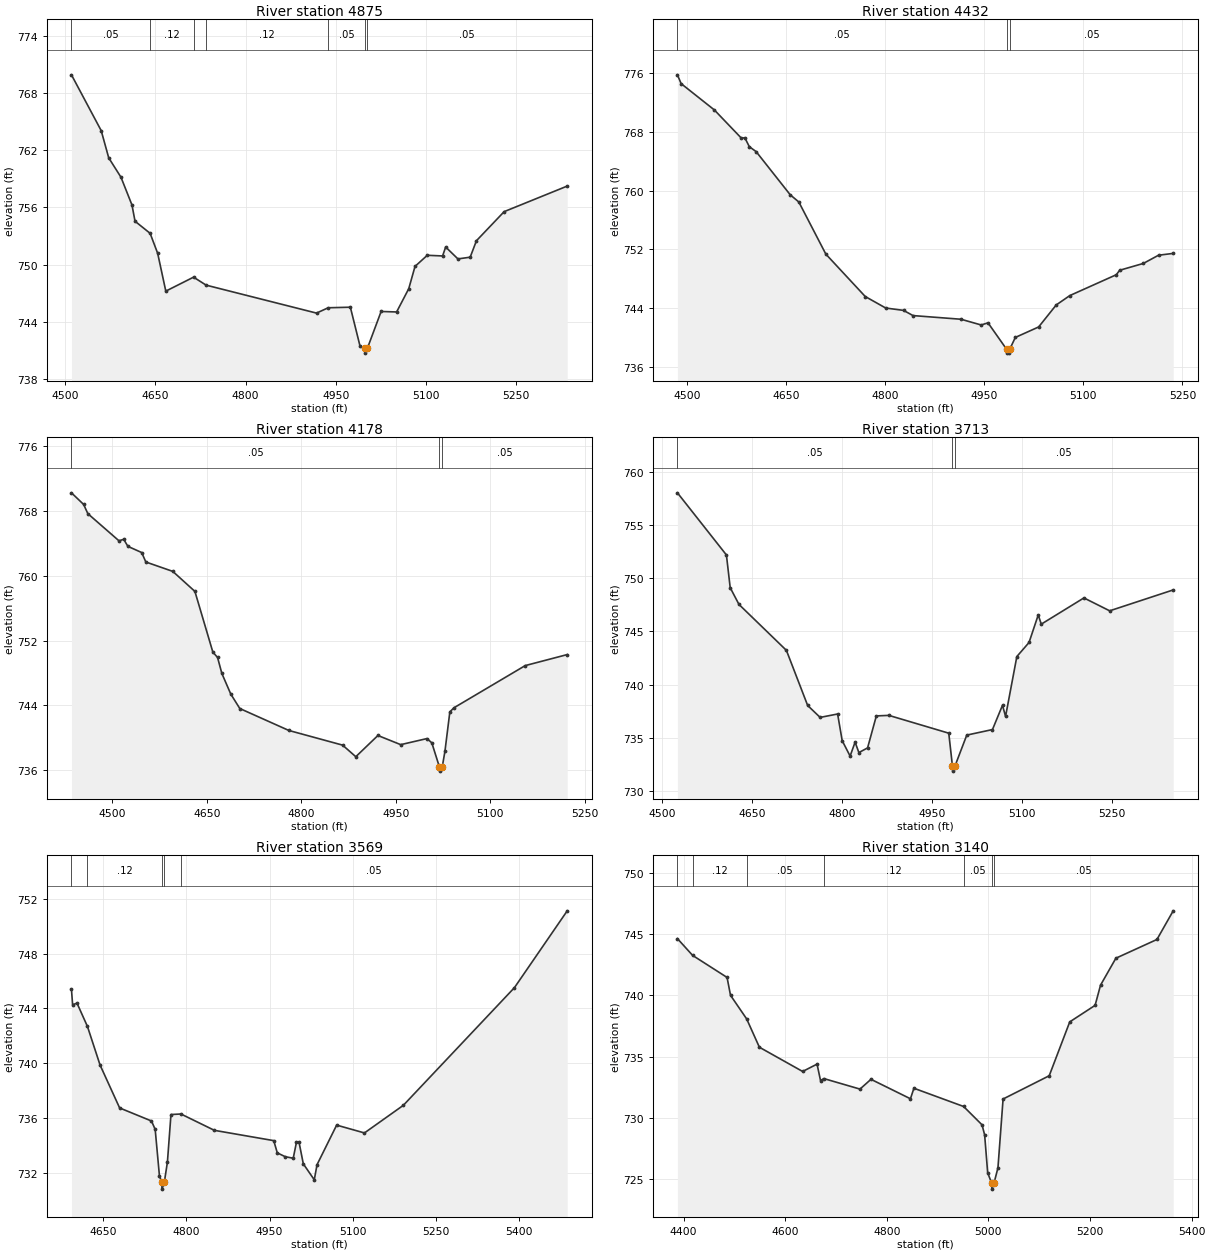
Type RM Length L Ch R = 1,4875,443,443,443
BEGIN DESCRIPTION:
Mapping XS 904cba15
END DESCRIPTION:
XS GIS Cut Line= 2
      2312819.81      7137274.82      2312010.57      7137435.35
#Sta/Elev= 30
  4510.2  769.95  4559.7  764.08  4572.2  761.22  4592.6  759.18  4610.9  756.26
  4616.0  754.55  4641.1  753.28  4653.7  751.17  4667.2  747.20  4713.4  748.67
  4734.3  747.83  4918.0  744.89  4937.4  745.45  4974.3  745.51  4990.2  741.47
  4998.2  741.18  4998.6  740.68  5002.6  741.18  5025.5  745.06  5051.3  745.01
  5071.5  747.46  5081.9  749.80  5102.3  750.97  5127.8  750.90  5132.9  751.84
  5153.3  750.59  5173.7  750.77  5184.1  752.50  5230.2  755.56  5335.2  758.25
#Mann=7,-1,0
  4510.2    0.05       0  4641.1    0.12       0  4713.4    0.05       0
  4734.3    0.12       0  4937.4    0.05       0  4998.2   0.033       0
  5002.6    0.05       0
Bank Sta=4998.2,5002.6
Exp/Cntr=0.3,0.1

Type RM Length L Ch R = 1,4432,254,254,254
BEGIN DESCRIPTION:
Mapping XS 762a55ac
END DESCRIPTION:
XS GIS Cut Line= 2
      2312554.42      7136960.24      2311827.45      7137145.48
#Sta/Elev= 30
  4485.8  775.78  4491.4  774.58  4541.7  770.99  4582.6  767.14  4587.8  767.20
  4594.6  765.98  4604.9  765.31  4656.5  759.42  4669.5  758.44  4710.4  751.33
  4770.0  745.55  4801.0  743.98  4827.9  743.66  4842.3  742.95  4914.9  742.45
  4945.4  741.67  4955.8  741.96  4984.1  738.33  4984.5  737.83  4988.1  737.83
  4988.5  738.33  4997.1  739.97  5032.4  741.40  5059.0  744.40  5079.6  745.68
  5149.9  748.52  5155.0  749.13  5190.8  750.06  5213.8  751.18  5236.0  751.43
#Mann=3,-1,0
  4485.8    0.05       0  4984.1   0.033       0  4988.5    0.05       0
Bank Sta=4984.1,4988.5
Exp/Cntr=0.3,0.1

Type RM Length L Ch R = 1,4178,465,465,465
BEGIN DESCRIPTION:
Denton Creek Tributary 40 9.0
END DESCRIPTION:
XS GIS Cut Line= 3
      2312314.38      7136548.58      2311875.98      7136928.31
      2311717.40      7137061.69
#Sta/Elev= 30
  4435.0  770.24  4454.4  768.80  4461.0  767.67  4510.4  764.32  4518.0  764.50
  4524.6  763.63  4546.5  762.87  4553.1  761.70  4595.9  760.54  4631.0  758.07
  4659.5  750.58  4667.0  749.91  4673.8  747.94  4688.0  745.39  4702.3  743.61
  4780.2  740.90  4865.5  739.09  4886.5  737.66  4921.6  740.28  4957.8  739.15
  4999.5  739.90  5007.2  739.37  5019.3  736.38  5019.7  735.88  5023.7  736.38
  5028.0  738.32  5035.8  743.19  5042.3  743.70  5155.5  748.91  5222.2  750.27
#Mann=3,-1,0
  4435.0    0.05       0  5019.3   0.033       0  5023.7    0.05       0
Bank Sta=5019.3,5023.7
Exp/Cntr=0.3,0.1

Type RM Length L Ch R = 1,3713,144,144,144
BEGIN DESCRIPTION:
Denton Creek Tributary 40 8.0
END DESCRIPTION:
XS GIS Cut Line= 3
      2311884.47      7136281.42      2311601.22      7136654.80
      2311662.70      7137006.51
#Sta/Elev= 30
  4526.1  758.01  4607.7  752.18  4614.0  749.11  4628.6  747.54  4707.6  743.23
  4743.0  738.06  4763.8  736.94  4792.9  737.26  4800.5  734.76  4813.7  733.31
  4822.0  734.62  4828.3  733.64  4842.8  734.08  4857.4  737.08  4878.2  737.13
  4978.0  735.46  4984.1  732.40  4984.5  731.90  4988.5  732.40  5008.0  735.28
  5050.8  735.80  5067.5  738.08  5072.6  737.03  5091.4  742.65  5111.7  743.97
  5127.0  746.55  5132.1  745.69  5203.1  748.15  5246.0  746.94  5351.8  748.90
#Mann=3,-1,0
  4526.1    0.05       0  4984.1   0.033       0  4988.5    0.05       0
Bank Sta=4984.1,4988.5
Exp/Cntr=0.3,0.1

Type RM Length L Ch R = 1,3569,429,429,429
BEGIN DESCRIPTION:
Mapping XS 8fbaca0c
END DESCRIPTION:
XS GIS Cut Line= 3
      2311734.47      7136292.24      2311476.69      7136612.36
      2310994.03      7136652.04
#Sta/Elev= 30
  4592.3  745.40  4594.4  744.27  4602.3  744.39  4621.2  742.69  4644.0  739.88
  4679.3  736.76  4736.8  735.81  4743.5  735.20  4751.2  731.81  4755.3  731.35
  4755.8  730.85  4760.0  731.35  4765.6  732.82  4772.0  736.28  4790.0  736.32
  4850.4  735.13  4957.6  734.38  4964.0  733.49  4978.4  733.21  4992.8  733.10
  4998.6  734.26  5003.3  734.26  5011.0  732.69  5030.8  731.53  5035.8  732.63
  5071.2  735.51  5121.4  734.94  5191.6  736.95  5392.3  745.52  5487.6  751.11
#Mann=5,-1,0
  4592.3    0.05       0  4621.2    0.12       0  4755.3   0.033       0
  4760.0    0.12       0  4790.0    0.05       0
Bank Sta=4755.3,4760
Exp/Cntr=0.3,0.1

Type RM Length L Ch R = 1,3140,535,535,535
BEGIN DESCRIPTION:
Denton Creek Tributary 40 7.0
END DESCRIPTION:
XS GIS Cut Line= 3
      2311632.46      7135995.67      2311313.00      7136347.75
      2310817.27      7136415.09
#Sta/Elev= 30
  4388.0  744.64  4417.9  743.27  4485.7  741.47  4492.5  740.01  4524.3  738.08
  4549.3  735.77  4634.4  733.79  4662.8  734.39  4669.6  733.05  4676.1  733.21
  4747.3  732.35  4768.9  733.15  4846.6  731.56  4853.4  732.42  4951.2  730.93
  4987.5  729.43  4992.6  728.61  4998.6  725.51  5006.3  724.68  5006.9  724.18
  5011.1  724.68  5018.8  725.92  5028.9  731.54  5119.7  733.44  5160.1  737.84
  5210.0  739.19  5220.7  740.84  5250.9  743.04  5331.7  744.57  5363.7  746.91
#Mann=7,-1,0
  4388.0    0.05       0  4417.9    0.12       0  4524.3    0.05       0
  4676.1    0.12       0  4951.2    0.05       0  5006.3    0.04       0
  5011.1    0.05       0
Bank Sta=5006.3,5011.1
Exp/Cntr=0.3,0.1

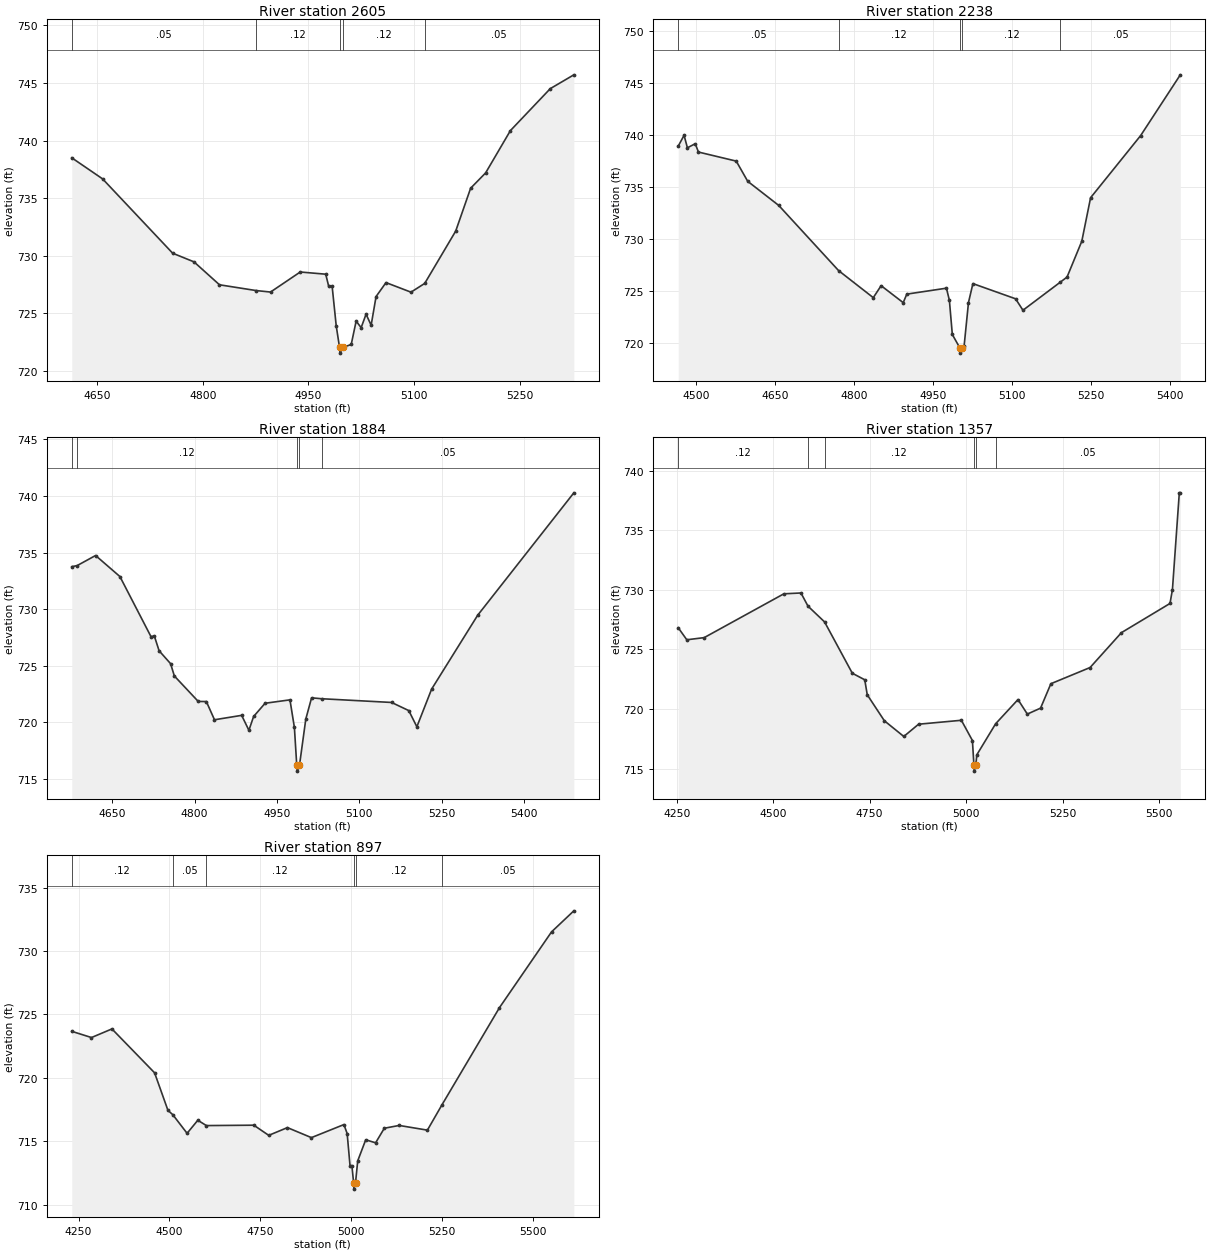
Type RM Length L Ch R = 1,2605,367,367,367
BEGIN DESCRIPTION:
Denton Creek Tributary 40 6.0
END DESCRIPTION:
XS GIS Cut Line= 3
      2311228.97      7135860.02      2310922.21      7136059.50
      2310674.07      7136302.32
#Sta/Elev= 30
  4614.0  738.51  4657.8  736.68  4757.3  730.23  4787.6  729.48  4823.8  727.49
  4875.8  726.99  4896.3  726.86  4938.5  728.60  4974.7  728.41  4978.9  727.36
  4983.8  727.36  4989.6  723.93  4994.3  722.06  4994.9  721.56  4999.2  722.06
  5010.9  722.31  5017.9  724.34  5025.0  723.77  5032.0  724.94  5039.2  723.98
  5046.2  726.47  5060.3  727.68  5095.8  726.85  5115.3  727.61  5159.3  732.15
  5180.5  735.87  5201.8  737.20  5237.0  740.87  5293.6  744.51  5327.1  745.71
#Mann=5,-1,0
  4614.0    0.05       0  4875.8    0.12       0  4994.3    0.07       0
  4999.2    0.12       0  5115.3    0.05       0
Bank Sta=4994.3,4999.2
Exp/Cntr=0.3,0.1

Type RM Length L Ch R = 1,2238,354,354,354
BEGIN DESCRIPTION:
Denton Creek Tributary 40 5.0
END DESCRIPTION:
XS GIS Cut Line= 3
      2311098.14      7135525.05      2310679.00      7135810.00
      2310479.02      7136209.96
#Sta/Elev= 30
  4465.8  738.95  4476.9  739.99  4483.2  738.79  4498.1  739.18  4504.2  738.38
  4576.0  737.51  4597.8  735.57  4656.8  733.25  4770.5  726.99  4836.4  724.39
  4851.3  725.54  4893.3  723.91  4900.1  724.73  4975.4  725.30  4981.0  724.14
  4986.6  720.85  5000.9  719.56  5001.5  719.06  5005.8  719.56  5009.0  719.74
  5017.3  723.92  5025.7  725.74  5106.8  724.28  5120.8  723.18  5191.8  725.88
  5204.6  726.37  5232.6  729.81  5249.3  733.99  5344.4  739.96  5419.8  745.80
#Mann=5,-1,0
  4465.8    0.05       0  4770.5    0.12       0  5000.9    0.07       0
  5005.8    0.12       0  5191.8    0.05       0
Bank Sta=5000.9,5005.8
Exp/Cntr=0.3,0.1

Type RM Length L Ch R = 1,1884,527,527,527
BEGIN DESCRIPTION:
Denton Creek Tributary 40 4.0
END DESCRIPTION:
XS GIS Cut Line= 3
      2310687.61      7135217.51      2310459.41      7135539.42
      2310313.56      7136038.66
#Sta/Elev= 30
  4576.1  733.75  4586.0  733.85  4619.5  734.74  4663.8  732.88  4720.4  727.57
  4726.5  727.63  4735.2  726.32  4756.1  725.18  4763.0  724.09  4806.5  721.84
  4821.3  721.83  4836.1  720.22  4885.6  720.61  4898.8  719.29  4907.4  720.51
  4928.3  721.68  4973.6  721.98  4981.7  719.54  4986.0  716.18  4986.6  715.68
  4990.9  716.18  5002.5  720.29  5013.0  722.16  5031.1  722.08  5158.8  721.75
  5190.1  721.03  5204.8  719.60  5231.7  722.93  5315.6  729.46  5490.8  740.28
#Mann=5,-1,0
  4576.1    0.05       0  4586.0    0.12       0  4986.0    0.07       0
  4990.9    0.12       0  5031.1    0.05       0
Bank Sta=4986,4990.9
Exp/Cntr=0.3,0.1

Type RM Length L Ch R = 1,1357,460,460,460
BEGIN DESCRIPTION:
Denton Creek Tributary 40 3.0
END DESCRIPTION:
XS GIS Cut Line= 3
      2310738.71      7134970.48      2310079.00      7135310.00
      2309978.99      7135860.03
#Sta/Elev= 30
  4254.0  726.82  4276.2  725.81  4321.2  725.99  4527.7  729.67  4572.0  729.74
  4590.3  728.63  4633.2  727.31  4705.1  723.00  4737.3  722.45  4743.8  721.19
  4788.1  719.01  4838.5  717.69  4876.8  718.72  4987.7  719.05  5016.3  717.35
  5020.2  715.28  5020.8  714.78  5025.1  715.28  5027.7  716.15  5076.5  718.76
  5134.4  720.79  5158.6  719.57  5192.9  720.07  5219.6  722.12  5321.2  723.48
  5402.5  726.41  5528.3  728.86  5534.6  730.03  5552.4  738.15  5555.0  738.15
#Mann=6,-1,0
  4254.0    0.12       0  4590.3    0.05       0  4633.2    0.12       0
  5020.2    0.07       0  5025.1    0.12       0  5076.5    0.05       0
Bank Sta=5020.2,5025.1
Exp/Cntr=0.3,0.1

Type RM Length L Ch R = 1,897,0,0,0
BEGIN DESCRIPTION:
Denton Creek Tributary 40 2.0
END DESCRIPTION:
XS GIS Cut Line= 3
      2310506.56      7134832.37      2309758.65      7135010.39
      2309628.99      7135610.03
#Sta/Elev= 30
  4231.2  723.67  4285.5  723.18  4341.8  723.86  4459.2  720.40  4496.0  717.44
  4509.3  717.10  4548.7  715.63  4578.2  716.66  4601.8  716.24  4732.4  716.27
  4773.5  715.47  4824.9  716.08  4891.0  715.29  4980.5  716.32  4989.4  715.61
  4997.3  713.08  5002.4  713.08  5007.2  711.73  5007.9  711.23  5012.4  711.73
  5018.5  713.46  5040.5  715.12  5067.7  714.88  5091.7  716.03  5132.6  716.25
  5210.3  715.88  5250.3  717.87  5408.8  725.54  5552.1  731.51  5613.5  733.17
#Mann=6,-1,0
  4231.2    0.12       0  4509.3    0.05       0  4601.8    0.12       0
  5007.2    0.07       0  5012.4    0.12       0  5250.3    0.05       0
Bank Sta=5007.2,5012.4
Exp/Cntr=0.3,0.1

Chan Stop Cuts=-1