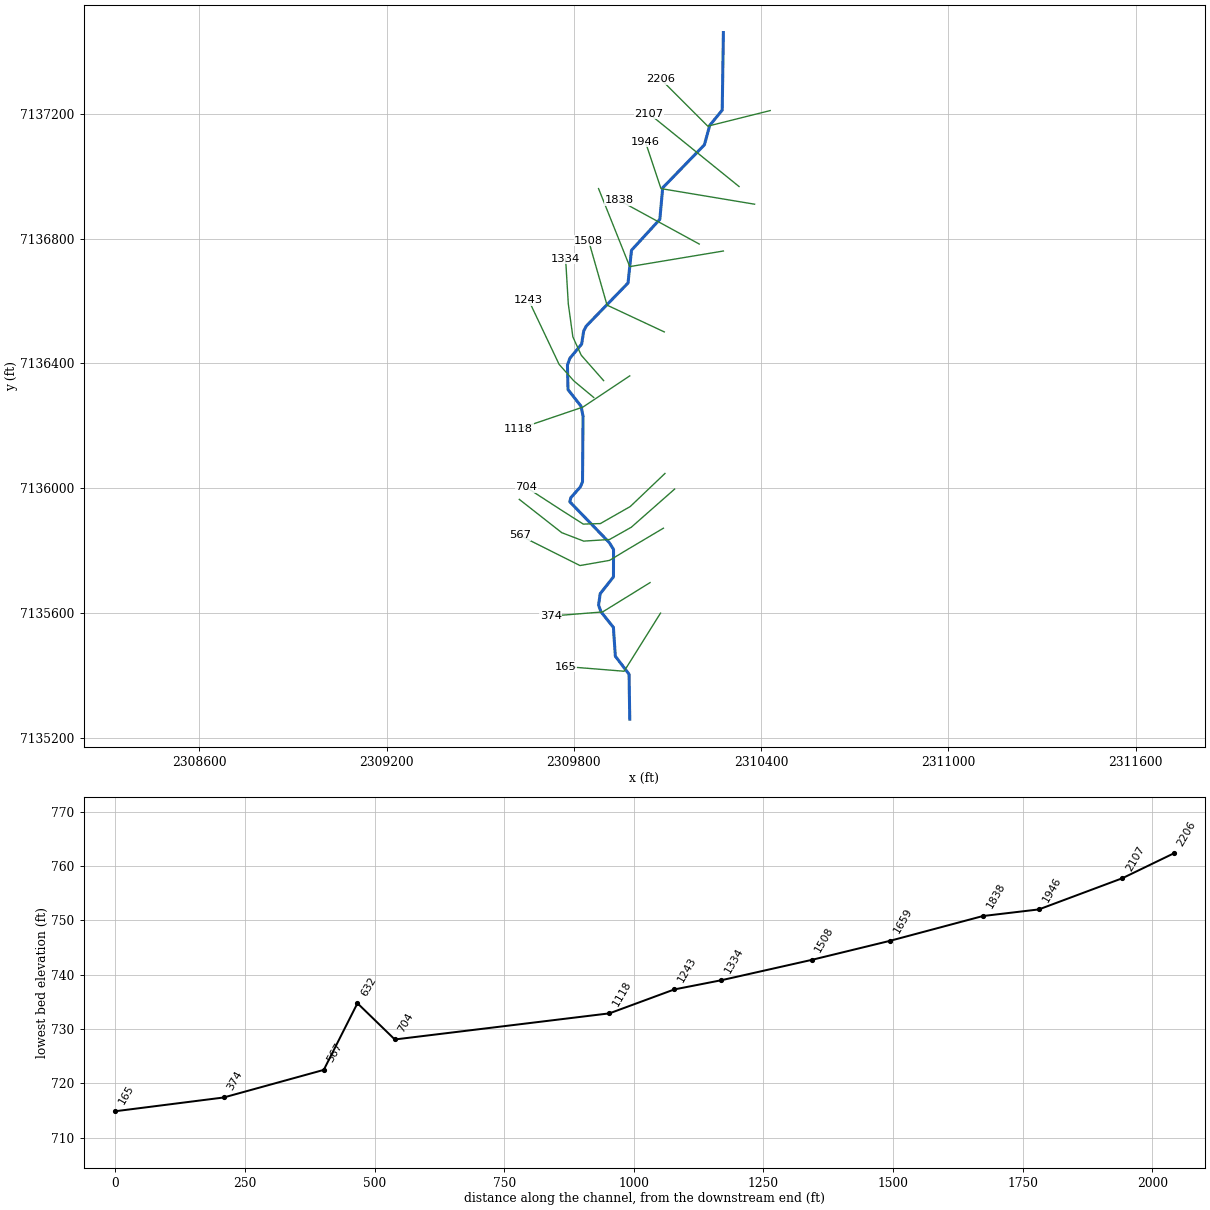
--- Denton Creek Tributary 40_1.prj (project) ---

Proj Title=Denton Creek Tributary 40_1 Base Level Engineering
Current Plan=p01
Default Exp/Contr=0.3,0.1
English Units
Geom File=g01
Flow File=f01
Plan File=p01
BEGIN DESCRIPTION:
Denton Creek Tributary 40_1
END DESCRIPTION:

--- Denton Creek Tributary 40_1.p01 (plan) ---

Plan Title=Multiple Run
Short Identifier=Multiple
Geom File=g01
Flow File=f01
Subcritical Flow
K Sum by GR= 0
Std Step Tol= 0.01
Critical Tol= 0.01
Num of Std Step Trials= 20
Max Error Tol= 0.3
Flow Tol Ratio= 0.001
Split Flow NTrial= 30
Split Flow Tol= 0.02
Split Flow Ratio= 0.02
Log Output Level= 0
Friction Slope Method= 1
Unsteady Friction Slope Method= 2
Unsteady Bridges Friction Slope Method= 1
Parabolic Critical Depth
Global Vel Dist=  1 , 1 , 1
Global Log Level= 0
CheckData=True
Encroach Param= -1, 0, 0, 0
BEGIN DESCRIPTION:
Multiple Run
END DESCRIPTION:

--- Denton Creek Tributary 40_1.f01 (steady flow) ---

Flow Title=Multiple
Number of Profiles=7
Profile Names=10-year,25-year,50-year,1pct_min,100-year,1pct_plu,500-year
River Rch & RM= Denton Creek Tri,Reach-1,2206
     167     212     246     143     286     570     383
Boundary for River Rch & Prof#=Denton Creek Tri,Reach-1,1
Up Type=0
Dn Type=3
Dn Slope=0.005
Boundary for River Rch & Prof#=Denton Creek Tri,Reach-1,2
Up Type=0
Dn Type=3
Dn Slope=0.005
Boundary for River Rch & Prof#=Denton Creek Tri,Reach-1,3
Up Type=0
Dn Type=3
Dn Slope=0.005
Boundary for River Rch & Prof#=Denton Creek Tri,Reach-1,4
Up Type=0
Dn Type=3
Dn Slope=0.005
Boundary for River Rch & Prof#=Denton Creek Tri,Reach-1,5
Up Type=0
Dn Type=3
Dn Slope=0.005
Boundary for River Rch & Prof#=Denton Creek Tri,Reach-1,6
Up Type=0
Dn Type=3
Dn Slope=0.005
Boundary for River Rch & Prof#=Denton Creek Tri,Reach-1,7
Up Type=0
Dn Type=3
Dn Slope=0.005

--- Denton Creek Tributary 40_1.g01 (geometry) ---

Geom Title=Existing Conditions

River Reach=Denton Creek Tri,Reach-1
Reach XY= 30
      2310279.00      7137460.00      2310275.25      7137211.55
      2310235.14      7137162.17      2310218.24      7137100.32
      2310084.52      7136962.43      2310075.37      7136861.50
      2309984.54      7136762.42      2309973.48      7136657.57
      2309839.76      7136519.68      2309831.50      7136503.97
      2309824.78      7136461.75      2309787.04      7136416.05
      2309779.37      7136394.73      2309781.17      7136315.98
      2309823.25      7136262.34      2309829.36      7136230.15
      2309827.61      7136020.43      2309820.53      7136003.81
      2309790.33      7135969.84      2309786.79      7135956.58
      2309912.60      7135826.75      2309927.04      7135804.11
      2309926.81      7135715.97      2309884.38      7135662.18
      2309879.09      7135625.39      2309886.81      7135604.08
      2309926.62      7135554.03      2309932.85      7135461.60
      2309976.78      7135404.08      2309979.00      7135260.00

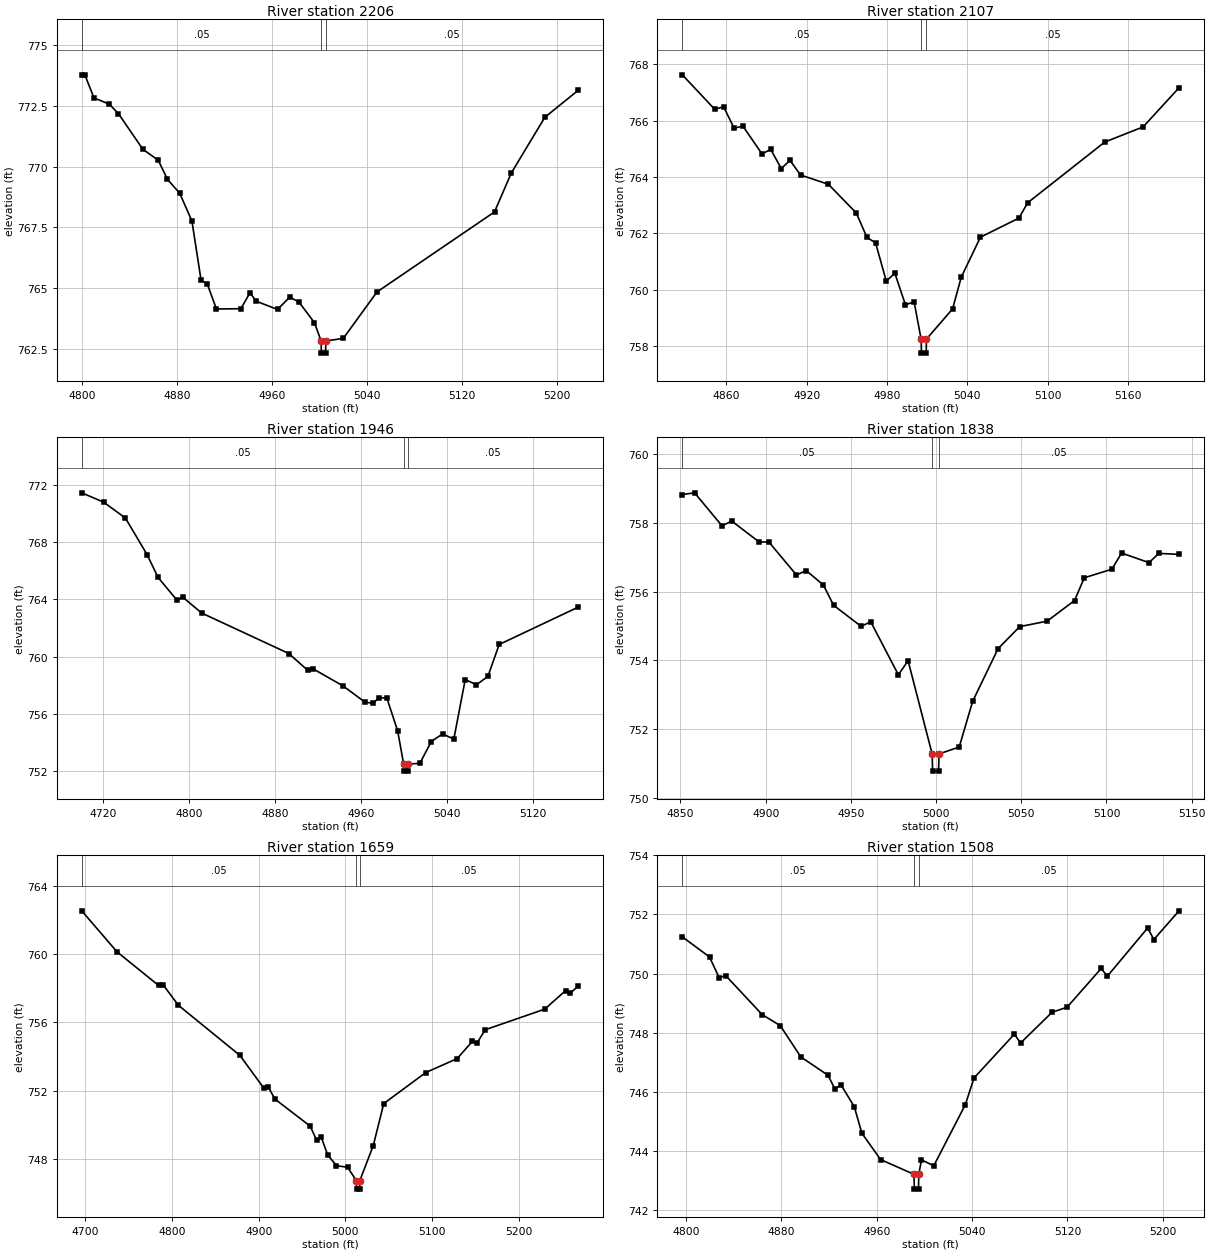
Type RM Length L Ch R = 1,2206,99,99,99
BEGIN DESCRIPTION:
Denton Creek Tributary 40_1 6.0
END DESCRIPTION:
XS GIS Cut Line= 3
      2310429.01      7137210.00      2310229.00      7137160.00
      2310079.00      7137310.00
#Sta/Elev= 30
  4799.8  773.78  4802.4  773.78  4810.1  772.83  4823.0  772.57  4830.7  772.18
  4851.3  770.71  4864.2  770.26  4872.0  769.47  4882.3  768.90  4892.6  767.75
  4900.3  765.31  4905.5  765.16  4913.2  764.13  4933.8  764.14  4941.5  764.80
  4946.7  764.45  4964.7  764.11  4975.0  764.62  4982.8  764.41  4995.7  763.57
  5001.4  762.81  5001.6  762.31  5005.1  762.31  5005.4  762.81  5020.1  762.92
  5048.4  764.83  5147.4  768.13  5161.5  769.73  5189.8  772.03  5218.1  773.15
#Mann=3,-1,0
  4799.8    0.05       0  5001.4    0.04       0  5005.4    0.05       0
Bank Sta=5001.4,5005.4
Exp/Cntr=0.3,0.1

Type RM Length L Ch R = 1,2107,161,161,161
BEGIN DESCRIPTION:
Mapping XS f5c01043
END DESCRIPTION:
XS GIS Cut Line= 2
      2310329.16      7136966.64      2310040.84      7137199.97
#Sta/Elev= 30
  4827.2  767.63  4851.5  766.40  4858.0  766.50  4865.9  765.73  4872.4  765.81
  4886.7  764.82  4893.2  764.98  4901.1  764.30  4907.6  764.59  4915.5  764.07
  4936.3  763.74  4957.1  762.72  4965.1  761.85  4971.5  761.66  4979.5  760.30
  4985.9  760.58  4993.8  759.46  5000.3  759.56  5005.5  758.24  5005.8  757.74
  5009.3  757.74  5009.5  758.24  5029.0  759.31  5035.5  760.44  5049.8  761.86
  5078.6  762.54  5085.0  763.08  5142.6  765.24  5171.3  765.78  5198.1  767.17
#Mann=3,-1,0
  4827.2    0.05       0  5005.5    0.04       0  5009.5    0.05       0
Bank Sta=5005.5,5009.5
Exp/Cntr=0.3,0.1

Type RM Length L Ch R = 1,1946,108,108,108
BEGIN DESCRIPTION:
Denton Creek Tributary 40_1 5.0
END DESCRIPTION:
XS GIS Cut Line= 3
      2310379.03      7136909.99      2310079.00      7136960.00
      2310029.00      7137110.01
#Sta/Elev= 30
  4699.9  771.45  4720.2  770.80  4740.5  769.69  4760.8  767.12  4770.9  765.54
  4788.6  763.94  4793.7  764.17  4811.5  763.05  4892.6  760.22  4910.3  759.04
  4915.4  759.14  4943.2  757.95  4963.5  756.82  4971.1  756.74  4976.2  757.12
  4983.8  757.12  4993.9  754.82  4999.5  752.50  4999.8  752.00  5003.3  752.00
  5003.5  752.50  5014.6  752.54  5025.2  754.07  5035.7  754.60  5046.2  754.24
  5056.8  758.40  5067.3  758.04  5077.9  758.62  5088.4  760.85  5162.2  763.47
#Mann=3,-1,0
  4699.9    0.05       0  4999.5    0.04       0  5003.5    0.05       0
Bank Sta=4999.5,5003.5
Exp/Cntr=0.3,0.1

Type RM Length L Ch R = 1,1838,179,179,179
BEGIN DESCRIPTION:
Mapping XS 2ad0f4bb
END DESCRIPTION:
XS GIS Cut Line= 2
      2310201.68      7136782.32      2309945.77      7136921.90
#Sta/Elev= 30
  4851.1  758.82  4858.3  758.87  4874.4  757.91  4880.1  758.05  4896.2  757.44
  4901.9  757.44  4918.1  756.48  4923.8  756.61  4933.9  756.19  4939.9  755.60
  4956.0  754.99  4961.7  755.12  4977.9  753.58  4983.6  753.99  4997.7  751.28
  4998.0  750.78  5001.5  750.78  5001.7  751.28  5013.6  751.48  5021.5  752.81
  5036.4  754.34  5049.1  754.98  5065.2  755.14  5081.3  755.74  5087.0  756.40
  5103.2  756.65  5108.9  757.12  5125.0  756.84  5130.7  757.11  5142.6  757.08
#Mann=3,-1,0
  4851.1    0.05       0  4997.7    0.04       0  5001.7    0.05       0
Bank Sta=4997.7,5001.7
Exp/Cntr=0.3,0.1

Type RM Length L Ch R = 1,1659,151,151,151
BEGIN DESCRIPTION:
Denton Creek Tributary 40_1 4.0
END DESCRIPTION:
XS GIS Cut Line= 3
      2310279.02      7136760.00      2309979.00      7136710.00
      2309879.01      7136959.98
#Sta/Elev= 30
  4695.8  762.55  4736.4  760.15  4784.5  758.17  4789.6  758.22  4807.3  757.01
  4878.3  754.07  4906.2  752.13  4911.3  752.19  4918.9  751.50  4959.4  749.92
  4967.0  749.09  4972.1  749.29  4979.7  748.23  4989.8  747.60  5002.7  747.50
  5012.8  746.72  5013.0  746.22  5016.5  746.22  5016.8  746.72  5032.3  748.77
  5044.4  751.24  5092.9  753.06  5129.2  753.88  5146.7  754.89  5152.1  754.79
  5161.5  755.57  5230.2  756.78  5254.4  757.87  5259.8  757.72  5269.2  758.15
#Mann=3,-1,0
  4695.8    0.05       0  5012.8    0.04       0  5016.8    0.05       0
Bank Sta=5012.8,5016.8
Exp/Cntr=0.3,0.1

Type RM Length L Ch R = 1,1508,174,174,174
BEGIN DESCRIPTION:
Mapping XS 0649b2e4
END DESCRIPTION:
XS GIS Cut Line= 3
      2310089.66      7136500.80      2309906.21      7136586.60
      2309847.39      7136792.44
#Sta/Elev= 30
  4797.0  751.24  4819.8  750.56  4827.9  749.86  4833.4  749.93  4864.0  748.61
  4879.1  748.24  4896.4  747.18  4919.2  746.56  4924.8  746.11  4930.3  746.22
  4941.2  745.50  4947.6  744.60  4963.3  743.71  4991.3  743.21  4991.6  742.71
  4995.1  742.71  4995.3  743.21  4997.6  743.70  5007.9  743.50  5034.3  745.56
  5041.7  746.47  5075.5  747.95  5080.7  747.65  5107.1  748.69  5119.7  748.86
  5148.3  750.17  5153.5  749.91  5187.3  751.54  5192.5  751.15  5213.6  752.12
#Mann=3,-1,0
  4797.0    0.05       0  4991.3   0.033       0  4995.3    0.05       0
Bank Sta=4991.3,4995.3
Exp/Cntr=0.3,0.1

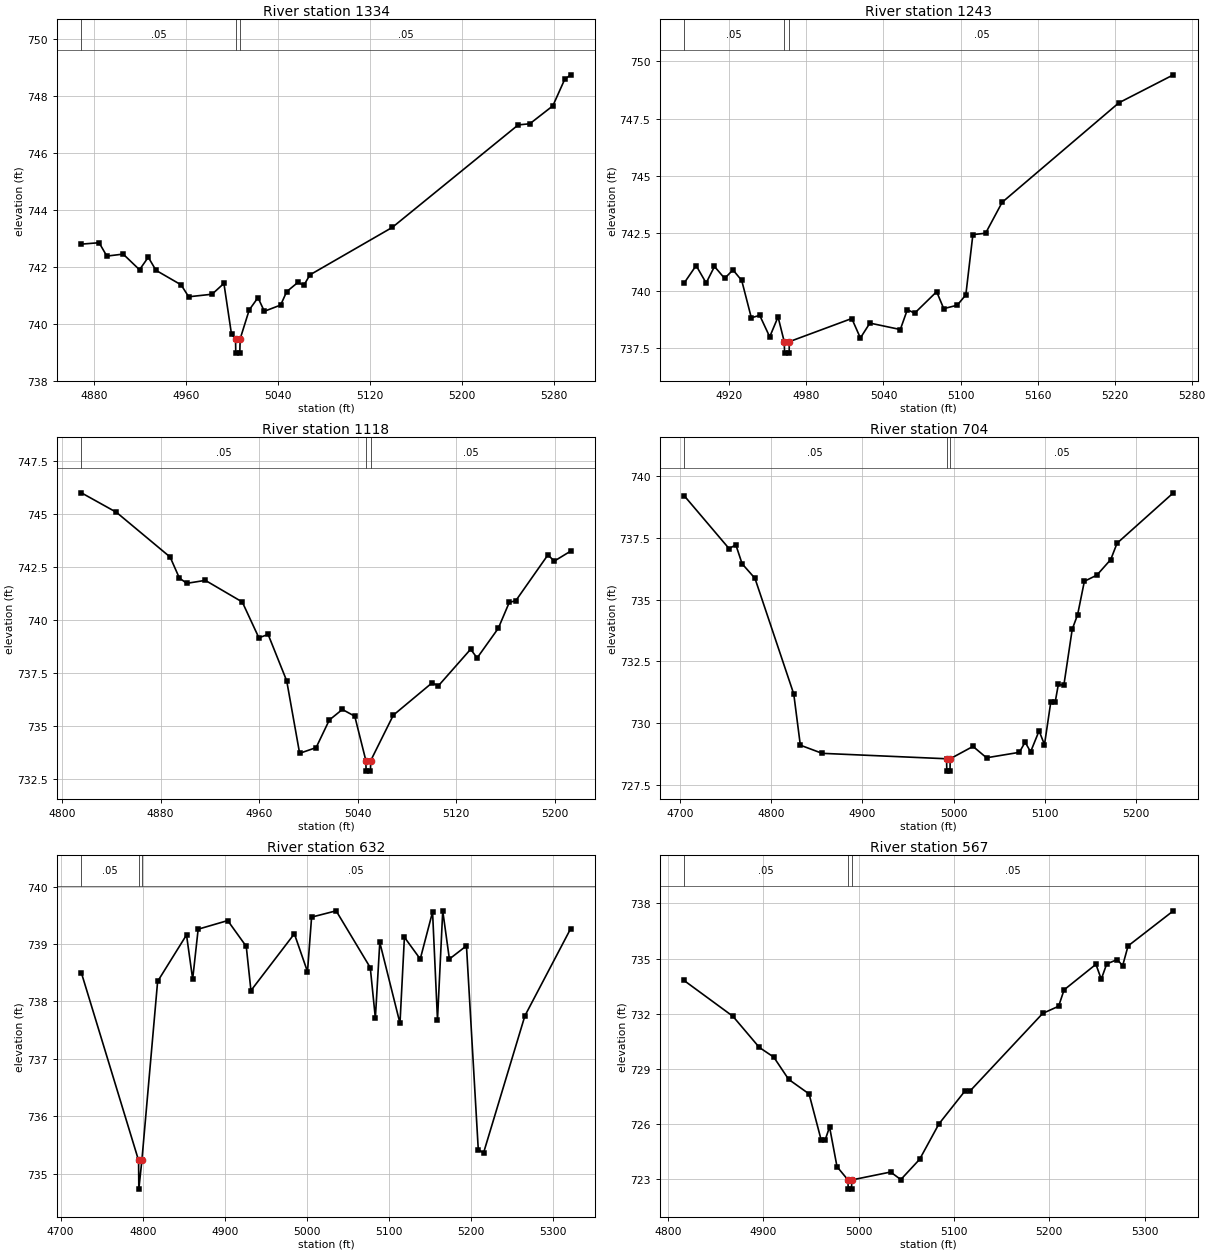
Type RM Length L Ch R = 1,1334,91,91,91
BEGIN DESCRIPTION:
Mapping XS 6fb6584e
END DESCRIPTION:
XS GIS Cut Line= 5
      2309895.31      7136344.69      2309823.41      7136426.31
      2309796.72      7136484.87      2309782.11      7136590.63
      2309773.41      7136735.48
#Sta/Elev= 30
  4869.3  742.80  4884.7  742.85  4891.4  742.38  4905.6  742.45  4919.8  741.90
  4927.4  742.34  4934.1  741.88  4955.9  741.37  4962.5  740.95  4982.8  741.04
  4993.1  741.42  4999.7  739.63  5003.2  739.47  5003.4  738.97  5006.9  738.97
  5007.2  739.47  5015.1  740.49  5022.7  740.92  5028.2  740.44  5042.4  740.66
  5047.6  741.13  5057.5  741.46  5062.5  741.35  5067.8  741.72  5139.4  743.39
  5248.7  746.99  5258.8  747.03  5278.8  747.66  5289.1  748.59  5294.3  748.75
#Mann=3,-1,0
  4869.3    0.05       0  5003.2    0.04       0  5007.2    0.05       0
Bank Sta=5003.2,5007.2
Exp/Cntr=0.3,0.1

Type RM Length L Ch R = 1,1243,125,125,125
BEGIN DESCRIPTION:
Mapping XS a3e6b3fc
END DESCRIPTION:
XS GIS Cut Line= 4
      2309863.51      7136290.86      2309800.02      7136343.68
      2309752.71      7136396.67      2309655.24      7136602.09
#Sta/Elev= 30
  4884.7  740.32  4894.1  741.09  4901.9  740.33  4908.4  741.05  4916.3  740.53
  4922.8  740.90  4929.6  740.44  4937.1  738.81  4943.6  738.92  4951.4  737.98
  4957.9  738.85  4962.7  737.77  4963.0  737.27  4966.5  737.27  4966.7  737.77
  5015.3  738.78  5022.0  737.93  5029.4  738.58  5053.1  738.30  5058.6  739.17
  5064.2  739.01  5081.4  739.95  5086.9  739.21  5097.4  739.36  5104.1  739.81
  5109.6  742.44  5119.5  742.50  5132.4  743.85  5223.3  748.19  5265.7  749.41
#Mann=3,-1,0
  4884.7    0.05       0  4962.7    0.04       0  4966.7    0.05       0
Bank Sta=4962.7,4966.7
Exp/Cntr=0.3,0.1

Type RM Length L Ch R = 1,1118,414,414,414
BEGIN DESCRIPTION:
Denton Creek Tributary 40_1 2.0
END DESCRIPTION:
XS GIS Cut Line= 3
      2309979.00      7136360.00      2309829.00      7136260.00
      2309623.34      7136190.08
#Sta/Elev= 30
  4815.6  746.00  4844.1  745.08  4887.7  742.97  4895.2  741.98  4901.2  741.73
  4916.3  741.87  4946.3  740.85  4959.8  739.16  4967.3  739.32  4982.4  737.13
  4992.9  733.71  5006.3  733.98  5017.0  735.28  5027.6  735.78  5037.7  735.46
  5046.7  733.37  5046.9  732.87  5050.4  732.87  5050.7  733.37  5069.0  735.51
  5100.4  737.03  5105.7  736.90  5131.8  738.62  5137.1  738.21  5154.3  739.61
  5163.2  740.83  5168.5  740.91  5194.6  743.07  5199.8  742.78  5213.1  743.25
#Mann=3,-1,0
  4815.6    0.05       0  5046.7    0.04       0  5050.7    0.05       0
Bank Sta=5046.7,5050.7
Exp/Cntr=0.3,0.1

Type RM Length L Ch R = 1,704,72,72,72
BEGIN DESCRIPTION:
Mapping XS 3952ccc6
END DESCRIPTION:
XS GIS Cut Line= 6
      2310091.74      7136047.22      2309980.50      7135941.20
      2309884.89      7135886.70      2309830.06      7135885.04
      2309755.84      7135932.40      2309647.24      7136002.90
#Sta/Elev= 30
  4704.6  739.21  4754.0  737.06  4761.3  737.22  4768.2  736.45  4782.3  735.86
  4824.8  731.18  4832.0  729.11  4855.9  728.78  4992.2  728.56  4992.5  728.06
  4996.0  728.06  4996.2  728.56  5021.2  729.06  5036.0  728.60  5071.9  728.82
  5078.3  729.23  5084.3  728.84  5093.6  729.69  5099.5  729.13  5106.4  730.85
  5111.2  730.85  5114.7  731.57  5120.7  731.53  5129.9  733.80  5135.8  734.39
  5143.2  735.74  5156.9  735.99  5172.1  736.62  5179.0  737.28  5240.7  739.32
#Mann=3,-1,0
  4704.6    0.05       0  4992.2    0.04       0  4996.2    0.05       0
Bank Sta=4992.2,4996.2
Exp/Cntr=0.3,0.1

Type RM Length L Ch R = 1,632,65,65,65
BEGIN DESCRIPTION:
Mapping XS 6620ff43
END DESCRIPTION:
XS GIS Cut Line= 6
      2310122.82      7135997.26      2309983.90      7135874.91
      2309914.20      7135835.66      2309831.54      7135830.50
      2309761.13      7135857.56      2309625.11      7135964.20
#Sta/Elev= 30
  4725.3  738.50  4795.0  735.23  4795.3  734.73  4799.0  735.23  4818.2  738.35
  4853.4  739.16  4860.9  738.39  4867.6  739.26  4903.6  739.41  4926.2  738.96
  4931.9  738.19  4984.8  739.18  5000.8  738.52  5005.8  739.47  5035.7  739.58
  5077.3  738.59  5083.5  737.71  5088.9  739.03  5113.5  737.62  5118.9  739.12
  5138.2  738.74  5153.2  739.56  5159.2  737.68  5165.6  739.58  5173.7  738.74
  5194.5  738.97  5208.9  735.42  5215.3  735.36  5265.7  737.75  5321.5  739.27
#Mann=3,-1,0
  4725.3    0.05       0  4795.0    0.04       0  4799.0    0.05       0
Bank Sta=4795,4799
Exp/Cntr=0.3,0.1

Type RM Length L Ch R = 1,567,193,193,193
BEGIN DESCRIPTION:
Mapping XS f3609cd5
END DESCRIPTION:
XS GIS Cut Line= 5
      2310086.83      7135871.92      2309962.10      7135797.87
      2309914.40      7135768.79      2309819.63      7135752.20
      2309626.50      7135848.86
#Sta/Elev= 30
  4817.0  733.81  4868.3  731.86  4895.9  730.17  4911.1  729.64  4926.7  728.43
  4948.1  727.64  4960.9  725.11  4964.8  725.11  4969.6  725.84  4977.4  723.68
  4988.9  722.96  4989.1  722.46  4992.6  722.46  4992.9  722.96  5033.6  723.39
  5044.3  722.98  5064.0  724.08  5084.3  726.01  5111.9  727.82  5117.3  727.82
  5193.1  732.02  5209.8  732.41  5215.5  733.30  5248.9  734.69  5254.5  733.88
  5260.2  734.71  5271.3  734.95  5276.9  734.61  5282.6  735.69  5330.1  737.60
#Mann=3,-1,0
  4817.0    0.05       0  4988.9    0.04       0  4992.9    0.05       0
Bank Sta=4988.9,4992.9
Exp/Cntr=0.3,0.1

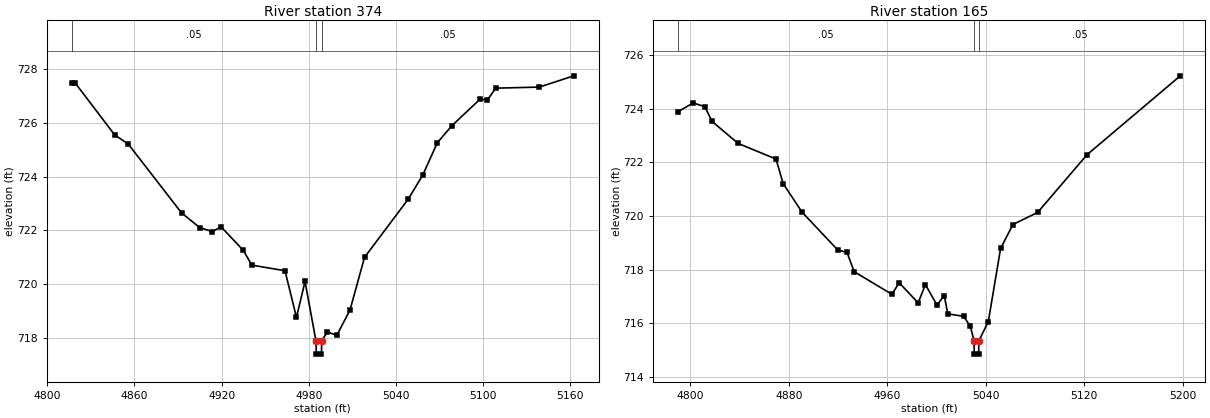
Type RM Length L Ch R = 1,374,209,209,209
BEGIN DESCRIPTION:
Mapping XS 22d41a95
END DESCRIPTION:
XS GIS Cut Line= 3
      2310043.97      7135697.47      2309892.14      7135603.62
      2309725.27      7135590.16
#Sta/Elev= 30
  4816.8  727.49  4819.2  727.49  4846.3  725.56  4855.8  725.21  4892.4  722.65
  4904.9  722.10  4913.7  721.95  4919.6  722.13  4935.0  721.25  4940.8  720.70
  4963.7  720.49  4971.6  718.75  4977.5  720.09  4985.0  717.88  4985.3  717.38
  4988.8  717.38  4989.0  717.88  4992.9  718.21  4999.4  718.08  5008.5  719.03
  5018.5  720.99  5048.6  723.16  5058.6  724.06  5068.7  725.27  5078.7  725.90
  5098.1  726.89  5103.2  726.86  5108.8  727.30  5138.9  727.34  5162.7  727.76
#Mann=3,-1,0
  4816.8    0.05       0  4985.0    0.04       0  4989.0    0.05       0
Bank Sta=4985,4989
Exp/Cntr=0.3,0.1

Type RM Length L Ch R = 1,165,0,0,0
BEGIN DESCRIPTION:
Denton Creek Tributary 40_1 1.0
END DESCRIPTION:
XS GIS Cut Line= 3
      2310077.61      7135599.86      2309960.94      7135413.57
      2309773.46      7135428.64
#Sta/Elev= 30
  4790.1  723.89  4802.3  724.21  4811.7  724.07  4817.6  723.52  4838.8  722.70
  4869.5  722.12  4875.4  721.20  4890.7  720.14  4919.7  718.73  4927.2  718.64
  4933.1  717.92  4963.7  717.08  4969.6  717.51  4985.0  716.76  4990.9  717.44
  5000.3  716.68  5006.2  717.03  5009.1  716.35  5021.9  716.26  5027.4  715.89
  5030.4  715.35  5030.6  714.85  5034.1  714.85  5034.4  715.35  5042.0  716.06
  5052.0  718.79  5062.0  719.68  5082.1  720.13  5122.2  722.28  5198.0  725.22
#Mann=3,-1,0
  4790.1    0.05       0  5030.4    0.04       0  5034.4    0.05       0
Bank Sta=5030.4,5034.4
Exp/Cntr=0.3,0.1

Chan Stop Cuts=-1