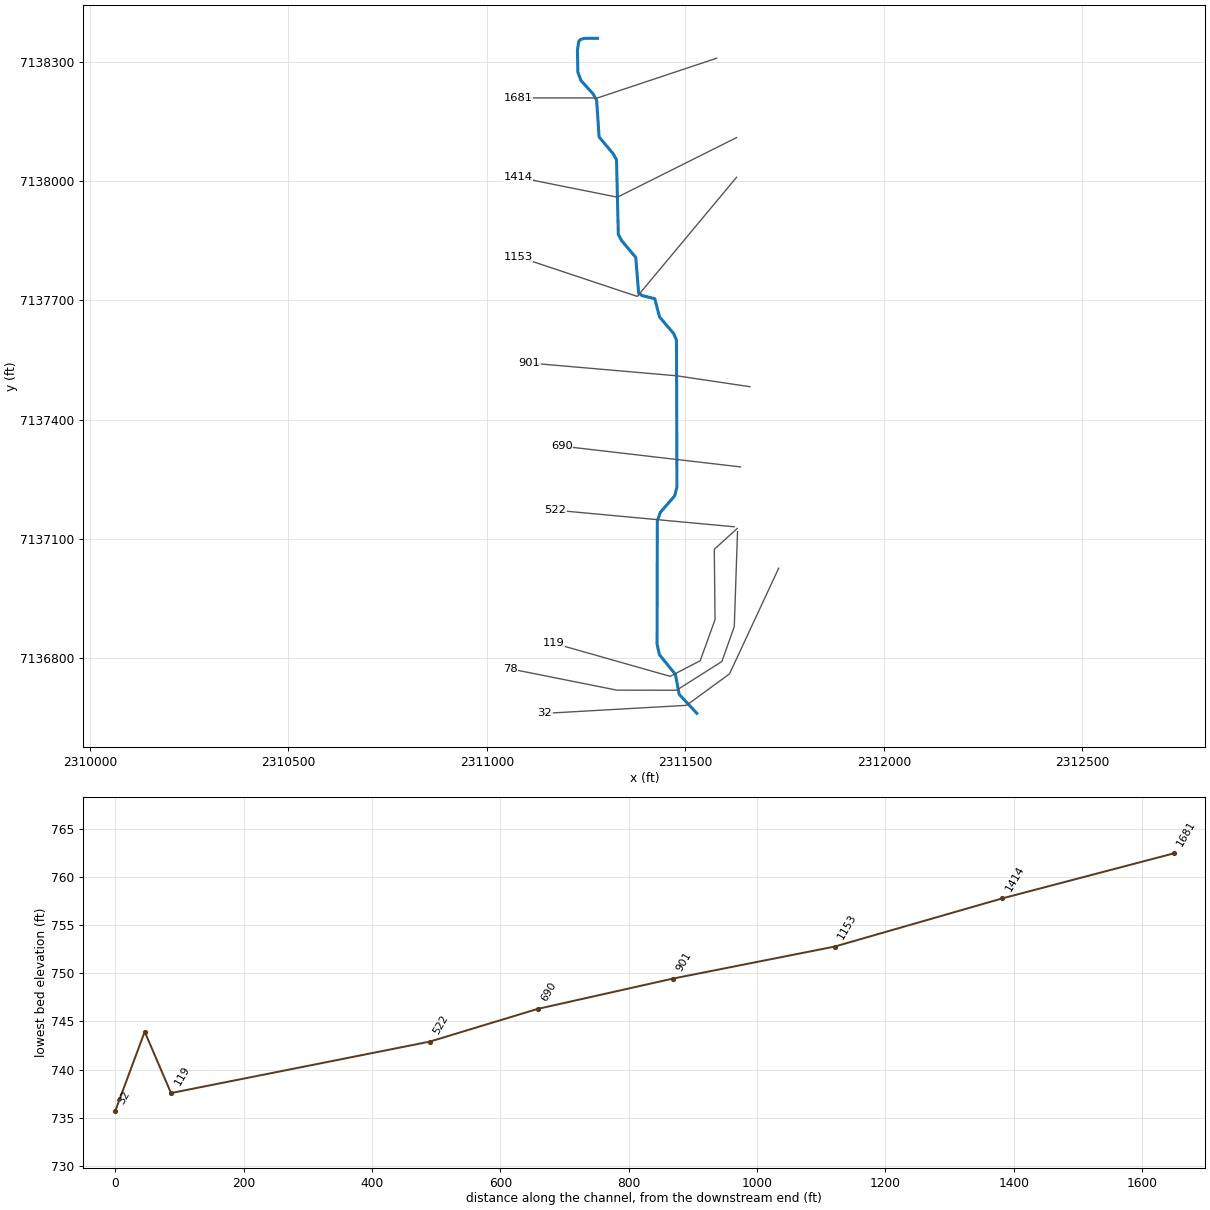
--- Denton Creek Tributary 40_2.prj (project) ---

Proj Title=Denton Creek Tributary 40_2 Base Level Engineering
Current Plan=p01
Default Exp/Contr=0.3,0.1
English Units
Geom File=g01
Flow File=f01
Plan File=p01
BEGIN DESCRIPTION:
Denton Creek Tributary 40_2
END DESCRIPTION:

--- Denton Creek Tributary 40_2.p01 (plan) ---

Plan Title=Multiple Run
Short Identifier=Multiple
Geom File=g01
Flow File=f01
Subcritical Flow
K Sum by GR= 0
Std Step Tol= 0.01
Critical Tol= 0.01
Num of Std Step Trials= 20
Max Error Tol= 0.3
Flow Tol Ratio= 0.001
Split Flow NTrial= 30
Split Flow Tol= 0.02
Split Flow Ratio= 0.02
Log Output Level= 0
Friction Slope Method= 1
Unsteady Friction Slope Method= 2
Unsteady Bridges Friction Slope Method= 1
Parabolic Critical Depth
Global Vel Dist=  1 , 1 , 1
Global Log Level= 0
CheckData=True
Encroach Param= -1, 0, 0, 0
BEGIN DESCRIPTION:
Multiple Run
END DESCRIPTION:

--- Denton Creek Tributary 40_2.f01 (steady flow) ---

Flow Title=Multiple
Number of Profiles=7
Profile Names=10-year,25-year,50-year,1pct_min,100-year,1pct_plu,500-year
River Rch & RM= Denton Creek Tri,Reach-1,1681
     190     242     283     165     329     657     446
River Rch & RM= Denton Creek Tri,Reach-1,32
     907    1274    1585     978    1952    3894    2967
Boundary for River Rch & Prof#=Denton Creek Tri,Reach-1,1
Up Type=0
Dn Type=3
Dn Slope=0.005
Boundary for River Rch & Prof#=Denton Creek Tri,Reach-1,2
Up Type=0
Dn Type=3
Dn Slope=0.005
Boundary for River Rch & Prof#=Denton Creek Tri,Reach-1,3
Up Type=0
Dn Type=3
Dn Slope=0.005
Boundary for River Rch & Prof#=Denton Creek Tri,Reach-1,4
Up Type=0
Dn Type=3
Dn Slope=0.005
Boundary for River Rch & Prof#=Denton Creek Tri,Reach-1,5
Up Type=0
Dn Type=3
Dn Slope=0.005
Boundary for River Rch & Prof#=Denton Creek Tri,Reach-1,6
Up Type=0
Dn Type=3
Dn Slope=0.005
Boundary for River Rch & Prof#=Denton Creek Tri,Reach-1,7
Up Type=0
Dn Type=3
Dn Slope=0.005

--- Denton Creek Tributary 40_2.g01 (geometry) ---

Geom Title=Existing Conditions

River Reach=Denton Creek Tri,Reach-1
Reach XY= 30
      2311279.00      7138360.00      2311246.99      7138360.08
      2311236.73      7138357.59      2311231.56      7138352.24
      2311228.33      7138330.23      2311229.32      7138275.33
      2311237.07      7138253.99      2311268.11      7138219.64
      2311276.65      7138204.03      2311282.86      7138111.60
      2311318.15      7138069.65      2311326.74      7138054.06
      2311331.26      7137865.93      2311339.85      7137850.35
      2311375.12      7137808.33      2311382.50      7137718.48
      2311391.12      7137712.16      2311422.98      7137704.21
      2311435.22      7137658.14      2311470.92      7137616.12
      2311477.81      7137599.52      2311478.93      7137230.03
      2311473.25      7137207.67      2311437.14      7137166.06
      2311429.52      7137144.78      2311428.79      7136834.91
      2311434.70      7136807.65      2311474.92      7136758.31
      2311484.67      7136707.63      2311529.00      7136660.00

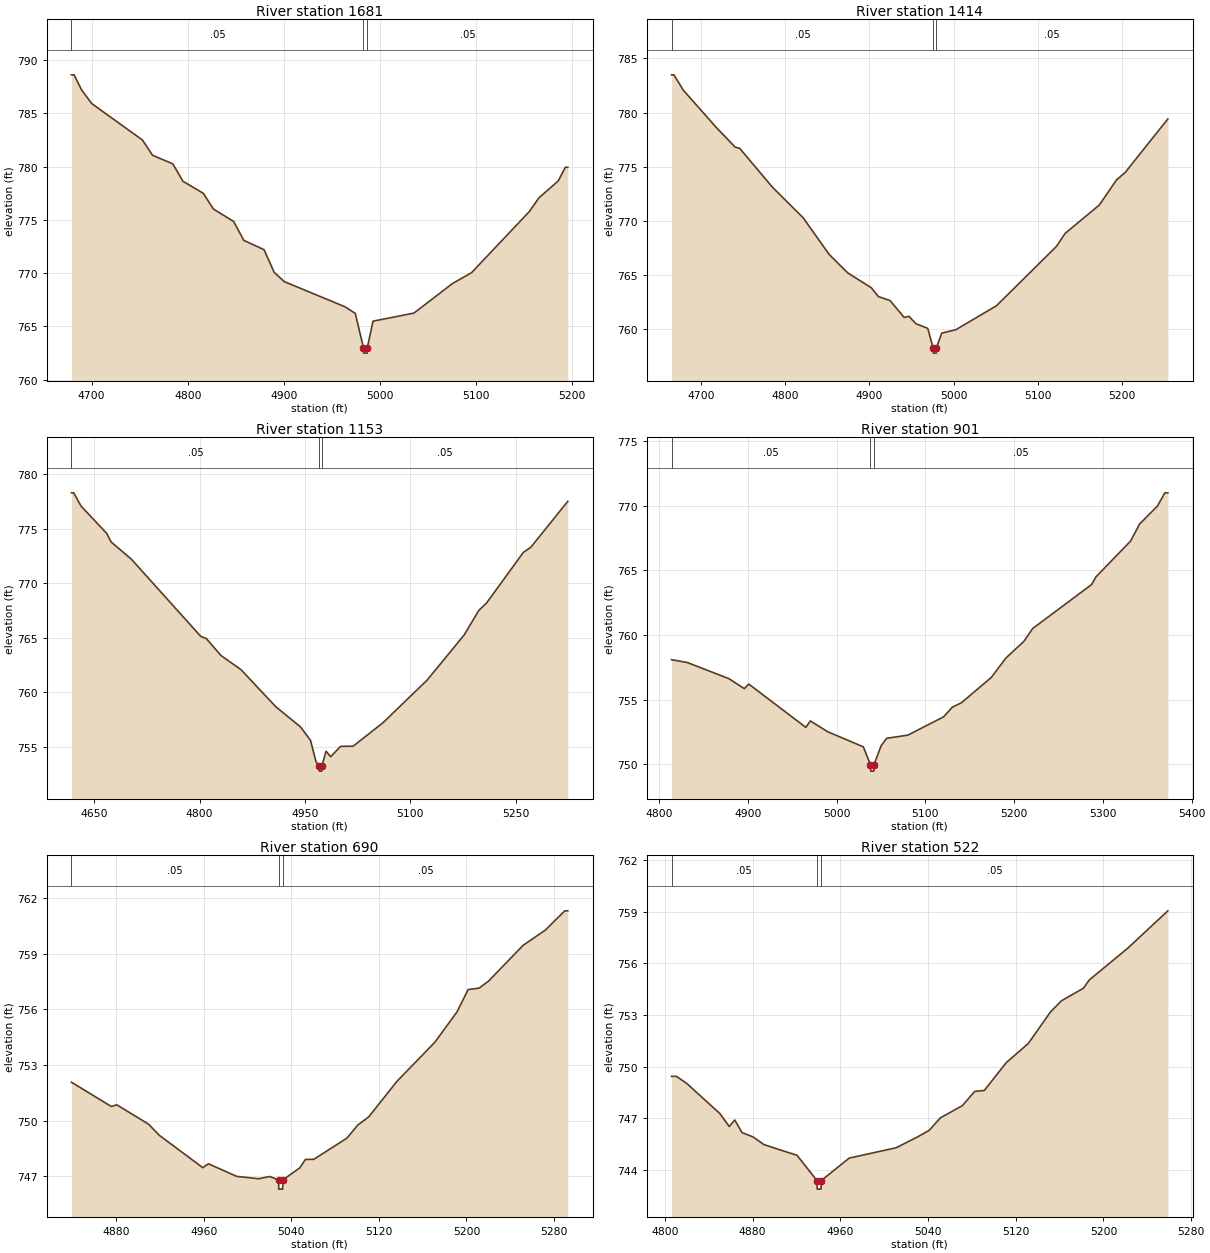
Type RM Length L Ch R = 1,1681,267,267,267
BEGIN DESCRIPTION:
Denton Creek Tributary 40_2 6.0
END DESCRIPTION:
XS GIS Cut Line= 3
      2311579.02      7138310.01      2311279.00      7138210.00
      2311079.05      7138210.00
#Sta/Elev= 30
  4679.1  788.61  4681.8  788.61  4689.7  787.18  4700.2  785.91  4752.9  782.49
  4763.4  781.06  4784.5  780.25  4795.1  778.61  4816.2  777.49  4826.7  776.01
  4847.8  774.84  4858.3  773.07  4879.4  772.19  4889.9  770.07  4900.5  769.19
  4963.7  766.83  4974.3  766.21  4982.8  762.98  4983.1  762.48  4986.6  762.48
  4986.8  762.98  4992.7  765.48  5035.3  766.24  5075.3  769.01  5095.3  770.04
  5155.3  775.77  5165.3  777.06  5185.3  778.64  5192.8  779.93  5195.3  779.93
#Mann=3,-1,0
  4679.1    0.05       0  4982.8   0.033       0  4986.8    0.05       0
Bank Sta=4982.8,4986.8
Exp/Cntr=0.3,0.1

Type RM Length L Ch R = 1,1414,261,261,261
BEGIN DESCRIPTION:
Denton Creek Tributary 40_2 5.0
END DESCRIPTION:
XS GIS Cut Line= 3
      2311628.99      7138109.99      2311329.00      7137960.00
      2311079.05      7138009.99
#Sta/Elev= 30
  4664.6  783.48  4667.4  783.48  4678.6  782.06  4717.7  778.63  4740.1  776.82
  4745.6  776.70  4784.8  773.09  4821.1  770.29  4851.9  766.92  4874.2  765.20
  4902.2  763.83  4910.6  763.02  4924.5  762.65  4941.3  761.09  4946.9  761.20
  4955.3  760.51  4969.3  760.09  4975.6  758.30  4975.9  757.80  4979.4  757.80
  4979.6  758.30  4986.0  759.65  5002.5  759.95  5051.0  762.17  5122.4  767.65
  5132.6  768.84  5173.4  771.47  5193.8  773.78  5204.0  774.46  5254.9  779.41
#Mann=3,-1,0
  4664.6    0.05       0  4975.6   0.033       0  4979.6    0.05       0
Bank Sta=4975.6,4979.6
Exp/Cntr=0.3,0.1

Type RM Length L Ch R = 1,1153,252,252,252
BEGIN DESCRIPTION:
Denton Creek Tributary 40_2 4.0
END DESCRIPTION:
XS GIS Cut Line= 3
      2311628.99      7138009.98      2311379.00      7137710.00
      2311079.02      7137809.99
#Sta/Elev= 30
  4617.6  778.27  4620.8  778.27  4631.2  777.06  4667.7  774.56  4674.2  773.76
  4702.8  772.20  4801.8  765.12  4809.6  764.93  4830.4  763.38  4859.0  762.08
  4908.5  758.69  4943.7  756.84  4958.0  755.61  4965.8  753.65  4970.3  753.29
  4970.5  752.79  4974.0  752.79  4974.3  753.29  4980.1  754.61  4986.6  754.11
  5000.9  755.06  5018.6  755.07  5060.8  757.20  5124.0  761.12  5176.7  765.25
  5197.8  767.52  5208.4  768.16  5261.1  772.82  5271.6  773.28  5324.3  777.49
#Mann=3,-1,0
  4617.6    0.05       0  4970.3   0.033       0  4974.3    0.05       0
Bank Sta=4970.3,4974.3
Exp/Cntr=0.3,0.1

Type RM Length L Ch R = 1,901,211,211,211
BEGIN DESCRIPTION:
Denton Creek Tributary 40_2 3.0
END DESCRIPTION:
XS GIS Cut Line= 3
      2311662.85      7137482.60      2311479.00      7137510.00
      2311107.28      7137542.34
#Sta/Elev= 30
  4814.2  758.09  4831.9  757.87  4878.8  756.62  4896.1  755.85  4901.2  756.20
  4965.4  752.85  4970.5  753.35  4990.0  752.51  5030.2  751.34  5038.2  749.96
  5038.5  749.46  5042.0  749.46  5042.2  749.96  5050.3  751.44  5056.5  752.00
  5080.4  752.25  5120.5  753.66  5130.6  754.42  5140.6  754.75  5174.4  756.72
  5190.8  758.22  5210.9  759.50  5220.9  760.50  5287.3  763.91  5292.3  764.51
  5331.3  767.28  5341.4  768.60  5361.4  769.98  5369.8  771.01  5373.2  771.01
#Mann=3,-1,0
  4814.2    0.05       0  5038.2   0.033       0  5042.2    0.05       0
Bank Sta=5038.2,5042.2
Exp/Cntr=0.3,0.1

Type RM Length L Ch R = 1,690,168,168,168
BEGIN DESCRIPTION:
Mapping XS a0c6cd68
END DESCRIPTION:
XS GIS Cut Line= 2
      2311638.78      7137280.64      2311188.61      7137332.98
#Sta/Elev= 30
  4839.3  752.07  4875.7  750.76  4880.7  750.85  4909.6  749.81  4919.6  749.20
  4959.2  747.46  4964.3  747.67  4990.1  746.99  5010.2  746.86  5020.3  746.98
  5028.4  746.80  5028.6  746.30  5032.1  746.30  5032.4  746.80  5047.8  747.45
  5052.9  747.90  5060.6  747.91  5090.8  749.05  5100.8  749.76  5110.9  750.21
  5136.4  752.11  5171.3  754.24  5191.4  755.87  5201.5  757.07  5211.6  757.15
  5220.0  757.52  5251.8  759.46  5272.0  760.28  5289.8  761.32  5292.5  761.32
#Mann=3,-1,0
  4839.3    0.05       0  5028.4   0.033       0  5032.4    0.05       0
Bank Sta=5028.4,5032.4
Exp/Cntr=0.3,0.1

Type RM Length L Ch R = 1,522,403,403,403
BEGIN DESCRIPTION:
Mapping XS 55c4addf
END DESCRIPTION:
XS GIS Cut Line= 2
      2311622.93      7137129.83      2311172.36      7137171.60
#Sta/Elev= 30
  4806.2  749.44  4810.7  749.44  4820.2  749.02  4850.3  747.28  4858.8  746.53
  4863.8  746.91  4870.4  746.18  4880.4  745.93  4890.5  745.48  4920.6  744.86
  4938.7  743.40  4939.0  742.90  4942.5  742.90  4942.7  743.40  4968.2  744.70
  5011.0  745.30  5031.1  745.95  5041.1  746.31  5051.2  747.03  5071.3  747.74
  5082.6  748.57  5091.3  748.62  5111.4  750.24  5131.5  751.35  5151.6  753.17
  5161.6  753.82  5181.7  754.55  5187.0  755.03  5221.9  756.86  5258.7  759.04
#Mann=3,-1,0
  4806.2    0.05       0  4938.7   0.033       0  4942.7    0.05       0
Bank Sta=4938.7,4942.7
Exp/Cntr=0.3,0.1

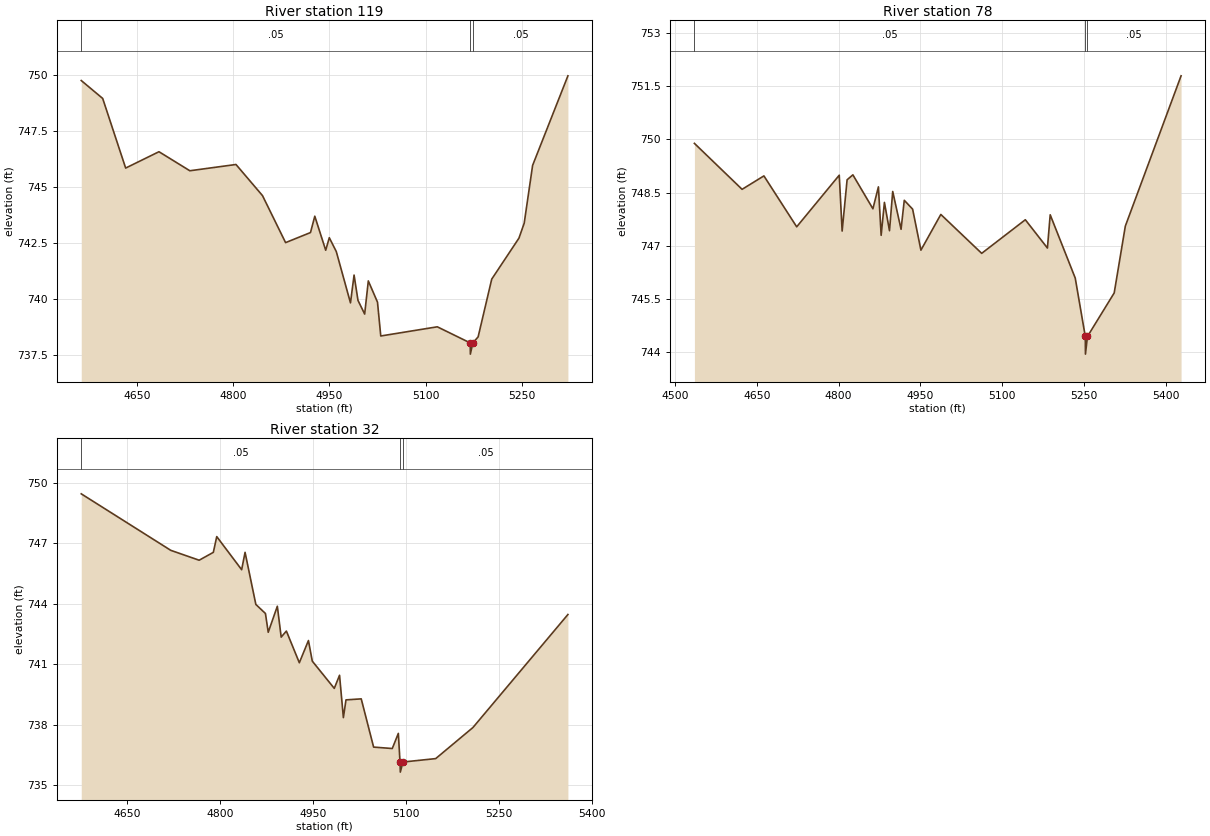
Type RM Length L Ch R = 1,119,41,41,41
BEGIN DESCRIPTION:
Mapping XS c98b8f76
END DESCRIPTION:
XS GIS Cut Line= 6
      2311630.75      7137125.62      2311572.99      7137072.95
      2311574.89      7136895.66      2311537.44      7136792.35
      2311461.80      7136753.10      2311167.10      7136836.75
#Sta/Elev= 30
  4563.5  749.77  4596.9  748.97  4632.7  745.86  4684.6  746.59  4732.7  745.74
  4804.6  746.02  4845.9  744.63  4881.9  742.53  4920.7  742.98  4927.4  743.71
  4944.4  742.19  4950.0  742.75  4960.9  742.13  4983.0  739.84  4988.6  741.08
  4994.7  739.95  5005.1  739.34  5010.8  740.82  5025.1  739.87  5030.2  738.36
  5118.3  738.77  5169.6  738.05  5169.8  737.55  5173.6  738.05  5181.9  738.32
  5203.1  740.90  5245.5  742.73  5253.7  743.40  5266.8  745.98  5321.8  749.98
#Mann=3,-1,0
  4563.5    0.05       0  5169.6   0.033       0  5173.6    0.05       0
Bank Sta=5169.6,5173.6
Exp/Cntr=0.3,0.1

Type RM Length L Ch R = 1,78,46,46,46
BEGIN DESCRIPTION:
Denton Creek Tributary 40_2 2.0
END DESCRIPTION:
XS GIS Cut Line= 6
      2311631.53      7137117.37      2311623.35      7136878.33
      2311592.10      7136790.43      2311477.90      7136718.06
      2311327.67      7136718.28      2311058.78      7136771.98
#Sta/Elev= 30
  4535.7  749.89  4623.1  748.59  4663.1  748.97  4723.2  747.53  4801.2  748.99
  4806.5  747.41  4815.6  748.86  4826.2  749.00  4862.9  748.04  4873.0  748.66
  4878.0  747.29  4884.0  748.22  4893.3  747.42  4899.2  748.53  4914.5  747.46
  4920.4  748.28  4935.7  748.03  4950.9  746.87  4987.4  747.88  5062.3  746.78
  5142.3  747.73  5182.8  746.93  5187.9  747.87  5233.8  746.08  5252.2  744.43
  5252.5  743.93  5256.2  744.43  5305.2  745.66  5325.6  747.55  5427.8  751.80
#Mann=3,-1,0
  4535.7    0.05       0  5252.2   0.033       0  5256.2    0.05       0
Bank Sta=5252.2,5256.2
Exp/Cntr=0.3,0.1

Type RM Length L Ch R = 1,32,0,0,0
BEGIN DESCRIPTION:
Denton Creek Tributary 40_2 1.0
END DESCRIPTION:
XS GIS Cut Line= 4
      2311735.23      7137025.50      2311611.32      7136759.25
      2311502.83      7136680.02      2311145.92      7136659.79
#Sta/Elev= 30
  4575.8  749.45  4720.3  746.65  4766.1  746.16  4789.0  746.55  4794.5  747.33
  4834.7  745.69  4840.2  746.55  4857.6  743.97  4873.1  743.52  4877.6  742.59
  4892.3  743.88  4898.5  742.35  4906.9  742.65  4927.8  741.08  4942.5  742.18
  4948.7  741.16  4984.2  739.81  4992.7  740.46  4998.9  738.36  5003.1  739.24
  5027.7  739.29  5047.7  736.90  5077.8  736.83  5087.6  737.58  5090.3  736.16
  5090.8  735.66  5095.0  736.16  5147.9  736.33  5208.0  737.87  5361.3  743.47
#Mann=3,-1,0
  4575.8    0.05       0  5090.3   0.033       0  5095.0    0.05       0
Bank Sta=5090.3,5095
Exp/Cntr=0.3,0.1

Chan Stop Cuts=-1