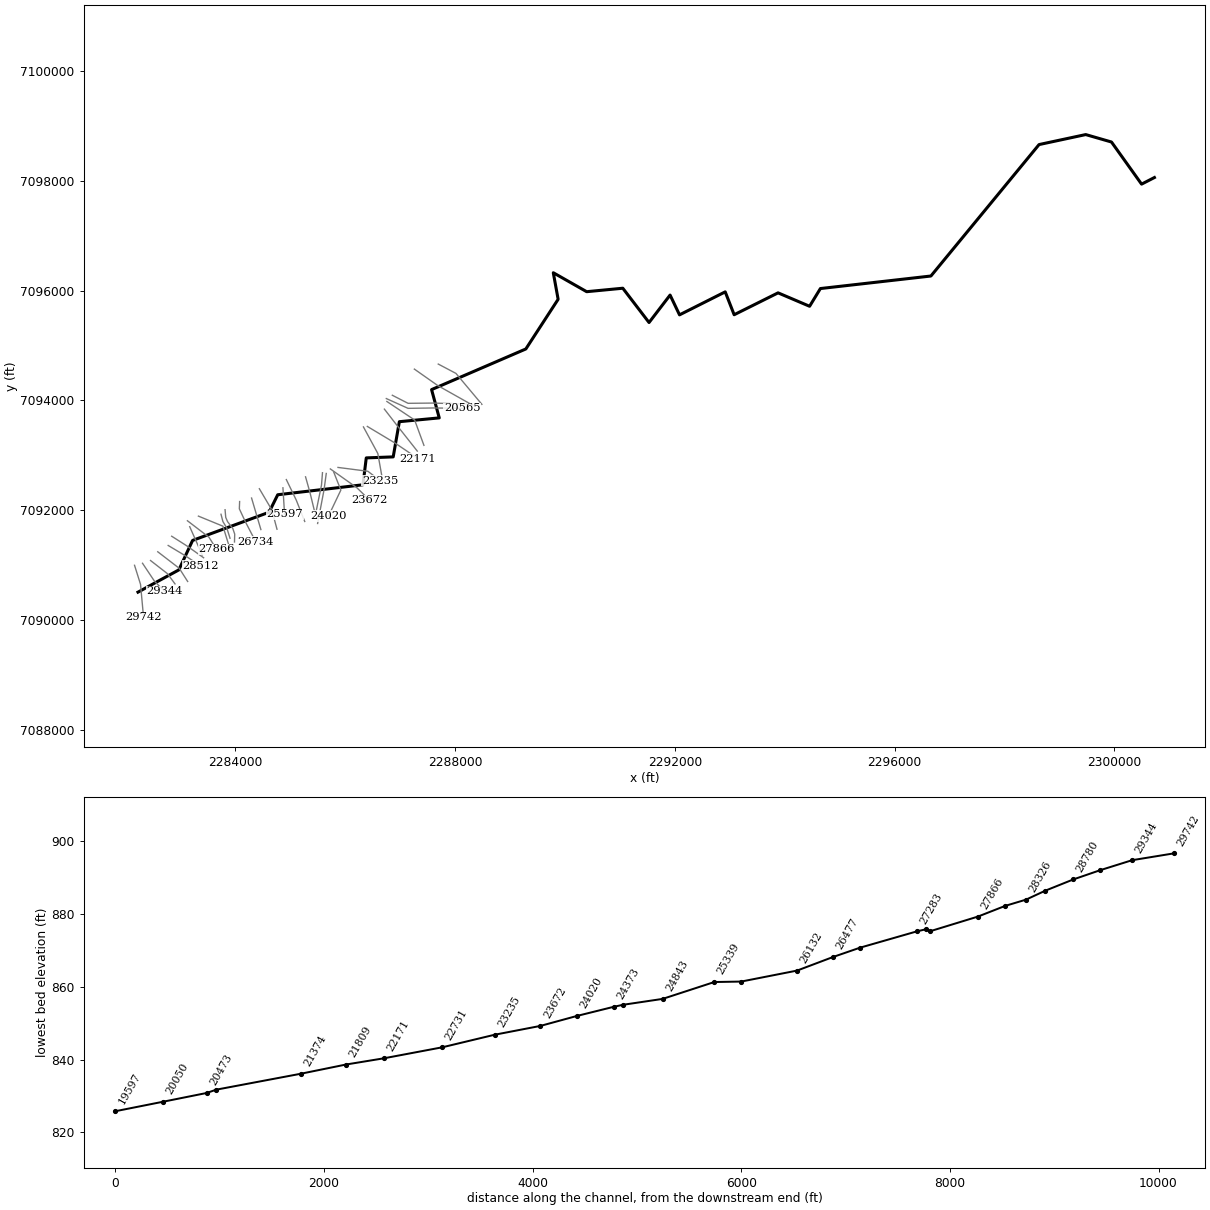
--- Hackberry Creek.prj (project) ---

Proj Title=Hackberry Creek Base Level Engineering
Current Plan=p01
Default Exp/Contr=0.3,0.1
English Units
Geom File=g01
Flow File=f01
Plan File=p01
Y Axis Title=Elevation
X Axis Title(PF)=Main Channel Distance
X Axis Title(XS)=Station
BEGIN DESCRIPTION:
Hackberry Creek
END DESCRIPTION:
DSS Export Rating Curves= 0
DSS Export Rating Curve Sorted= 0
DSS Export Volume Flow Curves= 0
DXF OffsetX= 0
DXF OffsetY= 0
DXF ScaleX= 1
DXF ScaleY= 10

--- Hackberry Creek.p01 (plan) ---

Plan Title=Multiple Run
Short Identifier=Multiple
Geom File=g01
Flow File=f01
Subcritical Flow
K Sum by GR= 0
Std Step Tol= 0.01
Critical Tol= 0.01
Num of Std Step Trials= 20
Max Error Tol= 0.3
Flow Tol Ratio= 0.001
Split Flow NTrial= 30
Split Flow Tol= 0.02
Split Flow Ratio= 0.02
Log Output Level= 0
Friction Slope Method= 1
Unsteady Friction Slope Method= 2
Unsteady Bridges Friction Slope Method= 1
Parabolic Critical Depth
Global Vel Dist=  1 , 1 , 1
Global Log Level= 0
CheckData=True
Encroach Param= -1, 0, 0, 0
BEGIN DESCRIPTION:
Multiple Run
END DESCRIPTION:

--- Hackberry Creek.f01 (steady flow) ---

Flow Title=Multiple
Program Version=4.10
Number of Profiles= 7
Profile Names=10-year,25-year,50-year,1pct_min,100-year,1pct_plu,500-year
River Rch & RM=Hackberry Creek,Reach-1         ,29742
     415     560     678     409     817    1629    1184
River Rch & RM=Hackberry Creek,Reach-1         ,26734
     549     753     922     562    1121    2236    1657
River Rch & RM=Hackberry Creek,Reach-1         ,23672
     880    1242    1550     960    1915    3820    2930
River Rch & RM=Hackberry Creek,Reach-1         ,22731
    1157    1653    2078    1296    2585    5158    4011
River Rch & RM=Hackberry Creek,Reach-1         ,17620
    1444    2084    2640    1656    3304    6592    5193
River Rch & RM=Hackberry Creek,Reach-1         ,15531
    1579    2285    2898    1820    3632    7246    5721
River Rch & RM=Hackberry Creek,Reach-1         ,12203
    1623    2349    2979    1870    3731    7445    5876
River Rch & RM=Hackberry Creek,Reach-1         ,9475
    1701    2465    3130    1967    3925    7831    6192
River Rch & RM=Hackberry Creek,Reach-1         ,7645
    2647    3911    5030    3197    6379   12728   10300
River Rch & RM=Hackberry Creek,Reach-1         ,3484
    2808    4157    5354    3408    6799   13567   11007
River Rch & RM=Hackberry Creek,Reach-1         ,2652
    2998    4445    5732    3652    7286   14538   11817
Boundary for River Rch & Prof#=Hackberry Creek,Reach-1         , 1
Up Type= 0
Dn Type= 3
Dn Slope=0.00386
Boundary for River Rch & Prof#=Hackberry Creek,Reach-1         , 2
Up Type= 0
Dn Type= 3
Dn Slope=0.00386
Boundary for River Rch & Prof#=Hackberry Creek,Reach-1         , 3
Up Type= 0
Dn Type= 3
Dn Slope=0.00386
Boundary for River Rch & Prof#=Hackberry Creek,Reach-1         , 4
Up Type= 0
Dn Type= 3
Dn Slope=0.00386
Boundary for River Rch & Prof#=Hackberry Creek,Reach-1         , 5
Up Type= 0
Dn Type= 3
Dn Slope=0.00386
Boundary for River Rch & Prof#=Hackberry Creek,Reach-1         , 6
Up Type= 0
Dn Type= 3
Dn Slope=0.00386
Boundary for River Rch & Prof#=Hackberry Creek,Reach-1         , 7
Up Type= 0
Dn Type= 3
Dn Slope=0.00386
DSS Import GetInterval= 0
DSS Import GetPeak= 0
DSS Import FillOption= 0

--- Hackberry Creek.g01 (geometry) ---

Geom Title=Existing Conditions

River Reach=Hackberry Creek,Reach-1
Reach XY= 30
      2282229.00      7090510.00      2282973.42      7090915.58
      2283222.94      7091451.86      2284614.59      7091964.69
      2284772.75      7092283.58      2286323.83      7092465.41
      2286383.99      7092954.73      2286874.35      7092973.05
      2286986.28      7093614.14      2287712.28      7093683.10
      2287572.76      7094198.18      2289288.41      7094938.29
      2289876.09      7095842.91      2289787.94      7096326.54
      2290395.27      7095981.21      2291053.17      7096044.24
      2291530.71      7095419.70      2291913.67      7095919.85
      2292085.57      7095559.27      2292917.21      7095978.01
      2293079.85      7095561.50      2293879.00      7095960.00
      2294452.83      7095715.63      2294649.51      7096038.38
      2296660.90      7096266.63      2298629.00      7098660.00
      2299478.49      7098842.09      2299947.49      7098706.67
      2300495.13      7097939.64      2300729.00      7098060.00

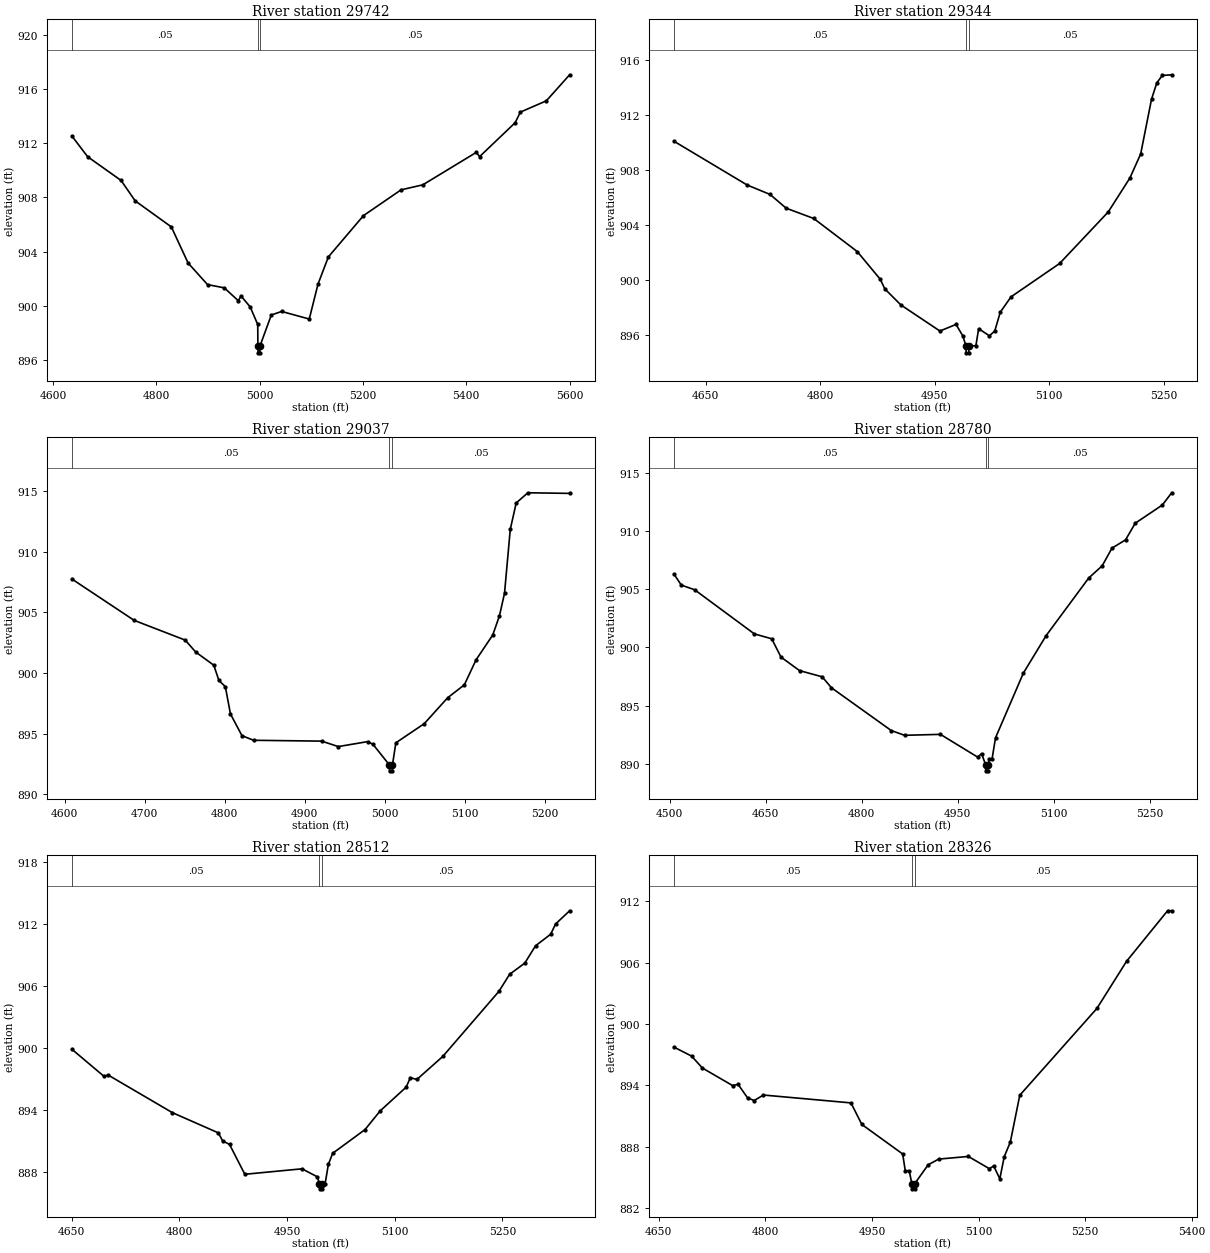
Type RM Length L Ch R = 1,29742,398,398,398
BEGIN DESCRIPTION:
Hackberry Creek 52.0
END DESCRIPTION:
XS GIS Cut Line= 3
      2282166.39      7090999.13      2282275.39      7090652.56
      2282330.24      7090055.08
#Sta/Elev= 30
  4636.7  912.53  4667.3  911.00  4732.0  909.25  4759.2  907.75  4829.2  905.83
  4861.6  903.17  4899.2  901.58  4931.6  901.34  4958.8  900.39  4964.0  900.74
  4981.7  899.94  4996.4  898.64  4996.7  897.05  4997.0  896.55  5000.5  896.55
  5000.7  897.05  5022.7  899.34  5042.7  899.60  5096.1  899.04  5113.0  901.61
  5133.1  903.62  5201.0  906.66  5273.7  908.56  5315.9  908.93  5419.3  911.32
  5425.8  911.01  5494.6  913.51  5504.7  914.29  5554.9  915.12  5600.0  917.04
#Mann=3,-1,0
  4636.7    0.05       0  4996.7   0.033       0  5000.7    0.05       0
Bank Sta=4996.7,5000.7
Exp/Cntr=0.3,0.1

Type RM Length L Ch R = 1,29344,307,307,307
BEGIN DESCRIPTION:
Hackberry Creek 51.0
END DESCRIPTION:
XS GIS Cut Line= 3
      2282311.77      7091036.06      2282529.00      7090710.00
      2282711.82      7090525.41
#Sta/Elev= 30
  4608.6  910.11  4704.4  906.92  4734.5  906.23  4755.5  905.23  4791.6  904.48
  4848.6  902.07  4878.7  900.05  4884.7  899.35  4905.7  898.18  4956.8  896.28
  4977.9  896.76  4986.9  895.91  4990.9  895.19  4991.1  894.69  4994.6  894.69
  4994.9  895.19  5003.9  895.21  5007.5  896.45  5021.6  895.93  5028.6  896.28
  5035.8  897.65  5049.9  898.77  5113.5  901.20  5177.2  904.96  5205.5  907.43
  5219.6  909.18  5233.8  913.17  5240.8  914.37  5247.9  914.90  5260.2  914.95
#Mann=3,-1,0
  4608.6    0.05       0  4990.9   0.033       0  4994.9    0.05       0
Bank Sta=4990.9,4994.9
Exp/Cntr=0.3,0.1

Type RM Length L Ch R = 1,29037,257,257,257
BEGIN DESCRIPTION:
Hackberry Creek 50.0
END DESCRIPTION:
XS GIS Cut Line= 3
      2282457.15      7091086.34      2282765.78      7090846.27
      2282902.97      7090660.30
#Sta/Elev= 30
  4609.0  907.76  4686.8  904.35  4750.7  902.72  4763.7  901.74  4786.4  900.65
  4792.7  899.40  4800.8  898.88  4807.2  896.63  4821.6  894.84  4836.1  894.46
  4921.2  894.39  4942.0  893.94  4978.7  894.35  4985.4  894.12  5005.7  892.44
  5006.0  891.94  5009.5  891.94  5009.7  892.44  5013.9  894.25  5049.4  895.83
  5078.7  897.97  5099.5  899.03  5114.2  901.10  5135.0  903.14  5143.4  904.73
  5149.7  906.58  5156.9  911.85  5164.3  914.03  5178.9  914.87  5231.1  914.82
#Mann=3,-1,0
  4609.0    0.05       0  5005.7   0.033       0  5009.7    0.05       0
Bank Sta=5005.7,5009.7
Exp/Cntr=0.3,0.1

Type RM Length L Ch R = 1,28780,268,268,268
BEGIN DESCRIPTION:
Hackberry Creek 49.0
END DESCRIPTION:
XS GIS Cut Line= 3
      2282589.07      7091245.21      2282980.16      7090944.23
      2283133.15      7090704.72
#Sta/Elev= 30
  4506.5  906.30  4518.0  905.35  4538.8  904.95  4632.2  901.16  4659.3  900.74
  4673.8  899.17  4702.8  898.01  4738.1  897.48  4752.6  896.54  4846.0  892.87
  4866.8  892.46  4922.9  892.54  4981.0  890.59  4987.3  890.89  4993.5  889.91
  4993.7  889.41  4997.2  889.41  4997.5  889.91  4999.4  890.45  5003.6  890.45
  5009.0  892.25  5052.5  897.80  5088.1  901.02  5154.5  905.95  5175.7  907.01
  5190.9  908.52  5212.1  909.23  5227.3  910.66  5269.6  912.22  5284.2  913.27
#Mann=3,-1,0
  4506.5    0.05       0  4993.5   0.033       0  4997.5    0.05       0
Bank Sta=4993.5,4997.5
Exp/Cntr=0.3,0.1

Type RM Length L Ch R = 1,28512,186,186,186
BEGIN DESCRIPTION:
Hackberry Creek 48.0
END DESCRIPTION:
XS GIS Cut Line= 3
      2282778.96      7091360.02      2283078.91      7091180.04
      2283365.36      7090989.93
#Sta/Elev= 30
  4650.2  899.85  4694.9  897.23  4700.8  897.35  4790.2  893.71  4854.3  891.75
  4860.2  890.98  4869.9  890.63  4891.2  887.74  4970.9  888.27  4992.3  887.49
  4995.1  886.83  4995.4  886.33  4998.9  886.33  4999.1  886.83  5003.1  886.83
  5007.6  888.70  5013.6  889.77  5058.7  892.07  5079.8  893.88  5115.9  896.17
  5121.9  897.10  5130.9  896.92  5167.0  899.15  5245.2  905.45  5260.2  907.11
  5281.3  908.19  5296.3  909.87  5317.4  910.99  5324.2  911.98  5343.8  913.26
#Mann=3,-1,0
  4650.2    0.05       0  4995.1   0.033       0  4999.1    0.05       0
Bank Sta=4995.1,4999.1
Exp/Cntr=0.3,0.1

Type RM Length L Ch R = 1,28326,199,199,199
BEGIN DESCRIPTION:
Hackberry Creek 47.0
END DESCRIPTION:
XS GIS Cut Line= 3
      2282842.74      7091528.21      2283120.08      7091351.59
      2283423.49      7091136.70
#Sta/Elev= 30
  4671.2  897.73  4696.1  896.85  4711.3  895.68  4753.7  893.97  4761.6  894.08
  4774.8  892.77  4784.1  892.50  4797.2  893.04  4920.4  892.27  4935.7  890.16
  4993.2  887.27  4996.8  885.63  5002.4  885.63  5006.1  884.36  5006.4  883.86
  5009.9  883.86  5010.1  884.36  5029.0  886.21  5043.8  886.77  5085.6  887.03
  5115.2  885.83  5121.3  886.10  5129.9  884.84  5136.1  887.00  5144.7  888.44
  5158.0  893.02  5266.5  901.51  5308.3  906.13  5366.0  911.07  5371.8  911.07
#Mann=3,-1,0
  4671.2    0.05       0  5006.1   0.033       0  5010.1    0.05       0
Bank Sta=5006.1,5010.1
Exp/Cntr=0.3,0.1

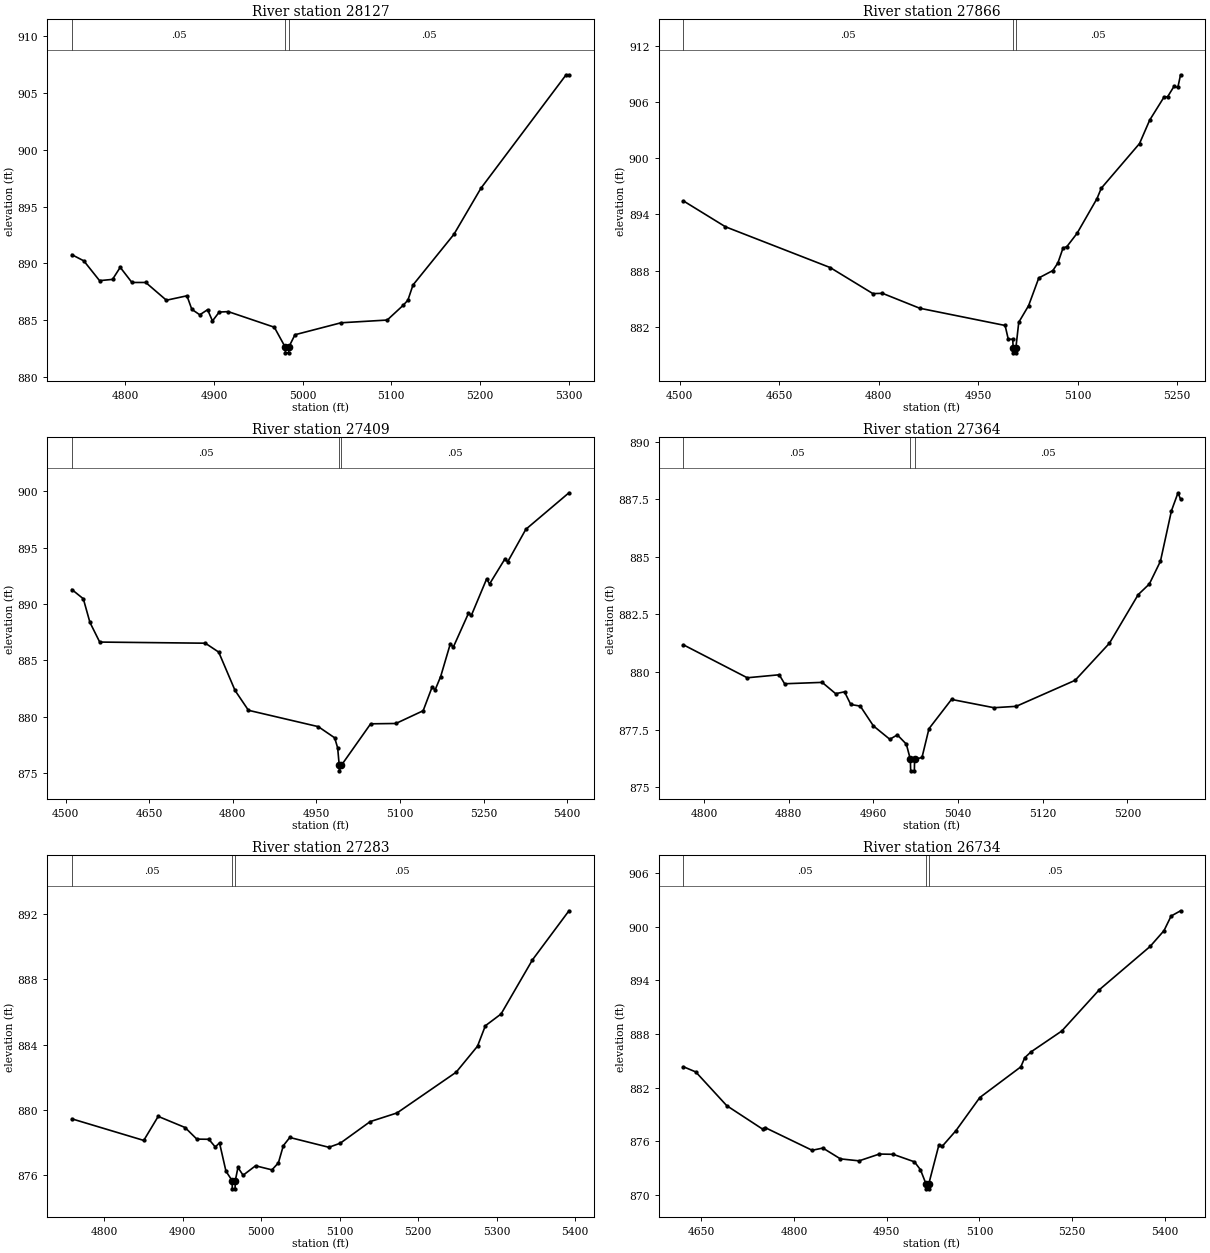
Type RM Length L Ch R = 1,28127,261,261,261
BEGIN DESCRIPTION:
Mapping XS a7765281
END DESCRIPTION:
XS GIS Cut Line= 2
      2283170.57      7091702.00      2283397.81      7091189.08
#Sta/Elev= 30
  4739.5  890.77  4753.0  890.23  4770.8  888.49  4785.4  888.60  4794.1  889.66
  4807.3  888.33  4822.9  888.33  4846.2  886.77  4869.4  887.16  4874.9  885.97
  4883.9  885.49  4892.7  885.94  4898.2  884.95  4905.8  885.73  4916.0  885.77
  4968.0  884.40  4980.3  882.65  4980.6  882.15  4984.1  882.15  4984.3  882.65
  4991.3  883.74  5043.3  884.79  5095.4  885.03  5113.2  886.31  5118.7  886.77
  5124.5  888.11  5170.7  892.56  5201.1  896.60  5297.3  906.57  5300.5  906.57
#Mann=3,-1,0
  4739.5    0.05       0  4980.3   0.033       0  4984.3    0.05       0
Bank Sta=4980.3,4984.3
Exp/Cntr=0.3,0.1

Type RM Length L Ch R = 1,27866,457,457,457
BEGIN DESCRIPTION:
Hackberry Creek 46.0
END DESCRIPTION:
XS GIS Cut Line= 3
      2283128.99      7091810.01      2283521.56      7091509.64
      2283657.31      7091293.30
#Sta/Elev= 30
  4505.7  895.43  4569.1  892.67  4727.0  888.32  4791.4  885.54  4805.9  885.57
  4862.0  883.98  4990.8  882.14  4995.6  880.67  5002.3  880.67  5003.0  879.72
  5003.3  879.22  5006.8  879.22  5007.0  879.72  5011.4  882.48  5026.2  884.25
  5041.6  887.21  5062.8  888.00  5070.4  888.81  5078.1  890.39  5084.0  890.56
  5099.3  891.97  5129.4  895.68  5135.8  896.78  5193.5  901.55  5208.9  904.06
  5230.1  906.47  5236.0  906.56  5245.4  907.64  5251.3  907.54  5255.4  908.89
#Mann=3,-1,0
  4505.7    0.05       0  5003.0   0.033       0  5007.0    0.05       0
Bank Sta=5003,5007
Exp/Cntr=0.3,0.1

Type RM Length L Ch R = 1,27409,45,45,45
BEGIN DESCRIPTION:
Hackberry Creek 45.0
END DESCRIPTION:
XS GIS Cut Line= 3
      2283328.96      7091894.47      2283775.12      7091711.41
      2283896.67      7091320.21
#Sta/Elev= 30
  4511.2  891.29  4531.8  890.47  4543.7  888.37  4561.2  886.63  4750.7  886.53
  4774.7  885.74  4804.0  882.34  4828.0  880.58  4953.3  879.13  4982.7  878.14
  4988.1  877.25  4990.9  875.71  4991.1  875.21  4994.9  875.71  5047.3  879.38
  5092.6  879.41  5141.5  880.54  5157.7  882.66  5162.9  882.38  5172.9  883.57
  5190.3  886.49  5195.5  886.17  5222.8  889.18  5228.1  889.01  5255.4  892.23
  5260.6  891.78  5287.9  893.98  5293.2  893.75  5325.7  896.63  5403.1  899.87
#Mann=3,-1,0
  4511.2    0.05       0  4990.9    0.04       0  4994.9    0.05       0
Bank Sta=4990.9,4994.9
Exp/Cntr=0.3,0.1

Type RM Length L Ch R = 1,27364,81,81,81
BEGIN DESCRIPTION:
Mapping XS 6adca1bf
END DESCRIPTION:
XS GIS Cut Line= 4
      2283740.24      7091928.35      2283774.33      7091796.62
      2283846.54      7091676.12      2283904.42      7091491.84
#Sta/Elev= 30
  4780.6  881.18  4840.9  879.75  4871.1  879.88  4876.2  879.49  4911.7  879.55
  4924.4  879.06  4932.8  879.14  4938.7  878.59  4947.7  878.52  4960.1  877.66
  4975.6  877.08  4982.7  877.27  4991.2  876.87  4995.0  876.21  4995.3  875.71
  4998.8  875.71  4999.0  876.21  5006.0  876.29  5012.6  877.54  5033.9  878.81
  5074.0  878.45  5095.0  878.51  5150.7  879.64  5183.1  881.25  5210.3  883.36
  5220.8  883.82  5231.3  884.81  5241.7  887.00  5247.9  887.78  5250.3  887.50
#Mann=3,-1,0
  4780.6    0.05       0  4995.0    0.04       0  4999.0    0.05       0
Bank Sta=4995,4999
Exp/Cntr=0.3,0.1

Type RM Length L Ch R = 1,27283,549,549,549
BEGIN DESCRIPTION:
Mapping XS 4cb78b10
END DESCRIPTION:
XS GIS Cut Line= 6
      2283814.11      7092011.26      2283826.42      7091870.72
      2283859.96      7091793.13      2283954.05      7091670.69
      2283989.67      7091567.15      2283985.67      7091423.52
#Sta/Elev= 30
  4758.9  879.46  4850.5  878.14  4868.9  879.61  4903.1  878.93  4918.1  878.22
  4933.4  878.21  4941.6  877.74  4947.0  877.99  4955.2  876.26  4963.1  875.68
  4963.3  875.18  4966.8  875.18  4967.1  875.68  4970.5  876.49  4977.0  876.01
  4992.9  876.59  5013.8  876.34  5022.0  876.77  5028.3  877.82  5036.5  878.32
  5086.3  877.72  5100.8  877.97  5138.9  879.29  5173.1  879.82  5248.4  882.31
  5275.6  883.90  5285.6  885.15  5305.6  885.87  5345.6  889.18  5392.1  892.18
#Mann=3,-1,0
  4758.9    0.05       0  4963.1    0.04       0  4967.1    0.05       0
Bank Sta=4963.1,4967.1
Exp/Cntr=0.3,0.1

Type RM Length L Ch R = 1,26734,257,257,257
BEGIN DESCRIPTION:
Hackberry Creek 44.0
END DESCRIPTION:
XS GIS Cut Line= 4
      2284079.00      7092160.03      2284073.94      7092027.18
      2284185.34      7091788.33      2284373.57      7091426.23
#Sta/Elev= 30
  4621.0  884.32  4641.0  883.74  4691.1  879.97  4749.3  877.34  4753.2  877.52
  4829.3  874.98  4846.7  875.23  4875.1  874.02  4905.3  873.80  4938.1  874.56
  4960.5  874.53  4994.9  873.69  5004.6  872.81  5013.9  871.17  5014.2  870.67
  5017.7  870.67  5017.9  871.17  5034.4  875.56  5040.0  875.44  5062.1  877.18
  5100.7  880.88  5167.1  884.31  5173.4  885.33  5183.5  885.98  5233.4  888.32
  5294.1  892.93  5376.3  897.77  5398.8  899.54  5410.3  901.17  5425.6  901.76
#Mann=3,-1,0
  4621.0    0.05       0  5013.9   0.033       0  5017.9    0.05       0
Bank Sta=5013.9,5017.9
Exp/Cntr=0.3,0.1

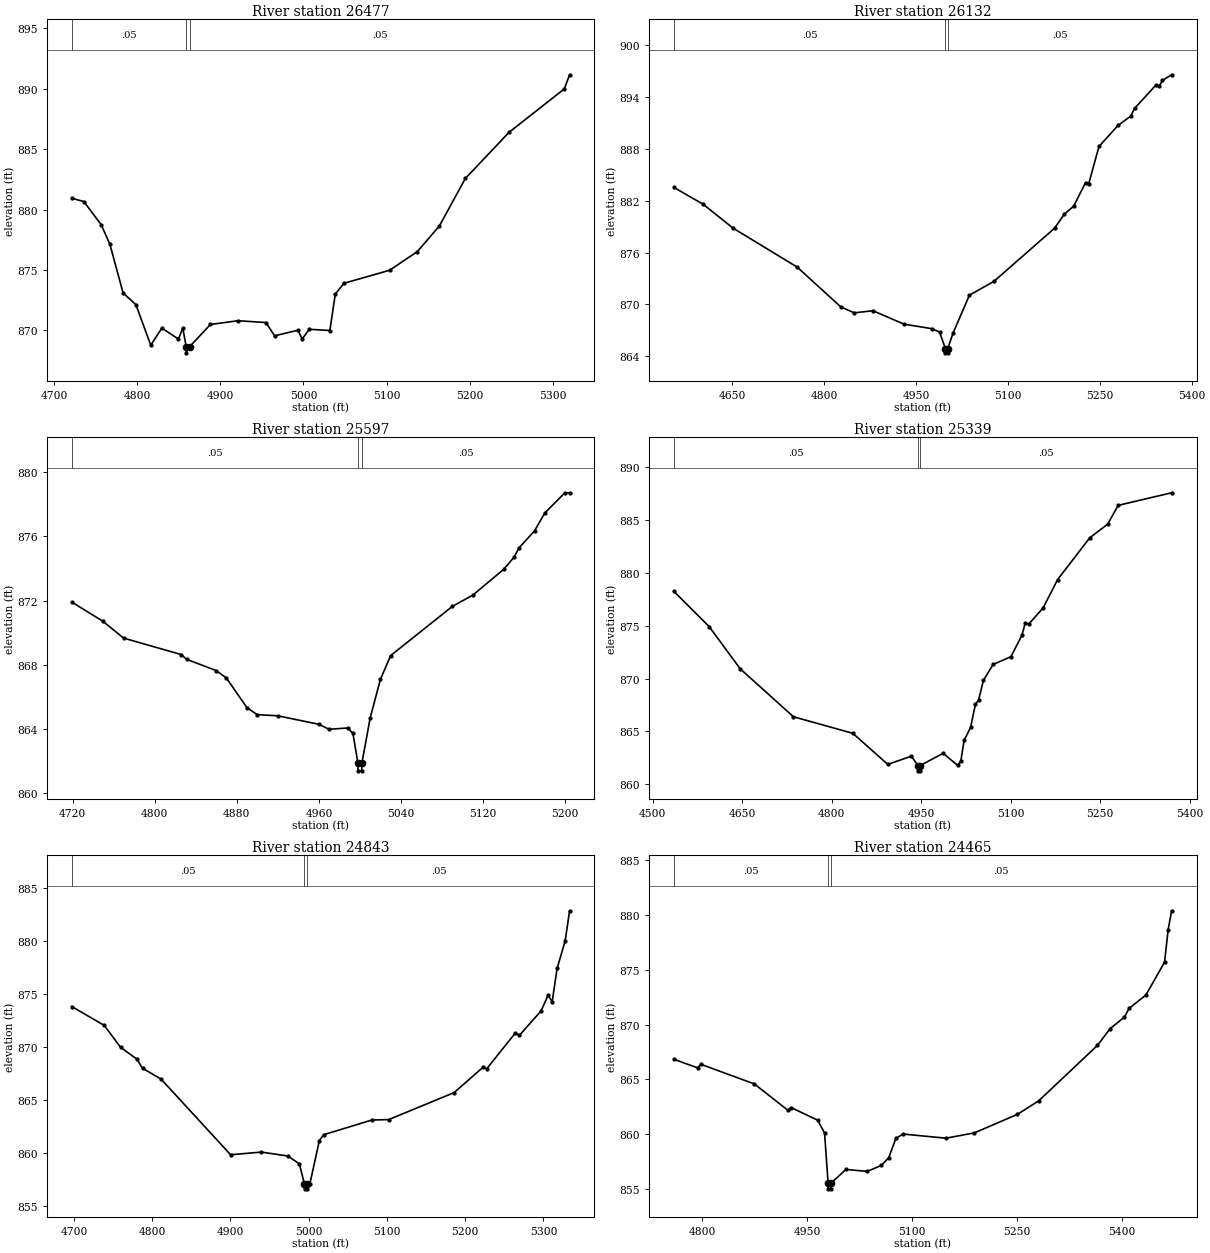
Type RM Length L Ch R = 1,26477,345,345,345
BEGIN DESCRIPTION:
Mapping XS 5b72d1df
END DESCRIPTION:
XS GIS Cut Line= 2
      2284296.48      7092223.80      2284466.04      7091649.72
#Sta/Elev= 30
  4721.5  880.93  4735.9  880.66  4756.7  878.75  4767.2  877.13  4783.1  873.09
  4798.5  872.12  4816.4  868.76  4829.7  870.18  4849.7  869.27  4854.9  870.19
  4859.0  868.63  4859.3  868.13  4863.0  868.63  4888.2  870.48  4921.5  870.79
  4954.8  870.64  4965.3  869.54  4993.3  870.00  4998.5  869.28  5007.0  870.08
  5031.8  869.98  5038.3  872.99  5048.7  873.89  5103.6  874.97  5136.9  876.51
  5163.4  878.63  5194.7  882.57  5247.2  886.39  5313.7  889.99  5320.1  891.16
#Mann=3,-1,0
  4721.5    0.05       0  4859.0   0.033       0  4863.0    0.05       0
Bank Sta=4859,4863
Exp/Cntr=0.3,0.1

Type RM Length L Ch R = 1,26132,535,535,535
BEGIN DESCRIPTION:
Hackberry Creek 43.0
END DESCRIPTION:
XS GIS Cut Line= 3
      2284438.21      7092393.38      2284664.17      7092009.97
      2284759.38      7091655.57
#Sta/Elev= 30
  4555.2  883.54  4602.9  881.60  4652.0  878.82  4756.4  874.32  4827.3  869.73
  4849.3  869.03  4880.0  869.27  4930.6  867.72  4975.7  867.20  4988.6  866.81
  4998.1  864.90  4998.3  864.40  5001.8  864.40  5002.1  864.90  5010.6  866.68
  5037.3  871.07  5077.3  872.67  5176.2  878.82  5192.0  880.44  5207.3  881.36
  5226.8  884.10  5232.0  883.98  5248.7  888.28  5279.8  890.72  5300.5  891.80
  5306.8  892.69  5341.6  895.39  5346.8  895.23  5352.3  895.94  5367.2  896.58
#Mann=3,-1,0
  4555.2    0.05       0  4998.1    0.04       0  5002.1    0.05       0
Bank Sta=4998.1,5002.1
Exp/Cntr=0.3,0.1

Type RM Length L Ch R = 1,25597,258,258,258
BEGIN DESCRIPTION:
Mapping XS 16fa48e5
END DESCRIPTION:
XS GIS Cut Line= 2
      2284867.43      7092410.33      2284896.96      7091925.83
#Sta/Elev= 30
  4719.1  871.90  4749.5  870.70  4769.5  869.66  4825.9  868.63  4830.9  868.34
  4859.7  867.64  4869.7  867.18  4889.8  865.33  4899.8  864.89  4919.8  864.82
  4959.9  864.29  4969.9  863.98  4988.2  864.06  4993.2  863.72  4998.0  861.89
  4998.2  861.39  5001.7  861.39  5002.0  861.89  5010.0  864.68  5020.0  867.09
  5030.0  868.57  5090.1  871.63  5110.2  872.34  5140.2  873.94  5150.2  874.69
  5155.5  875.30  5170.3  876.34  5180.3  877.45  5199.9  878.71  5204.5  878.71
#Mann=3,-1,0
  4719.1    0.05       0  4998.0    0.04       0  5002.0    0.05       0
Bank Sta=4998,5002
Exp/Cntr=0.3,0.1

Type RM Length L Ch R = 1,25339,496,496,496
BEGIN DESCRIPTION:
Hackberry Creek 41.0
END DESCRIPTION:
XS GIS Cut Line= 3
      2284929.01      7092559.99      2285110.18      7092185.33
      2285264.14      7091796.79
#Sta/Elev= 30
  4535.5  878.25  4594.7  874.91  4646.6  870.92  4735.9  866.38  4835.4  864.81
  4894.0  861.87  4933.6  862.65  4944.3  861.76  4944.5  861.26  4948.0  861.26
  4948.3  861.76  4986.7  862.92  5011.1  861.77  5016.4  862.20  5021.9  864.15
  5032.7  865.37  5040.8  867.55  5046.1  867.96  5054.2  869.82  5070.5  871.33
  5100.2  872.06  5118.7  874.08  5124.5  875.30  5129.9  875.13  5154.2  876.68
  5178.6  879.37  5232.6  883.33  5262.3  884.60  5280.1  886.39  5369.6  887.58
#Mann=3,-1,0
  4535.5    0.05       0  4944.3   0.033       0  4948.3    0.05       0
Bank Sta=4944.3,4948.3
Exp/Cntr=0.3,0.1

Type RM Length L Ch R = 1,24843,378,378,378
BEGIN DESCRIPTION:
Hackberry Creek 40.0
END DESCRIPTION:
XS GIS Cut Line= 3
      2285279.01      7092609.97      2285360.77      7092318.99
      2285439.52      7091994.45
#Sta/Elev= 30
  4697.3  873.84  4738.8  872.06  4759.6  869.99  4780.4  868.88  4787.6  868.02
  4811.5  866.98  4900.2  859.85  4939.5  860.10  4973.5  859.73  4988.1  858.99
  4994.4  857.13  4994.7  856.63  4998.2  856.63  4998.4  857.13  5001.6  857.13
  5013.6  861.18  5019.1  861.74  5080.8  863.13  5102.3  863.17  5185.9  865.72
  5222.5  868.09  5227.7  867.98  5264.3  871.36  5269.4  871.13  5296.9  873.42
  5306.1  874.92  5311.2  874.28  5317.5  877.44  5327.8  880.04  5333.5  882.89
#Mann=3,-1,0
  4697.3    0.05       0  4994.4    0.04       0  4998.4    0.05       0
Bank Sta=4994.4,4998.4
Exp/Cntr=0.3,0.1

Type RM Length L Ch R = 1,24465,92,92,92
BEGIN DESCRIPTION:
Mapping XS 76ebce09
END DESCRIPTION:
XS GIS Cut Line= 3
      2285586.98      7092684.67      2285569.31      7092460.91
      2285472.23      7091983.95
#Sta/Elev= 30
  4759.4  866.84  4793.2  866.06  4798.2  866.38  4874.4  864.59  4921.9  862.21
  4927.0  862.43  4964.7  861.29  4974.7  860.12  4979.8  855.52  4980.1  855.02
  4983.6  855.02  4983.8  855.52  5005.2  856.79  5035.8  856.61  5055.9  857.16
  5066.4  857.86  5076.6  859.62  5086.8  860.02  5148.1  859.64  5188.9  860.13
  5250.1  861.81  5280.7  863.05  5364.5  868.10  5382.8  869.64  5403.2  870.69
  5409.9  871.49  5433.8  872.70  5460.5  875.70  5465.6  878.64  5470.6  880.39
#Mann=3,-1,0
  4759.4    0.05       0  4979.8   0.033       0  4983.8    0.05       0
Bank Sta=4979.8,4983.8
Exp/Cntr=0.3,0.1

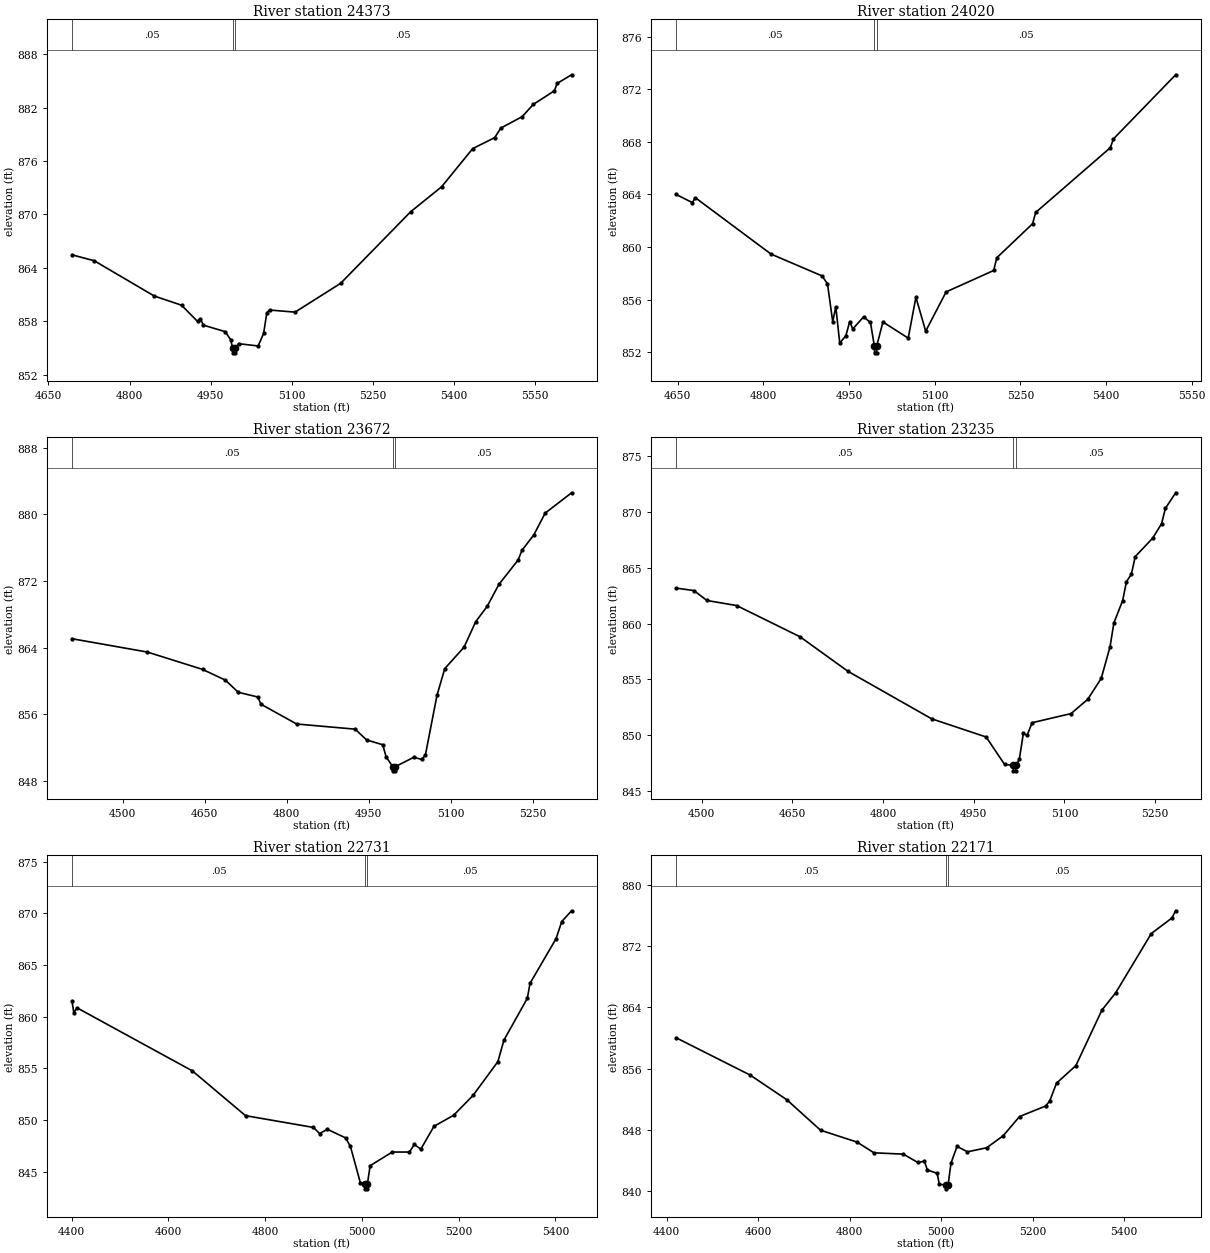
Type RM Length L Ch R = 1,24373,353,353,353
BEGIN DESCRIPTION:
Hackberry Creek 39.0
END DESCRIPTION:
XS GIS Cut Line= 3
      2285655.82      7092670.88      2285615.42      7092373.27
      2285498.71      7091760.33
#Sta/Elev= 30
  4693.5  865.46  4734.8  864.79  4845.8  860.83  4896.2  859.80  4925.8  857.98
  4930.8  858.30  4936.6  857.56  4977.0  856.83  4987.1  855.92  4991.0  854.95
  4991.2  854.45  4994.7  854.45  4995.0  854.95  5001.8  855.48  5037.9  855.22
  5048.1  856.63  5054.0  858.95  5059.1  859.26  5106.2  859.02  5190.6  862.26
  5320.0  870.29  5377.3  873.10  5434.9  877.39  5475.6  878.62  5486.7  879.69
  5526.5  880.98  5546.9  882.35  5586.0  883.88  5591.1  884.71  5617.8  885.68
#Mann=3,-1,0
  4693.5    0.05       0  4991.0   0.033       0  4995.0    0.05       0
Bank Sta=4991,4995
Exp/Cntr=0.3,0.1

Type RM Length L Ch R = 1,24020,348,348,348
BEGIN DESCRIPTION:
Hackberry Creek 38.0
END DESCRIPTION:
XS GIS Cut Line= 3
      2285791.59      7092696.59      2285921.51      7092368.37
      2285696.97      7091897.13
#Sta/Elev= 30
  4647.0  864.00  4675.5  863.38  4680.8  863.75  4813.3  859.46  4902.5  857.80
  4912.2  857.20  4921.4  854.31  4926.8  855.44  4933.7  852.68  4944.5  853.25
  4951.1  854.32  4956.5  853.76  4975.5  854.68  4987.5  854.25  4994.4  852.44
  4994.7  851.94  4998.2  851.94  4998.4  852.44  5009.3  854.29  5053.6  853.06
  5067.1  856.17  5084.2  853.59  5120.0  856.58  5203.3  858.21  5208.8  859.18
  5271.4  861.77  5276.9  862.63  5407.6  867.56  5413.1  868.23  5522.0  873.11
#Mann=3,-1,0
  4647.0    0.05       0  4994.4   0.033       0  4998.4    0.05       0
Bank Sta=4994.4,4998.4
Exp/Cntr=0.3,0.1

Type RM Length L Ch R = 1,23672,437,437,437
BEGIN DESCRIPTION:
Hackberry Creek 37.0
END DESCRIPTION:
XS GIS Cut Line= 3
      2285729.97      7092753.87      2286213.63      7092410.94
      2286443.50      7092186.17
#Sta/Elev= 30
  4407.1  865.07  4545.2  863.47  4646.1  861.39  4687.9  860.10  4711.3  858.65
  4747.0  858.08  4753.1  857.21  4818.3  854.84  4925.4  854.22  4946.3  852.93
  4975.8  852.35  4982.1  850.90  4994.1  849.72  4994.6  849.22  4998.3  849.22
  4998.8  849.72  5032.8  850.85  5046.9  850.59  5053.9  851.10  5075.2  858.29
  5089.4  861.48  5124.7  864.06  5146.0  867.11  5167.1  868.96  5188.4  871.58
  5223.7  874.52  5230.8  875.69  5252.0  877.49  5273.2  880.14  5321.5  882.58
#Mann=3,-1,0
  4407.1    0.05       0  4994.1   0.033       0  4998.8    0.05       0
Bank Sta=4994.1,4998.8
Exp/Cntr=0.3,0.1

Type RM Length L Ch R = 1,23235,504,504,504
BEGIN DESCRIPTION:
Hackberry Creek 36.0
END DESCRIPTION:
XS GIS Cut Line= 3
      2285869.69      7092781.07      2286413.24      7092711.07
      2286634.68      7092542.57
#Sta/Elev= 30
  4457.6  863.18  4487.2  862.96  4508.7  862.07  4557.7  861.62  4662.7  858.82
  4742.1  855.72  4880.4  851.47  4970.5  849.84  5001.0  847.38  5015.0  847.31
  5015.6  846.81  5019.3  846.81  5019.8  847.31  5025.4  847.86  5032.0  850.16
  5038.2  849.99  5046.5  851.12  5110.9  851.94  5138.5  853.22  5160.8  855.09
  5175.4  857.93  5181.7  860.05  5196.2  862.06  5202.5  863.75  5210.7  864.43
  5217.0  866.00  5246.1  867.67  5260.6  868.95  5266.9  870.32  5283.9  871.72
#Mann=3,-1,0
  4457.6    0.05       0  5015.0   0.033       0  5019.8    0.05       0
Bank Sta=5015,5019.8
Exp/Cntr=0.3,0.1

Type RM Length L Ch R = 1,22731,560,560,560
BEGIN DESCRIPTION:
Hackberry Creek 35.0
END DESCRIPTION:
XS GIS Cut Line= 3
      2286332.41      7093518.89      2286594.34      7093035.12
      2286678.99      7092560.03
#Sta/Elev= 30
  4400.8  861.52  4404.7  860.37  4410.9  860.87  4649.7  854.76  4759.5  850.43
  4899.9  849.29  4912.6  848.70  4928.8  849.11  4966.3  848.28  4976.4  847.45
  4996.8  843.96  5006.4  843.85  5007.1  843.35  5010.9  843.35  5011.6  843.85
  5017.1  845.59  5062.9  846.91  5098.3  846.91  5108.5  847.64  5121.9  847.19
  5149.1  849.40  5189.8  850.47  5229.7  852.38  5281.2  855.66  5293.7  857.74
  5342.1  861.79  5347.6  863.23  5401.5  867.56  5413.2  869.21  5433.5  870.25
#Mann=3,-1,0
  4400.8    0.05       0  5006.4   0.033       0  5011.6    0.05       0
Bank Sta=5006.4,5011.6
Exp/Cntr=0.3,0.1

Type RM Length L Ch R = 1,22171,362,362,362
BEGIN DESCRIPTION:
Hackberry Creek 34.0
END DESCRIPTION:
XS GIS Cut Line= 3
      2286403.57      7093527.59      2286899.54      7093230.15
      2287324.74      7092943.00
#Sta/Elev= 30
  4420.8  860.05  4583.0  855.17  4662.7  851.96  4736.5  847.98  4816.2  846.43
  4853.2  845.03  4917.3  844.86  4948.4  843.79  4963.5  843.92  4969.8  842.79
  4991.2  842.36  4995.9  840.92  5009.7  840.83  5010.5  840.33  5015.1  840.83
  5021.4  843.69  5034.7  845.87  5057.3  845.16  5099.4  845.69  5135.3  847.25
  5171.3  849.77  5228.3  851.14  5237.2  851.81  5251.9  854.12  5294.2  856.41
  5351.1  863.66  5381.1  865.91  5459.0  873.65  5503.9  875.67  5512.2  876.62
#Mann=3,-1,0
  4420.8    0.05       0  5009.7   0.033       0  5015.1    0.05       0
Bank Sta=5009.7,5015.1
Exp/Cntr=0.3,0.1

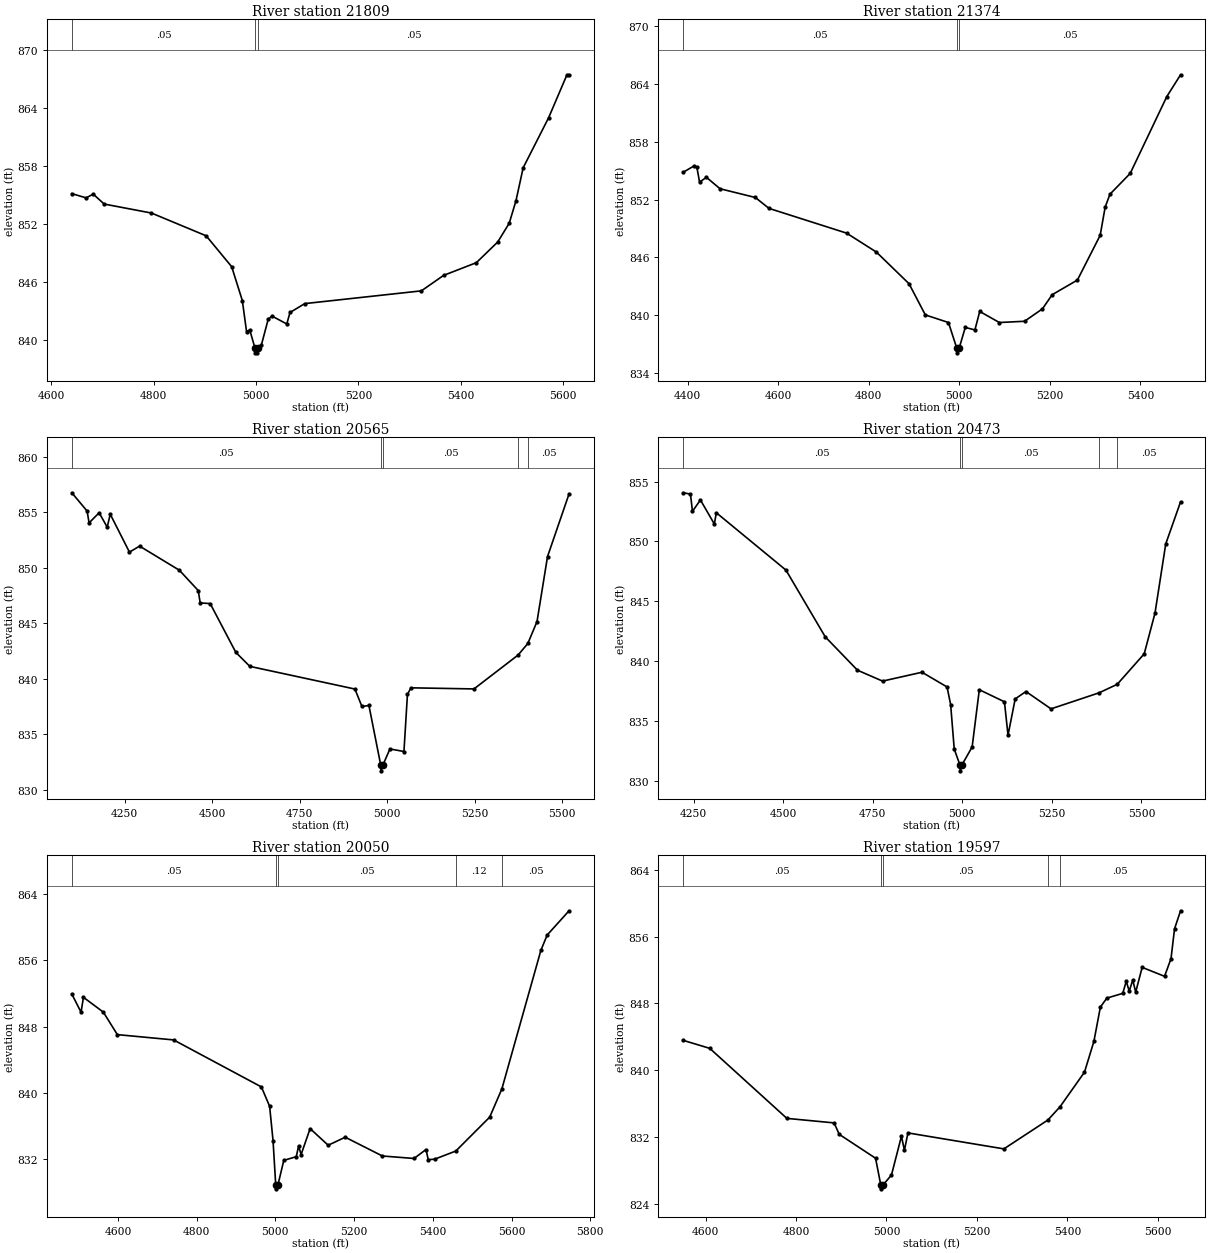
Type RM Length L Ch R = 1,21809,435,435,435
BEGIN DESCRIPTION:
Hackberry Creek 33.0
END DESCRIPTION:
XS GIS Cut Line= 3
      2286713.67      7093842.94      2286934.83      7093557.59
      2287312.65      7093078.58
#Sta/Elev= 30
  4640.2  855.12  4668.1  854.68  4681.9  855.07  4703.4  854.04  4795.7  853.11
  4902.6  850.75  4952.4  847.55  4973.2  844.04  4981.4  840.84  4987.7  841.00
  4997.8  839.13  4998.6  838.63  5002.5  838.63  5003.3  839.13  5010.3  839.42
  5023.6  842.09  5031.1  842.44  5060.0  841.62  5066.3  842.81  5095.2  843.73
  5322.9  845.05  5366.2  846.65  5430.3  847.97  5472.0  850.11  5494.5  852.06
  5507.6  854.38  5521.7  857.80  5571.3  862.97  5607.2  867.43  5611.3  867.43
#Mann=3,-1,0
  4640.2    0.05       0  4997.8   0.033       0  5003.3    0.05       0
Bank Sta=4997.8,5003.3
Exp/Cntr=0.3,0.1

Type RM Length L Ch R = 1,21374,809,809,809
BEGIN DESCRIPTION:
Hackberry Creek 32.0
END DESCRIPTION:
XS GIS Cut Line= 3
      2286759.42      7093981.81      2287264.47      7093644.13
      2287433.41      7093183.69
#Sta/Elev= 30
  4390.7  854.86  4414.3  855.51  4420.6  855.36  4426.6  853.82  4441.6  854.33
  4471.7  853.14  4549.7  852.23  4579.8  851.10  4751.1  848.53  4817.0  846.56
  4889.1  843.27  4925.1  840.03  4976.2  839.24  4994.4  836.59  4995.2  836.09
  4999.9  836.59  5013.3  838.73  5034.6  838.47  5045.2  840.39  5088.6  839.24
  5144.2  839.37  5183.7  840.66  5205.2  842.13  5260.9  843.65  5311.2  848.30
  5322.2  851.23  5332.8  852.57  5377.5  854.73  5458.4  862.72  5488.7  864.98
#Mann=3,-1,0
  4390.7    0.05       0  4994.4   0.033       0  4999.9    0.05       0
Bank Sta=4994.4,4999.9
Exp/Cntr=0.3,0.1

Type RM Length L Ch R = 1,20565,92,92,92
BEGIN DESCRIPTION:
Hackberry Creek 31.0
END DESCRIPTION:
XS GIS Cut Line= 4
      2286749.02      7094035.19      2287144.85      7093856.80
      2287597.46      7093863.75      2288130.50      7093858.10
#Sta/Elev= 30
  4099.5  856.75  4143.2  855.10  4148.7  854.04  4177.4  854.95  4200.5  853.66
  4209.2  854.82  4264.0  851.41  4293.0  851.95  4406.6  849.78  4460.5  847.95
  4466.0  846.84  4494.6  846.78  4567.8  842.39  4607.8  841.13  4907.9  839.09
  4927.9  837.52  4947.9  837.61  4981.7  832.23  4982.6  831.73  4987.5  832.23
  5007.9  833.70  5047.9  833.47  5057.9  838.61  5067.9  839.20  5247.9  839.10
  5373.9  842.15  5401.7  843.19  5427.9  845.16  5457.9  851.01  5519.4  856.65
#Mann=5,-1,0
  4099.5    0.05       0  4981.7   0.033       0  4987.5    0.05       0
  5373.9    0.12       0  5401.7    0.05       0
Bank Sta=4981.7,4987.5
Exp/Cntr=0.3,0.1

Type RM Length L Ch R = 1,20473,423,423,423
BEGIN DESCRIPTION:
Hackberry Creek 30.5
END DESCRIPTION:
XS GIS Cut Line= 4
      2286858.36      7094095.10      2287144.74      7093948.48
      2287601.32      7093953.00      2288210.32      7093935.08
#Sta/Elev= 30
  4221.6  854.06  4241.5  853.95  4247.1  852.51  4269.3  853.46  4308.1  851.45
  4313.7  852.39  4507.9  847.60  4617.6  842.02  4707.6  839.23  4777.6  838.32
  4887.6  839.06  4957.6  837.83  4967.6  836.35  4977.6  832.64  4993.4  831.32
  4994.3  830.82  4999.2  831.32  5027.6  832.82  5047.6  837.60  5117.7  836.59
  5127.7  833.80  5147.7  836.83  5177.7  837.45  5247.7  836.00  5381.8  837.34
  5432.4  838.05  5507.8  840.60  5537.8  843.99  5567.9  849.79  5609.2  853.30
#Mann=5,-1,0
  4221.6    0.05       0  4993.4   0.033       0  4999.2    0.05       0
  5381.8    0.12       0  5432.4    0.05       0
Bank Sta=4993.4,4999.2
Exp/Cntr=0.3,0.1

Type RM Length L Ch R = 1,20050,453,453,453
BEGIN DESCRIPTION:
Hackberry Creek 30.0
END DESCRIPTION:
XS GIS Cut Line= 3
      2287259.43      7094571.65      2287686.87      7094270.86
      2288332.31      7093907.61
#Sta/Elev= 30
  4482.9  851.93  4506.3  849.74  4512.4  851.54  4562.9  849.75  4598.6  847.03
  4741.5  846.39  4964.5  840.71  4985.4  838.37  4994.1  834.22  5000.9  828.89
  5001.8  828.39  5006.7  828.89  5021.4  831.83  5053.2  832.28  5059.0  833.57
  5065.4  832.54  5088.3  835.67  5134.2  833.66  5177.5  834.63  5271.9  832.36
  5352.3  832.06  5382.7  833.14  5388.5  831.92  5404.4  831.97  5458.5  832.96
  5544.6  837.06  5575.5  840.47  5674.6  857.21  5690.6  859.07  5746.2  862.00
#Mann=5,-1,0
  4482.9    0.05       0  5000.9   0.033       0  5006.7    0.05       0
  5458.5    0.12       0  5575.5    0.05       0
Bank Sta=5000.9,5006.7
Exp/Cntr=0.3,0.1

Type RM Length L Ch R = 1,19597,441,441,441
BEGIN DESCRIPTION:
Hackberry Creek 29.0
END DESCRIPTION:
XS GIS Cut Line= 3
      2287694.23      7094663.22      2288016.43      7094493.27
      2288488.41      7093929.80
#Sta/Elev= 30
  4551.0  843.57  4609.4  842.62  4779.9  834.24  4884.3  833.70  4895.7  832.33
  4976.0  829.47  4987.4  826.31  4988.3  825.81  4993.2  826.31  5011.2  827.47
  5033.2  832.10  5039.8  830.43  5047.6  832.50  5259.7  830.59  5356.9  834.04
  5383.7  835.62  5437.9  839.77  5458.7  843.45  5473.0  847.55  5487.3  848.63
  5522.5  849.20  5530.3  850.65  5536.8  849.46  5544.6  850.79  5551.1  849.35
  5565.4  852.31  5614.9  851.24  5629.2  853.35  5637.0  856.92  5650.3  859.08
#Mann=5,-1,0
  4551.0    0.05       0  4987.4   0.033       0  4993.2    0.05       0
  5356.9    0.12       0  5383.7    0.05       0
Bank Sta=4987.4,4993.2
Exp/Cntr=0.3,0.1