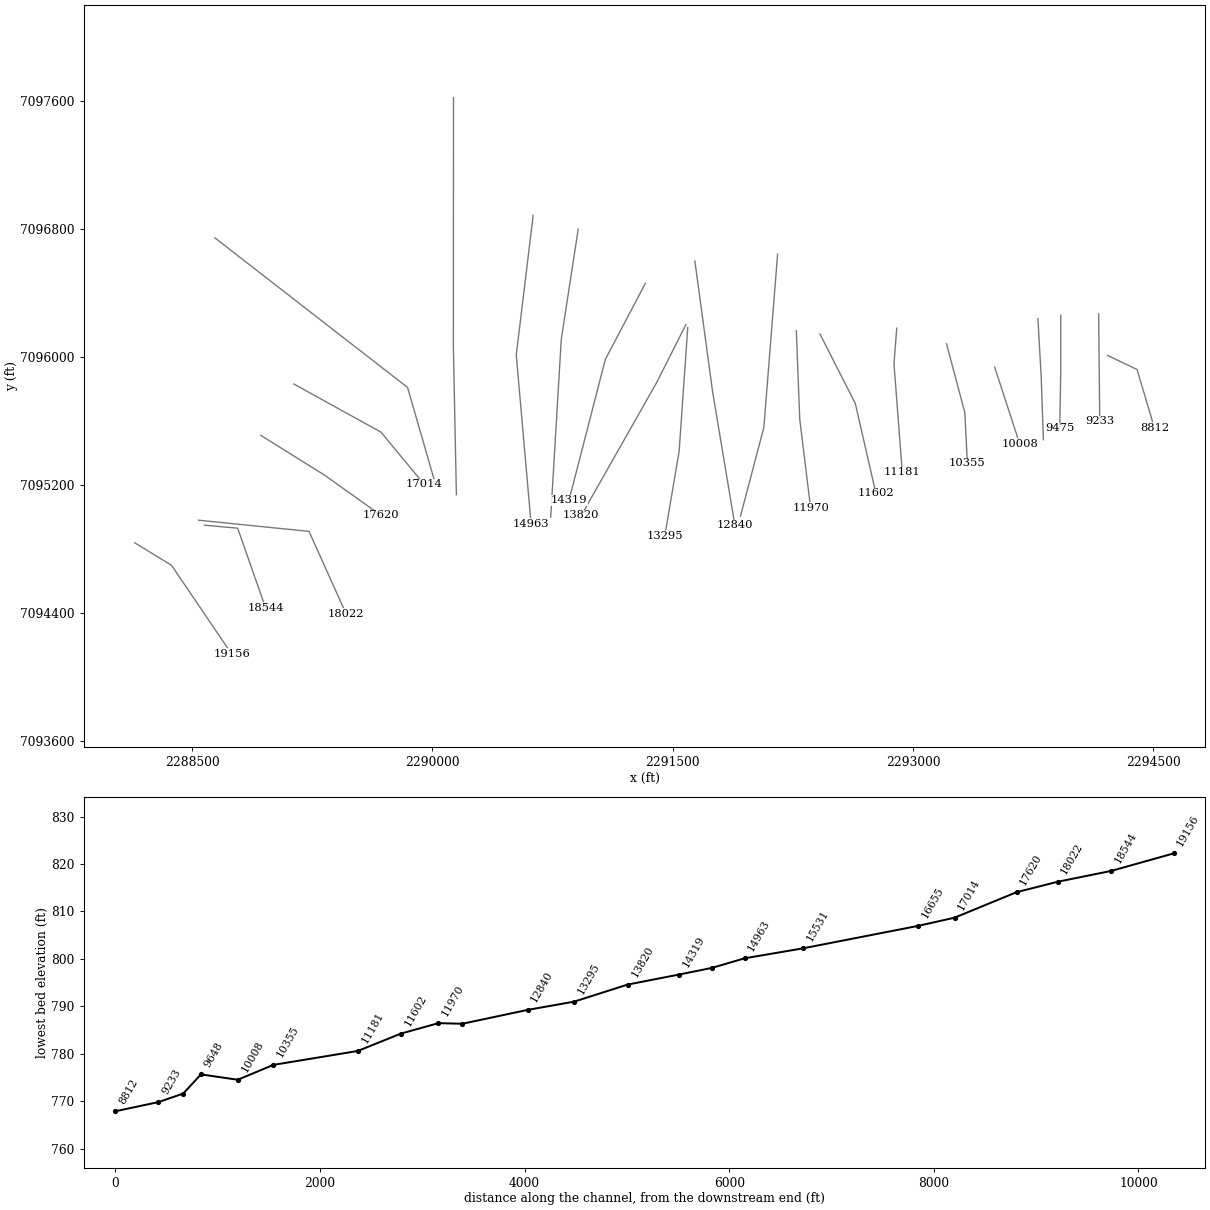
HEC-RAS study Hackberry Creek.prj: Hackberry Creek Base Level Engineering

--- Hackberry Creek.g01 (geometry) --- (continued)

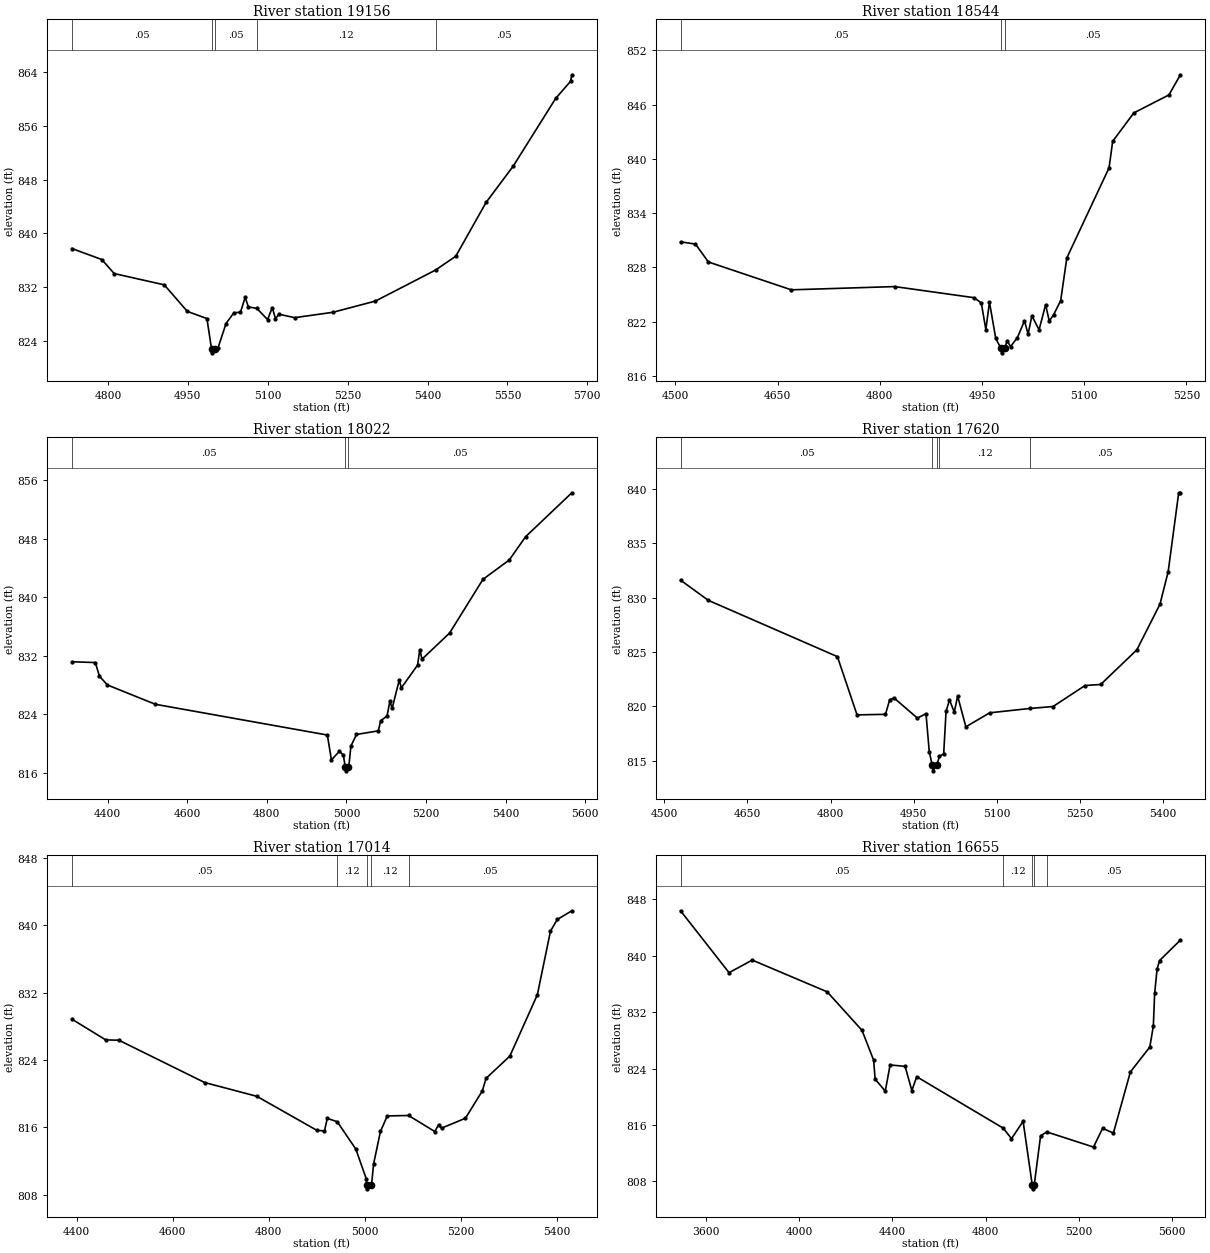
Type RM Length L Ch R = 1,19156,612,612,612
BEGIN DESCRIPTION:
Hackberry Creek 28.0
END DESCRIPTION:
XS GIS Cut Line= 3
      2288141.13      7094839.14      2288370.89      7094698.82
      2288746.49      7094144.87
#Sta/Elev= 30
  4732.5  837.76  4788.6  836.12  4811.7  834.04  4905.8  832.36  4949.1  828.41
  4985.9  827.35  4994.7  822.75  4995.7  822.25  5000.7  822.75  5006.8  823.00
  5021.7  826.61  5036.5  828.21  5048.8  828.28  5057.7  830.51  5063.7  829.07
  5079.4  828.87  5099.7  827.20  5108.6  828.98  5114.6  827.34  5121.1  827.99
  5150.6  827.48  5222.4  828.28  5302.3  829.95  5415.1  834.56  5453.1  836.62
  5510.0  844.62  5560.9  850.01  5640.6  860.08  5668.7  862.64  5671.0  863.60
#Mann=5,-1,0
  4732.5    0.05       0  4994.7    0.05       0  5000.7    0.05       0
  5079.4    0.12       0  5415.1    0.05       0
Bank Sta=4994.7,5000.7
Exp/Cntr=0.3,0.1

Type RM Length L Ch R = 1,18544,522,522,522
BEGIN DESCRIPTION:
Mapping XS fcb5ea23
END DESCRIPTION:
XS GIS Cut Line= 3
      2288577.20      7094949.03      2288784.23      7094930.32
      2288957.89      7094434.21
#Sta/Elev= 30
  4507.7  830.83  4529.6  830.58  4548.6  828.60  4670.2  825.52  4821.9  825.88
  4938.4  824.65  4949.0  824.07  4955.7  821.12  4961.0  824.16  4970.2  820.14
  4977.8  819.05  4978.8  818.55  4983.8  819.05  4986.7  819.90  4992.0  819.24
  5002.0  820.24  5012.4  822.09  5017.7  820.61  5023.2  822.65  5033.8  821.10
  5043.4  823.88  5048.7  822.07  5055.0  822.74  5065.5  824.33  5074.5  829.05
  5136.5  839.02  5141.8  841.95  5172.8  845.09  5224.3  847.08  5241.2  849.31
#Mann=3,-1,0
  4507.7    0.05       0  4977.8   0.033       0  4983.8    0.05       0
Bank Sta=4977.8,4983.8
Exp/Cntr=0.3,0.1

Type RM Length L Ch R = 1,18022,402,402,402
BEGIN DESCRIPTION:
Hackberry Creek 27.0
END DESCRIPTION:
XS GIS Cut Line= 3
      2288540.46      7094980.18      2289229.52      7094910.42
      2289460.63      7094396.37
#Sta/Elev= 30
  4310.3  831.17  4369.1  831.06  4379.2  829.21  4399.3  828.00  4519.9  825.36
  4952.1  821.16  4962.3  817.76  4982.3  818.94  4992.3  818.42  4997.1  816.77
  4998.1  816.27  5003.2  816.77  5005.9  816.77  5011.3  819.66  5025.3  821.24
  5080.1  821.73  5086.3  823.13  5102.0  823.74  5109.4  825.80  5114.9  824.79
  5132.6  828.64  5138.1  827.61  5178.8  830.71  5184.4  832.83  5189.9  831.52
  5259.3  835.09  5343.2  842.43  5409.3  845.07  5450.1  848.24  5566.5  854.25
#Mann=3,-1,0
  4310.3    0.05       0  4997.1   0.033       0  5003.2    0.05       0
Bank Sta=4997.1,5003.2
Exp/Cntr=0.3,0.1

Type RM Length L Ch R = 1,17620,606,606,606
BEGIN DESCRIPTION:
Hackberry Creek 26.0
END DESCRIPTION:
XS GIS Cut Line= 3
      2288929.03      7095509.98      2289329.00      7095260.00
      2289679.02      7095009.99
#Sta/Elev= 30
  4529.4  831.62  4579.5  829.76  4812.4  824.58  4847.8  819.22  4899.1  819.27
  4906.7  820.61  4914.4  820.78  4956.8  818.92  4972.2  819.33  4978.1  815.83
  4983.5  814.57  4984.7  814.07  4991.5  814.57  4996.5  815.42  5004.1  815.63
  5008.4  819.54  5014.6  820.60  5023.2  819.47  5029.3  820.95  5044.1  818.12
  5087.1  819.41  5159.5  819.81  5201.4  819.99  5259.1  821.92  5287.4  822.02
  5352.5  825.20  5394.3  829.40  5409.1  832.40  5428.1  839.66  5431.2  839.66
#Mann=5,-1,0
  4529.4    0.05       0  4983.5    0.07       0  4991.5    0.05       0
  4996.5    0.12       0  5159.5    0.05       0
Bank Sta=4983.5,4991.5
Exp/Cntr=0.3,0.1

Type RM Length L Ch R = 1,17014,359,359,359
BEGIN DESCRIPTION:
Hackberry Creek 25.0
END DESCRIPTION:
XS GIS Cut Line= 3
      2289135.38      7095830.66      2289678.94      7095530.19
      2289946.56      7095205.69
#Sta/Elev= 30
  4390.2  828.86  4460.5  826.40  4488.0  826.36  4666.7  821.33  4775.5  819.69
  4900.4  815.65  4916.4  815.57  4922.2  817.07  4943.0  816.67  4981.7  813.42
  5003.5  809.88  5004.4  809.19  5005.7  808.69  5012.5  809.19  5014.6  809.19
  5018.6  811.60  5033.0  815.51  5047.3  817.36  5091.7  817.41  5146.3  815.50
  5154.1  816.31  5160.6  815.91  5210.1  817.08  5245.3  820.33  5253.2  821.83
  5302.7  824.47  5360.0  831.76  5387.4  839.34  5401.7  840.72  5431.9  841.75
#Mann=5,-1,0
  4390.2    0.05       0  4943.0    0.12       0  5004.4    0.07       0
  5012.5    0.12       0  5091.7    0.05       0
Bank Sta=5004.4,5012.5
Exp/Cntr=0.3,0.1

Type RM Length L Ch R = 1,16655,1124,1124,1124
BEGIN DESCRIPTION:
Hackberry Creek 24.5
END DESCRIPTION:
XS GIS Cut Line= 3
      2288641.62      7096743.96      2289844.57      7095809.61
      2290016.30      7095213.86
#Sta/Elev= 30
  3491.8  846.36  3699.7  837.59  3799.3  839.37  4120.6  834.87  4269.9  829.41
  4319.7  825.18  4326.0  822.50  4369.5  820.80  4390.3  824.51  4454.5  824.31
  4483.5  820.88  4504.3  822.84  4875.4  815.55  4910.7  814.06  4960.5  816.52
  4999.9  807.45  5001.1  806.95  5008.0  807.45  5035.4  814.46  5061.6  815.02
  5262.4  812.87  5301.3  815.53  5347.6  814.85  5420.5  823.52  5503.7  827.04
  5518.9  830.03  5524.5  834.66  5534.9  838.08  5545.4  839.30  5635.0  842.21
#Mann=5,-1,0
  3491.8    0.05       0  4875.4    0.12       0  4999.9    0.07       0
  5008.0    0.12       0  5061.6    0.05       0
Bank Sta=4999.9,5008
Exp/Cntr=0.3,0.1

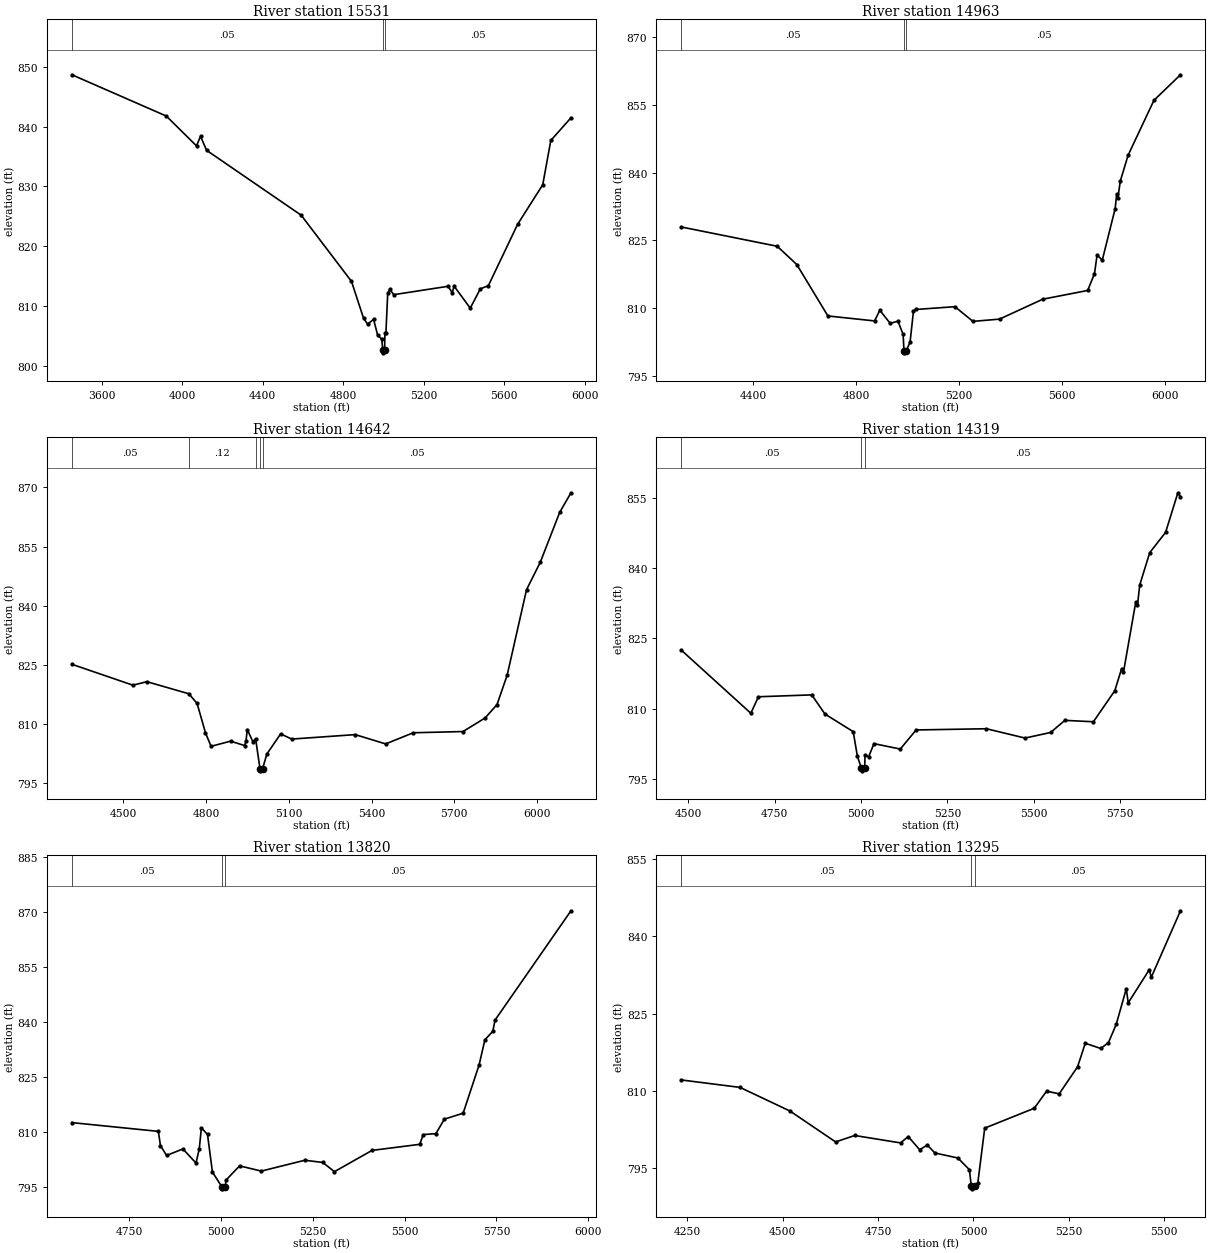
Type RM Length L Ch R = 1,15531,568,568,568
BEGIN DESCRIPTION:
Hackberry Creek 24.0
END DESCRIPTION:
XS GIS Cut Line= 3
      2290131.23      7097618.93      2290130.43      7096062.99
      2290149.45      7095139.82
#Sta/Elev= 30
  3452.0  848.64  3920.9  841.75  4070.9  836.77  4090.9  838.38  4120.9  836.03
  4590.9  825.20  4840.9  814.15  4900.9  807.99  4920.9  807.02  4950.9  807.80
  4970.9  805.16  4990.9  804.52  4996.4  802.72  4997.7  802.22  5005.5  802.72
  5006.9  805.52  5011.9  805.52  5020.9  812.18  5030.9  812.84  5050.9  811.93
  5321.0  813.33  5341.0  812.26  5351.0  813.34  5431.0  809.68  5481.0  812.90
  5521.0  813.44  5666.3  823.68  5791.1  830.28  5831.1  837.67  5931.3  841.46
#Mann=3,-1,0
  3452.0    0.05       0  4996.4   0.033       0  5005.5    0.05       0
Bank Sta=4996.4,5005.5
Exp/Cntr=0.3,0.1

Type RM Length L Ch R = 1,14963,321,321,321
BEGIN DESCRIPTION:
Hackberry Creek 23.0
END DESCRIPTION:
XS GIS Cut Line= 3
      2290628.63      7096884.60      2290523.07      7096012.23
      2290615.60      7094957.51
#Sta/Elev= 30
  4121.8  827.97  4493.7  823.71  4569.6  819.67  4690.5  808.29  4871.8  807.19
  4892.0  809.55  4932.3  806.65  4962.5  807.14  4982.6  804.20  4985.7  800.63
  4987.0  800.13  4994.8  800.63  5009.5  802.51  5022.8  809.41  5032.9  809.73
  5183.5  810.34  5253.7  807.09  5356.8  807.59  5524.8  812.00  5699.1  813.93
  5725.5  817.64  5735.6  821.78  5755.7  820.64  5805.8  832.04  5811.5  835.19
  5816.5  834.49  5825.9  838.17  5856.0  843.85  5956.4  856.00  6059.3  861.65
#Mann=3,-1,0
  4121.8    0.05       0  4985.7   0.033       0  4994.8    0.05       0
Bank Sta=4985.7,4994.8
Exp/Cntr=0.3,0.1

Type RM Length L Ch R = 1,14642,323,323,323
BEGIN DESCRIPTION:
Hackberry Creek 22.0
END DESCRIPTION:
XS GIS Cut Line= 3
      2290909.87      7096798.62      2290804.00      7096110.05
      2290738.00      7094999.17
#Sta/Elev= 30
  4313.5  825.13  4534.7  819.83  4585.3  820.72  4737.2  817.66  4767.4  815.20
  4797.7  807.75  4818.0  804.32  4888.8  805.63  4939.3  804.52  4944.4  805.55
  4949.5  808.55  4969.7  805.47  4979.5  806.26  4995.5  798.60  4996.8  798.10
  5004.7  798.60  5020.2  802.36  5070.3  807.47  5110.4  806.16  5340.8  807.29
  5451.0  804.93  5551.2  807.76  5731.5  808.07  5811.6  811.51  5854.9  814.91
  5891.8  822.41  5961.9  844.06  6012.0  851.07  6082.1  863.67  6123.0  868.65
#Mann=5,-1,0
  4313.5    0.05       0  4737.2    0.12       0  4979.5    0.05       0
  4995.5   0.033       0  5004.7    0.05       0
Bank Sta=4995.5,5004.7
Exp/Cntr=0.3,0.1

Type RM Length L Ch R = 1,14319,499,499,499
BEGIN DESCRIPTION:
Hackberry Creek 21.0
END DESCRIPTION:
XS GIS Cut Line= 3
      2291329.00      7096460.00      2291079.13      7095985.12
      2290852.59      7095105.95
#Sta/Elev= 30
  4480.2  822.44  4681.1  808.99  4703.1  812.51  4857.4  812.91  4895.8  808.81
  4977.4  805.06  4989.6  799.79  5001.4  797.19  5002.7  796.69  5010.6  797.19
  5011.6  800.04  5022.1  799.69  5037.5  802.50  5113.7  801.34  5159.5  805.42
  5363.0  805.68  5474.8  803.69  5548.8  804.88  5590.1  807.47  5672.7  807.17
  5734.6  813.80  5754.4  818.53  5759.6  817.70  5795.1  832.65  5800.3  832.13
  5806.9  836.41  5835.8  843.29  5881.7  847.62  5917.2  856.07  5924.7  855.23
#Mann=3,-1,0
  4480.2    0.05       0  5001.4   0.033       0  5010.6    0.05       0
Bank Sta=5001.4,5010.6
Exp/Cntr=0.3,0.1

Type RM Length L Ch R = 1,13820,525,525,525
BEGIN DESCRIPTION:
Hackberry Creek 20.0
END DESCRIPTION:
XS GIS Cut Line= 3
      2291581.76      7096201.65      2291399.66      7095840.60
      2290929.02      7095010.04
#Sta/Elev= 30
  4594.0  812.61  4829.4  810.23  4835.0  806.38  4851.7  803.67  4896.3  805.45
  4931.8  801.61  4940.9  805.52  4946.5  811.20  4963.2  809.39  4976.6  799.17
  5002.6  795.09  5004.0  794.59  5012.0  795.09  5013.1  796.92  5050.6  800.84
  5109.8  799.42  5228.1  802.37  5277.1  801.77  5308.9  799.27  5411.3  805.05
  5541.1  806.70  5550.8  809.35  5585.2  809.61  5608.2  813.55  5659.4  815.18
  5702.7  828.26  5718.6  835.14  5740.2  837.48  5746.2  840.51  5953.0  870.26
#Mann=3,-1,0
  4594.0    0.05       0  5002.6   0.033       0  5012.0    0.05       0
Bank Sta=5002.6,5012
Exp/Cntr=0.3,0.1

Type RM Length L Ch R = 1,13295,455,455,455
BEGIN DESCRIPTION:
Hackberry Creek 19.0
END DESCRIPTION:
XS GIS Cut Line= 3
      2291593.46      7096183.38      2291539.68      7095410.52
      2291450.45      7094883.85
#Sta/Elev= 30
  4234.1  812.12  4387.8  810.68  4518.8  806.09  4638.5  800.09  4688.6  801.34
  4808.9  799.90  4828.9  801.14  4859.0  798.57  4879.0  799.49  4899.1  797.94
  4959.2  796.97  4989.3  794.71  4994.5  791.48  4995.9  790.98  5004.1  791.48
  5011.6  792.20  5029.6  802.77  5159.5  806.63  5191.9  809.95  5224.9  809.43
  5273.1  814.68  5293.3  819.25  5333.9  818.24  5354.2  819.39  5374.5  822.92
  5400.9  829.84  5406.0  827.10  5461.3  833.55  5466.4  832.05  5543.0  844.98
#Mann=3,-1,0
  4234.1    0.05       0  4994.5   0.033       0  5004.1    0.05       0
Bank Sta=4994.5,5004.1
Exp/Cntr=0.3,0.1

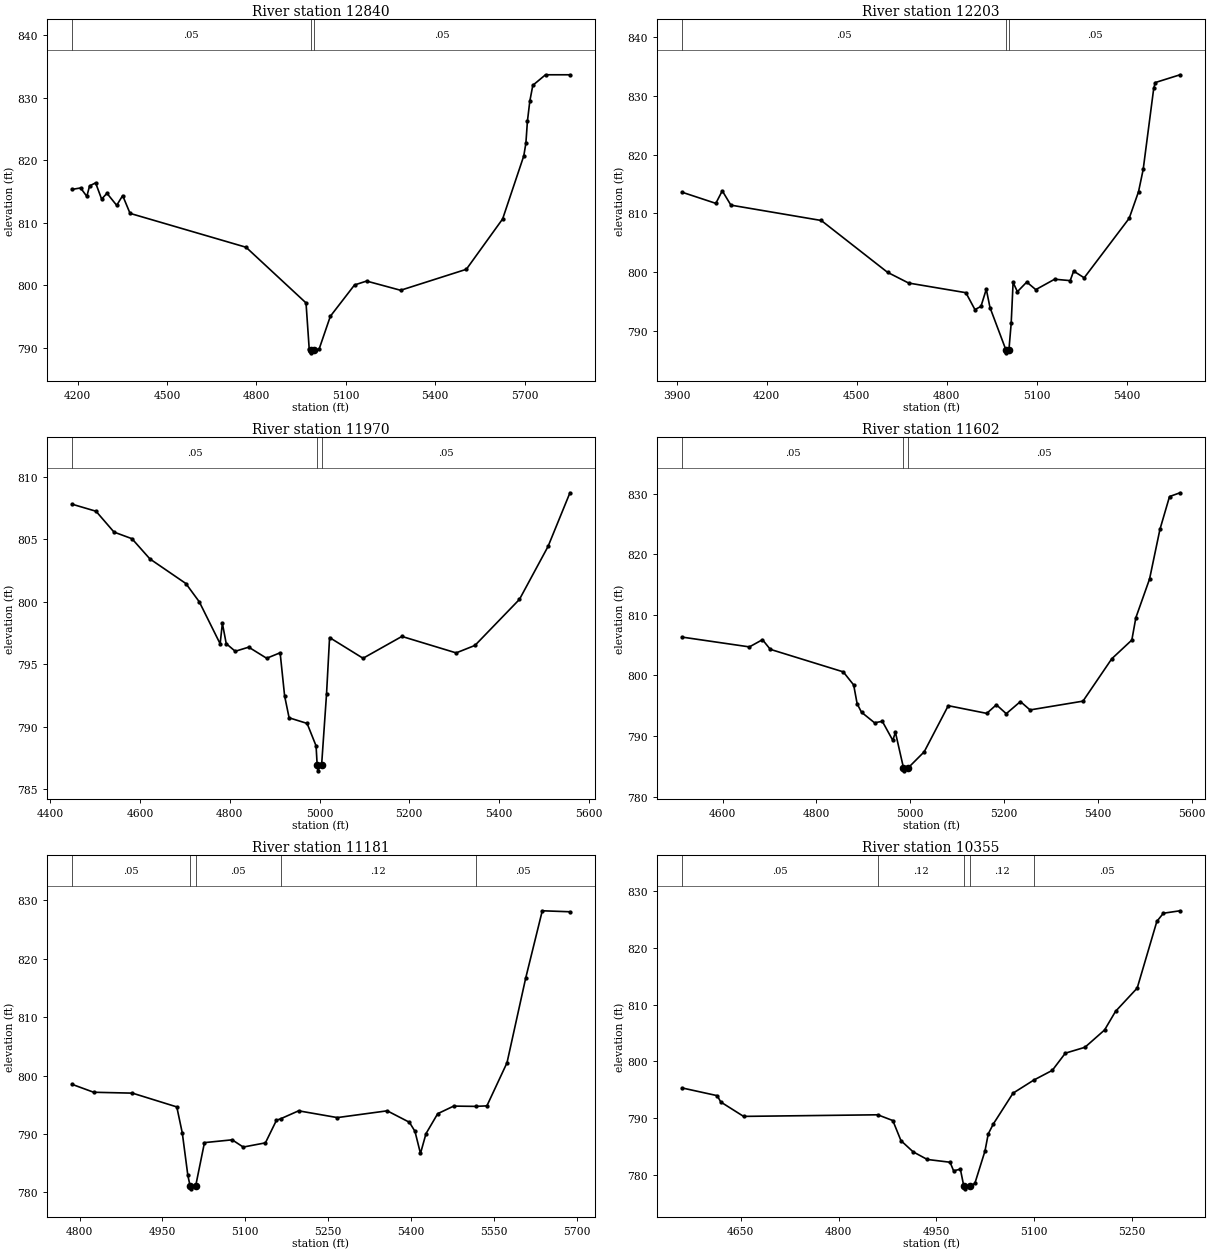
Type RM Length L Ch R = 1,12840,637,637,637
BEGIN DESCRIPTION:
Hackberry Creek 18.0
END DESCRIPTION:
XS GIS Cut Line= 3
      2291637.84      7096598.90      2291748.93      7095780.03
      2291888.02      7094947.24
#Sta/Elev= 30
  4181.1  815.33  4210.3  815.57  4231.2  814.22  4240.5  815.90  4260.7  816.38
  4280.9  813.78  4298.7  814.72  4331.4  812.79  4351.5  814.35  4376.2  811.51
  4765.3  806.10  4966.5  797.21  4977.2  789.84  4982.5  789.74  4983.9  789.24
  4992.1  789.74  5010.0  789.78  5048.1  795.08  5129.2  800.08  5169.7  800.70
  5283.7  799.23  5504.3  802.58  5626.0  810.62  5696.9  820.68  5704.0  822.71
  5709.1  826.20  5717.2  829.44  5727.3  831.96  5769.8  833.64  5851.8  833.64
#Mann=3,-1,0
  4181.1    0.05       0  4982.5   0.033       0  4992.1    0.05       0
Bank Sta=4982.5,4992.1
Exp/Cntr=0.3,0.1

Type RM Length L Ch R = 1,12203,233,233,233
BEGIN DESCRIPTION:
Hackberry Creek 17.0
END DESCRIPTION:
XS GIS Cut Line= 3
      2292154.33      7096642.35      2292068.43      7095559.29
      2291922.74      7095006.32
#Sta/Elev= 30
  3918.0  813.62  4030.7  811.72  4052.2  813.85  4080.9  811.42  4381.8  808.81
  4602.5  800.00  4672.7  798.18  4863.3  796.54  4893.4  793.67  4913.5  794.21
  4931.2  797.13  4943.6  794.01  4996.6  786.82  4998.0  786.32  5006.6  786.82
  5014.1  791.32  5020.5  798.29  5034.8  796.71  5066.0  798.35  5096.0  797.06
  5158.8  798.83  5210.6  798.59  5222.1  800.21  5257.2  799.07  5407.0  809.18
  5438.1  813.70  5453.6  817.48  5488.7  831.26  5493.9  832.25  5576.3  833.57
#Mann=3,-1,0
  3918.0    0.05       0  4996.6   0.033       0  5006.6    0.05       0
Bank Sta=4996.6,5006.6
Exp/Cntr=0.3,0.1

Type RM Length L Ch R = 1,11970,368,368,368
BEGIN DESCRIPTION:
Hackberry Creek 16.0
END DESCRIPTION:
XS GIS Cut Line= 3
      2292271.17      7096163.78      2292292.59      7095610.11
      2292360.16      7095058.32
#Sta/Elev= 30
  4448.0  807.82  4501.8  807.25  4541.9  805.58  4581.9  805.05  4621.9  803.43
  4702.0  801.46  4732.0  799.99  4778.4  796.63  4783.4  798.27  4792.0  796.64
  4812.1  796.03  4842.1  796.36  4882.1  795.47  4912.1  795.91  4922.1  792.45
  4932.1  790.70  4972.2  790.25  4992.2  788.45  4994.6  786.95  4996.0  786.45
  5004.6  786.95  5015.5  792.59  5022.3  797.13  5096.9  795.47  5183.5  797.22
  5304.4  795.90  5346.3  796.50  5445.5  800.19  5509.2  804.43  5558.0  808.73
#Mann=3,-1,0
  4448.0    0.05       0  4994.6   0.033       0  5004.6    0.05       0
Bank Sta=4994.6,5004.6
Exp/Cntr=0.3,0.1

Type RM Length L Ch R = 1,11602,421,421,421
BEGIN DESCRIPTION:
Hackberry Creek 15.0
END DESCRIPTION:
XS GIS Cut Line= 3
      2292418.73      7096143.01      2292639.15      7095709.84
      2292767.70      7095148.19
#Sta/Elev= 30
  4513.1  806.31  4656.9  804.69  4684.8  805.88  4701.4  804.29  4857.1  800.57
  4879.3  798.41  4886.7  795.30  4896.0  793.91  4923.8  792.17  4940.4  792.41
  4962.7  789.27  4968.3  790.60  4985.5  784.74  4986.9  784.24  4995.6  784.74
  5029.7  787.38  5081.0  794.99  5163.1  793.72  5183.6  795.14  5204.7  793.67
  5234.9  795.67  5255.4  794.29  5368.3  795.74  5429.8  802.74  5472.5  805.82
  5481.1  809.51  5510.3  815.89  5532.4  824.07  5552.9  829.50  5575.3  830.12
#Mann=3,-1,0
  4513.1    0.05       0  4985.5   0.033       0  4995.6    0.05       0
Bank Sta=4985.5,4995.6
Exp/Cntr=0.3,0.1

Type RM Length L Ch R = 1,11181,826,826,826
BEGIN DESCRIPTION:
Hackberry Creek 14.0
END DESCRIPTION:
XS GIS Cut Line= 3
      2292897.91      7096179.42      2292880.67      7095956.92
      2292932.64      7095280.07
#Sta/Elev= 30
  4786.0  798.50  4825.5  797.13  4895.7  796.98  4976.0  794.62  4986.0  790.13
  4996.0  782.89  5000.1  781.08  5001.5  780.58  5010.2  781.08  5026.1  788.50
  5076.3  788.98  5096.3  787.74  5136.5  788.46  5156.5  792.33  5164.2  792.59
  5196.6  793.95  5266.8  792.79  5357.1  793.95  5397.2  791.99  5407.3  790.44
  5417.3  786.64  5427.3  790.04  5448.5  793.46  5477.5  794.76  5517.3  794.71
  5537.6  794.80  5574.0  802.18  5607.8  816.67  5637.9  828.23  5688.0  828.06
#Mann=5,-1,0
  4786.0    0.05       0  5000.1   0.033       0  5010.2    0.05       0
  5164.2    0.12       0  5517.3    0.05       0
Bank Sta=5000.1,5010.2
Exp/Cntr=0.3,0.1

Type RM Length L Ch R = 1,10355,347,347,347
BEGIN DESCRIPTION:
Hackberry Creek 13.5
END DESCRIPTION:
XS GIS Cut Line= 3
      2293208.68      7096082.20      2293322.95      7095651.85
      2293338.85      7095334.51
#Sta/Elev= 30
  4560.2  795.36  4614.2  794.00  4619.6  792.89  4654.6  790.36  4860.1  790.64
  4883.2  789.63  4895.7  786.10  4914.3  784.14  4935.9  782.80  4970.9  782.31
  4976.3  780.81  4986.7  781.09  4991.9  778.14  4993.3  777.64  5002.1  778.14
  5008.9  778.60  5024.4  784.28  5029.4  787.29  5037.3  789.05  5067.4  794.44
  5099.1  796.73  5127.5  798.44  5147.5  801.46  5177.5  802.49  5207.6  805.53
  5224.4  808.80  5257.6  812.89  5287.7  824.60  5297.7  826.03  5323.2  826.46
#Mann=5,-1,0
  4560.2    0.05       0  4860.1    0.12       0  4991.9    0.07       0
  5002.1    0.12       0  5099.1    0.05       0
Bank Sta=4991.9,5002.1
Exp/Cntr=0.3,0.1

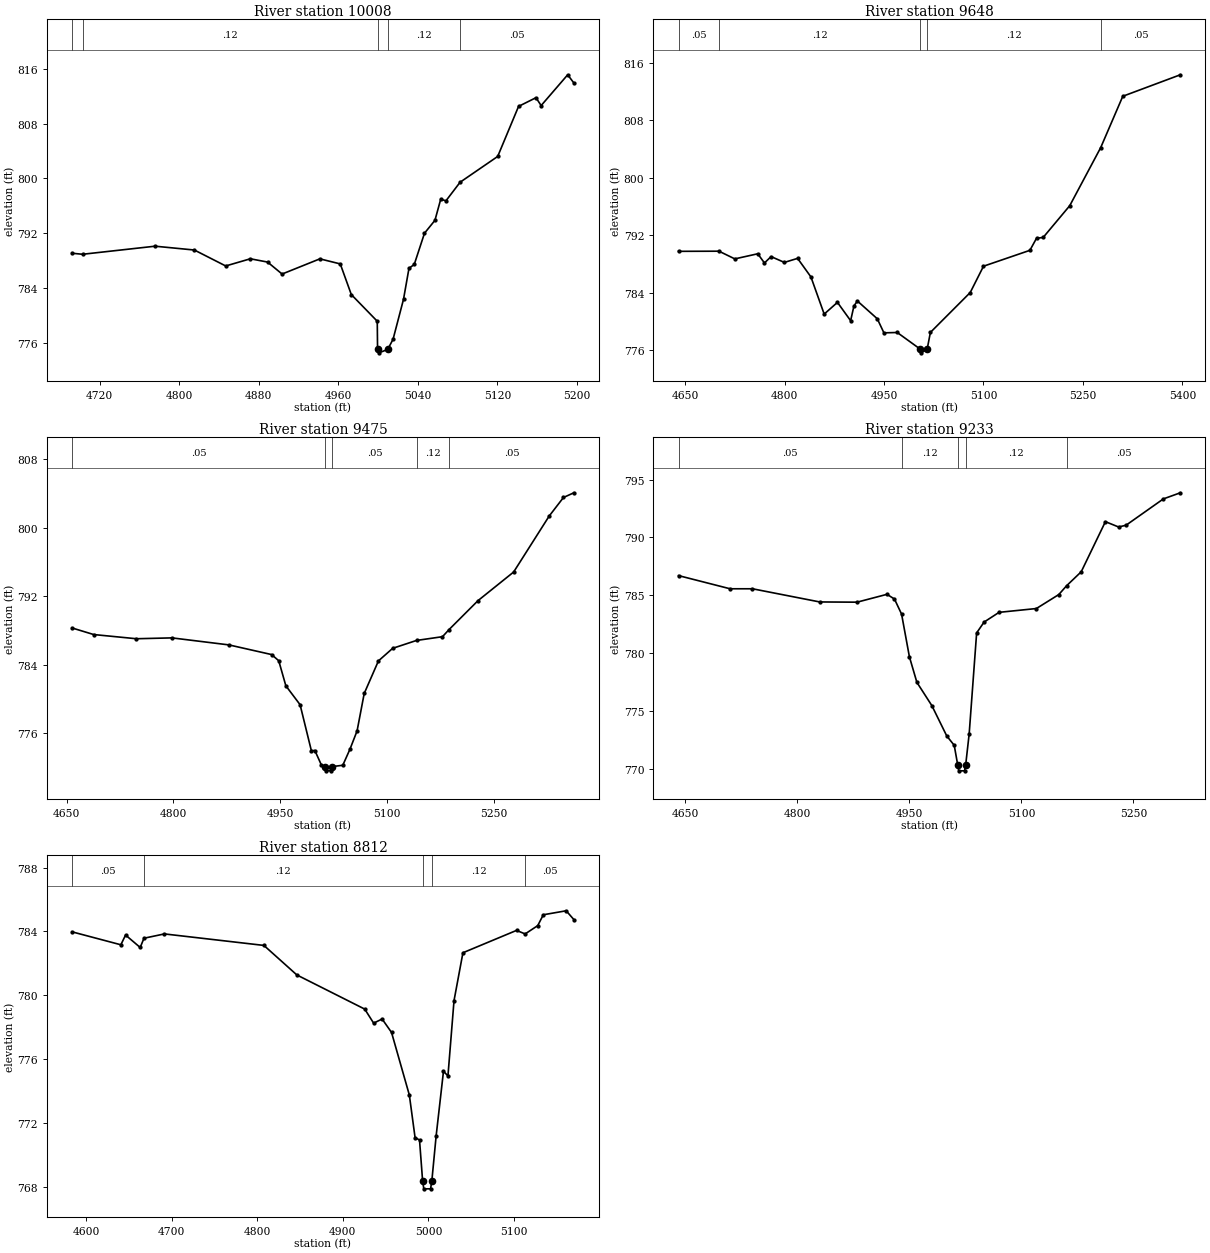
Type RM Length L Ch R = 1,10008,360,360,360
BEGIN DESCRIPTION:
Mapping XS c75ebf7c
END DESCRIPTION:
XS GIS Cut Line= 2
      2293508.94      7095936.93      2293665.30      7095457.17
#Sta/Elev= 30
  4692.3  789.07  4702.9  788.92  4775.8  790.10  4815.3  789.54  4846.8  787.21
  4871.6  788.26  4888.9  787.78  4903.5  786.03  4941.5  788.25  4962.0  787.51
  4973.1  783.03  4999.2  779.13  4999.5  775.01  5000.9  774.51  5009.7  775.01
  5015.1  776.50  5025.6  782.34  5031.1  786.87  5036.4  787.43  5046.7  792.00
  5057.2  793.88  5063.0  796.96  5068.3  796.74  5082.5  799.45  5120.3  803.22
  5141.3  810.54  5158.8  811.81  5164.0  810.66  5190.7  815.16  5196.9  813.96
#Mann=5,-1,0
  4692.3    0.05       0  4702.9    0.12       0  4999.5    0.07       0
  5009.7    0.12       0  5082.5    0.05       0
Bank Sta=4999.5,5009.7
Exp/Cntr=0.3,0.1

Type RM Length L Ch R = 1,9648,173,173,173
BEGIN DESCRIPTION:
Hackberry Creek 13.0
END DESCRIPTION:
XS GIS Cut Line= 3
      2293779.23      7096239.36      2293799.36      7095879.55
      2293813.24      7095483.26
#Sta/Elev= 30
  4640.0  789.76  4701.0  789.78  4724.9  788.71  4759.5  789.42  4769.6  788.14
  4779.6  789.03  4799.6  788.22  4819.6  788.78  4839.7  786.20  4859.7  781.03
  4879.7  782.66  4899.6  780.11  4904.6  782.17  4909.8  782.85  4939.8  780.38
  4949.8  778.42  4969.9  778.47  5004.8  776.14  5006.2  775.64  5015.0  776.14
  5019.9  778.48  5080.0  784.03  5100.0  787.69  5170.0  789.90  5180.0  791.58
  5190.0  791.69  5230.1  796.11  5276.8  804.19  5310.1  811.33  5396.9  814.32
#Mann=5,-1,0
  4640.0    0.05       0  4701.0    0.12       0  5004.8    0.07       0
  5015.0    0.12       0  5276.8    0.05       0
Bank Sta=5004.8,5015
Exp/Cntr=0.3,0.1

Type RM Length L Ch R = 1,9475,242,242,242
BEGIN DESCRIPTION:
Hackberry Creek 12.0
END DESCRIPTION:
XS GIS Cut Line= 3
      2293921.48      7096260.44      2293921.89      7095923.57
      2293915.50      7095555.40
#Sta/Elev= 30
  4657.6  788.30  4688.0  787.53  4748.0  787.04  4798.0  787.14  4878.0  786.32
  4938.0  785.19  4948.0  784.47  4958.0  781.54  4978.0  779.33  4993.8  773.97
  4998.8  773.97  5008.0  772.27  5012.7  772.10  5014.2  771.60  5021.8  771.60
  5023.3  772.10  5038.0  772.25  5048.1  774.13  5058.1  776.27  5068.1  780.64
  5088.1  784.45  5108.1  785.92  5141.6  786.84  5178.1  787.28  5187.3  788.11
  5228.1  791.50  5278.1  794.84  5328.1  801.39  5348.1  803.55  5362.7  804.10
#Mann=5,-1,0
  4657.6    0.05       0  5012.7    0.04       0  5023.3    0.05       0
  5141.6    0.12       0  5187.3    0.05       0
Bank Sta=5012.7,5023.3
Exp/Cntr=0.3,0.1

Type RM Length L Ch R = 1,9233,421,421,421
BEGIN DESCRIPTION:
Mapping XS fe4a391d
END DESCRIPTION:
XS GIS Cut Line= 2
      2294158.24      7096269.04      2294165.04      7095597.27
#Sta/Elev= 30
  4641.0  786.70  4710.0  785.56  4740.0  785.56  4830.0  784.42  4880.0  784.40
  4920.1  785.08  4930.1  784.67  4939.6  783.37  4950.1  779.67  4960.1  777.46
  4980.1  775.45  5000.1  772.82  5010.1  772.01  5014.8  770.30  5016.2  769.80
  5023.9  769.80  5025.4  770.30  5030.1  772.99  5040.1  781.74  5050.1  782.68
  5070.1  783.52  5120.1  783.85  5150.1  785.06  5160.5  785.82  5180.1  787.03
  5212.5  791.37  5230.1  790.91  5240.1  791.06  5290.1  793.34  5312.8  793.87
#Mann=5,-1,0
  4641.0    0.05       0  4939.6    0.12       0  5014.8    0.07       0
  5025.4    0.12       0  5160.5    0.05       0
Bank Sta=5014.8,5025.4
Exp/Cntr=0.3,0.1

Type RM Length L Ch R = 1,8812,337,337,337
BEGIN DESCRIPTION:
Mapping XS 6d6cb2c2
END DESCRIPTION:
XS GIS Cut Line= 3
      2294213.29      7096009.89      2294397.76      7095921.72
      2294506.36      7095555.76
#Sta/Elev= 30
  4583.7  783.97  4640.7  783.16  4646.2  783.77  4663.3  782.99  4667.7  783.57
  4691.6  783.84  4807.8  783.12  4846.3  781.27  4925.6  779.13  4936.0  778.25
  4945.9  778.51  4956.9  777.67  4977.7  773.75  4984.4  771.08  4989.6  770.93
  4993.2  768.37  4994.6  767.87  5002.5  767.87  5004.0  768.37  5009.0  771.18
  5017.6  775.24  5022.8  774.94  5029.9  779.66  5040.3  782.66  5102.9  784.06
  5113.0  783.84  5127.7  784.36  5134.2  785.04  5160.9  785.29  5169.9  784.74
#Mann=5,-1,0
  4583.7    0.05       0  4667.7    0.12       0  4993.2    0.07       0
  5004.0    0.12       0  5113.0    0.05       0
Bank Sta=4993.2,5004
Exp/Cntr=0.3,0.1