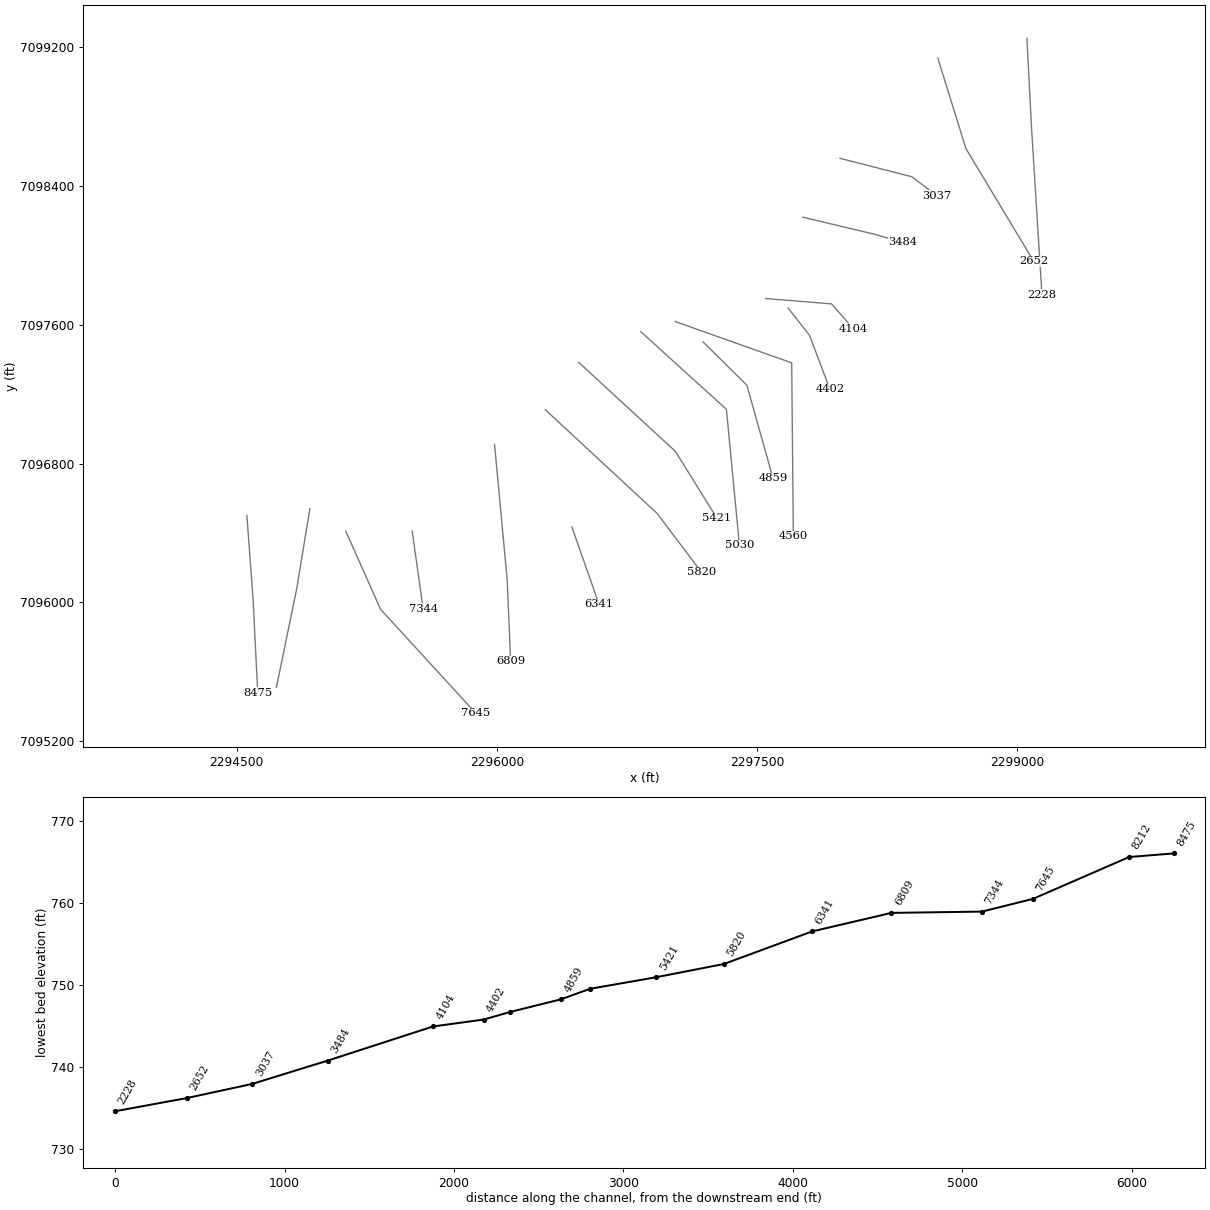
HEC-RAS study Hackberry Creek.prj: Hackberry Creek Base Level Engineering

--- Hackberry Creek.g01 (geometry) --- (continued)

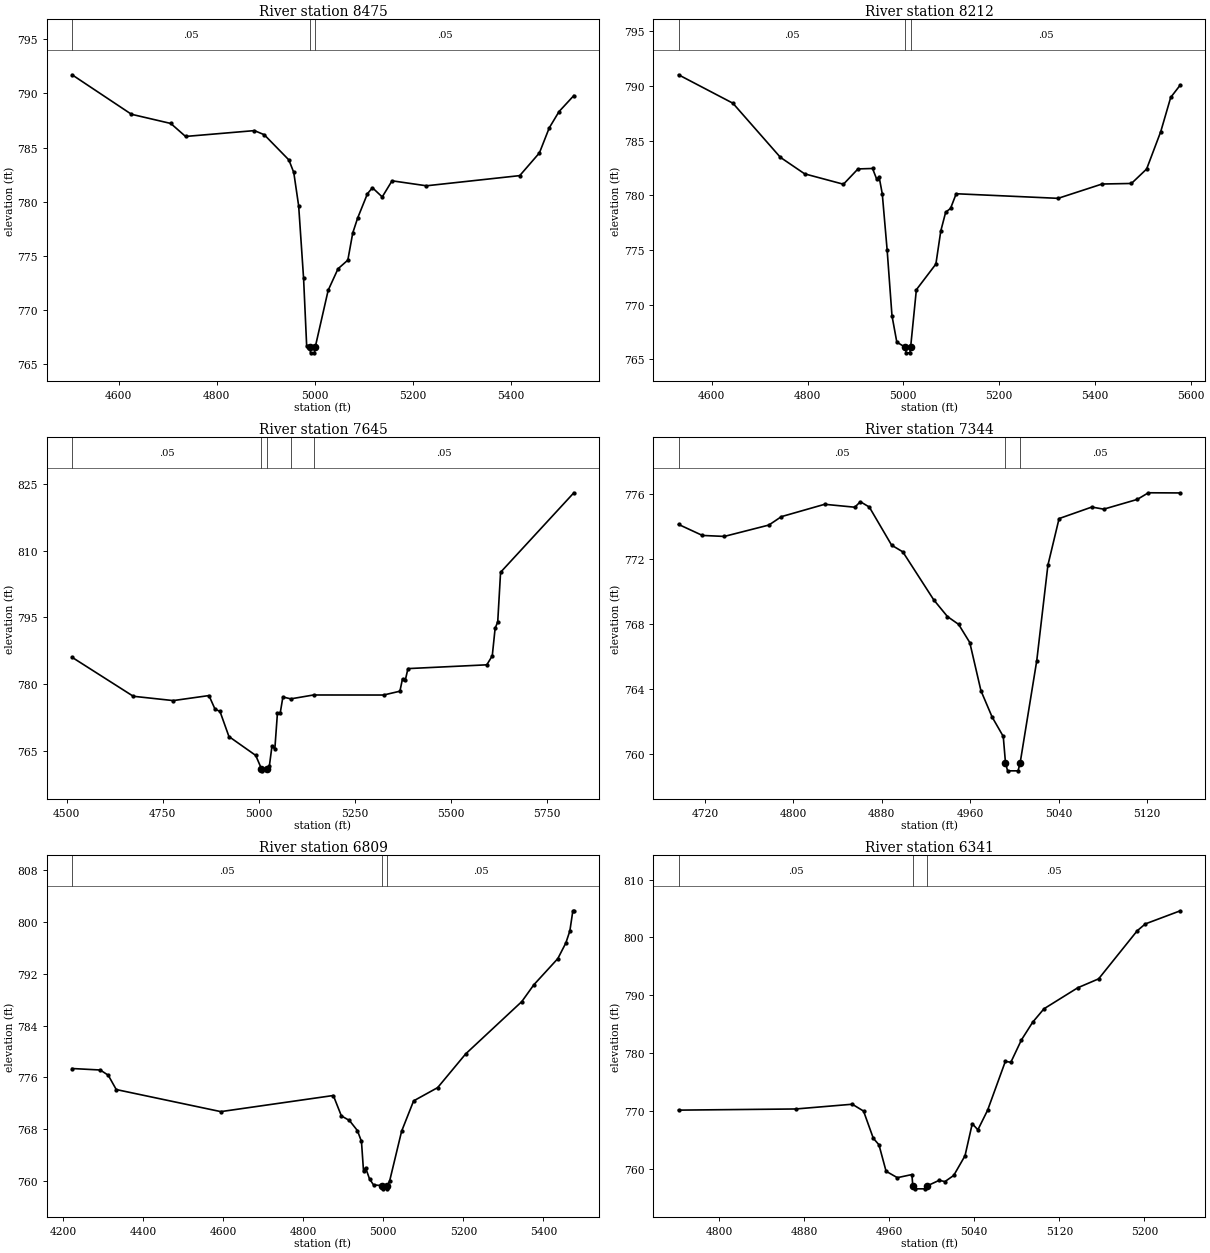
Type RM Length L Ch R = 1,8475,263,263,263
BEGIN DESCRIPTION:
Hackberry Creek 10.0
END DESCRIPTION:
XS GIS Cut Line= 3
      2294558.73      7096500.67      2294595.00      7096008.92
      2294621.23      7095479.86
#Sta/Elev= 30
  4505.1  791.73  4626.1  788.08  4706.3  787.23  4736.4  786.03  4876.8  786.57
  4896.8  786.19  4947.0  783.86  4957.0  782.70  4967.0  779.60  4977.0  772.91
  4983.3  766.65  4989.7  766.53  4991.2  766.03  4999.1  766.03  5000.6  766.53
  5027.1  771.81  5047.2  773.80  5067.2  774.60  5077.2  777.11  5087.2  778.49
  5107.2  780.74  5117.3  781.29  5137.3  780.44  5157.3  781.93  5227.4  781.47
  5417.6  782.41  5457.7  784.51  5477.7  786.82  5497.7  788.33  5527.9  789.81
#Mann=3,-1,0
  4505.1    0.05       0  4989.7    0.04       0  5000.6    0.05       0
Bank Sta=4989.7,5000.6
Exp/Cntr=0.3,0.1

Type RM Length L Ch R = 1,8212,567,567,567
BEGIN DESCRIPTION:
Hackberry Creek 9.0
END DESCRIPTION:
XS GIS Cut Line= 3
      2294922.03      7096539.83      2294845.58      7096076.91
      2294728.99      7095509.97
#Sta/Elev= 30
  4530.5  791.02  4644.0  788.42  4743.2  783.47  4793.9  781.96  4874.9  781.01
  4905.3  782.41  4935.7  782.45  4944.4  781.47  4949.5  781.66  4956.0  780.14
  4966.2  774.98  4976.3  768.98  4986.4  766.57  5004.3  766.09  5005.8  765.59
  5013.7  765.59  5015.2  766.09  5027.2  771.36  5068.0  773.71  5078.2  776.73
  5088.4  778.45  5098.6  778.80  5110.4  780.14  5323.2  779.72  5415.1  781.03
  5476.4  781.08  5508.1  782.40  5537.6  785.82  5558.4  788.95  5578.5  790.09
#Mann=3,-1,0
  4530.5    0.05       0  5004.3    0.04       0  5015.2    0.05       0
Bank Sta=5004.3,5015.2
Exp/Cntr=0.3,0.1

Type RM Length L Ch R = 1,7645,301,301,301
BEGIN DESCRIPTION:
Hackberry Creek 8.0
END DESCRIPTION:
XS GIS Cut Line= 3
      2295128.98      7096410.04      2295329.00      7095960.00
      2295878.98      7095360.02
#Sta/Elev= 30
  4514.0  786.01  4673.4  777.25  4777.4  776.28  4870.4  777.41  4886.1  774.37
  4899.1  773.84  4922.4  768.20  4992.1  763.96  5006.9  760.99  5008.8  760.49
  5020.2  760.99  5027.8  761.68  5034.5  766.07  5041.9  765.41  5048.7  773.49
  5056.1  773.59  5062.9  777.09  5083.5  776.67  5142.6  777.54  5325.0  777.53
  5367.5  778.39  5374.3  781.18  5381.7  780.93  5388.5  783.47  5593.8  784.32
  5608.0  786.35  5615.4  792.51  5622.2  793.98  5629.6  805.12  5820.4  822.99
#Mann=5,-1,0
  4514.0    0.05       0  5006.9   0.033       0  5020.2    0.05       0
  5083.5    0.12       0  5142.6    0.05       0
Bank Sta=5006.9,5020.2
Exp/Cntr=0.3,0.1

Type RM Length L Ch R = 1,7344,535,535,535
BEGIN DESCRIPTION:
Mapping XS 5e7fe259
END DESCRIPTION:
XS GIS Cut Line= 2
      2295511.64      7096410.96      2295574.50      7095961.33
#Sta/Elev= 30
  4696.1  774.13  4717.7  773.45  4737.5  773.39  4777.8  774.09  4789.2  774.61
  4828.3  775.37  4855.6  775.19  4860.6  775.53  4868.7  775.20  4888.9  772.85
  4899.0  772.44  4927.0  769.48  4939.4  768.45  4949.5  767.97  4959.6  766.85
  4969.7  763.88  4979.8  762.26  4989.9  761.06  4991.9  759.44  4993.8  758.94
  5003.3  758.94  5005.2  759.44  5020.2  765.73  5030.3  771.62  5040.4  774.49
  5070.0  775.20  5080.8  775.07  5111.1  775.67  5121.2  776.08  5150.1  776.07
#Mann=3,-1,0
  4696.1    0.05       0  4991.9   0.033       0  5005.2    0.05       0
Bank Sta=4991.9,5005.2
Exp/Cntr=0.3,0.1

Type RM Length L Ch R = 1,6809,468,468,468
BEGIN DESCRIPTION:
Hackberry Creek 6.0
END DESCRIPTION:
XS GIS Cut Line= 3
      2295986.21      7096909.95      2296059.11      7096129.92
      2296079.00      7095659.97
#Sta/Elev= 30
  4222.4  777.37  4292.7  777.14  4312.7  776.34  4332.8  774.12  4594.0  770.71
  4875.2  773.20  4895.3  770.05  4915.4  769.34  4935.4  767.78  4945.5  766.10
  4950.7  761.47  4955.7  762.05  4965.6  760.32  4975.6  759.39  4996.6  759.28
  4998.5  758.78  5008.1  758.78  5009.9  759.28  5015.8  759.97  5045.8  767.68
  5075.8  772.37  5135.9  774.42  5205.9  779.63  5346.1  787.71  5376.1  790.30
  5436.1  794.35  5456.2  796.77  5466.2  798.63  5473.7  801.74  5476.2  801.74
#Mann=3,-1,0
  4222.4    0.05       0  4996.6    0.04       0  5009.9    0.05       0
Bank Sta=4996.6,5009.9
Exp/Cntr=0.3,0.1

Type RM Length L Ch R = 1,6341,521,521,521
BEGIN DESCRIPTION:
Mapping XS 36830c51
END DESCRIPTION:
XS GIS Cut Line= 2
      2296432.13      7096434.12      2296588.18      7095988.98
#Sta/Elev= 30
  4762.0  770.13  4872.3  770.33  4925.3  771.15  4935.9  769.97  4945.1  765.26
  4950.4  764.14  4957.1  759.56  4967.7  758.45  4981.4  758.99  4982.2  757.02
  4984.1  756.52  4993.7  756.52  4995.6  757.02  5007.1  758.00  5012.4  757.77
  5020.7  758.84  5031.3  762.24  5038.1  767.78  5043.4  766.73  5052.5  770.10
  5069.2  778.55  5074.4  778.41  5084.3  782.26  5094.9  785.33  5105.5  787.65
  5137.3  791.29  5156.9  792.83  5193.2  801.15  5200.8  802.33  5233.7  804.60
#Mann=3,-1,0
  4762.0    0.05       0  4982.2    0.04       0  4995.6    0.05       0
Bank Sta=4982.2,4995.6
Exp/Cntr=0.3,0.1

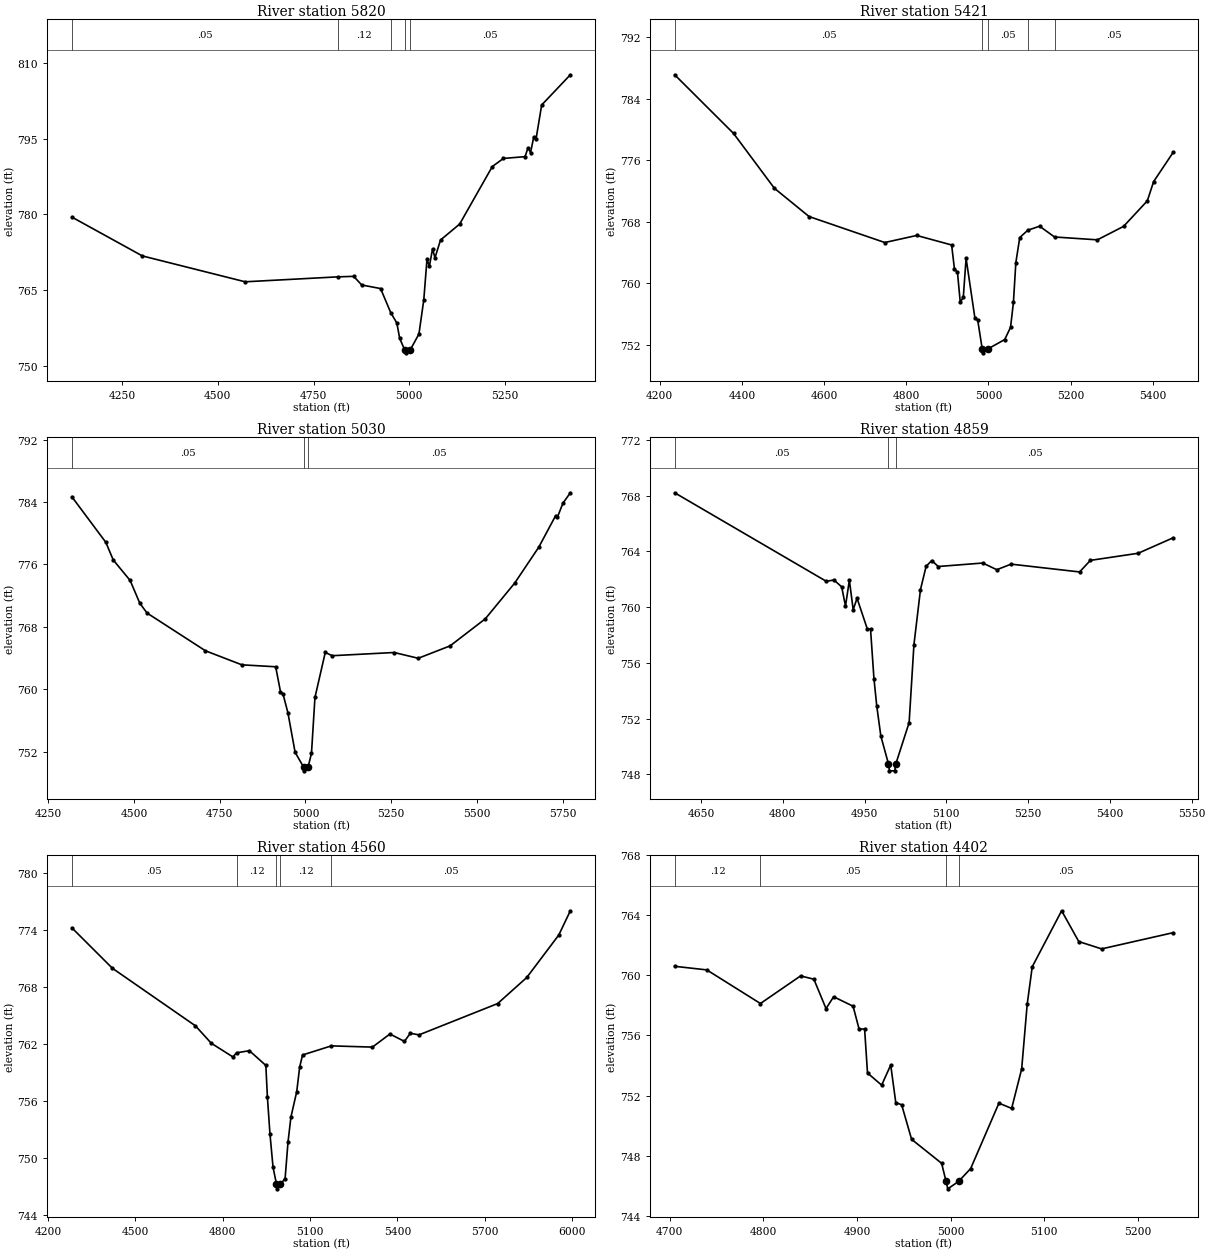
Type RM Length L Ch R = 1,5820,399,399,399
BEGIN DESCRIPTION:
Hackberry Creek 4.0
END DESCRIPTION:
XS GIS Cut Line= 3
      2296278.97      7097110.03      2296922.96      7096512.53
      2297178.48      7096174.40
#Sta/Elev= 30
  4118.7  779.45  4302.7  771.76  4571.4  766.63  4813.5  767.61  4854.9  767.71
  4875.9  766.00  4925.2  765.29  4951.9  760.49  4967.7  758.46  4975.1  755.42
  4988.7  753.05  4990.6  752.55  5002.1  753.05  5025.4  756.28  5038.1  763.05
  5046.4  771.06  5052.7  769.73  5061.0  773.15  5067.3  771.38  5081.8  774.91
  5131.8  778.07  5217.1  789.47  5246.2  791.08  5302.5  791.43  5310.7  793.21
  5317.0  792.22  5325.3  795.30  5331.6  795.03  5346.1  801.67  5421.0  807.66
#Mann=5,-1,0
  4118.7    0.05       0  4813.5    0.12       0  4951.9    0.05       0
  4988.7   0.033       0  5002.1    0.05       0
Bank Sta=4988.7,5002.1
Exp/Cntr=0.3,0.1

Type RM Length L Ch R = 1,5421,391,391,391
BEGIN DESCRIPTION:
Hackberry Creek 3.0
END DESCRIPTION:
XS GIS Cut Line= 3
      2296470.56      7097383.91      2297028.48      7096870.25
      2297268.53      7096483.93
#Sta/Elev= 30
  4236.3  787.11  4379.6  779.48  4478.9  772.35  4563.4  768.67  4747.7  765.29
  4825.4  766.21  4910.4  764.97  4917.2  761.87  4924.6  761.41  4931.4  757.51
  4938.8  758.17  4945.6  763.24  4967.1  755.45  4973.9  755.18  4984.9  751.44
  4986.8  750.94  4998.4  751.44  5039.6  752.67  5053.8  754.26  5060.8  757.50
  5066.7  762.68  5076.2  765.93  5095.7  766.89  5124.6  767.41  5160.8  766.01
  5265.1  765.64  5328.9  767.39  5386.7  770.71  5402.1  773.22  5449.5  777.01
#Mann=5,-1,0
  4236.3    0.05       0  4984.9   0.033       0  4998.4    0.05       0
  5095.7    0.12       0  5160.8    0.05       0
Bank Sta=4984.9,4998.4
Exp/Cntr=0.3,0.1

Type RM Length L Ch R = 1,5030,171,171,171
BEGIN DESCRIPTION:
Hackberry Creek 2.0
END DESCRIPTION:
XS GIS Cut Line= 3
      2296829.02      7097559.98      2297322.60      7097112.61
      2297397.67      7096328.35
#Sta/Elev= 30
  4318.6  784.68  4417.6  778.84  4439.2  776.58  4488.5  773.95  4516.9  771.01
  4537.9  769.77  4708.2  764.93  4814.3  763.13  4913.0  762.88  4927.1  759.68
  4934.6  759.36  4948.8  756.96  4969.7  751.91  4994.2  750.03  4996.1  749.53
  5007.7  750.03  5017.5  751.79  5027.6  758.94  5057.7  764.72  5077.8  764.30
  5258.6  764.71  5328.9  763.97  5421.8  765.56  5524.5  769.03  5610.2  773.61
  5680.5  778.22  5729.9  782.28  5734.9  782.06  5750.9  783.86  5772.6  785.20
#Mann=3,-1,0
  4318.6    0.05       0  4994.2   0.033       0  5007.7    0.05       0
Bank Sta=4994.2,5007.7
Exp/Cntr=0.3,0.1

Type RM Length L Ch R = 1,4859,299,299,299
BEGIN DESCRIPTION:
Mapping XS 6ee882f8
END DESCRIPTION:
XS GIS Cut Line= 3
      2297187.47      7097501.55      2297440.62      7097251.31
      2297591.48      7096713.84
#Sta/Elev= 30
  4601.8  768.20  4879.8  761.85  4893.9  761.94  4908.1  761.45  4915.1  760.07
  4922.2  761.93  4929.2  759.81  4936.3  760.63  4955.1  758.43  4961.0  758.43
  4967.3  754.86  4972.5  752.88  4979.9  750.75  4993.9  748.75  4995.8  748.25
  5005.5  748.25  5007.4  748.75  5031.8  751.71  5040.6  757.29  5052.6  761.25
  5063.0  762.93  5073.4  763.34  5085.1  762.91  5166.9  763.16  5192.6  762.68
  5218.8  763.08  5344.5  762.52  5364.2  763.35  5451.9  763.86  5516.0  764.97
#Mann=3,-1,0
  4601.8    0.05       0  4993.9   0.033       0  5007.4    0.05       0
Bank Sta=4993.9,5007.4
Exp/Cntr=0.3,0.1

Type RM Length L Ch R = 1,4560,158,158,158
BEGIN DESCRIPTION:
Hackberry Creek 1.0
END DESCRIPTION:
XS GIS Cut Line= 3
      2297027.90      7097618.25      2297698.87      7097380.30
      2297708.44      7096380.36
#Sta/Elev= 30
  4282.1  774.22  4421.2  769.96  4706.5  763.89  4760.7  762.06  4835.3  760.61
  4847.5  761.05  4891.8  761.27  4948.2  759.72  4953.5  756.41  4962.3  752.51
  4972.9  748.99  4984.7  747.21  4986.6  746.71  4998.2  747.21  5014.3  747.78
  5024.3  751.63  5034.3  754.27  5054.3  756.96  5064.3  759.54  5074.3  760.82
  5173.2  761.78  5314.3  761.65  5374.3  763.03  5424.3  762.25  5444.3  763.11
  5474.3  762.94  5744.4  766.24  5844.4  768.99  5954.4  773.47  5994.0  776.02
#Mann=5,-1,0
  4282.1    0.05       0  4847.5    0.12       0  4984.7    0.07       0
  4998.2    0.12       0  5173.2    0.05       0
Bank Sta=4984.7,4998.2
Exp/Cntr=0.3,0.1

Type RM Length L Ch R = 1,4402,298,298,298
BEGIN DESCRIPTION:
Mapping XS bc0113b2
END DESCRIPTION:
XS GIS Cut Line= 3
      2297677.92      7097696.96      2297801.87      7097538.97
      2297918.67      7097228.53
#Sta/Elev= 30
  4705.2  760.61  4739.5  760.37  4796.8  758.13  4839.7  759.97  4853.9  759.75
  4866.9  757.79  4875.0  758.58  4895.8  757.95  4902.2  756.43  4908.1  756.43
  4911.2  753.50  4926.3  752.69  4936.0  754.03  4941.4  751.53  4947.7  751.38
  4958.3  749.08  4990.4  747.48  4995.1  746.28  4997.0  745.78  5008.6  746.28
  5021.4  747.13  5051.6  751.49  5065.2  751.14  5075.9  753.77  5081.8  758.08
  5087.2  760.58  5118.6  764.31  5136.9  762.26  5161.3  761.77  5237.7  762.85
#Mann=4,-1,0
  4705.2    0.12       0  4796.8    0.05       0  4995.1   0.033       0
  5008.6    0.05       0
Bank Sta=4995.1,5008.6
Exp/Cntr=0.3,0.1

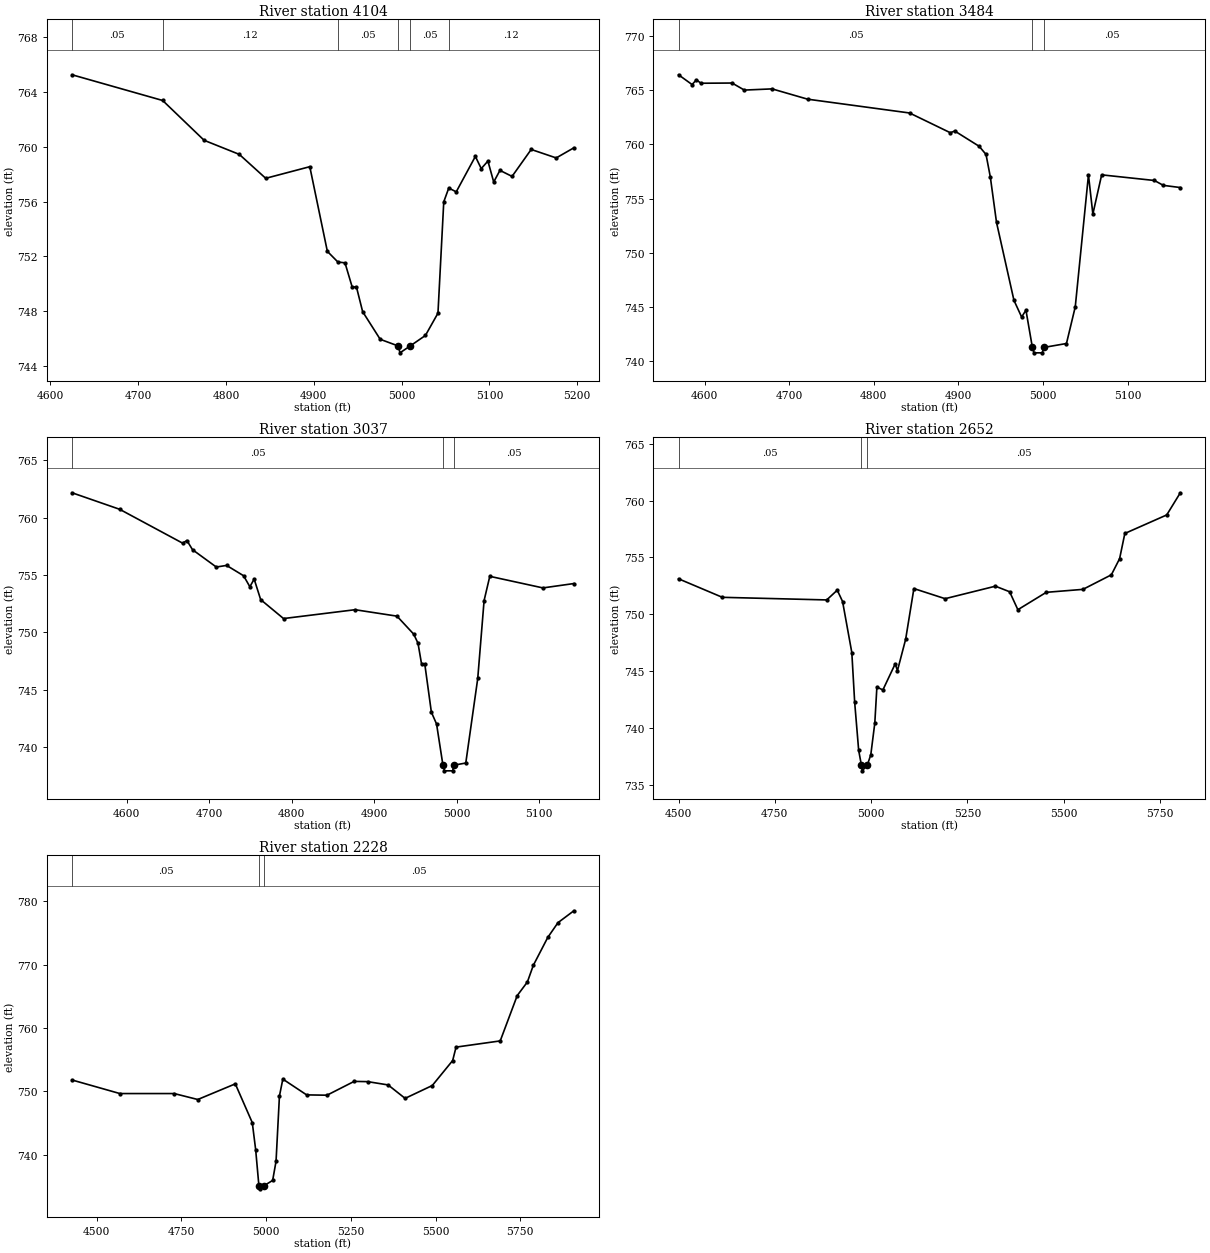
Type RM Length L Ch R = 1,4104,620,620,620
BEGIN DESCRIPTION:
Hackberry Creek 0.8
END DESCRIPTION:
XS GIS Cut Line= 3
      2297549.12      7097751.09      2297928.49      7097720.25
      2298054.50      7097576.74
#Sta/Elev= 30
  4624.6  765.27  4727.8  763.39  4775.0  760.48  4815.1  759.45  4845.2  757.70
  4895.4  758.55  4915.4  752.36  4927.4  751.58  4935.5  751.52  4943.6  749.77
  4948.6  749.74  4955.6  747.95  4975.6  745.93  4996.2  745.44  4998.1  744.94
  5009.7  745.44  5027.1  746.21  5041.4  747.84  5048.0  755.98  5053.7  756.99
  5062.2  756.71  5084.0  759.30  5090.7  758.41  5098.3  758.96  5104.9  757.43
  5112.0  758.28  5125.8  757.84  5147.6  759.81  5176.1  759.19  5196.2  759.93
#Mann=6,-1,0
  4624.6    0.05       0  4727.8    0.12       0  4927.4    0.05       0
  4996.2   0.033       0  5009.7    0.05       0  5053.7    0.12       0
Bank Sta=4996.2,5009.7
Exp/Cntr=0.3,0.1

Type RM Length L Ch R = 1,3484,447,447,447
BEGIN DESCRIPTION:
Hackberry Creek 0.6
END DESCRIPTION:
XS GIS Cut Line= 3
      2297763.29      7098219.88      2298179.72      7098120.71
      2298338.36      7098074.89
#Sta/Elev= 30
  4569.1  766.41  4585.1  765.51  4590.3  765.95  4595.5  765.63  4632.4  765.65
  4646.9  765.00  4679.7  765.11  4721.8  764.16  4842.2  762.89  4890.4  761.07
  4895.6  761.23  4924.5  759.82  4932.6  759.07  4937.7  756.99  4945.0  752.81
  4965.6  745.63  4974.7  744.09  4979.8  744.72  4987.4  741.29  4989.3  740.79
  4999.1  740.79  5001.1  741.29  5027.7  741.65  5038.1  745.03  5053.7  757.18
  5058.9  753.58  5069.3  757.19  5131.7  756.67  5142.2  756.22  5162.3  756.02
#Mann=3,-1,0
  4569.1    0.05       0  4987.4    0.04       0  5001.1    0.05       0
Bank Sta=4987.4,5001.1
Exp/Cntr=0.3,0.1

Type RM Length L Ch R = 1,3037,385,385,385
BEGIN DESCRIPTION:
Mapping XS e36a67a6
END DESCRIPTION:
XS GIS Cut Line= 3
      2297977.61      7098559.23      2298391.69      7098452.89
      2298535.73      7098343.81
#Sta/Elev= 30
  4533.7  762.17  4591.4  760.73  4667.7  757.78  4672.9  758.01  4679.7  757.21
  4708.5  755.70  4721.0  755.84  4741.6  754.94  4749.2  753.98  4754.4  754.65
  4762.3  752.86  4790.0  751.21  4876.7  751.98  4927.5  751.42  4947.8  749.85
  4953.0  749.06  4957.3  747.25  4961.2  747.25  4969.2  743.05  4975.5  742.02
  4983.2  738.44  4985.1  737.94  4994.9  737.94  4996.9  738.44  5010.9  738.62
  5025.4  745.99  5033.1  752.78  5040.0  754.89  5104.4  753.88  5141.9  754.26
#Mann=3,-1,0
  4533.7    0.05       0  4983.2    0.04       0  4996.9    0.05       0
Bank Sta=4983.2,4996.9
Exp/Cntr=0.3,0.1

Type RM Length L Ch R = 1,2652,424,424,424
BEGIN DESCRIPTION:
Mapping XS 1294e489
END DESCRIPTION:
XS GIS Cut Line= 3
      2298541.24      7099136.81      2298703.17      7098615.21
      2299093.30      7097966.55
#Sta/Elev= 30
  4500.0  753.12  4613.8  751.49  4884.8  751.26  4912.2  752.12  4926.0  751.12
  4950.0  746.63  4957.4  742.26  4967.8  738.02  4974.9  736.72  4976.9  736.22
  4990.2  736.72  4999.3  737.64  5009.7  740.43  5015.1  743.59  5030.7  743.34
  5062.6  745.63  5068.5  745.04  5089.8  747.80  5111.2  752.26  5192.3  751.37
  5322.9  752.47  5359.8  751.98  5381.2  750.40  5455.0  751.93  5550.2  752.19
  5624.0  753.47  5645.4  754.89  5659.0  757.11  5767.8  758.74  5803.1  760.69
#Mann=3,-1,0
  4500.0    0.05       0  4974.9    0.04       0  4990.2    0.05       0
Bank Sta=4974.9,4990.2
Exp/Cntr=0.3,0.1

Type RM Length L Ch R = 1,2228,0,0,0
BEGIN DESCRIPTION:
Hackberry Creek 0.4
END DESCRIPTION:
XS GIS Cut Line= 3
      2299054.53      7099250.83      2299081.77      7098726.49
      2299141.30      7097773.20
#Sta/Elev= 30
  4427.9  751.79  4568.9  749.65  4729.1  749.65  4798.7  748.71  4909.4  751.18
  4959.5  745.06  4969.5  740.78  4979.0  735.11  4981.0  734.61  4994.3  735.11
  5019.6  735.94  5029.6  738.96  5039.6  749.26  5049.6  751.93  5119.8  749.44
  5179.9  749.39  5260.0  751.57  5300.1  751.53  5360.2  751.01  5410.3  748.89
  5490.5  750.92  5550.6  754.86  5560.6  756.98  5690.9  757.96  5741.0  765.11
  5771.0  767.26  5788.5  769.89  5831.1  774.29  5861.2  776.62  5908.1  778.50
#Mann=3,-1,0
  4427.9    0.05       0  4979.0    0.04       0  4994.3    0.05       0
Bank Sta=4979,4994.3
Exp/Cntr=0.3,0.1

Chan Stop Cuts=-1