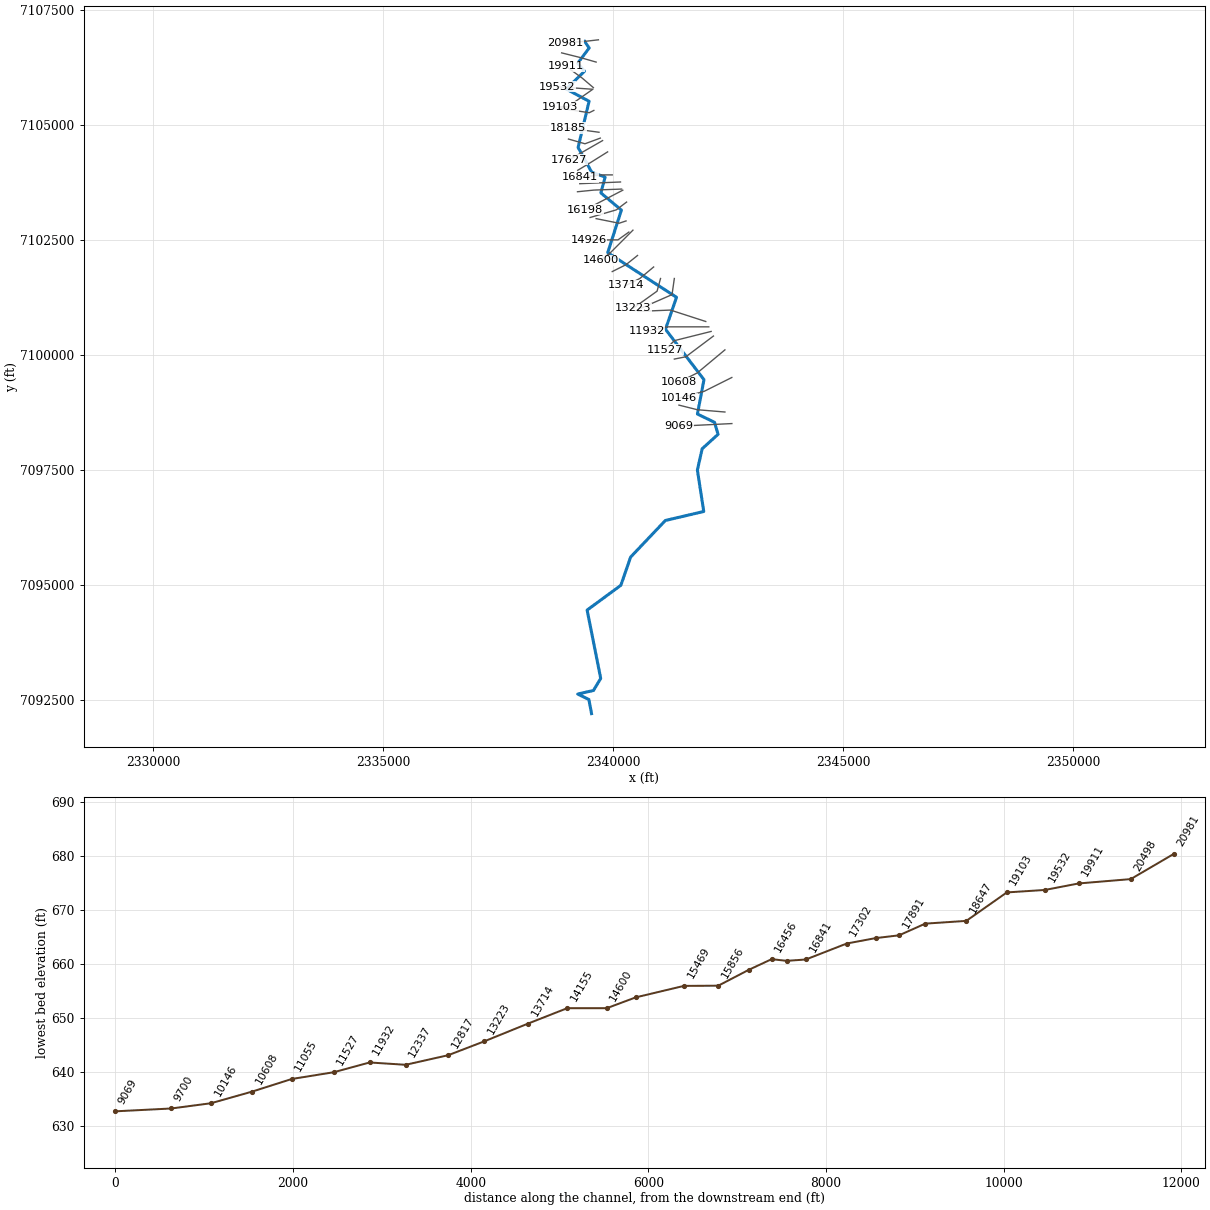
--- Hog Branch.prj (project) ---

Proj Title=Hog Branch Base Level Engineering
Current Plan=p01
Default Exp/Contr=0.3,0.1
English Units
Geom File=g01
Flow File=f01
Plan File=p01
Y Axis Title=Elevation
X Axis Title(PF)=Main Channel Distance
X Axis Title(XS)=Station
BEGIN DESCRIPTION:
Hog Branch
END DESCRIPTION:
DSS Export Rating Curves= 0
DSS Export Rating Curve Sorted= 0
DSS Export Volume Flow Curves= 0
DXF OffsetX= 0
DXF OffsetY= 0
DXF ScaleX= 1
DXF ScaleY= 10

--- Hog Branch.p01 (plan) ---

Plan Title=Multiple Run
Short Identifier=Multiple
Geom File=g01
Flow File=f01
Subcritical Flow
K Sum by GR= 0
Std Step Tol= 0.01
Critical Tol= 0.01
Num of Std Step Trials= 20
Max Error Tol= 0.3
Flow Tol Ratio= 0.001
Split Flow NTrial= 30
Split Flow Tol= 0.02
Split Flow Ratio= 0.02
Log Output Level= 0
Friction Slope Method= 1
Unsteady Friction Slope Method= 2
Unsteady Bridges Friction Slope Method= 1
Parabolic Critical Depth
Global Vel Dist=  1 , 1 , 1
Global Log Level= 0
CheckData=True
Encroach Param= -1, 0, 0, 0
BEGIN DESCRIPTION:
Multiple Run
END DESCRIPTION:

--- Hog Branch.f01 (steady flow) ---

Flow Title=Multiple
Number of Profiles=7
Profile Names=10-year,25-year,50-year,1pct_min,100-year,1pct_plu,500-year
River Rch & RM= Hog Branch,Reach-1,20981
    1219    1722    2148    1326    2646    5279    4029
River Rch & RM= Hog Branch,Reach-1,17627
    1455    2071    2596    1610    3212    6409    4936
River Rch & RM= Hog Branch,Reach-1,12337
    2627    3831    4882    3072    6129   12229    9698
River Rch & RM= Hog Branch,Reach-1,5981
    2641    3851    4906    3087    6159   12288    9740
River Rch & RM= Hog Branch,Reach-1,4562
    2827    4133    5275    3325    6633   13235   10527
River Rch & RM= Hog Branch,Reach-1,2668
    2838    4149    5297    3339    6662   13292   10574
Boundary for River Rch & Prof#=Hog Branch,Reach-1,1
Up Type=0
Dn Type=3
Dn Slope=0.00508
Boundary for River Rch & Prof#=Hog Branch,Reach-1,2
Up Type=0
Dn Type=3
Dn Slope=0.00508
Boundary for River Rch & Prof#=Hog Branch,Reach-1,3
Up Type=0
Dn Type=3
Dn Slope=0.00508
Boundary for River Rch & Prof#=Hog Branch,Reach-1,4
Up Type=0
Dn Type=3
Dn Slope=0.00508
Boundary for River Rch & Prof#=Hog Branch,Reach-1,5
Up Type=0
Dn Type=3
Dn Slope=0.00508
Boundary for River Rch & Prof#=Hog Branch,Reach-1,6
Up Type=0
Dn Type=3
Dn Slope=0.00508
Boundary for River Rch & Prof#=Hog Branch,Reach-1,7
Up Type=0
Dn Type=3
Dn Slope=0.00508

--- Hog Branch.g01 (geometry) ---

Geom Title=Existing Conditions

River Reach=Hog Branch,Reach-1
Reach XY= 30
      2339379.00      7106810.00      2339477.48      7106665.87
      2339228.46      7106334.88      2339376.02      7106161.43
      2338979.39      7105773.91      2339475.56      7105508.78
      2339236.81      7104506.59      2339534.41      7103965.18
      2339824.02      7103862.55      2339732.08      7103518.31
      2340178.12      7103145.31      2339880.85      7102221.14
      2341376.38      7101251.49      2341136.84      7100556.77
      2341973.54      7099462.45      2341830.96      7098715.88
      2342202.83      7098537.15      2342279.73      7098275.05
      2341934.46      7097962.45      2341830.21      7097500.41
      2341968.70      7096599.89      2341134.26      7096404.53
      2340379.00      7095610.00      2340166.04      7094996.37
      2339432.75      7094458.45      2339728.46      7092973.86
      2339570.83      7092712.78      2339228.45      7092634.87
      2339471.32      7092516.52      2339529.00      7092210.00

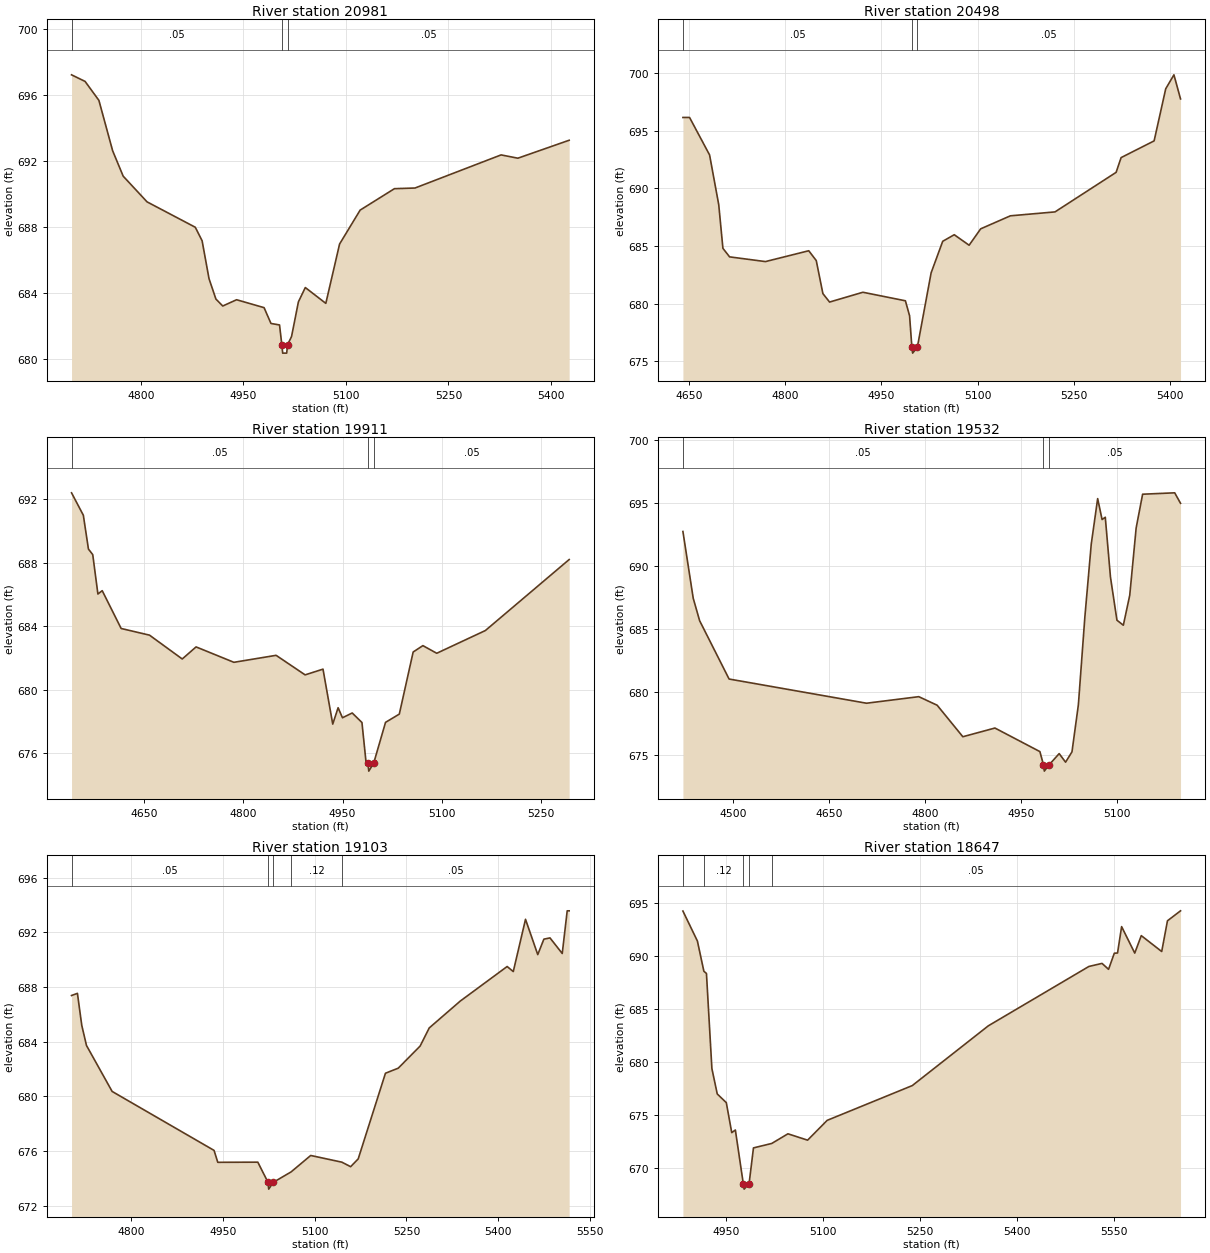
Type RM Length L Ch R = 1,20981,483,483,483
BEGIN DESCRIPTION:
Hog Branch 43.0
END DESCRIPTION:
XS GIS Cut Line= 3
      2339678.70      7106843.61      2339379.18      7106809.42
      2338954.23      7106777.62
#Sta/Elev= 30
  4698.9  697.24  4718.7  696.84  4738.9  695.69  4759.0  692.63  4774.4  691.09
  4809.3  689.53  4879.8  687.99  4889.8  687.17  4899.9  684.87  4910.0  683.63
  4920.0  683.21  4940.2  683.59  4980.4  683.11  4990.5  682.15  5003.0  682.06
  5006.4  680.85  5007.6  680.35  5013.5  680.35  5014.7  680.85  5020.6  681.36
  5030.6  683.46  5040.7  684.33  5070.7  683.37  5090.8  686.97  5120.9  689.03
  5171.0  690.33  5201.1  690.37  5327.0  692.38  5351.5  692.18  5426.5  693.27
#Mann=3,-1,0
  4698.9    0.05       0  5006.4    0.04       0  5014.7    0.05       0
Bank Sta=5006.4,5014.7
Exp/Cntr=0.3,0.1

Type RM Length L Ch R = 1,20498,587,587,587
BEGIN DESCRIPTION:
Hog Branch 42.0
END DESCRIPTION:
XS GIS Cut Line= 3
      2339629.03      7106359.99      2339279.00      7106460.00
      2338879.04      7106559.99
#Sta/Elev= 30
  4640.3  696.14  4650.7  696.14  4681.9  692.89  4696.2  688.57  4702.7  684.79
  4713.1  684.05  4769.0  683.64  4836.6  684.58  4848.3  683.73  4858.7  680.86
  4869.1  680.13  4921.1  680.98  4987.4  680.24  4993.9  678.94  4997.5  676.20
  4998.7  675.70  5006.0  676.20  5027.5  682.66  5045.6  685.40  5063.6  685.97
  5086.8  685.06  5104.8  686.48  5151.2  687.61  5220.8  687.95  5316.1  691.38
  5323.9  692.66  5375.4  694.11  5393.5  698.63  5406.3  699.84  5416.6  697.75
#Mann=3,-1,0
  4640.3    0.05       0  4997.5   0.033       0  5006.0    0.05       0
Bank Sta=4997.5,5006
Exp/Cntr=0.3,0.1

Type RM Length L Ch R = 1,19911,379,379,379
BEGIN DESCRIPTION:
Mapping XS 258c721a
END DESCRIPTION:
XS GIS Cut Line= 3
      2339569.31      7105805.01      2339324.08      7106013.72
      2338976.52      7106265.50
#Sta/Elev= 30
  4540.8  692.41  4558.6  691.00  4566.3  688.87  4572.8  688.52  4580.6  686.04
  4587.1  686.25  4615.7  683.87  4658.5  683.45  4707.9  681.95  4728.8  682.71
  4785.9  681.74  4849.6  682.18  4893.4  680.95  4920.4  681.31  4935.1  677.85
  4943.2  678.88  4949.8  678.25  4964.5  678.55  4979.2  677.95  4985.4  675.44
  4988.2  675.39  4989.5  674.89  4996.9  675.39  5014.8  677.96  5035.6  678.48
  5056.5  682.39  5071.2  682.79  5092.1  682.31  5165.5  683.74  5292.0  688.21
#Mann=3,-1,0
  4540.8    0.05       0  4988.2    0.04       0  4996.9    0.05       0
Bank Sta=4988.2,4996.9
Exp/Cntr=0.3,0.1

Type RM Length L Ch R = 1,19532,429,429,429
BEGIN DESCRIPTION:
Mapping XS 8bffe3a1
END DESCRIPTION:
XS GIS Cut Line= 2
      2339555.07      7105769.99      2338779.90      7105823.27
#Sta/Elev= 30
  4421.7  692.71  4437.8  687.41  4447.8  685.63  4493.8  681.00  4708.4  679.08
  4790.0  679.60  4818.7  678.92  4858.8  676.42  4908.9  677.11  4979.1  675.24
  4984.7  674.19  4986.0  673.69  4993.5  674.19  5009.2  675.08  5019.2  674.40
  5029.2  675.22  5039.2  678.96  5049.3  685.91  5059.3  691.71  5069.3  695.32
  5076.2  693.66  5081.2  693.84  5089.3  689.09  5099.4  685.67  5109.4  685.27
  5119.4  687.65  5129.4  692.99  5139.5  695.67  5189.6  695.78  5198.7  694.95
#Mann=3,-1,0
  4421.7    0.05       0  4984.7   0.033       0  4993.5    0.05       0
Bank Sta=4984.7,4993.5
Exp/Cntr=0.3,0.1

Type RM Length L Ch R = 1,19103,456,456,456
BEGIN DESCRIPTION:
Mapping XS 7a32df27
END DESCRIPTION:
XS GIS Cut Line= 3
      2339542.66      7105759.92      2339006.85      7105385.37
      2338847.69      7105386.03
#Sta/Elev= 30
  4702.9  687.38  4712.5  687.54  4719.6  685.20  4727.3  683.73  4769.2  680.37
  4935.7  676.06  4941.8  675.19  5007.2  675.20  5023.8  673.73  5025.0  673.23
  5032.6  673.73  5061.6  674.49  5093.6  675.69  5144.5  675.20  5158.8  674.87
  5171.2  675.44  5215.7  681.70  5236.6  682.07  5272.4  683.69  5287.2  685.01
  5337.8  686.97  5414.5  689.50  5424.5  689.13  5444.5  692.95  5464.5  690.37
  5474.5  691.50  5484.5  691.59  5504.5  690.45  5512.6  693.57  5515.8  693.57
#Mann=5,-1,0
  4702.9    0.05       0  5023.8    0.04       0  5032.6    0.05       0
  5061.6    0.12       0  5144.5    0.05       0
Bank Sta=5023.8,5032.6
Exp/Cntr=0.3,0.1

Type RM Length L Ch R = 1,18647,462,462,462
BEGIN DESCRIPTION:
Hog Branch 38.0
END DESCRIPTION:
XS GIS Cut Line= 3
      2339579.04      7105310.02      2339479.00      7105260.00
      2338828.99      7105360.00
#Sta/Elev= 30
  4883.9  694.20  4906.3  691.37  4916.3  688.52  4920.3  688.31  4928.7  679.34
  4937.0  676.94  4951.0  676.12  4959.4  673.29  4965.0  673.54  4977.3  668.46
  4978.6  667.96  4986.2  668.46  4993.0  671.85  5021.3  672.27  5046.3  673.18
  5076.7  672.58  5107.0  674.45  5238.6  677.73  5356.2  683.37  5511.7  688.97
  5532.0  689.26  5542.1  688.70  5551.0  690.22  5556.0  690.24  5562.3  692.73
  5582.6  690.23  5592.7  691.88  5624.3  690.38  5633.2  693.28  5653.4  694.22
#Mann=5,-1,0
  4883.9    0.05       0  4916.3    0.12       0  4977.3    0.07       0
  4986.2    0.12       0  5021.3    0.05       0
Bank Sta=4977.3,4986.2
Exp/Cntr=0.3,0.1

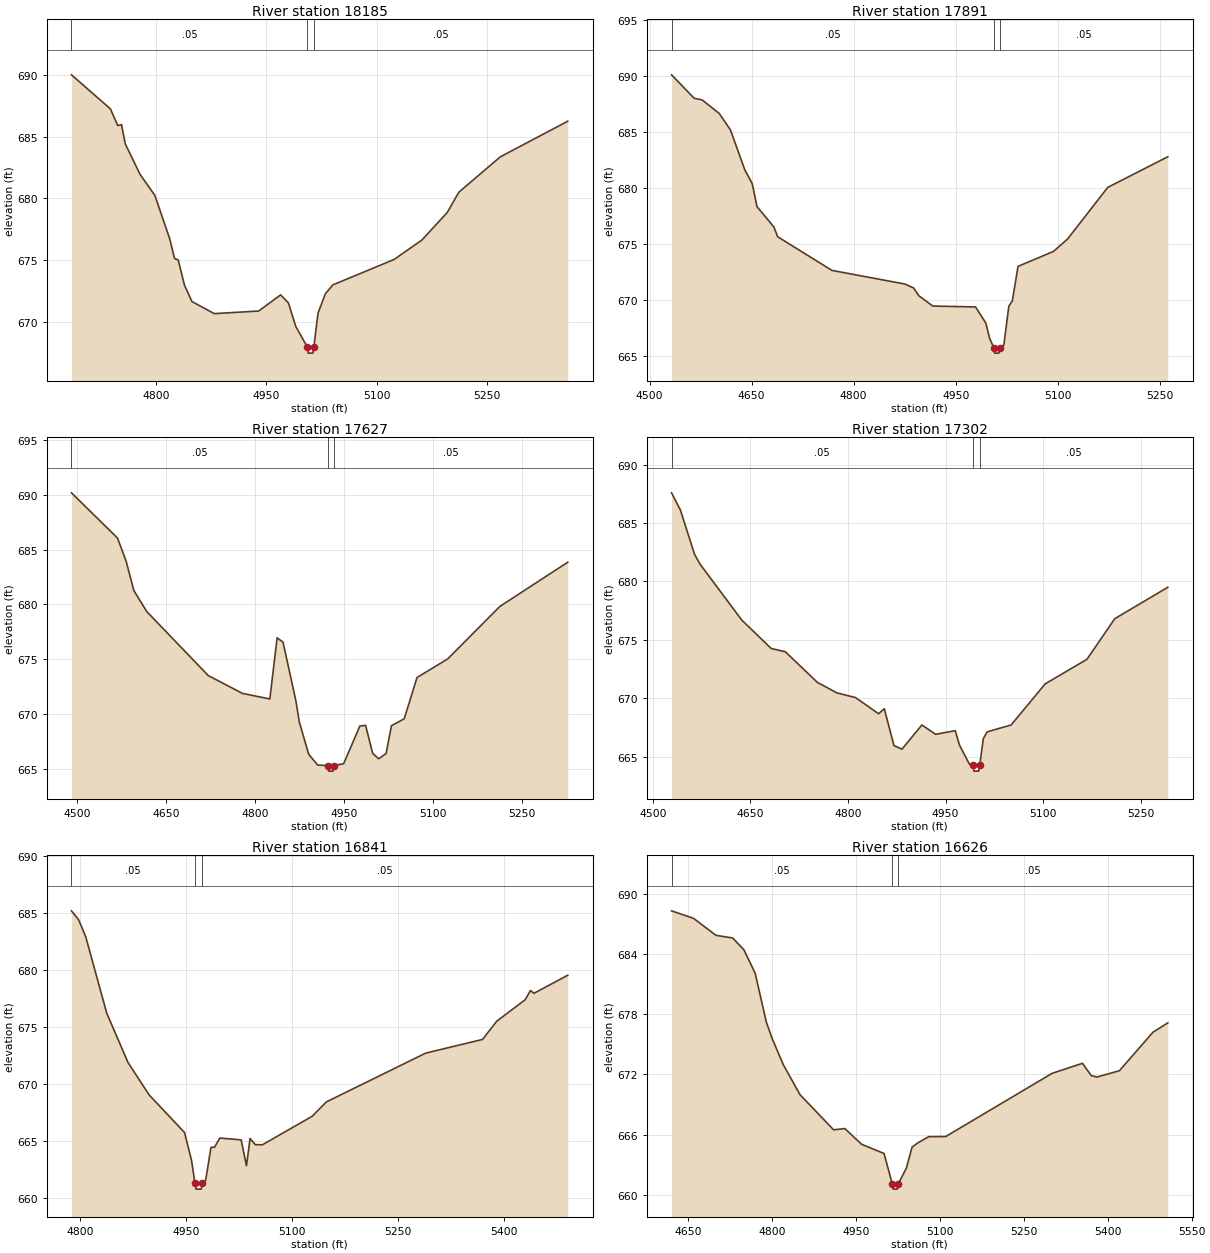
Type RM Length L Ch R = 1,18185,294,294,294
BEGIN DESCRIPTION:
Mapping XS b1c5aeb8
END DESCRIPTION:
XS GIS Cut Line= 2
      2339691.48      7104835.78      2339022.22      7104927.36
#Sta/Elev= 30
  4684.8  690.00  4737.8  687.24  4747.8  685.89  4752.9  685.97  4758.0  684.41
  4778.1  681.94  4798.3  680.23  4818.5  676.72  4825.1  675.12  4830.1  675.00
  4838.7  672.94  4848.8  671.63  4879.1  670.65  4939.6  670.86  4969.5  672.17
  4980.0  671.53  4990.1  669.61  5005.8  667.95  5007.1  667.45  5013.4  667.45
  5014.7  667.95  5020.4  670.69  5030.5  672.27  5040.6  672.98  5124.0  675.04
  5161.7  676.61  5196.2  678.84  5212.1  680.49  5268.4  683.35  5360.3  686.24
#Mann=3,-1,0
  4684.8    0.05       0  5005.8   0.033       0  5014.7    0.05       0
Bank Sta=5005.8,5014.7
Exp/Cntr=0.3,0.1

Type RM Length L Ch R = 1,17891,264,264,264
BEGIN DESCRIPTION:
Mapping XS 2595d0c3
END DESCRIPTION:
XS GIS Cut Line= 3
      2339720.11      7104709.17      2339386.61      7104585.87
      2339027.42      7104688.76
#Sta/Elev= 30
  4532.4  690.12  4565.6  688.03  4577.4  687.88  4602.5  686.67  4618.9  685.21
  4640.2  681.62  4650.9  680.42  4658.0  678.36  4682.8  676.54  4688.4  675.67
  4768.1  672.67  4874.8  671.46  4888.0  671.11  4895.9  670.40  4916.3  669.49
  4979.1  669.41  4994.2  667.97  4999.9  666.59  5005.9  665.79  5007.2  665.29
  5013.5  665.29  5014.8  665.79  5020.7  666.02  5028.0  669.48  5033.2  669.96
  5041.5  673.03  5093.5  674.36  5114.3  675.47  5173.4  680.08  5261.6  682.81
#Mann=3,-1,0
  4532.4    0.05       0  5005.9   0.033       0  5014.8    0.05       0
Bank Sta=5005.9,5014.8
Exp/Cntr=0.3,0.1

Type RM Length L Ch R = 1,17627,325,325,325
BEGIN DESCRIPTION:
Mapping XS 56d63618
END DESCRIPTION:
XS GIS Cut Line= 2
      2339768.94      7104655.00      2339043.50      7104238.69
#Sta/Elev= 30
  4490.9  690.19  4568.5  686.06  4583.1  683.93  4595.9  681.28  4617.7  679.35
  4721.4  673.50  4779.1  671.87  4825.2  671.36  4837.5  676.95  4847.5  676.54
  4869.1  671.20  4874.9  669.26  4890.7  666.31  4905.9  665.33  4922.9  665.27
  4924.3  664.77  4931.7  664.77  4933.1  665.27  4949.6  665.45  4977.0  668.89
  4986.6  668.95  4998.5  666.40  5008.6  665.90  5021.2  666.38  5030.2  668.92
  5051.7  669.55  5073.3  673.32  5125.0  675.02  5212.8  679.81  5327.3  683.85
#Mann=3,-1,0
  4490.9    0.05       0  4922.9   0.033       0  4933.1    0.05       0
Bank Sta=4922.9,4933.1
Exp/Cntr=0.3,0.1

Type RM Length L Ch R = 1,17302,461,461,461
BEGIN DESCRIPTION:
Hog Branch 35.0
END DESCRIPTION:
XS GIS Cut Line= 3
      2339879.00      7104410.00      2339479.00      7104160.00
      2339229.04      7104010.02
#Sta/Elev= 30
  4528.7  687.58  4542.3  686.11  4564.1  682.31  4572.9  681.45  4636.6  676.70
  4682.0  674.26  4703.8  673.98  4752.8  671.37  4782.8  670.47  4811.7  670.06
  4847.1  668.68  4855.9  669.11  4870.7  665.96  4883.1  665.65  4913.7  667.72
  4934.9  666.92  4965.0  667.23  4971.5  666.00  4986.8  664.36  4992.3  664.27
  4993.7  663.77  5001.1  663.77  5002.6  664.27  5008.2  666.55  5014.0  667.13
  5050.9  667.72  5103.4  671.24  5167.6  673.34  5210.3  676.81  5291.9  679.50
#Mann=3,-1,0
  4528.7    0.05       0  4992.3   0.033       0  5002.6    0.05       0
Bank Sta=4992.3,5002.6
Exp/Cntr=0.3,0.1

Type RM Length L Ch R = 1,16841,215,215,215
BEGIN DESCRIPTION:
Hog Branch 34.0
END DESCRIPTION:
XS GIS Cut Line= 3
      2339979.00      7103910.00      2339779.00      7103910.00
      2339278.99      7103860.00
#Sta/Elev= 30
  4787.9  685.22  4797.9  684.45  4807.9  682.98  4837.9  676.23  4867.9  671.92
  4897.9  669.07  4947.9  665.78  4957.9  663.32  4962.7  661.31  4964.1  660.81
  4971.6  660.81  4973.0  661.31  4977.9  661.61  4985.4  664.48  4990.4  664.48
  4997.9  665.29  5028.1  665.13  5035.6  662.86  5040.7  665.25  5048.2  664.71
  5058.2  664.70  5128.6  667.20  5148.7  668.46  5289.4  672.74  5369.8  673.94
  5389.9  675.54  5430.1  677.42  5437.6  678.23  5442.7  677.99  5490.4  679.57
#Mann=3,-1,0
  4787.9    0.05       0  4962.7    0.04       0  4973.0    0.05       0
Bank Sta=4962.7,4973
Exp/Cntr=0.3,0.1

Type RM Length L Ch R = 1,16626,170,170,170
BEGIN DESCRIPTION:
Mapping XS e94c4fc1
END DESCRIPTION:
XS GIS Cut Line= 2
      2340158.23      7103756.06      2339272.53      7103718.51
#Sta/Elev= 30
  4620.9  688.30  4660.2  687.55  4700.2  685.86  4730.2  685.59  4750.2  684.41
  4770.3  682.08  4790.3  677.19  4800.3  675.62  4820.3  672.99  4850.3  669.98
  4910.4  666.47  4930.4  666.60  4960.4  665.03  5000.5  664.11  5015.3  661.06
  5016.7  660.56  5024.2  660.56  5025.7  661.06  5040.5  662.67  5050.5  664.74
  5060.5  665.16  5080.5  665.79  5110.6  665.80  5300.7  672.10  5354.9  673.10
  5370.8  671.87  5380.8  671.73  5420.9  672.36  5480.9  676.20  5507.4  677.13
#Mann=3,-1,0
  4620.9    0.05       0  5015.3   0.033       0  5025.7    0.05       0
Bank Sta=5015.3,5025.7
Exp/Cntr=0.3,0.1

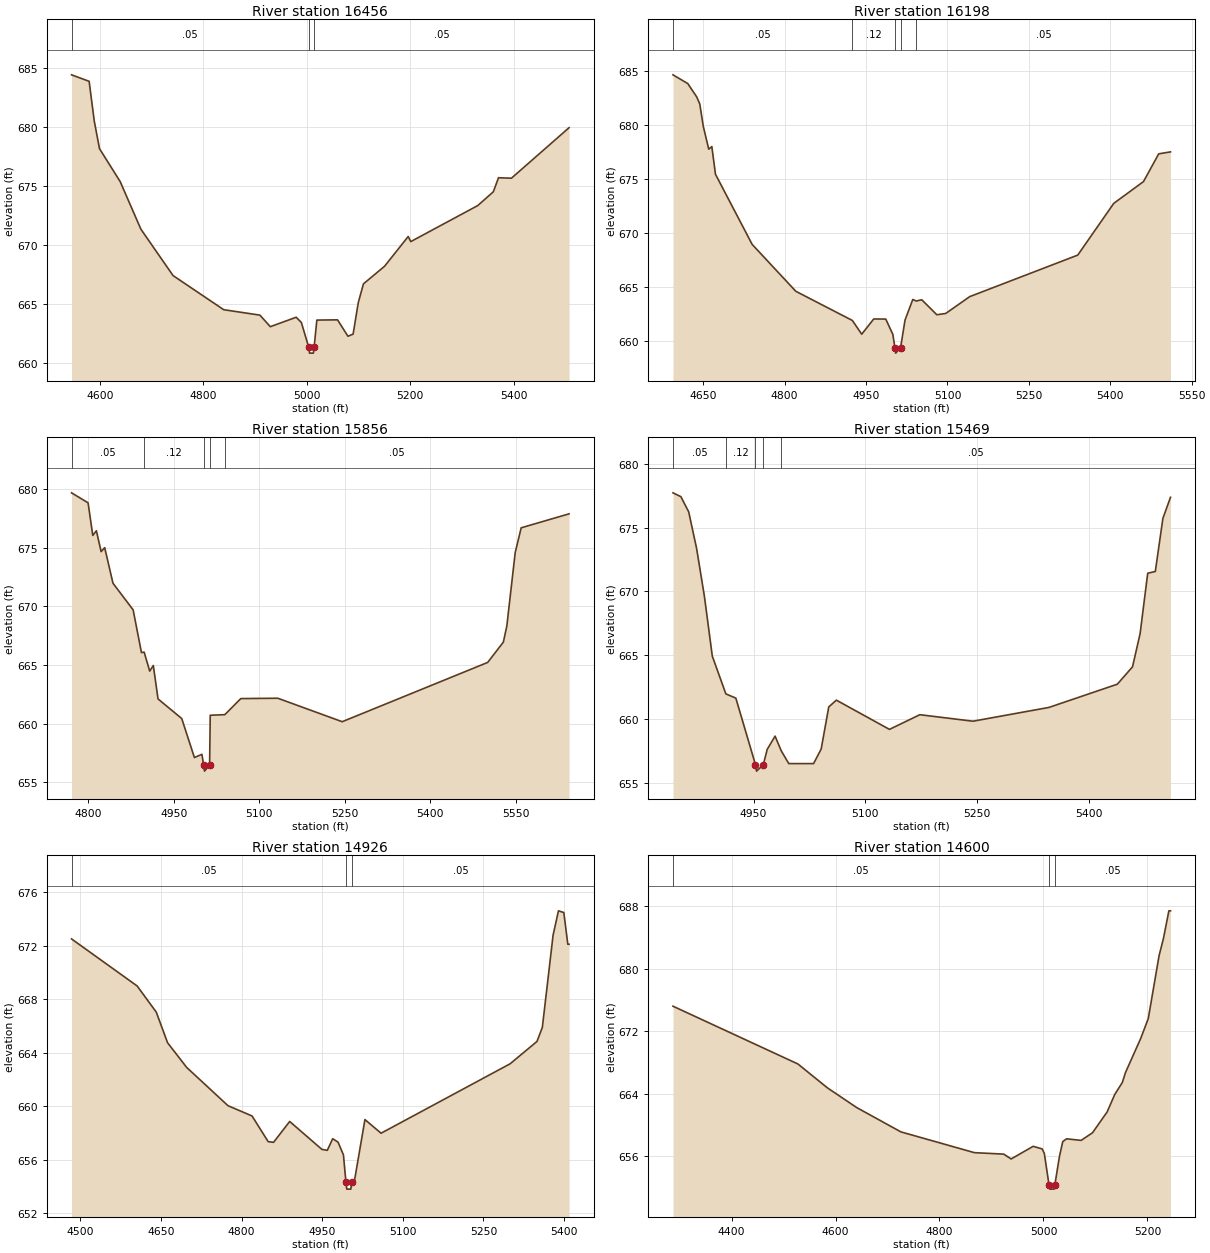
Type RM Length L Ch R = 1,16456,258,258,258
BEGIN DESCRIPTION:
Mapping XS 5d77bf66
END DESCRIPTION:
XS GIS Cut Line= 3
      2340183.00      7103602.04      2339582.45      7103580.17
      2339223.34      7103543.73
#Sta/Elev= 30
  4545.2  684.45  4579.2  683.90  4589.2  680.52  4599.2  678.20  4639.3  675.40
  4679.3  671.37  4741.5  667.44  4839.4  664.55  4909.4  664.09  4929.5  663.11
  4979.5  663.91  4989.5  663.47  5003.8  661.37  5005.3  660.87  5012.8  660.87
  5014.2  661.37  5019.5  663.67  5059.5  663.69  5079.6  662.30  5089.6  662.48
  5099.6  665.15  5109.6  666.74  5150.4  668.23  5196.1  670.75  5201.1  670.32
  5330.5  673.37  5360.7  674.54  5370.7  675.73  5395.7  675.69  5507.1  679.97
#Mann=3,-1,0
  4545.2    0.05       0  5003.8   0.033       0  5014.2    0.05       0
Bank Sta=5003.8,5014.2
Exp/Cntr=0.3,0.1

Type RM Length L Ch R = 1,16198,342,342,342
BEGIN DESCRIPTION:
Mapping XS e08ee175
END DESCRIPTION:
XS GIS Cut Line= 2
      2340208.49      7103577.47      2339394.85      7103154.97
#Sta/Elev= 30
  4594.2  684.64  4621.5  683.83  4638.0  682.59  4643.6  681.94  4650.0  679.88
  4660.1  677.76  4665.8  678.00  4672.5  675.44  4740.1  668.95  4820.6  664.61
  4924.8  661.91  4942.0  660.64  4964.1  662.05  4986.3  662.04  4999.3  660.63
  5003.2  659.39  5004.6  658.89  5013.6  659.39  5021.8  661.95  5036.1  663.85
  5042.6  663.71  5052.6  663.83  5080.4  662.44  5096.8  662.56  5141.1  664.12
  5340.1  667.96  5406.5  672.75  5461.2  674.76  5489.3  677.33  5511.0  677.51
#Mann=5,-1,0
  4594.2    0.05       0  4924.8    0.12       0  5003.2    0.07       0
  5013.6    0.12       0  5042.6    0.05       0
Bank Sta=5003.2,5013.6
Exp/Cntr=0.3,0.1

Type RM Length L Ch R = 1,15856,387,387,387
BEGIN DESCRIPTION:
Mapping XS 6e86738d
END DESCRIPTION:
XS GIS Cut Line= 3
      2340291.02      7103319.60      2340066.84      7103150.23
      2339498.31      7102984.69
#Sta/Elev= 30
  4770.7  679.67  4799.7  678.82  4808.0  676.04  4814.3  676.44  4822.6  674.66
  4828.9  675.00  4843.4  671.97  4878.8  669.70  4893.4  666.06  4898.1  666.10
  4907.9  664.48  4914.2  664.96  4922.5  662.11  4964.1  660.44  4986.3  657.12
  4999.5  657.39  5002.6  656.46  5004.0  655.96  5013.0  656.46  5014.1  660.72
  5039.7  660.77  5067.7  662.14  5132.7  662.17  5245.7  660.17  5501.0  665.22
  5528.5  666.95  5534.6  668.32  5549.3  674.58  5559.8  676.69  5643.8  677.88
#Mann=5,-1,0
  4770.7    0.05       0  4898.1    0.12       0  5002.6    0.07       0
  5013.0    0.12       0  5039.7    0.05       0
Bank Sta=5002.6,5013
Exp/Cntr=0.3,0.1

Type RM Length L Ch R = 1,15469,543,543,543
BEGIN DESCRIPTION:
Hog Branch 31.0
END DESCRIPTION:
XS GIS Cut Line= 3
      2340279.05      7102910.02      2340129.00      7102860.00
      2339628.97      7102960.01
#Sta/Elev= 30
  4841.8  677.72  4852.4  677.42  4862.9  676.23  4873.5  673.37  4884.0  669.61
  4894.6  664.93  4912.8  661.97  4926.2  661.64  4952.6  656.42  4954.0  655.92
  4963.1  656.42  4968.3  657.62  4978.9  658.66  4987.2  657.51  4997.3  656.51
  5030.6  656.51  5040.8  657.65  5051.0  660.95  5061.2  661.48  5132.5  659.19
  5173.3  660.34  5244.7  659.83  5346.7  660.91  5438.5  662.73  5458.9  664.09
  5469.1  666.69  5479.3  671.42  5489.5  671.56  5499.7  675.72  5509.9  677.37
#Mann=5,-1,0
  4841.8    0.05       0  4912.8    0.12       0  4952.6   0.033       0
  4963.1    0.12       0  4987.2    0.05       0
Bank Sta=4952.6,4963.1
Exp/Cntr=0.3,0.1

Type RM Length L Ch R = 1,14926,326,326,326
BEGIN DESCRIPTION:
Mapping XS 0957d1d4
END DESCRIPTION:
XS GIS Cut Line= 3
      2340340.42      7102668.10      2340103.68      7102498.59
      2339469.35      7102496.25
#Sta/Elev= 30
  4483.7  672.50  4605.8  668.98  4641.4  667.02  4662.3  664.74  4697.9  662.89
  4774.7  660.03  4819.5  659.26  4849.5  657.34  4859.5  657.29  4889.5  658.85
  4949.5  656.76  4959.5  656.69  4969.5  657.56  4979.5  657.30  4989.5  656.35
  4994.2  654.29  4995.7  653.79  5003.3  653.79  5004.8  654.29  5009.5  654.30
  5029.5  658.99  5059.5  657.97  5299.5  663.16  5349.5  664.83  5359.5  665.88
  5379.5  672.78  5389.5  674.60  5399.5  674.47  5406.9  672.10  5409.2  672.10
#Mann=3,-1,0
  4483.7    0.05       0  4994.2   0.033       0  5004.8    0.05       0
Bank Sta=4994.2,5004.8
Exp/Cntr=0.3,0.1

Type RM Length L Ch R = 1,14600,445,445,445
BEGIN DESCRIPTION:
Hog Branch 30.0
END DESCRIPTION:
XS GIS Cut Line= 3
      2340428.98      7102709.98      2339929.00      7102210.00
      2339728.98      7102059.99
#Sta/Elev= 30
  4287.3  675.21  4527.7  667.81  4584.3  664.76  4640.8  662.23  4725.7  659.12
  4867.1  656.46  4923.7  656.27  4937.8  655.65  4980.2  657.27  4997.5  656.94
  5001.7  656.36  5010.8  652.29  5012.3  651.79  5020.3  651.79  5021.8  652.29
  5030.8  655.98  5037.1  657.87  5044.4  658.23  5072.5  658.03  5094.4  659.01
  5122.5  661.67  5137.1  663.90  5151.7  665.44  5157.9  666.73  5187.1  671.08
  5201.7  673.64  5222.5  681.70  5230.8  683.87  5241.3  687.42  5244.4  687.42
#Mann=3,-1,0
  4287.3    0.05       0  5010.8   0.033       0  5021.8    0.05       0
Bank Sta=5010.8,5021.8
Exp/Cntr=0.3,0.1

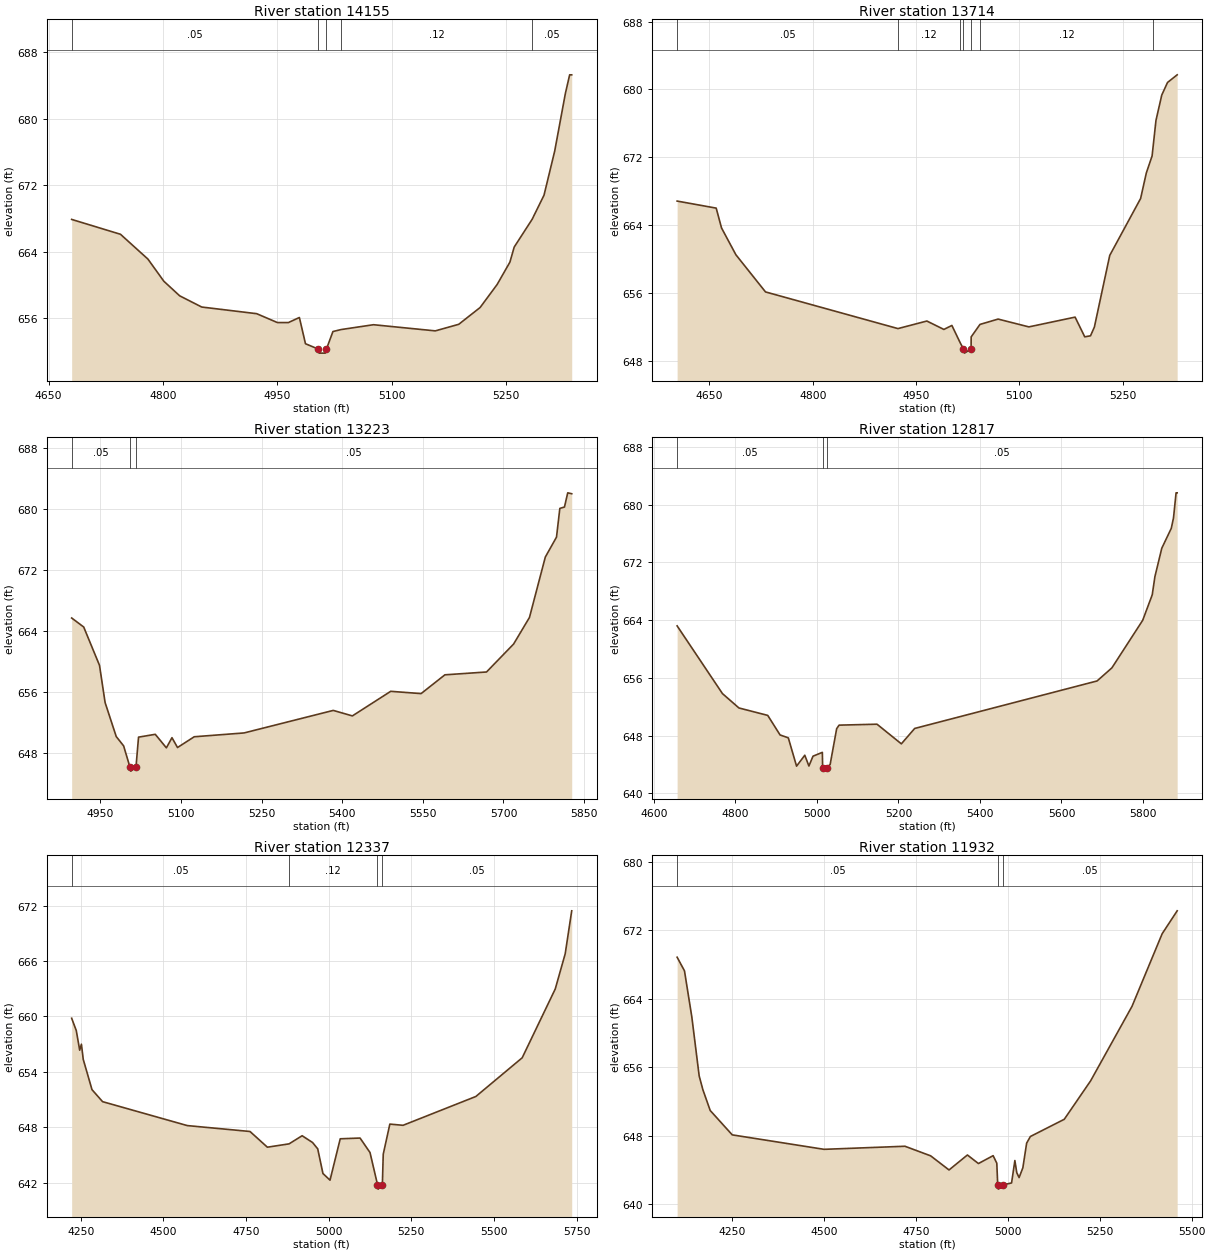
Type RM Length L Ch R = 1,14155,441,441,441
BEGIN DESCRIPTION:
Hog Branch 29.0
END DESCRIPTION:
XS GIS Cut Line= 3
      2340528.98      7102159.99      2340279.00      7101960.00
      2339979.04      7101810.02
#Sta/Elev= 30
  4680.3  667.89  4744.3  666.10  4780.3  663.11  4801.1  660.45  4821.9  658.69
  4850.8  657.34  4922.8  656.54  4950.0  655.47  4964.4  655.47  4978.8  656.08
  4986.8  652.92  5003.3  652.29  5004.8  651.79  5012.8  651.79  5014.3  652.29
  5022.8  654.39  5033.6  654.63  5075.9  655.21  5157.0  654.47  5187.7  655.26
  5215.7  657.28  5238.0  660.05  5254.8  662.75  5260.4  664.56  5283.9  667.90
  5299.5  670.81  5313.5  676.12  5327.5  683.06  5333.1  685.30  5335.8  685.30
#Mann=5,-1,0
  4680.3    0.05       0  5003.3   0.033       0  5014.3    0.05       0
  5033.6    0.12       0  5283.9    0.05       0
Bank Sta=5003.3,5014.3
Exp/Cntr=0.3,0.1

Type RM Length L Ch R = 1,13714,491,491,491
BEGIN DESCRIPTION:
Hog Branch 28.0
END DESCRIPTION:
XS GIS Cut Line= 3
      2340879.03      7101910.02      2340579.00      7101660.00
      2340278.96      7101509.98
#Sta/Elev= 30
  4603.1  666.85  4659.8  666.02  4667.6  663.68  4688.4  660.53  4731.4  656.15
  4923.7  651.83  4965.7  652.72  4990.4  651.73  5002.0  652.20  5014.2  650.14
  5018.8  649.44  5020.4  648.94  5029.9  649.44  5030.0  650.85  5042.8  652.32
  5069.1  652.95  5113.8  652.03  5180.9  653.18  5194.9  650.86  5203.3  650.98
  5208.9  652.01  5231.2  660.45  5276.0  667.15  5284.3  670.16  5292.7  672.17
  5294.3  673.36  5298.3  676.34  5306.7  679.33  5315.1  680.82  5329.1  681.72
#Mann=7,-1,0
  4603.1    0.05       0  4923.7    0.12       0  5014.2    0.05       0
  5018.8    0.07       0  5029.9    0.05       0  5042.8    0.12       0
  5294.3    0.05       0
Bank Sta=5018.8,5029.9
Exp/Cntr=0.3,0.1

Type RM Length L Ch R = 1,13223,406,406,406
BEGIN DESCRIPTION:
Hog Branch 27.0
END DESCRIPTION:
XS GIS Cut Line= 3
      2341029.00      7101659.99      2340954.00      7101385.00
      2340429.01      7101010.00
#Sta/Elev= 30
  4896.7  665.71  4919.1  664.53  4948.5  659.51  4958.9  654.64  4979.6  650.19
  4993.4  648.96  5005.2  646.16  5006.7  645.66  5016.3  646.16  5021.1  650.11
  5052.2  650.48  5072.9  648.71  5083.3  650.04  5093.6  648.75  5124.7  650.16
  5217.4  650.66  5383.3  653.61  5418.9  652.89  5490.2  656.11  5546.7  655.81
  5591.0  658.27  5668.4  658.64  5718.8  662.30  5748.3  665.78  5777.8  673.69
  5798.6  676.30  5804.8  680.06  5813.4  680.24  5819.5  682.10  5826.9  681.98
#Mann=3,-1,0
  4896.7    0.05       0  5005.2   0.033       0  5016.3    0.05       0
Bank Sta=5005.2,5016.3
Exp/Cntr=0.3,0.1

Type RM Length L Ch R = 1,12817,480,480,480
BEGIN DESCRIPTION:
Hog Branch 26.0
END DESCRIPTION:
XS GIS Cut Line= 3
      2341329.01      7101660.05      2341279.00      7101310.00
      2340479.01      7100960.00
#Sta/Elev= 30
  4657.1  663.21  4768.3  653.83  4808.7  651.84  4879.4  650.81  4909.7  648.10
  4929.9  647.70  4950.1  643.78  4970.3  645.29  4980.4  643.80  4990.5  645.16
  5013.4  645.69  5014.1  643.59  5015.6  643.09  5025.2  643.59  5032.5  644.01
  5048.5  648.97  5054.4  649.46  5147.5  649.59  5207.2  646.87  5239.9  649.00
  5687.4  655.58  5723.7  657.39  5799.3  663.98  5822.7  667.51  5829.3  670.03
  5846.1  673.96  5869.5  676.73  5874.9  678.17  5881.2  681.64  5883.9  681.64
#Mann=3,-1,0
  4657.1    0.05       0  5014.1   0.033       0  5025.2    0.05       0
Bank Sta=5014.1,5025.2
Exp/Cntr=0.3,0.1

Type RM Length L Ch R = 1,12337,405,405,405
BEGIN DESCRIPTION:
Mapping XS b1849e3b
END DESCRIPTION:
XS GIS Cut Line= 3
      2342012.35      7100726.00      2341244.73      7100974.22
      2340539.28      7100945.27
#Sta/Elev= 30
  4222.6  659.81  4236.6  658.47  4246.9  656.35  4252.1  657.00  4257.6  655.36
  4284.1  652.08  4316.1  650.78  4572.3  648.19  4762.1  647.55  4814.7  645.85
  4880.3  646.21  4919.8  647.09  4951.3  646.36  4967.0  645.67  4982.8  643.00
  5004.2  642.28  5035.1  646.76  5095.1  646.84  5125.2  645.27  5147.8  641.81
  5149.8  641.31  5162.6  641.81  5165.2  645.09  5185.2  648.35  5225.2  648.22
  5445.4  651.34  5585.6  655.53  5685.6  662.98  5715.7  666.79  5735.4  671.44
#Mann=4,-1,0
  4222.6    0.05       0  4880.3    0.12       0  5147.8    0.07       0
  5162.6    0.05       0
Bank Sta=5147.8,5162.6
Exp/Cntr=0.3,0.1

Type RM Length L Ch R = 1,11932,405,405,405
BEGIN DESCRIPTION:
Hog Branch 24.0
END DESCRIPTION:
XS GIS Cut Line= 3
      2342078.96      7100610.00      2341179.00      7100610.00
      2340729.04      7100510.01
#Sta/Elev= 30
  4099.8  668.84  4119.8  667.25  4139.8  661.86  4159.8  654.97  4169.8  653.37
  4189.8  650.93  4249.8  648.08  4499.8  646.39  4719.8  646.75  4789.8  645.63
  4839.8  643.98  4889.8  645.73  4919.8  644.73  4959.8  645.65  4969.8  644.77
  4972.3  642.24  4974.3  641.74  4987.2  642.24  5010.0  642.46  5019.0  645.08
  5024.1  643.67  5030.5  643.09  5040.7  644.23  5051.0  647.11  5061.2  647.89
  5153.4  649.90  5225.1  654.39  5337.8  663.10  5419.8  671.58  5460.7  674.26
#Mann=3,-1,0
  4099.8    0.05       0  4972.3   0.033       0  4987.2    0.05       0
Bank Sta=4972.3,4987.2
Exp/Cntr=0.3,0.1

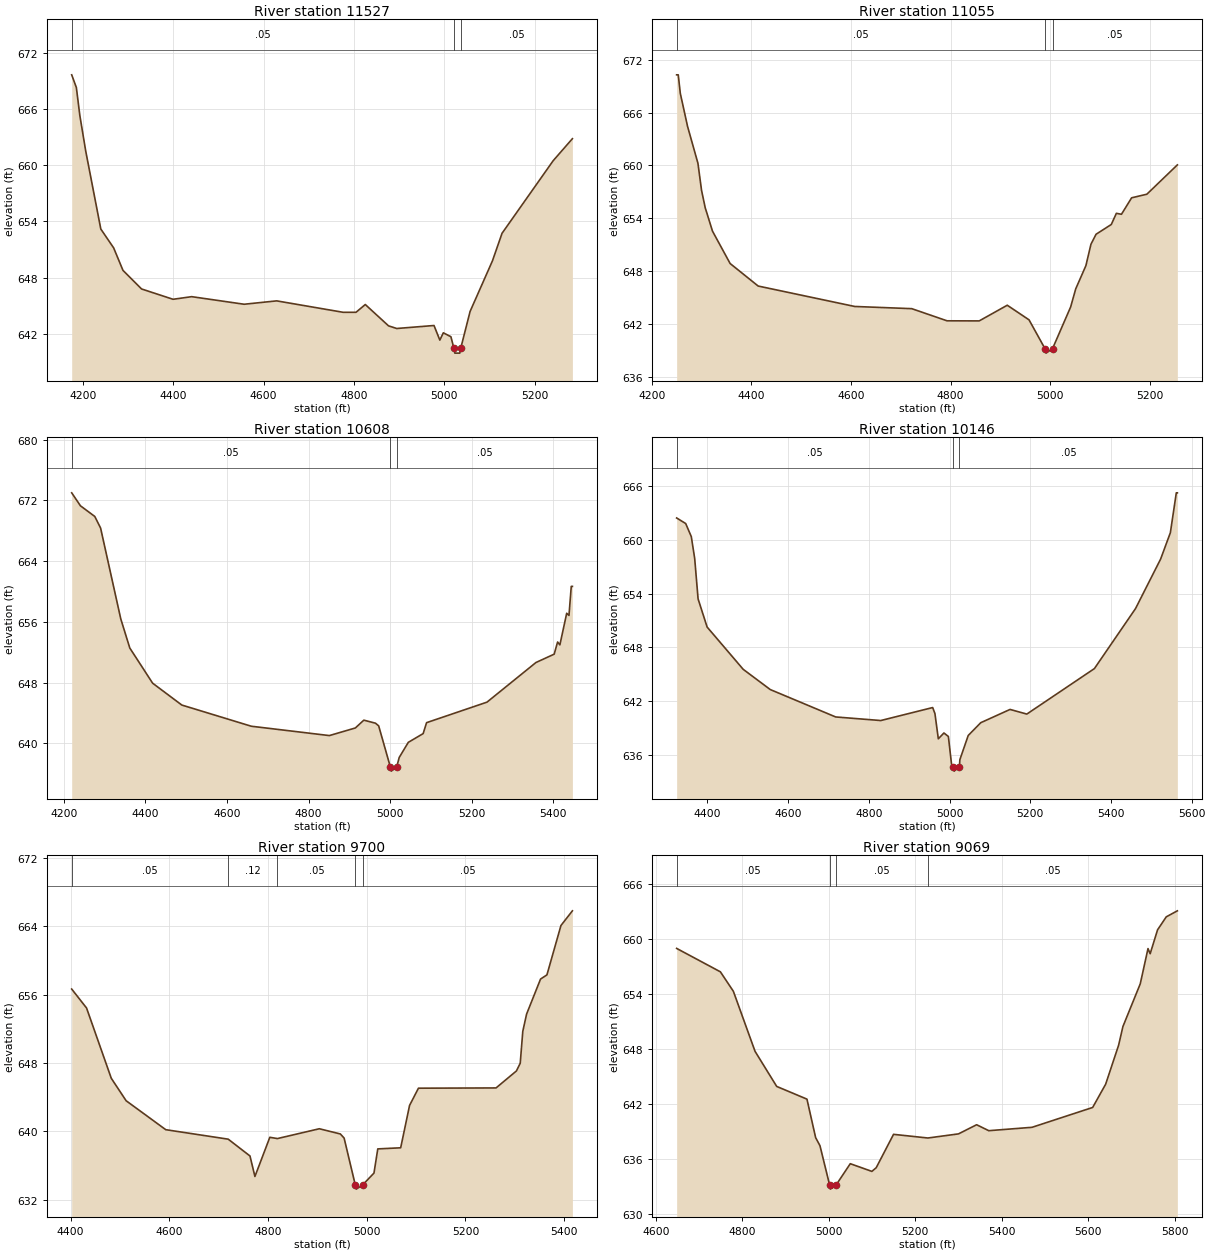
Type RM Length L Ch R = 1,11527,472,472,472
BEGIN DESCRIPTION:
Hog Branch 23.0
END DESCRIPTION:
XS GIS Cut Line= 3
      2342129.00      7100510.00      2341329.00      7100310.00
      2341128.98      7100109.98
#Sta/Elev= 30
  4175.6  669.65  4185.9  668.30  4193.6  665.31  4206.5  661.54  4240.0  653.18
  4268.4  651.17  4289.0  648.77  4330.2  646.78  4399.8  645.68  4441.0  645.96
  4557.0  645.15  4629.1  645.51  4776.0  644.29  4804.4  644.29  4825.0  645.12
  4876.5  642.84  4894.6  642.56  4977.0  642.88  4989.9  641.32  4997.6  642.10
  5014.4  641.68  5021.1  640.43  5023.1  639.93  5034.0  639.93  5036.0  640.43
  5056.8  644.38  5106.3  649.79  5127.5  652.73  5240.6  660.48  5283.1  662.83
#Mann=3,-1,0
  4175.6    0.05       0  5021.1   0.033       0  5036.0    0.05       0
Bank Sta=5021.1,5036
Exp/Cntr=0.3,0.1

Type RM Length L Ch R = 1,11055,447,447,447
BEGIN DESCRIPTION:
Hog Branch 22.0
END DESCRIPTION:
XS GIS Cut Line= 3
      2342179.03      7100410.02      2341579.00      7099960.00
      2341328.99      7099910.00
#Sta/Elev= 30
  4250.0  670.29  4253.2  670.29  4257.3  668.19  4271.9  664.43  4292.7  660.25
  4300.0  657.16  4307.3  655.20  4321.9  652.54  4357.3  648.86  4413.6  646.30
  4607.3  643.98  4721.9  643.73  4792.7  642.35  4857.3  642.34  4913.6  644.12
  4957.3  642.46  4989.4  639.18  4991.4  638.68  5004.4  639.18  5040.8  643.92
  5051.0  645.98  5071.4  648.61  5081.6  651.05  5091.8  652.18  5122.4  653.29
  5132.6  654.56  5142.8  654.45  5163.2  656.32  5193.8  656.73  5255.0  660.06
#Mann=3,-1,0
  4250.0    0.05       0  4989.4   0.033       0  5004.4    0.05       0
Bank Sta=4989.4,5004.4
Exp/Cntr=0.3,0.1

Type RM Length L Ch R = 1,10608,462,462,462
BEGIN DESCRIPTION:
Hog Branch 21.0
END DESCRIPTION:
XS GIS Cut Line= 3
      2342428.99      7100109.99      2341829.00      7099610.00
      2341429.02      7099410.01
#Sta/Elev= 30
  4219.0  672.98  4240.5  671.27  4275.6  669.87  4289.9  668.34  4339.4  656.38
  4361.5  652.55  4417.5  647.92  4489.1  645.04  4659.6  642.25  4851.0  641.02
  4914.7  642.02  4935.6  643.05  4964.2  642.65  4972.0  642.30  5000.9  636.84
  5002.9  636.34  5015.9  636.84  5022.4  638.14  5044.7  640.13  5081.1  641.28
  5089.5  642.72  5237.6  645.42  5357.8  650.64  5402.5  651.74  5410.9  653.34
  5416.5  652.96  5433.2  657.12  5438.8  656.84  5444.4  660.66  5447.2  660.66
#Mann=3,-1,0
  4219.0    0.05       0  5000.9    0.04       0  5015.9    0.05       0
Bank Sta=5000.9,5015.9
Exp/Cntr=0.3,0.1

Type RM Length L Ch R = 1,10146,446,446,446
BEGIN DESCRIPTION:
Hog Branch 20.0
END DESCRIPTION:
XS GIS Cut Line= 3
      2342578.99      7099510.00      2341979.00      7099210.00
      2341429.00      7099060.00
#Sta/Elev= 30
  4323.7  662.46  4346.1  661.84  4360.0  660.38  4368.4  657.94  4376.8  653.43
  4399.2  650.28  4488.6  645.56  4555.7  643.30  4717.8  640.24  4829.6  639.84
  4958.2  641.29  4963.8  640.62  4972.2  637.80  4986.1  638.45  4997.1  638.06
  5004.9  634.98  5009.5  634.69  5011.5  634.19  5024.5  634.69  5025.6  635.47
  5046.3  638.17  5077.4  639.60  5150.0  641.08  5191.5  640.56  5359.0  645.64
  5460.9  652.34  5523.1  657.87  5547.3  660.82  5562.0  665.27  5564.6  665.27
#Mann=3,-1,0
  4323.7    0.05       0  5009.5   0.033       0  5024.5    0.05       0
Bank Sta=5009.5,5024.5
Exp/Cntr=0.3,0.1

Type RM Length L Ch R = 1,9700,631,631,631
BEGIN DESCRIPTION:
Hog Branch 19.0
END DESCRIPTION:
XS GIS Cut Line= 3
      2342428.96      7098760.00      2341829.00      7098810.00
      2341428.96      7098910.01
#Sta/Elev= 30
  4402.3  656.65  4432.4  654.43  4482.5  646.20  4512.6  643.57  4592.9  640.18
  4719.4  639.07  4763.5  637.10  4773.5  634.70  4803.7  639.29  4819.0  639.14
  4904.0  640.29  4946.6  639.68  4954.2  639.20  4976.8  633.72  4978.8  633.22
  4991.8  633.72  5014.7  635.10  5022.4  637.93  5068.8  638.06  5086.8  643.02
  5104.8  645.04  5262.0  645.07  5303.3  647.06  5311.0  647.96  5316.2  651.70
  5323.9  653.72  5352.2  657.82  5365.1  658.31  5393.5  664.09  5416.7  665.81
#Mann=5,-1,0
  4402.3    0.05       0  4719.4    0.12       0  4819.0    0.05       0
  4976.8   0.033       0  4991.8    0.05       0
Bank Sta=4976.8,4991.8
Exp/Cntr=0.3,0.1

Type RM Length L Ch R = 1,9069,135,135,135
BEGIN DESCRIPTION:
Mapping XS 5c682eed
END DESCRIPTION:
XS GIS Cut Line= 2
      2342580.07      7098509.34      2341423.30      7098451.77
#Sta/Elev= 30
  4648.4  659.01  4749.6  656.45  4779.6  654.32  4829.7  647.76  4879.8  643.92
  4949.8  642.53  4969.9  638.32  4979.9  637.44  5002.0  633.19  5004.0  632.69
  5017.9  633.19  5050.0  635.47  5100.0  634.63  5110.0  635.03  5150.1  638.68
  5229.5  638.28  5300.3  638.73  5342.3  639.73  5370.4  639.08  5470.5  639.45
  5610.7  641.62  5640.7  644.16  5670.7  648.42  5680.7  650.47  5720.8  655.14
  5738.7  658.99  5743.7  658.43  5760.8  661.04  5780.9  662.46  5806.6  663.12
#Mann=4,-1,0
  4648.4    0.05       0  5002.0   0.033       0  5017.9    0.05       0
  5229.5    0.05       0
Bank Sta=5002,5017.9
Exp/Cntr=0.3,0.1