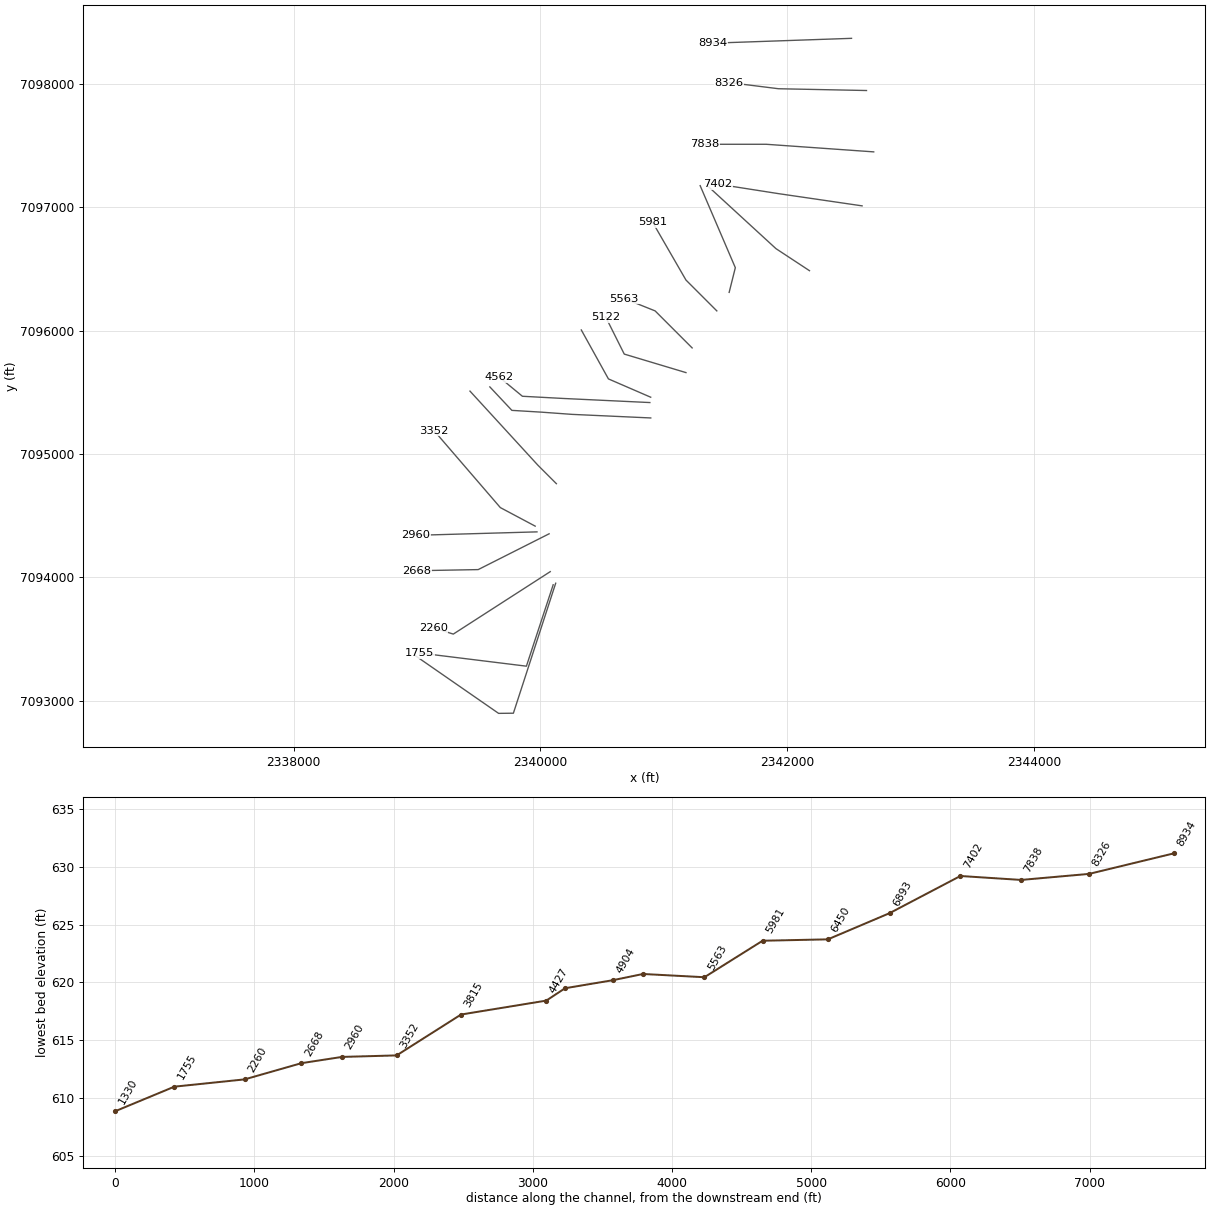
HEC-RAS study Hog Branch.prj: Hog Branch Base Level Engineering

--- Hog Branch.g01 (geometry) --- (continued)

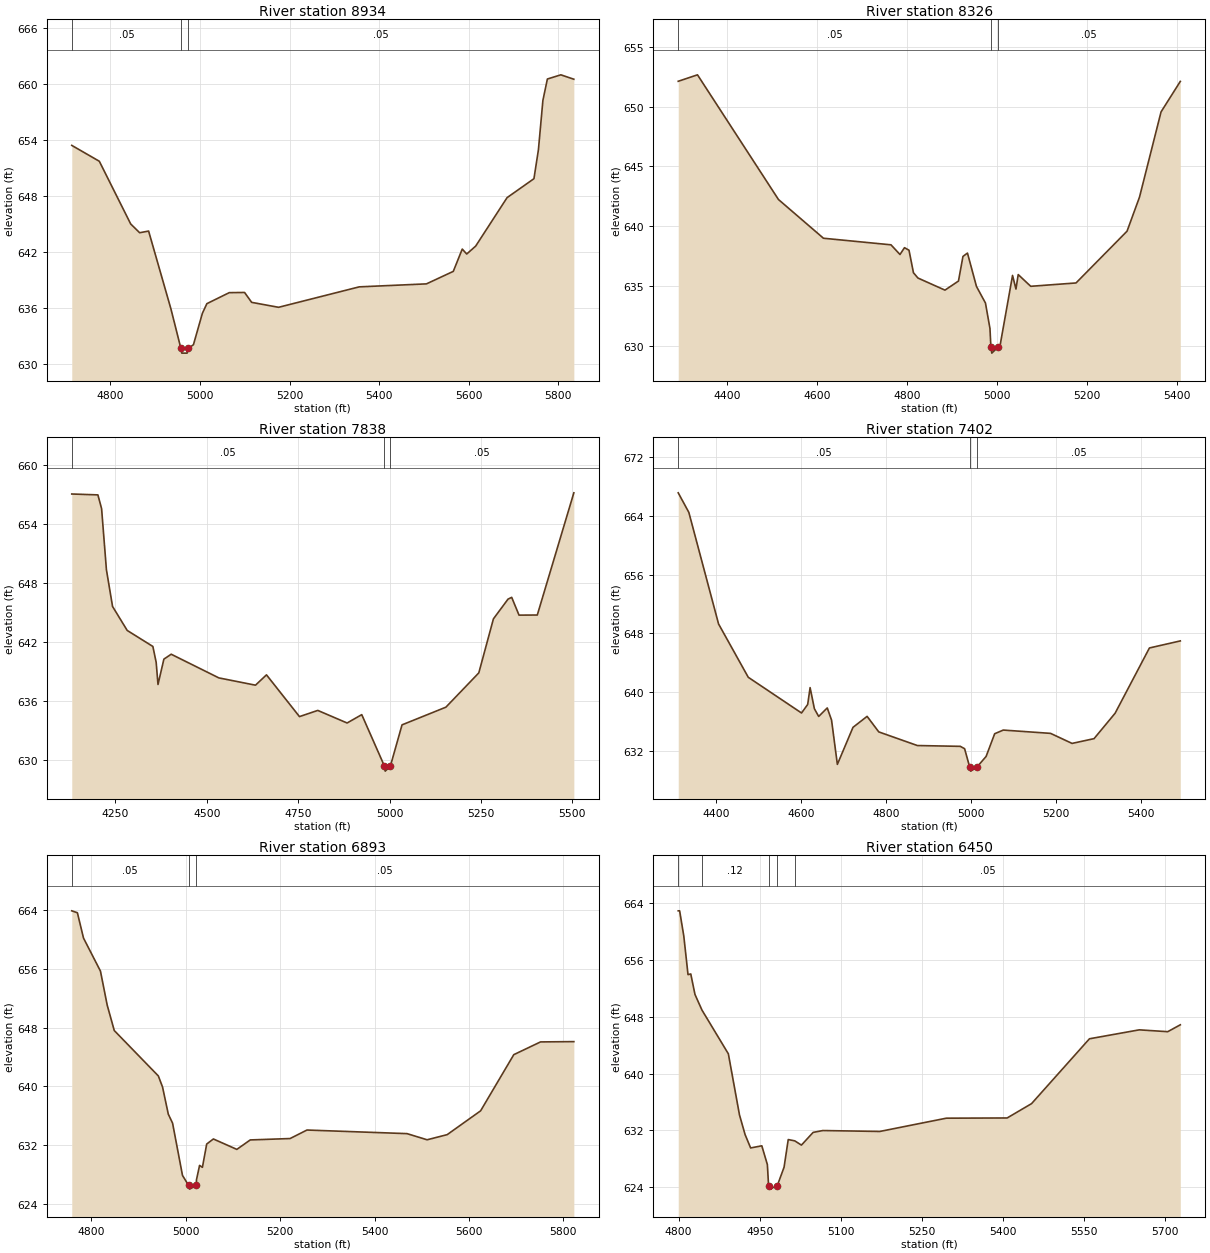
Type RM Length L Ch R = 1,8934,608,608,608
BEGIN DESCRIPTION:
Mapping XS 4a959373
END DESCRIPTION:
XS GIS Cut Line= 2
      2342520.50      7098368.39      2341399.98      7098329.40
#Sta/Elev= 30
  4713.7  653.40  4775.2  651.70  4845.3  644.98  4865.3  644.04  4885.3  644.22
  4935.3  635.85  4957.4  631.64  4959.4  631.14  4971.3  631.14  4973.3  631.64
  4985.4  632.04  5005.4  635.41  5015.4  636.44  5065.4  637.62  5099.6  637.64
  5115.4  636.58  5175.5  636.05  5355.6  638.24  5505.7  638.56  5565.7  639.90
  5585.7  642.29  5595.7  641.76  5615.7  642.61  5685.8  647.80  5745.8  649.83
  5755.8  652.93  5765.8  658.22  5775.8  660.51  5805.9  660.96  5834.9  660.49
#Mann=3,-1,0
  4713.7    0.05       0  4957.4   0.033       0  4973.3    0.05       0
Bank Sta=4957.4,4973.3
Exp/Cntr=0.3,0.1

Type RM Length L Ch R = 1,8326,488,488,488
BEGIN DESCRIPTION:
Hog Branch 17.0
END DESCRIPTION:
XS GIS Cut Line= 3
      2342641.77      7097945.58      2341929.00      7097960.00
      2341529.03      7098010.00
#Sta/Elev= 30
  4291.3  652.11  4334.1  652.65  4514.1  642.22  4614.1  638.98  4764.2  638.43
  4784.2  637.62  4794.2  638.19  4804.2  637.98  4814.2  636.09  4824.2  635.65
  4884.2  634.64  4914.2  635.40  4924.2  637.46  4934.2  637.74  4954.2  634.95
  4974.2  633.56  4984.2  631.43  4986.3  629.87  4988.3  629.37  5002.2  629.87
  5006.7  630.01  5034.4  635.87  5042.0  634.73  5047.0  635.94  5074.8  634.96
  5175.5  635.24  5288.9  639.57  5316.6  642.42  5364.5  649.55  5407.3  652.10
#Mann=3,-1,0
  4291.3    0.05       0  4986.3    0.04       0  5002.2    0.05       0
Bank Sta=4986.3,5002.2
Exp/Cntr=0.3,0.1

Type RM Length L Ch R = 1,7838,436,436,436
BEGIN DESCRIPTION:
Hog Branch 16.0
END DESCRIPTION:
XS GIS Cut Line= 3
      2342700.37      7097448.45      2341829.00      7097510.00
      2341329.04      7097510.00
#Sta/Elev= 30
  4130.6  657.06  4202.1  656.97  4212.2  655.57  4225.4  649.35  4242.2  645.61
  4282.3  643.17  4352.5  641.54  4361.5  639.92  4366.5  637.67  4382.6  640.25
  4402.6  640.75  4533.0  638.34  4633.2  637.60  4663.3  638.65  4753.5  634.40
  4803.6  635.03  4883.8  633.75  4923.9  634.60  4986.1  629.35  4988.1  628.85
  5002.1  629.35  5034.1  633.56  5154.1  635.36  5244.1  638.85  5284.1  644.35
  5324.1  646.36  5334.1  646.54  5354.1  644.73  5404.1  644.74  5504.1  657.18
#Mann=3,-1,0
  4130.6    0.05       0  4986.1   0.033       0  5002.1    0.05       0
Bank Sta=4986.1,5002.1
Exp/Cntr=0.3,0.1

Type RM Length L Ch R = 1,7402,509,509,509
BEGIN DESCRIPTION:
Hog Branch 15.0
END DESCRIPTION:
XS GIS Cut Line= 3
      2342606.22      7097011.01      2341929.00      7097110.00
      2341437.21      7097187.04
#Sta/Elev= 30
  4310.9  667.15  4335.9  664.48  4405.9  649.26  4475.8  641.99  4601.2  637.12
  4615.7  638.28  4621.4  640.58  4631.5  637.70  4641.6  636.65  4661.8  637.81
  4671.9  636.15  4685.6  630.11  4722.4  635.16  4755.6  636.66  4783.1  634.54
  4874.0  632.68  4975.1  632.57  4985.2  632.25  4997.4  629.69  4999.4  629.19
  5013.4  629.69  5035.8  631.19  5056.0  634.29  5076.3  634.79  5187.6  634.34
  5238.2  632.97  5290.0  633.62  5339.5  637.08  5420.4  645.99  5493.1  646.95
#Mann=3,-1,0
  4310.9    0.05       0  4997.4   0.033       0  5013.4    0.05       0
Bank Sta=4997.4,5013.4
Exp/Cntr=0.3,0.1

Type RM Length L Ch R = 1,6893,443,443,443
BEGIN DESCRIPTION:
Hog Branch 14.0
END DESCRIPTION:
XS GIS Cut Line= 3
      2342179.77      7096485.77      2341908.22      7096664.39
      2341363.70      7097164.25
#Sta/Elev= 30
  4758.2  663.94  4770.1  663.68  4783.1  660.22  4819.0  655.72  4833.3  651.08
  4848.3  647.61  4941.7  641.42  4950.6  639.91  4962.8  636.21  4971.9  634.97
  4992.9  627.85  5005.9  626.48  5007.9  625.98  5022.1  626.48  5022.5  627.24
  5029.1  629.22  5035.1  628.95  5044.2  632.13  5058.4  632.82  5108.1  631.40
  5136.5  632.69  5221.0  632.88  5256.7  634.04  5468.8  633.55  5511.4  632.71
  5553.9  633.41  5624.8  636.66  5695.1  644.32  5751.8  646.06  5822.4  646.10
#Mann=3,-1,0
  4758.2    0.05       0  5005.9   0.033       0  5022.1    0.05       0
Bank Sta=5005.9,5022.1
Exp/Cntr=0.3,0.1

Type RM Length L Ch R = 1,6450,469,469,469
BEGIN DESCRIPTION:
Hog Branch 13.0
END DESCRIPTION:
XS GIS Cut Line= 3
      2341528.99      7096309.97      2341579.00      7096510.00
      2341294.05      7097174.60
#Sta/Elev= 30
  4799.2  662.91  4801.8  662.91  4809.5  659.36  4817.3  653.93  4822.4  654.02
  4830.2  651.13  4843.1  648.94  4892.0  642.77  4912.6  634.16  4922.9  631.41
  4933.2  629.52  4953.9  629.82  4964.2  627.17  4966.4  624.22  4968.4  623.72
  4982.6  624.22  4995.1  626.81  5002.8  630.70  5014.8  630.52  5027.2  629.92
  5048.9  631.71  5067.0  631.97  5172.2  631.84  5295.5  633.71  5408.0  633.74
  5453.2  635.76  5560.3  644.89  5652.6  646.15  5705.2  645.89  5728.5  646.86
#Mann=5,-1,0
  4799.2    0.05       0  4843.1    0.12       0  4966.4    0.07       0
  4982.6    0.12       0  5014.8    0.05       0
Bank Sta=4966.4,4982.6
Exp/Cntr=0.3,0.1

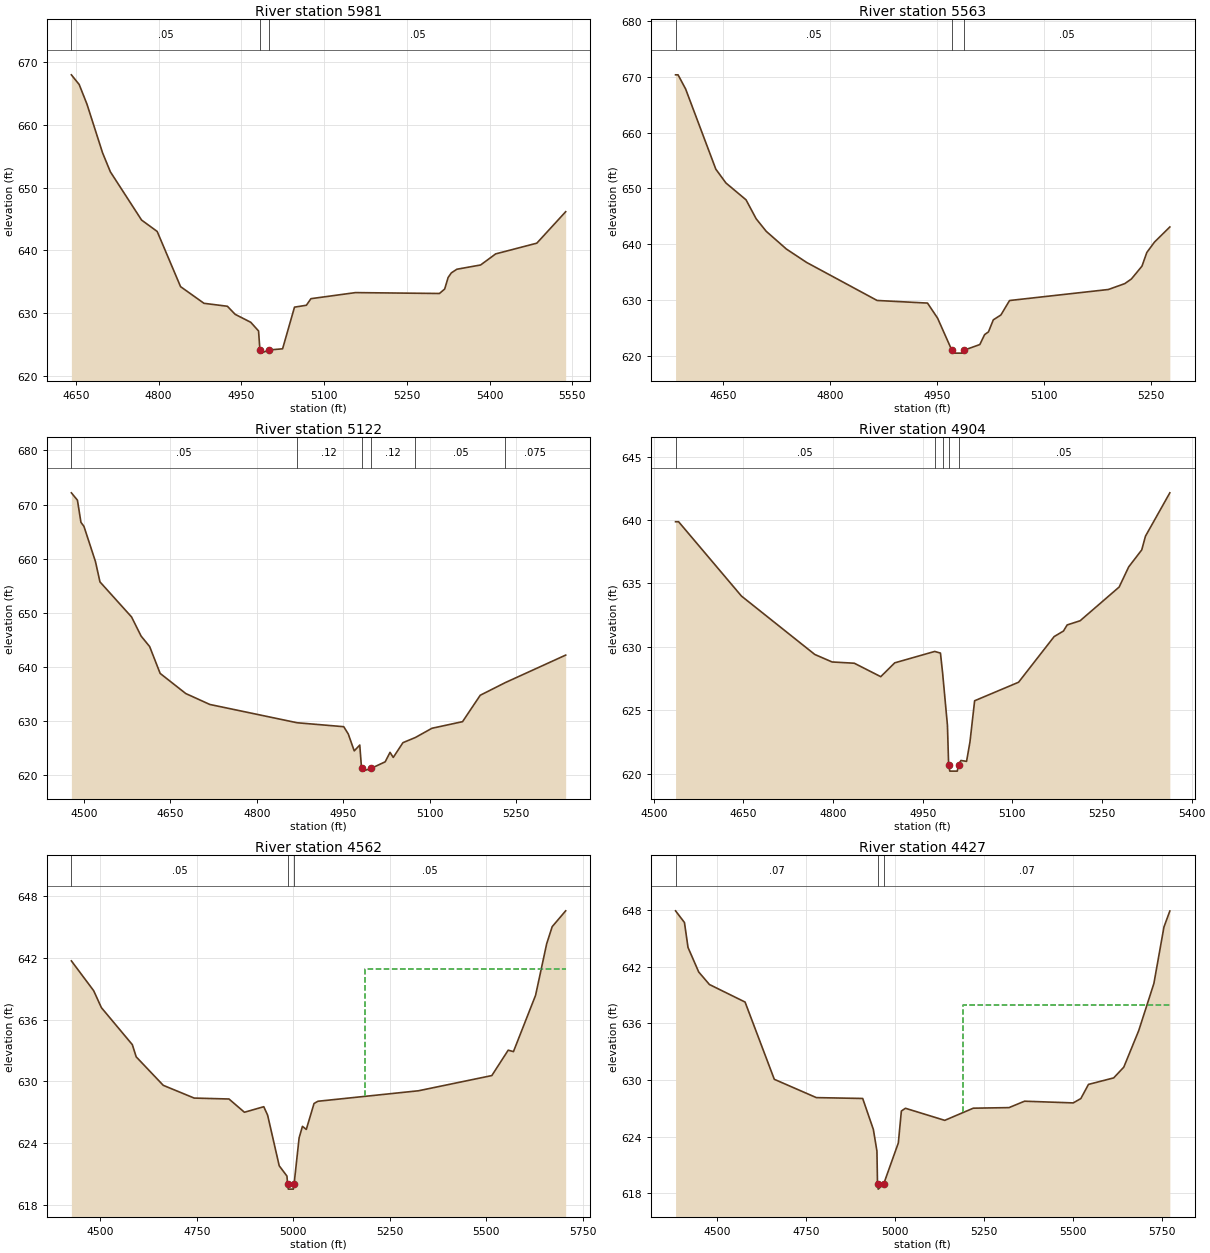
Type RM Length L Ch R = 1,5981,418,418,418
BEGIN DESCRIPTION:
Hog Branch 12.0
END DESCRIPTION:
XS GIS Cut Line= 3
      2341429.03      7096159.97      2341179.00      7096410.00
      2340907.76      7096880.07
#Sta/Elev= 30
  4641.7  668.02  4655.9  666.47  4670.0  663.33  4698.3  655.56  4712.4  652.54
  4769.0  644.84  4797.3  643.02  4839.7  634.21  4882.2  631.55  4924.6  631.08
  4938.7  629.79  4967.0  628.52  4981.1  627.14  4983.6  624.10  4985.6  623.60
  5000.0  624.10  5024.7  624.29  5046.3  630.94  5067.8  631.24  5076.1  632.29
  5156.9  633.26  5309.1  633.12  5318.6  633.83  5324.9  635.68  5330.7  636.41
  5340.7  636.99  5383.8  637.67  5411.1  639.44  5485.7  641.15  5538.0  646.17
#Mann=3,-1,0
  4641.7    0.05       0  4983.6    0.04       0  5000.0    0.05       0
Bank Sta=4983.6,5000
Exp/Cntr=0.3,0.1

Type RM Length L Ch R = 1,5563,441,441,441
BEGIN DESCRIPTION:
Hog Branch 11.0
END DESCRIPTION:
XS GIS Cut Line= 3
      2341228.97      7095860.03      2340929.00      7096160.00
      2340678.98      7096260.01
#Sta/Elev= 30
  4583.4  670.39  4586.9  670.39  4597.5  667.86  4639.9  653.46  4654.1  650.98
  4682.3  647.96  4696.5  644.56  4710.6  642.31  4738.9  639.13  4767.2  636.73
  4866.2  629.90  4936.9  629.43  4951.0  626.74  4971.1  620.95  4973.1  620.45
  4985.6  620.45  4987.6  620.95  5010.3  621.99  5017.0  623.77  5022.4  624.26
  5029.2  626.42  5039.9  627.30  5052.0  629.89  5190.7  631.87  5213.6  632.92
  5223.0  633.76  5237.8  636.06  5244.6  638.51  5255.3  640.37  5276.9  643.09
#Mann=3,-1,0
  4583.4    0.05       0  4971.1   0.033       0  4987.6    0.05       0
Bank Sta=4971.1,4987.6
Exp/Cntr=0.3,0.1

Type RM Length L Ch R = 1,5122,218,218,218
BEGIN DESCRIPTION:
Hog Branch 10.0
END DESCRIPTION:
XS GIS Cut Line= 3
      2341179.04      7095659.99      2340679.00      7095810.00
      2340528.98      7096110.03
#Sta/Elev= 30
  4478.2  672.16  4488.7  670.80  4494.8  666.71  4500.0  665.96  4520.0  659.45
  4527.8  655.70  4582.6  649.22  4599.2  645.68  4614.0  643.75  4632.2  638.79
  4676.6  635.07  4718.4  633.05  4869.8  629.67  4950.7  628.94  4958.5  627.61
  4968.9  624.47  4978.5  625.55  4981.6  621.23  4983.6  620.73  4998.1  621.23
  5022.6  622.45  5031.0  624.20  5036.6  623.26  5053.4  625.99  5075.1  626.95
  5103.7  628.65  5156.8  629.87  5187.5  634.75  5230.8  637.08  5335.7  642.17
#Mann=6,-1,0
  4478.2    0.05       0  4869.8    0.12       0  4981.6    0.07       0
  4998.1    0.12       0  5075.1    0.05       0  5230.8   0.075       0
Bank Sta=4981.6,4998.1
Exp/Cntr=0.3,0.1

Type RM Length L Ch R = 1,4904,342,342,342
BEGIN DESCRIPTION:
Mapping XS 7c8501d4
END DESCRIPTION:
XS GIS Cut Line= 3
      2340893.42      7095460.49      2340550.80      7095608.89
      2340330.95      7096005.67
#Sta/Elev= 30
  4536.5  639.86  4541.6  639.86  4646.7  634.00  4769.5  629.39  4798.4  628.80
  4835.6  628.70  4879.8  627.64  4903.2  628.73  4970.1  629.63  4979.7  629.50
  4983.3  627.94  4991.4  623.80  4993.4  620.69  4995.4  620.19  5007.9  620.19
  5009.9  620.69  5014.0  621.03  5023.4  620.96  5029.1  622.50  5036.9  625.74
  5110.4  627.20  5169.9  630.80  5185.5  631.24  5191.7  631.72  5213.4  632.05
  5278.7  634.71  5294.7  636.30  5316.5  637.64  5322.7  638.72  5363.5  642.14
#Mann=5,-1,0
  4536.5    0.05       0  4970.1    0.12       0  4983.3    0.05       0
  4993.4   0.033       0  5009.9    0.05       0
Bank Sta=4993.4,5009.9
Exp/Cntr=0.3,0.1

Type RM Length L Ch R = 1,4562,135,135,135
BEGIN DESCRIPTION:
Mapping XS 5070f7a4
END DESCRIPTION:
XS GIS Cut Line= 4
      2340886.59      7095417.29      2340182.44      7095450.61
      2339853.78      7095468.26      2339664.26      7095624.82
#Sta/Elev= 30
  4425.5  641.71  4483.2  638.81  4503.2  637.16  4583.3  633.56  4593.4  632.37
  4663.4  629.60  4743.5  628.36  4833.6  628.27  4873.6  626.98  4923.7  627.52
  4933.7  626.69  4963.7  621.77  4983.7  620.77  4985.3  620.00  4987.3  619.50
  5000.2  619.50  5002.2  620.00  5015.2  624.49  5023.8  625.61  5033.8  625.31
  5053.8  627.83  5063.8  628.05  5324.2  629.07  5514.2  630.55  5556.6  633.02
  5570.2  632.88  5627.5  638.36  5656.2  643.37  5670.5  645.04  5705.4  646.58
#Mann=3,-1,0
  4425.5    0.05       0  4985.3   0.033       0  5002.2    0.05       0
#XS Ineff=2,0
       0                 5185.70    0.00  640.94
Permanent Ineff=
       F       F
Bank Sta=4985.3,5002.2
Exp/Cntr=0.3,0.1

Type RM Length L Ch R = 1,4427,612,612,612
BEGIN DESCRIPTION:
Mapping XS 4174316f
END DESCRIPTION:
XS GIS Cut Line= 5
      2340893.95      7095292.53      2340256.92      7095321.52
      2340009.04      7095339.43      2339768.48      7095353.97
      2339590.00      7095544.10
#Sta/Elev= 30
  4383.1  647.93  4408.1  646.69  4418.1  644.05  4448.1  641.45  4478.2  640.12
  4578.3  638.26  4660.4  630.07  4778.5  628.13  4908.6  628.04  4938.6  624.75
  4948.6  622.46  4950.2  618.93  4952.2  618.43  4967.1  618.93  5008.7  623.33
  5017.2  626.71  5028.7  627.00  5139.0  625.72  5219.2  627.01  5319.5  627.07
  5363.1  627.75  5499.8  627.57  5521.2  628.03  5542.6  629.53  5613.4  630.22
  5641.8  631.36  5683.8  635.24  5726.3  640.23  5754.6  646.22  5771.1  647.91
#Mann=3,-1,0
  4383.1    0.07       0  4950.2   0.033       0  4967.1    0.07       0
#XS Ineff=2,0
       0                 5190.90    0.00  637.93
Permanent Ineff=
       F       F
Bank Sta=4950.2,4967.1
Exp/Cntr=0.3,0.1

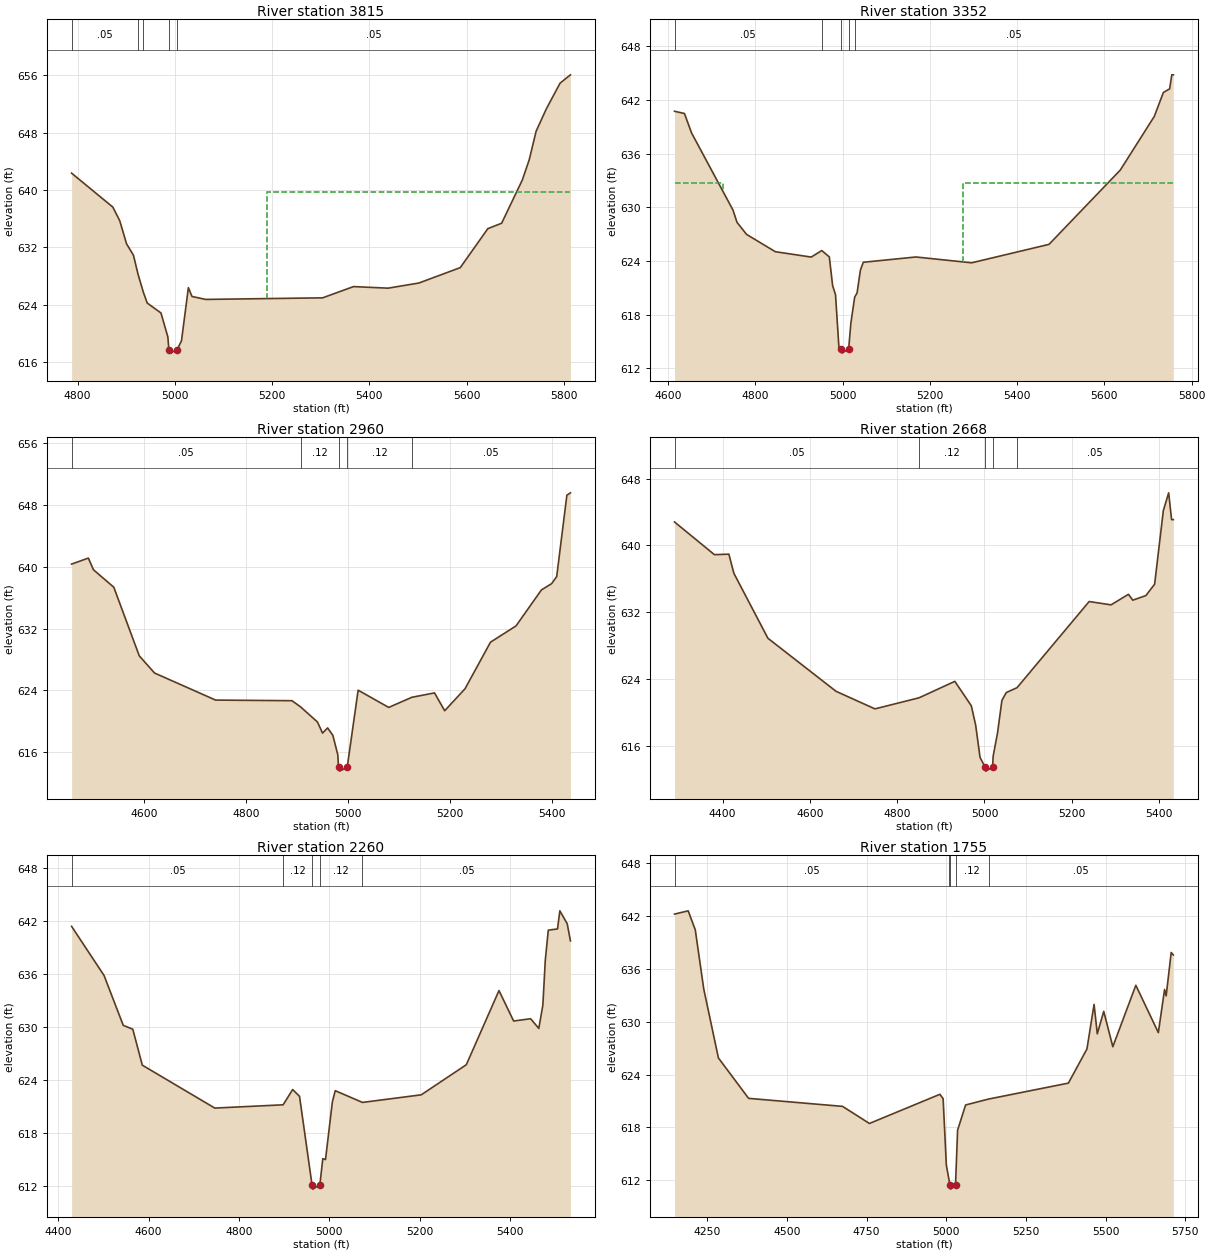
Type RM Length L Ch R = 1,3815,463,463,463
BEGIN DESCRIPTION:
Hog Branch 7.0
END DESCRIPTION:
XS GIS Cut Line= 3
      2340128.99      7094760.01      2339979.00      7094910.00
      2339428.98      7095510.03
#Sta/Elev= 30
  4787.6  642.36  4872.4  637.62  4886.6  635.72  4900.7  632.48  4914.9  630.89
  4924.0  628.31  4935.3  625.71  4943.2  624.22  4971.4  622.84  4985.6  619.49
  4987.7  617.73  4989.7  617.23  5004.7  617.73  5013.6  618.94  5027.8  626.37
  5035.2  625.14  5063.5  624.73  5304.0  624.95  5367.5  626.52  5438.5  626.30
  5502.0  627.02  5587.1  629.17  5643.8  634.61  5672.2  635.37  5714.7  641.40
  5728.9  644.22  5743.1  648.21  5764.0  651.32  5792.4  654.93  5813.7  656.09
#Mann=5,-1,0
  4787.6    0.05       0  4924.0    0.12       0  4935.3    0.05       0
  4987.7   0.033       0  5004.7    0.05       0
#XS Ineff=2,0
       0                 5190.20    0.00  639.71
Permanent Ineff=
       F       F
Bank Sta=4987.7,5004.7
Exp/Cntr=0.3,0.1

Type RM Length L Ch R = 1,3352,392,392,392
BEGIN DESCRIPTION:
Mapping XS 8eca3938
END DESCRIPTION:
XS GIS Cut Line= 3
      2339957.32      7094416.03      2339674.97      7094566.18
      2339137.41      7095190.29
#Sta/Elev= 30
  4614.5  640.72  4637.3  640.47  4653.6  638.30  4748.5  629.69  4757.8  628.31
  4779.8  626.96  4845.7  625.03  4927.9  624.43  4952.1  625.16  4969.4  624.45
  4977.0  621.23  4983.6  620.24  4991.3  614.43  4996.8  614.20  4998.8  613.70
  5013.8  614.20  5018.8  617.05  5027.5  619.95  5033.0  620.42  5040.7  622.98
  5047.3  623.85  5168.0  624.44  5295.7  623.79  5473.0  625.85  5636.4  634.15
  5714.3  640.14  5735.2  642.82  5749.5  643.22  5754.5  644.79  5758.0  644.79
#Mann=5,-1,0
  4614.5    0.05       0  4952.1    0.12       0  4996.8    0.07       0
  5013.8    0.12       0  5027.5    0.05       0
#XS Ineff=2,0
    0.00 4725.30  632.73 5274.70    0.00  632.73
Permanent Ineff=
       F       F
Bank Sta=4996.8,5013.8
Exp/Cntr=0.3,0.1

Type RM Length L Ch R = 1,2960,292,292,292
BEGIN DESCRIPTION:
Mapping XS 035e44e0
END DESCRIPTION:
XS GIS Cut Line= 2
      2339971.91      7094369.50      2338992.01      7094341.56
#Sta/Elev= 30
  4456.8  640.35  4489.7  641.13  4499.7  639.62  4539.7  637.36  4589.8  628.48
  4619.8  626.26  4739.8  622.76  4889.9  622.68  4906.8  621.88  4939.9  619.93
  4949.9  618.49  4959.9  619.16  4970.2  618.20  4979.9  615.70  4981.4  614.07
  4983.4  613.57  4998.4  614.07  5019.9  624.04  5080.0  621.81  5125.4  623.12
  5170.0  623.69  5190.0  621.38  5230.0  624.23  5280.0  630.25  5330.1  632.35
  5380.1  637.01  5400.1  637.82  5410.1  638.74  5430.1  649.26  5437.1  649.57
#Mann=5,-1,0
  4456.8    0.05       0  4906.8    0.12       0  4981.4    0.07       0
  4998.4    0.12       0  5125.4    0.05       0
Bank Sta=4981.4,4998.4
Exp/Cntr=0.3,0.1

Type RM Length L Ch R = 1,2668,408,408,408
BEGIN DESCRIPTION:
Mapping XS ef26a6dd
END DESCRIPTION:
XS GIS Cut Line= 3
      2340070.27      7094353.95      2339495.55      7094063.85
      2338996.12      7094054.76
#Sta/Elev= 30
  4289.6  642.81  4381.1  638.90  4414.2  638.96  4425.7  636.67  4503.7  628.91
  4659.8  622.57  4749.0  620.47  4850.0  621.79  4932.1  623.76  4969.9  620.84
  4979.9  618.52  4989.9  614.67  5001.2  613.53  5003.2  613.03  5018.6  613.53
  5020.0  614.83  5030.0  617.61  5040.0  621.48  5050.0  622.42  5074.6  623.00
  5240.0  633.30  5290.0  632.90  5330.0  634.16  5340.0  633.46  5370.0  634.01
  5390.0  635.37  5410.0  644.17  5422.2  646.29  5428.9  643.09  5432.9  643.09
#Mann=5,-1,0
  4289.6    0.05       0  4850.0    0.12       0  5001.2    0.07       0
  5018.6    0.12       0  5074.6    0.05       0
Bank Sta=5001.2,5018.6
Exp/Cntr=0.3,0.1

Type RM Length L Ch R = 1,2260,505,505,505
BEGIN DESCRIPTION:
Mapping XS b690d92d
END DESCRIPTION:
XS GIS Cut Line= 3
      2340079.46      7094047.25      2339293.91      7093541.26
      2339132.26      7093592.20
#Sta/Elev= 30
  4429.6  641.39  4501.5  635.82  4543.9  630.18  4565.0  629.74  4586.1  625.67
  4746.5  620.81  4897.7  621.18  4918.8  622.91  4934.0  622.14  4961.6  612.13
  4963.6  611.63  4979.0  612.13  4985.5  615.08  4991.5  614.98  5006.6  621.49
  5013.0  622.78  5073.2  621.45  5203.3  622.31  5303.1  625.72  5375.4  634.12
  5407.8  630.67  5445.4  630.93  5463.5  629.83  5472.5  632.48  5477.8  637.53
  5484.5  640.96  5504.9  641.10  5510.1  643.15  5526.4  641.68  5533.5  639.75
#Mann=5,-1,0
  4429.6    0.05       0  4897.7    0.12       0  4961.6    0.07       0
  4979.0    0.12       0  5073.2    0.05       0
Bank Sta=4961.6,4979
Exp/Cntr=0.3,0.1

Type RM Length L Ch R = 1,1755,425,425,425
BEGIN DESCRIPTION:
Mapping XS 7fdf5cee
END DESCRIPTION:
XS GIS Cut Line= 3
      2340103.12      7093940.77      2339886.24      7093281.29
      2339022.31      7093387.82
#Sta/Elev= 30
  4147.4  642.21  4190.3  642.58  4212.6  640.42  4239.1  633.72  4285.1  625.89
  4379.8  621.30  4674.6  620.39  4758.8  618.45  4979.9  621.76  4990.0  621.26
  5000.1  613.73  5007.3  612.28  5011.5  611.50  5013.5  611.00  5028.9  611.50
  5035.4  617.69  5060.5  620.55  5132.6  621.22  5382.9  623.03  5441.1  626.90
  5463.5  631.96  5473.6  628.62  5493.8  631.17  5522.3  627.16  5594.5  634.13
  5665.1  628.76  5684.6  633.65  5689.6  632.93  5705.4  637.85  5712.1  637.57
#Mann=5,-1,0
  4147.4    0.05       0  5007.3    0.12       0  5011.5   0.033       0
  5028.9    0.12       0  5132.6    0.05       0
Bank Sta=5011.5,5028.9
Exp/Cntr=0.3,0.1

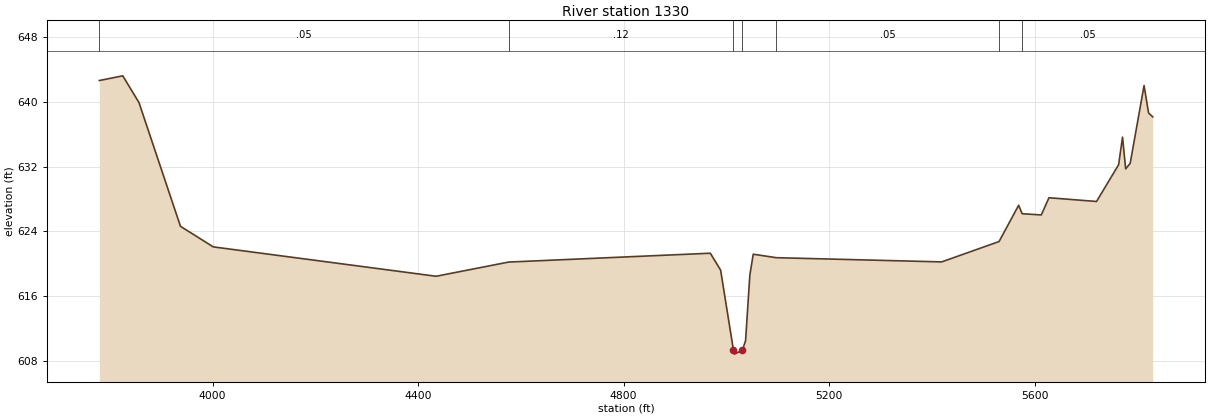
Type RM Length L Ch R = 1,1330,0,0,0
BEGIN DESCRIPTION:
Hog Branch 5.0
END DESCRIPTION:
XS GIS Cut Line= 4
      2340123.47      7093953.36      2339780.74      7092900.26
      2339660.97      7092898.87      2338984.42      7093367.60
#Sta/Elev= 30
  3779.5  642.61  3825.1  643.19  3856.6  639.90  3937.4  624.64  4001.3  622.10
  4435.0  618.48  4576.2  620.23  4968.7  621.32  4988.7  619.24  5013.7  609.38
  5015.7  608.88  5031.1  609.38  5037.3  610.53  5045.6  618.60  5052.2  621.20
  5096.8  620.77  5419.0  620.25  5530.7  622.76  5568.8  627.23  5575.6  626.19
  5612.9  626.04  5627.8  628.16  5720.4  627.70  5763.4  632.23  5771.0  635.63
  5777.1  631.72  5785.9  632.40  5812.9  641.99  5821.7  638.61  5829.8  638.13
#Mann=7,-1,0
  3779.5    0.05       0  4576.2    0.12       0  5013.7    0.07       0
  5031.1    0.12       0  5096.8    0.05       0  5530.7    0.12       0
  5575.6    0.05       0
Bank Sta=5013.7,5031.1
Exp/Cntr=0.3,0.1

Chan Stop Cuts=-1