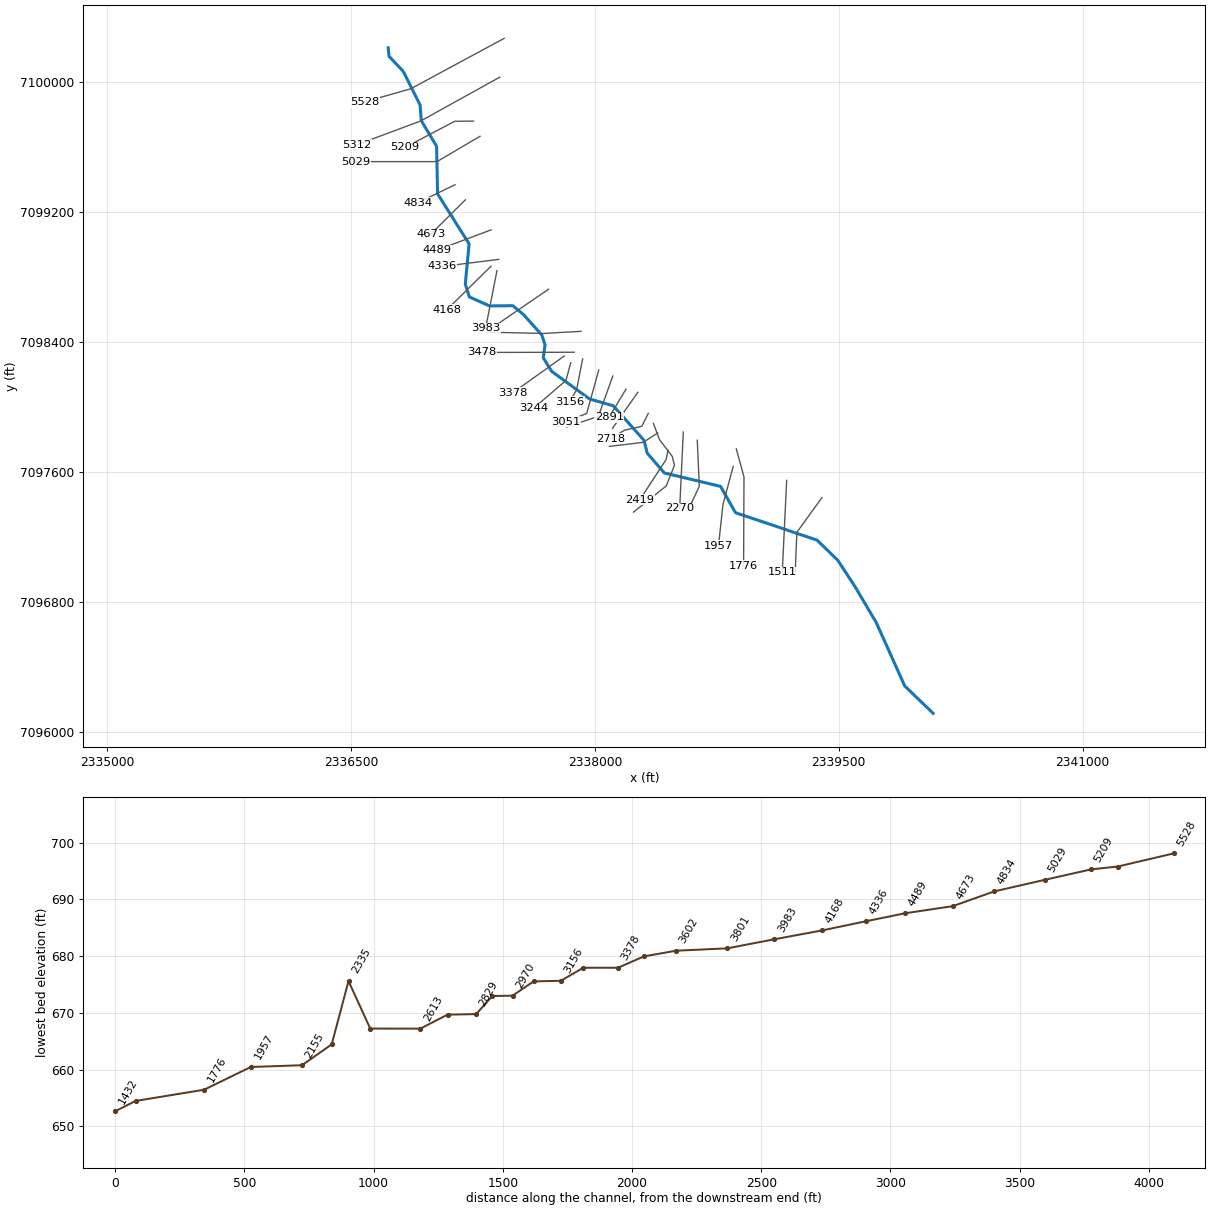
--- Hog Branch Tributary 1.prj (project) ---

Proj Title=Hog Branch Tributary 1 Base Level Engineering
Current Plan=p01
Default Exp/Contr=0.3,0.1
English Units
Geom File=g01
Flow File=f01
Plan File=p01
BEGIN DESCRIPTION:
Hog Branch Tributary 1
END DESCRIPTION:

--- Hog Branch Tributary 1.p01 (plan) ---

Plan Title=Multiple Run
Short Identifier=Multiple
Geom File=g01
Flow File=f01
Subcritical Flow
K Sum by GR= 0
Std Step Tol= 0.01
Critical Tol= 0.01
Num of Std Step Trials= 20
Max Error Tol= 0.3
Flow Tol Ratio= 0.001
Split Flow NTrial= 30
Split Flow Tol= 0.02
Split Flow Ratio= 0.02
Log Output Level= 0
Friction Slope Method= 1
Unsteady Friction Slope Method= 2
Unsteady Bridges Friction Slope Method= 1
Parabolic Critical Depth
Global Vel Dist=  1 , 1 , 1
Global Log Level= 0
CheckData=True
Encroach Param= -1, 0, 0, 0
BEGIN DESCRIPTION:
Multiple Run
END DESCRIPTION:

--- Hog Branch Tributary 1.f01 (steady flow) ---

Flow Title=Multiple
Number of Profiles=7
Profile Names=10-year,25-year,50-year,1pct_min,100-year,1pct_plu,500-year
River Rch & RM= Hog Branch Tribu,Reach-1,5528
     325     428     509     301     600    1198     837
River Rch & RM= Hog Branch Tribu,Reach-1,1511
     368     489     585     349     696    1388     984
Boundary for River Rch & Prof#=Hog Branch Tribu,Reach-1,1
Up Type=0
Dn Type=3
Dn Slope=0.005
Boundary for River Rch & Prof#=Hog Branch Tribu,Reach-1,2
Up Type=0
Dn Type=3
Dn Slope=0.005
Boundary for River Rch & Prof#=Hog Branch Tribu,Reach-1,3
Up Type=0
Dn Type=3
Dn Slope=0.005
Boundary for River Rch & Prof#=Hog Branch Tribu,Reach-1,4
Up Type=0
Dn Type=3
Dn Slope=0.005
Boundary for River Rch & Prof#=Hog Branch Tribu,Reach-1,5
Up Type=0
Dn Type=3
Dn Slope=0.005
Boundary for River Rch & Prof#=Hog Branch Tribu,Reach-1,6
Up Type=0
Dn Type=3
Dn Slope=0.005
Boundary for River Rch & Prof#=Hog Branch Tribu,Reach-1,7
Up Type=0
Dn Type=3
Dn Slope=0.005

--- Hog Branch Tributary 1.g01 (geometry) ---

Geom Title=Existing Conditions

River Reach=Hog Branch Tribu,Reach-1
Reach XY= 30
      2336729.00      7100210.00      2336734.33      7100157.49
      2336820.86      7100066.05      2336925.17      7099858.42
      2336932.83      7099761.58      2337026.76      7099604.07
      2337032.75      7099311.55      2337226.76      7099004.07
      2337203.20      7098757.14      2337228.16      7098677.88
      2337352.20      7098622.12      2337495.45      7098623.77
      2337561.97      7098568.59      2337674.26      7098443.10
      2337693.77      7098383.66      2337683.19      7098302.74
      2337734.34      7098220.05      2337967.41      7098049.95
      2338113.25      7098008.12      2338302.90      7097795.26
      2338322.29      7097716.73      2338427.84      7097594.75
      2338773.20      7097512.37      2338865.63      7097350.31
      2339366.89      7097181.83      2339495.41      7097056.99
      2339603.60      7096890.73      2339730.86      7096675.26
      2339906.34      7096284.60      2340081.26      7096115.94

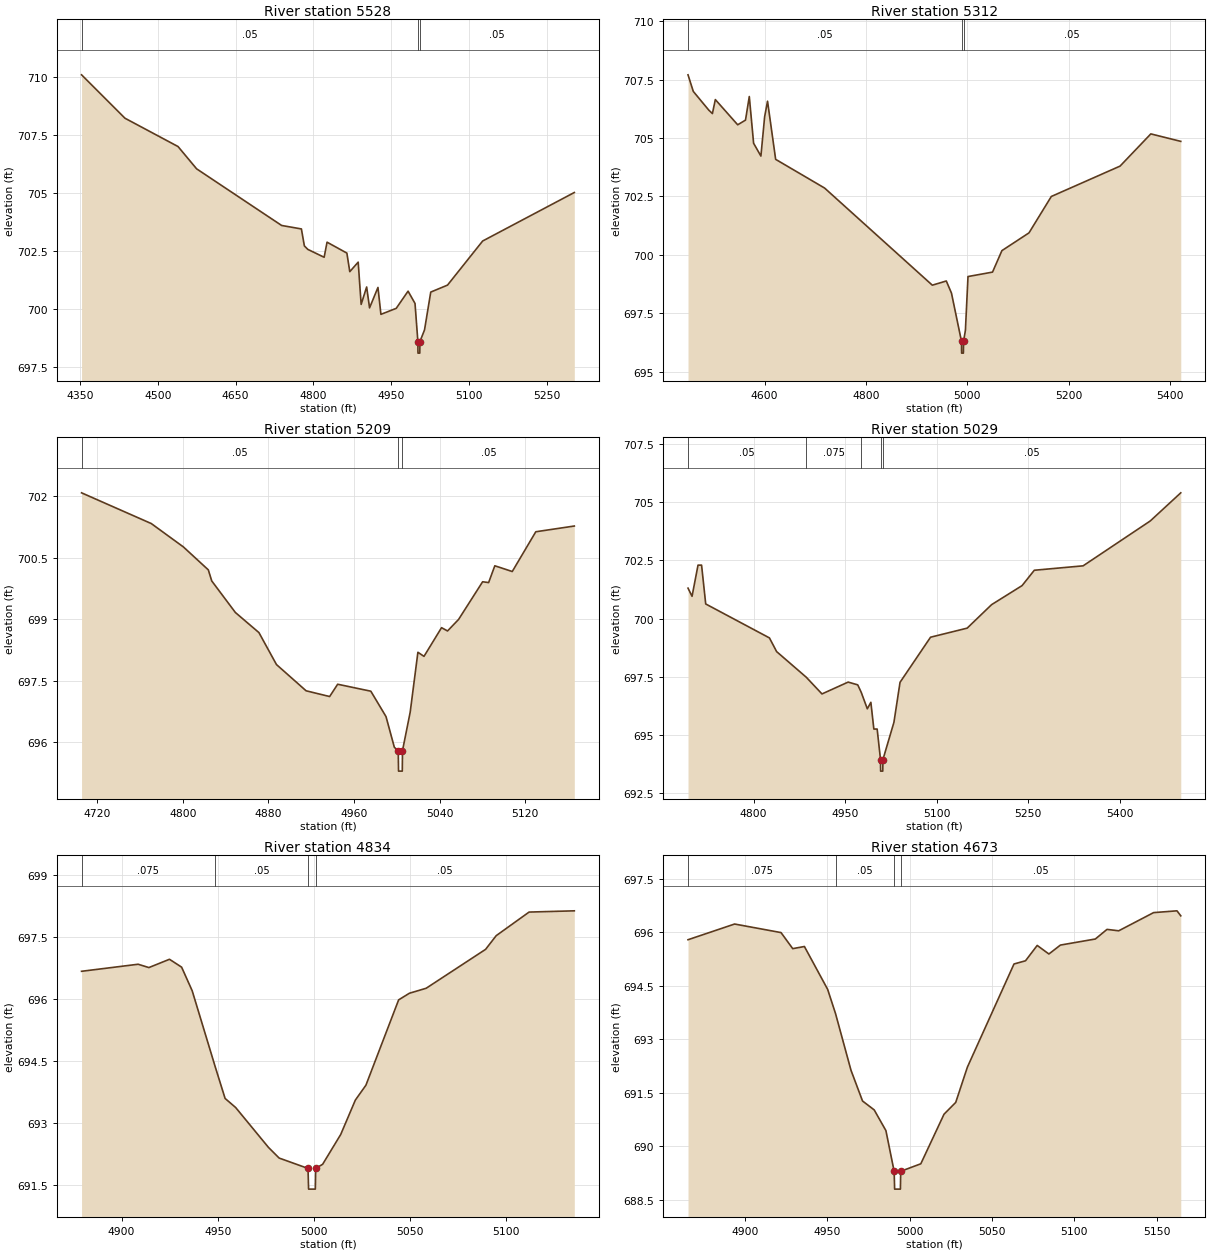
Type RM Length L Ch R = 1,5528,216,216,216
BEGIN DESCRIPTION:
Hog Branch Tributary 1 20.0
END DESCRIPTION:
XS GIS Cut Line= 3
      2337442.62      7100268.37      2336867.13      7099957.88
      2336582.92      7099877.01
#Sta/Elev= 30
  4353.2  710.09  4436.9  708.22  4539.1  707.00  4574.9  706.04  4738.7  703.60
  4776.8  703.45  4782.5  702.72  4789.1  702.57  4820.6  702.23  4826.2  702.88
  4864.4  702.41  4870.0  701.61  4886.2  702.02  4891.9  700.20  4902.5  700.95
  4908.1  700.05  4924.3  700.93  4930.0  699.77  4959.5  700.03  4982.3  700.77
  4995.7  700.24  5001.2  698.60  5001.4  698.10  5004.9  698.10  5005.2  698.60
  5014.0  699.10  5026.0  700.73  5058.3  701.03  5126.0  702.93  5302.6  705.02
#Mann=3,-1,0
  4353.2    0.05       0  5001.2   0.033       0  5005.2    0.05       0
Bank Sta=5001.2,5005.2
Exp/Cntr=0.3,0.1

Type RM Length L Ch R = 1,5312,103,103,103
BEGIN DESCRIPTION:
Hog Branch Tributary 1 19.0
END DESCRIPTION:
XS GIS Cut Line= 3
      2337414.75      7100029.08      2336929.00      7099760.00
      2336538.33      7099614.45
#Sta/Elev= 30
  4448.9  707.71  4459.3  707.00  4489.8  706.20  4497.0  706.05  4502.8  706.65
  4546.9  705.57  4562.3  705.77  4569.8  706.78  4578.3  704.78  4592.7  704.23
  4600.1  705.92  4605.8  706.58  4621.8  704.09  4718.4  702.86  4930.9  698.70
  4958.5  698.88  4968.7  698.36  4988.5  696.29  4988.7  695.79  4992.2  695.79
  4992.5  696.29  4996.2  696.77  5001.3  699.07  5049.7  699.26  5068.2  700.18
  5121.6  700.94  5165.7  702.50  5301.3  703.80  5362.0  705.18  5421.1  704.86
#Mann=3,-1,0
  4448.9    0.05       0  4988.5    0.04       0  4992.5    0.05       0
Bank Sta=4988.5,4992.5
Exp/Cntr=0.3,0.1

Type RM Length L Ch R = 1,5209,180,180,180
BEGIN DESCRIPTION:
Mapping XS 90d608e4
END DESCRIPTION:
XS GIS Cut Line= 3
      2337254.18      7099759.37      2337137.90      7099758.03
      2336833.21      7099597.67
#Sta/Elev= 30
  4705.3  702.08  4770.5  701.33  4800.5  700.76  4823.8  700.20  4827.0  699.93
  4849.1  699.16  4871.1  698.67  4887.5  697.89  4915.2  697.25  4937.2  697.11
  4944.7  697.41  4975.7  697.24  4989.9  696.62  4997.7  695.87  5001.3  695.79
  5001.6  695.29  5005.1  695.29  5005.3  695.79  5012.5  696.73  5019.7  698.19
  5025.4  698.09  5041.8  698.79  5047.4  698.71  5057.7  698.99  5080.2  699.91
  5085.8  699.89  5091.6  700.30  5107.9  700.16  5129.9  701.13  5165.9  701.27
#Mann=3,-1,0
  4705.3    0.05       0  5001.3   0.033       0  5005.3    0.05       0
Bank Sta=5001.3,5005.3
Exp/Cntr=0.3,0.1

Type RM Length L Ch R = 1,5029,195,195,195
BEGIN DESCRIPTION:
Hog Branch Tributary 1 18.0
END DESCRIPTION:
XS GIS Cut Line= 3
      2337293.98      7099665.80      2337029.00      7099510.00
      2336528.99      7099510.00
#Sta/Elev= 30
  4692.7  701.31  4699.3  700.96  4709.1  702.30  4714.9  702.30  4721.7  700.63
  4826.1  699.17  4837.9  698.58  4886.4  697.48  4912.2  696.76  4955.1  697.27
  4970.8  697.15  4976.5  696.83  4986.5  696.12  4992.3  696.40  4997.2  695.25
  5002.6  695.25  5008.1  693.94  5008.3  693.44  5011.8  693.44  5012.1  693.94
  5030.1  695.54  5040.1  697.26  5090.1  699.20  5150.1  699.59  5190.1  700.60
  5240.1  701.42  5260.1  702.08  5340.1  702.27  5450.1  704.20  5500.1  705.41
#Mann=5,-1,0
  4692.7    0.05       0  4886.4   0.075       0  4976.5    0.05       0
  5008.1    0.04       0  5012.1    0.05       0
Bank Sta=5008.1,5012.1
Exp/Cntr=0.3,0.1

Type RM Length L Ch R = 1,4834,161,161,161
BEGIN DESCRIPTION:
Mapping XS 2a56112d
END DESCRIPTION:
XS GIS Cut Line= 2
      2337140.15      7099367.99      2336909.73      7099256.23
#Sta/Elev= 26
  4879.2  696.67  4908.6  696.84  4914.2  696.76  4924.9  696.96  4931.2  696.77
  4936.7  696.20  4948.7  694.36  4953.8  693.60  4959.3  693.38  4976.3  692.42
  4981.9  692.16  4996.9  691.91  4997.2  691.41  5000.7  691.41  5000.9  691.91
  5004.5  692.01  5013.9  692.73  5021.5  693.56  5027.0  693.92  5044.0  695.98
  5049.6  696.14  5058.3  696.26  5089.2  697.20  5094.7  697.53  5111.8  698.10
  5135.3  698.13
#Mann=4,-1,0
  4879.2   0.075       0  4948.7    0.05       0  4996.9    0.04       0
  5000.9    0.05       0
Bank Sta=4996.9,5000.9
Exp/Cntr=0.3,0.1

Type RM Length L Ch R = 1,4673,184,184,184
BEGIN DESCRIPTION:
Mapping XS d084760c
END DESCRIPTION:
XS GIS Cut Line= 2
      2337203.78      7099275.17      2336991.54      7099064.14
#Sta/Elev= 30
  4865.4  695.79  4893.7  696.23  4921.9  695.99  4929.0  695.54  4936.1  695.60
  4950.2  694.40  4955.0  693.72  4964.4  692.13  4971.4  691.27  4978.5  691.02
  4985.6  690.44  4990.6  689.30  4990.9  688.80  4994.4  688.80  4994.6  689.30
  5006.8  689.51  5020.9  690.90  5028.0  691.23  5035.1  692.22  5063.4  695.11
  5070.4  695.20  5077.5  695.63  5084.6  695.39  5091.6  695.64  5112.8  695.81
  5119.9  696.08  5127.0  696.04  5148.2  696.55  5162.4  696.60  5164.7  696.46
#Mann=4,-1,0
  4865.4   0.075       0  4955.0    0.05       0  4990.6    0.04       0
  4994.6    0.05       0
Bank Sta=4990.6,4994.6
Exp/Cntr=0.3,0.1

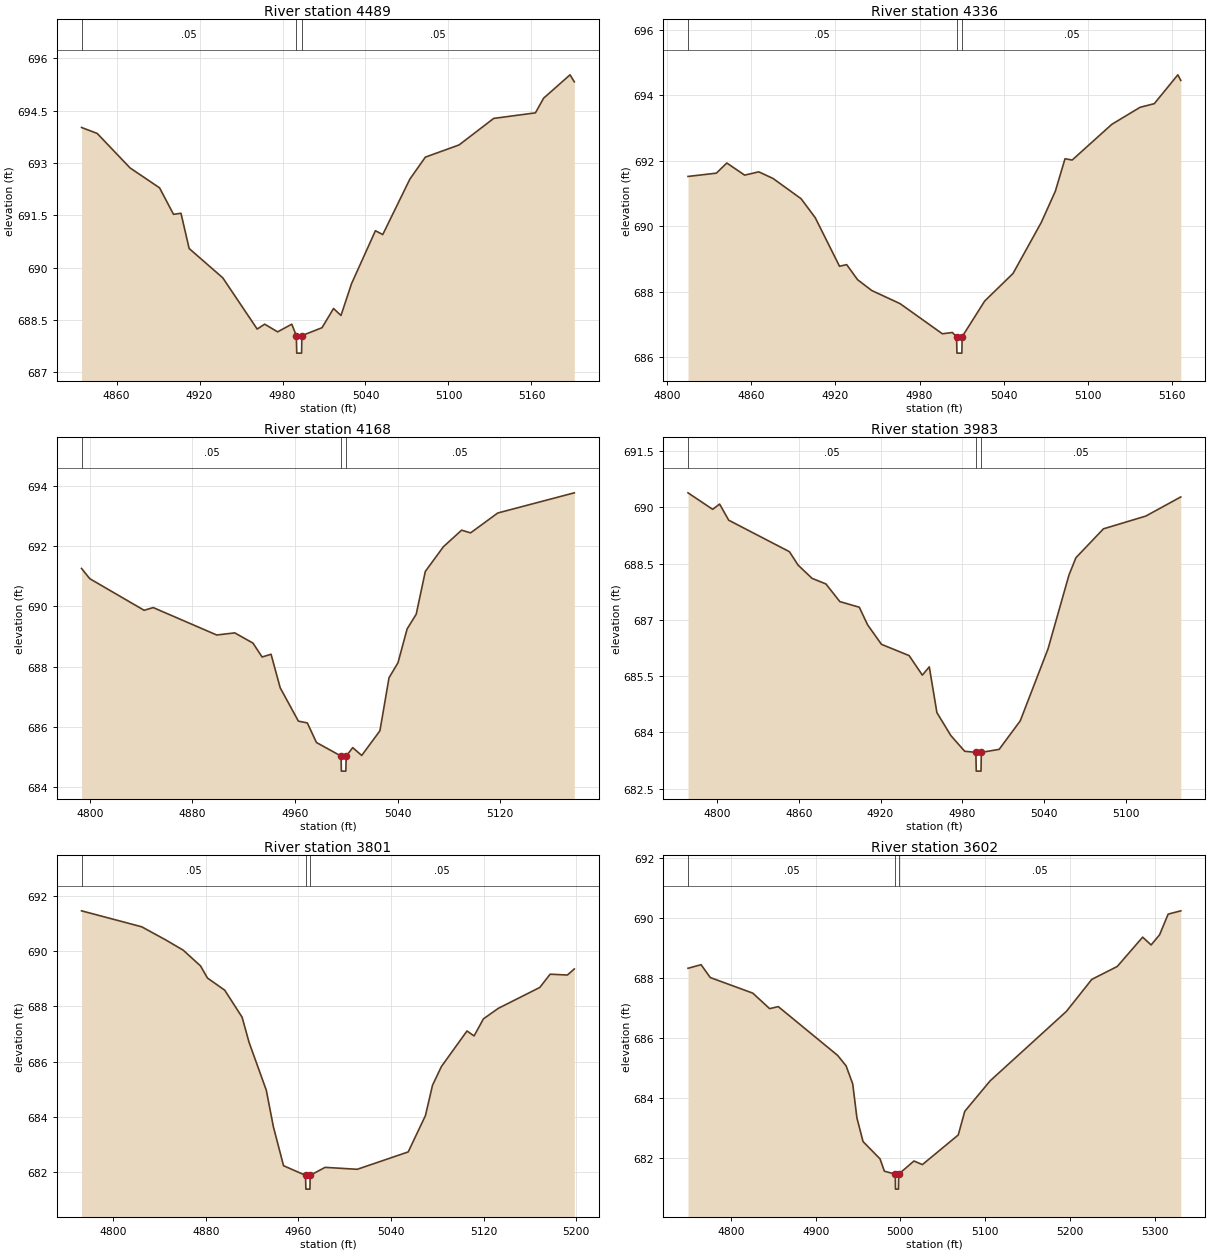
Type RM Length L Ch R = 1,4489,153,153,153
BEGIN DESCRIPTION:
Mapping XS 780b12f6
END DESCRIPTION:
XS GIS Cut Line= 2
      2337361.83      7099090.02      2337028.19      7098964.98
#Sta/Elev= 30
  4834.7  694.02  4846.0  693.85  4869.8  692.86  4891.1  692.29  4901.2  691.53
  4906.6  691.56  4912.5  690.55  4936.8  689.71  4961.7  688.24  4967.1  688.38
  4976.5  688.16  4986.7  688.38  4990.0  688.05  4990.3  687.55  4993.8  687.55
  4994.0  688.05  5008.6  688.28  5016.9  688.83  5022.3  688.63  5029.9  689.54
  5047.2  691.06  5052.5  690.95  5072.1  692.54  5083.3  693.17  5107.7  693.52
  5132.7  694.28  5162.9  694.44  5168.8  694.86  5187.9  695.53  5191.0  695.33
#Mann=3,-1,0
  4834.7    0.05       0  4990.0   0.033       0  4994.0    0.05       0
Bank Sta=4990,4994
Exp/Cntr=0.3,0.1

Type RM Length L Ch R = 1,4336,168,168,168
BEGIN DESCRIPTION:
Mapping XS dfc5742e
END DESCRIPTION:
XS GIS Cut Line= 2
      2337409.09      7098908.75      2337060.23      7098864.95
#Sta/Elev= 30
  4814.8  691.52  4835.0  691.62  4842.5  691.93  4855.2  691.56  4865.3  691.66
  4875.4  691.46  4895.5  690.84  4905.6  690.26  4922.9  688.78  4928.0  688.83
  4935.8  688.37  4945.9  688.04  4966.1  687.64  4996.3  686.72  5003.4  686.76
  5006.4  686.63  5006.7  686.13  5010.2  686.13  5010.4  686.63  5026.5  687.72
  5046.7  688.56  5066.9  690.12  5076.9  691.07  5083.8  692.06  5088.9  692.02
  5117.2  693.11  5137.4  693.63  5147.5  693.74  5164.3  694.62  5166.4  694.45
#Mann=3,-1,0
  4814.8    0.05       0  5006.4   0.033       0  5010.4    0.05       0
Bank Sta=5006.4,5010.4
Exp/Cntr=0.3,0.1

Type RM Length L Ch R = 1,4168,185,185,185
BEGIN DESCRIPTION:
Mapping XS 4aa7d977
END DESCRIPTION:
XS GIS Cut Line= 2
      2337361.44      7098866.62      2337087.75      7098596.83
#Sta/Elev= 30
  4793.5  691.26  4799.9  690.92  4842.3  689.87  4849.4  689.96  4898.9  689.05
  4913.0  689.12  4927.2  688.78  4934.3  688.32  4941.3  688.41  4948.4  687.30
  4962.6  686.19  4969.6  686.13  4976.7  685.48  4995.9  685.03  4996.1  684.53
  4999.6  684.53  4999.9  685.03  5005.0  685.31  5012.0  685.05  5026.2  685.87
  5033.3  687.63  5040.3  688.13  5047.4  689.25  5054.5  689.74  5061.6  691.16
  5075.7  691.98  5089.9  692.53  5096.9  692.44  5118.1  693.10  5177.8  693.77
#Mann=3,-1,0
  4793.5    0.05       0  4995.9    0.04       0  4999.9    0.05       0
Bank Sta=4995.9,4999.9
Exp/Cntr=0.3,0.1

Type RM Length L Ch R = 1,3983,182,182,182
BEGIN DESCRIPTION:
Mapping XS f6f8454f
END DESCRIPTION:
XS GIS Cut Line= 2
      2337398.19      7098839.37      2337328.12      7098484.32
#Sta/Elev= 30
  4778.6  690.39  4796.7  689.95  4801.8  690.09  4808.5  689.66  4853.1  688.82
  4859.5  688.46  4869.7  688.11  4879.9  687.96  4890.1  687.49  4904.4  687.34
  4910.5  686.87  4920.7  686.35  4941.0  686.05  4950.7  685.53  4955.8  685.75
  4961.4  684.53  4971.6  683.92  4981.8  683.50  4990.0  683.47  4990.3  682.97
  4993.8  682.97  4994.0  683.47  5007.1  683.55  5022.6  684.31  5043.0  686.23
  5058.4  688.20  5063.5  688.66  5083.7  689.43  5114.8  689.77  5140.5  690.28
#Mann=3,-1,0
  4778.6    0.05       0  4990.0    0.04       0  4994.0    0.05       0
Bank Sta=4990,4994
Exp/Cntr=0.3,0.1

Type RM Length L Ch R = 1,3801,199,199,199
BEGIN DESCRIPTION:
Mapping XS 93381580
END DESCRIPTION:
XS GIS Cut Line= 2
      2337715.59      7098725.24      2337364.24      7098484.88
#Sta/Elev= 30
  4772.6  691.47  4824.6  690.89  4845.5  690.41  4860.5  690.04  4875.4  689.47
  4881.4  689.03  4896.3  688.59  4911.3  687.61  4917.3  686.70  4932.2  684.96
  4938.3  683.64  4947.1  682.22  4966.1  681.87  4966.4  681.37  4969.9  681.37
  4970.1  681.87  4983.0  682.16  5010.8  682.09  5054.8  682.72  5069.7  684.04
  5075.8  685.14  5083.5  685.82  5105.6  687.11  5111.7  686.93  5119.8  687.55
  5132.6  687.93  5168.5  688.69  5177.4  689.17  5192.3  689.14  5198.3  689.36
#Mann=3,-1,0
  4772.6    0.05       0  4966.1    0.04       0  4970.1    0.05       0
Bank Sta=4966.1,4970.1
Exp/Cntr=0.3,0.1

Type RM Length L Ch R = 1,3602,124,124,124
BEGIN DESCRIPTION:
Mapping XS 3acc03ae
END DESCRIPTION:
XS GIS Cut Line= 3
      2337915.30      7098466.09      2337683.78      7098453.04
      2337334.06      7098461.15
#Sta/Elev= 30
  4749.3  688.33  4764.7  688.45  4775.6  688.02  4825.7  687.50  4845.7  686.98
  4855.8  687.05  4925.9  685.42  4935.9  685.07  4943.7  684.47  4948.7  683.33
  4955.9  682.54  4976.0  681.96  4981.1  681.55  4994.0  681.45  4994.2  680.95
  4997.7  680.95  4998.0  681.45  5016.0  681.89  5026.0  681.77  5068.3  682.76
  5076.0  683.55  5106.0  684.57  5196.0  686.89  5226.0  687.96  5256.0  688.39
  5286.0  689.37  5296.0  689.11  5306.0  689.45  5316.1  690.14  5331.0  690.25
#Mann=3,-1,0
  4749.3    0.05       0  4994.0    0.04       0  4998.0    0.05       0
Bank Sta=4994,4998
Exp/Cntr=0.3,0.1

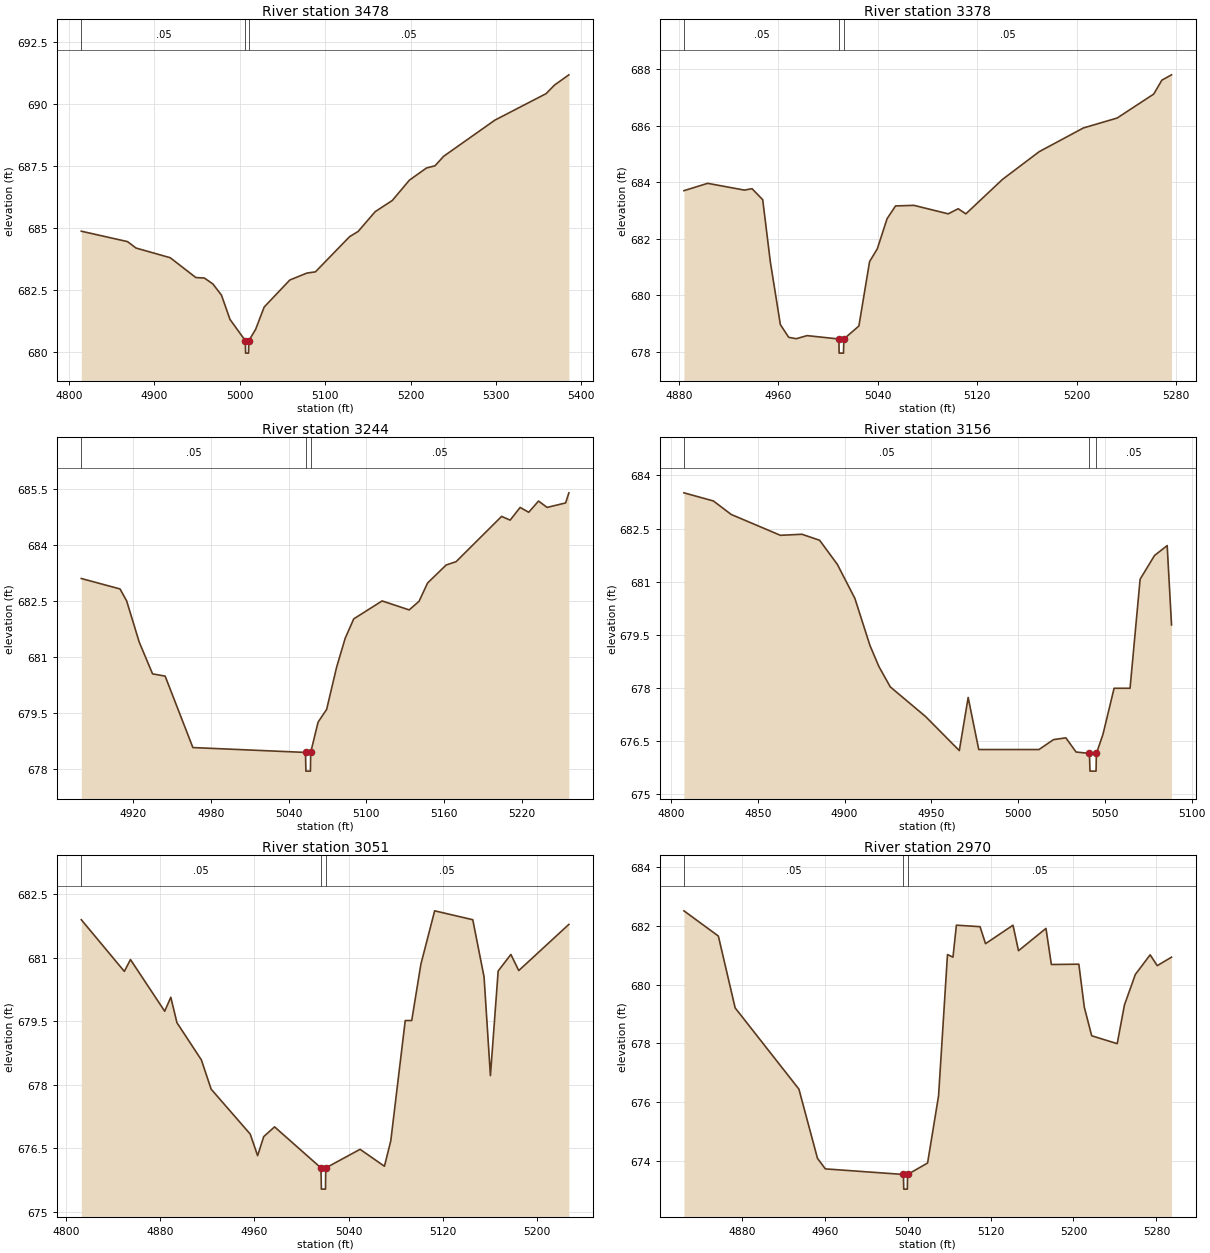
Type RM Length L Ch R = 1,3478,100,100,100
BEGIN DESCRIPTION:
Mapping XS 01f13b31
END DESCRIPTION:
XS GIS Cut Line= 2
      2337873.07      7098337.48      2337302.27      7098336.10
#Sta/Elev= 30
  4814.6  684.87  4868.7  684.45  4878.7  684.19  4918.7  683.80  4948.7  683.00
  4958.7  682.98  4968.7  682.74  4978.7  682.29  4988.7  681.31  5006.7  680.45
  5006.9  679.95  5010.4  679.95  5010.7  680.45  5018.7  680.91  5028.7  681.81
  5058.7  682.90  5078.7  683.18  5088.7  683.23  5128.7  684.65  5138.7  684.86
  5158.7  685.66  5178.7  686.11  5198.7  686.93  5218.7  687.42  5228.7  687.51
  5238.7  687.89  5298.7  689.35  5358.7  690.42  5368.7  690.77  5385.4  691.18
#Mann=3,-1,0
  4814.6    0.05       0  5006.7   0.033       0  5010.7    0.05       0
Bank Sta=5006.7,5010.7
Exp/Cntr=0.3,0.1

Type RM Length L Ch R = 1,3378,134,134,134
BEGIN DESCRIPTION:
Mapping XS e4d3f0f4
END DESCRIPTION:
XS GIS Cut Line= 2
      2337812.15      7098314.29      2337492.67      7098086.45
#Sta/Elev= 30
  4884.0  683.70  4903.1  683.96  4932.7  683.72  4938.8  683.77  4947.4  683.38
  4953.5  681.19  4961.6  678.96  4968.3  678.51  4974.4  678.46  4983.1  678.57
  5008.7  678.45  5008.9  677.95  5012.4  677.95  5012.7  678.45  5024.8  678.91
  5033.4  681.19  5039.6  681.64  5047.5  682.71  5054.3  683.16  5069.1  683.18
  5096.7  682.88  5104.7  683.06  5110.9  682.88  5140.4  684.10  5169.9  685.08
  5205.5  685.92  5232.6  686.27  5262.1  687.12  5268.6  687.61  5276.4  687.80
#Mann=3,-1,0
  4884.0    0.05       0  5008.7   0.033       0  5012.7    0.05       0
Bank Sta=5008.7,5012.7
Exp/Cntr=0.3,0.1

Type RM Length L Ch R = 1,3244,88,88,88
BEGIN DESCRIPTION:
Mapping XS 6e3d3d9d
END DESCRIPTION:
XS GIS Cut Line= 3
      2337851.91      7098273.16      2337822.58      7098163.75
      2337623.01      7097992.57
#Sta/Elev= 30
  4880.0  683.10  4909.9  682.82  4915.0  682.50  4924.7  681.40  4935.0  680.55
  4944.7  680.49  4966.1  678.58  5053.0  678.45  5053.3  677.95  5056.8  677.95
  5057.0  678.45  5062.7  679.26  5069.3  679.60  5077.0  680.73  5083.6  681.50
  5090.2  682.02  5112.1  682.50  5133.0  682.26  5140.6  682.49  5147.2  682.98
  5161.5  683.46  5169.2  683.55  5204.3  684.76  5210.9  684.66  5218.6  685.00
  5225.2  684.87  5232.8  685.17  5239.4  685.00  5253.7  685.12  5256.2  685.39
#Mann=3,-1,0
  4880.0    0.05       0  5053.0   0.033       0  5057.0    0.05       0
Bank Sta=5053,5057
Exp/Cntr=0.3,0.1

Type RM Length L Ch R = 1,3156,105,105,105
BEGIN DESCRIPTION:
Mapping XS fe1bd9aa
END DESCRIPTION:
XS GIS Cut Line= 3
      2337925.25      7098296.72      2337887.96      7098106.04
      2337843.48      7098031.60
#Sta/Elev= 30
  4807.4  683.51  4824.4  683.28  4834.6  682.90  4863.0  682.31  4875.4  682.34
  4885.6  682.17  4895.8  681.49  4905.9  680.53  4914.6  679.20  4919.7  678.61
  4926.3  678.03  4946.7  677.19  4966.1  676.23  4971.2  677.73  4977.3  676.26
  5012.0  676.26  5020.4  676.54  5027.5  676.59  5033.4  676.19  5041.1  676.15
  5041.4  675.65  5044.9  675.65  5045.1  676.15  5048.9  676.69  5055.3  677.99
  5064.5  677.99  5070.3  681.07  5078.6  681.74  5085.9  682.02  5088.4  679.78
#Mann=3,-1,0
  4807.4    0.05       0  5041.1   0.033       0  5045.1    0.05       0
Bank Sta=5041.1,5045.1
Exp/Cntr=0.3,0.1

Type RM Length L Ch R = 1,3051,81,81,81
BEGIN DESCRIPTION:
Mapping XS c937c1aa
END DESCRIPTION:
XS GIS Cut Line= 3
      2338024.32      7098228.36      2337950.19      7097960.89
      2337823.26      7097909.49
#Sta/Elev= 30
  4812.8  681.90  4849.4  680.68  4854.6  680.96  4883.7  679.74  4888.9  680.07
  4894.1  679.47  4914.9  678.59  4923.2  677.90  4956.4  676.84  4962.7  676.33
  4967.9  676.78  4977.1  677.01  5016.6  676.04  5016.9  675.54  5020.4  675.54
  5020.6  676.04  5049.8  676.48  5070.5  676.08  5075.9  676.68  5088.2  679.52
  5093.7  679.52  5101.5  680.85  5113.2  682.11  5145.6  681.90  5155.2  680.55
  5160.6  678.22  5167.2  680.69  5178.0  681.08  5184.7  680.70  5227.3  681.79
#Mann=3,-1,0
  4812.8    0.05       0  5016.6   0.033       0  5020.6    0.05       0
Bank Sta=5016.6,5020.6
Exp/Cntr=0.3,0.1

Type RM Length L Ch R = 1,2970,79,79,79
BEGIN DESCRIPTION:
Mapping XS 46c0c157
END DESCRIPTION:
XS GIS Cut Line= 3
      2338110.69      7098191.26      2338021.79      7097942.67
      2337825.87      7097878.09
#Sta/Elev= 30
  4824.3  682.52  4857.5  681.66  4873.7  679.21  4935.2  676.44  4953.1  674.08
  4960.7  673.72  5036.0  673.53  5036.3  673.03  5039.8  673.03  5040.0  673.53
  5059.3  673.92  5069.9  676.21  5078.5  681.03  5083.8  680.94  5087.1  682.03
  5109.9  681.98  5115.2  681.40  5141.7  682.03  5147.0  681.16  5173.5  681.92
  5178.7  680.69  5205.2  680.70  5210.5  679.23  5217.6  678.26  5242.2  677.99
  5249.2  679.31  5259.7  680.35  5274.0  681.02  5280.8  680.65  5294.6  680.94
#Mann=3,-1,0
  4824.3    0.05       0  5036.0   0.033       0  5040.0    0.05       0
Bank Sta=5036,5040
Exp/Cntr=0.3,0.1

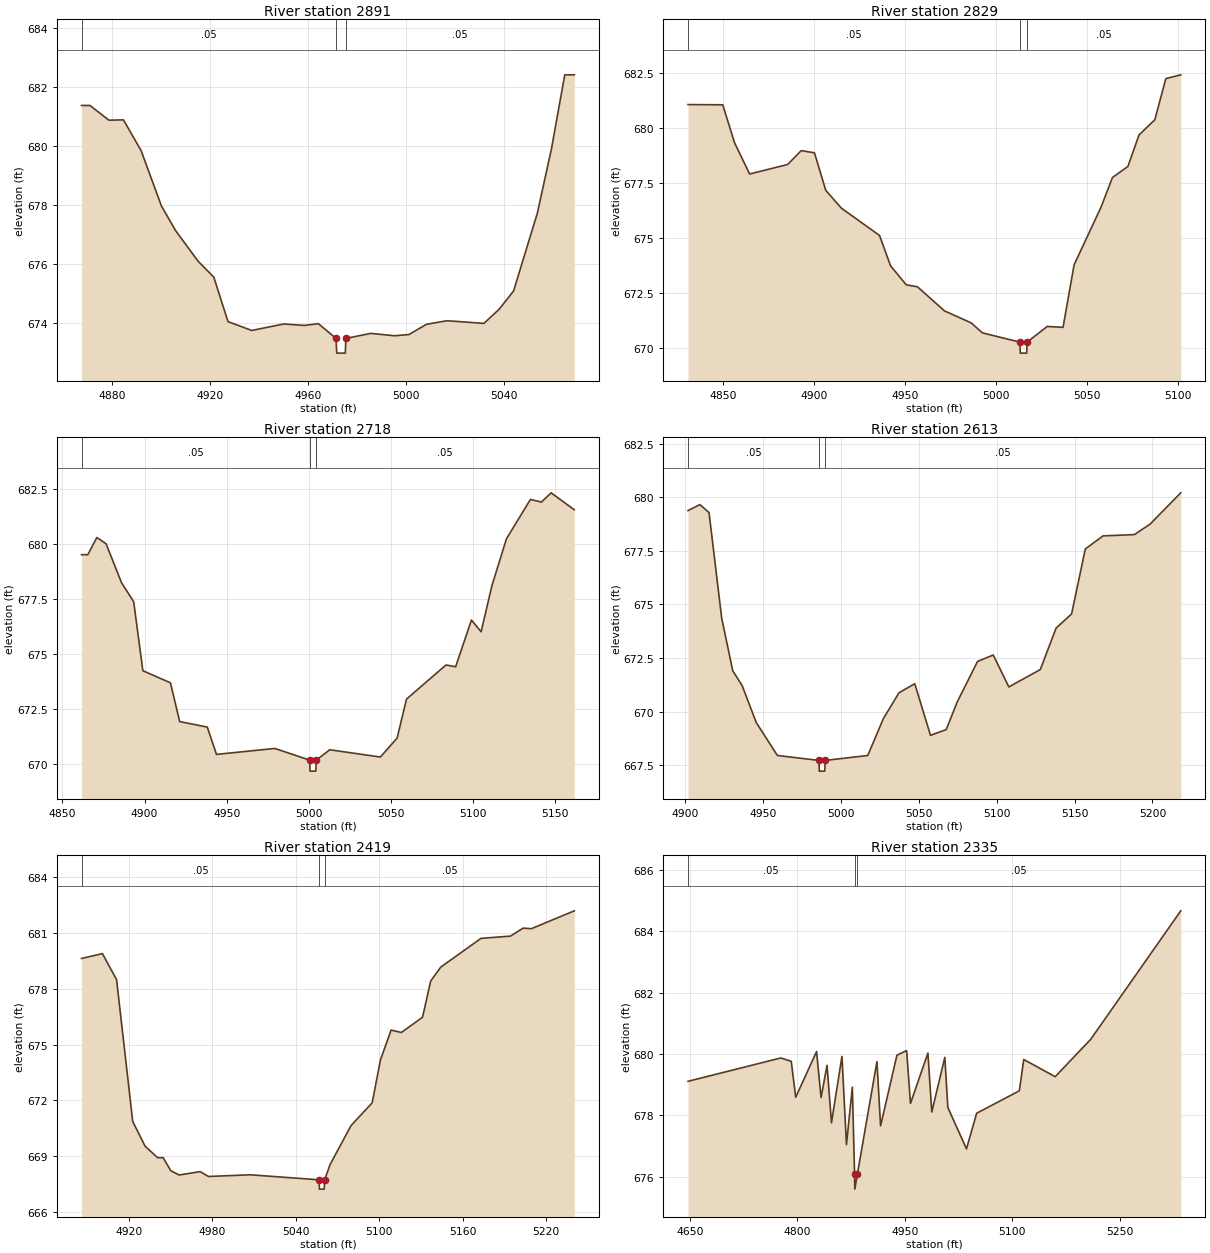
Type RM Length L Ch R = 1,2891,62,62,62
BEGIN DESCRIPTION:
Mapping XS 3c7e235a
END DESCRIPTION:
XS GIS Cut Line= 2
      2338192.08      7098110.79      2338088.41      7097938.36
#Sta/Elev= 30
  4867.5  681.37  4870.9  681.37  4878.7  680.87  4884.6  680.88  4891.8  679.84
  4900.1  677.96  4905.9  677.12  4915.1  676.08  4921.5  675.54  4927.3  674.03
  4937.0  673.73  4950.1  673.95  4958.4  673.90  4964.2  673.96  4971.4  673.46
  4971.7  672.96  4975.2  672.96  4975.4  673.46  4985.6  673.63  4995.3  673.55
  5001.1  673.59  5008.4  673.94  5016.7  674.06  5031.8  673.97  5038.0  674.45
  5043.9  675.07  5053.6  677.71  5059.4  679.91  5064.8  682.41  5068.7  682.41
#Mann=3,-1,0
  4867.5    0.05       0  4971.4   0.033       0  4975.4    0.05       0
Bank Sta=4971.4,4975.4
Exp/Cntr=0.3,0.1

Type RM Length L Ch R = 1,2829,111,111,111
BEGIN DESCRIPTION:
Mapping XS 1531740e
END DESCRIPTION:
XS GIS Cut Line= 2
      2338264.83      7098090.92      2338108.60      7097869.24
#Sta/Elev= 30
  4830.6  681.06  4849.7  681.05  4856.2  679.33  4864.5  677.91  4885.4  678.34
  4892.9  678.97  4900.2  678.87  4906.4  677.17  4915.0  676.36  4936.0  675.12
  4942.1  673.74  4950.7  672.88  4956.9  672.79  4971.7  671.70  4986.5  671.15
  4992.6  670.70  5013.2  670.28  5013.5  669.78  5017.0  669.78  5017.2  670.28
  5028.3  670.99  5037.0  670.95  5043.1  673.79  5057.9  676.40  5064.2  677.75
  5072.7  678.25  5078.8  679.68  5087.5  680.37  5093.6  682.24  5101.8  682.41
#Mann=3,-1,0
  4830.6    0.05       0  5013.2   0.033       0  5017.2    0.05       0
Bank Sta=5013.2,5017.2
Exp/Cntr=0.3,0.1

Type RM Length L Ch R = 1,2718,105,105,105
BEGIN DESCRIPTION:
Mapping XS 662e96dc
END DESCRIPTION:
XS GIS Cut Line= 4
      2338328.95      7097961.78      2338289.08      7097881.68
      2338183.01      7097857.95      2338096.24      7097805.03
#Sta/Elev= 30
  4861.7  679.51  4865.5  679.51  4871.0  680.29  4876.6  680.01  4886.0  678.24
  4893.4  677.38  4899.0  674.24  4915.8  673.69  4921.4  671.93  4938.2  671.68
  4943.8  670.44  4979.3  670.71  5000.5  670.18  5000.7  669.68  5004.2  669.68
  5004.5  670.18  5012.7  670.65  5043.5  670.32  5053.7  671.18  5059.4  672.95
  5083.4  674.50  5089.3  674.42  5098.9  676.54  5104.8  676.01  5111.4  678.11
  5120.2  680.23  5134.8  682.02  5141.5  681.90  5147.4  682.32  5161.5  681.55
#Mann=3,-1,0
  4861.7    0.05       0  5000.5   0.033       0  5004.5    0.05       0
Bank Sta=5000.5,5004.5
Exp/Cntr=0.3,0.1

Type RM Length L Ch R = 1,2613,194,194,194
BEGIN DESCRIPTION:
Mapping XS 697eb9ba
END DESCRIPTION:
XS GIS Cut Line= 3
      2338387.12      7097841.23      2338297.50      7097783.08
      2338089.42      7097758.17
#Sta/Elev= 30
  4901.8  679.38  4909.4  679.66  4915.3  679.29  4923.4  674.37  4930.5  671.91
  4936.5  671.22  4945.6  669.49  4959.2  667.95  4985.9  667.72  4986.1  667.22
  4989.6  667.22  4989.9  667.72  5017.2  667.95  5027.3  669.68  5037.3  670.88
  5047.4  671.30  5057.5  668.89  5067.6  669.16  5074.6  670.44  5087.7  672.34
  5097.8  672.64  5107.8  671.15  5128.0  671.96  5138.1  673.89  5148.1  674.56
  5156.9  677.59  5168.3  678.20  5188.4  678.26  5198.5  678.75  5218.2  680.21
#Mann=3,-1,0
  4901.8    0.05       0  4985.9   0.033       0  4989.9    0.05       0
Bank Sta=4985.9,4989.9
Exp/Cntr=0.3,0.1

Type RM Length L Ch R = 1,2419,84,84,84
BEGIN DESCRIPTION:
Mapping XS d4ea2d9a
END DESCRIPTION:
XS GIS Cut Line= 3
      2338451.03      7097734.66      2338438.57      7097677.35
      2338276.82      7097429.64
#Sta/Elev= 30
  4885.8  679.63  4900.8  679.89  4911.0  678.49  4922.6  670.87  4931.5  669.54
  4940.5  668.92  4944.5  668.92  4950.0  668.22  4956.0  667.99  4971.1  668.17
  4977.1  667.91  5007.3  668.00  5056.7  667.73  5056.9  667.23  5060.4  667.23
  5060.7  667.73  5064.6  668.55  5079.7  670.65  5094.9  671.87  5100.8  674.17
  5108.5  675.78  5115.9  675.65  5131.1  676.47  5137.0  678.42  5144.3  679.17
  5173.2  680.71  5194.3  680.83  5203.5  681.26  5209.4  681.23  5240.3  682.19
#Mann=3,-1,0
  4885.8    0.05       0  5056.7   0.033       0  5060.7    0.05       0
Bank Sta=5056.7,5060.7
Exp/Cntr=0.3,0.1

Type RM Length L Ch R = 1,2335,65,65,65
BEGIN DESCRIPTION:
Mapping XS ffc6e3fc
END DESCRIPTION:
XS GIS Cut Line= 6
      2338360.34      7097899.83      2338397.89      7097799.88
      2338476.29      7097696.89      2338490.03      7097641.64
      2338439.05      7097514.66      2338238.15      7097354.05
#Sta/Elev= 30
  4647.6  679.11  4777.0  679.87  4791.6  679.76  4797.8  678.59  4826.9  680.08
  4833.2  678.58  4841.5  679.63  4847.7  677.76  4862.3  679.92  4868.6  677.05
  4876.8  678.92  4879.9  676.10  4880.2  675.60  4883.9  676.10  4911.1  679.75
  4916.2  677.66  4939.0  679.96  4952.5  680.11  4957.9  678.39  4982.2  680.03
  4987.6  678.11  5005.8  679.89  5010.0  678.26  5036.0  676.91  5050.2  678.07
  5109.7  678.80  5115.9  679.82  5159.7  679.26  5209.4  680.48  5334.9  684.66
#Mann=3,-1,0
  4647.6    0.05       0  4879.9   0.033       0  4883.9    0.05       0
Bank Sta=4879.9,4883.9
Exp/Cntr=0.3,0.1

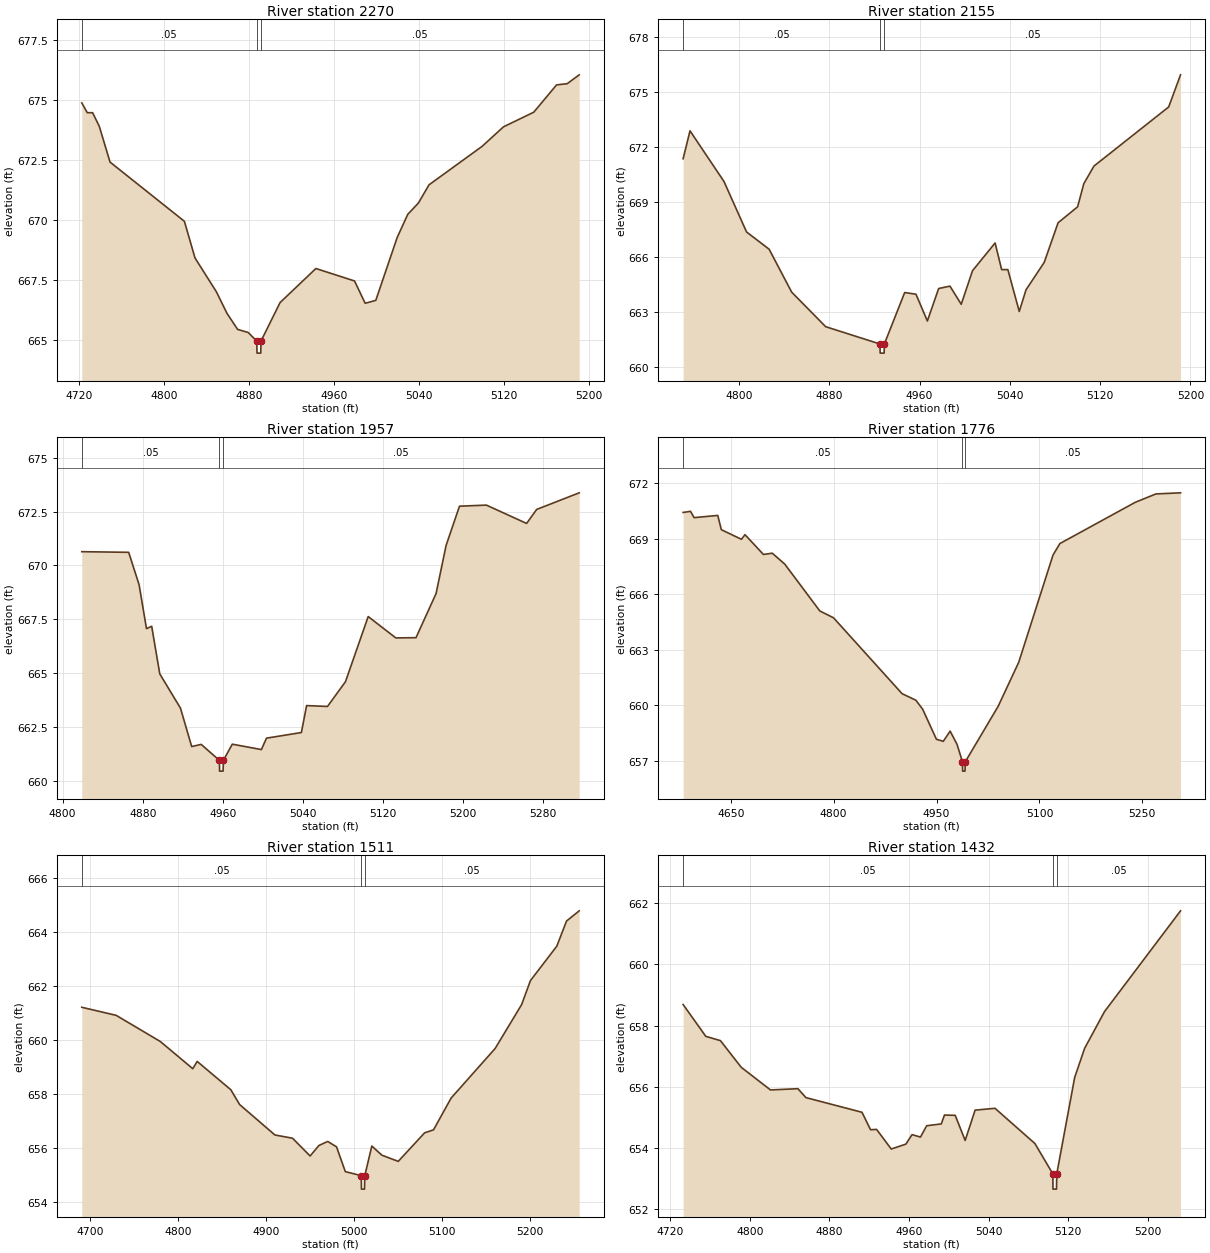
Type RM Length L Ch R = 1,2270,115,115,115
BEGIN DESCRIPTION:
Mapping XS 25879a0f
END DESCRIPTION:
XS GIS Cut Line= 2
      2338544.43      7097846.52      2338522.13      7097378.75
#Sta/Elev= 30
  4722.8  674.89  4728.0  674.48  4733.0  674.48  4739.3  673.91  4749.4  672.42
  4819.4  669.95  4829.4  668.42  4849.5  667.01  4859.5  666.11  4869.5  665.44
  4879.5  665.31  4887.5  664.95  4887.8  664.45  4891.3  664.45  4891.5  664.95
  4909.5  666.56  4943.2  667.98  4979.6  667.46  4989.6  666.53  4999.6  666.65
  5019.7  669.27  5029.7  670.24  5039.7  670.71  5049.7  671.47  5099.8  673.08
  5119.8  673.89  5148.3  674.50  5169.8  675.64  5179.8  675.69  5191.1  676.06
#Mann=3,-1,0
  4722.8    0.05       0  4887.5   0.033       0  4891.5    0.05       0
Bank Sta=4887.5,4891.5
Exp/Cntr=0.3,0.1

Type RM Length L Ch R = 1,2155,198,198,198
BEGIN DESCRIPTION:
Mapping XS bea2aff5
END DESCRIPTION:
XS GIS Cut Line= 3
      2338630.11      7097796.13      2338642.97      7097513.41
      2338576.29      7097370.52
#Sta/Elev= 30
  4750.5  671.36  4756.6  672.88  4786.7  670.12  4806.7  667.37  4826.7  666.43
  4846.7  664.09  4876.8  662.21  4924.8  661.27  4925.1  660.77  4928.6  660.77
  4928.8  661.27  4946.8  664.07  4956.8  663.98  4966.9  662.52  4976.9  664.29
  4986.9  664.42  4996.9  663.43  5006.9  665.26  5026.9  666.77  5032.7  665.32
  5038.2  665.32  5048.3  663.04  5054.3  664.22  5070.4  665.71  5082.7  667.87
  5100.0  668.74  5105.5  670.00  5114.5  670.96  5180.7  674.18  5191.2  675.93
#Mann=3,-1,0
  4750.5    0.05       0  4924.8   0.033       0  4928.8    0.05       0
Bank Sta=4924.8,4928.8
Exp/Cntr=0.3,0.1

Type RM Length L Ch R = 1,1957,181,181,181
BEGIN DESCRIPTION:
Mapping XS 40d86007
END DESCRIPTION:
XS GIS Cut Line= 3
      2338851.33      7097635.35      2338788.47      7097400.87
      2338760.79      7097147.73
#Sta/Elev= 30
  4819.1  670.64  4866.0  670.61  4876.4  669.11  4883.8  667.07  4889.0  667.18
  4897.1  664.97  4917.8  663.38  4929.0  661.60  4938.5  661.70  4956.7  660.96
  4956.9  660.46  4960.4  660.46  4960.7  660.96  4969.6  661.71  4998.7  661.46
  5003.8  661.99  5038.7  662.25  5043.9  663.50  5064.8  663.46  5082.8  664.61
  5105.5  667.63  5133.1  666.64  5153.3  666.65  5173.4  668.70  5183.4  670.93
  5196.8  672.75  5223.7  672.80  5263.9  671.95  5274.0  672.60  5316.5  673.37
#Mann=3,-1,0
  4819.1    0.05       0  4956.7   0.033       0  4960.7    0.05       0
Bank Sta=4956.7,4960.7
Exp/Cntr=0.3,0.1

Type RM Length L Ch R = 1,1776,265,265,265
BEGIN DESCRIPTION:
Mapping XS ca5d1448
END DESCRIPTION:
XS GIS Cut Line= 3
      2338870.48      7097742.94      2338917.63      7097570.31
      2338915.20      7097024.07
#Sta/Elev= 30
  4580.5  670.42  4591.3  670.48  4596.5  670.14  4631.0  670.26  4636.2  669.49
  4665.5  668.97  4670.7  669.22  4697.6  668.15  4710.4  668.22  4728.7  667.63
  4779.8  665.10  4799.8  664.73  4899.8  660.63  4919.8  660.28  4929.8  659.79
  4949.8  658.17  4959.8  658.06  4969.8  658.61  4979.8  657.90  4987.8  656.95
  4988.0  656.45  4991.5  656.45  4991.8  656.95  5039.8  659.95  5069.8  662.33
  5119.8  668.12  5129.8  668.74  5239.8  670.97  5269.8  671.42  5305.7  671.48
#Mann=3,-1,0
  4580.5    0.05       0  4987.8   0.033       0  4991.8    0.05       0
Bank Sta=4987.8,4991.8
Exp/Cntr=0.3,0.1

Type RM Length L Ch R = 1,1511,79,79,79
BEGIN DESCRIPTION:
Mapping XS f4d1fd6d
END DESCRIPTION:
XS GIS Cut Line= 2
      2339180.11      7097549.10      2339153.12      7096984.65
#Sta/Elev= 30
  4690.7  661.22  4729.8  660.92  4779.9  659.95  4816.8  658.94  4821.8  659.21
  4860.0  658.16  4870.0  657.61  4910.1  656.48  4930.1  656.36  4950.1  655.70
  4960.1  656.09  4970.1  656.24  4980.1  656.04  4990.1  655.12  5008.2  654.97
  5008.4  654.47  5011.9  654.47  5012.2  654.97  5020.2  656.07  5031.6  655.73
  5050.2  655.50  5080.2  656.56  5090.3  656.67  5110.3  657.85  5160.3  659.69
  5190.4  661.32  5200.4  662.21  5230.4  663.49  5241.4  664.42  5255.8  664.80
#Mann=3,-1,0
  4690.7    0.05       0  5008.2   0.033       0  5012.2    0.05       0
Bank Sta=5008.2,5012.2
Exp/Cntr=0.3,0.1

Type RM Length L Ch R = 1,1432,137,137,137
BEGIN DESCRIPTION:
Mapping XS d364f76b
END DESCRIPTION:
XS GIS Cut Line= 3
      2339397.35      7097443.49      2339242.89      7097229.81
      2339232.87      7096993.68
#Sta/Elev= 30
  4733.0  658.69  4755.8  657.65  4770.5  657.51  4791.4  656.64  4820.8  655.90
  4848.4  655.94  4856.4  655.65  4912.8  655.17  4921.4  654.60  4927.5  654.61
  4942.2  653.97  4956.9  654.13  4963.1  654.44  4971.6  654.36  4977.8  654.73
  4992.5  654.79  4995.7  655.08  5006.5  655.07  5016.5  654.25  5026.5  655.24
  5046.5  655.30  5086.6  654.15  5104.6  653.16  5104.8  652.66  5108.3  652.66
  5108.6  653.16  5126.6  656.31  5136.6  657.26  5156.6  658.46  5233.0  661.75
#Mann=3,-1,0
  4733.0    0.05       0  5104.6   0.033       0  5108.6    0.05       0
Bank Sta=5104.6,5108.6
Exp/Cntr=0.3,0.1