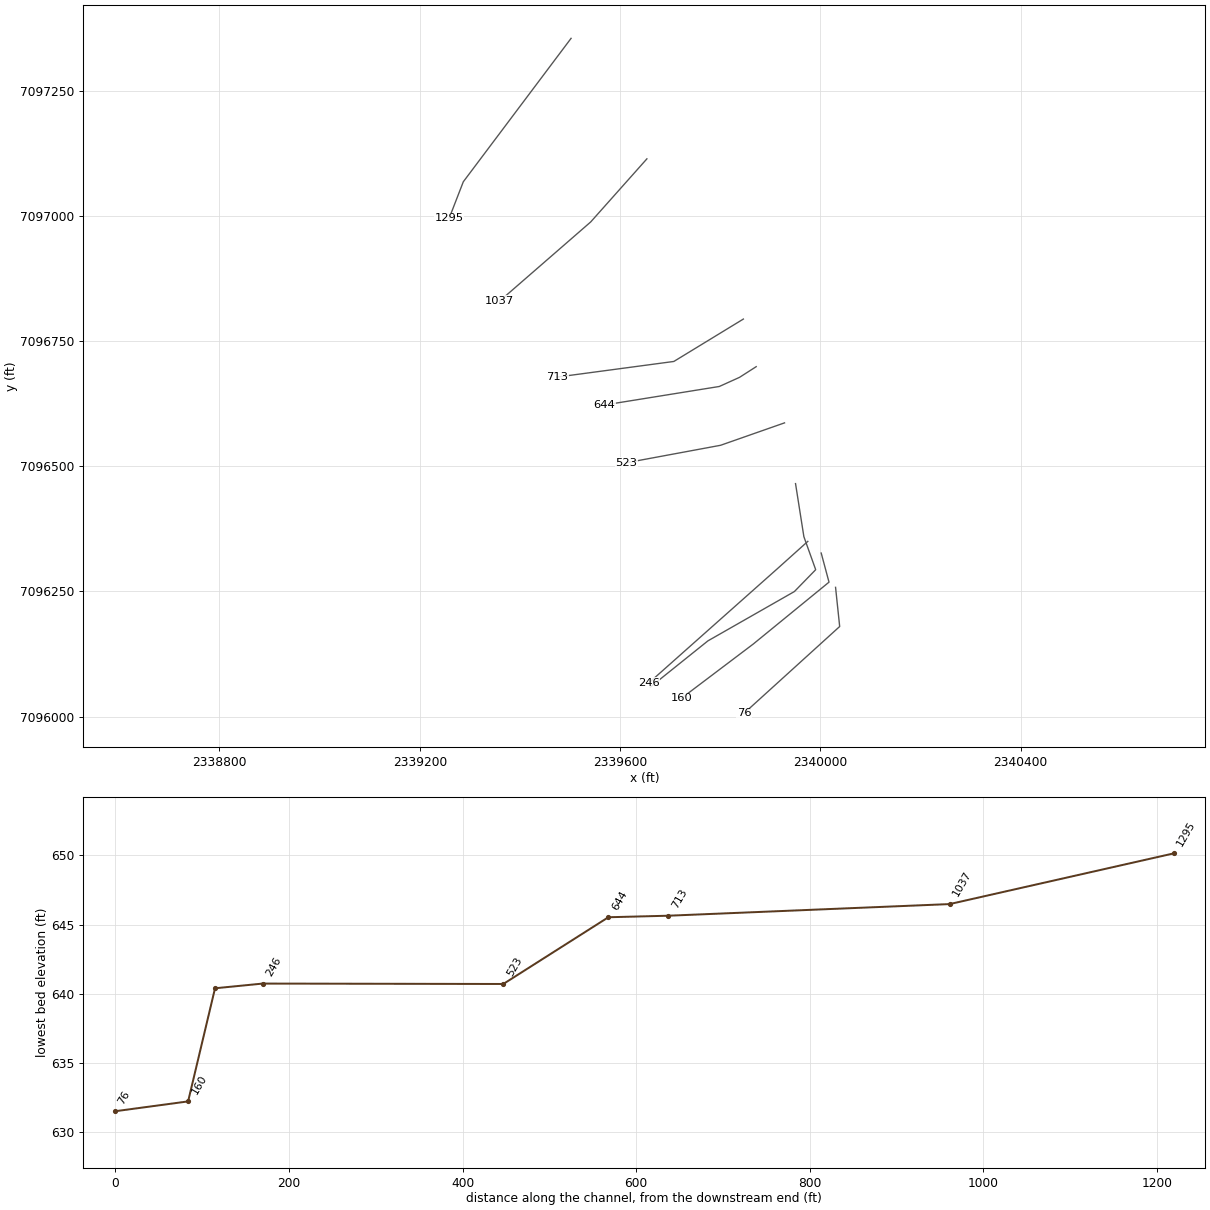
HEC-RAS study Hog Branch Tributary 1.prj: Hog Branch Tributary 1 Base Level Engineering

--- Hog Branch Tributary 1.g01 (geometry) --- (continued)

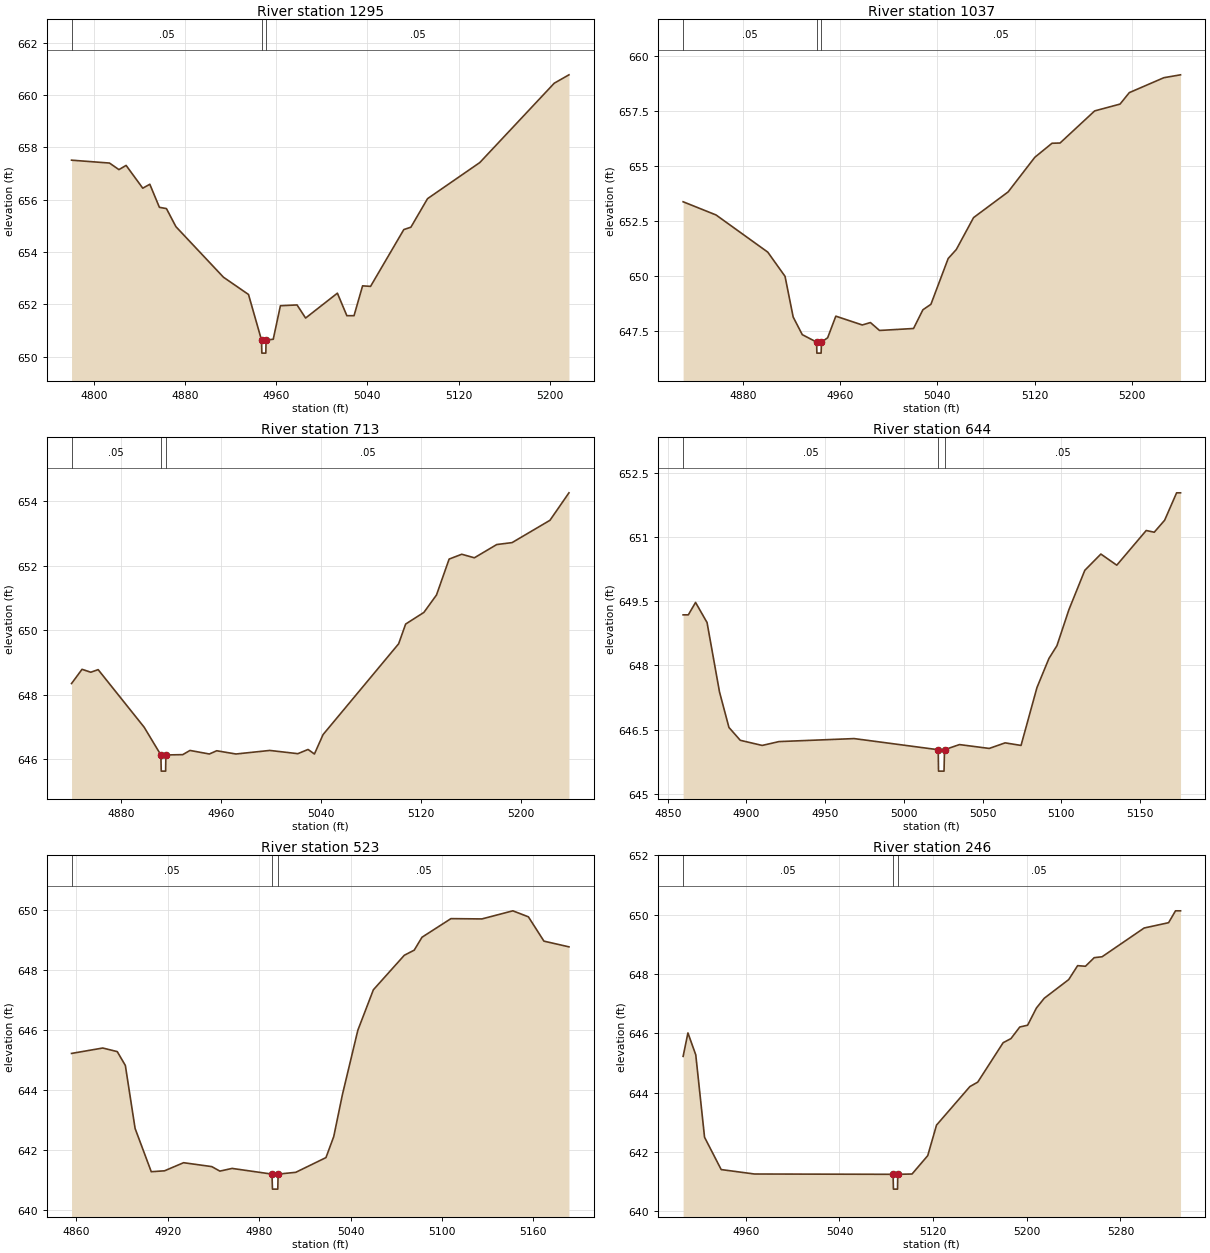
Type RM Length L Ch R = 1,1295,258,258,258
BEGIN DESCRIPTION:
Hog Branch Tributary 1 5.0
END DESCRIPTION:
XS GIS Cut Line= 3
      2339502.10      7097354.19      2339286.87      7097067.73
      2339258.63      7096994.81
#Sta/Elev= 30
  4780.4  657.51  4813.7  657.40  4822.0  657.15  4828.3  657.31  4842.9  656.44
  4849.1  656.59  4857.5  655.71  4863.7  655.66  4872.0  654.97  4913.7  653.04
  4935.7  652.38  4947.1  650.64  4947.4  650.14  4950.9  650.14  4951.1  650.64
  4957.4  650.67  4963.7  651.95  4978.3  651.98  4985.8  651.48  5013.7  652.43
  5022.0  651.57  5028.3  651.57  5035.8  652.71  5042.8  652.69  5072.0  654.86
  5078.2  654.95  5092.8  656.04  5138.7  657.42  5204.0  660.45  5216.9  660.77
#Mann=3,-1,0
  4780.4    0.05       0  4947.1    0.04       0  4951.1    0.05       0
Bank Sta=4947.1,4951.1
Exp/Cntr=0.3,0.1

Type RM Length L Ch R = 1,1037,324,324,324
BEGIN DESCRIPTION:
Hog Branch Tributary 1 4.0
END DESCRIPTION:
XS GIS Cut Line= 3
      2339653.49      7097113.55      2339541.29      7096987.55
      2339359.54      7096829.61
#Sta/Elev= 30
  4830.7  653.36  4857.8  652.76  4900.4  651.07  4914.6  649.97  4921.3  648.12
  4928.8  647.32  4940.6  646.98  4940.8  646.48  4944.3  646.48  4944.6  646.98
  4949.7  647.18  4956.4  648.16  4978.2  647.76  4984.9  647.87  4992.4  647.51
  5020.4  647.60  5028.1  648.45  5034.7  648.70  5048.9  650.78  5055.6  651.19
  5069.8  652.64  5098.3  653.81  5120.2  655.38  5134.4  656.02  5141.0  656.03
  5169.5  657.49  5190.4  657.80  5198.0  658.32  5226.5  659.00  5240.2  659.13
#Mann=3,-1,0
  4830.7    0.05       0  4940.6   0.033       0  4944.6    0.05       0
Bank Sta=4940.6,4944.6
Exp/Cntr=0.3,0.1

Type RM Length L Ch R = 1,713,69,69,69
BEGIN DESCRIPTION:
Hog Branch Tributary 1 3.0
END DESCRIPTION:
XS GIS Cut Line= 3
      2339846.15      7096793.66      2339707.31      7096708.96
      2339473.93      7096677.71
#Sta/Elev= 30
  4840.5  648.35  4848.9  648.79  4855.9  648.70  4861.8  648.78  4898.6  647.00
  4912.0  646.14  4912.3  645.64  4915.8  645.64  4916.0  646.14  4929.5  646.15
  4935.3  646.28  4950.8  646.17  4956.7  646.27  4972.1  646.17  4999.2  646.28
  5021.6  646.18  5029.8  646.31  5034.9  646.17  5041.8  646.77  5102.3  649.58
  5107.9  650.19  5122.5  650.55  5132.6  651.09  5142.7  652.20  5152.8  652.35
  5162.9  652.24  5180.8  652.65  5193.1  652.71  5223.4  653.40  5238.6  654.25
#Mann=3,-1,0
  4840.5    0.05       0  4912.0   0.033       0  4916.0    0.05       0
Bank Sta=4912,4916
Exp/Cntr=0.3,0.1

Type RM Length L Ch R = 1,644,121,121,121
BEGIN DESCRIPTION:
Mapping XS f8b74b56
END DESCRIPTION:
XS GIS Cut Line= 4
      2339871.77      7096698.57      2339838.45      7096677.23
      2339798.10      7096659.00      2339569.00      7096622.10
#Sta/Elev= 30
  4859.8  649.18  4863.1  649.18  4867.7  649.47  4875.0  649.00  4882.9  647.38
  4888.9  646.55  4896.1  646.25  4910.0  646.13  4920.7  646.22  4968.4  646.29
  5021.8  646.03  5022.0  645.53  5025.5  645.53  5025.8  646.03  5035.3  646.15
  5054.2  646.06  5064.3  646.19  5074.4  646.13  5084.5  647.48  5092.1  648.16
  5097.2  648.46  5104.8  649.30  5114.9  650.22  5125.1  650.60  5135.2  650.34
  5153.9  651.15  5159.0  651.11  5165.6  651.39  5173.2  652.03  5175.7  652.03
#Mann=3,-1,0
  4859.8    0.05       0  5021.8   0.033       0  5025.8    0.05       0
Bank Sta=5021.8,5025.8
Exp/Cntr=0.3,0.1

Type RM Length L Ch R = 1,523,277,277,277
BEGIN DESCRIPTION:
Mapping XS 1a4b65c3
END DESCRIPTION:
XS GIS Cut Line= 3
      2339928.33      7096586.34      2339800.69      7096541.59
      2339612.85      7096506.73
#Sta/Elev= 30
  4857.0  645.23  4877.5  645.41  4887.0  645.29  4892.3  644.83  4898.7  642.73
  4909.3  641.29  4918.0  641.32  4930.5  641.59  4949.0  641.46  4954.3  641.31
  4962.3  641.40  4988.5  641.21  4988.8  640.71  4992.3  640.71  4992.5  641.21
  5004.1  641.27  5023.9  641.76  5029.0  642.46  5034.7  643.86  5044.8  646.00
  5055.0  647.35  5075.3  648.50  5081.8  648.67  5086.9  649.10  5105.9  649.72
  5126.2  649.71  5146.5  649.98  5156.7  649.78  5166.9  648.97  5183.3  648.78
#Mann=3,-1,0
  4857.0    0.05       0  4988.5   0.033       0  4992.5    0.05       0
Bank Sta=4988.5,4992.5
Exp/Cntr=0.3,0.1

Type RM Length L Ch R = 1,246,55,55,55
BEGIN DESCRIPTION:
Mapping XS 4a294ed8
END DESCRIPTION:
XS GIS Cut Line= 3
      2339974.83      7096349.69      2339914.25      7096295.30
      2339657.55      7096067.23
#Sta/Elev= 30
  4906.5  645.22  4910.6  646.01  4917.3  645.27  4924.8  642.49  4939.0  641.40
  4967.4  641.25  5085.8  641.24  5086.1  640.74  5089.6  640.74  5089.8  641.24
  5102.0  641.25  5115.4  641.87  5122.9  642.90  5151.4  644.20  5158.1  644.35
  5179.8  645.68  5186.5  645.82  5194.0  646.21  5200.7  646.27  5208.2  646.85
  5214.9  647.18  5235.8  647.81  5243.4  648.28  5250.1  648.26  5257.6  648.55
  5264.3  648.58  5300.2  649.55  5321.1  649.73  5327.0  650.13  5331.3  650.13
#Mann=3,-1,0
  4906.5    0.05       0  5085.8   0.033       0  5089.8    0.05       0
Bank Sta=5085.8,5089.8
Exp/Cntr=0.3,0.1

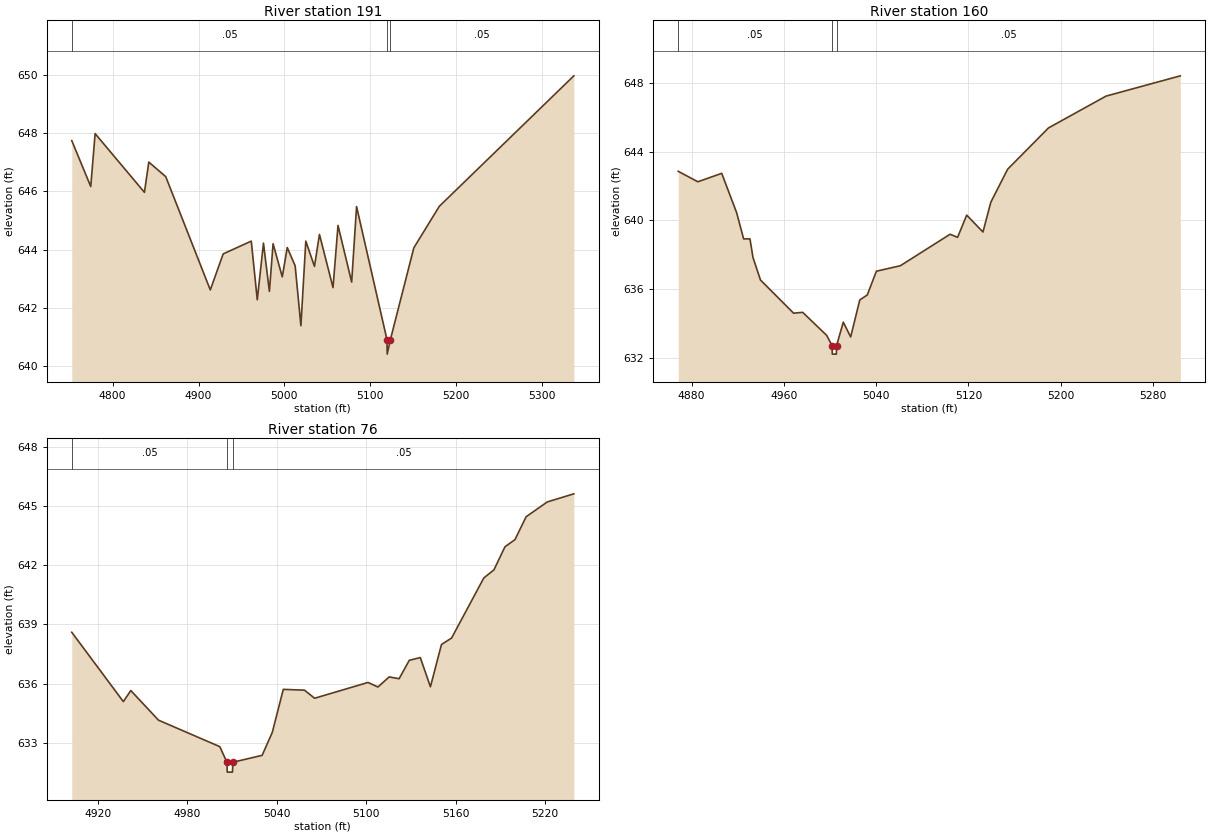
Type RM Length L Ch R = 1,191,31,31,31
BEGIN DESCRIPTION:
Mapping XS cb7d65bb
END DESCRIPTION:
XS GIS Cut Line= 6
      2339950.29      7096465.07      2339966.96      7096359.11
      2339990.55      7096293.15      2339948.08      7096249.56
      2339775.31      7096151.00      2339660.22      7096058.71
#Sta/Elev= 30
  4752.4  647.75  4774.5  646.17  4779.6  647.99  4837.0  645.97  4842.1  647.01
  4861.8  646.51  4913.7  642.61  4928.7  643.85  4961.4  644.29  4968.4  642.27
  4975.6  644.22  4982.5  642.56  4986.8  644.20  4997.5  643.06  5003.3  644.07
  5012.5  643.44  5019.2  641.38  5024.9  644.29  5035.0  643.42  5040.8  644.52
  5056.6  642.69  5062.4  644.83  5078.3  642.88  5084.0  645.48  5119.4  640.90
  5119.7  640.40  5123.4  640.90  5150.7  644.06  5180.4  645.49  5337.0  649.98
#Mann=3,-1,0
  4752.4    0.05       0  5119.4   0.033       0  5123.4    0.05       0
Bank Sta=5119.4,5123.4
Exp/Cntr=0.3,0.1

Type RM Length L Ch R = 1,160,84,84,84
BEGIN DESCRIPTION:
Mapping XS b179c02b
END DESCRIPTION:
XS GIS Cut Line= 4
      2340001.54      7096326.42      2340017.15      7096268.27
      2339865.94      7096144.74      2339722.45      7096036.34
#Sta/Elev= 30
  4868.4  642.86  4885.4  642.25  4906.1  642.74  4919.0  640.46  4925.1  638.93
  4930.6  638.93  4933.2  637.85  4939.7  636.54  4968.4  634.61  4976.3  634.66
  4997.1  633.32  5001.7  632.73  5002.0  632.23  5005.5  632.23  5005.7  632.73
  5011.5  634.09  5017.9  633.23  5025.8  635.38  5032.3  635.67  5040.2  637.05
  5061.0  637.37  5104.1  639.20  5110.6  639.02  5118.5  640.31  5132.6  639.33
  5139.4  641.06  5154.0  642.98  5189.4  645.38  5239.3  647.23  5303.7  648.41
#Mann=3,-1,0
  4868.4    0.05       0  5001.7    0.04       0  5005.7    0.05       0
Bank Sta=5001.7,5005.7
Exp/Cntr=0.3,0.1

Type RM Length L Ch R = 1,76,0,0,0
BEGIN DESCRIPTION:
Hog Branch Tributary 1 2.0
END DESCRIPTION:
XS GIS Cut Line= 3
      2340030.22      7096257.91      2340038.46      7096179.71
      2339847.26      7096006.24
#Sta/Elev= 30
  4902.4  638.60  4937.0  635.09  4942.0  635.65  4960.6  634.15  5001.7  632.81
  5006.5  632.02  5006.7  631.52  5010.2  631.52  5010.5  632.02  5030.1  632.37
  5036.9  633.53  5044.3  635.71  5058.5  635.67  5065.3  635.26  5101.1  636.06
  5107.8  635.83  5115.3  636.34  5122.0  636.25  5128.8  637.18  5136.2  637.32
  5143.0  635.84  5150.4  637.98  5157.2  638.31  5178.8  641.35  5185.6  641.76
  5193.0  642.93  5199.7  643.29  5207.2  644.45  5221.4  645.20  5239.2  645.61
#Mann=3,-1,0
  4902.4    0.05       0  5006.5    0.04       0  5010.5    0.05       0
Bank Sta=5006.5,5010.5
Exp/Cntr=0.3,0.1

Chan Stop Cuts=-1