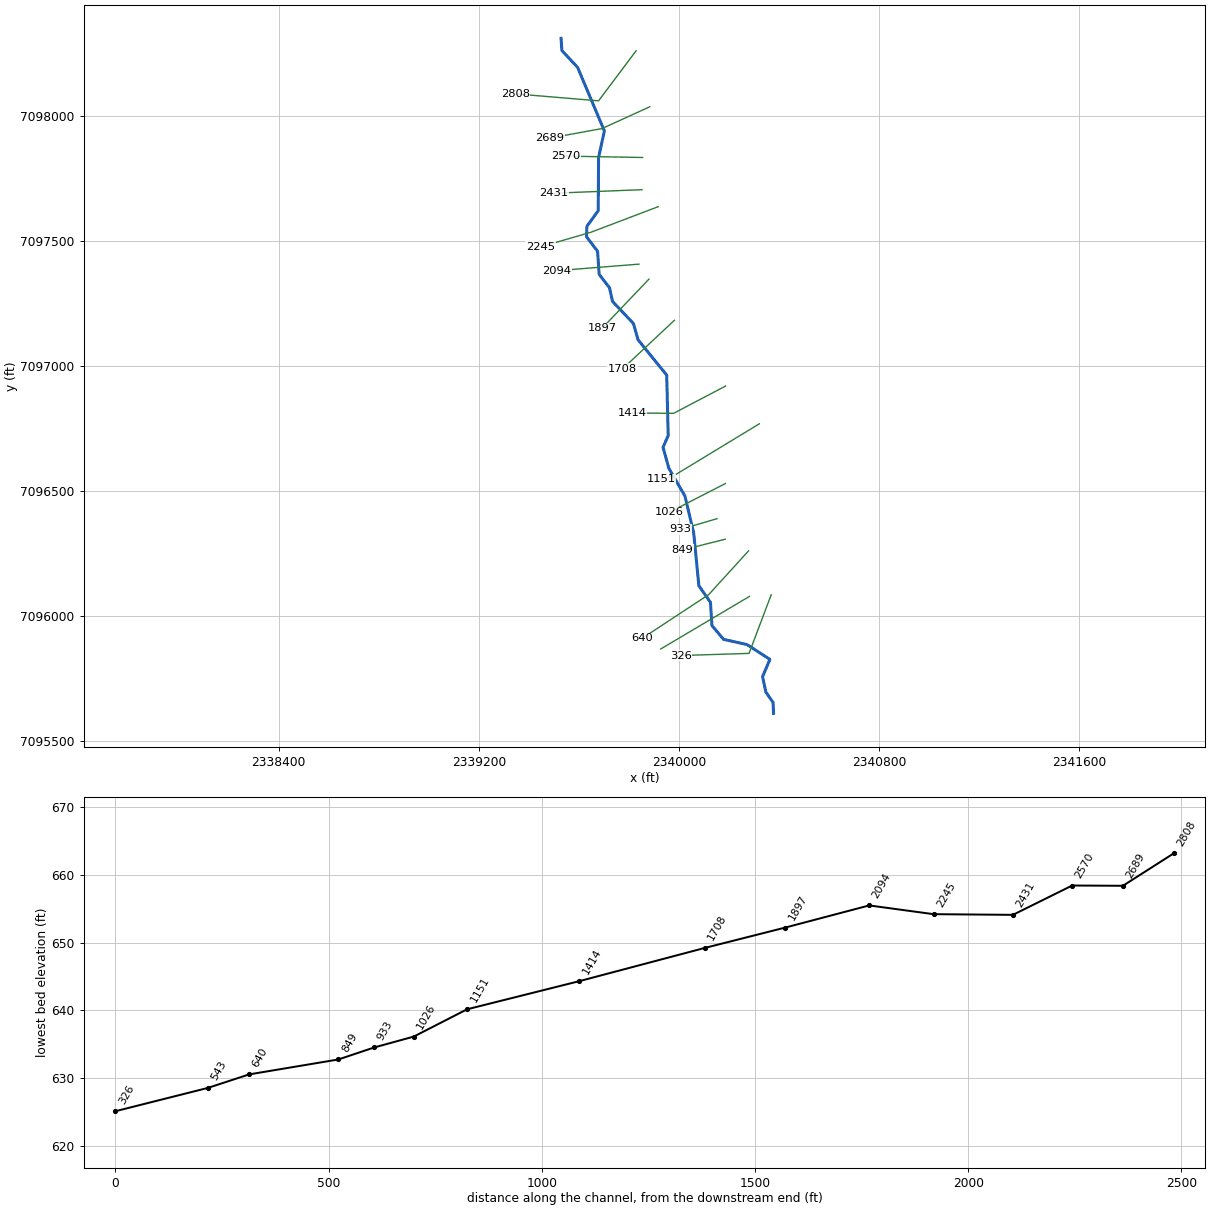
--- Hog Branch Tributary 1_1.prj (project) ---

Proj Title=Hog Branch Tributary 1_1 Base Level Engineering
Current Plan=p01
Default Exp/Contr=0.3,0.1
English Units
Geom File=g01
Flow File=f01
Plan File=p01
BEGIN DESCRIPTION:
Hog Branch Tributary 1_1
END DESCRIPTION:

--- Hog Branch Tributary 1_1.p01 (plan) ---

Plan Title=Multiple Run
Short Identifier=Multiple
Geom File=g01
Flow File=f01
Subcritical Flow
K Sum by GR= 0
Std Step Tol= 0.01
Critical Tol= 0.01
Num of Std Step Trials= 20
Max Error Tol= 0.3
Flow Tol Ratio= 0.001
Split Flow NTrial= 30
Split Flow Tol= 0.02
Split Flow Ratio= 0.02
Log Output Level= 0
Friction Slope Method= 1
Unsteady Friction Slope Method= 2
Unsteady Bridges Friction Slope Method= 1
Parabolic Critical Depth
Global Vel Dist=  1 , 1 , 1
Global Log Level= 0
CheckData=True
Encroach Param= -1, 0, 0, 0
BEGIN DESCRIPTION:
Multiple Run
END DESCRIPTION:

--- Hog Branch Tributary 1_1.f01 (steady flow) ---

Flow Title=Multiple
Number of Profiles=7
Profile Names=10-year,25-year,50-year,1pct_min,100-year,1pct_plu,500-year
River Rch & RM= Hog Branch Tribu,Reach-1,2808
     174     220     255     148     295     588     392
River Rch & RM= Hog Branch Tribu,Reach-1,640
     492     667     809     488     975    1945    1416
Boundary for River Rch & Prof#=Hog Branch Tribu,Reach-1,1
Up Type=0
Dn Type=3
Dn Slope=0.005
Boundary for River Rch & Prof#=Hog Branch Tribu,Reach-1,2
Up Type=0
Dn Type=3
Dn Slope=0.005
Boundary for River Rch & Prof#=Hog Branch Tribu,Reach-1,3
Up Type=0
Dn Type=3
Dn Slope=0.005
Boundary for River Rch & Prof#=Hog Branch Tribu,Reach-1,4
Up Type=0
Dn Type=3
Dn Slope=0.005
Boundary for River Rch & Prof#=Hog Branch Tribu,Reach-1,5
Up Type=0
Dn Type=3
Dn Slope=0.005
Boundary for River Rch & Prof#=Hog Branch Tribu,Reach-1,6
Up Type=0
Dn Type=3
Dn Slope=0.005
Boundary for River Rch & Prof#=Hog Branch Tribu,Reach-1,7
Up Type=0
Dn Type=3
Dn Slope=0.005

--- Hog Branch Tributary 1_1.g01 (geometry) ---

Geom Title=Existing Conditions

River Reach=Hog Branch Tribu,Reach-1
Reach XY= 30
      2339529.00      7098310.00      2339532.27      7098261.36
      2339595.24      7098193.71      2339702.31      7097939.52
      2339679.02      7097833.17      2339677.76      7097620.50
      2339632.37      7097558.26      2339630.82      7097516.12
      2339675.11      7097458.42      2339681.33      7097365.97
      2339722.86      7097312.17      2339734.84      7097257.71
      2339818.20      7097169.67      2339837.18      7097103.96
      2339951.60      7096962.98      2339957.50      7096721.52
      2339936.92      7096674.01      2339960.26      7096590.07
      2340024.30      7096480.02      2340059.58      7096331.22
      2340080.22      7096120.50      2340126.64      7096054.02
      2340132.52      7095961.28      2340179.10      7095905.97
      2340272.68      7095885.29      2340364.34      7095825.96
      2340335.01      7095756.82      2340348.13      7095695.18
      2340377.01      7095653.73      2340379.00      7095610.00

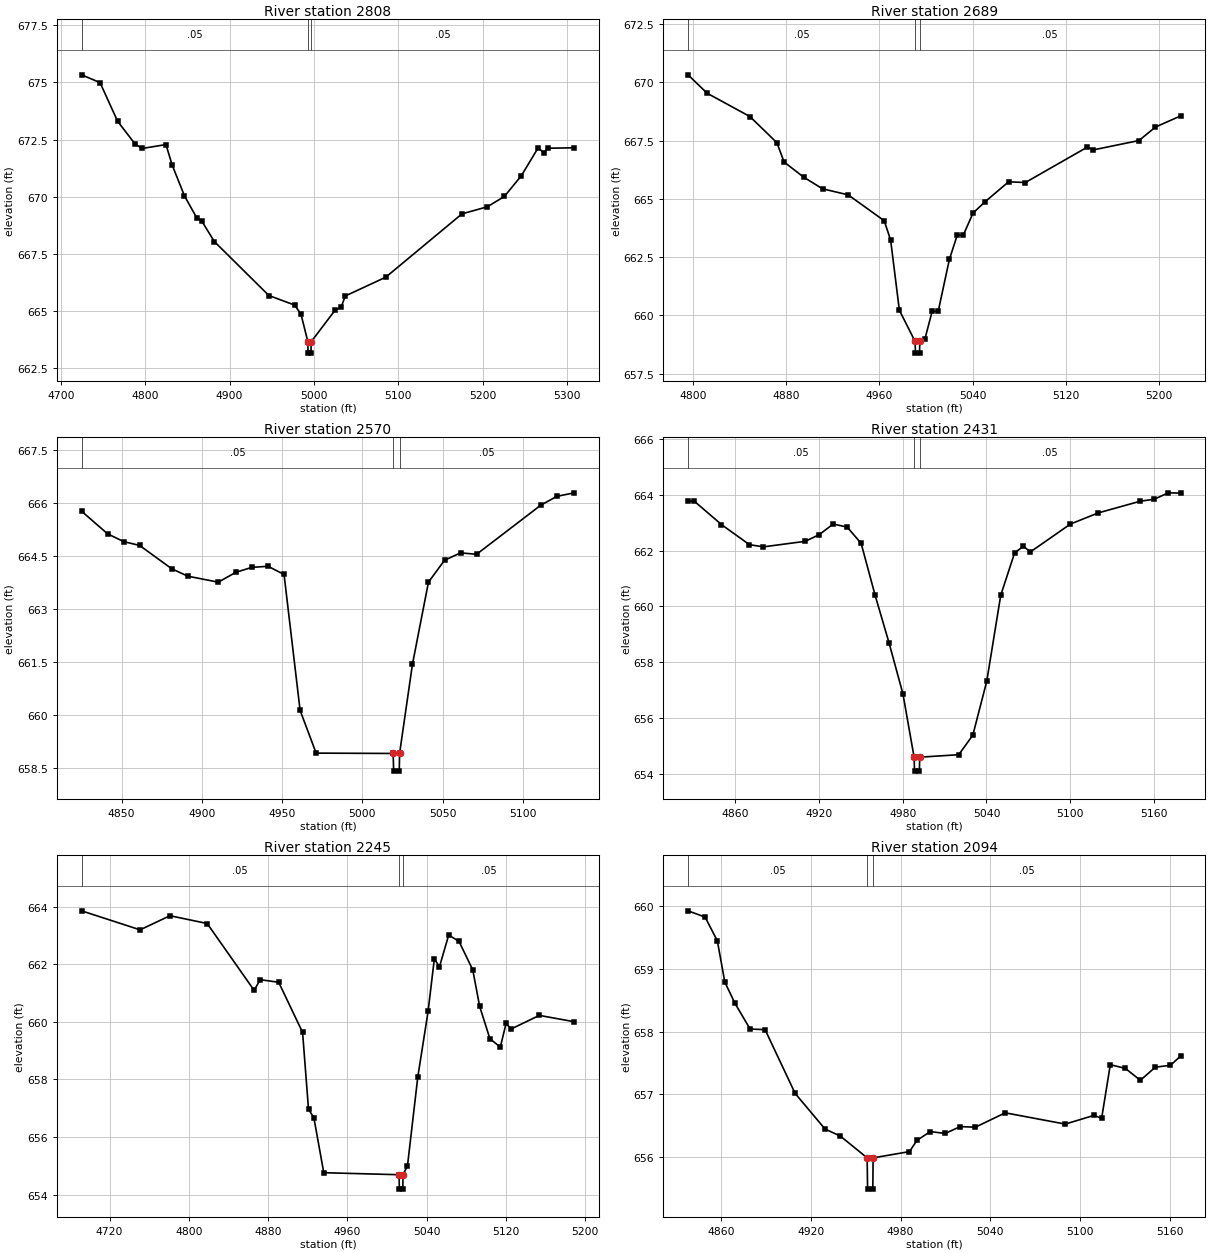
Type RM Length L Ch R = 1,2808,119,119,119
BEGIN DESCRIPTION:
Hog Branch Tributary 1_1 6.0
END DESCRIPTION:
XS GIS Cut Line= 3
      2339828.99      7098259.99      2339679.00      7098060.00
      2339346.35      7098087.88
#Sta/Elev= 30
  4724.6  675.33  4746.5  674.99  4767.3  673.30  4788.1  672.30  4796.5  672.11
  4824.6  672.28  4831.9  671.39  4846.5  670.04  4861.0  669.08  4867.3  668.92
  4881.9  668.04  4946.5  665.68  4977.1  665.26  4984.6  664.86  4992.7  663.66
  4992.9  663.16  4996.4  663.16  4996.7  663.66  5024.8  665.03  5032.1  665.17
  5037.1  665.66  5085.0  666.48  5175.3  669.25  5205.4  669.56  5225.5  670.01
  5245.5  670.91  5265.6  672.14  5272.3  671.92  5277.3  672.12  5308.4  672.14
#Mann=3,-1,0
  4724.6    0.05       0  4992.7    0.04       0  4996.7    0.05       0
Bank Sta=4992.7,4996.7
Exp/Cntr=0.3,0.1

Type RM Length L Ch R = 1,2689,119,119,119
BEGIN DESCRIPTION:
Mapping XS 2c435df8
END DESCRIPTION:
XS GIS Cut Line= 3
      2339883.95      7098036.35      2339692.86      7097949.08
      2339483.68      7097910.91
#Sta/Elev= 30
  4795.9  670.32  4812.3  669.53  4849.0  668.53  4872.1  667.41  4878.3  666.58
  4895.1  665.93  4911.3  665.43  4933.3  665.17  4964.2  664.06  4969.7  663.23
  4977.2  660.22  4990.7  658.88  4991.0  658.38  4994.5  658.38  4994.7  658.88
  4999.2  659.00  5005.3  660.17  5010.5  660.17  5020.1  662.40  5026.9  663.45
  5032.0  663.44  5040.4  664.39  5050.6  664.87  5070.9  665.73  5085.3  665.70
  5138.5  667.22  5143.6  667.10  5182.7  667.50  5196.9  668.08  5218.6  668.56
#Mann=3,-1,0
  4795.9    0.05       0  4990.7    0.04       0  4994.7    0.05       0
Bank Sta=4990.7,4994.7
Exp/Cntr=0.3,0.1

Type RM Length L Ch R = 1,2570,139,139,139
BEGIN DESCRIPTION:
Mapping XS 6428b291
END DESCRIPTION:
XS GIS Cut Line= 2
      2339855.18      7097833.43      2339548.13      7097838.84
#Sta/Elev= 25
  4825.0  665.78  4841.2  665.14  4851.2  664.92  4861.2  664.81  4881.2  664.15
  4891.2  663.94  4910.2  663.77  4921.2  664.05  4931.2  664.19  4941.2  664.22
  4951.2  663.99  4961.2  660.14  4971.2  658.93  5019.2  658.92  5019.5  658.42
  5023.0  658.42  5023.2  658.92  5031.2  661.44  5041.2  663.77  5051.2  664.39
  5061.2  664.60  5071.2  664.56  5111.2  665.95  5121.2  666.20  5132.1  666.30
#Mann=3,-1,0
  4825.0    0.05       0  5019.2    0.04       0  5023.2    0.05       0
Bank Sta=5019.2,5023.2
Exp/Cntr=0.3,0.1

Type RM Length L Ch R = 1,2431,186,186,186
BEGIN DESCRIPTION:
Mapping XS 864e5021
END DESCRIPTION:
XS GIS Cut Line= 2
      2339852.99      7097704.68      2339499.97      7097690.53
#Sta/Elev= 30
  4826.0  663.78  4830.5  663.78  4850.0  662.94  4870.0  662.22  4880.0  662.14
  4910.1  662.34  4920.1  662.58  4930.1  662.96  4940.1  662.85  4950.1  662.27
  4960.1  660.41  4970.1  658.70  4980.1  656.86  4988.1  654.59  4988.4  654.09
  4991.9  654.09  4992.1  654.59  5020.1  654.68  5030.2  655.38  5040.2  657.32
  5050.2  660.40  5060.2  661.93  5066.5  662.16  5071.5  661.96  5100.2  662.96
  5120.2  663.36  5150.3  663.78  5160.3  663.85  5170.3  664.08  5179.3  664.07
#Mann=3,-1,0
  4826.0    0.05       0  4988.1    0.04       0  4992.1    0.05       0
Bank Sta=4988.1,4992.1
Exp/Cntr=0.3,0.1

Type RM Length L Ch R = 1,2245,151,151,151
BEGIN DESCRIPTION:
Hog Branch Tributary 1_1 5.0
END DESCRIPTION:
XS GIS Cut Line= 3
      2339917.53      7097636.65      2339647.46      7097534.02
      2339447.21      7097475.99
#Sta/Elev= 30
  4691.7  663.85  4750.8  663.19  4780.9  663.68  4818.5  663.41  4865.9  661.09
  4872.0  661.46  4890.7  661.37  4914.8  659.63  4920.8  656.96  4926.2  656.67
  4936.2  654.76  5012.2  654.69  5012.5  654.19  5016.0  654.19  5016.2  654.69
  5020.7  655.00  5031.1  658.08  5041.5  660.36  5047.8  662.18  5053.0  661.91
  5062.3  663.01  5072.7  662.79  5086.6  661.80  5093.5  660.54  5103.9  659.41
  5114.4  659.12  5120.2  659.94  5125.4  659.75  5153.8  660.22  5189.1  660.00
#Mann=3,-1,0
  4691.7    0.05       0  5012.2    0.04       0  5016.2    0.05       0
Bank Sta=5012.2,5016.2
Exp/Cntr=0.3,0.1

Type RM Length L Ch R = 1,2094,197,197,197
BEGIN DESCRIPTION:
Mapping XS c1322bb9
END DESCRIPTION:
XS GIS Cut Line= 2
      2339840.35      7097406.80      2339512.08      7097380.76
#Sta/Elev= 30
  4838.0  659.93  4849.4  659.83  4857.6  659.45  4862.6  658.79  4869.4  658.45
  4879.5  658.04  4889.5  658.03  4909.6  657.01  4929.6  656.44  4939.7  656.33
  4957.7  655.98  4958.0  655.48  4961.5  655.48  4961.7  655.98  4986.0  656.08
  4991.0  656.26  4999.9  656.40  5009.9  656.37  5019.9  656.48  5030.0  656.47
  5050.0  656.70  5090.1  656.52  5109.4  656.66  5114.4  656.61  5120.2  657.47
  5130.3  657.41  5140.3  657.22  5150.3  657.43  5160.4  657.46  5167.3  657.61
#Mann=3,-1,0
  4838.0    0.05       0  4957.7    0.04       0  4961.7    0.05       0
Bank Sta=4957.7,4961.7
Exp/Cntr=0.3,0.1

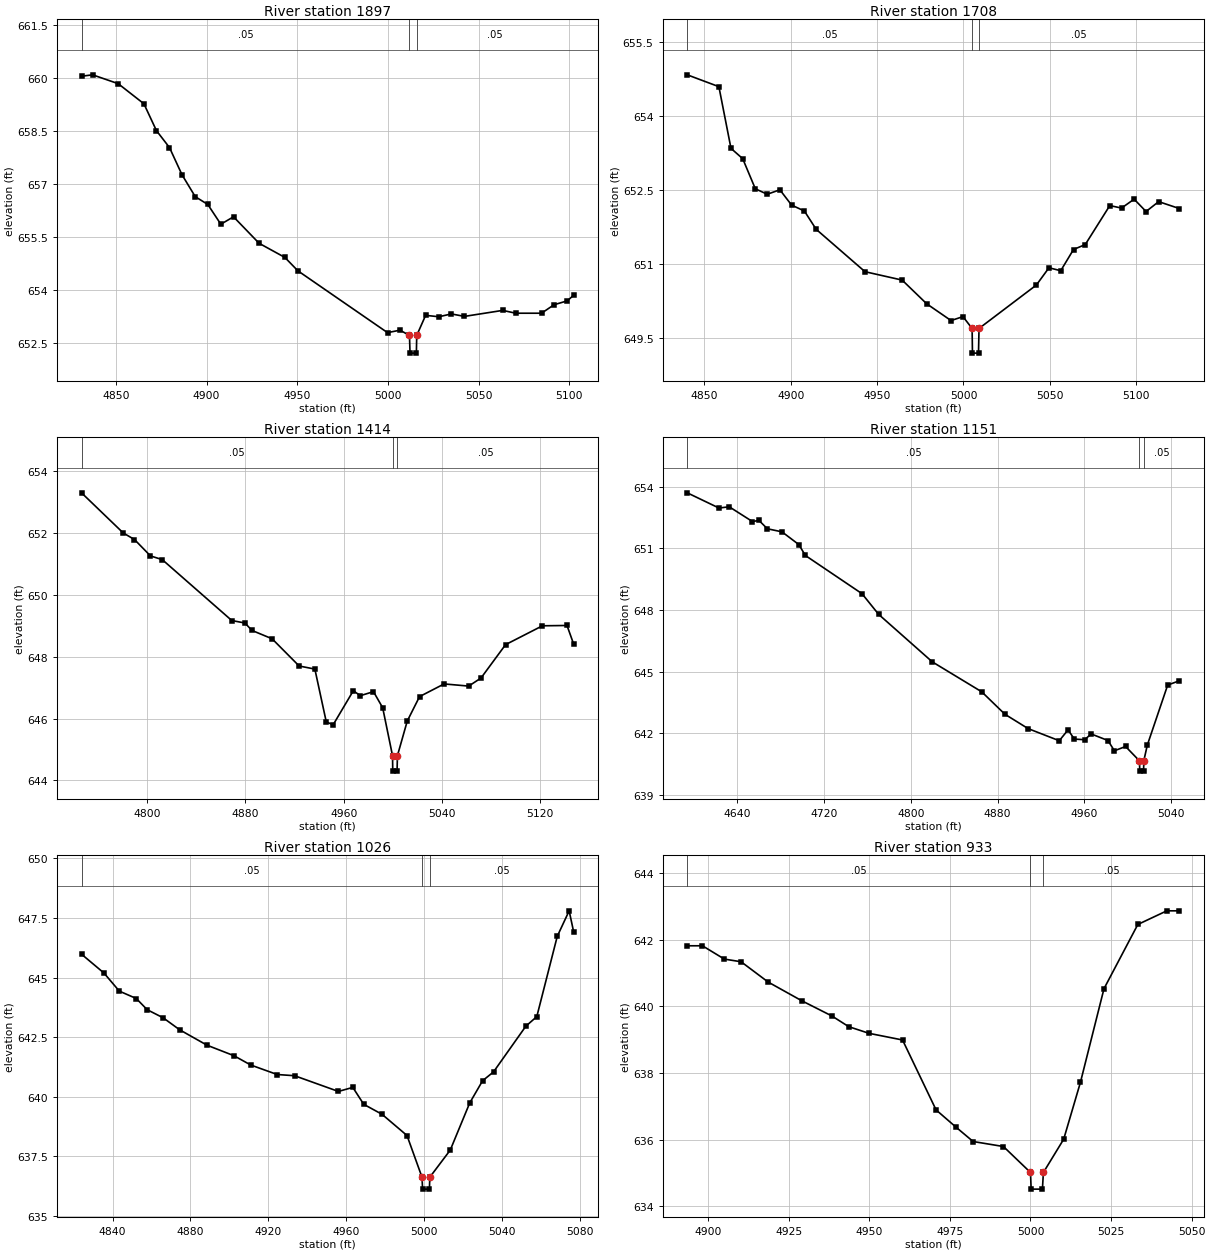
Type RM Length L Ch R = 1,1897,189,189,189
BEGIN DESCRIPTION:
Mapping XS af6e34df
END DESCRIPTION:
XS GIS Cut Line= 2
      2339880.60      7097346.87      2339693.36      7097150.54
#Sta/Elev= 30
  4831.1  660.05  4837.2  660.09  4851.3  659.84  4865.5  659.27  4872.4  658.51
  4879.6  658.03  4886.5  657.26  4893.8  656.64  4900.7  656.42  4907.9  655.86
  4914.9  656.07  4929.0  655.32  4943.2  654.92  4950.4  654.54  4999.8  652.79
  5006.7  652.86  5011.9  652.71  5012.2  652.21  5015.7  652.21  5015.9  652.71
  5020.8  653.28  5028.1  653.24  5035.0  653.32  5042.2  653.25  5063.3  653.42
  5070.5  653.34  5084.7  653.34  5091.6  653.58  5098.9  653.69  5102.4  653.85
#Mann=3,-1,0
  4831.1    0.05       0  5011.9    0.04       0  5015.9    0.05       0
Bank Sta=5011.9,5015.9
Exp/Cntr=0.3,0.1

Type RM Length L Ch R = 1,1708,294,294,294
BEGIN DESCRIPTION:
Mapping XS e61807bf
END DESCRIPTION:
XS GIS Cut Line= 2
      2339982.35      7097182.35      2339774.58      7096987.42
#Sta/Elev= 30
  4840.1  654.84  4858.4  654.60  4865.4  653.35  4872.2  653.14  4879.5  652.53
  4886.4  652.42  4893.7  652.51  4900.5  652.20  4907.9  652.08  4914.7  651.71
  4943.0  650.85  4964.5  650.68  4978.7  650.20  4992.8  649.86  4999.7  649.94
  5005.0  649.70  5005.2  649.20  5008.7  649.20  5009.0  649.70  5042.2  650.58
  5049.5  650.93  5056.3  650.87  5063.7  651.30  5070.5  651.40  5084.7  652.19
  5091.5  652.14  5098.8  652.32  5105.7  652.07  5113.0  652.27  5125.0  652.13
#Mann=3,-1,0
  4840.1    0.05       0  5005.0    0.04       0  5009.0    0.05       0
Bank Sta=5005,5009
Exp/Cntr=0.3,0.1

Type RM Length L Ch R = 1,1414,263,263,263
BEGIN DESCRIPTION:
Hog Branch Tributary 1_1 4.0
END DESCRIPTION:
XS GIS Cut Line= 3
      2340187.14      7096919.25      2339979.00      7096810.00
      2339813.58      7096811.40
#Sta/Elev= 30
  4746.6  653.30  4780.6  652.00  4789.7  651.79  4802.7  651.26  4812.3  651.14
  4868.9  649.17  4879.6  649.09  4885.3  648.85  4901.7  648.58  4923.7  647.70
  4936.5  647.60  4945.8  645.89  4951.4  645.80  4967.8  646.90  4973.5  646.74
  4984.2  646.87  4991.7  646.35  4999.7  644.80  4999.9  644.30  5003.4  644.30
  5003.7  644.80  5011.7  645.92  5021.7  646.71  5041.7  647.12  5061.7  647.05
  5071.7  647.31  5091.7  648.39  5121.7  649.00  5141.7  649.01  5147.1  648.41
#Mann=3,-1,0
  4746.6    0.05       0  4999.7    0.04       0  5003.7    0.05       0
Bank Sta=4999.7,5003.7
Exp/Cntr=0.3,0.1

Type RM Length L Ch R = 1,1151,125,125,125
BEGIN DESCRIPTION:
Hog Branch Tributary 1_1 3.0
END DESCRIPTION:
XS GIS Cut Line= 3
      2340322.04      7096768.25      2339979.00      7096560.00
      2339928.59      7096546.47
#Sta/Elev= 30
  4594.1  653.70  4623.3  652.96  4632.8  653.02  4654.2  652.30  4660.1  652.36
  4667.9  651.95  4681.4  651.80  4696.9  651.18  4702.9  650.65  4755.1  648.79
  4770.5  647.78  4819.9  645.47  4865.5  644.01  4886.8  642.92  4908.2  642.22
  4936.9  641.63  4945.0  642.16  4950.8  641.71  4960.3  641.68  4966.3  641.96
  4981.8  641.64  4987.7  641.14  4998.0  641.35  5010.8  640.65  5011.1  640.15
  5014.6  640.15  5014.8  640.65  5018.0  641.41  5036.8  644.34  5047.6  644.55
#Mann=3,-1,0
  4594.1    0.05       0  5010.8    0.04       0  5014.8    0.05       0
Bank Sta=5010.8,5014.8
Exp/Cntr=0.3,0.1

Type RM Length L Ch R = 1,1026,93,93,93
BEGIN DESCRIPTION:
Mapping XS 891448aa
END DESCRIPTION:
XS GIS Cut Line= 2
      2340186.29      7096529.23      2339961.55      7096414.13
#Sta/Elev= 30
  4824.1  645.98  4835.6  645.19  4843.5  644.43  4852.2  644.12  4857.8  643.65
  4866.0  643.31  4874.4  642.81  4888.5  642.16  4902.3  641.72  4910.9  641.33
  4924.5  640.93  4933.4  640.88  4955.9  640.22  4963.3  640.39  4968.9  639.68
  4978.3  639.26  4991.1  638.37  4998.8  636.62  4999.1  636.12  5002.6  636.12
  5002.8  636.62  5013.3  637.76  5023.3  639.74  5029.9  640.67  5035.5  641.04
  5052.1  642.96  5057.7  643.36  5068.2  646.73  5074.3  647.80  5076.6  646.92
#Mann=3,-1,0
  4824.1    0.05       0  4998.8   0.033       0  5002.8    0.05       0
Bank Sta=4998.8,5002.8
Exp/Cntr=0.3,0.1

Type RM Length L Ch R = 1,933,84,84,84
BEGIN DESCRIPTION:
Mapping XS b7b4326f
END DESCRIPTION:
XS GIS Cut Line= 2
      2340153.09      7096388.81      2340006.58      7096345.77
#Sta/Elev= 24
  4893.5  641.82  4898.2  641.82  4905.0  641.42  4910.2  641.34  4918.6  640.73
  4929.0  640.17  4938.4  639.71  4943.6  639.39  4949.9  639.19  4960.3  638.99
  4970.7  636.89  4976.9  636.37  4982.2  635.94  4991.6  635.79  5000.0  635.01
  5000.2  634.51  5003.7  634.51  5004.0  635.01  5010.3  636.01  5015.5  637.72
  5022.8  640.53  5033.3  642.46  5042.3  642.87  5046.2  642.87
#Mann=3,-1,0
  4893.5    0.05       0  5000.0   0.033       0  5004.0    0.05       0
Bank Sta=5000,5004
Exp/Cntr=0.3,0.1

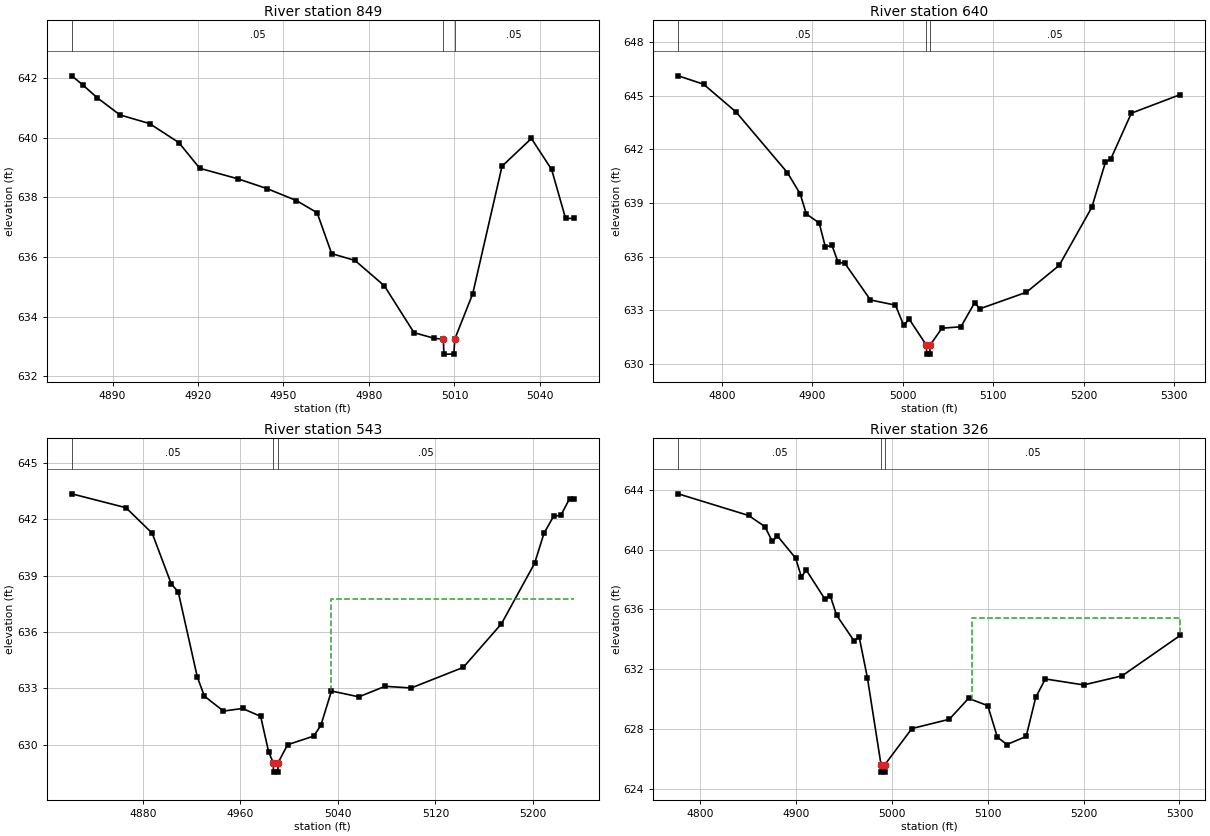
Type RM Length L Ch R = 1,849,209,209,209
BEGIN DESCRIPTION:
Mapping XS 49056435
END DESCRIPTION:
XS GIS Cut Line= 2
      2340185.43      7096306.49      2340014.54      7096263.56
#Sta/Elev= 26
  4875.7  642.07  4879.5  641.77  4884.7  641.33  4892.6  640.76  4903.0  640.47
  4913.3  639.83  4920.6  638.97  4933.9  638.62  4944.2  638.29  4954.5  637.89
  4961.8  637.48  4966.9  636.11  4975.1  635.88  4985.4  635.03  4995.8  633.46
  5002.9  633.27  5006.1  633.24  5006.3  632.74  5009.8  632.74  5010.1  633.24
  5016.4  634.76  5026.7  639.04  5037.0  639.97  5044.1  638.93  5049.0  637.29
  5051.9  637.29
#Mann=3,-1,0
  4875.7    0.05       0  5006.1   0.033       0  5010.1    0.05       0
Bank Sta=5006.1,5010.1
Exp/Cntr=0.3,0.1

Type RM Length L Ch R = 1,640,97,97,97
BEGIN DESCRIPTION:
Hog Branch Tributary 1_1 2.0
END DESCRIPTION:
XS GIS Cut Line= 3
      2340278.97      7096259.96      2340119.75      7096085.23
      2339853.84      7095910.27
#Sta/Elev= 30
  4751.9  646.11  4779.9  645.64  4815.7  644.09  4872.4  640.70  4886.6  639.51
  4893.4  638.38  4907.6  637.88  4914.4  636.55  4921.8  636.62  4928.5  635.68
  4936.0  635.62  4964.3  633.57  4991.9  633.28  5001.0  632.15  5007.0  632.50
  5026.1  631.04  5026.3  630.54  5029.8  630.54  5030.1  631.04  5043.2  631.99
  5064.2  632.07  5079.3  633.41  5085.3  633.08  5136.5  634.00  5172.7  635.50
  5208.8  638.75  5223.9  641.28  5229.9  641.47  5252.5  644.02  5306.6  645.06
#Mann=3,-1,0
  4751.9    0.05       0  5026.1   0.033       0  5030.1    0.05       0
Bank Sta=5026.1,5030.1
Exp/Cntr=0.3,0.1

Type RM Length L Ch R = 1,543,217,217,217
BEGIN DESCRIPTION:
Mapping XS cbac1d57
END DESCRIPTION:
XS GIS Cut Line= 2
      2340282.33      7096077.70      2339927.88      7095867.68
#Sta/Elev= 30
  4821.6  643.36  4866.1  642.62  4887.6  641.26  4903.2  638.57  4909.0  638.13
  4924.6  633.61  4930.4  632.59  4946.1  631.79  4961.7  631.93  4976.6  631.51
  4983.1  629.63  4986.9  629.04  4987.2  628.54  4990.7  628.54  4990.9  629.04
  4998.7  630.00  5020.2  630.46  5026.0  631.03  5034.7  632.86  5057.2  632.55
  5078.7  633.11  5100.1  633.02  5142.9  634.12  5174.2  636.44  5201.4  639.66
  5209.1  641.26  5217.1  642.18  5222.9  642.21  5230.1  643.10  5233.6  643.10
#Mann=3,-1,0
  4821.6    0.05       0  4986.9   0.033       0  4990.9    0.05       0
#XS Ineff=2,0
       0                 5034.60    0.00  637.78
Permanent Ineff=
       F       F
Bank Sta=4986.9,4990.9
Exp/Cntr=0.3,0.1

Type RM Length L Ch R = 1,326,0,0,0
BEGIN DESCRIPTION:
Hog Branch Tributary 1_1 1.0
END DESCRIPTION:
XS GIS Cut Line= 3
      2340369.56      7096084.46      2340280.89      7095849.93
      2340008.36      7095841.35
#Sta/Elev= 30
  4777.5  643.74  4850.8  642.29  4867.8  641.55  4875.6  640.55  4880.9  640.92
  4899.9  639.43  4905.8  638.19  4911.1  638.62  4930.6  636.67  4935.9  636.92
  4942.6  635.61  4960.8  633.89  4966.1  634.16  4974.7  631.42  4988.9  625.60
  4989.2  625.10  4992.7  625.10  4992.9  625.60  5021.1  628.02  5060.1  628.64
  5080.1  630.04  5100.2  629.55  5110.2  627.44  5120.2  626.95  5140.2  627.49
  5150.2  630.11  5160.2  631.34  5200.2  630.94  5240.2  631.55  5300.9  634.26
#Mann=3,-1,0
  4777.5    0.05       0  4988.9   0.033       0  4992.9    0.05       0
#XS Ineff=2,0
       0                 5083.90    0.00  635.40
Permanent Ineff=
       F       F
Bank Sta=4988.9,4992.9
Exp/Cntr=0.3,0.1

Chan Stop Cuts=-1