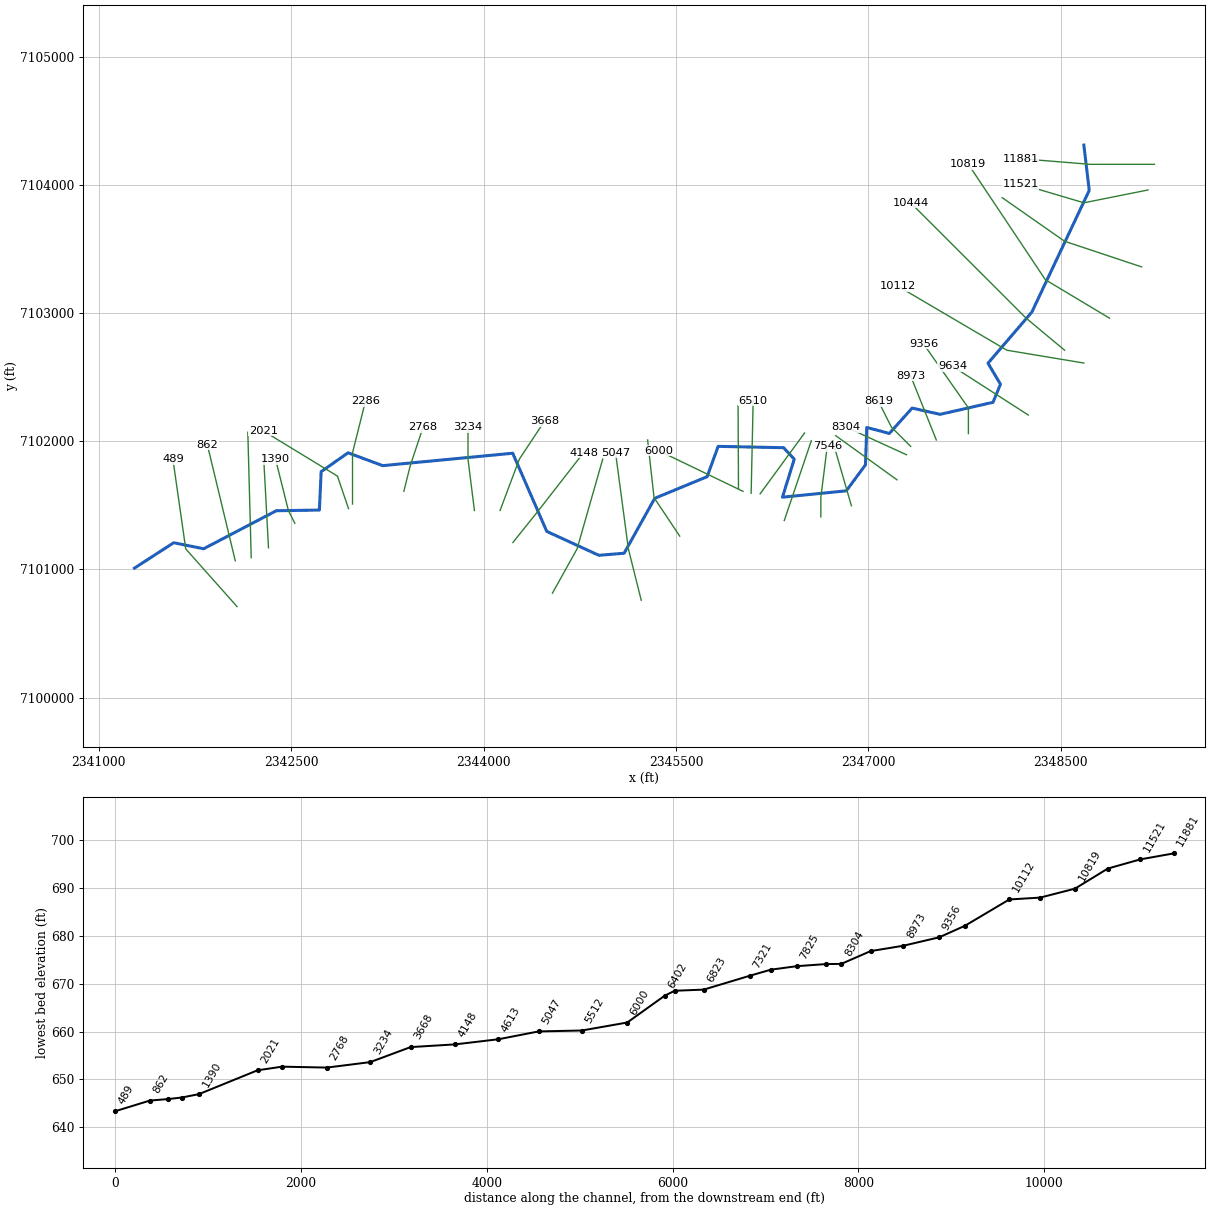
--- Hog Branch Tributary 3.prj (project) ---

Proj Title=Hog Branch Tributary 3 Base Level Engineering
Current Plan=p01
Default Exp/Contr=0.3,0.1
English Units
Geom File=g01
Flow File=f01
Plan File=p01
BEGIN DESCRIPTION:
Hog Branch Tributary 3
END DESCRIPTION:

--- Hog Branch Tributary 3.p01 (plan) ---

Plan Title=Multiple Run
Short Identifier=Multiple
Geom File=g01
Flow File=f01
Subcritical Flow
K Sum by GR= 0
Std Step Tol= 0.01
Critical Tol= 0.01
Num of Std Step Trials= 20
Max Error Tol= 0.3
Flow Tol Ratio= 0.001
Split Flow NTrial= 30
Split Flow Tol= 0.02
Split Flow Ratio= 0.02
Log Output Level= 0
Friction Slope Method= 1
Unsteady Friction Slope Method= 2
Unsteady Bridges Friction Slope Method= 1
Parabolic Critical Depth
Global Vel Dist=  1 , 1 , 1
Global Log Level= 0
CheckData=True
Encroach Param= -1, 0, 0, 0
BEGIN DESCRIPTION:
Multiple Run
END DESCRIPTION:

--- Hog Branch Tributary 3.f01 (steady flow) ---

Flow Title=Multiple
Number of Profiles=7
Profile Names=10-year,25-year,50-year,1pct_min,100-year,1pct_plu,500-year
River Rch & RM= Hog Branch Tribu,Reach-1,11881
     539     734     893     540    1077    2148    1569
River Rch & RM= Hog Branch Tribu,Reach-1,6000
    1170    1656    2070    1281    2556    5100    3910
River Rch & RM= Hog Branch Tribu,Reach-1,4148
    1211    1716    2145    1328    2649    5286    4054
River Rch & RM= Hog Branch Tribu,Reach-1,2021
    1637    2354    2971    1855    3701    7384    5765
Boundary for River Rch & Prof#=Hog Branch Tribu,Reach-1,1
Up Type=0
Dn Type=3
Dn Slope=0.005
Boundary for River Rch & Prof#=Hog Branch Tribu,Reach-1,2
Up Type=0
Dn Type=3
Dn Slope=0.005
Boundary for River Rch & Prof#=Hog Branch Tribu,Reach-1,3
Up Type=0
Dn Type=3
Dn Slope=0.005
Boundary for River Rch & Prof#=Hog Branch Tribu,Reach-1,4
Up Type=0
Dn Type=3
Dn Slope=0.005
Boundary for River Rch & Prof#=Hog Branch Tribu,Reach-1,5
Up Type=0
Dn Type=3
Dn Slope=0.005
Boundary for River Rch & Prof#=Hog Branch Tribu,Reach-1,6
Up Type=0
Dn Type=3
Dn Slope=0.005
Boundary for River Rch & Prof#=Hog Branch Tribu,Reach-1,7
Up Type=0
Dn Type=3
Dn Slope=0.005

--- Hog Branch Tributary 3.g01 (geometry) ---

Geom Title=Existing Conditions

River Reach=Hog Branch Tribu,Reach-1
Reach XY= 30
      2348679.00      7104310.00      2348720.92      7103956.72
      2348273.63      7103007.30      2347932.01      7102608.57
      2348029.05      7102444.66      2347971.00      7102303.61
      2347558.82      7102209.72      2347340.54      7102258.51
      2347162.99      7102060.81      2346987.09      7102107.53
      2346976.94      7101815.86      2346827.58      7101613.04
      2346329.97      7101563.54      2346421.69      7101860.11
      2346338.85      7101949.52      2345829.00      7101960.00
      2345742.63      7101723.46      2345334.47      7101554.74
      2345095.80      7101126.42      2344899.03      7101110.07
      2344492.61      7101296.76      2344227.55      7101906.47
      2343213.82      7101809.56      2342944.25      7101909.70
      2342734.39      7101762.47      2342720.73      7101463.06
      2342384.93      7101457.76      2341818.49      7101161.20
      2341585.11      7101208.20      2341279.00      7101010.00

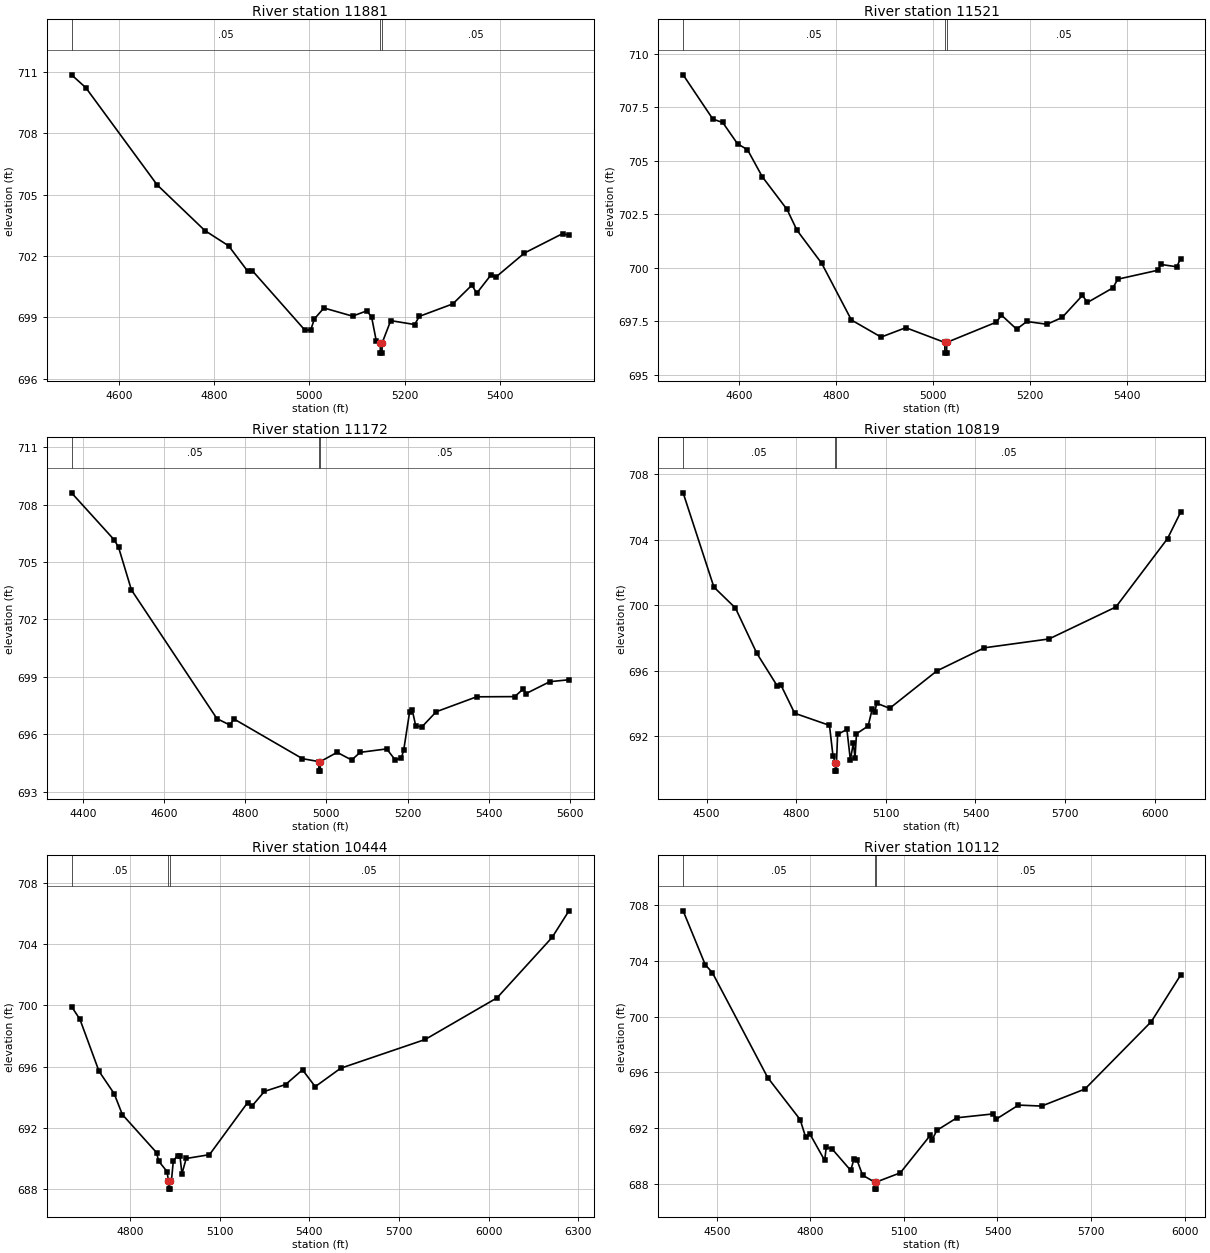
Type RM Length L Ch R = 1,11881,360,360,360
BEGIN DESCRIPTION:
Hog Branch Tributary 3 26.0
END DESCRIPTION:
XS GIS Cut Line= 3
      2349228.98      7104160.00      2348729.00      7104160.00
      2348185.88      7104204.21
#Sta/Elev= 30
  4500.5  710.87  4530.5  710.24  4680.5  705.48  4780.5  703.25  4830.5  702.50
  4870.5  701.26  4880.5  701.28  4990.5  698.38  5003.0  698.38  5010.5  698.92
  5030.6  699.46  5090.8  699.06  5120.9  699.32  5130.9  699.01  5140.9  697.82
  5149.0  697.75  5149.2  697.25  5152.7  697.25  5153.0  697.75  5171.0  698.84
  5221.2  698.65  5231.2  699.05  5301.5  699.66  5341.6  700.58  5351.6  700.18
  5381.7  701.08  5391.8  700.97  5452.0  702.15  5532.2  703.10  5545.4  703.01
#Mann=3,-1,0
  4500.5    0.05       0  5149.0   0.033       0  5153.0    0.05       0
Bank Sta=5149,5153
Exp/Cntr=0.3,0.1

Type RM Length L Ch R = 1,11521,349,349,349
BEGIN DESCRIPTION:
Hog Branch Tributary 3 25.0
END DESCRIPTION:
XS GIS Cut Line= 3
      2349179.03      7103960.01      2348679.00      7103860.00
      2348185.20      7104006.82
#Sta/Elev= 30
  4485.5  709.02  4546.7  706.95  4567.1  706.79  4597.7  705.79  4618.1  705.52
  4648.7  704.25  4699.7  702.72  4720.1  701.75  4771.1  700.20  4832.3  697.55
  4893.5  696.75  4944.4  697.19  5024.7  696.50  5025.0  696.00  5028.5  696.00
  5028.7  696.50  5131.1  697.45  5141.5  697.78  5172.8  697.12  5193.7  697.48
  5235.4  697.35  5266.7  697.67  5308.4  698.70  5318.8  698.37  5371.0  699.05
  5381.4  699.46  5464.4  699.88  5469.6  700.15  5502.8  700.04  5510.6  700.42
#Mann=3,-1,0
  4485.5    0.05       0  5024.7   0.033       0  5028.7    0.05       0
Bank Sta=5024.7,5028.7
Exp/Cntr=0.3,0.1

Type RM Length L Ch R = 1,11172,353,353,353
BEGIN DESCRIPTION:
Hog Branch Tributary 3 24.0
END DESCRIPTION:
XS GIS Cut Line= 3
      2349129.02      7103359.99      2348529.00      7103560.00
      2348042.45      7103900.09
#Sta/Elev= 30
  4371.7  708.61  4477.1  706.15  4487.7  705.76  4519.3  703.54  4730.1  696.82
  4761.7  696.49  4772.3  696.80  4940.9  694.73  4981.1  694.58  4981.3  694.08
  4984.8  694.08  4985.1  694.58  5026.4  695.06  5062.2  694.66  5083.1  695.06
  5148.5  695.24  5169.4  694.67  5184.3  694.75  5190.4  695.17  5205.2  697.19
  5211.6  697.27  5220.0  696.45  5234.9  696.38  5270.6  697.18  5370.2  697.96
  5464.2  697.97  5485.1  698.37  5492.2  698.13  5550.6  698.75  5597.8  698.85
#Mann=3,-1,0
  4371.7    0.05       0  4981.1   0.033       0  4985.1    0.05       0
Bank Sta=4981.1,4985.1
Exp/Cntr=0.3,0.1

Type RM Length L Ch R = 1,10819,375,375,375
BEGIN DESCRIPTION:
Hog Branch Tributary 3 23.0
END DESCRIPTION:
XS GIS Cut Line= 3
      2348878.98      7102960.01      2348379.00      7103260.00
      2347779.02      7104159.97
#Sta/Elev= 30
  4421.6  706.85  4524.6  701.10  4596.5  699.83  4668.4  697.06  4736.4  695.08
  4748.1  695.16  4794.8  693.41  4911.4  692.67  4923.0  690.83  4930.8  690.38
  4931.0  689.88  4934.5  689.88  4934.8  690.38  4938.6  692.12  4969.7  692.42
  4981.3  690.56  4991.1  691.58  4996.9  690.71  5001.8  692.16  5040.7  692.63
  5054.2  693.65  5063.3  693.48  5069.3  694.02  5112.8  693.71  5270.6  695.99
  5429.8  697.40  5646.2  697.94  5870.0  699.89  6042.8  704.06  6086.3  705.66
#Mann=3,-1,0
  4421.6    0.05       0  4930.8   0.033       0  4934.8    0.05       0
Bank Sta=4930.8,4934.8
Exp/Cntr=0.3,0.1

Type RM Length L Ch R = 1,10444,332,332,332
BEGIN DESCRIPTION:
Hog Branch Tributary 3 22.0
END DESCRIPTION:
XS GIS Cut Line= 3
      2348529.02      7102709.98      2348229.00      7102960.00
      2347329.02      7103859.98
#Sta/Elev= 30
  4604.8  699.93  4632.8  699.10  4696.6  695.71  4747.4  694.24  4774.7  692.88
  4889.3  690.39  4895.8  689.85  4924.4  689.15  4928.9  688.51  4929.2  688.01
  4932.7  688.01  4932.9  688.51  4938.7  688.53  4945.2  689.86  4959.5  690.20
  4967.4  690.17  4973.9  689.01  4988.2  690.01  5066.1  690.26  5193.3  693.65
  5207.5  693.42  5249.9  694.39  5320.6  694.84  5377.2  695.80  5419.6  694.70
  5504.5  695.90  5787.3  697.78  6027.7  700.50  6211.6  704.44  6268.1  706.18
#Mann=3,-1,0
  4604.8    0.05       0  4928.9   0.033       0  4932.9    0.05       0
Bank Sta=4928.9,4932.9
Exp/Cntr=0.3,0.1

Type RM Length L Ch R = 1,10112,478,478,478
BEGIN DESCRIPTION:
Hog Branch Tributary 3 21.0
END DESCRIPTION:
XS GIS Cut Line= 3
      2348679.03      7102609.99      2348079.00      7102710.00
      2347228.97      7103210.02
#Sta/Elev= 30
  4392.3  707.59  4463.3  703.72  4486.1  703.15  4663.5  695.62  4767.4  692.61
  4785.2  691.34  4797.9  691.61  4846.0  689.68  4851.1  690.62  4868.8  690.53
  4929.6  688.96  4939.8  689.77  4949.9  689.69  4967.7  688.62  5006.4  688.12
  5006.7  687.62  5010.2  687.62  5010.4  688.12  5088.5  688.79  5184.2  691.47
  5190.0  691.15  5205.7  691.84  5270.1  692.74  5387.2  693.02  5395.1  692.63
  5467.3  693.65  5541.5  693.58  5680.2  694.80  5893.1  699.64  5986.8  702.97
#Mann=3,-1,0
  4392.3    0.05       0  5006.4   0.033       0  5010.4    0.05       0
Bank Sta=5006.4,5010.4
Exp/Cntr=0.3,0.1

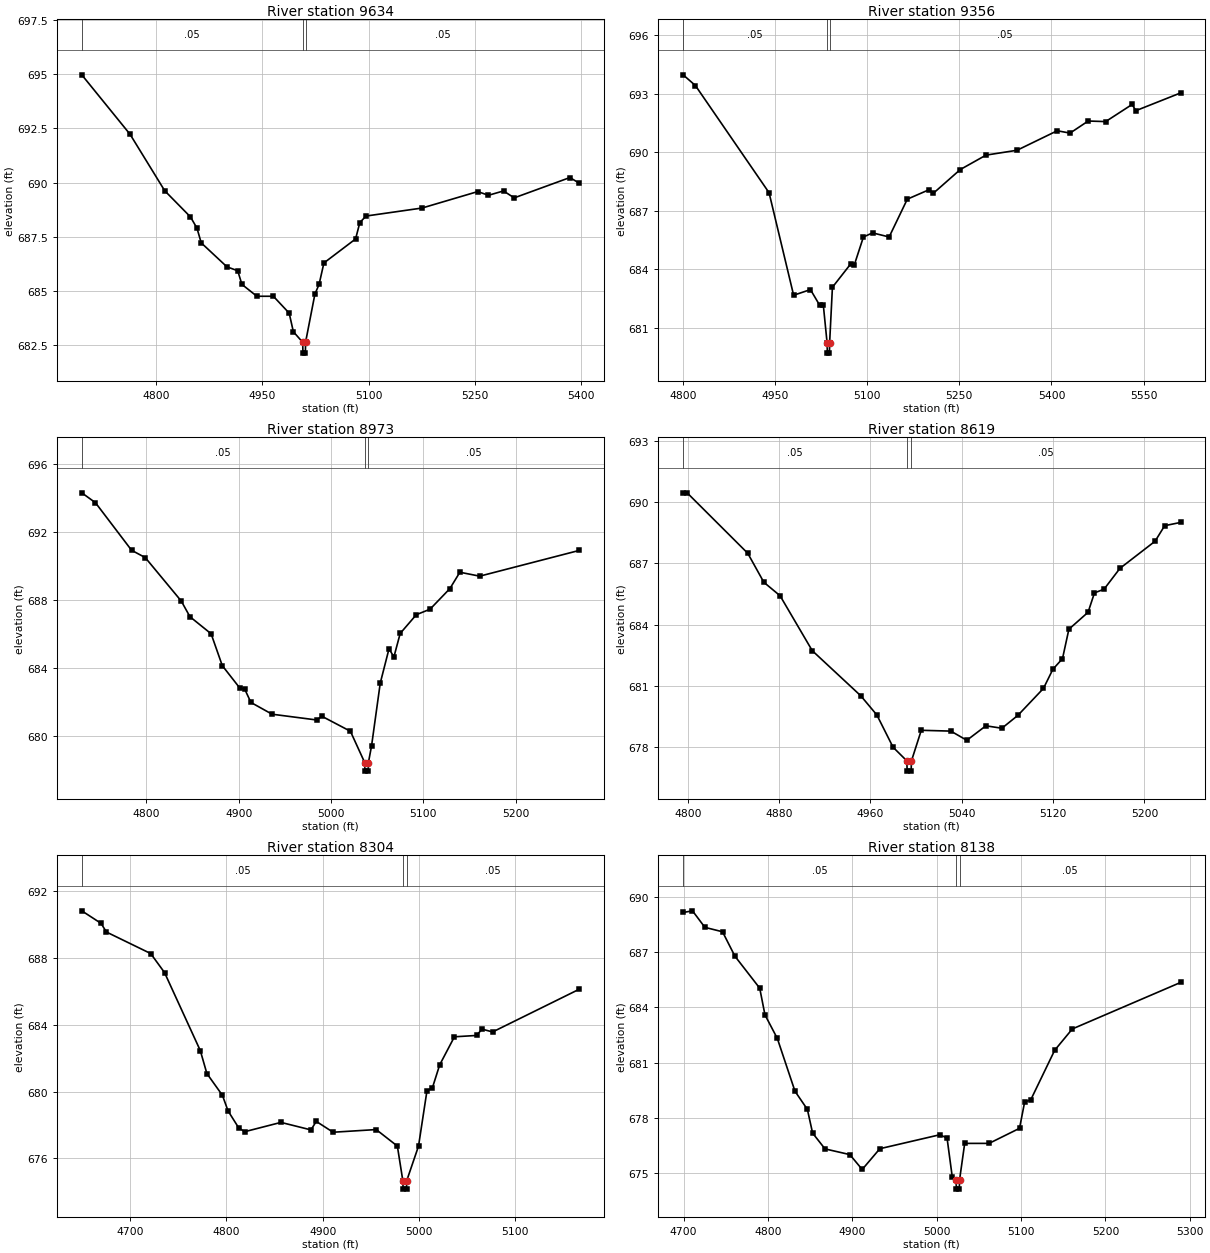
Type RM Length L Ch R = 1,9634,278,278,278
BEGIN DESCRIPTION:
Mapping XS 197ca42a
END DESCRIPTION:
XS GIS Cut Line= 2
      2348246.23      7102204.15      2347656.22      7102584.17
#Sta/Elev= 30
  4695.2  694.98  4763.3  692.23  4812.2  689.62  4848.5  688.41  4857.7  687.89
  4863.7  687.21  4900.0  686.10  4915.2  685.92  4921.1  685.29  4942.2  684.74
  4965.5  684.74  4987.8  683.96  4993.7  683.10  5006.9  682.61  5007.2  682.11
  5010.7  682.11  5010.9  682.61  5024.1  684.84  5030.0  685.29  5036.8  686.28
  5081.5  687.39  5087.5  688.15  5096.3  688.45  5175.3  688.82  5253.8  689.58
  5269.0  689.41  5290.2  689.61  5305.3  689.29  5383.9  690.23  5397.0  689.97
#Mann=3,-1,0
  4695.2    0.05       0  5006.9   0.033       0  5010.9    0.05       0
Bank Sta=5006.9,5010.9
Exp/Cntr=0.3,0.1

Type RM Length L Ch R = 1,9356,383,383,383
BEGIN DESCRIPTION:
Hog Branch Tributary 3 19.0
END DESCRIPTION:
XS GIS Cut Line= 3
      2347779.00      7102059.99      2347779.00      7102260.00
      2347429.02      7102759.97
#Sta/Elev= 30
  4800.0  693.98  4820.0  693.43  4940.0  687.93  4980.0  682.67  5007.4  682.96
  5022.2  682.17  5028.3  682.19  5034.6  680.20  5034.9  679.70  5038.4  679.70
  5038.6  680.20  5043.2  683.08  5072.8  684.27  5078.9  684.23  5093.7  685.66
  5108.6  685.87  5135.6  685.66  5165.2  687.60  5201.0  688.09  5207.5  687.90
  5251.5  689.12  5293.4  689.86  5344.0  690.11  5409.4  691.11  5430.3  690.99
  5459.9  691.61  5488.3  691.58  5531.4  692.46  5537.5  692.14  5610.3  693.05
#Mann=3,-1,0
  4800.0    0.05       0  5034.6   0.033       0  5038.6    0.05       0
Bank Sta=5034.6,5038.6
Exp/Cntr=0.3,0.1

Type RM Length L Ch R = 1,8973,354,354,354
BEGIN DESCRIPTION:
Hog Branch Tributary 3 18.0
END DESCRIPTION:
XS GIS Cut Line= 3
      2347529.01      7102009.98      2347429.00      7102260.00
      2347329.01      7102509.97
#Sta/Elev= 30
  4730.2  694.28  4745.0  693.70  4784.1  690.91  4798.9  690.48  4837.9  687.93
  4847.3  687.01  4870.2  686.01  4882.3  684.14  4901.2  682.83  4906.6  682.76
  4913.3  681.98  4936.2  681.29  4984.7  680.95  4990.1  681.17  5021.0  680.29
  5036.5  678.45  5036.8  677.95  5040.3  677.95  5040.5  678.45  5043.9  679.43
  5053.3  683.11  5062.8  685.13  5068.1  684.65  5074.9  686.03  5092.4  687.13
  5107.2  687.45  5128.7  688.66  5139.5  689.62  5161.0  689.39  5268.7  690.90
#Mann=3,-1,0
  4730.2    0.05       0  5036.5   0.033       0  5040.5    0.05       0
Bank Sta=5036.5,5040.5
Exp/Cntr=0.3,0.1

Type RM Length L Ch R = 1,8619,315,315,315
BEGIN DESCRIPTION:
Hog Branch Tributary 3 17.0
END DESCRIPTION:
XS GIS Cut Line= 3
      2347329.01      7101959.99      2347179.00      7102110.00
      2347079.02      7102309.96
#Sta/Elev= 30
  4795.9  690.45  4799.4  690.45  4852.5  687.49  4866.6  686.07  4880.8  685.41
  4909.0  682.72  4951.5  680.51  4965.6  679.57  4979.8  677.99  4991.9  677.32
  4992.1  676.82  4995.6  676.82  4995.9  677.32  5004.5  678.82  5030.4  678.78
  5044.4  678.33  5061.1  679.04  5075.1  678.92  5089.1  679.55  5111.5  680.87
  5119.8  681.81  5128.2  682.33  5133.8  683.77  5150.6  684.60  5156.2  685.55
  5164.6  685.73  5178.5  686.75  5209.3  688.08  5217.7  688.84  5231.6  689.00
#Mann=3,-1,0
  4795.9    0.05       0  4991.9   0.033       0  4995.9    0.05       0
Bank Sta=4991.9,4995.9
Exp/Cntr=0.3,0.1

Type RM Length L Ch R = 1,8304,166,166,166
BEGIN DESCRIPTION:
Mapping XS 882bd741
END DESCRIPTION:
XS GIS Cut Line= 2
      2347297.21      7101894.29      2346827.14      7102109.51
#Sta/Elev= 30
  4649.6  690.83  4669.6  690.08  4675.2  689.56  4721.2  688.27  4735.6  687.13
  4772.8  682.45  4779.6  681.08  4795.8  679.77  4801.6  678.84  4812.6  677.83
  4818.8  677.59  4856.6  678.15  4887.8  677.70  4893.3  678.21  4910.8  677.56
  4955.6  677.72  4977.6  676.73  4983.3  674.65  4983.6  674.15  4987.1  674.15
  4987.3  674.65  4999.6  676.73  5008.4  680.06  5013.9  680.20  5021.6  681.60
  5036.9  683.28  5059.9  683.36  5065.6  683.74  5076.6  683.57  5166.6  686.13
#Mann=3,-1,0
  4649.6    0.05       0  4983.3   0.033       0  4987.3    0.05       0
Bank Sta=4983.3,4987.3
Exp/Cntr=0.3,0.1

Type RM Length L Ch R = 1,8138,313,313,313
BEGIN DESCRIPTION:
Mapping XS 38af5426
END DESCRIPTION:
XS GIS Cut Line= 2
      2347223.11      7101698.58      2346744.88      7102043.61
#Sta/Elev= 30
  4699.4  689.17  4710.5  689.26  4725.2  688.36  4746.1  688.12  4760.8  686.79
  4790.2  685.05  4796.4  683.60  4811.1  682.31  4832.0  679.44  4846.7  678.45
  4852.9  677.16  4867.6  676.30  4897.0  675.99  4911.7  675.18  4932.6  676.31
  5003.7  677.07  5012.3  676.89  5018.5  674.76  5023.1  674.61  5023.3  674.11
  5026.8  674.11  5027.1  674.61  5033.2  676.60  5062.1  676.60  5098.2  677.42
  5104.3  678.86  5111.4  678.96  5139.9  681.67  5160.8  682.83  5289.1  685.36
#Mann=3,-1,0
  4699.4    0.05       0  5023.1   0.033       0  5027.1    0.05       0
Bank Sta=5023.1,5027.1
Exp/Cntr=0.3,0.1

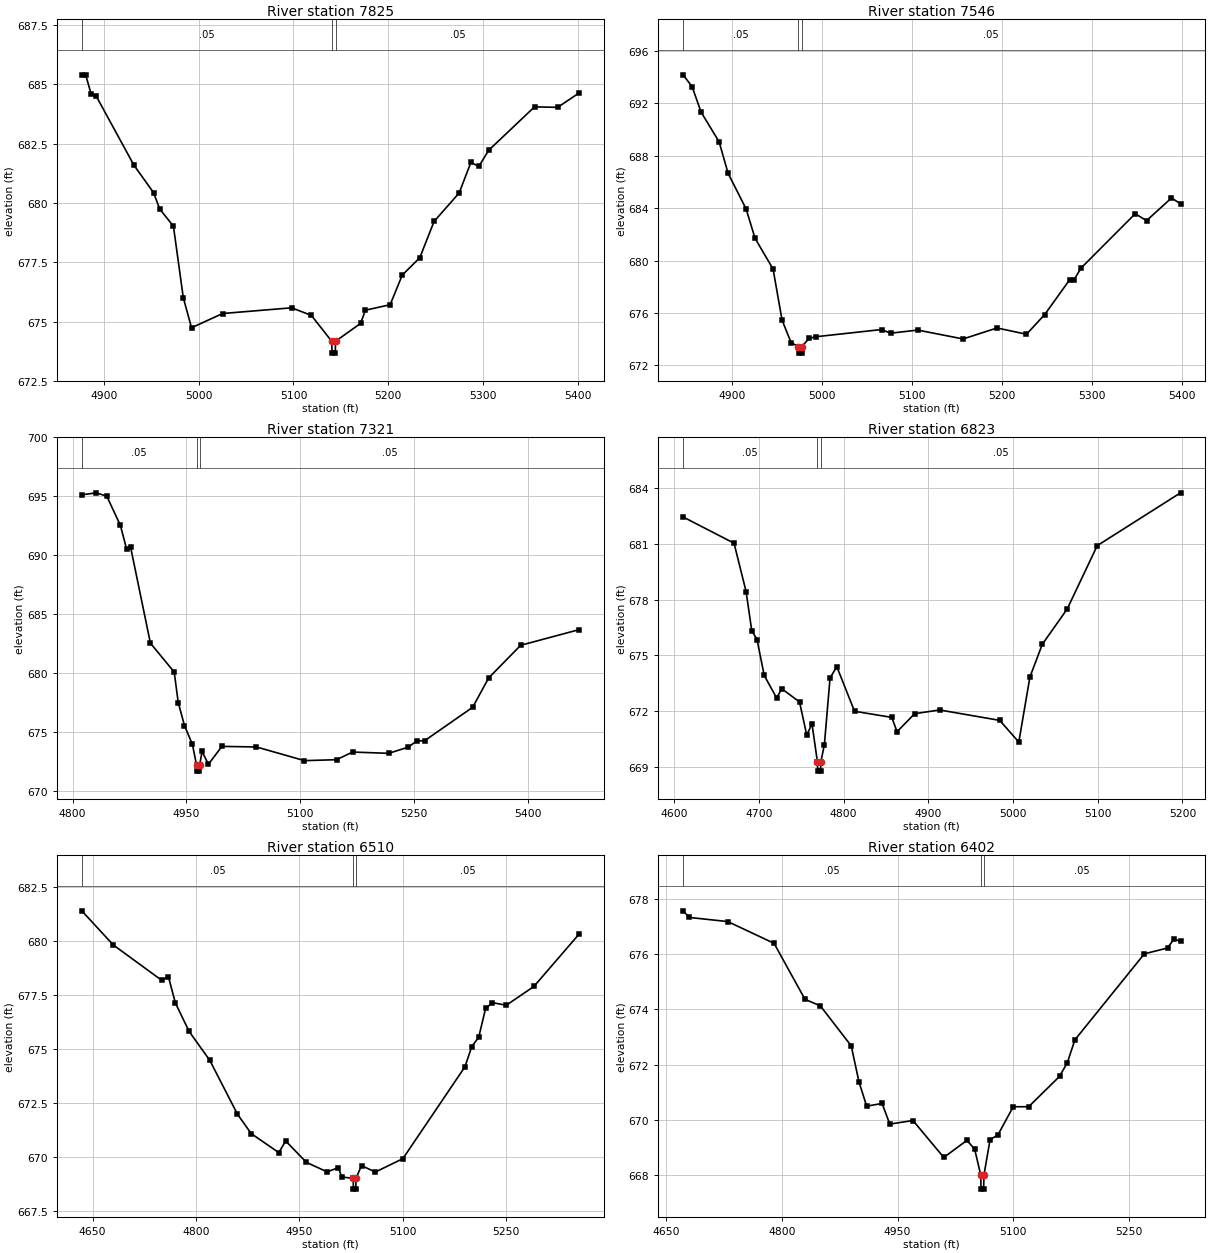
Type RM Length L Ch R = 1,7825,279,279,279
BEGIN DESCRIPTION:
Mapping XS f35289b8
END DESCRIPTION:
XS GIS Cut Line= 2
      2346867.12      7101497.05      2346721.34      7102001.82
#Sta/Elev= 30
  4876.4  685.40  4880.5  685.40  4886.2  684.60  4891.4  684.52  4931.5  681.59
  4952.3  680.43  4958.6  679.75  4973.2  679.02  4983.6  676.01  4992.3  674.74
  5025.2  675.34  5098.1  675.58  5118.9  675.26  5140.4  674.17  5140.7  673.67
  5144.2  673.67  5144.4  674.17  5170.8  674.92  5176.0  675.48  5202.1  675.71
  5214.9  676.96  5233.4  677.69  5248.5  679.22  5275.0  680.42  5287.4  681.71
  5295.8  681.54  5306.2  682.22  5354.6  684.05  5379.1  684.03  5401.8  684.64
#Mann=3,-1,0
  4876.4    0.05       0  5140.4   0.033       0  5144.4    0.05       0
Bank Sta=5140.4,5144.4
Exp/Cntr=0.3,0.1

Type RM Length L Ch R = 1,7546,225,225,225
BEGIN DESCRIPTION:
Hog Branch Tributary 3 14.0
END DESCRIPTION:
XS GIS Cut Line= 3
      2346629.00      7101409.99      2346629.00      7101560.00
      2346679.00      7101959.98
#Sta/Elev= 30
  4845.6  694.18  4855.6  693.27  4865.6  691.33  4885.6  689.07  4895.6  686.66
  4915.6  683.95  4925.6  681.70  4945.6  679.36  4955.6  675.46  4965.6  673.75
  4973.6  673.44  4973.9  672.94  4977.4  672.94  4977.6  673.44  4985.6  674.06
  4993.1  674.19  5066.2  674.74  5076.2  674.46  5106.5  674.70  5156.9  674.02
  5194.6  674.86  5227.4  674.38  5247.6  675.88  5275.3  678.53  5280.3  678.54
  5287.9  679.42  5348.3  683.58  5360.9  683.05  5388.6  684.78  5398.7  684.34
#Mann=3,-1,0
  4845.6    0.05       0  4973.6   0.033       0  4977.6    0.05       0
Bank Sta=4973.6,4977.6
Exp/Cntr=0.3,0.1

Type RM Length L Ch R = 1,7321,498,498,498
BEGIN DESCRIPTION:
Mapping XS ad5f2680
END DESCRIPTION:
XS GIS Cut Line= 2
      2346344.10      7101381.79      2346554.61      7102003.10
#Sta/Elev= 30
  4812.1  695.13  4831.3  695.30  4845.1  695.01  4863.0  692.54  4871.2  690.53
  4876.5  690.68  4902.6  682.54  4934.0  680.09  4939.3  677.50  4947.5  675.55
  4958.0  673.95  4963.5  672.18  4963.7  671.68  4967.2  671.68  4967.5  672.18
  4970.7  673.35  4979.1  672.26  4996.9  673.78  5042.5  673.73  5105.8  672.57
  5148.1  672.65  5169.2  673.30  5216.8  673.19  5242.9  673.72  5253.7  674.24
  5264.2  674.26  5327.6  677.10  5348.7  679.59  5390.9  682.36  5468.1  683.69
#Mann=3,-1,0
  4812.1    0.05       0  4963.5   0.033       0  4967.5    0.05       0
Bank Sta=4963.5,4967.5
Exp/Cntr=0.3,0.1

Type RM Length L Ch R = 1,6823,313,313,313
BEGIN DESCRIPTION:
Mapping XS 04c801d3
END DESCRIPTION:
XS GIS Cut Line= 2
      2346155.95      7101589.98      2346502.14      7102064.15
#Sta/Elev= 30
  4610.7  682.44  4670.8  681.03  4685.0  678.43  4691.7  676.33  4697.9  675.85
  4706.4  673.92  4721.0  672.71  4727.2  673.20  4748.1  672.49  4756.6  670.71
  4762.8  671.31  4769.2  669.27  4769.5  668.77  4773.0  668.77  4773.2  669.27
  4777.4  670.18  4784.1  673.78  4792.1  674.39  4813.0  671.99  4857.0  671.66
  4863.2  670.89  4884.0  671.86  4913.4  672.06  4984.4  671.50  5006.9  670.33
  5020.0  673.83  5034.6  675.59  5064.0  677.49  5099.5  680.90  5197.8  683.74
#Mann=3,-1,0
  4610.7    0.05       0  4769.2   0.033       0  4773.2    0.05       0
Bank Sta=4769.2,4773.2
Exp/Cntr=0.3,0.1

Type RM Length L Ch R = 1,6510,108,108,108
BEGIN DESCRIPTION:
Mapping XS dab4f901
END DESCRIPTION:
XS GIS Cut Line= 2
      2346085.96      7101594.30      2346101.49      7102315.73
#Sta/Elev= 30
  4634.2  681.41  4679.9  679.83  4749.9  678.20  4759.9  678.36  4769.9  677.15
  4789.9  675.83  4819.9  674.49  4860.0  672.00  4880.0  671.10  4920.0  670.22
  4930.0  670.76  4960.0  669.77  4990.0  669.33  5006.4  669.52  5011.4  669.09
  5028.0  669.03  5028.2  668.53  5031.7  668.53  5032.0  669.03  5040.0  669.62
  5060.0  669.32  5100.0  669.94  5190.0  674.19  5200.0  675.13  5210.0  675.56
  5220.0  676.89  5230.0  677.16  5250.0  677.04  5290.1  677.91  5355.8  680.34
#Mann=3,-1,0
  4634.2    0.05       0  5028.0   0.033       0  5032.0    0.05       0
Bank Sta=5028,5032
Exp/Cntr=0.3,0.1

Type RM Length L Ch R = 1,6402,402,402,402
BEGIN DESCRIPTION:
Mapping XS 04eedb93
END DESCRIPTION:
XS GIS Cut Line= 2
      2345987.19      7101632.11      2345983.98      7102276.90
#Sta/Elev= 30
  4672.1  677.58  4680.0  677.34  4730.0  677.19  4790.0  676.40  4830.0  674.37
  4850.0  674.13  4890.0  672.68  4900.0  671.38  4910.0  670.49  4930.0  670.59
  4940.0  669.84  4970.0  669.97  5010.0  668.63  5040.0  669.25  5050.0  668.93
  5058.0  667.98  5058.2  667.48  5061.7  667.48  5062.0  667.98  5070.0  669.28
  5080.0  669.44  5100.0  670.47  5120.0  670.47  5160.0  671.57  5170.0  672.06
  5180.0  672.90  5270.0  676.02  5300.0  676.23  5308.5  676.56  5316.9  676.47
#Mann=3,-1,0
  4672.1    0.05       0  5058.0   0.033       0  5062.0    0.05       0
Bank Sta=5058,5062
Exp/Cntr=0.3,0.1

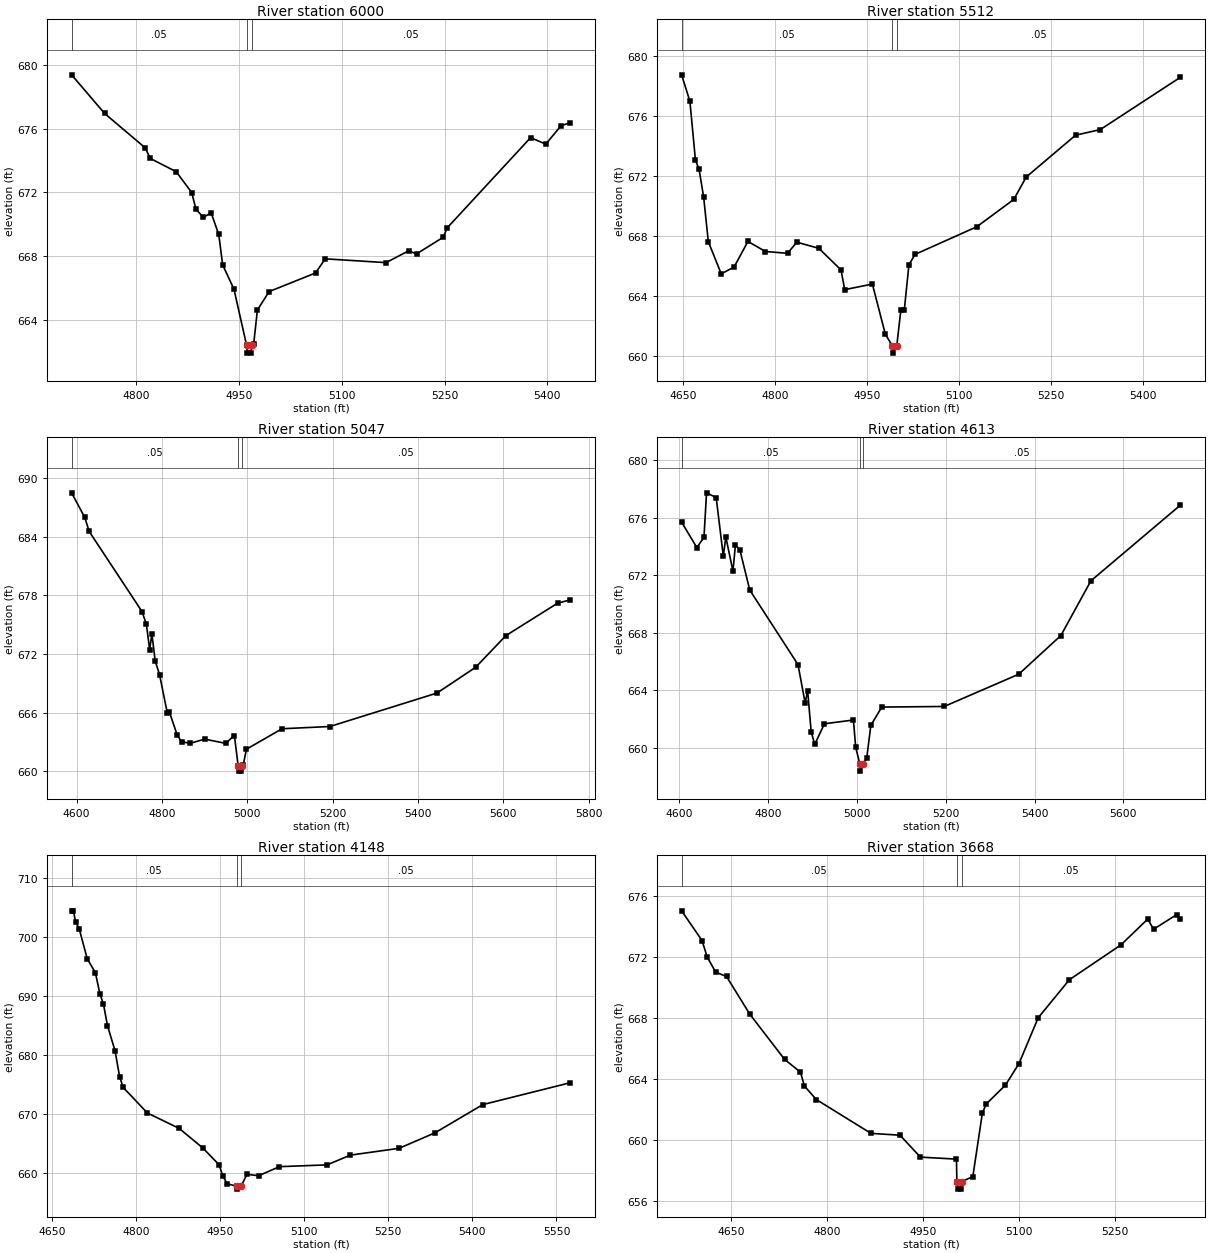
Type RM Length L Ch R = 1,6000,488,488,488
BEGIN DESCRIPTION:
Mapping XS 63ed59de
END DESCRIPTION:
XS GIS Cut Line= 2
      2346022.45      7101609.14      2345366.58      7101925.54
#Sta/Elev= 30
  4705.5  679.39  4753.7  676.96  4812.9  674.80  4820.4  674.13  4858.1  673.30
  4880.8  671.99  4887.0  670.94  4897.8  670.43  4909.2  670.71  4920.3  669.35
  4926.0  667.44  4942.5  665.91  4960.9  662.39  4962.1  661.89  4967.3  661.89
  4968.4  662.39  4971.2  662.44  4976.7  664.60  4993.8  665.76  5061.6  666.93
  5075.7  667.82  5164.5  667.58  5197.3  668.32  5209.0  668.13  5248.1  669.18
  5253.6  669.76  5375.5  675.44  5397.7  675.03  5419.9  676.19  5433.7  676.38
#Mann=3,-1,0
  4705.5    0.05       0  4960.9   0.033       0  4968.4    0.05       0
Bank Sta=4960.9,4968.4
Exp/Cntr=0.3,0.1

Type RM Length L Ch R = 1,5512,465,465,465
BEGIN DESCRIPTION:
Hog Branch Tributary 3 11.0
END DESCRIPTION:
XS GIS Cut Line= 3
      2345528.99      7101260.01      2345329.00      7101560.00
      2345279.00      7102009.99
#Sta/Elev= 30
  4647.5  678.76  4661.0  677.00  4670.0  673.09  4676.0  672.46  4683.5  670.59
  4691.0  667.65  4712.1  665.50  4733.1  665.96  4755.6  667.66  4784.2  666.99
  4820.2  666.87  4835.3  667.61  4871.3  667.20  4907.4  665.76  4913.4  664.45
  4958.5  664.82  4979.5  661.50  4990.7  660.72  4991.9  660.22  4998.3  660.72
  5005.0  663.11  5010.6  663.11  5018.1  666.11  5028.2  666.80  5128.8  668.64
  5189.1  670.46  5209.3  671.95  5289.8  674.74  5330.0  675.11  5460.8  678.60
#Mann=3,-1,0
  4647.5    0.05       0  4990.7   0.033       0  4998.3    0.05       0
Bank Sta=4990.7,4998.3
Exp/Cntr=0.3,0.1

Type RM Length L Ch R = 1,5047,434,434,434
BEGIN DESCRIPTION:
Hog Branch Tributary 3 10.0
END DESCRIPTION:
XS GIS Cut Line= 3
      2345229.00      7100760.01      2345129.00      7101160.00
      2345029.00      7101909.97
#Sta/Elev= 30
  4588.3  688.47  4619.2  685.95  4629.5  684.52  4753.2  676.34  4763.5  675.04
  4771.2  672.45  4776.4  674.05  4784.1  671.30  4794.4  669.89  4812.5  665.97
  4817.6  666.05  4835.7  663.72  4846.0  663.02  4866.6  662.88  4900.1  663.30
  4949.1  662.87  4969.7  663.67  4978.7  660.53  4979.9  660.03  4985.2  660.03
  4986.4  660.53  4990.3  660.64  4998.0  662.27  5081.3  664.36  5193.5  664.59
  5444.5  668.01  5535.3  670.65  5605.9  673.88  5727.0  677.19  5757.2  677.54
#Mann=3,-1,0
  4588.3    0.05       0  4978.7   0.033       0  4986.4    0.05       0
Bank Sta=4978.7,4986.4
Exp/Cntr=0.3,0.1

Type RM Length L Ch R = 1,4613,465,465,465
BEGIN DESCRIPTION:
Hog Branch Tributary 3 9.0
END DESCRIPTION:
XS GIS Cut Line= 3
      2344537.21      7100815.19      2344729.00      7101160.00
      2344929.01      7101860.03
#Sta/Elev= 30
  4605.8  675.68  4640.1  673.92  4656.1  674.63  4661.9  677.72  4683.6  677.39
  4699.6  673.32  4705.3  674.65  4721.3  672.28  4727.0  674.13  4737.2  673.72
  4759.1  670.97  4867.7  665.79  4883.7  663.14  4889.4  663.96  4897.4  661.11
  4905.4  660.25  4927.2  661.68  4992.4  661.94  4997.5  660.05  5006.9  658.89
  5008.1  658.39  5014.6  658.89  5022.5  659.32  5031.6  661.57  5056.3  662.84
  5196.7  662.88  5364.4  665.12  5459.3  667.81  5526.9  671.61  5728.4  676.87
#Mann=3,-1,0
  4605.8    0.05       0  5006.9    0.04       0  5014.6    0.05       0
Bank Sta=5006.9,5014.6
Exp/Cntr=0.3,0.1

Type RM Length L Ch R = 1,4148,480,480,480
BEGIN DESCRIPTION:
Hog Branch Tributary 3 8.0
END DESCRIPTION:
XS GIS Cut Line= 3
      2344229.00      7101210.00      2344429.00      7101460.00
      2344778.97      7101909.96
#Sta/Elev= 30
  4684.8  704.38  4688.0  704.38  4692.0  702.49  4698.4  701.32  4712.8  696.24
  4727.2  693.93  4735.2  690.37  4741.6  688.60  4748.8  684.98  4762.4  680.67
  4770.4  676.36  4776.8  674.52  4820.1  670.19  4876.9  667.58  4919.3  664.25
  4948.1  661.42  4954.5  659.56  4962.5  658.22  4979.4  657.82  4980.6  657.32
  4987.2  657.82  4997.8  659.83  5018.5  659.58  5055.6  661.12  5140.7  661.42
  5182.3  663.07  5269.2  664.22  5333.4  666.85  5418.5  671.61  5575.0  675.32
#Mann=3,-1,0
  4684.8    0.05       0  4979.4   0.033       0  4987.2    0.05       0
Bank Sta=4979.4,4987.2
Exp/Cntr=0.3,0.1

Type RM Length L Ch R = 1,3668,434,434,434
BEGIN DESCRIPTION:
Hog Branch Tributary 3 7.0
END DESCRIPTION:
XS GIS Cut Line= 3
      2344129.00      7101460.00      2344279.00      7101860.00
      2344474.08      7102154.92
#Sta/Elev= 30
  4572.3  675.02  4604.3  673.07  4612.3  671.99  4625.7  670.99  4642.6  670.71
  4679.1  668.23  4733.4  665.27  4758.3  664.43  4764.5  663.52  4783.2  662.63
  4868.7  660.41  4914.1  660.29  4946.1  658.85  5002.5  658.72  5003.1  657.25
  5004.3  656.75  5009.8  656.75  5010.9  657.25  5028.1  657.57  5043.1  661.76
  5049.1  662.34  5079.2  663.58  5100.3  664.99  5130.4  668.00  5179.3  670.50
  5259.8  672.78  5301.9  674.48  5311.0  673.81  5347.1  674.77  5353.1  674.47
#Mann=3,-1,0
  4572.3    0.05       0  5003.1    0.04       0  5010.9    0.05       0
Bank Sta=5003.1,5010.9
Exp/Cntr=0.3,0.1

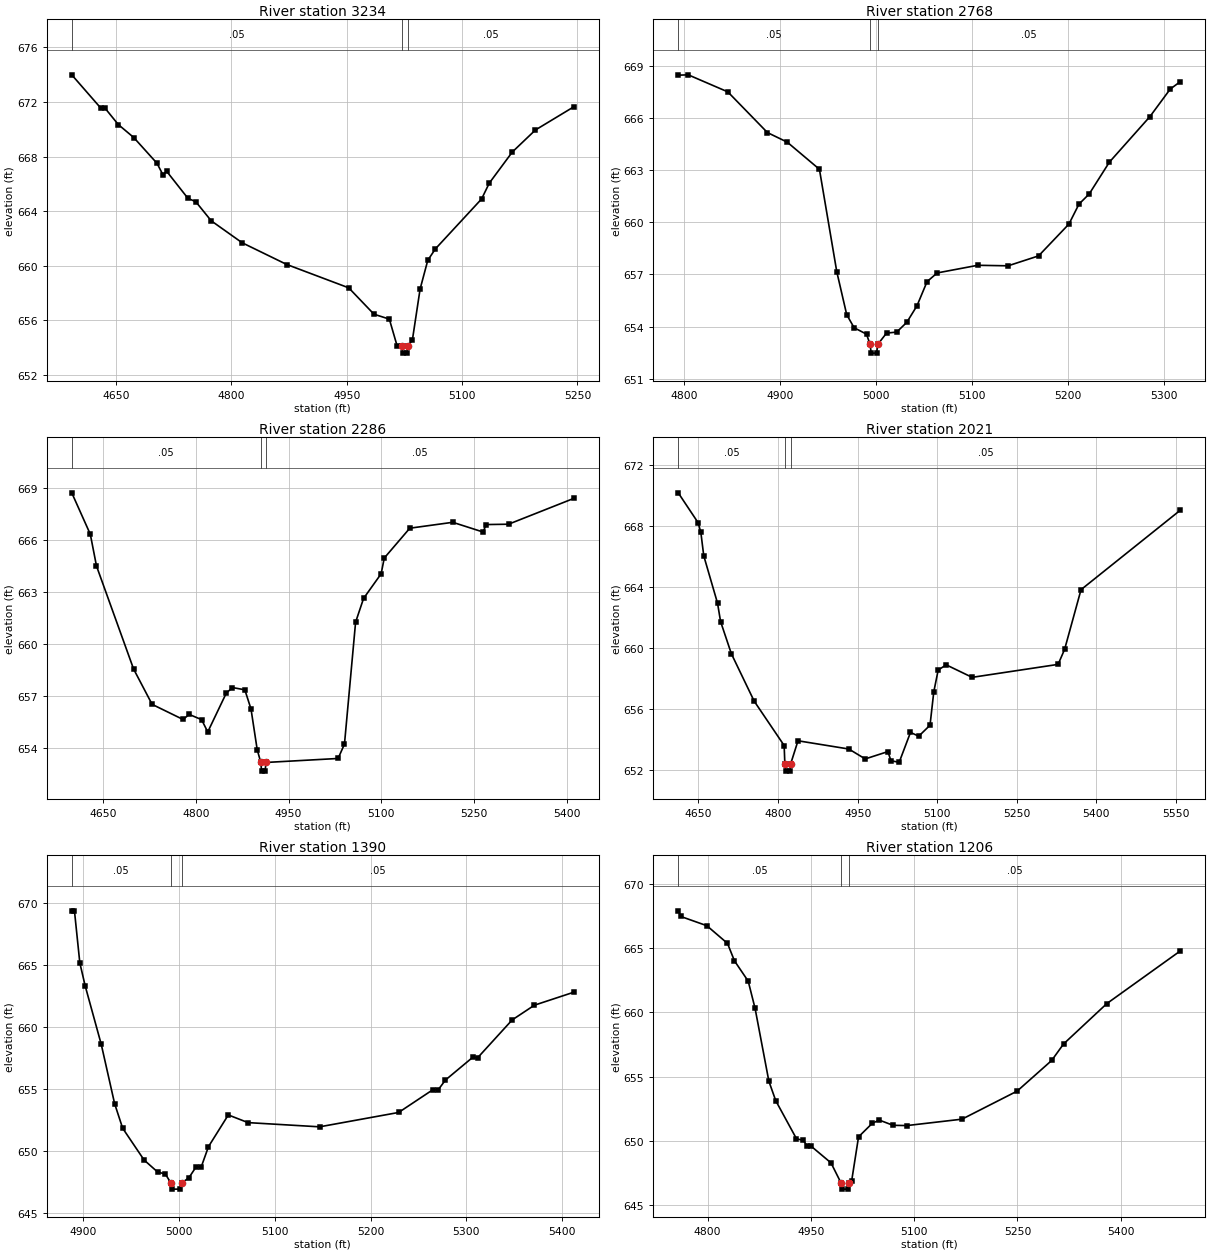
Type RM Length L Ch R = 1,3234,466,466,466
BEGIN DESCRIPTION:
Hog Branch Tributary 3 6.0
END DESCRIPTION:
XS GIS Cut Line= 3
      2343929.00      7101459.98      2343879.00      7101860.00
      2343879.00      7102109.97
#Sta/Elev= 30
  4592.3  673.99  4630.1  671.55  4635.1  671.58  4652.8  670.35  4672.9  669.40
  4703.2  667.51  4710.7  666.69  4715.8  666.92  4743.5  664.94  4753.6  664.70
  4773.7  663.30  4814.0  661.69  4872.0  660.10  4952.6  658.39  4985.4  656.46
  5005.4  656.10  5015.4  654.16  5021.4  654.11  5022.6  653.61  5028.2  653.61
  5029.4  654.11  5035.4  654.58  5045.4  658.30  5055.4  660.41  5065.4  661.25
  5125.4  664.90  5135.4  666.06  5165.4  668.34  5195.4  669.95  5245.4  671.65
#Mann=3,-1,0
  4592.3    0.05       0  5021.4    0.04       0  5029.4    0.05       0
Bank Sta=5021.4,5029.4
Exp/Cntr=0.3,0.1

Type RM Length L Ch R = 1,2768,482,482,482
BEGIN DESCRIPTION:
Hog Branch Tributary 3 5.0
END DESCRIPTION:
XS GIS Cut Line= 3
      2343378.99      7101609.96      2343429.00      7101810.00
      2343528.99      7102109.97
#Sta/Elev= 30
  4794.2  668.45  4804.6  668.47  4845.8  667.49  4887.0  665.15  4907.6  664.60
  4941.1  663.04  4959.2  657.14  4969.5  654.68  4977.2  653.93  4990.1  653.56
  4993.8  652.97  4995.0  652.47  5000.6  652.47  5001.8  652.97  5010.9  653.62
  5021.5  653.68  5032.0  654.24  5042.6  655.19  5053.1  656.58  5063.6  657.08
  5105.8  657.52  5137.4  657.49  5169.1  658.06  5200.7  659.89  5211.2  661.04
  5221.8  661.62  5242.8  663.45  5285.0  666.07  5306.1  667.65  5316.6  668.08
#Mann=3,-1,0
  4794.2    0.05       0  4993.8   0.033       0  5001.8    0.05       0
Bank Sta=4993.8,5001.8
Exp/Cntr=0.3,0.1

Type RM Length L Ch R = 1,2286,265,265,265
BEGIN DESCRIPTION:
Hog Branch Tributary 3 4.0
END DESCRIPTION:
XS GIS Cut Line= 3
      2342979.00      7101510.03      2342979.00      7101910.00
      2343079.01      7102310.02
#Sta/Elev= 30
  4599.2  668.71  4629.2  666.32  4639.2  664.49  4699.2  658.55  4729.2  656.51
  4779.2  655.64  4789.2  655.93  4809.2  655.63  4819.2  654.92  4849.2  657.16
  4859.2  657.48  4879.2  657.35  4889.2  656.24  4899.2  653.90  4905.0  653.16
  4906.3  652.66  4912.1  652.66  4913.3  653.16  5030.1  653.39  5040.4  654.22
  5058.4  661.25  5071.3  662.62  5099.7  664.04  5104.8  664.95  5146.1  666.67
  5215.6  667.01  5264.6  666.45  5269.7  666.88  5305.8  666.90  5411.5  668.39
#Mann=3,-1,0
  4599.2    0.05       0  4905.0   0.033       0  4913.3    0.05       0
Bank Sta=4905,4913.3
Exp/Cntr=0.3,0.1

Type RM Length L Ch R = 1,2021,631,631,631
BEGIN DESCRIPTION:
Mapping XS 61717207
END DESCRIPTION:
XS GIS Cut Line= 3
      2342947.59      7101474.47      2342861.59      7101728.03
      2342282.35      7102081.26
#Sta/Elev= 30
  4611.9  670.15  4649.2  668.20  4654.5  667.56  4660.0  666.02  4685.9  662.92
  4691.7  661.71  4712.0  659.60  4755.0  656.49  4811.5  653.58  4812.8  652.40
  4814.3  651.90  4822.4  651.90  4824.0  652.40  4837.6  653.89  4933.4  653.35
  4964.3  652.70  5007.0  653.18  5012.8  652.58  5028.3  652.48  5049.6  654.44
  5065.1  654.19  5086.4  654.91  5093.5  657.10  5101.8  658.53  5116.9  658.87
  5165.8  658.05  5327.8  658.90  5340.1  659.89  5371.0  663.80  5558.1  669.01
#Mann=3,-1,0
  4611.9    0.05       0  4812.8    0.04       0  4824.0    0.05       0
Bank Sta=4812.8,4824
Exp/Cntr=0.3,0.1

Type RM Length L Ch R = 1,1390,184,184,184
BEGIN DESCRIPTION:
Hog Branch Tributary 3 3.0
END DESCRIPTION:
XS GIS Cut Line= 3
      2342529.01      7101359.99      2342479.00      7101460.00
      2342379.01      7101859.98
#Sta/Elev= 30
  4888.1  669.38  4890.9  669.38  4896.5  665.18  4902.1  663.32  4918.9  658.59
  4932.8  653.82  4941.2  651.83  4963.6  649.26  4977.6  648.30  4985.9  648.12
  4991.5  647.41  4993.1  646.91  5001.2  646.91  5002.7  647.41  5010.2  647.81
  5018.0  648.72  5023.1  648.67  5030.8  650.34  5051.5  652.90  5072.1  652.28
  5146.8  651.94  5229.3  653.10  5265.3  654.95  5270.5  654.92  5278.2  655.72
  5306.6  657.55  5311.7  657.51  5347.8  660.57  5371.0  661.76  5412.2  662.81
#Mann=3,-1,0
  4888.1    0.05       0  4991.5   0.033       0  5002.7    0.05       0
Bank Sta=4991.5,5002.7
Exp/Cntr=0.3,0.1

Type RM Length L Ch R = 1,1206,144,144,144
BEGIN DESCRIPTION:
Mapping XS 78c5883b
END DESCRIPTION:
XS GIS Cut Line= 2
      2342324.05      7101168.56      2342285.05      7101896.51
#Sta/Elev= 30
  4757.5  667.93  4761.2  667.49  4799.0  666.77  4829.0  665.39  4839.1  664.03
  4859.1  662.44  4869.1  660.31  4889.1  654.63  4899.1  653.11  4929.2  650.14
  4939.2  650.01  4944.8  649.56  4949.8  649.59  4979.3  648.26  4993.7  646.71
  4995.2  646.21  5003.3  646.21  5004.9  646.71  5009.3  646.85  5019.3  650.29
  5039.3  651.35  5049.4  651.60  5069.4  651.19  5089.4  651.17  5169.5  651.67
  5249.6  653.86  5299.7  656.25  5317.0  657.54  5379.8  660.69  5486.5  664.80
#Mann=3,-1,0
  4757.5    0.05       0  4993.7   0.033       0  5004.9    0.05       0
Bank Sta=4993.7,5004.9
Exp/Cntr=0.3,0.1

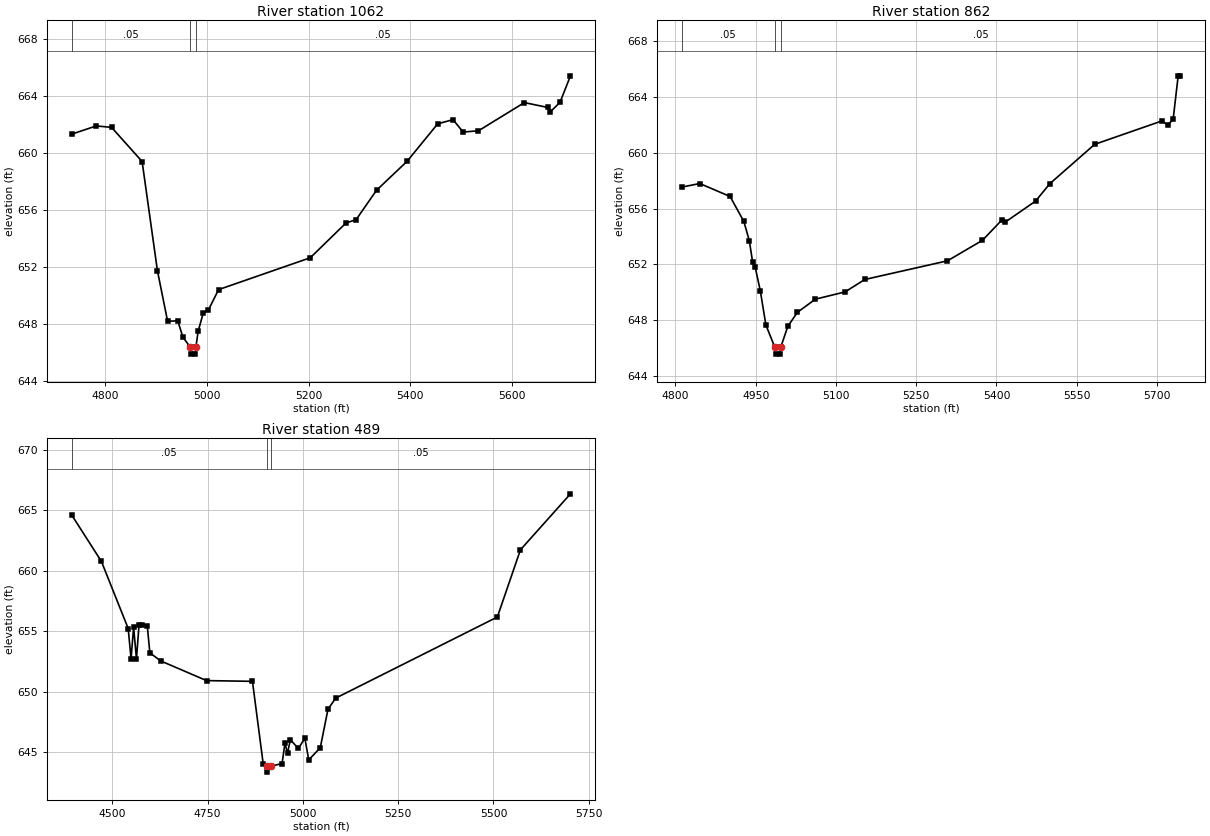
Type RM Length L Ch R = 1,1062,200,200,200
BEGIN DESCRIPTION:
Mapping XS cf8aa472
END DESCRIPTION:
XS GIS Cut Line= 2
      2342189.47      7101091.67      2342162.80      7102070.51
#Sta/Elev= 30
  4735.0  661.34  4783.3  661.92  4813.4  661.82  4873.4  659.42  4903.4  651.76
  4923.4  648.20  4943.4  648.23  4953.4  647.08  4967.8  646.39  4969.4  645.89
  4977.5  645.89  4979.0  646.39  4983.4  647.50  4993.4  648.78  5003.4  648.98
  5023.4  650.42  5203.5  652.66  5273.5  655.10  5293.5  655.34  5333.5  657.40
  5393.6  659.44  5453.6  662.07  5483.6  662.36  5503.6  661.49  5533.6  661.58
  5623.7  663.56  5669.4  663.22  5674.4  662.90  5693.7  663.58  5714.2  665.44
#Mann=3,-1,0
  4735.0    0.05       0  4967.8   0.033       0  4979.0    0.05       0
Bank Sta=4967.8,4979
Exp/Cntr=0.3,0.1

Type RM Length L Ch R = 1,862,373,373,373
BEGIN DESCRIPTION:
Mapping XS 5df277d3
END DESCRIPTION:
XS GIS Cut Line= 2
      2342065.20      7101066.90      2341847.12      7101973.33
#Sta/Elev= 30
  4811.6  657.54  4845.6  657.80  4902.2  656.87  4927.9  655.08  4938.2  653.69
  4944.2  652.19  4949.3  651.78  4958.8  650.08  4969.1  647.66  4985.7  646.07
  4987.2  645.57  4995.3  645.57  4996.9  646.07  5010.2  647.57  5028.1  648.57
  5061.6  649.51  5117.1  650.03  5153.9  650.92  5308.5  652.26  5373.9  653.73
  5410.7  655.21  5415.9  655.02  5473.1  656.54  5499.8  657.79  5583.6  660.61
  5709.5  662.29  5719.9  661.99  5730.2  662.40  5739.6  665.52  5743.9  665.52
#Mann=3,-1,0
  4811.6    0.05       0  4985.7   0.033       0  4996.9    0.05       0
Bank Sta=4985.7,4996.9
Exp/Cntr=0.3,0.1

Type RM Length L Ch R = 1,489,0,0,0
BEGIN DESCRIPTION:
Hog Branch Tributary 3 1.0
END DESCRIPTION:
XS GIS Cut Line= 3
      2342079.01      7100709.98      2341679.00      7101160.00
      2341579.00      7101859.99
#Sta/Elev= 30
  4392.9  664.62  4471.1  660.77  4541.4  655.22  4548.9  652.72  4555.6  655.32
  4563.1  652.71  4569.8  655.50  4577.3  655.54  4591.5  655.44  4598.2  653.21
  4626.6  652.54  4747.1  650.91  4867.5  650.85  4895.9  643.98  4904.5  643.84
  4906.0  643.34  4915.8  643.84  4945.2  644.04  4952.8  645.73  4959.5  644.91
  4967.0  646.02  4987.9  645.30  5005.1  646.14  5015.2  644.35  5045.5  645.36
  5065.7  648.54  5085.9  649.46  5510.2  656.17  5570.8  661.73  5702.1  666.36
#Mann=3,-1,0
  4392.9    0.05       0  4904.5   0.033       0  4915.8    0.05       0
Bank Sta=4904.5,4915.8
Exp/Cntr=0.3,0.1

Chan Stop Cuts=-1