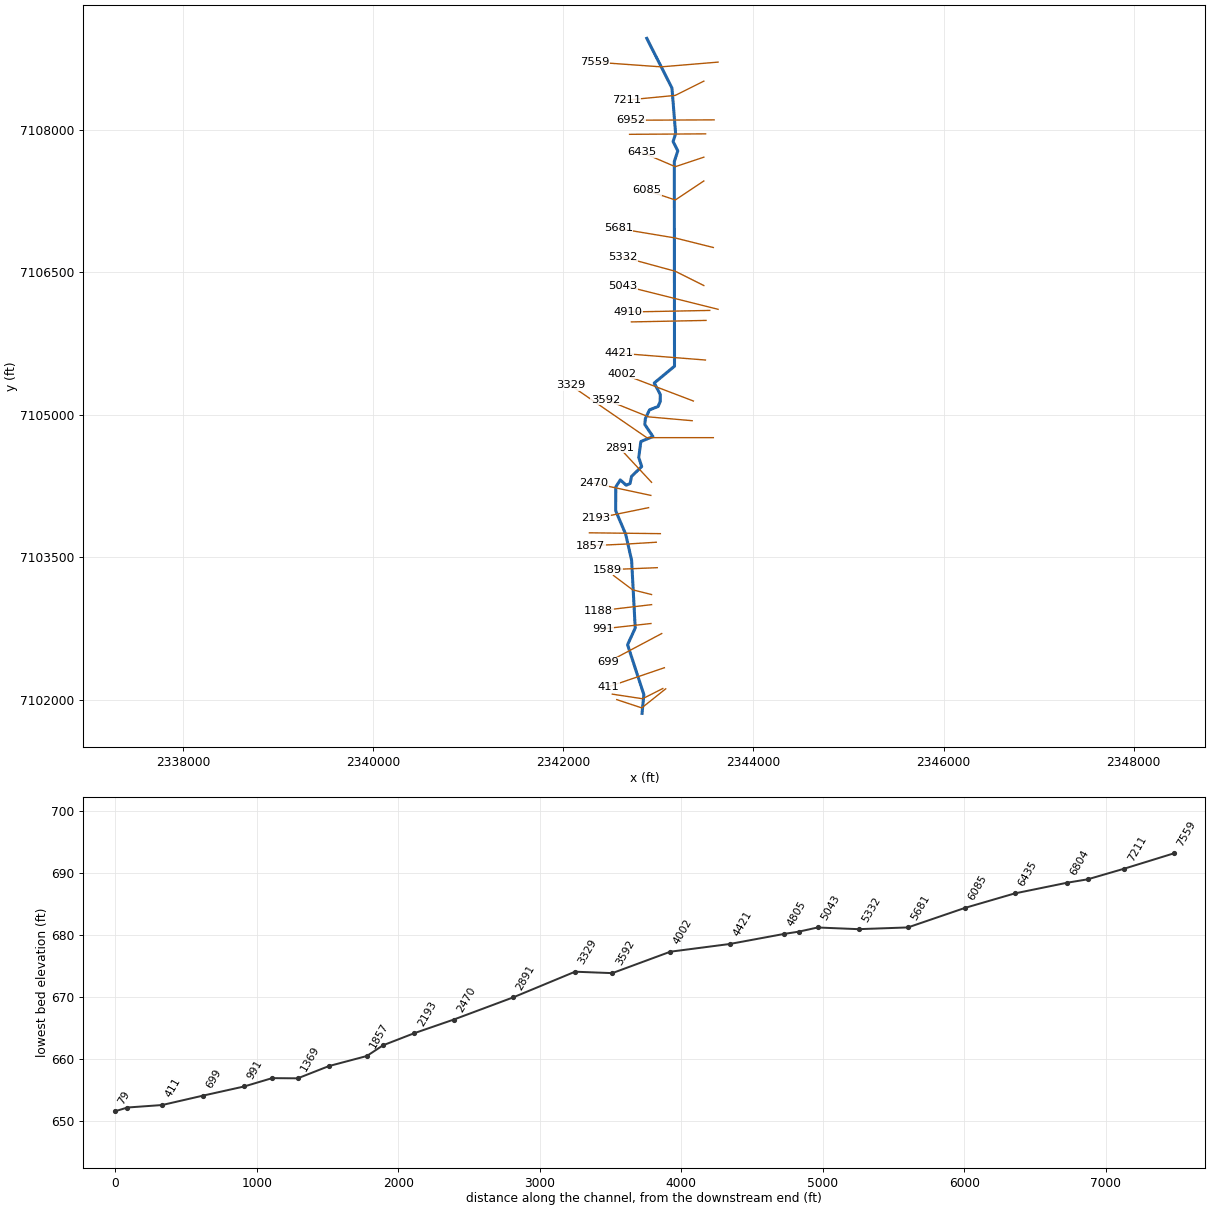
--- Hog Branch Tributary 3_1.prj (project) ---

Proj Title=Hog Branch Tributary 3_1 Base Level Engineering
Current Plan=p01
Default Exp/Contr=0.3,0.1
English Units
Geom File=g01
Flow File=f01
Plan File=p01
BEGIN DESCRIPTION:
Hog Branch Tributary 3_1
END DESCRIPTION:

--- Hog Branch Tributary 3_1.p01 (plan) ---

Plan Title=Multiple Run
Short Identifier=Multiple
Geom File=g01
Flow File=f01
Subcritical Flow
K Sum by GR= 0
Std Step Tol= 0.01
Critical Tol= 0.01
Num of Std Step Trials= 20
Max Error Tol= 0.3
Flow Tol Ratio= 0.001
Split Flow NTrial= 30
Split Flow Tol= 0.02
Split Flow Ratio= 0.02
Log Output Level= 0
Friction Slope Method= 1
Unsteady Friction Slope Method= 2
Unsteady Bridges Friction Slope Method= 1
Parabolic Critical Depth
Global Vel Dist=  1 , 1 , 1
Global Log Level= 0
CheckData=True
Encroach Param= -1, 0, 0, 0
BEGIN DESCRIPTION:
Multiple Run
END DESCRIPTION:

--- Hog Branch Tributary 3_1.f01 (steady flow) ---

Flow Title=Multiple
Number of Profiles=7
Profile Names=10-year,25-year,50-year,1pct_min,100-year,1pct_plu,500-year
River Rch & RM= Hog Branch Tribu,Reach-1,7559
     554     751     911     549    1095    2185    1585
River Rch & RM= Hog Branch Tribu,Reach-1,3592
     664     911    1114     676    1348    2690    1981
Boundary for River Rch & Prof#=Hog Branch Tribu,Reach-1,1
Up Type=0
Dn Type=3
Dn Slope=0.005
Boundary for River Rch & Prof#=Hog Branch Tribu,Reach-1,2
Up Type=0
Dn Type=3
Dn Slope=0.005
Boundary for River Rch & Prof#=Hog Branch Tribu,Reach-1,3
Up Type=0
Dn Type=3
Dn Slope=0.005
Boundary for River Rch & Prof#=Hog Branch Tribu,Reach-1,4
Up Type=0
Dn Type=3
Dn Slope=0.005
Boundary for River Rch & Prof#=Hog Branch Tribu,Reach-1,5
Up Type=0
Dn Type=3
Dn Slope=0.005
Boundary for River Rch & Prof#=Hog Branch Tribu,Reach-1,6
Up Type=0
Dn Type=3
Dn Slope=0.005
Boundary for River Rch & Prof#=Hog Branch Tribu,Reach-1,7
Up Type=0
Dn Type=3
Dn Slope=0.005

--- Hog Branch Tributary 3_1.g01 (geometry) ---

Geom Title=Existing Conditions

River Reach=Hog Branch Tribu,Reach-1
Reach XY= 30
      2342879.00      7108960.00      2343143.87      7108437.19
      2343182.17      7107956.88      2343155.63      7107874.38
      2343205.09      7107775.97      2343168.49      7107664.19
      2343170.53      7105511.39      2342957.01      7105334.80
      2343020.86      7105214.47      2343020.25      7105139.34
      2342997.80      7105087.83      2342907.53      7105052.31
      2342863.99      7104960.77      2342858.02      7104898.84
      2342943.50      7104771.69      2342816.26      7104718.95
      2342794.41      7104551.67      2342825.27      7104455.70
      2342718.67      7104352.83      2342703.20      7104277.53
      2342663.26      7104259.39      2342600.17      7104315.21
      2342552.71      7104241.31      2342551.90      7103991.20
      2342657.38      7103743.21      2342719.29      7103469.96
      2342757.32      7102757.22      2342676.84      7102582.18
      2342847.99      7102057.46      2342829.00      7101860.00

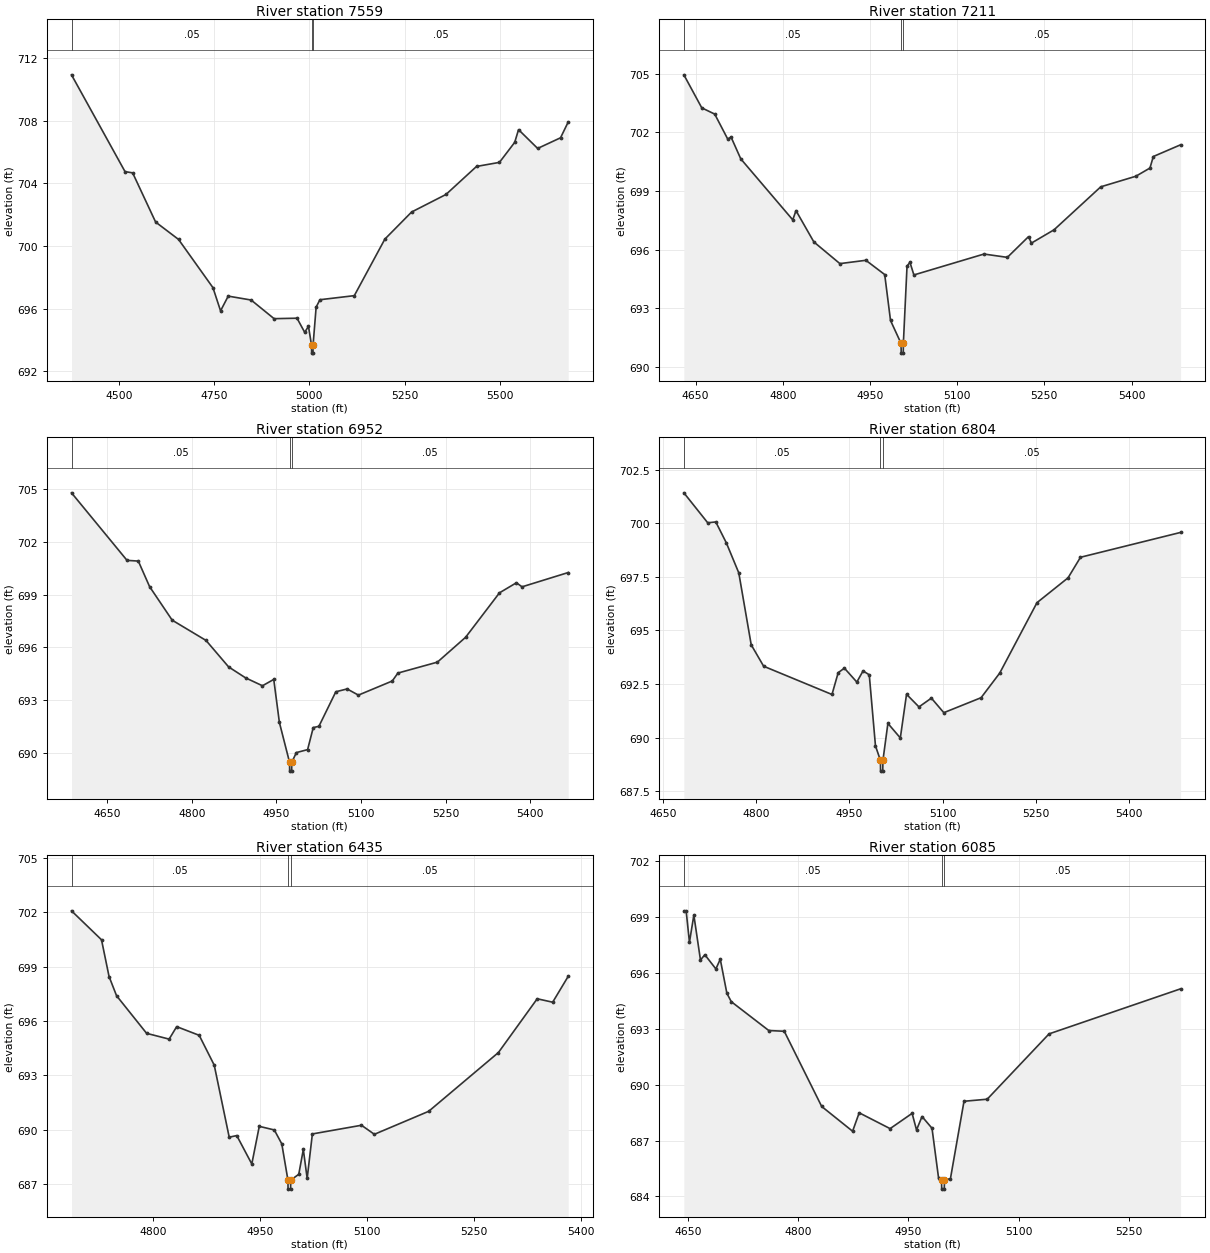
Type RM Length L Ch R = 1,7559,348,348,348
BEGIN DESCRIPTION:
Hog Branch Tributary 3_1 19.0
END DESCRIPTION:
XS GIS Cut Line= 3
      2343628.99      7108710.00      2343029.00      7108660.00
      2342328.96      7108710.00
#Sta/Elev= 30
  4375.8  710.93  4516.3  704.75  4536.3  704.67  4596.6  701.53  4656.8  700.42
  4747.1  697.34  4767.1  695.86  4787.2  696.80  4847.4  696.55  4907.6  695.36
  4967.8  695.39  4987.9  694.49  4997.9  694.87  5005.9  693.66  5006.2  693.16
  5009.7  693.16  5009.9  693.66  5018.0  696.10  5028.0  696.57  5118.2  696.83
  5198.4  700.44  5268.6  702.17  5358.8  703.29  5439.0  705.08  5499.2  705.34
  5539.3  706.62  5549.3  707.43  5599.5  706.23  5659.6  706.91  5679.7  707.92
#Mann=3,-1,0
  4375.8    0.05       0  5005.9   0.035       0  5009.9    0.05       0
Bank Sta=5005.9,5009.9
Exp/Cntr=0.3,0.1

Type RM Length L Ch R = 1,7211,259,259,259
BEGIN DESCRIPTION:
Hog Branch Tributary 3_1 18.0
END DESCRIPTION:
XS GIS Cut Line= 3
      2343479.02      7108510.01      2343179.00      7108360.00
      2342662.37      7108309.84
#Sta/Elev= 30
  4629.9  704.95  4660.7  703.26  4683.0  702.94  4705.4  701.66  4711.0  701.77
  4727.8  700.65  4817.2  697.53  4822.8  698.00  4853.5  696.40  4898.3  695.29
  4943.0  695.46  4975.4  694.73  4985.4  692.38  5003.5  691.21  5003.8  690.71
  5007.3  690.71  5007.5  691.21  5013.8  695.16  5018.8  695.36  5025.6  694.71
  5146.2  695.78  5186.4  695.61  5222.8  696.67  5227.8  696.34  5266.7  697.02
  5347.1  699.22  5407.4  699.76  5431.7  700.18  5437.5  700.77  5484.4  701.37
#Mann=3,-1,0
  4629.9    0.05       0  5003.5    0.04       0  5007.5    0.05       0
Bank Sta=5003.5,5007.5
Exp/Cntr=0.3,0.1

Type RM Length L Ch R = 1,6952,148,148,148
BEGIN DESCRIPTION:
Mapping XS 850bd960
END DESCRIPTION:
XS GIS Cut Line= 2
      2343587.38      7108102.44      2342707.19      7108098.72
#Sta/Elev= 30
  4586.8  704.77  4685.2  700.94  4705.2  700.90  4725.2  699.45  4765.2  697.55
  4825.2  696.40  4865.2  694.90  4895.2  694.28  4925.2  693.83  4945.2  694.19
  4955.2  691.75  4973.2  689.49  4973.4  688.99  4976.9  688.99  4977.2  689.49
  4985.2  690.04  5005.2  690.21  5015.2  691.46  5025.2  691.53  5055.2  693.49
  5075.2  693.65  5095.2  693.30  5155.2  694.10  5165.2  694.55  5235.2  695.17
  5285.2  696.58  5345.2  699.10  5375.2  699.67  5385.2  699.44  5467.0  700.25
#Mann=3,-1,0
  4586.8    0.05       0  4973.2    0.04       0  4977.2    0.05       0
Bank Sta=4973.2,4977.2
Exp/Cntr=0.3,0.1

Type RM Length L Ch R = 1,6804,369,369,369
BEGIN DESCRIPTION:
Mapping XS 5c3862ae
END DESCRIPTION:
XS GIS Cut Line= 2
      2343497.39      7107955.31      2342697.91      7107950.35
#Sta/Elev= 30
  4683.7  701.43  4722.1  700.03  4735.1  700.07  4752.1  699.09  4772.1  697.69
  4792.1  694.33  4812.1  693.33  4922.1  692.01  4932.1  693.03  4942.1  693.24
  4962.1  692.59  4972.1  693.11  4982.1  692.93  4992.1  689.61  5000.1  688.93
  5000.3  688.43  5003.8  688.43  5004.1  688.93  5012.1  690.66  5032.1  689.98
  5042.1  692.02  5062.1  691.43  5082.1  691.84  5102.1  691.16  5162.1  691.86
  5192.1  693.01  5252.1  696.30  5302.1  697.46  5322.1  698.42  5483.2  699.58
#Mann=3,-1,0
  4683.7    0.05       0  5000.1   0.033       0  5004.1    0.05       0
Bank Sta=5000.1,5004.1
Exp/Cntr=0.3,0.1

Type RM Length L Ch R = 1,6435,350,350,350
BEGIN DESCRIPTION:
Hog Branch Tributary 3_1 16.0
END DESCRIPTION:
XS GIS Cut Line= 3
      2343478.99      7107710.00      2343179.00      7107610.00
      2342829.00      7107760.00
#Sta/Elev= 30
  4685.3  702.09  4727.4  700.49  4738.0  698.46  4748.5  697.40  4790.7  695.32
  4822.3  695.00  4832.9  695.69  4864.5  695.21  4885.6  693.56  4906.6  689.58
  4917.2  689.67  4938.3  688.10  4948.8  690.18  4969.9  689.98  4980.4  689.21
  4989.0  687.21  4989.2  686.71  4992.7  686.71  4993.0  687.21  5004.2  687.53
  5010.6  688.90  5016.0  687.30  5023.3  689.76  5092.2  690.24  5110.3  689.74
  5186.5  691.01  5284.4  694.26  5338.8  697.23  5360.5  697.04  5382.3  698.47
#Mann=3,-1,0
  4685.3    0.05       0  4989.0   0.033       0  4993.0    0.05       0
Bank Sta=4989,4993
Exp/Cntr=0.3,0.1

Type RM Length L Ch R = 1,6085,404,404,404
BEGIN DESCRIPTION:
Hog Branch Tributary 3_1 15.0
END DESCRIPTION:
XS GIS Cut Line= 3
      2343479.04      7107460.03      2343179.00      7107260.00
      2342879.03      7107359.99
#Sta/Elev= 30
  4644.0  699.34  4647.1  699.34  4651.6  697.65  4657.6  699.11  4666.6  696.70
  4672.6  696.98  4687.6  696.22  4693.6  696.74  4702.6  694.91  4708.6  694.46
  4759.7  692.91  4780.8  692.87  4831.8  688.83  4873.9  687.50  4882.9  688.49
  4925.0  687.64  4955.0  688.46  4961.0  687.57  4968.5  688.29  4982.1  687.66
  4991.1  684.97  4995.1  684.89  4995.3  684.39  4998.8  684.39  4999.1  684.89
  5007.2  684.95  5025.7  689.11  5057.3  689.22  5141.6  692.73  5320.8  695.15
#Mann=3,-1,0
  4644.0    0.05       0  4995.1   0.033       0  4999.1    0.05       0
Bank Sta=4995.1,4999.1
Exp/Cntr=0.3,0.1

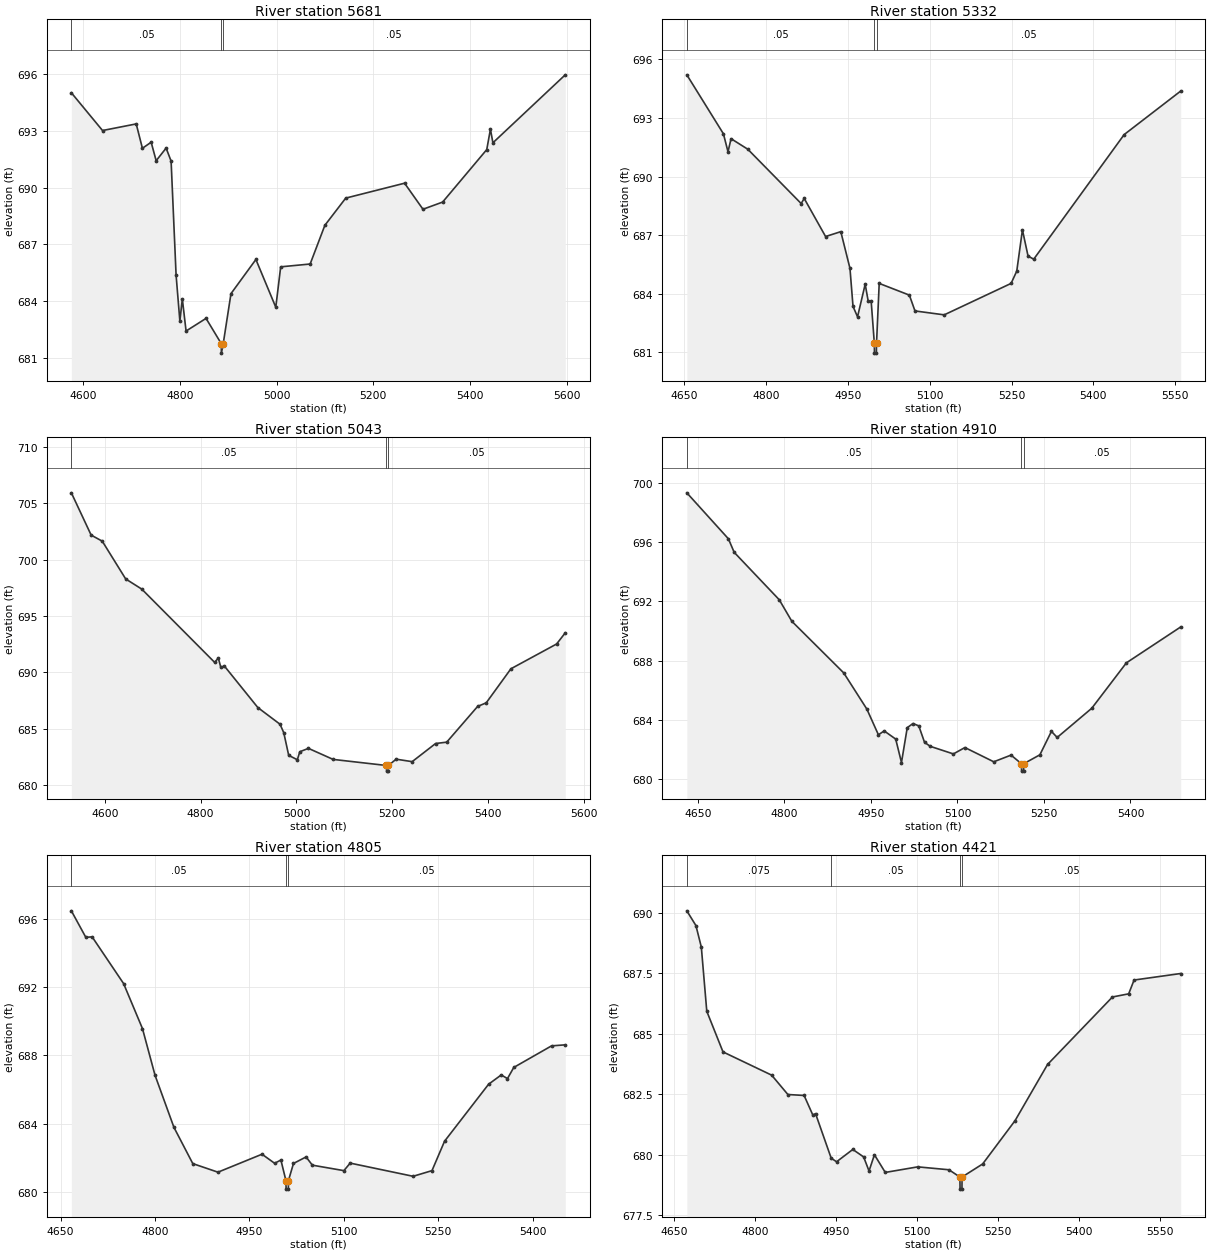
Type RM Length L Ch R = 1,5681,349,349,349
BEGIN DESCRIPTION:
Hog Branch Tributary 3_1 14.0
END DESCRIPTION:
XS GIS Cut Line= 3
      2343578.96      7106760.01      2343179.00      7106860.00
      2342579.04      7106959.99
#Sta/Elev= 30
  4576.1  695.03  4640.5  693.03  4710.1  693.38  4722.9  692.09  4741.0  692.41
  4751.3  691.43  4771.9  692.10  4782.2  691.41  4792.5  685.37  4800.3  682.94
  4805.4  684.11  4813.1  682.41  4854.4  683.08  4885.9  681.74  4886.1  681.24
  4889.9  681.74  4905.9  684.39  4957.4  686.20  4998.5  683.67  5008.6  685.81
  5069.5  685.96  5099.9  688.01  5143.0  689.45  5264.6  690.24  5302.6  688.86
  5343.2  689.24  5434.4  692.02  5442.0  693.10  5447.1  692.38  5596.6  695.98
#Mann=3,-1,0
  4576.1    0.05       0  4885.9   0.033       0  4889.9    0.05       0
Bank Sta=4885.9,4889.9
Exp/Cntr=0.3,0.1

Type RM Length L Ch R = 1,5332,289,289,289
BEGIN DESCRIPTION:
Hog Branch Tributary 3_1 13.0
END DESCRIPTION:
XS GIS Cut Line= 3
      2343479.00      7106360.00      2343179.00      7106510.00
      2342629.00      7106660.00
#Sta/Elev= 30
  4654.7  695.21  4721.8  692.19  4730.2  691.27  4735.8  691.94  4766.5  691.40
  4864.3  688.62  4869.9  688.88  4909.1  686.93  4937.0  687.18  4953.8  685.30
  4959.4  683.35  4967.7  682.82  4981.7  684.49  4987.3  683.61  4992.7  683.61
  4998.5  681.46  4998.7  680.96  5002.2  680.96  5002.5  681.46  5007.4  684.53
  5062.7  683.93  5073.0  683.12  5126.6  682.92  5249.2  684.53  5259.6  685.16
  5270.0  687.27  5280.3  685.93  5290.7  685.77  5456.5  692.15  5560.2  694.38
#Mann=3,-1,0
  4654.7    0.05       0  4998.5   0.033       0  5002.5    0.05       0
Bank Sta=4998.5,5002.5
Exp/Cntr=0.3,0.1

Type RM Length L Ch R = 1,5043,133,133,133
BEGIN DESCRIPTION:
Hog Branch Tributary 3_1 12.0
END DESCRIPTION:
XS GIS Cut Line= 3
      2343629.04      7106109.99      2343029.00      7106260.00
      2342629.01      7106360.00
#Sta/Elev= 30
  4530.2  705.92  4571.5  702.17  4594.7  701.63  4643.6  698.28  4677.1  697.38
  4829.2  690.88  4836.9  691.26  4842.0  690.46  4849.8  690.54  4919.4  686.87
  4965.7  685.39  4973.5  684.64  4983.8  682.63  5001.8  682.24  5007.0  682.95
  5025.0  683.25  5076.5  682.27  5187.9  681.73  5188.2  681.23  5191.7  681.23
  5191.9  681.73  5208.0  682.29  5241.5  682.07  5290.4  683.68  5313.6  683.80
  5378.1  686.97  5396.1  687.29  5447.6  690.31  5543.0  692.51  5561.0  693.50
#Mann=3,-1,0
  4530.2    0.05       0  5187.9   0.033       0  5191.9    0.05       0
Bank Sta=5187.9,5191.9
Exp/Cntr=0.3,0.1

Type RM Length L Ch R = 1,4910,105,105,105
BEGIN DESCRIPTION:
Mapping XS 689410f7
END DESCRIPTION:
XS GIS Cut Line= 2
      2343541.09      7106098.15      2342684.85      7106081.63
#Sta/Elev= 30
  4630.7  699.32  4702.8  696.22  4712.8  695.31  4791.0  692.11  4812.8  690.66
  4902.8  687.18  4942.9  684.74  4962.9  683.01  4972.9  683.27  4992.9  682.72
  5002.9  681.14  5012.9  683.49  5022.9  683.77  5032.9  683.61  5042.9  682.50
  5052.9  682.23  5092.9  681.72  5112.9  682.15  5162.9  681.19  5192.9  681.64
  5210.9  681.06  5211.2  680.56  5214.7  680.56  5214.9  681.06  5242.9  681.66
  5262.9  683.24  5272.9  682.83  5332.9  684.80  5392.9  687.86  5487.1  690.28
#Mann=3,-1,0
  4630.7    0.05       0  5210.9    0.05       0  5214.9    0.05       0
Bank Sta=5210.9,5214.9
Exp/Cntr=0.3,0.1

Type RM Length L Ch R = 1,4805,384,384,384
BEGIN DESCRIPTION:
Mapping XS 828849b7
END DESCRIPTION:
XS GIS Cut Line= 2
      2343501.96      7105993.04      2342717.22      7105977.35
#Sta/Elev= 30
  4667.1  696.45  4690.1  694.90  4700.1  694.93  4750.1  692.20  4780.1  689.57
  4800.1  686.84  4830.1  683.80  4860.1  681.68  4900.1  681.18  4970.1  682.23
  4990.1  681.70  5000.1  681.89  5008.1  680.69  5008.4  680.19  5011.9  680.19
  5012.1  680.69  5020.1  681.69  5040.1  682.07  5050.1  681.59  5100.2  681.27
  5110.2  681.71  5210.2  680.94  5240.2  681.27  5260.2  682.99  5330.2  686.32
  5350.2  686.86  5360.2  686.65  5370.2  687.30  5430.2  688.56  5452.0  688.62
#Mann=3,-1,0
  4667.1    0.05       0  5008.1    0.05       0  5012.1    0.05       0
Bank Sta=5008.1,5012.1
Exp/Cntr=0.3,0.1

Type RM Length L Ch R = 1,4421,419,419,419
BEGIN DESCRIPTION:
Mapping XS 8e000eec
END DESCRIPTION:
XS GIS Cut Line= 2
      2343495.85      7105576.52      2342582.80      7105648.63
#Sta/Elev= 30
  4673.4  690.07  4690.3  689.46  4700.3  688.57  4710.4  685.92  4740.5  684.24
  4830.7  683.28  4860.8  682.48  4890.9  682.44  4907.1  681.63  4912.1  681.69
  4941.1  679.85  4951.1  679.70  4981.2  680.21  5001.3  679.90  5011.3  679.32
  5021.3  679.99  5041.4  679.26  5101.6  679.49  5159.5  679.37  5179.8  679.07
  5180.1  678.57  5183.6  678.57  5183.8  679.07  5222.0  679.61  5282.1  681.40
  5342.3  683.72  5462.7  686.51  5492.8  686.64  5502.8  687.21  5589.3  687.48
#Mann=4,-1,0
  4673.4   0.075       0  4941.1    0.05       0  5179.8   0.033       0
  5183.8    0.05       0
Bank Sta=5179.8,5183.8
Exp/Cntr=0.3,0.1

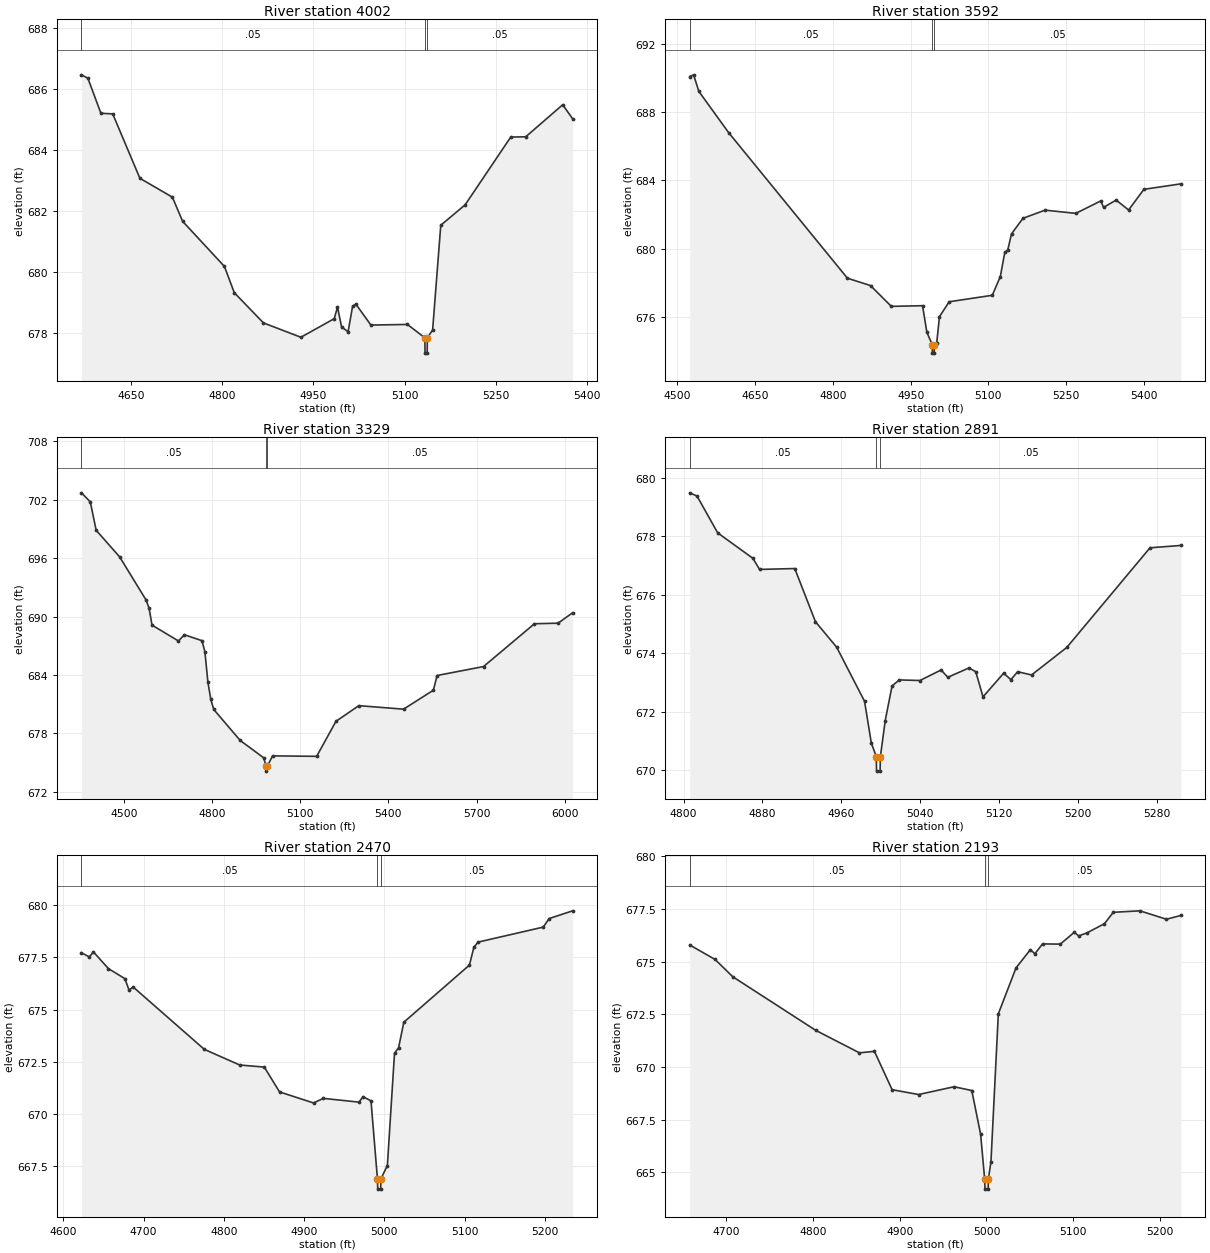
Type RM Length L Ch R = 1,4002,410,410,410
BEGIN DESCRIPTION:
Mapping XS 0b61c8d7
END DESCRIPTION:
XS GIS Cut Line= 2
      2343368.83      7105145.49      2342613.76      7105433.14
#Sta/Elev= 30
  4568.4  686.45  4578.9  686.34  4600.4  685.19  4619.8  685.17  4664.5  683.06
  4718.0  682.44  4734.8  681.65  4803.6  680.17  4819.8  679.31  4867.8  678.32
  4929.4  677.85  4984.3  678.46  4989.6  678.84  4996.3  678.19  5007.0  678.03
  5014.4  678.86  5019.7  678.94  5044.5  678.25  5104.7  678.27  5133.4  677.83
  5133.6  677.33  5137.1  677.33  5137.4  677.83  5146.1  678.09  5159.5  681.52
  5199.6  682.19  5274.6  684.41  5299.3  684.42  5360.1  685.47  5376.4  685.01
#Mann=3,-1,0
  4568.4    0.05       0  5133.4   0.033       0  5137.4    0.05       0
Bank Sta=5133.4,5137.4
Exp/Cntr=0.3,0.1

Type RM Length L Ch R = 1,3592,263,263,263
BEGIN DESCRIPTION:
Mapping XS 52fce8fb
END DESCRIPTION:
XS GIS Cut Line= 3
      2343356.49      7104938.24      2342897.56      7104978.67
      2342446.07      7105160.94
#Sta/Elev= 30
  4523.7  690.09  4531.2  690.19  4541.3  689.22  4598.6  686.81  4828.0  678.27
  4872.5  677.84  4912.7  676.62  4972.9  676.66  4981.2  675.11  4991.5  674.38
  4991.9  673.88  4995.4  673.88  4995.7  674.38  5000.2  674.47  5005.6  676.02
  5024.3  676.89  5107.5  677.27  5123.0  678.37  5131.7  679.80  5137.1  679.90
  5144.6  680.87  5166.6  681.78  5209.3  682.26  5268.5  682.07  5316.8  682.80
  5322.2  682.42  5346.4  682.85  5370.5  682.27  5400.0  683.48  5471.3  683.80
#Mann=3,-1,0
  4523.7    0.05       0  4991.5   0.033       0  4995.7    0.05       0
Bank Sta=4991.5,4995.7
Exp/Cntr=0.3,0.1

Type RM Length L Ch R = 1,3329,438,438,438
BEGIN DESCRIPTION:
Hog Branch Tributary 3_1 7.0
END DESCRIPTION:
XS GIS Cut Line= 3
      2343578.97      7104760.00      2342879.00      7104760.00
      2342079.00      7105310.00
#Sta/Elev= 30
  4356.0  702.72  4386.0  701.79  4406.0  698.87  4486.0  696.13  4576.0  691.69
  4586.0  690.86  4596.0  689.12  4686.0  687.49  4706.0  688.13  4766.0  687.52
  4776.0  686.36  4786.0  683.28  4796.0  681.48  4806.0  680.45  4896.0  677.26
  4976.0  675.48  4983.9  674.61  4984.2  674.11  4988.1  674.61  5006.0  675.68
  5156.1  675.63  5221.7  679.23  5299.5  680.84  5451.7  680.48  5553.2  682.43
  5565.7  683.94  5723.7  684.86  5896.9  689.26  5977.4  689.32  6026.8  690.39
#Mann=3,-1,0
  4356.0    0.05       0  4983.9   0.033       0  4988.1    0.05       0
Bank Sta=4983.9,4988.1
Exp/Cntr=0.3,0.1

Type RM Length L Ch R = 1,2891,421,421,421
BEGIN DESCRIPTION:
Mapping XS e6b3a609
END DESCRIPTION:
XS GIS Cut Line= 2
      2342929.45      7104290.02      2342589.57      7104654.55
#Sta/Elev= 30
  4806.2  679.49  4813.6  679.38  4834.6  678.12  4870.3  677.25  4877.1  676.87
  4912.8  676.90  4933.8  675.08  4955.3  674.21  4983.6  672.36  4990.5  670.93
  4995.5  670.47  4995.8  669.97  4999.4  669.97  4999.7  670.47  5004.6  671.70
  5011.5  672.88  5018.8  673.09  5039.8  673.07  5061.3  673.43  5068.1  673.18
  5089.6  673.50  5096.5  673.37  5103.8  672.51  5124.8  673.32  5132.1  673.10
  5139.0  673.37  5153.1  673.26  5188.8  674.20  5273.3  677.61  5304.6  677.69
#Mann=3,-1,0
  4806.2    0.05       0  4995.5    0.04       0  4999.7    0.05       0
Bank Sta=4995.5,4999.7
Exp/Cntr=0.3,0.1

Type RM Length L Ch R = 1,2470,277,277,277
BEGIN DESCRIPTION:
Mapping XS 3ed143d7
END DESCRIPTION:
XS GIS Cut Line= 2
      2342921.88      7104152.59      2342323.22      7104280.64
#Sta/Elev= 30
  4622.5  677.72  4632.3  677.52  4637.4  677.76  4656.1  676.96  4676.6  676.48
  4681.8  675.93  4686.9  676.08  4775.6  673.09  4819.7  672.34  4850.4  672.24
  4869.4  671.05  4911.8  670.52  4924.0  670.74  4968.4  670.56  4973.5  670.82
  4983.4  670.62  4991.4  666.89  4991.8  666.39  4995.4  666.39  4995.8  666.89
  5003.8  667.52  5012.7  672.90  5017.8  673.17  5024.3  674.39  5106.1  677.13
  5111.6  677.98  5116.8  678.23  5198.1  678.95  5205.5  679.36  5234.7  679.73
#Mann=3,-1,0
  4622.5    0.05       0  4991.4   0.033       0  4995.8    0.05       0
Bank Sta=4991.4,4995.8
Exp/Cntr=0.3,0.1

Type RM Length L Ch R = 1,2193,221,221,221
BEGIN DESCRIPTION:
Mapping XS 23027111
END DESCRIPTION:
XS GIS Cut Line= 2
      2342897.71      7104023.68      2342342.71      7103910.63
#Sta/Elev= 30
  4657.8  675.80  4687.1  675.11  4707.5  674.29  4803.0  671.75  4853.5  670.68
  4870.8  670.75  4891.2  668.93  4921.8  668.70  4962.6  669.07  4983.1  668.89
  4993.3  666.81  4997.9  664.71  4998.3  664.21  5001.9  664.21  5002.3  664.71
  5005.2  665.51  5013.7  672.53  5034.1  674.71  5050.7  675.58  5055.8  675.38
  5064.7  675.85  5085.1  675.84  5101.3  676.40  5106.4  676.23  5115.7  676.37
  5136.1  676.81  5146.3  677.35  5177.0  677.42  5207.6  677.02  5224.2  677.20
#Mann=3,-1,0
  4657.8    0.05       0  4997.9   0.033       0  5002.3    0.05       0
Bank Sta=4997.9,5002.3
Exp/Cntr=0.3,0.1

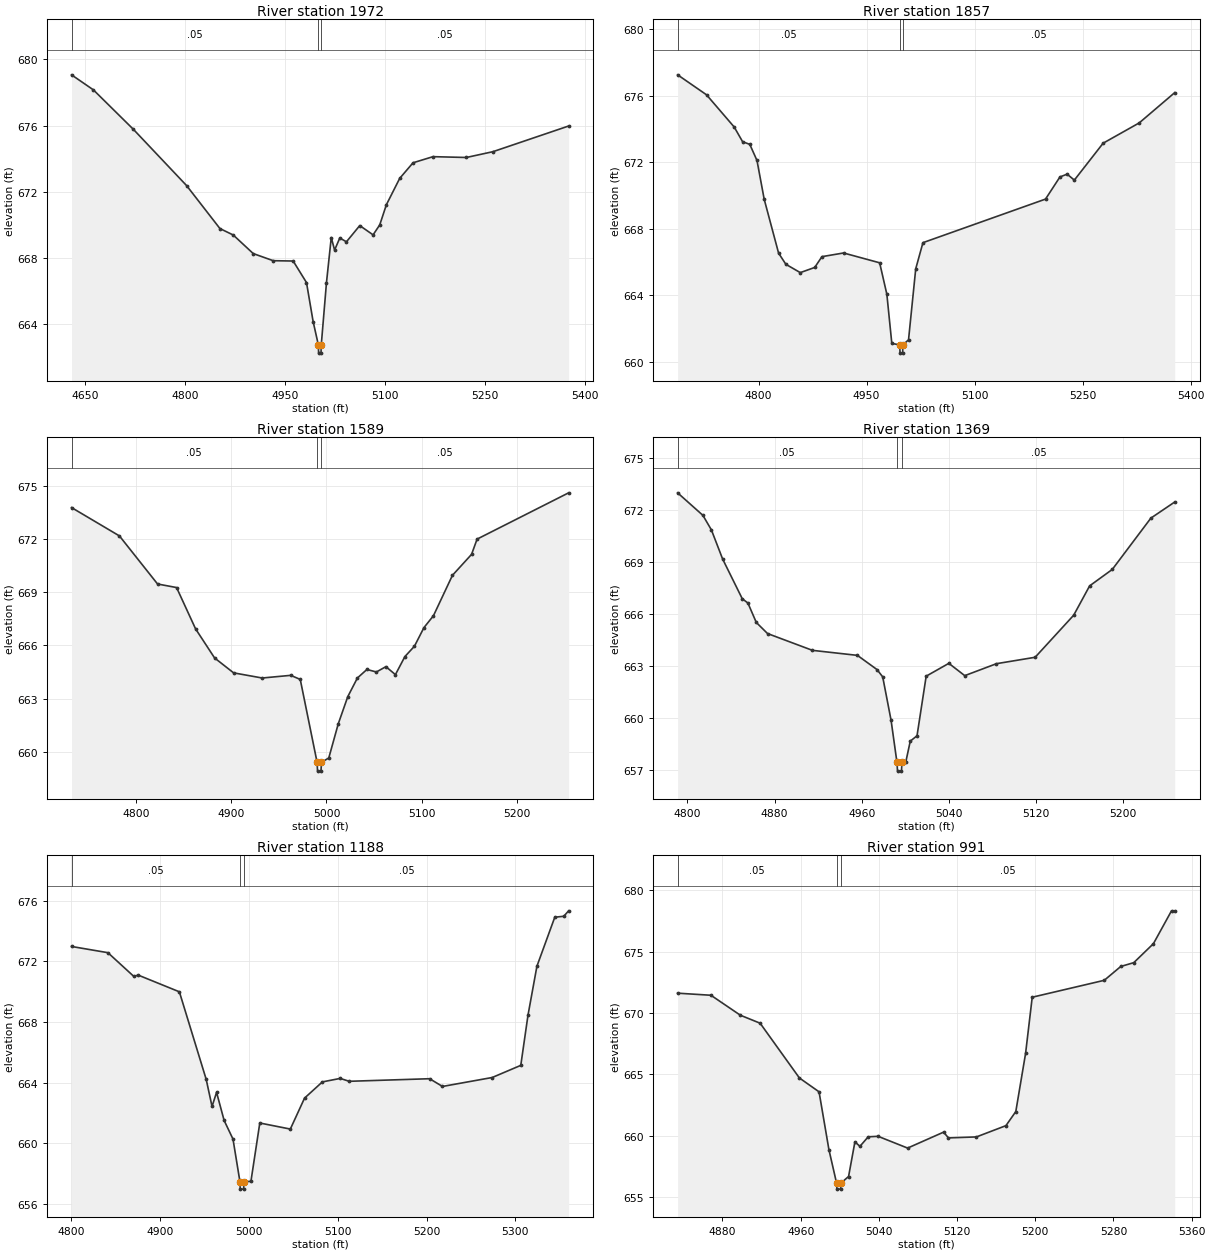
Type RM Length L Ch R = 1,1972,115,115,115
BEGIN DESCRIPTION:
Mapping XS 71db27dd
END DESCRIPTION:
XS GIS Cut Line= 2
      2343021.91      7103750.40      2342275.36      7103759.15
#Sta/Elev= 30
  4629.1  679.06  4662.0  678.15  4722.0  675.77  4802.0  672.37  4852.0  669.78
  4872.0  669.39  4902.0  668.27  4932.0  667.84  4962.0  667.82  4982.0  666.52
  4992.0  664.16  4999.8  662.76  5000.2  662.26  5003.8  662.26  5004.2  662.76
  5012.0  666.51  5019.2  669.24  5024.2  668.48  5032.0  669.21  5042.0  668.98
  5062.0  669.96  5082.0  669.40  5092.0  670.00  5102.0  671.22  5122.0  672.81
  5142.0  673.75  5172.0  674.12  5222.0  674.07  5262.0  674.42  5375.7  675.97
#Mann=3,-1,0
  4629.1    0.05       0  4999.8   0.033       0  5004.2    0.05       0
Bank Sta=4999.8,5004.2
Exp/Cntr=0.3,0.1

Type RM Length L Ch R = 1,1857,268,268,268
BEGIN DESCRIPTION:
Hog Branch Tributary 3_1 4.0
END DESCRIPTION:
XS GIS Cut Line= 3
      2342978.99      7103660.00      2342680.20      7103641.76
      2342289.74      7103624.14
#Sta/Elev= 30
  4687.6  677.26  4727.7  676.06  4766.2  674.12  4777.8  673.24  4787.8  673.08
  4797.8  672.11  4807.8  669.78  4827.8  666.54  4837.9  665.87  4857.9  665.37
  4877.9  665.68  4888.0  666.33  4918.0  666.55  4968.1  665.96  4978.1  664.07
  4985.0  661.11  4996.0  661.03  4996.4  660.53  5000.0  660.53  5000.4  661.03
  5008.2  661.33  5018.2  665.60  5028.2  667.17  5198.4  669.79  5218.4  671.12
  5228.4  671.29  5238.4  670.93  5278.4  673.15  5328.5  674.37  5377.8  676.19
#Mann=3,-1,0
  4687.6    0.05       0  4996.0    0.04       0  5000.4    0.05       0
Bank Sta=4996,5000.4
Exp/Cntr=0.3,0.1

Type RM Length L Ch R = 1,1589,220,220,220
BEGIN DESCRIPTION:
Mapping XS 7b86df17
END DESCRIPTION:
XS GIS Cut Line= 2
      2342989.41      7103392.44      2342466.94      7103371.10
#Sta/Elev= 30
  4731.8  673.77  4782.2  672.17  4822.3  669.46  4842.3  669.26  4862.3  666.93
  4882.3  665.29  4902.3  664.45  4932.4  664.16  4962.4  664.31  4972.4  664.08
  4990.1  659.41  4990.6  658.91  4994.2  658.91  4994.7  659.41  5002.4  659.65
  5012.4  661.58  5022.4  663.11  5032.5  664.16  5042.5  664.64  5052.5  664.50
  5062.5  664.80  5072.5  664.35  5082.5  665.37  5092.5  665.95  5102.5  667.00
  5112.5  667.67  5132.5  669.95  5152.6  671.13  5158.4  671.99  5254.7  674.60
#Mann=3,-1,0
  4731.8    0.05       0  4990.1    0.04       0  4994.7    0.05       0
Bank Sta=4990.1,4994.7
Exp/Cntr=0.3,0.1

Type RM Length L Ch R = 1,1369,181,181,181
BEGIN DESCRIPTION:
Hog Branch Tributary 3_1 3.0
END DESCRIPTION:
XS GIS Cut Line= 3
      2342929.03      7103109.99      2342729.00      7103160.00
      2342528.99      7103310.01
#Sta/Elev= 30
  4791.0  673.00  4814.2  671.70  4822.0  670.86  4832.3  669.18  4850.3  666.89
  4855.5  666.64  4863.2  665.52  4873.5  664.88  4914.7  663.91  4956.0  663.62
  4974.0  662.80  4979.2  662.38  4986.9  659.87  4992.3  657.44  4992.8  656.94
  4996.4  656.94  4996.9  657.44  5000.3  657.44  5004.5  658.67  5010.7  658.98
  5019.1  662.42  5039.9  663.16  5054.5  662.45  5083.6  663.14  5119.1  663.51
  5154.5  665.94  5169.1  667.63  5189.9  668.58  5225.3  671.54  5247.2  672.47
#Mann=3,-1,0
  4791.0    0.05       0  4992.3    0.04       0  4996.9    0.05       0
Bank Sta=4992.3,4996.9
Exp/Cntr=0.3,0.1

Type RM Length L Ch R = 1,1188,197,197,197
BEGIN DESCRIPTION:
Mapping XS 9cafb795
END DESCRIPTION:
XS GIS Cut Line= 2
      2342929.68      7103003.64      2342373.50      7102938.37
#Sta/Elev= 30
  4800.1  672.97  4841.1  672.56  4870.2  671.00  4875.3  671.08  4921.6  669.98
  4951.8  664.21  4958.4  662.42  4963.5  663.35  4972.0  661.50  4982.0  660.27
  4989.8  657.47  4990.2  656.97  4993.9  656.97  4994.4  657.47  5002.2  657.48
  5012.2  661.33  5046.6  660.93  5062.6  662.97  5082.7  664.04  5102.8  664.27
  5112.9  664.08  5203.5  664.25  5218.0  663.74  5274.0  664.33  5306.2  665.13
  5314.3  668.43  5324.4  671.67  5344.5  674.90  5354.6  674.96  5360.1  675.32
#Mann=3,-1,0
  4800.1    0.05       0  4989.8   0.033       0  4994.4    0.05       0
Bank Sta=4989.8,4994.4
Exp/Cntr=0.3,0.1

Type RM Length L Ch R = 1,991,292,292,292
BEGIN DESCRIPTION:
Mapping XS d32eeb09
END DESCRIPTION:
XS GIS Cut Line= 2
      2342922.85      7102805.15      2342417.34      7102749.13
#Sta/Elev= 30
  4834.1  671.62  4868.2  671.45  4898.3  669.82  4918.5  669.17  4958.7  664.70
  4978.8  663.57  4988.9  658.85  4996.7  656.13  4997.1  655.63  5000.8  655.63
  5001.3  656.13  5009.0  656.66  5015.5  659.49  5020.6  659.12  5029.1  659.90
  5039.2  659.94  5069.4  658.98  5106.2  660.28  5111.2  659.81  5139.8  659.89
  5170.0  660.81  5180.1  661.96  5190.1  666.70  5196.9  671.29  5270.6  672.67
  5287.5  673.80  5300.8  674.11  5320.9  675.66  5339.4  678.34  5342.7  678.34
#Mann=3,-1,0
  4834.1    0.05       0  4996.7    0.04       0  5001.3    0.05       0
Bank Sta=4996.7,5001.3
Exp/Cntr=0.3,0.1

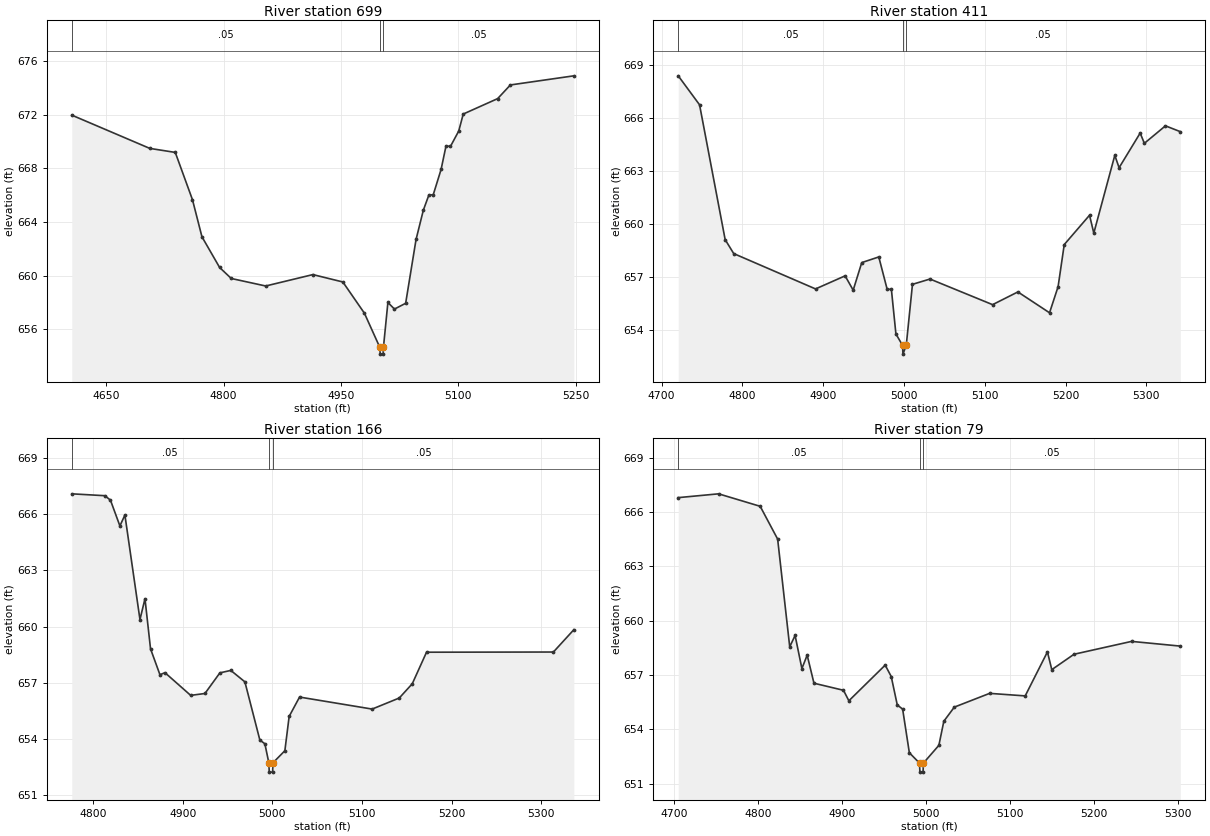
Type RM Length L Ch R = 1,699,288,288,288
BEGIN DESCRIPTION:
Mapping XS 7b64dd74
END DESCRIPTION:
XS GIS Cut Line= 2
      2343035.97      7102699.63      2342469.09      7102398.70
#Sta/Elev= 30
  4605.9  671.97  4705.6  669.49  4738.2  669.19  4760.2  665.66  4772.3  662.90
  4794.9  660.61  4809.8  659.79  4853.8  659.23  4914.1  660.08  4952.4  659.53
  4980.0  657.20  4999.7  654.65  5000.2  654.15  5003.9  654.15  5004.3  654.65
  5010.0  658.00  5018.4  657.51  5032.7  657.94  5046.0  662.70  5055.3  664.88
  5062.3  666.00  5068.0  666.04  5078.0  667.92  5084.3  669.67  5090.0  669.64
  5100.6  670.79  5106.3  672.05  5150.3  673.20  5166.6  674.22  5247.7  674.90
#Mann=3,-1,0
  4605.9    0.05       0  4999.7    0.04       0  5004.3    0.05       0
Bank Sta=4999.7,5004.3
Exp/Cntr=0.3,0.1

Type RM Length L Ch R = 1,411,245,245,245
BEGIN DESCRIPTION:
Mapping XS 46b5f7da
END DESCRIPTION:
XS GIS Cut Line= 2
      2343064.02      7102340.21      2342475.78      7102139.31
#Sta/Elev= 30
  4720.5  668.39  4746.9  666.75  4778.6  659.12  4789.2  658.33  4890.5  656.33
  4927.1  657.07  4937.1  656.26  4947.7  657.82  4968.8  658.14  4979.1  656.32
  4984.4  656.30  4990.0  653.78  4998.2  653.14  4998.7  652.64  5002.8  653.14
  5010.5  656.59  5032.2  656.89  5109.7  655.44  5141.0  656.16  5180.2  654.98
  5190.8  656.46  5198.4  658.84  5229.7  660.50  5235.0  659.49  5261.0  663.89
  5266.3  663.19  5292.4  665.15  5297.6  664.57  5323.7  665.56  5342.1  665.23
#Mann=3,-1,0
  4720.5    0.05       0  4998.2    0.04       0  5002.8    0.05       0
Bank Sta=4998.2,5002.8
Exp/Cntr=0.3,0.1

Type RM Length L Ch R = 1,166,87,87,87
BEGIN DESCRIPTION:
Mapping XS cf46e738
END DESCRIPTION:
XS GIS Cut Line= 3
      2343047.55      7102121.40      2342834.03      7102013.93
      2342516.42      7102062.18
#Sta/Elev= 30
  4776.1  667.07  4813.1  666.97  4819.3  666.73  4829.8  665.36  4835.4  665.94
  4852.2  660.37  4857.8  661.48  4864.0  658.81  4874.5  657.43  4880.1  657.54
  4908.8  656.33  4924.7  656.43  4941.4  657.53  4953.6  657.66  4969.3  657.05
  4986.0  653.95  4991.6  653.75  4996.0  652.74  4996.5  652.24  5000.2  652.24
  5000.7  652.74  5013.9  653.38  5018.7  655.21  5030.3  656.24  5111.3  655.60
  5141.6  656.19  5156.1  656.95  5172.0  658.63  5313.6  658.64  5336.4  659.83
#Mann=3,-1,0
  4776.1    0.05       0  4996.0    0.04       0  5000.7    0.05       0
Bank Sta=4996,5000.7
Exp/Cntr=0.3,0.1

Type RM Length L Ch R = 1,79,0,0,0
BEGIN DESCRIPTION:
Hog Branch Tributary 3_1 1.0
END DESCRIPTION:
XS GIS Cut Line= 3
      2343077.74      7102117.99      2342825.86      7101917.67
      2342563.24      7102004.72
#Sta/Elev= 30
  4704.6  666.80  4752.7  667.01  4802.3  666.32  4823.1  664.51  4837.5  658.56
  4843.9  659.19  4852.0  657.36  4858.3  658.10  4866.4  656.55  4901.6  656.16
  4908.0  655.58  4951.3  657.55  4958.5  656.92  4965.7  655.35  4972.1  655.12
  4980.1  652.71  4992.2  652.14  4992.7  651.64  4996.4  651.64  4996.9  652.14
  5015.3  653.12  5021.2  654.45  5033.7  655.23  5075.8  655.99  5118.2  655.85
  5144.7  658.28  5149.9  657.30  5176.4  658.15  5245.0  658.86  5303.1  658.60
#Mann=3,-1,0
  4704.6    0.05       0  4992.2    0.04       0  4996.9    0.05       0
Bank Sta=4992.2,4996.9
Exp/Cntr=0.3,0.1

Chan Stop Cuts=-1