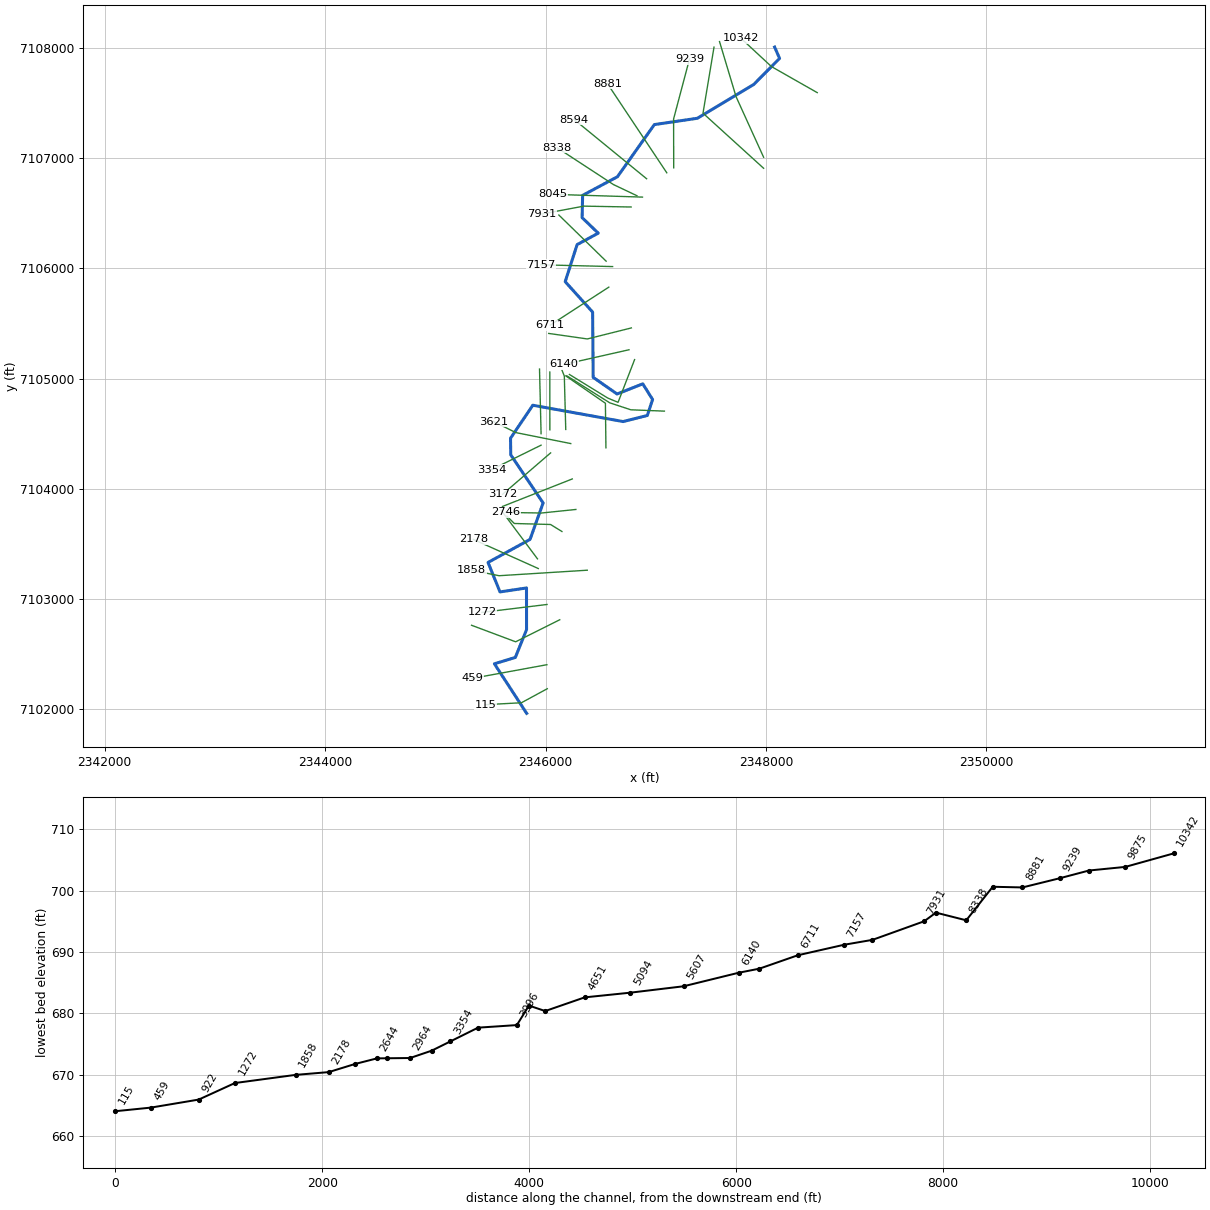
--- Hog Branch Tributary 3_2.prj (project) ---

Proj Title=Hog Branch Tributary 3_2 Base Level Engineering
Current Plan=p01
Default Exp/Contr=0.3,0.1
English Units
Geom File=g01
Flow File=f01
Plan File=p01
BEGIN DESCRIPTION:
Hog Branch Tributary 3_2
END DESCRIPTION:

--- Hog Branch Tributary 3_2.p01 (plan) ---

Plan Title=Multiple Run
Short Identifier=Multiple
Geom File=g01
Flow File=f01
Subcritical Flow
K Sum by GR= 0
Std Step Tol= 0.01
Critical Tol= 0.01
Num of Std Step Trials= 20
Max Error Tol= 0.3
Flow Tol Ratio= 0.001
Split Flow NTrial= 30
Split Flow Tol= 0.02
Split Flow Ratio= 0.02
Log Output Level= 0
Friction Slope Method= 1
Unsteady Friction Slope Method= 2
Unsteady Bridges Friction Slope Method= 1
Parabolic Critical Depth
Global Vel Dist=  1 , 1 , 1
Global Log Level= 0
CheckData=True
Encroach Param= -1, 0, 0, 0
BEGIN DESCRIPTION:
Multiple Run
END DESCRIPTION:

--- Hog Branch Tributary 3_2.f01 (steady flow) ---

Flow Title=Multiple
Number of Profiles=7
Profile Names=10-year,25-year,50-year,1pct_min,100-year,1pct_plu,500-year
River Rch & RM= Hog Branch Tribu,Reach-1,10342
     689     955    1178     721    1439    2872    2154
River Rch & RM= Hog Branch Tribu,Reach-1,8881
     837    1166    1440     882    1760    3512    2638
Boundary for River Rch & Prof#=Hog Branch Tribu,Reach-1,1
Up Type=0
Dn Type=3
Dn Slope=0.005
Boundary for River Rch & Prof#=Hog Branch Tribu,Reach-1,2
Up Type=0
Dn Type=3
Dn Slope=0.005
Boundary for River Rch & Prof#=Hog Branch Tribu,Reach-1,3
Up Type=0
Dn Type=3
Dn Slope=0.005
Boundary for River Rch & Prof#=Hog Branch Tribu,Reach-1,4
Up Type=0
Dn Type=3
Dn Slope=0.005
Boundary for River Rch & Prof#=Hog Branch Tribu,Reach-1,5
Up Type=0
Dn Type=3
Dn Slope=0.005
Boundary for River Rch & Prof#=Hog Branch Tribu,Reach-1,6
Up Type=0
Dn Type=3
Dn Slope=0.005
Boundary for River Rch & Prof#=Hog Branch Tribu,Reach-1,7
Up Type=0
Dn Type=3
Dn Slope=0.005

--- Hog Branch Tributary 3_2.g01 (geometry) ---

Geom Title=Existing Conditions

River Reach=Hog Branch Tribu,Reach-1
Reach XY= 30
      2348079.00      7108010.00      2348123.94      7107907.66
      2347889.08      7107670.44      2347377.45      7107363.75
      2346987.47      7107306.51      2346652.70      7106832.90
      2346336.72      7106663.66      2346332.04      7106461.42
      2346478.54      7106320.52      2346286.68      7106216.52
      2346178.53      7105880.16      2346427.38      7105603.97
      2346432.45      7105011.48      2346649.36      7104860.12
      2346882.66      7104952.33      2346971.47      7104810.01
      2346923.92      7104665.04      2346704.08      7104609.80
      2345884.68      7104758.03      2345682.54      7104458.53
      2345684.45      7104307.55      2345978.24      7103870.69
      2345859.42      7103539.42      2345478.42      7103330.42
      2345586.92      7103062.90      2345827.38      7103098.84
      2345827.94      7102720.44      2345726.08      7102467.92
      2345536.21      7102410.35      2345829.00      7101960.00

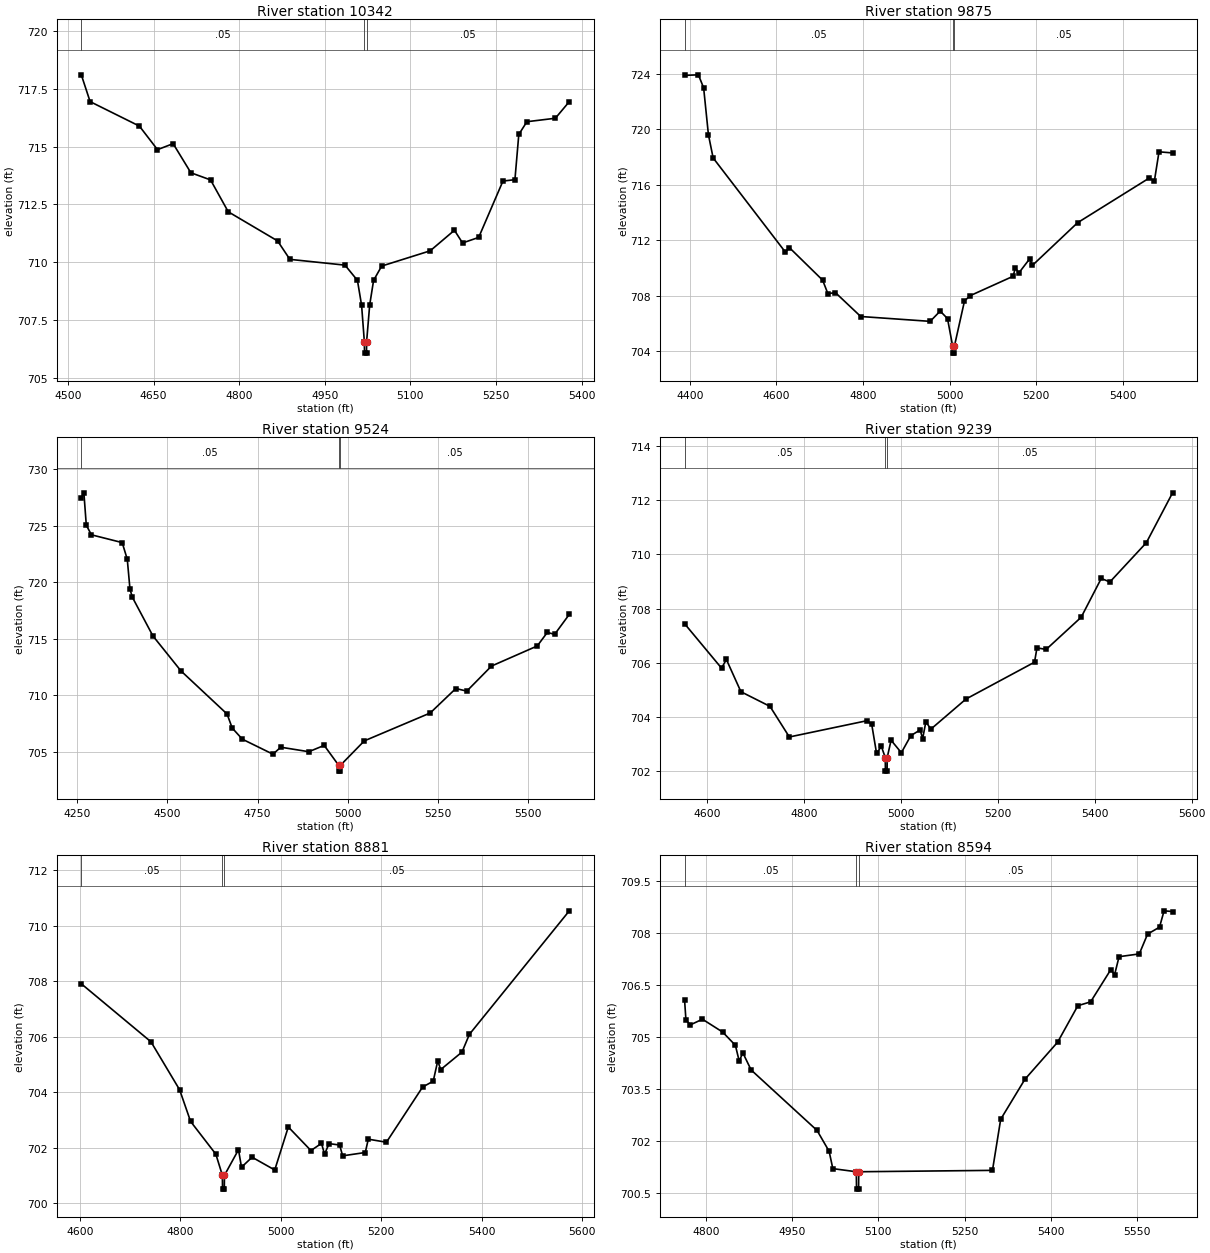
Type RM Length L Ch R = 1,10342,467,467,467
BEGIN DESCRIPTION:
Hog Branch Tributary 3_2 19.0
END DESCRIPTION:
XS GIS Cut Line= 3
      2348465.82      7107596.53      2348050.13      7107833.18
      2347774.01      7108089.67
#Sta/Elev= 30
  4523.3  718.11  4538.7  716.95  4625.1  715.89  4656.8  714.87  4684.2  715.13
  4715.3  713.87  4749.8  713.56  4780.8  712.18  4867.2  710.92  4888.8  710.12
  4985.4  709.87  5007.2  709.21  5014.5  708.13  5019.3  706.56  5019.6  706.06
  5023.1  706.06  5023.3  706.56  5028.7  708.15  5035.5  709.21  5049.7  709.83
  5134.7  710.49  5177.2  711.38  5191.4  710.83  5219.7  711.07  5262.2  713.51
  5283.2  713.57  5290.0  715.53  5304.2  716.08  5354.1  716.23  5378.5  716.95
#Mann=3,-1,0
  4523.3    0.05       0  5019.3   0.033       0  5023.3    0.05       0
Bank Sta=5019.3,5023.3
Exp/Cntr=0.3,0.1

Type RM Length L Ch R = 1,9875,351,351,351
BEGIN DESCRIPTION:
Hog Branch Tributary 3_2 18.0
END DESCRIPTION:
XS GIS Cut Line= 3
      2347979.02      7107009.97      2347729.00      7107560.00
      2347579.00      7108060.00
#Sta/Elev= 30
  4388.2  723.88  4420.1  723.92  4432.2  722.98  4443.2  719.61  4454.1  717.93
  4621.1  711.13  4629.9  711.47  4706.8  709.12  4718.9  708.15  4736.4  708.22
  4794.7  706.50  4955.0  706.15  4978.1  706.89  4995.0  706.35  5006.9  704.36
  5007.2  703.86  5010.7  703.86  5010.9  704.36  5034.2  707.62  5047.2  708.00
  5146.4  709.40  5151.6  710.01  5159.4  709.63  5184.7  710.66  5190.8  710.18
  5295.2  713.26  5459.6  716.46  5472.6  716.30  5483.1  718.37  5514.4  718.29
#Mann=3,-1,0
  4388.2    0.05       0  5006.9    0.04       0  5010.9    0.05       0
Bank Sta=5006.9,5010.9
Exp/Cntr=0.3,0.1

Type RM Length L Ch R = 1,9524,285,285,285
BEGIN DESCRIPTION:
Hog Branch Tributary 3_2 17.0
END DESCRIPTION:
XS GIS Cut Line= 3
      2347978.98      7106910.02      2347429.00      7107410.00
      2347529.01      7108010.05
#Sta/Elev= 30
  4261.9  727.50  4269.0  727.93  4275.7  725.06  4289.9  724.21  4375.1  723.52
  4389.2  722.04  4396.7  719.39  4403.4  718.67  4460.2  715.25  4537.9  712.15
  4665.6  708.33  4679.8  707.09  4707.9  706.10  4792.7  704.77  4814.3  705.39
  4892.0  704.99  4934.6  705.55  4975.1  703.77  4975.4  703.27  4978.9  703.27
  4979.1  703.77  5045.7  705.95  5228.2  708.42  5299.2  710.59  5329.6  710.36
  5398.0  712.58  5524.7  714.36  5552.6  715.56  5572.9  715.39  5613.5  717.16
#Mann=3,-1,0
  4261.9    0.05       0  4975.1    0.04       0  4979.1    0.05       0
Bank Sta=4975.1,4979.1
Exp/Cntr=0.3,0.1

Type RM Length L Ch R = 1,9239,358,358,358
BEGIN DESCRIPTION:
Mapping XS 25a497f7
END DESCRIPTION:
XS GIS Cut Line= 3
      2347163.12      7106913.69      2347162.25      7107357.79
      2347306.56      7107902.29
#Sta/Elev= 30
  4553.2  707.44  4629.5  705.80  4639.5  706.12  4669.5  704.93  4729.5  704.39
  4769.5  703.26  4929.5  703.86  4939.5  703.73  4949.5  702.66  4959.5  702.91
  4967.5  702.50  4967.8  702.00  4971.3  702.00  4971.5  702.50  4979.5  703.14
  5000.7  702.68  5020.3  703.31  5039.5  703.52  5044.7  703.20  5051.3  703.82
  5061.7  703.55  5134.1  704.66  5275.6  706.02  5280.7  706.55  5299.6  706.49
  5372.0  707.68  5413.4  709.11  5431.2  708.98  5506.5  710.43  5560.6  712.27
#Mann=3,-1,0
  4553.2    0.05       0  4967.5   0.033       0  4971.5    0.05       0
Bank Sta=4967.5,4971.5
Exp/Cntr=0.3,0.1

Type RM Length L Ch R = 1,8881,287,287,287
BEGIN DESCRIPTION:
Mapping XS cf65b02e
END DESCRIPTION:
XS GIS Cut Line= 2
      2347100.29      7106868.78      2346562.12      7107677.96
#Sta/Elev= 30
  4603.0  707.91  4741.7  705.82  4798.8  704.09  4820.6  702.95  4870.9  701.77
  4883.9  701.01  4884.2  700.51  4887.7  700.51  4888.1  701.01  4916.0  701.93
  4922.0  701.30  4943.1  701.66  4988.2  701.20  5015.2  702.75  5060.3  701.90
  5081.3  702.16  5087.4  701.77  5096.4  702.15  5117.4  702.10  5123.4  701.71
  5168.5  701.83  5174.5  702.31  5210.6  702.20  5282.7  704.19  5303.8  704.40
  5312.8  705.13  5318.8  704.82  5361.1  705.45  5375.9  706.09  5574.8  710.54
#Mann=3,-1,0
  4603.0    0.05       0  4883.9   0.033       0  4888.1    0.05       0
Bank Sta=4883.9,4888.1
Exp/Cntr=0.3,0.1

Type RM Length L Ch R = 1,8594,256,256,256
BEGIN DESCRIPTION:
Mapping XS f46de8bb
END DESCRIPTION:
XS GIS Cut Line= 2
      2346917.39      7106814.70      2346260.09      7107352.37
#Sta/Elev= 30
  4762.7  706.06  4765.1  705.48  4773.0  705.35  4793.8  705.51  4829.0  705.14
  4851.1  704.76  4857.7  704.31  4864.2  704.54  4878.5  704.05  4993.2  702.31
  5014.2  701.71  5020.7  701.21  5061.6  701.12  5061.9  700.62  5065.5  700.62
  5065.8  701.12  5298.5  701.16  5312.8  702.63  5354.9  703.78  5411.9  704.85
  5447.1  705.90  5469.3  706.01  5504.5  706.94  5511.0  706.79  5518.8  707.31
  5554.0  707.39  5568.4  707.96  5589.2  708.16  5597.1  708.63  5611.9  708.61
#Mann=3,-1,0
  4762.7    0.05       0  5061.6   0.033       0  5065.8    0.05       0
Bank Sta=5061.6,5065.8
Exp/Cntr=0.3,0.1

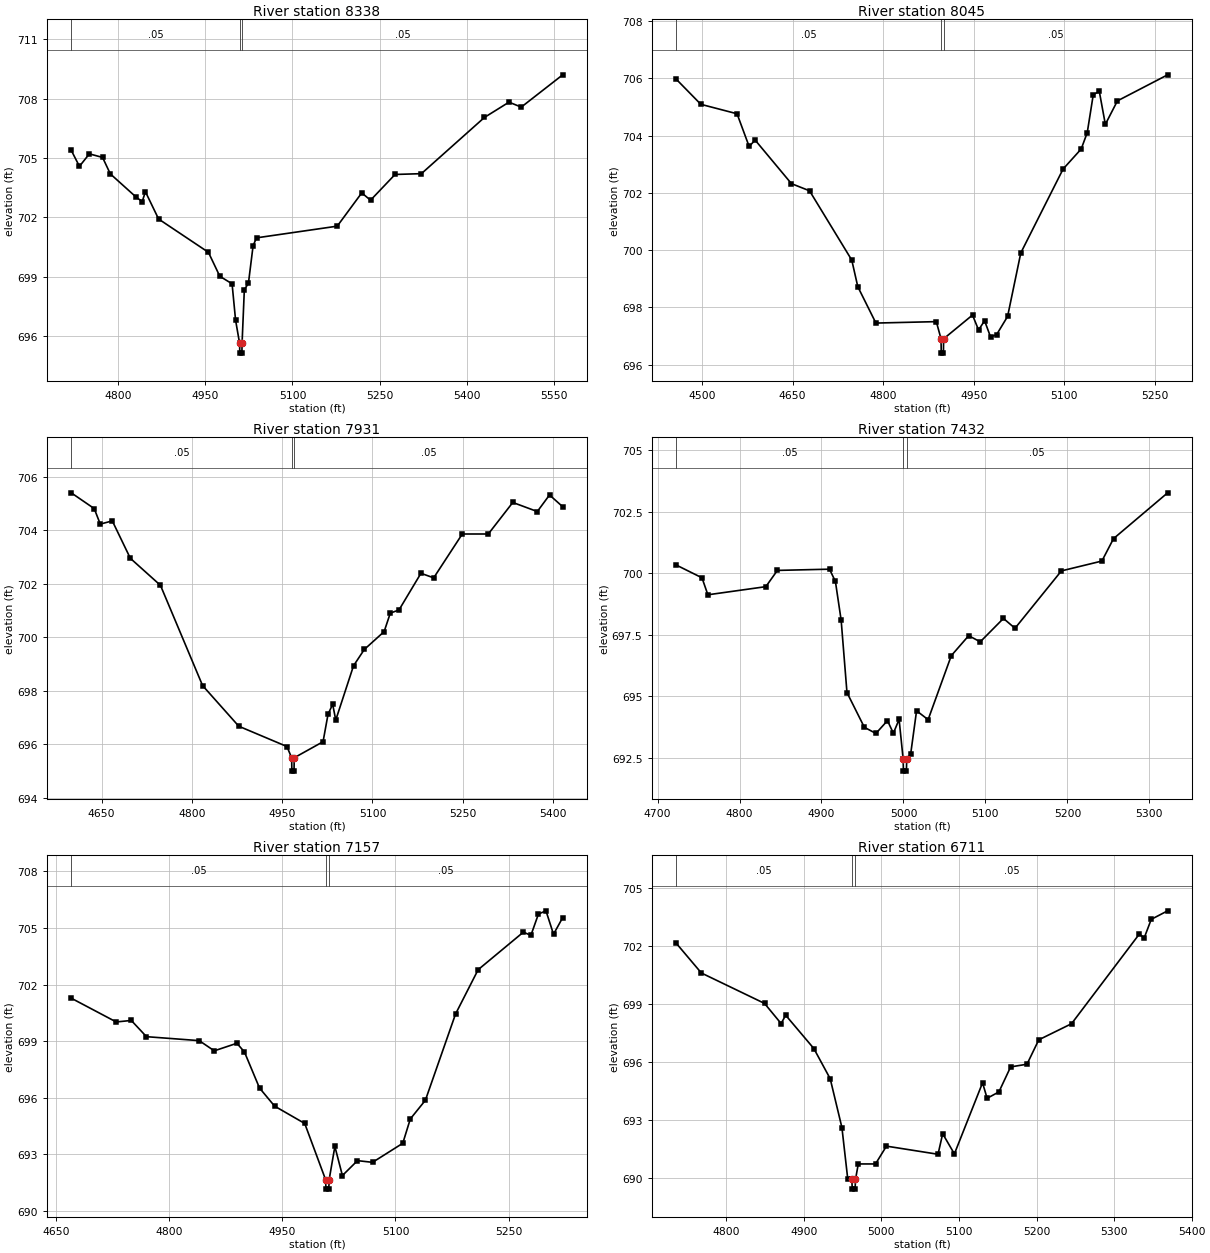
Type RM Length L Ch R = 1,8338,293,293,293
BEGIN DESCRIPTION:
Mapping XS 7a98e677
END DESCRIPTION:
XS GIS Cut Line= 3
      2346829.70      7106660.39      2346616.57      7106761.79
      2346106.58      7107095.52
#Sta/Elev= 30
  4719.4  705.39  4733.5  704.58  4750.6  705.21  4773.3  705.03  4786.6  704.20
  4830.9  703.03  4841.5  702.80  4847.0  703.30  4869.7  701.92  4955.4  700.24
  4975.0  699.03  4996.1  698.65  5002.1  696.82  5009.0  695.65  5009.4  695.15
  5013.0  695.15  5013.3  695.65  5017.2  698.36  5024.2  698.67  5032.3  700.58
  5038.2  700.97  5177.0  701.56  5219.2  703.24  5234.3  702.87  5276.5  704.17
  5321.8  704.21  5430.3  707.05  5472.5  707.82  5493.6  707.57  5564.9  709.20
#Mann=3,-1,0
  4719.4    0.05       0  5009.0   0.033       0  5013.3    0.05       0
Bank Sta=5009,5013.3
Exp/Cntr=0.3,0.1

Type RM Length L Ch R = 1,8045,114,114,114
BEGIN DESCRIPTION:
Mapping XS 8101c31a
END DESCRIPTION:
XS GIS Cut Line= 2
      2346879.87      7106648.01      2346065.86      7106673.06
#Sta/Elev= 30
  4457.0  705.97  4497.9  705.09  4557.9  704.76  4577.9  703.62  4587.9  703.84
  4648.0  702.32  4678.0  702.07  4748.0  699.65  4758.0  698.72  4788.0  697.45
  4888.1  697.50  4895.9  696.90  4896.3  696.40  4899.9  696.40  4900.2  696.90
  4948.1  697.73  4958.1  697.21  4968.1  697.53  4978.1  696.96  4988.1  697.05
  5006.2  697.68  5028.1  699.90  5098.2  702.83  5128.2  703.53  5138.2  704.10
  5148.2  705.43  5158.2  705.54  5168.2  704.39  5188.2  705.21  5271.4  706.12
#Mann=3,-1,0
  4457.0    0.05       0  4895.9   0.033       0  4900.2    0.05       0
Bank Sta=4895.9,4900.2
Exp/Cntr=0.3,0.1

Type RM Length L Ch R = 1,7931,499,499,499
BEGIN DESCRIPTION:
Mapping XS f054688b
END DESCRIPTION:
XS GIS Cut Line= 3
      2346777.20      7106558.06      2346347.43      7106565.99
      2345967.51      7106494.70
#Sta/Elev= 30
  4599.6  705.40  4637.8  704.81  4647.8  704.23  4667.8  704.35  4697.8  702.95
  4747.8  701.94  4817.8  698.19  4877.9  696.67  4957.9  695.91  4965.7  695.49
  4966.1  694.99  4969.7  694.99  4970.0  695.49  5017.9  696.09  5026.2  697.12
  5033.9  697.49  5039.0  696.90  5068.5  698.93  5086.4  699.54  5119.4  700.21
  5129.6  700.90  5144.1  701.02  5180.5  702.39  5201.7  702.22  5249.2  703.86
  5292.4  703.86  5333.1  705.04  5373.8  704.70  5394.1  705.32  5416.0  704.88
#Mann=3,-1,0
  4599.6    0.05       0  4965.7   0.033       0  4970.0    0.05       0
Bank Sta=4965.7,4970
Exp/Cntr=0.3,0.1

Type RM Length L Ch R = 1,7432,275,275,275
BEGIN DESCRIPTION:
Mapping XS d6307cbd
END DESCRIPTION:
XS GIS Cut Line= 2
      2346549.90      7106066.25      2346120.99      7106485.24
#Sta/Elev= 30
  4722.7  700.33  4754.2  699.81  4761.4  699.12  4832.1  699.45  4846.2  700.11
  4909.8  700.16  4917.0  699.66  4924.0  698.09  4931.1  695.15  4952.3  693.74
  4966.4  693.49  4980.5  694.01  4987.7  693.50  4994.7  694.06  4999.6  692.46
  5000.0  691.96  5003.6  691.96  5004.0  692.46  5008.8  692.65  5016.0  694.41
  5030.1  694.05  5058.4  696.65  5079.6  697.46  5093.7  697.21  5122.0  698.16
  5136.1  697.76  5192.7  700.09  5242.1  700.49  5256.3  701.40  5322.3  703.26
#Mann=3,-1,0
  4722.7    0.05       0  4999.6   0.033       0  5004.0    0.05       0
Bank Sta=4999.6,5004
Exp/Cntr=0.3,0.1

Type RM Length L Ch R = 1,7157,446,446,446
BEGIN DESCRIPTION:
Mapping XS 7af96461
END DESCRIPTION:
XS GIS Cut Line= 2
      2346608.72      7106017.14      2345956.82      7106033.29
#Sta/Elev= 30
  4669.8  701.28  4729.5  700.02  4749.5  700.10  4769.6  699.24  4839.6  699.03
  4859.6  698.49  4889.6  698.89  4899.6  698.43  4919.6  696.52  4939.6  695.56
  4979.6  694.64  5007.3  691.66  5007.8  691.16  5011.5  691.16  5012.0  691.66
  5019.6  693.42  5029.6  691.88  5049.6  692.67  5069.6  692.58  5109.7  693.59
  5119.7  694.88  5139.7  695.87  5179.7  700.44  5209.7  702.79  5269.7  704.78
  5279.7  704.61  5289.7  705.74  5299.7  705.91  5309.7  704.67  5321.9  705.55
#Mann=3,-1,0
  4669.8    0.05       0  5007.3   0.033       0  5012.0    0.05       0
Bank Sta=5007.3,5012
Exp/Cntr=0.3,0.1

Type RM Length L Ch R = 1,6711,372,372,372
BEGIN DESCRIPTION:
Mapping XS 49bb3bcd
END DESCRIPTION:
XS GIS Cut Line= 2
      2346574.52      7105830.58      2346043.11      7105485.54
#Sta/Elev= 30
  4735.4  702.15  4767.9  700.61  4849.3  699.04  4870.7  698.00  4876.6  698.43
  4912.9  696.71  4934.0  695.15  4949.1  692.63  4956.6  689.98  4961.9  689.95
  4962.4  689.45  4966.1  689.45  4966.6  689.95  4970.2  690.75  4992.4  690.75
  5006.5  691.67  5073.0  691.25  5079.0  692.31  5094.1  691.27  5130.4  694.94
  5136.3  694.14  5151.5  694.47  5166.6  695.76  5187.7  695.90  5202.9  697.16
  5245.1  697.99  5332.7  702.63  5338.7  702.41  5347.9  703.38  5369.0  703.82
#Mann=3,-1,0
  4735.4    0.05       0  4961.9   0.033       0  4966.6    0.05       0
Bank Sta=4961.9,4966.6
Exp/Cntr=0.3,0.1

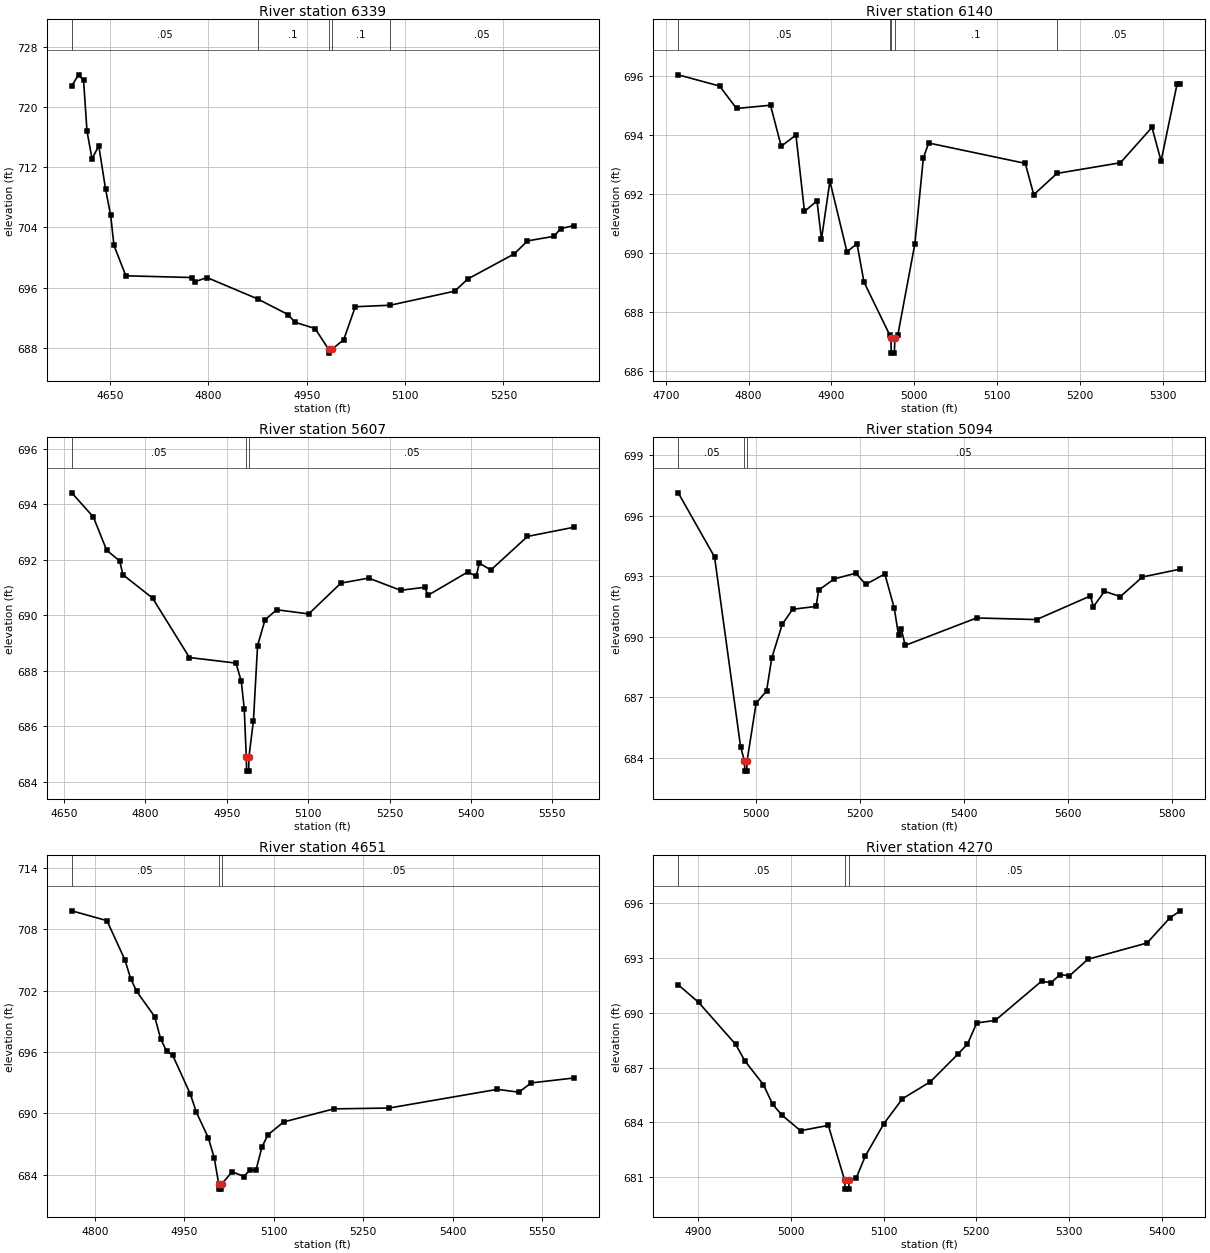
Type RM Length L Ch R = 1,6339,199,199,199
BEGIN DESCRIPTION:
Hog Branch Tributary 3_2 10.0
END DESCRIPTION:
XS GIS Cut Line= 3
      2346779.00      7105460.00      2346379.00      7105360.00
      2346028.97      7105410.00
#Sta/Elev= 30
  4591.6  722.87  4601.9  724.33  4609.6  723.58  4614.8  716.85  4622.5  713.14
  4632.8  714.87  4643.1  709.14  4650.9  705.62  4656.0  701.60  4674.1  697.56
  4774.6  697.33  4779.7  696.77  4797.8  697.33  4875.1  694.48  4921.5  692.40
  4931.8  691.38  4962.7  690.54  4983.5  687.76  4984.0  687.26  4988.3  687.76
  5006.4  689.04  5024.1  693.44  5077.3  693.64  5175.6  695.51  5195.8  697.14
  5266.6  700.48  5286.8  702.21  5327.2  702.82  5337.3  703.84  5357.5  704.25
#Mann=5,-1,0
  4591.6    0.05       0  4875.1     0.1       0  4983.5    0.07       0
  4988.3     0.1       0  5077.3    0.05       0
Bank Sta=4983.5,4988.3
Exp/Cntr=0.3,0.1

Type RM Length L Ch R = 1,6140,533,533,533
BEGIN DESCRIPTION:
Mapping XS fb4ba8fb
END DESCRIPTION:
XS GIS Cut Line= 2
      2346757.66      7105261.79      2346166.41      7105128.43
#Sta/Elev= 30
  4715.1  696.03  4765.0  695.65  4785.5  694.89  4826.5  695.00  4839.4  693.61
  4857.2  693.99  4867.5  691.40  4882.6  691.76  4888.0  690.46  4898.2  692.43
  4918.8  690.03  4930.9  690.31  4939.3  689.01  4970.3  687.22  4971.8  687.10
  4972.3  686.60  4976.0  686.60  4976.6  687.10  4980.3  687.23  5000.8  690.31
  5011.0  693.21  5017.4  693.72  5134.0  693.03  5144.3  691.97  5172.3  692.69
  5248.9  693.05  5287.0  694.25  5298.0  693.11  5317.3  695.72  5321.2  695.72
#Mann=5,-1,0
  4715.1    0.05       0  4970.3     0.1       0  4971.8    0.07       0
  4976.6     0.1       0  5172.3    0.05       0
Bank Sta=4971.8,4976.6
Exp/Cntr=0.3,0.1

Type RM Length L Ch R = 1,5607,513,513,513
BEGIN DESCRIPTION:
Mapping XS de6636bd
END DESCRIPTION:
XS GIS Cut Line= 4
      2346808.23      7105172.37      2346658.40      7104784.45
      2346564.73      7104823.17      2346217.05      7105037.24
#Sta/Elev= 30
  4664.2  694.41  4704.0  693.54  4728.6  692.34  4752.5  691.96  4758.5  691.46
  4813.1  690.62  4881.1  688.48  4966.9  688.28  4976.7  687.62  4982.1  686.64
  4985.9  684.89  4986.5  684.39  4990.2  684.39  4990.7  684.89  4999.1  686.21
  5006.7  688.91  5020.5  689.84  5042.0  690.20  5101.0  690.05  5160.3  691.16
  5211.6  691.34  5270.3  690.90  5314.9  691.01  5320.8  690.72  5394.2  691.56
  5409.6  691.41  5415.5  691.88  5436.7  691.63  5504.2  692.84  5589.7  693.17
#Mann=3,-1,0
  4664.2    0.05       0  4985.9   0.033       0  4990.7    0.05       0
Bank Sta=4985.9,4990.7
Exp/Cntr=0.3,0.1

Type RM Length L Ch R = 1,5094,443,443,443
BEGIN DESCRIPTION:
Mapping XS b3bc277f
END DESCRIPTION:
XS GIS Cut Line= 4
      2347078.81      7104704.55      2346774.26      7104716.55
      2346582.71      7104780.09      2346193.93      7105024.82
#Sta/Elev= 30
  4850.3  697.14  4920.2  693.96  4970.2  684.57  4977.7  683.85  4978.4  683.35
  4982.1  683.35  4982.7  683.85  5000.2  686.72  5020.2  687.32  5030.3  688.96
  5050.3  690.62  5070.3  691.37  5115.5  691.51  5120.5  692.32  5150.2  692.87
  5192.2  693.16  5210.9  692.60  5247.8  693.12  5266.0  691.42  5274.2  690.08
  5279.5  690.37  5287.1  689.58  5424.4  690.94  5539.7  690.86  5643.3  692.03
  5649.2  691.50  5670.4  692.26  5701.0  692.00  5743.4  692.97  5816.3  693.36
#Mann=3,-1,0
  4850.3    0.05       0  4977.7   0.033       0  4982.7    0.05       0
Bank Sta=4977.7,4982.7
Exp/Cntr=0.3,0.1

Type RM Length L Ch R = 1,4651,381,381,381
BEGIN DESCRIPTION:
Mapping XS be3c4796
END DESCRIPTION:
XS GIS Cut Line= 3
      2346548.20      7104371.04      2346543.43      7104776.17
      2346183.87      7105024.60
#Sta/Elev= 30
  4761.3  709.80  4820.3  708.84  4850.3  705.02  4860.3  703.14  4870.3  701.91
  4900.3  699.46  4910.3  697.31  4920.3  696.06  4930.3  695.71  4960.3  691.86
  4970.3  690.10  4990.3  687.61  5000.3  685.63  5007.8  683.08  5008.4  682.58
  5012.1  682.58  5012.8  683.08  5030.3  684.28  5050.3  683.81  5060.3  684.49
  5070.3  684.43  5080.3  686.70  5090.3  687.89  5116.7  689.15  5200.9  690.43
  5293.5  690.51  5475.3  692.34  5511.2  692.06  5532.1  692.97  5603.5  693.45
#Mann=3,-1,0
  4761.3    0.05       0  5007.8   0.033       0  5012.8    0.05       0
Bank Sta=5007.8,5012.8
Exp/Cntr=0.3,0.1

Type RM Length L Ch R = 1,4270,157,157,157
BEGIN DESCRIPTION:
Mapping XS 3825e7ff
END DESCRIPTION:
XS GIS Cut Line= 3
      2346183.56      7104538.14      2346170.58      7105022.86
      2346149.82      7105075.63
#Sta/Elev= 30
  4878.5  691.54  4900.4  690.58  4940.4  688.28  4950.4  687.37  4970.4  686.07
  4980.4  684.99  4990.4  684.40  5010.4  683.55  5040.4  683.84  5057.9  680.85
  5058.6  680.35  5062.3  680.35  5062.9  680.85  5070.4  680.95  5080.4  682.17
  5100.4  683.94  5120.4  685.30  5150.5  686.23  5180.5  687.76  5190.5  688.29
  5200.5  689.45  5220.5  689.59  5270.5  691.74  5280.5  691.65  5290.5  692.10
  5300.5  692.03  5320.5  692.94  5384.3  693.83  5408.7  695.20  5420.1  695.59
#Mann=3,-1,0
  4878.5    0.05       0  5057.9   0.033       0  5062.9    0.05       0
Bank Sta=5057.9,5062.9
Exp/Cntr=0.3,0.1

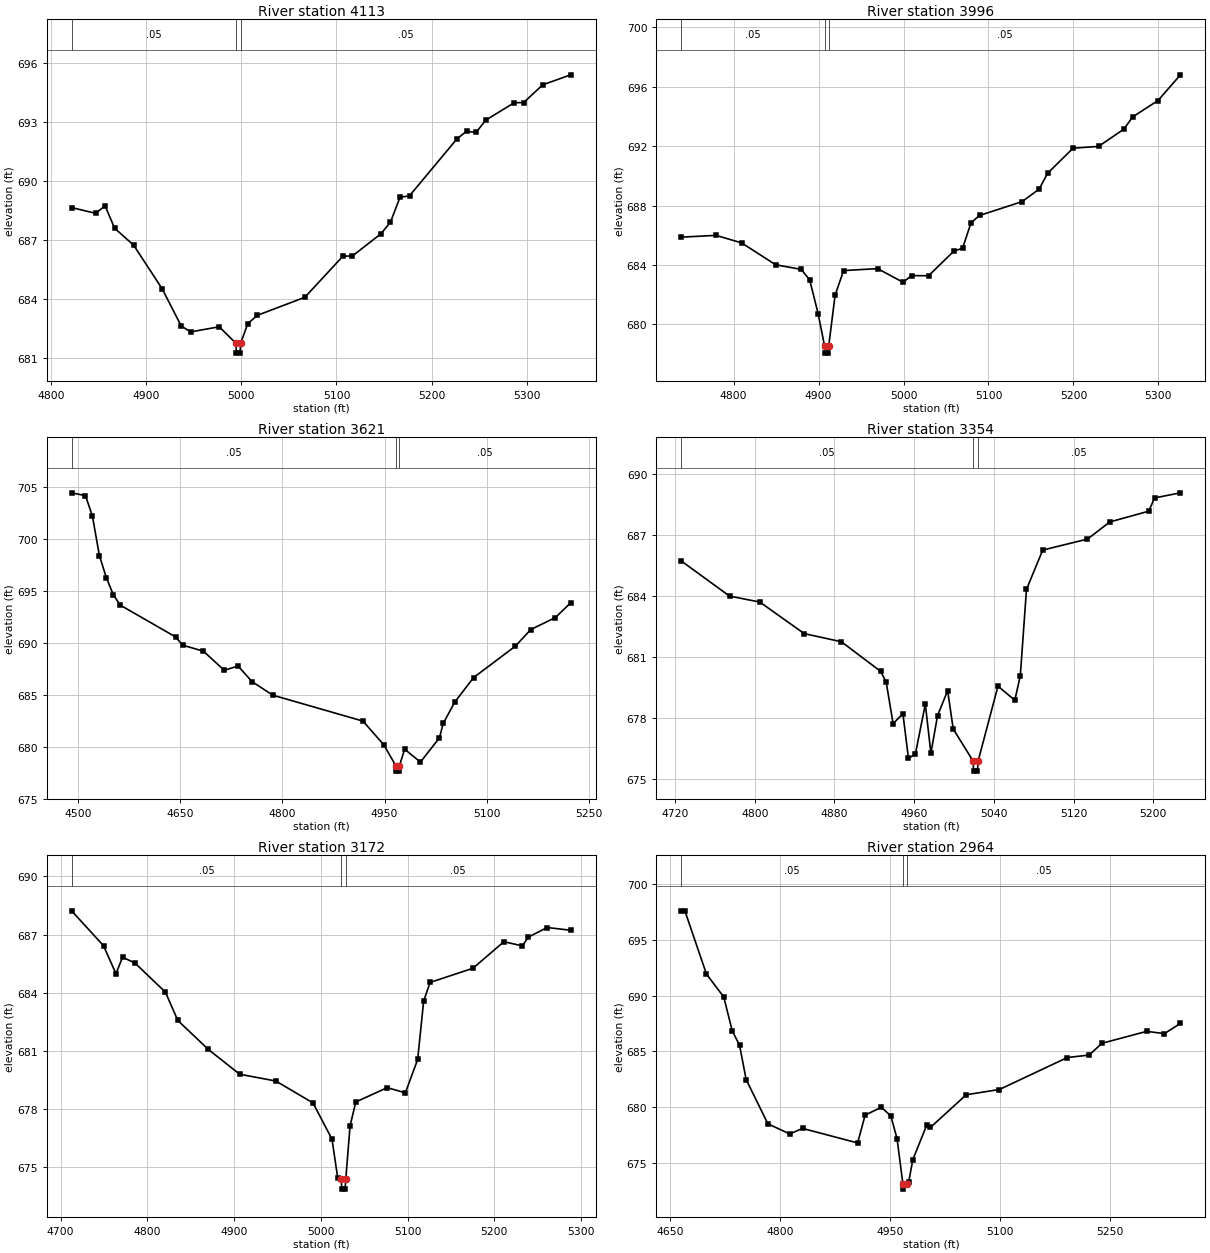
Type RM Length L Ch R = 1,4113,117,117,117
BEGIN DESCRIPTION:
Mapping XS 95287749
END DESCRIPTION:
XS GIS Cut Line= 2
      2346039.41      7104534.81      2346039.07      7105059.41
#Sta/Elev= 30
  4821.6  688.64  4846.8  688.35  4856.8  688.73  4866.8  687.59  4886.8  686.73
  4916.8  684.51  4936.8  682.62  4946.8  682.32  4976.8  682.58  4994.3  681.74
  4994.9  681.24  4998.6  681.24  4999.3  681.74  5006.8  682.74  5016.8  683.16
  5066.8  684.08  5106.8  686.17  5116.8  686.18  5146.8  687.31  5156.8  687.90
  5166.8  689.16  5176.8  689.24  5226.8  692.14  5236.8  692.52  5246.8  692.46
  5256.8  693.08  5286.8  693.97  5296.8  693.98  5316.8  694.88  5346.2  695.39
#Mann=3,-1,0
  4821.6    0.05       0  4994.3   0.033       0  4999.3    0.05       0
Bank Sta=4994.3,4999.3
Exp/Cntr=0.3,0.1

Type RM Length L Ch R = 1,3996,375,375,375
BEGIN DESCRIPTION:
Mapping XS 5dbce7c5
END DESCRIPTION:
XS GIS Cut Line= 2
      2345959.72      7104499.17      2345945.56      7105086.40
#Sta/Elev= 30
  4738.6  685.87  4779.4  685.99  4809.5  685.48  4849.5  684.01  4879.5  683.70
  4889.5  683.00  4899.5  680.72  4907.0  678.56  4907.6  678.06  4911.4  678.06
  4912.0  678.56  4919.5  681.97  4929.5  683.62  4969.5  683.75  4999.5  682.83
  5009.5  683.28  5029.5  683.27  5059.5  684.94  5069.5  685.12  5079.5  686.84
  5089.5  687.33  5139.5  688.26  5159.6  689.10  5169.6  690.17  5199.6  691.86
  5229.6  691.98  5259.6  693.15  5269.6  693.96  5299.6  695.07  5326.0  696.80
#Mann=3,-1,0
  4738.6    0.05       0  4907.0   0.033       0  4912.0    0.05       0
Bank Sta=4907,4912
Exp/Cntr=0.3,0.1

Type RM Length L Ch R = 1,3621,267,267,267
BEGIN DESCRIPTION:
Hog Branch Tributary 3_2 8.0
END DESCRIPTION:
XS GIS Cut Line= 3
      2346228.97      7104410.01      2345729.00      7104510.00
      2345528.98      7104610.01
#Sta/Elev= 30
  4490.1  704.46  4510.5  704.19  4520.7  702.21  4530.9  698.42  4541.1  696.29
  4551.3  694.65  4561.5  693.64  4643.0  690.57  4653.2  689.78  4683.8  689.20
  4714.4  687.36  4734.8  687.77  4755.2  686.27  4785.8  684.96  4918.4  682.46
  4949.0  680.17  4966.8  678.14  4967.5  677.64  4971.3  677.64  4971.9  678.14
  4979.6  679.75  5002.8  678.51  5030.7  680.85  5036.3  682.23  5053.1  684.28
  5081.0  686.66  5142.5  689.69  5164.9  691.28  5201.2  692.44  5223.6  693.86
#Mann=3,-1,0
  4490.1    0.05       0  4966.8   0.033       0  4971.9    0.05       0
Bank Sta=4966.8,4971.9
Exp/Cntr=0.3,0.1

Type RM Length L Ch R = 1,3354,182,182,182
BEGIN DESCRIPTION:
Mapping XS d026c44d
END DESCRIPTION:
XS GIS Cut Line= 2
      2345959.45      7104395.29      2345510.52      7104173.57
#Sta/Elev= 30
  4726.5  685.71  4774.8  683.99  4805.1  683.70  4849.7  682.15  4887.0  681.75
  4926.3  680.30  4931.9  679.78  4938.9  677.73  4948.7  678.22  4954.3  676.03
  4961.2  676.23  4971.2  678.69  4976.8  676.28  4983.5  678.13  4993.6  679.35
  4999.2  677.47  5019.1  675.90  5019.7  675.40  5023.5  675.40  5024.2  675.90
  5044.1  679.57  5061.0  678.88  5066.5  680.08  5072.7  684.32  5089.0  686.25
  5133.9  686.79  5156.3  687.63  5195.4  688.16  5201.2  688.81  5227.2  689.06
#Mann=3,-1,0
  4726.5    0.05       0  5019.1   0.033       0  5024.2    0.05       0
Bank Sta=5019.1,5024.2
Exp/Cntr=0.3,0.1

Type RM Length L Ch R = 1,3172,208,208,208
BEGIN DESCRIPTION:
Mapping XS 570176df
END DESCRIPTION:
XS GIS Cut Line= 2
      2346046.22      7104325.31      2345610.76      7103949.66
#Sta/Elev= 30
  4712.8  688.22  4749.6  686.42  4763.9  684.98  4771.5  685.83  4785.8  685.53
  4820.9  684.03  4835.2  682.57  4870.3  681.08  4906.5  679.80  4948.2  679.45
  4991.0  678.32  5012.9  676.45  5019.5  674.44  5023.5  674.38  5024.2  673.88
  5028.0  673.88  5028.7  674.38  5033.7  677.14  5040.3  678.37  5076.5  679.11
  5097.4  678.84  5111.6  680.56  5118.5  683.57  5125.9  684.53  5175.3  685.26
  5211.0  686.63  5232.3  686.41  5238.9  686.86  5260.8  687.36  5287.9  687.22
#Mann=3,-1,0
  4712.8    0.05       0  5023.5   0.033       0  5028.7    0.05       0
Bank Sta=5023.5,5028.7
Exp/Cntr=0.3,0.1

Type RM Length L Ch R = 1,2964,218,218,218
BEGIN DESCRIPTION:
Mapping XS 70fc21a4
END DESCRIPTION:
XS GIS Cut Line= 2
      2346242.78      7104088.70      2345609.17      7103838.83
#Sta/Elev= 30
  4665.7  697.58  4670.4  697.58  4699.8  691.93  4723.5  689.87  4735.0  686.85
  4745.0  685.57  4754.0  682.49  4783.7  678.53  4813.5  677.63  4831.0  678.12
  4906.2  676.82  4916.4  679.31  4938.5  680.01  4951.5  679.24  4960.0  677.20
  4967.9  673.19  4968.6  672.69  4973.1  673.19  4975.9  673.34  4981.5  675.32
  5000.3  678.39  5005.6  678.21  5054.4  681.13  5099.7  681.60  5192.4  684.46
  5222.2  684.68  5239.5  685.73  5300.7  686.80  5325.0  686.60  5346.8  687.52
#Mann=3,-1,0
  4665.7    0.05       0  4967.9   0.033       0  4973.1    0.05       0
Bank Sta=4967.9,4973.1
Exp/Cntr=0.3,0.1

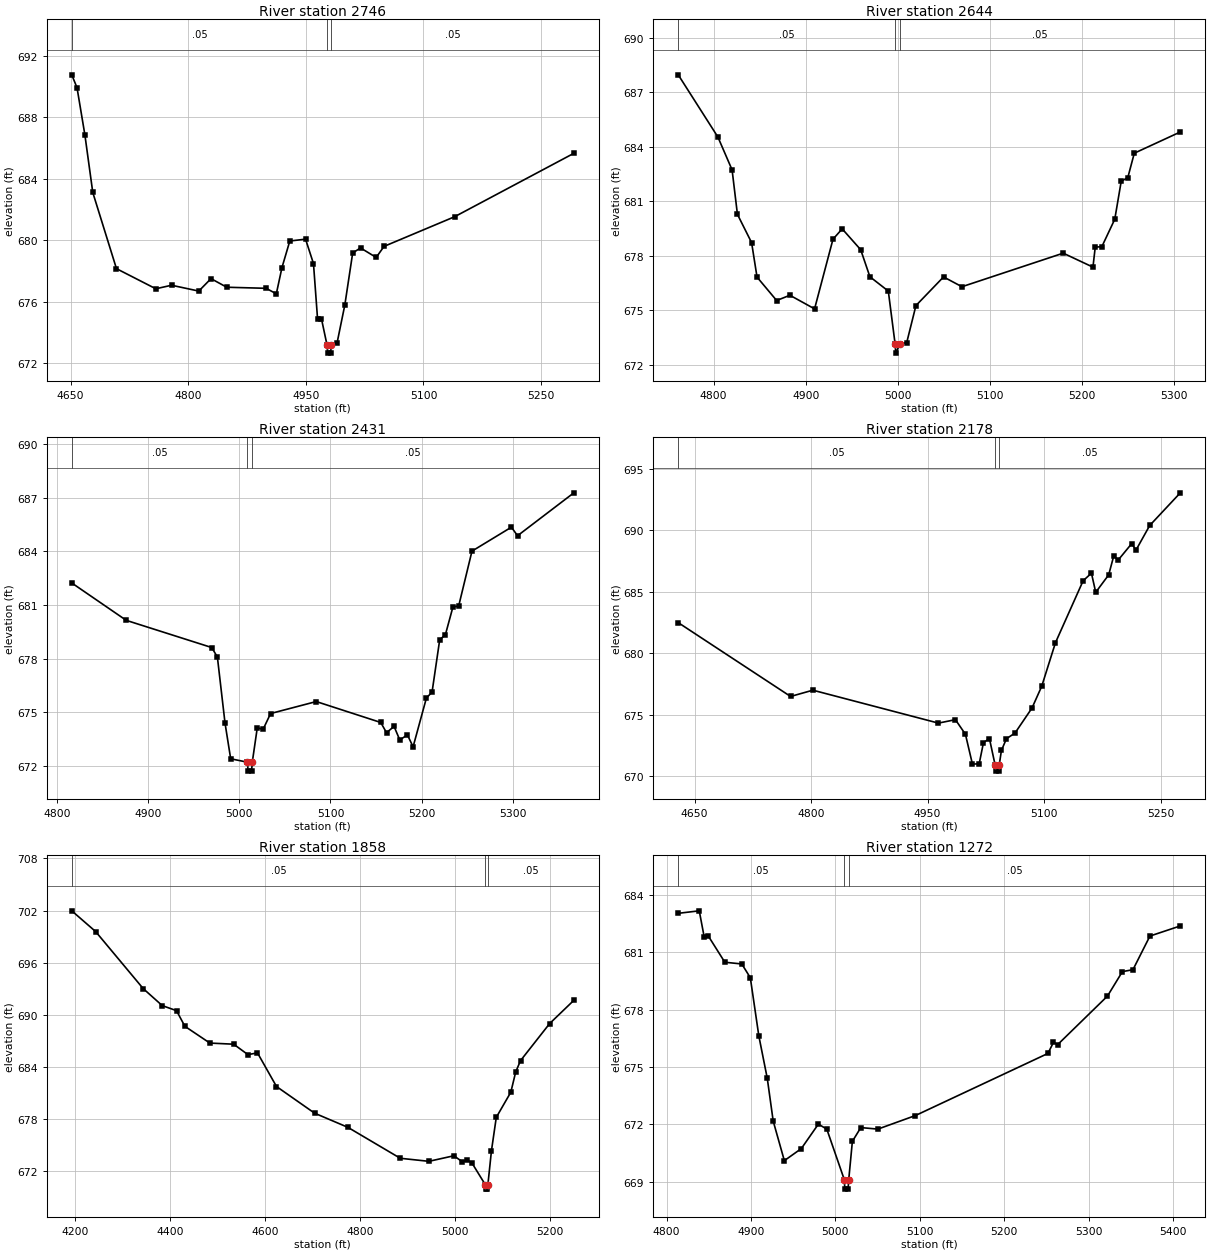
Type RM Length L Ch R = 1,2746,102,102,102
BEGIN DESCRIPTION:
Mapping XS 19f90395
END DESCRIPTION:
XS GIS Cut Line= 3
      2346275.66      7103811.59      2345963.62      7103779.36
      2345636.96      7103784.62
#Sta/Elev= 30
  4651.4  690.77  4658.1  689.93  4668.1  686.87  4678.2  683.11  4708.4  678.15
  4758.6  676.84  4778.7  677.07  4813.4  676.69  4829.0  677.50  4849.1  676.94
  4899.4  676.87  4912.3  676.51  4919.5  678.22  4929.5  679.95  4949.6  680.07
  4959.7  678.48  4964.9  674.88  4969.9  674.88  4977.1  673.15  4977.8  672.65
  4981.6  672.65  4982.3  673.15  4989.7  673.29  4999.7  675.79  5009.7  679.17
  5019.7  679.50  5039.7  678.88  5049.7  679.60  5139.7  681.53  5291.8  685.66
#Mann=3,-1,0
  4651.4    0.05       0  4977.1   0.033       0  4982.3    0.05       0
Bank Sta=4977.1,4982.3
Exp/Cntr=0.3,0.1

Type RM Length L Ch R = 1,2644,213,213,213
BEGIN DESCRIPTION:
Mapping XS 0c8668d6
END DESCRIPTION:
XS GIS Cut Line= 4
      2346149.08      7103611.44      2346045.68      7103675.13
      2345716.76      7103684.26      2345649.31      7103751.03
#Sta/Elev= 30
  4761.6  687.97  4804.7  684.54  4820.1  682.73  4825.9  680.28  4841.3  678.72
  4847.2  676.82  4868.5  675.53  4882.9  675.82  4909.7  675.07  4929.7  678.91
  4939.7  679.48  4959.8  678.33  4969.8  676.84  4989.8  676.05  4997.2  673.13
  4997.9  672.63  5002.4  673.13  5009.8  673.21  5019.8  675.25  5049.8  676.83
  5069.8  676.29  5179.8  678.14  5212.1  677.37  5214.6  678.48  5221.7  678.49
  5235.8  680.01  5242.8  682.10  5250.0  682.31  5257.0  683.65  5307.0  684.82
#Mann=3,-1,0
  4761.6    0.05       0  4997.2   0.033       0  5002.4    0.05       0
Bank Sta=4997.2,5002.4
Exp/Cntr=0.3,0.1

Type RM Length L Ch R = 1,2431,253,253,253
BEGIN DESCRIPTION:
Mapping XS c407b3b6
END DESCRIPTION:
XS GIS Cut Line= 2
      2345926.97      7103363.39      2345597.36      7103804.93
#Sta/Elev= 30
  4816.1  682.23  4875.9  680.14  4969.7  678.62  4975.9  678.09  4984.3  674.39
  4990.5  672.40  5008.9  672.21  5009.6  671.71  5013.4  671.71  5014.2  672.21
  5019.7  674.14  5026.0  674.04  5034.3  674.93  5084.4  675.60  5155.2  674.43
  5161.5  673.86  5169.8  674.21  5176.1  673.45  5184.4  673.74  5190.7  673.07
  5205.3  675.80  5211.5  676.13  5219.9  679.06  5226.1  679.33  5234.4  680.89
  5240.7  680.94  5255.3  684.01  5298.6  685.35  5305.3  684.87  5367.1  687.27
#Mann=3,-1,0
  4816.1    0.05       0  5008.9   0.033       0  5014.2    0.05       0
Bank Sta=5008.9,5014.2
Exp/Cntr=0.3,0.1

Type RM Length L Ch R = 1,2178,320,320,320
BEGIN DESCRIPTION:
Mapping XS 77b9adb0
END DESCRIPTION:
XS GIS Cut Line= 2
      2345934.54      7103275.16      2345344.84      7103539.65
#Sta/Elev= 30
  4629.0  682.48  4773.6  676.47  4802.3  676.98  4963.9  674.30  4985.8  674.58
  4998.7  673.39  5007.7  670.96  5016.4  670.99  5021.9  672.71  5029.6  673.04
  5036.9  670.89  5037.7  670.39  5041.5  670.39  5042.2  670.89  5045.0  672.07
  5051.5  673.03  5062.5  673.49  5084.4  675.53  5096.9  677.30  5114.6  680.85
  5150.2  685.89  5160.9  686.51  5166.4  684.95  5183.1  686.37  5189.6  687.91
  5195.1  687.56  5212.8  688.92  5218.2  688.38  5235.9  690.39  5275.3  693.05
#Mann=3,-1,0
  4629.0    0.05       0  5036.9   0.033       0  5042.2    0.05       0
Bank Sta=5036.9,5042.2
Exp/Cntr=0.3,0.1

Type RM Length L Ch R = 1,1858,586,586,586
BEGIN DESCRIPTION:
Hog Branch Tributary 3_2 4.0
END DESCRIPTION:
XS GIS Cut Line= 3
      2346378.99      7103260.00      2345579.00      7103210.00
      2345329.00      7103260.00
#Sta/Elev= 30
  4193.6  701.97  4243.7  699.59  4343.9  693.02  4384.0  691.06  4414.0  690.48
  4431.6  688.68  4484.2  686.75  4534.3  686.62  4564.3  685.42  4584.4  685.62
  4624.4  681.75  4704.6  678.68  4774.7  677.05  4884.9  673.49  4945.1  673.14
  4997.7  673.78  5015.5  673.08  5025.7  673.29  5035.9  672.93  5063.9  670.44
  5064.6  669.94  5068.4  669.94  5069.2  670.44  5076.7  674.35  5086.9  678.20
  5117.5  681.10  5127.7  683.42  5137.9  684.73  5199.1  688.99  5250.1  691.67
#Mann=3,-1,0
  4193.6    0.05       0  5063.9   0.033       0  5069.2    0.05       0
Bank Sta=5063.9,5069.2
Exp/Cntr=0.3,0.1

Type RM Length L Ch R = 1,1272,350,350,350
BEGIN DESCRIPTION:
Mapping XS dfd424b6
END DESCRIPTION:
XS GIS Cut Line= 2
      2346013.76      7102948.82      2345423.31      7102877.04
#Sta/Elev= 30
  4813.9  683.04  4838.8  683.17  4844.7  681.79  4849.7  681.84  4869.1  680.48
  4889.2  680.39  4899.3  679.67  4909.4  676.62  4919.4  674.40  4926.4  672.17
  4939.6  670.10  4959.7  670.73  4979.9  672.01  4989.9  671.75  5010.6  669.11
  5011.3  668.61  5015.1  668.61  5015.9  669.11  5020.2  671.11  5030.2  671.83
  5050.4  671.75  5094.9  672.46  5251.9  675.71  5258.4  676.29  5263.4  676.17
  5322.4  678.71  5340.1  679.99  5352.6  680.09  5372.7  681.85  5408.7  682.38
#Mann=3,-1,0
  4813.9    0.05       0  5010.6   0.033       0  5015.9    0.05       0
Bank Sta=5010.6,5015.9
Exp/Cntr=0.3,0.1

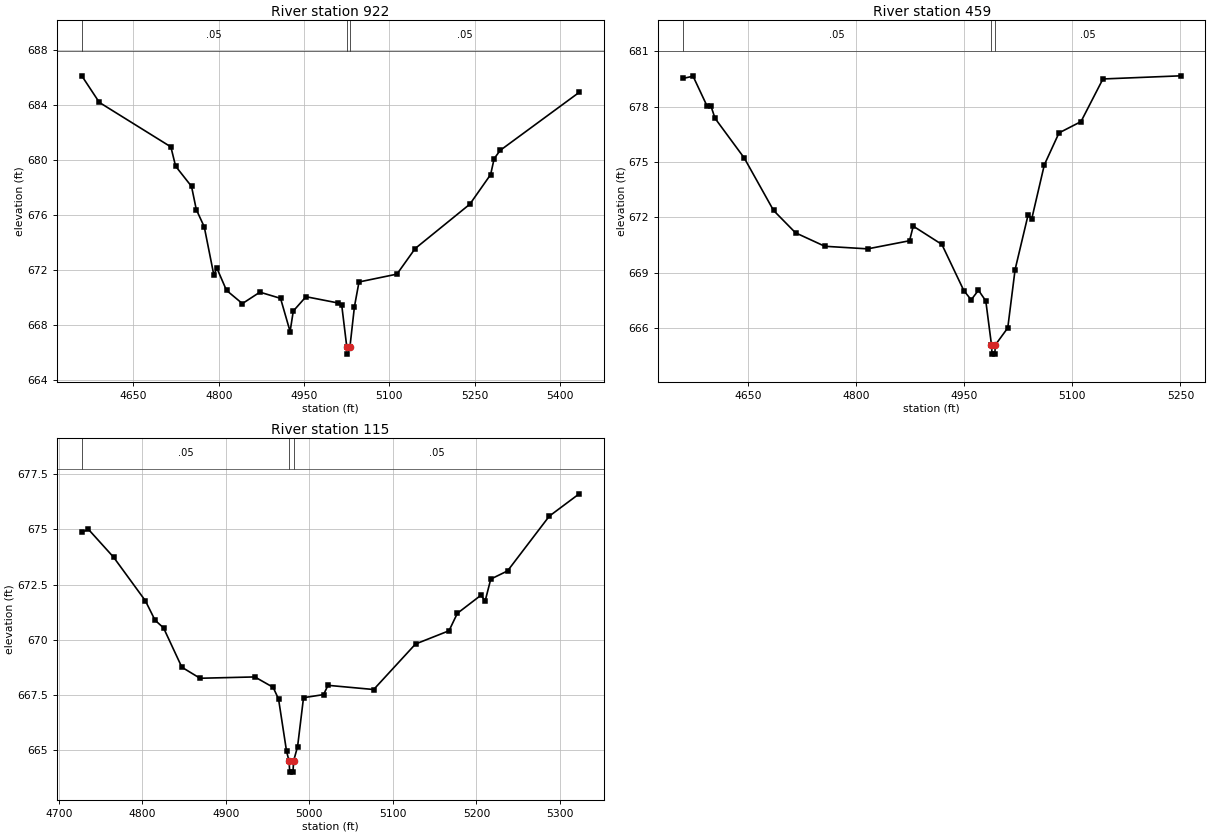
Type RM Length L Ch R = 1,922,463,463,463
BEGIN DESCRIPTION:
Hog Branch Tributary 3_2 2.0
END DESCRIPTION:
XS GIS Cut Line= 3
      2346129.03      7102810.01      2345729.00      7102610.00
      2345329.04      7102759.98
#Sta/Elev= 30
  4559.2  686.12  4590.0  684.19  4715.8  680.96  4724.1  679.56  4752.1  678.09
  4760.5  676.41  4774.5  675.15  4791.2  671.68  4796.8  672.14  4813.6  670.54
  4841.5  669.58  4872.3  670.41  4908.6  669.96  4925.4  667.55  4931.0  669.04
  4953.3  670.08  5009.1  669.63  5016.2  669.45  5025.1  666.41  5025.9  665.91
  5030.5  666.41  5038.5  669.36  5046.5  671.15  5113.2  671.72  5145.3  673.58
  5241.4  676.80  5277.9  678.95  5284.1  680.11  5294.8  680.71  5433.6  684.92
#Mann=3,-1,0
  4559.2    0.05       0  5025.1   0.033       0  5030.5    0.05       0
Bank Sta=5025.1,5030.5
Exp/Cntr=0.3,0.1

Type RM Length L Ch R = 1,459,344,344,344
BEGIN DESCRIPTION:
Mapping XS f40b7c9e
END DESCRIPTION:
XS GIS Cut Line= 2
      2346012.53      7102401.82      2345332.94      7102277.35
#Sta/Elev= 30
  4559.3  679.53  4573.1  679.65  4592.7  678.02  4597.8  678.05  4603.6  677.37
  4644.2  675.22  4684.9  672.38  4715.4  671.17  4756.1  670.44  4815.6  670.30
  4873.8  670.74  4878.9  671.53  4918.7  670.54  4949.2  668.04  4959.4  667.54
  4969.5  668.06  4979.7  667.48  4987.6  665.10  4988.4  664.60  4992.2  664.60
  4993.0  665.10  5010.2  666.02  5020.4  669.18  5038.4  672.13  5043.5  671.92
  5061.0  674.85  5081.4  676.58  5111.9  677.19  5142.4  679.50  5250.2  679.67
#Mann=3,-1,0
  4559.3    0.05       0  4987.6   0.033       0  4993.0    0.05       0
Bank Sta=4987.6,4993
Exp/Cntr=0.3,0.1

Type RM Length L Ch R = 1,115,0,0,0
BEGIN DESCRIPTION:
Hog Branch Tributary 3_2 1.0
END DESCRIPTION:
XS GIS Cut Line= 3
      2346016.03      7102183.95      2345781.56      7102056.53
      2345453.30      7102038.85
#Sta/Elev= 30
  4727.5  674.87  4735.5  675.00  4765.6  673.74  4803.6  671.77  4815.2  670.89
  4825.4  670.54  4847.3  668.76  4869.1  668.26  4934.7  668.32  4956.6  667.85
  4963.1  667.32  4972.7  664.95  4975.7  664.51  4976.5  664.01  4980.4  664.01
  4981.1  664.51  4985.9  665.17  4993.0  667.38  5017.0  667.52  5022.3  667.94
  5077.0  667.75  5127.1  669.81  5167.2  670.41  5177.2  671.20  5205.5  672.02
  5210.5  671.76  5217.2  672.75  5237.3  673.12  5287.3  675.60  5323.1  676.61
#Mann=3,-1,0
  4727.5    0.05       0  4975.7   0.033       0  4981.1    0.05       0
Bank Sta=4975.7,4981.1
Exp/Cntr=0.3,0.1

Chan Stop Cuts=-1