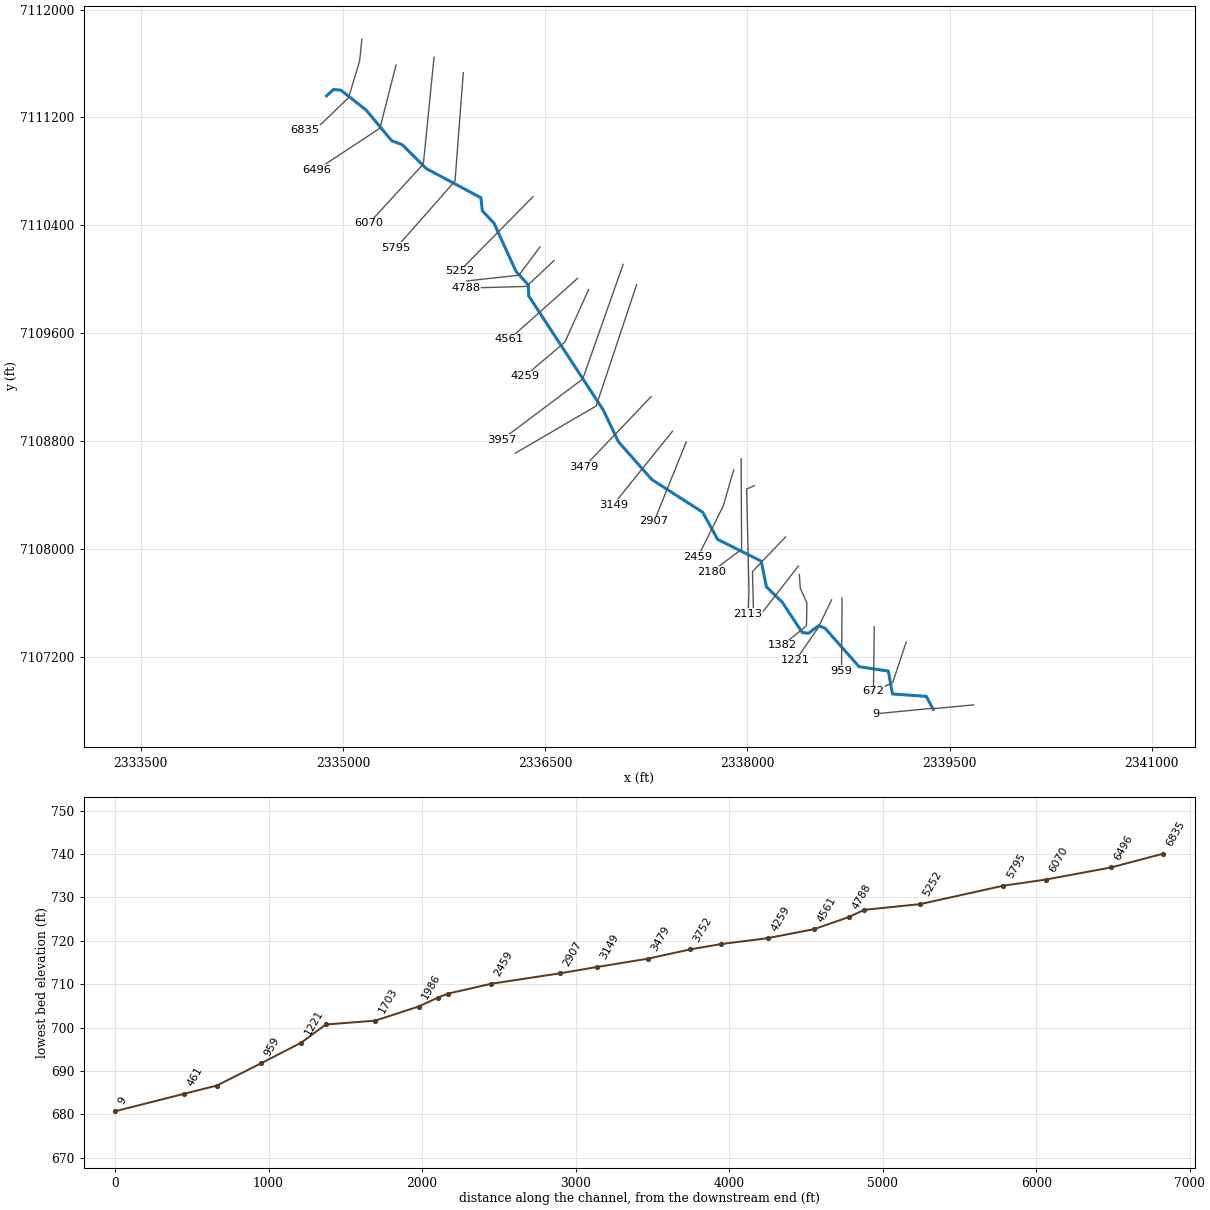
--- Hog Branch Tributary 5.prj (project) ---

Proj Title=Hog Branch Tributary 5 Base Level Engineering
Current Plan=p01
Default Exp/Contr=0.3,0.1
English Units
Geom File=g01
Flow File=f01
Plan File=p01
BEGIN DESCRIPTION:
Hog Branch Tributary 5
END DESCRIPTION:

--- Hog Branch Tributary 5.p01 (plan) ---

Plan Title=Multiple Run
Short Identifier=Multiple
Geom File=g01
Flow File=f01
Subcritical Flow
K Sum by GR= 0
Std Step Tol= 0.01
Critical Tol= 0.01
Num of Std Step Trials= 20
Max Error Tol= 0.3
Flow Tol Ratio= 0.001
Split Flow NTrial= 30
Split Flow Tol= 0.02
Split Flow Ratio= 0.02
Log Output Level= 0
Friction Slope Method= 1
Unsteady Friction Slope Method= 2
Unsteady Bridges Friction Slope Method= 1
Parabolic Critical Depth
Global Vel Dist=  1 , 1 , 1
Global Log Level= 0
CheckData=True
Encroach Param= -1, 0, 0, 0
BEGIN DESCRIPTION:
Multiple Run
END DESCRIPTION:

--- Hog Branch Tributary 5.f01 (steady flow) ---

Flow Title=Multiple
Number of Profiles=7
Profile Names=10-year,25-year,50-year,1pct_min,100-year,1pct_plu,500-year
River Rch & RM= Hog Branch Tribu,Reach-1,6835
     365     484     579     344     687    1371     969
Boundary for River Rch & Prof#=Hog Branch Tribu,Reach-1,1
Up Type=0
Dn Type=1
Dn Known WS=684.56
Boundary for River Rch & Prof#=Hog Branch Tribu,Reach-1,2
Up Type=0
Dn Type=1
Dn Known WS=684.94
Boundary for River Rch & Prof#=Hog Branch Tribu,Reach-1,3
Up Type=0
Dn Type=1
Dn Known WS=685.38
Boundary for River Rch & Prof#=Hog Branch Tribu,Reach-1,4
Up Type=0
Dn Type=1
Dn Known WS=684.63
Boundary for River Rch & Prof#=Hog Branch Tribu,Reach-1,5
Up Type=0
Dn Type=1
Dn Known WS=685.84
Boundary for River Rch & Prof#=Hog Branch Tribu,Reach-1,6
Up Type=0
Dn Type=1
Dn Known WS=687.67
Boundary for River Rch & Prof#=Hog Branch Tribu,Reach-1,7
Up Type=0
Dn Type=1
Dn Known WS=686.99

--- Hog Branch Tributary 5.g01 (geometry) ---

Geom Title=Existing Conditions

River Reach=Hog Branch Tribu,Reach-1
Reach XY= 30
      2334879.00      7111360.00      2334930.62      7111407.33
      2334985.09      7111402.53      2335173.38      7111254.38
      2335362.33      7111026.65      2335438.68      7110999.22
      2335619.32      7110820.76      2336023.74      7110604.53
      2336034.56      7110507.64      2336120.84      7110416.05
      2336284.85      7110057.71      2336375.45      7109958.53
      2336378.90      7109876.03      2336931.11      7109031.14
      2337043.77      7108795.22      2337292.38      7108514.10
      2337668.70      7108272.54      2337779.50      7108071.40
      2338103.21      7107909.76      2338141.82      7107718.87
      2338259.64      7107604.21      2338407.86      7107379.96
      2338453.07      7107374.42      2338528.89      7107429.83
      2338576.40      7107412.26      2338828.75      7107126.81
      2339046.13      7107093.82      2339076.49      7106924.48
      2339327.74      7106906.62      2339379.00      7106810.00

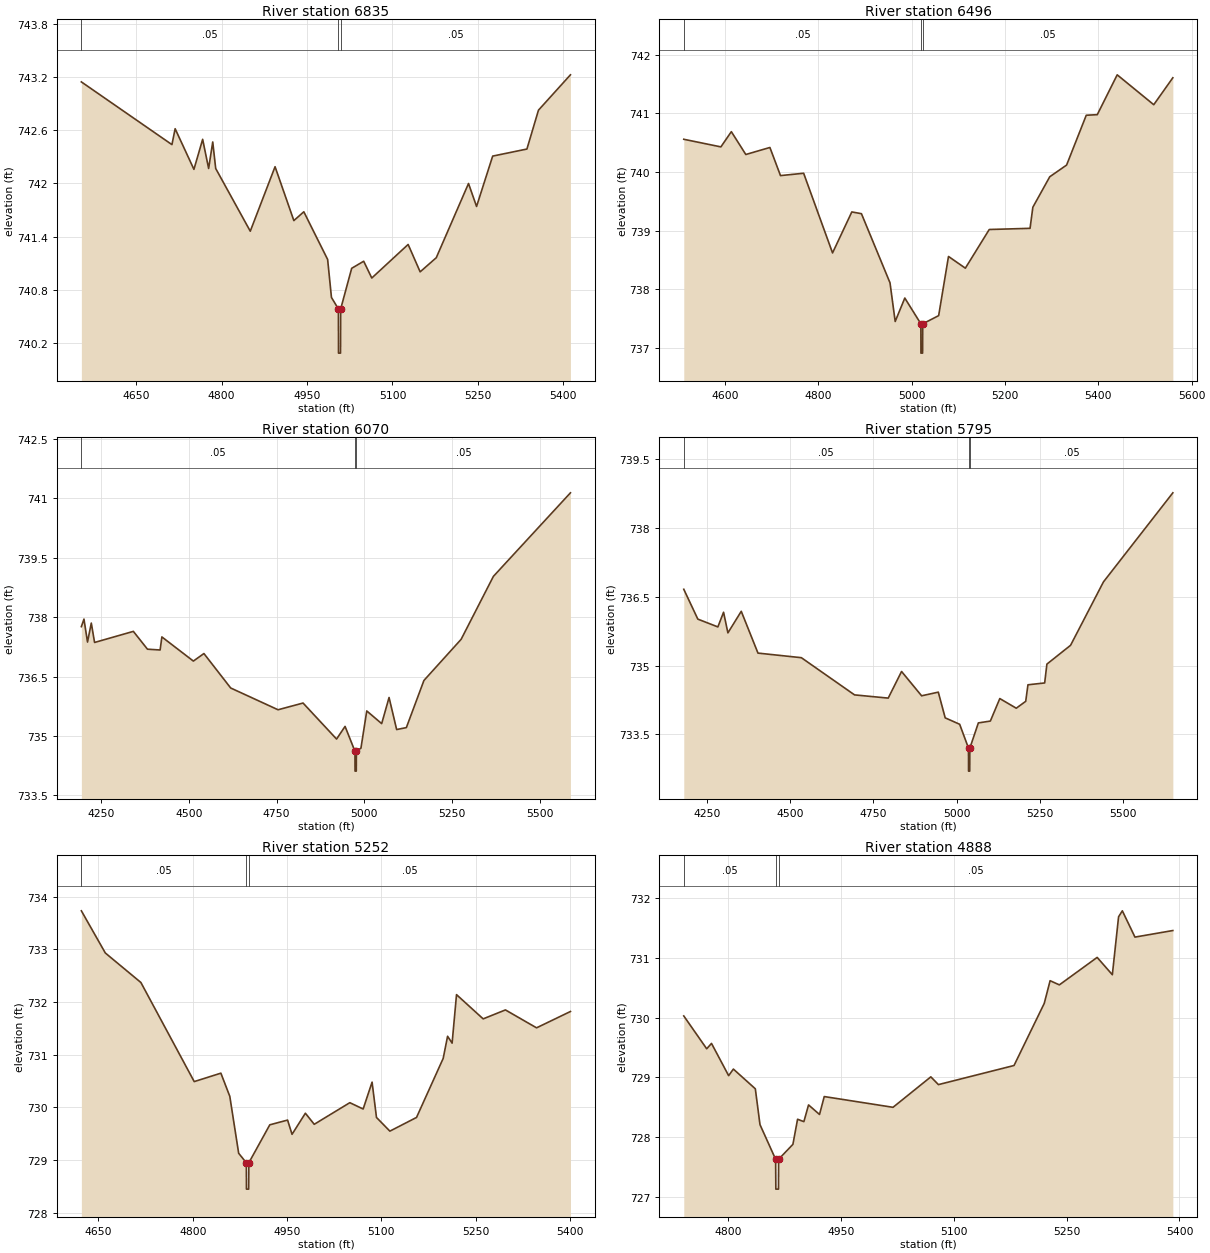
Type RM Length L Ch R = 1,6835,339,339,339
BEGIN DESCRIPTION:
Hog Branch Tributary 5 18.0
END DESCRIPTION:
XS GIS Cut Line= 5
      2335141.00      7111779.93      2335124.30      7111618.48
      2335042.37      7111346.77      2334839.39      7111151.14
      2334715.97      7111108.75
#Sta/Elev= 30
  4553.9  743.15  4712.9  742.44  4718.5  742.62  4751.5  742.16  4766.8  742.50
  4777.3  742.17  4784.5  742.47  4789.7  742.17  4850.4  741.46  4893.9  742.19
  4926.9  741.58  4944.4  741.68  4986.2  741.14  4992.9  740.71  5005.1  740.58
  5005.3  740.08  5008.8  740.08  5009.1  740.58  5028.4  741.04  5049.5  741.12
  5063.7  740.93  5127.5  741.31  5148.6  741.00  5176.9  741.16  5233.5  742.00
  5247.6  741.74  5275.9  742.31  5336.0  742.39  5356.3  742.83  5412.4  743.23
#Mann=3,-1,0
  4553.9    0.05       0  5005.1   0.033       0  5009.1    0.05       0
Bank Sta=5005.1,5009.1
Exp/Cntr=0.3,0.1

Type RM Length L Ch R = 1,6496,426,426,426
BEGIN DESCRIPTION:
Mapping XS ec484346
END DESCRIPTION:
XS GIS Cut Line= 3
      2335394.55      7111588.76      2335274.68      7111119.92
      2334803.74      7110809.97
#Sta/Elev= 30
  4512.0  740.56  4591.5  740.43  4613.9  740.69  4644.9  740.30  4696.5  740.42
  4719.2  739.94  4768.8  739.98  4830.7  738.62  4872.0  739.32  4892.6  739.29
  4953.8  738.11  4964.9  737.45  4985.5  737.85  5019.9  737.41  5020.1  736.91
  5023.6  736.91  5023.9  737.41  5058.0  737.55  5079.1  738.56  5115.2  738.36
  5166.4  739.02  5253.8  739.04  5259.8  739.40  5296.0  739.92  5332.1  740.12
  5374.2  740.97  5397.8  740.98  5440.5  741.66  5518.8  741.15  5559.7  741.61
#Mann=3,-1,0
  4512.0    0.05       0  5019.9    0.04       0  5023.9    0.05       0
Bank Sta=5019.9,5023.9
Exp/Cntr=0.3,0.1

Type RM Length L Ch R = 1,6070,275,275,275
BEGIN DESCRIPTION:
Mapping XS a268f5aa
END DESCRIPTION:
XS GIS Cut Line= 3
      2335676.38      7111647.41      2335597.18      7110855.02
      2335193.99      7110415.19
#Sta/Elev= 30
  4194.0  737.76  4201.4  737.95  4211.5  737.37  4222.3  737.85  4231.6  737.36
  4342.1  737.64  4382.3  737.19  4418.3  737.17  4423.3  737.50  4513.0  736.89
  4543.1  737.08  4619.3  736.21  4754.2  735.66  4825.4  735.83  4920.9  734.92
  4945.1  735.24  4973.3  734.61  4973.5  734.11  4977.0  734.11  4977.3  734.61
  4990.3  734.69  5006.9  735.63  5049.4  735.31  5070.4  735.97  5092.0  735.16
  5119.7  735.21  5169.7  736.40  5275.7  737.44  5367.6  739.03  5587.0  741.14
#Mann=3,-1,0
  4194.0    0.05       0  4973.3   0.033       0  4977.3    0.05       0
Bank Sta=4973.3,4977.3
Exp/Cntr=0.3,0.1

Type RM Length L Ch R = 1,5795,543,543,543
BEGIN DESCRIPTION:
Mapping XS d91559a2
END DESCRIPTION:
XS GIS Cut Line= 3
      2335893.21      7111532.12      2335832.10      7110728.75
      2335393.70      7110231.51
#Sta/Elev= 30
  4180.6  736.66  4222.8  736.01  4283.0  735.84  4300.1  736.16  4313.1  735.71
  4353.2  736.18  4403.4  735.27  4533.7  735.17  4693.4  734.36  4794.5  734.29
  4834.6  734.87  4894.8  734.34  4944.9  734.42  4965.6  733.86  5009.1  733.72
  5035.6  733.20  5035.8  732.70  5039.3  732.70  5039.6  733.20  5065.2  733.75
  5101.2  733.79  5129.6  734.28  5179.0  734.07  5207.4  734.22  5214.1  734.58
  5264.3  734.62  5271.0  735.03  5342.1  735.44  5440.8  736.82  5649.2  738.76
#Mann=3,-1,0
  4180.6    0.05       0  5035.6    0.04       0  5039.6    0.05       0
Bank Sta=5035.6,5039.6
Exp/Cntr=0.3,0.1

Type RM Length L Ch R = 1,5252,364,364,364
BEGIN DESCRIPTION:
Mapping XS 6d2954d6
END DESCRIPTION:
XS GIS Cut Line= 2
      2336410.69      7110612.17      2335863.83      7110058.93
#Sta/Elev= 30
  4622.9  733.73  4661.0  732.93  4717.6  732.37  4802.4  730.49  4844.8  730.65
  4859.0  730.21  4873.1  729.13  4885.3  728.95  4885.5  728.45  4889.0  728.45
  4889.3  728.95  4922.6  729.67  4950.9  729.76  4958.0  729.49  4979.2  729.89
  4993.3  729.68  5049.9  730.09  5071.1  729.97  5085.3  730.48  5092.3  729.81
  5113.6  729.55  5156.0  729.81  5198.4  730.93  5205.4  731.35  5212.6  731.22
  5219.6  732.14  5262.0  731.68  5297.4  731.85  5346.9  731.51  5400.8  731.82
#Mann=3,-1,0
  4622.9    0.05       0  4885.3    0.04       0  4889.3    0.05       0
Bank Sta=4885.3,4889.3
Exp/Cntr=0.3,0.1

Type RM Length L Ch R = 1,4888,100,100,100
BEGIN DESCRIPTION:
Mapping XS d8db2e59
END DESCRIPTION:
XS GIS Cut Line= 3
      2336462.18      7110239.56      2336305.85      7110029.99
      2335918.94      7109987.47
#Sta/Elev= 30
  4740.5  730.03  4771.0  729.48  4777.4  729.57  4800.2  729.03  4806.5  729.14
  4835.7  728.81  4841.9  728.21  4862.7  727.63  4863.0  727.13  4866.5  727.13
  4866.7  727.63  4885.7  727.88  4891.9  728.30  4900.3  728.26  4906.5  728.54
  4921.1  728.38  4927.4  728.68  5018.9  728.50  5069.2  729.01  5079.3  728.88
  5179.9  729.20  5220.1  730.24  5227.9  730.62  5240.2  730.55  5290.5  731.01
  5310.7  730.72  5319.0  731.69  5324.0  731.79  5340.8  731.35  5391.2  731.46
#Mann=3,-1,0
  4740.5    0.05       0  4862.7   0.033       0  4866.7    0.05       0
Bank Sta=4862.7,4866.7
Exp/Cntr=0.3,0.1

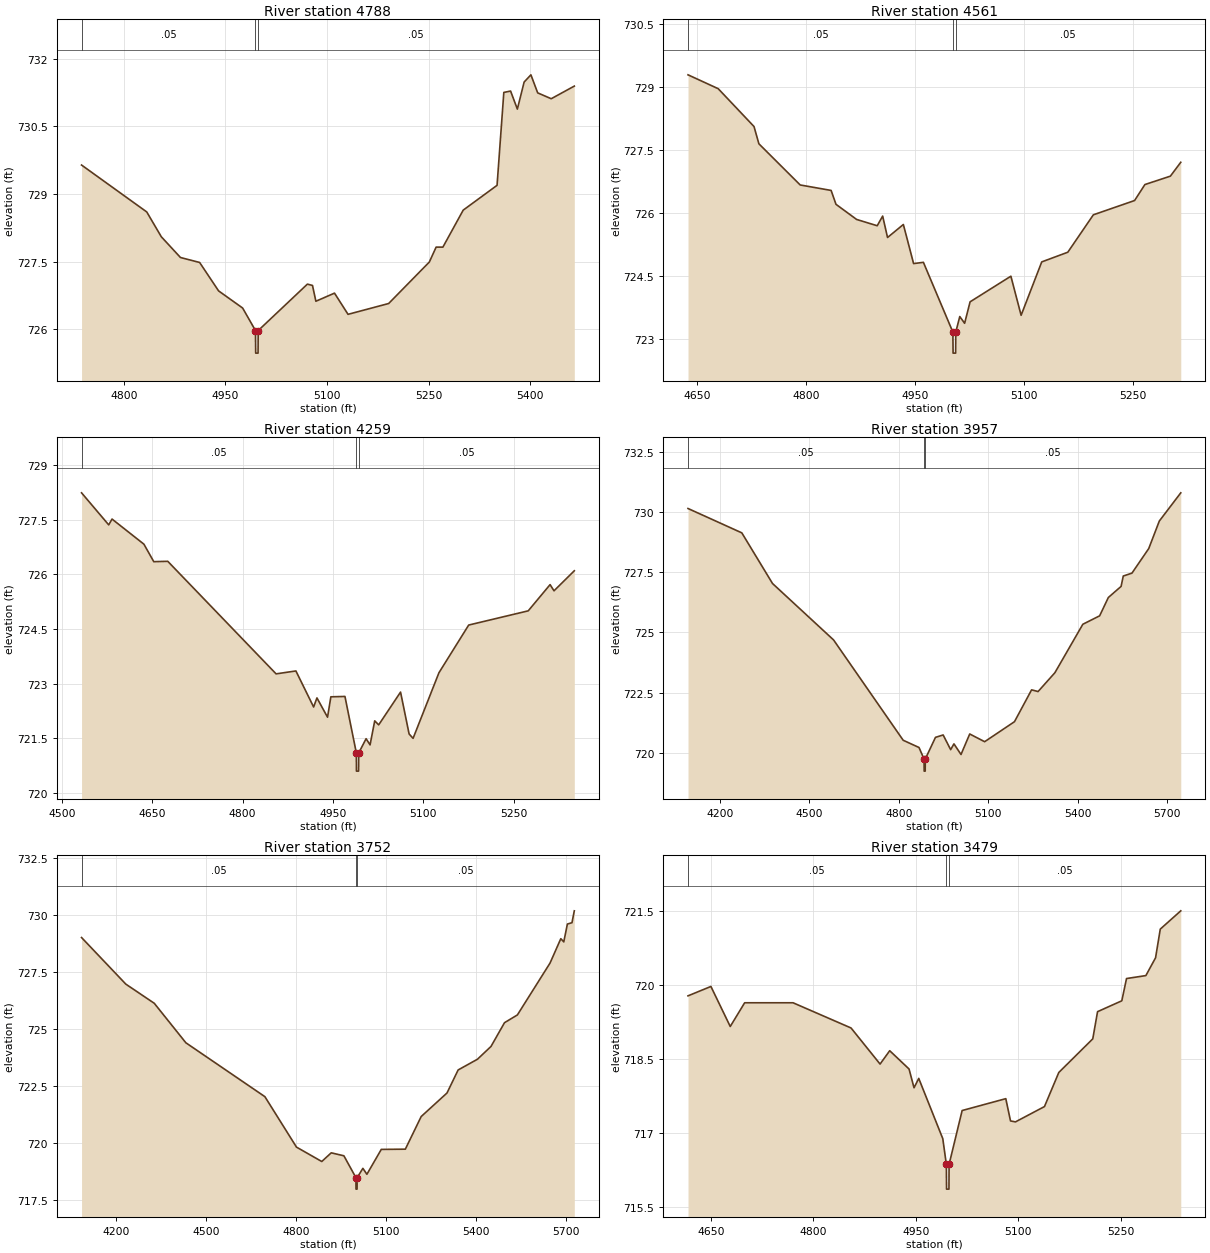
Type RM Length L Ch R = 1,4788,227,227,227
BEGIN DESCRIPTION:
Mapping XS 4141a691
END DESCRIPTION:
XS GIS Cut Line= 3
      2336566.36      7110138.90      2336362.23      7109946.74
      2335914.95      7109934.46
#Sta/Elev= 30
  4737.5  729.64  4833.8  728.60  4855.3  728.05  4883.6  727.59  4911.9  727.48
  4939.9  726.85  4975.4  726.47  4994.4  725.97  4994.7  725.47  4998.2  725.47
  4998.4  725.97  5071.1  727.00  5078.6  726.97  5083.6  726.62  5111.1  726.80
  5131.1  726.33  5191.1  726.57  5251.2  727.49  5261.2  727.82  5271.2  727.82
  5301.2  728.64  5351.2  729.19  5361.2  731.25  5371.2  731.28  5381.2  730.88
  5391.2  731.48  5401.2  731.64  5411.2  731.24  5431.2  731.11  5465.3  731.39
#Mann=3,-1,0
  4737.5    0.05       0  4994.4   0.033       0  4998.4    0.05       0
Bank Sta=4994.4,4998.4
Exp/Cntr=0.3,0.1

Type RM Length L Ch R = 1,4561,302,302,302
BEGIN DESCRIPTION:
Mapping XS a42fc85b
END DESCRIPTION:
XS GIS Cut Line= 2
      2336740.85      7110006.40      2336234.33      7109554.66
#Sta/Elev= 30
  4637.2  729.29  4678.8  728.96  4728.1  728.06  4734.8  727.65  4791.7  726.67
  4834.3  726.54  4841.0  726.21  4869.4  725.85  4897.8  725.70  4905.3  725.93
  4912.0  725.42  4933.8  725.73  4947.9  724.80  4961.4  724.83  5002.0  723.17
  5002.3  722.67  5005.8  722.67  5006.0  723.17  5011.5  723.54  5018.2  723.38
  5025.7  723.89  5081.9  724.50  5096.0  723.57  5124.4  724.84  5160.3  725.07
  5195.5  725.96  5252.3  726.30  5266.5  726.68  5301.6  726.88  5315.9  727.21
#Mann=3,-1,0
  4637.2    0.05       0  5002.0   0.035       0  5006.0    0.05       0
Bank Sta=5002,5006
Exp/Cntr=0.3,0.1

Type RM Length L Ch R = 1,4259,302,302,302
BEGIN DESCRIPTION:
Mapping XS 765fb54d
END DESCRIPTION:
XS GIS Cut Line= 3
      2336823.38      7109924.28      2336647.26      7109534.38
      2336350.16      7109281.64
#Sta/Elev= 30
  4532.6  728.24  4577.7  727.36  4583.2  727.52  4636.1  726.83  4652.5  726.35
  4675.7  726.36  4855.5  723.27  4888.4  723.35  4917.8  722.36  4923.3  722.61
  4940.9  722.08  4946.4  722.64  4969.8  722.65  4988.7  721.10  4988.9  720.60
  4992.4  720.60  4992.7  721.10  5004.9  721.49  5011.5  721.32  5019.2  721.98
  5025.8  721.87  5062.1  722.77  5076.3  721.62  5082.9  721.50  5125.8  723.30
  5175.2  724.61  5274.0  725.00  5310.3  725.72  5316.8  725.55  5350.5  726.10
#Mann=3,-1,0
  4532.6    0.05       0  4988.7   0.033       0  4992.7    0.05       0
Bank Sta=4988.7,4992.7
Exp/Cntr=0.3,0.1

Type RM Length L Ch R = 1,3957,205,205,205
BEGIN DESCRIPTION:
Hog Branch Tributary 5 10.0
END DESCRIPTION:
XS GIS Cut Line= 3
      2337078.99      7110109.98      2336779.00      7109260.00
      2336178.98      7108809.98
#Sta/Elev= 30
  4093.9  730.14  4274.2  729.13  4377.1  727.03  4581.7  724.69  4815.0  720.53
  4868.0  720.23  4885.0  719.75  4885.3  719.25  4888.8  719.25  4889.0  719.75
  4923.2  720.65  4948.9  720.75  4974.1  720.14  4985.1  720.38  5008.8  719.94
  5038.0  720.79  5088.0  720.47  5188.0  721.30  5245.3  722.62  5267.1  722.55
  5323.4  723.33  5417.1  725.34  5473.4  725.69  5502.6  726.45  5545.3  726.91
  5552.6  727.34  5581.7  727.46  5638.0  728.48  5673.4  729.62  5745.3  730.79
#Mann=3,-1,0
  4093.9    0.05       0  4885.0   0.033       0  4889.0    0.05       0
Bank Sta=4885,4889
Exp/Cntr=0.3,0.1

Type RM Length L Ch R = 1,3752,273,273,273
BEGIN DESCRIPTION:
Hog Branch Tributary 5 9.0
END DESCRIPTION:
XS GIS Cut Line= 3
      2337179.00      7109960.01      2336879.00      7109060.00
      2336279.02      7108710.01
#Sta/Elev= 30
  4083.6  729.01  4231.2  726.97  4326.1  726.13  4431.5  724.40  4695.0  722.04
  4800.4  719.83  4884.7  719.20  4916.3  719.58  4958.5  719.45  4998.7  718.49
  4998.9  717.99  5002.4  717.99  5002.7  718.49  5021.8  718.90  5035.2  718.64
  5083.2  719.73  5163.4  719.74  5216.3  721.17  5302.3  722.20  5339.5  723.21
  5404.0  723.68  5449.1  724.24  5494.1  725.28  5537.1  725.62  5645.9  727.89
  5681.9  728.96  5691.8  728.82  5703.8  729.60  5719.1  729.66  5726.9  730.18
#Mann=3,-1,0
  4083.6    0.05       0  4998.7   0.033       0  5002.7    0.05       0
Bank Sta=4998.7,5002.7
Exp/Cntr=0.3,0.1

Type RM Length L Ch R = 1,3479,330,330,330
BEGIN DESCRIPTION:
Mapping XS 85118ee5
END DESCRIPTION:
XS GIS Cut Line= 2
      2337286.83      7109129.60      2336788.91      7108607.87
#Sta/Elev= 30
  4616.8  719.78  4650.3  719.97  4678.6  719.16  4699.7  719.64  4770.5  719.64
  4855.4  719.13  4897.9  718.40  4912.0  718.67  4940.3  718.30  4947.6  717.92
  4954.5  718.11  4989.7  716.89  4994.9  716.37  4995.2  715.87  4998.7  715.87
  4998.9  716.37  5018.0  717.46  5081.9  717.70  5088.8  717.25  5096.0  717.23
  5138.5  717.54  5159.5  718.23  5209.2  718.91  5216.2  719.46  5251.7  719.68
  5258.6  720.13  5286.9  720.19  5301.1  720.55  5308.0  721.13  5338.0  721.50
#Mann=3,-1,0
  4616.8    0.05       0  4994.9   0.033       0  4998.9    0.05       0
Bank Sta=4994.9,4998.9
Exp/Cntr=0.3,0.1

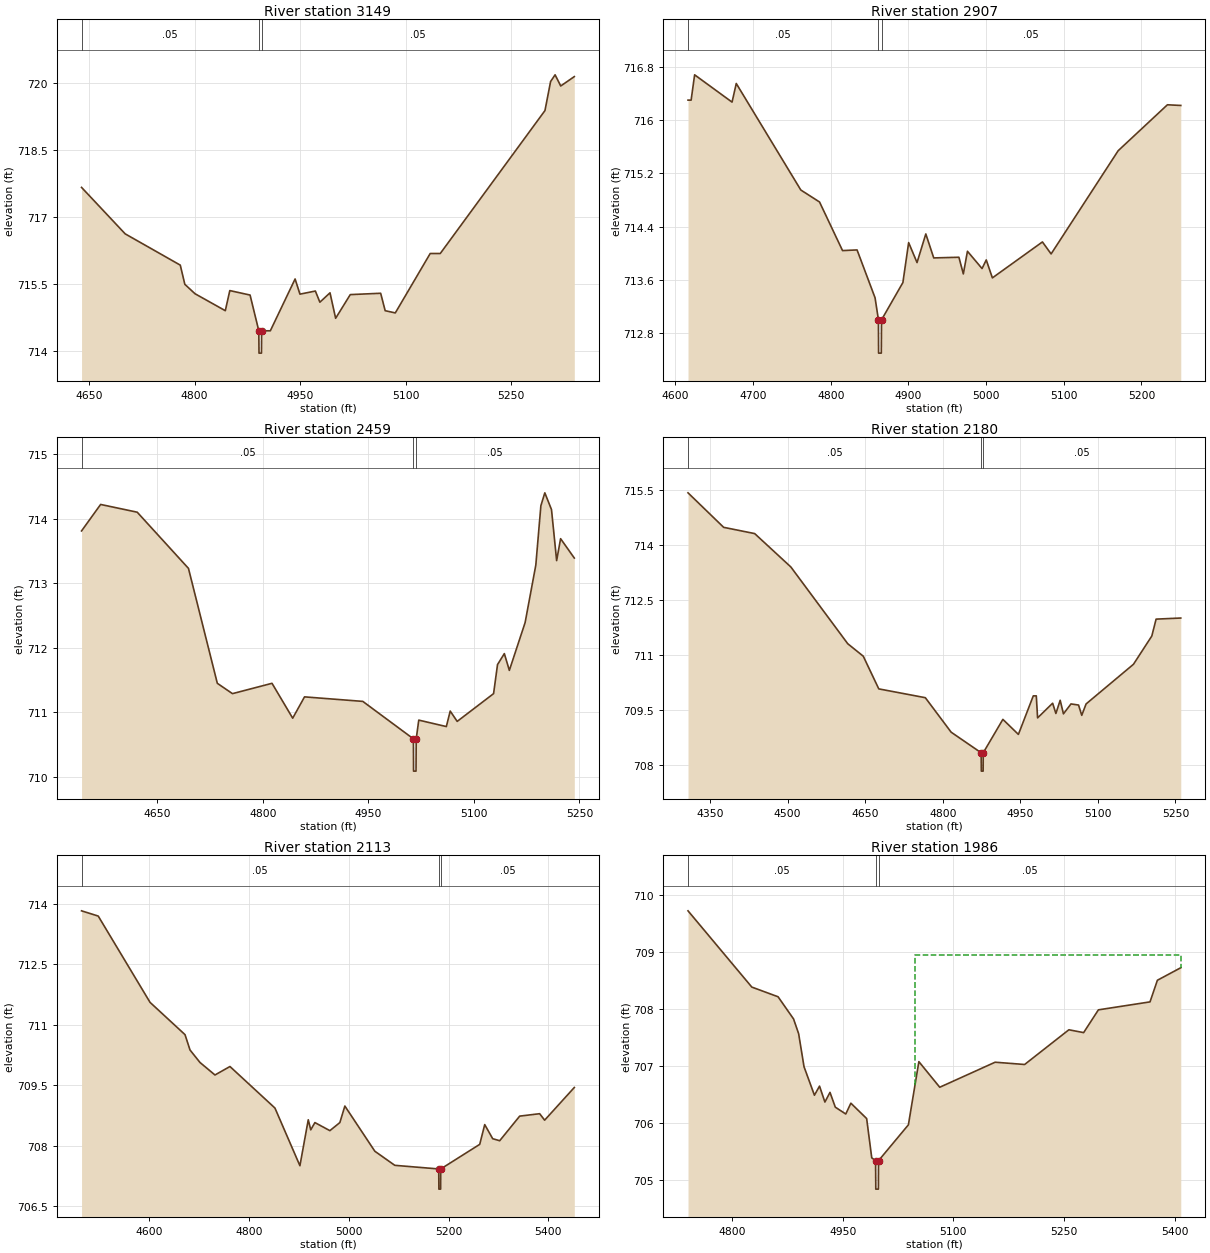
Type RM Length L Ch R = 1,3149,242,242,242
BEGIN DESCRIPTION:
Mapping XS cb11be3b
END DESCRIPTION:
XS GIS Cut Line= 2
      2337444.16      7108871.68      2337004.76      7108326.38
#Sta/Elev= 30
  4639.3  717.67  4701.3  716.63  4779.6  715.93  4786.1  715.50  4800.5  715.29
  4843.6  714.91  4850.0  715.36  4878.8  715.26  4891.2  714.46  4891.5  713.96
  4895.0  713.96  4895.2  714.46  4907.6  714.46  4942.8  715.62  4949.7  715.28
  4971.6  715.35  4978.0  715.10  4992.4  715.31  5000.4  714.74  5021.2  715.27
  5064.4  715.30  5070.8  714.91  5085.2  714.86  5134.8  716.19  5149.1  716.19
  5297.9  719.39  5305.9  720.04  5312.3  720.19  5320.3  719.94  5339.6  720.15
#Mann=3,-1,0
  4639.3    0.05       0  4891.2   0.033       0  4895.2    0.05       0
Bank Sta=4891.2,4895.2
Exp/Cntr=0.3,0.1

Type RM Length L Ch R = 1,2907,448,448,448
BEGIN DESCRIPTION:
Mapping XS 25551984
END DESCRIPTION:
XS GIS Cut Line= 2
      2337547.01      7108793.23      2337309.10      7108205.24
#Sta/Elev= 30
  4616.3  716.30  4620.3  716.30  4624.8  716.68  4673.0  716.27  4678.4  716.55
  4761.5  714.95  4785.6  714.77  4815.2  714.04  4833.9  714.05  4857.1  713.33
  4861.4  713.00  4861.6  712.50  4865.1  712.50  4865.4  713.00  4892.9  713.56
  4900.3  714.16  4911.1  713.86  4922.4  714.29  4932.6  713.93  4965.0  713.94
  4970.7  713.69  4976.0  714.03  4994.8  713.77  5000.2  713.90  5008.1  713.63
  5072.5  714.17  5083.7  713.99  5170.0  715.54  5233.4  716.23  5250.6  716.22
#Mann=3,-1,0
  4616.3    0.05       0  4861.4   0.033       0  4865.4    0.05       0
Bank Sta=4861.4,4865.4
Exp/Cntr=0.3,0.1

Type RM Length L Ch R = 1,2459,279,279,279
BEGIN DESCRIPTION:
Mapping XS 8149e436
END DESCRIPTION:
XS GIS Cut Line= 3
      2337898.71      7108586.00      2337821.69      7108318.90
      2337633.53      7107941.04
#Sta/Elev= 30
  4542.6  713.81  4569.7  714.22  4621.7  714.10  4694.5  713.23  4735.5  711.45
  4757.0  711.29  4813.2  711.45  4842.6  710.91  4859.4  711.24  4942.2  711.17
  5014.1  710.59  5014.3  710.09  5017.8  710.09  5018.1  710.59  5021.7  710.88
  5060.9  710.78  5066.4  711.02  5076.3  710.86  5128.0  711.29  5133.6  711.74
  5143.3  711.91  5150.4  711.65  5172.8  712.39  5188.0  713.28  5195.2  714.20
  5200.8  714.40  5210.3  714.14  5217.6  713.35  5223.2  713.69  5242.7  713.39
#Mann=3,-1,0
  4542.6    0.05       0  5014.1   0.033       0  5018.1    0.05       0
Bank Sta=5014.1,5018.1
Exp/Cntr=0.3,0.1

Type RM Length L Ch R = 1,2180,67,67,67
BEGIN DESCRIPTION:
Mapping XS 439e0fa6
END DESCRIPTION:
XS GIS Cut Line= 3
      2337954.20      7108668.93      2337957.92      7107997.56
      2337732.51      7107828.91
#Sta/Elev= 30
  4307.4  715.41  4376.3  714.47  4436.3  714.30  4506.3  713.39  4616.3  711.30
  4646.3  710.96  4676.3  710.07  4766.3  709.83  4816.3  708.89  4874.3  708.33
  4874.6  707.83  4878.1  707.83  4878.3  708.33  4916.3  709.24  4946.3  708.83
  4975.1  709.88  4980.9  709.88  4983.4  709.28  5012.5  709.68  5018.8  709.40
  5027.1  709.76  5033.4  709.39  5048.0  709.66  5062.6  709.63  5068.8  709.35
  5077.2  709.66  5168.8  710.74  5204.3  711.51  5212.6  711.97  5260.3  712.00
#Mann=3,-1,0
  4307.4    0.05       0  4874.3   0.033       0  4878.3    0.05       0
Bank Sta=4874.3,4878.3
Exp/Cntr=0.3,0.1

Type RM Length L Ch R = 1,2113,127,127,127
BEGIN DESCRIPTION:
Mapping XS beb065cf
END DESCRIPTION:
XS GIS Cut Line= 4
      2338052.96      7108468.74      2337995.01      7108444.27
      2338012.44      7107683.05      2338006.51      7107520.68
#Sta/Elev= 30
  4465.1  713.82  4498.5  713.69  4602.3  711.55  4672.3  710.75  4682.3  710.37
  4702.3  710.06  4732.3  709.75  4762.3  709.96  4852.4  708.93  4902.4  707.50
  4919.1  708.64  4924.1  708.39  4932.4  708.57  4962.4  708.37  4982.4  708.57
  4992.4  708.98  5052.4  707.86  5092.4  707.51  5180.4  707.42  5180.7  706.92
  5184.2  706.92  5184.4  707.42  5262.5  708.03  5272.5  708.52  5288.5  708.17
  5302.5  708.12  5342.5  708.73  5382.5  708.79  5392.5  708.63  5451.9  709.44
#Mann=3,-1,0
  4465.1    0.05       0  5180.4   0.033       0  5184.4    0.05       0
Bank Sta=5180.4,5184.4
Exp/Cntr=0.3,0.1

Type RM Length L Ch R = 1,1986,283,283,283
BEGIN DESCRIPTION:
Mapping XS 79e66215
END DESCRIPTION:
XS GIS Cut Line= 3
      2338283.07      7108088.27      2338038.45      7107832.24
      2338046.06      7107518.34
#Sta/Elev= 30
  4740.2  709.73  4826.7  708.39  4862.3  708.22  4883.3  707.83  4890.2  707.57
  4897.5  706.99  4911.6  706.49  4918.5  706.65  4925.8  706.37  4932.7  706.54
  4939.9  706.28  4954.1  706.16  4961.0  706.35  4982.4  706.08  4989.3  705.39
  4994.5  705.34  4994.8  704.84  4998.3  704.84  4998.5  705.34  5039.0  705.97
  5053.2  707.08  5081.5  706.63  5156.6  707.07  5196.6  707.03  5256.6  707.64
  5276.6  707.59  5296.6  707.99  5366.6  708.13  5376.6  708.51  5408.3  708.73
#Mann=3,-1,0
  4740.2    0.05       0  4994.5   0.033       0  4998.5    0.05       0
#XS Ineff=2,0
       0                 5048.00    0.00  708.95
Permanent Ineff=
       F       F
Bank Sta=4994.5,4998.5
Exp/Cntr=0.3,0.1

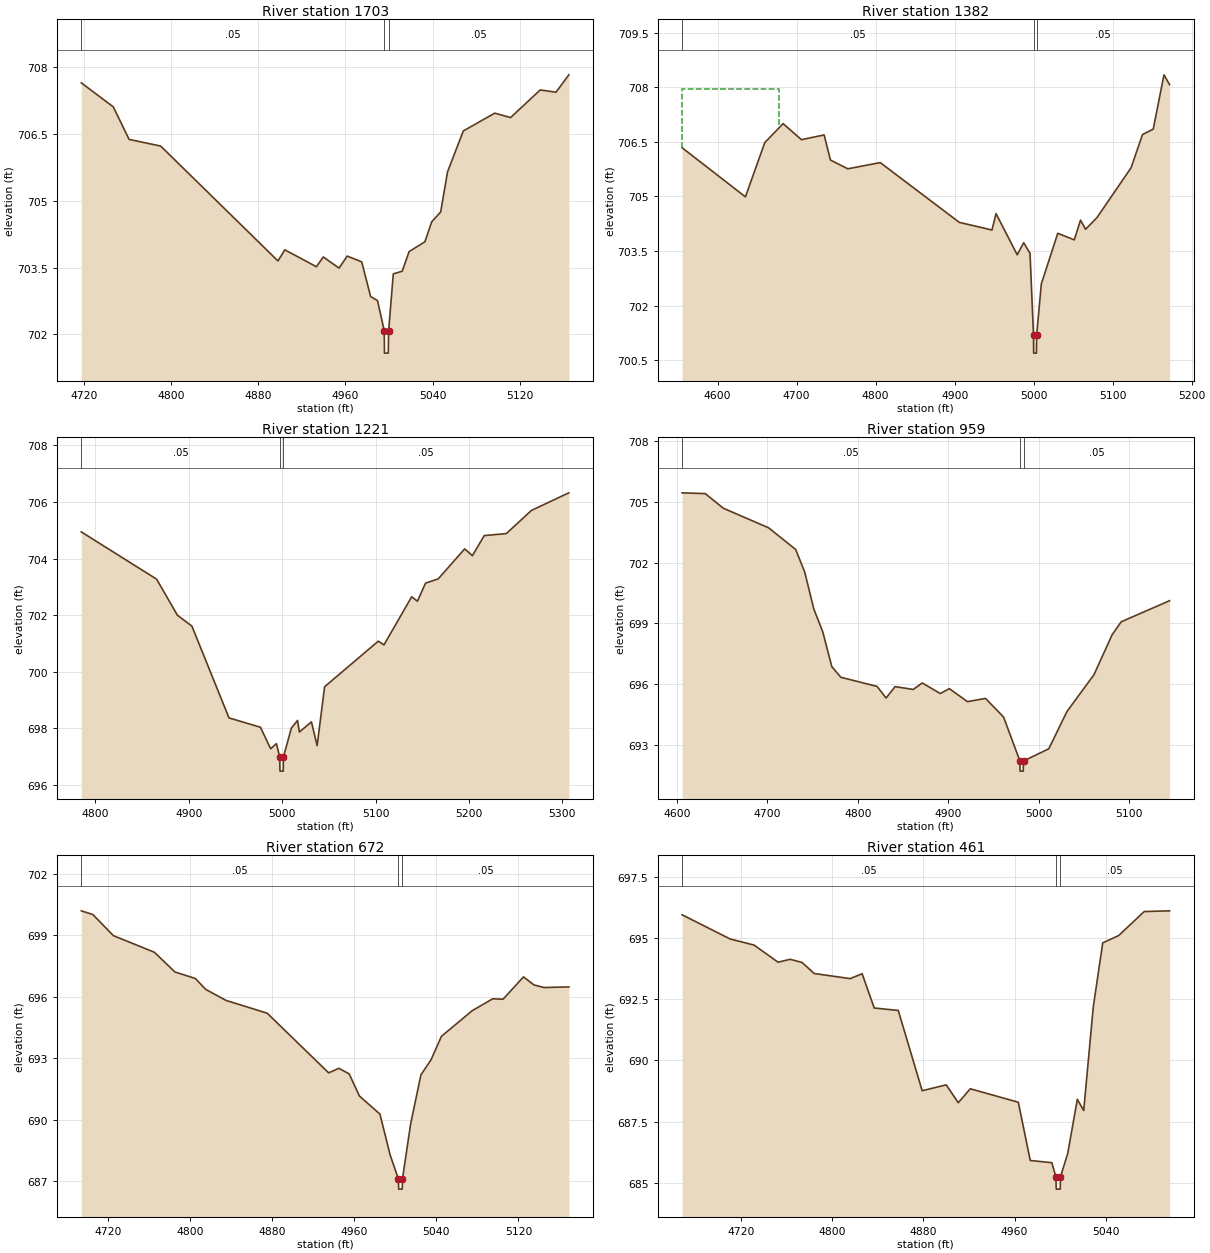
Type RM Length L Ch R = 1,1703,321,321,321
BEGIN DESCRIPTION:
Mapping XS d18bf387
END DESCRIPTION:
XS GIS Cut Line= 2
      2338378.40      7107872.94      2338103.98      7107519.20
#Sta/Elev= 30
  4717.4  707.65  4746.8  707.11  4761.3  706.38  4790.3  706.23  4898.0  703.65
  4904.3  703.90  4933.3  703.52  4939.6  703.74  4954.1  703.49  4961.6  703.76
  4974.9  703.63  4983.1  702.85  4989.4  702.76  4995.6  702.08  4995.8  701.58
  4999.3  701.58  4999.6  702.08  5003.9  703.36  5012.1  703.42  5018.4  703.86
  5032.9  704.08  5039.2  704.53  5047.4  704.75  5053.7  705.65  5068.2  706.57
  5097.1  706.97  5111.6  706.87  5138.8  707.49  5153.3  707.44  5165.1  707.83
#Mann=3,-1,0
  4717.4    0.05       0  4995.6   0.035       0  4999.6    0.05       0
Bank Sta=4995.6,4999.6
Exp/Cntr=0.3,0.1

Type RM Length L Ch R = 1,1382,161,161,161
BEGIN DESCRIPTION:
Mapping XS 7a583f9a
END DESCRIPTION:
XS GIS Cut Line= 6
      2338386.37      7107810.06      2338393.03      7107708.93
      2338442.37      7107598.47      2338438.79      7107431.87
      2338411.61      7107407.06      2338262.93      7107286.95
#Sta/Elev= 30
  4555.1  706.34  4635.3  704.99  4659.8  706.48  4683.0  707.00  4706.2  706.56
  4734.9  706.69  4742.9  706.00  4764.8  705.76  4805.9  705.93  4905.9  704.29
  4947.3  704.08  4952.4  704.53  4979.2  703.40  4987.4  703.73  4995.4  703.44
  4999.8  701.20  5000.0  700.70  5003.5  700.70  5003.8  701.20  5009.7  702.60
  5030.5  703.99  5051.4  703.81  5059.3  704.35  5065.7  704.10  5080.1  704.42
  5123.3  705.79  5137.7  706.70  5151.3  706.85  5164.9  708.34  5172.0  708.07
#Mann=3,-1,0
  4555.1    0.05       0  4999.8   0.033       0  5003.8    0.05       0
#XS Ineff=2,0
    0.00 4678.10  707.95               0
Permanent Ineff=
       F       F
Bank Sta=4999.8,5003.8
Exp/Cntr=0.3,0.1

Type RM Length L Ch R = 1,1221,262,262,262
BEGIN DESCRIPTION:
Mapping XS 90c1e0ff
END DESCRIPTION:
XS GIS Cut Line= 3
      2338625.00      7107622.70      2338523.10      7107411.34
      2338359.14      7107175.10
#Sta/Elev= 30
  4784.8  704.94  4865.5  703.27  4887.7  702.00  4903.3  701.61  4943.0  698.37
  4976.7  698.04  4987.6  697.28  4993.8  697.46  4997.3  696.99  4997.6  696.49
  5001.1  696.49  5001.3  696.99  5009.8  698.01  5016.4  698.28  5018.4  697.87
  5031.3  698.23  5037.4  697.39  5045.4  699.47  5102.9  701.08  5109.0  700.95
  5138.7  702.65  5144.8  702.49  5153.5  703.13  5167.1  703.28  5195.4  704.34
  5203.7  704.10  5216.4  704.81  5240.0  704.88  5267.0  705.70  5307.0  706.32
#Mann=3,-1,0
  4784.8    0.05       0  4997.3   0.033       0  5001.3    0.05       0
Bank Sta=4997.3,5001.3
Exp/Cntr=0.3,0.1

Type RM Length L Ch R = 1,959,287,287,287
BEGIN DESCRIPTION:
Mapping XS d0db6352
END DESCRIPTION:
XS GIS Cut Line= 2
      2338703.11      7107635.66      2338699.18      7107096.38
#Sta/Elev= 30
  4605.6  705.43  4631.3  705.39  4651.3  704.67  4701.3  703.71  4731.3  702.64
  4741.3  701.53  4751.3  699.72  4761.3  698.58  4771.3  696.87  4781.3  696.35
  4821.3  695.90  4831.3  695.33  4841.3  695.89  4861.3  695.75  4871.3  696.07
  4891.3  695.55  4901.3  695.79  4921.3  695.15  4941.3  695.31  4961.3  694.39
  4979.3  692.23  4979.5  691.73  4983.0  691.73  4983.3  692.23  5011.3  692.83
  5031.3  694.66  5061.3  696.48  5081.3  698.44  5091.3  699.08  5144.9  700.12
#Mann=3,-1,0
  4605.6    0.05       0  4979.3   0.033       0  4983.3    0.05       0
Bank Sta=4979.3,4983.3
Exp/Cntr=0.3,0.1

Type RM Length L Ch R = 1,672,211,211,211
BEGIN DESCRIPTION:
Mapping XS e907cc34
END DESCRIPTION:
XS GIS Cut Line= 2
      2338941.80      7107421.32      2338935.69      7106945.76
#Sta/Elev= 30
  4693.6  700.19  4704.9  700.01  4724.9  698.98  4764.9  698.17  4784.9  697.21
  4804.9  696.89  4814.9  696.36  4834.9  695.82  4874.9  695.20  4934.9  692.29
  4944.9  692.51  4954.9  692.24  4964.9  691.16  4984.9  690.28  4994.9  688.28
  5002.9  687.12  5003.2  686.62  5006.7  686.62  5006.9  687.12  5014.9  689.81
  5024.9  692.19  5034.9  692.94  5044.9  694.07  5074.9  695.32  5094.9  695.90
  5105.0  695.88  5125.0  696.97  5135.0  696.58  5145.0  696.45  5169.2  696.48
#Mann=3,-1,0
  4693.6    0.05       0  5002.9   0.033       0  5006.9    0.05       0
Bank Sta=5002.9,5006.9
Exp/Cntr=0.3,0.1

Type RM Length L Ch R = 1,461,452,452,452
BEGIN DESCRIPTION:
Hog Branch Tributary 5 1.0
END DESCRIPTION:
XS GIS Cut Line= 3
      2339179.00      7107310.01      2339079.00      7107010.00
      2338979.04      7106960.02
#Sta/Elev= 30
  4668.1  695.95  4710.3  694.96  4731.4  694.71  4752.4  694.01  4763.0  694.13
  4773.5  694.00  4784.1  693.55  4815.7  693.34  4826.2  693.54  4836.8  692.14
  4857.9  692.04  4878.9  688.76  4900.0  689.00  4910.6  688.27  4921.1  688.84
  4963.3  688.29  4973.8  685.91  4992.7  685.82  4996.3  685.24  4996.6  684.74
  5000.1  684.74  5000.3  685.24  5006.7  686.20  5015.1  688.41  5020.7  687.95
  5029.1  692.18  5037.4  694.80  5051.4  695.10  5073.8  696.08  5096.1  696.11
#Mann=3,-1,0
  4668.1    0.05       0  4996.3    0.04       0  5000.3    0.05       0
Bank Sta=4996.3,5000.3
Exp/Cntr=0.3,0.1

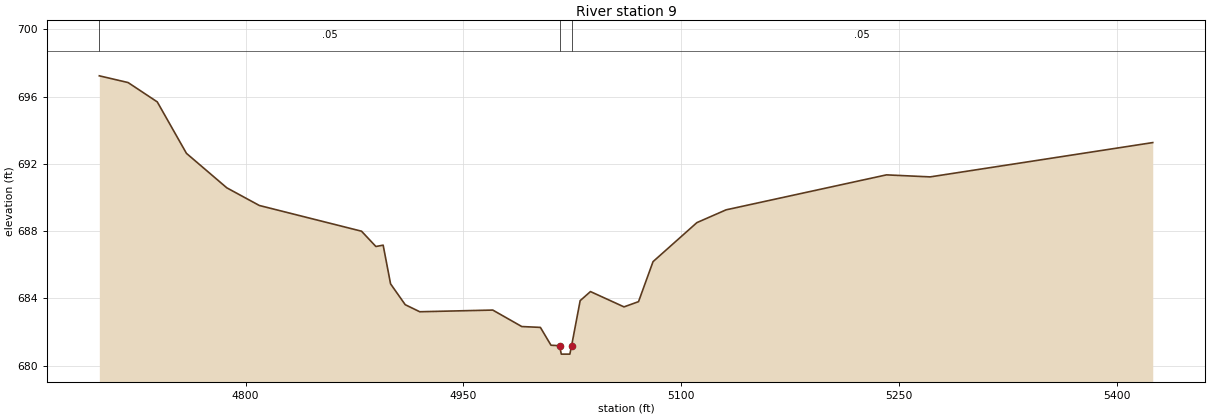
Type RM Length L Ch R = 1,9,0,0,0
BEGIN DESCRIPTION:
Hog Trib 5 0.5
END DESCRIPTION:
XS GIS Cut Line= 4
      2339678.73      7106843.61      2339400.57      7106817.00
      2339378.60      7106818.75      2338956.45      7106777.88
#Sta/Elev= 30
  4699.2  697.24  4719.0  696.84  4739.1  695.69  4759.2  692.63  4787.0  690.58
  4809.4  689.53  4879.8  688.00  4889.7  687.09  4894.7  687.17  4899.8  684.87
  4909.9  683.63  4919.9  683.21  4970.2  683.31  4990.2  682.33  5003.0  682.28
  5010.3  681.22  5016.2  681.19  5017.4  680.69  5023.3  680.69  5024.5  681.19
  5030.4  683.87  5037.5  684.41  5060.6  683.50  5070.6  683.81  5080.6  686.19
  5110.8  688.51  5130.9  689.27  5241.4  691.35  5271.5  691.23  5424.8  693.27
#Mann=3,-1,0
  4699.2    0.05       0  5016.2    0.04       0  5024.5    0.05       0
Bank Sta=5016.2,5024.5
Exp/Cntr=0.3,0.1

Chan Stop Cuts=-1