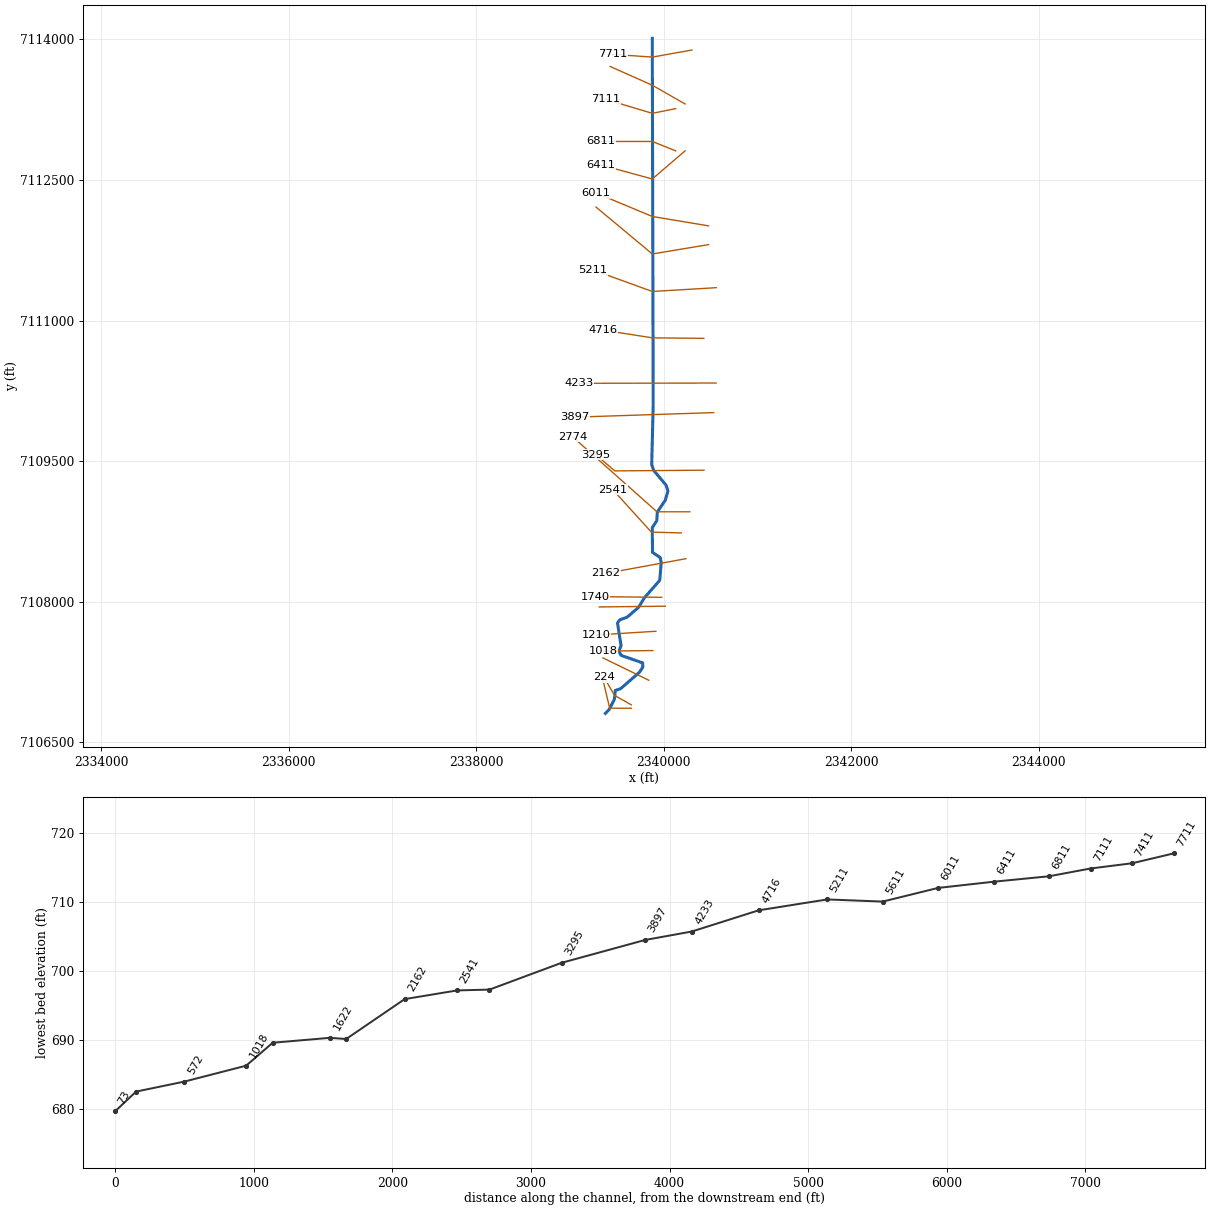
--- Hog Branch Tributary 6.prj (project) ---

Proj Title=Hog Branch Tributary 6 Base Level Engineering
Current Plan=p01
Default Exp/Contr=0.3,0.1
English Units
Geom File=g01
Flow File=f01
Plan File=p01
Y Axis Title=Elevation
X Axis Title(PF)=Main Channel Distance
X Axis Title(XS)=Station
BEGIN DESCRIPTION:
Hog Branch Tributary 6
END DESCRIPTION:
DSS Export Rating Curves= 0
DSS Export Rating Curve Sorted= 0
DSS Export Volume Flow Curves= 0
DXF OffsetX= 0
DXF OffsetY= 0
DXF ScaleX= 1
DXF ScaleY= 10

--- Hog Branch Tributary 6.p01 (plan) ---

Plan Title=Multiple Run
Short Identifier=Multiple
Geom File=g01
Flow File=f01
Subcritical Flow
K Sum by GR= 0
Std Step Tol= 0.01
Critical Tol= 0.01
Num of Std Step Trials= 20
Max Error Tol= 0.3
Flow Tol Ratio= 0.001
Split Flow NTrial= 30
Split Flow Tol= 0.02
Split Flow Ratio= 0.02
Log Output Level= 0
Friction Slope Method= 1
Unsteady Friction Slope Method= 2
Unsteady Bridges Friction Slope Method= 1
Parabolic Critical Depth
Global Vel Dist=  1 , 1 , 1
Global Log Level= 0
CheckData=True
Encroach Param= -1, 0, 0, 0
BEGIN DESCRIPTION:
Multiple Run
END DESCRIPTION:

--- Hog Branch Tributary 6.f01 (steady flow) ---

Flow Title=Multiple
Program Version=4.10
Number of Profiles= 7
Profile Names=10-year,25-year,50-year,1pct_min,100-year,1pct_plu,500-year
River Rch & RM=Hog Branch Tribu,Reach-1         ,7711
     334     438     519     306     610    1217     844
River Rch & RM=Hog Branch Tribu,Reach-1         ,4716
     613     832    1011     609    1215    2424    1759
River Rch & RM=Hog Branch Tribu,Reach-1         ,2162
     986    1379    1709    1049    2092    4175    3147
Boundary for River Rch & Prof#=Hog Branch Tribu,Reach-1         , 1
Up Type= 0
Dn Type= 3
Dn Slope=0.02
Boundary for River Rch & Prof#=Hog Branch Tribu,Reach-1         , 2
Up Type= 0
Dn Type= 3
Dn Slope=0.02
Boundary for River Rch & Prof#=Hog Branch Tribu,Reach-1         , 3
Up Type= 0
Dn Type= 3
Dn Slope=0.02
Boundary for River Rch & Prof#=Hog Branch Tribu,Reach-1         , 4
Up Type= 0
Dn Type= 3
Dn Slope=0.02
Boundary for River Rch & Prof#=Hog Branch Tribu,Reach-1         , 5
Up Type= 0
Dn Type= 3
Dn Slope=0.02
Boundary for River Rch & Prof#=Hog Branch Tribu,Reach-1         , 6
Up Type= 0
Dn Type= 3
Dn Slope=0.02
Boundary for River Rch & Prof#=Hog Branch Tribu,Reach-1         , 7
Up Type= 0
Dn Type= 3
Dn Slope=0.02
DSS Import GetInterval= 0
DSS Import GetPeak= 0
DSS Import FillOption= 0

--- Hog Branch Tributary 6.g01 (geometry) ---

Geom Title=Existing Conditions

River Reach=Hog Branch Tribu,Reach-1
Reach XY= 30
      2339879.00      7114010.00      2339888.49      7110102.26
      2339872.78      7109460.49      2339896.63      7109397.91
      2340026.16      7109243.59      2340045.59      7109182.28
      2340018.09      7109083.76      2339932.83      7108958.42
      2339926.65      7108865.97      2339879.00      7108790.00
      2339881.37      7108527.01      2339963.50      7108471.65
      2339974.01      7108419.40      2339958.59      7108229.36
      2339794.45      7108042.85      2339730.68      7107938.67
      2339610.72      7107836.46      2339530.67      7107806.73
      2339507.92      7107773.74      2339545.94      7107533.25
      2339522.41      7107472.75      2339546.05      7107428.51
      2339776.04      7107348.67      2339777.67      7107302.86
      2339740.87      7107247.44      2339541.94      7107073.76
      2339484.26      7107054.53      2339475.15      7106961.65
      2339421.09      7106853.85      2339379.00      7106810.00

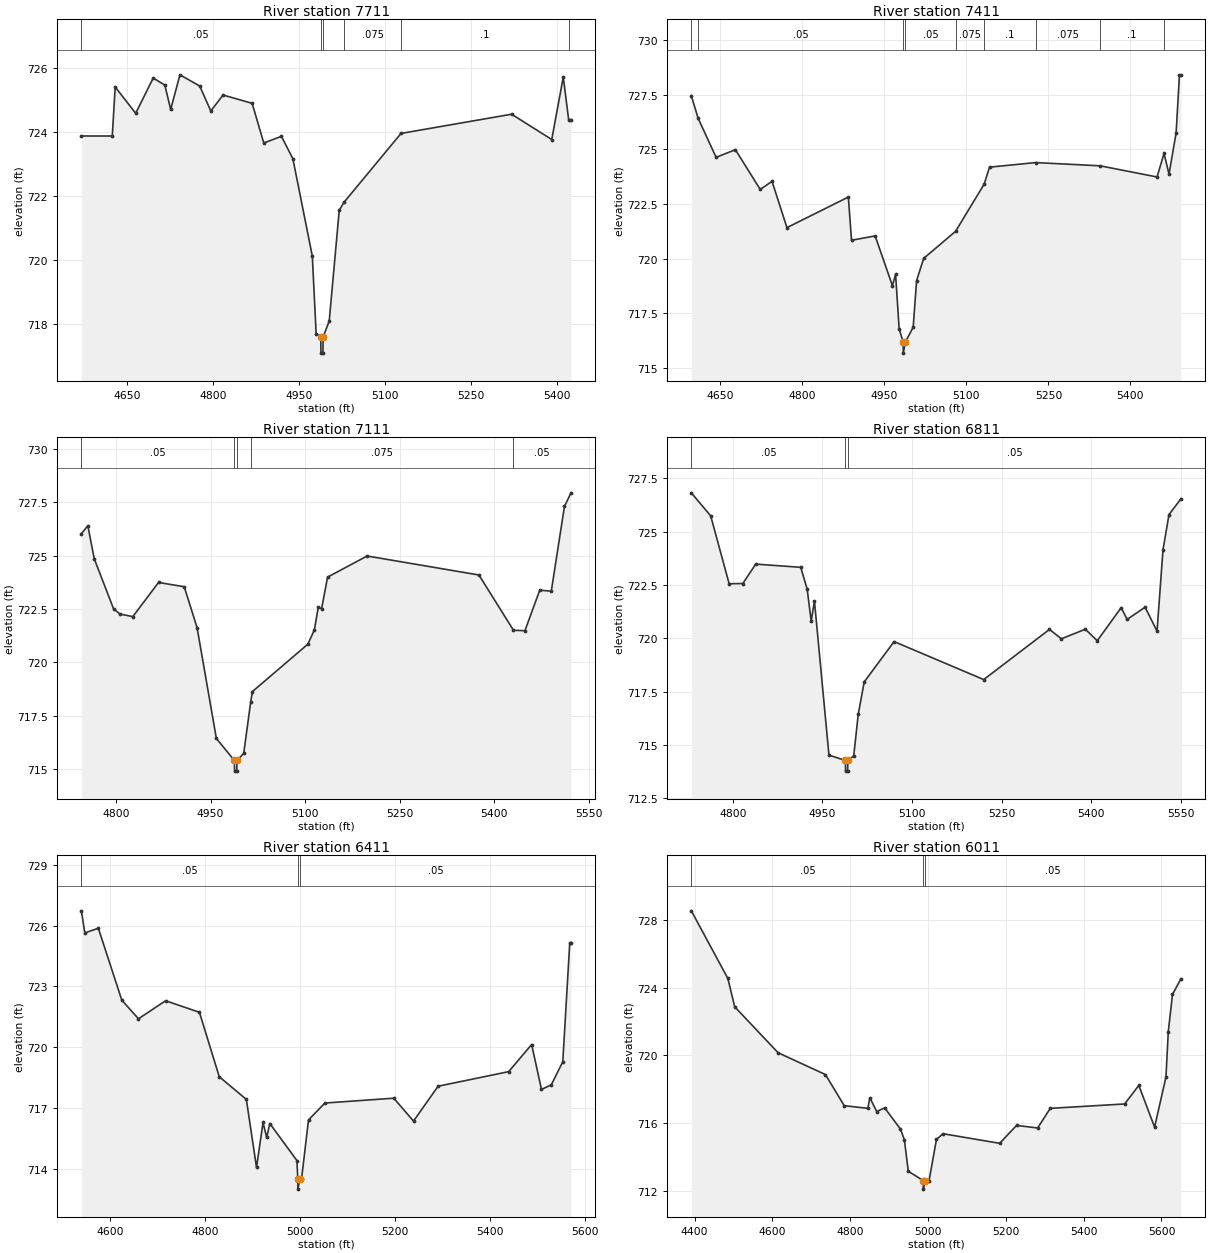
Type RM Length L Ch R = 1,7711,300,300,300
BEGIN DESCRIPTION:
MDE S 115 8.0
END DESCRIPTION:
XS GIS Cut Line= 3
      2340302.36      7113885.27      2339879.00      7113810.00
      2339455.50      7113839.13
#Sta/Elev= 30
  4570.0  723.88  4623.9  723.88  4629.0  725.41  4664.8  724.59  4695.3  725.69
  4715.6  725.47  4725.8  724.71  4742.0  725.79  4776.5  725.44  4795.9  724.66
  4817.2  725.16  4868.0  724.90  4888.3  723.66  4919.1  723.87  4939.1  723.17
  4973.0  720.13  4979.7  717.71  4987.8  717.60  4988.1  717.10  4991.6  717.10
  4991.8  717.60  5002.5  718.10  5020.0  721.56  5028.3  721.81  5127.8  723.96
  5320.8  724.56  5390.9  723.77  5411.0  725.72  5420.4  724.39  5424.5  724.39
#Mann=6,-1,0
  4570.0    0.05       0  4987.8   0.033       0  4991.8    0.05       0
  5028.3   0.075       0  5127.8     0.1       0  5420.4   0.075       0
Bank Sta=4987.8,4991.8
Exp/Cntr=0.3,0.1

Type RM Length L Ch R = 1,7411,300,300,300
BEGIN DESCRIPTION:
MDE S 115 7.0
END DESCRIPTION:
XS GIS Cut Line= 3
      2340228.99      7113310.01      2339879.00      7113510.00
      2339429.04      7113709.98
#Sta/Elev= 30
  4596.9  727.46  4609.5  726.42  4642.2  724.64  4677.5  724.99  4722.9  723.17
  4744.5  723.54  4771.8  721.42  4884.1  722.82  4889.9  720.84  4933.1  721.04
  4964.7  718.76  4970.5  719.28  4977.0  716.79  4984.3  716.17  4984.6  715.67
  4988.3  716.17  5002.7  716.86  5008.9  718.99  5021.9  720.01  5080.2  721.25
  5132.5  723.41  5142.3  724.19  5226.8  724.40  5344.9  724.25  5448.7  723.74
  5461.5  724.82  5470.6  723.87  5483.6  725.76  5489.7  728.42  5492.4  728.42
#Mann=9,-1,0
  4596.9   0.075       0  4609.5    0.05       0  4984.3   0.033       0
  4988.3    0.05       0  5080.2   0.075       0  5132.5     0.1       0
  5226.8   0.075       0  5344.9     0.1       0  5461.5    0.05       0
Bank Sta=4984.3,4988.3
Exp/Cntr=0.3,0.1

Type RM Length L Ch R = 1,7111,300,300,300
BEGIN DESCRIPTION:
MDE S 115 6.0
END DESCRIPTION:
XS GIS Cut Line= 3
      2340129.05      7113260.01      2339879.00      7113210.00
      2339379.01      7113360.00
#Sta/Elev= 30
  4745.0  726.03  4755.2  726.41  4765.4  724.86  4796.0  722.52  4806.2  722.27
  4826.6  722.15  4867.4  723.75  4908.2  723.55  4928.6  721.63  4959.2  716.44
  4987.8  715.41  4988.1  714.91  4991.6  714.91  4991.8  715.41  5002.6  715.74
  5013.7  718.16  5016.5  718.64  5104.4  720.86  5114.8  721.53  5120.9  722.59
  5126.2  722.52  5135.7  724.00  5198.4  724.99  5375.9  724.10  5430.7  721.51
  5448.9  721.49  5472.4  723.39  5490.7  723.34  5511.6  727.31  5522.0  727.95
#Mann=5,-1,0
  4745.0    0.05       0  4987.8   0.033       0  4991.8    0.05       0
  5013.7   0.075       0  5430.7    0.05       0
Bank Sta=4987.8,4991.8
Exp/Cntr=0.3,0.1

Type RM Length L Ch R = 1,6811,400,400,400
BEGIN DESCRIPTION:
MDE S 115 5.0
END DESCRIPTION:
XS GIS Cut Line= 3
      2340129.04      7112809.98      2339879.00      7112910.00
      2339329.00      7112910.00
#Sta/Elev= 30
  4730.7  726.82  4763.1  725.74  4794.0  722.56  4816.9  722.57  4838.4  723.48
  4913.8  723.33  4924.6  722.30  4931.3  720.80  4936.7  721.76  4961.0  714.53
  4988.6  714.28  4988.8  713.78  4992.3  713.78  4992.6  714.28  5002.5  714.50
  5010.0  716.44  5020.0  717.96  5070.0  719.85  5220.0  718.07  5330.0  720.42
  5350.0  719.98  5390.0  720.43  5410.0  719.89  5450.0  721.44  5460.0  720.89
  5490.0  721.46  5510.0  720.34  5520.0  724.15  5530.0  725.80  5550.0  726.54
#Mann=3,-1,0
  4730.7    0.05       0  4988.6    0.04       0  4992.6    0.05       0
Bank Sta=4988.6,4992.6
Exp/Cntr=0.3,0.1

Type RM Length L Ch R = 1,6411,400,400,400
BEGIN DESCRIPTION:
MDE S 115 4.0
END DESCRIPTION:
XS GIS Cut Line= 3
      2340229.02      7112810.01      2339879.00      7112510.00
      2339328.99      7112660.00
#Sta/Elev= 30
  4539.0  726.73  4546.2  725.64  4574.7  725.87  4624.1  722.32  4659.2  721.40
  4716.3  722.29  4787.6  721.72  4829.3  718.54  4886.4  717.42  4907.8  714.06
  4921.5  716.28  4929.2  715.54  4935.8  716.23  4992.9  714.40  4994.7  713.49
  4995.0  712.99  4998.7  713.49  5002.6  713.49  5017.3  716.41  5051.8  717.24
  5196.9  717.48  5238.4  716.35  5290.2  718.07  5438.8  718.79  5487.2  720.13
  5507.9  717.91  5528.6  718.14  5552.8  719.28  5567.5  725.16  5570.1  725.16
#Mann=3,-1,0
  4539.0    0.05       0  4994.7    0.04       0  4998.7    0.05       0
Bank Sta=4994.7,4998.7
Exp/Cntr=0.3,0.1

Type RM Length L Ch R = 1,6011,400,400,400
BEGIN DESCRIPTION:
MDE S 115 3.0
END DESCRIPTION:
XS GIS Cut Line= 3
      2340479.02      7112010.00      2339879.00      7112110.00
      2339279.00      7112360.00
#Sta/Elev= 30
  4391.7  728.56  4485.5  724.56  4503.2  722.88  4614.8  720.16  4736.4  718.87
  4784.6  717.03  4845.4  716.87  4850.5  717.50  4868.2  716.68  4888.5  716.90
  4929.0  715.65  4939.2  715.02  4949.3  713.15  4987.9  712.59  4988.1  712.09
  4991.9  712.59  5002.7  712.60  5021.7  715.03  5038.5  715.37  5184.2  714.80
  5227.5  715.86  5281.7  715.71  5314.2  716.87  5505.4  717.13  5541.7  718.23
  5582.3  715.76  5611.5  718.72  5617.5  721.41  5628.3  723.61  5650.0  724.54
#Mann=3,-1,0
  4391.7    0.05       0  4987.9   0.033       0  4991.9    0.05       0
Bank Sta=4987.9,4991.9
Exp/Cntr=0.3,0.1

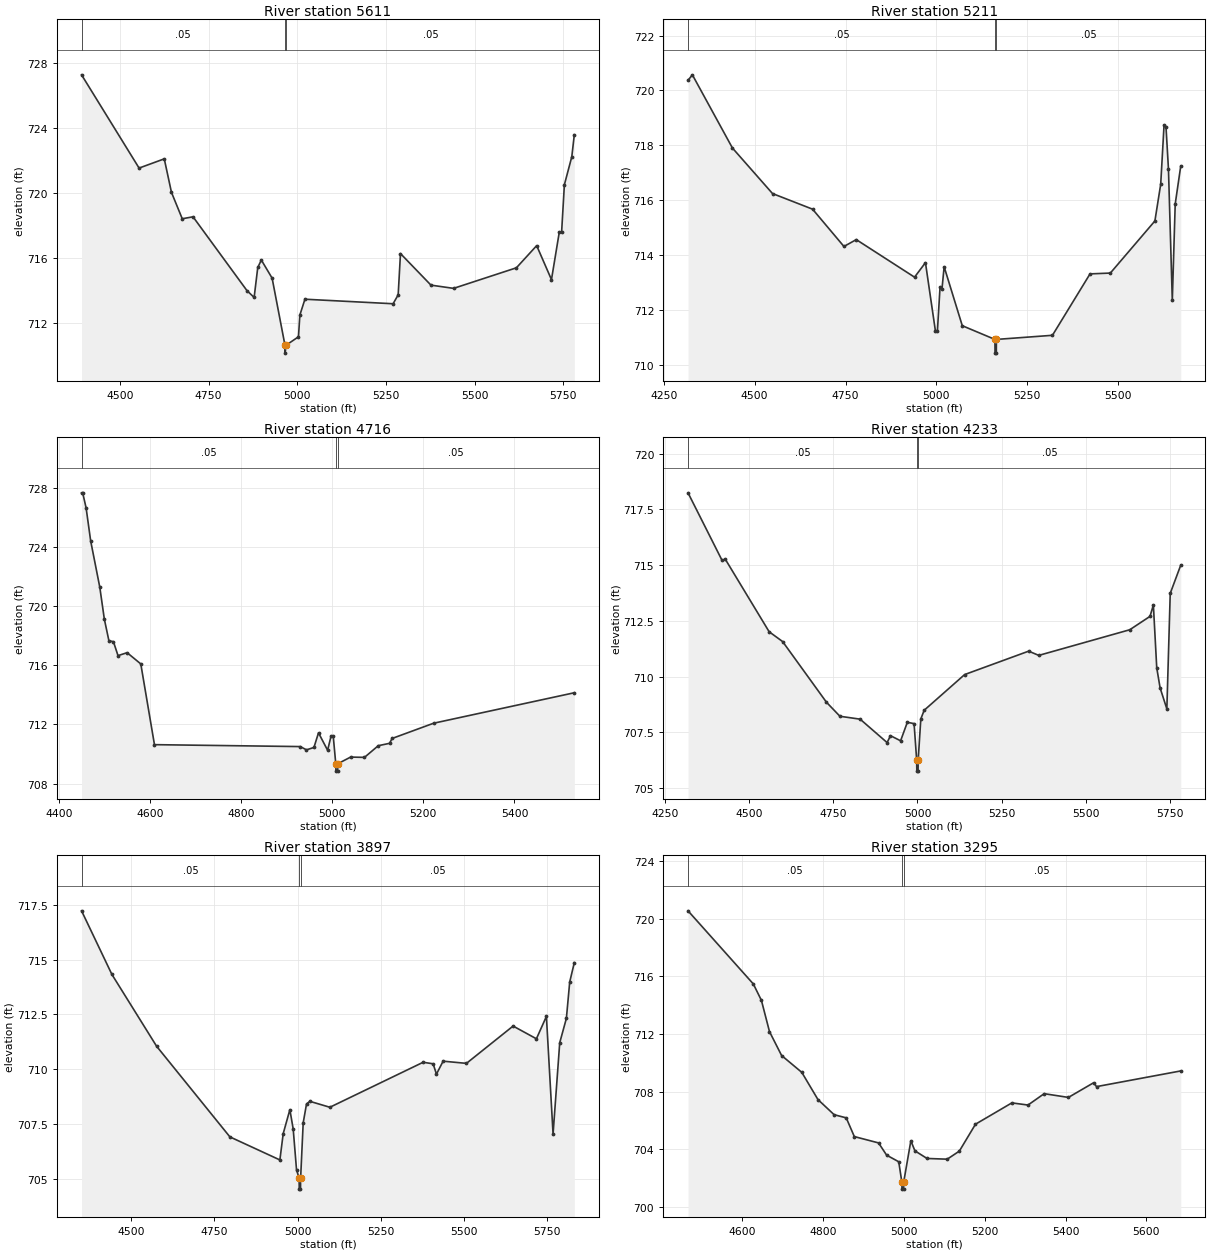
Type RM Length L Ch R = 1,5611,400,400,400
BEGIN DESCRIPTION:
MDE S 115 2.0
END DESCRIPTION:
XS GIS Cut Line= 3
      2340479.02      7111810.00      2339879.00      7111710.00
      2339279.02      7112209.98
#Sta/Elev= 30
  4391.7  727.30  4553.9  721.54  4624.9  722.11  4645.2  720.04  4675.6  718.41
  4706.0  718.53  4858.1  713.97  4878.3  713.55  4888.5  715.40  4898.6  715.86
  4929.0  714.74  4965.1  710.61  4965.3  710.11  4969.1  710.61  5003.3  711.12
  5007.2  712.46  5021.5  713.44  5270.1  713.16  5284.4  713.71  5290.9  716.26
  5376.8  714.31  5440.6  714.11  5617.7  715.38  5674.9  716.75  5716.6  714.65
  5738.7  717.59  5745.2  717.58  5753.0  720.51  5773.9  722.24  5781.0  723.60
#Mann=3,-1,0
  4391.7    0.05       0  4965.1    0.04       0  4969.1    0.05       0
Bank Sta=4965.1,4969.1
Exp/Cntr=0.3,0.1

Type RM Length L Ch R = 1,5211,495,495,495
BEGIN DESCRIPTION:
MDE S 115 1.0
END DESCRIPTION:
XS GIS Cut Line= 3
      2340561.00      7111350.47      2339879.00      7111310.00
      2339247.14      7111539.35
#Sta/Elev= 30
  4316.8  720.37  4328.8  720.57  4439.0  717.90  4549.2  716.24  4659.4  715.67
  4745.7  714.31  4779.6  714.56  4939.9  713.19  4969.9  713.72  4997.5  711.21
  5002.7  711.21  5010.0  712.82  5015.3  712.75  5021.3  713.57  5071.2  711.42
  5161.0  710.92  5161.3  710.42  5164.8  710.42  5165.0  710.92  5319.2  711.07
  5422.6  713.31  5478.5  713.34  5601.0  715.24  5617.0  716.58  5626.2  718.74
  5631.6  718.66  5638.3  717.14  5648.9  712.34  5656.9  715.86  5672.2  717.25
#Mann=3,-1,0
  4316.8    0.05       0  5161.0   0.033       0  5165.0    0.05       0
Bank Sta=5161,5165
Exp/Cntr=0.3,0.1

Type RM Length L Ch R = 1,4716,483,483,483
BEGIN DESCRIPTION:
Hog Branch Tributary 6 9.0
END DESCRIPTION:
XS GIS Cut Line= 3
      2340428.97      7110810.00      2339879.19      7110815.58
      2339354.00      7110897.83
#Sta/Elev= 30
  4450.0  727.66  4452.5  727.66  4460.0  726.64  4470.0  724.41  4490.0  721.28
  4500.0  719.12  4510.0  717.66  4520.0  717.59  4530.0  716.65  4550.0  716.85
  4580.0  716.09  4610.0  710.63  4930.0  710.50  4943.6  710.28  4960.0  710.44
  4970.0  711.43  4990.0  710.25  4997.4  711.19  5002.4  711.19  5007.9  709.34
  5008.3  708.84  5011.9  708.84  5012.3  709.34  5040.5  709.79  5070.9  709.77
  5101.2  710.56  5125.9  710.72  5131.6  711.05  5222.7  712.08  5531.4  714.14
#Mann=3,-1,0
  4450.0    0.05       0  5007.9   0.033       0  5012.3    0.05       0
Bank Sta=5007.9,5012.3
Exp/Cntr=0.3,0.1

Type RM Length L Ch R = 1,4233,336,336,336
BEGIN DESCRIPTION:
Mapping XS 7d57a346
END DESCRIPTION:
XS GIS Cut Line= 2
      2340559.70      7110333.43      2339097.70      7110330.39
#Sta/Elev= 30
  4319.3  718.24  4420.0  715.22  4430.0  715.26  4560.0  712.01  4600.0  711.57
  4730.0  708.85  4770.0  708.22  4830.0  708.09  4910.0  707.04  4920.0  707.35
  4950.0  707.12  4970.0  707.95  4990.0  707.89  4997.7  706.26  4998.2  705.76
  5001.8  705.76  5002.2  706.26  5010.0  708.10  5020.0  708.49  5140.0  710.09
  5330.0  711.14  5360.0  710.95  5630.0  712.10  5690.0  712.70  5700.0  713.21
  5710.0  710.39  5720.0  709.49  5740.0  708.55  5750.0  713.73  5781.3  715.00
#Mann=3,-1,0
  4319.3    0.05       0  4997.7   0.033       0  5002.2    0.05       0
Bank Sta=4997.7,5002.2
Exp/Cntr=0.3,0.1

Type RM Length L Ch R = 1,3897,602,602,602
BEGIN DESCRIPTION:
Mapping XS 08b25a9f
END DESCRIPTION:
XS GIS Cut Line= 2
      2340534.27      7110018.00      2339055.26      7109969.75
#Sta/Elev= 30
  4351.3  717.22  4442.5  714.32  4576.7  711.05  4796.8  706.92  4946.9  705.87
  4956.9  707.07  4976.9  708.16  4986.9  707.28  4996.9  705.42  5004.6  705.04
  5005.1  704.54  5008.8  704.54  5009.2  705.04  5016.9  707.56  5026.9  708.42
  5036.9  708.54  5097.0  708.27  5377.1  710.32  5407.1  710.25  5417.1  709.78
  5437.1  710.37  5507.2  710.27  5647.3  711.97  5717.3  711.39  5747.3  712.41
  5767.3  707.05  5787.3  711.21  5807.3  712.32  5817.3  713.98  5831.1  714.86
#Mann=3,-1,0
  4351.3    0.05       0  5004.6   0.033       0  5009.2    0.05       0
Bank Sta=5004.6,5009.2
Exp/Cntr=0.3,0.1

Type RM Length L Ch R = 1,3295,521,521,521
BEGIN DESCRIPTION:
Mapping XS 2ad83fd6
END DESCRIPTION:
XS GIS Cut Line= 3
      2340430.67      7109403.84      2339478.37      7109396.30
      2339275.36      7109570.60
#Sta/Elev= 30
  4465.3  720.56  4627.0  715.48  4647.0  714.34  4667.0  712.17  4697.0  710.51
  4747.0  709.34  4787.0  707.45  4827.0  706.40  4857.0  706.18  4877.0  704.88
  4937.0  704.44  4957.0  703.59  4987.0  703.13  4994.6  701.73  4995.1  701.23
  4998.8  701.23  4999.3  701.73  5017.0  704.59  5027.0  703.89  5057.0  703.36
  5107.0  703.31  5137.0  703.87  5177.0  705.74  5267.0  707.22  5307.0  707.07
  5347.0  707.86  5407.0  707.60  5469.5  708.62  5476.6  708.35  5685.2  709.44
#Mann=3,-1,0
  4465.3    0.05       0  4994.6    0.04       0  4999.3    0.05       0
Bank Sta=4994.6,4999.3
Exp/Cntr=0.3,0.1

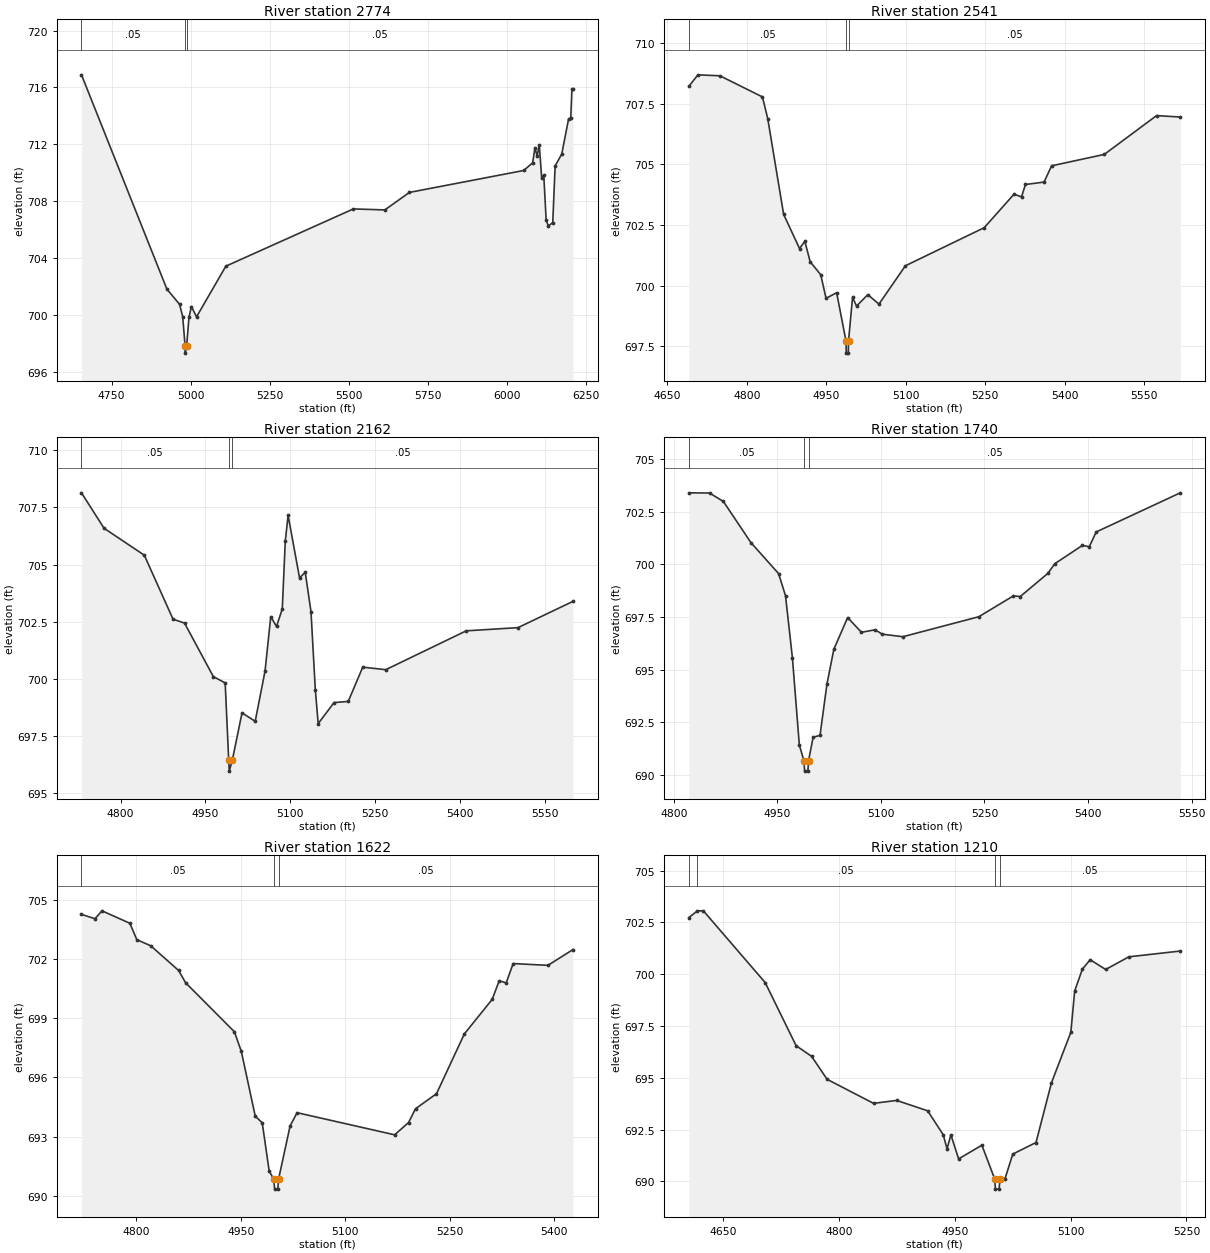
Type RM Length L Ch R = 1,2774,233,233,233
BEGIN DESCRIPTION:
Hog Branch Tributary 6 5.0
END DESCRIPTION:
XS GIS Cut Line= 3
      2340279.01      7108960.00      2339929.00      7108960.00
      2339028.98      7109760.02
#Sta/Elev= 30
  4654.6  716.89  4924.6  701.84  4964.6  700.77  4974.6  699.91  4982.2  697.84
  4982.8  697.34  4987.0  697.84  4994.6  699.87  5002.1  700.61  5018.4  699.89
  5111.2  703.45  5514.3  707.47  5613.8  707.40  5691.6  708.63  6052.8  710.17
  6081.3  710.71  6088.4  711.76  6095.5  711.18  6102.2  711.98  6109.7  709.67
  6116.4  709.84  6123.9  706.71  6130.6  706.27  6144.8  706.51  6152.3  710.49
  6173.2  711.32  6195.0  713.81  6201.7  713.83  6205.4  715.89  6208.8  715.89
#Mann=3,-1,0
  4654.6    0.05       0  4982.2    0.04       0  4987.0    0.05       0
Bank Sta=4982.2,4987
Exp/Cntr=0.3,0.1

Type RM Length L Ch R = 1,2541,379,379,379
BEGIN DESCRIPTION:
Mapping XS 41a1cb55
END DESCRIPTION:
XS GIS Cut Line= 3
      2340187.81      7108734.40      2339869.09      7108743.70
      2339459.78      7109193.49
#Sta/Elev= 30
  4690.7  708.21  4707.9  708.69  4749.5  708.65  4829.6  707.78  4839.6  706.89
  4869.6  702.94  4899.6  701.53  4909.6  701.83  4919.6  700.99  4939.6  700.45
  4949.6  699.48  4969.6  699.71  4987.2  697.72  4987.8  697.22  4991.5  697.22
  4992.0  697.72  4999.6  699.52  5007.1  699.16  5028.4  699.63  5049.4  699.24
  5099.2  700.82  5247.9  702.39  5304.1  703.77  5318.3  703.66  5325.7  704.17
  5360.8  704.27  5375.0  704.94  5474.4  705.41  5573.0  707.01  5617.7  706.95
#Mann=3,-1,0
  4690.7    0.05       0  4987.2    0.04       0  4992.0    0.05       0
Bank Sta=4987.2,4992
Exp/Cntr=0.3,0.1

Type RM Length L Ch R = 1,2162,422,422,422
BEGIN DESCRIPTION:
Mapping XS ff207c80
END DESCRIPTION:
XS GIS Cut Line= 2
      2340238.25      7108460.10      2339383.33      7108303.16
#Sta/Elev= 30
  4730.7  708.14  4770.6  706.59  4841.8  705.41  4892.6  702.61  4912.9  702.44
  4963.8  700.10  4984.8  699.82  4991.0  696.46  4992.0  695.96  4997.6  696.46
  5014.6  698.51  5037.9  698.14  5055.3  700.34  5065.4  702.72  5075.6  702.29
  5085.8  703.06  5091.1  706.03  5096.1  707.15  5116.3  704.42  5126.4  704.66
  5136.6  702.93  5144.2  699.53  5149.3  698.04  5177.3  698.96  5202.4  699.01
  5228.1  700.51  5268.8  700.40  5411.1  702.10  5502.6  702.24  5599.9  703.39
#Mann=3,-1,0
  4730.7    0.05       0  4991.0    0.04       0  4997.6    0.05       0
Bank Sta=4991,4997.6
Exp/Cntr=0.3,0.1

Type RM Length L Ch R = 1,1740,118,118,118
BEGIN DESCRIPTION:
Mapping XS 71b566e1
END DESCRIPTION:
XS GIS Cut Line= 2
      2339979.11      7108048.03      2339267.25      7108054.97
#Sta/Elev= 30
  4821.7  703.40  4851.8  703.39  4871.8  702.99  4911.8  701.03  4951.8  699.56
  4961.8  698.51  4971.8  695.56  4981.8  691.42  4988.4  690.67  4989.5  690.17
  4994.2  690.17  4995.2  690.67  5001.8  691.78  5011.8  691.87  5021.8  694.30
  5031.8  695.96  5051.8  697.47  5071.8  696.77  5091.8  696.89  5101.8  696.68
  5131.8  696.56  5241.8  697.51  5291.8  698.50  5301.8  698.47  5341.8  699.57
  5351.8  700.03  5391.8  700.90  5401.8  700.84  5411.8  701.54  5533.6  703.40
#Mann=3,-1,0
  4821.7    0.05       0  4988.4   0.033       0  4995.2    0.05       0
Bank Sta=4988.4,4995.2
Exp/Cntr=0.3,0.1

Type RM Length L Ch R = 1,1622,412,412,412
BEGIN DESCRIPTION:
Mapping XS 27f658fe
END DESCRIPTION:
XS GIS Cut Line= 2
      2340018.42      7107953.26      2339313.06      7107945.11
#Sta/Elev= 30
  4721.3  704.25  4740.7  704.03  4750.7  704.43  4790.7  703.80  4800.7  702.97
  4820.7  702.66  4860.7  701.41  4870.7  700.79  4940.7  698.31  4950.7  697.31
  4970.7  694.03  4980.7  693.70  4990.7  691.25  4997.3  690.84  4998.4  690.34
  5003.1  690.34  5004.1  690.84  5020.7  693.54  5030.7  694.21  5170.7  693.09
  5190.7  693.71  5200.7  694.41  5230.8  695.17  5270.8  698.20  5310.8  699.95
  5320.8  700.89  5330.8  700.78  5340.8  701.76  5390.8  701.67  5426.7  702.47
#Mann=3,-1,0
  4721.3    0.05       0  4997.3   0.033       0  5004.1    0.05       0
Bank Sta=4997.3,5004.1
Exp/Cntr=0.3,0.1

Type RM Length L Ch R = 1,1210,192,192,192
BEGIN DESCRIPTION:
Mapping XS be3217a9
END DESCRIPTION:
XS GIS Cut Line= 2
      2339917.72      7107685.87      2339282.56      7107646.15
#Sta/Elev= 30
  4605.6  702.73  4616.8  703.06  4624.5  703.06  4704.5  699.60  4744.6  696.55
  4764.6  696.04  4784.7  694.93  4844.8  693.77  4874.8  693.91  4914.9  693.41
  4935.0  692.26  4940.0  691.58  4945.0  692.25  4955.0  691.09  4985.1  691.75
  5001.6  690.13  5002.7  689.63  5007.4  689.63  5008.5  690.13  5015.1  690.14
  5025.1  691.32  5055.2  691.88  5075.2  694.76  5100.3  697.20  5105.3  699.20
  5115.3  700.25  5125.3  700.70  5145.4  700.23  5175.4  700.84  5242.0  701.12
#Mann=4,-1,0
  4605.6   0.075       0  4616.8    0.05       0  5001.6    0.04       0
  5008.5    0.05       0
Bank Sta=5001.6,5008.5
Exp/Cntr=0.3,0.1

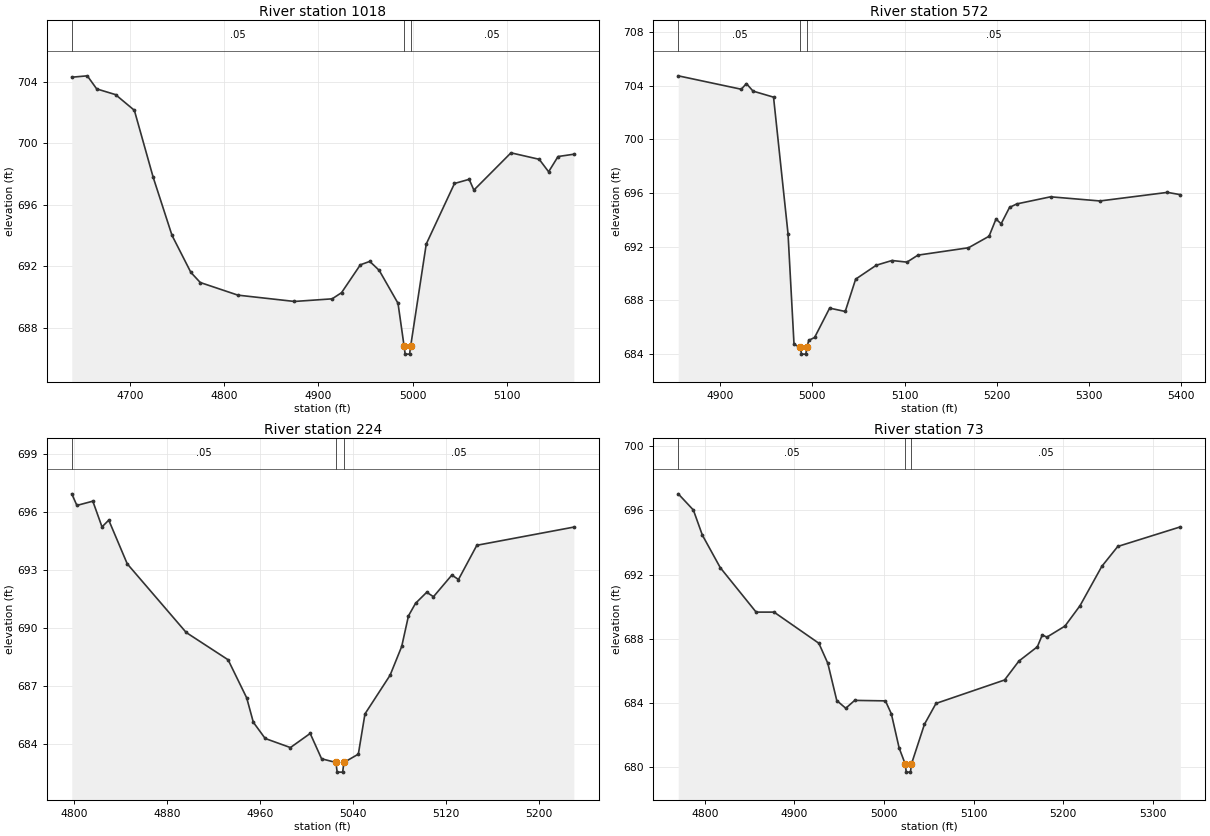
Type RM Length L Ch R = 1,1018,446,446,446
BEGIN DESCRIPTION:
Mapping XS b4316cb5
END DESCRIPTION:
XS GIS Cut Line= 2
      2339885.53      7107479.88      2339352.17      7107473.72
#Sta/Elev= 30
  4638.0  704.28  4654.5  704.37  4664.5  703.52  4684.5  703.15  4704.5  702.13
  4724.5  697.78  4744.5  694.01  4764.5  691.61  4774.5  690.95  4814.5  690.13
  4874.6  689.72  4914.6  689.89  4924.6  690.29  4944.6  692.10  4954.6  692.32
  4964.6  691.74  4984.6  689.60  4991.1  686.80  4992.2  686.30  4996.9  686.30
  4998.0  686.80  5014.6  693.45  5044.6  697.38  5060.2  697.65  5065.2  696.95
  5104.6  699.37  5134.6  698.95  5144.6  698.14  5154.6  699.13  5171.4  699.28
#Mann=3,-1,0
  4638.0    0.05       0  4991.1   0.033       0  4998.0    0.05       0
Bank Sta=4991.1,4998
Exp/Cntr=0.3,0.1

Type RM Length L Ch R = 1,572,348,348,348
BEGIN DESCRIPTION:
Mapping XS cecd000a
END DESCRIPTION:
XS GIS Cut Line= 2
      2339841.87      7107163.36      2339352.60      7107401.60
#Sta/Elev= 30
  4854.6  704.74  4922.9  703.74  4928.5  704.16  4935.7  703.60  4957.9  703.15
  4973.6  692.97  4980.1  684.72  4987.1  684.49  4988.2  683.99  4992.9  683.99
  4994.0  684.49  4996.1  685.02  5002.4  685.23  5018.7  687.42  5035.6  687.17
  5046.9  689.58  5069.3  690.62  5086.3  690.97  5102.5  690.85  5114.4  691.37
  5169.2  691.92  5191.5  692.78  5199.0  694.06  5204.6  693.71  5213.7  694.93
  5221.6  695.19  5258.2  695.72  5311.7  695.41  5384.9  696.05  5398.8  695.88
#Mann=3,-1,0
  4854.6    0.05       0  4987.1    0.04       0  4994.0    0.05       0
Bank Sta=4987.1,4994
Exp/Cntr=0.3,0.1

Type RM Length L Ch R = 1,224,151,151,151
BEGIN DESCRIPTION:
Mapping XS cef0edf1
END DESCRIPTION:
XS GIS Cut Line= 3
      2339654.82      7106901.19      2339476.08      7107001.61
      2339362.68      7107197.88
#Sta/Elev= 30
  4798.3  696.93  4802.7  696.33  4816.4  696.55  4824.3  695.22  4830.1  695.57
  4846.0  693.31  4896.7  689.76  4932.7  688.35  4948.7  686.38  4954.4  685.12
  4964.6  684.28  4986.3  683.81  5003.3  684.54  5013.1  683.23  5025.4  683.04
  5026.5  682.54  5031.2  682.54  5032.3  683.04  5044.7  683.47  5050.4  685.55
  5072.0  687.55  5082.0  689.04  5087.8  690.62  5093.9  691.27  5103.5  691.84
  5109.3  691.61  5125.1  692.73  5130.8  692.50  5146.6  694.27  5230.0  695.21
#Mann=3,-1,0
  4798.3    0.05       0  5025.4   0.033       0  5032.3    0.05       0
Bank Sta=5025.4,5032.3
Exp/Cntr=0.3,0.1

Type RM Length L Ch R = 1,73,0,0,0
BEGIN DESCRIPTION:
Mapping XS 846c60dc
END DESCRIPTION:
XS GIS Cut Line= 3
      2339655.93      7106864.70      2339424.69      7106865.20
      2339348.34      7107185.18
#Sta/Elev= 30
  4770.3  697.03  4787.2  696.02  4797.2  694.46  4817.2  692.43  4857.2  689.66
  4877.2  689.66  4927.2  687.72  4937.2  686.47  4947.2  684.15  4957.2  683.67
  4967.2  684.16  5001.5  684.13  5008.1  683.32  5016.8  681.19  5023.6  680.19
  5024.7  679.69  5029.4  679.69  5030.5  680.19  5045.0  682.67  5057.9  683.97
  5134.4  685.43  5150.4  686.61  5171.0  687.50  5176.5  688.24  5181.6  688.10
  5201.8  688.79  5218.6  690.06  5242.9  692.51  5260.7  693.75  5330.5  694.97
#Mann=3,-1,0
  4770.3    0.05       0  5023.6    0.04       0  5030.5    0.05       0
Bank Sta=5023.6,5030.5
Exp/Cntr=0.3,0.1

Chan Stop Cuts=-1