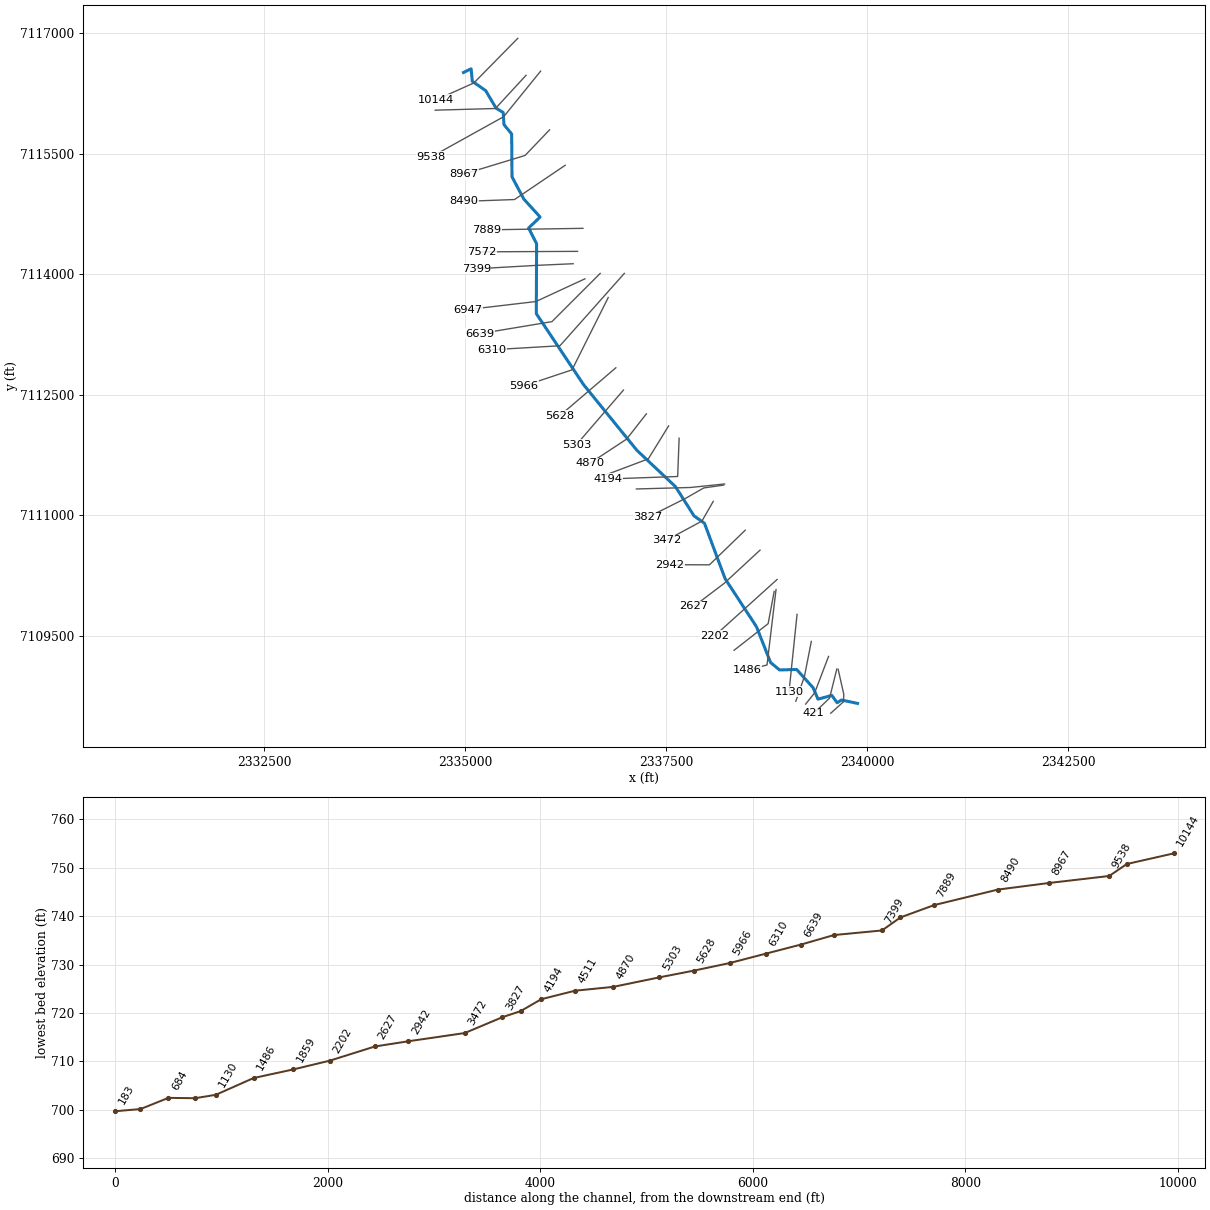
--- Hog Branch Tributary 6_1.prj (project) ---

Proj Title=Hog Branch Tributary 6_1 Base Level Engineering
Current Plan=p01
Default Exp/Contr=0.3,0.1
English Units
Geom File=g01
Flow File=f01
Plan File=p01
BEGIN DESCRIPTION:
Hog Branch Tributary 6_1
END DESCRIPTION:

--- Hog Branch Tributary 6_1.p01 (plan) ---

Plan Title=Multiple Run
Short Identifier=Multiple
Geom File=g01
Flow File=f01
Subcritical Flow
K Sum by GR= 0
Std Step Tol= 0.01
Critical Tol= 0.01
Num of Std Step Trials= 20
Max Error Tol= 0.3
Flow Tol Ratio= 0.001
Split Flow NTrial= 30
Split Flow Tol= 0.02
Split Flow Ratio= 0.02
Log Output Level= 0
Friction Slope Method= 1
Unsteady Friction Slope Method= 2
Unsteady Bridges Friction Slope Method= 1
Parabolic Critical Depth
Global Vel Dist=  1 , 1 , 1
Global Log Level= 0
CheckData=True
Encroach Param= -1, 0, 0, 0
BEGIN DESCRIPTION:
Multiple Run
END DESCRIPTION:

--- Hog Branch Tributary 6_1.f01 (steady flow) ---

Flow Title=Multiple
Number of Profiles=7
Profile Names=10-year,25-year,50-year,1pct_min,100-year,1pct_plu,500-year
River Rch & RM= Hog Branch Tribu,Reach-1,10144
     284     368     433     254     506    1010     692
River Rch & RM= Hog Branch Tribu,Reach-1,6947
     448     598     718     428     855    1705    1213
Boundary for River Rch & Prof#=Hog Branch Tribu,Reach-1,1
Up Type=0
Dn Type=3
Dn Slope=0.005
Boundary for River Rch & Prof#=Hog Branch Tribu,Reach-1,2
Up Type=0
Dn Type=3
Dn Slope=0.005
Boundary for River Rch & Prof#=Hog Branch Tribu,Reach-1,3
Up Type=0
Dn Type=3
Dn Slope=0.005
Boundary for River Rch & Prof#=Hog Branch Tribu,Reach-1,4
Up Type=0
Dn Type=3
Dn Slope=0.005
Boundary for River Rch & Prof#=Hog Branch Tribu,Reach-1,5
Up Type=0
Dn Type=3
Dn Slope=0.005
Boundary for River Rch & Prof#=Hog Branch Tribu,Reach-1,6
Up Type=0
Dn Type=3
Dn Slope=0.005
Boundary for River Rch & Prof#=Hog Branch Tribu,Reach-1,7
Up Type=0
Dn Type=3
Dn Slope=0.005

--- Hog Branch Tributary 6_1.g01 (geometry) ---

Geom Title=Existing Conditions

River Reach=Hog Branch Tribu,Reach-1
Reach XY= 30
      2334979.00      7116510.00      2335073.97      7116555.50
      2335089.47      7116400.18      2335256.14      7116283.84
      2335384.65      7116065.64      2335473.60      7116012.68
      2335482.56      7115861.47      2335578.61      7115744.84
      2335582.75      7115211.55      2335728.79      7114936.02
      2335932.52      7114711.48      2335789.26      7114575.38
      2335888.71      7114378.35      2335884.75      7113510.19
      2336470.76      7112628.14      2337135.01      7111809.52
      2337614.42      7111357.85      2337845.63      7110993.29
      2337975.49      7110901.52      2338232.47      7110211.50
      2338623.15      7109612.29      2338797.72      7109168.20
      2338909.96      7109075.85      2339121.83      7109082.43
      2339326.00      7108855.45      2339387.46      7108712.62
      2339558.74      7108760.10      2339625.43      7108667.93
      2339678.89      7108702.20      2339879.00      7108660.00

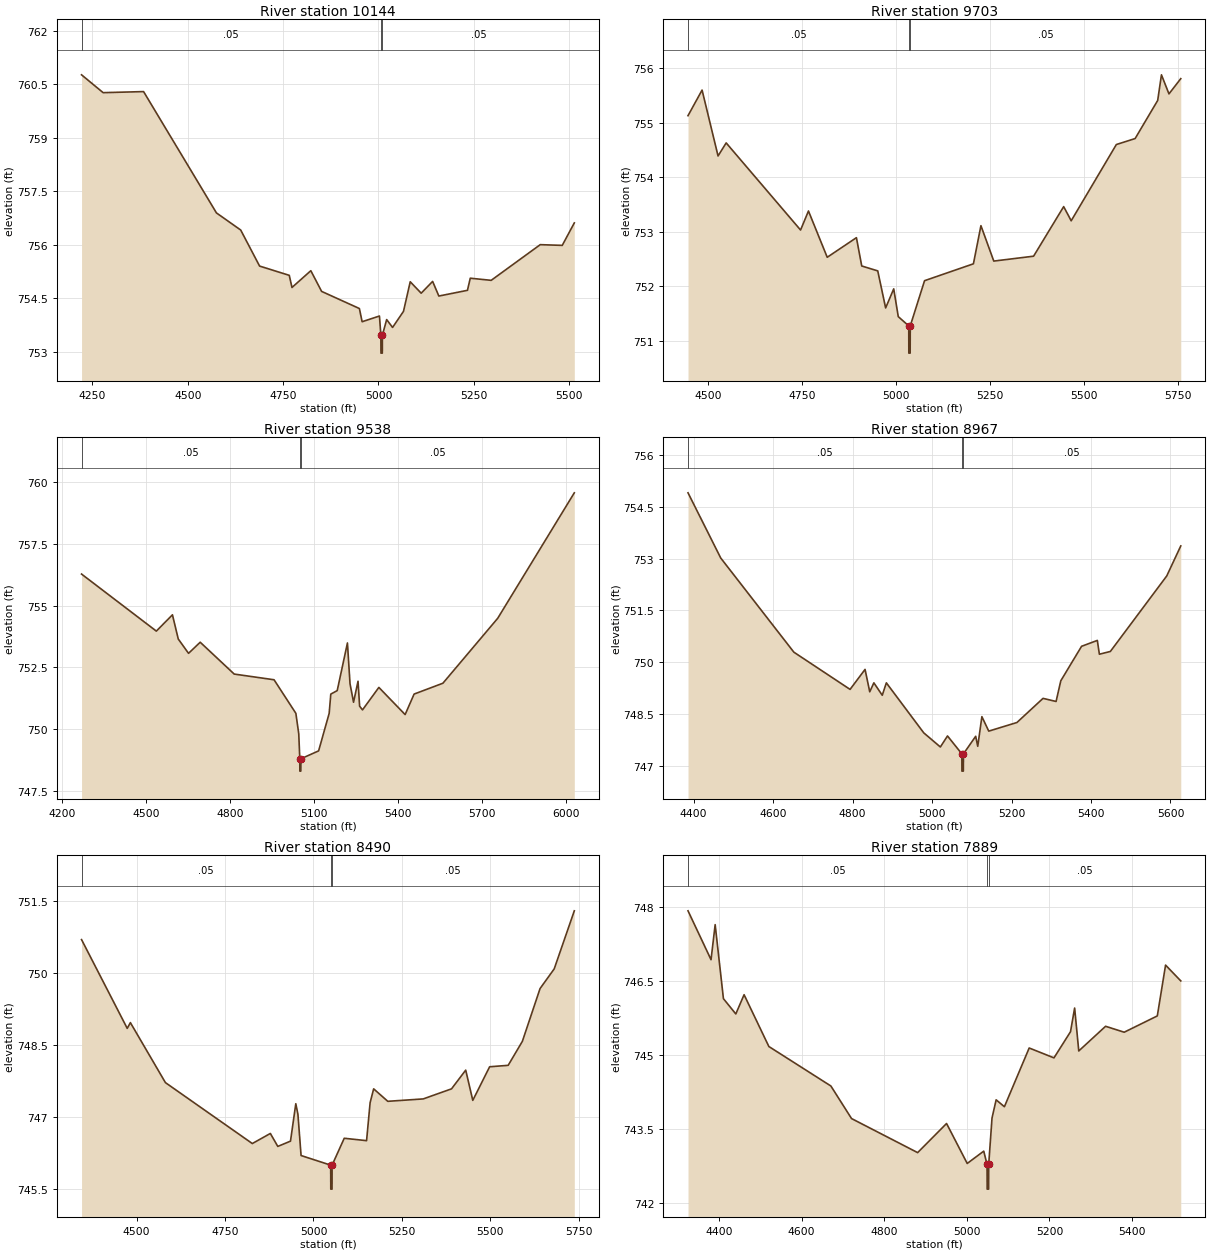
Type RM Length L Ch R = 1,10144,441,441,441
BEGIN DESCRIPTION:
Hog Branch Tributary 6_1 18.0
END DESCRIPTION:
XS GIS Cut Line= 3
      2335653.99      7116934.99      2335108.48      7116379.72
      2334640.21      7116169.49
#Sta/Elev= 30
  4221.6  760.76  4278.2  760.26  4384.2  760.29  4575.2  756.89  4638.8  756.41
  4688.3  755.40  4766.1  755.14  4773.2  754.80  4822.6  755.27  4850.9  754.69
  4949.9  754.21  4957.1  753.84  5002.5  754.00  5006.2  753.46  5006.5  752.96
  5010.0  752.96  5010.2  753.46  5021.4  753.90  5036.9  753.68  5065.5  754.13
  5083.2  754.96  5111.9  754.64  5141.9  754.97  5158.2  754.56  5233.2  754.72
  5240.6  755.06  5295.4  755.00  5424.0  756.00  5481.7  755.98  5513.3  756.61
#Mann=3,-1,0
  4221.6    0.05       0  5006.2   0.033       0  5010.2    0.05       0
Bank Sta=5006.2,5010.2
Exp/Cntr=0.3,0.1

Type RM Length L Ch R = 1,9703,165,165,165
BEGIN DESCRIPTION:
Mapping XS fb9157d5
END DESCRIPTION:
XS GIS Cut Line= 3
      2335757.19      7116474.84      2335376.80      7116062.02
      2334627.65      7116041.09
#Sta/Elev= 30
  4447.3  755.13  4484.7  755.60  4527.2  754.39  4548.8  754.63  4746.7  753.03
  4767.7  753.38  4817.6  752.53  4895.3  752.89  4909.4  752.37  4952.0  752.28
  4973.0  751.60  4994.5  751.95  5006.6  751.44  5034.5  751.27  5034.7  750.77
  5038.2  750.77  5038.5  751.27  5076.5  752.10  5206.5  752.41  5226.5  753.11
  5260.7  752.46  5366.6  752.55  5446.6  753.46  5466.6  753.20  5586.7  754.60
  5636.7  754.71  5696.7  755.41  5706.7  755.88  5726.7  755.53  5758.1  755.81
#Mann=3,-1,0
  4447.3    0.05       0  5034.5   0.033       0  5038.5    0.05       0
Bank Sta=5034.5,5038.5
Exp/Cntr=0.3,0.1

Type RM Length L Ch R = 1,9538,571,571,571
BEGIN DESCRIPTION:
Hog Branch Tributary 6_1 17.0
END DESCRIPTION:
XS GIS Cut Line= 3
      2335938.56      7116526.76      2335479.37      7115960.18
      2334578.98      7115459.99
#Sta/Elev= 30
  4270.7  756.28  4537.7  753.97  4595.2  754.63  4616.0  753.65  4652.7  753.07
  4694.3  753.52  4815.8  752.23  4958.0  752.00  5035.9  750.64  5046.2  749.81
  5049.9  748.80  5050.1  748.30  5053.6  748.30  5053.9  748.80  5117.1  749.12
  5154.8  750.64  5160.6  751.42  5183.5  751.56  5220.0  753.49  5229.2  751.84
  5241.8  751.09  5257.8  751.94  5263.5  750.93  5273.8  750.78  5332.2  751.69
  5426.0  750.59  5458.0  751.42  5560.9  751.86  5756.6  754.49  6030.0  759.57
#Mann=3,-1,0
  4270.7    0.05       0  5049.9   0.033       0  5053.9    0.05       0
Bank Sta=5049.9,5053.9
Exp/Cntr=0.3,0.1

Type RM Length L Ch R = 1,8967,477,477,477
BEGIN DESCRIPTION:
Mapping XS cd3ce72c
END DESCRIPTION:
XS GIS Cut Line= 3
      2336049.48      7115795.98      2335744.89      7115477.50
      2334980.23      7115244.71
#Sta/Elev= 30
  4385.9  754.91  4468.2  753.02  4652.2  750.29  4793.7  749.21  4831.4  749.79
  4843.2  749.14  4853.6  749.40  4874.7  749.04  4885.0  749.40  4979.1  747.95
  5020.9  747.54  5038.9  747.86  5075.0  747.34  5075.2  746.84  5078.7  746.84
  5079.0  747.34  5109.8  747.85  5115.0  747.56  5125.4  748.42  5142.7  748.00
  5213.6  748.25  5279.3  748.95  5312.1  748.86  5324.0  749.46  5376.3  750.46
  5415.9  750.63  5421.1  750.23  5448.7  750.31  5590.6  752.50  5625.9  753.37
#Mann=3,-1,0
  4385.9    0.05       0  5075.0   0.033       0  5079.0    0.05       0
Bank Sta=5075,5079
Exp/Cntr=0.3,0.1

Type RM Length L Ch R = 1,8490,601,601,601
BEGIN DESCRIPTION:
Mapping XS 9ca3b21e
END DESCRIPTION:
XS GIS Cut Line= 3
      2336243.85      7115355.38      2335614.08      7114929.30
      2334982.26      7114906.45
#Sta/Elev= 30
  4344.6  750.69  4473.7  748.84  4482.6  748.96  4581.6  747.71  4827.2  746.44
  4878.2  746.65  4899.2  746.38  4935.1  746.49  4950.1  747.27  4956.1  747.05
  4965.0  746.19  5048.7  745.99  5049.0  745.49  5052.5  745.49  5052.7  745.99
  5087.0  746.55  5150.1  746.50  5160.1  747.29  5170.1  747.58  5210.1  747.32
  5310.2  747.37  5390.2  747.58  5430.3  747.97  5450.3  747.34  5497.9  748.04
  5550.3  748.07  5590.4  748.57  5640.4  749.67  5680.4  750.08  5737.2  751.29
#Mann=3,-1,0
  4344.6    0.05       0  5048.7   0.033       0  5052.7    0.05       0
Bank Sta=5048.7,5052.7
Exp/Cntr=0.3,0.1

Type RM Length L Ch R = 1,7889,317,317,317
BEGIN DESCRIPTION:
Mapping XS 34534d98
END DESCRIPTION:
XS GIS Cut Line= 2
      2336464.72      7114570.94      2335272.17      7114552.13
#Sta/Elev= 30
  4325.1  747.92  4380.8  746.93  4390.8  747.64  4410.8  746.14  4440.8  745.83
  4460.8  746.22  4520.8  745.17  4670.9  744.37  4720.9  743.71  4880.9  743.02
  4950.9  743.61  5000.9  742.80  5040.9  743.05  5048.9  742.78  5049.2  742.28
  5052.7  742.28  5052.9  742.78  5060.9  743.72  5070.9  744.09  5090.9  743.95
  5150.9  745.14  5210.9  744.94  5250.9  745.47  5260.9  745.95  5270.9  745.08
  5335.8  745.58  5380.9  745.46  5461.0  745.79  5481.0  746.82  5517.8  746.50
#Mann=3,-1,0
  4325.1    0.05       0  5048.9   0.033       0  5052.9    0.05       0
Bank Sta=5048.9,5052.9
Exp/Cntr=0.3,0.1

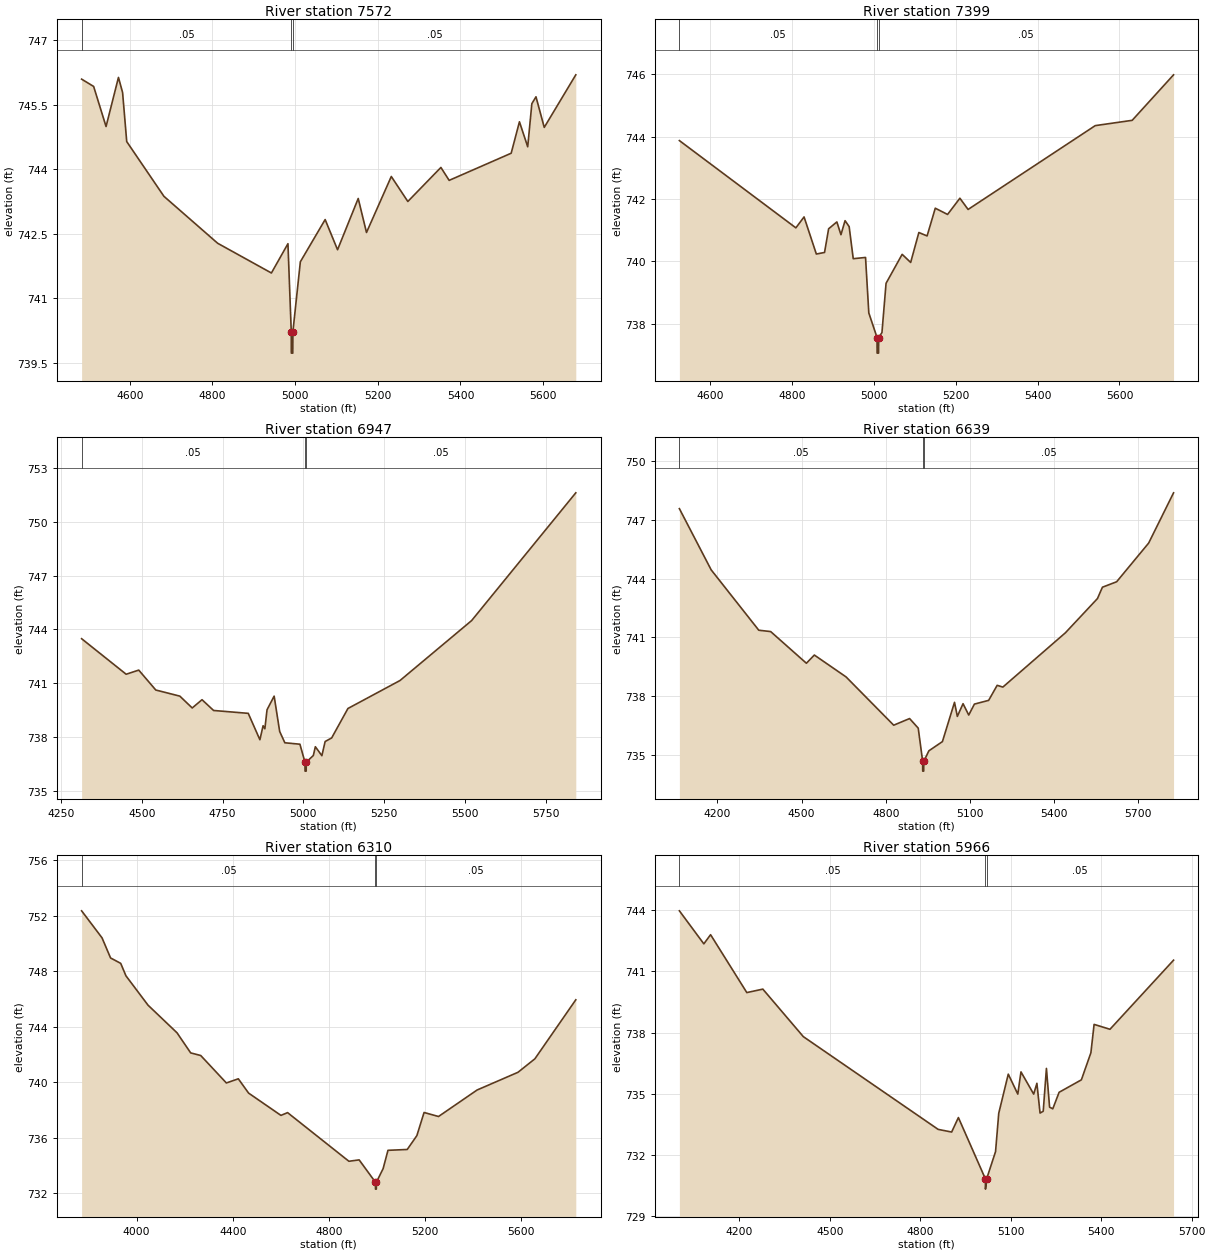
Type RM Length L Ch R = 1,7572,173,173,173
BEGIN DESCRIPTION:
Mapping XS 56d23a61
END DESCRIPTION:
XS GIS Cut Line= 2
      2336398.06      7114284.48      2335202.68      7114278.60
#Sta/Elev= 30
  4483.6  746.09  4512.7  745.92  4542.7  744.99  4572.7  746.13  4582.7  745.78
  4592.7  744.64  4682.7  743.37  4812.7  742.28  4942.7  741.59  4982.7  742.27
  4990.7  740.23  4990.9  739.73  4994.4  739.73  4994.7  740.23  5012.7  741.85
  5072.7  742.83  5102.7  742.13  5152.7  743.32  5172.7  742.53  5232.7  743.83
  5272.7  743.25  5352.7  744.04  5372.7  743.74  5522.7  744.37  5542.7  745.10
  5562.7  744.52  5572.7  745.52  5582.7  745.68  5602.7  744.97  5679.0  746.19
#Mann=3,-1,0
  4483.6    0.05       0  4990.7   0.033       0  4994.7    0.05       0
Bank Sta=4990.7,4994.7
Exp/Cntr=0.3,0.1

Type RM Length L Ch R = 1,7399,452,452,452
BEGIN DESCRIPTION:
Mapping XS 402fc451
END DESCRIPTION:
XS GIS Cut Line= 3
      2336343.07      7114130.61      2335878.09      7114109.71
      2335138.14      7114067.49
#Sta/Elev= 30
  4525.5  743.87  4809.9  741.07  4829.9  741.42  4859.9  740.23  4879.9  740.28
  4889.9  741.04  4910.0  741.26  4920.0  740.85  4930.0  741.30  4940.0  741.11
  4950.0  740.08  4980.0  740.12  4988.0  738.34  5008.1  737.55  5008.3  737.05
  5011.8  737.05  5012.1  737.55  5020.1  737.71  5030.1  739.29  5069.4  740.22
  5090.2  739.96  5110.2  740.92  5130.3  740.81  5150.3  741.70  5180.3  741.50
  5210.4  742.02  5230.4  741.66  5540.9  744.35  5631.1  744.52  5732.1  745.98
#Mann=3,-1,0
  4525.5    0.05       0  5008.1   0.033       0  5012.1    0.05       0
Bank Sta=5008.1,5012.1
Exp/Cntr=0.3,0.1

Type RM Length L Ch R = 1,6947,308,308,308
BEGIN DESCRIPTION:
Hog Branch Tributary 6_1 11.0
END DESCRIPTION:
XS GIS Cut Line= 3
      2336489.38      7113942.69      2335879.00      7113660.00
      2335029.03      7113560.00
#Sta/Elev= 30
  4314.2  743.48  4451.9  741.50  4490.9  741.73  4543.6  740.62  4617.9  740.28
  4656.3  739.62  4686.6  740.08  4722.4  739.48  4829.6  739.32  4865.6  737.85
  4875.5  738.63  4881.0  738.46  4887.7  739.52  4909.7  740.28  4926.8  738.31
  4942.8  737.68  4989.4  737.60  5005.0  736.60  5005.3  736.10  5008.8  736.10
  5009.0  736.60  5030.9  736.97  5037.2  737.46  5057.3  736.96  5067.4  737.75
  5087.6  737.95  5137.9  739.59  5299.0  741.15  5520.5  744.49  5842.7  751.61
#Mann=3,-1,0
  4314.2    0.05       0  5005.0   0.035       0  5009.0    0.05       0
Bank Sta=5005,5009
Exp/Cntr=0.3,0.1

Type RM Length L Ch R = 1,6639,329,329,329
BEGIN DESCRIPTION:
Hog Branch Tributary 6_1 10.0
END DESCRIPTION:
XS GIS Cut Line= 3
      2336679.03      7114010.03      2336079.00      7113410.00
      2335178.99      7113260.00
#Sta/Elev= 30
  4064.4  747.58  4177.6  744.45  4347.3  741.36  4389.7  741.29  4517.0  739.67
  4545.3  740.09  4658.4  738.97  4828.1  736.50  4884.7  736.84  4915.5  736.35
  4931.3  734.65  4931.5  734.15  4935.0  734.15  4935.3  734.65  4953.5  735.19
  5001.7  735.66  5044.8  737.67  5054.9  736.95  5075.2  737.60  5095.5  737.02
  5115.7  737.58  5166.4  737.77  5196.8  738.54  5217.1  738.45  5440.1  741.23
  5554.2  742.98  5571.9  743.56  5622.6  743.84  5736.7  745.82  5825.4  748.39
#Mann=3,-1,0
  4064.4    0.05       0  4931.3   0.033       0  4935.3    0.05       0
Bank Sta=4931.3,4935.3
Exp/Cntr=0.3,0.1

Type RM Length L Ch R = 1,6310,344,344,344
BEGIN DESCRIPTION:
Hog Branch Tributary 6_1 9.0
END DESCRIPTION:
XS GIS Cut Line= 3
      2336979.00      7114009.99      2336179.00      7113110.00
      2335329.02      7113060.00
#Sta/Elev= 30
  3771.1  752.36  3856.0  750.41  3891.5  748.96  3933.7  748.57  3955.5  747.67
  4047.5  745.55  4167.9  743.56  4224.7  742.11  4266.6  741.92  4373.2  739.94
  4422.9  740.24  4465.6  739.21  4600.2  737.60  4627.8  737.80  4882.9  734.29
  4925.5  734.39  4993.3  732.78  4993.5  732.28  4997.0  732.28  4997.3  732.78
  5025.3  733.76  5045.4  735.08  5125.5  735.14  5165.6  736.14  5195.6  737.81
  5255.7  737.52  5416.0  739.43  5586.3  740.71  5656.4  741.68  5826.7  745.94
#Mann=3,-1,0
  3771.1    0.05       0  4993.3   0.033       0  4997.3    0.05       0
Bank Sta=4993.3,4997.3
Exp/Cntr=0.3,0.1

Type RM Length L Ch R = 1,5966,338,338,338
BEGIN DESCRIPTION:
Hog Branch Tributary 6_1 8.0
END DESCRIPTION:
XS GIS Cut Line= 3
      2336779.01      7113710.02      2336329.00      7112810.00
      2335729.01      7112610.00
#Sta/Elev= 30
  4001.3  743.97  4082.4  742.35  4104.7  742.80  4224.9  739.96  4278.0  740.13
  4412.2  737.80  4859.4  733.25  4904.1  733.12  4926.5  733.83  5016.1  730.82
  5016.3  730.32  5020.1  730.82  5049.7  732.16  5060.3  734.04  5091.9  735.96
  5123.5  734.98  5134.0  736.07  5176.2  734.98  5186.8  735.51  5197.3  734.05
  5207.8  734.14  5218.4  736.24  5228.9  734.34  5239.5  734.26  5260.5  735.07
  5334.3  735.68  5365.9  737.01  5376.5  738.40  5429.2  738.16  5640.0  741.55
#Mann=3,-1,0
  4001.3    0.05       0  5016.1   0.033       0  5020.1    0.05       0
Bank Sta=5016.1,5020.1
Exp/Cntr=0.3,0.1

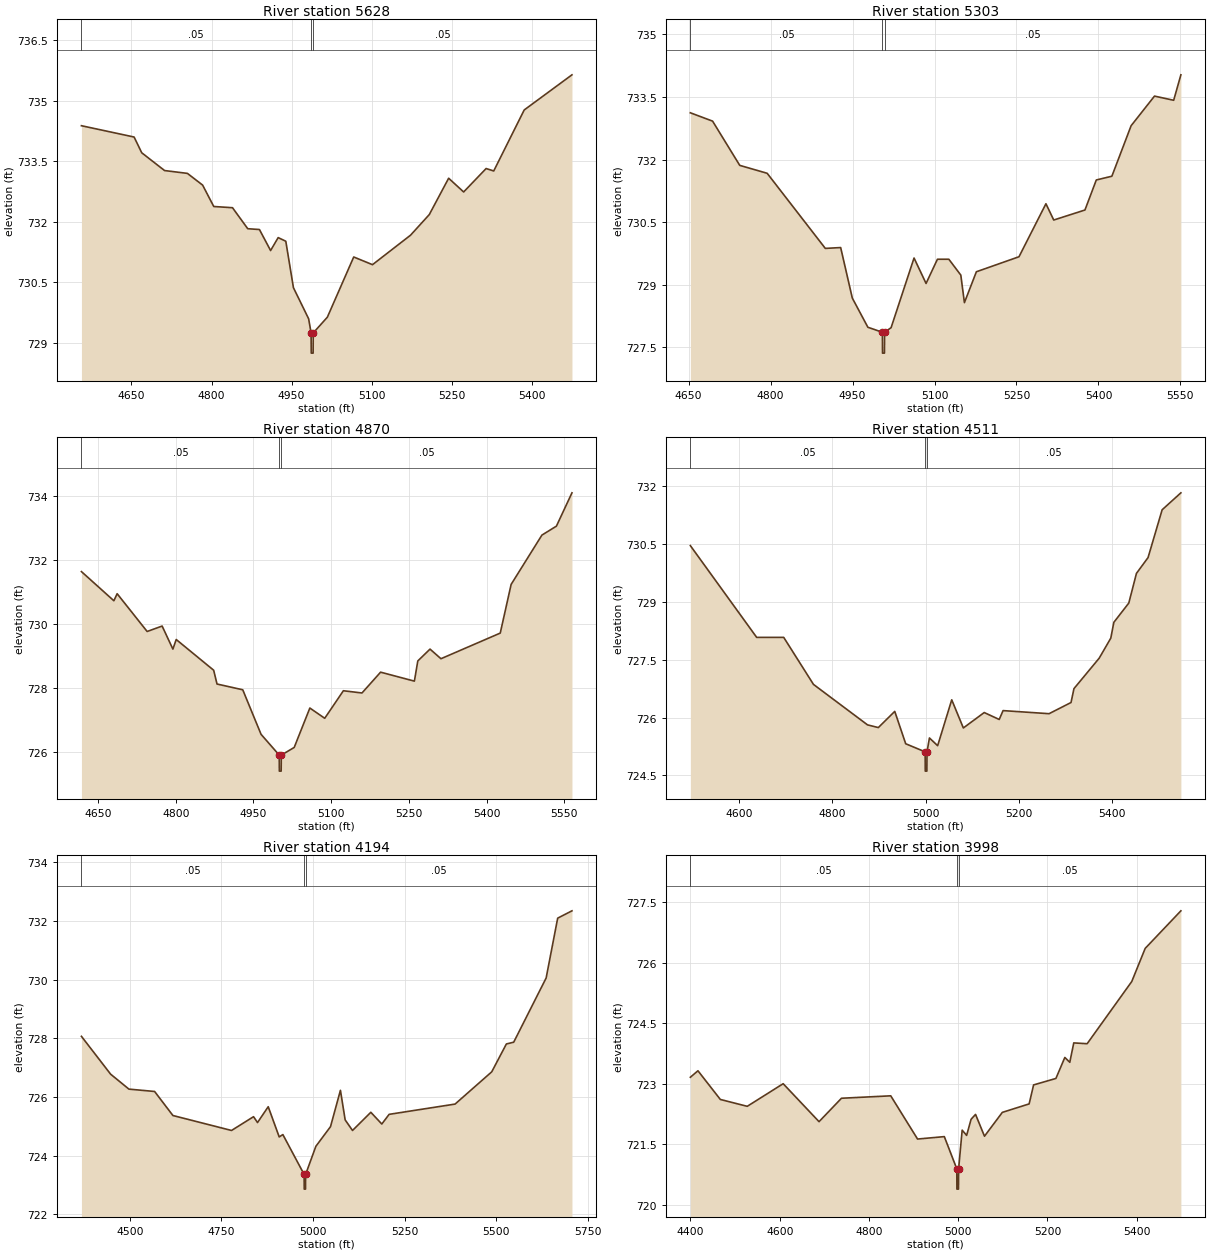
Type RM Length L Ch R = 1,5628,325,325,325
BEGIN DESCRIPTION:
Mapping XS 1d0a8e80
END DESCRIPTION:
XS GIS Cut Line= 2
      2336873.34      7112835.43      2336174.73      7112237.89
#Sta/Elev= 30
  4556.2  734.38  4654.9  734.10  4669.2  733.71  4712.0  733.27  4754.8  733.20
  4783.3  732.91  4804.2  732.38  4839.3  732.35  4867.9  731.83  4889.8  731.81
  4910.7  731.29  4924.9  731.61  4939.2  731.52  4953.5  730.37  4982.0  729.60
  4986.6  729.25  4986.9  728.75  4990.4  728.75  4990.6  729.25  5017.1  729.64
  5066.5  731.13  5101.7  730.94  5173.0  731.67  5208.1  732.18  5244.4  733.08
  5272.5  732.74  5314.6  733.32  5328.9  733.26  5386.0  734.77  5475.5  735.64
#Mann=3,-1,0
  4556.2    0.05       0  4986.6   0.033       0  4990.6    0.05       0
Bank Sta=4986.6,4990.6
Exp/Cntr=0.3,0.1

Type RM Length L Ch R = 1,5303,433,433,433
BEGIN DESCRIPTION:
Mapping XS 4d71b752
END DESCRIPTION:
XS GIS Cut Line= 2
      2336968.23      7112558.59      2336382.97      7111877.77
#Sta/Elev= 30
  4653.1  733.12  4693.8  732.92  4743.5  731.86  4793.7  731.67  4900.1  729.87
  4928.2  729.89  4949.5  728.68  4978.0  727.98  5004.6  727.86  5004.8  727.36
  5008.3  727.36  5008.6  727.86  5020.5  727.97  5062.5  729.64  5084.5  729.03
  5105.3  729.61  5126.2  729.61  5148.1  729.23  5154.7  728.57  5176.6  729.31
  5254.6  729.67  5303.9  730.94  5318.2  730.55  5375.3  730.79  5396.1  731.51
  5424.6  731.60  5459.8  732.81  5502.6  733.52  5537.7  733.42  5550.9  734.03
#Mann=3,-1,0
  4653.1    0.05       0  5004.6   0.033       0  5008.6    0.05       0
Bank Sta=5004.6,5008.6
Exp/Cntr=0.3,0.1

Type RM Length L Ch R = 1,4870,359,359,359
BEGIN DESCRIPTION:
Mapping XS f16908ca
END DESCRIPTION:
XS GIS Cut Line= 3
      2337253.38      7112263.17      2337008.02      7111948.72
      2336550.60      7111647.39
#Sta/Elev= 30
  4618.0  731.63  4680.6  730.72  4686.9  730.94  4744.8  729.76  4773.7  729.93
  4794.5  729.21  4800.9  729.51  4873.2  728.55  4879.6  728.12  4929.3  727.94
  4964.6  726.55  4999.7  725.90  4999.9  725.40  5003.4  725.40  5003.7  725.90
  5028.6  726.14  5058.8  727.37  5087.5  727.05  5123.5  727.91  5159.4  727.84
  5195.3  728.49  5260.5  728.21  5267.1  728.84  5290.7  729.21  5311.8  728.91
  5426.2  729.71  5447.2  731.23  5506.6  732.77  5534.6  733.05  5564.6  734.09
#Mann=3,-1,0
  4618.0    0.05       0  4999.7   0.033       0  5003.7    0.05       0
Bank Sta=4999.7,5003.7
Exp/Cntr=0.3,0.1

Type RM Length L Ch R = 1,4511,317,317,317
BEGIN DESCRIPTION:
Mapping XS 0ac1717f
END DESCRIPTION:
XS GIS Cut Line= 3
      2337530.37      7112113.18      2337277.32      7111702.47
      2336744.45      7111501.55
#Sta/Elev= 30
  4495.5  730.46  4637.7  728.08  4695.7  728.08  4759.5  726.86  4875.4  725.81
  4898.6  725.74  4933.8  726.16  4957.3  725.32  4999.0  725.11  4999.2  724.61
  5002.7  724.61  5003.0  725.11  5008.2  725.47  5025.8  725.27  5056.0  726.46
  5080.9  725.73  5125.7  726.13  5157.8  725.95  5166.1  726.18  5264.7  726.10
  5311.8  726.39  5318.1  726.75  5372.2  727.54  5397.1  728.06  5403.6  728.47
  5435.7  728.97  5452.1  729.74  5477.0  730.15  5507.2  731.39  5547.4  731.83
#Mann=3,-1,0
  4495.5    0.05       0  4999.0   0.033       0  5003.0    0.05       0
Bank Sta=4999,5003
Exp/Cntr=0.3,0.1

Type RM Length L Ch R = 1,4194,196,196,196
BEGIN DESCRIPTION:
Mapping XS ff405966
END DESCRIPTION:
XS GIS Cut Line= 3
      2337660.55      7111959.64      2337642.36      7111483.26
      2336780.03      7111452.62
#Sta/Elev= 30
  4367.6  728.07  4447.3  726.78  4497.3  726.27  4567.4  726.19  4617.4  725.37
  4777.5  724.86  4837.6  725.33  4848.5  725.13  4877.7  725.67  4907.7  724.64
  4917.7  724.72  4975.8  723.36  4976.0  722.86  4979.5  722.86  4979.8  723.36
  5007.8  724.32  5047.8  724.99  5074.9  726.23  5087.8  725.22  5107.9  724.86
  5157.9  725.48  5187.9  725.08  5207.9  725.41  5388.0  725.76  5488.1  726.86
  5528.1  727.81  5548.1  727.87  5636.7  730.06  5668.2  732.10  5707.2  732.35
#Mann=3,-1,0
  4367.6    0.05       0  4975.8   0.033       0  4979.8    0.05       0
Bank Sta=4975.8,4979.8
Exp/Cntr=0.3,0.1

Type RM Length L Ch R = 1,3998,171,171,171
BEGIN DESCRIPTION:
Mapping XS 7de094ec
END DESCRIPTION:
XS GIS Cut Line= 3
      2338225.88      7111390.40      2337800.47      7111346.55
      2337128.99      7111328.02
#Sta/Elev= 30
  4399.7  723.16  4416.7  723.32  4466.9  722.61  4527.2  722.44  4607.7  723.00
  4688.1  722.06  4738.4  722.64  4848.8  722.70  4908.9  721.63  4968.9  721.69
  4996.9  720.89  4997.1  720.39  5000.6  720.39  5000.9  720.89  5008.9  721.85
  5018.9  721.72  5028.9  722.12  5038.9  722.24  5058.9  721.70  5098.9  722.29
  5159.0  722.50  5169.0  722.97  5219.0  723.13  5239.0  723.65  5250.1  723.53
  5259.0  724.01  5289.0  723.99  5389.0  725.53  5419.1  726.35  5499.1  727.28
#Mann=3,-1,0
  4399.7    0.05       0  4996.9   0.033       0  5000.9    0.05       0
Bank Sta=4996.9,5000.9
Exp/Cntr=0.3,0.1

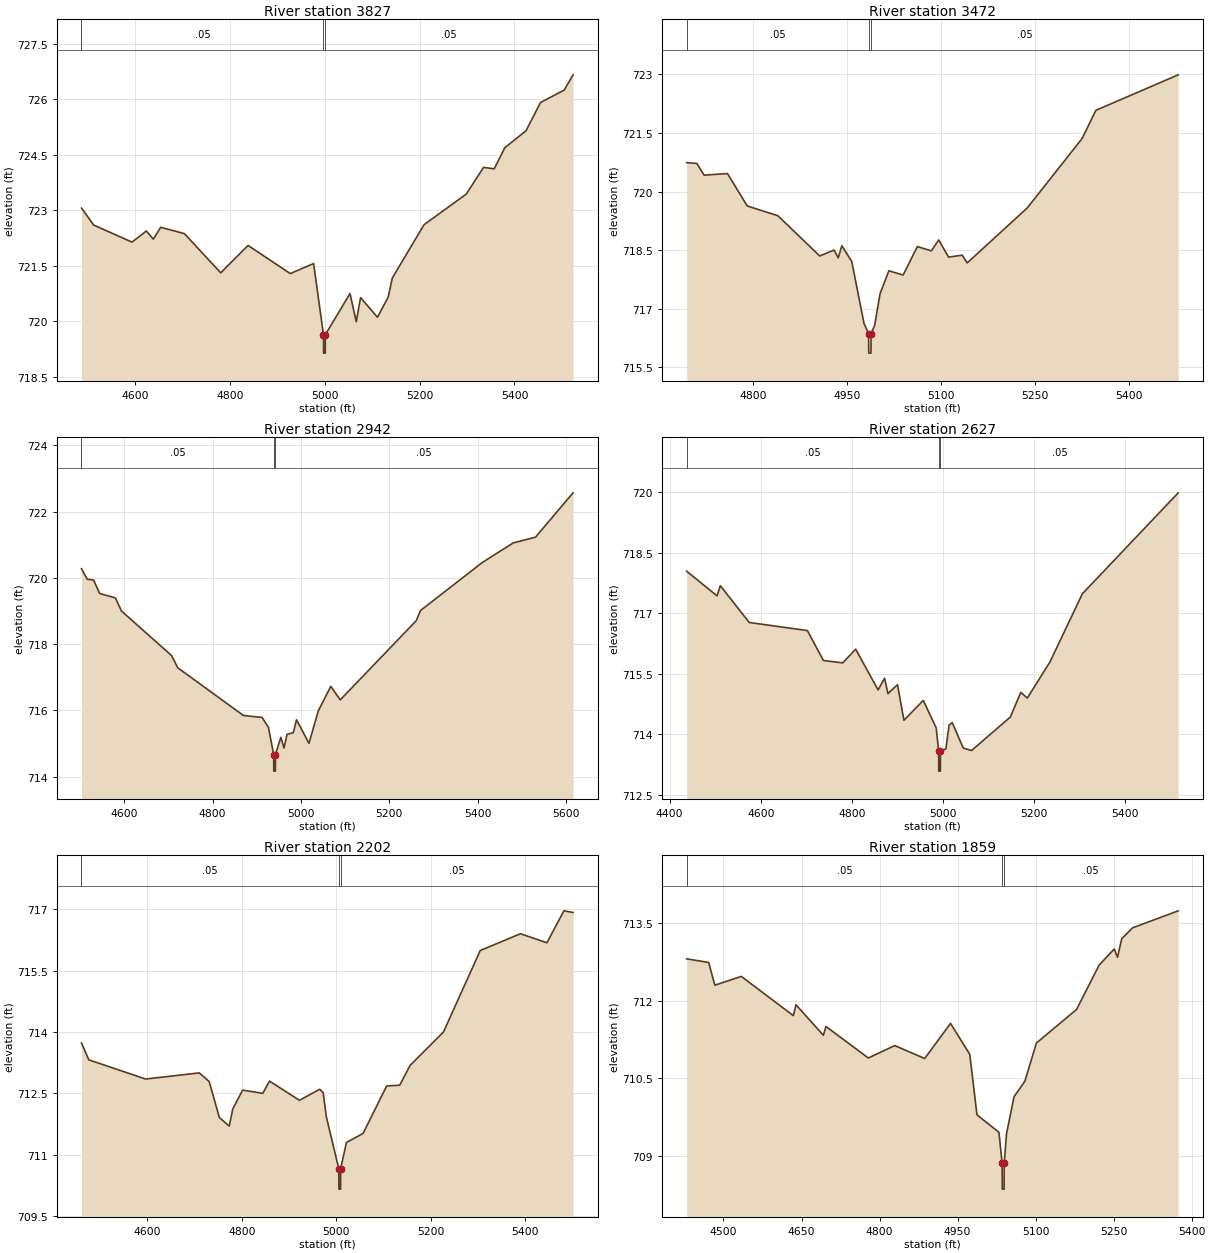
Type RM Length L Ch R = 1,3827,355,355,355
BEGIN DESCRIPTION:
Mapping XS fd168a43
END DESCRIPTION:
XS GIS Cut Line= 4
      2338214.49      7111376.44      2337966.87      7111340.90
      2337745.99      7111214.36      2337270.38      7110975.15
#Sta/Elev= 30
  4486.5  723.06  4512.3  722.60  4593.1  722.14  4623.4  722.44  4638.0  722.22
  4653.7  722.54  4703.5  722.37  4780.3  721.31  4837.9  722.05  4927.0  721.29
  4976.2  721.56  4997.0  719.64  4997.3  719.14  5000.8  719.14  5001.0  719.64
  5053.0  720.75  5066.2  719.99  5075.3  720.64  5111.0  720.11  5133.4  720.65
  5142.3  721.17  5209.2  722.61  5298.5  723.44  5334.8  724.16  5357.2  724.12
  5379.6  724.69  5424.4  725.15  5454.8  725.91  5505.0  726.25  5523.6  726.66
#Mann=3,-1,0
  4486.5    0.05       0  4997.0   0.033       0  5001.0    0.05       0
Bank Sta=4997,5001
Exp/Cntr=0.3,0.1

Type RM Length L Ch R = 1,3472,530,530,530
BEGIN DESCRIPTION:
Mapping XS 94967d48
END DESCRIPTION:
XS GIS Cut Line= 3
      2338085.03      7111174.12      2337943.68      7110928.34
      2337502.40      7110690.34
#Sta/Elev= 30
  4694.2  720.74  4710.5  720.72  4722.1  720.42  4759.4  720.46  4791.0  719.63
  4839.9  719.38  4906.6  718.35  4929.7  718.50  4936.2  718.30  4942.0  718.61
  4957.8  718.21  4977.4  716.62  4984.7  716.36  4985.0  715.86  4988.5  715.86
  4988.7  716.36  4994.4  716.57  5003.0  717.38  5017.1  717.97  5039.9  717.86
  5062.6  718.59  5084.9  718.48  5096.7  718.76  5112.4  718.32  5134.3  718.37
  5142.1  718.17  5238.1  719.58  5325.7  721.36  5347.6  722.08  5479.1  722.99
#Mann=3,-1,0
  4694.2    0.05       0  4984.7   0.033       0  4988.7    0.05       0
Bank Sta=4984.7,4988.7
Exp/Cntr=0.3,0.1

Type RM Length L Ch R = 1,2942,315,315,315
BEGIN DESCRIPTION:
Mapping XS af45faa5
END DESCRIPTION:
XS GIS Cut Line= 3
      2338482.32      7110815.06      2338037.31      7110383.98
      2337543.78      7110386.10
#Sta/Elev= 30
  4503.1  720.28  4516.1  719.96  4530.3  719.94  4544.4  719.53  4579.7  719.40
  4593.8  719.00  4707.0  717.66  4721.1  717.29  4869.7  715.85  4912.0  715.79
  4926.2  715.50  4938.3  714.67  4938.6  714.17  4942.1  714.17  4942.3  714.67
  4954.5  715.19  4961.7  714.87  4968.6  715.28  4982.8  715.33  4990.0  715.72
  5018.2  715.01  5039.4  715.99  5067.6  716.73  5089.0  716.32  5261.0  718.71
  5271.0  719.02  5411.0  720.47  5481.0  721.06  5531.0  721.23  5616.2  722.57
#Mann=3,-1,0
  4503.1    0.05       0  4938.3   0.033       0  4942.3    0.05       0
Bank Sta=4938.3,4942.3
Exp/Cntr=0.3,0.1

Type RM Length L Ch R = 1,2627,425,425,425
BEGIN DESCRIPTION:
Mapping XS 3cb6d699
END DESCRIPTION:
XS GIS Cut Line= 3
      2338666.47      7110566.98      2338220.16      7110153.40
      2337845.18      7109868.51
#Sta/Elev= 30
  4437.4  718.04  4504.1  717.43  4511.4  717.68  4574.9  716.77  4702.5  716.57
  4737.6  715.83  4780.2  715.77  4808.5  716.11  4857.8  715.10  4872.0  715.39
  4879.4  715.01  4900.4  715.23  4914.5  714.35  4957.0  714.84  4985.4  714.16
  4990.7  713.59  4991.0  713.09  4994.5  713.09  4994.7  713.59  5006.6  713.64
  5013.7  714.23  5020.6  714.29  5044.7  713.66  5063.0  713.60  5148.2  714.43
  5171.1  715.04  5185.5  714.90  5235.5  715.80  5306.3  717.48  5516.8  719.98
#Mann=3,-1,0
  4437.4    0.05       0  4990.7   0.033       0  4994.7    0.05       0
Bank Sta=4990.7,4994.7
Exp/Cntr=0.3,0.1

Type RM Length L Ch R = 1,2202,343,343,343
BEGIN DESCRIPTION:
Mapping XS 624e3ef0
END DESCRIPTION:
XS GIS Cut Line= 2
      2338878.88      7110202.25      2338106.57      7109504.69
#Sta/Elev= 30
  4460.6  713.73  4476.0  713.32  4596.3  712.85  4709.9  713.00  4730.9  712.79
  4752.5  711.91  4773.4  711.70  4780.9  712.12  4801.8  712.58  4844.4  712.50
  4858.6  712.80  4922.2  712.33  4964.8  712.60  4972.2  712.52  4978.9  711.93
  5005.3  710.66  5005.6  710.16  5009.1  710.16  5009.3  710.66  5021.5  711.30
  5056.7  711.52  5106.7  712.68  5134.4  712.70  5156.1  713.18  5227.0  714.00
  5304.8  715.99  5389.9  716.40  5446.0  716.18  5481.9  716.96  5501.3  716.92
#Mann=3,-1,0
  4460.6    0.05       0  5005.3   0.033       0  5009.3    0.05       0
Bank Sta=5005.3,5009.3
Exp/Cntr=0.3,0.1

Type RM Length L Ch R = 1,1859,373,373,373
BEGIN DESCRIPTION:
Mapping XS 1de19d98
END DESCRIPTION:
XS GIS Cut Line= 3
      2338842.42      7110053.25      2338767.24      7109652.22
      2338344.25      7109321.42
#Sta/Elev= 30
  4429.2  712.81  4471.5  712.74  4483.4  712.30  4534.3  712.47  4634.3  711.71
  4639.4  711.92  4692.0  711.33  4697.1  711.50  4778.4  710.89  4829.3  711.13
  4886.8  710.88  4936.5  711.56  4973.5  710.96  4987.3  709.79  5029.6  709.45
  5035.7  708.85  5036.0  708.35  5039.5  708.35  5039.7  708.85  5044.1  709.42
  5058.6  710.14  5079.4  710.44  5101.6  711.18  5178.8  711.83  5222.2  712.69
  5251.2  713.00  5257.5  712.84  5265.6  713.20  5286.4  713.41  5374.2  713.74
#Mann=3,-1,0
  4429.2    0.05       0  5035.7   0.033       0  5039.7    0.05       0
Bank Sta=5035.7,5039.7
Exp/Cntr=0.3,0.1

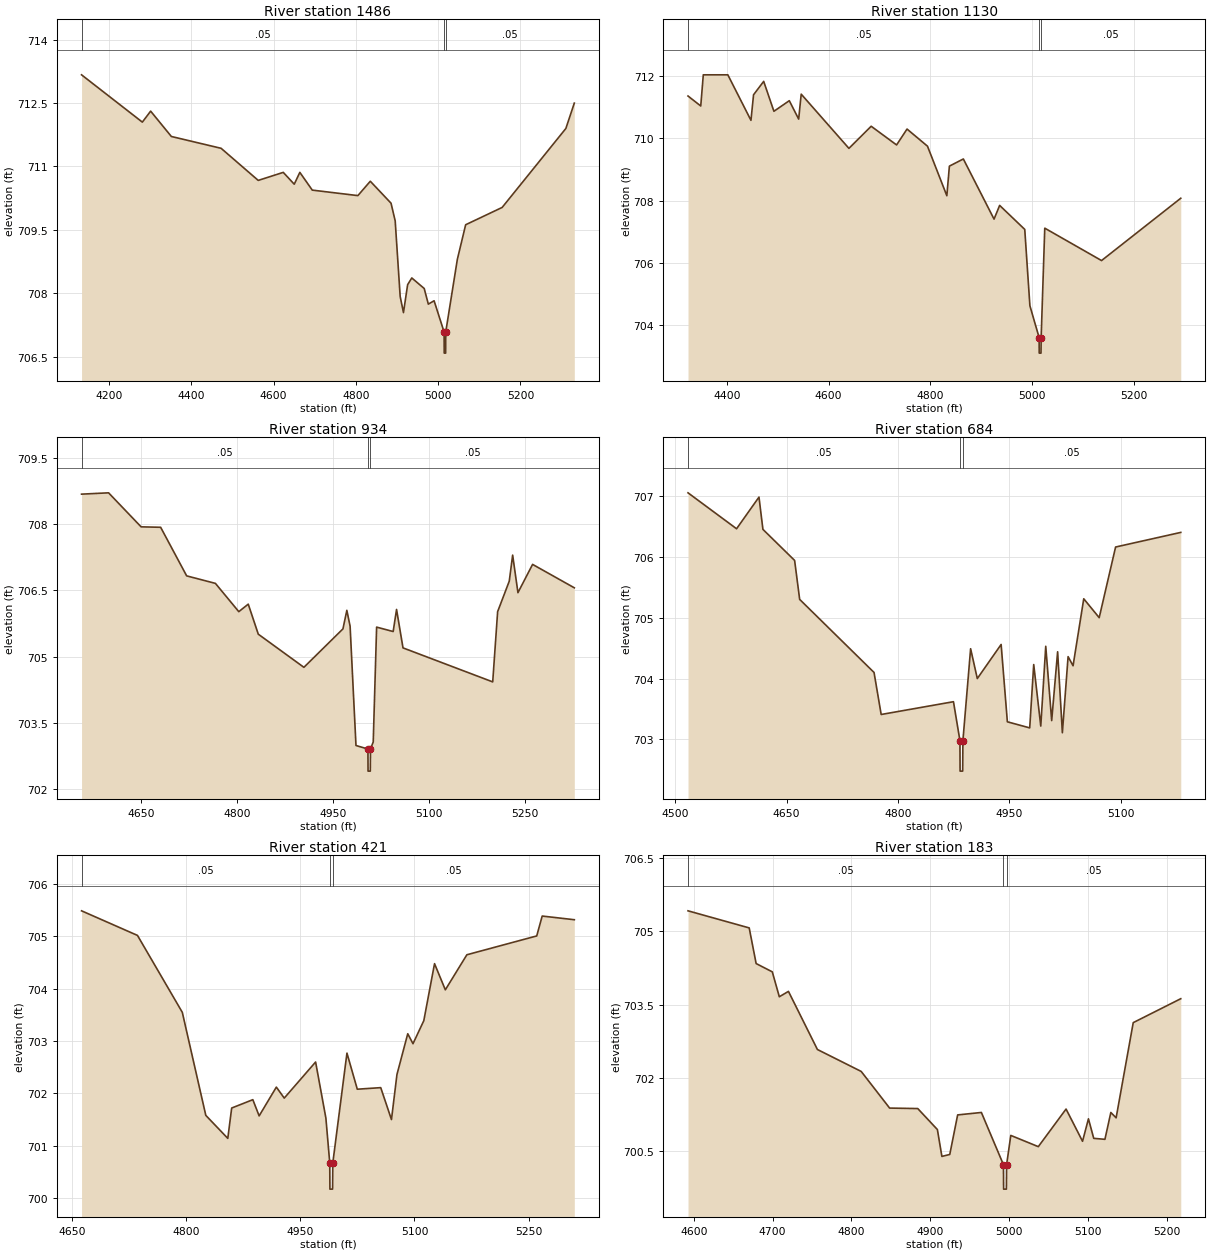
Type RM Length L Ch R = 1,1486,356,356,356
BEGIN DESCRIPTION:
Mapping XS c9b1594c
END DESCRIPTION:
XS GIS Cut Line= 3
      2338865.45      7110076.69      2338753.36      7109138.15
      2338509.16      7109075.58
#Sta/Elev= 30
  4133.5  713.17  4281.2  712.05  4301.4  712.31  4351.7  711.71  4472.6  711.43
  4562.8  710.67  4623.6  710.86  4650.3  710.58  4663.9  710.86  4694.1  710.44
  4804.9  710.31  4835.1  710.65  4885.5  710.13  4895.6  709.71  4907.7  707.92
  4915.7  707.54  4925.8  708.20  4935.9  708.36  4966.1  708.11  4976.1  707.74
  4990.1  707.82  5014.4  707.08  5014.7  706.58  5018.2  706.58  5018.4  707.08
  5046.6  708.80  5066.8  709.62  5155.5  710.03  5310.3  711.90  5330.8  712.50
#Mann=3,-1,0
  4133.5    0.05       0  5014.4   0.033       0  5018.4    0.05       0
Bank Sta=5014.4,5018.4
Exp/Cntr=0.3,0.1

Type RM Length L Ch R = 1,1130,196,196,196
BEGIN DESCRIPTION:
Mapping XS 003f4979
END DESCRIPTION:
XS GIS Cut Line= 2
      2339126.79      7109767.80      2339026.84      7108805.27
#Sta/Elev= 30
  4323.9  711.36  4348.9  711.04  4353.9  712.04  4402.1  712.04  4447.5  710.58
  4452.6  711.40  4472.5  711.83  4492.6  710.87  4522.8  711.21  4541.2  710.62
  4546.2  711.42  4639.9  709.68  4683.6  710.39  4733.5  709.79  4754.0  710.30
  4794.2  709.75  4832.2  708.16  4837.2  709.11  4864.6  709.34  4924.9  707.41
  4935.9  707.85  4985.2  707.08  4995.3  704.63  5013.4  703.61  5013.6  703.11
  5017.1  703.11  5017.4  703.61  5024.5  707.12  5136.0  706.08  5291.6  708.08
#Mann=3,-1,0
  4323.9    0.05       0  5013.4   0.033       0  5017.4    0.05       0
Bank Sta=5013.4,5017.4
Exp/Cntr=0.3,0.1

Type RM Length L Ch R = 1,934,250,250,250
BEGIN DESCRIPTION:
Mapping XS bfdef2bb
END DESCRIPTION:
XS GIS Cut Line= 3
      2339304.16      7109431.46      2339218.95      7108997.30
      2339111.48      7108686.61
#Sta/Elev= 30
  4556.7  708.68  4599.0  708.71  4649.9  707.94  4680.5  707.93  4721.2  706.83
  4766.2  706.66  4802.8  706.02  4817.6  706.19  4833.3  705.51  4904.7  704.76
  4965.8  705.63  4971.9  706.05  4977.0  705.69  4986.2  702.99  5004.9  702.91
  5005.1  702.41  5008.6  702.41  5008.9  702.91  5013.2  703.07  5018.5  705.67
  5044.4  705.57  5049.7  706.07  5059.8  705.20  5200.2  704.43  5207.9  706.02
  5226.1  706.71  5231.4  707.30  5239.7  706.45  5262.6  707.09  5327.9  706.56
#Mann=3,-1,0
  4556.7    0.05       0  5004.9   0.033       0  5008.9    0.05       0
Bank Sta=5004.9,5008.9
Exp/Cntr=0.3,0.1

Type RM Length L Ch R = 1,684,263,263,263
BEGIN DESCRIPTION:
Mapping XS 4298c8eb
END DESCRIPTION:
XS GIS Cut Line= 3
      2339518.01      7109244.21      2339346.23      7108792.48
      2339233.71      7108651.34
#Sta/Elev= 30
  4517.2  707.05  4582.6  706.46  4612.8  706.98  4618.1  706.45  4660.8  705.94
  4667.6  705.30  4767.8  704.10  4777.4  703.41  4874.8  703.62  4883.5  702.98
  4883.7  702.48  4887.2  702.48  4887.5  702.98  4897.9  704.49  4906.9  704.00
  4939.0  704.56  4947.4  703.29  4977.5  703.19  4982.9  704.23  4992.4  703.22
  4999.1  704.53  5007.1  703.31  5015.1  704.44  5021.5  703.11  5029.2  704.36
  5035.9  704.21  5050.3  705.31  5071.1  705.00  5093.2  706.16  5181.0  706.40
#Mann=3,-1,0
  4517.2    0.05       0  4883.5   0.033       0  4887.5    0.05       0
Bank Sta=4883.5,4887.5
Exp/Cntr=0.3,0.1

Type RM Length L Ch R = 1,421,238,238,238
BEGIN DESCRIPTION:
Mapping XS ff079f0c
END DESCRIPTION:
XS GIS Cut Line= 3
      2339621.29      7109088.42      2339530.82      7108725.91
      2339333.41      7108535.94
#Sta/Elev= 30
  4662.5  705.49  4736.0  705.02  4794.9  703.55  4825.8  701.58  4854.7  701.14
  4859.8  701.72  4887.6  701.88  4895.9  701.57  4918.5  702.12  4928.9  701.91
  4970.1  702.60  4983.6  701.53  4988.7  700.67  4988.9  700.17  4992.4  700.17
  4992.7  700.67  5011.3  702.77  5024.9  702.08  5055.7  702.11  5069.8  701.50
  5077.0  702.36  5091.2  703.14  5098.1  702.95  5112.3  703.39  5126.4  704.48
  5140.6  703.98  5168.9  704.65  5260.7  705.01  5267.9  705.39  5310.1  705.32
#Mann=3,-1,0
  4662.5    0.05       0  4988.7    0.04       0  4992.7    0.05       0
Bank Sta=4988.7,4992.7
Exp/Cntr=0.3,0.1

Type RM Length L Ch R = 1,183,0,0,0
BEGIN DESCRIPTION:
Hog Branch Tributary 6_1 1.0
END DESCRIPTION:
XS GIS Cut Line= 4
      2339637.72      7109084.28      2339707.27      7108775.76
      2339704.28      7108680.30      2339545.70      7108537.75
#Sta/Elev= 30
  4592.7  705.42  4670.3  705.07  4679.1  704.34  4699.6  704.17  4708.5  703.66
  4720.1  703.77  4756.8  702.58  4812.4  702.13  4848.4  701.38  4884.1  701.37
  4909.0  700.94  4914.7  700.39  4924.7  700.43  4934.7  701.24  4964.8  701.29
  4992.8  700.22  4993.0  699.72  4996.5  699.72  4996.8  700.22  5002.1  700.82
  5037.0  700.59  5072.2  701.36  5093.1  700.70  5100.6  701.16  5107.3  700.76
  5121.5  700.74  5129.0  701.29  5135.7  701.18  5157.4  703.13  5217.7  703.62
#Mann=3,-1,0
  4592.7    0.05       0  4992.8    0.04       0  4996.8    0.05       0
Bank Sta=4992.8,4996.8
Exp/Cntr=0.3,0.1

Chan Stop Cuts=-1