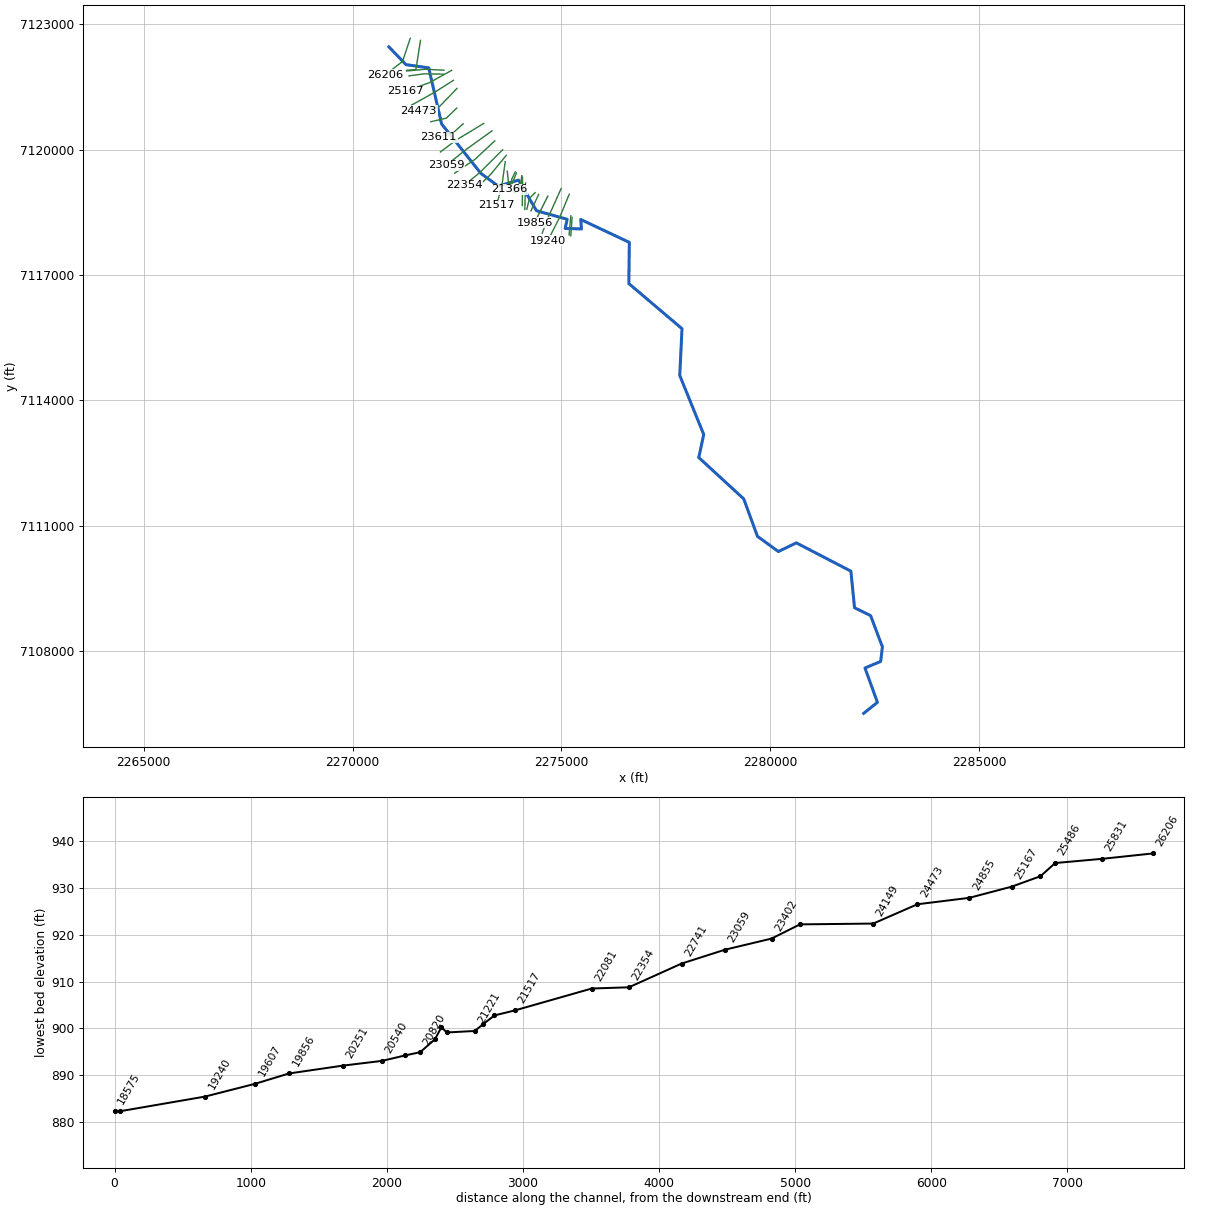
--- Long Branch.prj (project) ---

Proj Title=Long Branch Base Level Engineering
Current Plan=p01
Default Exp/Contr=0.3,0.1
English Units
Geom File=g01
Flow File=f01
Plan File=p01
BEGIN DESCRIPTION:
Long Branch
END DESCRIPTION:

--- Long Branch.p01 (plan) ---

Plan Title=Multiple Run
Short Identifier=Multiple
Geom File=g01
Flow File=f01
Subcritical Flow
K Sum by GR= 0
Std Step Tol= 0.01
Critical Tol= 0.01
Num of Std Step Trials= 20
Max Error Tol= 0.3
Flow Tol Ratio= 0.001
Split Flow NTrial= 30
Split Flow Tol= 0.02
Split Flow Ratio= 0.02
Log Output Level= 0
Friction Slope Method= 1
Unsteady Friction Slope Method= 2
Unsteady Bridges Friction Slope Method= 1
Parabolic Critical Depth
Global Vel Dist=  1 , 1 , 1
Global Log Level= 0
CheckData=True
Encroach Param= -1, 0, 0, 0
BEGIN DESCRIPTION:
Multiple Run
END DESCRIPTION:

--- Long Branch.f01 (steady flow) ---

Flow Title=Multiple
Number of Profiles=7
Profile Names=10-year,25-year,50-year,1pct_min,100-year,1pct_plu,500-year
River Rch & RM= Long Branch,Reach-1,26206
     555     760     929     565    1127    2248    1659
River Rch & RM= Long Branch,Reach-1,20709
     623     858    1052     641    1278    2551    1893
River Rch & RM= Long Branch,Reach-1,16314
    1064    1509    1889    1172    2338    4664    3592
River Rch & RM= Long Branch,Reach-1,14709
    1425    2053    2596    1626    3244    6472    5082
River Rch & RM= Long Branch,Reach-1,13727
    1555    2239    2830    1770    3532    7047    5521
River Rch & RM= Long Branch,Reach-1,8396
    1641    2373    3008    1888    3766    7515    5923
River Rch & RM= Long Branch,Reach-1,5777
    2037    2968    3781    2382    4753    9483    7538
Boundary for River Rch & Prof#=Long Branch,Reach-1,1
Up Type=0
Dn Type=3
Dn Slope=0.005
Boundary for River Rch & Prof#=Long Branch,Reach-1,2
Up Type=0
Dn Type=3
Dn Slope=0.005
Boundary for River Rch & Prof#=Long Branch,Reach-1,3
Up Type=0
Dn Type=3
Dn Slope=0.005
Boundary for River Rch & Prof#=Long Branch,Reach-1,4
Up Type=0
Dn Type=3
Dn Slope=0.005
Boundary for River Rch & Prof#=Long Branch,Reach-1,5
Up Type=0
Dn Type=3
Dn Slope=0.005
Boundary for River Rch & Prof#=Long Branch,Reach-1,6
Up Type=0
Dn Type=3
Dn Slope=0.005
Boundary for River Rch & Prof#=Long Branch,Reach-1,7
Up Type=0
Dn Type=3
Dn Slope=0.005

--- Long Branch.g01 (geometry) ---

Geom Title=Existing Conditions

River Reach=Long Branch,Reach-1
Reach XY= 30
      2270870.07      7122455.99      2271278.01      7122031.29
      2271823.46      7121952.47      2272132.13      7120611.62
      2273070.73      7119428.91      2273487.79      7119123.80
      2273971.56      7119267.56      2274401.37      7118536.30
      2275136.93      7118330.67      2275087.47      7118112.66
      2275477.82      7118099.45      2275459.98      7118326.18
      2276622.52      7117778.54      2276611.54      7116792.40
      2277883.08      7115713.78      2277828.99      7114595.31
      2278402.98      7113180.86      2278284.73      7112630.68
      2279359.91      7111641.69      2279688.94      7110744.50
      2280189.01      7110382.27      2280619.48      7110589.03
      2281923.54      7109912.47      2282010.69      7109037.30
      2282395.53      7108848.86      2282677.56      7108100.98
      2282636.18      7107753.10      2282260.83      7107595.25
      2282558.61      7106774.21      2282229.00      7106510.00

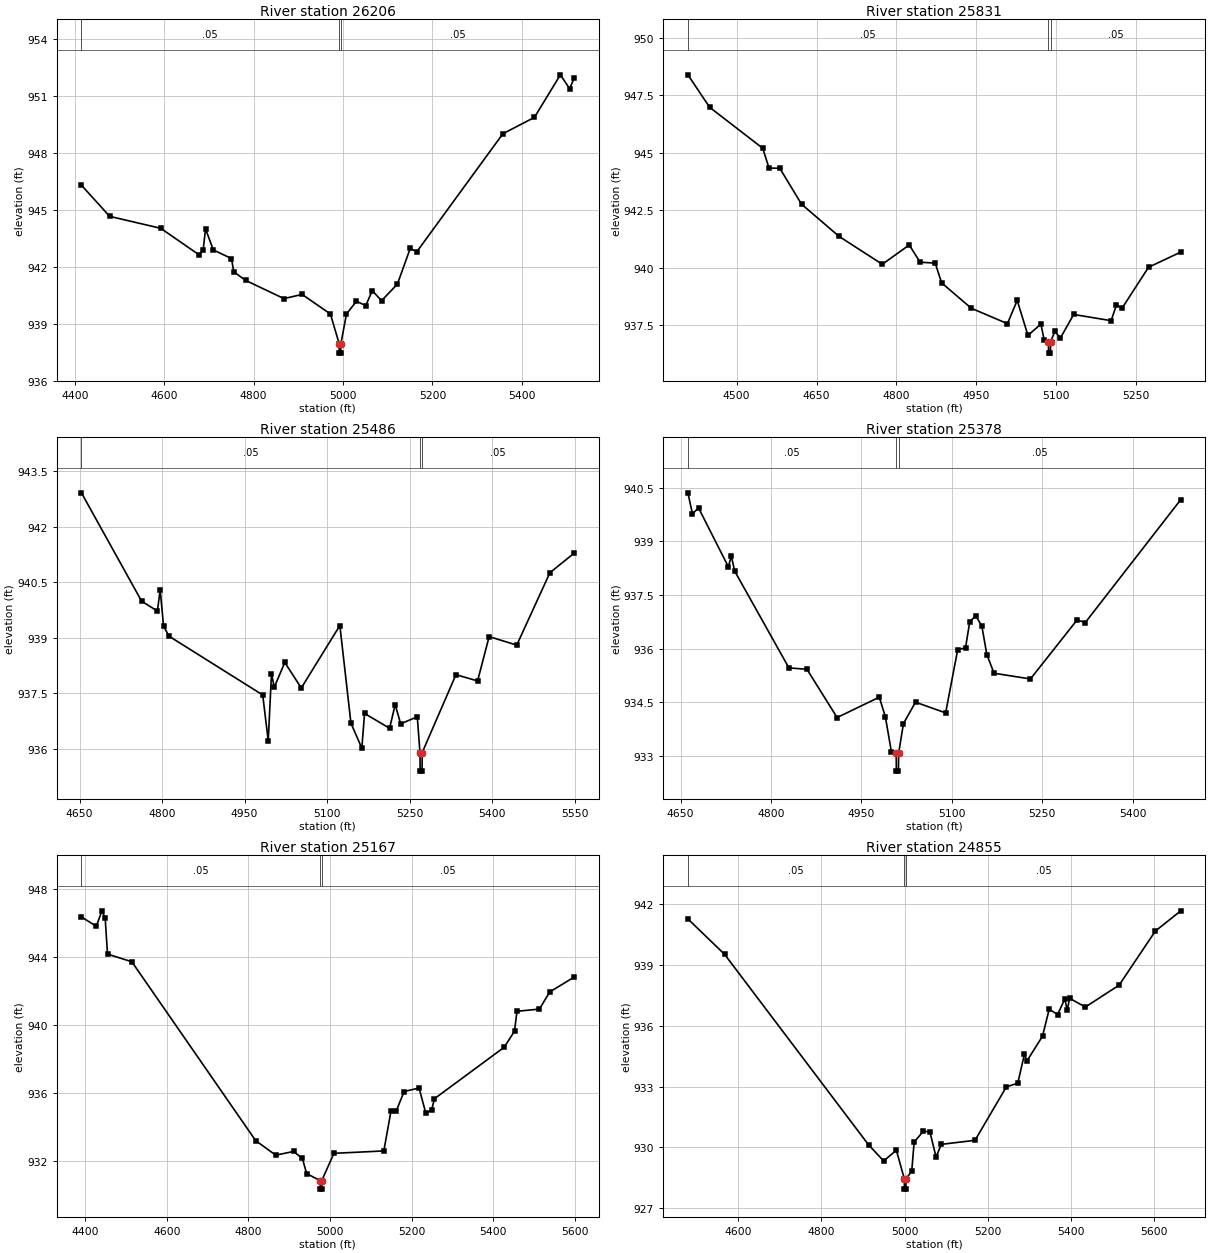
Type RM Length L Ch R = 1,26206,375,375,375
BEGIN DESCRIPTION:
Long Branch 57.0
END DESCRIPTION:
XS GIS Cut Line= 3
      2271381.25      7122659.97      2271197.02      7122106.97
      2270786.20      7121788.30
#Sta/Elev= 30
  4414.6  946.29  4477.8  944.65  4592.1  944.02  4678.1  942.62  4687.0  942.89
  4692.3  943.99  4709.7  942.88  4750.3  942.43  4755.5  941.73  4781.9  941.28
  4867.8  940.32  4908.4  940.54  4971.7  939.51  4991.2  937.95  4991.5  937.45
  4995.0  937.45  4995.2  937.95  5007.6  939.51  5030.0  940.18  5050.8  939.95
  5065.3  940.74  5086.1  940.21  5121.5  941.08  5150.4  942.97  5164.8  942.78
  5357.6  949.00  5428.2  949.86  5486.2  952.10  5507.0  951.37  5517.4  951.94
#Mann=3,-1,0
  4414.6    0.05       0  4991.2   0.035       0  4995.2    0.05       0
Bank Sta=4991.2,4995.2
Exp/Cntr=0.3,0.1

Type RM Length L Ch R = 1,25831,345,345,345
BEGIN DESCRIPTION:
Mapping XS bb0a6356
END DESCRIPTION:
XS GIS Cut Line= 3
      2271626.26      7122610.33      2271517.11      7121913.23
      2271298.68      7121895.94
#Sta/Elev= 30
  4408.7  948.38  4449.5  946.97  4549.1  945.19  4560.9  944.33  4581.1  944.32
  4621.9  942.76  4692.4  941.36  4773.4  940.15  4824.0  940.99  4844.3  940.24
  4872.7  940.20  4884.8  939.34  4940.4  938.24  5008.2  937.57  5026.5  938.58
  5046.7  937.06  5070.9  937.55  5077.1  936.87  5085.2  936.79  5085.4  936.29
  5088.9  936.29  5089.2  936.79  5097.3  937.24  5107.4  936.94  5132.5  937.97
  5202.7  937.70  5212.7  938.38  5223.2  938.24  5272.9  940.02  5333.4  940.68
#Mann=3,-1,0
  4408.7    0.05       0  5085.2   0.035       0  5089.2    0.05       0
Bank Sta=5085.2,5089.2
Exp/Cntr=0.3,0.1

Type RM Length L Ch R = 1,25486,108,108,108
BEGIN DESCRIPTION:
Mapping XS dfc97679
END DESCRIPTION:
XS GIS Cut Line= 3
      2272188.12      7121898.06      2271731.32      7121920.43
      2271294.87      7121878.64
#Sta/Elev= 30
  4653.5  942.92  4762.8  939.99  4791.6  939.72  4796.6  940.30  4802.8  939.31
  4812.8  939.04  4983.0  937.45  4993.0  936.21  4998.9  938.02  5004.0  937.66
  5023.1  938.33  5053.1  937.64  5123.2  939.33  5143.3  936.69  5163.1  936.01
  5168.1  936.95  5213.6  936.55  5223.7  937.19  5233.7  936.67  5263.9  936.86
  5268.8  935.89  5269.1  935.39  5272.6  935.39  5272.8  935.89  5334.2  938.00
  5373.5  937.83  5394.5  939.03  5444.7  938.80  5505.0  940.76  5549.3  941.29
#Mann=3,-1,0
  4653.5    0.05       0  5268.8   0.035       0  5272.8    0.05       0
Bank Sta=5268.8,5272.8
Exp/Cntr=0.3,0.1

Type RM Length L Ch R = 1,25378,211,211,211
BEGIN DESCRIPTION:
Mapping XS cf5a354c
END DESCRIPTION:
XS GIS Cut Line= 3
      2272166.62      7121803.99      2271708.04      7121810.48
      2271352.06      7121761.92
#Sta/Elev= 30
  4662.0  940.36  4669.6  939.77  4679.6  939.94  4729.1  938.29  4734.1  938.59
  4739.6  938.17  4829.6  935.46  4859.6  935.42  4909.6  934.07  4979.6  934.64
  4989.7  934.09  4999.7  933.11  5007.7  933.07  5007.9  932.57  5011.4  932.57
  5011.7  933.07  5019.7  933.90  5039.7  934.50  5089.7  934.20  5109.7  935.97
  5122.7  936.02  5129.7  936.75  5139.8  936.92  5149.9  936.62  5158.1  935.83
  5170.1  935.31  5230.4  935.15  5307.8  936.80  5321.5  936.73  5479.9  940.17
#Mann=3,-1,0
  4662.0    0.05       0  5007.7    0.05       0  5011.7    0.05       0
Bank Sta=5007.7,5011.7
Exp/Cntr=0.3,0.1

Type RM Length L Ch R = 1,25167,312,312,312
BEGIN DESCRIPTION:
Long Branch 54.0
END DESCRIPTION:
XS GIS Cut Line= 3
      2272373.02      7121894.21      2271839.51      7121599.49
      2271276.86      7121394.60
#Sta/Elev= 30
  4390.5  946.38  4426.9  945.83  4440.8  946.74  4448.7  946.31  4454.4  944.19
  4514.0  943.74  4817.6  933.20  4866.9  932.34  4910.4  932.56  4932.2  932.15
  4942.5  931.26  4975.7  930.84  4976.0  930.34  4979.5  930.34  4979.7  930.84
  5009.5  932.45  5131.8  932.59  5149.5  934.96  5162.4  934.95  5181.5  936.09
  5218.2  936.30  5234.7  934.82  5248.8  934.99  5256.0  935.67  5426.9  938.70
  5452.2  939.65  5458.2  940.82  5513.3  940.95  5538.6  941.96  5598.8  942.84
#Mann=3,-1,0
  4390.5    0.05       0  4975.7   0.033       0  4979.7    0.05       0
Bank Sta=4975.7,4979.7
Exp/Cntr=0.3,0.1

Type RM Length L Ch R = 1,24855,382,382,382
BEGIN DESCRIPTION:
Long Branch 53.0
END DESCRIPTION:
XS GIS Cut Line= 3
      2272414.71      7121654.64      2271967.81      7121371.46
      2271395.61      7121052.21
#Sta/Elev= 30
  4479.5  941.28  4567.7  939.53  4913.5  930.13  4949.9  929.33  4980.4  929.86
  4999.6  928.44  4999.8  927.94  5003.3  927.94  5003.6  928.44  5017.4  928.84
  5023.1  930.26  5044.8  930.79  5060.8  930.78  5075.9  929.52  5088.2  930.15
  5169.4  930.35  5244.8  932.99  5272.2  933.17  5288.2  934.61  5293.9  934.26
  5331.6  935.49  5347.6  936.82  5367.9  936.56  5385.1  937.33  5391.0  936.78
  5396.8  937.36  5434.5  936.93  5515.6  938.01  5602.7  940.68  5663.8  941.68
#Mann=3,-1,0
  4479.5    0.05       0  4999.6   0.033       0  5003.6    0.05       0
Bank Sta=4999.6,5003.6
Exp/Cntr=0.3,0.1

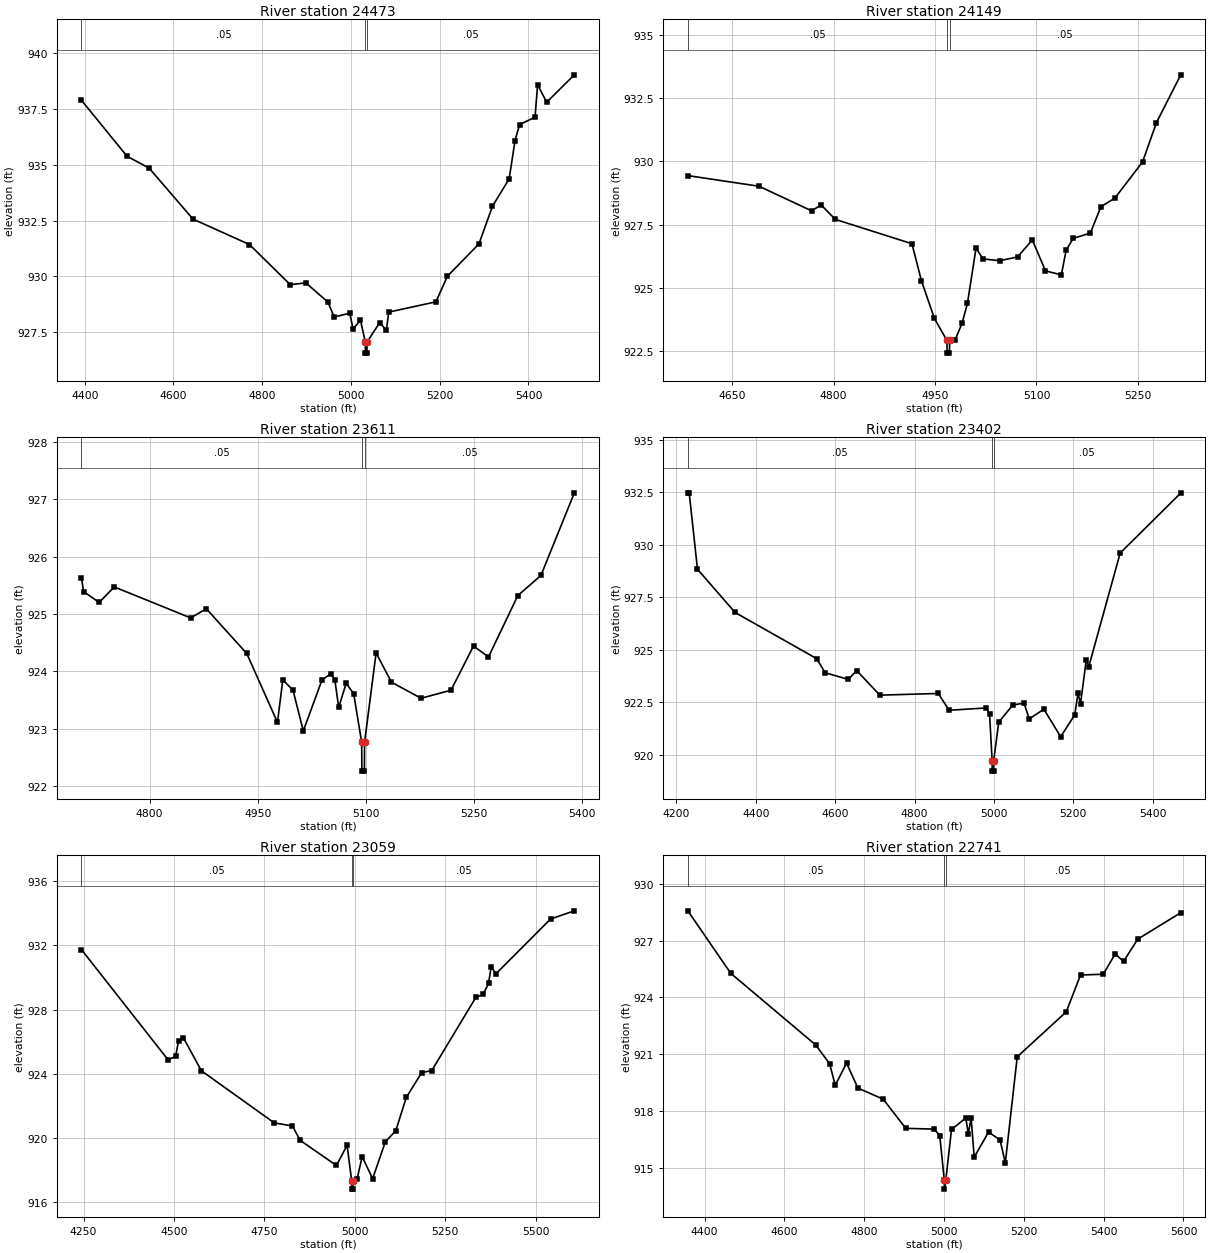
Type RM Length L Ch R = 1,24473,324,324,324
BEGIN DESCRIPTION:
Long Branch 52.0
END DESCRIPTION:
XS GIS Cut Line= 3
      2272501.53      7121462.83      2272069.08      7121016.77
      2271587.49      7120928.99
#Sta/Elev= 30
  4392.6  937.90  4495.3  935.39  4544.9  934.86  4644.0  932.57  4771.3  931.43
  4863.1  929.63  4898.4  929.71  4948.0  928.85  4962.2  928.18  4997.4  928.35
  5004.6  927.64  5021.4  928.04  5032.3  927.06  5032.5  926.56  5036.0  926.56
  5036.3  927.06  5064.8  927.93  5079.8  927.58  5085.1  928.40  5191.4  928.86
  5217.3  930.01  5288.4  931.46  5318.9  933.15  5356.4  934.37  5369.7  936.09
  5379.9  936.81  5414.8  937.14  5420.5  938.60  5440.9  937.81  5503.4  939.04
#Mann=3,-1,0
  4392.6    0.05       0  5032.3   0.033       0  5036.3    0.05       0
Bank Sta=5032.3,5036.3
Exp/Cntr=0.3,0.1

Type RM Length L Ch R = 1,24149,538,538,538
BEGIN DESCRIPTION:
Mapping XS 8cba08cd
END DESCRIPTION:
XS GIS Cut Line= 3
      2272495.08      7120992.64      2272244.14      7120749.99
      2271873.93      7120665.02
#Sta/Elev= 30
  4584.5  929.44  4689.8  929.02  4767.5  928.05  4781.6  928.28  4802.7  927.71
  4915.9  926.75  4930.0  925.28  4949.1  923.80  4967.6  922.93  4967.9  922.43
  4971.4  922.43  4971.6  922.93  4979.9  922.96  4990.1  923.62  4997.9  924.39
  5010.7  926.58  5020.9  926.15  5045.9  926.08  5072.2  926.23  5093.9  926.90
  5113.3  925.68  5136.8  925.52  5144.0  926.50  5154.3  926.96  5179.7  927.17
  5195.3  928.21  5215.9  928.55  5256.9  929.98  5277.4  931.53  5313.4  933.42
#Mann=3,-1,0
  4584.5    0.05       0  4967.6   0.033       0  4971.6    0.05       0
Bank Sta=4967.6,4971.6
Exp/Cntr=0.3,0.1

Type RM Length L Ch R = 1,23611,209,209,209
BEGIN DESCRIPTION:
Mapping XS 8a56a644
END DESCRIPTION:
XS GIS Cut Line= 3
      2272647.30      7120615.94      2272396.55      7120388.50
      2272064.32      7120294.92
#Sta/Elev= 30
  4705.5  925.63  4708.4  925.39  4730.1  925.20  4751.0  925.47  4857.1  924.93
  4878.7  925.09  4934.8  924.31  4977.4  923.11  4984.8  923.85  4999.0  923.67
  5013.2  922.96  5039.2  923.85  5051.8  923.96  5057.0  923.85  5062.3  923.37
  5072.7  923.79  5083.1  923.61  5094.2  922.76  5094.5  922.26  5098.0  922.26
  5098.2  922.76  5114.2  924.32  5135.5  923.81  5176.6  923.53  5218.1  923.67
  5249.3  924.44  5270.1  924.25  5310.8  925.32  5342.8  925.67  5389.2  927.11
#Mann=3,-1,0
  4705.5    0.05       0  5094.2   0.033       0  5098.2    0.05       0
Bank Sta=5094.2,5098.2
Exp/Cntr=0.3,0.1

Type RM Length L Ch R = 1,23402,343,343,343
BEGIN DESCRIPTION:
Long Branch 50.0
END DESCRIPTION:
XS GIS Cut Line= 3
      2273139.82      7120624.11      2272479.65      7120225.27
      2272103.20      7119942.36
#Sta/Elev= 30
  4228.7  932.48  4232.1  932.48  4253.0  928.84  4347.7  926.78  4553.3  924.58
  4574.7  923.91  4632.9  923.59  4654.3  924.01  4712.5  922.84  4859.9  922.92
  4887.1  922.12  4981.2  922.23  4989.1  921.93  4995.5  919.72  4995.7  919.22
  4999.2  919.22  4999.5  919.72  5012.1  921.55  5047.5  922.37  5075.9  922.46
  5089.1  921.71  5125.9  922.17  5168.3  920.86  5203.7  921.90  5212.0  922.94
  5218.3  922.43  5232.8  924.53  5239.1  924.20  5318.2  929.61  5470.9  932.47
#Mann=3,-1,0
  4228.7    0.05       0  4995.5   0.033       0  4999.5    0.05       0
Bank Sta=4995.5,4999.5
Exp/Cntr=0.3,0.1

Type RM Length L Ch R = 1,23059,318,318,318
BEGIN DESCRIPTION:
Long Branch 49.0
END DESCRIPTION:
XS GIS Cut Line= 3
      2273336.81      7120446.12      2272723.39      7120004.41
      2272249.14      7119626.68
#Sta/Elev= 30
  4244.3  931.73  4483.8  924.87  4504.7  925.09  4512.7  926.06  4525.6  926.26
  4575.9  924.19  4777.2  920.95  4827.5  920.76  4848.4  919.87  4949.0  918.30
  4978.4  919.56  4991.2  917.33  4991.4  916.83  4994.9  916.83  4995.2  917.33
  5006.2  917.48  5020.1  918.85  5049.0  917.48  5084.2  919.78  5113.0  920.46
  5141.9  922.53  5184.8  924.08  5212.3  924.20  5334.1  928.75  5354.9  928.95
  5369.3  929.63  5376.6  930.65  5390.1  930.23  5540.7  933.63  5606.5  934.14
#Mann=3,-1,0
  4244.3    0.05       0  4991.2   0.033       0  4995.2    0.05       0
Bank Sta=4991.2,4995.2
Exp/Cntr=0.3,0.1

Type RM Length L Ch R = 1,22741,387,387,387
BEGIN DESCRIPTION:
Long Branch 48.0
END DESCRIPTION:
XS GIS Cut Line= 3
      2273403.89      7120207.21      2272931.76      7119766.17
      2272444.58      7119434.93
#Sta/Elev= 30
  4358.0  928.57  4465.5  925.27  4678.1  921.49  4713.2  920.50  4727.4  919.35
  4755.7  920.53  4784.1  919.21  4847.6  918.62  4904.2  917.08  4975.1  917.04
  4989.2  916.70  5000.5  914.37  5000.8  913.87  5004.5  914.37  5018.7  917.02
  5054.6  917.63  5060.7  916.80  5067.9  917.61  5075.6  915.56  5111.5  916.88
  5140.4  916.47  5153.5  915.25  5183.4  920.86  5306.1  923.23  5342.0  925.18
  5398.9  925.22  5428.8  926.29  5449.8  925.90  5485.7  927.08  5593.2  928.47
#Mann=3,-1,0
  4358.0    0.05       0  5000.5   0.033       0  5004.5    0.05       0
Bank Sta=5000.5,5004.5
Exp/Cntr=0.3,0.1

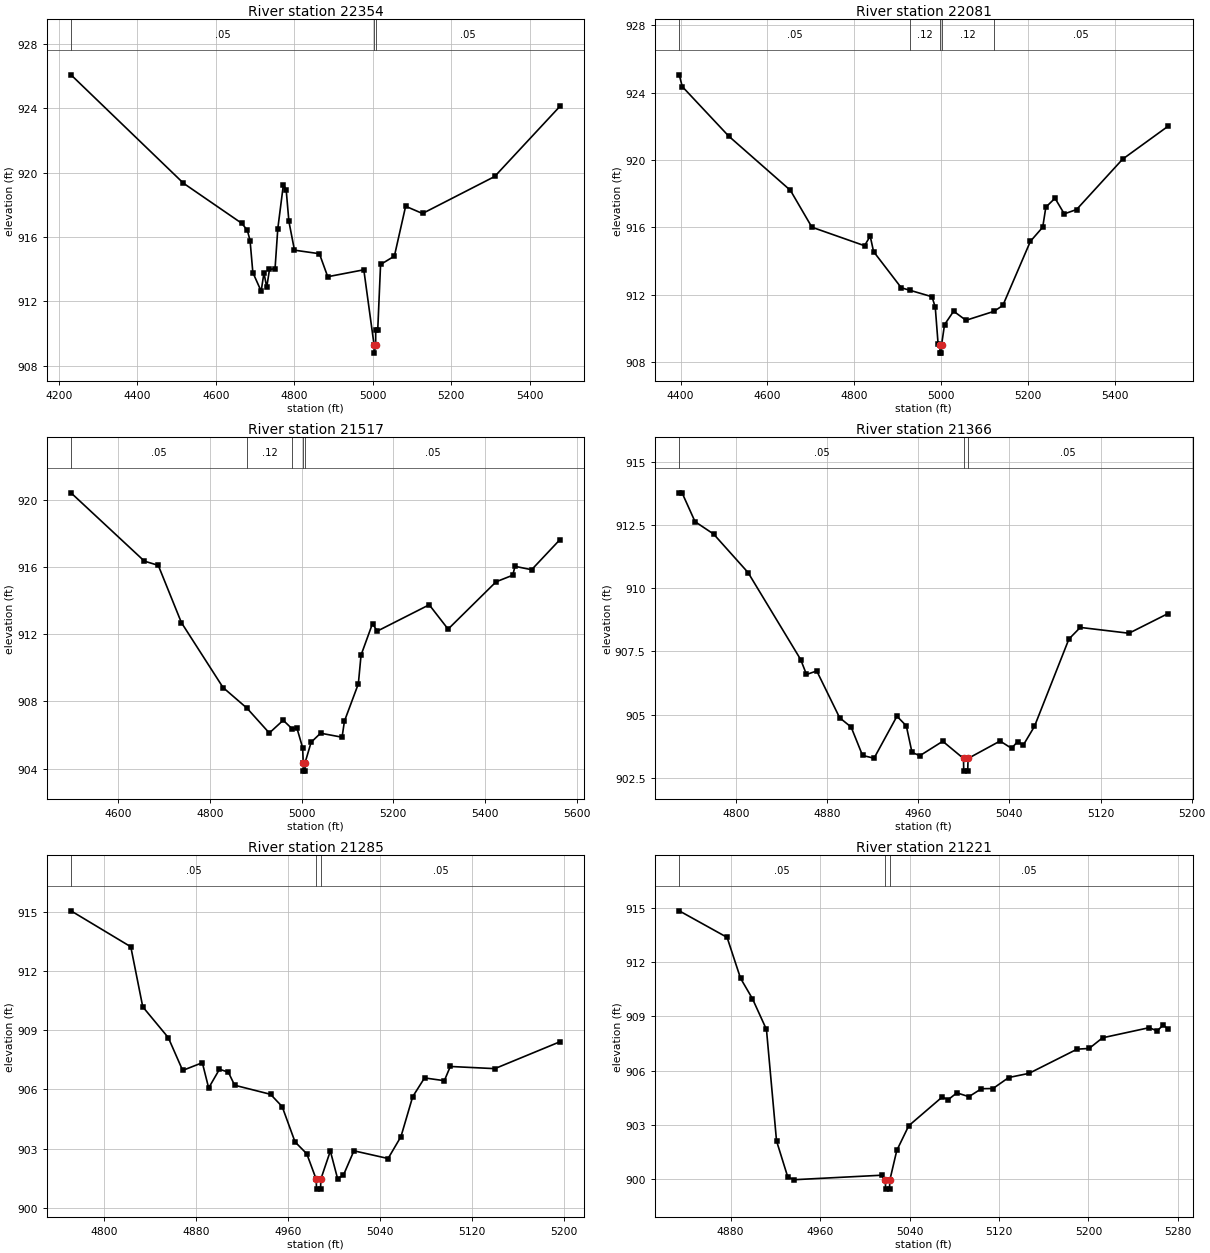
Type RM Length L Ch R = 1,22354,273,273,273
BEGIN DESCRIPTION:
Long Branch 47.0
END DESCRIPTION:
XS GIS Cut Line= 3
      2273591.41      7119993.25      2273041.04      7119444.18
      2272677.29      7119148.15
#Sta/Elev= 30
  4230.6  926.09  4517.4  919.35  4665.9  916.86  4680.1  916.43  4687.1  915.79
  4694.2  913.80  4715.4  912.64  4722.5  913.78  4729.6  912.88  4736.6  913.99
  4750.8  914.04  4757.8  916.53  4772.0  919.25  4779.1  918.96  4786.1  916.98
  4800.3  915.19  4863.9  914.97  4885.1  913.54  4977.1  913.97  5003.3  909.29
  5003.6  908.79  5007.3  909.29  5007.4  910.25  5012.6  910.25  5019.8  914.30
  5055.0  914.82  5083.7  917.92  5126.7  917.47  5310.7  919.77  5477.0  924.13
#Mann=3,-1,0
  4230.6    0.05       0  5003.3   0.033       0  5007.3    0.05       0
Bank Sta=5003.3,5007.3
Exp/Cntr=0.3,0.1

Type RM Length L Ch R = 1,22081,564,564,564
BEGIN DESCRIPTION:
Long Branch 46.0
END DESCRIPTION:
XS GIS Cut Line= 3
      2273678.97      7119859.96      2273296.22      7119393.76
      2272915.69      7119034.97
#Sta/Elev= 30
  4396.8  925.06  4403.9  924.36  4510.8  921.42  4652.9  918.20  4702.4  916.01
  4823.7  914.91  4836.7  915.48  4844.5  914.56  4908.4  912.41  4928.6  912.26
  4979.0  911.88  4986.6  911.26  4993.1  909.08  4997.2  909.03  4997.4  908.53
  5000.9  908.53  5001.2  909.03  5007.9  910.22  5028.9  911.02  5057.3  910.48
  5121.6  911.01  5142.2  911.36  5205.7  915.17  5234.1  916.01  5241.3  917.20
  5262.4  917.73  5283.8  916.80  5312.1  917.06  5418.1  920.05  5523.0  922.01
#Mann=5,-1,0
  4396.8    0.05       0  4928.6    0.12       0  4997.2    0.07       0
  5001.2    0.12       0  5121.6    0.05       0
Bank Sta=4997.2,5001.2
Exp/Cntr=0.3,0.1

Type RM Length L Ch R = 1,21517,151,151,151
BEGIN DESCRIPTION:
Long Branch 45.0
END DESCRIPTION:
XS GIS Cut Line= 3
      2273653.16      7119708.61      2273584.86      7119207.92
      2273449.60      7118663.29
#Sta/Elev= 30
  4496.9  920.43  4657.0  916.36  4687.3  916.11  4737.7  912.70  4828.6  908.83
  4880.8  907.60  4929.5  906.12  4959.8  906.88  4978.9  906.38  4990.0  906.39
  5002.2  905.24  5003.5  904.35  5003.8  903.85  5007.3  903.85  5007.5  904.35
  5020.7  905.57  5041.3  906.11  5088.2  905.87  5093.4  906.83  5123.7  909.05
  5129.6  910.76  5154.6  912.64  5164.9  912.19  5278.3  913.76  5319.5  912.31
  5424.2  915.13  5460.4  915.52  5465.5  916.05  5501.7  915.85  5563.4  917.64
#Mann=5,-1,0
  4496.9    0.05       0  4880.8    0.12       0  4978.9    0.05       0
  5003.5   0.033       0  5007.5    0.05       0
Bank Sta=5003.5,5007.5
Exp/Cntr=0.3,0.1

Type RM Length L Ch R = 1,21366,81,81,81
BEGIN DESCRIPTION:
Mapping XS e05a1497
END DESCRIPTION:
XS GIS Cut Line= 2
      2273702.66      7119480.05      2273747.89      7119053.34
#Sta/Elev= 30
  4750.2  913.77  4752.7  913.77  4764.1  912.63  4780.4  912.14  4810.6  910.62
  4856.8  907.18  4861.9  906.59  4870.9  906.73  4891.0  904.88  4901.1  904.51
  4911.1  903.39  4921.2  903.28  4941.3  904.94  4949.5  904.56  4954.5  903.51
  4961.4  903.38  4981.5  903.95  4999.7  903.27  4999.9  902.77  5003.4  902.77
  5003.7  903.27  5031.8  903.96  5041.9  903.67  5047.2  903.94  5052.2  903.80
  5062.0  904.54  5092.2  907.99  5102.2  908.45  5144.9  908.22  5179.3  909.00
#Mann=3,-1,0
  4750.2    0.05       0  4999.7   0.033       0  5003.7    0.05       0
Bank Sta=4999.7,5003.7
Exp/Cntr=0.3,0.1

Type RM Length L Ch R = 1,21285,64,64,64
BEGIN DESCRIPTION:
Mapping XS 2bc42557
END DESCRIPTION:
XS GIS Cut Line= 3
      2273894.50      7119466.19      2273814.56      7119300.94
      2273762.94      7119064.99
#Sta/Elev= 30
  4771.3  915.04  4823.3  913.22  4833.7  910.18  4855.9  908.62  4868.4  906.96
  4885.5  907.35  4891.0  906.07  4900.4  907.02  4908.1  906.87  4913.6  906.21
  4944.8  905.75  4954.9  905.13  4966.1  903.34  4976.3  902.74  4984.5  901.45
  4984.8  900.95  4988.3  900.95  4988.5  901.45  4996.8  902.88  5003.1  901.48
  5008.2  901.66  5017.3  902.89  5047.0  902.50  5058.2  903.61  5068.4  905.63
  5078.7  906.58  5095.9  906.44  5101.1  907.16  5139.8  907.05  5196.4  908.41
#Mann=3,-1,0
  4771.3    0.05       0  4984.5   0.033       0  4988.5    0.05       0
Bank Sta=4984.5,4988.5
Exp/Cntr=0.3,0.1

Type RM Length L Ch R = 1,21221,205,205,205
BEGIN DESCRIPTION:
Mapping XS b3b92d22
END DESCRIPTION:
XS GIS Cut Line= 2
      2273921.24      7119440.95      2273761.03      7119034.28
#Sta/Elev= 30
  4834.1  914.85  4876.9  913.38  4888.9  911.12  4899.6  909.98  4912.1  908.28
  4921.1  902.11  4931.1  900.12  4936.5  899.96  5015.0  900.21  5018.4  899.94
  5018.6  899.44  5022.1  899.44  5022.4  899.94  5028.6  901.58  5039.3  902.95
  5069.2  904.54  5074.5  904.39  5082.3  904.77  5093.1  904.56  5104.3  905.00
  5114.6  905.01  5128.7  905.62  5146.8  905.85  5189.8  907.19  5200.6  907.23
  5212.6  907.82  5254.3  908.38  5261.4  908.20  5266.8  908.53  5271.2  908.29
#Mann=3,-1,0
  4834.1    0.05       0  5018.4   0.033       0  5022.4    0.05       0
Bank Sta=5018.4,5022.4
Exp/Cntr=0.3,0.1

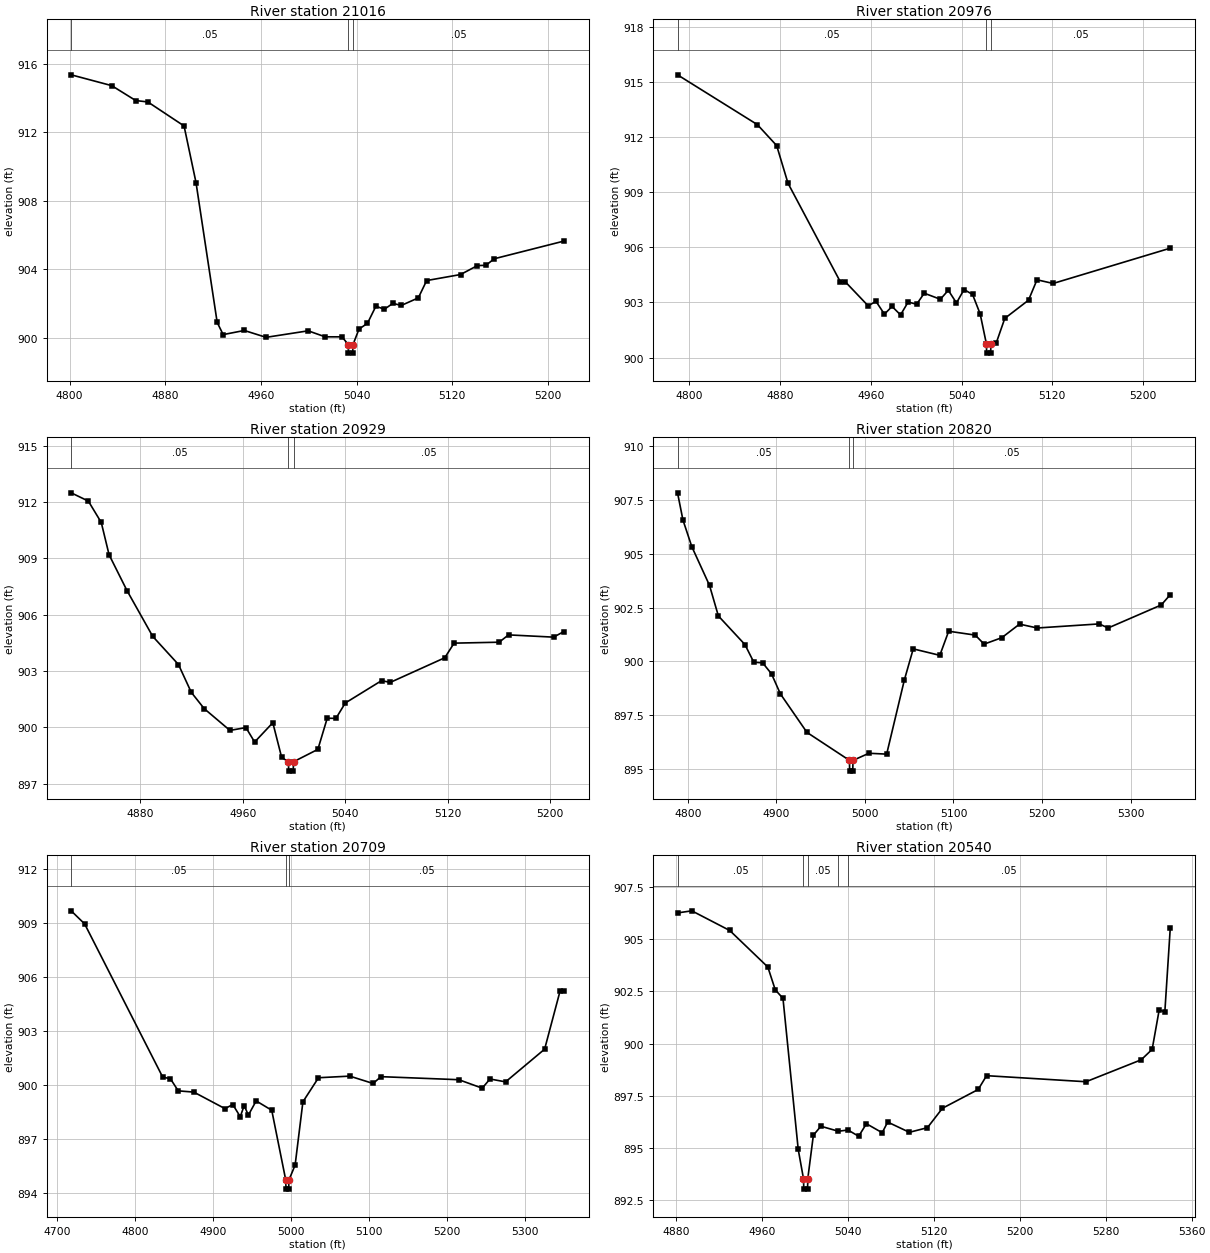
Type RM Length L Ch R = 1,21016,40,40,40
BEGIN DESCRIPTION:
Mapping XS 8f576ea0
END DESCRIPTION:
XS GIS Cut Line= 3
      2274049.74      7119373.60      2274030.06      7119219.04
      2273851.11      7119035.57
#Sta/Elev= 30
  4801.3  915.34  4835.2  914.71  4855.3  913.84  4865.4  913.76  4895.7  912.36
  4905.7  909.06  4923.4  900.91  4928.4  900.20  4946.1  900.44  4964.3  900.04
  4999.5  900.42  5013.7  900.07  5027.8  900.07  5033.0  899.62  5033.2  899.12
  5036.7  899.12  5037.0  899.62  5042.0  900.52  5049.1  900.86  5056.1  901.85
  5063.3  901.68  5070.3  902.02  5077.4  901.90  5091.6  902.34  5098.6  903.35
  5126.9  903.70  5141.0  904.22  5148.2  904.24  5155.1  904.62  5213.4  905.65
#Mann=3,-1,0
  4801.3    0.05       0  5033.0   0.033       0  5037.0    0.05       0
Bank Sta=5033,5037
Exp/Cntr=0.3,0.1

Type RM Length L Ch R = 1,20976,47,47,47
BEGIN DESCRIPTION:
Mapping XS a2bcc66f
END DESCRIPTION:
XS GIS Cut Line= 3
      2274068.36      7119337.21      2274059.15      7119193.02
      2273843.36      7118999.40
#Sta/Elev= 30
  4789.6  915.38  4860.0  912.67  4877.0  911.53  4887.0  909.48  4933.1  904.12
  4937.5  904.12  4957.7  902.81  4964.5  903.06  4972.0  902.36  4978.7  902.78
  4986.2  902.32  4992.9  903.02  5000.4  902.90  5007.1  903.50  5021.3  903.17
  5028.3  903.66  5035.5  902.97  5042.2  903.70  5049.7  903.43  5056.4  902.37
  5061.9  900.74  5062.1  900.24  5065.6  900.24  5065.9  900.74  5070.6  900.80
  5078.1  902.13  5099.0  903.12  5106.5  904.23  5120.7  904.03  5224.0  905.95
#Mann=3,-1,0
  4789.6    0.05       0  5061.9   0.033       0  5065.9    0.05       0
Bank Sta=5061.9,5065.9
Exp/Cntr=0.3,0.1

Type RM Length L Ch R = 1,20929,109,109,109
BEGIN DESCRIPTION:
Mapping XS 13b74822
END DESCRIPTION:
XS GIS Cut Line= 3
      2274067.11      7119263.35      2274053.94      7119134.28
      2273868.48      7118959.03
#Sta/Elev= 30
  4825.9  912.49  4839.3  912.05  4849.4  910.91  4855.5  909.19  4869.5  907.28
  4889.6  904.84  4909.7  903.34  4919.7  901.86  4929.8  900.99  4949.9  899.83
  4962.4  899.98  4969.2  899.21  4983.4  900.24  4990.3  898.39  4995.6  898.16
  4995.8  897.66  4999.3  897.66  4999.6  898.16  5018.6  898.82  5025.9  900.48
  5032.7  900.47  5040.0  901.29  5068.3  902.48  5075.2  902.39  5117.7  903.70
  5125.0  904.48  5160.2  904.53  5167.5  904.92  5202.7  904.80  5210.8  905.10
#Mann=3,-1,0
  4825.9    0.05       0  4995.6   0.033       0  4999.6    0.05       0
Bank Sta=4995.6,4999.6
Exp/Cntr=0.3,0.1

Type RM Length L Ch R = 1,20820,111,111,111
BEGIN DESCRIPTION:
Mapping XS 9c39046c
END DESCRIPTION:
XS GIS Cut Line= 2
      2274069.04      7119216.08      2274061.59      7118659.83
#Sta/Elev= 30
  4788.5  907.83  4794.6  906.57  4804.6  905.33  4824.6  903.53  4834.6  902.11
  4864.6  900.78  4874.6  899.96  4884.6  899.93  4894.6  899.42  4904.6  898.49
  4934.6  896.70  4982.6  895.40  4982.8  894.90  4986.3  894.90  4986.6  895.40
  5004.6  895.73  5024.6  895.69  5044.6  899.14  5054.6  900.58  5084.6  900.28
  5094.6  901.40  5124.6  901.22  5134.6  900.80  5154.6  901.10  5174.6  901.73
  5194.6  901.55  5264.6  901.74  5274.6  901.55  5334.6  902.62  5344.8  903.10
#Mann=3,-1,0
  4788.5    0.05       0  4982.6   0.033       0  4986.6    0.05       0
Bank Sta=4982.6,4986.6
Exp/Cntr=0.3,0.1

Type RM Length L Ch R = 1,20709,169,169,169
BEGIN DESCRIPTION:
Mapping XS a978625c
END DESCRIPTION:
XS GIS Cut Line= 2
      2274140.18      7119197.32      2274122.54      7118565.16
#Sta/Elev= 30
  4717.6  909.69  4734.9  908.96  4835.0  900.44  4845.0  900.34  4855.0  899.67
  4875.0  899.60  4915.0  898.68  4925.0  898.91  4934.6  898.23  4939.6  898.85
  4945.0  898.32  4955.0  899.11  4975.0  898.59  4993.0  894.70  4993.3  894.20
  4996.8  894.20  4997.0  894.70  5005.0  895.54  5015.0  899.06  5035.0  900.40
  5075.1  900.49  5105.1  900.08  5115.1  900.46  5215.1  900.29  5245.1  899.82
  5255.1  900.33  5275.1  900.17  5325.2  901.99  5345.1  905.24  5350.0  905.24
#Mann=3,-1,0
  4717.6    0.05       0  4993.0   0.033       0  4997.0    0.05       0
Bank Sta=4993,4997
Exp/Cntr=0.3,0.1

Type RM Length L Ch R = 1,20540,289,289,289
BEGIN DESCRIPTION:
Mapping XS 0d57d825
END DESCRIPTION:
XS GIS Cut Line= 3
      2274369.82      7118967.91      2274234.60      7118836.77
      2274171.96      7118573.59
#Sta/Elev= 30
  4881.2  906.26  4894.5  906.36  4929.8  905.42  4965.3  903.67  4972.2  902.58
  4979.4  902.17  4993.6  894.94  4998.5  893.54  4998.8  893.04  5002.3  893.04
  5002.5  893.54  5007.7  895.62  5014.7  896.05  5031.0  895.81  5039.9  895.87
  5049.9  895.57  5057.1  896.17  5071.8  895.74  5076.9  896.25  5097.1  895.76
  5113.9  895.98  5127.9  896.91  5161.2  897.81  5169.0  898.47  5261.6  898.18
  5313.0  899.23  5323.2  899.73  5329.8  901.63  5335.0  901.51  5340.1  905.56
#Mann=5,-1,0
  4881.2    0.05       0  4998.5   0.033       0  5002.5    0.05       0
  5031.0    0.12       0  5039.9    0.05       0
Bank Sta=4998.5,5002.5
Exp/Cntr=0.3,0.1

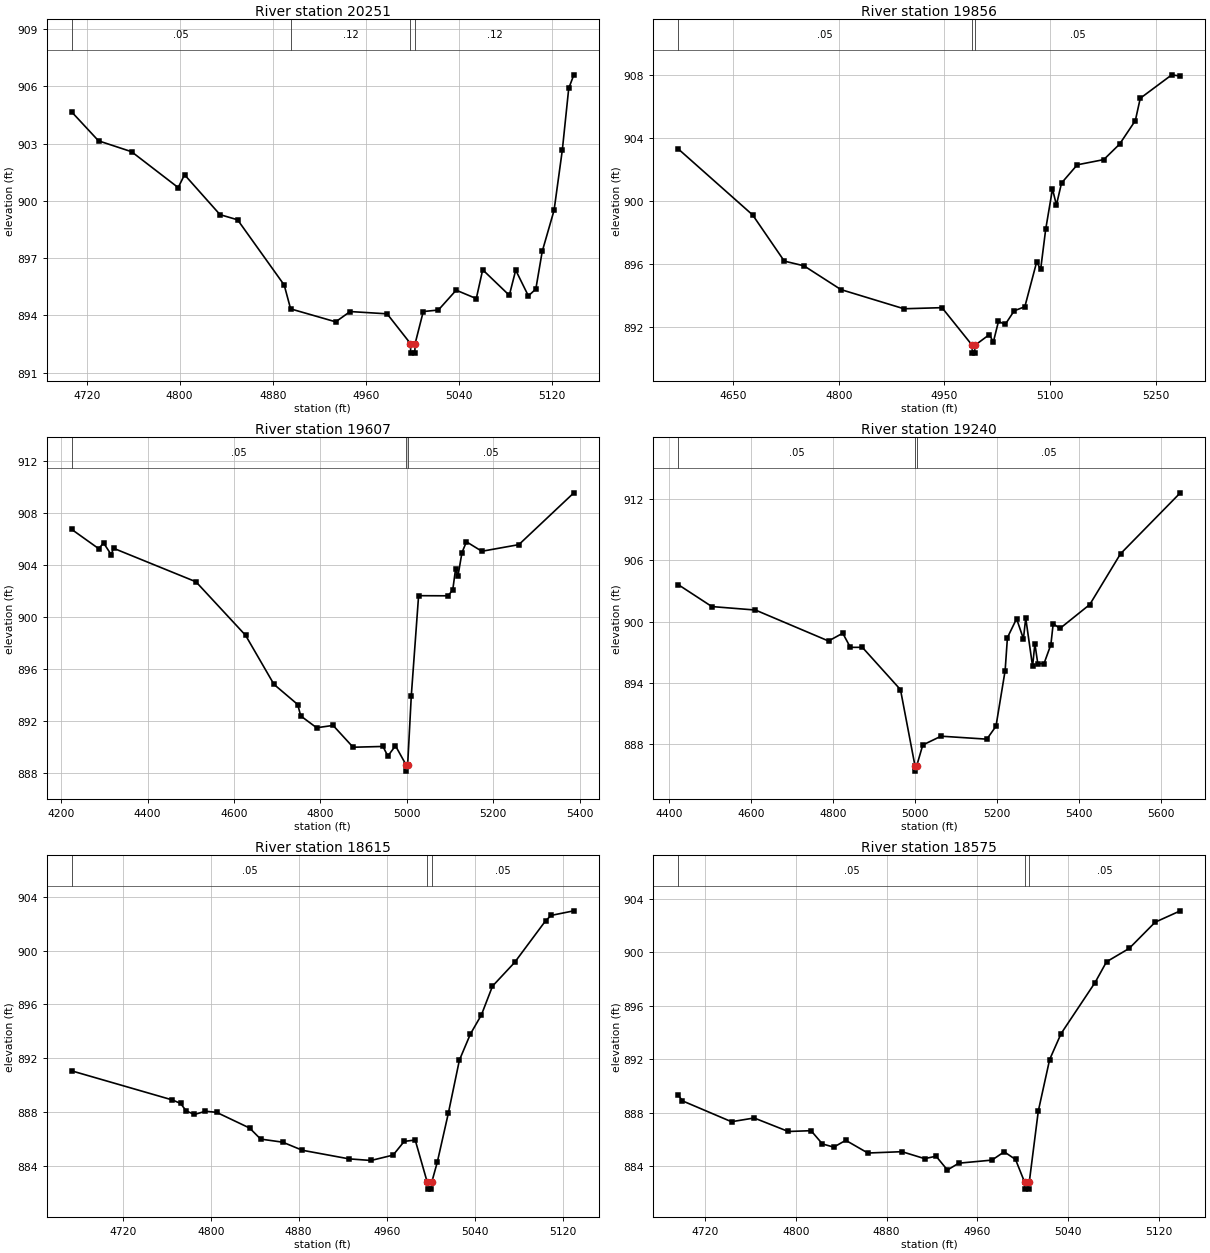
Type RM Length L Ch R = 1,20251,395,395,395
BEGIN DESCRIPTION:
Mapping XS 7472f5d4
END DESCRIPTION:
XS GIS Cut Line= 2
      2274453.96      7118925.46      2274270.46      7118534.58
#Sta/Elev= 30
  4707.2  904.66  4730.2  903.15  4758.6  902.58  4798.7  900.70  4804.2  901.37
  4834.7  899.28  4849.8  899.01  4889.9  895.59  4895.4  894.34  4934.2  893.66
  4946.6  894.20  4978.4  894.08  4998.5  892.52  4998.7  892.02  5002.2  892.02
  5002.5  892.52  5009.5  894.20  5022.5  894.28  5037.8  895.32  5055.1  894.88
  5060.6  896.39  5083.5  895.05  5089.0  896.37  5099.9  895.02  5106.3  895.38
  5111.8  897.35  5122.0  899.51  5129.1  902.67  5134.6  905.90  5139.0  906.61
#Mann=4,-1,0
  4707.2    0.05       0  4895.4    0.12       0  4998.5    0.07       0
  5002.5    0.12       0
Bank Sta=4998.5,5002.5
Exp/Cntr=0.3,0.1

Type RM Length L Ch R = 1,19856,249,249,249
BEGIN DESCRIPTION:
Mapping XS bdb4f2b8
END DESCRIPTION:
XS GIS Cut Line= 2
      2274672.70      7118886.42      2274354.83      7118249.20
#Sta/Elev= 30
  4572.4  903.32  4678.0  899.12  4722.8  896.19  4750.7  895.89  4803.1  894.38
  4892.5  893.16  4946.5  893.23  4989.3  890.84  4989.5  890.34  4993.0  890.34
  4993.3  890.84  5013.7  891.52  5019.3  891.04  5026.6  892.36  5036.1  892.16
  5048.9  893.03  5064.0  893.29  5080.8  896.14  5086.4  895.66  5093.6  898.22
  5103.2  900.77  5108.8  899.76  5116.0  901.15  5138.3  902.31  5175.9  902.64
  5198.3  903.62  5220.7  905.12  5227.7  906.54  5272.4  908.03  5284.5  907.95
#Mann=3,-1,0
  4572.4    0.05       0  4989.3   0.033       0  4993.3    0.05       0
Bank Sta=4989.3,4993.3
Exp/Cntr=0.3,0.1

Type RM Length L Ch R = 1,19607,367,367,367
BEGIN DESCRIPTION:
Long Branch 41.0
END DESCRIPTION:
XS GIS Cut Line= 3
      2274992.06      7119066.82      2274673.80      7118359.52
      2274538.96      7117997.41
#Sta/Elev= 30
  4224.4  906.74  4286.7  905.26  4298.0  905.70  4315.6  904.80  4321.1  905.29
  4511.8  902.71  4626.6  898.59  4692.4  894.81  4747.3  893.26  4754.3  892.38
  4791.1  891.47  4829.2  891.65  4875.5  889.97  4944.6  890.03  4955.9  889.29
  4973.6  890.08  4997.8  888.63  4998.0  888.13  5001.8  888.63  5010.2  893.94
  5027.1  901.64  5095.5  901.63  5106.2  902.10  5112.8  903.72  5118.1  903.14
  5127.5  904.96  5137.8  905.79  5173.5  905.06  5259.1  905.57  5386.4  909.56
#Mann=3,-1,0
  4224.4    0.05       0  4997.8   0.033       0  5001.8    0.05       0
Bank Sta=4997.8,5001.8
Exp/Cntr=0.3,0.1

Type RM Length L Ch R = 1,19240,625,625,625
BEGIN DESCRIPTION:
Long Branch 40.0
END DESCRIPTION:
XS GIS Cut Line= 3
      2275185.48      7118930.34      2274962.38      7118392.12
      2274673.69      7117819.95
#Sta/Elev= 30
  4422.7  903.60  4504.6  901.46  4610.9  901.12  4788.9  898.10  4823.6  898.86
  4842.1  897.48  4871.4  897.48  4964.3  893.35  4999.7  885.90  4999.9  885.40
  5003.7  885.90  5018.6  887.95  5063.2  888.81  5174.7  888.52  5197.0  889.78
  5219.3  895.21  5224.9  898.43  5247.2  900.27  5263.9  898.31  5269.5  900.34
  5286.2  895.63  5291.8  897.84  5298.9  895.88  5314.1  895.90  5330.8  897.75
  5336.4  899.78  5353.1  899.33  5425.6  901.66  5500.5  906.61  5646.2  912.56
#Mann=3,-1,0
  4422.7    0.05       0  4999.7   0.033       0  5003.7    0.05       0
Bank Sta=4999.7,5003.7
Exp/Cntr=0.3,0.1

Type RM Length L Ch R = 1,18615,40,40,40
BEGIN DESCRIPTION:
Mapping XS 1c76d45f
END DESCRIPTION:
XS GIS Cut Line= 2
      2275223.14      7118411.13      2275181.99      7117956.28
#Sta/Elev= 30
  4673.6  891.05  4765.1  888.89  4772.6  888.63  4777.6  888.08  4785.2  887.81
  4795.2  888.05  4805.3  887.97  4835.4  886.80  4845.4  885.98  4865.5  885.75
  4883.3  885.15  4925.8  884.51  4945.8  884.39  4965.9  884.79  4976.0  885.81
  4986.0  885.91  4997.0  882.76  4997.3  882.26  5000.8  882.26  5001.0  882.76
  5006.1  884.27  5016.1  887.89  5026.2  891.85  5036.2  893.79  5046.2  895.21
  5056.3  897.35  5076.4  899.11  5104.7  902.22  5109.7  902.61  5130.3  902.95
#Mann=3,-1,0
  4673.6    0.05       0  4997.0   0.033       0  5001.0    0.05       0
Bank Sta=4997,5001
Exp/Cntr=0.3,0.1

Type RM Length L Ch R = 1,18575,114,114,114
BEGIN DESCRIPTION:
Mapping XS c10da704
END DESCRIPTION:
XS GIS Cut Line= 2
      2275254.40      7118376.86      2275222.23      7117935.03
#Sta/Elev= 30
  4696.1  889.31  4699.8  888.88  4743.1  887.32  4763.1  887.60  4793.2  886.59
  4813.3  886.65  4823.3  885.66  4833.3  885.42  4843.9  885.93  4863.4  884.98
  4893.5  885.08  4913.5  884.56  4923.6  884.74  4933.6  883.71  4943.6  884.22
  4972.9  884.45  4983.7  885.07  4993.7  884.50  5001.8  882.78  5002.0  882.28
  5005.5  882.28  5005.8  882.78  5013.8  888.12  5023.8  891.97  5033.9  893.91
  5063.9  897.73  5074.0  899.28  5094.0  900.28  5116.9  902.24  5139.1  903.09
#Mann=3,-1,0
  4696.1    0.05       0  5001.8   0.033       0  5005.8    0.05       0
Bank Sta=5001.8,5005.8
Exp/Cntr=0.3,0.1