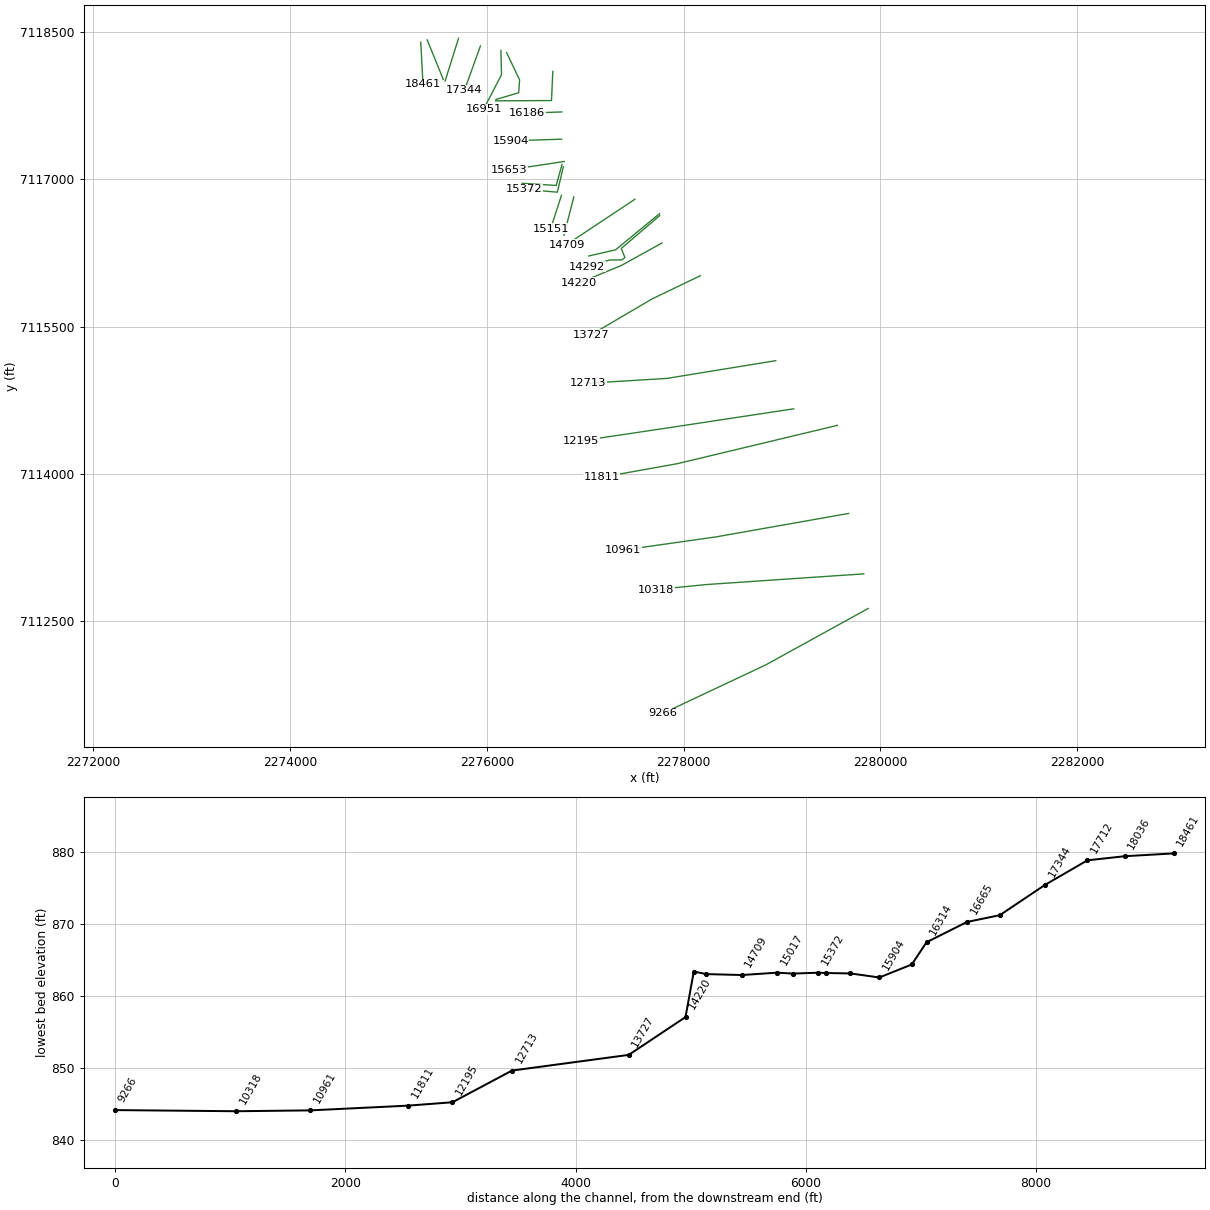
HEC-RAS study Long Branch.prj: Long Branch Base Level Engineering

--- Long Branch.g01 (geometry) --- (continued)

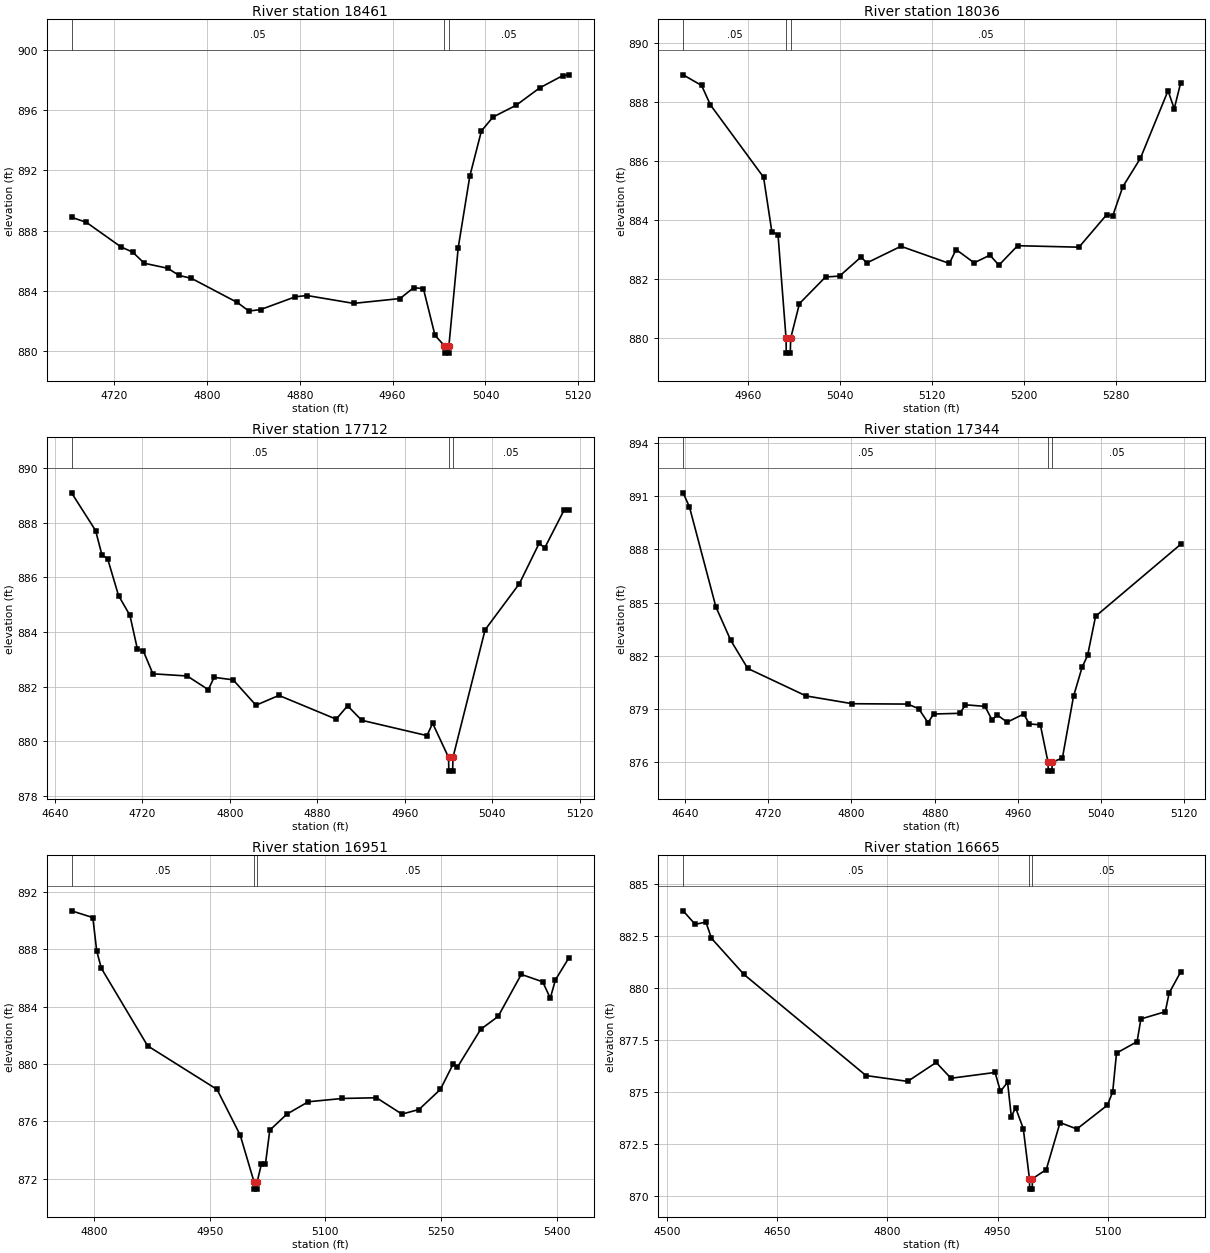
Type RM Length L Ch R = 1,18461,425,425,425
BEGIN DESCRIPTION:
Mapping XS 512f2236
END DESCRIPTION:
XS GIS Cut Line= 2
      2275328.86      7118392.64      2275351.13      7117964.72
#Sta/Elev= 30
  4683.4  888.88  4696.1  888.55  4726.1  886.91  4736.1  886.57  4746.1  885.83
  4766.2  885.50  4776.2  885.02  4786.7  884.83  4826.2  883.23  4836.2  882.66
  4846.3  882.76  4876.3  883.61  4886.3  883.69  4926.4  883.17  4966.4  883.49
  4978.1  884.21  4986.5  884.15  4996.5  881.05  5004.5  880.37  5004.7  879.87
  5008.2  879.87  5008.5  880.37  5016.5  886.86  5026.5  891.61  5036.5  894.61
  5046.5  895.53  5066.6  896.32  5086.6  897.46  5106.6  898.28  5111.9  898.33
#Mann=3,-1,0
  4683.4    0.05       0  5004.5   0.033       0  5008.5    0.05       0
Bank Sta=5004.5,5008.5
Exp/Cntr=0.3,0.1

Type RM Length L Ch R = 1,18036,324,324,324
BEGIN DESCRIPTION:
Mapping XS eb5cd580
END DESCRIPTION:
XS GIS Cut Line= 2
      2275394.17      7118414.93      2275557.50      7118013.38
#Sta/Elev= 30
  4903.1  888.91  4919.2  888.55  4926.9  887.89  4973.2  885.44  4980.4  883.60
  4985.8  883.49  4992.8  879.98  4993.0  879.48  4996.5  879.48  4996.8  879.98
  5004.5  881.16  5027.2  882.06  5039.4  882.09  5058.0  882.73  5063.4  882.54
  5092.9  883.10  5135.1  882.52  5141.0  882.99  5156.7  882.54  5170.5  882.80
  5178.3  882.46  5194.6  883.12  5248.1  883.07  5272.2  884.17  5277.5  884.13
  5286.3  885.12  5301.6  886.08  5325.7  888.37  5331.1  887.76  5336.6  888.62
#Mann=3,-1,0
  4903.1    0.05       0  4992.8   0.033       0  4996.8    0.05       0
Bank Sta=4992.8,4996.8
Exp/Cntr=0.3,0.1

Type RM Length L Ch R = 1,17712,368,368,368
BEGIN DESCRIPTION:
Mapping XS 1a191b32
END DESCRIPTION:
XS GIS Cut Line= 2
      2275712.47      7118431.00      2275576.49      7117996.80
#Sta/Elev= 30
  4655.1  889.09  4677.1  887.71  4682.9  886.82  4688.1  886.68  4698.1  885.33
  4708.5  884.61  4715.3  883.38  4720.6  883.32  4729.5  882.47  4760.9  882.39
  4780.2  881.89  4785.5  882.34  4802.9  882.25  4823.8  881.32  4844.8  881.68
  4897.2  880.81  4907.6  881.30  4920.5  880.77  4980.2  880.21  4985.4  880.66
  5000.0  879.41  5000.2  878.91  5003.7  878.91  5004.0  879.41  5033.4  884.08
  5064.8  885.77  5082.8  887.24  5088.0  887.08  5105.8  888.47  5110.1  888.47
#Mann=3,-1,0
  4655.1    0.05       0  5000.0   0.033       0  5004.0    0.05       0
Bank Sta=5000,5004
Exp/Cntr=0.3,0.1

Type RM Length L Ch R = 1,17344,393,393,393
BEGIN DESCRIPTION:
Mapping XS 96df2b6b
END DESCRIPTION:
XS GIS Cut Line= 2
      2275935.23      7118353.06      2275772.81      7117903.18
#Sta/Elev= 30
  4638.1  891.19  4644.2  890.39  4669.6  884.76  4683.9  882.87  4700.2  881.29
  4756.3  879.74  4800.8  879.30  4854.0  879.28  4864.6  879.02  4873.6  878.23
  4878.9  878.72  4904.3  878.76  4909.6  879.24  4928.4  879.15  4935.0  878.40
  4940.3  878.66  4949.7  878.26  4965.6  878.72  4971.0  878.16  4981.6  878.11
  4989.0  876.00  4989.2  875.50  4992.7  875.50  4993.0  876.00  5002.8  876.24
  5013.5  879.72  5021.7  881.35  5027.0  882.02  5034.7  884.23  5116.4  888.28
#Mann=3,-1,0
  4638.1    0.05       0  4989.0   0.033       0  4993.0    0.05       0
Bank Sta=4989,4993
Exp/Cntr=0.3,0.1

Type RM Length L Ch R = 1,16951,286,286,286
BEGIN DESCRIPTION:
Long Branch 35.0
END DESCRIPTION:
XS GIS Cut Line= 3
      2276143.23      7118308.55      2276149.30      7118060.32
      2275966.37      7117708.54
#Sta/Elev= 30
  4770.9  890.68  4798.5  890.21  4803.5  887.89  4809.5  886.68  4869.5  881.27
  4959.5  878.23  4989.5  875.05  5007.5  871.78  5007.8  871.28  5011.3  871.28
  5011.5  871.78  5016.9  873.00  5022.2  873.00  5027.9  875.39  5050.1  876.51
  5077.8  877.37  5122.0  877.60  5166.2  877.65  5199.2  876.51  5221.3  876.83
  5249.0  878.23  5265.5  879.99  5271.1  879.78  5301.3  882.42  5323.9  883.32
  5353.9  886.25  5381.7  885.73  5391.5  884.59  5398.2  885.87  5415.7  887.41
#Mann=3,-1,0
  4770.9    0.05       0  5007.5   0.033       0  5011.5    0.05       0
Bank Sta=5007.5,5011.5
Exp/Cntr=0.3,0.1

Type RM Length L Ch R = 1,16665,351,351,351
BEGIN DESCRIPTION:
Mapping XS 20ac620c
END DESCRIPTION:
XS GIS Cut Line= 4
      2276201.56      7118284.80      2276333.24      7118008.77
      2276323.80      7117877.52      2276093.64      7117809.23
#Sta/Elev= 30
  4521.7  883.71  4538.1  883.06  4552.7  883.17  4560.3  882.39  4604.6  880.65
  4770.8  875.79  4827.5  875.51  4866.4  876.42  4886.5  875.66  4946.6  875.94
  4953.9  875.03  4963.6  875.47  4968.7  873.82  4974.6  874.24  4985.0  873.24
  4993.4  870.83  4993.7  870.33  4997.2  870.33  4997.4  870.83  5016.3  871.27
  5035.1  873.53  5058.0  873.22  5099.7  874.37  5106.8  875.01  5112.0  876.87
  5140.0  877.42  5145.2  878.51  5178.4  878.86  5183.7  879.76  5199.2  880.76
#Mann=3,-1,0
  4521.7    0.05       0  4993.4   0.033       0  4997.4    0.05       0
Bank Sta=4993.4,4997.4
Exp/Cntr=0.3,0.1

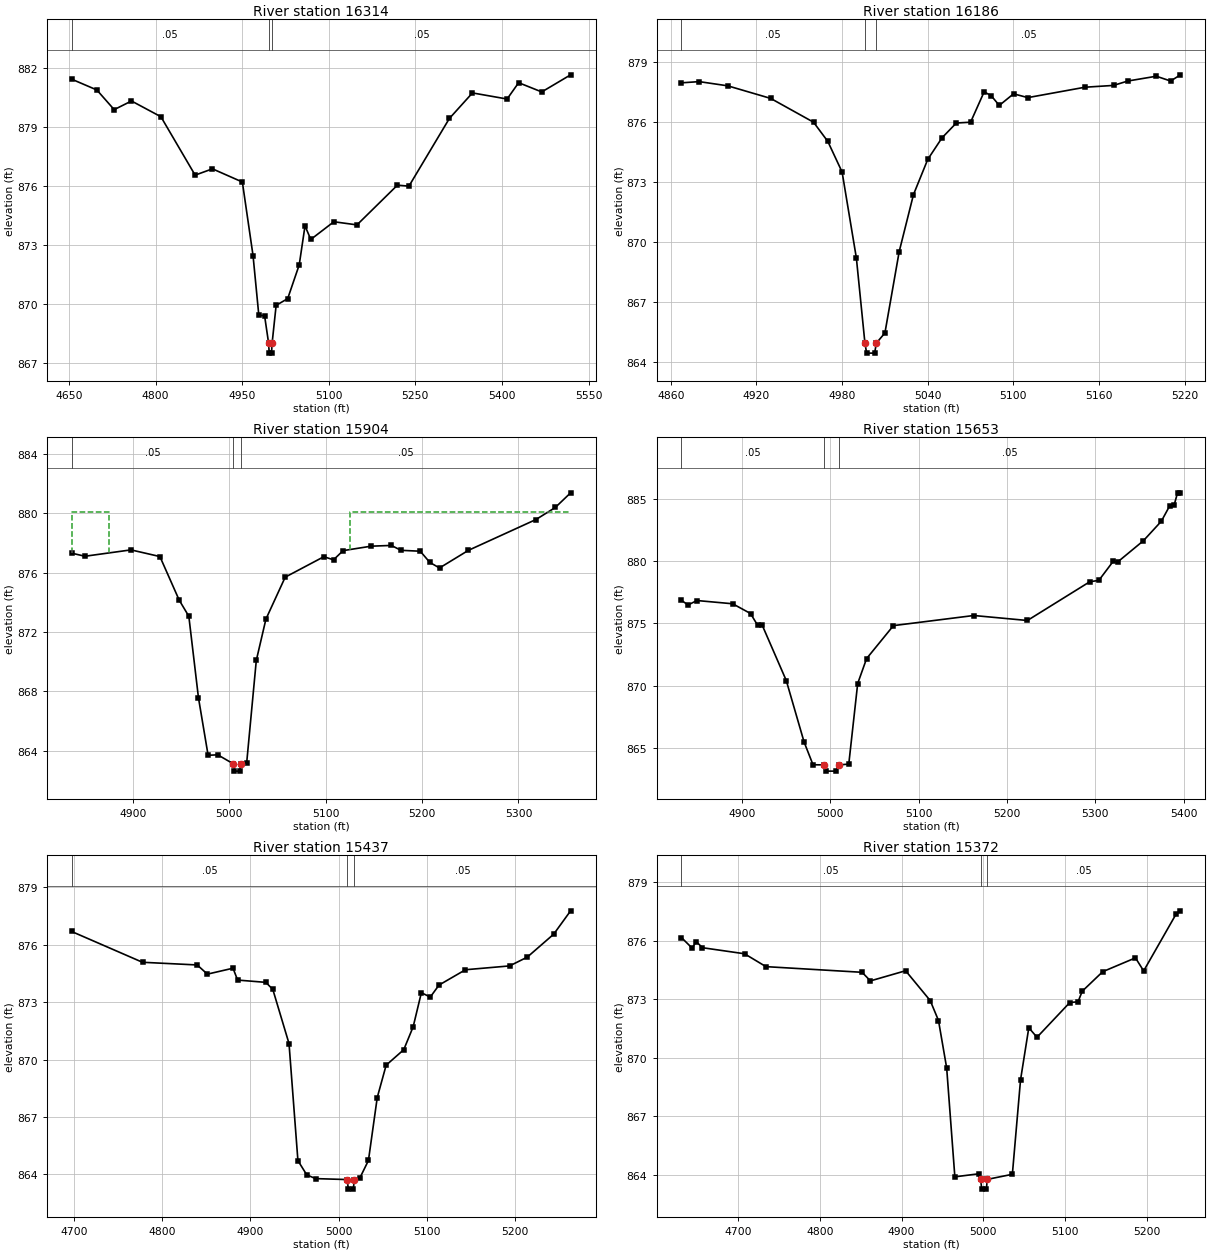
Type RM Length L Ch R = 1,16314,128,128,128
BEGIN DESCRIPTION:
Mapping XS d62d6f0d
END DESCRIPTION:
XS GIS Cut Line= 3
      2276670.70      7118093.65      2276657.53      7117798.27
      2276089.01      7117795.05
#Sta/Elev= 30
  4654.7  881.44  4698.4  880.89  4728.4  879.89  4758.4  880.33  4809.3  879.53
  4868.6  876.56  4898.6  876.88  4950.4  876.21  4968.9  872.47  4978.9  869.44
  4988.9  869.41  4995.9  868.01  4996.9  867.51  5000.9  867.51  5001.9  868.01
  5008.9  869.94  5028.9  870.28  5048.9  872.00  5058.9  873.98  5068.9  873.29
  5108.9  874.19  5148.9  874.03  5218.9  876.05  5238.9  876.00  5308.9  879.44
  5348.9  880.74  5408.9  880.43  5428.9  881.26  5468.9  880.79  5518.9  881.66
#Mann=3,-1,0
  4654.7    0.05       0  4995.9   0.033       0  5001.9    0.05       0
Bank Sta=4995.9,5001.9
Exp/Cntr=0.3,0.1

Type RM Length L Ch R = 1,16186,282,282,282
BEGIN DESCRIPTION:
Mapping XS 141480c8
END DESCRIPTION:
XS GIS Cut Line= 2
      2276761.42      7117682.41      2276412.13      7117670.45
#Sta/Elev= 30
  4867.5  877.94  4879.9  878.00  4899.9  877.79  4930.0  877.16  4960.0  875.97
  4970.0  875.01  4980.0  873.48  4990.0  869.18  4996.0  864.92  4997.2  864.42
  5002.8  864.42  5004.0  864.92  5010.0  865.43  5020.0  869.50  5030.0  872.35
  5040.0  874.11  5050.0  875.19  5060.0  875.93  5070.0  875.97  5079.5  877.49
  5084.5  877.29  5090.1  876.81  5100.1  877.39  5110.1  877.20  5150.1  877.72
  5170.1  877.81  5180.1  878.03  5200.1  878.27  5210.1  878.03  5217.0  878.34
#Mann=3,-1,0
  4867.5    0.05       0  4996.0    0.04       0  5004.0    0.05       0
Bank Sta=4996,5004
Exp/Cntr=0.3,0.1

Type RM Length L Ch R = 1,15904,251,251,251
BEGIN DESCRIPTION:
Mapping XS 526b3712
END DESCRIPTION:
XS GIS Cut Line= 2
      2276760.52      7117405.36      2276243.10      7117388.32
#Sta/Elev= 30
  4836.4  877.32  4850.2  877.11  4898.0  877.54  4928.0  877.09  4948.0  874.15
  4958.0  873.06  4968.0  867.56  4978.0  863.68  4988.0  863.71  5004.0  863.11
  5005.2  862.61  5010.8  862.61  5012.0  863.11  5018.0  863.15  5028.0  870.08
  5038.0  872.87  5058.0  875.70  5098.1  877.08  5108.1  876.87  5118.1  877.49
  5147.2  877.79  5168.1  877.84  5178.1  877.51  5198.1  877.45  5208.1  876.69
  5218.1  876.32  5248.1  877.51  5318.2  879.59  5338.2  880.40  5354.1  881.39
#Mann=3,-1,0
  4836.4    0.05       0  5004.0   0.033       0  5012.0    0.05       0
#XS Ineff=2,0
    0.00 4874.70  880.08 5125.30    0.00  880.08
Permanent Ineff=
       F       F
Bank Sta=5004,5012
Exp/Cntr=0.3,0.1

Type RM Length L Ch R = 1,15653,216,216,216
BEGIN DESCRIPTION:
Mapping XS 507af97f
END DESCRIPTION:
XS GIS Cut Line= 2
      2276786.36      7117178.36      2276227.52      7117093.80
#Sta/Elev= 30
  4831.3  876.86  4838.7  876.48  4848.8  876.84  4889.3  876.58  4909.5  875.80
  4917.6  874.85  4922.6  874.89  4950.0  870.43  4970.2  865.50  4980.3  863.68
  4993.0  863.67  4995.4  863.17  5006.8  863.17  5009.2  863.67  5020.8  863.73
  5030.9  870.19  5041.0  872.19  5071.4  874.83  5162.4  875.64  5223.1  875.24
  5293.9  878.35  5304.0  878.45  5320.4  879.99  5325.4  879.93  5354.5  881.63
  5374.8  883.19  5384.1  884.40  5389.2  884.46  5393.2  885.47  5396.5  885.47
#Mann=3,-1,0
  4831.3    0.05       0  4993.0   0.033       0  5009.2    0.05       0
Bank Sta=4993,5009.2
Exp/Cntr=0.3,0.1

Type RM Length L Ch R = 1,15437,65,65,65
BEGIN DESCRIPTION:
Mapping XS 00ef74c3
END DESCRIPTION:
XS GIS Cut Line= 3
      2276764.22      7117147.41      2276705.16      7116934.73
      2276359.88      7116956.54
#Sta/Elev= 30
  4696.9  876.70  4777.4  875.09  4839.5  874.95  4851.1  874.47  4880.2  874.78
  4885.4  874.16  4917.5  874.04  4925.4  873.67  4943.8  870.84  4953.9  864.72
  4963.9  863.98  4973.9  863.78  5009.9  863.73  5011.1  863.23  5016.8  863.23
  5018.0  863.73  5024.0  863.79  5034.0  864.73  5044.0  868.02  5054.1  869.71
  5074.1  870.52  5084.8  871.72  5094.1  873.50  5104.2  873.27  5114.2  873.90
  5144.2  874.70  5194.3  874.90  5214.4  875.36  5244.4  876.56  5263.6  877.78
#Mann=3,-1,0
  4696.9    0.05       0  5009.9   0.033       0  5018.0    0.05       0
Bank Sta=5009.9,5018
Exp/Cntr=0.3,0.1

Type RM Length L Ch R = 1,15372,221,221,221
BEGIN DESCRIPTION:
Mapping XS 9806e19b
END DESCRIPTION:
XS GIS Cut Line= 3
      2276777.54      7117125.05      2276717.29      7116866.26
      2276374.20      7116895.02
#Sta/Elev= 30
  4630.9  876.16  4643.9  875.62  4649.0  875.95  4656.6  875.64  4708.0  875.33
  4734.2  874.67  4851.7  874.38  4861.9  873.94  4904.9  874.46  4935.0  872.93
  4945.1  871.91  4955.1  869.48  4965.1  863.90  4995.2  864.06  4996.7  863.77
  4997.9  863.27  5003.6  863.27  5004.8  863.77  5035.4  864.03  5045.4  868.87
  5055.5  871.54  5065.5  871.05  5105.6  872.83  5115.7  872.87  5120.8  873.41
  5145.8  874.41  5185.9  875.12  5195.9  874.45  5235.9  877.39  5240.9  877.53
#Mann=3,-1,0
  4630.9    0.05       0  4996.7   0.033       0  5004.8    0.05       0
Bank Sta=4996.7,5004.8
Exp/Cntr=0.3,0.1

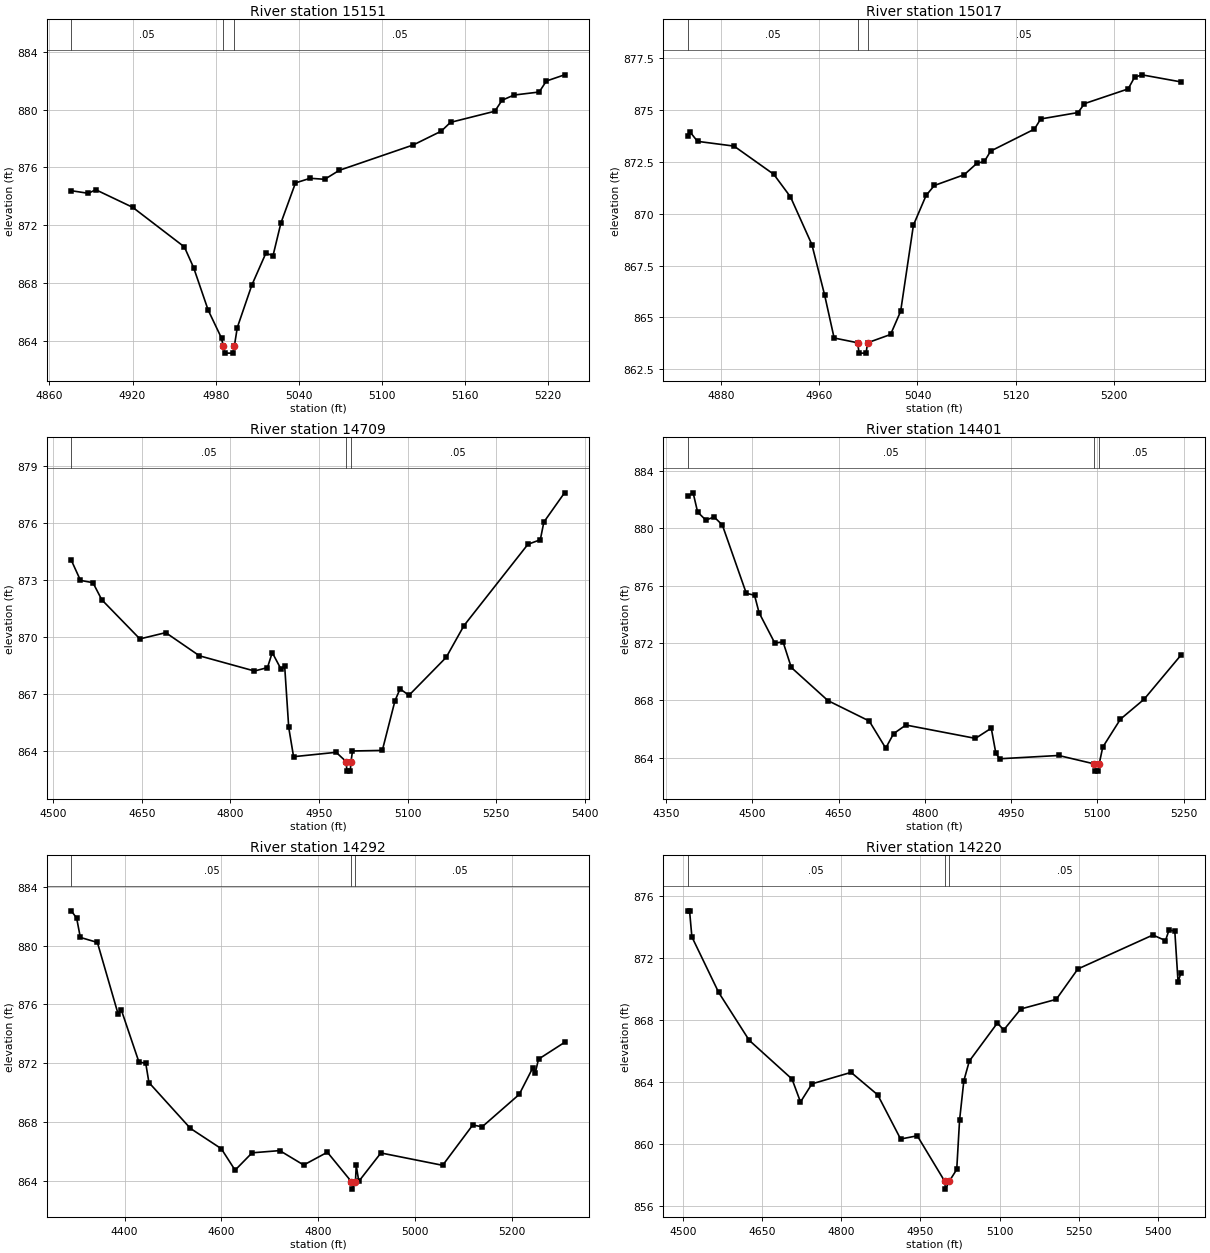
Type RM Length L Ch R = 1,15151,134,134,134
BEGIN DESCRIPTION:
Mapping XS bc016f41
END DESCRIPTION:
XS GIS Cut Line= 2
      2276758.69      7116833.99      2276649.10      7116495.28
#Sta/Elev= 30
  4875.8  874.39  4888.1  874.21  4893.4  874.46  4920.1  873.24  4957.4  870.50
  4964.1  869.06  4974.6  866.12  4984.2  864.19  4985.4  863.65  4986.6  863.15
  4992.3  863.15  4993.5  863.65  4995.6  864.92  5006.1  867.86  5016.2  870.06
  5021.4  869.90  5027.1  872.16  5037.6  874.93  5048.2  875.25  5058.7  875.18
  5069.2  875.80  5122.7  877.56  5142.8  878.51  5149.5  879.12  5181.5  879.89
  5186.7  880.65  5195.3  881.01  5213.5  881.22  5218.7  881.98  5231.8  882.41
#Mann=3,-1,0
  4875.8    0.05       0  4985.4   0.033       0  4993.5    0.05       0
Bank Sta=4985.4,4993.5
Exp/Cntr=0.3,0.1

Type RM Length L Ch R = 1,15017,308,308,308
BEGIN DESCRIPTION:
Mapping XS e7c4c7d2
END DESCRIPTION:
XS GIS Cut Line= 2
      2276884.41      7116817.87      2276784.39      7116429.44
#Sta/Elev= 30
  4853.0  873.75  4855.3  873.93  4861.1  873.50  4890.8  873.27  4923.1  871.91
  4936.7  870.82  4954.1  868.52  4964.4  866.10  4972.2  864.01  4991.3  863.78
  4992.5  863.28  4998.2  863.28  4999.4  863.78  5018.1  864.18  5026.3  865.30
  5036.7  869.46  5047.0  870.89  5053.7  871.37  5078.0  871.89  5088.3  872.44
  5094.4  872.53  5099.5  873.03  5135.1  874.09  5140.2  874.58  5170.6  874.89
  5175.8  875.32  5211.3  876.03  5216.5  876.59  5222.5  876.71  5254.1  876.37
#Mann=3,-1,0
  4853.0    0.05       0  4991.3    0.04       0  4999.4    0.05       0
Bank Sta=4991.3,4999.4
Exp/Cntr=0.3,0.1

Type RM Length L Ch R = 1,14709,308,308,308
BEGIN DESCRIPTION:
Mapping XS e6a069e6
END DESCRIPTION:
XS GIS Cut Line= 2
      2277505.73      7116794.39      2276809.87      7116332.31
#Sta/Elev= 30
  4530.5  874.05  4546.0  872.99  4567.1  872.87  4582.1  871.97  4646.6  869.91
  4690.4  870.24  4747.5  869.02  4840.7  868.22  4862.7  868.40  4870.8  869.19
  4885.8  868.31  4891.8  868.49  4898.7  865.25  4906.9  863.71  4979.0  863.94
  4996.0  863.45  4997.2  862.95  5002.9  862.95  5004.2  863.45  5006.7  864.01
  5057.2  864.04  5078.7  866.66  5087.3  867.28  5102.3  866.94  5165.4  868.94
  5195.5  870.61  5303.8  874.89  5324.8  875.13  5330.8  876.06  5365.8  877.60
#Mann=3,-1,0
  4530.5    0.05       0  4996.0   0.033       0  5004.2    0.05       0
Bank Sta=4996,5004.2
Exp/Cntr=0.3,0.1

Type RM Length L Ch R = 1,14401,109,109,109
BEGIN DESCRIPTION:
Long Branch 30.0
END DESCRIPTION:
XS GIS Cut Line= 3
      2277755.71      7116647.64      2277309.00      7116280.00
      2277036.70      7116217.60
#Sta/Elev= 30
  4387.3  882.23  4397.0  882.46  4404.8  881.12  4419.2  880.56  4433.5  880.78
  4447.8  880.22  4489.5  875.46  4503.8  875.33  4511.7  874.11  4539.0  872.00
  4553.4  872.08  4567.7  870.30  4631.5  867.99  4703.3  866.57  4732.0  864.68
  4745.7  865.69  4767.1  866.29  4888.1  865.36  4915.6  866.07  4923.5  864.34
  4930.0  863.94  5032.8  864.17  5095.1  863.58  5096.4  863.08  5102.1  863.08
  5103.3  863.58  5109.5  864.75  5140.3  866.70  5181.3  868.08  5245.2  871.14
#Mann=3,-1,0
  4387.3    0.05       0  5095.1   0.033       0  5103.3    0.05       0
Bank Sta=5095.1,5103.3
Exp/Cntr=0.3,0.1

Type RM Length L Ch R = 1,14292,72,72,72
BEGIN DESCRIPTION:
Long Branch 29.5
END DESCRIPTION:
XS GIS Cut Line= 6
      2277757.34      7116627.80      2277366.75      7116293.97
      2277403.28      7116200.84      2277372.42      7116177.44
      2277247.12      7116176.23      2277017.59      7116107.03
#Sta/Elev= 30
  4290.0  882.36  4301.0  881.86  4308.6  880.55  4343.8  880.21  4386.6  875.34
  4393.2  875.62  4429.4  872.09  4443.7  871.98  4450.2  870.68  4535.9  867.56
  4599.6  866.18  4628.1  864.72  4663.2  865.90  4720.3  866.05  4769.7  865.07
  4818.6  865.94  4868.4  863.93  4869.7  863.43  4876.6  863.93  4878.2  865.04
  4883.5  863.96  4929.1  865.89  5056.6  865.05  5118.7  867.79  5138.2  867.67
  5214.6  869.87  5242.4  871.66  5247.6  871.31  5254.5  872.27  5308.2  873.41
#Mann=3,-1,0
  4290.0    0.05       0  4868.4   0.033       0  4876.6    0.05       0
Bank Sta=4868.4,4876.6
Exp/Cntr=0.3,0.1

Type RM Length L Ch R = 1,14220,493,493,493
BEGIN DESCRIPTION:
Mapping XS 3eab6e52
END DESCRIPTION:
XS GIS Cut Line= 3
      2277780.63      7116349.24      2277368.28      7116121.30
      2276938.53      7115943.34
#Sta/Elev= 30
  4507.8  875.05  4511.6  875.05  4516.0  873.37  4566.8  869.79  4624.8  866.70
  4706.1  864.20  4722.2  862.72  4743.9  863.89  4818.2  864.63  4868.8  863.18
  4912.3  860.33  4943.9  860.54  4996.1  857.60  4997.4  857.10  5004.5  857.60
  5018.8  858.37  5024.2  861.55  5032.3  864.09  5042.7  865.36  5095.9  867.81
  5108.1  867.37  5140.5  868.72  5207.7  869.34  5248.8  871.30  5391.2  873.49
  5415.1  873.13  5421.9  873.82  5432.8  873.74  5439.0  870.46  5444.1  871.01
#Mann=3,-1,0
  4507.8    0.05       0  4996.1   0.033       0  5004.5    0.05       0
Bank Sta=4996.1,5004.5
Exp/Cntr=0.3,0.1

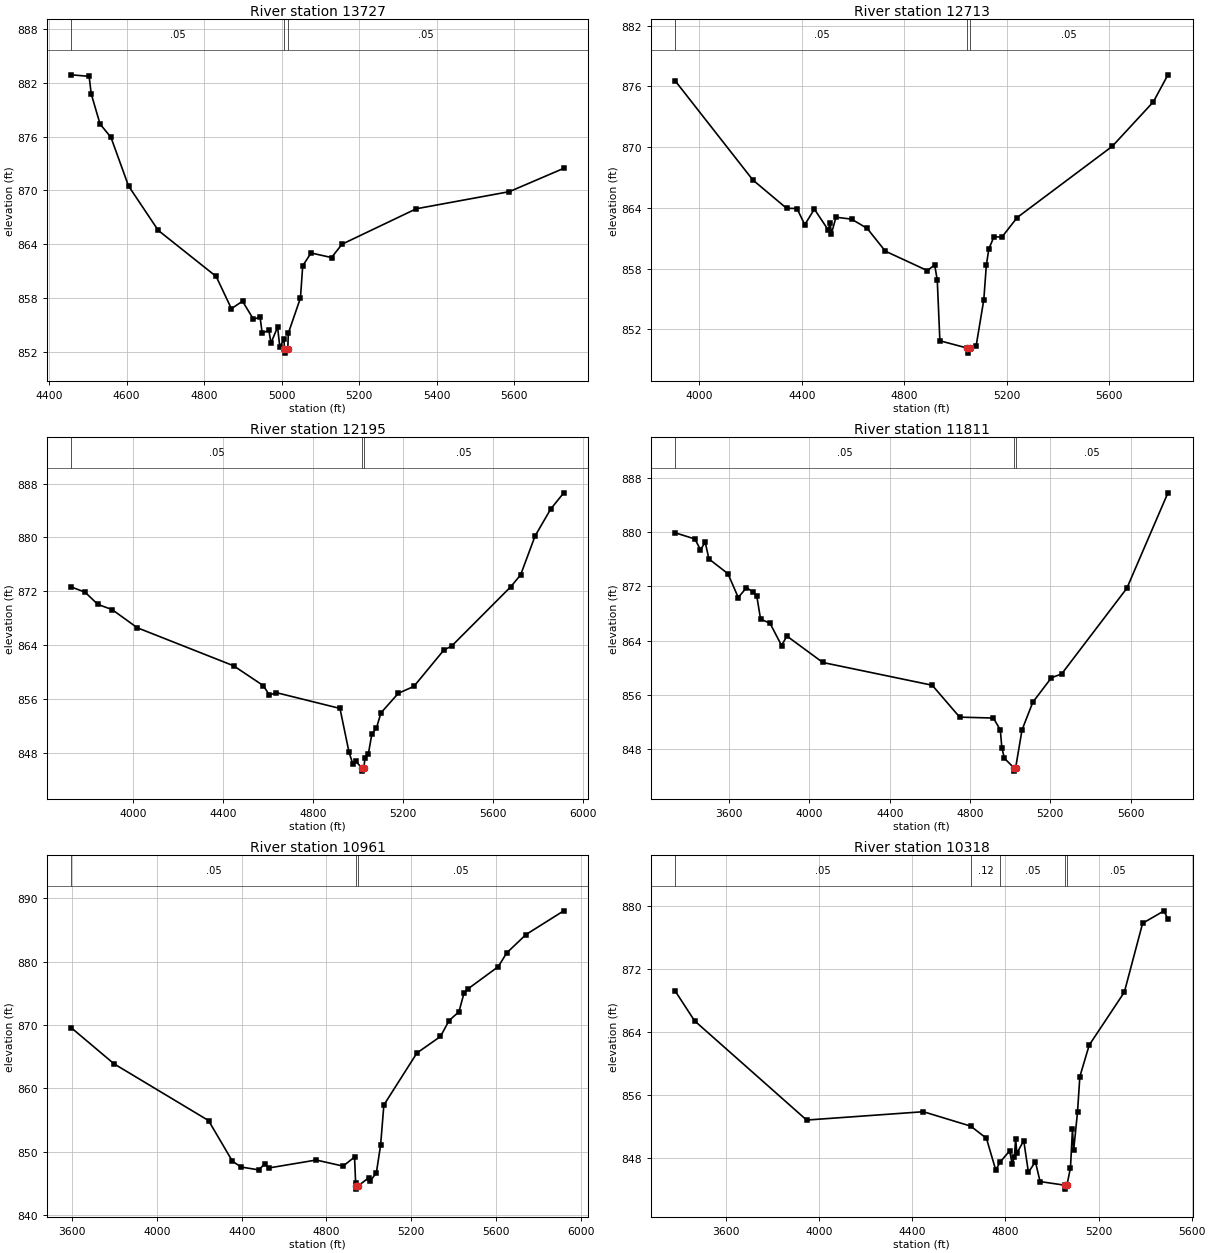
Type RM Length L Ch R = 1,13727,1014,1014,1014
BEGIN DESCRIPTION:
Long Branch 28.0
END DESCRIPTION:
XS GIS Cut Line= 3
      2278171.09      7116017.03      2277679.49      7115780.37
      2277054.77      7115412.86
#Sta/Elev= 30
  4457.3  882.88  4503.3  882.71  4508.8  880.74  4531.5  877.39  4559.6  875.91
  4604.9  870.49  4681.6  865.53  4831.1  860.39  4870.3  856.80  4899.0  857.63
  4927.2  855.62  4944.3  855.86  4949.8  854.04  4966.9  854.41  4972.4  852.96
  4989.5  854.75  4995.1  852.56  5006.1  853.37  5007.0  852.34  5008.2  851.84
  5015.8  852.34  5017.2  854.06  5048.5  858.00  5054.3  861.58  5075.8  863.01
  5128.6  862.50  5155.8  863.99  5347.2  867.94  5587.4  869.85  5727.7  872.45
#Mann=3,-1,0
  4457.3    0.05       0  5007.0   0.033       0  5015.8    0.05       0
Bank Sta=5007,5015.8
Exp/Cntr=0.3,0.1

Type RM Length L Ch R = 1,12713,518,518,518
BEGIN DESCRIPTION:
Long Branch 27.0
END DESCRIPTION:
XS GIS Cut Line= 3
      2278936.74      7115152.47      2277829.00      7114971.91
      2277032.23      7114923.41
#Sta/Elev= 30
  3907.7  876.51  4209.4  866.76  4341.1  863.96  4381.6  863.94  4412.0  862.34
  4449.4  863.88  4503.2  861.83  4510.9  862.51  4516.0  861.45  4533.6  863.08
  4594.4  862.89  4655.2  861.98  4726.1  859.73  4889.9  857.81  4918.6  858.37
  4928.7  856.86  4938.9  850.88  5045.6  850.16  5046.9  849.66  5054.6  850.16
  5080.1  850.34  5110.2  854.93  5120.2  858.39  5130.2  859.98  5150.3  861.17
  5180.3  861.10  5240.4  863.05  5611.1  870.08  5771.4  874.47  5828.3  877.14
#Mann=3,-1,0
  3907.7    0.05       0  5045.6   0.033       0  5054.6    0.05       0
Bank Sta=5045.6,5054.6
Exp/Cntr=0.3,0.1

Type RM Length L Ch R = 1,12195,384,384,384
BEGIN DESCRIPTION:
Long Branch 26.0
END DESCRIPTION:
XS GIS Cut Line= 3
      2279119.05      7114662.89      2277853.82      7114470.83
      2276955.84      7114336.49
#Sta/Elev= 30
  3727.2  872.62  3787.9  871.86  3845.0  870.04  3908.6  869.26  4020.6  866.56
  4448.3  860.91  4580.6  857.95  4607.2  856.55  4637.6  856.92  4920.8  854.57
  4961.2  848.03  4977.8  846.35  4991.6  846.70  5017.4  845.75  5018.7  845.25
  5026.5  845.75  5032.0  847.14  5046.8  847.79  5062.4  850.76  5082.6  851.63
  5102.8  853.91  5180.1  856.82  5249.3  857.85  5382.6  863.26  5416.3  863.82
  5679.1  872.64  5723.4  874.43  5787.6  880.21  5856.8  884.20  5914.9  886.62
#Mann=3,-1,0
  3727.2    0.05       0  5017.4   0.033       0  5026.5    0.05       0
Bank Sta=5017.4,5026.5
Exp/Cntr=0.3,0.1

Type RM Length L Ch R = 1,11811,850,850,850
BEGIN DESCRIPTION:
Long Branch 25.0
END DESCRIPTION:
XS GIS Cut Line= 3
      2279563.17      7114494.56      2277936.69      7114104.77
      2277167.62      7113966.70
#Sta/Elev= 30
  3332.5  879.87  3429.3  878.97  3457.2  877.39  3480.8  878.49  3499.2  876.03
  3593.9  873.86  3645.3  870.35  3686.4  871.80  3719.6  871.16  3737.8  870.56
  3756.5  867.17  3803.6  866.56  3861.2  863.28  3887.7  864.67  4066.9  860.78
  4611.9  857.43  4748.7  852.73  4916.7  852.60  4951.2  850.85  4958.8  848.22
  4971.8  846.66  5018.5  845.28  5019.8  844.78  5027.6  845.28  5059.4  850.85
  5113.1  854.93  5205.9  858.54  5256.7  859.09  5581.8  871.72  5786.4  885.77
#Mann=3,-1,0
  3332.5    0.05       0  5018.5   0.033       0  5027.6    0.05       0
Bank Sta=5018.5,5027.6
Exp/Cntr=0.3,0.1

Type RM Length L Ch R = 1,10961,643,643,643
BEGIN DESCRIPTION:
Long Branch 23.0
END DESCRIPTION:
XS GIS Cut Line= 3
      2279678.02      7113598.64      2278329.00      7113360.00
      2277382.56      7113225.58
#Sta/Elev= 30
  3594.9  869.57  3797.0  863.88  4243.0  854.94  4355.6  848.54  4396.2  847.61
  4479.7  847.16  4507.9  848.05  4528.2  847.46  4751.6  848.71  4878.7  847.75
  4932.7  849.18  4937.8  845.16  4939.8  844.62  4941.1  844.12  4949.4  844.62
  5000.3  845.93  5005.4  845.35  5035.6  846.67  5055.8  851.05  5071.2  857.39
  5227.5  865.60  5338.6  868.20  5379.0  870.70  5425.8  872.10  5449.7  875.03
  5469.9  875.74  5611.3  879.21  5651.7  881.39  5742.6  884.28  5920.8  888.02
#Mann=3,-1,0
  3594.9    0.05       0  4939.8   0.033       0  4949.4    0.05       0
Bank Sta=4939.8,4949.4
Exp/Cntr=0.3,0.1

Type RM Length L Ch R = 1,10318,1052,1052,1052
BEGIN DESCRIPTION:
Long Branch 22.0
END DESCRIPTION:
XS GIS Cut Line= 3
      2279830.88      7112984.07      2278228.21      7112875.14
      2277722.71      7112824.47
#Sta/Elev= 30
  3383.7  869.10  3465.8  865.37  3946.9  852.77  4448.0  853.83  4651.3  852.00
  4718.7  850.46  4758.7  846.44  4777.6  847.43  4818.9  848.88  4828.9  847.17
  4838.9  848.09  4844.3  850.42  4849.3  848.55  4879.0  850.16  4899.1  846.14
  4929.1  847.47  4949.2  844.96  5054.7  844.50  5056.1  844.00  5064.5  844.50
  5079.7  846.72  5088.2  851.60  5093.3  848.92  5109.9  853.80  5119.9  858.29
  5160.1  862.29  5310.9  869.01  5389.4  877.76  5481.7  879.34  5498.1  878.25
#Mann=5,-1,0
  3383.7    0.05       0  4651.3    0.12       0  4777.6    0.05       0
  5054.7   0.033       0  5064.5    0.05       0
Bank Sta=5054.7,5064.5
Exp/Cntr=0.3,0.1

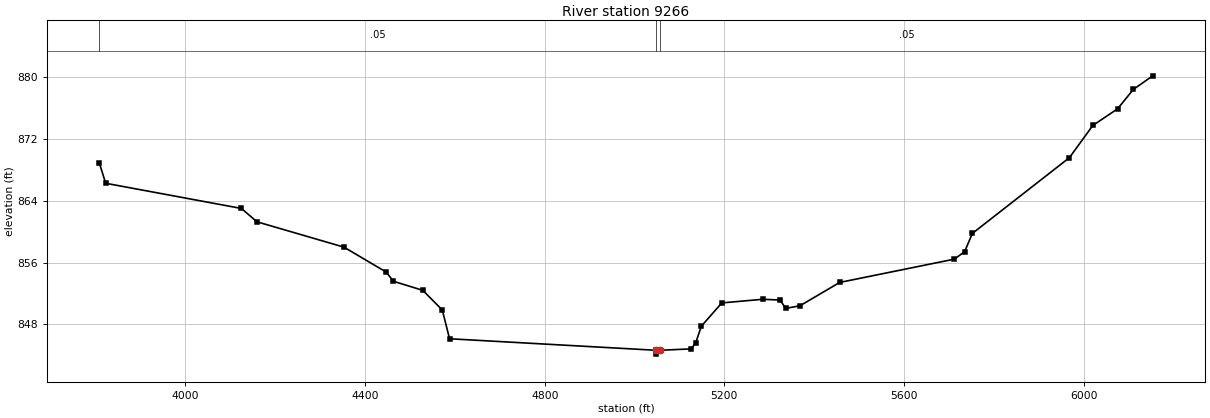
Type RM Length L Ch R = 1,9266,653,653,653
BEGIN DESCRIPTION:
Long Branch 20.0
END DESCRIPTION:
XS GIS Cut Line= 4
      2279876.12      7112631.94      2278832.35      7112056.67
      2278051.33      7111688.93      2277788.20      7111565.04
#Sta/Elev= 30
  3808.2  868.91  3822.3  866.28  4124.6  863.02  4159.3  861.29  4353.0  858.01
  4447.1  854.78  4463.1  853.59  4528.5  852.42  4572.0  849.87  4588.1  846.15
  5047.2  844.66  5048.6  844.16  5057.2  844.66  5126.1  844.84  5136.3  845.62
  5148.8  847.77  5194.4  850.79  5285.6  851.26  5324.2  851.16  5336.7  850.08
  5368.5  850.42  5456.9  853.44  5712.4  856.46  5735.2  857.43  5752.4  859.79
  5968.6  869.60  6020.6  873.76  6075.8  875.92  6110.9  878.43  6154.1  880.19
#Mann=3,-1,0
  3808.2    0.05       0  5047.2   0.033       0  5057.2    0.05       0
Bank Sta=5047.2,5057.2
Exp/Cntr=0.3,0.1