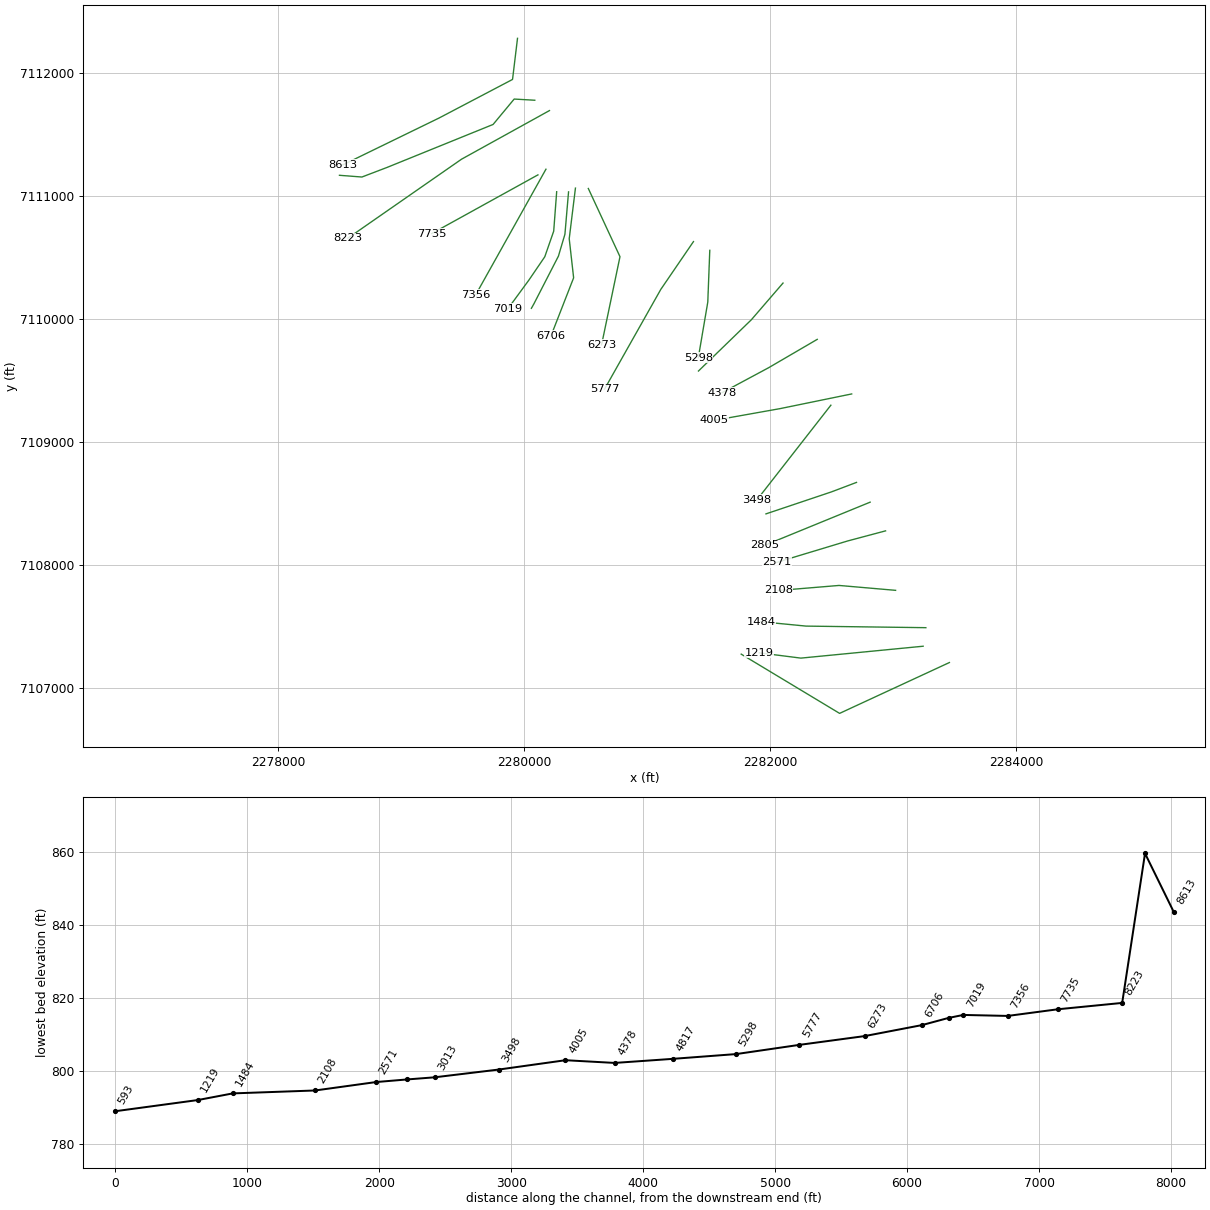
HEC-RAS study Long Branch.prj: Long Branch Base Level Engineering

--- Long Branch.g01 (geometry) --- (continued)

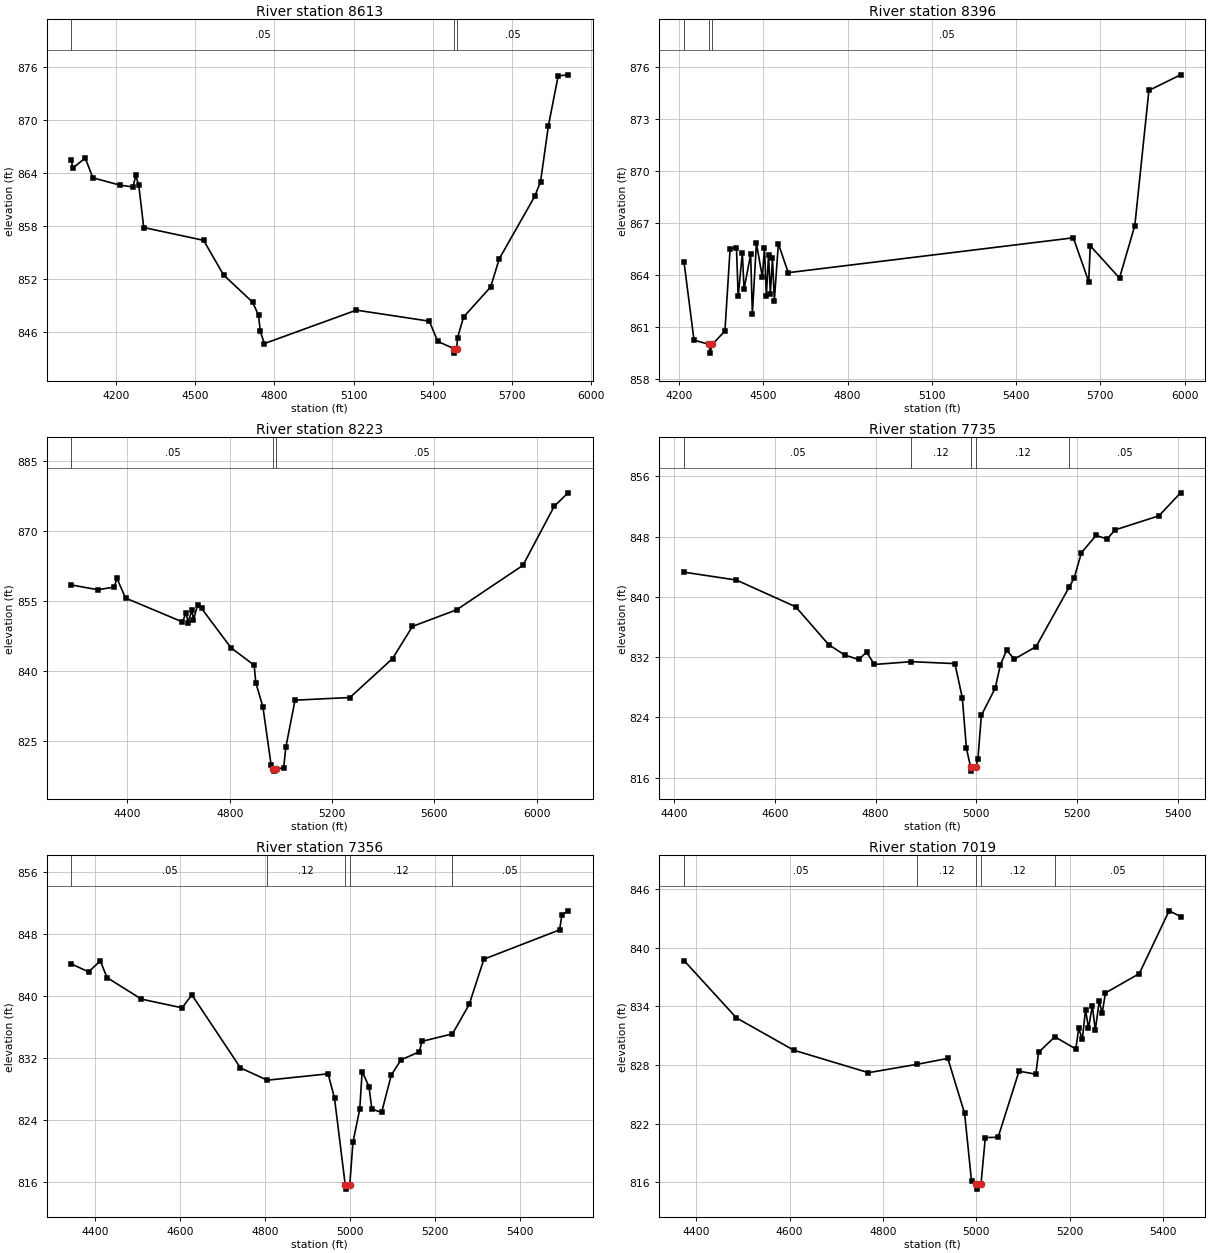
Type RM Length L Ch R = 1,8613,217,217,217
BEGIN DESCRIPTION:
Long Branch 18.0
END DESCRIPTION:
XS GIS Cut Line= 4
      2279944.18      7112281.48      2279903.75      7111947.23
      2279306.31      7111633.52      2278525.29      7111253.16
#Sta/Elev= 30
  4032.1  865.48  4036.1  864.48  4084.0  865.66  4113.0  863.41  4214.9  862.59
  4265.3  862.37  4275.3  863.68  4286.9  862.56  4305.6  857.78  4532.3  856.33
  4607.9  852.41  4718.2  849.31  4740.2  847.84  4746.9  846.03  4762.3  844.63
  5110.8  848.42  5386.9  847.17  5418.8  844.88  5480.5  844.05  5481.9  843.55
  5490.6  844.05  5494.0  845.32  5516.6  847.64  5619.0  851.04  5651.8  854.24
  5785.8  861.30  5808.1  862.98  5837.7  869.29  5874.8  874.96  5912.3  875.08
#Mann=3,-1,0
  4032.1    0.05       0  5480.5   0.033       0  5490.6    0.05       0
Bank Sta=5480.5,5490.6
Exp/Cntr=0.3,0.1

Type RM Length L Ch R = 1,8396,173,173,173
BEGIN DESCRIPTION:
Long Branch 17.5
END DESCRIPTION:
XS GIS Cut Line= 6
      2280084.56      7111778.19      2279917.20      7111787.80
      2279745.65      7111581.31      2278885.31      7111232.57
      2278679.06      7111153.82      2278496.40      7111167.94
#Sta/Elev= 30
  4217.0  864.78  4252.6  860.27  4307.6  860.02  4309.0  859.52  4317.9  860.02
  4362.8  860.80  4381.2  865.54  4403.9  865.61  4410.0  862.79  4424.8  865.31
  4430.9  863.21  4454.4  865.22  4460.5  861.79  4474.9  865.86  4496.0  863.91
  4503.7  865.59  4510.3  862.80  4518.0  865.17  4524.6  862.95  4532.2  864.98
  4538.8  862.55  4553.1  865.83  4588.3  864.16  5603.9  866.17  5658.7  863.64
  5664.1  865.71  5768.3  863.85  5822.9  866.88  5873.0  874.67  5985.9  875.57
#Mann=3,-1,0
  4217.0    0.05       0  4307.6   0.033       0  4317.9    0.05       0
Bank Sta=4307.6,4317.9
Exp/Cntr=0.3,0.1

Type RM Length L Ch R = 1,8223,488,488,488
BEGIN DESCRIPTION:
Long Branch 17.0
END DESCRIPTION:
XS GIS Cut Line= 3
      2280204.13      7111694.15      2279489.00      7111298.76
      2278565.47      7110656.78
#Sta/Elev= 30
  4181.3  858.41  4283.6  857.40  4348.9  857.95  4358.6  859.86  4392.8  855.61
  4614.6  850.52  4630.7  852.51  4636.4  850.31  4652.4  853.03  4658.1  850.96
  4674.2  854.05  4689.9  853.40  4804.7  845.00  4895.6  841.26  4902.1  837.51
  4929.9  832.31  4961.7  819.99  4970.5  819.11  4971.9  818.61  4980.8  819.11
  5010.9  819.30  5019.6  823.74  5055.4  833.78  5270.2  834.35  5436.9  842.68
  5514.6  849.55  5687.4  853.10  5946.7  862.61  6068.9  875.22  6123.2  878.11
#Mann=3,-1,0
  4181.3    0.05       0  4970.5   0.033       0  4980.8    0.05       0
Bank Sta=4970.5,4980.8
Exp/Cntr=0.3,0.1

Type RM Length L Ch R = 1,7735,379,379,379
BEGIN DESCRIPTION:
Mapping XS ce20d748
END DESCRIPTION:
XS GIS Cut Line= 2
      2280110.25      7111171.27      2279246.47      7110694.13
#Sta/Elev= 30
  4419.3  843.28  4523.5  842.23  4641.3  838.68  4706.6  833.67  4738.7  832.28
  4766.2  831.69  4782.2  832.65  4797.7  831.03  4871.3  831.40  4957.7  831.14
  4972.4  826.57  4980.5  819.90  4989.0  817.37  4990.4  816.87  4999.4  817.37
  5003.4  818.52  5010.2  824.28  5037.7  827.88  5048.0  830.97  5060.5  832.93
  5075.5  831.73  5119.0  833.40  5184.7  841.29  5194.7  842.51  5209.0  845.86
  5238.2  848.16  5260.0  847.68  5276.0  848.89  5363.1  850.76  5406.1  853.81
#Mann=5,-1,0
  4419.3    0.05       0  4871.3    0.12       0  4989.0    0.07       0
  4999.4    0.12       0  5184.7    0.05       0
Bank Sta=4989,4999.4
Exp/Cntr=0.3,0.1

Type RM Length L Ch R = 1,7356,337,337,337
BEGIN DESCRIPTION:
Mapping XS aed8b290
END DESCRIPTION:
XS GIS Cut Line= 2
      2280175.31      7111217.31      2279604.58      7110196.76
#Sta/Elev= 30
  4344.0  844.11  4384.3  843.09  4411.8  844.51  4427.7  842.35  4508.8  839.57
  4604.4  838.45  4627.4  840.13  4741.9  830.70  4804.9  829.11  4948.2  829.93
  4963.3  826.79  4988.7  815.55  4990.2  815.05  4999.2  815.55  5006.7  821.10
  5022.7  825.34  5028.4  830.23  5044.4  828.29  5051.3  825.39  5074.2  824.95
  5097.1  829.78  5119.8  831.73  5163.2  832.78  5168.9  834.12  5241.1  835.09
  5280.4  838.88  5315.1  844.73  5493.2  848.51  5498.9  850.44  5513.3  850.97
#Mann=5,-1,0
  4344.0    0.05       0  4804.9    0.12       0  4988.7    0.07       0
  4999.2    0.12       0  5241.1    0.05       0
Bank Sta=4988.7,4999.2
Exp/Cntr=0.3,0.1

Type RM Length L Ch R = 1,7019,112,112,112
BEGIN DESCRIPTION:
Mapping XS 4c6d2dde
END DESCRIPTION:
XS GIS Cut Line= 5
      2280262.65      7111034.23      2280238.46      7110713.67
      2280165.85      7110505.18      2280036.63      7110315.63
      2279864.16      7110080.19
#Sta/Elev= 30
  4373.8  838.68  4486.1  832.82  4608.7  829.52  4768.8  827.22  4873.6  828.08
  4938.8  828.68  4974.7  823.07  4989.6  816.13  4999.3  815.82  5000.7  815.32
  5009.8  815.82  5019.1  820.59  5046.5  820.62  5091.3  827.37  5127.2  827.07
  5133.2  829.30  5168.0  830.89  5212.9  829.64  5219.1  831.74  5226.8  830.64
  5233.8  833.67  5240.0  831.77  5248.4  834.04  5254.6  831.57  5263.1  834.53
  5269.3  833.28  5276.4  835.37  5348.8  837.34  5412.7  843.76  5437.3  843.18
#Mann=5,-1,0
  4373.8    0.05       0  4873.6    0.12       0  4999.3    0.07       0
  5009.8    0.12       0  5168.0    0.05       0
Bank Sta=4999.3,5009.8
Exp/Cntr=0.3,0.1

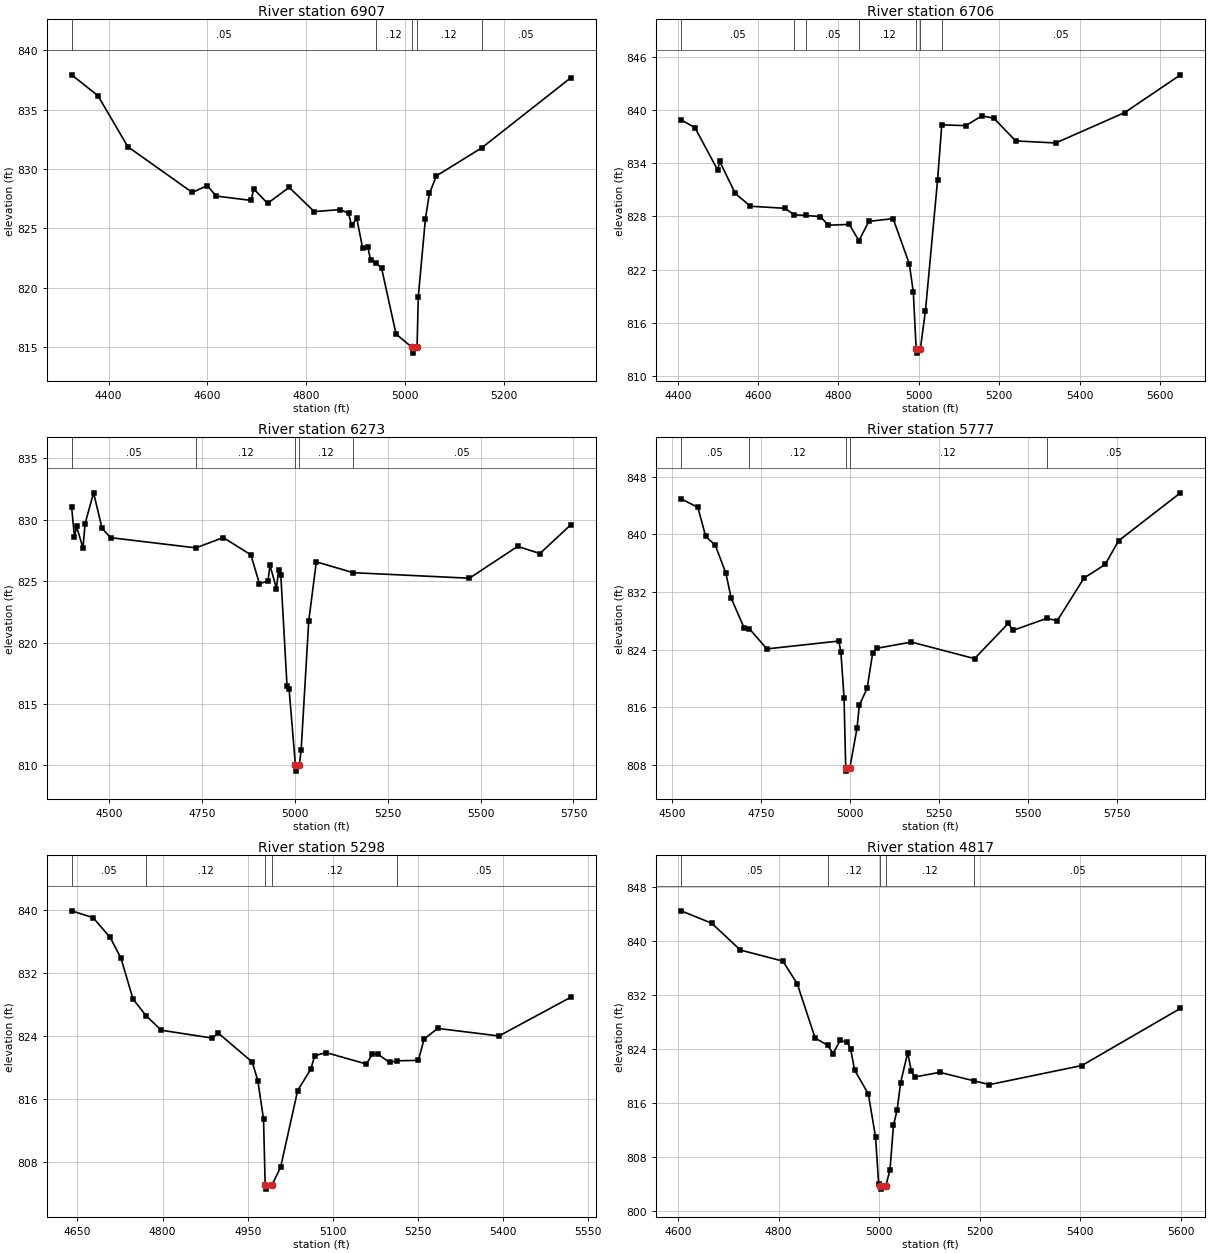
Type RM Length L Ch R = 1,6907,201,201,201
BEGIN DESCRIPTION:
Mapping XS dab87c8a
END DESCRIPTION:
XS GIS Cut Line= 5
      2280359.14      7111033.04      2280329.71      7110688.58
      2280276.83      7110510.59      2280076.74      7110121.23
      2280057.04      7110086.38
#Sta/Elev= 30
  4325.4  837.94  4378.6  836.18  4438.9  831.89  4569.3  828.03  4599.4  828.61
  4617.6  827.73  4688.2  827.36  4693.4  828.34  4721.4  827.11  4765.1  828.46
  4815.7  826.42  4868.7  826.59  4885.2  826.27  4891.2  825.25  4901.8  825.84
  4913.7  823.32  4924.0  823.46  4929.6  822.34  4940.7  822.09  4951.8  821.67
  4981.1  816.11  5013.0  815.00  5014.5  814.50  5023.6  815.00  5026.1  819.26
  5040.5  825.83  5048.6  827.95  5062.7  829.43  5154.0  831.78  5334.6  837.70
#Mann=5,-1,0
  4325.4    0.05       0  4940.7    0.12       0  5013.0    0.07       0
  5023.6    0.12       0  5154.0    0.05       0
Bank Sta=5013,5023.6
Exp/Cntr=0.3,0.1

Type RM Length L Ch R = 1,6706,433,433,433
BEGIN DESCRIPTION:
Mapping XS 48618d7b
END DESCRIPTION:
XS GIS Cut Line= 4
      2280415.26      7111063.84      2280364.65      7110652.12
      2280400.50      7110334.31      2280215.79      7109860.70
#Sta/Elev= 30
  4408.3  838.92  4442.4  838.07  4499.2  833.26  4504.2  834.23  4543.2  830.61
  4580.5  829.16  4666.8  828.93  4689.5  828.19  4719.5  828.12  4754.7  827.98
  4774.9  827.01  4826.7  827.11  4851.0  825.26  4875.6  827.45  4936.0  827.76
  4976.2  822.65  4986.3  819.45  4993.3  813.04  4994.7  812.54  5003.9  813.04
  5016.5  817.34  5046.7  832.14  5057.1  838.37  5117.1  838.28  5156.9  839.39
  5186.7  839.12  5241.1  836.55  5340.8  836.32  5512.5  839.76  5651.3  844.03
#Mann=7,-1,0
  4408.3    0.05       0  4689.5    0.12       0  4719.5    0.05       0
  4851.0    0.12       0  4993.3    0.07       0  5003.9    0.12       0
  5057.1    0.05       0
Bank Sta=4993.3,5003.9
Exp/Cntr=0.3,0.1

Type RM Length L Ch R = 1,6273,496,496,496
BEGIN DESCRIPTION:
Long Branch 12.0
END DESCRIPTION:
XS GIS Cut Line= 3
      2280520.08      7111060.45      2280777.36      7110506.05
      2280627.72      7109789.60
#Sta/Elev= 30
  4400.0  831.03  4407.7  828.58  4413.2  829.46  4430.6  827.70  4436.1  829.67
  4459.0  832.19  4481.9  829.30  4504.8  828.54  4734.2  827.71  4808.0  828.55
  4882.2  827.14  4905.1  824.80  4928.0  825.00  4933.6  826.29  4950.9  824.40
  4956.5  825.87  4962.7  825.47  4979.4  816.49  4984.9  816.24  5001.9  810.04
  5003.3  809.54  5012.5  810.04  5017.4  811.26  5037.8  821.75  5058.2  826.57
  5157.9  825.69  5469.9  825.24  5599.7  827.83  5659.7  827.25  5743.1  829.60
#Mann=5,-1,0
  4400.0    0.05       0  4734.2    0.12       0  5001.9    0.07       0
  5012.5    0.12       0  5157.9    0.05       0
Bank Sta=5001.9,5012.5
Exp/Cntr=0.3,0.1

Type RM Length L Ch R = 1,5777,479,479,479
BEGIN DESCRIPTION:
Long Branch 11.0
END DESCRIPTION:
XS GIS Cut Line= 3
      2281374.84      7110628.89      2281108.90      7110239.69
      2280651.30      7109428.43
#Sta/Elev= 30
  4524.6  844.93  4571.7  843.75  4593.4  839.72  4620.5  838.50  4650.3  834.60
  4665.2  831.13  4701.1  827.07  4715.6  826.93  4765.5  824.10  4967.3  825.19
  4973.3  823.73  4982.2  817.35  4986.9  807.63  4988.5  807.13  4998.7  807.63
  5018.6  813.07  5025.3  816.30  5047.0  818.61  5062.9  823.59  5076.0  824.20
  5171.2  825.05  5348.9  822.75  5443.4  827.63  5457.2  826.68  5551.3  828.33
  5581.4  828.03  5656.5  833.94  5715.8  835.82  5753.4  839.11  5927.4  845.77
#Mann=5,-1,0
  4524.6    0.05       0  4715.6    0.12       0  4986.9    0.07       0
  4998.7    0.12       0  5551.3    0.05       0
Bank Sta=4986.9,4998.7
Exp/Cntr=0.3,0.1

Type RM Length L Ch R = 1,5298,481,481,481
BEGIN DESCRIPTION:
Mapping XS 4899f6ff
END DESCRIPTION:
XS GIS Cut Line= 3
      2281507.51      7110557.88      2281491.28      7110136.77
      2281414.40      7109684.99
#Sta/Elev= 30
  4639.8  839.90  4677.7  839.03  4707.7  836.52  4726.8  833.88  4747.8  828.74
  4770.7  826.61  4797.8  824.76  4887.9  823.76  4897.9  824.41  4957.9  820.73
  4967.9  818.35  4977.9  813.48  4980.8  805.11  4982.5  804.61  4992.7  805.11
  5008.0  807.39  5038.0  817.11  5061.2  819.83  5068.1  821.53  5088.4  821.92
  5159.3  820.47  5169.5  821.73  5179.7  821.70  5200.0  820.68  5213.5  820.88
  5250.7  820.94  5260.8  823.65  5284.8  824.99  5392.7  824.03  5519.5  828.95
#Mann=5,-1,0
  4639.8    0.05       0  4770.7    0.12       0  4980.8    0.07       0
  4992.7    0.12       0  5213.5    0.05       0
Bank Sta=4980.8,4992.7
Exp/Cntr=0.3,0.1

Type RM Length L Ch R = 1,4817,439,439,439
BEGIN DESCRIPTION:
Long Branch 9.0
END DESCRIPTION:
XS GIS Cut Line= 3
      2282103.00      7110291.79      2281845.80      7109993.58
      2281415.47      7109576.48
#Sta/Elev= 30
  4606.2  844.52  4667.0  842.68  4724.0  838.71  4808.5  837.07  4837.0  833.73
  4872.7  825.67  4897.5  824.62  4908.3  823.38  4922.5  825.32  4936.8  825.03
  4943.4  824.01  4951.1  820.95  4978.5  817.40  4992.8  811.04  4999.1  804.01
  5001.5  803.80  5003.1  803.30  5013.4  803.80  5021.6  806.17  5028.5  812.74
  5035.7  815.00  5042.7  819.06  5056.8  823.53  5064.0  820.81  5071.0  819.91
  5120.6  820.60  5189.6  819.32  5219.4  818.78  5403.3  821.61  5599.3  830.07
#Mann=5,-1,0
  4606.2    0.05       0  4897.5    0.12       0  5001.5    0.07       0
  5013.4    0.12       0  5189.6    0.05       0
Bank Sta=5001.5,5013.4
Exp/Cntr=0.3,0.1

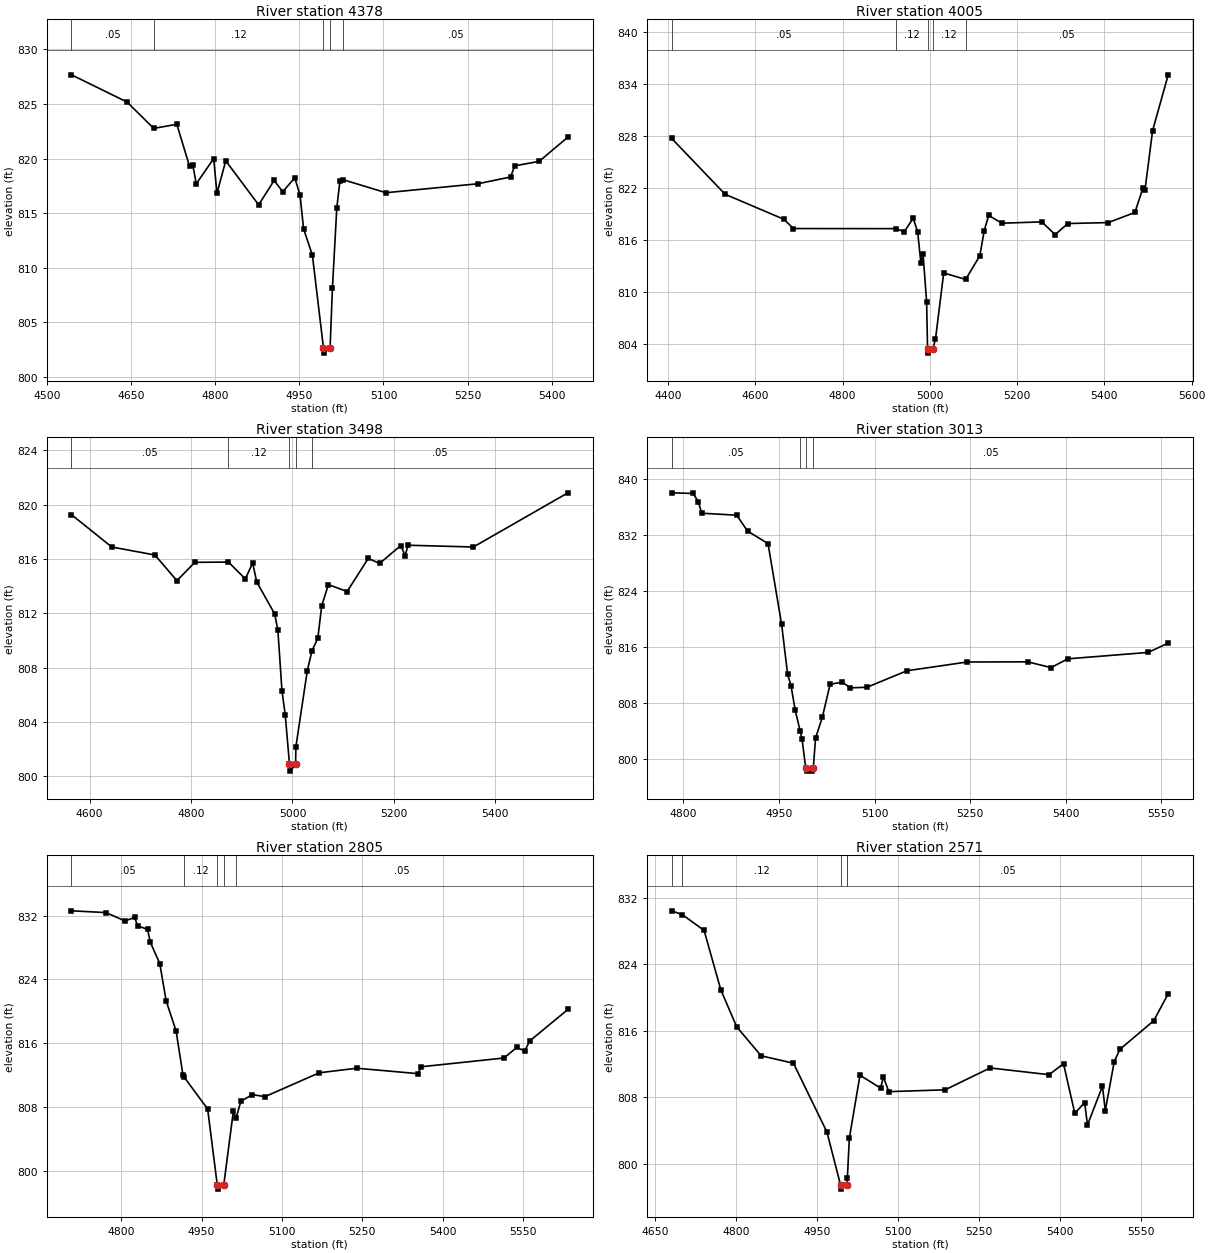
Type RM Length L Ch R = 1,4378,373,373,373
BEGIN DESCRIPTION:
Long Branch 8.0
END DESCRIPTION:
XS GIS Cut Line= 3
      2282381.27      7109833.92      2281986.88      7109603.84
      2281608.75      7109401.00
#Sta/Elev= 30
  4543.4  827.66  4642.5  825.17  4690.1  822.76  4731.3  823.13  4754.1  819.28
  4759.9  819.40  4766.0  817.68  4797.1  820.00  4802.9  816.81  4818.6  819.79
  4877.3  815.76  4904.9  817.99  4920.3  816.96  4941.8  818.24  4951.2  816.63
  4957.5  813.56  4973.2  811.15  4992.9  802.69  4994.5  802.19  5004.8  802.69
  5008.9  808.11  5016.7  815.45  5022.3  817.94  5027.6  818.07  5104.4  816.87
  5268.4  817.69  5326.7  818.31  5334.2  819.33  5377.7  819.74  5429.1  821.96
#Mann=5,-1,0
  4543.4    0.05       0  4690.1    0.12       0  4992.9    0.07       0
  5004.8    0.12       0  5027.6    0.05       0
Bank Sta=4992.9,5004.8
Exp/Cntr=0.3,0.1

Type RM Length L Ch R = 1,4005,507,507,507
BEGIN DESCRIPTION:
Long Branch 7.0
END DESCRIPTION:
XS GIS Cut Line= 3
      2282661.25      7109390.13      2282077.78      7109270.50
      2281543.80      7109175.32
#Sta/Elev= 30
  4408.2  827.74  4530.6  821.29  4665.7  818.39  4687.0  817.33  4921.6  817.32
  4941.3  816.97  4961.7  818.53  4971.9  816.94  4979.2  813.40  4984.3  814.38
  4992.4  808.87  4994.6  803.43  4996.3  802.93  5006.6  803.43  5012.7  804.53
  5031.6  812.20  5081.9  811.45  5114.3  814.18  5124.5  817.08  5134.6  818.85
  5165.1  817.95  5256.5  818.10  5287.0  816.63  5316.2  817.91  5408.9  818.02
  5469.8  819.19  5488.1  821.97  5493.1  821.82  5510.4  828.64  5546.2  835.10
#Mann=5,-1,0
  4408.2    0.05       0  4921.6    0.12       0  4994.6    0.07       0
  5006.6    0.12       0  5081.9    0.05       0
Bank Sta=4994.6,5006.6
Exp/Cntr=0.3,0.1

Type RM Length L Ch R = 1,3498,485,485,485
BEGIN DESCRIPTION:
Mapping XS 10b7accd
END DESCRIPTION:
XS GIS Cut Line= 2
      2282492.04      7109298.61      2281889.78      7108527.41
#Sta/Elev= 30
  4564.4  819.26  4643.8  816.88  4728.8  816.29  4772.2  814.40  4807.5  815.75
  4873.8  815.77  4907.0  814.53  4921.4  815.70  4929.6  814.30  4964.9  811.95
  4971.2  810.75  4979.3  806.27  4985.7  804.52  4994.1  800.87  4995.8  800.37
  5006.1  800.87  5006.7  802.16  5029.1  807.75  5038.4  809.23  5049.9  810.15
  5057.5  812.53  5070.7  814.11  5107.7  813.60  5149.4  816.04  5171.7  815.67
  5213.6  816.99  5221.7  816.25  5228.1  817.01  5356.5  816.88  5542.9  820.87
#Mann=5,-1,0
  4564.4    0.05       0  4873.8    0.12       0  4994.1    0.07       0
  5006.1    0.12       0  5038.4    0.05       0
Bank Sta=4994.1,5006.1
Exp/Cntr=0.3,0.1

Type RM Length L Ch R = 1,3013,208,208,208
BEGIN DESCRIPTION:
Long Branch 5.0
END DESCRIPTION:
XS GIS Cut Line= 3
      2282700.29      7108670.73      2282496.10      7108593.51
      2281964.30      7108414.91
#Sta/Elev= 30
  4781.7  838.08  4815.2  837.99  4823.3  836.83  4828.7  835.16  4883.7  834.88
  4900.7  832.60  4932.8  830.82  4954.1  819.29  4963.5  812.16  4968.9  810.48
  4975.5  806.97  4983.3  803.97  4986.2  802.85  4991.9  798.75  4993.6  798.25
  5002.3  798.25  5003.9  798.75  5007.5  803.00  5018.0  805.94  5030.3  810.69
  5049.7  810.98  5061.8  810.17  5088.1  810.25  5151.1  812.62  5245.7  813.87
  5340.3  813.89  5377.1  813.07  5403.4  814.32  5529.5  815.24  5561.0  816.57
#Mann=4,-1,0
  4781.7    0.05       0  4983.3    0.12       0  4991.9    0.04       0
  5003.9    0.05       0
Bank Sta=4991.9,5003.9
Exp/Cntr=0.3,0.1

Type RM Length L Ch R = 1,2805,234,234,234
BEGIN DESCRIPTION:
Mapping XS a25b1a32
END DESCRIPTION:
XS GIS Cut Line= 2
      2282811.45      7108510.23      2281954.35      7108159.46
#Sta/Elev= 30
  4707.4  832.59  4771.7  832.37  4807.3  831.32  4825.2  831.77  4830.6  830.72
  4849.2  830.26  4854.6  828.62  4872.1  825.97  4884.0  821.29  4902.6  817.50
  4915.3  812.00  4918.1  811.68  4961.4  807.72  4979.4  798.17  4981.0  797.67
  4991.4  798.17  5009.4  807.47  5014.3  806.56  5023.4  808.70  5045.0  809.53
  5068.2  809.27  5169.7  812.27  5239.5  812.84  5353.9  812.16  5359.3  813.02
  5514.1  814.12  5538.2  815.45  5552.8  815.00  5562.2  816.26  5633.5  820.22
#Mann=5,-1,0
  4707.4    0.05       0  4918.1    0.12       0  4979.4    0.07       0
  4991.4    0.12       0  5014.3    0.05       0
Bank Sta=4979.4,4991.4
Exp/Cntr=0.3,0.1

Type RM Length L Ch R = 1,2571,463,463,463
BEGIN DESCRIPTION:
Long Branch 4.0
END DESCRIPTION:
XS GIS Cut Line= 3
      2282936.88      7108276.86      2282628.05      7108194.61
      2282053.29      7108021.01
#Sta/Elev= 30
  4680.4  830.42  4700.2  829.95  4740.3  828.07  4771.3  820.92  4800.7  816.48
  4846.0  812.99  4905.9  812.10  4968.0  803.82  4993.2  797.46  4994.9  796.96
  5005.2  797.46  5005.8  798.24  5009.5  803.08  5029.2  810.65  5067.4  809.11
  5072.6  810.45  5082.6  808.68  5187.0  808.90  5270.4  811.53  5379.7  810.72
  5406.4  812.04  5427.3  806.08  5445.6  807.36  5450.8  804.67  5478.6  809.34
  5483.8  806.40  5500.4  812.29  5510.9  813.77  5573.5  817.20  5600.4  820.44
#Mann=5,-1,0
  4680.4    0.05       0  4700.2    0.12       0  4993.2    0.07       0
  5005.2    0.12       0  5005.8    0.05       0
Bank Sta=4993.2,5005.2
Exp/Cntr=0.3,0.1

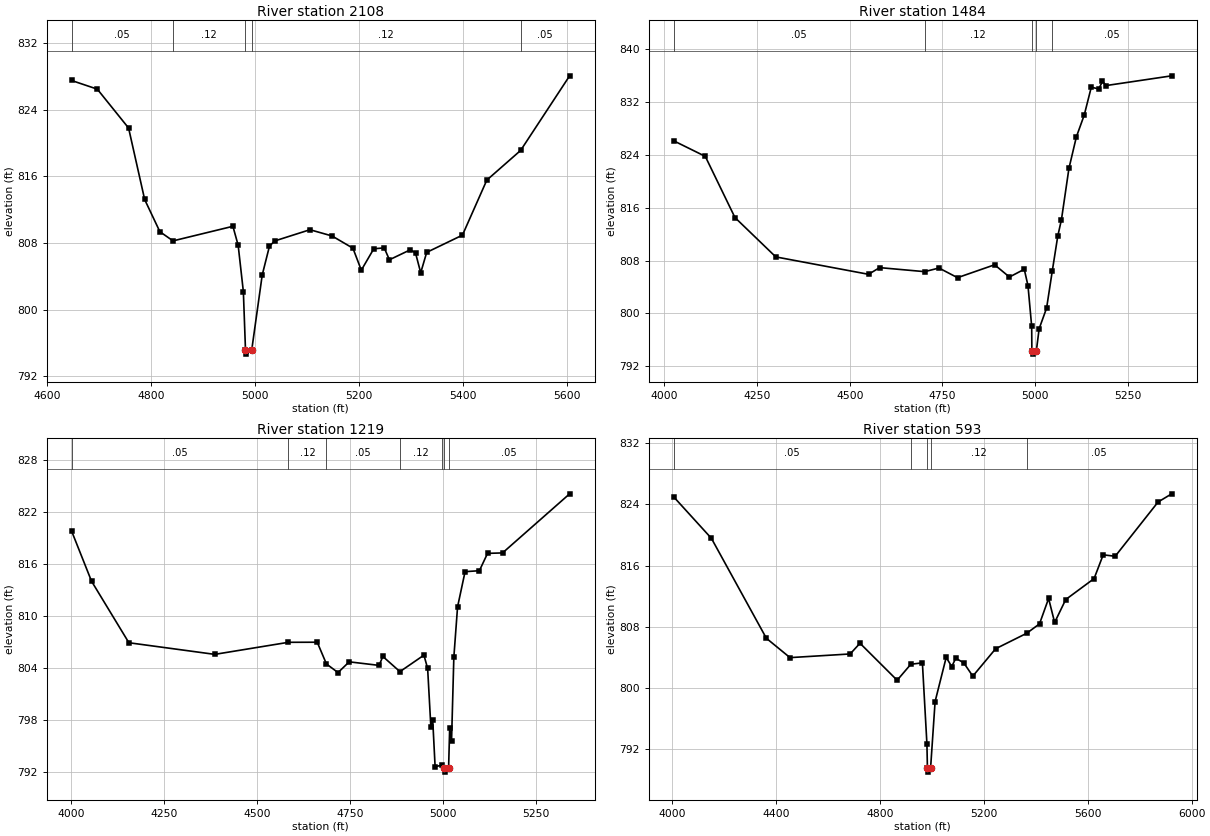
Type RM Length L Ch R = 1,2108,624,624,624
BEGIN DESCRIPTION:
Mapping XS cdc3073a
END DESCRIPTION:
XS GIS Cut Line= 3
      2283018.29      7107793.23      2282558.88      7107833.05
      2282063.51      7107792.00
#Sta/Elev= 30
  4647.1  827.51  4696.6  826.47  4756.8  821.80  4787.7  813.22  4817.0  809.35
  4842.3  808.25  4957.5  810.00  4967.6  807.72  4977.6  802.16  4981.7  795.15
  4983.3  794.65  4993.7  795.15  5013.9  804.16  5027.8  807.61  5037.8  808.24
  5105.7  809.59  5148.2  808.84  5188.4  807.37  5204.5  804.73  5228.5  807.30
  5248.6  807.41  5258.6  805.98  5298.8  807.18  5308.8  806.80  5318.8  804.42
  5330.3  806.87  5399.1  808.94  5446.0  815.55  5511.0  819.11  5605.3  828.07
#Mann=5,-1,0
  4647.1    0.05       0  4842.3    0.12       0  4981.7    0.07       0
  4993.7    0.12       0  5511.0    0.05       0
Bank Sta=4981.7,4993.7
Exp/Cntr=0.3,0.1

Type RM Length L Ch R = 1,1484,265,265,265
BEGIN DESCRIPTION:
Long Branch 2.0
END DESCRIPTION:
XS GIS Cut Line= 3
      2283264.43      7107489.68      2282290.83      7107502.45
      2281923.25      7107538.21
#Sta/Elev= 30
  4025.0  826.11  4110.4  823.75  4190.4  814.50  4300.5  808.55  4550.5  805.92
  4580.5  806.93  4701.9  806.32  4740.5  806.87  4790.5  805.41  4890.5  807.36
  4930.5  805.51  4970.5  806.68  4980.5  804.21  4990.5  798.03  4991.0  794.35
  4992.7  793.85  5003.1  794.35  5010.6  797.69  5030.7  800.81  5046.1  806.45
  5060.8  811.69  5070.8  814.20  5090.9  821.92  5111.0  826.70  5132.2  830.00
  5151.2  834.21  5171.3  833.95  5181.4  835.08  5191.4  834.46  5368.0  835.93
#Mann=5,-1,0
  4025.0    0.05       0  4701.9    0.12       0  4991.0    0.07       0
  5003.1    0.12       0  5046.1    0.05       0
Bank Sta=4991,5003.1
Exp/Cntr=0.3,0.1

Type RM Length L Ch R = 1,1219,626,626,626
BEGIN DESCRIPTION:
Mapping XS 6aa256e7
END DESCRIPTION:
XS GIS Cut Line= 3
      2283242.44      7107338.89      2282248.09      7107242.21
      2281909.95      7107285.24
#Sta/Elev= 30
  4001.4  819.82  4055.1  814.03  4155.6  806.94  4386.6  805.60  4584.8  806.99
  4662.3  807.00  4687.0  804.50  4718.2  803.50  4748.3  804.74  4828.7  804.33
  4838.8  805.36  4884.8  803.61  4949.3  805.51  4959.3  803.98  4968.0  797.22
  4973.0  798.02  4979.4  792.65  4998.1  792.84  5003.6  792.53  5005.3  792.03
  5015.7  792.53  5018.6  797.09  5023.6  795.62  5029.8  805.27  5039.8  811.07
  5060.0  815.13  5098.5  815.24  5120.5  817.24  5160.8  817.29  5341.3  824.10
#Mann=7,-1,0
  4001.4    0.05       0  4584.8    0.12       0  4687.0    0.05       0
  4884.8    0.12       0  4998.1    0.05       0  5003.6   0.033       0
  5015.7    0.05       0
Bank Sta=5003.6,5015.7
Exp/Cntr=0.3,0.1

Type RM Length L Ch R = 1,593,0,0,0
BEGIN DESCRIPTION:
Long Branch 1.0
END DESCRIPTION:
XS GIS Cut Line= 3
      2283455.67      7107206.18      2282563.00      7106792.87
      2281763.11      7107274.49
#Sta/Elev= 30
  4005.7  824.99  4151.1  819.56  4362.8  806.48  4453.8  803.95  4685.3  804.43
  4723.2  805.83  4866.2  800.99  4918.8  803.08  4963.4  803.27  4980.8  792.68
  4982.8  789.47  4984.5  788.97  4994.9  789.47  5012.3  798.20  5055.0  803.98
  5076.4  802.78  5091.9  803.87  5122.5  803.27  5157.5  801.53  5245.3  805.11
  5365.2  807.14  5414.3  808.37  5449.3  811.69  5472.5  808.55  5515.2  811.55
  5624.4  814.29  5659.4  817.40  5705.6  817.21  5870.7  824.31  5923.1  825.38
#Mann=5,-1,0
  4005.7    0.05       0  4918.8    0.12       0  4982.8    0.07       0
  4994.9    0.12       0  5365.2    0.05       0
Bank Sta=4982.8,4994.9
Exp/Cntr=0.3,0.1

Chan Stop Cuts=-1