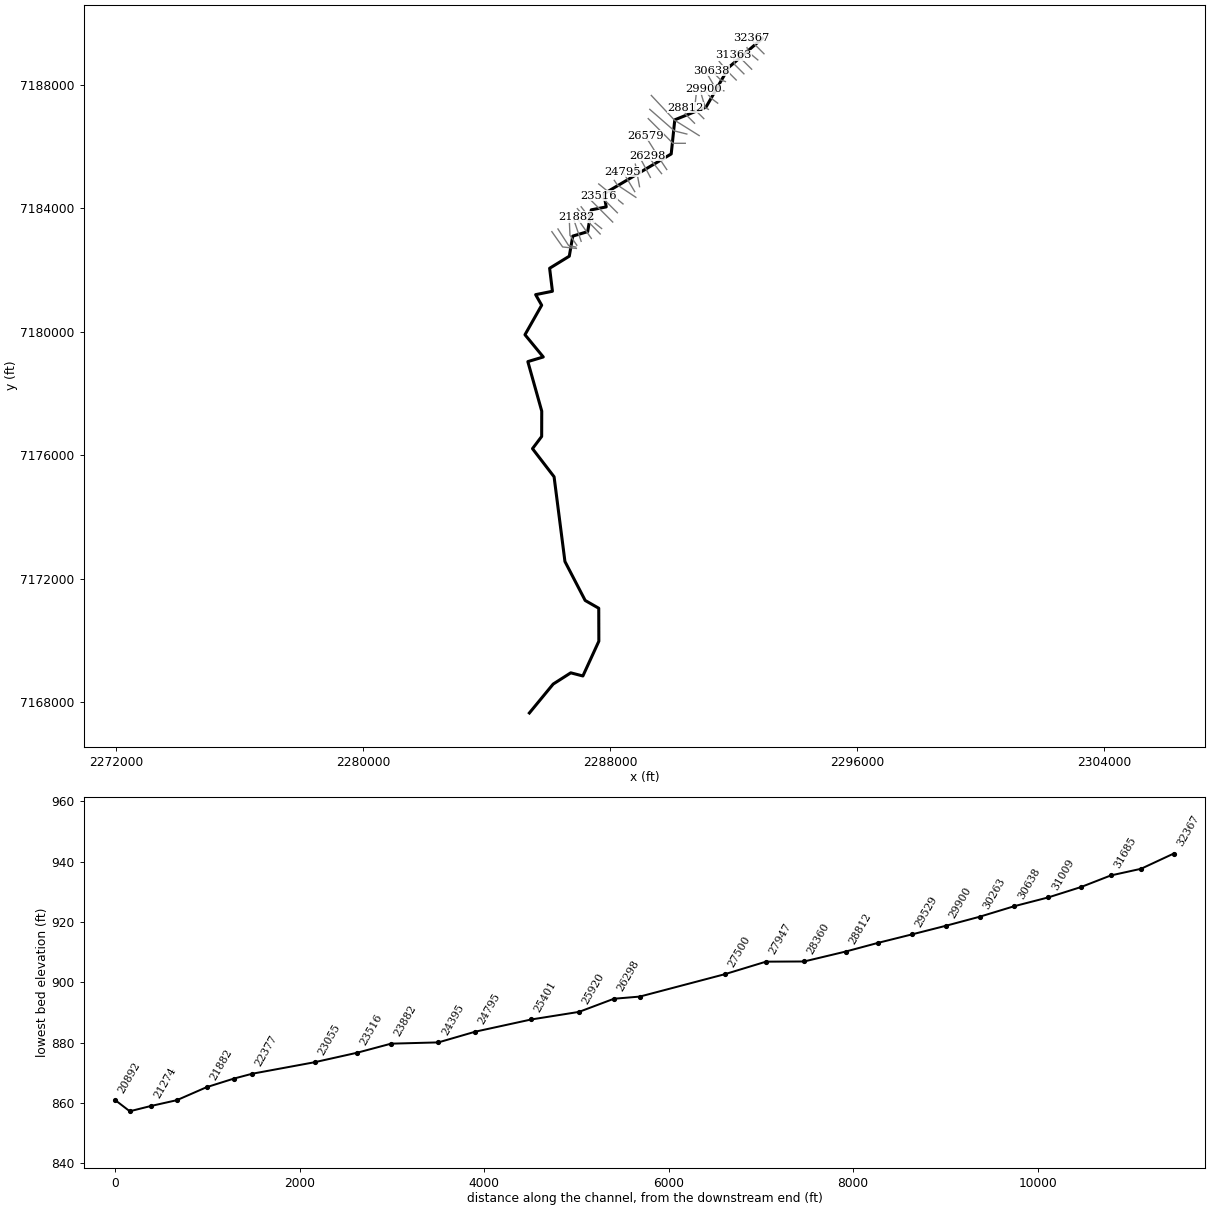
--- MDE S 001.prj (project) ---

Proj Title=MDE S 001 Base Level Engineering
Current Plan=p01
Default Exp/Contr=0.3,0.1
English Units
Geom File=g01
Flow File=f01
Plan File=p01
Y Axis Title=Elevation
X Axis Title(PF)=Main Channel Distance
X Axis Title(XS)=Station
BEGIN DESCRIPTION:
MDE S 001
END DESCRIPTION:
DSS Export Rating Curves= 0
DSS Export Rating Curve Sorted= 0
DSS Export Volume Flow Curves= 0
DXF OffsetX= 0
DXF OffsetY= 0
DXF ScaleX= 1
DXF ScaleY= 10

--- MDE S 001.p01 (plan) ---

Plan Title=Multiple Run
Short Identifier=Multiple
Geom File=g01
Flow File=f01
Subcritical Flow
K Sum by GR= 0
Std Step Tol= 0.01
Critical Tol= 0.01
Num of Std Step Trials= 20
Max Error Tol= 0.3
Flow Tol Ratio= 0.001
Split Flow NTrial= 30
Split Flow Tol= 0.02
Split Flow Ratio= 0.02
Log Output Level= 0
Friction Slope Method= 1
Unsteady Friction Slope Method= 2
Unsteady Bridges Friction Slope Method= 1
Parabolic Critical Depth
Global Vel Dist=  1 , 1 , 1
Global Log Level= 0
CheckData=True
Encroach Param= -1, 0, 0, 0
BEGIN DESCRIPTION:
Multiple Run
END DESCRIPTION:

--- MDE S 001.f01 (steady flow) ---

Flow Title=Multiple
Number of Profiles=7
Profile Names=10-year,25-year,50-year,1pct_min,100-year,1pct_plu,500-year
River Rch & RM= MDE S 001,Reach-1,32367
     680     935    1147     699    1394    2782    2064
River Rch & RM= MDE S 001,Reach-1,28360
    1050    1477    1839    1135    2265    4519    3445
River Rch & RM= MDE S 001,Reach-1,23882
    1286    1828    2292    1424    2841    5668    4375
River Rch & RM= MDE S 001,Reach-1,21049
    1532    2192    2760    1720    3432    6848    5324
River Rch & RM= MDE S 001,Reach-1,13914
    1721    2470    3115    1945    3881    7743    6038
River Rch & RM= MDE S 001,Reach-1,9934
    1861    2681    3391    2122    4233    8446    6616
River Rch & RM= MDE S 001,Reach-1,6154
    2065    2987    3788    2376    4741    9459    7445
River Rch & RM= MDE S 001,Reach-1,4381
    2085    3013    3819    2393    4775    9528    7489
Boundary for River Rch & Prof#=MDE S 001,Reach-1,1
Up Type=0
Dn Type=3
Dn Slope=0.005
Boundary for River Rch & Prof#=MDE S 001,Reach-1,2
Up Type=0
Dn Type=3
Dn Slope=0.005
Boundary for River Rch & Prof#=MDE S 001,Reach-1,3
Up Type=0
Dn Type=3
Dn Slope=0.005
Boundary for River Rch & Prof#=MDE S 001,Reach-1,4
Up Type=0
Dn Type=3
Dn Slope=0.005
Boundary for River Rch & Prof#=MDE S 001,Reach-1,5
Up Type=0
Dn Type=3
Dn Slope=0.005
Boundary for River Rch & Prof#=MDE S 001,Reach-1,6
Up Type=0
Dn Type=3
Dn Slope=0.005
Boundary for River Rch & Prof#=MDE S 001,Reach-1,7
Up Type=0
Dn Type=3
Dn Slope=0.005

--- MDE S 001.g01 (geometry) ---

Geom Title=Existing Conditions
Program Version=4.10

River Reach=MDE S 001       ,Reach-1
Reach XY= 30
        2292929.        7189510.      2291842.45      7188573.63
      2291099.47      7187279.62      2290089.22      7186870.11
      2289973.49      7185765.07      2287792.36      7184473.32
      2287868.72      7184049.84      2287384.03      7183955.08
      2287268.35      7183249.89      2286784.61      7183104.41
      2286671.66      7182453.61      2286034.82      7182062.31
      2286125.78      7181317.98      2285581.99       7181208.6
       2285777.1      7180865.72      2285236.08      7179909.98
      2285829.12       7179189.9      2285329.04      7179039.82
      2285779.13      7177437.31      2285777.06      7176615.71
       2285479.7      7176220.71        2286179.        7175310.
      2286530.86      7172566.13      2287186.81      7171303.81
      2287626.09      7171052.09      2287629.41        7169985.
      2287112.46      7168858.57      2286719.66       7168960.4
      2286149.67      7168596.33        2285379.        7167660.

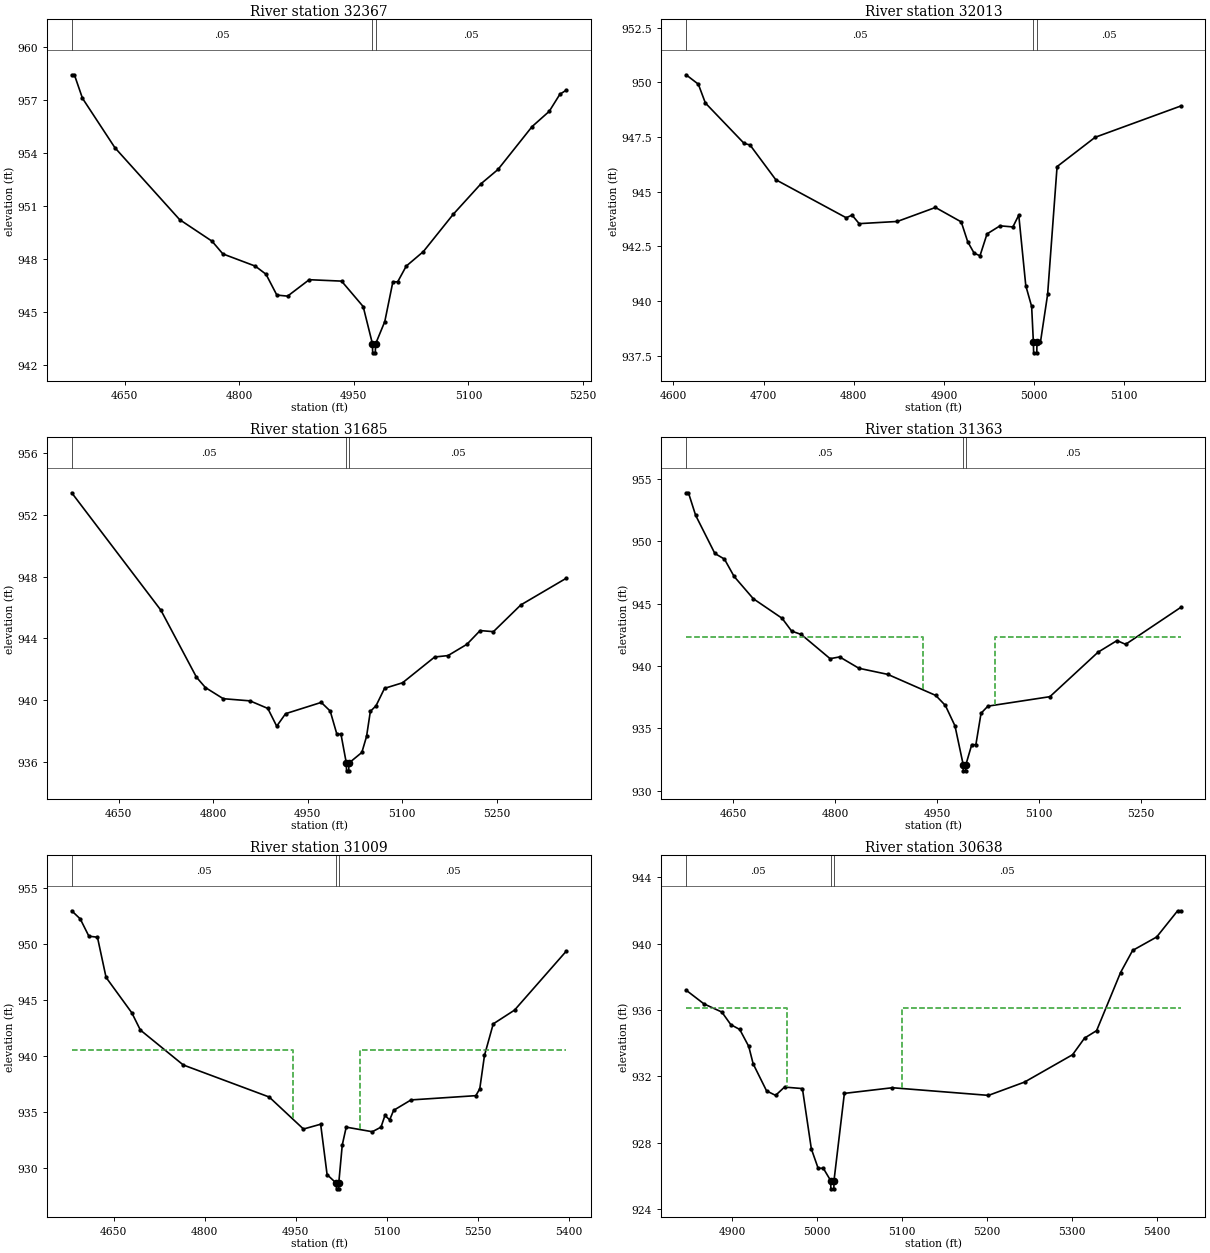
Type RM Length L Ch R = 1 ,32367   ,354,354,354
BEGIN DESCRIPTION:
MDE S 001 68.0
END DESCRIPTION:
XS GIS Cut Line= 3
      2292978.99      7189010.01        2292679.        7189310.
      2292578.98      7189510.04
#Sta/Elev= 30
  4580.4  958.41  4583.9  958.41  4594.5  957.08    4637  954.28  4721.8  950.21
  4764.2  948.99  4778.4  948.27  4820.8  947.58  4834.9  947.12  4849.1  945.94
  4863.2  945.88  4891.5  946.81  4933.9  946.73  4962.2  945.29  4974.4  943.17
  4974.6  942.67  4978.1  942.67  4978.4  943.17  4990.5  944.44  5001.1  946.69
  5007.4  946.69  5018.6  947.58    5041   948.4  5080.1  950.51  5116.5  952.24
  5138.8  953.05  5183.5  955.48  5205.9  956.34  5219.9  957.31  5228.3  957.54
#Mann= 3 ,-1 , 0
  4580.4     .05       0  4974.4    .033       0  4978.4     .05       0
Bank Sta=4974.4,4978.4
XS Rating Curve= 0 ,0
Exp/Cntr=0.3,0.1

Type RM Length L Ch R = 1 ,32013   ,328,328,328
BEGIN DESCRIPTION:
MDE S 001 67.0
END DESCRIPTION:
XS GIS Cut Line= 3
      2292778.96      7188810.03        2292479.        7189060.
      2292428.99      7189210.02
#Sta/Elev= 30
    4614  950.35  4627.6  949.92  4635.4  949.06  4678.4  947.21  4684.9  947.14
  4713.5  945.55  4791.6  943.81  4798.1  943.93    4806  943.54  4848.3  943.64
  4890.6  944.28  4919.2  943.62  4926.4  942.71  4933.5  942.19    4940  942.07
  4947.8  943.07  4962.2  943.44  4976.5  943.39    4983  943.93  4990.8   940.7
  4997.3  939.75  4999.2  938.13  4999.5  937.63    5003  937.63  5003.2  938.13
  5007.1  938.13    5015   940.3  5025.5  946.15  5067.7  947.49  5162.6  948.92
#Mann= 3 ,-1 , 0
    4614     .05       0  4999.2    .033       0  5003.2     .05       0
Bank Sta=4999.2,5003.2
XS Rating Curve= 0 ,0
Exp/Cntr=0.3,0.1

Type RM Length L Ch R = 1 ,31685   ,322,322,322
BEGIN DESCRIPTION:
MDE S 001 66.0
END DESCRIPTION:
XS GIS Cut Line= 3
      2292579.02      7188509.98        2292279.        7188810.
      2292078.97      7189110.04
#Sta/Elev= 30
  4575.5  953.42    4717  945.82  4773.5  941.48  4787.7  940.81    4816  940.09
  4858.4  939.95  4886.7  939.46  4900.8  938.31  4914.9  939.12  4971.5  939.85
  4985.7  939.29  4996.3  937.79  5002.8  937.79  5011.3  935.92  5011.6  935.42
  5015.1  935.42  5015.3  935.92  5035.9  936.61  5043.4  937.65  5049.4  939.27
  5058.4  939.63  5071.9  940.76  5100.5  941.12  5151.5  942.79  5172.6  942.88
  5202.6  943.61  5223.6   944.5  5244.7  944.43  5288.2  946.16  5360.4  947.89
#Mann= 3 ,-1 , 0
  4575.5     .05       0  5011.3    .033       0  5015.3     .05       0
Bank Sta=5011.3,5015.3
XS Rating Curve= 0 ,0
Exp/Cntr=0.3,0.1

Type RM Length L Ch R = 1 ,31363   ,354,354,354
BEGIN DESCRIPTION:
MDE S 001 65.0
END DESCRIPTION:
XS GIS Cut Line= 3
      2292328.98      7188360.02        2292029.        7188660.
        2291979.      7188960.03
#Sta/Elev= 30
  4580.4   953.9  4583.9   953.9  4594.5  952.09  4622.8  949.03  4636.9  948.58
  4651.1  947.19  4679.4   945.4  4721.8  943.83  4735.9   942.8  4750.1  942.53
  4792.5  940.59  4806.6  940.73  4834.9  939.82  4877.4  939.33  4948.1  937.64
  4962.2  936.84  4976.4   935.2  4988.5  932.09  4988.7  931.59  4992.2  931.59
  4992.5  932.09  5001.1  933.69  5007.2  933.69  5014.8  936.21  5024.9  936.78
  5116.2  937.54  5187.1  941.11    5215  942.04  5227.7  941.74  5308.8   944.7
#Mann= 3 ,-1 , 0
  4580.4     .05       0  4988.5    .033       0  4992.5     .05       0
#XS Ineff= 2 , 0
       0    4930  942.33  5035.4       0  942.33
Permanent Ineff=
       F       F
Bank Sta=4988.5,4992.5
XS Rating Curve= 0 ,0
Exp/Cntr=0.3,0.1

Type RM Length L Ch R = 1 ,31009   ,371,371,371
BEGIN DESCRIPTION:
MDE S 001 64.0
END DESCRIPTION:
XS GIS Cut Line= 3
      2292078.99      7188160.01        2291779.        7188460.
      2291528.98      7188760.03
#Sta/Elev= 30
  4580.8  952.99  4594.9  952.26  4609.1  950.72  4623.2  950.63  4637.4  947.04
  4679.8  943.88  4693.9  942.34  4764.6  939.22  4906.1  936.36  4962.6   933.5
  4990.9  933.93  5001.5  929.43  5016.7  928.66    5017  928.16  5020.5  928.16
  5020.7  928.66  5026.5  932.08    5033  933.67    5076  933.26  5090.3  933.67
  5096.8  934.71  5104.6  934.32  5111.1  935.17  5139.8   936.1  5246.5  936.48
    5253  937.09  5260.8  940.08  5275.2  942.89  5310.3  944.12  5395.6  949.39
#Mann= 3 ,-1 , 0
  4580.8     .05       0  5016.7     .04       0  5020.7     .05       0
#XS Ineff= 2 , 0
       0    4945  940.58    5055       0  940.58
Permanent Ineff=
       F       F
Bank Sta=5016.7,5020.7
XS Rating Curve= 0 ,0
Exp/Cntr=0.3,0.1

Type RM Length L Ch R = 1 ,30638   ,375,375,375
BEGIN DESCRIPTION:
MDE S 001 63.0
END DESCRIPTION:
XS GIS Cut Line= 3
      2291728.98      7188110.01        2291579.        7188160.
      2291278.97      7188460.03
#Sta/Elev= 30
    4846   937.2  4867.1  936.37  4888.1  935.88  4898.7  935.12  4909.2  934.83
  4919.8  933.81    4925  932.76  4940.8  931.13  4951.4  930.86  4961.9  931.36
    4983  931.27  4993.5  927.64  5001.5  926.47  5007.6  926.47  5016.2  925.73
  5016.5  925.23    5020  925.23  5020.2  925.73  5032.4  930.98  5088.9  931.32
  5202.1  930.86  5244.5  931.66  5301.1  933.31  5315.2  934.31  5329.4  934.76
  5357.6  938.26  5371.8  939.59  5400.1   940.4  5424.8  941.98  5428.4  941.98
#Mann= 3 ,-1 , 0
    4846     .05       0  5016.2    .033       0  5020.2     .05       0
#XS Ineff= 2 , 0
       0  4965.1  936.11    5100       0  936.11
Permanent Ineff=
       F       F
Bank Sta=5016.2,5020.2
XS Rating Curve= 0 ,0
Exp/Cntr=0.3,0.1

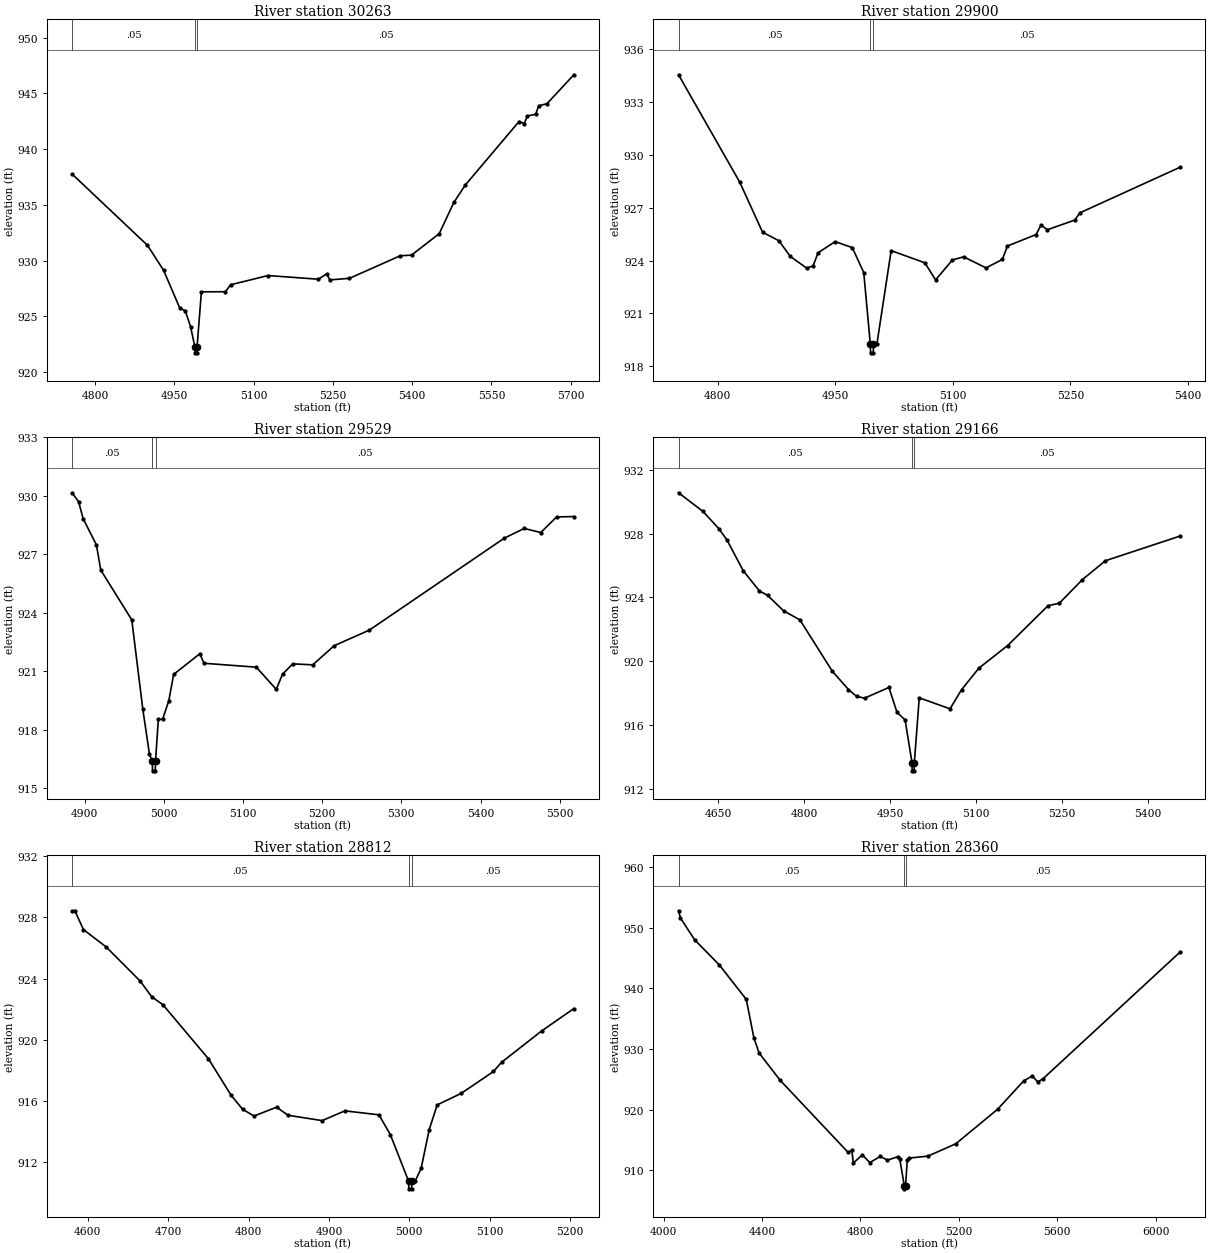
Type RM Length L Ch R = 1 ,30263   ,363,363,363
BEGIN DESCRIPTION:
MDE S 001 62.0
END DESCRIPTION:
XS GIS Cut Line= 3
      2291678.97      7187810.01        2291429.        7187860.
      2291079.02      7188459.97
#Sta/Elev= 30
  4756.4  937.77  4899.1  931.38  4929.7  929.13  4960.3  925.74  4970.5  925.52
  4980.7  924.08  4988.9  922.24  4989.2  921.74  4992.7  921.74  4992.9  922.24
  5001.1  927.21  5046.5  927.22  5056.4  927.84  5127.1  928.67  5222.6  928.34
  5238.3  928.83  5244.1  928.28  5281.3  928.42  5377.2  930.44  5398.7   930.5
  5451.2  932.43  5478.9  935.23  5500.4  936.78  5602.2  942.48  5612.1   942.3
  5617.9  942.97  5633.6  943.14  5639.4  943.89  5655.1  944.08  5705.9  946.67
#Mann= 3 ,-1 , 0
  4756.4     .05       0  4988.9    .033       0  4992.9     .05       0
Bank Sta=4988.9,4992.9
XS Rating Curve= 0 ,0
Exp/Cntr=0.3,0.1

Type RM Length L Ch R = 1 ,29900   ,371,371,371
BEGIN DESCRIPTION:
MDE S 001 61.0
END DESCRIPTION:
XS GIS Cut Line= 3
      2291478.98      7187410.02        2291279.        7187560.
      2291028.99      7187860.01
#Sta/Elev= 30
  4749.8  934.52  4827.9  928.44  4857.1   925.6  4877.9  925.12  4892.5  924.23
  4913.3  923.57  4921.6   923.7  4927.9  924.44  4949.8  925.07  4971.6  924.73
  4986.2  923.32  4994.6  919.27  4994.9  918.77  4998.4  918.77  4998.6  919.27
    5003  919.27  5021.2  924.56  5064.2  923.87  5077.9   922.9  5099.4  924.03
  5113.7  924.21  5142.3  923.58  5163.1  924.06  5169.6  924.82  5206.1  925.47
  5212.6  926.01  5220.4  925.74  5255.6  926.29  5262.1   926.7  5390.3  929.29
#Mann= 3 ,-1 , 0
  4749.8     .05       0  4994.6    .033       0  4998.6     .05       0
Bank Sta=4994.6,4998.6
XS Rating Curve= 0 ,0
Exp/Cntr=0.3,0.1

Type RM Length L Ch R = 1 ,29529   ,363,363,363
BEGIN DESCRIPTION:
MDE S 001 60.0
END DESCRIPTION:
XS GIS Cut Line= 3
      2291178.96      7187210.02        2291079.        7187260.
      2290928.99      7187760.02
#Sta/Elev= 30
  4884.1  930.16  4892.4   929.7    4898  928.84  4914.8  927.49  4920.4  926.19
  4959.5  923.64  4973.5  919.04  4981.9  916.73  4985.5  916.39  4985.7  915.89
  4989.2  915.89  4989.5  916.39  4993.1  918.54  4998.5  918.54  5006.3  919.49
  5012.4  920.84  5045.5   921.9  5050.7  921.41  5116.8  921.21    5142  920.07
  5149.9  920.85  5162.9  921.38  5188.1  921.33  5215.1  922.31  5259.5  923.11
    5430  927.83  5455.2  928.33  5476.1  928.12  5496.1  928.92  5517.9  928.94
#Mann= 3 ,-1 , 0
  4884.1     .05       0  4985.5    .033       0  4989.5     .05       0
Bank Sta=4985.5,4989.5
XS Rating Curve= 0 ,0
Exp/Cntr=0.3,0.1

Type RM Length L Ch R = 1 ,29166   ,354,354,354
BEGIN DESCRIPTION:
MDE S 001 59.0
END DESCRIPTION:
XS GIS Cut Line= 3
      2291028.98      7186910.02        2290729.        7187210.
        2290779.      7187659.99
#Sta/Elev= 30
  4580.3  930.56  4622.7   929.4    4651   928.3  4665.1  927.59  4693.4  925.67
  4721.7   924.4  4735.8  924.13  4764.1  923.15  4792.4  922.59    4849  919.37
  4877.3  918.22  4891.4  917.79  4905.5  917.68    4948  918.35  4962.1  916.79
  4976.3  916.31  4988.4  913.62  4988.6  913.12  4992.1  913.12  4992.4  913.62
    5001   917.7  5054.8  917.01    5075  918.21  5105.2  919.56  5155.5  920.98
  5225.9  923.47    5246  923.64  5286.3  925.12  5326.5   926.3  5457.3  927.85
#Mann= 3 ,-1 , 0
  4580.3     .05       0  4988.4    .033       0  4992.4     .05       0
Bank Sta=4988.4,4992.4
XS Rating Curve= 0 ,0
Exp/Cntr=0.3,0.1

Type RM Length L Ch R = 1 ,28812   ,452,452,452
BEGIN DESCRIPTION:
MDE S 001 58.0
END DESCRIPTION:
XS GIS Cut Line= 3
      2290728.99      7186760.01        2290429.        7187060.
        2290429.      7187260.05
#Sta/Elev= 30
  4580.4  928.44  4583.9  928.44  4594.5  927.21  4622.8  926.07  4665.2  923.83
  4679.4  922.81  4693.5  922.28  4750.1  918.74  4778.4  916.34  4792.5  915.44
  4806.7  914.99  4834.9  915.57  4849.1  915.04  4891.5  914.69  4919.8  915.33
  4962.2  915.07  4976.4  913.77  4999.1  910.72  4999.4  910.22  5002.9  910.22
  5003.1  910.72  5007.2  910.72  5014.7  911.56  5024.7   914.1  5034.7  915.72
  5064.7  916.48  5104.7  917.91  5114.7  918.51  5164.7  920.57  5204.7  922.03
#Mann= 3 ,-1 , 0
  4580.4     .05       0  4999.1    .033       0  5003.1     .05       0
Bank Sta=4999.1,5003.1
XS Rating Curve= 0 ,0
Exp/Cntr=0.3,0.1

Type RM Length L Ch R = 1 ,28360   ,413,413,413
BEGIN DESCRIPTION:
MDE S 001 57.0
END DESCRIPTION:
XS GIS Cut Line= 3
      2290879.02      7186359.99        2290079.        7186860.
        2289329.        7187660.
#Sta/Elev= 30
  4060.3  952.81    4068  951.63  4125.8  948.02    4226  943.88  4335.7  938.19
  4366.3  931.89  4387.6  929.35  4473.1  924.85  4749.6  912.94  4764.9  913.25
  4770.8  911.17  4807.4  912.52    4838  911.25  4880.5  912.27  4909.4  911.66
  4953.6  912.24  4959.5   911.9  4978.2  907.42  4978.8  906.92  4983.3  907.42
  4990.2   911.7  4996.1  911.99  5074.3  912.32  5187.6  914.36  5357.6  920.06
  5463.6  924.74  5498.8  925.55  5520.3  924.57  5541.3  925.06  6100.3  946.04
#Mann= 3 ,-1 , 0
  4060.3     .05       0  4978.2    .033       0  4983.3     .05       0
Bank Sta=4978.2,4983.3
XS Rating Curve= 0 ,0
Exp/Cntr=0.3,0.1

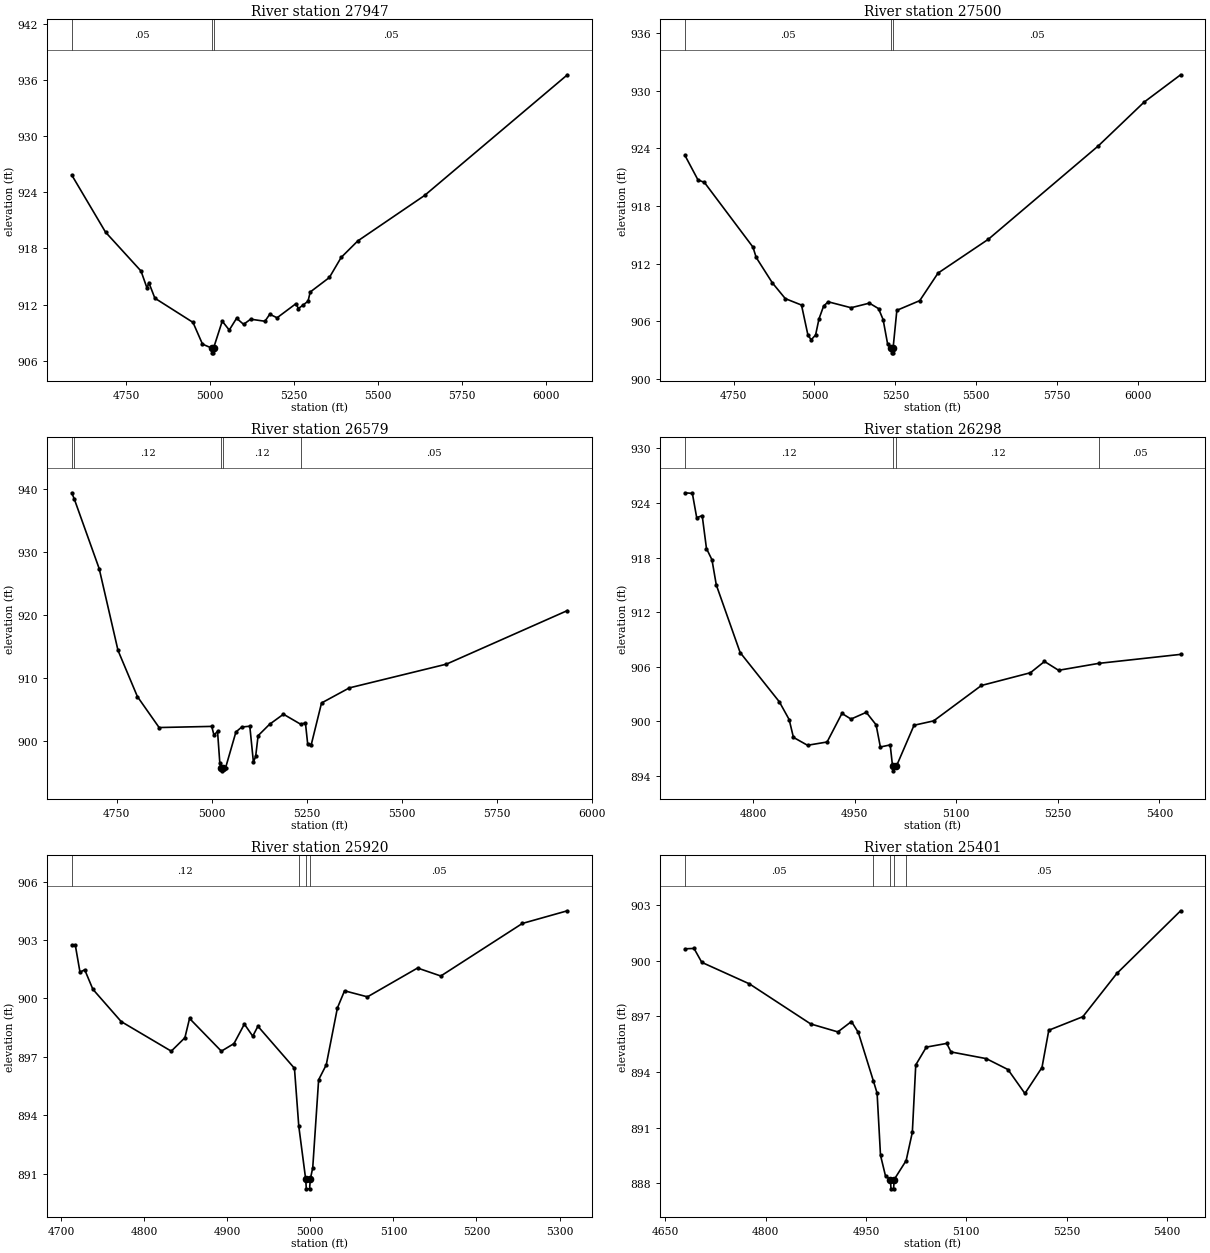
Type RM Length L Ch R = 1 ,27947   ,447,447,447
BEGIN DESCRIPTION:
MDE S 001 56.0
END DESCRIPTION:
XS GIS Cut Line= 3
      2290478.99        7186410.        2290079.        7186510.
      2289279.01      7187209.99
#Sta/Elev= 30
  4587.8  925.83  4688.3  919.74  4793.9  915.59    4812  913.75  4817.1  914.36
  4835.2  912.69  4948.6  910.11  4976.9  907.79  5004.7  907.36  5005.3  906.86
  5009.1  906.86  5009.8  907.36  5035.7  910.24  5056.6  909.29  5078.4  910.55
  5099.3   909.9  5120.2  910.45  5162.9  910.23  5177.1  910.98  5198.9   910.6
  5254.9   912.1  5262.5  911.59  5276.8  911.97    5291  912.37  5297.6  913.35
  5354.6   914.9  5389.7  917.04  5439.1   918.8  5637.9  923.65  6063.1  936.53
#Mann= 3 ,-1 , 0
  4587.8     .05       0  5004.7    .033       0  5009.8     .05       0
Bank Sta=5004.7,5009.8
XS Rating Curve= 0 ,0
Exp/Cntr=0.3,0.1

Type RM Length L Ch R = 1 ,27500   ,921,921,921
BEGIN DESCRIPTION:
MDE S 001 55.0
END DESCRIPTION:
XS GIS Cut Line= 3
        2290429.        7186110.        2290029.        7186110.
      2289228.98      7186910.02
#Sta/Elev= 30
    4600  923.27    4640  920.73    4660  920.46    4810  913.72    4820  912.64
    4870  909.99    4910  908.35    4960  907.68    4980  904.53    4990  904.06
  5003.5  904.56  5014.1  906.25  5028.3  907.57  5042.4  908.02  5113.1   907.4
  5169.7  907.88    5198  907.31  5212.1  906.17  5226.3  903.58  5237.8   903.2
  5238.5   902.7  5242.3   902.7    5243   903.2  5254.6  907.13  5325.3  908.14
  5381.8  911.01  5537.4  914.54  5876.8  924.26  6018.2  928.82  6131.4  931.68
#Mann= 3 ,-1 , 0
    4600     .05       0  5237.8    .033       0    5243     .05       0
Bank Sta=5237.8,5243
XS Rating Curve= 0 ,0
Exp/Cntr=0.3,0.1

Type RM Length L Ch R = 1 ,26579   ,281,281,281
BEGIN DESCRIPTION:
MDE S 001 54.0
END DESCRIPTION:
XS GIS Cut Line= 3
      2289828.99      7185260.02        2289629.        7185560.
      2289129.02      7186359.97
#Sta/Elev= 30
  4631.5  939.34  4638.4  938.31  4703.6  927.33  4753.2  914.36  4804.2  907.05
  4861.3  902.15  4999.7  902.33  5005.6  900.96    5015  901.54  5020.9  896.61
  5024.6  895.79  5025.5  895.29  5030.2  895.79  5036.3   895.8  5063.4  901.45
  5078.7  902.23  5099.9  902.36  5109.4  896.65  5115.3  897.58  5121.7  900.86
  5151.8  902.66  5188.4  904.26  5233.8  902.67  5246.2  902.88  5252.1  899.58
  5261.5  899.43  5288.6  906.04  5361.7  908.43    5617  912.19  5935.4  920.68
#Mann= 5 ,-1 , 0
  4631.5     .05       0  4638.4     .12       0  5024.6     .07       0
  5030.2     .12       0  5233.8     .05       0
Bank Sta=5024.6,5030.2
XS Rating Curve= 0 ,0
Exp/Cntr=0.3,0.1

Type RM Length L Ch R = 1 ,26298   ,378,378,378
BEGIN DESCRIPTION:
Mapping XS de035995
END DESCRIPTION:
XS GIS Cut Line= 2
      2289662.05      7185128.07      2289209.59      7185702.72
#Sta/Elev= 30
  4699.8  925.13  4710.7  925.06  4717.1  922.39  4725.2  922.62  4731.5     919
  4739.6  917.77    4746     915  4781.2  907.57    4839  902.16  4853.5  900.21
  4859.8  898.25  4880.6  897.38  4909.5  897.74  4931.4  900.88  4944.8  900.26
  4967.3     901  4981.8  899.63  4988.1  897.19  5002.6  897.42  5006.1  895.07
    5007  894.57  5011.7  895.07  5037.8  899.58  5066.7  900.06  5137.2  903.95
  5209.5  905.35  5230.3  906.59  5251.1  905.62  5310.2  906.38  5431.2  907.37
#Mann= 4 ,-1 , 0
  4699.8     .12       0  5006.1     .07       0  5011.7     .12       0
  5310.2     .05       0
Bank Sta=5006.1,5011.7
XS Rating Curve= 0 ,0
Exp/Cntr=0.3,0.1

Type RM Length L Ch R = 1 ,25920   ,519,519,519
BEGIN DESCRIPTION:
Mapping XS 617ef4df
END DESCRIPTION:
XS GIS Cut Line= 2
      2289299.35      7185007.55      2289019.52      7185534.57
#Sta/Elev= 30
  4712.8  902.75    4717  902.75  4722.7  901.35  4728.4  901.47  4738.2  900.47
  4772.3  898.81  4832.6  897.29    4849  897.98  4854.6  898.97  4892.9  897.29
  4908.1  897.68  4920.6  898.68  4930.7  898.06  4936.9  898.57  4980.9  896.41
  4986.1  893.44  4994.4  890.72  4995.2  890.22  4999.1  890.22    5000  890.72
  5002.9   891.3    5010  895.82  5019.2  896.59  5032.6  899.51  5041.2  900.39
  5068.8  900.08  5129.1  901.56  5157.1  901.15  5255.3  903.85  5309.5   904.5
#Mann= 4 ,-1 , 0
  4712.8     .12       0  4986.1     .05       0  4994.4    .033       0
    5000     .05       0
Bank Sta=4994.4,5000
XS Rating Curve= 0 ,0
Exp/Cntr=0.3,0.1

Type RM Length L Ch R = 1 ,25401   ,606,606,606
BEGIN DESCRIPTION:
Mapping XS 3f6afe8e
END DESCRIPTION:
XS GIS Cut Line= 2
      2288947.16      7184705.32      2288811.32      7185433.77
#Sta/Elev= 30
  4679.4  900.64  4692.9  900.66  4704.5  899.91  4775.7  898.75  4867.3  896.59
  4907.9  896.16  4928.3  896.72  4938.5  896.13  4961.2   893.5  4966.6  892.86
  4971.7  889.51  4979.2  888.39  4986.5   888.2  4987.4   887.7  4991.3   887.7
  4992.1   888.2    5010  889.22  5019.3  890.75  5024.4  894.38  5040.2  895.34
  5070.7  895.54  5077.1  895.08  5129.8  894.72  5162.3  894.13  5187.6  892.84
  5213.1  894.24  5223.3  896.25  5274.2  896.98    5325  899.31  5420.4  902.69
#Mann= 5 ,-1 , 0
  4679.4     .05       0  4961.2     .12       0  4986.5     .07       0
  4992.1     .12       0    5010     .05       0
Bank Sta=4986.5,4992.1
XS Rating Curve= 0 ,0
Exp/Cntr=0.3,0.1

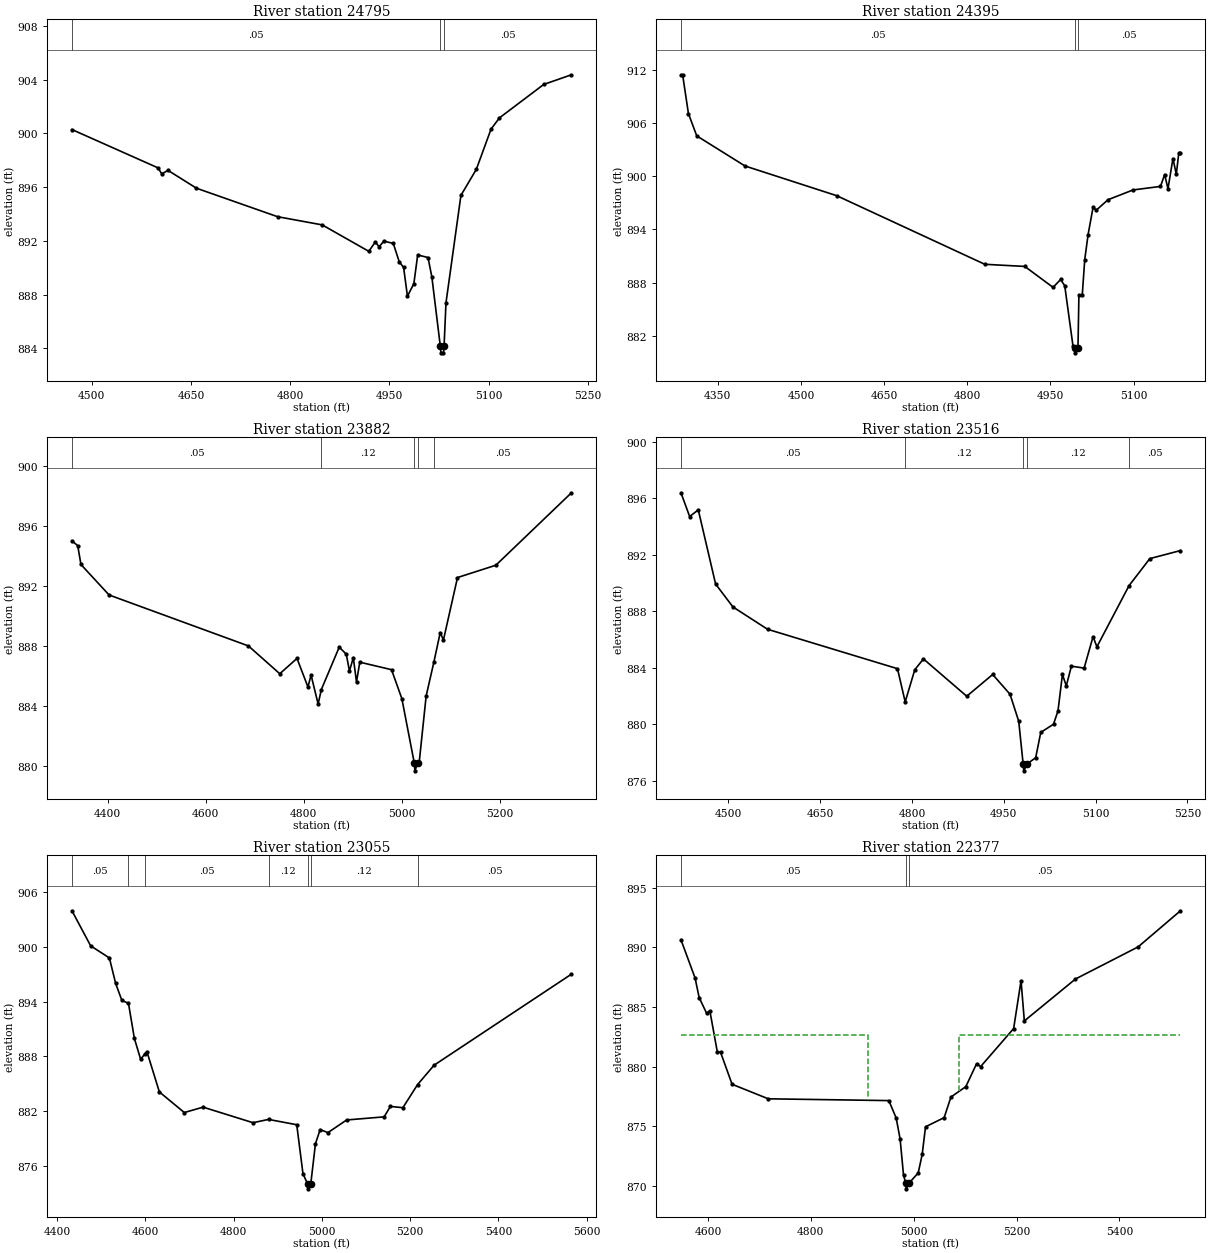
Type RM Length L Ch R = 1 ,24795   ,400,400,400
BEGIN DESCRIPTION:
Mapping XS 18393f50
END DESCRIPTION:
XS GIS Cut Line= 2
      2288791.87      7184545.31      2288404.01      7185193.42
#Sta/Elev= 30
    4470  900.29    4600  897.44  4605.8  896.99  4615.3  897.25  4658.3  895.92
  4780.9   893.8  4848.4  893.19  4918.9  891.22  4928.7  891.92  4934.5  891.56
  4941.6  891.98  4955.9  891.81  4964.9  890.44  4971.5  890.02  4977.3  887.88
    4987  888.81  4992.8  890.95  5008.4  890.76  5014.2  889.32    5027  884.16
  5027.9  883.66  5031.8  883.66  5032.7  884.16  5035.6  887.39  5058.2  895.39
  5081.5  897.33  5103.7  900.32  5116.4  901.16  5183.4  903.65  5225.3  904.37
#Mann= 3 ,-1 , 0
    4470     .05       0    5027    .033       0  5032.7     .05       0
Bank Sta=5027,5032.7
XS Rating Curve= 0 ,0
Exp/Cntr=0.3,0.1

Type RM Length L Ch R = 1 ,24395   ,513,513,513
BEGIN DESCRIPTION:
MDE S 001 49.0
END DESCRIPTION:
XS GIS Cut Line= 3
      2288828.96      7184360.02        2288229.        7184760.
      2288129.02      7184909.96
#Sta/Elev= 30
  4283.4  911.42  4286.4  911.42  4296.9  907.05  4311.9  904.54    4399  901.15
  4564.3  897.81  4831.7  890.08  4903.8  889.84  4954.9  887.48  4968.4  888.37
  4975.9  887.67  4990.9  880.84  4994.1  880.61    4995  880.11  4999.8  880.61
  5001.5   886.6  5007.5   886.6    5012  890.59    5018  893.41    5027  896.48
    5033  896.18    5054  897.35  5099.1  898.45  5148.7  898.85  5156.2  900.19
  5162.2  898.59  5171.2  901.99  5177.2  900.22  5181.7  902.58  5184.7  902.58
#Mann= 3 ,-1 , 0
  4283.4     .05       0  4994.1    .033       0  4999.8     .05       0
Bank Sta=4994.1,4999.8
XS Rating Curve= 0 ,0
Exp/Cntr=0.3,0.1

Type RM Length L Ch R = 1 ,23882   ,366,366,366
BEGIN DESCRIPTION:
Mapping XS a9806c62
END DESCRIPTION:
XS GIS Cut Line= 2
      2288412.26      7184146.75      2287625.67      7184793.44
#Sta/Elev= 30
  4327.5  894.99  4339.3  894.67  4345.8  893.42  4403.2  891.39  4687.3     888
  4751.2  886.15  4786.3  887.17  4808.6  885.27    4815  886.06  4829.4  884.13
  4835.8  885.09  4872.4  887.92  4886.8  887.45  4893.2  886.33  4901.1  887.22
  4907.6   885.6  4914.3  886.92    4979  886.42  5000.1  884.49  5025.5  880.19
  5026.6  879.69  5032.2  880.19  5035.3  880.22  5049.6  884.67  5065.3  886.92
  5078.3  888.89  5084.8  888.39  5113.5  892.55  5191.7  893.37  5345.8  898.19
#Mann= 5 ,-1 , 0
  4327.5     .05       0  4835.8     .12       0  5025.5     .07       0
  5032.2     .12       0  5065.3     .05       0
Bank Sta=5025.5,5032.2
XS Rating Curve= 0 ,0
Exp/Cntr=0.3,0.1

Type RM Length L Ch R = 1 ,23516   ,461,461,461
BEGIN DESCRIPTION:
MDE S 001 47.0
END DESCRIPTION:
XS GIS Cut Line= 3
      2288229.02      7183859.98        2287829.        7184260.
      2287629.01      7184409.99
#Sta/Elev= 30
  4422.8  896.38    4437   894.7  4451.1  895.17  4479.4  889.92  4507.7   888.3
  4564.2  886.72  4776.4  883.93    4789  881.58  4804.7  883.86  4818.8  884.62
  4889.5  881.98  4931.9  883.52  4960.2  882.12  4974.4  880.21  4981.6   877.2
  4982.7   876.7  4988.4   877.2  5002.1  877.63  5010.4  879.42  5031.2     880
  5038.5  880.94  5045.8  883.52  5052.1  882.71  5060.4  884.11  5081.2  883.97
  5095.8   886.2  5102.1  885.48  5154.6  889.81  5188.5  891.72  5238.5  892.29
#Mann= 5 ,-1 , 0
  4422.8     .05       0    4789     .12       0  4981.6     .07       0
  4988.4     .12       0  5154.6     .05       0
Bank Sta=4981.6,4988.4
XS Rating Curve= 0 ,0
Exp/Cntr=0.3,0.1

Type RM Length L Ch R = 1 ,23055   ,678,678,678
BEGIN DESCRIPTION:
MDE S 001 46.0
END DESCRIPTION:
XS GIS Cut Line= 3
      2288078.98      7183560.02        2287679.        7183960.
      2287279.03      7184359.97
#Sta/Elev= 30
  4434.1  903.91  4476.5  900.08  4518.9  898.76  4533.1  895.97  4547.2  894.12
  4562.1  893.81  4575.5  889.97  4589.6  887.71  4599.4  888.28  4603.8  888.54
  4632.1  884.13  4688.6  881.88  4731.1  882.47  4844.2  880.77  4879.3  881.13
  4943.2  880.55  4957.3  875.22    4968  874.05  4969.1  873.55  4974.9  874.05
  4985.6  878.47  4996.2  880.02  5013.9  879.69  5056.3  881.07  5141.2  881.41
  5155.3  882.55  5183.6  882.41    5217  884.94  5254.3  887.05  5565.4  896.99
#Mann= 7 ,-1 , 0
  4434.1     .05       0  4562.1     .12       0  4599.4     .05       0
  4879.3     .12       0    4968     .07       0  4974.9     .12       0
    5217     .05       0
Bank Sta=4968,4974.9
XS Rating Curve= 0 ,0
Exp/Cntr=0.3,0.1

Type RM Length L Ch R = 1 ,22377   ,199,199,199
BEGIN DESCRIPTION:
Mapping XS c526add8
END DESCRIPTION:
XS GIS Cut Line= 4
      2287718.46      7183350.25      2287441.68      7183573.44
      2287342.46      7183689.33      2287055.55       7184052.7
#Sta/Elev= 30
  4547.5  890.65    4575  887.43  4582.9  885.79  4597.3  884.48  4603.7  884.68
  4618.1  881.25  4624.5   881.2  4646.9  878.51  4717.3  877.29  4951.7  877.14
    4966  875.67  4973.6  873.91  4980.2  870.89  4984.4  870.23  4985.5  869.73
  4991.4  870.23  5008.8  871.07  5016.5  872.62    5023  874.94  5059.2  875.71
  5072.4  877.44  5101.3  878.31  5122.1  880.22  5130.2     880  5194.3  883.19
  5208.7  887.21  5215.1  883.83  5314.5  887.35  5436.4  890.05  5518.6  893.08
#Mann= 3 ,-1 , 0
  4547.5     .05       0  4984.4    .033       0  4991.4     .05       0
#XS Ineff= 2 , 0
       0    4912  882.63    5088       0  882.63
Permanent Ineff=
       F       F
Bank Sta=4984.4,4991.4
XS Rating Curve= 0 ,0
Exp/Cntr=0.3,0.1

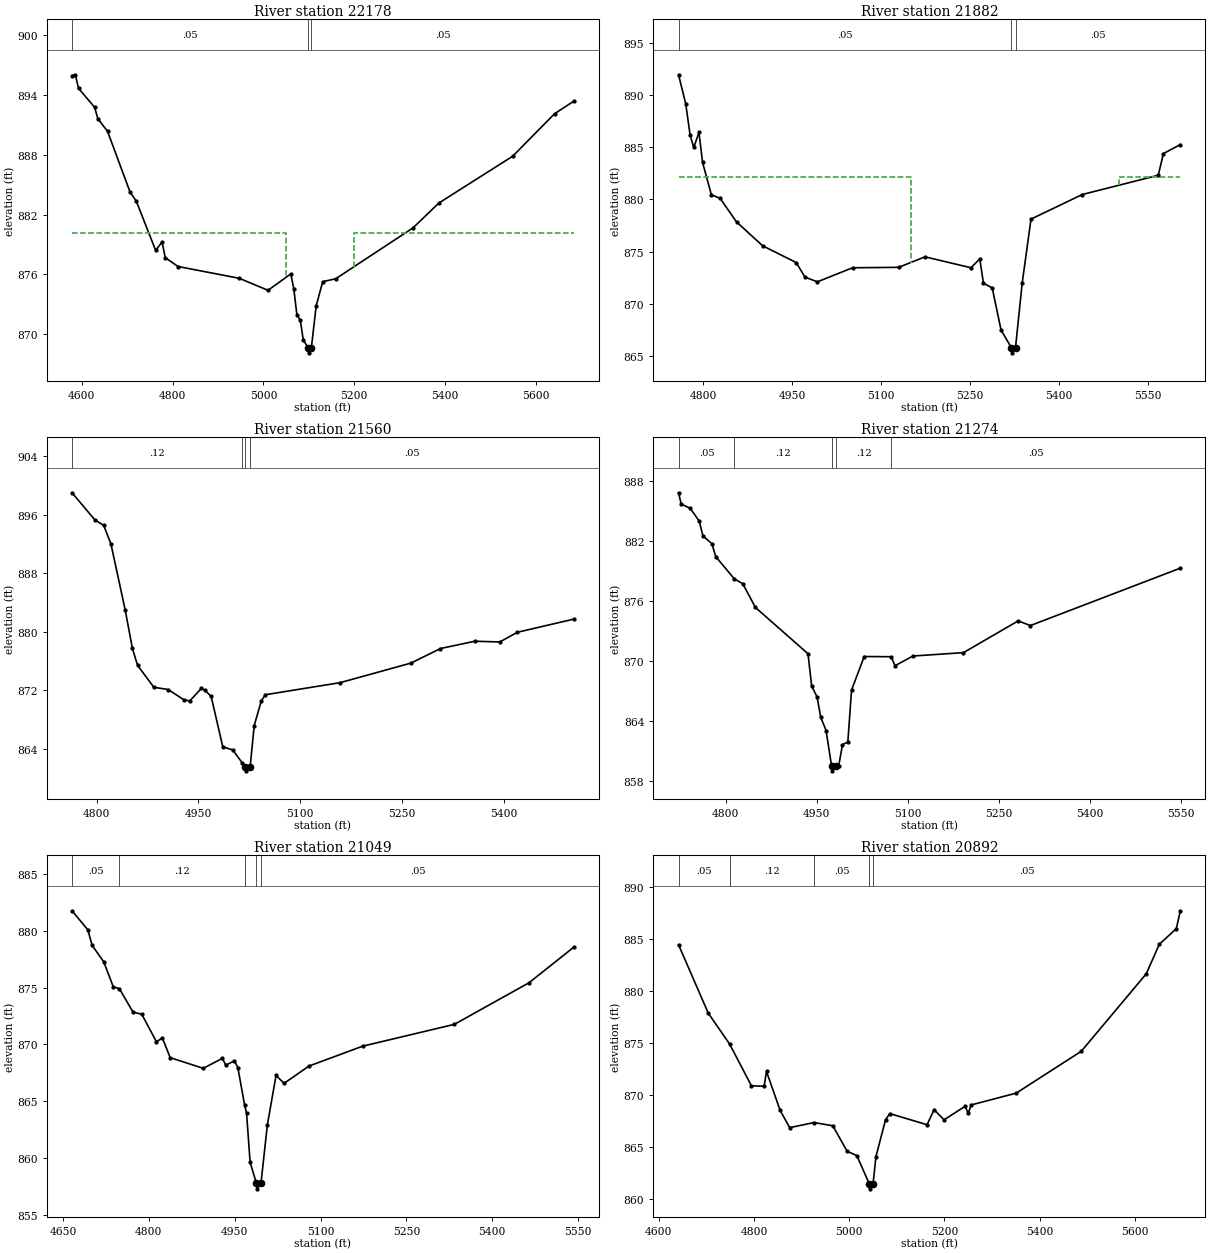
Type RM Length L Ch R = 1 ,22178   ,296,296,296
BEGIN DESCRIPTION:
Mapping XS 2360f097
END DESCRIPTION:
XS GIS Cut Line= 4
      2287672.29      7183173.17      2287355.24      7183499.85
      2287183.26      7183700.74      2286932.93      7183993.14
#Sta/Elev= 30
  4578.8  895.97    4586  896.05    4593  894.69  4628.5  892.78  4635.4  891.65
  4656.8  890.38  4706.2   884.3  4720.3  883.34  4762.8  878.41  4776.9  879.26
  4783.9  877.68  4812.2  876.79  4946.7  875.61  5010.2   874.4  5060.3  876.05
  5066.9  874.55  5073.7  871.94  5081.2   871.4  5087.8  869.41  5098.5  868.62
  5099.6  868.12  5105.5  868.62  5116.3  872.87  5130.6  875.27  5159.1  875.56
  5329.3  880.67  5386.3  883.17  5548.8  887.87    5641  892.14  5683.4   893.4
#Mann= 3 ,-1 , 0
  4578.8     .05       0  5098.5    .033       0  5105.5     .05       0
#XS Ineff= 2 , 0
       0    5050   880.2    5200       0   880.2
Permanent Ineff=
       F       F
Bank Sta=5098.5,5105.5
XS Rating Curve= 0 ,0
Exp/Cntr=0.3,0.1

Type RM Length L Ch R = 1 ,21882   ,322,322,322
BEGIN DESCRIPTION:
Mapping XS 2f890dae
END DESCRIPTION:
XS GIS Cut Line= 2
      2287386.04      7183030.07      2286899.72      7183721.34
#Sta/Elev= 30
  4758.9  891.97    4771  889.19  4778.5  886.14  4784.6  884.99  4793.3  886.43
  4799.4  883.55  4814.2  880.45    4829   880.1  4856.6  877.84  4900.5  875.55
  4957.1  873.94  4971.9  872.54  4992.8  872.09    5052  873.44  5129.6  873.48
    5174  874.49  5251.5  873.44  5266.3  874.29  5272.5  871.96  5287.3   871.5
  5302.1  867.47  5319.4  865.77  5320.5  865.27  5326.5  865.77  5337.8     872
  5352.6  878.11  5438.8  880.47  5566.9  882.32  5575.6   884.4  5604.1  885.27
#Mann= 3 ,-1 , 0
  4758.9     .05       0  5319.4    .033       0  5326.5     .05       0
#XS Ineff= 2 , 0
       0    5150  882.12    5500       0  882.12
Permanent Ineff=
       F       F
Bank Sta=5319.4,5326.5
XS Rating Curve= 0 ,0
Exp/Cntr=0.3,0.1

Type RM Length L Ch R = 1 ,21560   ,286,286,286
BEGIN DESCRIPTION:
Mapping XS afab325f
END DESCRIPTION:
XS GIS Cut Line= 2
      2287055.73      7182935.87      2286818.17      7183636.17
#Sta/Elev= 30
  4763.7  899.03  4797.3  895.32  4810.3  894.57  4820.9  892.06    4842  882.99
  4852.5  877.78  4860.2  875.41  4884.2  872.41  4905.3   872.1  4928.2  870.71
    4937  870.53  4954.4  872.27  4959.6  871.99  4968.7  871.15  4985.8  864.26
  5000.4  863.83  5014.5  862.06  5018.9  861.47    5020  860.97  5026.1  861.47
  5032.1  867.16  5042.6  870.55  5048.6  871.39  5158.8  873.04  5263.1  875.72
  5306.6  877.71  5357.3  878.71    5394  878.61  5420.1  879.94  5503.2  881.74
#Mann= 4 ,-1 , 0
  4763.7     .12       0  5014.5     .05       0  5018.9     .07       0
  5026.1     .05       0
Bank Sta=5018.9,5026.1
XS Rating Curve= 0 ,0
Exp/Cntr=0.3,0.1

Type RM Length L Ch R = 1 ,21274   ,225,225,225
BEGIN DESCRIPTION:
Mapping XS 9891ddf5
END DESCRIPTION:
XS GIS Cut Line= 3
      2286915.36      7182809.74      2286694.22      7183129.66
      2286674.69      7183566.71
#Sta/Elev= 30
  4722.2  886.86  4726.6  885.73  4741.5   885.3  4756.3  884.02  4762.4  882.54
  4777.3  881.75  4783.4  880.47    4814  878.24    4828  877.75  4848.9  875.37
  4935.4  870.74  4941.5   867.5  4950.3  866.42  4956.4  864.38  4965.2  863.04
  4974.2  859.51  4975.4  859.01  4981.4  859.51  4986.1  859.54  4992.2  861.64
    5001  861.89  5007.1  867.09    5028  870.46  5072.3  870.44  5078.7  869.54
  5108.3  870.51  5191.5  870.85  5281.6  874.03  5301.6  873.56  5548.6  879.31
#Mann= 5 ,-1 , 0
  4722.2     .05       0    4814     .12       0  4974.2     .07       0
  4981.4     .12       0  5072.3     .05       0
Bank Sta=4974.2,4981.4
XS Rating Curve= 0 ,0
Exp/Cntr=0.3,0.1

Type RM Length L Ch R = 1 ,21049   ,157,157,157
BEGIN DESCRIPTION:
Mapping XS 489bc74d
END DESCRIPTION:
XS GIS Cut Line= 3
      2286883.22      7182749.73      2286649.56      7182799.35
      2286304.62      7183335.62
#Sta/Elev= 30
    4666  881.77  4693.6  880.09    4701  878.73  4721.4  877.27  4738.1  875.06
  4748.6  874.92  4772.5  872.85  4787.8  872.66  4813.4  870.23  4823.7  870.58
  4837.4  868.84  4895.2   867.9  4928.6  868.78  4934.5  868.18  4949.7  868.56
  4955.6  867.96  4967.5  864.63  4970.8  863.95    4977  859.63  4987.9  857.79
  4989.1  857.29    4996  857.79  5007.1  862.91  5022.3  867.27  5036.4  866.58
  5079.8   868.1  5173.6  869.85  5333.7  871.77  5464.1  875.43  5542.5  878.57
#Mann= 5 ,-1 , 0
    4666     .05       0  4748.6     .12       0  4967.5     .05       0
  4987.9    .033       0    4996     .05       0
Bank Sta=4987.9,4996
XS Rating Curve= 0 ,0
Exp/Cntr=0.3,0.1

Type RM Length L Ch R = 1 ,20892   ,563,563,563
BEGIN DESCRIPTION:
Mapping XS 7142fbfb
END DESCRIPTION:
XS GIS Cut Line= 3
       2286901.1      7182705.75      2286456.05      7182753.28
      2286106.79      7183248.54
#Sta/Elev= 30
  4641.8  884.46  4704.2  877.88  4749.1   874.9  4794.8  870.89  4821.5  870.84
  4826.5  872.27  4855.1  868.52  4875.2  866.86  4926.3  867.35  4965.7  867.04
  4995.9  864.58  5016.2  864.17  5042.1  861.47  5043.3  860.97  5050.3  861.47
  5056.2  864.05  5076.4  867.62  5085.4  868.21  5163.6  867.14  5178.4  868.59
  5199.3  867.61  5243.7  868.92  5249.8  868.24  5256.7  869.05  5350.8  870.18
  5487.5  874.21  5623.8  881.66  5651.3  884.51    5687  886.01  5695.4  887.73
#Mann= 5 ,-1 , 0
  4641.8     .05       0  4749.1     .12       0  4926.3     .05       0
  5042.1    .033       0  5050.3     .05       0
Bank Sta=5042.1,5050.3
XS Rating Curve= 0 ,0
Exp/Cntr=0.3,0.1