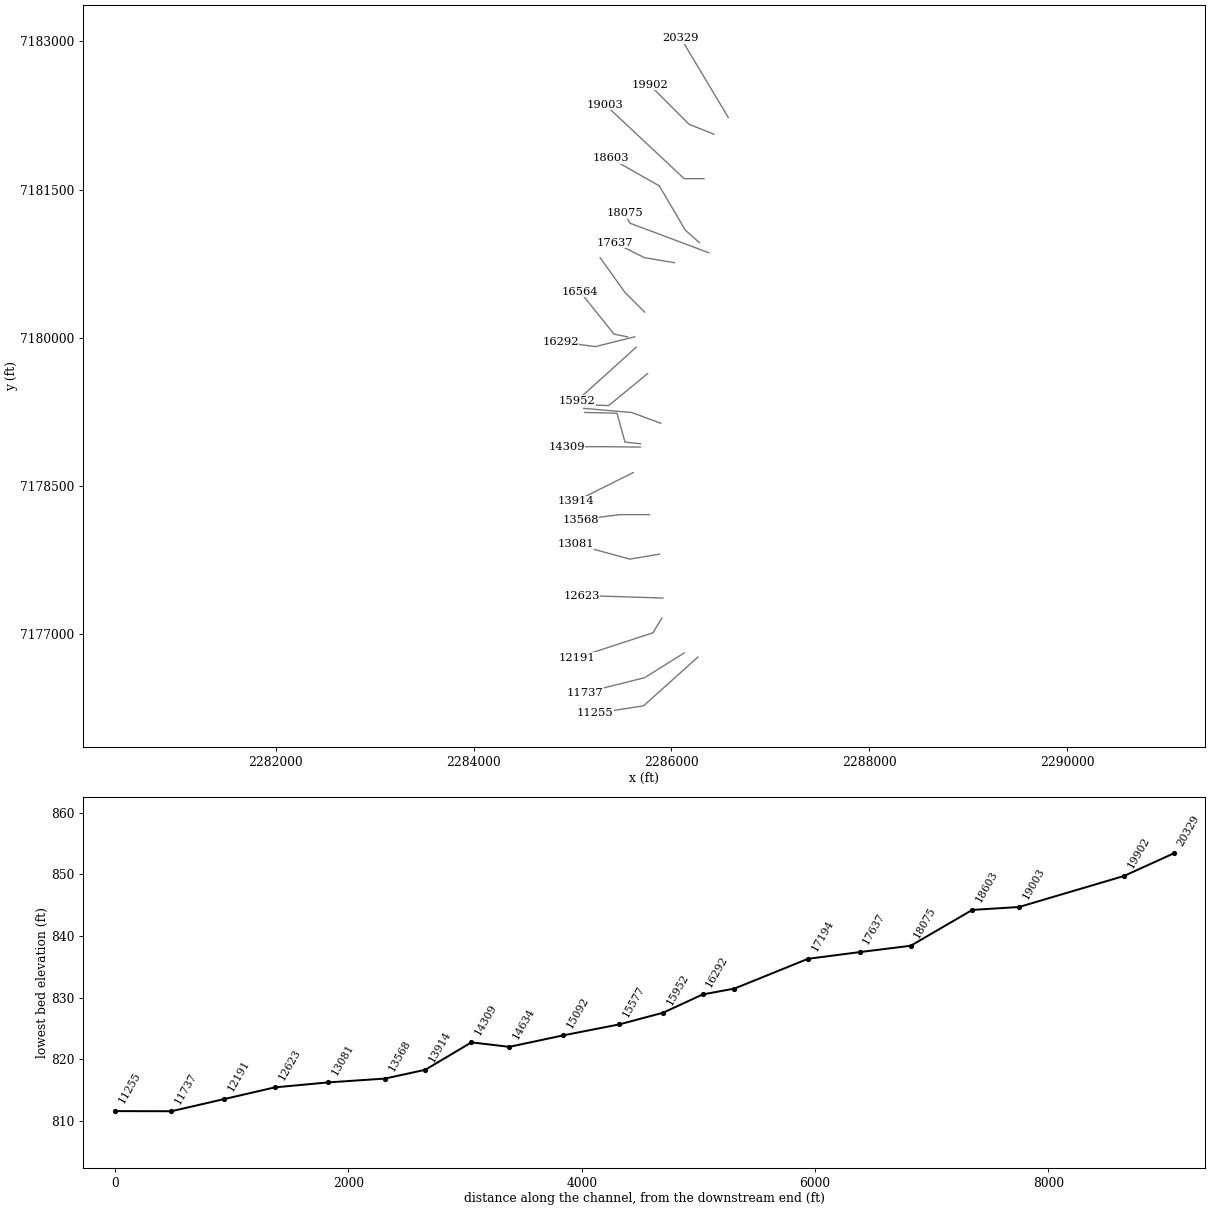
HEC-RAS study MDE S 001.prj: MDE S 001 Base Level Engineering

--- MDE S 001.g01 (geometry) --- (continued)

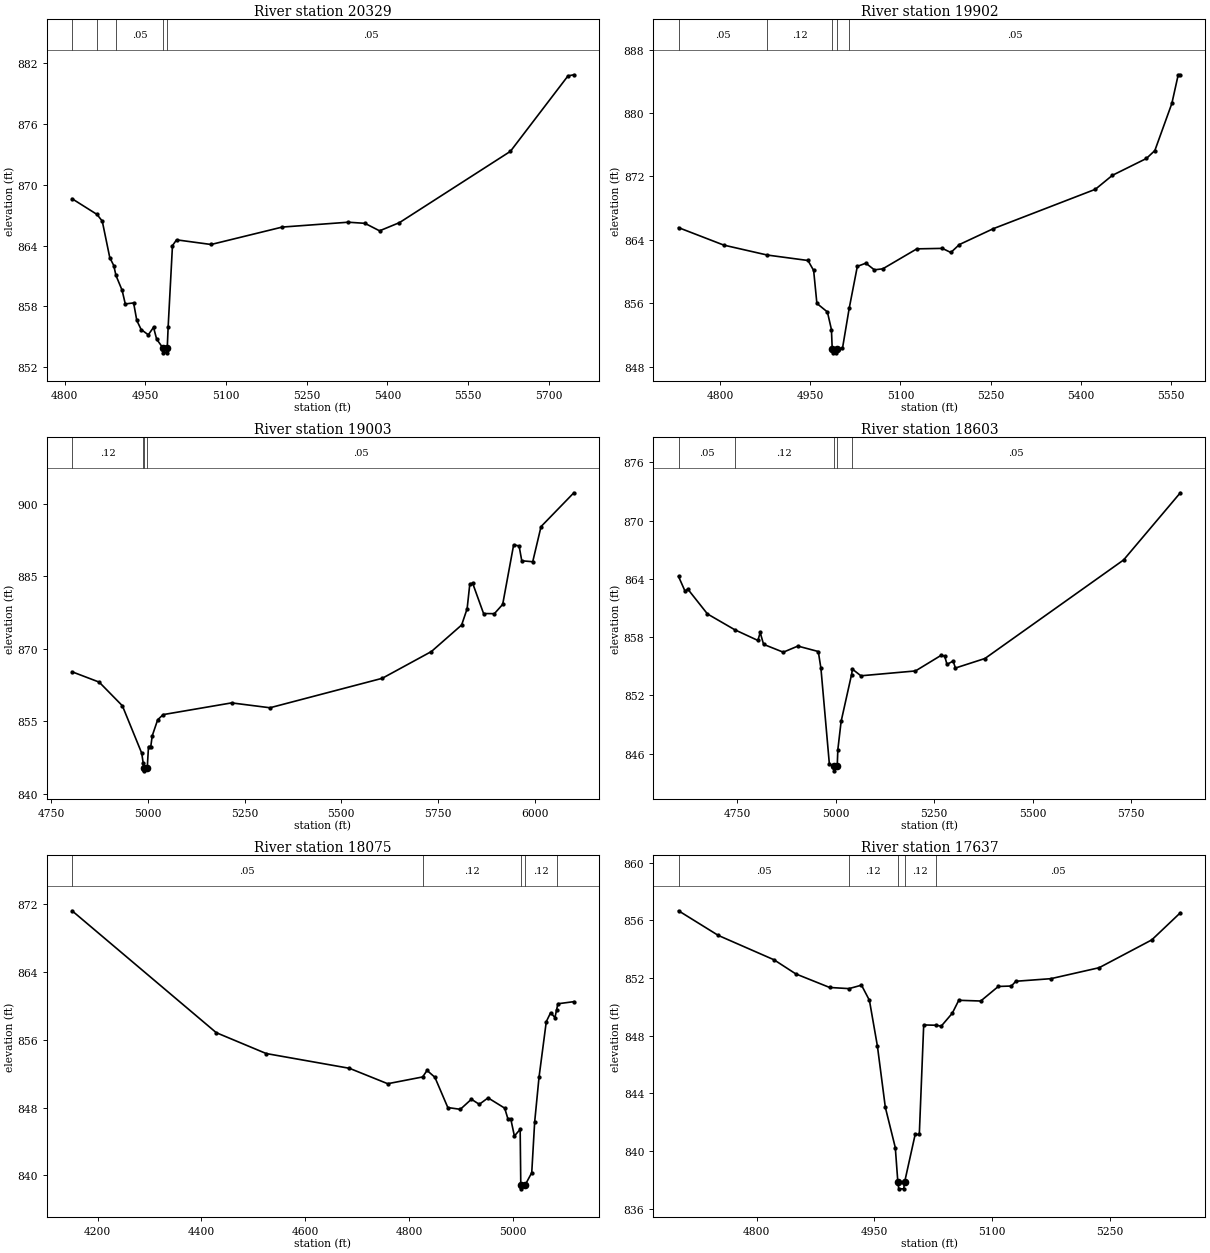
Type RM Length L Ch R = 1 ,20329   ,427,427,427
BEGIN DESCRIPTION:
Mapping XS 989d67d4
END DESCRIPTION:
XS GIS Cut Line= 2
      2286574.55      7182229.82       2286095.9      7183030.22
#Sta/Elev= 30
    4814  868.62  4860.3  867.07  4870.1  866.41  4884.1   862.8  4891.5  862.02
  4895.6  861.04    4907  859.58  4912.9  858.23  4928.4  858.33  4934.3   856.6
  4942.4   855.7  4955.7  855.18  4965.4  855.92  4971.2  854.75  4982.6   853.9
  4983.9   853.4  4989.7   853.4  4990.9   853.9  4992.6  855.99  5000.6  863.99
  5008.2  864.56  5072.4   864.1  5204.6  865.82  5327.2   866.3  5358.3  866.19
  5385.5  865.45  5422.5  866.26  5628.7   873.3  5735.7  880.75  5746.6  880.86
#Mann= 5 ,-1 , 0
    4814     .05       0  4860.3     .12       0  4895.6     .05       0
  4982.6    .033       0  4990.9     .05       0
Bank Sta=4982.6,4990.9
XS Rating Curve= 0 ,0
Exp/Cntr=0.3,0.1

Type RM Length L Ch R = 1 ,19902   ,899,899,899
BEGIN DESCRIPTION:
MDE S 001 39.0
END DESCRIPTION:
XS GIS Cut Line= 3
      2286428.98      7182060.01        2286179.        7182160.
      2285779.02      7182559.98
#Sta/Elev= 30
  4730.7  865.54  4806.1  863.33  4878.2  862.08  4946.1  861.39  4955.5  860.13
  4960.9  855.97  4978.4  854.89  4985.1  852.67  4986.4  850.23  4987.6  849.73
  4993.5  849.73  4994.7  850.23  5003.5  850.31  5014.6  855.33  5028.2  860.65
  5042.4  861.05  5056.5  860.21  5070.6  860.34  5127.2  862.86  5169.6  862.92
  5183.8   862.4  5197.9   863.4  5254.5  865.41  5424.2  870.38  5452.5  872.14
  5509.1  874.27  5523.2  875.27  5551.5  881.22  5562.1  884.84  5565.6  884.84
#Mann= 5 ,-1 , 0
  4730.7     .05       0  4878.2     .12       0  4986.4     .07       0
  4994.7     .12       0  5014.6     .05       0
Bank Sta=4986.4,4994.7
XS Rating Curve= 0 ,0
Exp/Cntr=0.3,0.1

Type RM Length L Ch R = 1 ,19003   ,400,400,400
BEGIN DESCRIPTION:
MDE S 001 38.0
END DESCRIPTION:
XS GIS Cut Line= 3
      2286328.97        7181610.        2286129.        7181610.
      2285328.97      7182360.03
#Sta/Elev= 30
  4804.3  865.24  4874.3   863.1  4934.3  858.19  4984.3  848.36  4988.1  846.29
  4990.1   845.2  4991.3   844.7  4998.5   845.2  5001.8  849.74  5007.7  849.74
  5011.4  851.95  5025.5  855.29  5039.7  856.36  5216.5  858.79  5315.7  857.78
  5605.8  863.89  5732.8  869.44  5810.9  874.94  5825.1  878.31    5832  883.42
  5839.3  883.62  5867.6  877.32  5895.5  877.29    5917  879.22  5945.3  891.56
  5959.4  891.34  5966.3  888.26  5994.6  888.06  6016.1  895.35  6100.9  902.36
#Mann= 4 ,-1 , 0
  4804.3     .12       0  4988.1     .05       0  4990.1    .033       0
  4998.5     .05       0
Bank Sta=4990.1,4998.5
XS Rating Curve= 0 ,0
Exp/Cntr=0.3,0.1

Type RM Length L Ch R = 1 ,18603   ,528,528,528
BEGIN DESCRIPTION:
Mapping XS 5335cca4
END DESCRIPTION:
XS GIS Cut Line= 4
      2286284.18      7180962.01      2286141.28      7181087.85
      2285877.48      7181537.18      2285386.94      7181815.21
#Sta/Elev= 30
  4600.4  864.25    4617  862.73  4623.7  862.96  4673.9  860.39  4743.4  858.76
  4802.1  857.66  4807.9  858.48  4816.5  857.26  4866.6  856.45  4903.7  857.08
  4955.6  856.52  4962.3  854.79  4983.8   844.9  4995.2  844.73  4996.5  844.23
  5003.7  844.73  5005.3  846.42  5013.6  849.32  5040.1  854.14  5042.4   854.7
  5063.9  854.02  5202.6  854.52  5268.7  856.15  5276.9  856.03  5282.7  855.19
  5298.3  855.54  5304.1  854.82  5379.1   855.8  5731.5  865.95  5875.7  872.87
#Mann= 5 ,-1 , 0
  4600.4     .05       0  4743.4     .12       0  4995.2     .07       0
  5003.7     .12       0  5040.1     .05       0
Bank Sta=4995.2,5003.7
XS Rating Curve= 0 ,0
Exp/Cntr=0.3,0.1

Type RM Length L Ch R = 1 ,18075   ,438,438,438
BEGIN DESCRIPTION:
MDE S 001 36.0
END DESCRIPTION:
XS GIS Cut Line= 3
      2286378.98      7180860.01        2285579.        7181160.
      2285528.99      7181260.02
#Sta/Elev= 30
  4150.8  871.21  4428.5  856.83  4524.6  854.37  4684.8  852.63  4758.6  850.81
  4825.9  851.61  4834.3  852.38  4849.4  851.57  4874.3     848  4898.4  847.79
  4919.7  848.98  4934.9  848.38  4951.8  849.14  4983.8  847.93    4990  846.67
  4995.4  846.69  5002.5  844.64  5013.6  845.43  5014.8  838.91  5016.1  838.41
  5023.6  838.91  5035.9  840.31  5041.5  846.27  5049.9  851.56  5063.9  858.13
  5072.3  859.19  5080.6  858.61  5083.8  859.54  5086.2  860.24    5117  860.49
#Mann= 5 ,-1 , 0
  4150.8     .05       0  4825.9     .12       0  5014.8     .07       0
  5023.6     .12       0  5083.8     .05       0
Bank Sta=5014.8,5023.6
XS Rating Curve= 0 ,0
Exp/Cntr=0.3,0.1

Type RM Length L Ch R = 1 ,17637   ,443,443,443
BEGIN DESCRIPTION:
MDE S 001 35.0
END DESCRIPTION:
XS GIS Cut Line= 3
        2286029.        7180760.        2285729.        7180810.
      2285428.96      7180960.02
#Sta/Elev= 30
  4700.3  856.67    4751  854.96    4822  853.27  4849.8  852.29  4892.9  851.35
  4917.6  851.27  4933.5  851.51  4943.6  850.46  4953.8  847.28  4963.9  843.03
  4976.6  840.24  4979.8  837.88    4981  837.38  4987.3  837.38  4988.6  837.88
  5001.9  841.15  5007.2  841.15  5012.8  848.75  5027.9  848.73  5035.2  848.67
  5049.2  849.56  5057.5  850.46  5085.5  850.41  5107.9  851.42  5124.6  851.45
  5130.2  851.78  5174.9  851.96  5236.4  852.72  5303.5  854.65  5339.9  856.53
#Mann= 5 ,-1 , 0
  4700.3     .05       0  4917.6     .12       0  4979.8     .07       0
  4988.6     .12       0  5027.9     .05       0
Bank Sta=4979.8,4988.6
XS Rating Curve= 0 ,0
Exp/Cntr=0.3,0.1

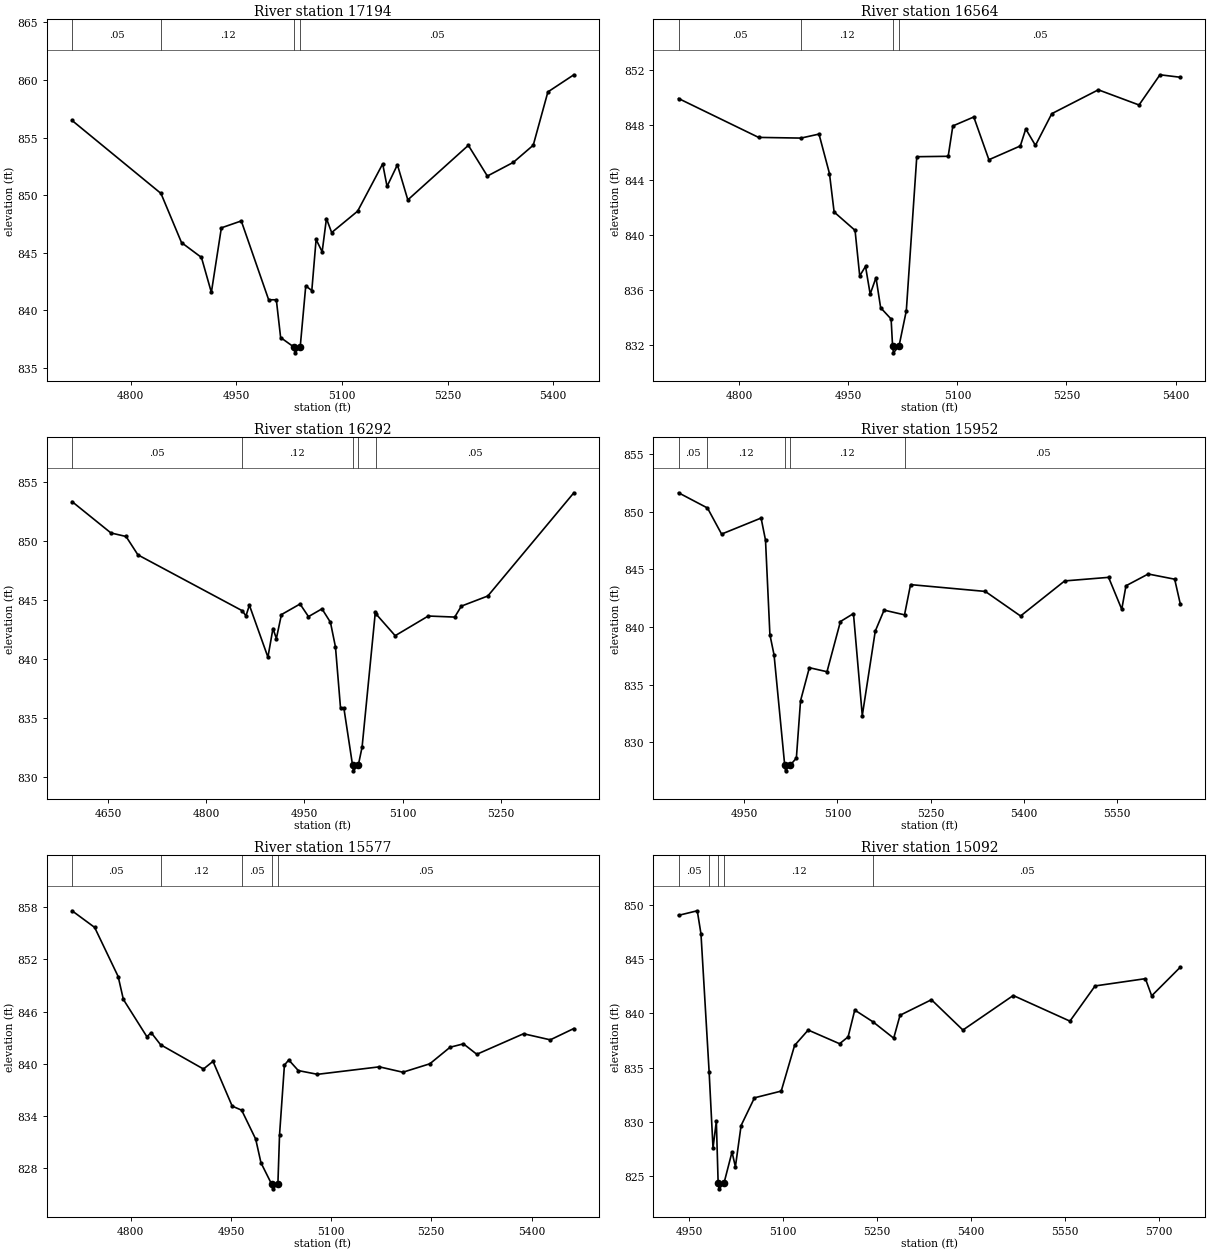
Type RM Length L Ch R = 1 ,17194   ,630,630,630
BEGIN DESCRIPTION:
MDE S 001 34.0
END DESCRIPTION:
XS GIS Cut Line= 3
      2285728.97      7180260.03        2285529.        7180460.
      2285279.01      7180809.99
#Sta/Elev= 30
  4716.5  856.48  4842.8  850.14    4872  845.87  4900.3  844.58  4914.4  841.54
  4928.6  847.15  4956.9  847.75  4995.8   840.9  5006.7   840.9  5012.8  837.62
  5031.7  836.79    5033  836.29  5040.6  836.79  5048.5  842.11  5057.1   841.7
  5063.2  846.14  5071.8  845.07  5077.9  847.96  5085.3  846.74  5122.2   848.6
  5157.8  852.71    5164  850.75  5178.7  852.63  5193.5  849.58  5279.5  854.32
  5306.5  851.65  5343.4  852.84  5371.7  854.33  5392.5  858.96  5429.4  860.45
#Mann= 4 ,-1 , 0
  4716.5     .05       0  4842.8     .12       0  5031.7     .07       0
  5040.6     .05       0
Bank Sta=5031.7,5040.6
XS Rating Curve= 0 ,0
Exp/Cntr=0.3,0.1

Type RM Length L Ch R = 1 ,16564   ,272,272,272
BEGIN DESCRIPTION:
Mapping XS 5109e390
END DESCRIPTION:
XS GIS Cut Line= 3
      2285556.99      7180009.36      2285419.37      7180036.57
      2285075.86        7180466.
#Sta/Elev= 30
  4716.4   849.9  4826.5  847.08  4884.8  847.03  4909.6  847.32    4924  844.46
  4930.4  841.67  4959.2  840.34  4965.6  837.04  4973.6  837.73    4980  835.72
    4988  836.91  4994.4  834.73  5008.8  833.91  5010.8  831.96    5012  831.46
  5019.7  831.96  5029.7  834.51  5044.1  845.68  5087.3  845.71  5093.7  847.91
  5122.5  848.56  5143.3  845.46  5186.5  846.46    5194  847.69  5207.3   846.5
  5229.8   848.8  5293.8  850.53  5349.8  849.43  5378.6  851.62  5406.6  851.44
#Mann= 4 ,-1 , 0
  4716.4     .05       0  4884.8     .12       0  5010.8     .07       0
  5019.7     .05       0
Bank Sta=5010.8,5019.7
XS Rating Curve= 0 ,0
Exp/Cntr=0.3,0.1

Type RM Length L Ch R = 1 ,16292   ,340,340,340
BEGIN DESCRIPTION:
MDE S 001 33.0
END DESCRIPTION:
XS GIS Cut Line= 3
      2285628.98        7180010.        2285229.        7179910.
      2284879.05      7179959.99
#Sta/Elev= 30
  4595.3  853.36  4654.6   850.7  4677.7   850.4  4695.8  848.84    4855   844.1
  4860.7  843.66  4865.9  844.57  4894.2  840.16  4901.9  842.59  4907.1  841.74
  4914.8  843.77  4943.2  844.67  4956.1   843.6  4976.7  844.26  4989.6  843.12
  4997.3  841.02    5005  835.84  5010.1  835.84  5023.3  831.01  5024.6  830.51
  5032.2  831.01  5037.9  832.52  5058.1  843.97  5059.4  843.81  5088.4  841.98
  5138.9  843.65  5179.3  843.56  5189.4  844.49  5229.8  845.35  5361.1  854.11
#Mann= 5 ,-1 , 0
  4595.3     .05       0    4855     .12       0  5023.3     .07       0
  5032.2     .12       0  5059.4     .05       0
Bank Sta=5023.3,5032.2
XS Rating Curve= 0 ,0
Exp/Cntr=0.3,0.1

Type RM Length L Ch R = 1 ,15952   ,375,375,375
BEGIN DESCRIPTION:
Mapping XS 450b4ea5
END DESCRIPTION:
XS GIS Cut Line= 3
      2285642.98       7179903.7       2285223.9      7179525.56
      2285043.23      7179362.55
#Sta/Elev= 30
  4844.1  851.64  4890.7  850.32  4913.4  848.06    4977  849.45  4984.1  847.54
  4991.2  839.34  4997.9  837.58    5015  828.04  5016.3  827.54  5024.1  828.04
  5033.8  828.65  5040.5  833.61  5054.7  836.48  5083.1  836.13  5104.7  840.48
  5125.7  841.17  5139.9  832.33  5160.8  839.65    5175  841.47  5207.9  841.06
  5217.6  843.68  5337.9  843.09  5394.7  840.96  5465.7     844  5536.4  844.31
  5557.6  841.54  5564.4  843.58  5600.2   844.6  5642.8  844.15  5651.9  841.99
#Mann= 5 ,-1 , 0
  4844.1     .05       0  4890.7     .12       0    5015     .07       0
  5024.1     .12       0  5207.9     .05       0
Bank Sta=5015,5024.1
XS Rating Curve= 0 ,0
Exp/Cntr=0.3,0.1

Type RM Length L Ch R = 1 ,15577   ,485,485,485
BEGIN DESCRIPTION:
Mapping XS 7e055308
END DESCRIPTION:
XS GIS Cut Line= 3
        2285759.      7179637.37      2285365.48      7179313.98
      2285123.77      7179321.97
#Sta/Elev= 30
  4712.2  857.58    4746  855.67  4781.2  850.03    4789   847.4  4824.2  843.12
  4830.7  843.58  4844.7   842.2  4908.9  839.41  4923.2  840.29  4951.9  835.15
  4966.1  834.68  4987.1  831.36    4995  828.64  5011.2  826.15  5012.5  825.65
  5020.3  826.15  5022.8  831.86  5030.1  839.86  5036.6  840.45  5050.9  839.23
  5079.6   838.8  5172.2  839.66  5207.4  839.04  5247.8  840.01  5278.1  841.91
  5298.1   842.3  5318.1   841.1  5388.1  843.46  5428.1  842.76  5463.4  844.06
#Mann= 5 ,-1 , 0
  4712.2     .05       0  4844.7     .12       0  4966.1     .05       0
  5011.2    .035       0  5020.3     .05       0
Bank Sta=5011.2,5020.3
XS Rating Curve= 0 ,0
Exp/Cntr=0.3,0.1

Type RM Length L Ch R = 1 ,15092   ,458,458,458
BEGIN DESCRIPTION:
Mapping XS c240e781
END DESCRIPTION:
XS GIS Cut Line= 3
      2285892.57      7179134.77      2285599.39      7179243.56
      2285113.51      7179285.46
#Sta/Elev= 30
  4933.1  849.03    4963  849.45  4968.9  847.32  4981.9  834.62  4988.1  827.61
  4993.4  830.08  4996.3  824.35  4997.7  823.85  5005.5  824.35  5018.4  827.24
  5023.8  825.88  5032.9  829.68  5054.2  832.23  5096.9  832.85  5118.2  837.05
  5139.9  838.47    5190  837.21  5203.6  837.84  5214.2  840.31  5243.4  839.22
  5276.3  837.72  5286.4  839.83  5336.5  841.26  5386.7  838.47    5467  841.65
  5557.4  839.29  5597.5  842.53  5677.8   843.2  5687.8  841.62  5733.5  844.26
#Mann= 5 ,-1 , 0
  4933.1     .05       0  4981.9     .12       0  4996.3     .07       0
  5005.5     .12       0  5243.4     .05       0
Bank Sta=4996.3,5005.5
XS Rating Curve= 0 ,0
Exp/Cntr=0.3,0.1

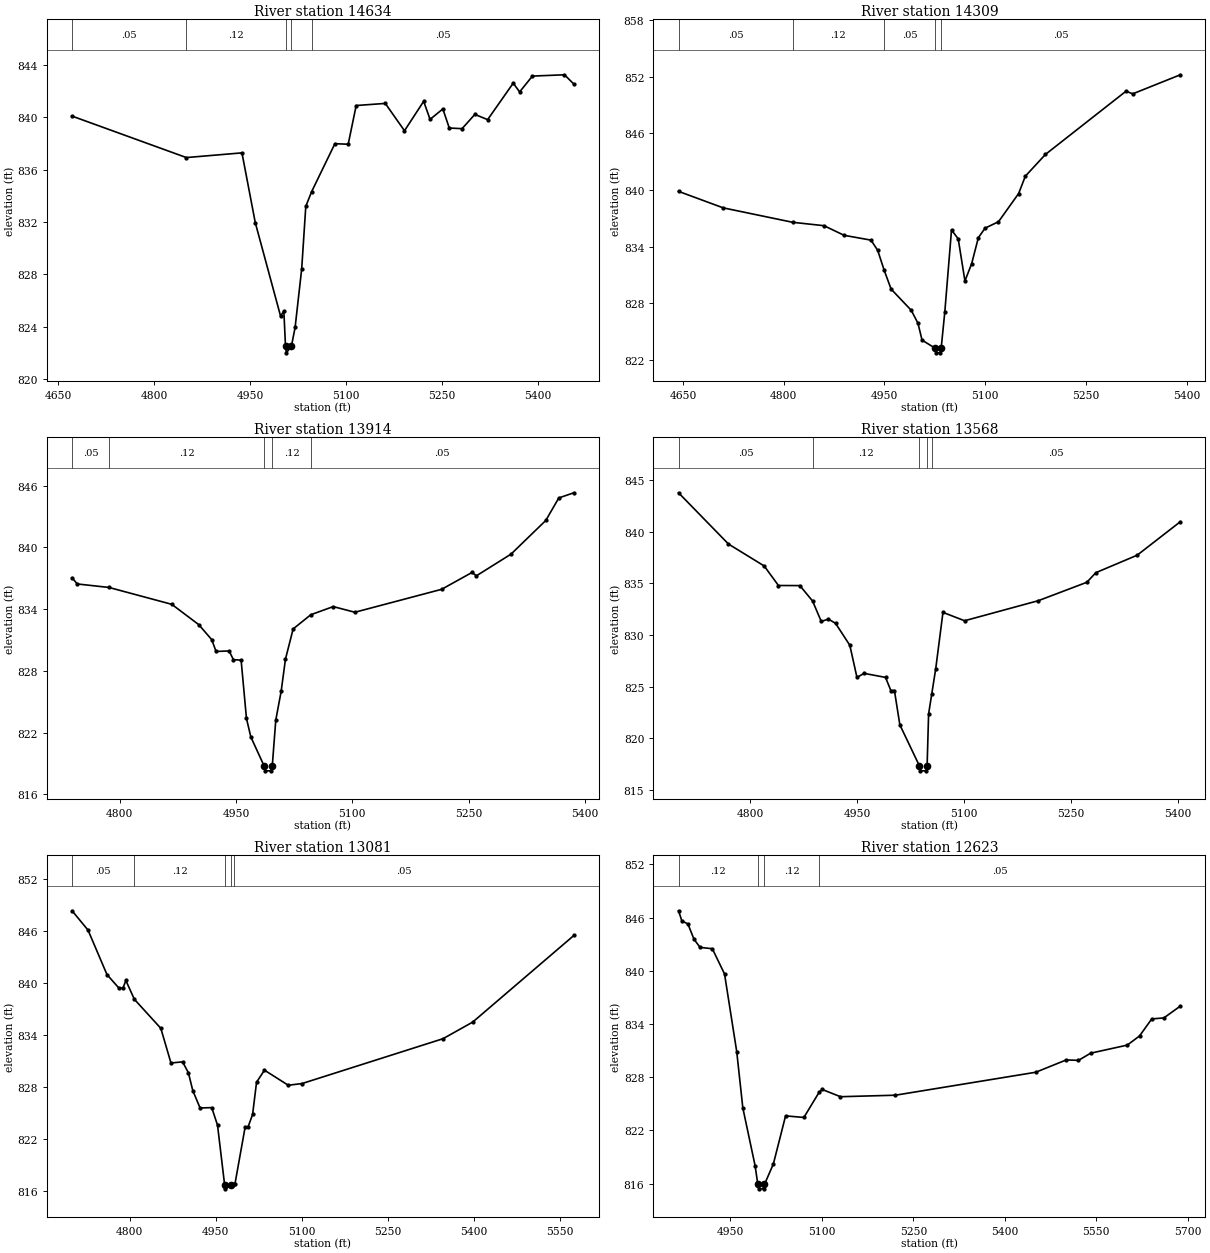
Type RM Length L Ch R = 1 ,14634   ,325,325,325
BEGIN DESCRIPTION:
Mapping XS bdcbaf32
END DESCRIPTION:
XS GIS Cut Line= 4
      2285685.35      7178927.54      2285530.43      7178944.19
      2285449.07      7179236.88      2285124.25      7179244.06
#Sta/Elev= 30
  4671.6   840.1  4850.3  836.93  4937.2  837.29    4958  831.96  4997.5  824.82
  5002.7  825.18  5005.3   822.5  5006.6     822  5014.5   822.5  5020.3  823.94
  5030.6  828.42    5037   833.2    5046  834.31  5082.5  837.99  5103.3  837.95
  5115.8  840.91  5161.3  841.07  5191.3  838.98  5221.3  841.23  5231.3  839.85
  5251.3  840.65  5261.3  839.19  5281.3  839.14  5301.3  840.23  5321.3  839.83
  5361.3  842.62  5371.3  841.95  5391.3  843.16  5441.4  843.26  5456.1  842.55
#Mann= 5 ,-1 , 0
  4671.6     .05       0  4850.3     .12       0  5005.3     .07       0
  5014.5     .12       0    5046     .05       0
Bank Sta=5005.3,5014.5
XS Rating Curve= 0 ,0
Exp/Cntr=0.3,0.1

Type RM Length L Ch R = 1 ,14309   ,395,395,395
BEGIN DESCRIPTION:
Mapping XS 11298d1e
END DESCRIPTION:
XS GIS Cut Line= 3
      2285685.64      7178893.78      2285321.64      7178897.97
      2284938.06      7178896.78
#Sta/Elev= 30
  4643.2  839.85  4709.8   838.1  4813.3  836.57  4859.9  836.21  4889.9  835.19
  4929.9  834.68  4939.9   833.6  4949.5   831.5  4959.9  829.49  4989.9  827.24
  4999.9  825.87    5006  824.08  5025.3  823.23  5026.6  822.73  5033.2  822.73
  5034.5  823.23  5039.9  827.06  5049.9  835.76  5059.9  834.81  5069.9  830.35
  5079.9  832.18  5089.9  834.94  5099.9  835.95  5119.9  836.63  5149.9  839.62
  5159.9  841.46  5189.9  843.77  5309.9  850.47  5319.9  850.19  5390.8  852.21
#Mann= 5 ,-1 , 0
  4643.2     .05       0  4813.3     .12       0  4949.5     .05       0
  5025.3    .033       0  5034.5     .05       0
Bank Sta=5025.3,5034.5
XS Rating Curve= 0 ,0
Exp/Cntr=0.3,0.1

Type RM Length L Ch R = 1 ,13914   ,346,346,346
BEGIN DESCRIPTION:
Mapping XS 56022749
END DESCRIPTION:
XS GIS Cut Line= 2
      2285614.11      7178635.92      2285035.04      7178347.11
#Sta/Elev= 30
  4738.7  837.04  4745.4  836.44  4786.3   836.1  4867.3  834.46    4902  832.49
  4918.8  831.03  4924.4  829.88  4941.2  829.93  4946.8  829.08  4956.7  829.04
  4963.6  823.37  4969.2  821.58  4986.2  818.78  4987.6  818.28  4995.4  818.28
  4996.9  818.78  5001.4  823.21  5008.3  825.99  5013.9  829.14  5023.8  832.07
  5046.6  833.45  5075.5  834.24  5103.4  833.69  5215.3  835.92  5254.5  837.56
  5260.1  837.23  5304.8  839.34  5349.6  842.61  5366.4   844.8  5385.8   845.3
#Mann= 5 ,-1 , 0
  4738.7     .05       0  4786.3     .12       0  4986.2     .07       0
  4996.9     .12       0  5046.6     .05       0
Bank Sta=4986.2,4996.9
XS Rating Curve= 0 ,0
Exp/Cntr=0.3,0.1

Type RM Length L Ch R = 1 ,13568   ,487,487,487
BEGIN DESCRIPTION:
MDE S 001 27.0
END DESCRIPTION:
XS GIS Cut Line= 3
      2285778.98        7178210.        2285479.        7178210.
      2285078.99        7178160.
#Sta/Elev= 30
    4700  843.75    4770  838.79    4820  836.67    4840  834.78    4870  834.77
  4887.8  833.28    4900   831.3    4910  831.53    4920  831.12    4940     829
    4950  825.89    4960  826.28    4990  825.89  4997.5  824.62  5002.5  824.62
  5010.1   821.3  5037.4  817.35  5038.9  816.85  5046.8  816.85  5048.3  817.35
  5050.4  822.36  5054.9  824.33  5060.4  826.74  5070.5  832.18  5100.8  831.37
  5204.1  833.31  5272.1  835.09  5284.7  836.02  5342.6  837.71  5403.1  840.95
#Mann= 5 ,-1 , 0
    4700     .05       0  4887.8     .12       0  5037.4     .07       0
  5048.3     .12       0  5054.9     .05       0
Bank Sta=5037.4,5048.3
XS Rating Curve= 0 ,0
Exp/Cntr=0.3,0.1

Type RM Length L Ch R = 1 ,13081   ,458,458,458
BEGIN DESCRIPTION:
MDE S 001 26.0
END DESCRIPTION:
XS GIS Cut Line= 3
      2285878.96      7177809.99        2285579.        7177760.
      2285028.99        7177910.
#Sta/Elev= 30
  4699.9  848.31  4727.7  846.08  4760.7  840.95    4781  839.43  4788.6  839.39
  4793.6  840.27  4808.4   838.1  4854.5  834.75  4872.2  830.75  4892.5  830.88
  4902.6  829.61  4910.2  827.57  4922.9  825.56  4943.2   825.6  4953.3  823.58
  4965.6  816.73  4967.1  816.23  4976.5  816.73    4982  816.78  4983.7   816.8
  5001.5  823.39  5006.6  823.39  5014.4  824.81  5021.3  828.53  5035.1  829.92
  5076.6  828.18  5100.7  828.38  5346.1  833.55  5397.9  835.47  5574.1  845.46
#Mann= 5 ,-1 , 0
  4699.9     .05       0  4808.4     .12       0  4965.6    .035       0
  4976.5     .12       0    4982     .05       0
Bank Sta=4965.6,4976.5
XS Rating Curve= 0 ,0
Exp/Cntr=0.3,0.1

Type RM Length L Ch R = 1 ,12623   ,432,432,432
BEGIN DESCRIPTION:
Mapping XS b0b74f20
END DESCRIPTION:
XS GIS Cut Line= 2
      2285914.39       7177366.2      2285092.09      7177391.76
#Sta/Elev= 30
    4865  846.78  4870.4  845.65  4880.4  845.29  4890.4  843.56  4900.4  842.65
  4920.4   842.5  4940.4  839.66  4960.4   830.9  4970.4  824.55  4990.5  818.04
    4995  815.92  4996.5  815.42  5004.4  815.42  5005.9  815.92  5020.5  818.23
  5040.5  823.65  5070.5  823.47  5095.4   826.3  5100.5  826.63  5130.5  825.81
  5220.6  825.98  5450.7  828.57  5500.7  829.96  5520.7  829.91  5540.7  830.72
  5600.7  831.63  5620.8  832.66  5640.8  834.58  5660.8   834.7  5687.7  836.03
#Mann= 4 ,-1 , 0
    4865     .12       0    4995     .07       0  5005.9     .12       0
  5095.4     .05       0
Bank Sta=4995,5005.9
XS Rating Curve= 0 ,0
Exp/Cntr=0.3,0.1

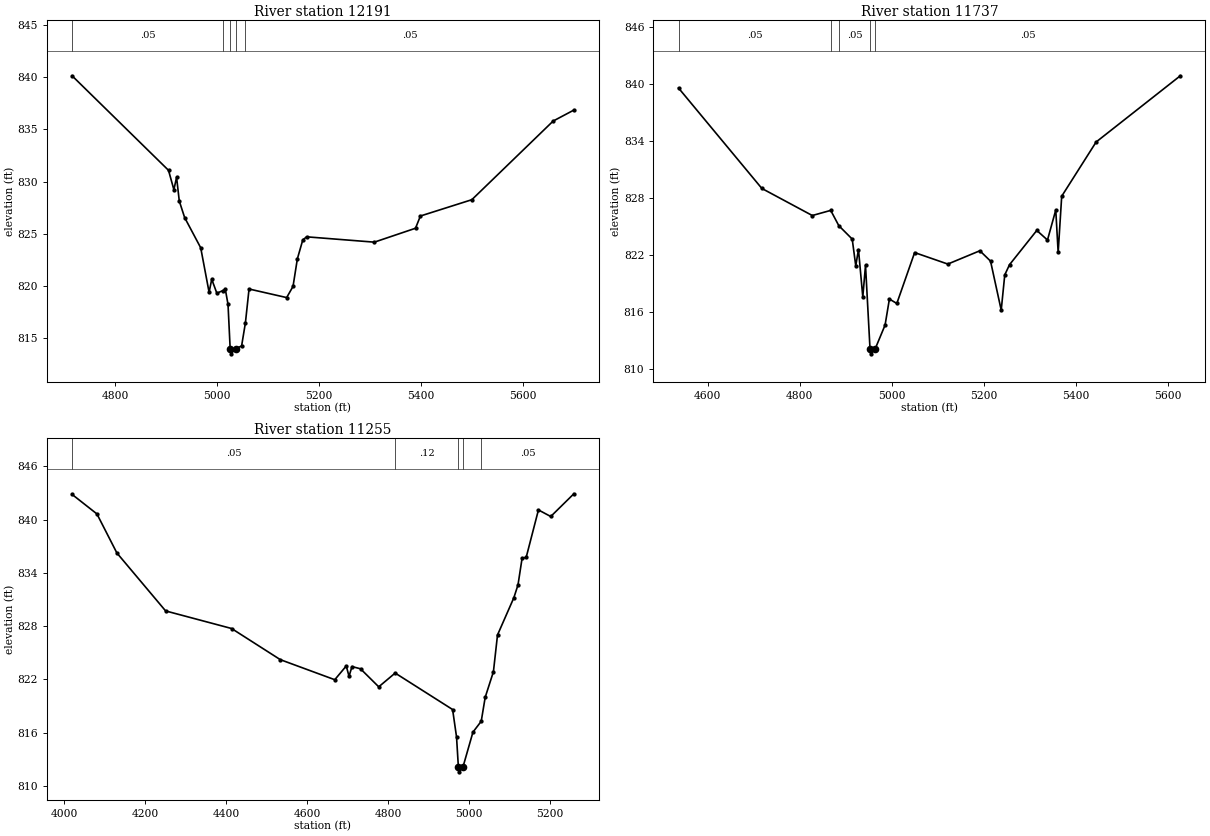
Type RM Length L Ch R = 1 ,12191   ,454,454,454
BEGIN DESCRIPTION:
Mapping XS 45ad4746
END DESCRIPTION:
XS GIS Cut Line= 3
       2285903.3      7177163.46      2285813.25      7177014.56
      2285044.12      7176762.81
#Sta/Elev= 30
  4715.8  840.12  4904.8  831.08  4915.3  829.23  4920.6  830.41  4925.9  828.14
  4936.4  826.56  4967.9  823.67  4984.3  819.42  4989.5  820.66  4999.5  819.33
    5011  819.57  5016.1   819.7  5021.4  818.26  5025.6  814.03  5027.1  813.53
  5036.6  814.03    5048  814.28  5055.5   816.5  5062.6  819.73  5136.3  818.91
  5148.8  819.98  5157.3  822.62  5167.9  824.42  5175.4  824.72  5308.1  824.21
  5388.8  825.54  5398.4  826.71  5499.2  828.27  5658.5  835.79  5699.1  836.84
#Mann= 5 ,-1 , 0
  4715.8     .05       0    5011     .12       0  5025.6    .033       0
  5036.6     .12       0  5055.5     .05       0
Bank Sta=5025.6,5036.6
XS Rating Curve= 0 ,0
Exp/Cntr=0.3,0.1

Type RM Length L Ch R = 1 ,11737   ,482,482,482
BEGIN DESCRIPTION:
MDE S 001 23.0
END DESCRIPTION:
XS GIS Cut Line= 3
      2286128.96      7176809.97        2285729.        7176560.
      2285129.02        7176410.
#Sta/Elev= 30
  4536.8  839.53  4717.8  828.96  4827.4  826.11  4867.4  826.65    4885  825.04
  4914.1  823.63  4921.8  820.82  4927.7  822.53  4937.1  817.54    4943  820.87
  4952.8  812.05  4954.3  811.55  4963.8  812.05  4985.5  814.58  4994.9  817.32
    5011  816.85  5049.7  822.21  5121.8     821  5191.4   822.4  5214.6  821.31
  5237.8  816.15  5245.5  819.86  5255.8  820.93  5315.1  824.54  5338.3  823.53
  5356.3  826.69  5361.5  822.22  5369.2  828.14    5444  833.85  5626.9  840.82
#Mann= 5 ,-1 , 0
  4536.8     .05       0  4867.4     .12       0    4885     .05       0
  4952.8    .033       0  4963.8     .05       0
Bank Sta=4952.8,4963.8
XS Rating Curve= 0 ,0
Exp/Cntr=0.3,0.1

Type RM Length L Ch R = 1 ,11255   ,444,444,444
BEGIN DESCRIPTION:
MDE S 001 22.0
END DESCRIPTION:
XS GIS Cut Line= 3
      2286267.31      7176768.14      2285717.93      7176274.88
      2285222.55      7176198.89
#Sta/Elev= 30
  4019.5  842.83  4080.9  840.63  4130.2  836.23  4250.6   829.7  4413.5  827.72
  4533.9  824.21  4668.4  821.95  4696.8   823.5  4703.6  822.34    4711  823.43
    4732  823.18    4777  821.15  4817.6   822.7  4959.5  818.59  4969.2   815.5
  4973.8  812.07  4975.3  811.57  4984.8  812.07  5009.7  816.04  5030.2  817.27
    5040  819.97  5060.3  822.85  5070.4  826.99  5110.8  831.19    5121  832.63
  5131.1  835.63  5141.2  835.73  5171.5  841.08  5201.9  840.34    5259   842.9
#Mann= 5 ,-1 , 0
  4019.5     .05       0  4817.6     .12       0  4973.8     .07       0
  4984.8     .12       0  5030.2     .05       0
Bank Sta=4973.8,4984.8
XS Rating Curve= 0 ,0
Exp/Cntr=0.3,0.1