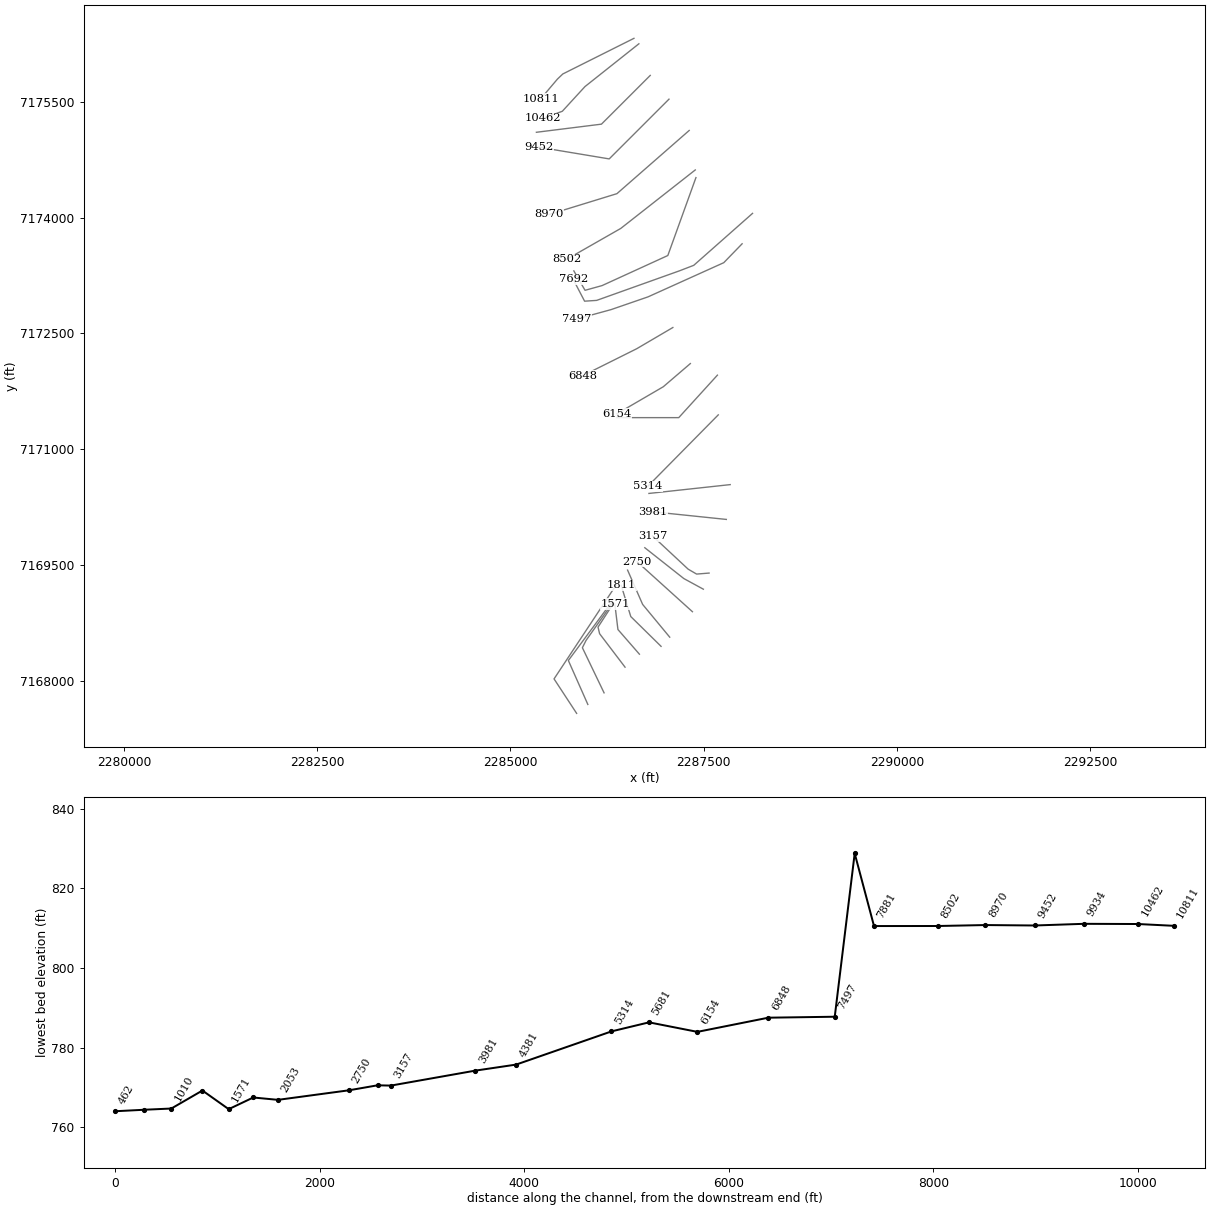
HEC-RAS study MDE S 001.prj: MDE S 001 Base Level Engineering

--- MDE S 001.g01 (geometry) --- (continued)

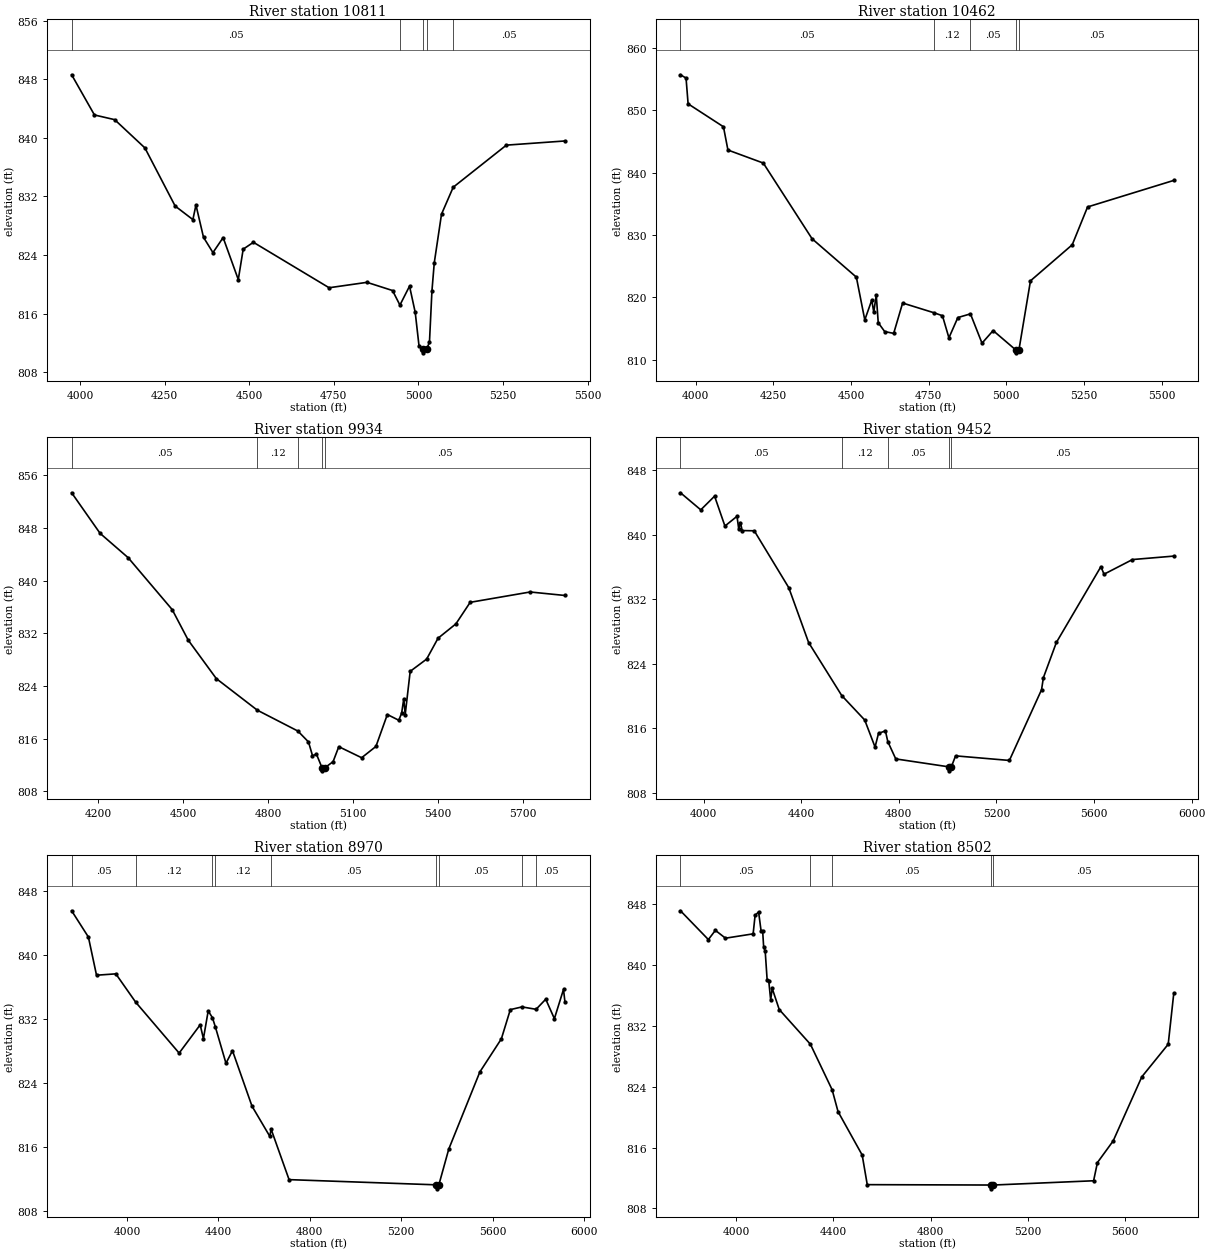
Type RM Length L Ch R = 1 ,10811   ,349,349,349
BEGIN DESCRIPTION:
MDE S 001 21.0
END DESCRIPTION:
XS GIS Cut Line= 4
       2286599.3      7176321.13        2285679.        7175860.
      2285609.31      7175793.46      2285394.53      7175539.93
#Sta/Elev= 30
  3975.2  848.61  4042.6  843.12  4102.3  842.48  4191.7  838.62  4281.1  830.68
  4333.5  828.83  4342.6  830.82  4364.9  826.41  4392.8  824.32  4422.9  826.37
  4467.7  820.64  4482.2  824.79  4512.4  825.73  4736.1  819.52    4848  820.26
  4923.6  819.14  4945.4  817.15  4973.8  819.74  4990.6  816.16  5001.8   811.6
  5013.1  811.13  5014.6  810.63  5024.1  811.13  5032.7  812.06    5040  819.07
  5046.9  822.92  5068.3  829.57  5102.9  833.25    5260     839  5433.2  839.57
#Mann= 5 ,-1 , 0
  3975.2     .05       0  4945.4     .12       0  5013.1     .07       0
  5024.1     .12       0  5102.9     .05       0
Bank Sta=5013.1,5024.1
XS Rating Curve= 0 ,0
Exp/Cntr=0.3,0.1

Type RM Length L Ch R = 1 ,10462   ,528,528,528
BEGIN DESCRIPTION:
Mapping XS 2c4f1b43
END DESCRIPTION:
XS GIS Cut Line= 4
      2286662.99      7176250.46       2285965.8      7175696.62
       2285672.5      7175376.84      2285425.41      7175285.05
#Sta/Elev= 30
  3951.4  855.68  3969.3  855.15  3975.9  851.02  4089.7  847.34  4104.1  843.61
  4217.9  841.52  4374.9  829.38  4517.5  823.22  4544.6  816.36  4567.1  819.54
  4573.5   817.6  4581.5  820.36  4587.9  815.91  4608.7  814.49  4637.6   814.2
  4666.4  819.07  4767.8   817.5  4794.6  817.03  4815.4  813.49  4844.2  816.74
  4884.7  817.33  4921.9  812.63  4957.7  814.65  5029.8  811.58  5031.4  811.08
  5040.9  811.58  5077.9  822.63  5212.3  828.41  5261.7  834.48  5539.3  838.74
#Mann= 5 ,-1 , 0
  3951.4     .05       0  4767.8     .12       0  4884.7     .05       0
  5029.8    .033       0  5040.9     .05       0
Bank Sta=5029.8,5040.9
XS Rating Curve= 0 ,0
Exp/Cntr=0.3,0.1

Type RM Length L Ch R = 1 ,9934    ,482,482,482
BEGIN DESCRIPTION:
MDE S 001 19.0
END DESCRIPTION:
XS GIS Cut Line= 5
      2286809.96      7175840.96        2286579.        7175610.
        2286179.        7175210.        2285779.        7175160.
      2285337.06      7175104.76
#Sta/Elev= 30
  4107.2  853.34  4207.6  847.18  4306.5  843.49  4462.1   835.6  4518.7  830.96
  4617.7  825.13  4762.3  820.34  4905.5  817.17  4942.9  815.52  4957.1  813.44
  4971.2  813.65  4990.4  811.63  4991.9  811.13  5001.6  811.63  5029.7  812.52
  5049.9   814.8  5130.5  813.12  5180.9  814.83  5221.2  819.68  5261.5  818.81
  5271.6  819.87  5279.2  822.08  5284.2  819.66  5301.8  826.23  5359.8  828.09
  5400.1  831.26  5463.1  833.44  5513.5  836.71  5725.1  838.28    5848  837.75
#Mann= 5 ,-1 , 0
  4107.2     .05       0  4762.3     .12       0  4905.5     .05       0
  4990.4    .033       0  5001.6     .05       0
Bank Sta=4990.4,5001.6
XS Rating Curve= 0 ,0
Exp/Cntr=0.3,0.1

Type RM Length L Ch R = 1 ,9452    ,482,482,482
BEGIN DESCRIPTION:
MDE S 001 18.0
END DESCRIPTION:
XS GIS Cut Line= 5
      2287052.76      7175533.77        2286679.        7175160.
        2286279.        7174760.        2285679.        7174860.
      2285364.38      7174912.44
#Sta/Elev= 30
  3905.4  845.23  3988.5  843.11  4045.1  844.81  4087.5   841.1    4137  842.31
  4144.1  840.73  4151.1  841.52  4158.2  840.54  4207.7  840.51  4349.1  833.45
  4430.4  826.64  4566.3  820.05  4660.3  817.02  4702.7  813.66  4716.8  815.36
  4745.1  815.67  4754.9  814.34  4787.5  812.19  5004.2  811.21  5005.7  810.71
  5015.4  811.21  5032.6  812.57  5253.1     812  5384.9  820.78  5392.5  822.28
  5445.7  826.65  5628.2  836.06  5640.9  835.12  5757.5  836.94  5926.9  837.37
#Mann= 5 ,-1 , 0
  3905.4     .05       0  4566.3     .12       0  4754.9     .05       0
  5004.2    .033       0  5015.4     .05       0
Bank Sta=5004.2,5015.4
XS Rating Curve= 0 ,0
Exp/Cntr=0.3,0.1

Type RM Length L Ch R = 1 ,8970    ,468,468,468
BEGIN DESCRIPTION:
MDE S 001 17.0
END DESCRIPTION:
XS GIS Cut Line= 5
      2287314.17       7175128.3        2286779.        7174660.
        2286379.        7174310.        2285729.        7174110.
      2285502.88      7174040.43
#Sta/Elev= 30
  3757.4  845.56  3830.7  842.28  3866.3  837.51  3950.8  837.68  4037.7  834.14
  4227.9  827.78    4320  831.31  4334.2  829.59  4355.1  833.05  4373.7   832.2
    4387     831  4432.9  826.51  4461.4  828.08  4546.8  821.15  4624.7  817.38
  4630.5  818.27  4709.1  811.97  5353.4  811.32  5354.9  810.82  5364.7  811.32
  5408.1  815.79  5544.1  825.42  5638.3  829.56  5677.5  833.21  5728.7  833.55
  5790.2  833.25  5832.5  834.51  5870.4  832.08  5910.3  835.74  5916.7  834.14
#Mann= 9 ,-1 , 0
  3757.4     .05       0  4037.7     .12       0  4373.7     .05       0
    4387     .12       0  4630.5     .05       0  5353.4    .033       0
  5364.7     .05       0  5728.7     .12       0  5790.2     .05       0
Bank Sta=5353.4,5364.7
XS Rating Curve= 0 ,0
Exp/Cntr=0.3,0.1

Type RM Length L Ch R = 1 ,8502    ,621,621,621
BEGIN DESCRIPTION:
MDE S 001 16.0
END DESCRIPTION:
XS GIS Cut Line= 4
      2287392.66      7174617.17        2287129.        7174410.
        2286429.        7173860.      2285728.97      7173459.98
#Sta/Elev= 30
  3770.3   847.1  3885.1  843.32    3914  844.53  3955.6   843.5  4069.5  844.07
  4077.6   846.5    4092  846.95  4102.4  844.41  4108.8  844.41  4112.8  842.35
  4119.2  841.79  4127.3  837.97  4133.7  837.93  4141.7  835.39  4148.1   836.9
    4177  834.13  4305.4  829.57  4394.9  823.59  4419.2  820.72  4518.6  815.02
  4539.5  811.13  5047.8  811.08  5049.3  810.58  5059.1  811.08  5471.7  811.64
  5487.5  814.03  5552.3  816.87  5670.3  825.29    5779  829.57  5802.1  836.31
#Mann= 5 ,-1 , 0
  3770.3     .05       0  4305.4     .12       0  4394.9     .05       0
  5047.8    .033       0  5059.1     .05       0
Bank Sta=5047.8,5059.1
XS Rating Curve= 0 ,0
Exp/Cntr=0.3,0.1

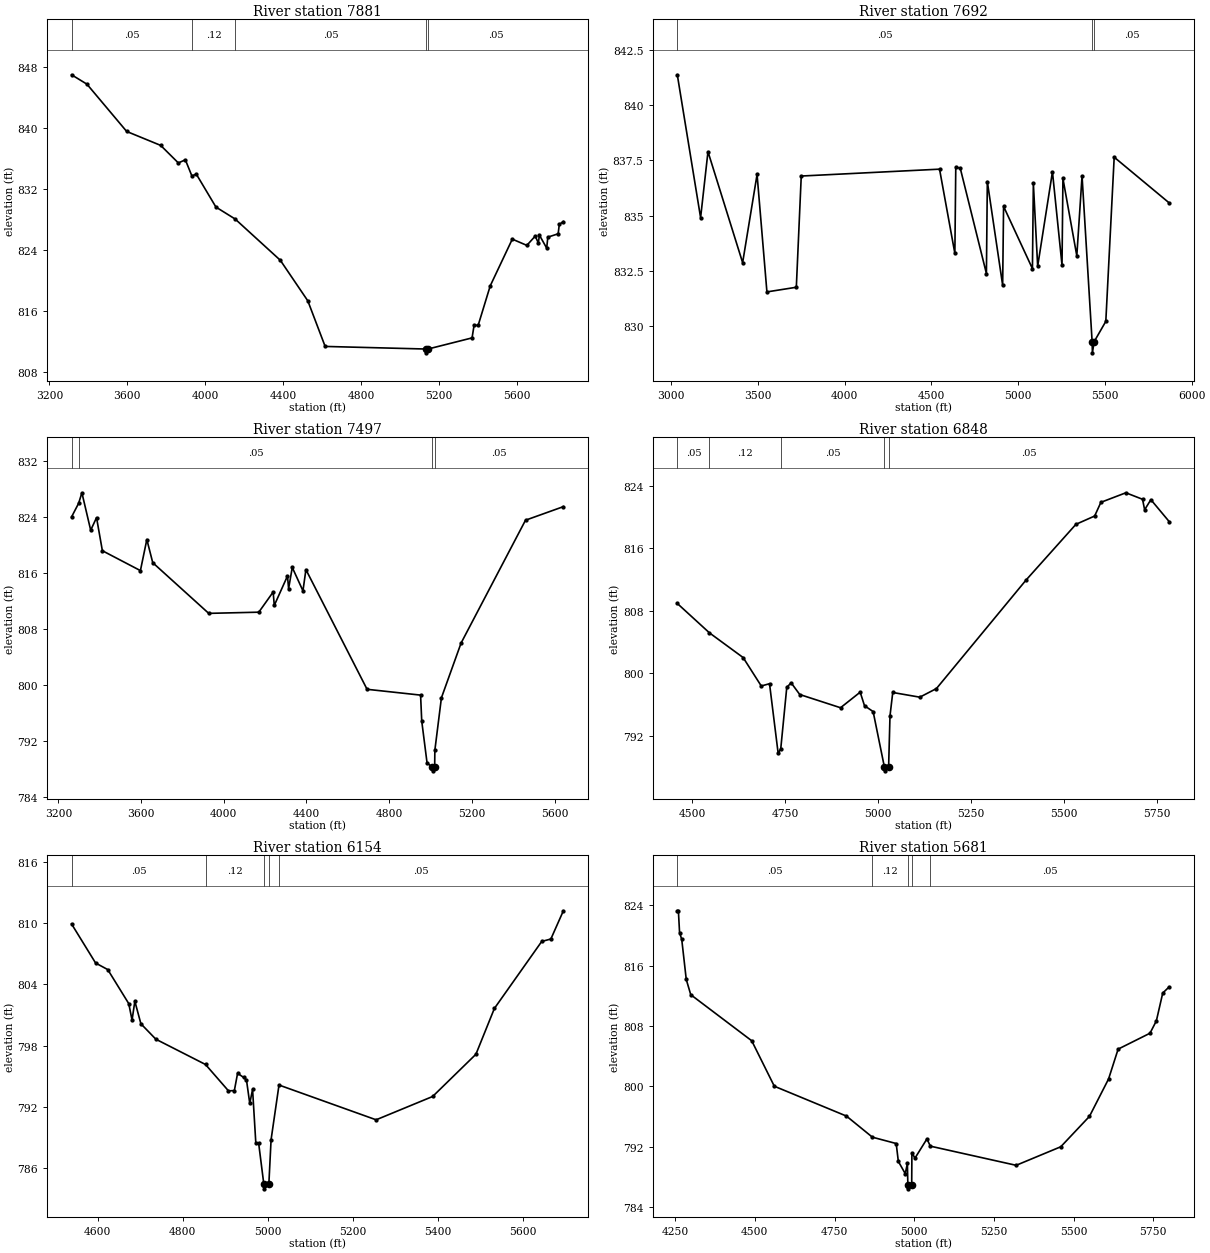
Type RM Length L Ch R = 1 ,7881    ,189,189,189
BEGIN DESCRIPTION:
Mapping XS d418cbfa
END DESCRIPTION:
XS GIS Cut Line= 6
      2287401.29      7174517.84       2287246.8      7174089.44
      2287037.47      7173509.02      2286186.78      7173119.65
      2285966.47      7173058.59      2285821.58      7173309.93
#Sta/Elev= 30
  3313.4  847.03  3392.3   845.8  3596.5   839.6  3771.2  837.77    3862  835.47
    3898  835.88  3931.6  833.76  3954.1  834.01  4055.2  829.68  4153.6  828.12
  4385.8  822.71  4527.1  817.39  4616.2  811.41  5133.3  811.07  5134.8  810.57
  5144.6  811.07    5371  812.53  5381.4   814.2  5402.1  814.16  5464.4  819.36
  5577.7  825.48  5652.4  824.66  5695.5  825.88  5711.3  824.98  5717.1     826
  5754.4   824.3  5760.2  825.74  5813.3  826.18  5819.1  827.41  5840.1  827.78
#Mann= 5 ,-1 , 0
  3313.4     .05       0  3931.6     .12       0  4153.6     .05       0
  5133.3    .033       0  5144.6     .05       0
Bank Sta=5133.3,5144.6
XS Rating Curve= 0 ,0
Exp/Cntr=0.3,0.1

Type RM Length L Ch R = 1 ,7692    ,195,195,195
BEGIN DESCRIPTION:
Mapping XS d1cc3da7
END DESCRIPTION:
XS GIS Cut Line= 6
       2288133.9      7174054.94        2287373.      7173382.06
      2287188.41      7173310.96      2286116.73      7172928.05
       2285960.6      7172917.84      2285812.44      7173202.13
#Sta/Elev= 30
  3034.9  841.36  3169.2  834.91  3211.7  837.89  3411.5  832.88  3494.7  836.86
  3551.5  831.56    3721  831.77  3749.4  836.79  4546.6   837.1  4634.9   833.3
  4640.2   837.2  4666.1  837.14  4816.8  832.39  4822.1  836.54  4910.4  831.86
  4915.7  835.42  5082.1  832.61  5087.4  836.46  5112.3  832.72  5197.5  836.98
  5252.6  832.77  5257.9  836.68  5337.9  833.19  5368.1  836.79  5426.2  829.31
  5427.8  828.81  5437.6  829.31  5505.1  830.23  5553.4  837.64    5870  835.58
#Mann= 3 ,-1 , 0
  3034.9     .05       0  5426.2    .033       0  5437.6     .05       0
Bank Sta=5426.2,5437.6
XS Rating Curve= 0 ,0
Exp/Cntr=0.3,0.1

Type RM Length L Ch R = 1 ,7497    ,649,649,649
BEGIN DESCRIPTION:
Mapping XS 7fe30eb4
END DESCRIPTION:
XS GIS Cut Line= 5
      2287998.75      7173660.97      2287761.42      7173416.22
      2286781.19      7172973.59      2286303.22      7172808.68
      2285862.57      7172687.82
#Sta/Elev= 30
  3263.8  824.08    3298  826.03  3313.8  827.53  3356.3  822.18  3384.6  823.98
  3412.8  819.25  3596.8  816.41  3627.9  820.85  3656.5  817.54  3927.3   810.3
  4169.5  810.47  4238.9  813.35  4244.4  811.44  4308.2  815.64  4313.7  813.84
  4331.4  816.86  4383.1  813.52  4397.4  816.55  4693.2  799.45  4952.1  798.62
  4957.6  794.92  4983.3  788.95  5008.8   788.3  5010.4   787.8  5020.2   788.3
  5021.1  790.74  5052.8  798.23    5148  806.06  5459.6  823.61  5642.8  825.55
#Mann= 4 ,-1 , 0
  3263.8     .12       0    3298     .05       0  5008.8    .033       0
  5020.2     .05       0
Bank Sta=5008.8,5020.2
XS Rating Curve= 0 ,0
Exp/Cntr=0.3,0.1

Type RM Length L Ch R = 1 ,6848    ,694,694,694
BEGIN DESCRIPTION:
Mapping XS 130c992c
END DESCRIPTION:
XS GIS Cut Line= 3
      2287102.71      7172576.81      2286634.68      7172301.93
       2285937.9      7171954.21
#Sta/Elev= 30
  4460.2  808.94  4546.7  805.18  4637.1  802.03  4685.8   798.4    4708  798.69
  4731.2  789.79  4738.2  790.39  4754.3  798.21    4766  798.81  4789.2  797.31
  4898.8  795.62  4951.6  797.61  4963.2  795.88  4986.4  795.13  5016.6  788.06
  5018.1  787.56    5028  788.06  5031.7  794.58  5039.1  797.57  5111.8  796.97
  5156.5  798.07  5397.1  811.92  5531.3  819.05  5581.6  820.11  5598.4  821.86
  5665.5  823.08  5710.3  822.25  5715.9  820.91  5732.7   822.2  5781.7  819.41
#Mann= 5 ,-1 , 0
  4460.2     .05       0  4546.7     .12       0  4738.2     .05       0
  5016.6    .033       0    5028     .05       0
Bank Sta=5016.6,5028
XS Rating Curve= 0 ,0
Exp/Cntr=0.3,0.1

Type RM Length L Ch R = 1 ,6154    ,473,473,473
BEGIN DESCRIPTION:
MDE S 001 11.0
END DESCRIPTION:
XS GIS Cut Line= 3
      2287328.97      7172109.97        2286979.        7171810.
      2286378.96      7171459.98
#Sta/Elev= 30
  4538.6   809.9  4595.1  806.08  4623.6  805.44    4673  802.11  4680.7   800.5
  4687.3  802.34  4701.5  800.14  4736.7  798.63  4853.3  796.16  4907.3  793.58
  4921.1  793.61  4928.7   795.3    4943  794.89  4949.6  794.64  4957.3  792.35
  4963.9  793.72  4971.5   788.5  4978.1  788.49  4990.2   784.5  4991.9     784
  5002.2   784.5  5007.4  788.81    5026  794.15  5254.2  790.75    5387  793.03
  5488.7  797.16  5532.1  801.64  5643.3  808.19  5664.8  808.43  5694.2  811.19
#Mann= 5 ,-1 , 0
  4538.6     .05       0  4853.3     .12       0  4990.2     .07       0
  5002.2     .12       0    5026     .05       0
Bank Sta=4990.2,5002.2
XS Rating Curve= 0 ,0
Exp/Cntr=0.3,0.1

Type RM Length L Ch R = 1 ,5681    ,367,367,367
BEGIN DESCRIPTION:
MDE S 001 10.0
END DESCRIPTION:
XS GIS Cut Line= 3
      2287679.01      7171960.01        2287179.        7171410.
      2286379.01        7171410.
#Sta/Elev= 30
  4256.7  823.27  4260.1  823.27  4263.8  820.37  4270.6  819.48  4284.8  814.16
  4298.9  812.14  4490.2  806.03  4561.1     800  4787.5  796.04  4868.9  793.24
  4943.6   792.4  4950.3  790.03    4972   788.4  4978.7  789.77  4980.2  786.89
  4981.9  786.39  4992.2  786.89  4992.9  791.18  5002.5  790.46    5040  793.01
  5050.8  792.05    5320  789.51    5460  791.97    5550     796    5610  800.96
    5640  804.92    5740  807.03    5760  808.67    5780  812.36    5800  813.17
#Mann= 5 ,-1 , 0
  4256.7     .05       0  4868.9     .12       0  4980.2     .07       0
  4992.2     .12       0  5050.8     .05       0
Bank Sta=4980.2,4992.2
XS Rating Curve= 0 ,0
Exp/Cntr=0.3,0.1

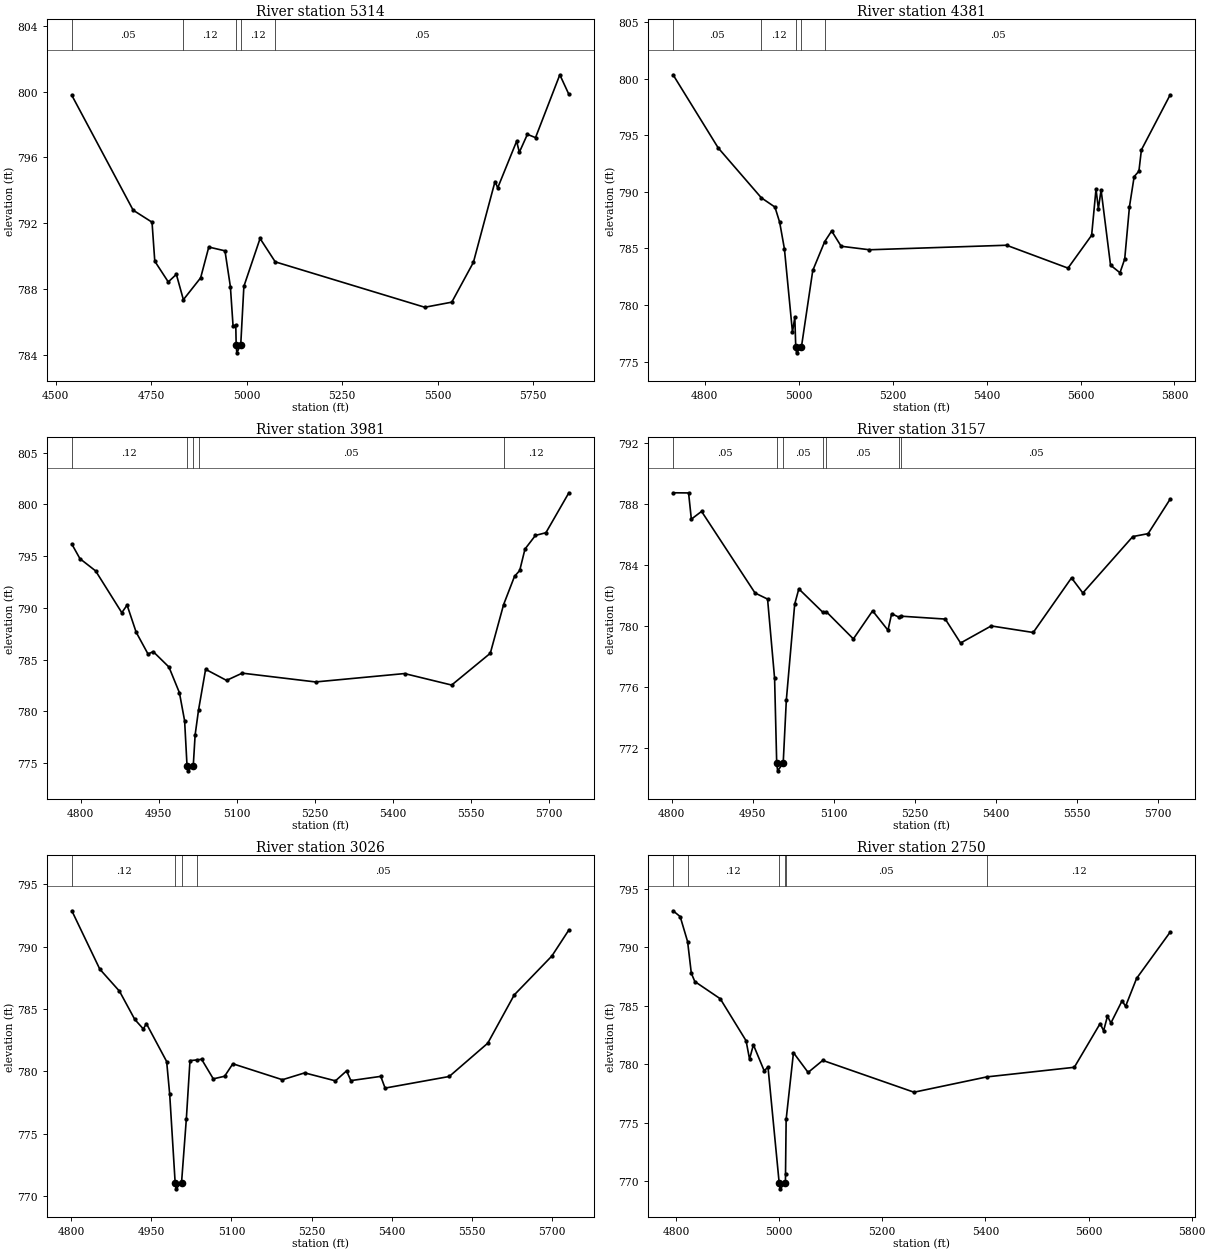
Type RM Length L Ch R = 1 ,5314    ,933,933,933
BEGIN DESCRIPTION:
Mapping XS 9314e55f
END DESCRIPTION:
XS GIS Cut Line= 2
      2287690.19      7171445.86      2286776.45      7170519.05
#Sta/Elev= 30
  4542.3  799.77  4702.9  792.79  4752.3  792.06  4759.5  789.69  4794.8  788.43
    4816  788.89  4834.4  787.35  4879.6  788.68  4900.9  790.55  4943.3  790.32
  4957.5  788.14  4964.5  785.74  4971.6  785.81  4972.6  784.62  4974.3  784.12
  4984.6  784.62  4992.8  788.16  5035.2  791.07  5074.9  789.65  5466.5  786.89
  5537.2   787.2  5593.8  789.62  5650.4  794.53  5657.5  794.15    5707  796.98
  5714.1  796.31  5735.2   797.4  5756.5   797.2  5820.1  801.02  5843.8  799.83
#Mann= 5 ,-1 , 0
  4542.3     .05       0  4834.4     .12       0  4972.6     .07       0
  4984.6     .12       0  5074.9     .05       0
Bank Sta=4972.6,4984.6
XS Rating Curve= 0 ,0
Exp/Cntr=0.3,0.1

Type RM Length L Ch R = 1 ,4381    ,400,400,400
BEGIN DESCRIPTION:
Mapping XS b732fd67
END DESCRIPTION:
XS GIS Cut Line= 2
      2287844.57      7170542.67      2286792.96      7170428.42
#Sta/Elev= 30
  4732.9  800.33    4829  793.87  4920.7  789.47  4949.7  788.65  4959.8   787.3
  4969.9  784.95    4987  777.61    4992  778.93    4994  776.28  4995.7  775.78
    5006  776.28  5030.2  783.05  5055.6   785.6  5070.4  786.54  5090.6  785.19
  5150.9  784.88  5442.6  785.28  5573.4  783.26  5623.7  786.16    5633  790.24
    5638   788.5  5643.8  790.16  5663.9  783.52    5684  782.85  5694.1  784.07
  5704.2  788.69  5714.2  791.34  5724.3  791.82  5729.6   793.7  5790.7  798.55
#Mann= 5 ,-1 , 0
  4732.9     .05       0  4920.7     .12       0    4994     .07       0
    5006     .12       0  5055.6     .05       0
Bank Sta=4994,5006
XS Rating Curve= 0 ,0
Exp/Cntr=0.3,0.1

Type RM Length L Ch R = 1 ,3981    ,824,824,824
BEGIN DESCRIPTION:
Mapping XS a8970b3a
END DESCRIPTION:
XS GIS Cut Line= 2
      2287794.49      7170091.96      2286845.11      7170190.75
#Sta/Elev= 30
    4783  796.17  4798.6  794.76  4828.7  793.58    4879  789.54  4889.1  790.28
  4906.5  787.66  4929.3  785.55  4939.3  785.78  4969.5  784.29  4989.6  781.81
  4999.6  779.09  5004.2  774.76  5005.8  774.26  5016.2  774.76  5019.8  777.74
  5026.3  780.13  5039.9  784.07  5080.1     783  5110.2   783.7    5251  782.85
  5421.9  783.66  5512.4  782.55  5586.6  785.62  5612.2  790.33  5633.1  793.05
  5643.1  793.62  5653.2  795.69  5673.3  797.01  5693.4  797.27  5737.5  801.13
#Mann= 5 ,-1 , 0
    4783     .12       0  5004.2     .07       0  5016.2     .12       0
  5026.3     .05       0  5612.2     .12       0
Bank Sta=5004.2,5016.2
XS Rating Curve= 0 ,0
Exp/Cntr=0.3,0.1

Type RM Length L Ch R = 1 ,3157    ,131,131,131
BEGIN DESCRIPTION:
Mapping XS abc8a669
END DESCRIPTION:
XS GIS Cut Line= 4
      2287571.57      7169397.38      2287409.67      7169384.42
      2287301.05      7169447.66      2286839.38      7169878.23
#Sta/Elev= 30
  4802.4  788.74  4831.1  788.73  4836.2  787.01  4855.1  787.52    4954  782.17
  4977.2  781.77  4990.2  776.57  4994.1  771.01  4995.8  770.51  5006.1  771.01
  5011.9  775.15  5027.4  781.44    5035  782.44    5079  780.92  5085.9  780.94
  5135.9  779.16  5171.5     781  5199.9  779.73  5206.7  780.81  5220.5  780.58
  5223.9  780.65  5305.9  780.46  5334.2  778.89  5390.9  780.01  5468.6  779.58
  5539.4  783.16  5560.4  782.17  5652.8  785.87  5681.1  786.06  5721.8  788.32
#Mann= 7 ,-1 , 0
  4802.4     .05       0  4994.1    .033       0  5006.1     .05       0
    5079     .12       0  5085.9     .05       0  5220.5     .12       0
  5223.9     .05       0
Bank Sta=4994.1,5006.1
XS Rating Curve= 0 ,0
Exp/Cntr=0.3,0.1

Type RM Length L Ch R = 1 ,3026    ,276,276,276
BEGIN DESCRIPTION:
Mapping XS 0ddd1943
END DESCRIPTION:
XS GIS Cut Line= 3
       2287497.4      7169188.52      2287245.09      7169326.02
      2286739.84      7169725.42
#Sta/Elev= 30
  4800.8  792.88  4853.2   788.2  4890.1  786.43  4918.7  784.17  4934.8   783.4
  4940.5  783.83  4978.5  780.79  4984.2  778.16  4994.4  771.08    4996  770.58
  5006.4  771.08  5015.4   776.2  5022.2  780.86  5035.3  780.92    5044  780.97
  5065.9   779.4  5087.1  779.61  5102.5  780.61  5195.4  779.33  5237.1  779.88
  5294.8  779.24  5315.6  780.04  5323.7  779.26  5379.7   779.6  5387.8  778.66
    5508  779.59  5580.2  782.26  5629.8  786.13  5700.3  789.25  5732.2  791.34
#Mann= 4 ,-1 , 0
  4800.8     .12       0  4994.4     .07       0  5006.4     .12       0
  5035.3     .05       0
Bank Sta=4994.4,5006.4
XS Rating Curve= 0 ,0
Exp/Cntr=0.3,0.1

Type RM Length L Ch R = 1 ,2750    ,697,697,697
BEGIN DESCRIPTION:
Mapping XS 45c54ede
END DESCRIPTION:
XS GIS Cut Line= 2
      2287355.79      7168897.16      2286640.78      7169543.73
#Sta/Elev= 30
  4794.2  793.11    4808  792.61  4822.4  790.47  4829.6  787.77  4836.4  787.06
  4885.7  785.59  4935.8     782  4942.5  780.43    4950  781.65  4970.9  779.43
  4978.3  779.75    5000  769.84  5001.7  769.34  5012.1  769.84  5012.3  770.62
  5013.5  775.27  5027.7  780.98  5056.1  779.29  5084.5  780.32  5261.5   777.6
  5402.8  778.91  5572.4  779.73  5622.5  783.47  5629.2  782.85  5636.7   784.1
  5643.4  783.52  5665.1  785.42  5671.8  784.94  5693.2  787.33  5758.2  791.28
#Mann= 6 ,-1 , 0
  4794.2     .05       0  4822.4     .12       0    5000     .07       0
  5012.1     .12       0  5012.3     .05       0  5402.8     .12       0
Bank Sta=5000,5012.1
XS Rating Curve= 0 ,0
Exp/Cntr=0.3,0.1

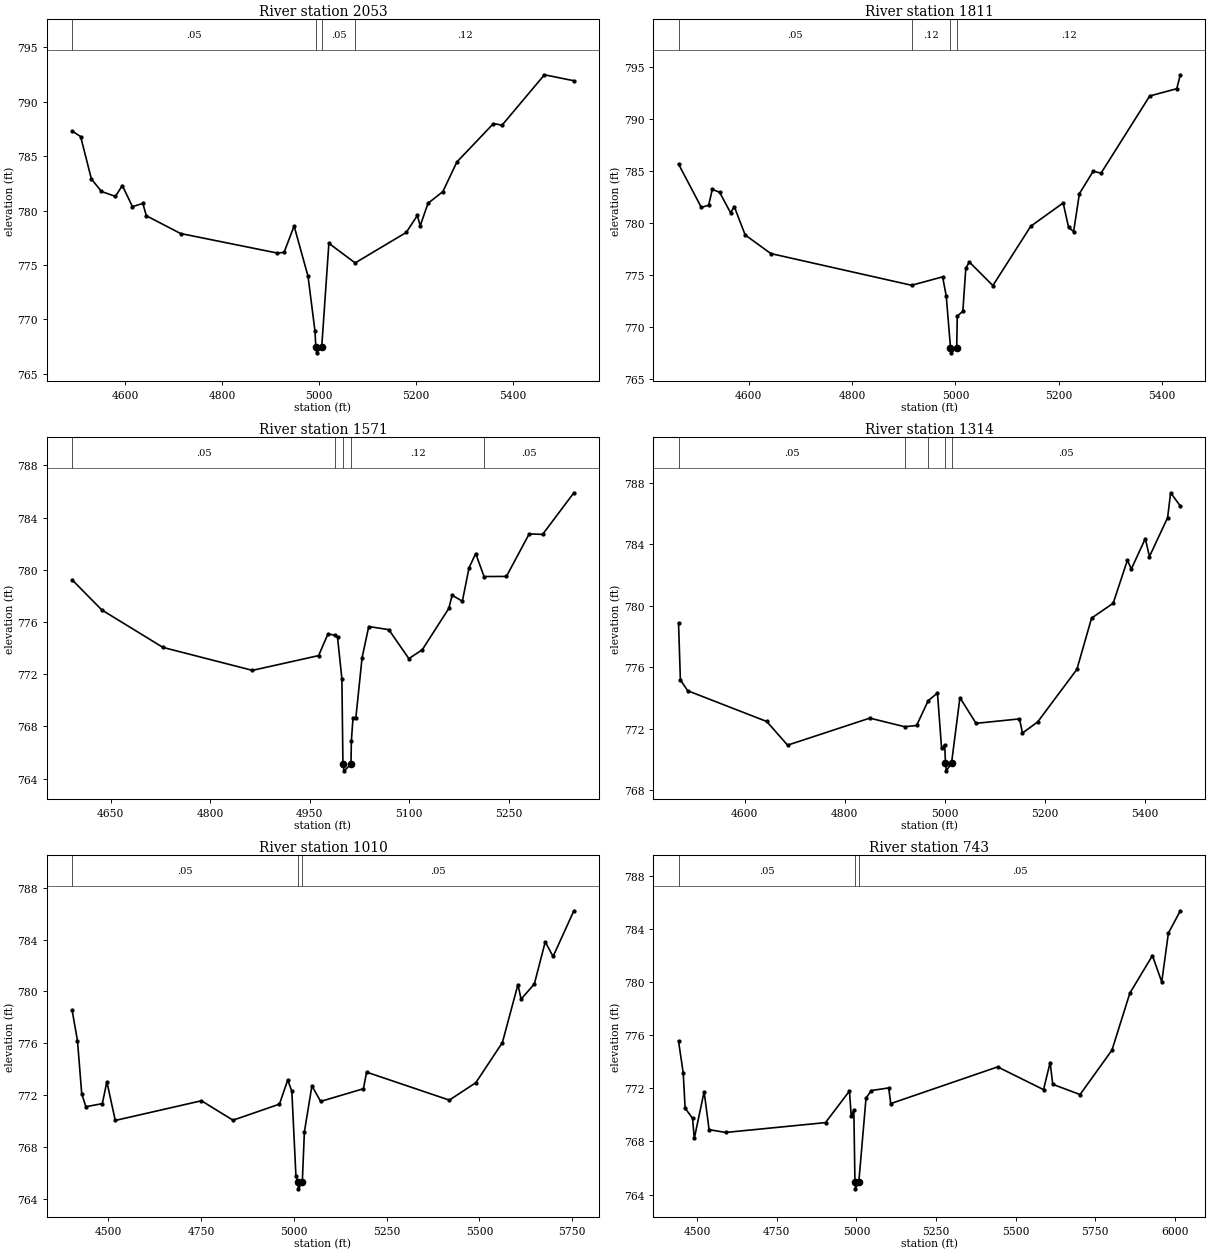
Type RM Length L Ch R = 1 ,2053    ,242,242,242
BEGIN DESCRIPTION:
Mapping XS a8f31c4b
END DESCRIPTION:
XS GIS Cut Line= 3
      2287062.04      7168567.46      2286711.63      7168991.54
      2286516.87      7169435.59
#Sta/Elev= 30
  4490.6  787.31  4508.3  786.79  4530.5  782.89  4551.3  781.75    4580   781.3
  4594.3   782.3  4615.1  780.36  4636.6  780.65  4643.8  779.52  4714.4  777.89
  4913.4   776.1  4927.8  776.15  4948.6  778.58  4977.3  773.96  4991.6  768.94
  4993.4  767.43  4995.1  766.93  5005.5  767.43  5020.3  776.99  5074.5  775.19
  5179.9  777.99  5202.8  779.55  5208.7   778.6  5224.7  780.66  5255.4  781.74
  5284.3  784.46  5359.8  787.99  5377.5  787.84  5464.9  792.47  5525.6  791.92
#Mann= 4 ,-1 , 0
  4490.6     .05       0  4993.4    .033       0  5005.5     .05       0
  5074.5     .12       0
Bank Sta=4993.4,5005.5
XS Rating Curve= 0 ,0
Exp/Cntr=0.3,0.1

Type RM Length L Ch R = 1 ,1811    ,240,240,240
BEGIN DESCRIPTION:
Mapping XS 6000a5c8
END DESCRIPTION:
XS GIS Cut Line= 3
      2286950.11      7168448.69      2286558.21      7168834.38
      2286434.81      7169236.62
#Sta/Elev= 30
  4464.3  785.68  4508.4  781.51  4522.5  781.72  4529.7  783.25  4543.8  782.96
    4565  780.99  4572.1  781.59  4593.2  778.86  4642.8  777.07  4915.1  774.02
  4975.1  774.83  4982.2  772.96  4990.3  768.02    4992  767.52  5002.4  768.02
  5003.4  771.05  5014.2  771.52    5020  775.68  5026.9  776.25  5072.3  773.99
  5145.6   779.7  5208.3  781.94  5218.8  779.58  5228.5  779.19  5239.7  782.84
  5266.5     785  5281.5   784.8  5375.7  792.23    5428  792.93  5434.9  794.27
#Mann= 4 ,-1 , 0
  4464.3     .05       0  4915.1     .12       0  4990.3     .07       0
  5002.4     .12       0
Bank Sta=4990.3,5002.4
XS Rating Curve= 0 ,0
Exp/Cntr=0.3,0.1

Type RM Length L Ch R = 1 ,1571    ,257,257,257
BEGIN DESCRIPTION:
Mapping XS 9b9dbead
END DESCRIPTION:
XS GIS Cut Line= 3
      2286669.87      7168347.19      2286391.99       7168666.5
      2286351.85      7168996.78
#Sta/Elev= 30
    4592  779.23  4636.8  776.92  4728.9  774.05  4863.7  772.29  4963.4  773.42
  4977.6  775.09  4988.6  774.97  4991.9  774.83  4998.5  771.66  5000.1  765.09
  5001.8  764.59  5012.2  765.09  5012.8  766.89  5015.3  768.67  5019.6  768.67
  5028.9  773.25    5039  775.65  5069.2  775.41  5099.4  773.19  5119.6  773.87
  5159.6  777.04  5164.6  778.05    5180  777.59  5190.1  780.15  5200.1  781.24
  5212.7  779.48  5246.4  779.49  5280.7  782.75  5300.9  782.71    5348   785.9
#Mann= 5 ,-1 , 0
    4592     .05       0  4988.6     .12       0  5000.1     .07       0
  5012.2     .12       0  5212.7     .05       0
Bank Sta=5000.1,5012.2
XS Rating Curve= 0 ,0
Exp/Cntr=0.3,0.1

Type RM Length L Ch R = 1 ,1314    ,304,304,304
BEGIN DESCRIPTION:
Mapping XS 581aa709
END DESCRIPTION:
XS GIS Cut Line= 4
      2286484.03      7168179.11      2286154.87      7168612.21
       2286134.4      7168697.72      2286336.24      7169008.76
#Sta/Elev= 30
    4468  778.88  4471.7  775.19  4486.3  774.48  4644.3  772.48  4685.9  770.94
  4850.2   772.7  4919.9  772.14  4943.7  772.22    4967  773.84  4985.4  774.33
  4993.6  770.75  4999.9  770.97  5001.4  769.77  5003.1  769.27  5013.5  769.77
  5030.3  774.03  5062.5  772.36  5149.3  772.65  5155.3  771.73  5185.6  772.45
    5264  775.87  5293.4  779.21  5336.5  780.17  5364.9  782.97  5372.8   782.4
  5400.7  784.38    5409  783.21  5445.3  785.74  5451.3  787.36  5470.7   786.5
#Mann= 5 ,-1 , 0
    4468     .05       0  4919.9     .12       0    4967     .05       0
  5001.4    .033       0  5013.5     .05       0
Bank Sta=5001.4,5013.5
XS Rating Curve= 0 ,0
Exp/Cntr=0.3,0.1

Type RM Length L Ch R = 1 ,1010    ,267,267,267
BEGIN DESCRIPTION:
Mapping XS f3c53391
END DESCRIPTION:
XS GIS Cut Line= 4
      2286212.61      7167846.54      2285932.09      7168430.79
      2285979.13      7168524.75      2286324.66      7169012.96
#Sta/Elev= 30
  4402.9  778.56  4417.5  776.18  4428.9   772.1    4440  771.09  4484.4  771.33
  4496.6  773.02  4519.2  770.03  4751.2  771.55  4836.2  770.05  4961.4  771.29
  4983.6  773.15  4994.7   772.3  5005.8  765.71  5010.8  765.25  5012.5  764.75
  5022.9  765.25  5028.5  769.14  5048.8   772.7  5072.3   771.5  5187.5  772.48
  5196.1  773.76  5418.9   771.6  5490.3  772.95  5561.7  776.04  5603.6  780.52
  5612.1   779.4  5647.8  780.57  5677.1  783.82  5698.3  782.69  5754.2  786.22
#Mann= 3 ,-1 , 0
  4402.9     .05       0  5010.8    .033       0  5022.9     .05       0
Bank Sta=5010.8,5022.9
XS Rating Curve= 0 ,0
Exp/Cntr=0.3,0.1

Type RM Length L Ch R = 1 ,743     ,281,281,281
BEGIN DESCRIPTION:
Mapping XS df35c861
END DESCRIPTION:
XS GIS Cut Line= 3
      2286002.58      7167696.46      2285750.58      7168265.36
      2286318.63      7169032.04
#Sta/Elev= 30
  4441.3  775.55  4456.1  773.14    4462  770.51  4485.3  769.74  4490.8  768.23
  4521.7  771.75  4537.3  768.89  4589.4  768.68    4903  769.42  4978.3   771.8
  4983.8  769.91    4992  770.38  4995.5  764.94  4997.2  764.44  5007.6  764.94
  5030.3  771.26  5046.7  771.83  5101.6  772.03  5107.9  770.85  5443.8  773.61
  5587.9   771.9  5608.7  773.94  5616.9   772.3  5702.7  771.53  5802.9  774.87
  5859.2  779.16  5930.1  781.98  5959.3     780  5980.2  783.67  6017.7  785.35
#Mann= 3 ,-1 , 0
  4441.3     .05       0  4995.5    .033       0  5007.6     .05       0
Bank Sta=4995.5,5007.6
XS Rating Curve= 0 ,0
Exp/Cntr=0.3,0.1

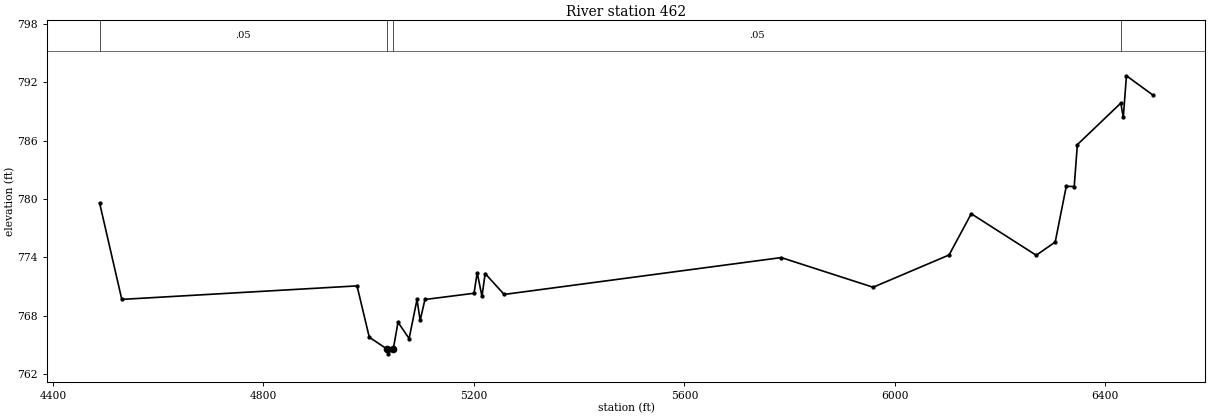
Type RM Length L Ch R = 1 ,462     ,0,0,0
BEGIN DESCRIPTION:
Mapping XS b24d4969
END DESCRIPTION:
XS GIS Cut Line= 3
      2285857.66      7167580.71      2285565.43      7168027.17
      2286374.76      7169251.91
#Sta/Elev= 30
  4488.6  779.57  4530.7  769.67  4977.8  771.06  5001.1  765.78  5034.6  764.57
  5036.3  764.07  5046.7  764.57  5055.7  767.32  5076.8  765.64  5091.8  769.66
  5097.8  767.51  5106.9  769.66  5200.2   770.3  5206.2  772.42  5215.3  769.98
  5221.3  772.33  5257.4  770.18  5784.1  773.97  5958.7  770.92  6103.1  774.24
  6145.2  778.48  6268.7  774.21  6304.8  775.57  6325.8   781.3  6340.9  781.28
  6346.9  785.59  6429.5  789.86  6434.2  788.39  6440.2  792.67  6490.2   790.7
#Mann= 4 ,-1 , 0
  4488.6     .05       0  5034.6    .033       0  5046.7     .05       0
  6429.5     .12       0
Bank Sta=5034.6,5046.7
XS Rating Curve= 0 ,0
Exp/Cntr=0.3,0.1

Chan Stop Cuts=-1
Use User Specified Reach Order=0
Composite Channel Slope=5