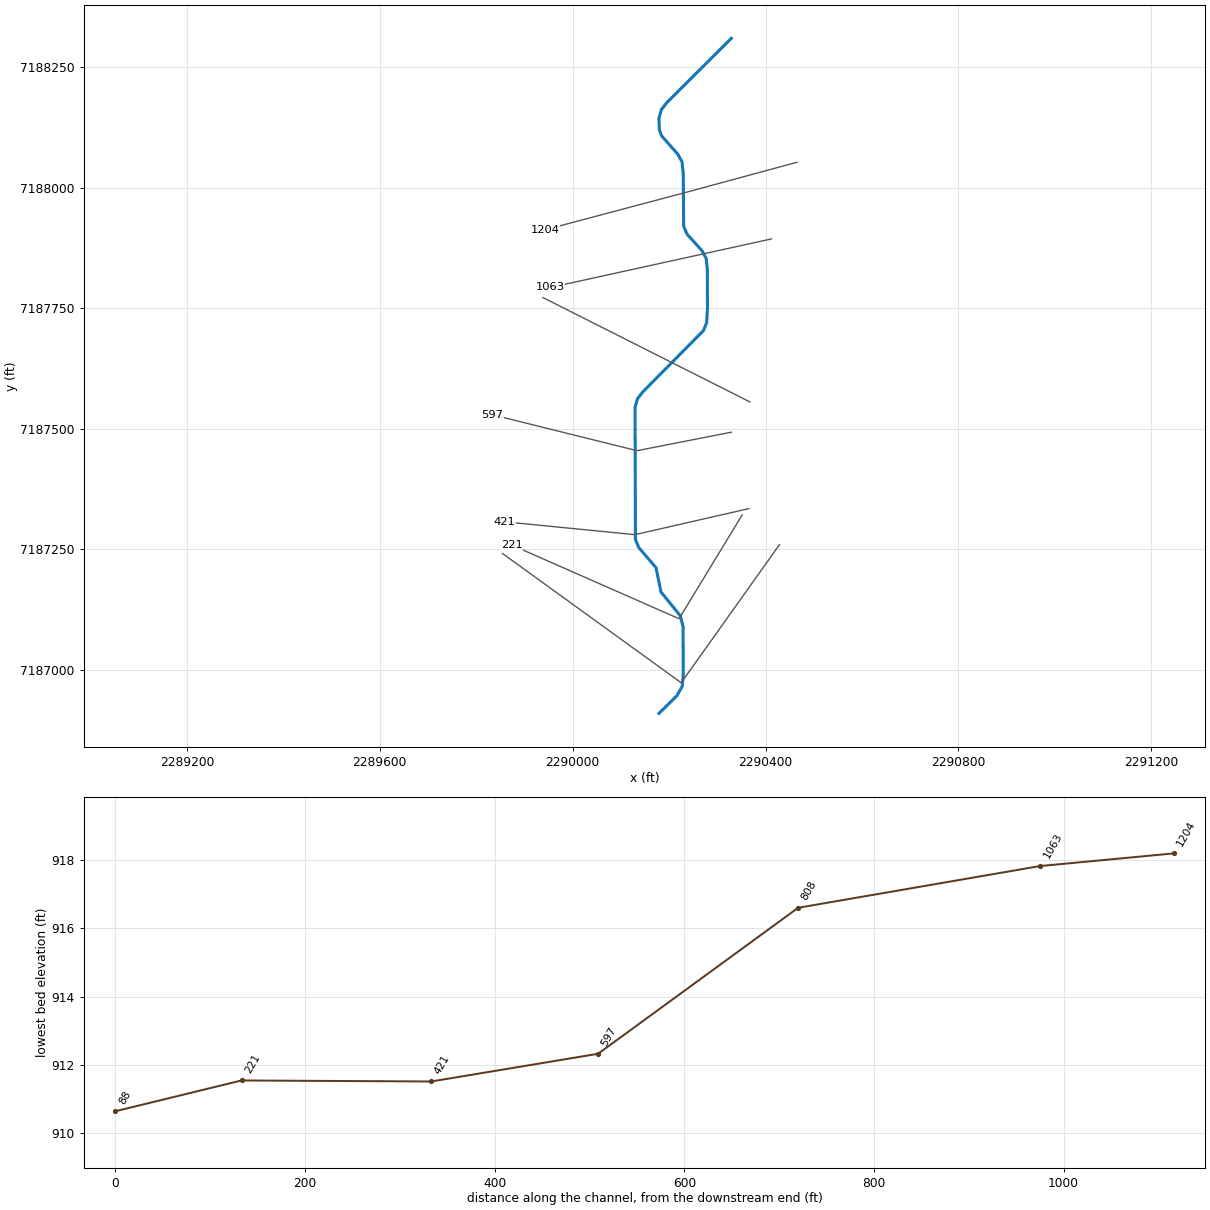
--- MDE S 002.prj (project) ---

Proj Title=MDE S 002 Base Level Engineering
Current Plan=p01
Default Exp/Contr=0.3,0.1
English Units
Geom File=g01
Flow File=f01
Plan File=p01
BEGIN DESCRIPTION:
MDE S 002
END DESCRIPTION:

--- MDE S 002.p01 (plan) ---

Plan Title=Multiple Run
Short Identifier=Multiple
Geom File=g01
Flow File=f01
Subcritical Flow
K Sum by GR= 0
Std Step Tol= 0.01
Critical Tol= 0.01
Num of Std Step Trials= 20
Max Error Tol= 0.3
Flow Tol Ratio= 0.001
Split Flow NTrial= 30
Split Flow Tol= 0.02
Split Flow Ratio= 0.02
Log Output Level= 0
Friction Slope Method= 1
Unsteady Friction Slope Method= 2
Unsteady Bridges Friction Slope Method= 1
Parabolic Critical Depth
Global Vel Dist=  1 , 1 , 1
Global Log Level= 0
CheckData=True
Encroach Param= -1, 0, 0, 0
BEGIN DESCRIPTION:
Multiple Run
END DESCRIPTION:

--- MDE S 002.f01 (steady flow) ---

Flow Title=Multiple
Number of Profiles=7
Profile Names=10-year,25-year,50-year,1pct_min,100-year,1pct_plu,500-year
River Rch & RM= MDE S 002,Reach-1,1204
     421     562     676     405     807    1611    1152
Boundary for River Rch & Prof#=MDE S 002,Reach-1,1
Up Type=0
Dn Type=3
Dn Slope=0.005
Boundary for River Rch & Prof#=MDE S 002,Reach-1,2
Up Type=0
Dn Type=3
Dn Slope=0.005
Boundary for River Rch & Prof#=MDE S 002,Reach-1,3
Up Type=0
Dn Type=3
Dn Slope=0.005
Boundary for River Rch & Prof#=MDE S 002,Reach-1,4
Up Type=0
Dn Type=3
Dn Slope=0.005
Boundary for River Rch & Prof#=MDE S 002,Reach-1,5
Up Type=0
Dn Type=3
Dn Slope=0.005
Boundary for River Rch & Prof#=MDE S 002,Reach-1,6
Up Type=0
Dn Type=3
Dn Slope=0.005
Boundary for River Rch & Prof#=MDE S 002,Reach-1,7
Up Type=0
Dn Type=3
Dn Slope=0.005

--- MDE S 002.g01 (geometry) ---

Geom Title=Existing Conditions

River Reach=MDE S 002,Reach-1
Reach XY= 30
      2290329.00      7188310.00      2290195.21      7188176.68
      2290184.08      7188162.30      2290178.95      7188144.66
      2290179.72      7188120.71      2290184.35      7188107.83
      2290218.08      7188069.67      2290226.70      7188054.07
      2290229.32      7188030.14      2290230.23      7187920.51
      2290237.15      7187903.95      2290268.15      7187869.65
      2290276.75      7187854.06      2290279.39      7187830.13
      2290279.55      7187749.81      2290277.96      7187720.44
      2290271.19      7187703.81      2290145.43      7187576.76
      2290134.46      7187562.45      2290129.38      7187544.84
      2290130.20      7187270.50      2290137.09      7187253.92
      2290172.88      7187212.18      2290183.19      7187161.74
      2290223.30      7187112.35      2290228.96      7187089.97
      2290229.40      7186989.87      2290227.12      7186965.79
      2290216.09      7186946.50      2290179.00      7186910.00

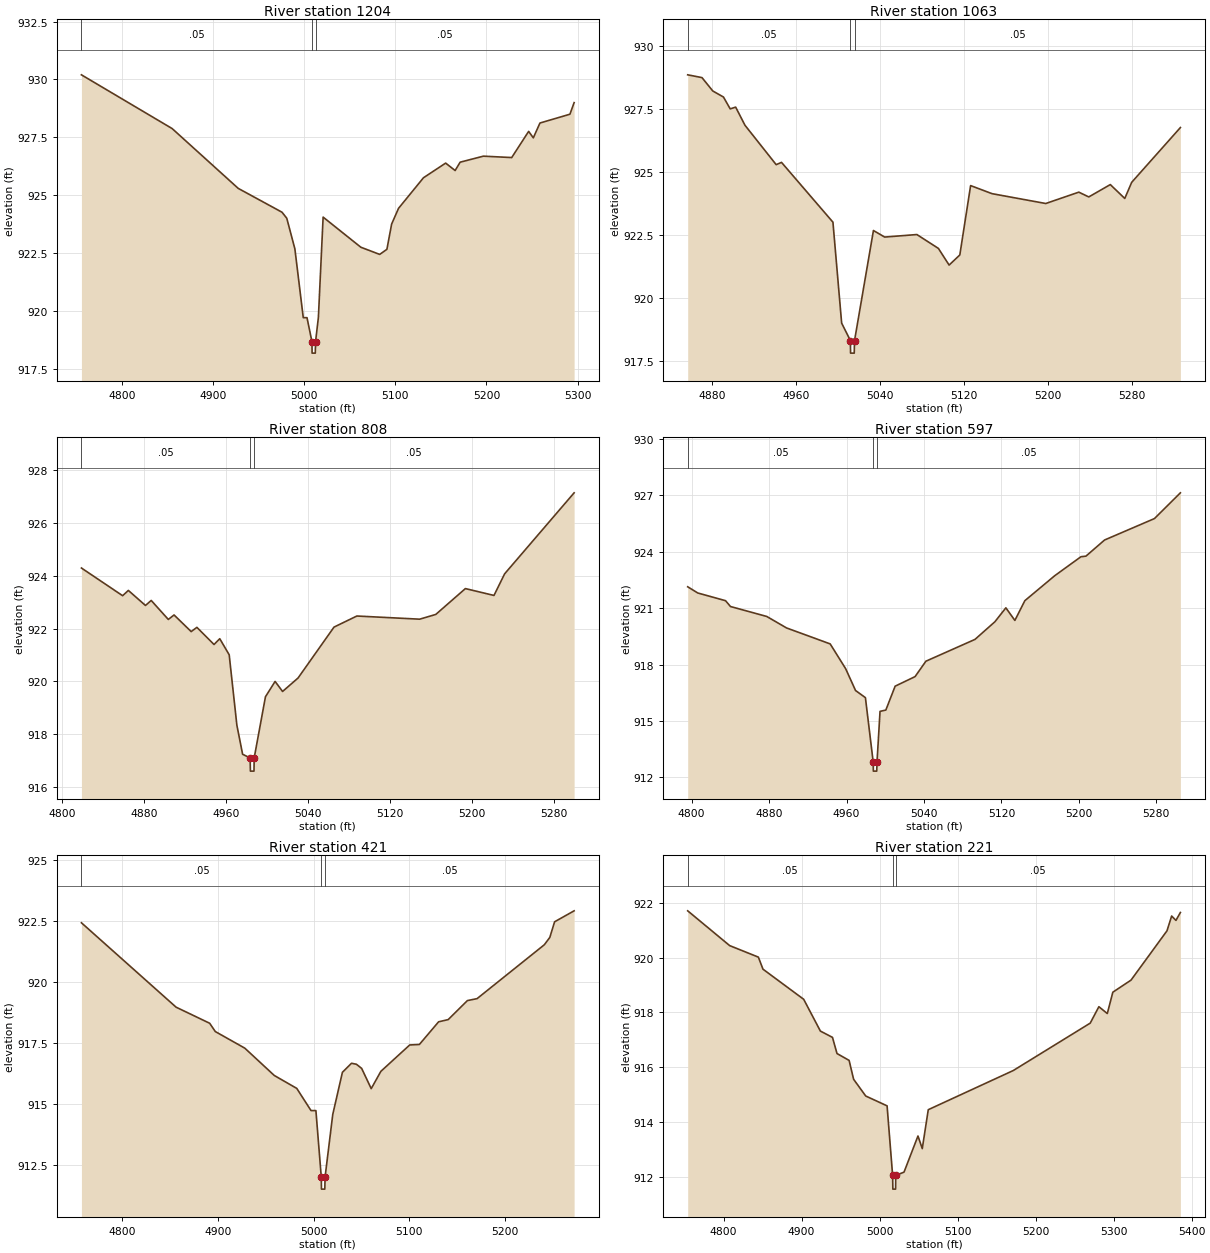
Type RM Length L Ch R = 1,1204,141,141,141
BEGIN DESCRIPTION:
MDE S 002 3.0
END DESCRIPTION:
XS GIS Cut Line= 3
      2290465.13      7188052.93      2290226.12      7187988.20
      2289942.76      7187912.98
#Sta/Elev= 30
  4755.4  930.20  4855.0  927.88  4927.5  925.30  4975.6  924.27  4980.8  924.01
  4989.7  922.69  4998.9  919.72  5003.0  919.72  5008.4  918.69  5008.6  918.19
  5012.1  918.19  5012.4  918.69  5015.5  919.73  5020.7  924.06  5062.1  922.76
  5082.8  922.45  5090.7  922.67  5095.9  923.76  5103.5  924.44  5130.9  925.76
  5155.2  926.39  5165.6  926.07  5171.1  926.43  5196.6  926.69  5227.7  926.63
  5246.3  927.76  5251.4  927.48  5258.7  928.12  5291.6  928.50  5296.2  929.00
#Mann=3,-1,0
  4755.4    0.05       0  5008.4   0.033       0  5012.4    0.05       0
Bank Sta=5008.4,5012.4
Exp/Cntr=0.3,0.1

Type RM Length L Ch R = 1,1063,255,255,255
BEGIN DESCRIPTION:
Mapping XS 2213ba29
END DESCRIPTION:
XS GIS Cut Line= 2
      2290412.30      7187893.97      2289953.72      7187793.31
#Sta/Elev= 30
  4857.0  928.85  4870.6  928.74  4880.9  928.21  4891.1  927.97  4897.5  927.50
  4902.7  927.57  4911.6  926.85  4941.3  925.29  4946.4  925.38  4995.4  923.01
  5003.7  919.01  5012.0  918.32  5012.2  917.82  5015.7  917.82  5016.0  918.32
  5034.0  922.68  5044.7  922.42  5075.4  922.52  5095.9  921.97  5106.1  921.31
  5116.3  921.71  5126.6  924.46  5147.0  924.14  5198.2  923.75  5229.7  924.20
  5239.2  924.01  5259.7  924.50  5273.5  923.95  5280.1  924.59  5326.5  926.76
#Mann=3,-1,0
  4857.0    0.05       0  5012.0   0.033       0  5016.0    0.05       0
Bank Sta=5012,5016
Exp/Cntr=0.3,0.1

Type RM Length L Ch R = 1,808,211,211,211
BEGIN DESCRIPTION:
Mapping XS c66308a5
END DESCRIPTION:
XS GIS Cut Line= 2
      2290367.76      7187555.85      2289938.46      7187772.34
#Sta/Elev= 30
  4819.2  924.30  4859.4  923.25  4865.0  923.45  4881.7  922.88  4887.3  923.07
  4904.0  922.35  4909.6  922.52  4926.3  921.89  4931.9  922.05  4948.6  921.40
  4954.2  921.62  4963.4  921.01  4970.9  918.34  4976.5  917.24  4983.8  917.10
  4984.1  916.60  4987.6  916.60  4987.8  917.10  4998.8  919.42  5008.2  920.00
  5015.5  919.62  5030.6  920.13  5065.7  922.06  5088.0  922.48  5149.3  922.36
  5165.0  922.54  5193.9  923.52  5221.8  923.26  5232.2  924.08  5300.0  927.15
#Mann=3,-1,0
  4819.2    0.05       0  4983.8   0.033       0  4987.8    0.05       0
Bank Sta=4983.8,4987.8
Exp/Cntr=0.3,0.1

Type RM Length L Ch R = 1,597,176,176,176
BEGIN DESCRIPTION:
Mapping XS ce39ce27
END DESCRIPTION:
XS GIS Cut Line= 3
      2290329.16      7187493.14      2290133.41      7187454.81
      2289833.01      7187529.45
#Sta/Elev= 30
  4795.9  922.14  4806.3  921.81  4835.0  921.40  4840.1  921.09  4877.6  920.56
  4898.0  919.95  4943.1  919.10  4959.1  917.78  4969.3  916.62  4979.5  916.24
  4987.5  912.83  4987.7  912.33  4991.2  912.33  4991.5  912.83  4994.6  915.51
  5000.6  915.58  5010.2  916.85  5030.8  917.36  5042.0  918.18  5092.7  919.34
  5113.3  920.28  5124.6  921.02  5133.9  920.35  5144.2  921.40  5175.1  922.73
  5202.2  923.74  5207.3  923.77  5226.6  924.63  5278.1  925.77  5304.9  927.14
#Mann=3,-1,0
  4795.9    0.05       0  4987.5   0.033       0  4991.5    0.05       0
Bank Sta=4987.5,4991.5
Exp/Cntr=0.3,0.1

Type RM Length L Ch R = 1,421,200,200,200
BEGIN DESCRIPTION:
Mapping XS 5e96dd58
END DESCRIPTION:
XS GIS Cut Line= 3
      2290365.43      7187334.67      2290129.14      7187280.63
      2289858.05      7187307.43
#Sta/Elev= 30
  4757.5  922.44  4856.4  918.98  4891.5  918.32  4897.4  917.98  4928.2  917.30
  4959.0  916.18  4982.5  915.65  4997.4  914.74  5002.5  914.74  5008.1  912.02
  5008.3  911.52  5011.8  911.52  5012.1  912.02  5020.1  914.58  5030.2  916.31
  5039.7  916.68  5044.8  916.64  5050.3  916.47  5060.3  915.64  5070.4  916.35
  5100.5  917.43  5110.6  917.45  5130.7  918.38  5140.7  918.47  5160.8  919.25
  5170.9  919.33  5241.2  921.54  5246.9  921.84  5251.9  922.48  5272.3  922.93
#Mann=3,-1,0
  4757.5    0.05       0  5008.1   0.033       0  5012.1    0.05       0
Bank Sta=5008.1,5012.1
Exp/Cntr=0.3,0.1

Type RM Length L Ch R = 1,221,133,133,133
BEGIN DESCRIPTION:
Mapping XS 1b8d526b
END DESCRIPTION:
XS GIS Cut Line= 3
      2290351.59      7187321.60      2290220.66      7187106.30
      2289873.23      7187259.27
#Sta/Elev= 30
  4754.0  921.71  4807.8  920.44  4844.6  920.02  4850.5  919.58  4902.7  918.48
  4924.1  917.32  4939.6  917.09  4945.4  916.50  4960.9  916.25  4966.7  915.56
  4982.2  914.95  5009.6  914.59  5016.7  912.05  5017.0  911.55  5020.5  911.55
  5020.7  912.05  5031.3  912.17  5049.2  913.49  5054.7  913.03  5062.4  914.45
  5171.4  915.88  5270.0  917.61  5281.1  918.21  5291.9  917.96  5299.0  918.74
  5322.3  919.18  5368.4  920.98  5374.4  921.52  5379.9  921.36  5385.6  921.65
#Mann=3,-1,0
  4754.0    0.05       0  5016.7   0.033       0  5020.7    0.05       0
Bank Sta=5016.7,5020.7
Exp/Cntr=0.3,0.1

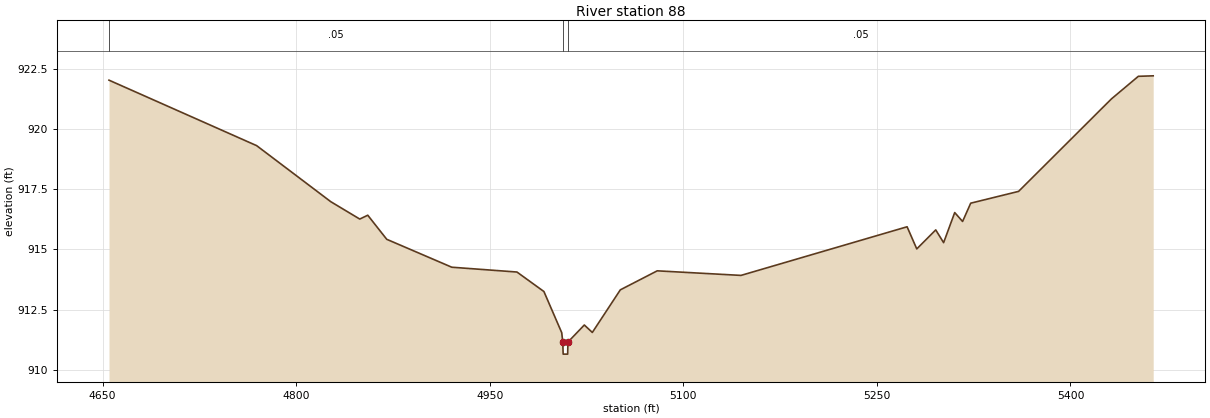
Type RM Length L Ch R = 1,88,0,0,0
BEGIN DESCRIPTION:
MDE S 002 1.0
END DESCRIPTION:
XS GIS Cut Line= 3
      2290429.03      7187260.04      2290225.08      7186973.52
      2289854.47      7187241.62
#Sta/Elev= 30
  4655.0  922.03  4769.4  919.31  4826.9  916.98  4849.3  916.26  4855.5  916.42
  4870.2  915.42  4920.6  914.26  4971.1  914.06  4992.0  913.25  5005.8  911.54
  5006.6  911.15  5006.9  910.65  5010.4  910.65  5010.6  911.15  5023.3  911.86
  5029.5  911.55  5051.2  913.32  5079.8  914.11  5144.7  913.92  5273.4  915.94
  5280.9  915.02  5295.6  915.81  5301.7  915.28  5310.3  916.53  5316.4  916.16
  5322.7  916.92  5359.8  917.41  5431.7  921.25  5452.6  922.19  5464.1  922.21
#Mann=3,-1,0
  4655.0    0.05       0  5006.6   0.033       0  5010.6    0.05       0
Bank Sta=5006.6,5010.6
Exp/Cntr=0.3,0.1

Chan Stop Cuts=-1