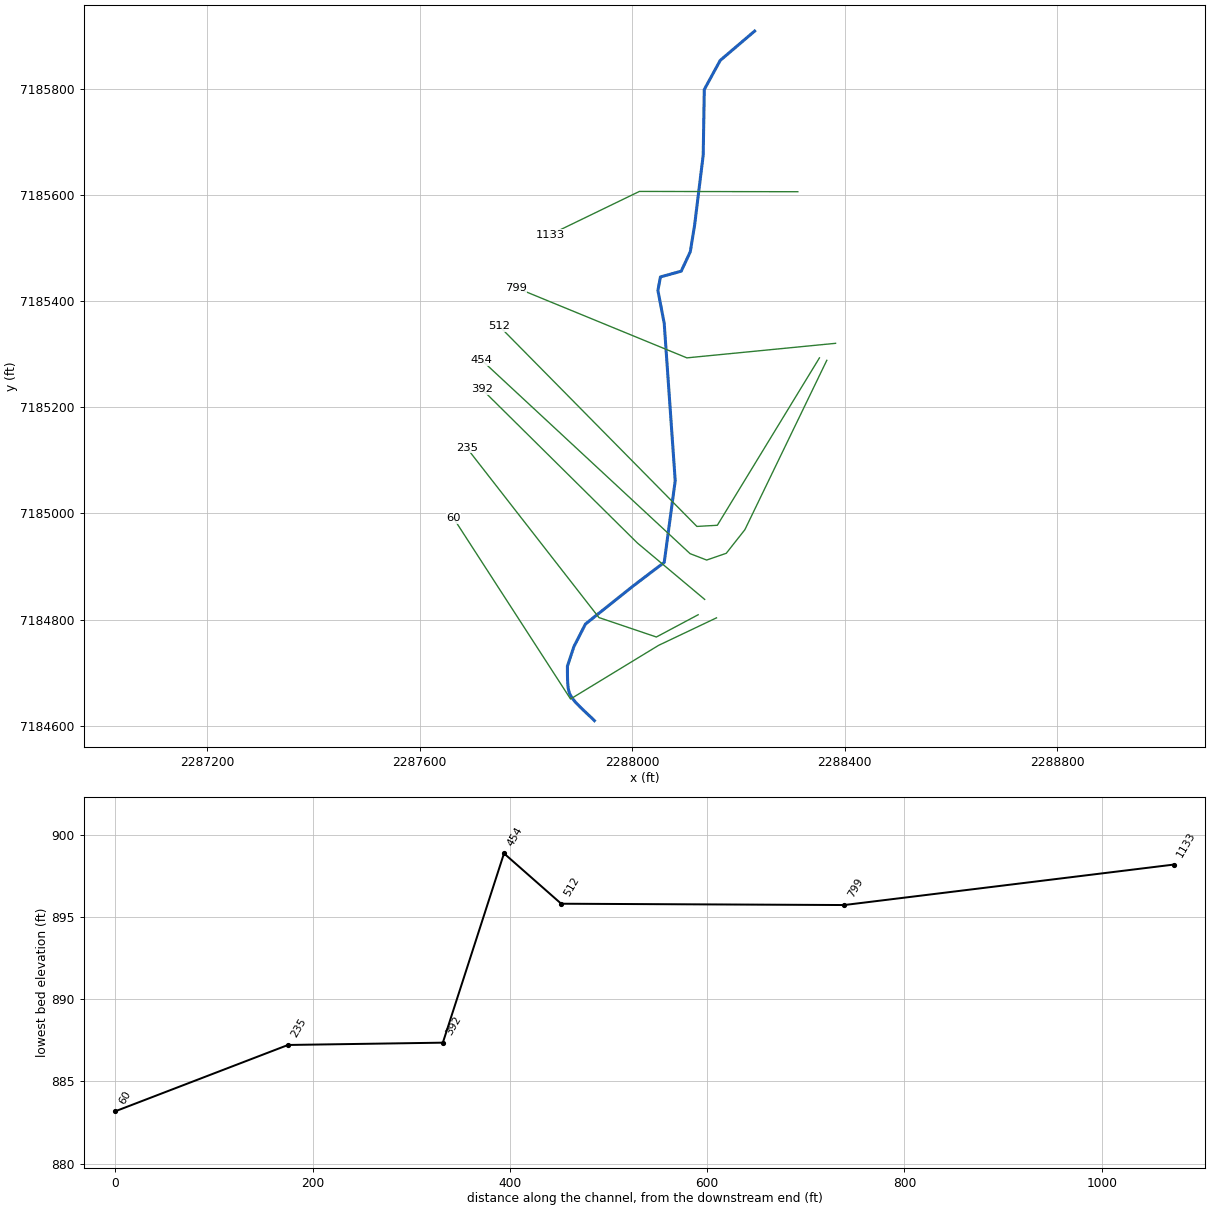
--- MDE S 003.prj (project) ---

Proj Title=MDE S 003 Base Level Engineering
Current Plan=p01
Default Exp/Contr=0.3,0.1
English Units
Geom File=g01
Flow File=f01
Plan File=p01
BEGIN DESCRIPTION:
MDE S 003
END DESCRIPTION:

--- MDE S 003.p01 (plan) ---

Plan Title=Multiple Run
Short Identifier=Multiple
Geom File=g01
Flow File=f01
Subcritical Flow
K Sum by GR= 0
Std Step Tol= 0.01
Critical Tol= 0.01
Num of Std Step Trials= 20
Max Error Tol= 0.3
Flow Tol Ratio= 0.001
Split Flow NTrial= 30
Split Flow Tol= 0.02
Split Flow Ratio= 0.02
Log Output Level= 0
Friction Slope Method= 1
Unsteady Friction Slope Method= 2
Unsteady Bridges Friction Slope Method= 1
Parabolic Critical Depth
Global Vel Dist=  1 , 1 , 1
Global Log Level= 0
CheckData=True
Encroach Param= -1, 0, 0, 0
BEGIN DESCRIPTION:
Multiple Run
END DESCRIPTION:

--- MDE S 003.f01 (steady flow) ---

Flow Title=Multiple
Number of Profiles=7
Profile Names=10-year,25-year,50-year,1pct_min,100-year,1pct_plu,500-year
River Rch & RM= MDE S 003,Reach-1,1133
     368     488     585     349     696    1389     987
Boundary for River Rch & Prof#=MDE S 003,Reach-1,1
Up Type=0
Dn Type=3
Dn Slope=0.005
Boundary for River Rch & Prof#=MDE S 003,Reach-1,2
Up Type=0
Dn Type=3
Dn Slope=0.005
Boundary for River Rch & Prof#=MDE S 003,Reach-1,3
Up Type=0
Dn Type=3
Dn Slope=0.005
Boundary for River Rch & Prof#=MDE S 003,Reach-1,4
Up Type=0
Dn Type=3
Dn Slope=0.005
Boundary for River Rch & Prof#=MDE S 003,Reach-1,5
Up Type=0
Dn Type=3
Dn Slope=0.005
Boundary for River Rch & Prof#=MDE S 003,Reach-1,6
Up Type=0
Dn Type=3
Dn Slope=0.005
Boundary for River Rch & Prof#=MDE S 003,Reach-1,7
Up Type=0
Dn Type=3
Dn Slope=0.005

--- MDE S 003.g01 (geometry) ---

Geom Title=Existing Conditions

River Reach=MDE S 003,Reach-1
Reach XY= 30
      2288230.65      7185908.11      2288165.82      7185852.92
      2288135.86      7185798.08      2288133.82      7185674.68
      2288117.70      7185543.35      2288109.49      7185492.62
      2288092.42      7185456.09      2288053.30      7185445.31
      2288048.55      7185419.80      2288060.42      7185357.70
      2288081.12      7185061.62      2288060.46      7184907.97
      2288001.72      7184863.30      2287912.16      7184791.86
      2287890.39      7184749.31      2287878.20      7184712.52
      2287878.27      7184694.96      2287878.52      7184685.00
      2287879.19      7184675.22      2287879.82      7184670.46
      2287880.77      7184665.83      2287882.19      7184661.40
      2287884.05      7184657.45      2287886.36      7184653.68
      2287888.99      7184650.05      2287891.87      7184646.52
      2287895.04      7184642.95      2287903.09      7184634.72
      2287926.73      7184612.28      2287929.00      7184610.00

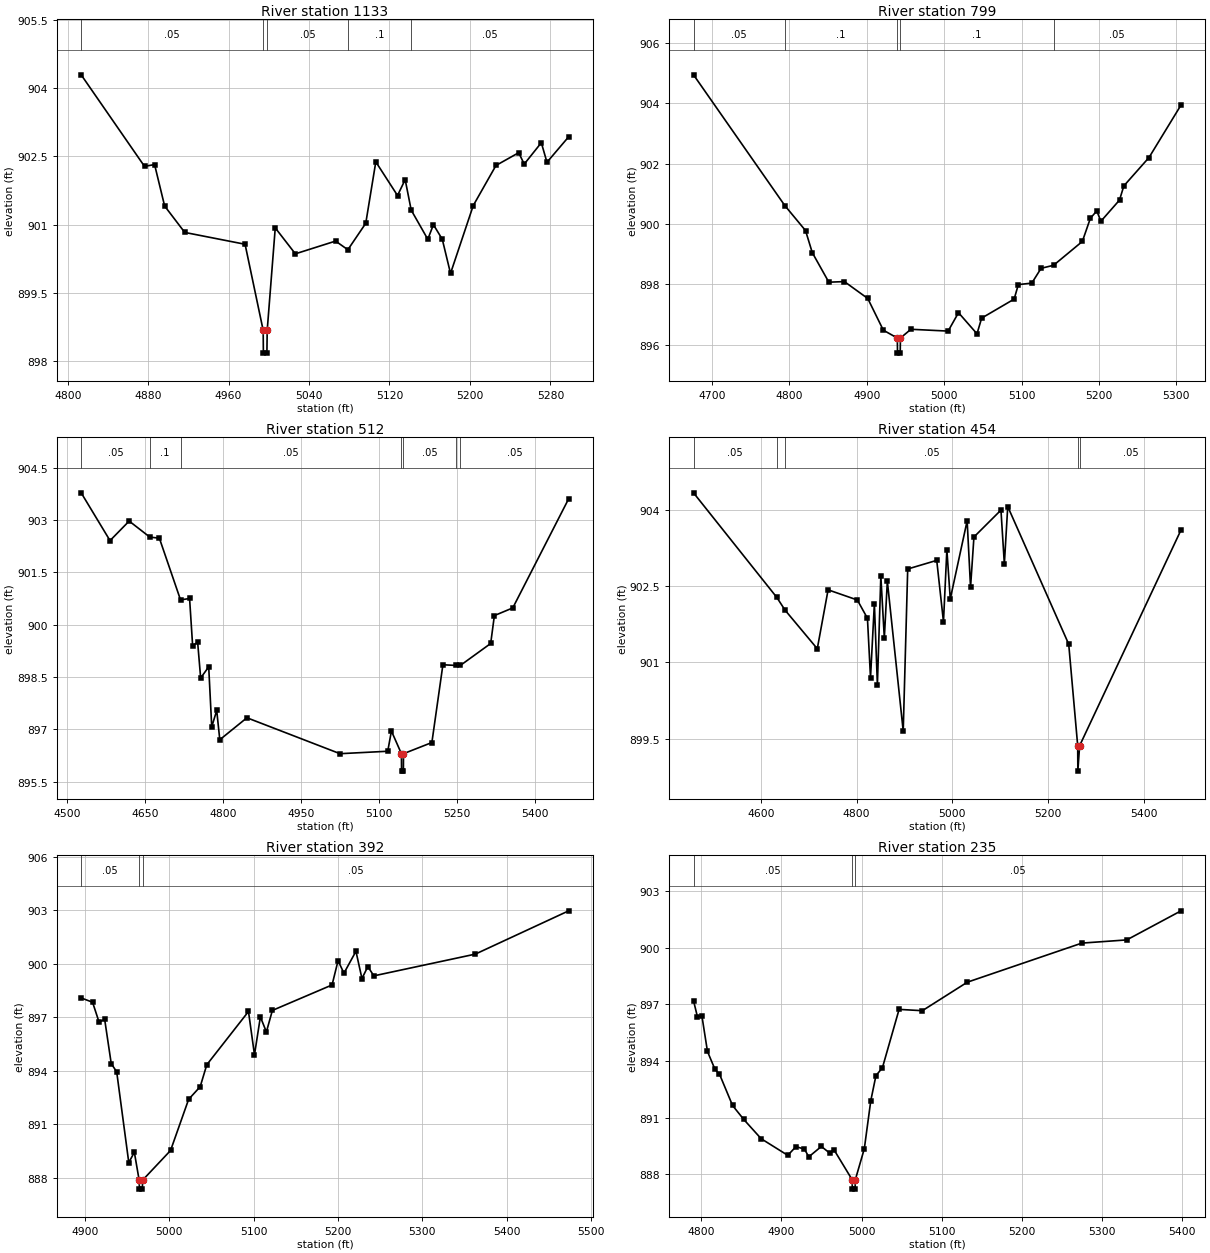
Type RM Length L Ch R = 1,1133,334,334,334
BEGIN DESCRIPTION:
MDE S 003 3.0
END DESCRIPTION:
XS GIS Cut Line= 3
      2288311.99      7185605.69      2288013.68      7185606.25
      2287845.85      7185524.95
#Sta/Elev= 30
  4813.4  904.29  4876.4  902.28  4886.4  902.32  4896.4  901.41  4916.4  900.83
  4976.4  900.57  4994.4  898.68  4994.6  898.18  4998.1  898.18  4998.4  898.68
  5006.4  900.93  5026.4  900.36  5066.4  900.64  5078.6  900.45  5096.4  901.03
  5106.4  902.38  5128.0  901.64  5135.6  901.99  5141.6  901.32  5158.1  900.68
  5163.7  901.00  5172.5  900.68  5180.7  899.93  5203.3  901.42  5225.9  902.30
  5248.5  902.58  5254.0  902.33  5271.0  902.80  5276.6  902.37  5298.2  902.93
#Mann=5,-1,0
  4813.4    0.05       0  4994.4   0.033       0  4998.4    0.05       0
  5078.6     0.1       0  5141.6    0.05       0
Bank Sta=4994.4,4998.4
Exp/Cntr=0.3,0.1

Type RM Length L Ch R = 1,799,287,287,287
BEGIN DESCRIPTION:
Mapping XS 01a7d610
END DESCRIPTION:
XS GIS Cut Line= 4
      2288383.00      7185320.30      2288103.06      7185292.92
      2287830.60      7185404.79      2287780.66      7185425.30
#Sta/Elev= 30
  4676.3  904.94  4794.2  900.61  4821.0  899.78  4829.7  899.05  4851.1  898.07
  4871.2  898.09  4901.4  897.53  4921.5  896.48  4939.6  896.22  4939.8  895.72
  4943.3  895.72  4943.6  896.22  4957.1  896.51  5005.2  896.45  5018.6  897.06
  5042.5  896.36  5048.5  896.88  5090.5  897.51  5095.9  897.99  5113.3  898.04
  5125.3  898.53  5141.4  898.63  5178.6  899.42  5189.0  900.19  5197.2  900.43
  5202.6  900.09  5226.6  900.79  5232.2  901.26  5264.7  902.20  5306.1  903.94
#Mann=5,-1,0
  4676.3    0.05       0  4794.2     0.1       0  4939.6    0.07       0
  4943.6     0.1       0  5141.4    0.05       0
Bank Sta=4939.6,4943.6
Exp/Cntr=0.3,0.1

Type RM Length L Ch R = 1,512,58,58,58
BEGIN DESCRIPTION:
Mapping XS bed24722
END DESCRIPTION:
XS GIS Cut Line= 4
      2288352.63      7185292.90      2288160.38      7184977.75
      2288121.93      7184975.60      2287749.74      7185352.83
#Sta/Elev= 30
  4526.7  903.78  4582.2  902.41  4619.0  902.97  4658.8  902.51  4677.1  902.48
  4717.8  900.71  4735.2  900.75  4741.1  899.39  4750.7  899.50  4756.5  898.47
  4772.0  898.79  4777.8  897.07  4787.4  897.54  4793.3  896.70  4845.5  897.33
  5024.5  896.30  5116.3  896.37  5123.4  896.95  5142.6  896.30  5142.9  895.80
  5146.4  895.80  5146.6  896.30  5201.2  896.62  5222.4  898.85  5248.4  898.83
  5255.9  898.83  5314.3  899.46  5321.4  900.26  5356.8  900.48  5464.3  903.61
#Mann=7,-1,0
  4526.7    0.05       0  4658.8     0.1       0  4717.8    0.05       0
  5142.6   0.033       0  5146.6    0.05       0  5248.4     0.1       0
  5255.9    0.05       0
Bank Sta=5142.6,5146.6
Exp/Cntr=0.3,0.1

Type RM Length L Ch R = 1,454,62,62,62
BEGIN DESCRIPTION:
Mapping XS 6a92c99e
END DESCRIPTION:
XS GIS Cut Line= 6
      2288366.51      7185288.33      2288212.26      7184969.45
      2288177.19      7184925.01      2288140.32      7184912.30
      2288109.13      7184924.33      2287716.36      7185289.00
#Sta/Elev= 30
  4458.9  904.34  4633.1  902.28  4650.3  902.03  4717.7  901.27  4740.3  902.43
  4801.4  902.23  4822.6  901.87  4829.0  900.70  4837.1  902.16  4843.4  900.56
  4850.6  902.70  4857.9  901.48  4864.2  902.60  4897.4  899.65  4906.8  902.84
  4967.5  903.01  4981.6  901.80  4988.7  903.22  4995.8  902.25  5031.1  903.79
  5038.2  902.48  5045.3  903.47  5101.8  904.00  5108.9  902.94  5116.0  904.07
  5243.5  901.36  5262.3  899.36  5262.6  898.86  5266.3  899.36  5478.4  903.61
#Mann=5,-1,0
  4458.9    0.05       0  4633.1     0.1       0  4650.3    0.05       0
  5262.3   0.033       0  5266.3    0.05       0
Bank Sta=5262.3,5266.3
Exp/Cntr=0.3,0.1

Type RM Length L Ch R = 1,392,157,157,157
BEGIN DESCRIPTION:
Mapping XS a5450843
END DESCRIPTION:
XS GIS Cut Line= 3
      2288136.60      7184838.21      2288009.79      7184944.50
      2287716.91      7185234.32
#Sta/Elev= 30
  4895.8  898.08  4909.3  897.84  4917.1  896.71  4923.6  896.89  4931.4  894.40
  4937.9  893.93  4952.2  888.84  4958.8  889.42  4964.5  887.85  4964.8  887.35
  4968.3  887.35  4968.5  887.85  5001.7  889.52  5023.1  892.39  5036.8  893.10
  5044.6  894.33  5094.0  897.32  5101.1  894.89  5108.1  897.02  5115.2  896.17
  5122.3  897.38  5193.0  898.81  5200.1  900.17  5207.1  899.47  5221.3  900.70
  5228.4  899.17  5235.4  899.84  5242.5  899.32  5362.7  900.54  5473.3  902.97
#Mann=3,-1,0
  4895.8    0.05       0  4964.5   0.033       0  4968.5    0.05       0
Bank Sta=4964.5,4968.5
Exp/Cntr=0.3,0.1

Type RM Length L Ch R = 1,235,175,175,175
BEGIN DESCRIPTION:
Mapping XS ee8cbf51
END DESCRIPTION:
XS GIS Cut Line= 4
      2288124.33      7184809.34      2288045.67      7184767.43
      2287937.54      7184804.03      2287688.64      7185123.54
#Sta/Elev= 30
  4790.4  897.19  4795.2  896.35  4800.9  896.37  4807.8  894.50  4817.2  893.55
  4822.8  893.30  4839.1  891.64  4853.1  890.90  4874.8  889.88  4908.0  889.00
  4918.2  889.46  4928.8  889.33  4934.2  888.92  4949.9  889.47  4960.3  889.12
  4965.6  889.30  4988.3  887.71  4988.5  887.21  4992.0  887.21  4992.3  887.71
  5003.5  889.35  5011.6  891.90  5018.0  893.22  5026.1  893.64  5046.9  896.73
  5075.9  896.66  5132.0  898.17  5274.9  900.24  5331.0  900.41  5398.7  901.95
#Mann=3,-1,0
  4790.4    0.05       0  4988.3   0.033       0  4992.3    0.05       0
Bank Sta=4988.3,4992.3
Exp/Cntr=0.3,0.1

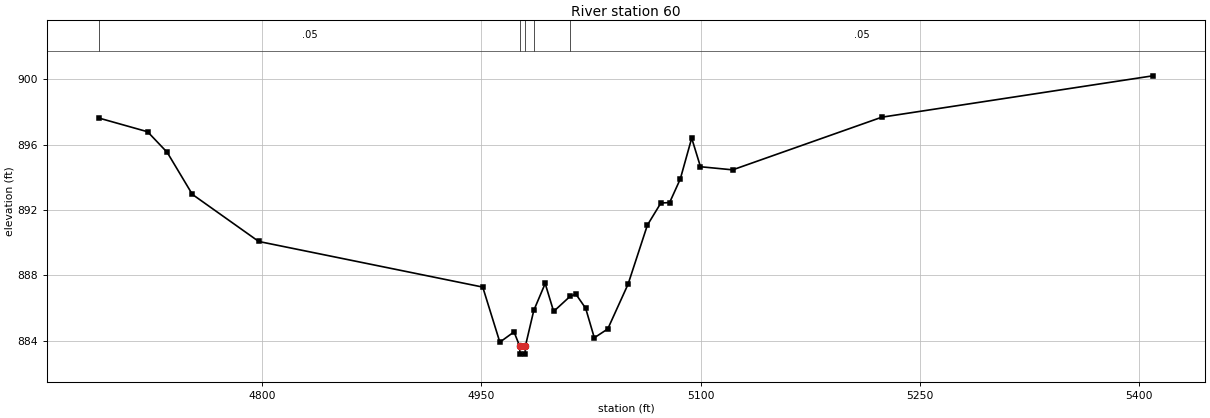
Type RM Length L Ch R = 1,60,0,0,0
BEGIN DESCRIPTION:
MDE S 003 1.0
END DESCRIPTION:
XS GIS Cut Line= 4
      2288158.85      7184803.51      2288049.71      7184751.64
      2287884.05      7184650.71      2287663.75      7184991.25
#Sta/Elev= 30
  4688.8  897.61  4721.8  896.78  4735.2  895.52  4752.4  892.95  4797.8  890.07
  4951.0  887.28  4962.7  883.91  4972.4  884.54  4976.2  883.68  4976.5  883.18
  4980.0  883.18  4980.2  883.68  4985.9  885.85  4993.7  887.50  4999.5  885.79
  5010.7  886.71  5014.7  886.85  5021.4  885.98  5027.3  884.18  5036.5  884.72
  5050.4  887.46  5063.6  891.07  5072.8  892.42  5078.8  892.45  5086.1  893.89
  5093.9  896.39  5099.9  894.64  5121.9  894.45  5223.9  897.67  5409.2  900.20
#Mann=5,-1,0
  4688.8    0.05       0  4976.2    0.07       0  4980.2    0.05       0
  4985.9    0.12       0  5010.7    0.05       0
Bank Sta=4976.2,4980.2
Exp/Cntr=0.3,0.1

Chan Stop Cuts=-1