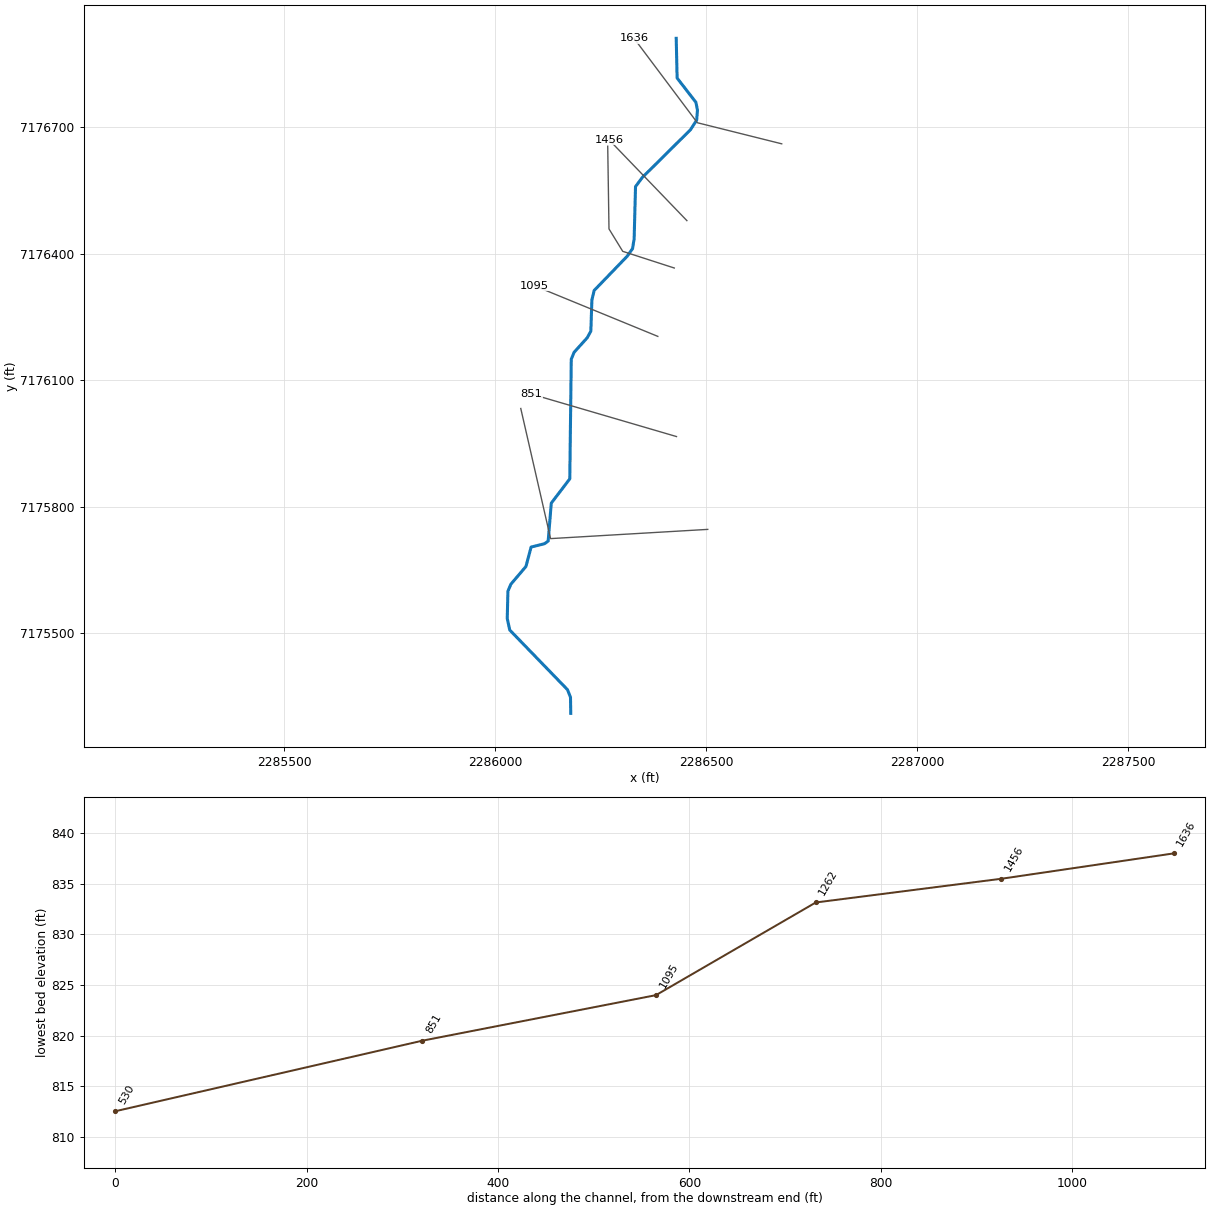
--- MDE S 004.prj (project) ---

Proj Title=MDE S 004 Base Level Engineering
Current Plan=p01
Default Exp/Contr=0.3,0.1
English Units
Geom File=g01
Flow File=f01
Plan File=p01
BEGIN DESCRIPTION:
MDE S 004
END DESCRIPTION:

--- MDE S 004.p01 (plan) ---

Plan Title=Multiple Run
Short Identifier=Multiple
Geom File=g01
Flow File=f01
Subcritical Flow
K Sum by GR= 0
Std Step Tol= 0.01
Critical Tol= 0.01
Num of Std Step Trials= 20
Max Error Tol= 0.3
Flow Tol Ratio= 0.001
Split Flow NTrial= 30
Split Flow Tol= 0.02
Split Flow Ratio= 0.02
Log Output Level= 0
Friction Slope Method= 1
Unsteady Friction Slope Method= 2
Unsteady Bridges Friction Slope Method= 1
Parabolic Critical Depth
Global Vel Dist=  1 , 1 , 1
Global Log Level= 0
CheckData=True
Encroach Param= -1, 0, 0, 0
BEGIN DESCRIPTION:
Multiple Run
END DESCRIPTION:

--- MDE S 004.f01 (steady flow) ---

Flow Title=Multiple
Number of Profiles=7
Profile Names=10-year,25-year,50-year,1pct_min,100-year,1pct_plu,500-year
River Rch & RM= MDE S 004,Reach-1,1636
     217     279     327     191     382     762     520
Boundary for River Rch & Prof#=MDE S 004,Reach-1,1
Up Type=0
Dn Type=3
Dn Slope=0.005
Boundary for River Rch & Prof#=MDE S 004,Reach-1,2
Up Type=0
Dn Type=3
Dn Slope=0.005
Boundary for River Rch & Prof#=MDE S 004,Reach-1,3
Up Type=0
Dn Type=3
Dn Slope=0.005
Boundary for River Rch & Prof#=MDE S 004,Reach-1,4
Up Type=0
Dn Type=3
Dn Slope=0.005
Boundary for River Rch & Prof#=MDE S 004,Reach-1,5
Up Type=0
Dn Type=3
Dn Slope=0.005
Boundary for River Rch & Prof#=MDE S 004,Reach-1,6
Up Type=0
Dn Type=3
Dn Slope=0.005
Boundary for River Rch & Prof#=MDE S 004,Reach-1,7
Up Type=0
Dn Type=3
Dn Slope=0.005

--- MDE S 004.g01 (geometry) ---

Geom Title=Existing Conditions

River Reach=MDE S 004,Reach-1
Reach XY= 30
      2286429.00      7176910.00      2286431.13      7176815.86
      2286475.70      7176758.26      2286479.38      7176739.79
      2286477.39      7176716.03      2286462.78      7176693.32
      2286348.61      7176580.16      2286332.54      7176558.53
      2286329.27      7176434.89      2286325.44      7176411.47
      2286312.53      7176393.25      2286234.54      7176312.42
      2286229.13      7176289.95      2286226.64      7176215.98
      2286218.10      7176200.37      2286187.14      7176166.06
      2286180.22      7176149.50      2286176.74      7175865.93
      2286132.88      7175808.33      2286125.50      7175718.48
      2286116.88      7175712.16      2286085.02      7175704.21
      2286072.78      7175658.13      2286037.03      7175616.10
      2286030.07      7175599.47      2286028.50      7175534.96
      2286034.40      7175507.57      2286171.24      7175366.21
      2286178.41      7175348.16      2286179.00      7175310.00

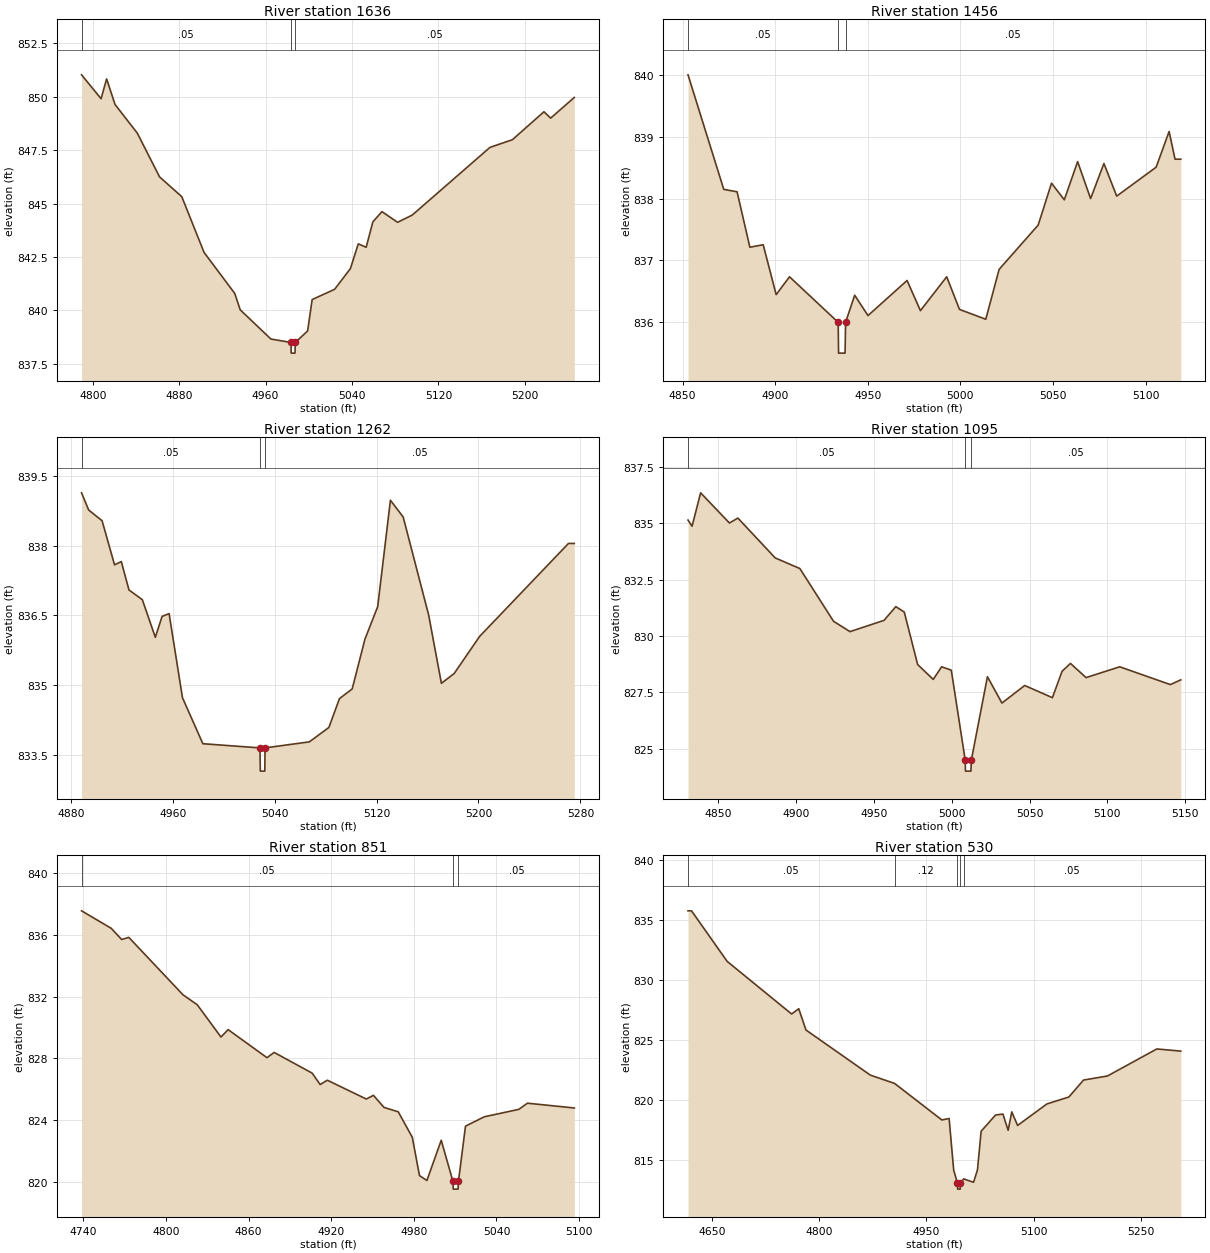
Type RM Length L Ch R = 1,1636,180,180,180
BEGIN DESCRIPTION:
MDE S 004 2.0
END DESCRIPTION:
XS GIS Cut Line= 3
      2286679.03      7176659.99      2286479.00      7176710.00
      2286328.99      7176910.01
#Sta/Elev= 30
  4789.6  851.03  4807.7  849.91  4812.8  850.84  4820.6  849.64  4841.2  848.30
  4861.8  846.25  4882.4  845.32  4903.0  842.71  4931.4  840.79  4936.5  840.02
  4964.9  838.65  4983.5  838.49  4983.7  837.99  4987.2  837.99  4987.5  838.49
  4998.9  839.03  5003.1  840.50  5023.9  840.98  5038.5  841.95  5045.8  843.11
  5053.1  842.95  5059.3  844.14  5067.7  844.62  5082.2  844.12  5095.8  844.46
  5167.7  847.63  5188.5  847.99  5217.7  849.30  5223.9  849.00  5245.8  849.97
#Mann=3,-1,0
  4789.6    0.05       0  4983.5   0.033       0  4987.5    0.05       0
Bank Sta=4983.5,4987.5
Exp/Cntr=0.3,0.1

Type RM Length L Ch R = 1,1456,194,194,194
BEGIN DESCRIPTION:
Mapping XS 0984e076
END DESCRIPTION:
XS GIS Cut Line= 2
      2286454.28      7176477.93      2286269.70      7176669.60
#Sta/Elev= 30
  4852.9  840.01  4872.2  838.15  4879.4  838.11  4886.3  837.21  4893.5  837.25
  4900.5  836.44  4907.7  836.73  4934.0  835.99  4934.2  835.49  4937.7  835.49
  4938.0  835.99  4942.9  836.43  4950.1  836.10  4971.2  836.67  4978.4  836.18
  4992.6  836.73  4999.5  836.20  5013.7  836.04  5020.9  836.85  5042.0  837.57
  5049.2  838.25  5056.1  837.98  5063.3  838.60  5070.3  838.00  5077.5  838.57
  5084.4  838.04  5105.7  838.51  5112.7  839.09  5115.9  838.64  5119.0  838.64
#Mann=3,-1,0
  4852.9    0.05       0  4934.0   0.033       0  4938.0    0.05       0
Bank Sta=4934,4938
Exp/Cntr=0.3,0.1

Type RM Length L Ch R = 1,1262,167,167,167
BEGIN DESCRIPTION:
Mapping XS a03ec9a7
END DESCRIPTION:
XS GIS Cut Line= 4
      2286424.37      7176365.63      2286302.22      7176405.14
      2286269.65      7176458.28      2286266.64      7176654.25
#Sta/Elev= 30
  4888.5  839.14  4894.1  838.77  4904.6  838.54  4914.4  837.59  4919.7  837.66
  4925.7  837.05  4936.2  836.84  4946.4  836.03  4951.7  836.48  4957.2  836.54
  4967.7  834.73  4983.7  833.74  5028.5  833.65  5028.8  833.15  5032.3  833.15
  5032.5  833.65  5067.3  833.78  5082.6  834.09  5090.9  834.71  5100.9  834.92
  5110.9  835.99  5120.9  836.69  5130.9  838.98  5140.9  838.62  5160.9  836.51
  5170.9  835.04  5180.9  835.25  5200.9  836.05  5270.6  838.05  5275.2  838.05
#Mann=3,-1,0
  4888.5    0.05       0  5028.5   0.033       0  5032.5    0.05       0
Bank Sta=5028.5,5032.5
Exp/Cntr=0.3,0.1

Type RM Length L Ch R = 1,1095,244,244,244
BEGIN DESCRIPTION:
Mapping XS cad4ceaa
END DESCRIPTION:
XS GIS Cut Line= 2
      2286385.39      7176203.56      2286092.76      7176323.60
#Sta/Elev= 30
  4830.8  835.15  4833.4  834.88  4838.9  836.36  4857.4  835.02  4862.8  835.24
  4886.8  833.47  4902.6  833.00  4924.2  830.66  4934.8  830.20  4956.6  830.70
  4964.2  831.31  4969.6  831.07  4978.2  828.74  4988.2  828.08  4993.6  828.64
  4999.8  828.49  5008.7  824.51  5008.9  824.01  5012.4  824.01  5012.7  824.51
  5023.0  828.20  5032.3  827.03  5046.9  827.81  5064.7  827.27  5070.9  828.44
  5076.3  828.79  5086.3  828.16  5107.9  828.64  5140.4  827.85  5147.1  828.06
#Mann=3,-1,0
  4830.8    0.05       0  5008.7   0.033       0  5012.7    0.05       0
Bank Sta=5008.7,5012.7
Exp/Cntr=0.3,0.1

Type RM Length L Ch R = 1,851,321,321,321
BEGIN DESCRIPTION:
Mapping XS 4e4a631a
END DESCRIPTION:
XS GIS Cut Line= 2
      2286429.62      7175966.14      2286086.34      7176066.65
#Sta/Elev= 30
  4738.8  837.56  4760.3  836.43  4767.9  835.70  4773.1  835.84  4812.4  832.12
  4822.8  831.47  4840.0  829.38  4845.2  829.86  4873.4  828.04  4878.6  828.38
  4906.2  827.04  4912.0  826.30  4917.2  826.58  4945.5  825.36  4950.7  825.60
  4958.3  824.82  4968.7  824.53  4978.9  822.88  4984.1  820.40  4989.5  820.08
  4999.9  822.69  5008.4  820.02  5008.6  819.52  5012.1  819.52  5012.4  820.02
  5017.5  823.60  5031.2  824.21  5056.2  824.69  5062.5  825.09  5096.5  824.78
#Mann=3,-1,0
  4738.8    0.05       0  5008.4   0.033       0  5012.4    0.05       0
Bank Sta=5008.4,5012.4
Exp/Cntr=0.3,0.1

Type RM Length L Ch R = 1,530,0,0,0
BEGIN DESCRIPTION:
MDE S 004 1.0
END DESCRIPTION:
XS GIS Cut Line= 3
      2286503.74      7175746.10      2286131.19      7175724.23
      2286060.55      7176032.65
#Sta/Elev= 30
  4616.5  835.73  4621.4  835.73  4671.3  831.52  4761.5  827.14  4771.5  827.58
  4781.5  825.81  4871.7  822.05  4905.6  821.36  4971.7  818.32  4981.9  818.44
  4988.3  814.14  4993.6  813.06  4993.9  812.56  4997.4  812.56  4997.6  813.06
  5002.3  813.41  5016.1  813.13  5021.6  814.17  5026.7  817.38  5046.9  818.73
  5057.2  818.81  5064.5  817.46  5069.6  818.99  5077.7  817.86  5118.7  819.65
  5149.5  820.23  5170.0  821.64  5203.5  821.98  5272.6  824.23  5306.1  824.05
#Mann=5,-1,0
  4616.5    0.05       0  4905.6    0.12       0  4993.6    0.07       0
  4997.6    0.12       0  5002.3    0.05       0
Bank Sta=4993.6,4997.6
Exp/Cntr=0.3,0.1

Chan Stop Cuts=-1