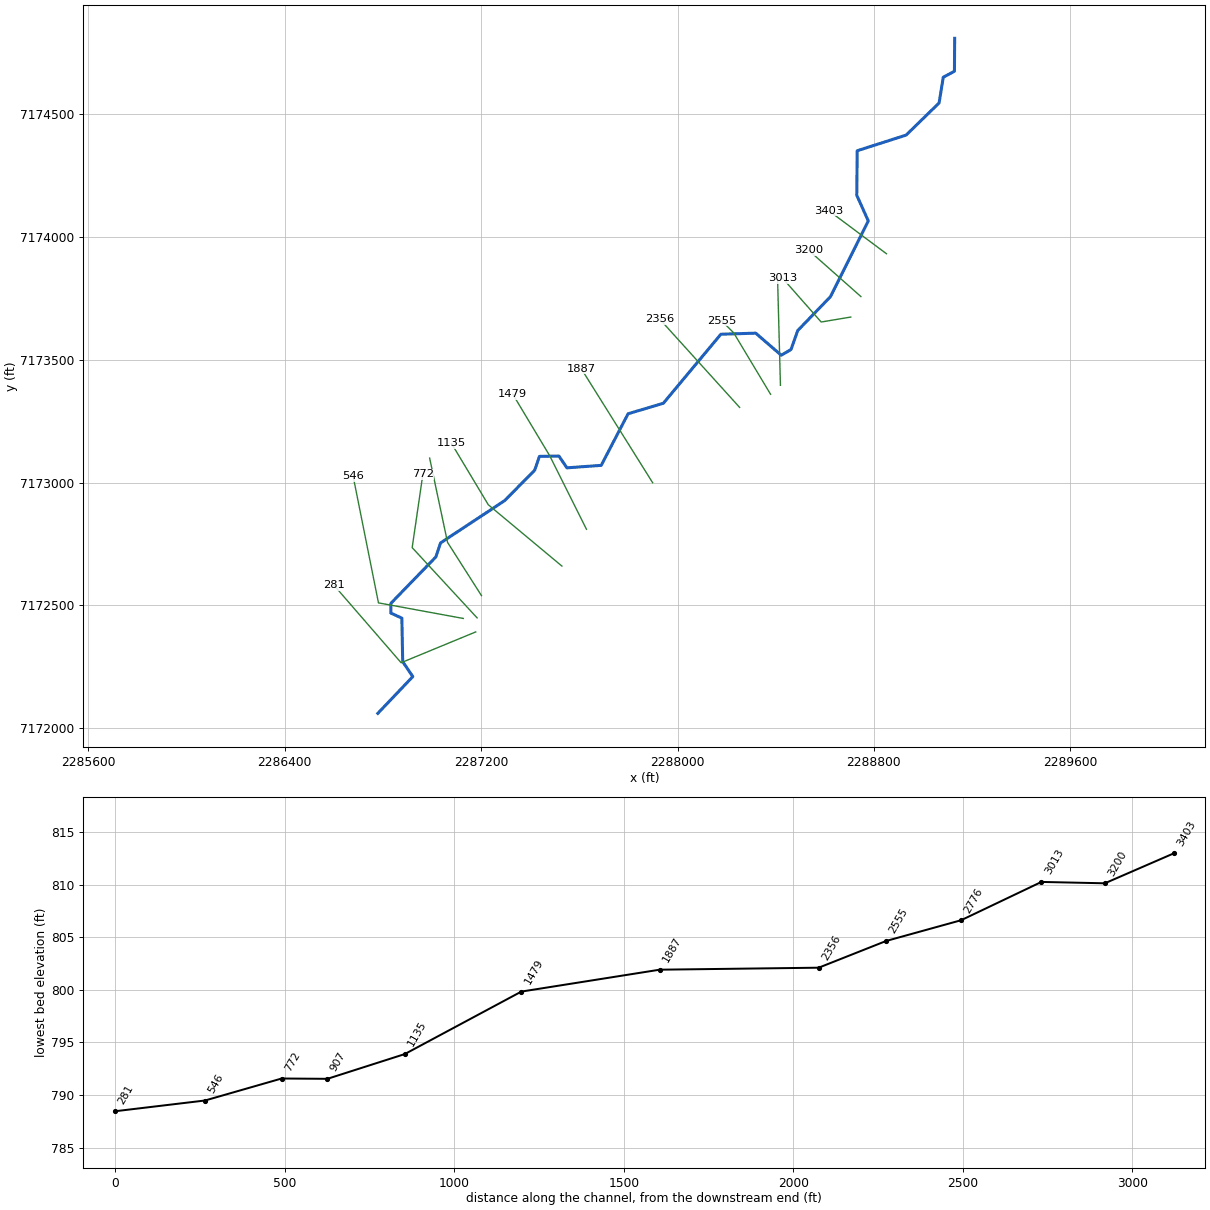
--- MDE S 005.prj (project) ---

Proj Title=MDE S 005 Base Level Engineering
Current Plan=p01
Default Exp/Contr=0.3,0.1
English Units
Geom File=g01
Flow File=f01
Plan File=p01
BEGIN DESCRIPTION:
MDE S 005
END DESCRIPTION:

--- MDE S 005.p01 (plan) ---

Plan Title=Multiple Run
Short Identifier=Multiple
Geom File=g01
Flow File=f01
Subcritical Flow
K Sum by GR= 0
Std Step Tol= 0.01
Critical Tol= 0.01
Num of Std Step Trials= 20
Max Error Tol= 0.3
Flow Tol Ratio= 0.001
Split Flow NTrial= 30
Split Flow Tol= 0.02
Split Flow Ratio= 0.02
Log Output Level= 0
Friction Slope Method= 1
Unsteady Friction Slope Method= 2
Unsteady Bridges Friction Slope Method= 1
Parabolic Critical Depth
Global Vel Dist=  1 , 1 , 1
Global Log Level= 0
CheckData=True
Encroach Param= -1, 0, 0, 0
BEGIN DESCRIPTION:
Multiple Run
END DESCRIPTION:

--- MDE S 005.f01 (steady flow) ---

Flow Title=Multiple
Number of Profiles=7
Profile Names=10-year,25-year,50-year,1pct_min,100-year,1pct_plu,500-year
River Rch & RM= MDE S 005,Reach-1,3403
     598     820    1004     612    1221    2436    1805
Boundary for River Rch & Prof#=MDE S 005,Reach-1,1
Up Type=0
Dn Type=3
Dn Slope=0.005
Boundary for River Rch & Prof#=MDE S 005,Reach-1,2
Up Type=0
Dn Type=3
Dn Slope=0.005
Boundary for River Rch & Prof#=MDE S 005,Reach-1,3
Up Type=0
Dn Type=3
Dn Slope=0.005
Boundary for River Rch & Prof#=MDE S 005,Reach-1,4
Up Type=0
Dn Type=3
Dn Slope=0.005
Boundary for River Rch & Prof#=MDE S 005,Reach-1,5
Up Type=0
Dn Type=3
Dn Slope=0.005
Boundary for River Rch & Prof#=MDE S 005,Reach-1,6
Up Type=0
Dn Type=3
Dn Slope=0.005
Boundary for River Rch & Prof#=MDE S 005,Reach-1,7
Up Type=0
Dn Type=3
Dn Slope=0.005

--- MDE S 005.g01 (geometry) ---

Geom Title=Existing Conditions

River Reach=MDE S 005,Reach-1
Reach XY= 30
      2289129.00      7174810.00      2289128.12      7174675.88
      2289082.55      7174651.51      2289065.59      7174546.73
      2288931.30      7174415.83      2288731.93      7174352.03
      2288730.24      7174170.50      2288777.20      7174066.11
      2288623.17      7173757.70      2288489.78      7173619.64
      2288462.35      7173542.40      2288422.50      7173518.91
      2288318.56      7173608.95      2288176.54      7173604.55
      2287942.30      7173323.40      2287798.58      7173280.57
      2287689.12      7173070.34      2287549.30      7173060.28
      2287516.88      7173108.19      2287437.42      7173107.05
      2287418.10      7173050.63      2287295.67      7172926.65
      2287034.62      7172754.38      2287015.27      7172697.02
      2286832.02      7172508.02      2286831.98      7172468.66
      2286876.98      7172448.05      2286880.39      7172270.44
      2286921.69      7172209.90      2286779.00      7172060.00

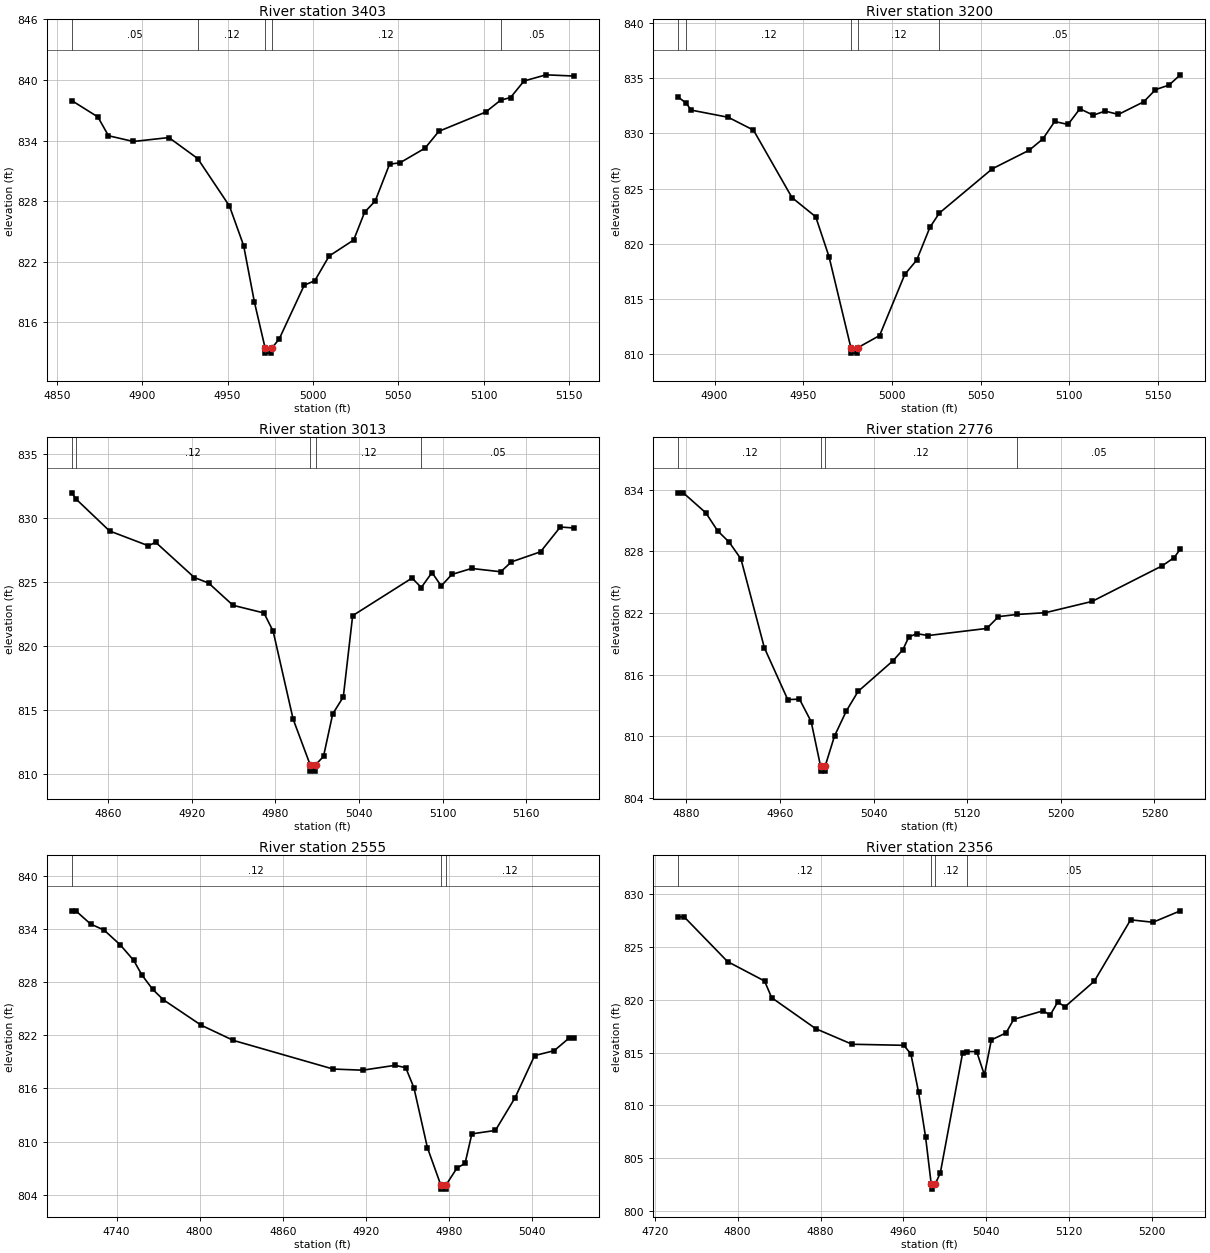
Type RM Length L Ch R = 1,3403,203,203,203
BEGIN DESCRIPTION:
Mapping XS 8e7e1717
END DESCRIPTION:
XS GIS Cut Line= 2
      2288851.38      7173932.26      2288615.63      7174108.26
#Sta/Elev= 30
  4858.7  837.96  4874.0  836.34  4880.2  834.48  4894.8  833.91  4915.6  834.30
  4932.5  832.22  4951.1  827.52  4959.4  823.61  4965.7  818.03  4972.0  813.46
  4972.2  812.96  4975.7  812.96  4976.0  813.46  4980.3  814.38  4994.9  819.68
  5001.1  820.13  5009.5  822.57  5023.9  824.16  5030.3  826.91  5036.5  828.02
  5044.9  831.66  5051.1  831.81  5065.7  833.25  5073.8  834.92  5101.2  836.82
  5110.0  838.00  5115.8  838.26  5123.7  839.90  5136.6  840.51  5152.9  840.39
#Mann=5,-1,0
  4858.7    0.05       0  4932.5    0.12       0  4972.0    0.07       0
  4976.0    0.12       0  5110.0    0.05       0
Bank Sta=4972,4976
Exp/Cntr=0.3,0.1

Type RM Length L Ch R = 1,3200,187,187,187
BEGIN DESCRIPTION:
Mapping XS e7e1da89
END DESCRIPTION:
XS GIS Cut Line= 2
      2288747.02      7173758.06      2288535.19      7173945.72
#Sta/Elev= 30
  4879.5  833.28  4884.0  832.72  4886.8  832.10  4907.7  831.45  4921.9  830.29
  4943.6  824.19  4957.0  822.45  4964.5  818.84  4976.8  810.62  4977.0  810.12
  4980.5  810.12  4980.8  810.62  4993.0  811.71  5007.2  817.24  5013.9  818.53
  5021.4  821.51  5026.7  822.79  5056.5  826.79  5077.4  828.48  5085.0  829.49
  5091.7  831.07  5099.2  830.80  5105.9  832.22  5113.4  831.64  5120.1  832.01
  5127.6  831.71  5141.9  832.85  5148.5  833.95  5156.1  834.36  5162.5  835.29
#Mann=5,-1,0
  4879.5    0.05       0  4884.0    0.12       0  4976.8    0.07       0
  4980.8    0.12       0  5026.7    0.05       0
Bank Sta=4976.8,4980.8
Exp/Cntr=0.3,0.1

Type RM Length L Ch R = 1,3013,237,237,237
BEGIN DESCRIPTION:
Mapping XS d0d195a0
END DESCRIPTION:
XS GIS Cut Line= 3
      2288705.70      7173674.55      2288585.27      7173654.30
      2288428.01      7173832.78
#Sta/Elev= 30
  4834.0  832.00  4837.2  831.50  4861.1  829.02  4889.0  827.86  4894.1  828.14
  4921.9  825.38  4932.1  824.95  4949.6  823.21  4971.8  822.61  4978.4  821.18
  4992.7  814.32  5004.9  810.75  5005.1  810.25  5008.6  810.25  5008.9  810.75
  5014.5  811.40  5021.1  814.72  5028.7  816.05  5035.4  822.40  5078.0  825.34
  5084.6  824.60  5092.3  825.77  5098.9  824.72  5106.5  825.62  5120.7  826.09
  5141.6  825.83  5149.2  826.60  5170.1  827.39  5184.3  829.33  5194.0  829.25
#Mann=5,-1,0
  4834.0    0.05       0  4837.2    0.12       0  5004.9    0.07       0
  5008.9    0.12       0  5084.6    0.05       0
Bank Sta=5004.9,5008.9
Exp/Cntr=0.3,0.1

Type RM Length L Ch R = 1,2776,221,221,221
BEGIN DESCRIPTION:
Mapping XS 06ad02f5
END DESCRIPTION:
XS GIS Cut Line= 2
      2288419.25      7173396.40      2288407.71      7173825.35
#Sta/Elev= 30
  4873.0  833.70  4877.3  833.70  4896.6  831.75  4906.6  830.01  4916.6  828.89
  4926.6  827.26  4946.6  818.62  4966.6  813.57  4976.6  813.62  4986.6  811.43
  4994.6  807.11  4994.9  806.61  4998.4  806.61  4998.6  807.11  5006.6  810.04
  5016.7  812.47  5026.7  814.37  5056.7  817.37  5065.0  818.43  5070.0  819.66
  5076.7  819.99  5086.7  819.81  5136.7  820.50  5146.7  821.65  5162.5  821.86
  5186.7  822.03  5226.7  823.13  5286.7  826.60  5296.8  827.39  5302.1  828.22
#Mann=4,-1,0
  4873.0    0.12       0  4994.6    0.07       0  4998.6    0.12       0
  5162.5    0.05       0
Bank Sta=4994.6,4998.6
Exp/Cntr=0.3,0.1

Type RM Length L Ch R = 1,2555,199,199,199
BEGIN DESCRIPTION:
MDE S 005 6.0
END DESCRIPTION:
XS GIS Cut Line= 3
      2288379.01      7173359.98      2288229.00      7173610.00
      2288178.99      7173660.01
#Sta/Elev= 30
  4707.7  836.02  4710.6  836.02  4721.3  834.53  4731.0  833.85  4742.7  832.18
  4752.4  830.43  4758.3  828.79  4766.0  827.18  4773.8  825.99  4801.0  823.13
  4824.3  821.41  4896.3  818.18  4917.6  818.05  4941.0  818.60  4948.7  818.33
  4954.6  816.07  4964.3  809.33  4973.9  805.14  4974.2  804.64  4977.7  804.64
  4977.9  805.14  4985.7  807.03  4991.5  807.54  4996.4  810.87  5013.4  811.26
  5027.6  814.95  5041.7  819.70  5055.8  820.25  5066.4  821.65  5070.0  821.65
#Mann=3,-1,0
  4707.7    0.12       0  4973.9    0.07       0  4977.9    0.12       0
Bank Sta=4973.9,4977.9
Exp/Cntr=0.3,0.1

Type RM Length L Ch R = 1,2356,469,469,469
BEGIN DESCRIPTION:
Mapping XS dbcbfffd
END DESCRIPTION:
XS GIS Cut Line= 2
      2288252.99      7173306.44      2287927.57      7173665.92
#Sta/Elev= 30
  4742.6  827.80  4748.4  827.80  4790.2  823.59  4826.0  821.75  4832.8  820.18
  4875.4  817.25  4910.5  815.78  4960.5  815.68  4967.3  814.86  4974.7  811.25
  4981.5  807.01  4986.9  802.60  4987.2  802.10  4990.9  802.60  4995.7  803.62
  5017.2  814.93  5021.1  815.09  5030.8  815.09  5038.3  812.88  5045.0  816.19
  5059.2  816.85  5066.6  818.13  5095.0  818.94  5101.8  818.53  5109.2  819.78
  5116.0  819.31  5144.4  821.73  5179.5  827.53  5201.1  827.30  5227.5  828.38
#Mann=4,-1,0
  4742.6    0.12       0  4986.9    0.07       0  4990.9    0.12       0
  5021.1    0.05       0
Bank Sta=4986.9,4990.9
Exp/Cntr=0.3,0.1

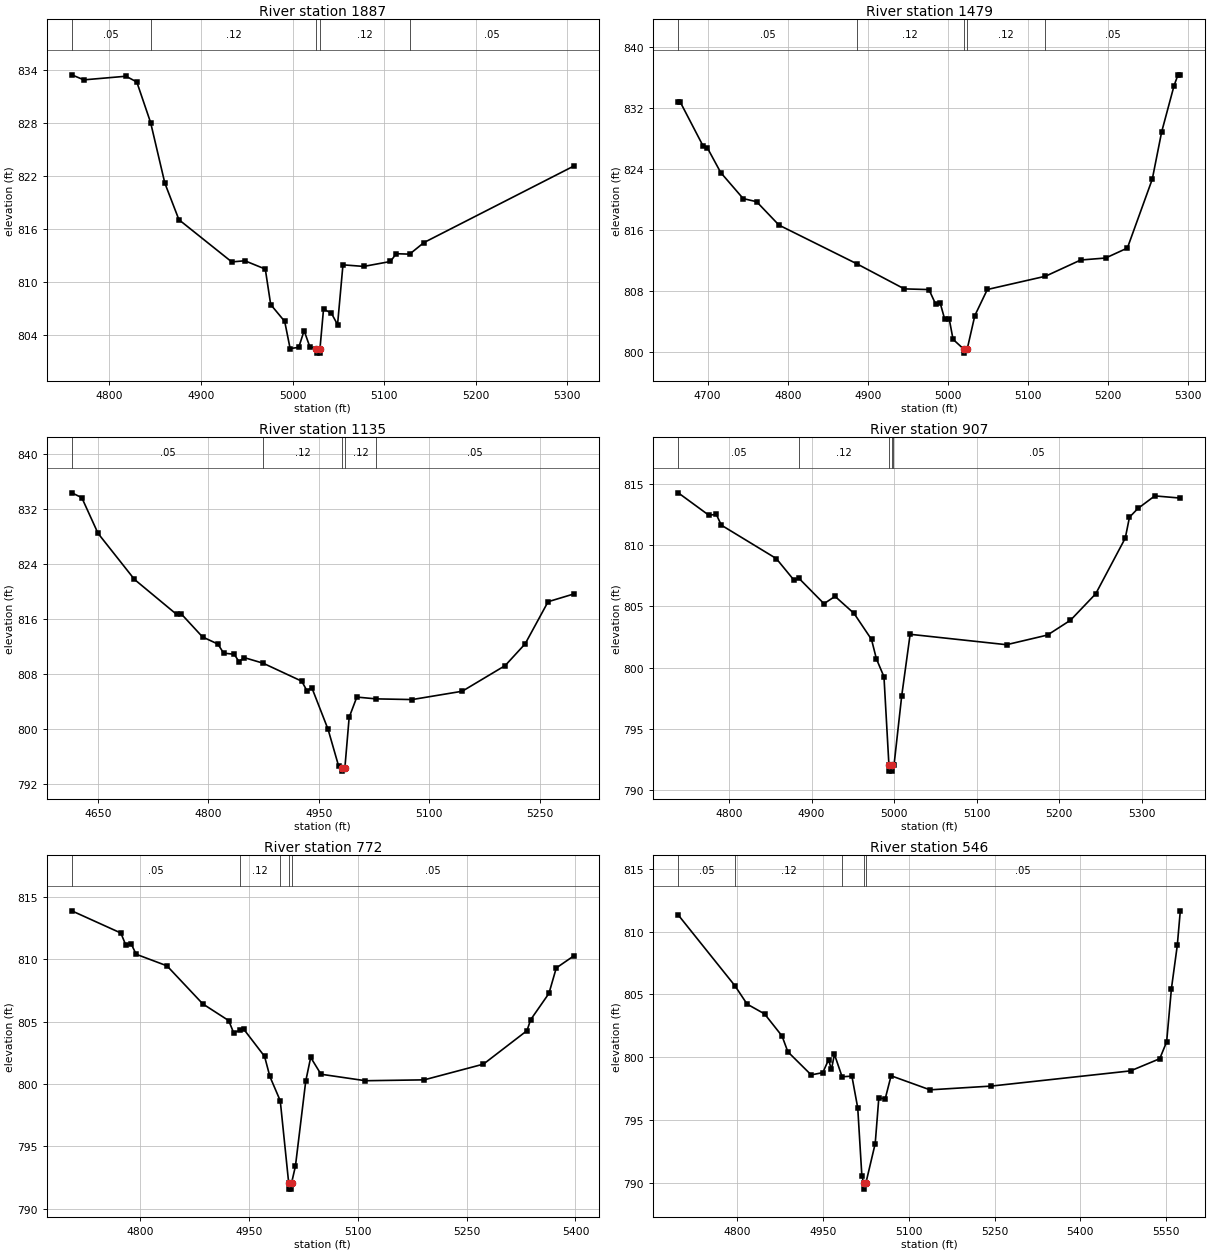
Type RM Length L Ch R = 1,1887,408,408,408
BEGIN DESCRIPTION:
Mapping XS c2fe79d0
END DESCRIPTION:
XS GIS Cut Line= 2
      2287898.56      7172999.83      2287607.63      7173464.46
#Sta/Elev= 30
  4758.9  833.43  4772.1  832.86  4818.1  833.27  4829.9  832.62  4845.0  828.02
  4860.5  821.17  4875.9  817.02  4933.6  812.24  4947.9  812.37  4970.2  811.43
  4976.1  807.41  4991.4  805.50  4997.3  802.43  5006.7  802.56  5012.6  804.45
  5018.7  802.66  5025.9  802.41  5026.2  801.91  5029.7  801.91  5029.9  802.41
  5033.8  806.90  5042.3  806.44  5049.1  805.14  5055.0  811.91  5077.7  811.73
  5106.9  812.29  5113.1  813.17  5127.8  813.12  5143.4  814.43  5307.1  823.10
#Mann=5,-1,0
  4758.9    0.05       0  4845.0    0.12       0  5025.9    0.07       0
  5029.9    0.12       0  5127.8    0.05       0
Bank Sta=5025.9,5029.9
Exp/Cntr=0.3,0.1

Type RM Length L Ch R = 1,1479,344,344,344
BEGIN DESCRIPTION:
MDE S 005 3.0
END DESCRIPTION:
XS GIS Cut Line= 3
      2287629.02      7172809.96      2287479.00      7173110.00
      2287329.00      7173360.00
#Sta/Elev= 30
  4663.3  832.72  4666.1  832.72  4694.1  827.06  4699.7  826.76  4716.4  823.52
  4744.4  820.11  4761.2  819.70  4789.1  816.63  4886.2  811.56  4945.6  808.26
  4976.4  808.17  4984.8  806.25  4990.4  806.41  4996.0  804.31  5001.7  804.31
  5006.5  801.64  5020.1  800.33  5020.3  799.83  5024.1  800.33  5033.7  804.76
  5049.3  808.18  5121.9  809.92  5165.9  812.05  5197.0  812.31  5224.2  813.62
  5255.3  822.66  5267.0  828.86  5282.5  834.93  5287.4  836.35  5290.3  836.35
#Mann=5,-1,0
  4663.3    0.05       0  4886.2    0.12       0  5020.1    0.07       0
  5024.1    0.12       0  5121.9    0.05       0
Bank Sta=5020.1,5024.1
Exp/Cntr=0.3,0.1

Type RM Length L Ch R = 1,1135,228,228,228
BEGIN DESCRIPTION:
MDE S 005 2.0
END DESCRIPTION:
XS GIS Cut Line= 3
      2287528.96      7172660.03      2287229.00      7172910.00
      2287079.01      7173159.99
#Sta/Elev= 30
  4614.6  834.37  4628.2  833.67  4650.3  828.47  4699.8  821.77  4757.1  816.68
  4763.6  816.73  4792.2  813.41  4813.1  812.37  4820.9  811.05  4835.2  810.89
  4841.7  809.83  4848.9  810.40  4874.5  809.59  4927.0  806.97  4934.1  805.57
  4940.6  806.05  4962.8  799.95  4977.1  794.62  4981.6  794.39  4981.8  793.89
  4985.6  794.39  4991.4  801.71  5001.8  804.66  5027.8  804.40  5077.0  804.30
  5145.0  805.51  5203.3  809.24  5230.5  812.41  5261.6  818.53  5296.6  819.66
#Mann=5,-1,0
  4614.6    0.05       0  4874.5    0.12       0  4981.6    0.07       0
  4985.6    0.12       0  5027.8    0.05       0
Bank Sta=4981.6,4985.6
Exp/Cntr=0.3,0.1

Type RM Length L Ch R = 1,907,135,135,135
BEGIN DESCRIPTION:
Mapping XS c5c55763
END DESCRIPTION:
XS GIS Cut Line= 3
      2287201.25      7172539.78      2287063.00      7172756.82
      2286990.15      7173100.24
#Sta/Elev= 30
  4738.5  814.28  4775.4  812.46  4784.7  812.51  4790.7  811.64  4857.3  808.91
  4878.7  807.15  4885.0  807.28  4915.1  805.22  4928.5  805.82  4951.5  804.43
  4972.7  802.30  4978.6  800.72  4987.8  799.25  4993.8  792.04  4994.1  791.54
  4997.6  791.54  4997.8  792.04  4998.7  792.04  5000.0  792.04  5009.3  797.69
  5019.5  802.72  5136.3  801.87  5186.0  802.66  5213.8  803.87  5244.4  806.03
  5280.2  810.58  5285.3  812.29  5295.5  813.00  5316.0  814.03  5346.9  813.85
#Mann=5,-1,0
  4738.5    0.05       0  4885.0    0.12       0  4993.8   0.033       0
  4997.8    0.12       0  4998.7    0.05       0
Bank Sta=4993.8,4997.8
Exp/Cntr=0.3,0.1

Type RM Length L Ch R = 1,772,226,226,226
BEGIN DESCRIPTION:
Mapping XS 17b7e0c7
END DESCRIPTION:
XS GIS Cut Line= 3
      2287183.39      7172449.19      2286919.00      7172735.24
      2286962.58      7173033.96
#Sta/Elev= 30
  4706.4  813.88  4774.0  812.10  4780.8  811.13  4788.2  811.24  4795.0  810.40
  4837.5  809.47  4886.8  806.42  4922.5  805.08  4929.3  804.11  4938.4  804.31
  4943.5  804.37  4971.9  802.21  4979.2  800.60  4993.5  798.65  5005.1  792.07
  5005.3  791.57  5008.8  791.57  5009.1  792.07  5014.4  793.41  5028.6  800.23
  5035.4  802.13  5049.6  800.78  5110.8  800.26  5191.7  800.33  5273.3  801.59
  5333.2  804.27  5338.3  805.15  5363.5  807.26  5373.6  809.30  5397.8  810.27
#Mann=5,-1,0
  4706.4    0.05       0  4938.4    0.12       0  4993.5    0.05       0
  5005.1   0.033       0  5009.1    0.05       0
Bank Sta=5005.1,5009.1
Exp/Cntr=0.3,0.1

Type RM Length L Ch R = 1,546,265,265,265
BEGIN DESCRIPTION:
Mapping XS c6c59d14
END DESCRIPTION:
XS GIS Cut Line= 3
      2287127.24      7172446.70      2286781.63      7172510.18
      2286678.66      7173025.20
#Sta/Elev= 30
  4697.8  811.32  4796.8  805.68  4818.0  804.22  4848.5  803.44  4879.0  801.68
  4889.2  800.42  4929.9  798.58  4950.2  798.76  4960.2  799.78  4965.3  799.02
  4970.5  800.22  4983.9  798.43  5001.0  798.48  5011.2  795.95  5018.4  790.54
  5021.5  789.98  5021.7  789.48  5025.5  789.98  5041.7  793.11  5048.0  796.74
  5059.2  796.68  5069.4  798.51  5137.4  797.39  5244.5  797.69  5487.5  798.90
  5538.5  799.87  5550.5  801.21  5558.9  805.46  5569.1  808.89  5574.4  811.65
#Mann=5,-1,0
  4697.8    0.05       0  4796.8    0.12       0  4983.9    0.05       0
  5021.5   0.033       0  5025.5    0.05       0
Bank Sta=5021.5,5025.5
Exp/Cntr=0.3,0.1

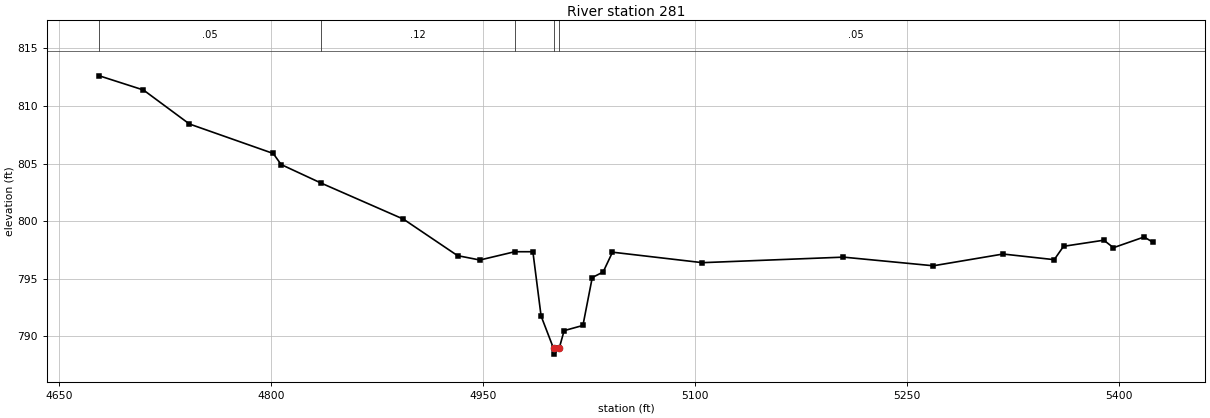
Type RM Length L Ch R = 1,281,0,0,0
BEGIN DESCRIPTION:
MDE S 005 1.0
END DESCRIPTION:
XS GIS Cut Line= 3
      2287177.88      7172391.81      2286873.91      7172266.37
      2286601.22      7172581.01
#Sta/Elev= 30
  4678.5  812.62  4709.7  811.39  4742.2  808.44  4801.5  805.88  4807.1  804.92
  4835.0  803.33  4893.6  800.18  4931.9  797.01  4947.7  796.63  4972.4  797.35
  4985.2  797.35  4991.0  791.77  4999.8  788.96  5000.1  788.46  5003.8  788.96
  5007.3  790.50  5020.6  790.95  5027.2  795.11  5034.9  795.59  5041.5  797.31
  5105.1  796.40  5204.9  796.88  5268.5  796.13  5317.8  797.15  5354.0  796.66
  5360.6  797.82  5389.1  798.35  5395.9  797.70  5417.6  798.63  5423.7  798.18
#Mann=5,-1,0
  4678.5    0.05       0  4835.0    0.12       0  4972.4    0.05       0
  4999.8   0.033       0  5003.8    0.05       0
Bank Sta=4999.8,5003.8
Exp/Cntr=0.3,0.1

Chan Stop Cuts=-1