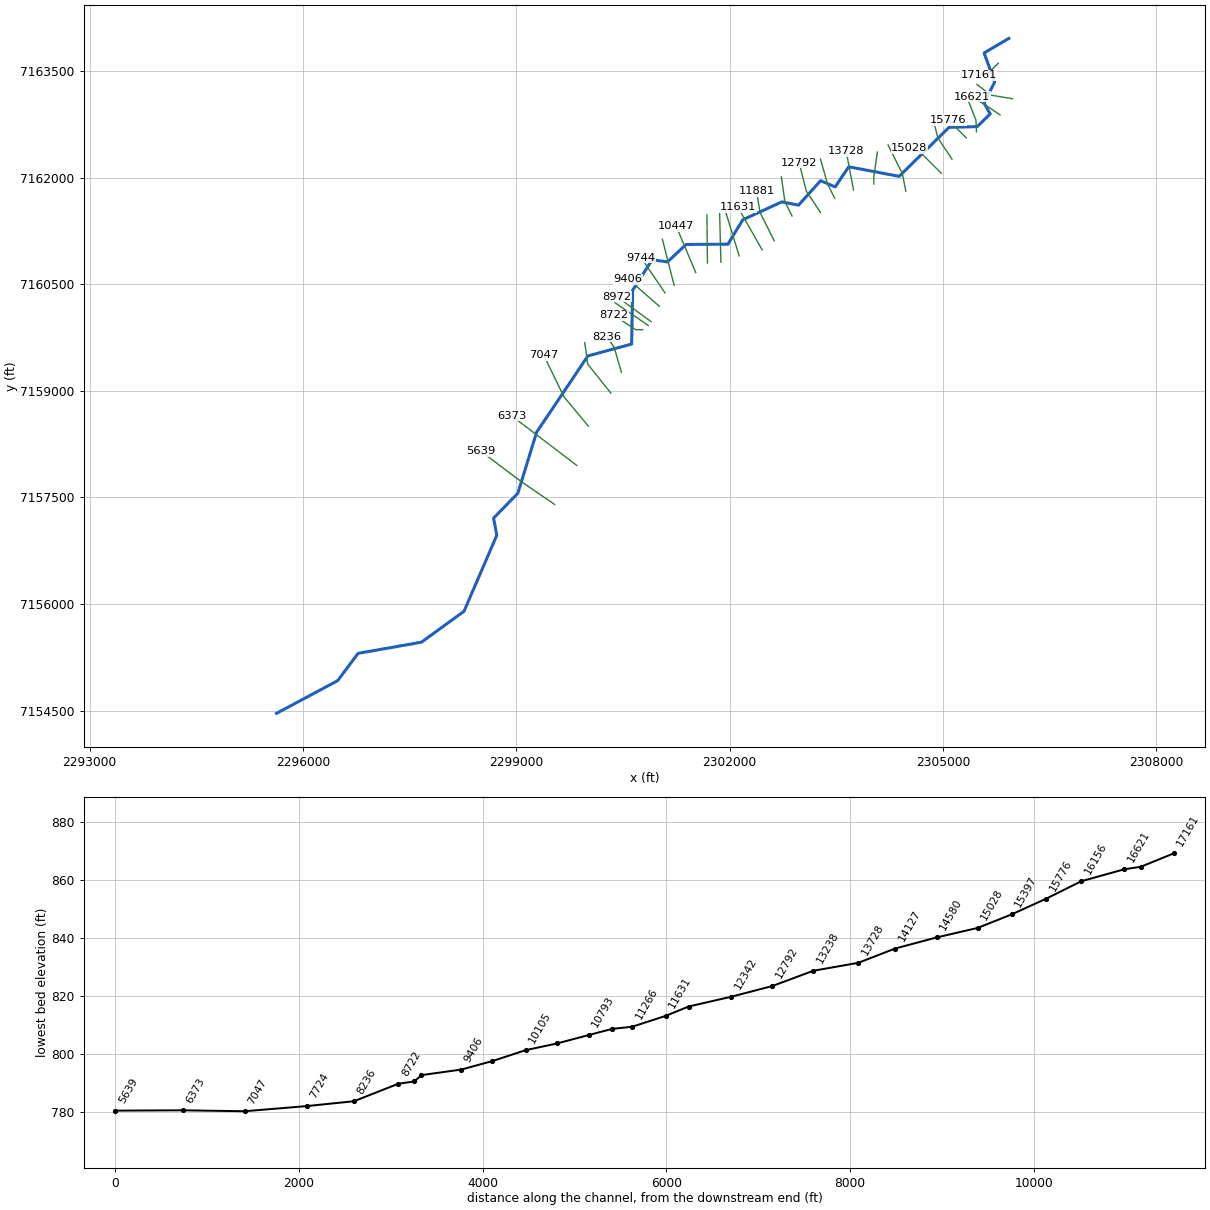
--- MDE S 006.prj (project) ---

Proj Title=MDE S 006 Base Level Engineering
Current Plan=p01
Default Exp/Contr=0.3,0.1
English Units
Geom File=g01
Flow File=f01
Plan File=p01
BEGIN DESCRIPTION:
MDE S 006
END DESCRIPTION:

--- MDE S 006.p01 (plan) ---

Plan Title=Multiple Run
Short Identifier=Multiple
Geom File=g01
Flow File=f01
Subcritical Flow
K Sum by GR= 0
Std Step Tol= 0.01
Critical Tol= 0.01
Num of Std Step Trials= 20
Max Error Tol= 0.3
Flow Tol Ratio= 0.001
Split Flow NTrial= 30
Split Flow Tol= 0.02
Split Flow Ratio= 0.02
Log Output Level= 0
Friction Slope Method= 1
Unsteady Friction Slope Method= 2
Unsteady Bridges Friction Slope Method= 1
Parabolic Critical Depth
Global Vel Dist=  1 , 1 , 1
Global Log Level= 0
CheckData=True
Encroach Param= -1, 0, 0, 0
BEGIN DESCRIPTION:
Multiple Run
END DESCRIPTION:

--- MDE S 006.f01 (steady flow) ---

Flow Title=Multiple
Number of Profiles=7
Profile Names=10-year,25-year,50-year,1pct_min,100-year,1pct_plu,500-year
River Rch & RM= MDE S 006,Reach-1,17161
     708     977    1202     734    1465    2924    2181
River Rch & RM= MDE S 006,Reach-1,14580
    1020    1434    1785    1102    2199    4388    3344
River Rch & RM= MDE S 006,Reach-1,7047
    1648    2369    2991    1870    3732    7445    5823
Boundary for River Rch & Prof#=MDE S 006,Reach-1,1
Up Type=0
Dn Type=3
Dn Slope=0.005
Boundary for River Rch & Prof#=MDE S 006,Reach-1,2
Up Type=0
Dn Type=3
Dn Slope=0.005
Boundary for River Rch & Prof#=MDE S 006,Reach-1,3
Up Type=0
Dn Type=3
Dn Slope=0.005
Boundary for River Rch & Prof#=MDE S 006,Reach-1,4
Up Type=0
Dn Type=3
Dn Slope=0.005
Boundary for River Rch & Prof#=MDE S 006,Reach-1,5
Up Type=0
Dn Type=3
Dn Slope=0.005
Boundary for River Rch & Prof#=MDE S 006,Reach-1,6
Up Type=0
Dn Type=3
Dn Slope=0.005
Boundary for River Rch & Prof#=MDE S 006,Reach-1,7
Up Type=0
Dn Type=3
Dn Slope=0.005

--- MDE S 006.g01 (geometry) ---

Geom Title=Existing Conditions

River Reach=MDE S 006,Reach-1
Reach XY= 30
      2305929.00      7163960.00      2305580.53      7163754.17
      2305728.63      7163344.83      2305579.51      7163049.50
      2305665.73      7162896.32      2305482.66      7162717.67
      2305086.96      7162706.99      2304385.34      7162018.02
      2303675.58      7162152.21      2303486.06      7161868.97
      2303280.42      7161956.96      2302970.85      7161612.50
      2302734.85      7161657.96      2302186.95      7161406.99
      2301977.53      7161063.54      2301389.62      7161059.40
      2301127.72      7160813.37      2300912.32      7160843.78
      2300636.84      7160413.23      2300623.65      7159657.26
      2300008.49      7159490.90      2299286.86      7158416.17
      2299023.29      7157557.42      2298682.53      7157208.53
      2298727.20      7156966.11      2298265.77      7155896.27
      2297667.19      7155461.63      2296776.32      7155304.70
      2296489.17      7154920.33      2295629.00      7154460.00

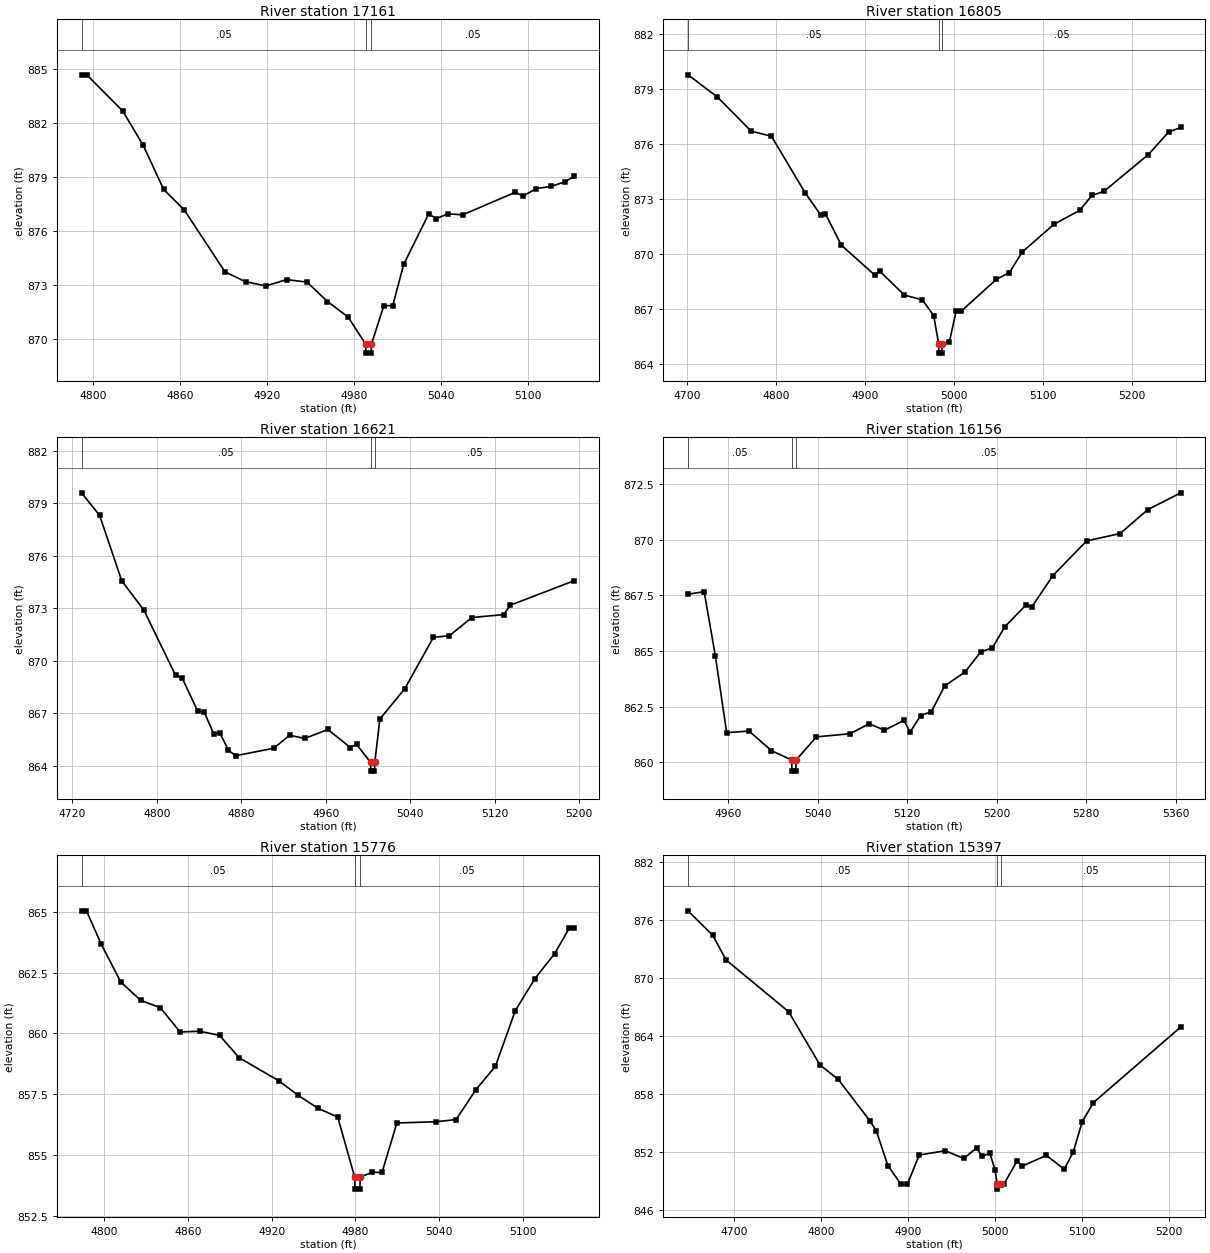
Type RM Length L Ch R = 1,17161,356,356,356
BEGIN DESCRIPTION:
MDE S 006 38.0
END DESCRIPTION:
XS GIS Cut Line= 3
      2305779.03      7163610.03      2305629.00      7163460.00
      2305503.04      7163438.28
#Sta/Elev= 30
  4792.1  884.68  4795.7  884.68  4820.4  882.68  4834.6  880.77  4848.7  878.31
  4862.9  877.17  4891.1  873.72  4905.3  873.17  4919.4  872.94  4933.6  873.29
  4947.7  873.15  4961.8  872.07  4976.0  871.21  4988.1  869.70  4988.4  869.20
  4991.9  869.20  4992.1  869.70  5000.7  871.84  5006.8  871.84  5014.4  874.14
  5031.7  876.95  5036.7  876.68  5044.9  876.95  5055.0  876.89  5091.5  878.15
  5096.6  877.93  5105.8  878.35  5115.9  878.47  5126.0  878.74  5132.1  879.05
#Mann=3,-1,0
  4792.1    0.05       0  4988.1   0.033       0  4992.1    0.05       0
Bank Sta=4988.1,4992.1
Exp/Cntr=0.3,0.1

Type RM Length L Ch R = 1,16805,184,184,184
BEGIN DESCRIPTION:
MDE S 006 37.0
END DESCRIPTION:
XS GIS Cut Line= 3
      2305979.02      7163110.00      2305679.00      7163160.00
      2305478.96      7163310.03
#Sta/Elev= 30
  4700.9  879.78  4733.9  878.57  4771.9  876.71  4794.7  876.43  4832.7  873.34
  4850.5  872.11  4855.5  872.20  4873.3  870.49  4911.3  868.84  4916.3  869.08
  4944.2  867.77  4964.5  867.50  4977.2  866.65  4982.8  865.10  4983.0  864.60
  4986.5  864.60  4986.8  865.10  4994.9  865.23  5002.5  866.89  5008.2  866.89
  5047.8  868.63  5062.3  868.99  5076.9  870.12  5112.3  871.62  5141.5  872.39
  5155.1  873.20  5168.6  873.42  5218.6  875.43  5241.5  876.66  5255.1  876.91
#Mann=3,-1,0
  4700.9    0.05       0  4982.8   0.033       0  4986.8    0.05       0
Bank Sta=4982.8,4986.8
Exp/Cntr=0.3,0.1

Type RM Length L Ch R = 1,16621,465,465,465
BEGIN DESCRIPTION:
Mapping XS a486f12e
END DESCRIPTION:
XS GIS Cut Line= 3
      2305804.42      7162882.87      2305637.53      7162995.38
      2305413.79      7163138.36
#Sta/Elev= 30
  4728.6  879.60  4745.7  878.31  4766.7  874.57  4787.7  872.89  4817.7  869.16
  4823.7  869.04  4838.7  867.11  4844.7  867.08  4853.7  865.83  4859.7  865.86
  4867.8  864.88  4874.7  864.57  4910.7  865.00  4925.6  865.74  4940.0  865.56
  4962.0  866.07  4983.2  865.04  4989.1  865.22  5002.4  864.19  5002.6  863.69
  5006.1  863.69  5006.4  864.19  5011.2  866.67  5034.8  868.40  5061.9  871.34
  5077.1  871.43  5098.3  872.47  5128.7  872.64  5134.6  873.17  5195.4  874.58
#Mann=3,-1,0
  4728.6    0.05       0  5002.4   0.033       0  5006.4    0.05       0
Bank Sta=5002.4,5006.4
Exp/Cntr=0.3,0.1

Type RM Length L Ch R = 1,16156,380,380,380
BEGIN DESCRIPTION:
Mapping XS 9d286b52
END DESCRIPTION:
XS GIS Cut Line= 3
      2305473.29      7162645.58      2305465.03      7162809.16
      2305364.73      7163066.42
#Sta/Elev= 30
  4924.4  867.55  4938.8  867.67  4948.8  864.78  4958.9  861.33  4978.9  861.40
  4998.9  860.52  5016.9  860.10  5017.2  859.60  5020.7  859.60  5020.9  860.10
  5039.0  861.14  5069.0  861.28  5086.1  861.73  5099.8  861.44  5117.2  861.88
  5122.6  861.35  5132.0  862.09  5141.7  862.28  5153.5  863.43  5171.6  864.05
  5185.7  864.96  5196.1  865.14  5207.2  866.09  5226.0  867.06  5231.3  866.98
  5250.1  868.39  5280.3  869.95  5310.2  870.28  5334.7  871.35  5364.3  872.11
#Mann=3,-1,0
  4924.4    0.05       0  5016.9   0.033       0  5020.9    0.05       0
Bank Sta=5016.9,5020.9
Exp/Cntr=0.3,0.1

Type RM Length L Ch R = 1,15776,379,379,379
BEGIN DESCRIPTION:
MDE S 006 34.0
END DESCRIPTION:
XS GIS Cut Line= 3
      2305328.97      7162560.03      2305179.00      7162710.00
      2305079.01      7162809.99
#Sta/Elev= 30
  4783.6  865.04  4787.1  865.04  4797.7  863.67  4811.8  862.11  4826.0  861.36
  4840.1  861.06  4854.3  860.06  4868.4  860.09  4882.6  859.92  4896.7  859.00
  4925.0  858.06  4939.1  857.45  4953.3  856.92  4967.4  856.56  4979.5  854.10
  4979.8  853.60  4983.3  853.60  4983.5  854.10  4992.2  854.29  4999.2  854.29
  5009.8  856.32  5038.1  856.37  5052.3  856.46  5066.4  857.68  5080.5  858.65
  5094.7  860.93  5108.8  862.25  5123.0  863.28  5133.6  864.34  5137.1  864.34
#Mann=3,-1,0
  4783.6    0.05       0  4979.5   0.033       0  4983.5    0.05       0
Bank Sta=4979.5,4983.5
Exp/Cntr=0.3,0.1

Type RM Length L Ch R = 1,15397,369,369,369
BEGIN DESCRIPTION:
MDE S 006 33.0
END DESCRIPTION:
XS GIS Cut Line= 3
      2305129.02      7162259.98      2304929.00      7162560.00
      2304879.01      7162759.96
#Sta/Elev= 30
  4647.4  876.98  4676.0  874.43  4691.0  871.90  4763.1  866.52  4799.2  861.00
  4820.2  859.50  4856.3  855.24  4863.8  854.20  4877.3  850.56  4892.3  848.63
  4899.8  848.67  4913.3  851.67  4943.4  852.11  4964.4  851.31  4979.4  852.40
  4985.5  851.52  4994.5  851.86  5000.5  850.13  5003.0  848.63  5003.2  848.13
  5007.0  848.63  5010.6  848.63  5026.0  851.08  5031.2  850.49  5059.5  851.63
  5080.1  850.19  5090.4  851.97  5100.8  855.13  5113.6  857.10  5214.1  864.94
#Mann=3,-1,0
  4647.4    0.05       0  5003.0   0.033       0  5007.0    0.05       0
Bank Sta=5003,5007
Exp/Cntr=0.3,0.1

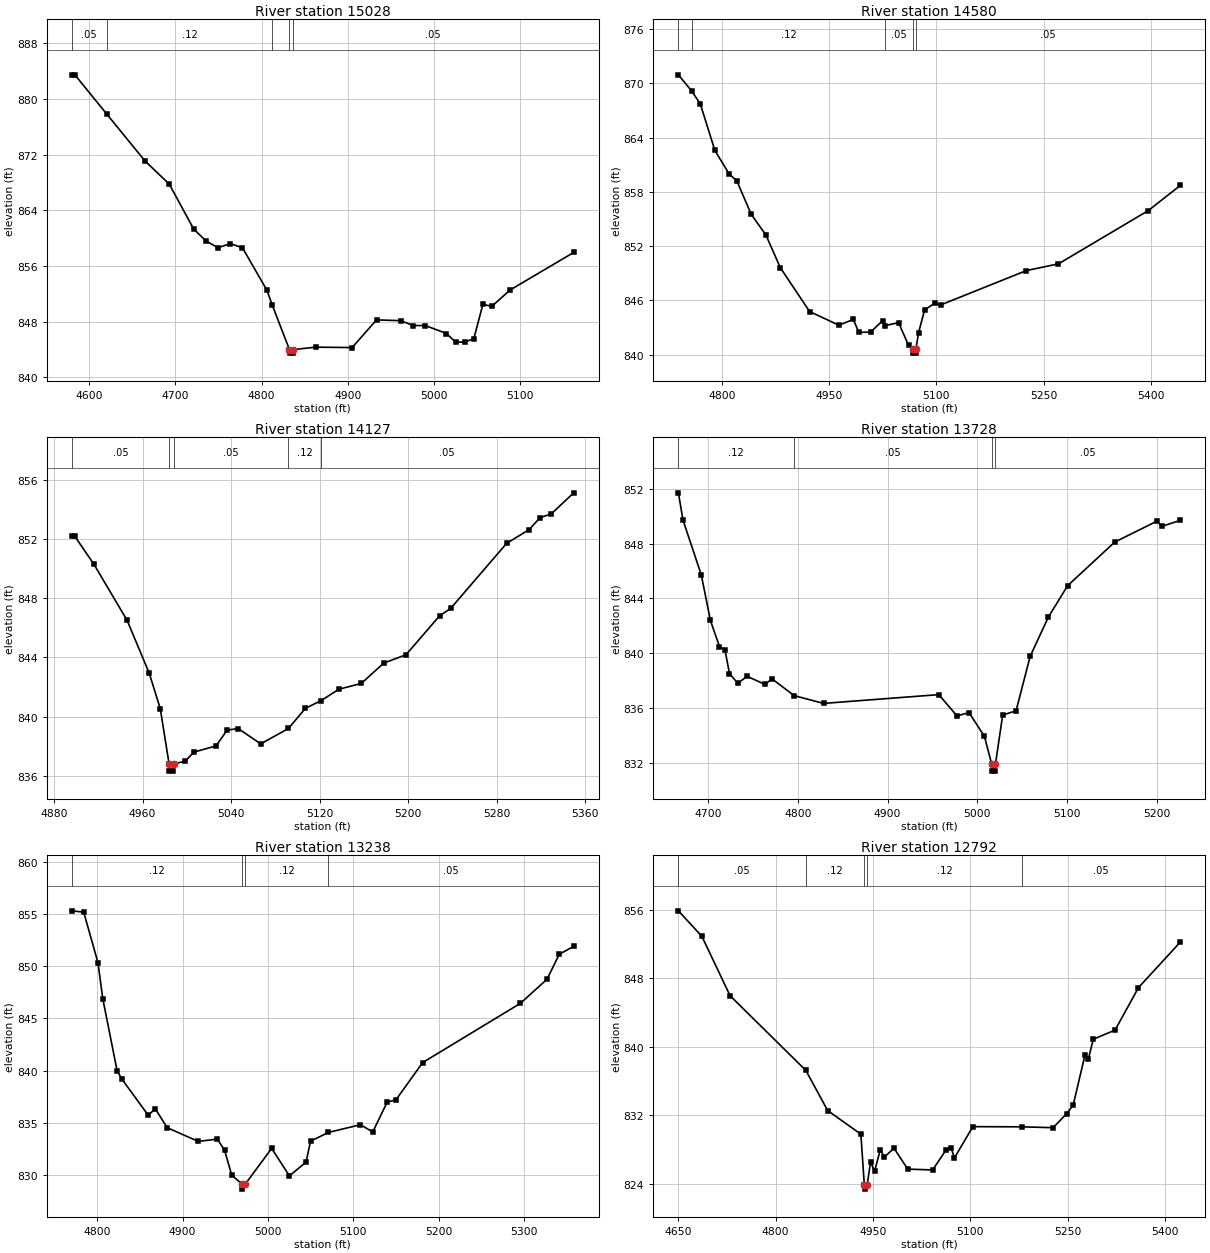
Type RM Length L Ch R = 1,15028,448,448,448
BEGIN DESCRIPTION:
MDE S 006 32.0
END DESCRIPTION:
XS GIS Cut Line= 3
      2304979.02      7162059.98      2304679.00      7162360.00
      2304529.01      7162410.00
#Sta/Elev= 30
  4579.8  883.49  4583.4  883.49  4620.5  877.83  4664.7  871.11  4693.0  867.76
  4721.3  861.30  4735.4  859.61  4749.5  858.62  4763.7  859.20  4777.8  858.63
  4806.1  852.54  4812.4  850.38  4832.4  843.96  4832.6  843.46  4836.1  843.46
  4836.4  843.96  4862.7  844.32  4905.1  844.26  4933.4  848.24  4961.7  848.13
  4975.8  847.43  4990.0  847.43  5014.6  846.28  5025.2  845.04  5035.7  845.05
  5046.3  845.53  5056.8  850.46  5067.3  850.20  5088.4  852.54  5162.2  857.94
#Mann=5,-1,0
  4579.8    0.05       0  4620.5    0.12       0  4812.4    0.05       0
  4832.4   0.033       0  4836.4    0.05       0
Bank Sta=4832.4,4836.4
Exp/Cntr=0.3,0.1

Type RM Length L Ch R = 1,14580,453,453,453
BEGIN DESCRIPTION:
MDE S 006 31.0
END DESCRIPTION:
XS GIS Cut Line= 3
      2304479.00      7161810.01      2304429.00      7162060.00
      2304228.98      7162460.04
#Sta/Elev= 30
  4739.1  870.93  4757.5  869.16  4769.7  867.73  4790.1  862.58  4810.5  859.92
  4820.7  859.23  4841.1  855.49  4861.5  853.23  4881.9  849.58  4922.7  844.76
  4963.5  843.25  4983.8  843.88  4991.5  842.46  5008.0  842.48  5024.8  843.75
  5028.5  843.21  5047.2  843.53  5061.1  841.02  5067.5  840.66  5067.8  840.16
  5071.3  840.16  5071.5  840.66  5075.1  842.41  5083.5  844.93  5097.5  845.67
  5105.8  845.48  5226.0  849.29  5270.8  850.03  5396.5  855.92  5441.3  858.70
#Mann=5,-1,0
  4739.1    0.05       0  4757.5    0.12       0  5028.5    0.05       0
  5067.5    0.07       0  5071.5    0.05       0
Bank Sta=5067.5,5071.5
Exp/Cntr=0.3,0.1

Type RM Length L Ch R = 1,14127,399,399,399
BEGIN DESCRIPTION:
MDE S 006 30.0
END DESCRIPTION:
XS GIS Cut Line= 3
      2304029.00      7161910.04      2304029.00      7162010.00
      2304079.00      7162359.99
#Sta/Elev= 30
  4896.0  852.20  4898.5  852.20  4916.0  850.29  4946.0  846.50  4966.0  842.93
  4976.0  840.53  4983.9  836.82  4984.2  836.32  4987.7  836.32  4988.0  836.82
  4998.5  836.98  5006.1  837.60  5026.3  838.02  5036.4  839.09  5046.5  839.19
  5066.7  838.16  5091.8  839.20  5107.1  840.56  5121.0  841.07  5137.4  841.85
  5157.6  842.24  5177.8  843.61  5198.0  844.18  5228.3  846.80  5238.4  847.31
  5288.9  851.70  5309.1  852.62  5319.2  853.44  5329.3  853.69  5349.5  855.11
#Mann=5,-1,0
  4896.0    0.05       0  4983.9   0.033       0  4988.0    0.05       0
  5091.8    0.12       0  5121.0    0.05       0
Bank Sta=4983.9,4988
Exp/Cntr=0.3,0.1

Type RM Length L Ch R = 1,13728,490,490,490
BEGIN DESCRIPTION:
Mapping XS 6f640c98
END DESCRIPTION:
XS GIS Cut Line= 2
      2303743.80      7161824.97      2303639.94      7162374.44
#Sta/Elev= 30
  4667.0  851.70  4672.1  849.72  4692.5  845.72  4702.7  842.39  4712.8  840.48
  4718.8  840.27  4723.9  838.52  4733.2  837.80  4743.4  838.32  4763.7  837.72
  4771.2  838.14  4795.9  836.91  4828.7  836.34  4957.1  836.98  4977.4  835.43
  4990.8  835.67  5008.0  833.93  5016.1  831.90  5016.4  831.40  5019.9  831.40
  5020.2  831.90  5028.3  835.49  5043.2  835.80  5058.9  839.77  5079.2  842.64
  5100.7  844.93  5153.0  848.10  5200.3  849.64  5205.4  849.25  5226.2  849.69
#Mann=4,-1,0
  4667.0    0.12       0  4795.9    0.05       0  5016.1   0.033       0
  5020.2    0.05       0
Bank Sta=5016.1,5020.2
Exp/Cntr=0.3,0.1

Type RM Length L Ch R = 1,13238,446,446,446
BEGIN DESCRIPTION:
MDE S 006 28.0
END DESCRIPTION:
XS GIS Cut Line= 3
      2303478.99      7161710.02      2303379.00      7161910.00
      2303279.00      7162260.01
#Sta/Elev= 30
  4770.3  855.30  4784.3  855.17  4801.0  850.33  4806.6  846.89  4823.4  839.98
  4829.0  839.18  4859.7  835.74  4868.1  836.33  4882.1  834.53  4918.4  833.22
  4940.8  833.44  4949.2  832.37  4957.5  830.00  4969.4  829.15  4969.8  828.65
  4973.6  829.15  5004.3  832.55  5025.1  829.92  5044.6  831.24  5049.8  833.24
  5070.8  834.08  5108.3  834.82  5122.6  834.12  5139.5  836.97  5149.9  837.21
  5181.1  840.77  5295.5  846.44  5326.7  848.75  5341.0  851.14  5357.9  851.90
#Mann=4,-1,0
  4770.3    0.12       0  4969.4    0.07       0  4973.6    0.12       0
  5070.8    0.05       0
Bank Sta=4969.4,4973.6
Exp/Cntr=0.3,0.1

Type RM Length L Ch R = 1,12792,450,450,450
BEGIN DESCRIPTION:
MDE S 006 27.0
END DESCRIPTION:
XS GIS Cut Line= 3
      2303279.01      7161509.98      2303079.00      7161810.00
      2302979.00      7162210.01
#Sta/Elev= 30
  4650.4  855.90  4686.5  852.93  4730.0  845.98  4846.7  837.25  4880.3  832.56
  4931.4  829.80  4936.7  823.88  4937.1  823.38  4941.1  823.88  4946.4  826.59
  4952.4  825.44  4961.4  828.00  4967.4  827.11  4982.4  828.16  5003.5  825.72
  5041.9  825.62  5062.5  827.95  5070.3  828.24  5075.4  827.02  5103.8  830.68
  5179.2  830.66  5227.4  830.56  5248.1  832.18  5258.4  833.21  5276.4  839.03
  5281.6  838.56  5289.3  840.90  5322.8  841.96  5358.9  846.93  5423.3  852.25
#Mann=5,-1,0
  4650.4    0.05       0  4846.7    0.12       0  4936.7    0.07       0
  4941.1    0.12       0  5179.2    0.05       0
Bank Sta=4936.7,4941.1
Exp/Cntr=0.3,0.1

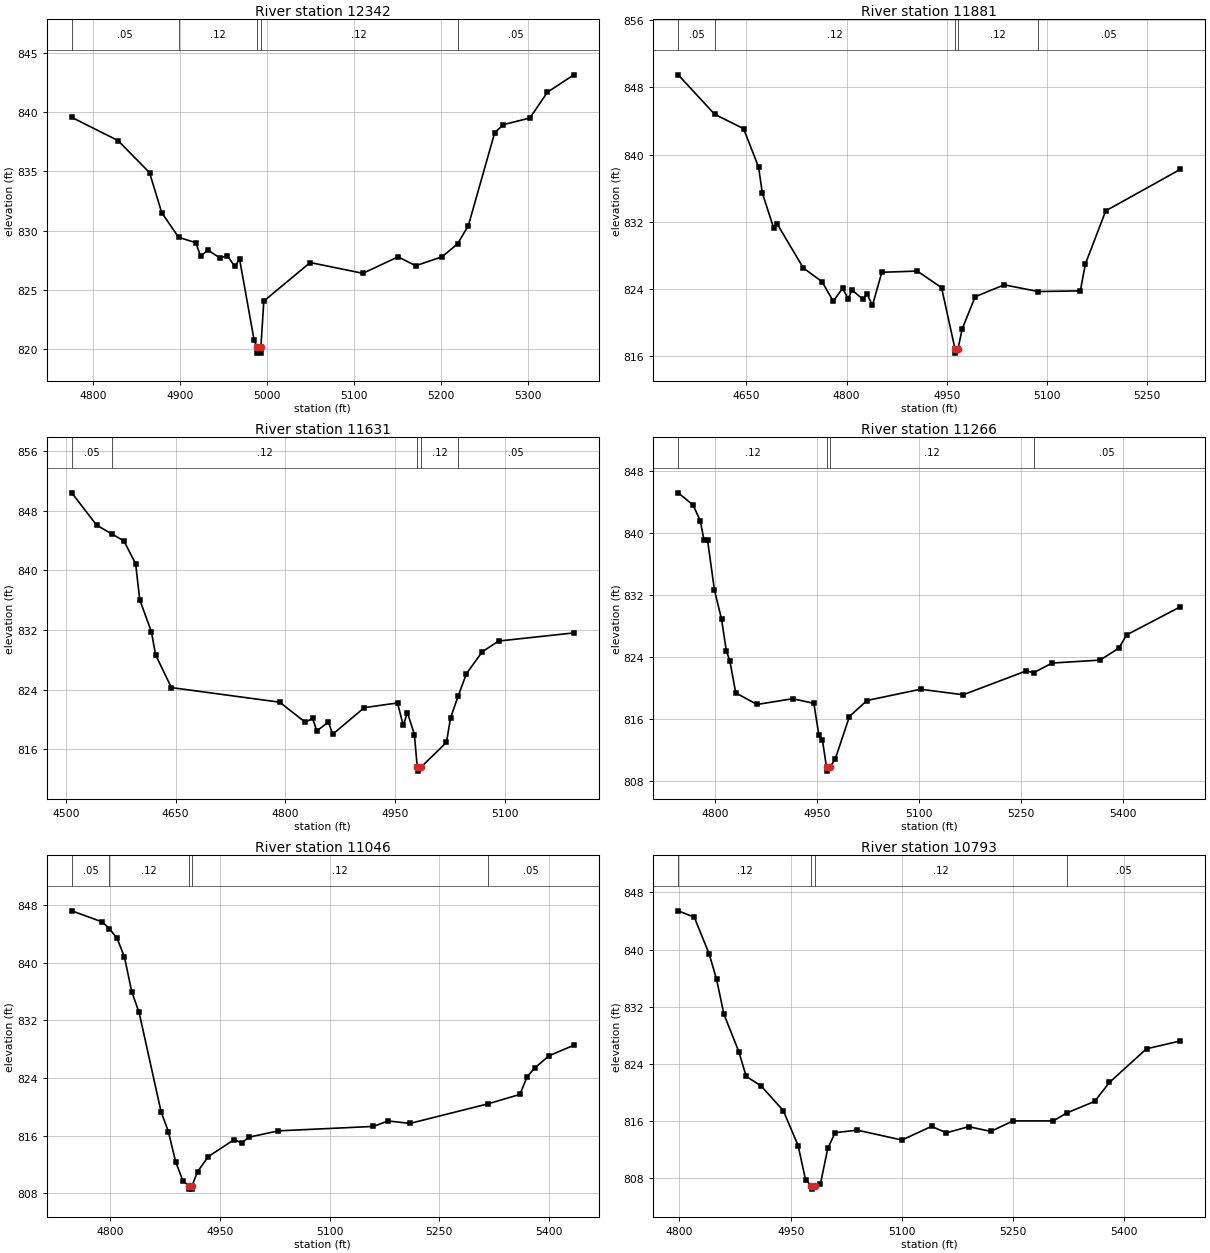
Type RM Length L Ch R = 1,12342,461,461,461
BEGIN DESCRIPTION:
MDE S 006 26.0
END DESCRIPTION:
XS GIS Cut Line= 3
      2302879.00      7161460.00      2302779.00      7161660.00
      2302728.99      7162010.04
#Sta/Elev= 30
  4775.9  839.54  4829.0  837.59  4865.3  834.88  4879.3  831.51  4898.7  829.43
  4918.5  828.97  4924.0  827.84  4932.4  828.35  4946.4  827.68  4954.8  827.89
  4963.2  826.97  4968.8  827.59  4985.5  820.77  4988.9  820.16  4989.3  819.66
  4992.9  819.66  4993.3  820.16  4996.7  824.05  5050.0  827.30  5110.6  826.39
  5151.0  827.78  5171.2  827.03  5201.5  827.78  5219.4  828.87  5231.8  830.41
  5262.1  838.25  5272.2  838.93  5302.6  839.49  5322.8  841.67  5353.1  843.13
#Mann=5,-1,0
  4775.9    0.05       0  4898.7    0.12       0  4988.9    0.07       0
  4993.3    0.12       0  5219.4    0.05       0
Bank Sta=4988.9,4993.3
Exp/Cntr=0.3,0.1

Type RM Length L Ch R = 1,11881,250,250,250
BEGIN DESCRIPTION:
MDE S 006 25.0
END DESCRIPTION:
XS GIS Cut Line= 3
      2302629.00      7161110.00      2302429.00      7161510.00
      2302378.99      7161810.04
#Sta/Elev= 30
  4548.0  849.51  4602.4  844.81  4645.8  843.08  4668.2  838.51  4673.8  835.43
  4690.6  831.28  4696.1  831.71  4735.3  826.45  4763.2  824.83  4780.0  822.49
  4794.0  824.05  4802.4  822.77  4807.9  823.85  4824.7  822.70  4830.3  823.40
  4838.7  822.00  4852.7  825.95  4905.8  826.09  4942.1  824.11  4962.2  816.80
  4962.7  816.30  4966.7  816.80  4972.9  819.18  4992.4  823.03  5035.8  824.45
  5086.7  823.65  5149.8  823.73  5157.4  826.96  5187.8  833.28  5299.4  838.23
#Mann=5,-1,0
  4548.0    0.05       0  4602.4    0.12       0  4962.2    0.07       0
  4966.7    0.12       0  5086.7    0.05       0
Bank Sta=4962.2,4966.7
Exp/Cntr=0.3,0.1

Type RM Length L Ch R = 1,11631,365,365,365
BEGIN DESCRIPTION:
Mapping XS ce3cdf5a
END DESCRIPTION:
XS GIS Cut Line= 2
      2302459.36      7160982.98      2302119.48      7161579.44
#Sta/Elev= 30
  4508.1  850.38  4542.0  846.05  4563.6  844.83  4579.5  843.92  4595.4  840.87
  4601.1  836.03  4617.0  831.74  4622.7  828.66  4644.3  824.27  4792.4  822.31
  4827.3  819.63  4837.4  820.13  4843.2  818.46  4859.0  819.65  4864.8  818.01
  4908.0  821.58  4953.5  822.21  4961.3  819.21  4967.1  820.91  4976.6  817.98
  4980.5  813.57  4981.1  813.07  4985.3  813.57  5020.4  816.92  5026.1  820.24
  5036.3  823.09  5047.7  826.13  5069.3  829.06  5091.7  830.51  5194.6  831.60
#Mann=5,-1,0
  4508.1    0.05       0  4563.6    0.12       0  4980.5    0.07       0
  4985.3    0.12       0  5036.3    0.05       0
Bank Sta=4980.5,4985.3
Exp/Cntr=0.3,0.1

Type RM Length L Ch R = 1,11266,220,220,220
BEGIN DESCRIPTION:
Mapping XS 4b5d2500
END DESCRIPTION:
XS GIS Cut Line= 2
      2302135.27      7160899.13      2301918.71      7161605.48
#Sta/Elev= 30
  4746.1  845.13  4767.9  843.56  4778.4  841.56  4784.1  839.03  4789.3  839.01
  4799.3  832.66  4809.8  828.87  4816.8  824.83  4822.1  823.49  4830.7  819.38
  4862.1  817.89  4914.4  818.63  4945.7  818.03  4953.0  813.97  4958.3  813.29
  4964.3  809.81  4964.8  809.31  4969.1  809.81  4977.1  810.86  4998.0  816.34
  5023.8  818.40  5102.6  819.85  5165.4  819.14  5258.2  822.21  5269.2  821.98
  5296.2  823.22  5366.9  823.60  5394.4  825.14  5406.0  826.85  5484.9  830.46
#Mann=4,-1,0
  4746.1    0.12       0  4964.3    0.07       0  4969.1    0.12       0
  5269.2    0.05       0
Bank Sta=4964.3,4969.1
Exp/Cntr=0.3,0.1

Type RM Length L Ch R = 1,11046,253,253,253
BEGIN DESCRIPTION:
Mapping XS aba6c851
END DESCRIPTION:
XS GIS Cut Line= 2
      2301878.88      7160808.17      2301860.86      7161493.64
#Sta/Elev= 30
  4748.0  847.21  4789.8  845.66  4799.5  844.72  4809.8  843.41  4819.9  840.82
  4829.9  835.97  4839.9  833.12  4869.9  819.34  4879.9  816.56  4889.9  812.35
  4899.9  809.68  4907.5  809.06  4908.0  808.56  4911.7  808.56  4912.3  809.06
  4919.9  810.99  4934.3  813.07  4969.9  815.44  4979.9  814.96  4989.9  815.77
  5029.9  816.65  5160.0  817.27  5180.0  818.03  5210.0  817.69  5315.9  820.39
  5360.0  821.71  5370.0  824.18  5380.0  825.36  5400.1  827.10  5433.7  828.54
#Mann=5,-1,0
  4748.0    0.05       0  4799.5    0.12       0  4907.5    0.07       0
  4912.3    0.12       0  5315.9    0.05       0
Bank Sta=4907.5,4912.3
Exp/Cntr=0.3,0.1

Type RM Length L Ch R = 1,10793,346,346,346
BEGIN DESCRIPTION:
Mapping XS 57d201bc
END DESCRIPTION:
XS GIS Cut Line= 2
      2301689.25      7160798.35      2301682.22      7161475.61
#Sta/Elev= 30
  4798.3  845.43  4820.0  844.53  4840.0  839.39  4850.0  835.84  4860.0  830.92
  4880.0  825.71  4890.0  822.23  4910.0  820.91  4940.0  817.44  4960.0  812.55
  4970.0  807.76  4977.6  806.94  4978.1  806.44  4982.4  806.94  4990.0  807.10
  5000.0  812.15  5010.0  814.35  5040.0  814.70  5100.0  813.32  5140.0  815.23
  5160.0  814.33  5190.0  815.19  5220.0  814.53  5250.0  816.00  5304.4  816.00
  5322.2  817.10  5360.0  818.73  5380.0  821.39  5430.0  826.10  5475.6  827.20
#Mann=4,-1,0
  4798.3    0.12       0  4977.6    0.07       0  4982.4    0.12       0
  5322.2    0.05       0
Bank Sta=4977.6,4982.4
Exp/Cntr=0.3,0.1

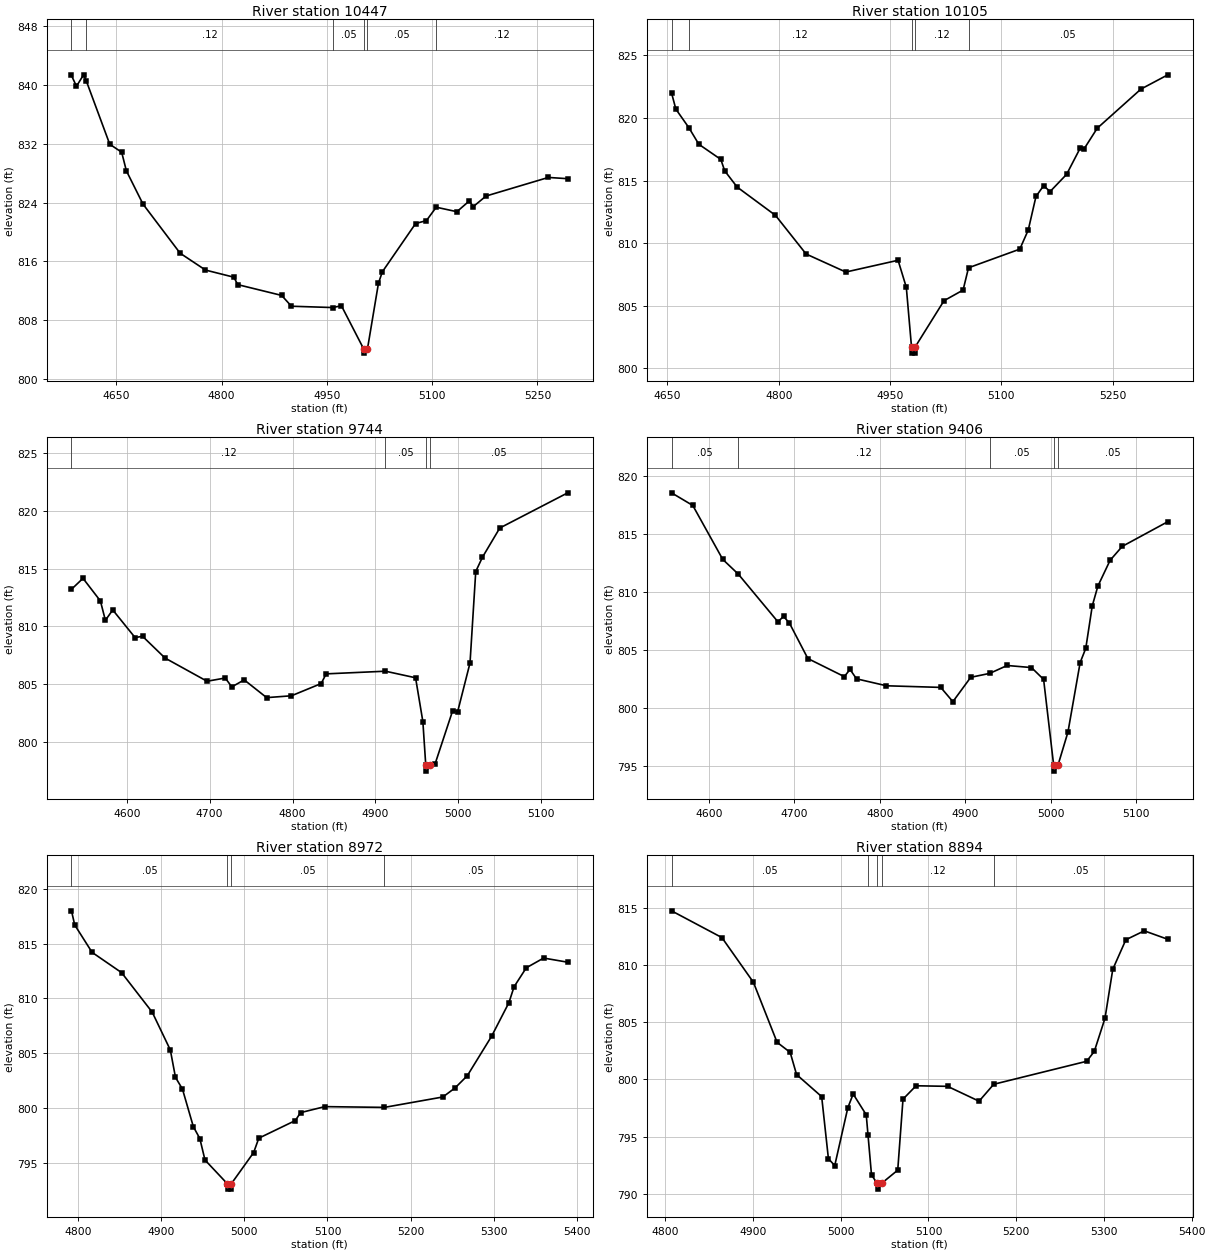
Type RM Length L Ch R = 1,10447,342,342,342
BEGIN DESCRIPTION:
Mapping XS 30c55e4b
END DESCRIPTION:
XS GIS Cut Line= 2
      2301524.91      7160664.15      2301250.07      7161315.43
#Sta/Elev= 30
  4586.3  841.30  4593.4  839.83  4603.5  841.39  4607.3  840.59  4640.8  831.95
  4657.8  830.86  4664.5  828.33  4688.2  823.80  4741.1  817.12  4777.2  814.83
  4817.6  813.86  4823.1  812.85  4885.7  811.38  4899.6  809.91  4958.6  809.73
  4970.8  809.98  5002.9  804.03  5003.5  803.53  5007.8  804.03  5023.6  813.05
  5029.1  814.59  5076.5  821.16  5091.9  821.56  5105.9  823.38  5135.3  822.77
  5153.1  824.24  5158.5  823.45  5176.8  824.90  5265.6  827.43  5293.2  827.26
#Mann=6,-1,0
  4586.3    0.05       0  4607.3    0.12       0  4958.6    0.05       0
  5002.9   0.033       0  5007.8    0.05       0  5105.9    0.12       0
Bank Sta=5002.9,5007.8
Exp/Cntr=0.3,0.1

Type RM Length L Ch R = 1,10105,361,361,361
BEGIN DESCRIPTION:
Mapping XS 5726a83e
END DESCRIPTION:
XS GIS Cut Line= 2
      2301221.44      7160484.40      2301055.51      7161132.08
#Sta/Elev= 30
  4655.6  822.00  4661.4  820.71  4678.9  819.23  4692.4  817.90  4722.0  816.69
  4727.2  815.78  4744.0  814.48  4795.6  812.22  4836.9  809.13  4890.4  807.69
  4960.8  808.63  4971.9  806.47  4978.9  801.71  4979.5  801.21  4983.2  801.21
  4983.9  801.71  5022.7  805.40  5048.4  806.25  5055.7  808.03  5124.8  809.52
  5136.2  811.05  5146.6  813.73  5156.9  814.59  5165.6  814.12  5187.9  815.50
  5206.4  817.62  5211.5  817.54  5229.1  819.18  5288.0  822.31  5324.2  823.45
#Mann=5,-1,0
  4655.6    0.05       0  4678.9    0.12       0  4978.9    0.07       0
  4983.9    0.12       0  5055.7    0.05       0
Bank Sta=4978.9,4983.9
Exp/Cntr=0.3,0.1

Type RM Length L Ch R = 1,9744,338,338,338
BEGIN DESCRIPTION:
Mapping XS d4a0cd3c
END DESCRIPTION:
XS GIS Cut Line= 2
      2301093.89      7160376.59      2300757.26      7160871.81
#Sta/Elev= 30
  4533.3  813.21  4547.2  814.16  4568.2  812.20  4574.2  810.52  4583.1  811.42
  4610.1  809.02  4619.0  809.14  4646.2  807.25  4696.9  805.24  4718.8  805.52
  4726.8  804.75  4741.7  805.36  4768.8  803.82  4798.7  803.98  4834.6  805.04
  4840.6  805.88  4912.2  806.11  4948.5  805.54  4957.3  801.74  4960.8  797.95
  4961.5  797.45  4965.8  797.95  4972.2  798.11  4993.2  802.68  4999.3  802.61
  5014.2  806.83  5021.1  814.75  5029.2  815.99  5050.1  818.52  5132.1  821.57
#Mann=4,-1,0
  4533.3    0.12       0  4912.2    0.05       0  4960.8   0.033       0
  4965.8    0.05       0
Bank Sta=4960.8,4965.8
Exp/Cntr=0.3,0.1

Type RM Length L Ch R = 1,9406,434,434,434
BEGIN DESCRIPTION:
Mapping XS 5c070527
END DESCRIPTION:
XS GIS Cut Line= 2
      2301012.95      7160188.77      2300575.03      7160571.21
#Sta/Elev= 30
  4556.0  818.52  4580.9  817.43  4616.0  812.78  4634.2  811.51  4680.6  807.40
  4687.2  807.86  4694.0  807.30  4715.7  804.23  4758.4  802.67  4765.1  803.29
  4772.7  802.48  4807.8  801.88  4871.4  801.74  4885.6  800.51  4906.5  802.61
  4928.8  802.95  4949.2  803.63  4977.7  803.45  4991.9  802.43  5003.7  795.02
  5004.3  794.52  5008.7  795.02  5020.4  797.88  5034.7  803.88  5041.3  805.11
  5048.9  808.77  5055.5  810.48  5069.8  812.70  5084.0  813.90  5137.4  816.03
#Mann=5,-1,0
  4556.0    0.05       0  4634.2    0.12       0  4928.8    0.05       0
  5003.7   0.033       0  5008.7    0.05       0
Bank Sta=5003.7,5008.7
Exp/Cntr=0.3,0.1

Type RM Length L Ch R = 1,8972,78,78,78
BEGIN DESCRIPTION:
Mapping XS ceeef624
END DESCRIPTION:
XS GIS Cut Line= 2
      2300897.41      7159972.83      2300415.30      7160325.62
#Sta/Elev= 30
  4791.8  818.00  4795.7  816.71  4816.6  814.21  4852.1  812.36  4889.0  808.75
  4910.8  805.30  4917.0  802.80  4925.4  801.73  4938.5  798.30  4946.3  797.22
  4952.5  795.26  4979.3  793.10  4979.9  792.60  4983.7  792.60  4984.3  793.10
  5011.1  795.94  5017.3  797.25  5061.3  798.86  5067.5  799.58  5096.8  800.13
  5168.5  800.06  5238.9  801.01  5253.6  801.84  5268.3  802.95  5297.6  806.56
  5318.4  809.62  5324.6  811.07  5339.3  812.80  5360.2  813.69  5389.2  813.31
#Mann=4,-1,0
  4791.8    0.05       0  4979.3    0.07       0  4984.3    0.05       0
  5168.5    0.05       0
Bank Sta=4979.3,4984.3
Exp/Cntr=0.3,0.1

Type RM Length L Ch R = 1,8894,172,172,172
BEGIN DESCRIPTION:
Mapping XS 6c5f683c
END DESCRIPTION:
XS GIS Cut Line= 2
      2300856.57      7159919.30      2300389.84      7160238.78
#Sta/Elev= 30
  4807.2  814.74  4864.6  812.40  4900.5  808.49  4927.5  803.24  4942.4  802.36
  4949.7  800.42  4978.3  798.49  4986.0  793.06  4993.2  792.46  5008.1  797.51
  5014.2  798.72  5029.1  796.90  5031.1  795.15  5035.1  791.65  5041.5  790.90
  5042.1  790.40  5046.5  790.90  5065.0  792.06  5071.0  798.27  5085.9  799.44
  5121.8  799.39  5157.7  798.09  5174.4  799.57  5280.3  801.58  5289.0  802.44
  5301.2  805.34  5310.1  809.63  5325.0  812.21  5346.0  812.99  5372.8  812.25
#Mann=5,-1,0
  4807.2    0.05       0  5031.1    0.12       0  5041.5   0.033       0
  5046.5    0.12       0  5174.4    0.05       0
Bank Sta=5041.5,5046.5
Exp/Cntr=0.3,0.1

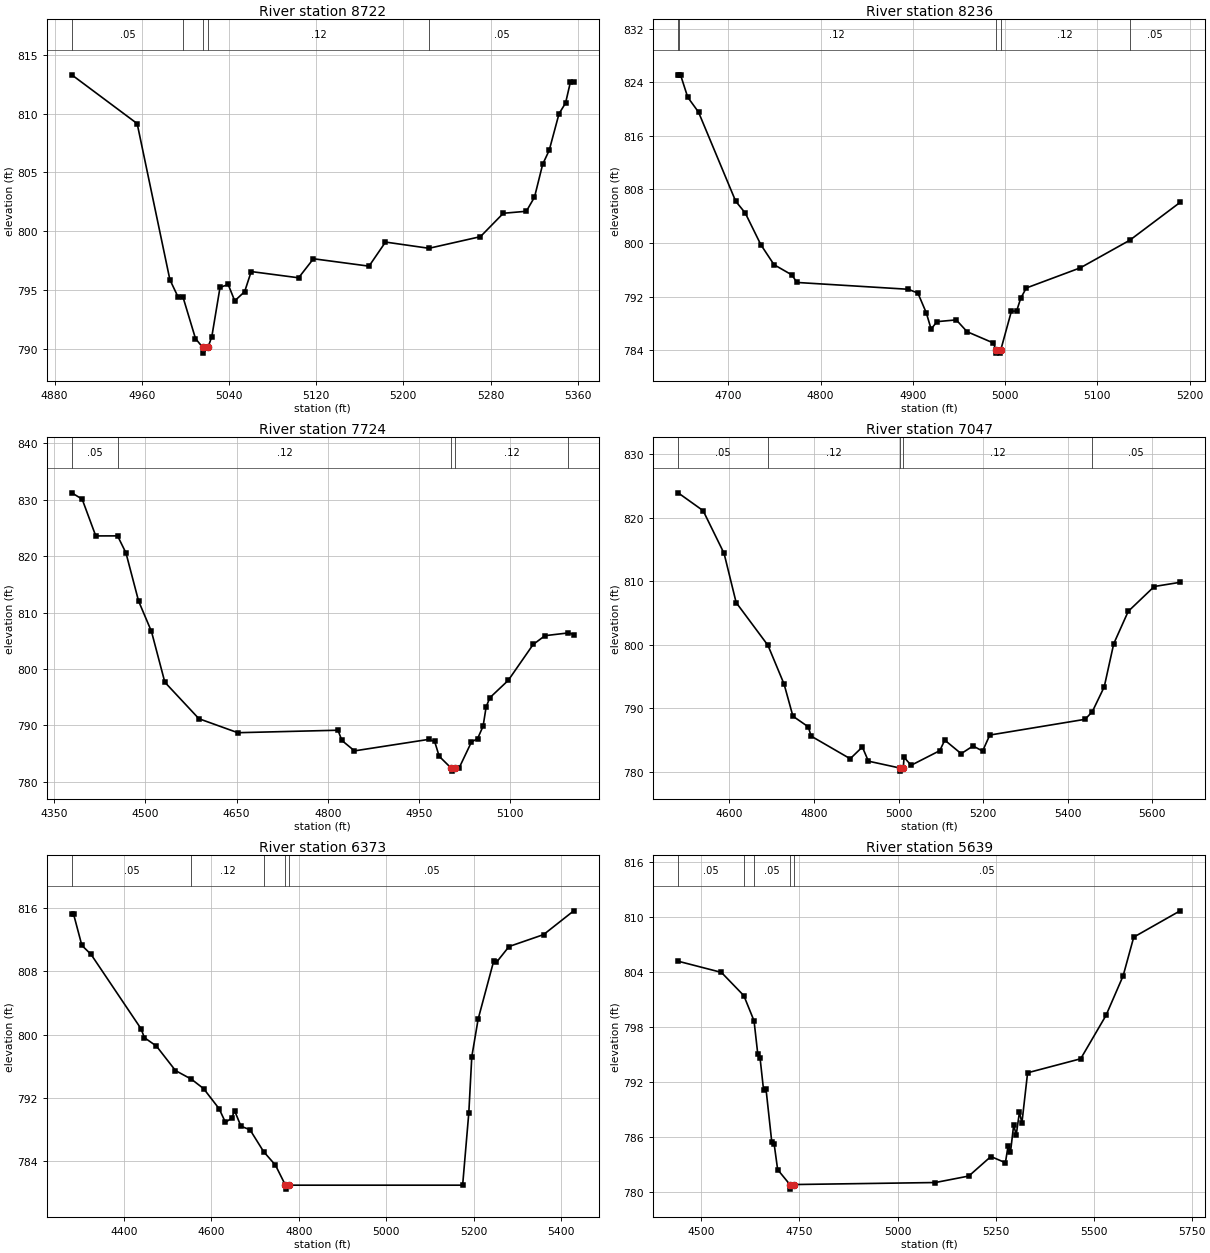
Type RM Length L Ch R = 1,8722,486,486,486
BEGIN DESCRIPTION:
MDE S 006 18.0
END DESCRIPTION:
XS GIS Cut Line= 3
      2300778.97      7159860.00      2300679.00      7159860.00
      2300379.02      7160059.99
#Sta/Elev= 30
  4895.8  813.31  4955.8  809.16  4985.8  795.88  4993.3  794.41  4997.8  794.41
  5009.3  790.87  5015.8  790.13  5016.4  789.63  5020.8  790.13  5024.3  791.04
  5031.8  795.22  5039.3  795.47  5045.3  794.08  5054.4  794.86  5060.4  796.57
  5103.9  796.04  5117.5  797.66  5168.5  797.03  5183.6  799.08  5223.5  798.55
  5270.7  799.54  5291.7  801.53  5312.8  801.70  5320.3  802.90  5327.8  805.70
  5333.8  806.89  5342.8  810.00  5348.8  810.91  5353.3  812.72  5356.3  812.72
#Mann=5,-1,0
  4895.8    0.05       0  4997.8    0.12       0  5015.8    0.07       0
  5020.8    0.12       0  5223.5    0.05       0
Bank Sta=5015.8,5020.8
Exp/Cntr=0.3,0.1

Type RM Length L Ch R = 1,8236,512,512,512
BEGIN DESCRIPTION:
MDE S 006 17.0
END DESCRIPTION:
XS GIS Cut Line= 3
      2300479.00      7159259.98      2300379.00      7159610.00
      2300279.00      7159760.00
#Sta/Elev= 30
  4645.5  825.11  4646.3  825.11  4648.1  825.11  4655.9  821.77  4667.6  819.55
  4707.9  806.25  4718.3  804.48  4735.2  799.75  4749.5  796.77  4769.0  795.23
  4774.2  794.12  4895.1  793.10  4905.5  792.53  4914.6  789.58  4919.8  787.17
  4926.3  788.27  4947.1  788.53  4958.8  786.77  4987.4  785.08  4989.9  784.07
  4990.7  783.57  4994.6  783.57  4995.4  784.07  5006.9  789.84  5012.5  789.84
  5017.0  791.76  5023.0  793.29  5081.6  796.30  5135.2  800.42  5189.8  806.07
#Mann=5,-1,0
  4645.5    0.05       0  4646.3    0.12       0  4989.9    0.07       0
  4995.4    0.12       0  5135.2    0.05       0
Bank Sta=4989.9,4995.4
Exp/Cntr=0.3,0.1

Type RM Length L Ch R = 1,7724,677,677,677
BEGIN DESCRIPTION:
Mapping XS 5e2c321a
END DESCRIPTION:
XS GIS Cut Line= 3
      2300331.38      7158967.50      2300005.46      7159375.69
      2299964.37      7159676.85
#Sta/Elev= 30
  4378.7  831.23  4395.8  830.11  4418.2  823.59  4454.1  823.60  4467.9  820.58
  4488.7  812.04  4509.9  806.65  4531.9  797.66  4588.0  791.19  4652.0  788.71
  4816.9  789.15  4823.3  787.34  4844.1  785.49  4966.0  787.52  4976.0  787.17
  4983.5  784.53  5003.6  782.40  5004.4  781.90  5009.1  782.40  5016.4  782.48
  5036.6  787.06  5046.7  787.66  5055.8  789.87  5060.8  793.29  5066.9  794.91
  5097.2  797.99  5138.2  804.35  5157.7  805.91  5196.2  806.40  5205.0  806.11
#Mann=5,-1,0
  4378.7    0.05       0  4454.1    0.12       0  5003.6    0.07       0
  5009.1    0.12       0  5196.2    0.05       0
Bank Sta=5003.6,5009.1
Exp/Cntr=0.3,0.1

Type RM Length L Ch R = 1,7047,674,674,674
BEGIN DESCRIPTION:
Mapping XS ab3702b1
END DESCRIPTION:
XS GIS Cut Line= 3
      2300014.14      7158502.42      2299672.56      7158914.46
      2299387.37      7159500.21
#Sta/Elev= 30
  4478.7  823.94  4537.8  821.13  4587.3  814.41  4615.9  806.66  4691.1  799.92
  4729.2  793.82  4750.1  788.77  4786.5  787.09  4793.0  785.64  4885.5  782.07
  4914.2  783.92  4928.5  781.69  5002.2  780.62  5003.5  780.12  5011.0  780.62
  5012.8  782.30  5029.5  781.04  5097.2  783.34  5109.1  785.00  5147.8  782.87
  5175.9  784.08  5198.5  783.28  5215.5  785.80  5440.9  788.28  5457.9  789.49
  5486.0  793.38  5508.5  800.18  5542.8  805.28  5604.3  809.19  5665.4  809.85
#Mann=5,-1,0
  4478.7    0.05       0  4691.1    0.12       0  5002.2    0.07       0
  5011.0    0.12       0  5457.9    0.05       0
Bank Sta=5002.2,5011
Exp/Cntr=0.3,0.1

Type RM Length L Ch R = 1,6373,734,734,734
BEGIN DESCRIPTION:
Mapping XS e8c2cd61
END DESCRIPTION:
XS GIS Cut Line= 2
      2299851.19      7157950.09      2298938.09      7158646.07
#Sta/Elev= 30
  4280.5  815.26  4284.6  815.26  4303.6  811.29  4324.4  810.17  4438.7  800.76
  4446.7  799.61  4474.1  798.55  4517.7  795.45  4554.3  794.35  4582.1  793.16
  4617.5  790.62  4632.0  788.89  4646.6  789.44  4652.8  790.38  4667.4  788.41
  4688.2  787.95  4719.4  785.18  4746.3  783.48  4769.2  780.94  4770.5  780.44
  4778.1  780.94  5174.5  780.94  5188.6  790.10  5195.4  797.19  5209.9  801.95
  5245.3  809.27  5251.5  809.13  5280.6  811.15  5359.6  812.66  5428.6  815.67
#Mann=5,-1,0
  4280.5    0.05       0  4554.3    0.12       0  4719.4    0.05       0
  4769.2   0.033       0  4778.1    0.05       0
Bank Sta=4769.2,4778.1
Exp/Cntr=0.3,0.1

Type RM Length L Ch R = 1,5639,533,533,533
BEGIN DESCRIPTION:
Mapping XS 43b37953
END DESCRIPTION:
XS GIS Cut Line= 3
      2299541.04      7157400.02      2299061.41      7157728.35
      2298503.15      7158148.75
#Sta/Elev= 30
  4440.5  805.21  4550.8  803.99  4608.1  801.45  4634.1  798.70  4643.5  795.12
  4649.6  794.59  4658.4  791.14  4664.5  791.31  4679.4  785.44  4685.4  785.25
  4694.3  782.46  4725.5  780.83  4726.8  780.33  4734.8  780.83  5096.5  781.05
  5181.8  781.76  5238.1  783.89  5275.1  783.21  5281.8  785.01  5288.0  784.35
  5296.3  787.36  5302.6  786.22  5310.9  788.74  5317.2  787.55  5331.7  793.03
  5467.1  794.56  5531.6  799.29  5575.3  803.61  5602.4  807.84  5720.6  810.71
#Mann=5,-1,0
  4440.5    0.05       0  4608.1    0.12       0  4634.1    0.05       0
  4725.5   0.033       0  4734.8    0.05       0
Bank Sta=4725.5,4734.8
Exp/Cntr=0.3,0.1