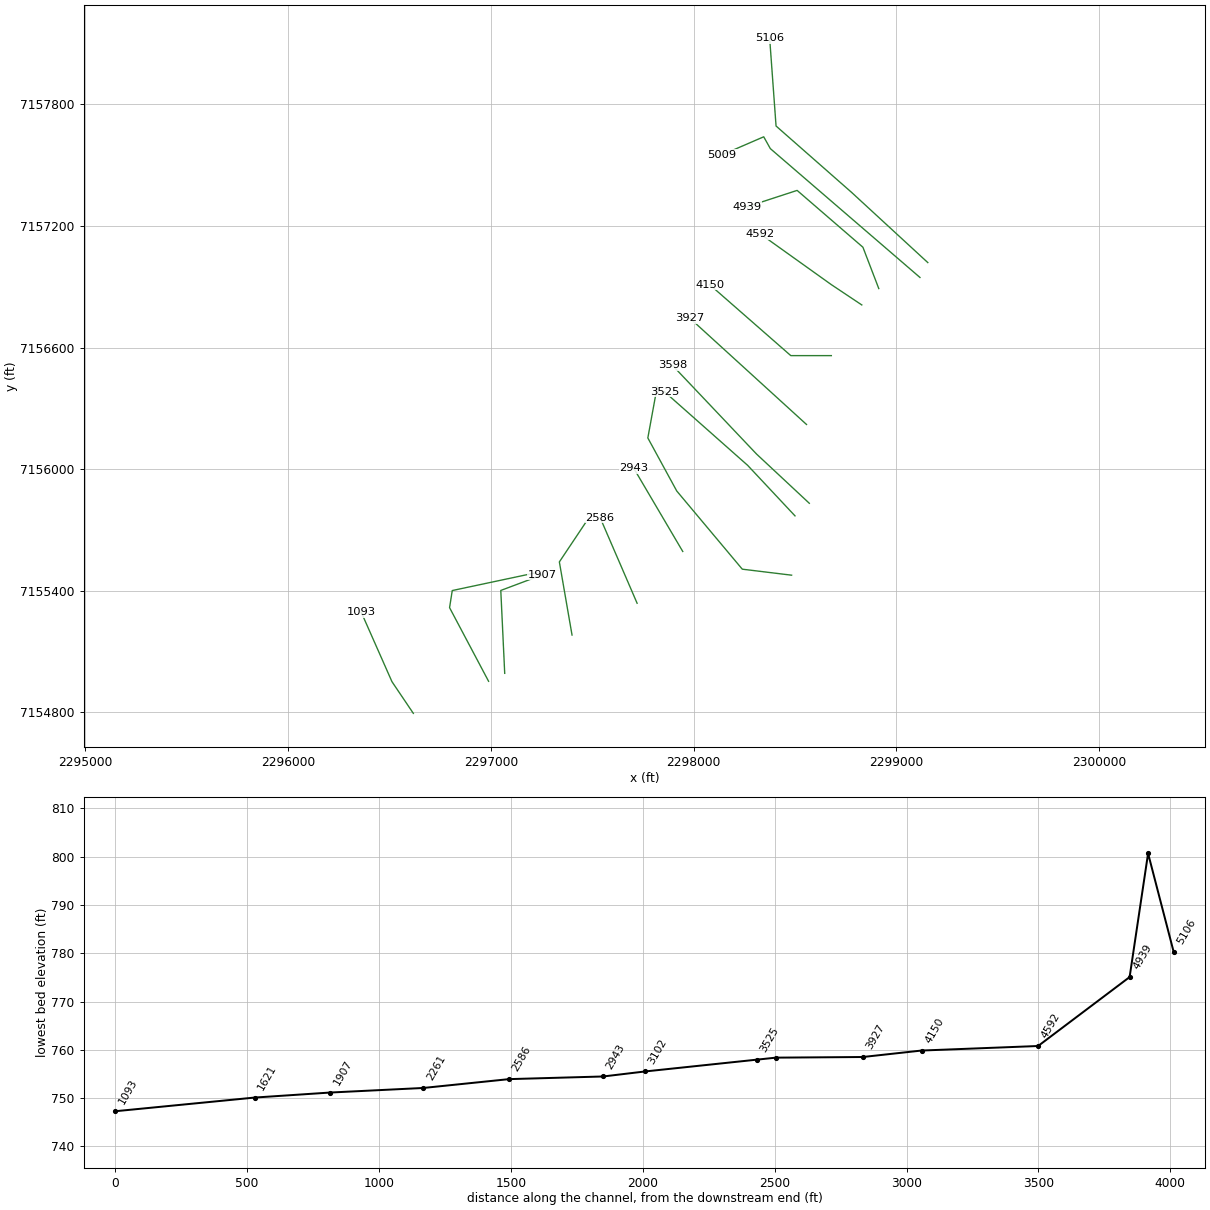
HEC-RAS study MDE S 006.prj: MDE S 006 Base Level Engineering

--- MDE S 006.g01 (geometry) --- (continued)

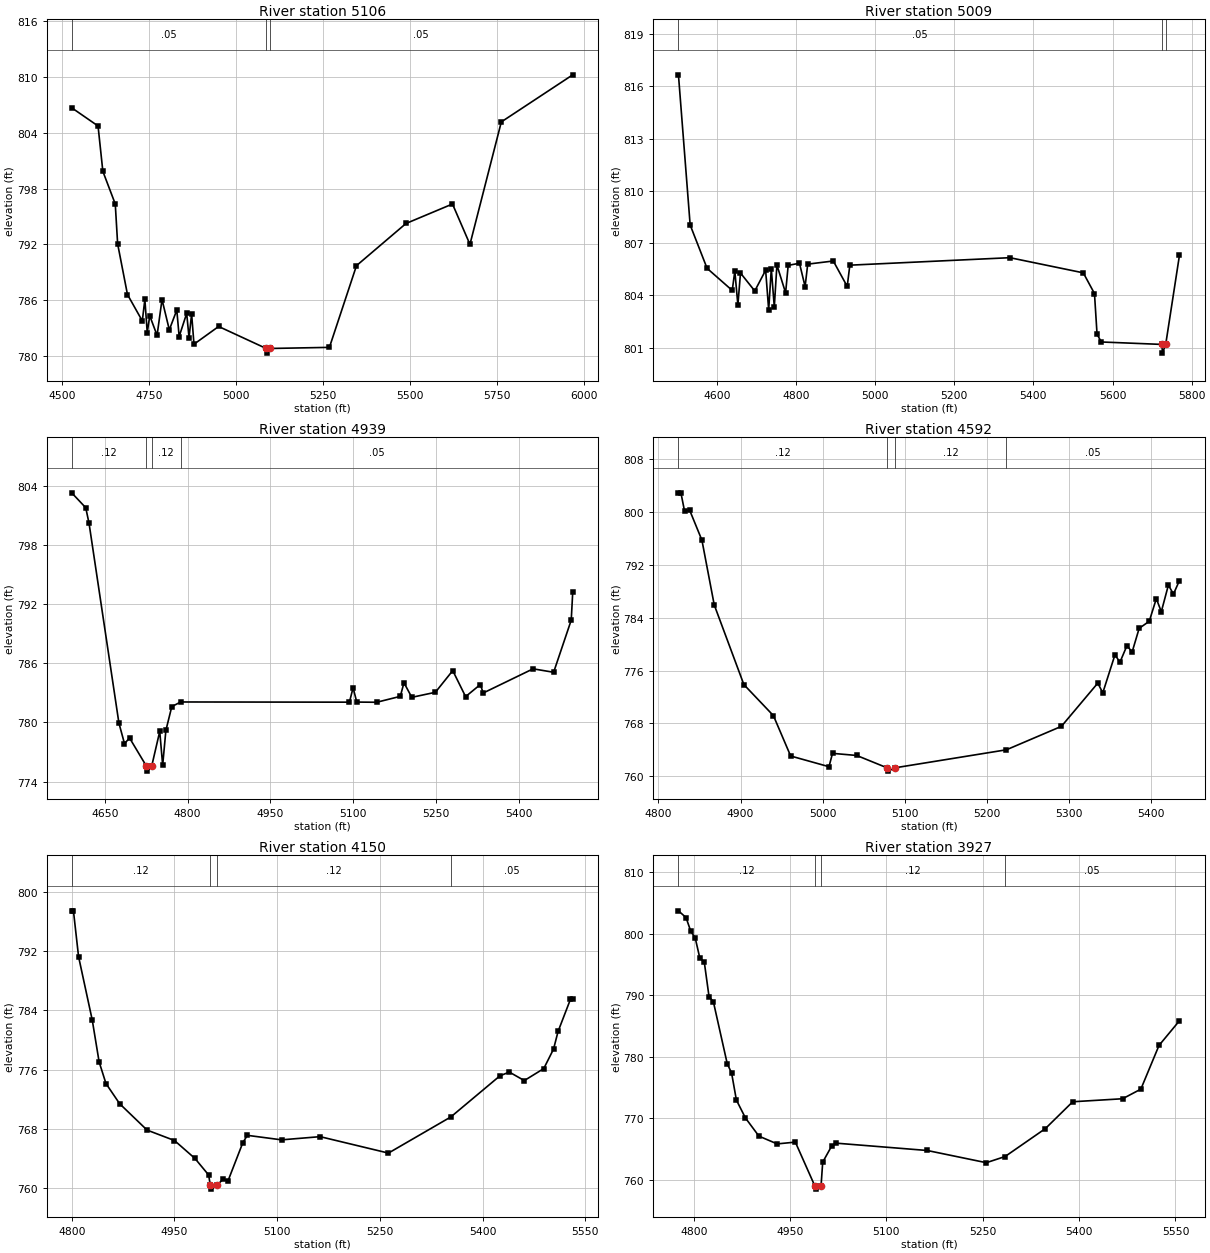
Type RM Length L Ch R = 1,5106,97,97,97
BEGIN DESCRIPTION:
Mapping XS d349772c
END DESCRIPTION:
XS GIS Cut Line= 4
      2299154.66      7157018.87      2298777.90      7157365.83
      2298406.29      7157692.37      2298374.84      7158124.76
#Sta/Elev= 30
  4528.5  806.70  4604.2  804.74  4618.0  799.86  4653.7  796.34  4660.5  792.05
  4688.8  786.59  4731.4  783.75  4738.8  786.06  4745.6  782.50  4752.9  784.30
  4773.9  782.19  4788.1  786.05  4809.1  782.79  4830.6  784.92  4837.4  782.07
  4859.0  784.56  4865.8  781.95  4873.2  784.50  4880.0  781.24  4950.9  783.15
  5087.7  780.78  5089.1  780.28  5097.2  780.78  5269.4  780.90  5347.2  789.70
  5489.5  794.24  5623.2  796.34  5673.4  791.99  5763.6  805.18  5968.9  810.25
#Mann=3,-1,0
  4528.5    0.05       0  5087.7   0.033       0  5097.2    0.05       0
Bank Sta=5087.7,5097.2
Exp/Cntr=0.3,0.1

Type RM Length L Ch R = 1,5009,70,70,70
BEGIN DESCRIPTION:
Mapping XS 8d134d45
END DESCRIPTION:
XS GIS Cut Line= 4
      2299116.09      7156945.42      2298377.98      7157580.98
      2298345.47      7157639.12      2298137.71      7157549.28
#Sta/Elev= 30
  4502.3  816.66  4531.9  808.04  4574.7  805.55  4638.3  804.28  4644.9  805.39
  4652.6  803.44  4659.2  805.28  4695.3  804.25  4722.8  805.44  4730.5  803.16
  4737.1  805.52  4744.7  803.33  4751.3  805.74  4773.3  804.14  4779.8  805.72
  4808.4  805.84  4822.6  804.50  4829.2  805.79  4893.9  805.97  4929.1  804.51
  4935.7  805.73  5340.5  806.16  5526.1  805.29  5554.4  804.10  5560.9  801.76
  5571.8  801.32  5725.0  801.18  5726.3  800.68  5734.5  801.18  5769.3  806.30
#Mann=3,-1,0
  4502.3    0.05       0  5725.0   0.033       0  5734.5    0.05       0
Bank Sta=5725,5734.5
Exp/Cntr=0.3,0.1

Type RM Length L Ch R = 1,4939,347,347,347
BEGIN DESCRIPTION:
Mapping XS 30da8fb9
END DESCRIPTION:
XS GIS Cut Line= 4
      2298912.90      7156890.71      2298834.71      7157094.53
      2298510.21      7157374.77      2298262.35      7157293.83
#Sta/Elev= 30
  4589.9  803.28  4615.3  801.77  4621.3  800.19  4675.4  779.95  4685.5  777.86
  4694.7  778.43  4725.3  775.57  4726.7  775.07  4734.8  775.57  4749.4  779.10
  4754.7  775.66  4760.5  779.19  4771.2  781.61  4787.4  782.08  5093.1  782.06
  5099.7  783.52  5106.4  782.07  5142.5  782.05  5185.3  782.65  5191.9  784.03
  5206.1  782.55  5248.8  783.06  5280.3  785.26  5303.6  782.62  5330.3  783.85
  5335.5  782.99  5425.9  785.44  5463.1  785.09  5495.0  790.38  5497.7  793.21
#Mann=4,-1,0
  4589.9    0.12       0  4725.3   0.033       0  4734.8    0.12       0
  4787.4    0.05       0
Bank Sta=4725.3,4734.8
Exp/Cntr=0.3,0.1

Type RM Length L Ch R = 1,4592,442,442,442
BEGIN DESCRIPTION:
MDE S 006 9.0
END DESCRIPTION:
XS GIS Cut Line= 3
      2298829.03      7156809.98      2298679.00      7156910.00
      2298329.02      7157159.98
#Sta/Elev= 30
  4824.4  802.91  4827.4  802.91  4831.9  800.10  4838.0  800.30  4853.0  795.74
  4868.0  785.95  4904.1  773.89  4940.1  769.19  4961.1  763.08  5007.8  761.46
  5012.1  763.48  5041.6  763.16  5078.6  761.29  5080.0  760.79  5088.1  761.29
  5224.0  764.02  5291.0  767.57  5335.3  774.11  5341.4  772.64  5356.2  778.39
  5362.3  777.28  5370.9  779.80  5377.1  778.80  5385.7  782.40  5398.0  783.47
  5406.6  786.89  5412.7  784.92  5421.3  788.94  5427.5  787.59  5434.8  789.64
#Mann=4,-1,0
  4824.4    0.12       0  5078.6    0.07       0  5088.1    0.12       0
  5224.0    0.05       0
Bank Sta=5078.6,5088.1
Exp/Cntr=0.3,0.1

Type RM Length L Ch R = 1,4150,223,223,223
BEGIN DESCRIPTION:
MDE S 006 8.0
END DESCRIPTION:
XS GIS Cut Line= 3
      2298678.97      7156560.00      2298479.00      7156560.00
      2298078.98      7156910.01
#Sta/Elev= 30
  4800.0  797.46  4802.5  797.46  4810.0  791.27  4830.0  782.69  4840.0  777.05
  4850.0  774.12  4870.0  771.39  4910.0  767.83  4950.0  766.42  4980.0  763.99
  5000.0  761.75  5002.3  760.35  5003.6  759.85  5011.9  760.35  5021.3  761.23
  5028.0  760.92  5049.8  766.12  5056.4  767.12  5106.3  766.51  5162.7  766.94
  5262.4  764.72  5353.6  769.61  5425.2  775.16  5438.9  775.67  5460.8  774.52
  5489.2  776.14  5503.5  778.78  5510.1  781.16  5528.2  785.51  5531.5  785.51
#Mann=4,-1,0
  4800.0    0.12       0  5002.3    0.07       0  5011.9    0.12       0
  5353.6    0.05       0
Bank Sta=5002.3,5011.9
Exp/Cntr=0.3,0.1

Type RM Length L Ch R = 1,3927,329,329,329
BEGIN DESCRIPTION:
Mapping XS ff715bc7
END DESCRIPTION:
XS GIS Cut Line= 2
      2298556.45      7156220.46      2297979.89      7156745.80
#Sta/Elev= 30
  4776.2  803.68  4788.0  802.59  4795.4  800.36  4802.2  799.32  4809.6  795.96
  4816.4  795.38  4823.8  789.77  4830.6  788.91  4852.2  778.85  4858.9  777.38
  4866.4  772.97  4880.5  770.06  4901.5  767.11  4929.9  765.85  4958.2  766.14
  4988.6  759.01  4989.9  758.51  4998.2  759.01  5000.8  762.89  5015.0  765.55
  5021.8  765.97  5163.6  764.78  5255.5  762.80  5284.7  763.80  5347.4  768.33
  5390.0  772.69  5467.7  773.18  5496.1  774.74  5524.4  781.84  5556.2  785.84
#Mann=4,-1,0
  4776.2    0.12       0  4988.6    0.07       0  4998.2    0.12       0
  5284.7    0.05       0
Bank Sta=4988.6,4998.2
Exp/Cntr=0.3,0.1

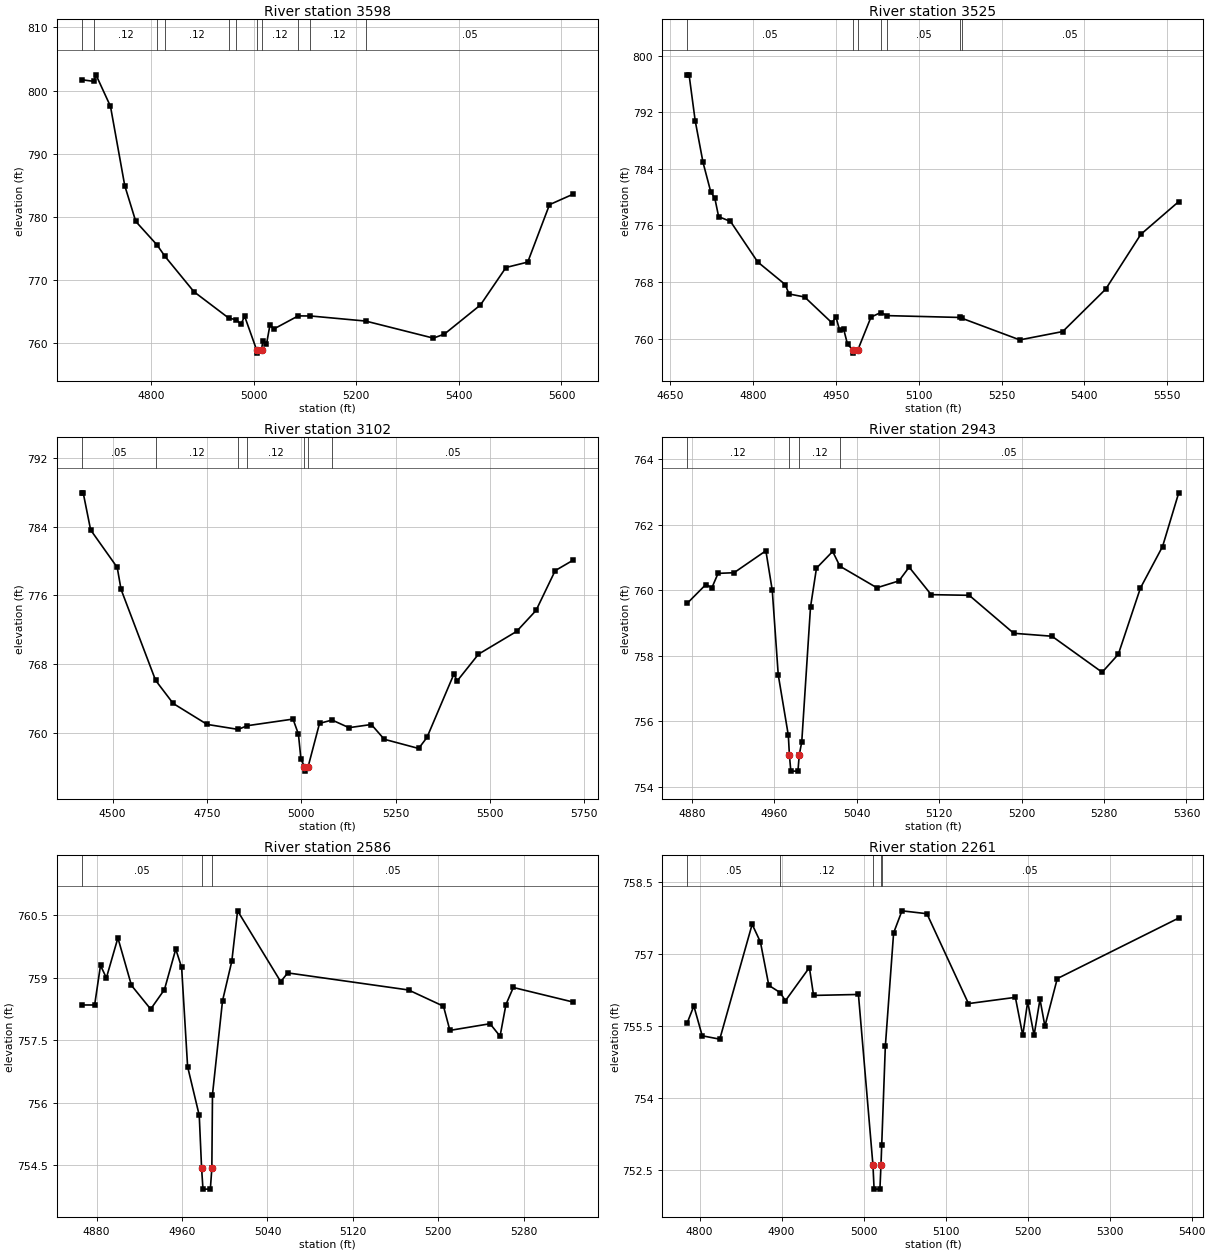
Type RM Length L Ch R = 1,3598,73,73,73
BEGIN DESCRIPTION:
Mapping XS 767d7c5d
END DESCRIPTION:
XS GIS Cut Line= 3
      2298570.27      7155831.77      2298309.99      7156074.67
      2297895.47      7156511.89
#Sta/Elev= 30
  4664.3  801.72  4688.4  801.45  4692.5  802.49  4720.8  797.49  4748.6  784.93
  4770.1  779.25  4811.6  775.52  4827.2  773.70  4883.5  768.11  4951.2  763.94
  4966.1  763.66  4975.3  762.96  4982.2  764.25  5005.7  758.88  5007.0  758.38
  5015.3  758.88  5017.6  760.27  5024.9  759.79  5031.8  762.89  5039.1  762.20
  5086.7  764.28  5110.5  764.27  5218.4  763.46  5350.1  760.76  5371.6  761.39
  5442.0  766.01  5491.7  771.95  5534.2  772.81  5576.6  781.91  5622.8  783.58
#Mann=11,-1,0
  4664.3    0.05       0  4688.4    0.12       0  4811.6    0.05       0
  4827.2    0.12       0  4951.2    0.05       0  4966.1    0.12       0
  5005.7    0.07       0  5015.3    0.12       0  5086.7    0.05       0
  5110.5    0.12       0  5218.4    0.05       0
Bank Sta=5005.7,5015.3
Exp/Cntr=0.3,0.1

Type RM Length L Ch R = 1,3525,423,423,423
BEGIN DESCRIPTION:
Mapping XS 1f8ce960
END DESCRIPTION:
XS GIS Cut Line= 3
      2298499.72      7155769.65      2298266.37      7156018.68
      2297855.08      7156382.82
#Sta/Elev= 30
  4680.3  797.28  4684.0  797.28  4695.0  790.82  4709.2  784.92  4723.3  780.73
  4730.6  779.86  4737.5  777.24  4759.0  776.57  4808.3  770.84  4858.1  767.65
  4865.0  766.32  4893.3  765.89  4942.6  762.25  4950.0  763.05  4956.8  761.17
  4964.1  761.31  4971.0  759.20  4980.3  758.46  4981.7  757.96  4989.9  758.46
  5013.5  763.05  5031.0  763.69  5042.6  763.26  5174.5  763.00  5178.0  762.89
  5283.0  759.83  5360.8  761.01  5438.6  767.00  5502.2  774.74  5570.9  779.37
#Mann=7,-1,0
  4680.3    0.05       0  4980.3   0.033       0  4989.9    0.05       0
  5031.0    0.12       0  5042.6    0.05       0  5174.5    0.12       0
  5178.0    0.05       0
Bank Sta=4980.3,4989.9
Exp/Cntr=0.3,0.1

Type RM Length L Ch R = 1,3102,159,159,159
BEGIN DESCRIPTION:
Mapping XS 90530d44
END DESCRIPTION:
XS GIS Cut Line= 5
      2298483.04      7155477.13      2298239.71      7155506.79
      2297916.58      7155892.30      2297773.96      7156153.95
      2297820.11      7156406.93
#Sta/Elev= 30
  4417.5  787.93  4422.0  787.93  4441.7  783.61  4512.2  779.24  4522.3  776.69
  4613.9  766.09  4660.5  763.40  4750.5  760.96  4832.9  760.38  4856.8  760.81
  4978.2  761.58  4992.5  759.82  4999.0  756.98  5008.5  756.02  5009.8  755.52
  5018.1  756.02  5048.4  761.08  5081.7  761.47  5126.5  760.58  5185.8  760.95
  5220.0  759.23  5311.1  758.16  5333.2  759.44  5404.4  766.80  5413.6  766.04
  5469.8  769.14  5570.8  771.79  5622.3  774.23  5673.1  778.87  5720.8  780.09
#Mann=7,-1,0
  4417.5    0.05       0  4613.9    0.12       0  4832.9    0.05       0
  4856.8    0.12       0  5008.5    0.07       0  5018.1    0.12       0
  5081.7    0.05       0
Bank Sta=5008.5,5018.1
Exp/Cntr=0.3,0.1

Type RM Length L Ch R = 1,2943,357,357,357
BEGIN DESCRIPTION:
Mapping XS 65cb335f
END DESCRIPTION:
XS GIS Cut Line= 2
      2297946.15      7155594.09      2297704.08      7156005.22
#Sta/Elev= 30
  4875.4  759.60  4893.7  760.18  4899.5  760.08  4905.5  760.52  4921.0  760.54
  4951.9  761.21  4958.1  760.00  4963.9  757.42  4973.7  755.57  4974.7  754.98
  4976.1  754.48  4983.0  754.48  4984.3  754.98  4986.7  755.37  4995.2  759.49
  5001.0  760.68  5016.7  761.19  5023.7  760.74  5059.6  760.08  5081.0  760.29
  5090.9  760.71  5112.3  759.87  5149.2  759.85  5192.4  758.69  5229.5  758.60
  5278.2  757.50  5293.9  758.05  5315.3  760.07  5336.8  761.34  5352.5  762.98
#Mann=4,-1,0
  4875.4    0.12       0  4974.7    0.07       0  4984.3    0.12       0
  5023.7    0.05       0
Bank Sta=4974.7,4984.3
Exp/Cntr=0.3,0.1

Type RM Length L Ch R = 1,2586,325,325,325
BEGIN DESCRIPTION:
Mapping XS a293273b
END DESCRIPTION:
XS GIS Cut Line= 2
      2297721.09      7155338.71      2297538.42      7155761.54
#Sta/Elev= 30
  4865.8  758.35  4878.1  758.35  4883.6  759.30  4889.1  759.00  4899.9  759.96
  4912.6  758.82  4930.6  758.25  4943.5  758.72  4954.1  759.69  4959.6  759.25
  4965.2  756.87  4976.1  755.70  4978.3  754.43  4979.6  753.93  4986.5  753.93
  4987.9  754.43  4988.5  756.20  4997.9  758.45  5006.6  759.40  5012.0  760.61
  5052.4  758.91  5059.0  759.12  5172.2  758.71  5204.9  758.32  5210.9  757.74
  5248.5  757.90  5257.9  757.60  5263.4  758.36  5270.3  758.77  5326.4  758.42
#Mann=3,-1,0
  4865.8    0.05       0  4978.3   0.033       0  4987.9    0.05       0
Bank Sta=4978.3,4987.9
Exp/Cntr=0.3,0.1

Type RM Length L Ch R = 1,2261,354,354,354
BEGIN DESCRIPTION:
Mapping XS 5ee7e3f6
END DESCRIPTION:
XS GIS Cut Line= 3
      2297400.14      7155181.79      2297337.62      7155542.63
      2297467.35      7155736.65
#Sta/Elev= 30
  4784.7  755.55  4793.0  755.91  4803.2  755.29  4824.6  755.22  4864.1  757.61
  4874.2  757.24  4884.4  756.34  4898.1  756.19  4904.7  756.02  4933.9  756.71
  4939.0  756.13  4993.7  756.15  5011.4  752.60  5012.8  752.10  5019.9  752.10
  5021.2  752.60  5022.1  753.02  5026.5  755.07  5036.6  757.43  5046.8  757.89
  5077.2  757.83  5127.9  755.96  5185.1  756.09  5194.1  755.30  5200.1  756.00
  5207.9  755.30  5215.1  756.05  5221.1  755.49  5236.2  756.48  5384.3  757.74
#Mann=5,-1,0
  4784.7    0.05       0  4898.1    0.12       0  5011.4    0.07       0
  5021.2    0.12       0  5022.1    0.05       0
Bank Sta=5011.4,5021.2
Exp/Cntr=0.3,0.1

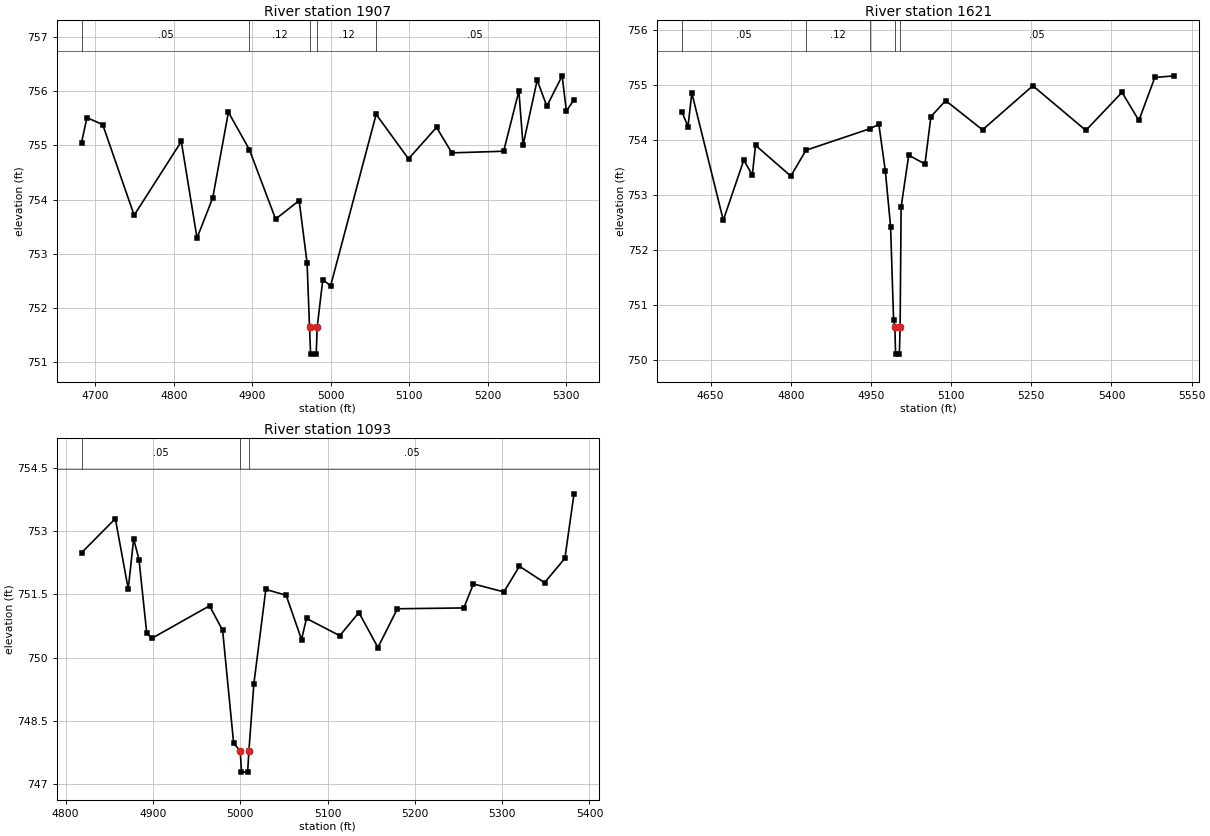
Type RM Length L Ch R = 1,1907,286,286,286
BEGIN DESCRIPTION:
Mapping XS 8de94f23
END DESCRIPTION:
XS GIS Cut Line= 3
      2297068.12      7154993.07      2297048.76      7155401.85
      2297252.90      7155478.50
#Sta/Elev= 30
  4682.6  755.05  4689.5  755.51  4709.6  755.38  4749.6  753.71  4809.7  755.07
  4829.7  753.29  4849.7  754.03  4869.7  755.61  4896.4  754.92  4929.8  753.64
  4959.8  753.98  4969.9  752.83  4973.0  751.65  4974.4  751.15  4981.5  751.15
  4982.8  751.65  4989.9  752.52  4999.9  752.41  5057.9  755.57  5099.1  754.75
  5134.8  755.33  5154.3  754.86  5220.3  754.89  5239.7  756.00  5245.0  755.00
  5263.0  756.20  5275.3  755.72  5294.8  756.28  5300.2  755.63  5309.9  755.84
#Mann=5,-1,0
  4682.6    0.05       0  4896.4    0.12       0  4973.0    0.07       0
  4982.8    0.12       0  5057.9    0.05       0
Bank Sta=4973,4982.8
Exp/Cntr=0.3,0.1

Type RM Length L Ch R = 1,1621,528,528,528
BEGIN DESCRIPTION:
Mapping XS b191aae9
END DESCRIPTION:
XS GIS Cut Line= 4
      2296988.56      7154953.84      2296796.15      7155317.00
      2296809.44      7155401.39      2297225.04      7155489.71
#Sta/Elev= 30
  4596.6  754.50  4607.8  754.24  4614.9  754.85  4673.8  752.54  4712.1  753.63
  4728.1  753.36  4734.1  753.90  4800.1  753.34  4828.5  753.81  4948.0  754.20
  4964.8  754.28  4977.0  753.43  4986.8  752.42  4992.4  750.73  4994.8  750.61
  4996.1  750.11  5003.2  750.11  5004.6  750.61  5006.5  752.78  5020.7  753.72
  5051.1  753.56  5062.2  754.42  5089.8  754.71  5158.8  754.18  5252.9  754.98
  5352.1  754.17  5419.7  754.86  5451.3  754.35  5481.1  755.13  5517.9  755.16
#Mann=5,-1,0
  4596.6    0.05       0  4828.5    0.12       0  4948.0    0.05       0
  4994.8   0.033       0  5004.6    0.05       0
Bank Sta=4994.8,5004.6
Exp/Cntr=0.3,0.1

Type RM Length L Ch R = 1,1093,0,0,0
BEGIN DESCRIPTION:
MDE S 006 4.0
END DESCRIPTION:
XS GIS Cut Line= 3
      2296617.48      7154795.61      2296512.12      7154951.79
      2296360.15      7155295.39
#Sta/Elev= 30
  4818.2  752.49  4856.9  753.30  4871.7  751.63  4877.9  752.82  4884.0  752.33
  4892.9  750.58  4898.9  750.46  4964.8  751.23  4979.8  750.65  4992.4  747.97
  5000.0  747.78  5001.4  747.28  5008.5  747.28  5009.9  747.78  5015.6  749.38
  5029.3  751.62  5052.6  751.48  5070.2  750.43  5075.9  750.93  5114.0  750.52
  5135.9  751.07  5157.7  750.24  5180.0  751.16  5256.1  751.18  5267.1  751.75
  5302.0  751.56  5319.8  752.17  5348.6  751.78  5371.9  752.36  5382.3  753.89
#Mann=3,-1,0
  4818.2    0.05       0  5000.0   0.033       0  5009.9    0.05       0
Bank Sta=5000,5009.9
Exp/Cntr=0.3,0.1

Chan Stop Cuts=-1