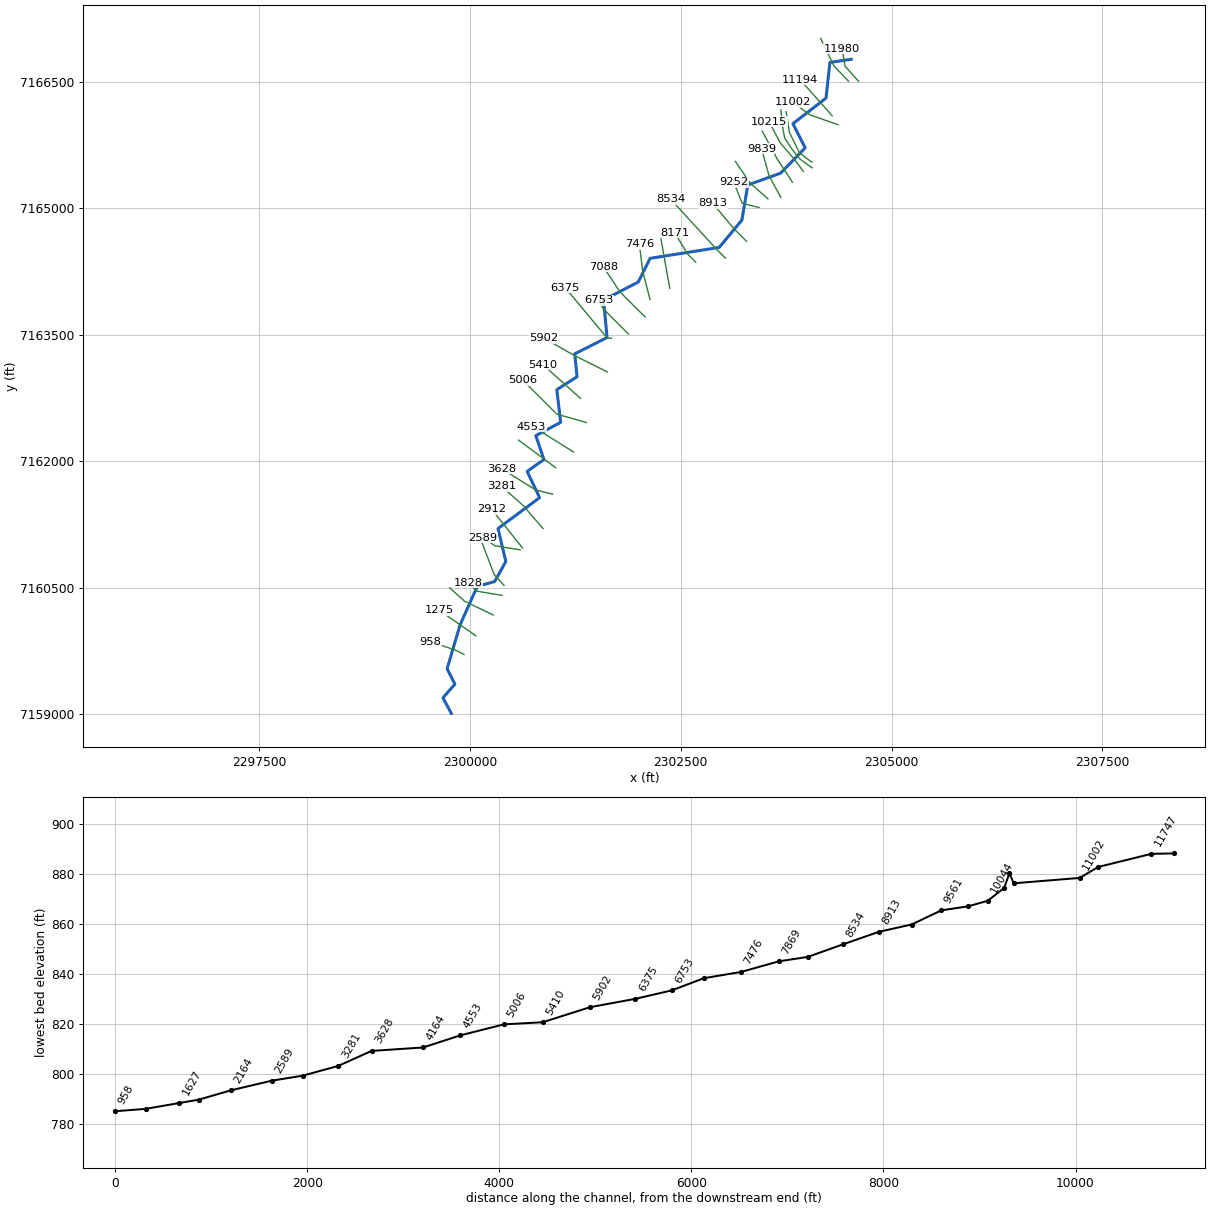
--- MDE S 007.prj (project) ---

Proj Title=MDE S 007 Base Level Engineering
Current Plan=p01
Default Exp/Contr=0.3,0.1
English Units
Geom File=g01
Flow File=f01
Plan File=p01
BEGIN DESCRIPTION:
MDE S 007
END DESCRIPTION:

--- MDE S 007.p01 (plan) ---

Plan Title=Multiple Run
Short Identifier=Multiple
Geom File=g01
Flow File=f01
Subcritical Flow
K Sum by GR= 0
Std Step Tol= 0.01
Critical Tol= 0.01
Num of Std Step Trials= 20
Max Error Tol= 0.3
Flow Tol Ratio= 0.001
Split Flow NTrial= 30
Split Flow Tol= 0.02
Split Flow Ratio= 0.02
Log Output Level= 0
Friction Slope Method= 1
Unsteady Friction Slope Method= 2
Unsteady Bridges Friction Slope Method= 1
Parabolic Critical Depth
Global Vel Dist=  1 , 1 , 1
Global Log Level= 0
CheckData=True
Encroach Param= -1, 0, 0, 0
BEGIN DESCRIPTION:
Multiple Run
END DESCRIPTION:

--- MDE S 007.f01 (steady flow) ---

Flow Title=Multiple
Number of Profiles=7
Profile Names=10-year,25-year,50-year,1pct_min,100-year,1pct_plu,500-year
River Rch & RM= MDE S 007,Reach-1,11980
     697     959    1176     717    1430    2853    2116
River Rch & RM= MDE S 007,Reach-1,5410
     818    1135    1399     856    1708    3408    2551
Boundary for River Rch & Prof#=MDE S 007,Reach-1,1
Up Type=0
Dn Type=3
Dn Slope=0.005
Boundary for River Rch & Prof#=MDE S 007,Reach-1,2
Up Type=0
Dn Type=3
Dn Slope=0.005
Boundary for River Rch & Prof#=MDE S 007,Reach-1,3
Up Type=0
Dn Type=3
Dn Slope=0.005
Boundary for River Rch & Prof#=MDE S 007,Reach-1,4
Up Type=0
Dn Type=3
Dn Slope=0.005
Boundary for River Rch & Prof#=MDE S 007,Reach-1,5
Up Type=0
Dn Type=3
Dn Slope=0.005
Boundary for River Rch & Prof#=MDE S 007,Reach-1,6
Up Type=0
Dn Type=3
Dn Slope=0.005
Boundary for River Rch & Prof#=MDE S 007,Reach-1,7
Up Type=0
Dn Type=3
Dn Slope=0.005

--- MDE S 007.g01 (geometry) ---

Geom Title=Existing Conditions

River Reach=MDE S 007,Reach-1
Reach XY= 30
      2304521.43      7166768.15      2304268.89      7166730.44
      2304223.17      7166307.70      2303830.49      7166004.15
      2303975.70      7165718.48      2303685.17      7165417.86
      2303295.11      7165277.17      2303225.47      7164861.45
      2302955.89      7164536.26      2302137.46      7164407.38
      2301996.13      7164126.30      2301584.34      7163912.74
      2301626.08      7163467.98      2301242.37      7163273.79
      2301269.99      7163002.94      2301030.04      7162849.57
      2301075.67      7162461.69      2300780.58      7162303.97
      2300877.51      7162021.54      2300678.53      7161880.17
      2300825.98      7161568.64      2300332.00      7161201.65
      2300425.53      7160811.50      2300292.73      7160573.20
      2300086.68      7160516.52      2299882.52      7160058.72
      2299728.89      7159539.90      2299821.40      7159356.66
      2299679.36      7159194.82      2299779.00      7159010.00

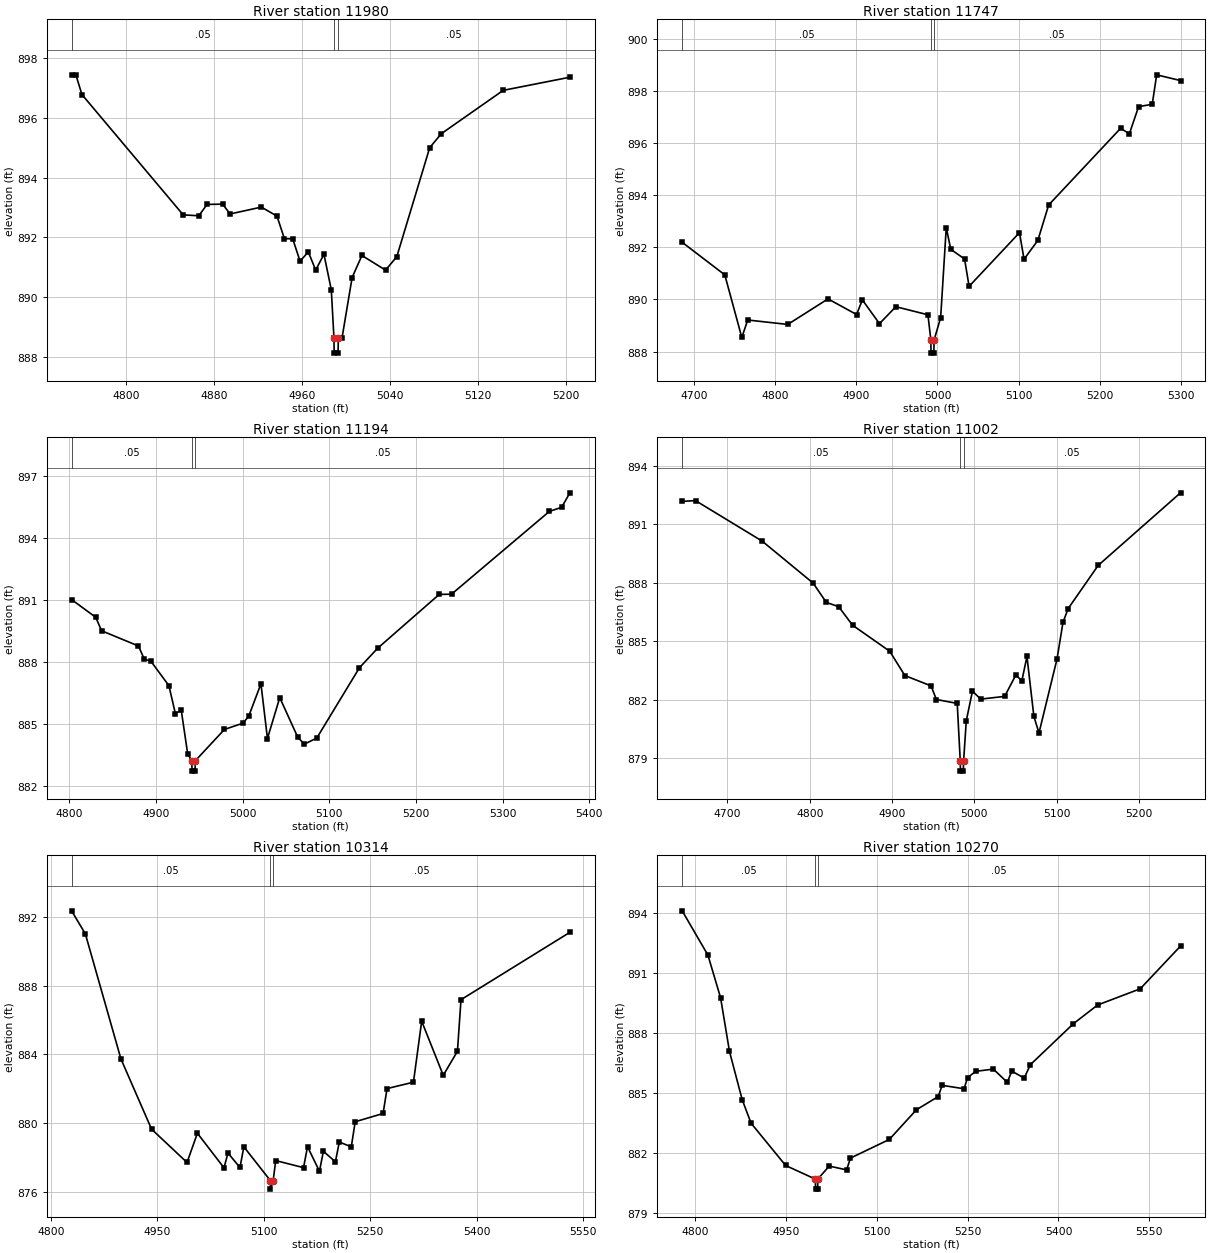
Type RM Length L Ch R = 1,11980,233,233,233
BEGIN DESCRIPTION:
MDE S 007 26.0
END DESCRIPTION:
XS GIS Cut Line= 3
      2304609.20      7166506.74      2304448.15      7166686.86
      2304414.39      7166895.33
#Sta/Elev= 30
  4750.5  897.44  4754.4  897.44  4759.9  896.78  4851.9  892.75  4866.1  892.72
  4873.6  893.10  4887.8  893.11  4894.5  892.78  4922.9  893.01  4937.1  892.71
  4943.9  891.95  4951.4  891.95  4958.1  891.20  4965.6  891.51  4972.3  890.90
  4979.8  891.43  4986.5  890.24  4988.9  888.62  4989.1  888.12  4992.6  888.12
  4992.9  888.62  4996.2  888.62  5005.4  890.65  5014.3  891.39  5035.8  890.90
  5046.0  891.35  5075.9  895.00  5086.5  895.47  5142.7  896.92  5203.3  897.36
#Mann=3,-1,0
  4750.5    0.05       0  4988.9    0.04       0  4992.9    0.05       0
Bank Sta=4988.9,4992.9
Exp/Cntr=0.3,0.1

Type RM Length L Ch R = 1,11747,553,553,553
BEGIN DESCRIPTION:
Mapping XS 28008601
END DESCRIPTION:
XS GIS Cut Line= 3
      2304490.55      7166507.22      2304317.11      7166688.95
      2304158.86      7167016.52
#Sta/Elev= 30
  4684.9  892.19  4737.5  890.94  4758.5  888.54  4765.8  889.21  4815.2  889.04
  4864.9  890.02  4900.1  889.42  4907.3  889.98  4928.4  889.07  4948.6  889.72
  4988.2  889.41  4991.8  888.44  4992.0  887.94  4995.5  887.94  4995.8  888.44
  5003.9  889.30  5010.8  892.75  5016.4  891.92  5033.4  891.55  5039.0  890.50
  5101.2  892.56  5106.8  891.54  5123.8  892.26  5137.2  893.62  5226.0  896.56
  5236.8  896.35  5248.2  897.39  5265.0  897.48  5270.5  898.61  5299.9  898.39
#Mann=3,-1,0
  4684.9    0.05       0  4991.8   0.033       0  4995.8    0.05       0
Bank Sta=4991.8,4995.8
Exp/Cntr=0.3,0.1

Type RM Length L Ch R = 1,11194,192,192,192
BEGIN DESCRIPTION:
Mapping XS 90c22f2c
END DESCRIPTION:
XS GIS Cut Line= 2
      2304296.19      7166098.31      2303913.73      7166527.66
#Sta/Elev= 30
  4802.6  891.01  4830.5  890.15  4837.2  889.50  4879.8  888.76  4886.5  888.12
  4894.0  888.03  4914.9  886.84  4922.4  885.48  4929.1  885.66  4936.6  883.53
  4941.3  883.20  4941.6  882.70  4945.1  882.70  4945.3  883.20  4979.0  884.72
  5000.2  885.02  5006.9  885.35  5021.1  886.93  5028.6  884.28  5042.8  886.26
  5063.7  884.33  5071.3  884.01  5085.5  884.30  5134.8  887.71  5155.7  888.65
  5226.8  891.26  5241.0  891.27  5353.9  895.28  5368.1  895.48  5377.6  896.18
#Mann=3,-1,0
  4802.6    0.05       0  4941.3    0.04       0  4945.3    0.05       0
Bank Sta=4941.3,4945.3
Exp/Cntr=0.3,0.1

Type RM Length L Ch R = 1,11002,688,688,688
BEGIN DESCRIPTION:
MDE S 007 25.0
END DESCRIPTION:
XS GIS Cut Line= 3
      2304364.24      7165992.35      2304029.00      7166110.00
      2303828.99      7166260.01
#Sta/Elev= 30
  4645.0  892.18  4661.2  892.22  4742.1  890.14  4804.1  887.98  4820.1  886.99
  4835.1  886.77  4851.9  885.82  4897.1  884.48  4915.5  883.23  4947.3  882.70
  4953.8  882.00  4979.1  881.80  4982.8  878.82  4983.0  878.32  4986.5  878.32
  4986.8  878.82  4990.1  880.91  4997.6  882.43  5007.6  882.02  5036.7  882.16
  5050.3  883.26  5057.6  882.96  5063.8  884.21  5072.2  881.13  5078.4  880.28
  5100.3  884.08  5107.6  885.97  5113.8  886.67  5150.3  888.89  5250.3  892.62
#Mann=3,-1,0
  4645.0    0.05       0  4982.8   0.033       0  4986.8    0.05       0
Bank Sta=4982.8,4986.8
Exp/Cntr=0.3,0.1

Type RM Length L Ch R = 1,10314,44,44,44
BEGIN DESCRIPTION:
Mapping XS 2f6cf376
END DESCRIPTION:
XS GIS Cut Line= 4
      2304054.52      7165547.57      2303909.84      7165656.43
      2303789.19      7165899.76      2303749.65      7166146.25
#Sta/Elev= 30
  4829.1  892.35  4848.5  891.01  4898.6  883.74  4941.8  879.65  4991.8  877.71
  5006.4  879.41  5043.9  877.40  5049.5  878.26  5066.4  877.42  5071.9  878.62
  5109.2  876.66  5109.4  876.16  5113.2  876.66  5116.8  877.82  5156.0  877.41
  5161.6  878.63  5178.4  877.20  5184.0  878.36  5200.9  877.75  5206.4  878.90
  5223.3  878.62  5228.8  880.08  5268.1  880.56  5273.7  882.01  5310.9  882.38
  5322.5  885.93  5352.9  882.78  5372.9  884.18  5377.9  887.18  5531.4  891.10
#Mann=3,-1,0
  4829.1    0.05       0  5109.2    0.04       0  5113.2    0.05       0
Bank Sta=5109.2,5113.2
Exp/Cntr=0.3,0.1

Type RM Length L Ch R = 1,10270,55,55,55
BEGIN DESCRIPTION:
Mapping XS c3b60f3f
END DESCRIPTION:
XS GIS Cut Line= 6
      2304058.87      7165480.50      2303916.06      7165582.91
      2303820.34      7165700.95      2303732.93      7165832.56
      2303708.74      7165961.47      2303688.54      7166166.12
#Sta/Elev= 30
  4778.9  894.10  4821.4  891.89  4842.3  889.76  4857.0  887.08  4877.9  884.68
  4892.6  883.50  4949.7  881.39  4998.7  880.71  4999.0  880.21  5002.5  880.21
  5002.7  880.71  5021.6  881.36  5050.3  881.17  5056.7  881.76  5120.8  882.69
  5165.5  884.17  5201.5  884.83  5208.0  885.39  5244.1  885.22  5250.1  885.78
  5263.6  886.09  5292.5  886.20  5315.5  885.54  5323.0  886.10  5343.4  885.75
  5353.6  886.42  5424.4  888.46  5464.6  889.40  5535.0  890.21  5601.4  892.34
#Mann=3,-1,0
  4778.9    0.05       0  4998.7    0.04       0  5002.7    0.05       0
Bank Sta=4998.7,5002.7
Exp/Cntr=0.3,0.1

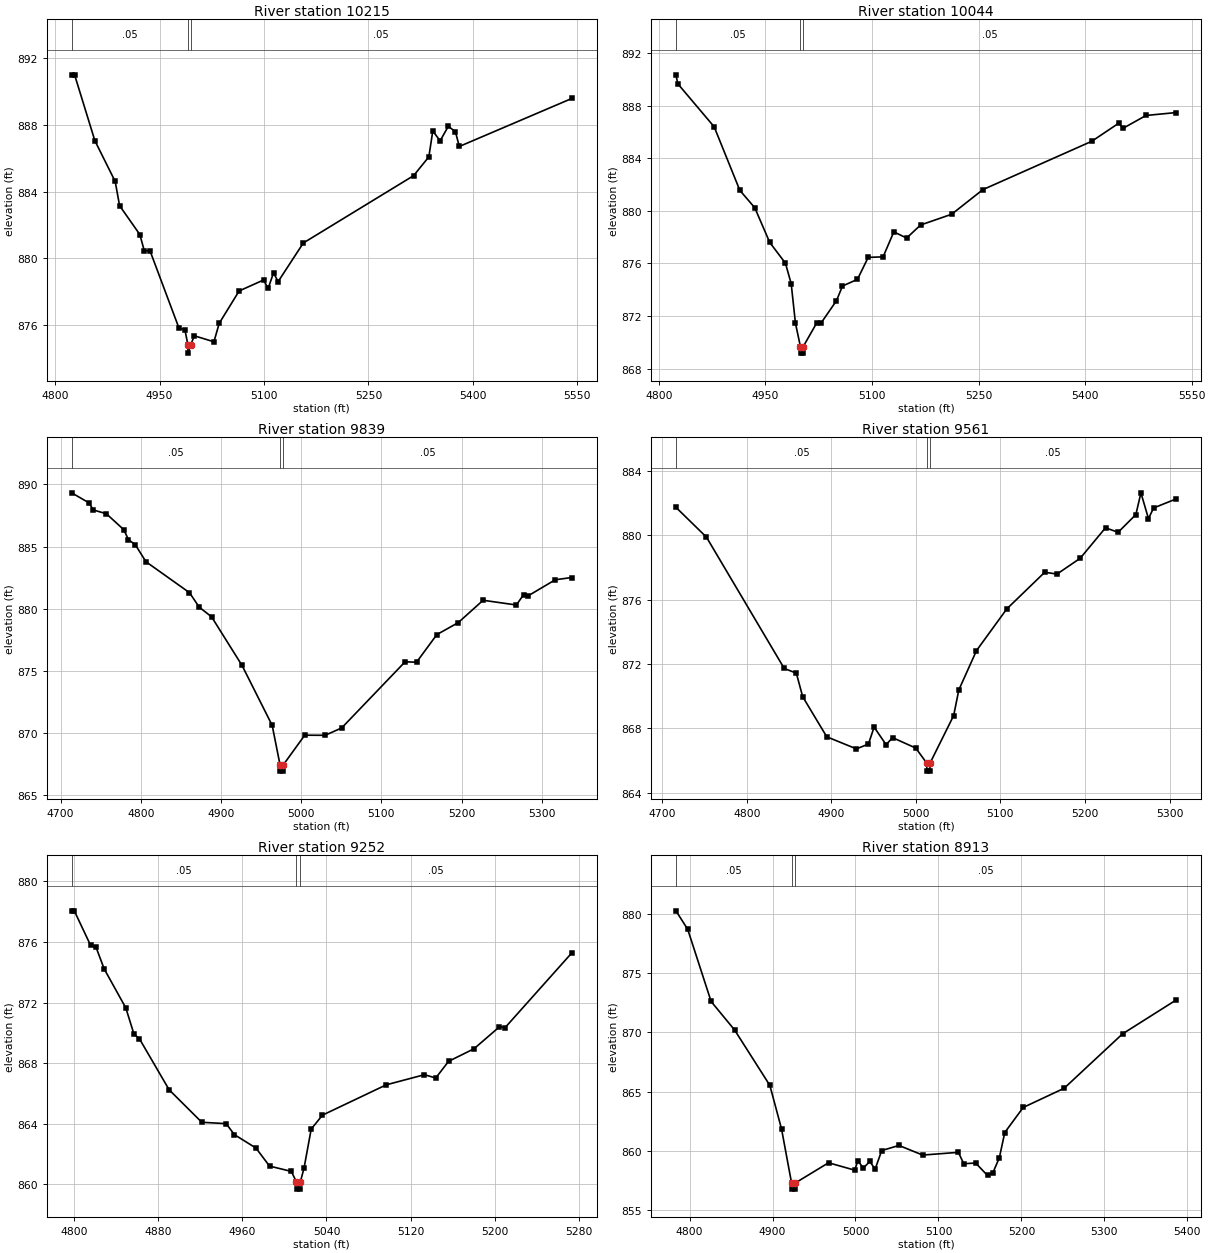
Type RM Length L Ch R = 1,10215,171,171,171
BEGIN DESCRIPTION:
Mapping XS 1a668906
END DESCRIPTION:
XS GIS Cut Line= 4
      2303953.91      7165438.30      2303845.18      7165584.33
      2303683.30      7165773.11      2303546.74      7166026.06
#Sta/Elev= 30
  4823.8  891.01  4828.0  891.01  4857.1  887.06  4886.3  884.61  4892.6  883.16
  4921.8  881.42  4928.0  880.46  4936.4  880.44  4978.1  875.79  4986.4  875.72
  4990.7  874.81  4990.9  874.31  4994.7  874.81  5000.0  875.35  5028.1  874.99
  5035.7  876.10  5064.3  878.04  5099.4  878.70  5106.0  878.19  5113.7  879.13
  5120.3  878.60  5156.5  880.92  5314.9  884.96  5336.8  886.09  5342.4  887.64
  5353.0  887.05  5364.7  887.92  5374.9  887.60  5380.5  886.71  5542.0  889.59
#Mann=3,-1,0
  4823.8    0.05       0  4990.7    0.04       0  4994.7    0.05       0
Bank Sta=4990.7,4994.7
Exp/Cntr=0.3,0.1

Type RM Length L Ch R = 1,10044,205,205,205
BEGIN DESCRIPTION:
Mapping XS 192dc1dc
END DESCRIPTION:
XS GIS Cut Line= 3
      2303824.43      7165311.36      2303647.16      7165580.10
      2303466.34      7165916.55
#Sta/Elev= 30
  4824.1  890.34  4826.7  889.66  4877.9  886.39  4914.0  881.56  4935.1  880.23
  4956.1  877.60  4978.2  876.02  4986.3  874.47  4992.3  871.46  4999.3  869.68
  4999.6  869.18  5003.1  869.18  5003.3  869.68  5022.4  871.49  5028.4  871.47
  5050.1  873.17  5058.5  874.28  5079.6  874.79  5094.7  876.46  5115.7  876.50
  5130.8  878.40  5148.8  877.93  5168.4  878.92  5212.2  879.74  5256.1  881.61
  5409.5  885.29  5447.6  886.67  5453.3  886.27  5485.8  887.25  5528.0  887.47
#Mann=3,-1,0
  4824.1    0.05       0  4999.3    0.04       0  5003.3    0.05       0
Bank Sta=4999.3,5003.3
Exp/Cntr=0.3,0.1

Type RM Length L Ch R = 1,9839,278,278,278
BEGIN DESCRIPTION:
Mapping XS 19bf4684
END DESCRIPTION:
XS GIS Cut Line= 3
      2303686.39      7165130.28      2303547.42      7165386.42
      2303459.06      7165706.53
#Sta/Elev= 30
  4713.9  889.33  4735.3  888.53  4741.0  887.95  4757.1  887.65  4779.0  886.36
  4784.7  885.56  4793.2  885.16  4806.5  883.79  4860.8  881.30  4872.9  880.14
  4888.3  879.36  4926.3  875.45  4963.9  870.63  4973.7  867.45  4974.0  866.95
  4977.5  866.95  4977.7  867.45  5004.5  869.84  5029.8  869.83  5050.5  870.42
  5129.6  875.74  5143.9  875.71  5169.2  877.93  5195.8  878.89  5226.9  880.69
  5268.4  880.31  5277.4  881.15  5282.6  881.03  5316.9  882.34  5337.4  882.52
#Mann=3,-1,0
  4713.9    0.05       0  4973.7   0.033       0  4977.7    0.05       0
Bank Sta=4973.7,4977.7
Exp/Cntr=0.3,0.1

Type RM Length L Ch R = 1,9561,309,309,309
BEGIN DESCRIPTION:
Mapping XS 96840805
END DESCRIPTION:
XS GIS Cut Line= 3
      2303533.88      7165113.59      2303324.84      7165297.52
      2303148.58      7165556.25
#Sta/Elev= 30
  4716.2  881.72  4752.3  879.87  4844.3  871.72  4858.6  871.43  4866.1  869.97
  4894.6  867.48  4929.7  866.73  4943.9  867.03  4950.6  868.08  4964.8  866.99
  4972.4  867.43  4999.9  866.78  5012.8  865.85  5013.1  865.35  5016.6  865.35
  5016.8  865.85  5044.7  868.80  5050.8  870.39  5071.7  872.83  5107.6  875.42
  5152.4  877.69  5167.0  877.58  5194.4  878.56  5224.3  880.45  5239.2  880.17
  5260.2  881.27  5266.2  882.62  5275.1  881.02  5281.2  881.68  5307.7  882.24
#Mann=3,-1,0
  4716.2    0.05       0  5012.8    0.04       0  5016.8    0.05       0
Bank Sta=5012.8,5016.8
Exp/Cntr=0.3,0.1

Type RM Length L Ch R = 1,9252,339,339,339
BEGIN DESCRIPTION:
MDE S 007 20.0
END DESCRIPTION:
XS GIS Cut Line= 3
      2303428.97      7165010.01      2303229.00      7165060.00
      2303128.99      7165310.02
#Sta/Elev= 30
  4797.8  878.05  4800.3  878.05  4815.8  875.77  4821.0  875.64  4828.7  874.22
  4849.3  871.64  4857.0  869.92  4862.2  869.61  4890.5  866.24  4921.5  864.10
  4944.7  864.01  4952.4  863.29  4973.0  862.40  4985.9  861.21  5006.6  860.86
  5011.3  860.19  5011.6  859.69  5015.1  859.69  5015.3  860.19  5018.7  861.08
  5025.5  863.65  5036.2  864.57  5096.8  866.57  5133.2  867.24  5143.9  867.02
  5156.1  868.12  5180.3  868.95  5204.5  870.40  5209.9  870.35  5273.2  875.27
#Mann=3,-1,0
  4797.8    0.05       0  5011.3    0.04       0  5015.3    0.05       0
Bank Sta=5011.3,5015.3
Exp/Cntr=0.3,0.1

Type RM Length L Ch R = 1,8913,379,379,379
BEGIN DESCRIPTION:
MDE S 007 19.0
END DESCRIPTION:
XS GIS Cut Line= 3
      2303279.02      7164609.98      2303129.00      7164760.00
      2302878.98      7165060.03
#Sta/Elev= 30
  4783.6  880.25  4797.8  878.69  4826.0  872.61  4854.3  870.21  4896.8  865.54
  4910.9  861.86  4923.0  857.30  4923.3  856.80  4926.8  856.80  4927.0  857.30
  4967.5  859.02  4999.0  858.40  5002.9  859.19  5009.4  858.57  5017.2  859.13
  5023.7  858.49  5031.6  860.05  5052.4  860.48  5081.0  859.67  5124.0  859.90
  5130.5  858.94  5144.8  859.00  5159.1  857.95  5165.6  858.18  5173.4  859.45
  5179.9  861.57  5202.1  863.68  5251.5  865.30  5321.8  869.88  5386.3  872.73
#Mann=3,-1,0
  4783.6    0.05       0  4923.0   0.033       0  4927.0    0.05       0
Bank Sta=4923,4927
Exp/Cntr=0.3,0.1

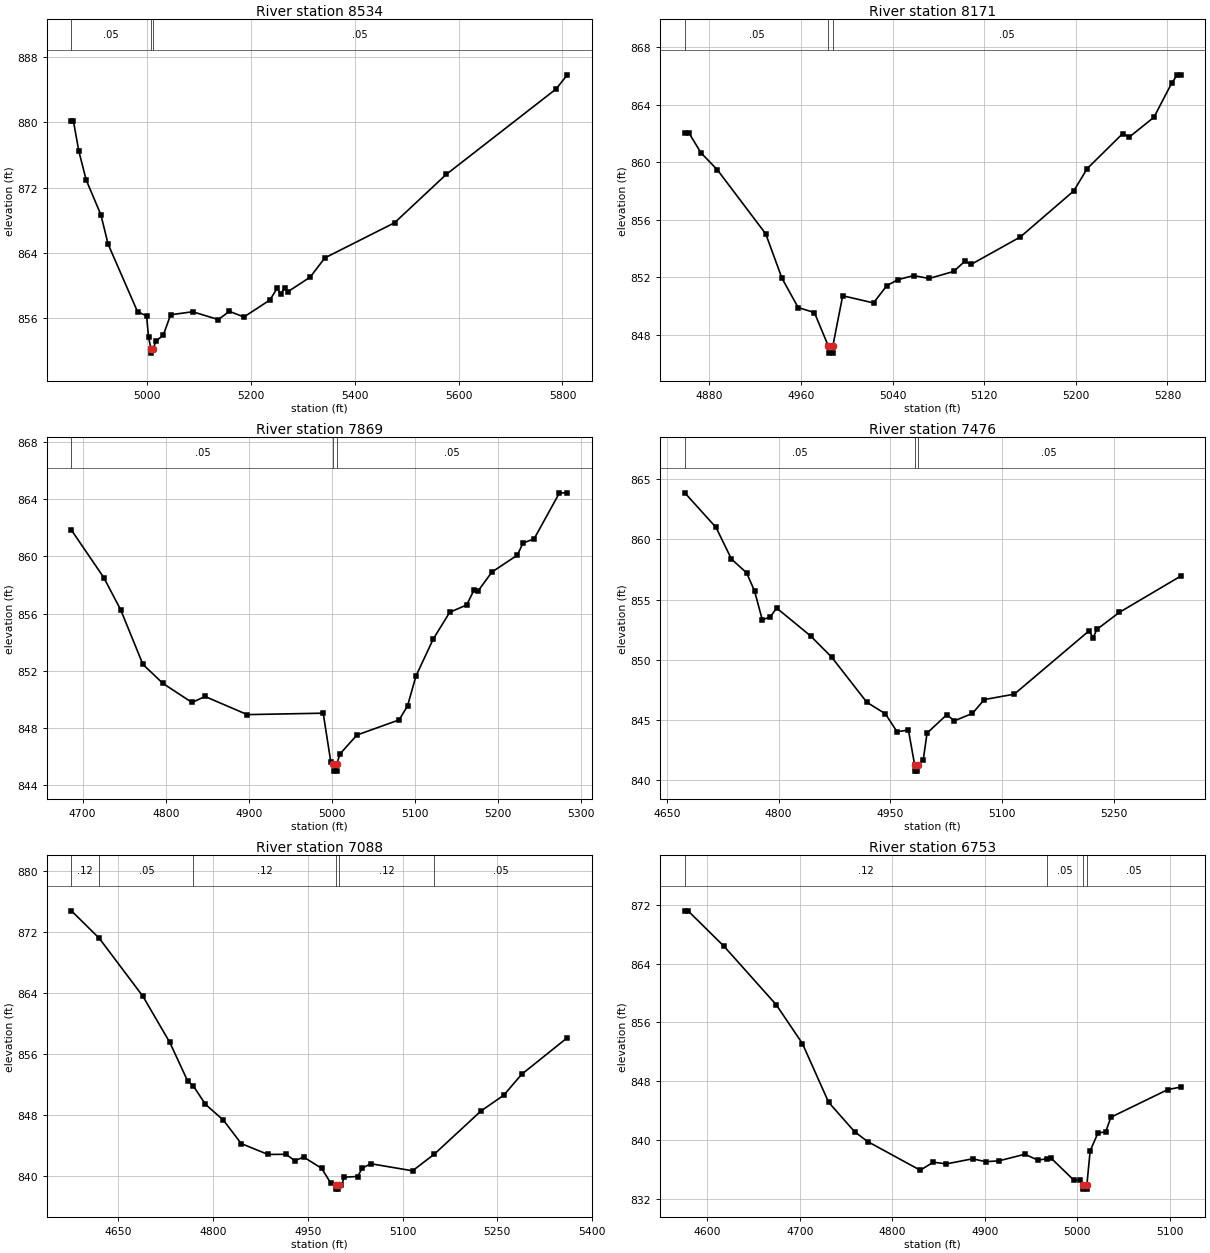
Type RM Length L Ch R = 1,8534,363,363,363
BEGIN DESCRIPTION:
MDE S 007 18.0
END DESCRIPTION:
XS GIS Cut Line= 3
      2303029.01      7164409.99      2302929.00      7164510.00
      2302378.99      7165110.02
#Sta/Elev= 30
  4853.9  880.22  4857.5  880.22  4868.1  876.47  4882.2  872.95  4910.5  868.69
  4924.6  865.06  4981.2  856.80  4998.7  856.28  5002.4  853.68  5007.2  852.22
  5007.5  851.72  5011.2  852.22  5016.6  853.18  5030.8  853.92  5045.0  856.42
  5087.5  856.79  5136.9  855.83  5158.1  856.84  5186.2  856.15  5236.1  858.22
  5250.3  859.67  5257.1  858.95  5264.5  859.70  5271.3  859.26  5313.8  861.03
  5342.2  863.39  5476.6  867.70  5575.9  873.61  5788.0  884.10  5809.3  885.82
#Mann=3,-1,0
  4853.9    0.05       0  5007.2   0.033       0  5011.2    0.05       0
Bank Sta=5007.2,5011.2
Exp/Cntr=0.3,0.1

Type RM Length L Ch R = 1,8171,302,302,302
BEGIN DESCRIPTION:
MDE S 007 17.0
END DESCRIPTION:
XS GIS Cut Line= 3
      2302679.03      7164359.97      2302579.00      7164460.00
      2302429.00      7164710.00
#Sta/Elev= 30
  4858.5  862.05  4862.1  862.05  4872.7  860.66  4886.8  859.50  4929.2  855.03
  4943.4  851.94  4957.5  849.91  4971.7  849.56  4983.8  847.24  4984.1  846.74
  4987.6  846.74  4987.8  847.24  4996.4  850.73  5023.3  850.23  5034.9  851.43
  5044.7  851.85  5058.3  852.13  5071.9  851.93  5093.3  852.42  5103.0  853.12
  5108.8  852.92  5151.6  854.82  5198.2  858.02  5209.9  859.57  5241.0  862.01
  5246.8  861.77  5268.2  863.14  5283.7  865.51  5288.6  866.09  5291.5  866.09
#Mann=3,-1,0
  4858.5    0.05       0  4983.8    0.04       0  4987.8    0.05       0
Bank Sta=4983.8,4987.8
Exp/Cntr=0.3,0.1

Type RM Length L Ch R = 1,7869,393,393,393
BEGIN DESCRIPTION:
Mapping XS ff1e4e4a
END DESCRIPTION:
XS GIS Cut Line= 2
      2302369.27      7164051.67      2302265.03      7164639.30
#Sta/Elev= 30
  4686.5  861.85  4725.4  858.52  4745.7  856.27  4772.5  852.44  4796.5  851.11
  4831.6  849.77  4847.3  850.19  4898.1  848.92  4989.5  849.02  4998.7  845.59
  5001.8  845.46  5002.1  844.96  5005.6  844.96  5005.8  845.46  5009.8  846.17
  5030.1  847.49  5080.9  848.55  5091.0  849.53  5101.2  851.63  5122.0  854.22
  5141.8  856.09  5162.1  856.60  5171.0  857.64  5176.0  857.59  5192.6  858.91
  5223.1  860.09  5230.0  860.94  5243.4  861.24  5273.9  864.46  5283.3  864.45
#Mann=3,-1,0
  4686.5    0.05       0  5001.8   0.033       0  5005.8    0.05       0
Bank Sta=5001.8,5005.8
Exp/Cntr=0.3,0.1

Type RM Length L Ch R = 1,7476,388,388,388
BEGIN DESCRIPTION:
Mapping XS 5b9b6bb2
END DESCRIPTION:
XS GIS Cut Line= 3
      2302136.23      7163919.37      2302049.18      7164251.79
      2302009.51      7164571.71
#Sta/Elev= 30
  4674.1  863.87  4716.1  860.99  4736.8  858.36  4757.1  857.22  4767.8  855.71
  4778.1  853.33  4788.5  853.52  4797.5  854.29  4843.1  851.97  4871.2  850.22
  4918.7  846.45  4943.5  845.50  4959.1  844.01  4974.5  844.14  4982.9  841.23
  4983.1  840.73  4986.6  840.73  4986.9  841.23  4994.4  841.68  4999.5  843.89
  5026.0  845.42  5036.1  844.91  5060.5  845.53  5076.4  846.68  5116.7  847.13
  5217.4  852.41  5222.4  851.79  5227.5  852.51  5257.8  853.93  5340.1  856.94
#Mann=3,-1,0
  4674.1    0.05       0  4982.9   0.033       0  4986.9    0.05       0
Bank Sta=4982.9,4986.9
Exp/Cntr=0.3,0.1

Type RM Length L Ch R = 1,7088,335,335,335
BEGIN DESCRIPTION:
MDE S 007 14.0
END DESCRIPTION:
XS GIS Cut Line= 3
      2302079.00      7163710.00      2301779.00      7164010.00
      2301579.01      7164309.99
#Sta/Elev= 30
  4576.0  874.81  4620.0  871.20  4689.1  863.57  4731.6  857.51  4759.8  852.45
  4769.0  851.77  4788.1  849.36  4816.4  847.29  4844.7  844.20  4887.1  842.77
  4915.4  842.79  4929.5  841.96  4943.7  842.42  4972.0  840.94  4986.1  839.05
  4994.7  838.71  4995.0  838.21  4998.5  838.21  4998.7  838.71  5003.3  838.71
  5007.8  839.79  5028.8  839.87  5036.3  840.96  5049.8  841.55  5115.9  840.62
  5150.6  842.83  5224.1  848.48  5260.2  850.56  5288.7  853.32  5360.8  858.12
#Mann=6,-1,0
  4576.0    0.12       0  4620.0    0.05       0  4769.0    0.12       0
  4994.7    0.07       0  4998.7    0.12       0  5150.6    0.05       0
Bank Sta=4994.7,4998.7
Exp/Cntr=0.3,0.1

Type RM Length L Ch R = 1,6753,378,378,378
BEGIN DESCRIPTION:
MDE S 007 13.0
END DESCRIPTION:
XS GIS Cut Line= 3
      2301878.97      7163510.03      2301579.00      7163810.00
      2301529.01      7163909.98
#Sta/Elev= 30
  4575.6  871.16  4579.1  871.16  4618.0  866.34  4674.5  858.39  4702.8  853.11
  4731.1  845.14  4759.4  841.11  4773.5  839.79  4830.1  835.91  4844.3  837.00
  4858.4  836.77  4886.7  837.46  4900.8  837.07  4915.0  837.18  4943.2  838.08
  4957.4  837.28  4966.7  837.46  4971.5  837.56  4996.3  834.54  5002.6  834.54
  5006.2  833.84  5006.5  833.34  5010.0  833.34  5010.2  833.84  5013.8  838.53
  5022.2  840.97  5030.6  841.12  5036.2  843.11  5097.6  846.86  5111.6  847.21
#Mann=4,-1,0
  4575.6    0.12       0  4966.7    0.05       0  5006.2   0.033       0
  5010.2    0.05       0
Bank Sta=5006.2,5010.2
Exp/Cntr=0.3,0.1

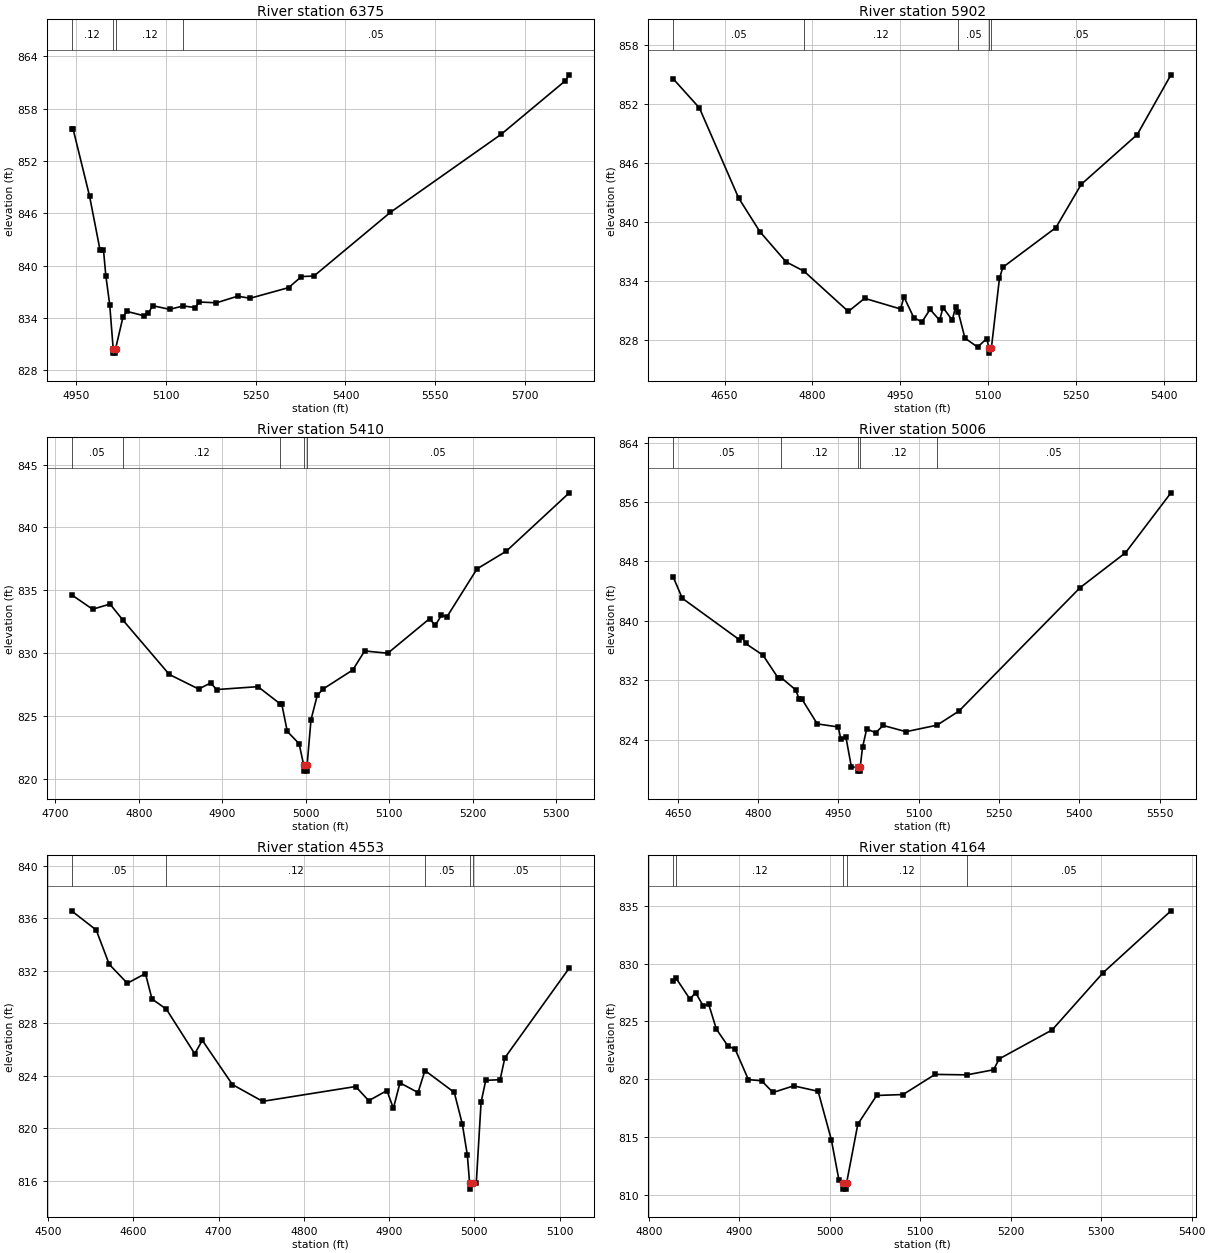
Type RM Length L Ch R = 1,6375,473,473,473
BEGIN DESCRIPTION:
MDE S 007 12.0
END DESCRIPTION:
XS GIS Cut Line= 3
      2301679.02      7163460.00      2301629.00      7163460.00
      2301129.03      7164059.96
#Sta/Elev= 30
  4942.7  855.69  4945.2  855.69  4972.7  847.99  4990.2  841.81  4996.0  841.81
  4999.9  838.86  5006.4  835.53  5012.2  830.47  5012.5  829.97  5016.0  829.97
  5016.2  830.47  5028.5  834.09  5035.0  834.76  5063.7  834.25  5070.8  834.52
  5078.0  835.41  5106.6  834.99  5129.1  835.38  5148.9  835.20  5156.1  835.83
  5184.7  835.74  5219.9  836.50  5240.7  836.26  5305.1  837.48  5326.6  838.75
  5347.4  838.81  5475.0  846.11  5659.8  855.05  5766.6  861.17  5773.7  861.88
#Mann=4,-1,0
  4942.7    0.12       0  5012.2    0.07       0  5016.2    0.12       0
  5129.1    0.05       0
Bank Sta=5012.2,5016.2
Exp/Cntr=0.3,0.1

Type RM Length L Ch R = 1,5902,492,492,492
BEGIN DESCRIPTION:
MDE S 007 11.0
END DESCRIPTION:
XS GIS Cut Line= 3
      2301628.98      7163060.01      2301229.00      7163260.00
      2300879.00      7163460.00
#Sta/Elev= 30
  4562.1  854.54  4606.8  851.58  4673.9  842.40  4710.2  838.98  4754.9  835.91
  4785.5  834.96  4861.2  830.86  4889.1  832.20  4950.6  831.11  4956.2  832.35
  4973.0  830.24  4986.9  829.79  5000.9  831.07  5017.2  829.97  5023.0  831.26
  5038.8  829.98  5044.6  831.35  5048.9  830.84  5060.4  828.15  5082.0  827.24
  5097.8  828.10  5101.5  827.12  5101.8  826.62  5105.6  827.12  5119.4  834.22
  5125.2  835.36  5215.9  839.40  5259.1  843.80  5354.8  848.87  5412.4  854.95
#Mann=5,-1,0
  4562.1    0.05       0  4785.5    0.12       0  5048.9    0.05       0
  5101.5    0.07       0  5105.6    0.05       0
Bank Sta=5101.5,5105.6
Exp/Cntr=0.3,0.1

Type RM Length L Ch R = 1,5410,404,404,404
BEGIN DESCRIPTION:
Mapping XS c4b76902
END DESCRIPTION:
XS GIS Cut Line= 2
      2301310.66      7162746.32      2300866.75      7163144.32
#Sta/Elev= 30
  4719.5  834.64  4744.7  833.49  4765.6  833.90  4780.7  832.65  4836.6  828.30
  4871.8  827.14  4886.0  827.62  4893.4  827.10  4942.8  827.33  4969.4  825.96
  4971.2  825.98  4977.9  823.77  4992.1  822.79  4997.5  821.11  4997.8  820.61
  5001.3  820.61  5001.7  821.11  5006.3  824.69  5013.8  826.63  5020.5  827.13
  5056.4  828.66  5070.6  830.17  5098.3  829.99  5148.4  832.74  5155.1  832.20
  5162.6  833.01  5169.3  832.90  5205.2  836.70  5240.3  838.11  5315.7  842.75
#Mann=5,-1,0
  4719.5    0.05       0  4780.7    0.12       0  4969.4    0.05       0
  4997.5   0.033       0  5001.7    0.05       0
Bank Sta=4997.5,5001.7
Exp/Cntr=0.3,0.1

Type RM Length L Ch R = 1,5006,453,453,453
BEGIN DESCRIPTION:
MDE S 007 9.0
END DESCRIPTION:
XS GIS Cut Line= 3
      2301378.98      7162460.00      2301029.00      7162560.00
      2300628.98      7162960.02
#Sta/Elev= 30
  4641.6  845.89  4658.5  843.04  4765.1  837.46  4770.3  837.81  4776.8  836.95
  4809.3  835.37  4837.9  832.27  4843.0  832.36  4870.4  830.70  4876.9  829.45
  4882.1  829.44  4910.7  826.12  4949.7  825.71  4954.9  824.02  4964.0  824.40
  4974.4  820.32  4986.6  820.26  4986.9  819.76  4990.5  819.76  4990.8  820.26
  4995.2  822.97  5003.0  825.44  5019.7  824.93  5033.9  825.91  5076.3  825.07
  5134.4  825.95  5175.3  827.85  5401.6  844.47  5486.4  849.17  5571.3  857.24
#Mann=5,-1,0
  4641.6    0.05       0  4843.0    0.12       0  4986.6    0.07       0
  4990.8    0.12       0  5134.4    0.05       0
Bank Sta=4986.6,4990.8
Exp/Cntr=0.3,0.1

Type RM Length L Ch R = 1,4553,389,389,389
BEGIN DESCRIPTION:
MDE S 007 8.0
END DESCRIPTION:
XS GIS Cut Line= 3
      2301228.97      7162110.02      2300829.00      7162360.00
      2300728.97      7162410.01
#Sta/Elev= 30
  4527.7  836.58  4556.6  835.12  4571.9  832.50  4593.1  831.06  4614.3  831.80
  4622.0  829.86  4638.8  829.09  4672.1  825.69  4681.0  826.71  4716.3  823.34
  4751.7  822.06  4860.8  823.19  4876.1  822.11  4897.4  822.88  4905.0  821.53
  4912.7  823.47  4933.9  822.73  4942.0  824.41  4976.4  822.74  4985.8  820.33
  4991.7  817.97  4994.3  815.87  4994.6  815.37  4998.5  815.87  5002.2  815.87
  5007.8  821.99  5013.3  823.66  5030.1  823.71  5035.7  825.38  5111.2  832.22
#Mann=5,-1,0
  4527.7    0.05       0  4638.8    0.12       0  4942.0    0.05       0
  4994.3   0.033       0  4998.5    0.05       0
Bank Sta=4994.3,4998.5
Exp/Cntr=0.3,0.1

Type RM Length L Ch R = 1,4164,536,536,536
BEGIN DESCRIPTION:
Mapping XS 5dc65d1a
END DESCRIPTION:
XS GIS Cut Line= 2
      2301017.48      7161922.99      2300576.15      7162251.71
#Sta/Elev= 30
  4826.8  828.53  4830.1  828.72  4845.3  826.93  4851.5  827.50  4859.9  826.35
  4866.1  826.47  4874.5  824.34  4887.3  822.88  4895.3  822.60  4909.9  819.98
  4924.5  819.88  4937.1  818.87  4960.0  819.44  4987.0  818.97  5001.6  814.79
  5010.0  811.32  5014.1  811.02  5014.4  810.52  5018.0  810.52  5018.4  811.02
  5030.9  816.13  5051.7  818.61  5080.9  818.69  5116.3  820.43  5151.5  820.39
  5181.0  820.83  5187.2  821.77  5245.7  824.27  5301.9  829.20  5377.1  834.56
#Mann=5,-1,0
  4826.8    0.05       0  4830.1    0.12       0  5014.1    0.07       0
  5018.4    0.12       0  5151.5    0.05       0
Bank Sta=5014.1,5018.4
Exp/Cntr=0.3,0.1

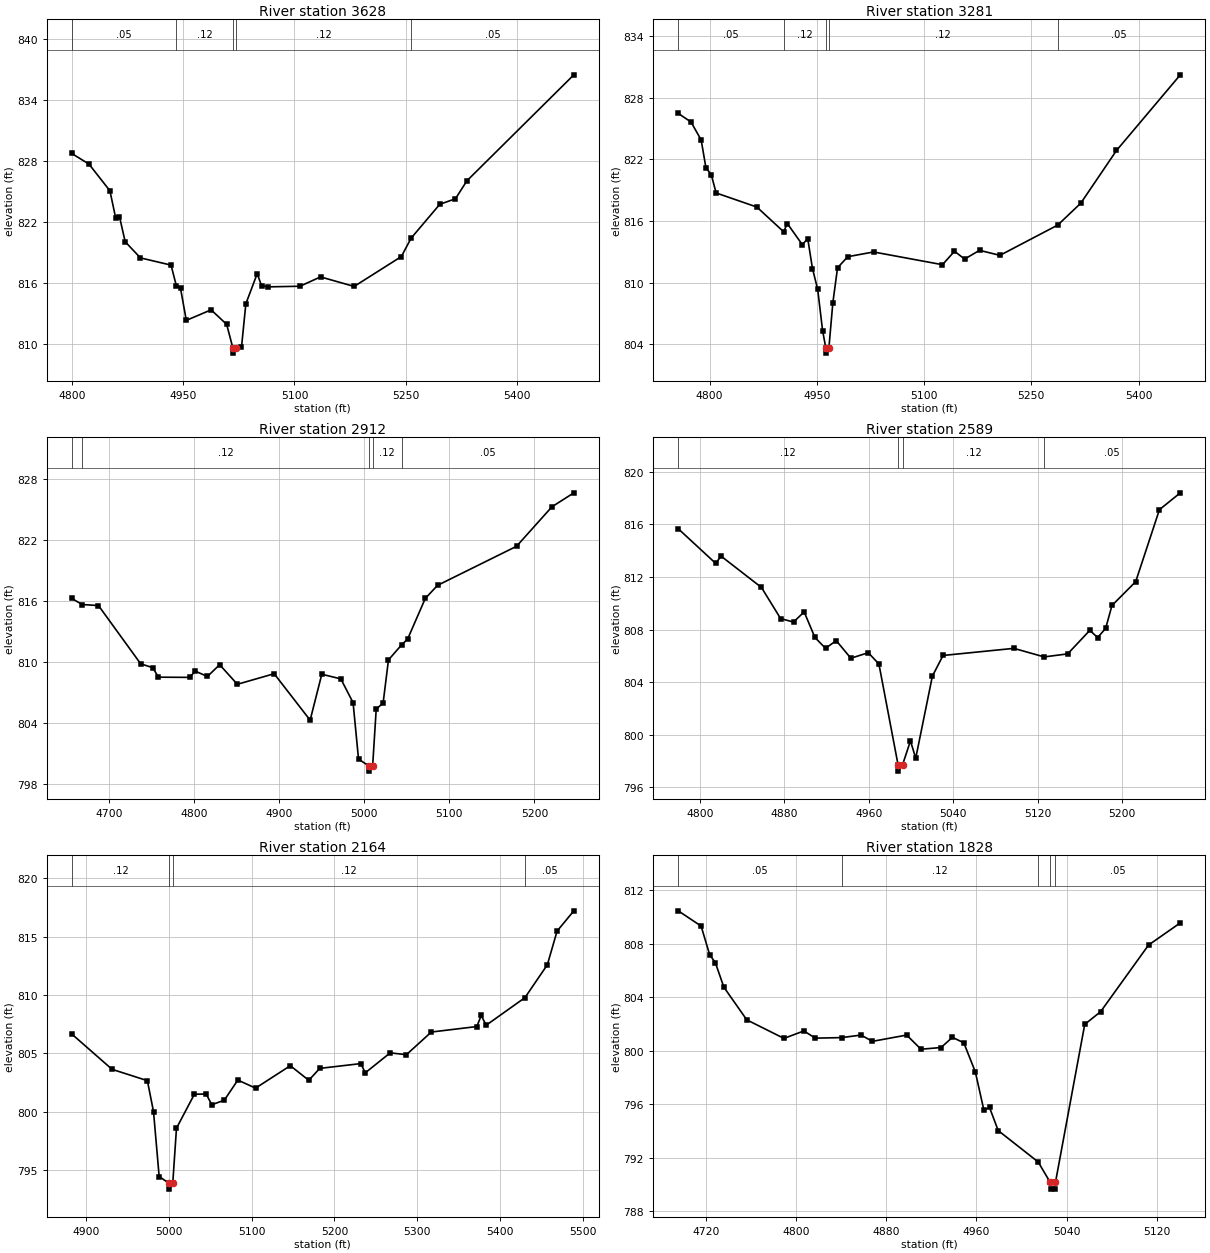
Type RM Length L Ch R = 1,3628,347,347,347
BEGIN DESCRIPTION:
MDE S 007 6.0
END DESCRIPTION:
XS GIS Cut Line= 3
      2300978.96      7161610.01      2300779.00      7161660.00
      2300379.01      7161909.99
#Sta/Elev= 30
  4799.4  828.78  4822.6  827.74  4850.9  825.11  4858.6  822.46  4863.8  822.57
  4871.5  820.10  4892.1  818.51  4933.4  817.80  4940.5  815.79  4946.2  815.53
  4954.0  812.36  4987.5  813.40  5008.5  811.97  5016.9  809.64  5017.3  809.14
  5021.2  809.64  5028.5  809.70  5034.4  813.99  5049.7  816.95  5055.6  815.78
  5064.5  815.66  5107.5  815.72  5135.2  816.64  5180.6  815.70  5244.3  818.64
  5257.6  820.46  5296.2  823.78  5317.4  824.33  5332.8  826.09  5477.2  836.52
#Mann=5,-1,0
  4799.4    0.05       0  4940.5    0.12       0  5016.9    0.07       0
  5021.2    0.12       0  5257.6    0.05       0
Bank Sta=5016.9,5021.2
Exp/Cntr=0.3,0.1

Type RM Length L Ch R = 1,3281,369,369,369
BEGIN DESCRIPTION:
Mapping XS 8d8cd35a
END DESCRIPTION:
XS GIS Cut Line= 3
      2300866.86      7161202.83      2300624.09      7161481.67
      2300374.69      7161702.00
#Sta/Elev= 30
  4756.0  826.46  4773.9  825.62  4788.1  823.87  4794.7  821.19  4802.3  820.48
  4809.0  818.72  4866.0  817.35  4903.4  814.95  4908.7  815.74  4929.6  813.69
  4937.2  814.28  4943.8  811.37  4951.1  809.35  4958.0  805.32  4962.5  803.64
  4962.9  803.14  4966.8  803.64  4972.3  808.02  4978.9  811.44  4993.2  812.52
  5029.3  812.98  5125.7  811.74  5142.5  813.05  5156.7  812.29  5177.6  813.14
  5206.1  812.65  5287.1  815.60  5319.3  817.73  5369.2  822.85  5458.5  830.21
#Mann=5,-1,0
  4756.0    0.05       0  4903.4    0.12       0  4962.5    0.07       0
  4966.8    0.12       0  5287.1    0.05       0
Bank Sta=4962.5,4966.8
Exp/Cntr=0.3,0.1

Type RM Length L Ch R = 1,2912,323,323,323
BEGIN DESCRIPTION:
Mapping XS d8360166
END DESCRIPTION:
XS GIS Cut Line= 2
      2300623.91      7160970.89      2300255.69      7161432.39
#Sta/Elev= 30
  4655.9  816.27  4668.2  815.67  4687.3  815.57  4736.9  809.83  4751.3  809.44
  4757.7  808.51  4794.6  808.49  4801.0  809.11  4815.4  808.58  4829.8  809.74
  4850.6  807.81  4893.9  808.85  4936.2  804.27  4949.9  808.80  4972.3  808.34
  4986.7  806.00  4993.1  800.44  5005.4  799.75  5005.7  799.25  5009.7  799.75
  5013.9  805.37  5022.0  805.95  5028.3  810.21  5043.8  811.70  5050.8  812.26
  5071.6  816.27  5086.0  817.56  5178.9  821.41  5220.5  825.30  5246.3  826.68
#Mann=5,-1,0
  4655.9    0.05       0  4668.2    0.12       0  5005.4    0.07       0
  5009.7    0.12       0  5043.8    0.05       0
Bank Sta=5005.4,5009.7
Exp/Cntr=0.3,0.1

Type RM Length L Ch R = 1,2589,425,425,425
BEGIN DESCRIPTION:
Mapping XS 10bb7a1e
END DESCRIPTION:
XS GIS Cut Line= 3
      2300596.87      7160948.94      2300296.52      7160997.78
      2300153.92      7161093.60
#Sta/Elev= 30
  4779.3  815.66  4814.8  813.03  4819.9  813.58  4858.2  811.20  4876.4  808.83
  4888.6  808.57  4898.7  809.34  4908.9  807.40  4919.0  806.57  4929.1  807.16
  4943.0  805.82  4959.5  806.24  4969.6  805.38  4987.7  797.74  4988.1  797.24
  4992.1  797.74  4999.5  799.54  5004.5  798.22  5020.3  804.46  5030.4  806.03
  5097.6  806.57  5126.3  805.92  5148.6  806.15  5169.6  807.94  5177.0  807.39
  5184.6  808.09  5190.6  809.83  5213.1  811.64  5235.6  817.11  5255.4  818.39
#Mann=4,-1,0
  4779.3    0.12       0  4987.7    0.07       0  4992.1    0.12       0
  5126.3    0.05       0
Bank Sta=4987.7,4992.1
Exp/Cntr=0.3,0.1

Type RM Length L Ch R = 1,2164,336,336,336
BEGIN DESCRIPTION:
Mapping XS cd9fefed
END DESCRIPTION:
XS GIS Cut Line= 3
      2300404.96      7160527.07      2300287.34      7160655.70
      2300134.14      7161058.87
#Sta/Elev= 30
  4883.2  806.66  4931.8  803.64  4974.4  802.67  4981.8  800.02  4988.6  794.47
  5000.5  793.89  5001.0  793.39  5005.0  793.89  5009.5  798.60  5031.1  801.51
  5045.3  801.53  5052.1  800.61  5067.2  801.00  5083.5  802.72  5104.9  802.03
  5146.8  803.95  5169.1  802.70  5182.3  803.72  5231.9  804.13  5237.2  803.34
  5267.3  805.05  5286.8  804.89  5316.9  806.83  5371.8  807.30  5377.1  808.25
  5383.0  807.41  5429.8  809.77  5456.8  812.58  5468.6  815.47  5488.8  817.20
#Mann=4,-1,0
  4883.2    0.12       0  5000.5    0.07       0  5005.0    0.12       0
  5429.8    0.05       0
Bank Sta=5000.5,5005
Exp/Cntr=0.3,0.1

Type RM Length L Ch R = 1,1828,201,201,201
BEGIN DESCRIPTION:
MDE S 007 3.0
END DESCRIPTION:
XS GIS Cut Line= 3
      2300378.99      7160410.00      2300079.00      7160460.00
      2299979.03      7160559.97
#Sta/Elev= 30
  4695.4  810.46  4715.7  809.32  4723.3  807.17  4728.3  806.59  4735.9  804.75
  4756.2  802.31  4789.2  800.92  4806.9  801.48  4817.0  800.94  4840.4  800.98
  4857.6  801.17  4867.7  800.70  4898.1  801.17  4910.8  800.11  4928.6  800.24
  4938.7  801.00  4948.8  800.59  4959.0  798.42  4966.6  795.56  4971.6  795.76
  4979.3  794.03  5014.8  791.68  5025.5  790.15  5026.0  789.65  5029.6  789.65
  5030.1  790.15  5056.1  801.97  5070.2  802.92  5112.7  807.90  5140.9  809.56
#Mann=5,-1,0
  4695.4    0.05       0  4840.4    0.12       0  5014.8    0.05       0
  5025.5    0.07       0  5030.1    0.05       0
Bank Sta=5025.5,5030.1
Exp/Cntr=0.3,0.1

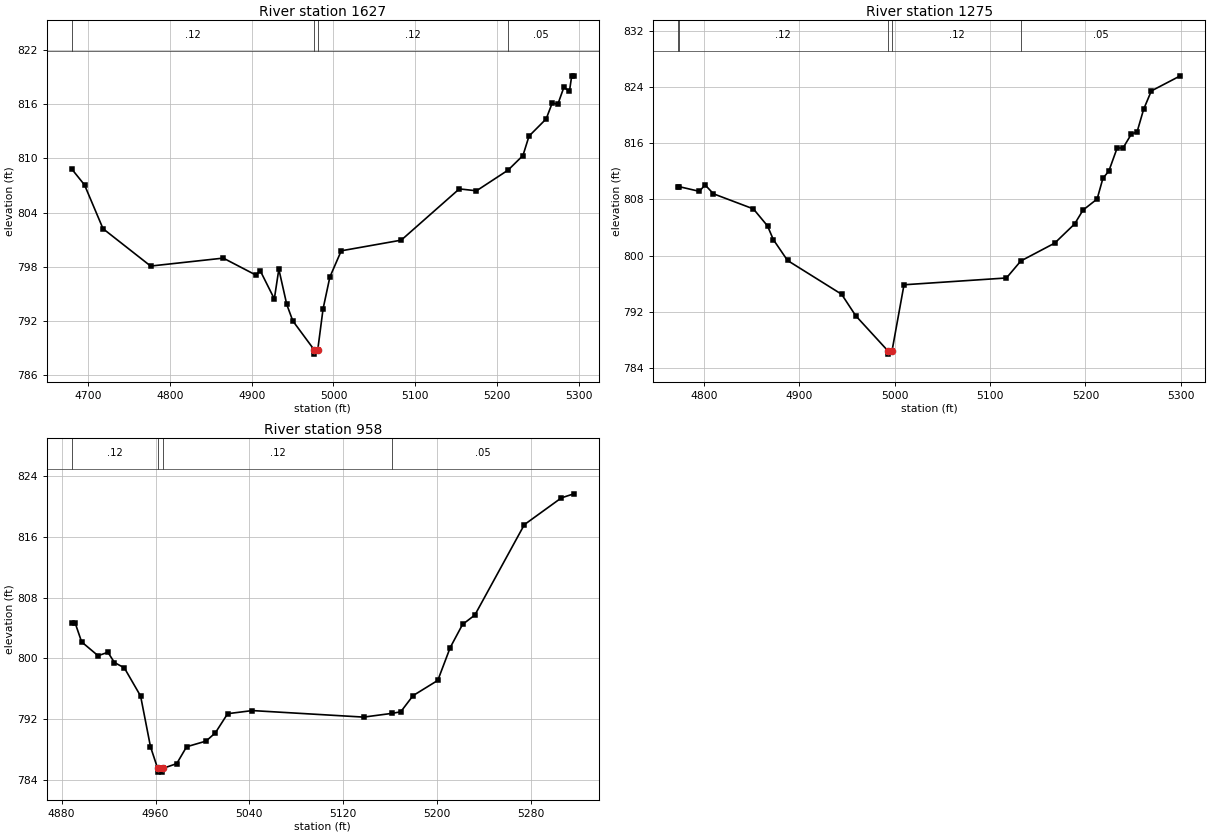
Type RM Length L Ch R = 1,1627,352,352,352
BEGIN DESCRIPTION:
Mapping XS cc07faf9
END DESCRIPTION:
XS GIS Cut Line= 3
      2300275.93      7160177.24      2299936.20      7160340.39
      2299760.10      7160498.74
#Sta/Elev= 30
  4680.1  808.82  4695.7  807.06  4718.3  802.21  4776.5  798.07  4865.3  798.95
  4905.0  797.08  4910.6  797.53  4927.7  794.43  4933.2  797.72  4942.9  793.81
  4950.3  791.99  4976.2  788.81  4976.7  788.31  4980.8  788.81  4987.3  793.34
  4995.6  796.86  5009.5  799.76  5082.8  800.94  5153.8  806.62  5174.8  806.41
  5213.4  808.70  5231.6  810.32  5239.0  812.47  5260.0  814.38  5267.4  816.15
  5274.2  815.99  5281.7  817.90  5288.4  817.42  5291.2  819.15  5293.8  819.15
#Mann=4,-1,0
  4680.1    0.12       0  4976.2    0.07       0  4980.8    0.12       0
  5213.4    0.05       0
Bank Sta=4976.2,4980.8
Exp/Cntr=0.3,0.1

Type RM Length L Ch R = 1,1275,317,317,317
BEGIN DESCRIPTION:
Mapping XS 363681d7
END DESCRIPTION:
XS GIS Cut Line= 2
      2300069.45      7159930.54      2299637.41      7160231.28
#Sta/Elev= 30
  4773.1  809.82  4773.6  809.82  4795.2  809.14  4801.3  810.05  4810.0  808.79
  4851.9  806.64  4866.7  804.22  4872.8  802.27  4887.7  799.30  4944.4  794.49
  4959.2  791.43  4992.7  786.47  4993.2  785.97  4997.3  786.47  5009.8  795.84
  5117.2  796.81  5132.3  799.23  5167.8  801.77  5188.7  804.50  5197.5  806.47
  5212.3  808.05  5218.4  811.02  5224.5  812.00  5233.3  815.32  5239.4  815.30
  5248.1  817.27  5254.2  817.61  5261.0  820.80  5269.1  823.43  5299.5  825.58
#Mann=5,-1,0
  4773.1    0.05       0  4773.6    0.12       0  4992.7    0.07       0
  4997.3    0.12       0  5132.3    0.05       0
Bank Sta=4992.7,4997.3
Exp/Cntr=0.3,0.1

Type RM Length L Ch R = 1,958,0,0,0
BEGIN DESCRIPTION:
MDE S 007 1.0
END DESCRIPTION:
XS GIS Cut Line= 3
      2299929.04      7159709.98      2299829.00      7159760.00
      2299528.97      7159860.01
#Sta/Elev= 30
  4888.6  804.71  4891.4  804.71  4897.0  802.18  4911.0  800.36  4919.4  800.81
  4925.0  799.46  4933.4  798.76  4947.3  795.04  4955.7  788.38  4961.8  785.52
  4962.3  785.02  4965.9  785.02  4966.4  785.52  4978.1  786.14  4986.5  788.36
  5003.1  789.11  5011.0  790.19  5021.5  792.72  5042.6  793.13  5137.5  792.27
  5162.0  792.77  5169.1  792.97  5179.6  795.10  5200.7  797.11  5211.3  801.44
  5221.8  804.48  5232.3  805.72  5274.5  817.63  5306.1  821.16  5316.7  821.69
#Mann=4,-1,0
  4888.6    0.12       0  4961.8    0.07       0  4966.4    0.12       0
  5162.0    0.05       0
Bank Sta=4961.8,4966.4
Exp/Cntr=0.3,0.1

Chan Stop Cuts=-1