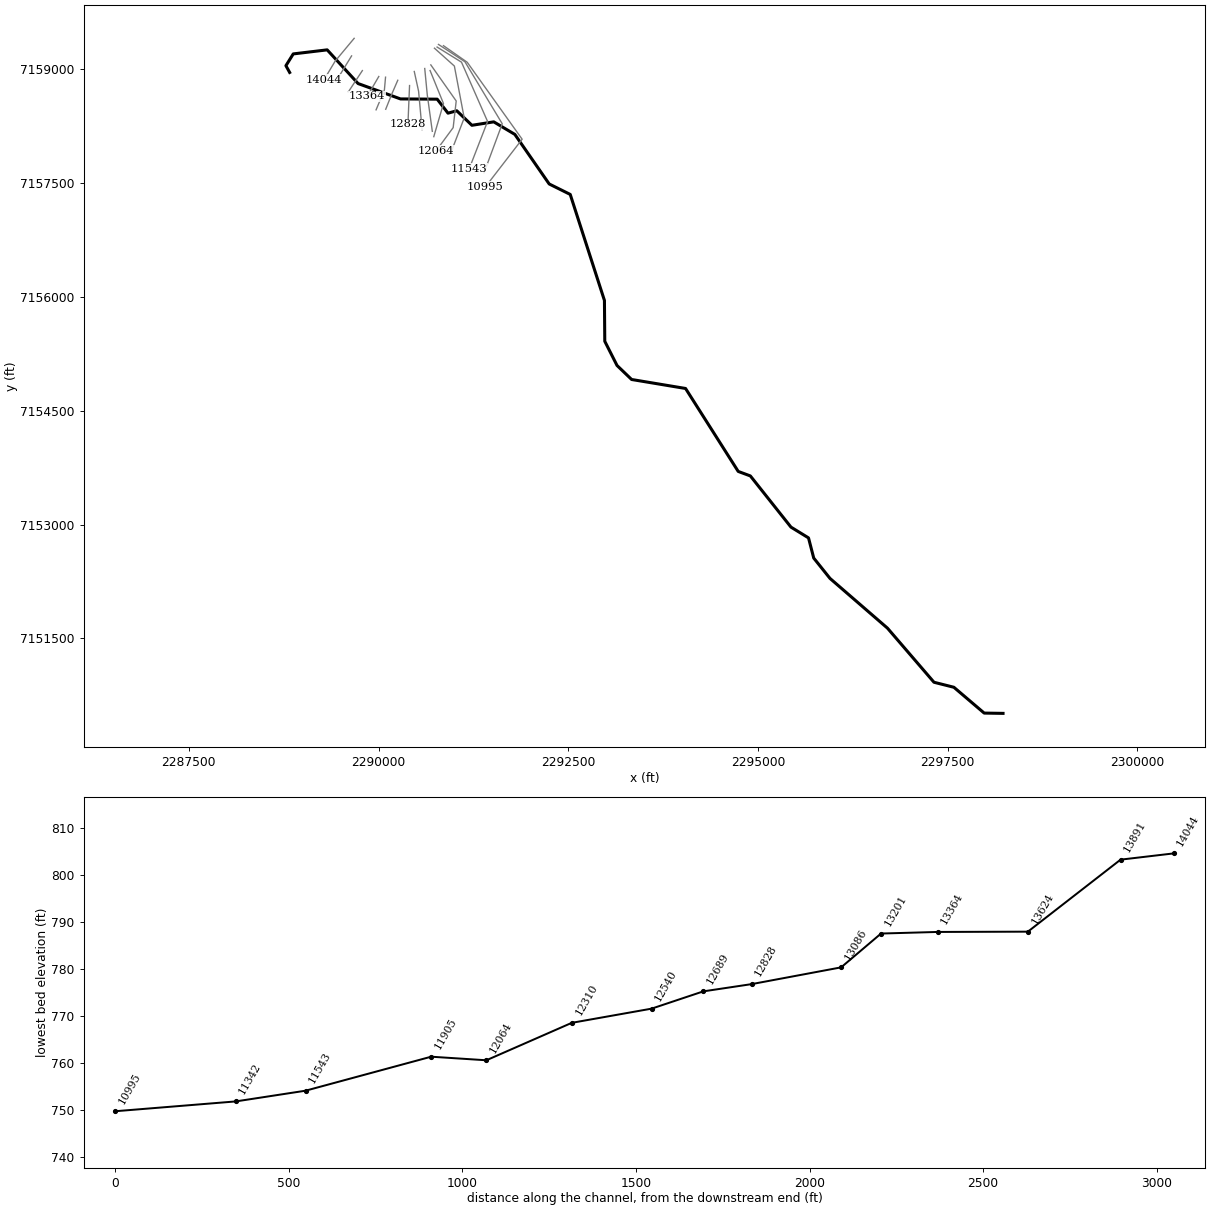
--- MDE S 008.prj (project) ---

Proj Title=MDE S 008 Base Level Engineering
Current Plan=p01
Default Exp/Contr=0.3,0.1
English Units
Geom File=g01
Flow File=f01
Plan File=p01
BEGIN DESCRIPTION:
MDE S 008
END DESCRIPTION:

--- MDE S 008.p01 (plan) ---

Plan Title=Multiple Run
Short Identifier=Multiple
Geom File=g01
Flow File=f01
Subcritical Flow
K Sum by GR= 0
Std Step Tol= 0.01
Critical Tol= 0.01
Num of Std Step Trials= 20
Max Error Tol= 0.3
Flow Tol Ratio= 0.001
Split Flow NTrial= 30
Split Flow Tol= 0.02
Split Flow Ratio= 0.02
Log Output Level= 0
Friction Slope Method= 1
Unsteady Friction Slope Method= 2
Unsteady Bridges Friction Slope Method= 1
Parabolic Critical Depth
Global Vel Dist=  1 , 1 , 1
Global Log Level= 0
CheckData=True
Encroach Param= -1, 0, 0, 0
BEGIN DESCRIPTION:
Multiple Run
END DESCRIPTION:

--- MDE S 008.f01 (steady flow) ---

Flow Title=Multiple
Number of Profiles=7
Profile Names=10-year,25-year,50-year,1pct_min,100-year,1pct_plu,500-year
River Rch & RM= MDE S 008,Reach-1,14044
     396     534     646     390     779    1554    1130
Boundary for River Rch & Prof#=MDE S 008,Reach-1,1
Up Type=0
Dn Type=3
Dn Slope=0.005
Boundary for River Rch & Prof#=MDE S 008,Reach-1,2
Up Type=0
Dn Type=3
Dn Slope=0.005
Boundary for River Rch & Prof#=MDE S 008,Reach-1,3
Up Type=0
Dn Type=3
Dn Slope=0.005
Boundary for River Rch & Prof#=MDE S 008,Reach-1,4
Up Type=0
Dn Type=3
Dn Slope=0.005
Boundary for River Rch & Prof#=MDE S 008,Reach-1,5
Up Type=0
Dn Type=3
Dn Slope=0.005
Boundary for River Rch & Prof#=MDE S 008,Reach-1,6
Up Type=0
Dn Type=3
Dn Slope=0.005
Boundary for River Rch & Prof#=MDE S 008,Reach-1,7
Up Type=0
Dn Type=3
Dn Slope=0.005

--- MDE S 008.g01 (geometry) ---

Geom Title=Existing Conditions

River Reach=MDE S 008,Reach-1
Reach XY= 30
      2288829.00      7158960.00      2288779.66      7159049.38
      2288876.32      7159204.58      2289323.33      7159258.02
      2289730.55      7158813.75      2290289.55      7158611.10
      2290773.14      7158607.93      2290915.27      7158423.40
      2291031.29      7158454.88      2291230.50      7158263.46
      2291518.50      7158308.81      2291796.05      7158143.50
      2292248.77      7157489.87      2292525.97      7157351.99
      2292976.74      7155954.06      2292981.24      7155415.93
      2293142.62      7155096.79      2293334.85      7154912.06
      2294045.76      7154793.57      2294739.54      7153699.89
      2294899.54      7153640.53      2295434.62      7152965.62
      2295665.74      7152823.65      2295734.52      7152557.57
      2295948.63      7152289.53      2296706.08      7151633.70
      2297318.88      7150920.35      2297581.29      7150854.16
      2297980.58      7150513.82      2298229.00      7150510.00

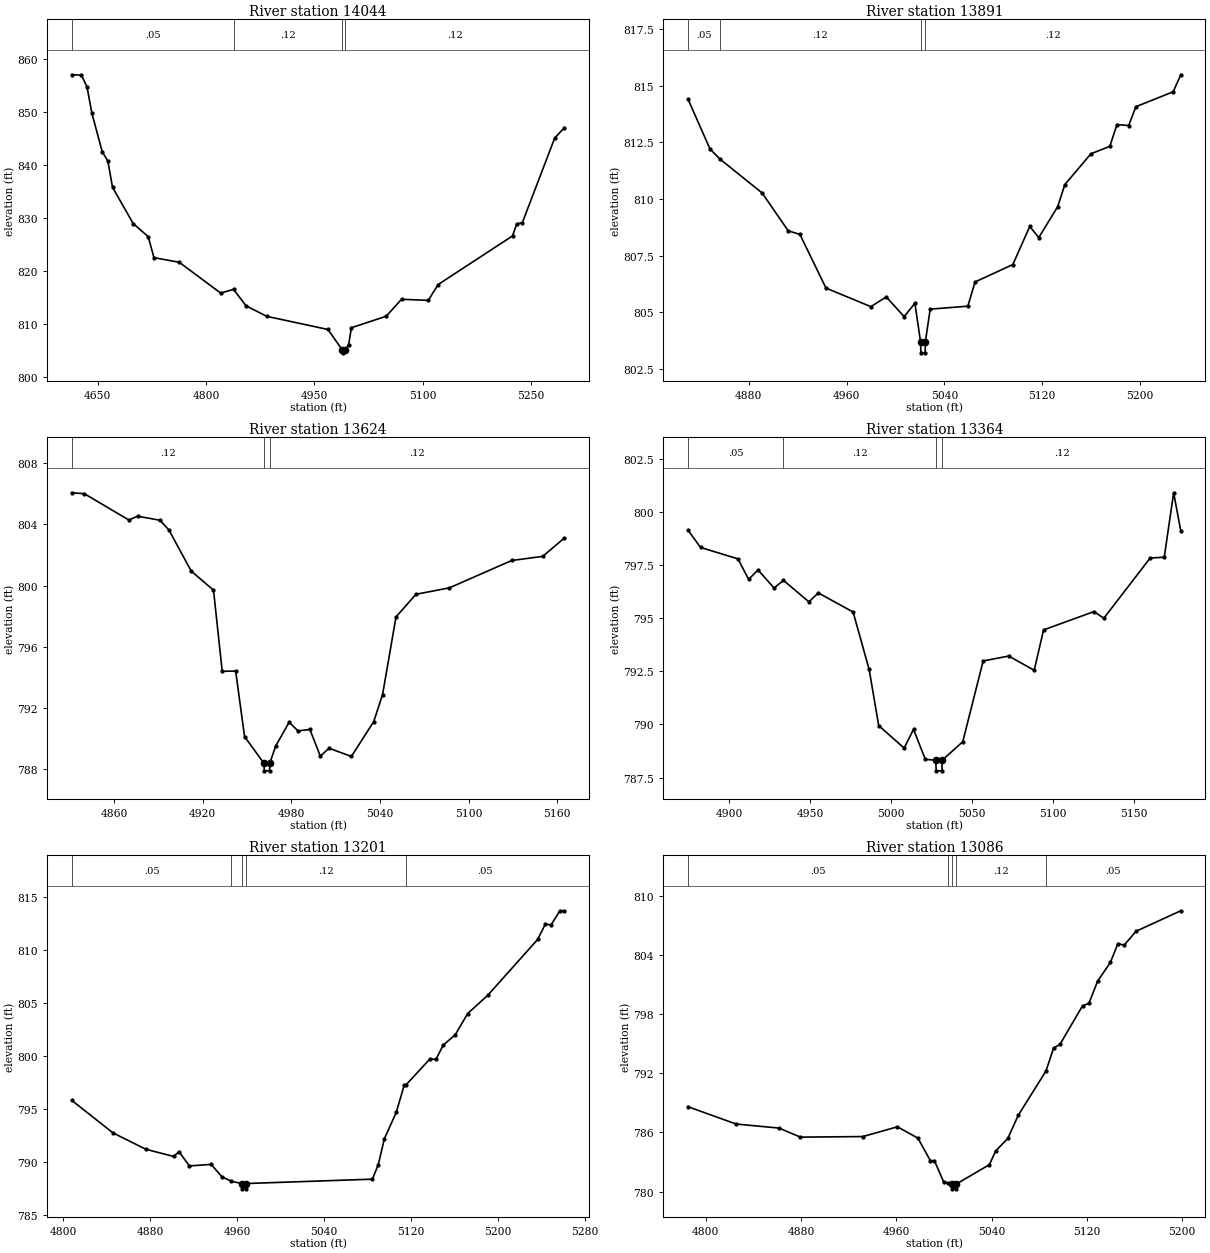
Type RM Length L Ch R = 1,14044,153,153,153
BEGIN DESCRIPTION:
MDE S 008 18.0
END DESCRIPTION:
XS GIS Cut Line= 3
      2289678.97      7159409.96      2289429.00      7159110.00
      2289279.01      7158860.01
#Sta/Elev= 30
  4614.0  856.96  4627.6  856.91  4635.4  854.61  4641.9  849.79  4656.3  842.47
  4664.1  840.70  4670.6  835.75  4699.2  828.91  4720.0  826.44  4727.9  822.49
  4763.0  821.61  4820.3  815.80  4838.0  816.51  4855.4  813.40  4884.1  811.42
  4968.7  808.94  4988.8  805.04  4989.0  804.54  4992.8  805.04  4997.3  806.11
  5001.2  809.28  5049.2  811.43  5070.5  814.64  5107.5  814.43  5121.1  817.41
  5224.1  826.58  5229.9  828.84  5237.7  829.09  5282.4  845.02  5296.0  847.01
#Mann=4,-1,0
  4614.0    0.05       0  4838.0    0.12       0  4988.8    0.07       0
  4992.8    0.12       0
Bank Sta=4988.8,4992.8
Exp/Cntr=0.3,0.1

Type RM Length L Ch R = 1,13891,267,267,267
BEGIN DESCRIPTION:
Mapping XS 2efc815c
END DESCRIPTION:
XS GIS Cut Line= 2
      2289644.83      7159178.26      2289434.17      7158834.71
#Sta/Elev= 30
  4830.3  814.42  4848.4  812.21  4856.7  811.76  4891.0  810.27  4912.3  808.60
  4921.9  808.44  4943.2  806.07  4979.9  805.25  4992.5  805.68  5007.1  804.81
  5015.9  805.40  5020.5  803.71  5020.8  803.21  5024.3  803.21  5024.5  803.71
  5028.4  805.14  5059.2  805.27  5065.1  806.34  5096.0  807.11  5109.8  808.79
  5117.2  808.30  5132.7  809.67  5138.5  810.64  5159.8  812.00  5175.3  812.33
  5181.1  813.29  5190.7  813.25  5196.6  814.08  5227.1  814.74  5233.3  815.49
#Mann=4,-1,0
  4830.3    0.05       0  4856.7    0.12       0  5020.5    0.07       0
  5024.5    0.12       0
Bank Sta=5020.5,5024.5
Exp/Cntr=0.3,0.1

Type RM Length L Ch R = 1,13624,260,260,260
BEGIN DESCRIPTION:
Mapping XS 4adf0e30
END DESCRIPTION:
XS GIS Cut Line= 2
      2289787.07      7158984.68      2289603.75      7158706.08
#Sta/Elev= 30
  4831.4  806.07  4840.0  806.01  4870.1  804.29  4876.1  804.54  4891.2  804.27
  4897.2  803.64  4912.3  800.95  4927.4  799.70  4933.3  794.39  4942.4  794.41
  4948.4  790.12  4961.5  788.38  4961.8  787.88  4965.3  787.88  4965.5  788.38
  4969.5  789.51  4978.6  791.06  4984.6  790.49  4992.6  790.59  4999.7  788.84
  5005.6  789.36  5020.7  788.82  5035.8  791.10  5041.8  792.87  5050.9  797.95
  5064.4  799.43  5087.0  799.85  5129.2  801.64  5150.2  801.91  5164.9  803.12
#Mann=3,-1,0
  4831.4    0.12       0  4961.5    0.07       0  4965.5    0.12       0
Bank Sta=4961.5,4965.5
Exp/Cntr=0.3,0.1

Type RM Length L Ch R = 1,13364,163,163,163
BEGIN DESCRIPTION:
Mapping XS a89276f9
END DESCRIPTION:
XS GIS Cut Line= 2
      2290003.21      7158906.76      2289850.36      7158643.63
#Sta/Elev= 30
  4874.6  799.15  4882.4  798.33  4905.5  797.79  4912.1  796.83  4917.9  797.27
  4927.8  796.42  4933.6  796.78  4949.3  795.77  4955.1  796.19  4976.6  795.29
  4986.5  792.59  4992.4  789.95  5008.1  788.89  5013.9  789.77  5021.2  788.36
  5027.6  788.32  5027.9  787.82  5031.4  787.82  5031.6  788.32  5044.3  789.19
  5056.9  792.99  5072.7  793.22  5088.4  792.55  5094.2  794.45  5125.3  795.31
  5131.4  795.00  5160.0  797.83  5168.7  797.87  5174.5  800.90  5178.9  799.11
#Mann=4,-1,0
  4874.6    0.05       0  4933.6    0.12       0  5027.6    0.07       0
  5031.6    0.12       0
Bank Sta=5027.6,5031.6
Exp/Cntr=0.3,0.1

Type RM Length L Ch R = 1,13201,115,115,115
BEGIN DESCRIPTION:
Mapping XS 1e675356
END DESCRIPTION:
XS GIS Cut Line= 3
      2290092.39      7158897.90      2290077.26      7158728.61
      2289967.77      7158467.17
#Sta/Elev= 30
  4807.9  795.82  4845.9  792.75  4876.1  791.21  4901.7  790.53  4906.7  790.98
  4916.2  789.64  4936.3  789.78  4946.3  788.60  4954.8  788.20  4964.4  787.98
  4964.7  787.48  4968.2  787.48  4968.4  787.98  5084.6  788.39  5090.0  789.76
  5095.6  792.20  5106.5  794.67  5113.8  797.22  5115.7  797.29  5137.6  799.72
  5143.0  799.66  5149.8  801.02  5160.7  801.97  5172.2  803.98  5190.6  805.69
  5236.6  810.96  5243.6  812.39  5249.0  812.34  5257.1  813.66  5261.3  813.66
#Mann=5,-1,0
  4807.9    0.05       0  4954.8    0.12       0  4964.4    0.07       0
  4968.4    0.12       0  5115.7    0.05       0
Bank Sta=4964.4,4968.4
Exp/Cntr=0.3,0.1

Type RM Length L Ch R = 1,13086,258,258,258
BEGIN DESCRIPTION:
Mapping XS 35e14a2a
END DESCRIPTION:
XS GIS Cut Line= 3
      2290253.49      7158857.21      2290171.31      7158667.24
      2290094.76      7158475.12
#Sta/Elev= 30
  4785.1  788.61  4825.6  786.85  4861.6  786.44  4879.6  785.52  4932.0  785.58
  4961.0  786.57  4978.2  785.42  4988.7  783.13  4992.1  783.13  4999.9  780.96
  5003.8  780.86  5006.6  780.78  5006.8  780.28  5010.3  780.28  5010.6  780.78
  5038.2  782.73  5043.6  784.14  5053.7  785.39  5062.5  787.75  5085.7  792.22
  5092.1  794.54  5097.5  794.93  5116.4  798.83  5121.8  799.09  5129.1  801.34
  5139.8  803.23  5146.1  805.14  5151.4  804.99  5161.3  806.39  5198.9  808.47
#Mann=5,-1,0
  4785.1    0.05       0  5003.8    0.12       0  5006.6   0.033       0
  5010.6    0.12       0  5085.7    0.05       0
Bank Sta=5006.6,5010.6
Exp/Cntr=0.3,0.1

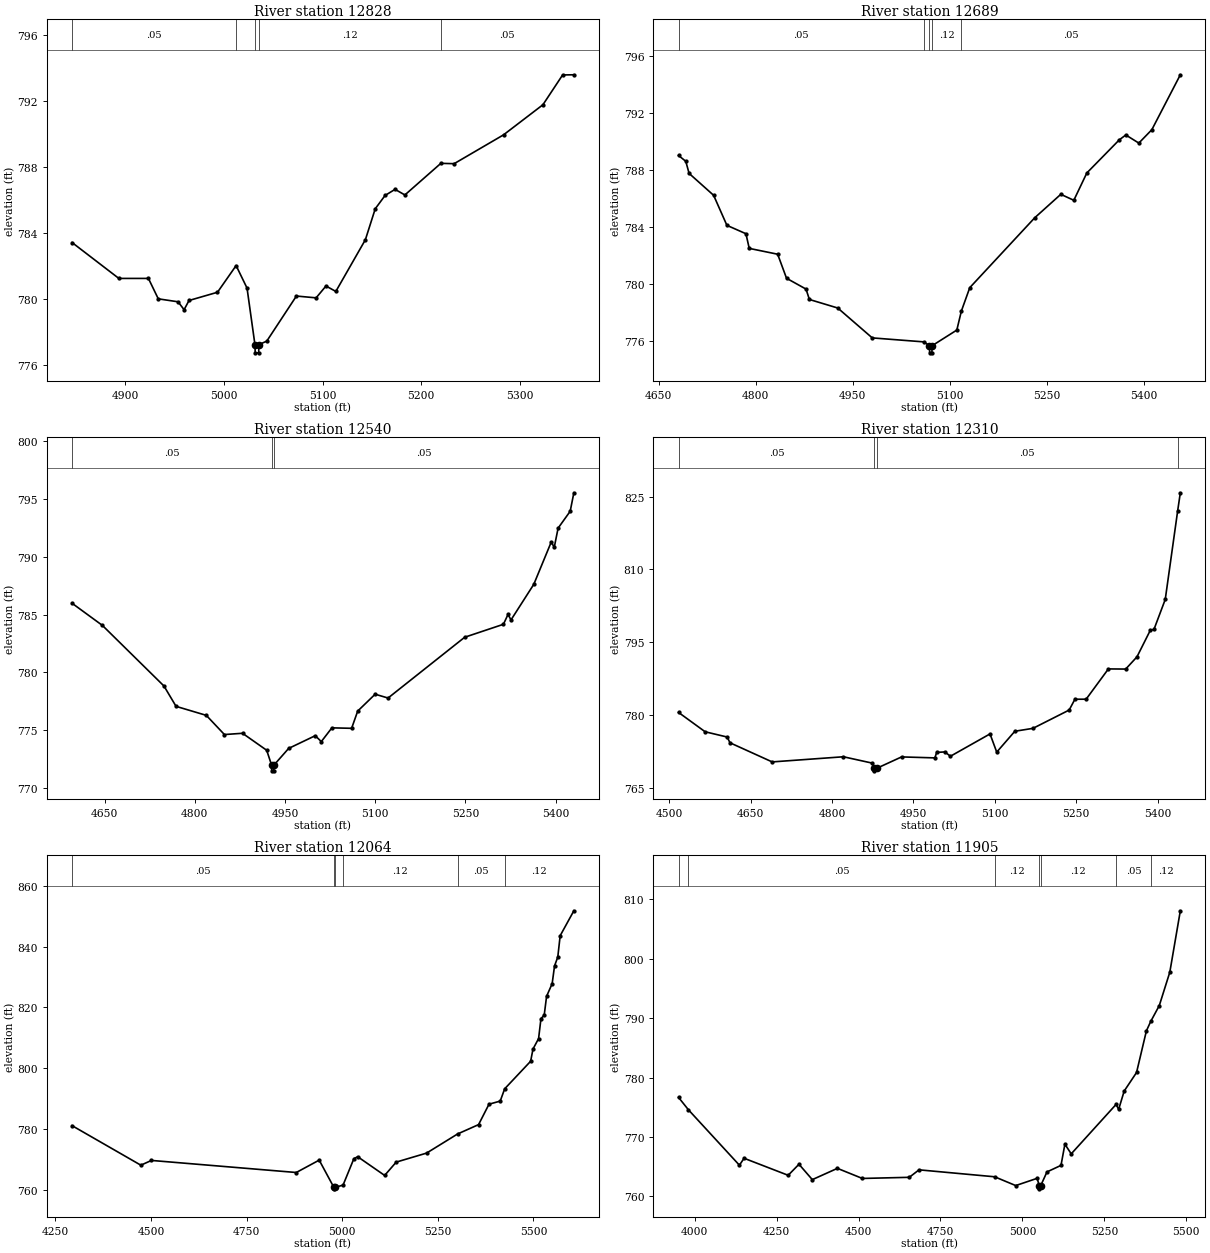
Type RM Length L Ch R = 1,12828,139,139,139
BEGIN DESCRIPTION:
Mapping XS c204e918
END DESCRIPTION:
XS GIS Cut Line= 2
      2290408.79      7158787.47      2290387.54      7158278.62
#Sta/Elev= 30
  4845.8  783.41  4893.3  781.23  4923.3  781.23  4933.3  779.99  4953.4  779.81
  4959.5  779.33  4964.5  779.89  4993.4  780.39  5012.3  782.01  5023.4  780.64
  5031.4  777.21  5031.7  776.71  5035.2  776.71  5035.4  777.21  5043.4  777.42
  5073.5  780.16  5093.5  780.05  5103.5  780.77  5113.5  780.44  5143.5  783.58
  5153.5  785.46  5163.5  786.27  5173.6  786.64  5183.6  786.30  5220.1  788.22
  5233.6  788.20  5283.7  789.95  5323.7  791.78  5343.7  793.59  5355.1  793.60
#Mann=5,-1,0
  4845.8    0.05       0  5012.3    0.12       0  5031.4   0.033       0
  5035.4    0.12       0  5220.1    0.05       0
Bank Sta=5031.4,5035.4
Exp/Cntr=0.3,0.1

Type RM Length L Ch R = 1,12689,149,149,149
BEGIN DESCRIPTION:
Mapping XS 7c2cd8b6
END DESCRIPTION:
XS GIS Cut Line= 3
      2290470.97      7158972.94      2290527.77      7158713.10
      2290573.97      7158206.18
#Sta/Elev= 30
  4680.9  789.04  4692.1  788.63  4697.2  787.78  4735.1  786.24  4755.6  784.13
  4785.0  783.54  4790.1  782.51  4834.0  782.10  4847.7  780.41  4877.8  779.65
  4883.0  778.92  4926.8  778.32  4980.1  776.22  5059.8  775.94  5068.5  775.67
  5068.7  775.17  5072.2  775.17  5072.5  775.67  5110.7  776.77  5117.7  778.10
  5130.7  779.75  5231.0  784.66  5271.3  786.31  5291.4  785.89  5311.5  787.81
  5361.7  790.14  5371.7  790.48  5391.8  789.91  5411.9  790.85  5455.9  794.71
#Mann=5,-1,0
  4680.9    0.05       0  5059.8    0.12       0  5068.5   0.033       0
  5072.5    0.12       0  5117.7    0.05       0
Bank Sta=5068.5,5072.5
Exp/Cntr=0.3,0.1

Type RM Length L Ch R = 1,12540,230,230,230
BEGIN DESCRIPTION:
Mapping XS 9332cdba
END DESCRIPTION:
XS GIS Cut Line= 3
      2290608.86      7159012.15      2290642.24      7158665.29
      2290708.62      7158184.00
#Sta/Elev= 30
  4596.0  785.99  4646.5  784.07  4748.8  778.83  4768.9  777.07  4819.2  776.29
  4849.3  774.63  4879.4  774.74  4919.6  773.27  4927.7  771.99  4927.9  771.49
  4931.4  771.49  4931.7  771.99  4956.1  773.43  5000.3  774.53  5010.4  774.02
  5028.0  775.21  5060.8  775.17  5070.9  776.66  5099.9  778.12  5121.4  777.79
  5248.8  783.05  5313.2  784.17  5320.8  785.02  5325.8  784.55  5363.7  787.63
  5392.7  791.29  5397.7  790.83  5404.1  792.49  5424.2  793.95  5430.3  795.55
#Mann=3,-1,0
  4596.0    0.05       0  4927.7   0.033       0  4931.7    0.05       0
Bank Sta=4927.7,4931.7
Exp/Cntr=0.3,0.1

Type RM Length L Ch R = 1,12310,246,246,246
BEGIN DESCRIPTION:
Mapping XS 557e66cb
END DESCRIPTION:
XS GIS Cut Line= 3
      2290679.35      7158985.52      2290855.85      7158550.15
      2290728.01      7158113.36
#Sta/Elev= 30
  4517.0  780.51  4566.1  776.52  4606.6  775.44  4611.9  774.25  4689.6  770.31
  4820.9  771.37  4874.5  770.05  4877.9  768.97  4878.2  768.47  4881.9  768.97
  4928.1  771.34  4989.5  771.14  4992.8  772.27  5007.8  772.37  5018.2  771.48
  5091.1  776.08  5103.5  772.33  5136.9  776.63  5170.3  777.23  5237.0  781.00
  5247.6  783.23  5268.3  783.24  5309.3  789.48  5341.2  789.45  5362.0  791.97
  5386.5  797.43  5393.3  797.62  5414.1  803.80  5436.9  821.99  5441.9  825.79
#Mann=4,-1,0
  4517.0    0.05       0  4877.9   0.033       0  4881.9    0.05       0
  5436.9    0.12       0
Bank Sta=4877.9,4881.9
Exp/Cntr=0.3,0.1

Type RM Length L Ch R = 1,12064,159,159,159
BEGIN DESCRIPTION:
Mapping XS 89a57f4c
END DESCRIPTION:
XS GIS Cut Line= 4
      2290688.97      7159059.74      2291023.51      7158583.94
      2290983.49      7158232.81      2290760.48      7157929.26
#Sta/Elev= 30
  4293.9  781.23  4473.7  768.26  4501.4  769.82  4880.0  765.86  4939.9  769.92
  4978.2  761.00  4978.4  760.50  4982.2  761.00  5002.3  761.73  5030.5  770.38
  5040.5  771.04  5111.0  764.90  5141.2  769.27  5220.5  772.22  5301.6  778.50
  5356.5  781.57  5383.8  788.27  5413.1  789.29  5424.7  793.31  5492.6  802.36
  5498.8  806.37  5513.4  809.80  5519.6  816.34  5528.1  817.48  5534.3  823.67
  5548.9  827.83  5555.1  833.64  5563.6  836.57  5569.8  843.55  5605.6  851.73
#Mann=6,-1,0
  4293.9    0.05       0  4978.2    0.04       0  4982.2    0.05       0
  5002.3    0.12       0  5301.6    0.05       0  5424.7    0.12       0
Bank Sta=4978.2,4982.2
Exp/Cntr=0.3,0.1

Type RM Length L Ch R = 1,11905,362,362,362
BEGIN DESCRIPTION:
MDE S 008 11.0
END DESCRIPTION:
XS GIS Cut Line= 4
      2290736.63      7159279.93      2290999.37      7159044.64
      2291129.00      7158360.00      2290956.24      7157910.03
#Sta/Elev= 30
  3950.5  776.66  3980.7  774.57  4136.3  765.24  4150.5  766.41  4285.1  763.54
  4318.1  765.40  4358.8  762.81  4435.4  764.71  4511.5  763.01  4654.8  763.20
  4684.5  764.46  4915.3  763.29  4979.6  761.81  5045.0  763.03  5051.6  761.76
  5051.8  761.26  5055.6  761.76  5075.0  764.11  5117.8  765.21  5129.7  768.78
  5149.0  767.15  5286.0  775.48  5293.8  774.64  5310.6  777.72  5348.4  780.85
  5378.5  787.87  5391.7  789.45  5417.8  792.12  5449.9  797.74  5482.0  808.08
#Mann=7,-1,0
  3950.5    0.12       0  3980.7    0.05       0  4915.3    0.12       0
  5051.6    0.07       0  5055.6    0.12       0  5286.0    0.05       0
  5391.7    0.12       0
Bank Sta=5051.6,5055.6
Exp/Cntr=0.3,0.1

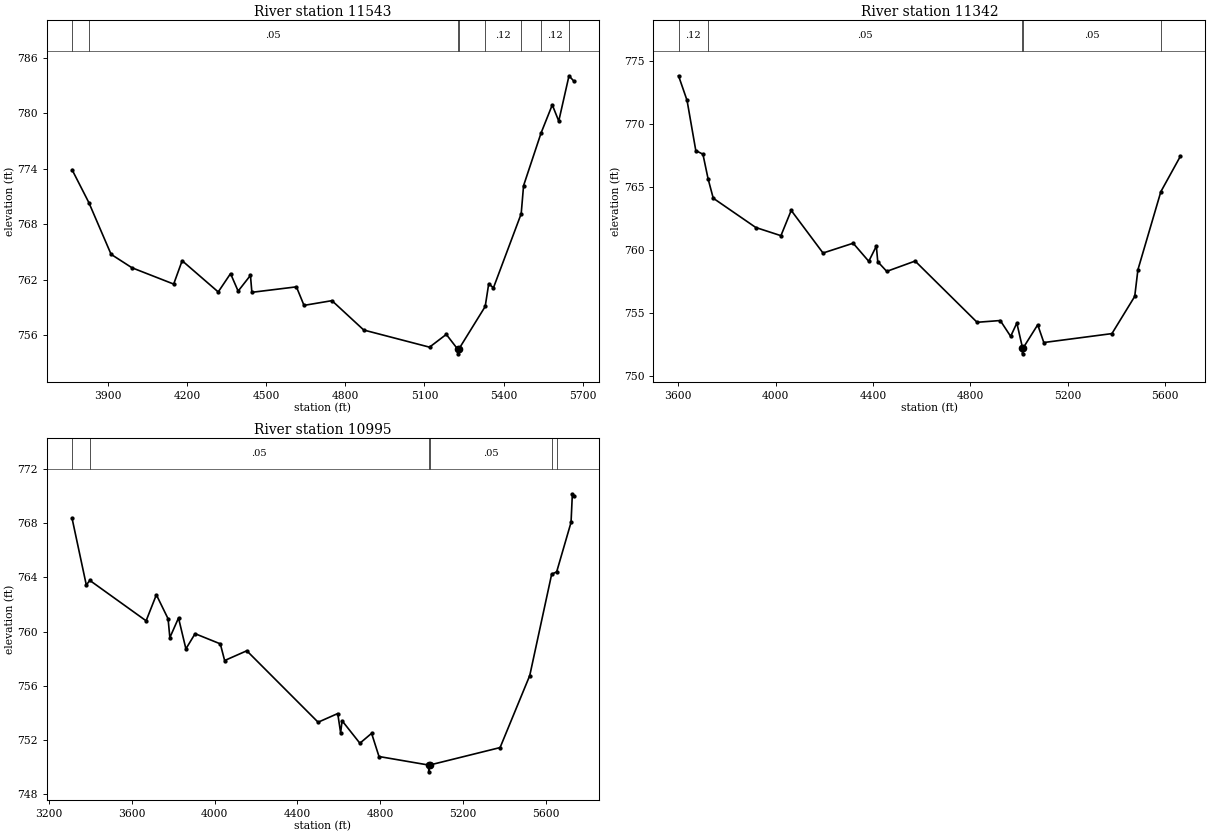
Type RM Length L Ch R = 1,11543,201,201,201
BEGIN DESCRIPTION:
Mapping XS fdd84669
END DESCRIPTION:
XS GIS Cut Line= 4
      2290771.56      7159295.00      2291093.03      7159095.92
      2291436.89      7158313.93      2291194.28      7157689.05
#Sta/Elev= 30
  3763.9  773.89  3827.6  770.34  3911.9  764.76  3991.0  763.31  4149.2  761.55
  4181.3  764.07  4318.1  760.70  4364.8  762.68  4393.6  760.79  4440.3  762.49
  4445.7  760.66  4614.6  761.25  4643.4  759.25  4749.3  759.76  4869.9  756.59
  5119.3  754.74  5182.9  756.12  5226.2  754.52  5226.5  754.02  5230.2  754.52
  5330.4  759.13  5343.8  761.59  5361.6  761.14  5466.9  769.14  5475.9  772.17
  5542.2  777.85  5584.8  780.89  5609.3  779.14  5648.2  784.03  5666.6  783.45
#Mann=8,-1,0
  3763.9    0.12       0  3827.6    0.05       0  5226.2    0.04       0
  5230.2    0.05       0  5330.4    0.12       0  5466.9    0.05       0
  5542.2    0.12       0  5648.2    0.05       0
Bank Sta=5226.2,5230.2
Exp/Cntr=0.3,0.1

Type RM Length L Ch R = 1,11342,347,347,347
BEGIN DESCRIPTION:
Mapping XS d8ca504f
END DESCRIPTION:
XS GIS Cut Line= 4
      2290789.71      7159329.59      2291138.61      7159101.31
      2291630.08      7158283.77      2291389.77      7157636.69
#Sta/Elev= 30
  3601.7  773.86  3636.7  771.90  3672.6  767.91  3701.9  767.62  3723.1  765.66
  3744.3  764.12  3919.1  761.79  4022.3  761.14  4064.5  763.15  4195.2  759.76
  4319.0  760.54  4383.1  759.10  4414.2  760.31  4420.0  759.07  4456.9  758.30
  4573.5  759.12  4828.0  754.25  4923.2  754.39  4965.9  753.13  4991.3  754.19
  5014.3  752.24  5014.6  751.74  5018.3  752.24  5077.0  754.05  5102.1  752.64
  5381.9  753.35  5475.5  756.31  5488.6  758.43  5582.8  764.64  5662.8  767.45
#Mann=5,-1,0
  3601.7    0.12       0  3723.1    0.05       0  5014.3   0.033       0
  5018.3    0.05       0  5582.8    0.12       0
Bank Sta=5014.3,5018.3
Exp/Cntr=0.3,0.1

Type RM Length L Ch R = 1,10995,0,0,0
BEGIN DESCRIPTION:
MDE S 008 10.0
END DESCRIPTION:
XS GIS Cut Line= 4
      2290855.85      7159313.07      2291168.99      7159093.97
      2291892.39      7158079.64      2291407.95      7157451.36
#Sta/Elev= 30
  3312.4  768.35  3381.1  763.43  3398.0  763.77  3669.7  760.79  3719.2  762.71
  3775.7  760.94  3784.3  759.55  3826.1  761.00  3861.7  758.72  3906.0  759.84
  4027.7  759.09  4048.6  757.86  4155.5  758.58  4499.7  753.31  4594.4  753.95
  4608.4  752.52  4615.3  753.42  4701.3  751.76  4757.8  752.49  4793.5  750.78
  5033.4  750.15  5033.6  749.65  5037.4  750.15  5377.8  751.44  5520.9  756.75
  5626.7  764.23  5650.8  764.40  5720.2  768.05  5726.6  770.16  5733.8  770.02
#Mann=6,-1,0
  3312.4    0.12       0  3398.0    0.05       0  5033.4   0.033       0
  5037.4    0.05       0  5626.7    0.12       0  5650.8    0.05       0
Bank Sta=5033.4,5037.4
Exp/Cntr=0.3,0.1

Chan Stop Cuts=-1