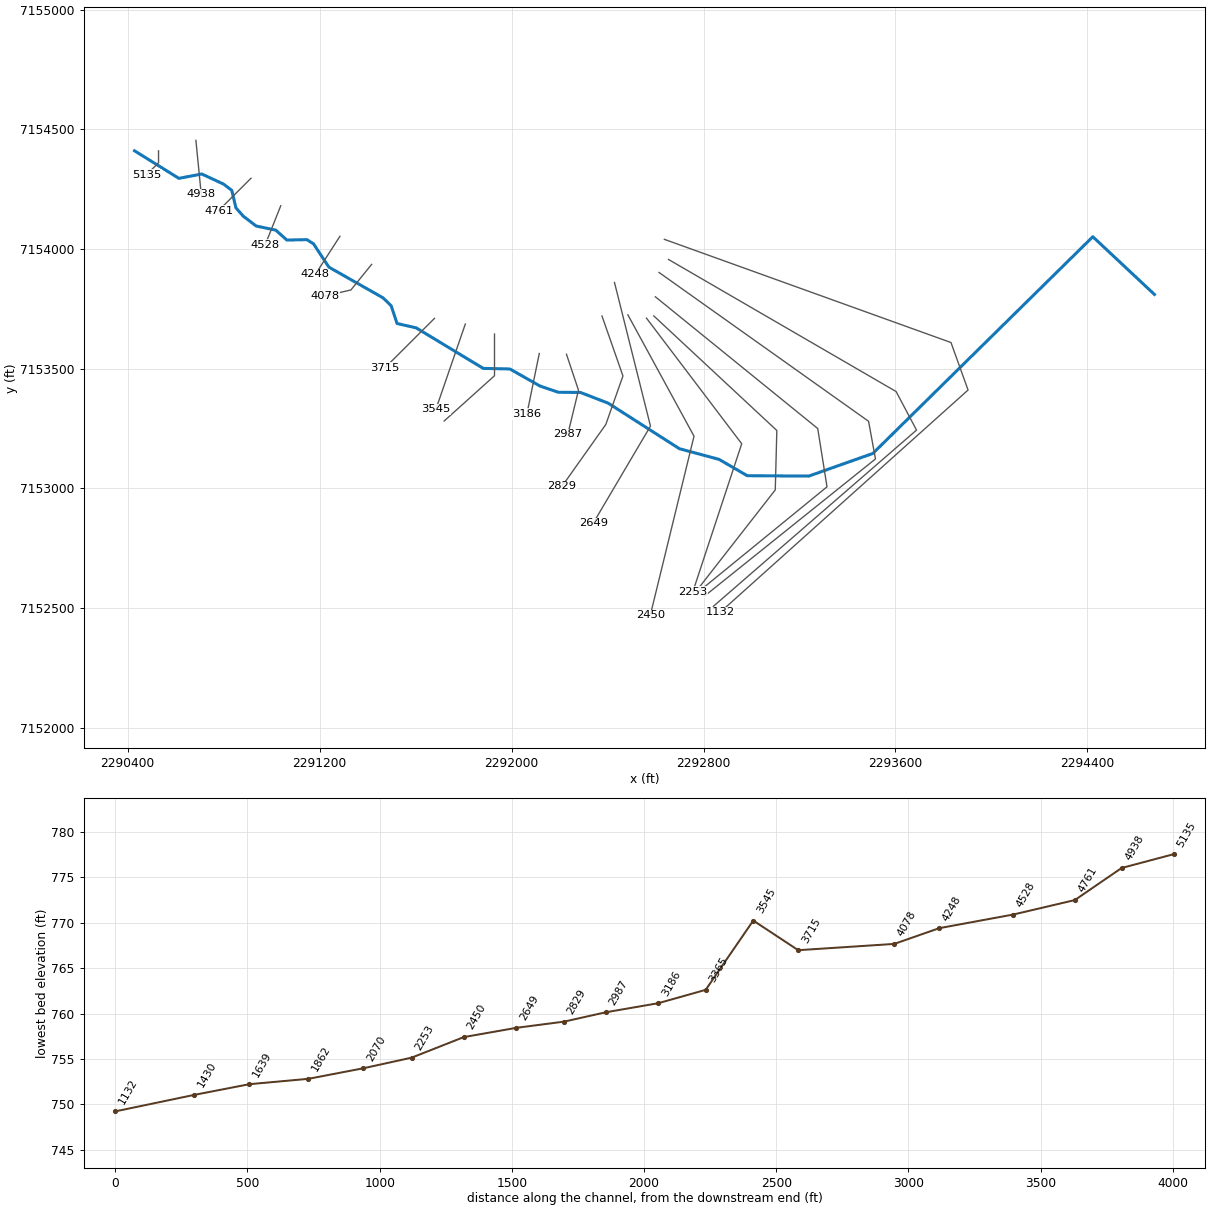
--- MDE S 009.prj (project) ---

Proj Title=MDE S 009 Base Level Engineering
Current Plan=p01
Default Exp/Contr=0.3,0.1
English Units
Geom File=g01
Flow File=f01
Plan File=p01
BEGIN DESCRIPTION:
MDE S 009
END DESCRIPTION:

--- MDE S 009.p01 (plan) ---

Plan Title=Multiple Run
Short Identifier=Multiple
Geom File=g01
Flow File=f01
Subcritical Flow
K Sum by GR= 0
Std Step Tol= 0.01
Critical Tol= 0.01
Num of Std Step Trials= 20
Max Error Tol= 0.3
Flow Tol Ratio= 0.001
Split Flow NTrial= 30
Split Flow Tol= 0.02
Split Flow Ratio= 0.02
Log Output Level= 0
Friction Slope Method= 1
Unsteady Friction Slope Method= 2
Unsteady Bridges Friction Slope Method= 1
Parabolic Critical Depth
Global Vel Dist=  1 , 1 , 1
Global Log Level= 0
CheckData=True
Encroach Param= -1, 0, 0, 0
BEGIN DESCRIPTION:
Multiple Run
END DESCRIPTION:

--- MDE S 009.f01 (steady flow) ---

Flow Title=Multiple
Number of Profiles=7
Profile Names=10-year,25-year,50-year,1pct_min,100-year,1pct_plu,500-year
River Rch & RM= MDE S 009,Reach-1,5135
     782    1097    1364     843    1682    3355    2560
River Rch & RM= MDE S 009,Reach-1,2253
     749    1045    1294     797    1589    3171    2401
Boundary for River Rch & Prof#=MDE S 009,Reach-1,1
Up Type=0
Dn Type=3
Dn Slope=0.005
Boundary for River Rch & Prof#=MDE S 009,Reach-1,2
Up Type=0
Dn Type=3
Dn Slope=0.005
Boundary for River Rch & Prof#=MDE S 009,Reach-1,3
Up Type=0
Dn Type=3
Dn Slope=0.005
Boundary for River Rch & Prof#=MDE S 009,Reach-1,4
Up Type=0
Dn Type=3
Dn Slope=0.005
Boundary for River Rch & Prof#=MDE S 009,Reach-1,5
Up Type=0
Dn Type=3
Dn Slope=0.005
Boundary for River Rch & Prof#=MDE S 009,Reach-1,6
Up Type=0
Dn Type=3
Dn Slope=0.005
Boundary for River Rch & Prof#=MDE S 009,Reach-1,7
Up Type=0
Dn Type=3
Dn Slope=0.005

--- MDE S 009.g01 (geometry) ---

Geom Title=Existing Conditions

River Reach=MDE S 009,Reach-1
Reach XY= 30
      2290429.00      7154410.00      2290613.77      7154294.92
      2290709.21      7154313.14      2290800.08      7154270.89
      2290834.18      7154244.93      2290851.48      7154171.52
      2290882.21      7154136.89      2290935.79      7154095.91
      2291017.44      7154078.64      2291063.77      7154037.18
      2291147.30      7154038.84      2291174.74      7154021.44
      2291238.95      7153923.95      2291464.77      7153795.66
      2291498.85      7153761.72      2291522.85      7153688.54
      2291602.73      7153670.30      2291882.19      7153501.00
      2291993.03      7153498.65      2292118.23      7153427.54
      2292194.98      7153401.30      2292287.19      7153400.50
      2292402.64      7153355.83      2292699.48      7153165.53
      2292864.99      7153120.89      2292982.38      7153052.72
      2293238.92      7153051.16      2293505.55      7153145.63
      2294422.33      7154051.05      2294679.00      7153810.00

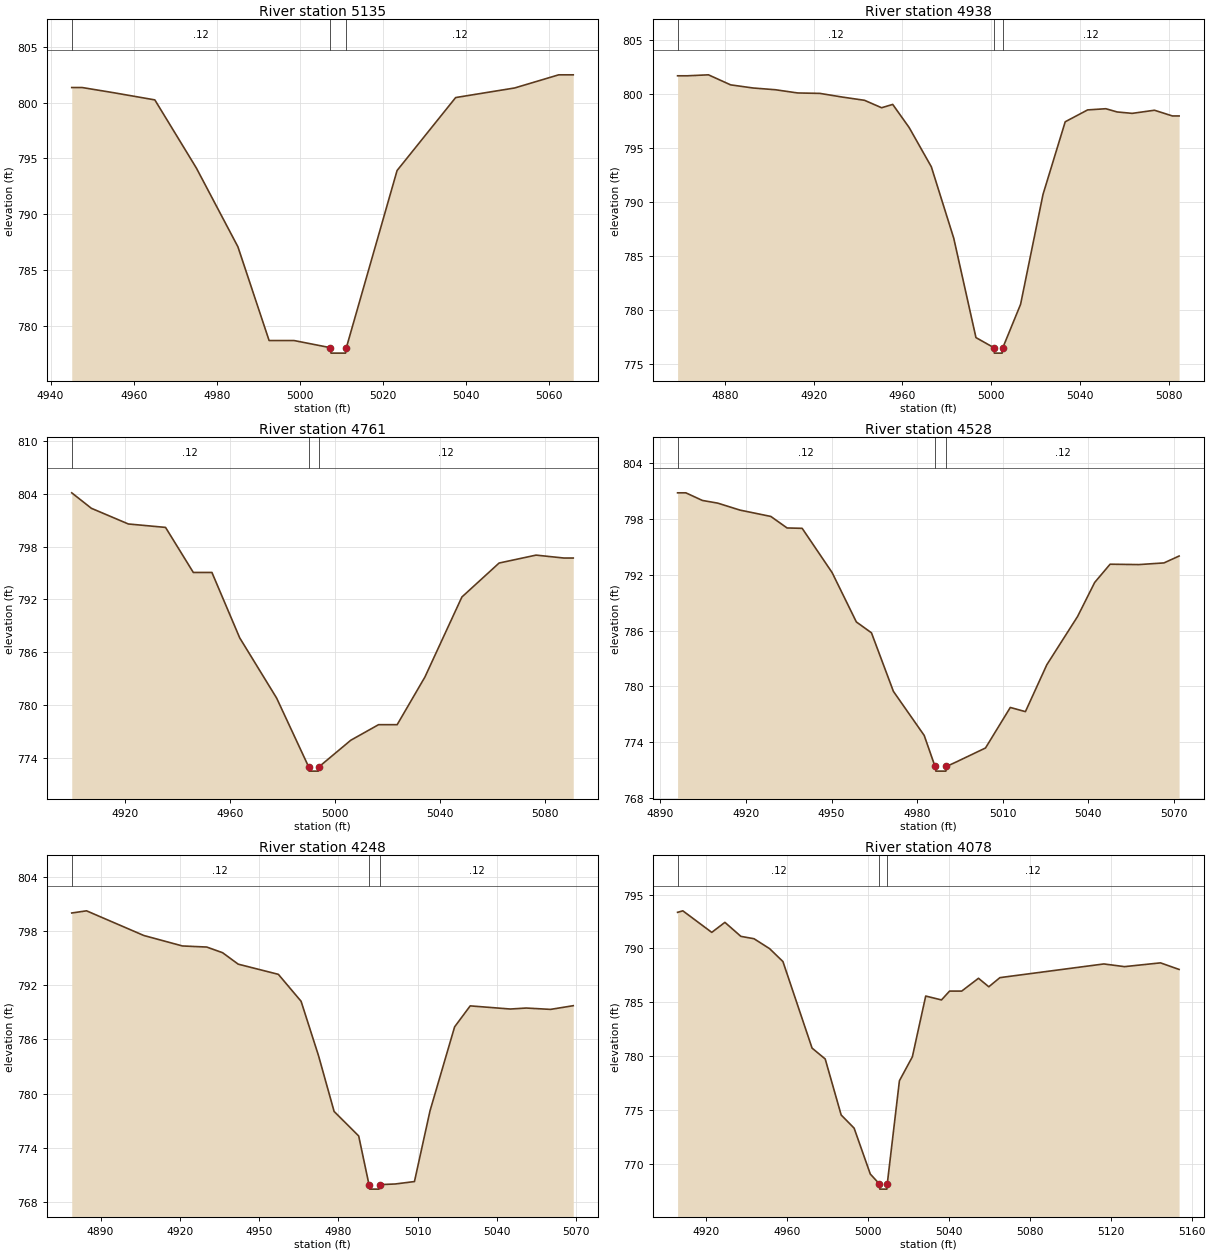
Type RM Length L Ch R = 1,5135,197,197,197
BEGIN DESCRIPTION:
MDE S 009 12.0
END DESCRIPTION:
XS GIS Cut Line= 3
      2290529.00      7154410.00      2290529.00      7154360.00
      2290479.01      7154310.01
#Sta/Elev= 18
  4945.1  801.37  4947.6  801.37  4955.1  800.91  4965.1  800.26  4975.1  794.14
  4985.1  787.07  4992.6  778.66  4995.1  778.66  4998.6  778.66  5007.2  778.03
  5007.5  777.53  5011.0  777.53  5011.2  778.03  5023.4  793.92  5037.5  800.47
  5051.7  801.33  5062.3  802.51  5065.8  802.51
#Mann=3,-1,0
  4945.1    0.12       0  5007.2    0.07       0  5011.2    0.12       0
Bank Sta=5007.2,5011.2
Exp/Cntr=0.3,0.1

Type RM Length L Ch R = 1,4938,177,177,177
BEGIN DESCRIPTION:
Mapping XS 185316d3
END DESCRIPTION:
XS GIS Cut Line= 2
      2290684.68      7154453.79      2290706.93      7154228.99
#Sta/Elev= 30
  4858.7  801.70  4863.1  801.70  4872.6  801.79  4882.6  800.86  4892.7  800.57
  4902.7  800.41  4912.8  800.11  4922.8  800.07  4932.9  799.73  4942.9  799.43
  4950.6  798.74  4955.6  799.05  4963.0  796.91  4973.0  793.27  4983.1  786.65
  4993.1  777.45  5001.2  776.51  5001.4  776.01  5004.9  776.01  5005.2  776.51
  5013.2  780.53  5023.3  790.71  5033.3  797.44  5043.4  798.54  5051.6  798.65
  5056.7  798.35  5063.5  798.22  5073.5  798.51  5081.6  797.98  5084.6  797.98
#Mann=3,-1,0
  4858.7    0.12       0  5001.2    0.07       0  5005.2    0.12       0
Bank Sta=5001.2,5005.2
Exp/Cntr=0.3,0.1

Type RM Length L Ch R = 1,4761,233,233,233
BEGIN DESCRIPTION:
MDE S 009 11.0
END DESCRIPTION:
XS GIS Cut Line= 4
      2290914.31      7154295.31      2290879.00      7154260.00
      2290829.00      7154210.00      2290778.97      7154159.97
#Sta/Elev= 21
  4899.5  804.11  4907.0  802.35  4921.1  800.57  4935.3  800.18  4945.9  795.06
  4953.0  795.06  4963.6  787.63  4977.7  780.78  4989.9  772.98  4990.1  772.48
  4993.6  772.48  4993.9  772.98  5006.0  775.99  5016.6  777.76  5023.7  777.76
  5034.3  783.18  5048.4  792.27  5062.6  796.13  5076.7  797.03  5087.3  796.70
  5090.9  796.70
#Mann=3,-1,0
  4899.5    0.12       0  4989.9    0.07       0  4993.9    0.12       0
Bank Sta=4989.9,4993.9
Exp/Cntr=0.3,0.1

Type RM Length L Ch R = 1,4528,280,280,280
BEGIN DESCRIPTION:
Mapping XS 30f96a5f
END DESCRIPTION:
XS GIS Cut Line= 2
      2291038.27      7154180.38      2290973.34      7154016.90
#Sta/Elev= 28
  4896.0  800.83  4898.9  800.83  4904.7  800.01  4910.1  799.72  4917.9  798.97
  4928.7  798.29  4934.4  797.05  4939.7  797.01  4950.2  792.25  4958.7  786.94
  4964.0  785.77  4971.7  779.47  4982.5  774.73  4986.3  771.39  4986.6  770.89
  4990.1  770.89  4990.3  771.39  4993.7  771.87  5004.0  773.38  5012.7  777.74
  5018.0  777.29  5025.5  782.33  5036.3  787.53  5042.3  791.19  5047.7  793.15
  5057.8  793.11  5066.6  793.29  5071.9  794.03
#Mann=3,-1,0
  4896.0    0.12       0  4986.3    0.07       0  4990.3    0.12       0
Bank Sta=4986.3,4990.3
Exp/Cntr=0.3,0.1

Type RM Length L Ch R = 1,4248,170,170,170
BEGIN DESCRIPTION:
Mapping XS 529a4c22
END DESCRIPTION:
XS GIS Cut Line= 2
      2291284.93      7154052.95      2291182.17      7153893.37
#Sta/Elev= 25
  4879.1  800.04  4884.7  800.28  4906.4  797.54  4921.0  796.38  4930.2  796.26
  4936.2  795.63  4942.1  794.36  4957.3  793.23  4965.9  790.24  4972.5  784.20
  4978.4  778.01  4987.7  775.29  4991.6  769.89  4991.9  769.39  4995.4  769.39
  4995.6  769.89  5001.5  769.96  5008.8  770.23  5014.7  778.09  5024.0  787.40
  5029.9  789.73  5045.1  789.38  5051.1  789.49  5060.3  789.34  5068.9  789.75
#Mann=3,-1,0
  4879.1    0.12       0  4991.6    0.07       0  4995.6    0.12       0
Bank Sta=4991.6,4995.6
Exp/Cntr=0.3,0.1

Type RM Length L Ch R = 1,4078,363,363,363
BEGIN DESCRIPTION:
MDE S 009 9.0
END DESCRIPTION:
XS GIS Cut Line= 3
      2291416.90      7153935.40      2291330.75      7153828.79
      2291222.76      7153803.42
#Sta/Elev= 30
  4905.8  793.35  4908.4  793.49  4922.7  791.49  4929.2  792.42  4937.1  791.12
  4943.6  790.90  4951.3  789.98  4957.9  788.78  4972.3  780.75  4978.8  779.74
  4986.7  774.54  4993.1  773.32  5001.1  769.06  5005.5  768.16  5005.8  767.66
  5009.3  767.66  5009.5  768.16  5015.5  777.72  5021.9  779.94  5028.5  785.58
  5036.3  785.22  5040.3  786.04  5046.3  786.04  5054.6  787.23  5059.7  786.44
  5065.2  787.29  5116.6  788.56  5126.8  788.31  5144.6  788.66  5153.8  788.05
#Mann=3,-1,0
  4905.8    0.12       0  5005.5    0.07       0  5009.5    0.12       0
Bank Sta=5005.5,5009.5
Exp/Cntr=0.3,0.1

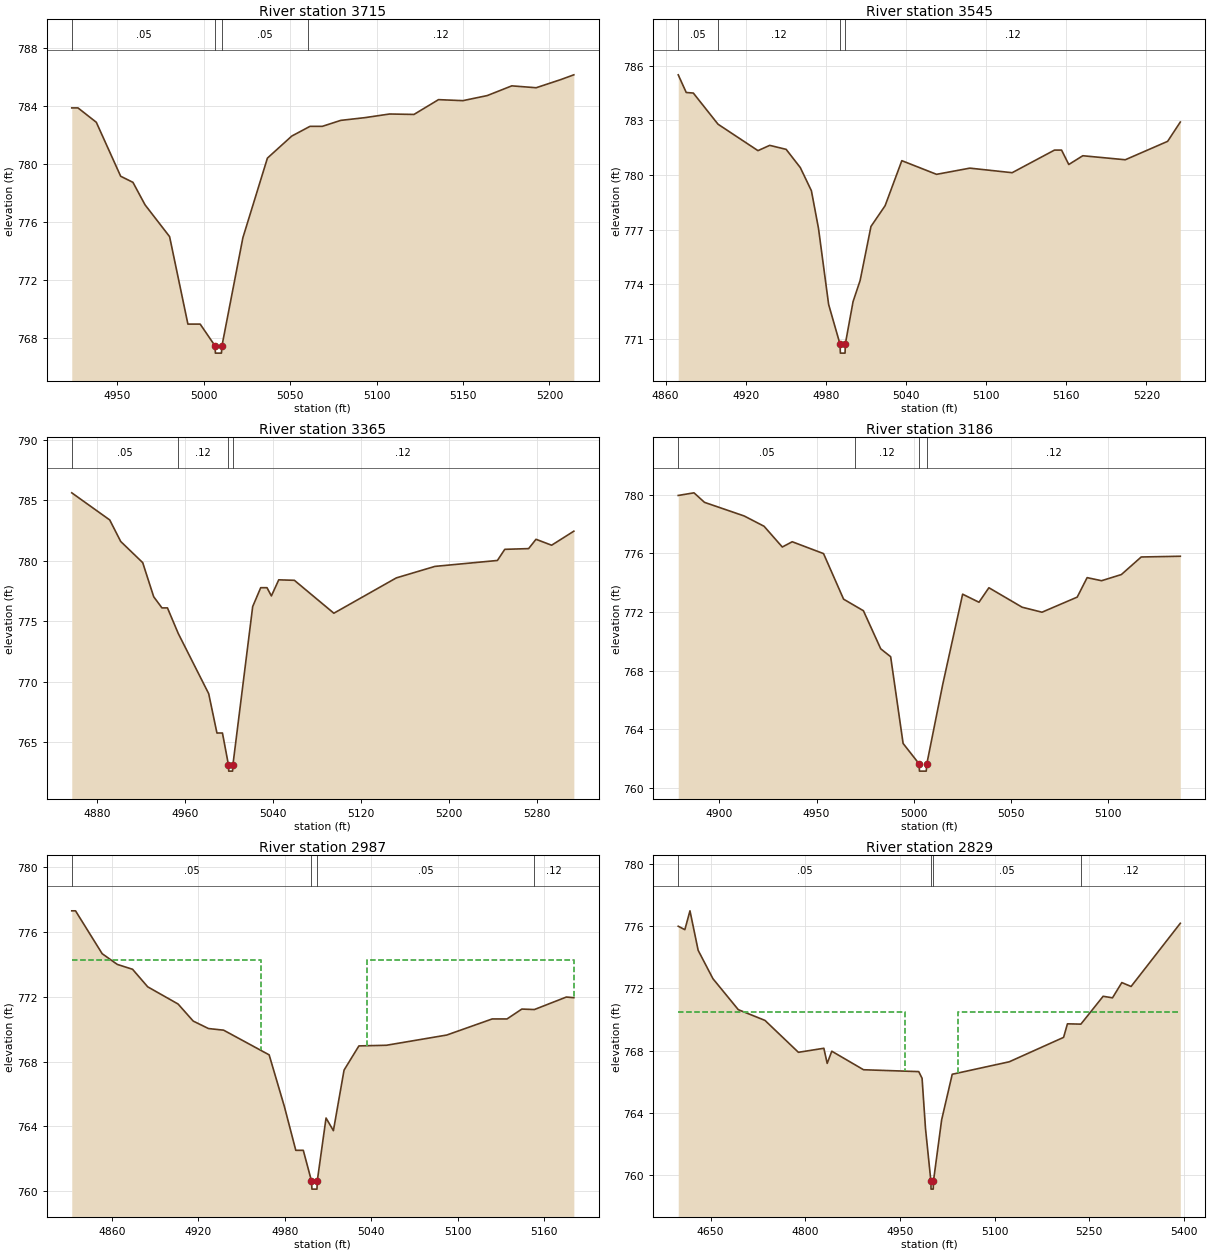
Type RM Length L Ch R = 1,3715,170,170,170
BEGIN DESCRIPTION:
MDE S 009 8.0
END DESCRIPTION:
XS GIS Cut Line= 4
      2291679.02      7153710.02      2291629.00      7153660.00
      2291579.00      7153610.00      2291473.60      7153504.60
#Sta/Elev= 30
  4923.6  783.87  4927.2  783.87  4937.8  782.88  4951.9  779.16  4959.0  778.74
  4966.0  777.19  4980.2  775.00  4990.8  768.97  4997.9  768.97  5006.5  767.47
  5006.7  766.97  5010.2  766.97  5010.5  767.47  5022.6  774.92  5036.8  780.41
  5050.9  781.93  5060.5  782.54  5061.5  782.60  5068.6  782.60  5079.2  783.01
  5093.3  783.20  5107.5  783.45  5121.6  783.42  5135.8  784.44  5149.9  784.37
  5164.0  784.72  5178.2  785.39  5192.3  785.26  5206.5  785.82  5214.1  786.15
#Mann=4,-1,0
  4923.6    0.05       0  5006.5   0.033       0  5010.5    0.05       0
  5060.5    0.12       0
Bank Sta=5006.5,5010.5
Exp/Cntr=0.3,0.1

Type RM Length L Ch R = 1,3545,180,180,180
BEGIN DESCRIPTION:
Mapping XS f1c09bed
END DESCRIPTION:
XS GIS Cut Line= 3
      2291807.44      7153686.42      2291728.52      7153457.27
      2291685.04      7153331.01
#Sta/Elev= 30
  4869.5  785.50  4875.5  784.53  4880.8  784.50  4899.3  782.79  4929.2  781.34
  4938.0  781.63  4950.3  781.41  4960.9  780.41  4969.2  779.14  4974.5  777.08
  4982.1  772.90  4990.6  770.73  4990.9  770.23  4994.4  770.23  4994.6  770.73
  5000.4  773.06  5005.7  774.22  5013.8  777.18  5024.4  778.32  5036.9  780.79
  5062.9  780.04  5087.8  780.38  5119.5  780.13  5151.2  781.37  5156.5  781.37
  5161.9  780.58  5172.4  781.06  5204.2  780.84  5235.9  781.85  5245.4  782.91
#Mann=4,-1,0
  4869.5    0.05       0  4899.3    0.12       0  4990.6    0.07       0
  4994.6    0.12       0
Bank Sta=4990.6,4994.6
Exp/Cntr=0.3,0.1

Type RM Length L Ch R = 1,3365,179,179,179
BEGIN DESCRIPTION:
MDE S 009 7.0
END DESCRIPTION:
XS GIS Cut Line= 5
      2291929.00      7153644.45      2291929.00      7153560.00
      2291929.00      7153510.00      2291929.00      7153470.34
      2291719.28      7153281.24
#Sta/Elev= 30
  4856.8  785.61  4891.3  783.37  4901.3  781.59  4921.3  779.84  4931.3  777.02
  4938.8  776.10  4943.8  776.10  4953.6  773.99  4981.3  769.01  4988.8  765.76
  4993.8  765.76  4999.3  763.11  4999.5  762.61  5003.0  762.61  5003.3  763.11
  5021.3  776.21  5028.6  777.77  5034.3  777.77  5038.3  777.09  5045.0  778.42
  5059.2  778.38  5095.1  775.66  5151.9  778.58  5187.0  779.53  5243.8  780.02
  5250.5  780.94  5272.2  781.00  5278.9  781.77  5293.1  781.28  5313.3  782.44
#Mann=4,-1,0
  4856.8    0.05       0  4953.6    0.12       0  4999.3    0.07       0
  5003.3    0.12       0
Bank Sta=4999.3,5003.3
Exp/Cntr=0.3,0.1

Type RM Length L Ch R = 1,3186,199,199,199
BEGIN DESCRIPTION:
Mapping XS 3896ac8f
END DESCRIPTION:
XS GIS Cut Line= 2
      2292115.55      7153563.24      2292063.98      7153310.35
#Sta/Elev= 30
  4878.9  779.96  4887.0  780.14  4892.4  779.49  4912.8  778.56  4923.0  777.86
  4932.4  776.44  4937.5  776.80  4953.6  775.99  4963.9  772.88  4969.7  772.43
  4974.1  772.09  4983.0  769.49  4988.1  768.95  4994.5  763.03  5002.7  761.64
  5002.9  761.14  5006.4  761.14  5006.7  761.64  5014.9  767.08  5025.1  773.22
  5033.5  772.67  5038.6  773.66  5055.7  772.33  5065.9  771.99  5084.0  773.02
  5089.1  774.35  5096.5  774.14  5106.7  774.56  5116.9  775.76  5137.0  775.81
#Mann=4,-1,0
  4878.9    0.05       0  4969.7    0.12       0  5002.7    0.07       0
  5006.7    0.12       0
Bank Sta=5002.7,5006.7
Exp/Cntr=0.3,0.1

Type RM Length L Ch R = 1,2987,158,158,158
BEGIN DESCRIPTION:
MDE S 009 6.0
END DESCRIPTION:
XS GIS Cut Line= 3
      2292229.00      7153560.00      2292279.00      7153410.00
      2292234.33      7153224.93
#Sta/Elev= 30
  4832.1  777.28  4834.7  777.28  4853.2  774.64  4863.7  773.98  4874.3  773.68
  4884.8  772.60  4905.9  771.54  4916.4  770.49  4927.0  770.03  4937.5  769.93
  4969.1  768.41  4979.7  765.22  4987.6  762.53  4992.8  762.53  4998.5  760.64
  4998.8  760.14  5002.3  760.14  5002.5  760.64  5008.6  764.52  5013.7  763.74
  5021.1  767.47  5031.4  768.96  5050.5  769.00  5092.4  769.63  5123.9  770.62
  5134.2  770.62  5144.5  771.23  5153.2  771.20  5175.4  771.97  5180.6  771.93
#Mann=4,-1,0
  4832.1    0.05       0  4998.5   0.033       0  5002.5    0.05       0
  5153.2    0.12       0
#XS Ineff=2,0
    0.00 4963.30  774.23 5036.70    0.00  774.23
Permanent Ineff=
       F       F
Bank Sta=4998.5,5002.5
Exp/Cntr=0.3,0.1

Type RM Length L Ch R = 1,2829,180,180,180
BEGIN DESCRIPTION:
Mapping XS e7a97ca8
END DESCRIPTION:
XS GIS Cut Line= 4
      2292376.94      7153719.87      2292464.29      7153469.37
      2292392.82      7153266.65      2292210.69      7153008.96
#Sta/Elev= 30
  4598.6  776.00  4609.1  775.78  4617.2  776.99  4630.2  774.45  4653.6  772.63
  4693.8  770.64  4736.1  769.95  4789.1  767.90  4829.4  768.16  4834.7  767.19
  4842.0  767.97  4892.3  766.78  4979.8  766.66  4985.1  766.23  4990.5  763.01
  4999.1  759.61  4999.3  759.11  5002.8  759.11  5003.1  759.61  5016.1  763.56
  5032.9  766.49  5123.2  767.29  5209.4  768.86  5215.5  769.73  5236.8  769.71
  5272.1  771.50  5286.9  771.40  5301.7  772.38  5316.4  772.13  5394.4  776.19
#Mann=4,-1,0
  4598.6    0.05       0  4999.1   0.033       0  5003.1    0.05       0
  5236.8    0.12       0
#XS Ineff=2,0
    0.00 4957.30  770.46 5042.70    0.00  770.46
Permanent Ineff=
       F       F
Bank Sta=4999.1,5003.1
Exp/Cntr=0.3,0.1

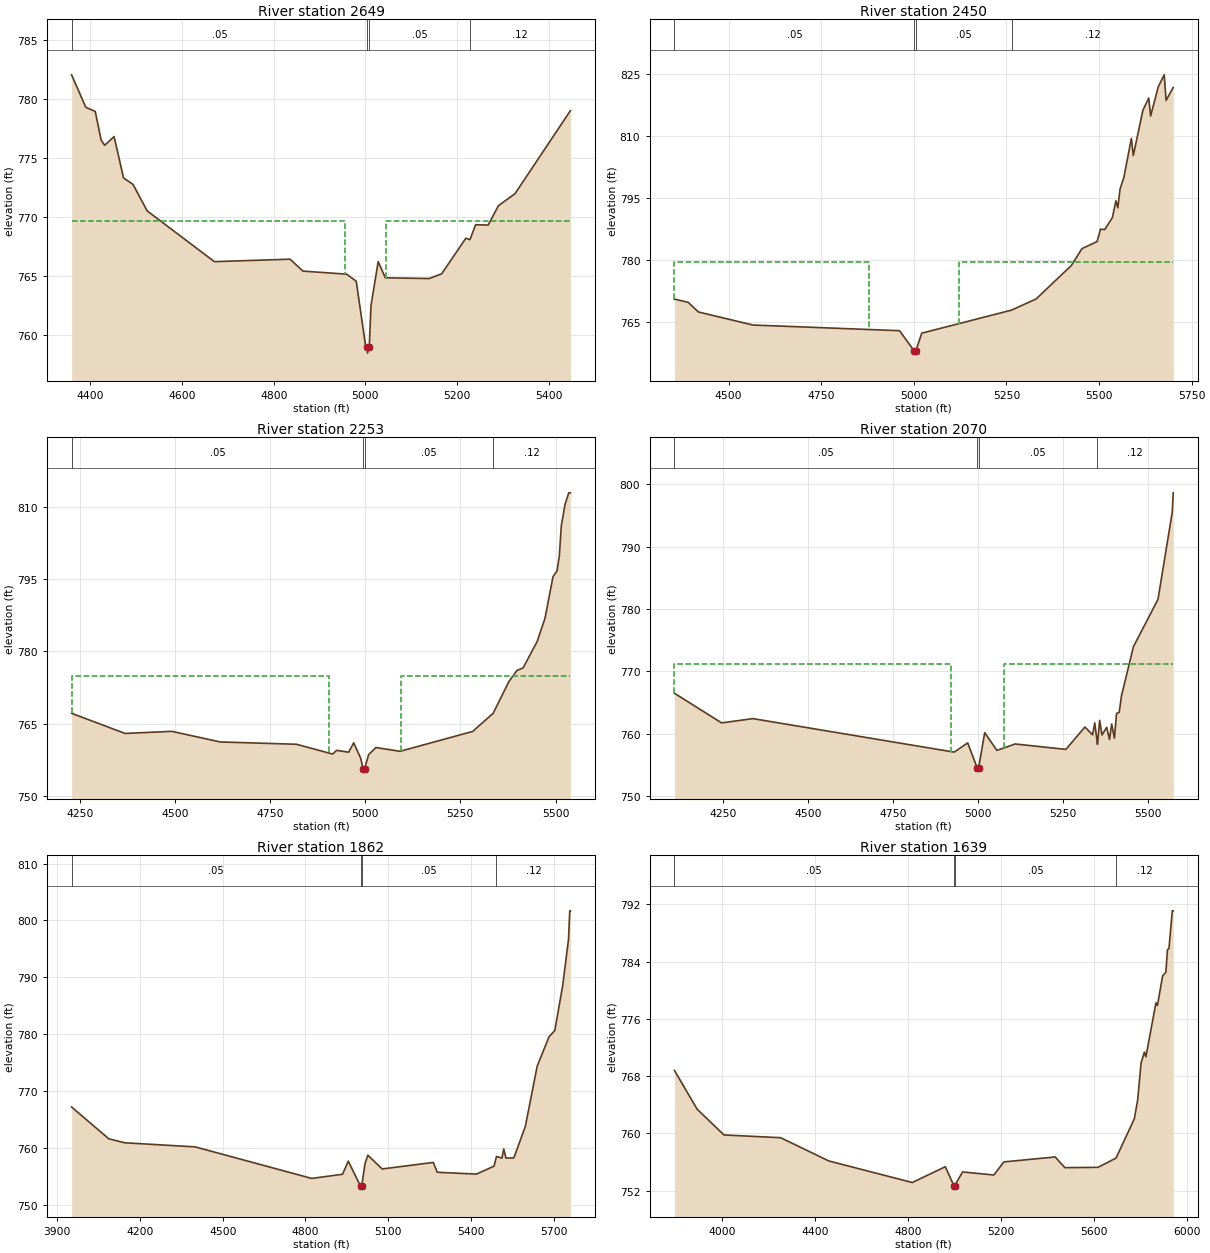
Type RM Length L Ch R = 1,2649,199,199,199
BEGIN DESCRIPTION:
MDE S 009 5.0
END DESCRIPTION:
XS GIS Cut Line= 3
      2292428.99      7153860.04      2292579.00      7153260.00
      2292340.41      7152854.60
#Sta/Elev= 30
  4358.8  782.01  4389.8  779.26  4410.4  778.91  4423.3  776.48  4431.0  776.04
  4451.6  776.78  4472.2  773.27  4492.8  772.73  4523.8  770.48  4670.6  766.18
  4835.6  766.39  4863.9  765.38  4959.3  765.12  4980.2  764.52  5000.5  759.07
  5004.6  758.93  5004.8  758.43  5008.6  758.93  5012.4  762.46  5028.1  766.18
  5043.7  764.81  5139.4  764.75  5166.7  765.15  5219.5  768.17  5228.4  768.04
  5240.9  769.31  5268.2  769.28  5290.6  770.92  5326.8  771.94  5447.7  778.97
#Mann=4,-1,0
  4358.8    0.05       0  5004.6   0.033       0  5008.6    0.05       0
  5228.4    0.12       0
#XS Ineff=2,0
    0.00 4955.80  769.60 5044.20    0.00  769.60
Permanent Ineff=
       F       F
Bank Sta=5004.6,5008.6
Exp/Cntr=0.3,0.1

Type RM Length L Ch R = 1,2450,197,197,197
BEGIN DESCRIPTION:
Mapping XS dd18a070
END DESCRIPTION:
XS GIS Cut Line= 3
      2292484.79      7153724.85      2292760.41      7153217.82
      2292578.43      7152470.47
#Sta/Elev= 30
  4354.0  770.48  4391.1  769.70  4418.6  767.37  4565.9  764.21  4961.6  762.84
  5001.3  757.91  5001.5  757.41  5005.3  757.91  5021.5  762.24  5264.0  767.82
  5330.3  770.53  5425.6  778.65  5453.8  782.69  5494.9  784.42  5503.9  787.41
  5515.5  787.32  5536.1  790.23  5545.6  794.29  5550.7  792.58  5556.7  797.11
  5567.0  799.91  5587.3  809.36  5592.5  805.23  5618.4  816.18  5634.2  819.14
  5639.3  814.79  5659.6  821.81  5675.9  824.76  5681.0  818.57  5700.3  821.71
#Mann=4,-1,0
  4354.0    0.05       0  5001.3   0.033       0  5005.3    0.05       0
  5264.0    0.12       0
#XS Ineff=2,0
    0.00 4878.60  779.49 5121.40    0.00  779.49
Permanent Ineff=
       F       F
Bank Sta=5001.3,5005.3
Exp/Cntr=0.3,0.1

Type RM Length L Ch R = 1,2253,183,183,183
BEGIN DESCRIPTION:
Mapping XS 993fcc14
END DESCRIPTION:
XS GIS Cut Line= 3
      2292562.22      7153711.18      2292959.21      7153186.21
      2292755.12      7152566.63
#Sta/Elev= 30
  4228.6  767.14  4369.2  762.96  4492.0  763.40  4618.9  761.20  4819.3  760.72
  4914.4  758.69  4924.9  759.46  4956.5  759.07  4969.8  761.02  4988.1  757.83
  4994.3  755.65  4994.6  755.15  4998.3  755.65  5009.1  758.57  5028.1  760.04
  5091.6  759.26  5282.3  763.38  5336.1  767.13  5377.6  773.73  5398.7  776.02
  5414.7  776.54  5451.7  782.01  5472.4  786.85  5493.4  795.46  5504.0  796.67
  5510.0  799.71  5515.2  805.99  5525.0  810.45  5534.7  812.85  5539.1  812.85
#Mann=4,-1,0
  4228.6    0.05       0  4994.3    0.04       0  4998.3    0.05       0
  5336.1    0.12       0
#XS Ineff=2,0
    0.00 4904.70  774.93 5095.30    0.00  774.93
Permanent Ineff=
       F       F
Bank Sta=4994.3,4998.3
Exp/Cntr=0.3,0.1

Type RM Length L Ch R = 1,2070,208,208,208
BEGIN DESCRIPTION:
Mapping XS 93a1298c
END DESCRIPTION:
XS GIS Cut Line= 4
      2292592.91      7153720.19      2293105.54      7153241.67
      2293098.98      7152993.29      2292780.65      7152584.56
#Sta/Elev= 30
  4107.8  766.48  4246.7  761.72  4338.5  762.41  4930.8  757.03  4970.8  758.51
  4998.8  754.48  4999.1  753.98  5002.8  754.48  5020.8  760.15  5056.7  757.31
  5110.3  758.34  5259.6  757.47  5315.7  761.06  5338.3  759.81  5344.6  761.72
  5350.8  759.08  5352.7  758.27  5359.1  762.13  5365.9  759.79  5379.9  761.02
  5388.0  759.07  5394.4  761.55  5402.5  759.27  5408.8  763.24  5416.6  763.42
  5423.3  766.08  5458.6  773.98  5530.7  781.55  5572.6  795.52  5575.6  798.66
#Mann=4,-1,0
  4107.8    0.05       0  4998.8    0.04       0  5002.8    0.05       0
  5350.8    0.12       0
#XS Ineff=2,0
    0.00 4922.60  771.14 5077.40    0.00  771.14
Permanent Ineff=
       F       F
Bank Sta=4998.8,5002.8
Exp/Cntr=0.3,0.1

Type RM Length L Ch R = 1,1862,223,223,223
BEGIN DESCRIPTION:
Mapping XS 0ef05686
END DESCRIPTION:
XS GIS Cut Line= 4
      2292599.39      7153800.12      2293275.92      7153249.87
      2293314.66      7153006.27      2292780.50      7152569.04
#Sta/Elev= 30
  3951.9  767.24  4086.8  761.66  4144.2  760.96  4399.9  760.24  4822.7  754.70
  4934.6  755.43  4955.4  757.74  4999.9  753.32  5000.1  752.82  5003.9  753.32
  5016.2  757.34  5026.3  758.78  5078.5  756.36  5263.7  757.51  5278.0  755.78
  5420.2  755.46  5484.0  756.85  5492.8  758.55  5512.8  758.27  5519.2  759.87
  5527.1  758.28  5555.8  758.30  5597.5  763.83  5640.5  774.42  5683.6  779.58
  5704.4  780.67  5733.1  788.60  5753.9  796.62  5758.7  801.69  5760.9  801.69
#Mann=4,-1,0
  3951.9    0.05       0  4999.9    0.04       0  5003.9    0.05       0
  5492.8    0.12       0
Bank Sta=4999.9,5003.9
Exp/Cntr=0.3,0.1

Type RM Length L Ch R = 1,1639,209,209,209
BEGIN DESCRIPTION:
Mapping XS ea1a4b05
END DESCRIPTION:
XS GIS Cut Line= 4
      2292614.69      7153901.75      2293487.79      7153280.08
      2293516.59      7153122.75      2292804.24      7152549.83
#Sta/Elev= 30
  3796.2  768.80  3893.8  763.39  4009.4  759.79  4252.8  759.41  4460.6  756.16
  4819.6  753.15  4961.4  755.36  4998.2  752.73  4998.5  752.23  5002.2  752.73
  5035.8  754.63  5170.2  754.20  5213.4  756.03  5434.2  756.72  5475.8  755.23
  5618.2  755.27  5696.0  756.56  5774.9  762.07  5789.3  764.74  5803.7  769.85
  5818.1  771.36  5824.5  770.70  5867.7  778.24  5874.1  777.87  5896.5  782.02
  5910.3  782.50  5917.3  785.65  5923.7  785.83  5938.0  791.08  5942.1  791.08
#Mann=4,-1,0
  3796.2    0.05       0  4998.2    0.04       0  5002.2    0.05       0
  5696.0    0.12       0
Bank Sta=4998.2,5002.2
Exp/Cntr=0.3,0.1

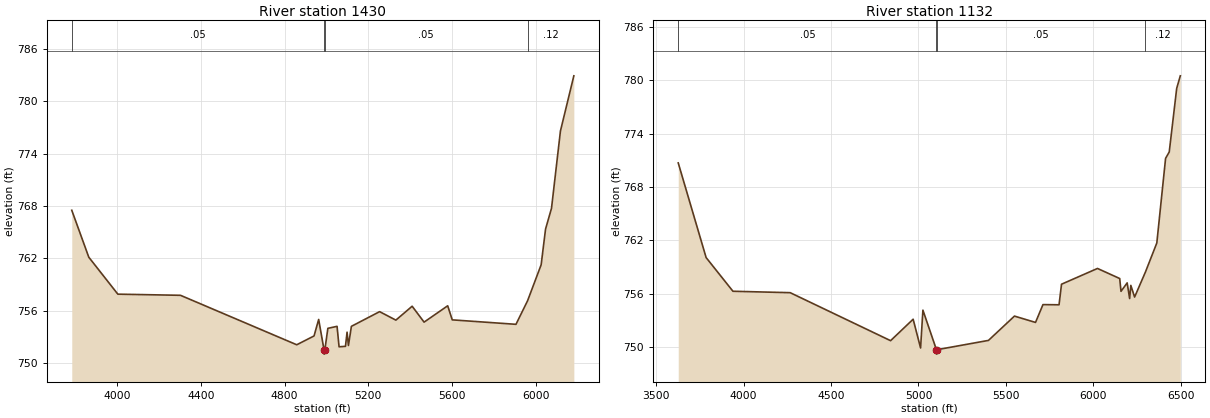
Type RM Length L Ch R = 1,1430,298,298,298
BEGIN DESCRIPTION:
Mapping XS 72876d88
END DESCRIPTION:
XS GIS Cut Line= 4
      2292653.99      7153956.15      2293602.59      7153404.32
      2293687.64      7153243.24      2292840.95      7152507.02
#Sta/Elev= 30
  3781.7  767.51  3863.1  762.14  4002.1  757.91  4301.7  757.78  4857.8  752.12
  4940.6  753.13  4962.7  755.02  4988.3  751.55  4988.6  751.05  4992.3  751.55
  5006.7  754.00  5050.7  754.23  5060.3  751.89  5090.9  751.94  5098.5  753.56
  5105.1  752.04  5119.3  754.23  5254.2  755.91  5332.0  754.94  5409.9  756.53
  5466.9  754.71  5579.9  756.58  5601.7  754.97  5906.5  754.46  5961.9  757.15
  6026.9  761.27  6048.0  765.36  6076.5  767.74  6119.2  776.58  6183.3  782.89
#Mann=4,-1,0
  3781.7    0.05       0  4988.3    0.04       0  4992.3    0.05       0
  5961.9    0.12       0
Bank Sta=4988.3,4992.3
Exp/Cntr=0.3,0.1

Type RM Length L Ch R = 1,1132,0,0,0
BEGIN DESCRIPTION:
Mapping XS 3b91049e
END DESCRIPTION:
XS GIS Cut Line= 4
      2292636.87      7154040.17      2293831.31      7153609.04
      2293902.40      7153410.63      2292868.42      7152481.39
#Sta/Elev= 30
  3626.4  770.71  3785.9  760.08  3939.2  756.30  4266.5  756.14  4840.6  750.75
  4969.6  753.16  5012.1  749.93  5025.4  754.18  5102.7  749.74  5102.9  749.24
  5106.7  749.74  5400.2  750.78  5548.9  753.51  5669.3  752.80  5711.9  754.80
  5803.8  754.78  5818.0  757.09  6023.6  758.86  6150.6  757.73  6158.1  756.29
  6193.3  757.24  6207.5  755.48  6214.2  756.96  6235.9  755.65  6297.8  758.46
  6362.9  761.72  6413.0  771.22  6433.9  771.94  6476.5  779.08  6497.2  780.49
#Mann=4,-1,0
  3626.4    0.05       0  5102.7    0.04       0  5106.7    0.05       0
  6297.8    0.12       0
Bank Sta=5102.7,5106.7
Exp/Cntr=0.3,0.1

Chan Stop Cuts=-1