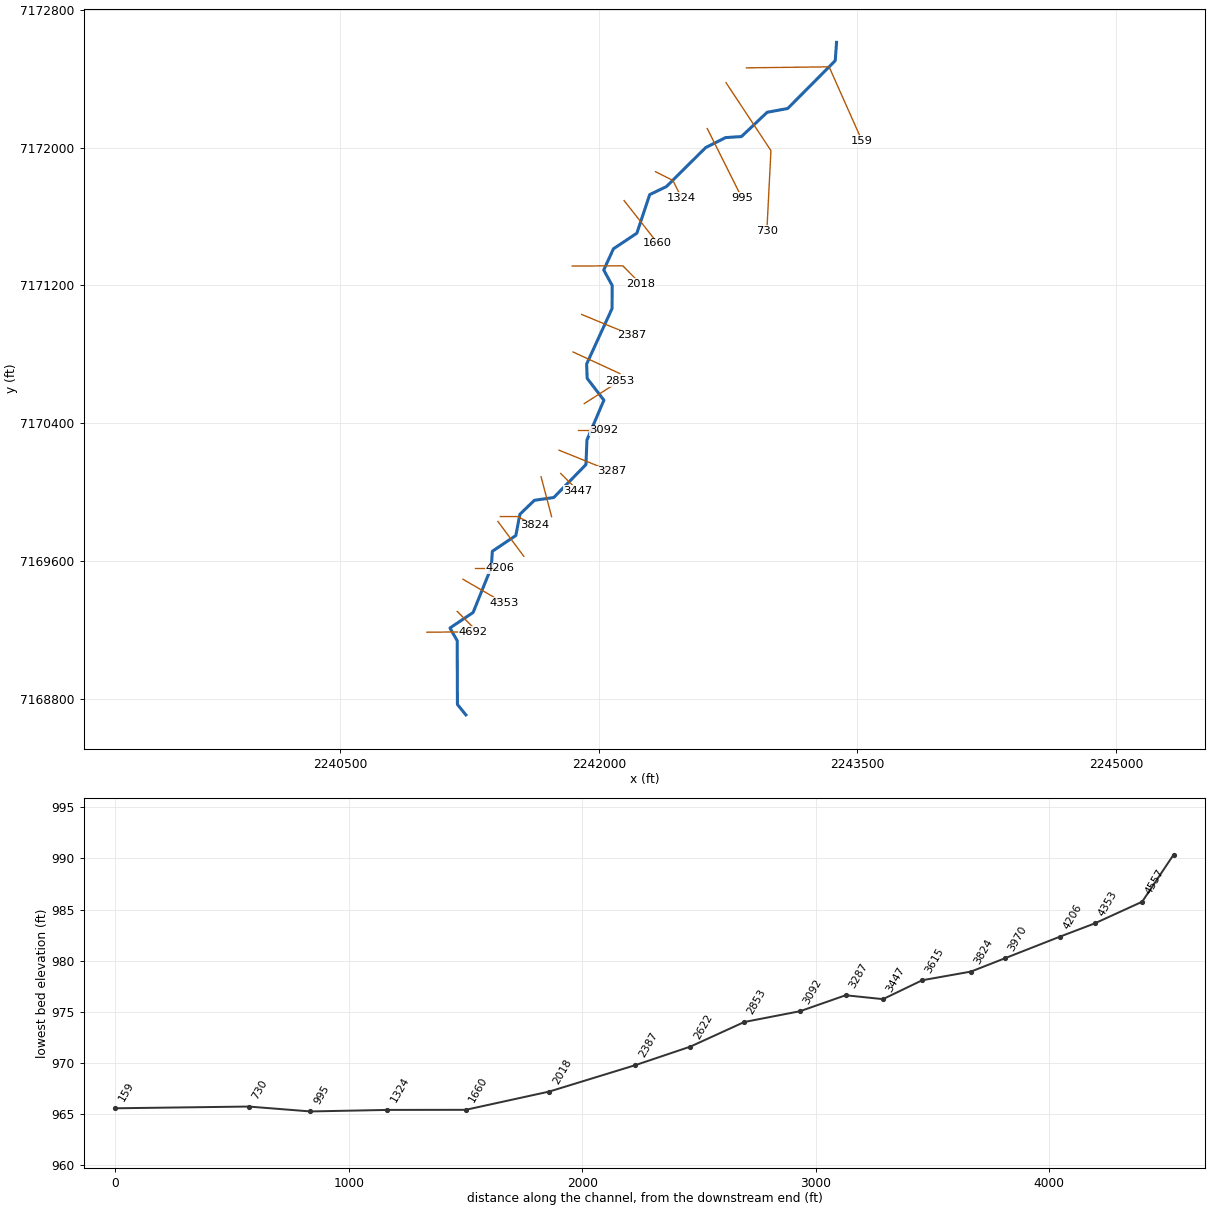
--- MDE S 01.prj (project) ---

Proj Title=MDE S 01 Base Level Engineering
Current Plan=p01
Default Exp/Contr=0.3,0.1
English Units
Geom File=g01
Flow File=f01
Plan File=p01
BEGIN DESCRIPTION:
MDE S 01
END DESCRIPTION:

--- MDE S 01.p01 (plan) ---

Plan Title=Multiple Run
Short Identifier=Multiple
Geom File=g01
Flow File=f01
Subcritical Flow
K Sum by GR= 0
Std Step Tol= 0.01
Critical Tol= 0.01
Num of Std Step Trials= 20
Max Error Tol= 0.3
Flow Tol Ratio= 0.001
Split Flow NTrial= 30
Split Flow Tol= 0.02
Split Flow Ratio= 0.02
Log Output Level= 0
Friction Slope Method= 1
Unsteady Friction Slope Method= 2
Unsteady Bridges Friction Slope Method= 1
Parabolic Critical Depth
Global Vel Dist=  1 , 1 , 1
Global Log Level= 0
CheckData=True
Encroach Param= -1, 0, 0, 0
BEGIN DESCRIPTION:
Multiple Run
END DESCRIPTION:

--- MDE S 01.f01 (steady flow) ---

Flow Title=Multiple
Number of Profiles=7
Profile Names=10-year,25-year,50-year,1pct_min,100-year,1pct_plu,500-year
River Rch & RM= MDE S 01,Reach-1,4692
     725    1012    1253     770    1537    3066    2319
River Rch & RM= MDE S 01,Reach-1,159
     728    1015    1257     772    1541    3074    2322
Boundary for River Rch & Prof#=MDE S 01,Reach-1,1
Up Type=0
Dn Type=3
Dn Slope=0.005
Boundary for River Rch & Prof#=MDE S 01,Reach-1,2
Up Type=0
Dn Type=3
Dn Slope=0.005
Boundary for River Rch & Prof#=MDE S 01,Reach-1,3
Up Type=0
Dn Type=3
Dn Slope=0.005
Boundary for River Rch & Prof#=MDE S 01,Reach-1,4
Up Type=0
Dn Type=3
Dn Slope=0.005
Boundary for River Rch & Prof#=MDE S 01,Reach-1,5
Up Type=0
Dn Type=3
Dn Slope=0.005
Boundary for River Rch & Prof#=MDE S 01,Reach-1,6
Up Type=0
Dn Type=3
Dn Slope=0.005
Boundary for River Rch & Prof#=MDE S 01,Reach-1,7
Up Type=0
Dn Type=3
Dn Slope=0.005

--- MDE S 01.g01 (geometry) ---

Geom Title=Existing Conditions

River Reach=MDE S 01,Reach-1
Reach XY= 30
      2241229.00      7168710.00      2241179.96      7168770.40
      2241178.81      7169140.02      2241136.69      7169213.67
      2241270.97      7169303.66      2241376.64      7169565.98
      2241382.52      7169658.72      2241518.61      7169749.90
      2241542.39      7169873.33      2241626.56      7169954.48
      2241738.79      7169970.52      2241925.46      7170161.47
      2241931.27      7170304.06      2242029.49      7170535.04
      2241932.47      7170661.50      2241929.36      7170744.73
      2242076.75      7171065.94      2242077.77      7171199.50
      2242028.70      7171289.83      2242084.73      7171412.55
      2242220.98      7171503.66      2242295.30      7171727.13
      2242392.20      7171773.64      2242619.32      7171999.24
      2242734.97      7172057.67      2242827.50      7172063.61
      2242976.57      7172204.48      2243095.75      7172226.46
      2243371.26      7172503.78      2243379.00      7172610.00

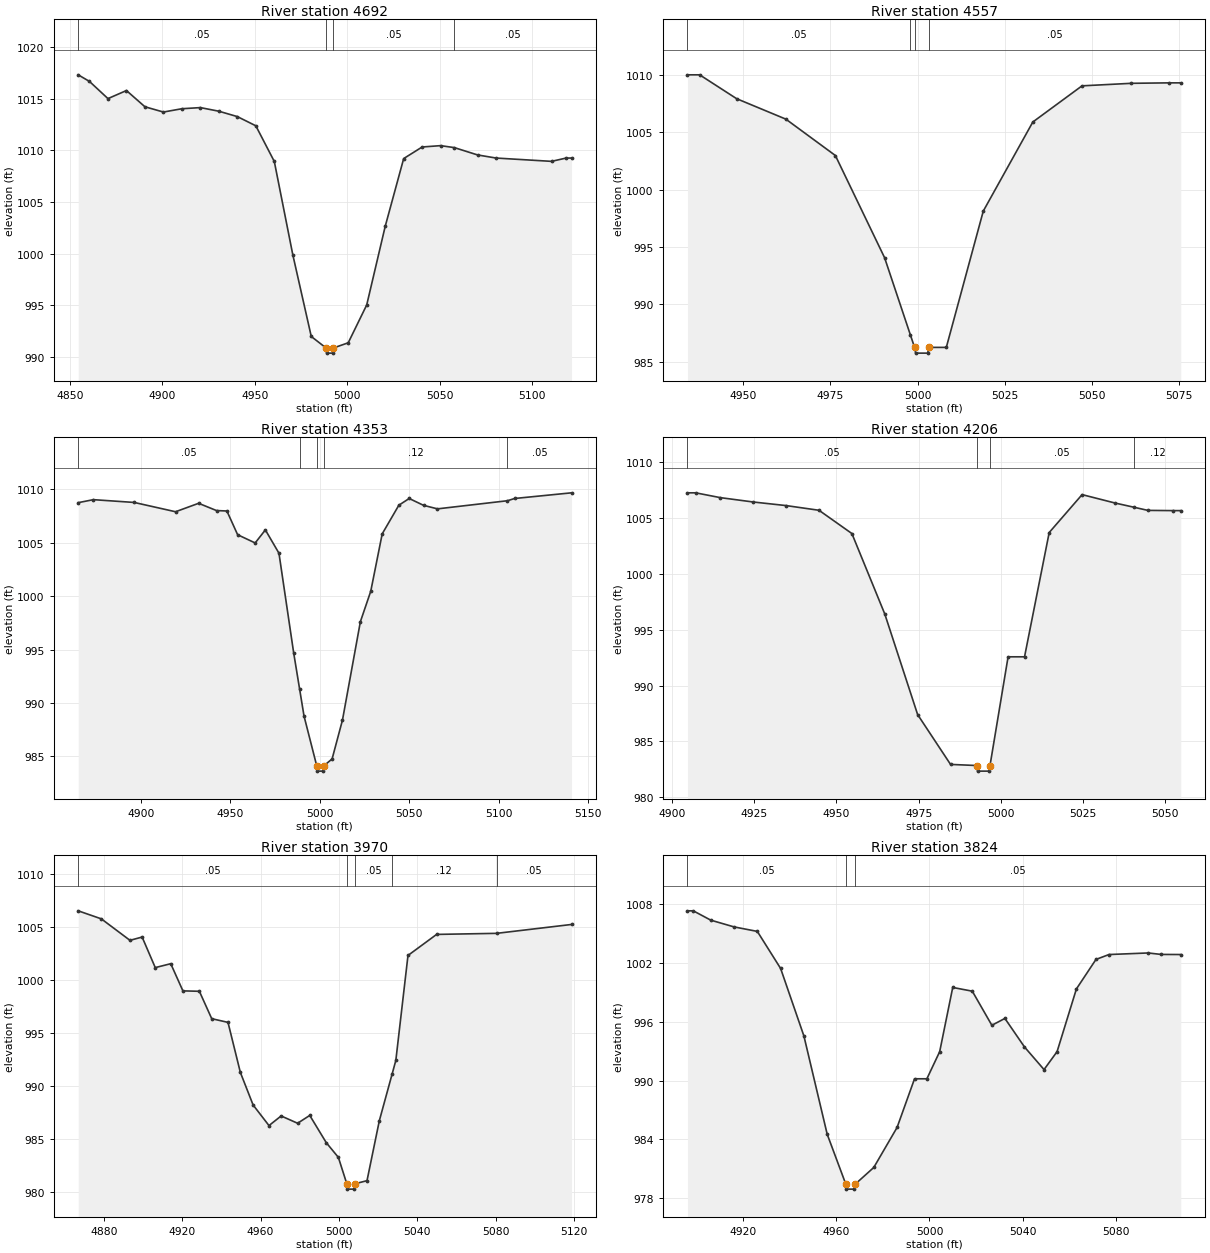
Type RM Length L Ch R = 1,4692,135,135,135
BEGIN DESCRIPTION:
Mapping XS 4c90675a
END DESCRIPTION:
XS GIS Cut Line= 2
      2241002.88      7169189.37      2241269.77      7169191.64
#Sta/Elev= 30
  4854.5 1017.30  4860.6 1016.66  4870.6 1015.00  4880.6 1015.78  4890.6 1014.21
  4900.6 1013.70  4910.6 1014.02  4920.6 1014.13  4930.6 1013.78  4940.6 1013.26
  4950.6 1012.37  4960.6 1008.92  4970.6  999.90  4980.6  991.99  4988.6  990.88
  4988.9  990.38  4992.4  990.38  4992.6  990.88  5000.6  991.38  5010.6  995.04
  5020.6 1002.64  5030.6 1009.20  5040.6 1010.32  5050.6 1010.45  5058.0 1010.26
  5070.6 1009.55  5080.6 1009.25  5110.6 1008.93  5118.5 1009.25  5121.4 1009.25
#Mann=4,-1,0
  4854.5    0.05       0  4988.6    0.07       0  4992.6    0.05       0
  5058.0    0.05       0
Bank Sta=4988.6,4992.6
Exp/Cntr=0.3,0.1

Type RM Length L Ch R = 1,4557,204,204,204
BEGIN DESCRIPTION:
MDE S 01 12.0
END DESCRIPTION:
XS GIS Cut Line= 3
      2241179.02      7169309.98      2241229.00      7169260.00
      2241279.01      7169209.99
#Sta/Elev= 18
  4934.0 1010.01  4937.5 1010.01  4948.1 1007.93  4962.2 1006.15  4976.4 1002.98
  4990.5  994.08  4997.9  987.35  4999.1  986.26  4999.4  985.76  5002.9  985.76
  5003.1  986.26  5008.2  986.26  5018.8  998.14  5033.0 1005.90  5047.1 1009.05
  5061.2 1009.27  5071.9 1009.31  5075.4 1009.31
#Mann=4,-1,0
  4934.0    0.05       0  4997.9    0.12       0  4999.1    0.07       0
  5003.1    0.05       0
Bank Sta=4999.1,5003.1
Exp/Cntr=0.3,0.1

Type RM Length L Ch R = 1,4353,147,147,147
BEGIN DESCRIPTION:
Mapping XS 9672378c
END DESCRIPTION:
XS GIS Cut Line= 2
      2241211.90      7169496.50      2241450.56      7169358.47
#Sta/Elev= 30
  4865.1 1008.75  4873.6 1009.03  4896.4 1008.77  4919.5 1007.90  4932.4 1008.69
  4942.4 1008.01  4948.2 1007.97  4954.2 1005.75  4964.0 1004.98  4969.7 1006.20
  4977.3 1004.02  4985.5  994.72  4988.8  991.35  4991.3  988.79  4998.4  984.13
  4998.6  983.63  5002.1  983.63  5002.4  984.13  5007.0  984.77  5012.8  988.41
  5022.8  997.61  5028.6 1000.46  5035.0 1005.83  5044.3 1008.51  5050.1 1009.14
  5058.1 1008.50  5065.9 1008.17  5105.0 1008.93  5109.0 1009.14  5140.8 1009.67
#Mann=5,-1,0
  4865.1    0.05       0  4988.8    0.12       0  4998.4    0.07       0
  5002.4    0.12       0  5105.0    0.05       0
Bank Sta=4998.4,5002.4
Exp/Cntr=0.3,0.1

Type RM Length L Ch R = 1,4206,236,236,236
BEGIN DESCRIPTION:
MDE S 01 11.0
END DESCRIPTION:
XS GIS Cut Line= 3
      2241279.04      7169560.00      2241379.00      7169560.00
      2241429.04      7169560.00
#Sta/Elev= 23
  4904.7 1007.23  4907.2 1007.23  4914.7 1006.80  4924.7 1006.41  4934.7 1006.09
  4944.7 1005.67  4954.7 1003.59  4964.7  996.40  4974.7  987.40  4984.7  982.95
  4992.7  982.85  4992.9  982.35  4996.4  982.35  4996.7  982.85  5002.2  992.57
  5007.2  992.57  5014.7 1003.68  5024.7 1007.07  5034.7 1006.32  5040.5 1005.94
  5044.7 1005.66  5052.2 1005.64  5054.7 1005.64
#Mann=4,-1,0
  4904.7    0.05       0  4992.7   0.033       0  4996.7    0.05       0
  5040.5    0.12       0
Bank Sta=4992.7,4996.7
Exp/Cntr=0.3,0.1

Type RM Length L Ch R = 1,3970,146,146,146
BEGIN DESCRIPTION:
Mapping XS da9e18c6
END DESCRIPTION:
XS GIS Cut Line= 2
      2241414.84      7169831.55      2241564.93      7169629.62
#Sta/Elev= 30
  4867.0 1006.55  4878.8 1005.79  4893.4 1003.76  4899.6 1004.07  4906.3 1001.18
  4914.2 1001.55  4920.4  998.98  4928.8  998.94  4935.1  996.35  4943.4  996.00
  4949.7  991.27  4956.2  988.19  4964.3  986.24  4970.5  987.15  4978.9  986.46
  4985.1  987.20  4993.5  984.63  4999.7  983.23  5004.0  980.73  5004.2  980.23
  5007.7  980.23  5008.0  980.73  5014.3  981.03  5020.6  986.71  5027.1  991.11
  5029.0  992.40  5035.2 1002.33  5049.8 1004.32  5080.4 1004.42  5118.6 1005.26
#Mann=5,-1,0
  4867.0    0.05       0  5004.0   0.033       0  5008.0    0.05       0
  5027.1    0.12       0  5080.4    0.05       0
Bank Sta=5004,5008
Exp/Cntr=0.3,0.1

Type RM Length L Ch R = 1,3824,209,209,209
BEGIN DESCRIPTION:
MDE S 01 10.0
END DESCRIPTION:
XS GIS Cut Line= 3
      2241429.04      7169860.00      2241529.00      7169860.00
      2241629.03      7169809.99
#Sta/Elev= 30
  4896.1 1007.32  4898.6 1007.32  4906.1 1006.37  4916.1 1005.68  4926.1 1005.22
  4936.1 1001.44  4946.1  994.55  4956.1  984.52  4964.1  979.42  4964.3  978.92
  4967.8  978.92  4968.1  979.42  4976.1  981.13  4986.1  985.21  4993.6  990.18
  4998.9  990.18  5004.4  992.95  5010.0  999.50  5018.4  999.12  5026.8  995.64
  5032.4  996.34  5040.8  993.43  5049.2  991.12  5054.8  992.95  5063.1  999.35
  5071.5 1002.36  5077.1 1002.86  5093.9 1003.02  5099.5 1002.87  5107.9 1002.86
#Mann=3,-1,0
  4896.1    0.05       0  4964.1   0.033       0  4968.1    0.05       0
Bank Sta=4964.1,4968.1
Exp/Cntr=0.3,0.1

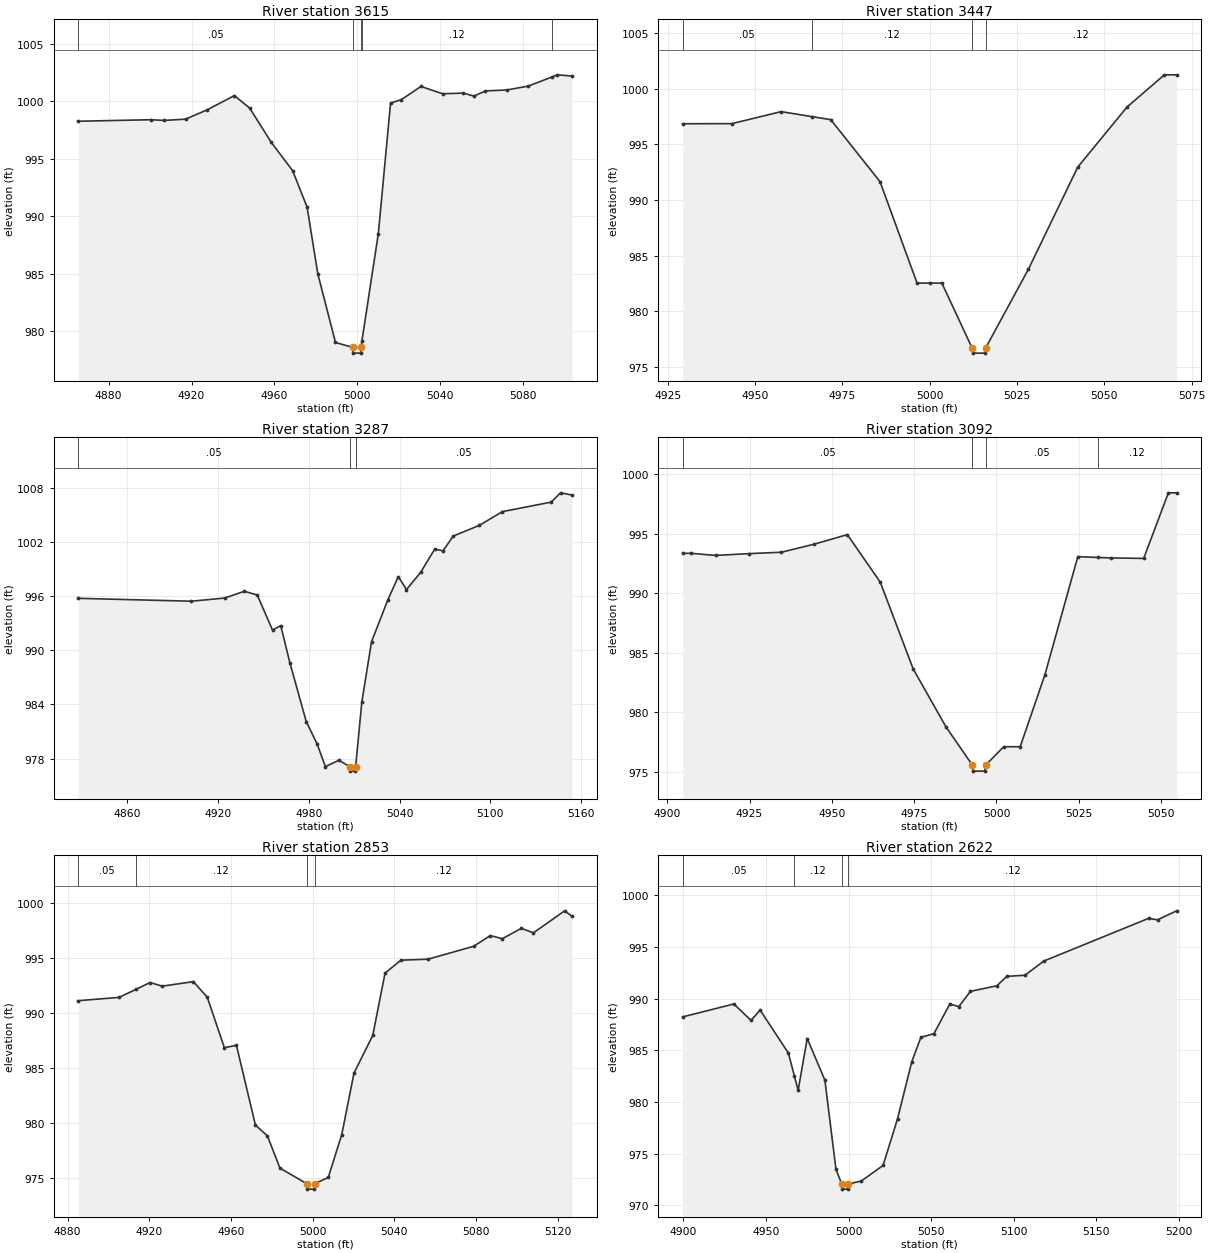
Type RM Length L Ch R = 1,3615,168,168,168
BEGIN DESCRIPTION:
Mapping XS c1854db6
END DESCRIPTION:
XS GIS Cut Line= 2
      2241665.39      7170090.09      2241726.15      7169859.46
#Sta/Elev= 30
  4865.3  998.26  4900.3  998.39  4906.8  998.33  4917.1  998.44  4927.4  999.24
  4940.7 1000.49  4948.1  999.40  4958.5  996.42  4968.8  993.96  4975.8  990.78
  4981.0  984.95  4989.5  979.00  4997.8  978.57  4998.1  978.07  5001.6  978.07
  5001.8  978.57  5002.3  979.16  5010.2  988.48  5016.1  999.84  5021.3 1000.14
  5030.8 1001.29  5041.2 1000.65  5051.2 1000.71  5056.4 1000.45  5061.9 1000.90
  5072.2 1000.98  5082.6 1001.32  5094.0 1002.11  5096.7 1002.30  5103.8 1002.19
#Mann=5,-1,0
  4865.3    0.05       0  4997.8    0.04       0  5001.8    0.05       0
  5002.3    0.12       0  5094.0    0.05       0
Bank Sta=4997.8,5001.8
Exp/Cntr=0.3,0.1

Type RM Length L Ch R = 1,3447,160,160,160
BEGIN DESCRIPTION:
MDE S 01 9.0
END DESCRIPTION:
XS GIS Cut Line= 3
      2241779.02      7170109.98      2241829.00      7170060.00
      2241879.01      7170009.99
#Sta/Elev= 18
  4929.3  996.85  4943.4  996.86  4957.5  997.94  4966.3  997.49  4971.7  997.22
  4985.8  991.64  4996.4  982.52  5000.0  982.52  5003.5  982.52  5012.1  976.72
  5012.4  976.22  5015.9  976.22  5016.1  976.72  5028.3  983.78  5042.4  992.95
  5056.5  998.35  5067.2 1001.25  5070.7 1001.25
#Mann=4,-1,0
  4929.3    0.05       0  4966.3    0.12       0  5012.1    0.07       0
  5016.1    0.12       0
Bank Sta=5012.1,5016.1
Exp/Cntr=0.3,0.1

Type RM Length L Ch R = 1,3287,195,195,195
BEGIN DESCRIPTION:
MAPPING XS B896D
END DESCRIPTION:
XS GIS Cut Line= 2
      2241769.36      7170245.00      2242071.85      7170122.37
#Sta/Elev= 30
  4827.7  995.78  4902.5  995.46  4924.4  995.81  4937.4  996.56  4946.0  996.15
  4956.1  992.25  4961.5  992.75  4967.6  988.59  4978.4  982.08  4985.6  979.60
  4991.0  977.10  5000.0  977.81  5007.0  977.10  5007.3  976.60  5010.8  976.60
  5011.0  977.10  5015.1  984.28  5021.5  990.96  5032.3  995.62  5039.2  998.19
  5044.6  996.75  5053.9  998.65  5063.3 1001.25  5068.7 1001.05  5075.5 1002.69
  5092.8 1003.88  5107.9 1005.40  5140.2 1006.46  5146.4 1007.49  5154.1 1007.24
#Mann=3,-1,0
  4827.7    0.05       0  5007.0    0.04       0  5011.0    0.05       0
Bank Sta=5007,5011
Exp/Cntr=0.3,0.1

Type RM Length L Ch R = 1,3092,239,239,239
BEGIN DESCRIPTION:
MDE S 01 8.0
END DESCRIPTION:
XS GIS Cut Line= 3
      2241879.05      7170360.00      2241979.00      7170360.00
      2242029.05      7170360.00
#Sta/Elev= 23
  4904.7  993.34  4907.2  993.34  4914.7  993.16  4924.7  993.31  4934.7  993.43
  4944.7  994.11  4954.7  994.91  4964.7  990.92  4974.7  983.63  4984.7  978.74
  4992.7  975.54  4992.9  975.04  4996.4  975.04  4996.7  975.54  5002.2  977.09
  5007.2  977.09  5014.7  983.13  5024.7  993.06  5030.8  992.99  5034.7  992.95
  5044.7  992.91  5052.2  998.42  5054.7  998.42
#Mann=4,-1,0
  4904.7    0.05       0  4992.7    0.04       0  4996.7    0.05       0
  5030.8    0.12       0
Bank Sta=4992.7,4996.7
Exp/Cntr=0.3,0.1

Type RM Length L Ch R = 1,2853,231,231,231
BEGIN DESCRIPTION:
Mapping XS 94a2651d
END DESCRIPTION:
XS GIS Cut Line= 2
      2241915.72      7170515.17      2242119.71      7170645.37
#Sta/Elev= 30
  4885.2  991.09  4905.2  991.39  4913.4  992.11  4920.4  992.74  4926.3  992.41
  4941.6  992.82  4948.4  991.41  4956.8  986.82  4962.7  987.04  4972.0  979.80
  4977.9  978.81  4984.0  975.89  4997.1  974.48  4997.3  973.98  5000.8  973.98
  5001.1  974.48  5007.7  975.04  5014.3  978.93  5020.3  984.52  5029.5  987.94
  5035.5  993.59  5043.3  994.77  5056.6  994.86  5078.9  996.03  5087.1  997.00
  5093.0  996.72  5102.3  997.66  5108.2  997.25  5123.5  999.25  5127.2  998.74
#Mann=4,-1,0
  4885.2    0.05       0  4913.4    0.12       0  4997.1    0.07       0
  5001.1    0.12       0
Bank Sta=4997.1,5001.1
Exp/Cntr=0.3,0.1

Type RM Length L Ch R = 1,2622,235,235,235
BEGIN DESCRIPTION:
Mapping XS 6760eb7f
END DESCRIPTION:
XS GIS Cut Line= 2
      2241850.84      7170814.39      2242122.38      7170689.22
#Sta/Elev= 30
  4899.6  988.23  4930.6  989.48  4941.0  987.89  4946.5  988.89  4963.6  984.73
  4967.3  982.47  4969.5  981.13  4975.0  986.14  4985.7  982.11  4992.4  973.48
  4995.9  972.07  4996.2  971.57  4999.7  971.57  4999.9  972.07  5007.7  972.35
  5020.9  973.86  5029.7  978.39  5038.3  983.90  5043.8  986.25  5051.7  986.61
  5061.3  989.47  5066.8  989.23  5073.8  990.70  5089.8  991.24  5095.8  992.15
  5106.8  992.26  5118.2  993.63  5181.6  997.76  5187.1  997.62  5198.6  998.49
#Mann=4,-1,0
  4899.6    0.05       0  4967.3    0.12       0  4995.9    0.07       0
  4999.9    0.12       0
Bank Sta=4995.9,4999.9
Exp/Cntr=0.3,0.1

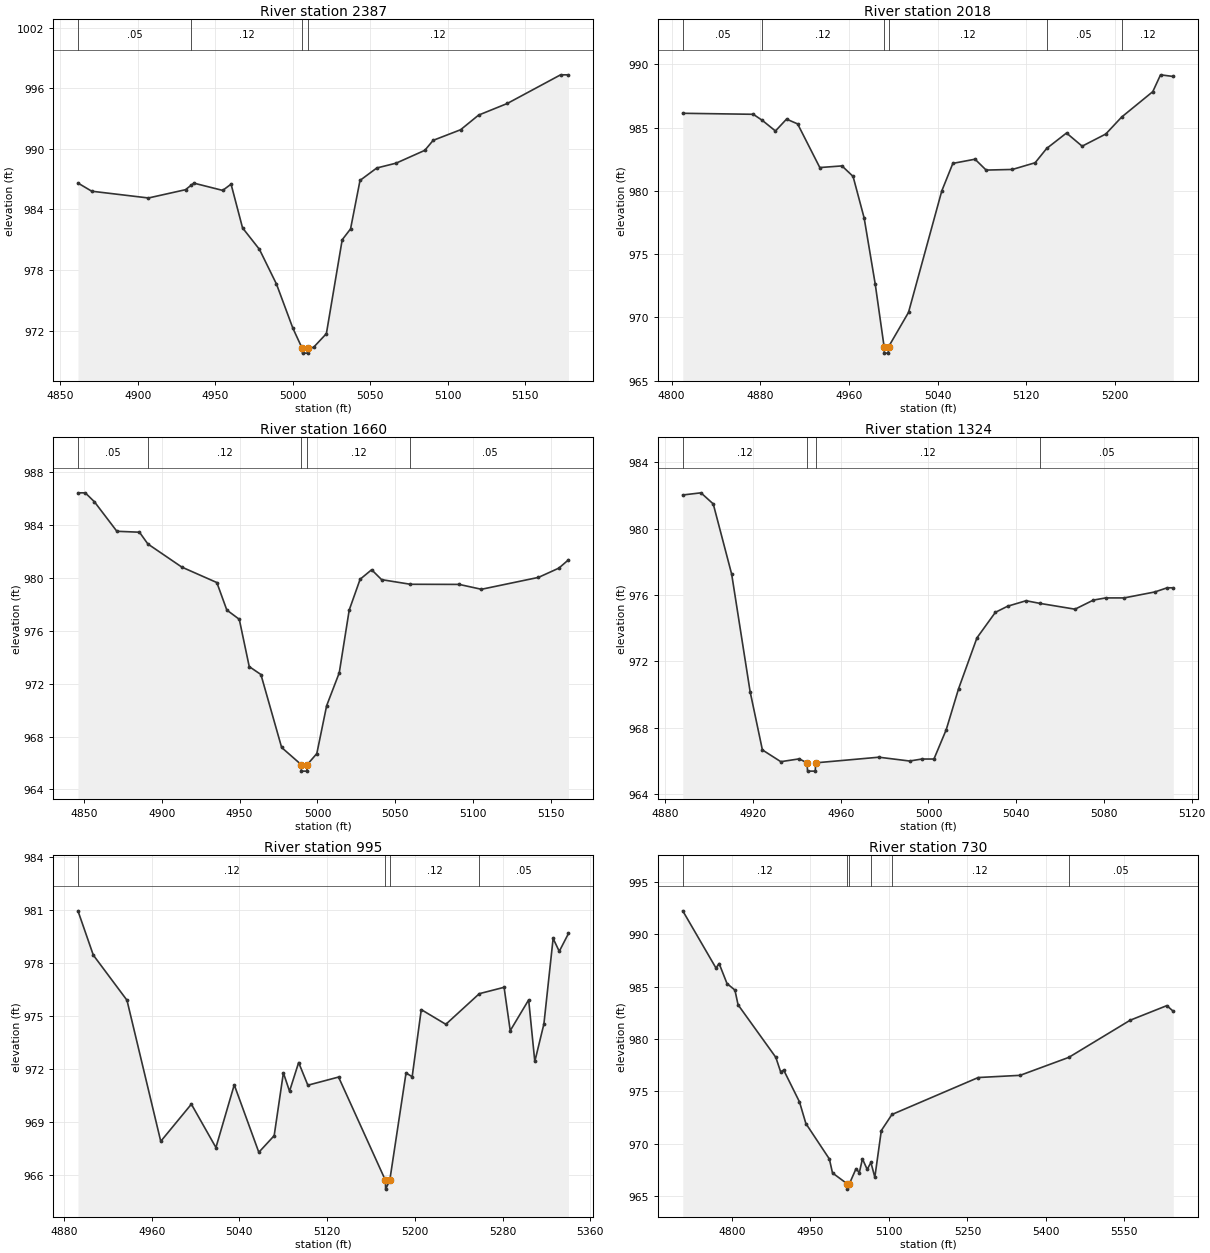
Type RM Length L Ch R = 1,2387,369,369,369
BEGIN DESCRIPTION:
Mapping XS 3bc9dcff
END DESCRIPTION:
XS GIS Cut Line= 2
      2241900.79      7171031.89      2242193.36      7170911.14
#Sta/Elev= 30
  4861.4  986.61  4870.3  985.80  4906.9  985.13  4930.8  985.95  4934.5  986.40
  4936.2  986.60  4954.8  985.88  4960.2  986.50  4967.6  982.17  4978.5  980.04
  4989.5  976.60  5000.1  972.22  5006.0  970.26  5006.3  969.76  5009.8  969.76
  5010.0  970.26  5013.4  970.33  5021.7  971.69  5031.9  980.99  5037.3  982.07
  5043.4  986.87  5054.2  988.10  5066.7  988.58  5085.2  989.85  5090.6  990.84
  5108.3  991.89  5119.9  993.34  5138.4  994.49  5172.8  997.33  5177.9  997.33
#Mann=4,-1,0
  4861.4    0.05       0  4934.5    0.12       0  5006.0    0.07       0
  5010.0    0.12       0
Bank Sta=5006,5010
Exp/Cntr=0.3,0.1

Type RM Length L Ch R = 1,2018,358,358,358
BEGIN DESCRIPTION:
Mapping XS b67b6d03
END DESCRIPTION:
XS GIS Cut Line= 3
      2241845.40      7171312.98      2242139.36      7171314.08
      2242243.72      7171208.52
#Sta/Elev= 30
  4810.1  986.13  4873.7  986.05  4882.0  985.56  4893.7  984.73  4903.7  985.67
  4913.7  985.29  4933.7  981.84  4953.7  981.97  4963.7  981.14  4973.7  977.85
  4983.7  972.62  4991.7  967.67  4991.9  967.17  4995.4  967.17  4995.7  967.67
  5013.7  970.39  5043.7  979.99  5053.7  982.17  5073.7  982.50  5083.7  981.64
  5107.4  981.69  5127.9  982.22  5138.3  983.35  5156.2  984.57  5170.3  983.53
  5191.6  984.49  5205.9  985.83  5234.0  987.84  5241.0  989.17  5252.5  989.04
#Mann=6,-1,0
  4810.1    0.05       0  4882.0    0.12       0  4991.7    0.07       0
  4995.7    0.12       0  5138.3    0.05       0  5205.9    0.12       0
Bank Sta=4991.7,4995.7
Exp/Cntr=0.3,0.1

Type RM Length L Ch R = 1,1660,336,336,336
BEGIN DESCRIPTION:
Mapping XS 7a027883
END DESCRIPTION:
XS GIS Cut Line= 2
      2242146.68      7171692.37      2242341.50      7171444.84
#Sta/Elev= 30
  4846.2  986.44  4850.9  986.44  4856.8  985.76  4871.2  983.53  4885.7  983.46
  4891.1  982.57  4912.9  980.82  4935.4  979.65  4941.8  977.57  4949.8  976.87
  4956.2  973.29  4963.7  972.69  4977.0  967.17  4989.5  965.88  4989.7  965.38
  4993.2  965.38  4993.5  965.88  4999.6  966.71  5005.9  970.33  5014.0  972.82
  5020.4  977.57  5027.4  979.90  5034.8  980.62  5041.2  979.87  5059.7  979.52
  5091.0  979.51  5105.3  979.14  5141.9  980.04  5155.0  980.74  5161.2  981.37
#Mann=5,-1,0
  4846.2    0.05       0  4891.1    0.12       0  4989.5    0.07       0
  4993.5    0.12       0  5059.7    0.05       0
Bank Sta=4989.5,4993.5
Exp/Cntr=0.3,0.1

Type RM Length L Ch R = 1,1324,329,329,329
BEGIN DESCRIPTION:
MDE S 01 3.0
END DESCRIPTION:
XS GIS Cut Line= 3
      2242329.04      7171859.98      2242429.00      7171810.00
      2242479.02      7171709.96
#Sta/Elev= 30
  4888.0  982.03  4896.3  982.16  4901.9  981.49  4910.3  977.25  4918.7  970.17
  4924.3  966.65  4932.7  965.94  4941.1  966.11  4944.6  965.87  4944.9  965.37
  4948.4  965.37  4948.6  965.87  4977.4  966.21  4991.4  965.98  4997.0  966.10
  5002.5  966.10  5008.1  967.87  5013.7  970.33  5022.1  973.41  5030.5  974.95
  5036.1  975.32  5044.5  975.65  5050.8  975.49  5066.8  975.14  5075.2  975.69
  5080.8  975.82  5089.2  975.82  5103.2  976.18  5108.8  976.43  5111.6  976.43
#Mann=4,-1,0
  4888.0    0.12       0  4944.6    0.07       0  4948.6    0.12       0
  5050.8    0.05       0
Bank Sta=4944.6,4948.6
Exp/Cntr=0.3,0.1

Type RM Length L Ch R = 1,995,265,265,265
BEGIN DESCRIPTION:
MDE S 01 2.0
END DESCRIPTION:
XS GIS Cut Line= 3
      2242629.00      7172110.00      2242679.00      7172010.00
      2242829.00      7171710.01
#Sta/Elev= 30
  4892.8  980.94  4906.8  978.44  4937.5  975.89  4968.3  967.92  4996.2  970.02
  5018.6  967.57  5035.3  971.11  5057.7  967.30  5071.7  968.24  5080.1  971.79
  5085.7  970.75  5094.0  972.37  5102.4  971.09  5130.4  971.55  5173.1  965.72
  5173.3  965.22  5177.1  965.72  5191.9  971.78  5197.5  971.57  5205.8  975.36
  5228.2  974.53  5258.7  976.26  5281.3  976.62  5286.9  974.17  5303.7  975.91
  5309.3  972.43  5317.6  974.55  5326.0  979.38  5331.6  978.65  5340.0  979.66
#Mann=4,-1,0
  4892.8    0.12       0  5173.1    0.07       0  5177.1    0.12       0
  5258.7    0.05       0
Bank Sta=5173.1,5177.1
Exp/Cntr=0.3,0.1

Type RM Length L Ch R = 1,730,571,571,571
BEGIN DESCRIPTION:
Mapping XS 696c4084
END DESCRIPTION:
XS GIS Cut Line= 3
      2242737.82      7172376.28      2242998.42      7171982.00
      2242974.78      7171517.72
#Sta/Elev= 30
  4705.9  992.21  4769.4  986.76  4775.4  987.19  4790.5  985.28  4805.6  984.66
  4811.6  983.26  4883.8  978.25  4892.9  976.88  4898.8  977.04  4929.0  974.01
  4941.2  971.95  4986.1  968.57  4992.1  967.24  5020.3  966.20  5020.5  965.70
  5024.3  966.20  5037.1  967.65  5043.3  967.26  5049.3  968.58  5058.4  967.58
  5065.5  968.24  5073.0  966.83  5085.4  971.28  5105.7  972.81  5270.6  976.33
  5350.7  976.54  5443.7  978.25  5561.0  981.79  5631.1  983.18  5643.4  982.64
#Mann=6,-1,0
  4705.9    0.12       0  5020.3    0.07       0  5024.3    0.12       0
  5065.5    0.05       0  5105.7    0.12       0  5443.7    0.05       0
Bank Sta=5020.3,5024.3
Exp/Cntr=0.3,0.1

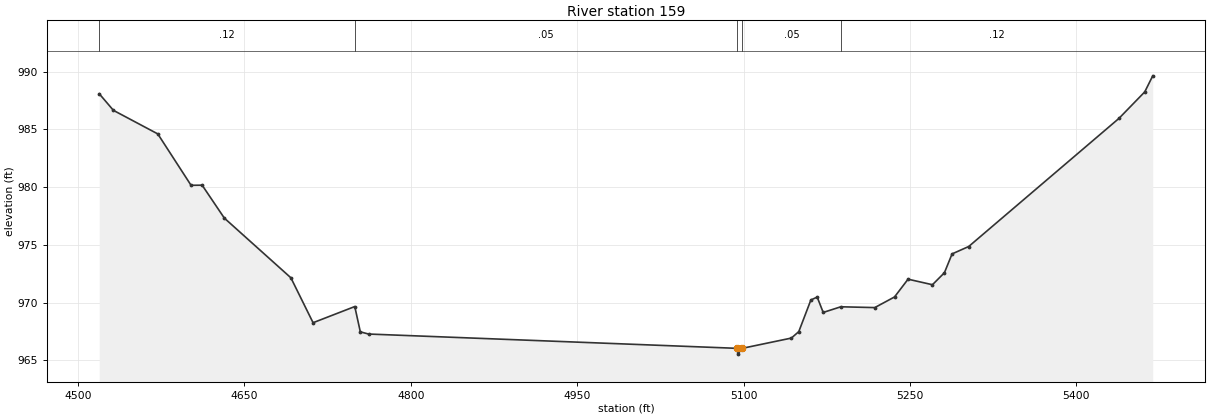
Type RM Length L Ch R = 1,159,0,0,0
BEGIN DESCRIPTION:
MDE S 01 1.0
END DESCRIPTION:
XS GIS Cut Line= 3
      2242856.17      7172462.18      2243335.80      7172467.99
      2243526.96      7172038.47
#Sta/Elev= 30
  4519.1  988.08  4531.9  986.64  4571.9  984.60  4601.9  980.15  4611.9  980.16
  4631.9  977.31  4691.9  972.14  4711.9  968.25  4749.5  969.65  4754.5  967.46
  4761.9  967.27  5094.5  966.03  5094.8  965.53  5098.7  966.03  5143.1  966.92
  5149.8  967.48  5160.7  970.22  5166.4  970.47  5171.8  969.14  5187.7  969.63
  5218.3  969.56  5236.1  970.48  5248.3  972.02  5270.3  971.54  5281.1  972.58
  5288.0  974.21  5303.0  974.85  5438.4  985.94  5461.7  988.24  5468.9  989.63
#Mann=5,-1,0
  4519.1    0.12       0  4749.5    0.05       0  5094.5   0.033       0
  5098.7    0.05       0  5187.7    0.12       0
Bank Sta=5094.5,5098.7
Exp/Cntr=0.3,0.1

Chan Stop Cuts=-1