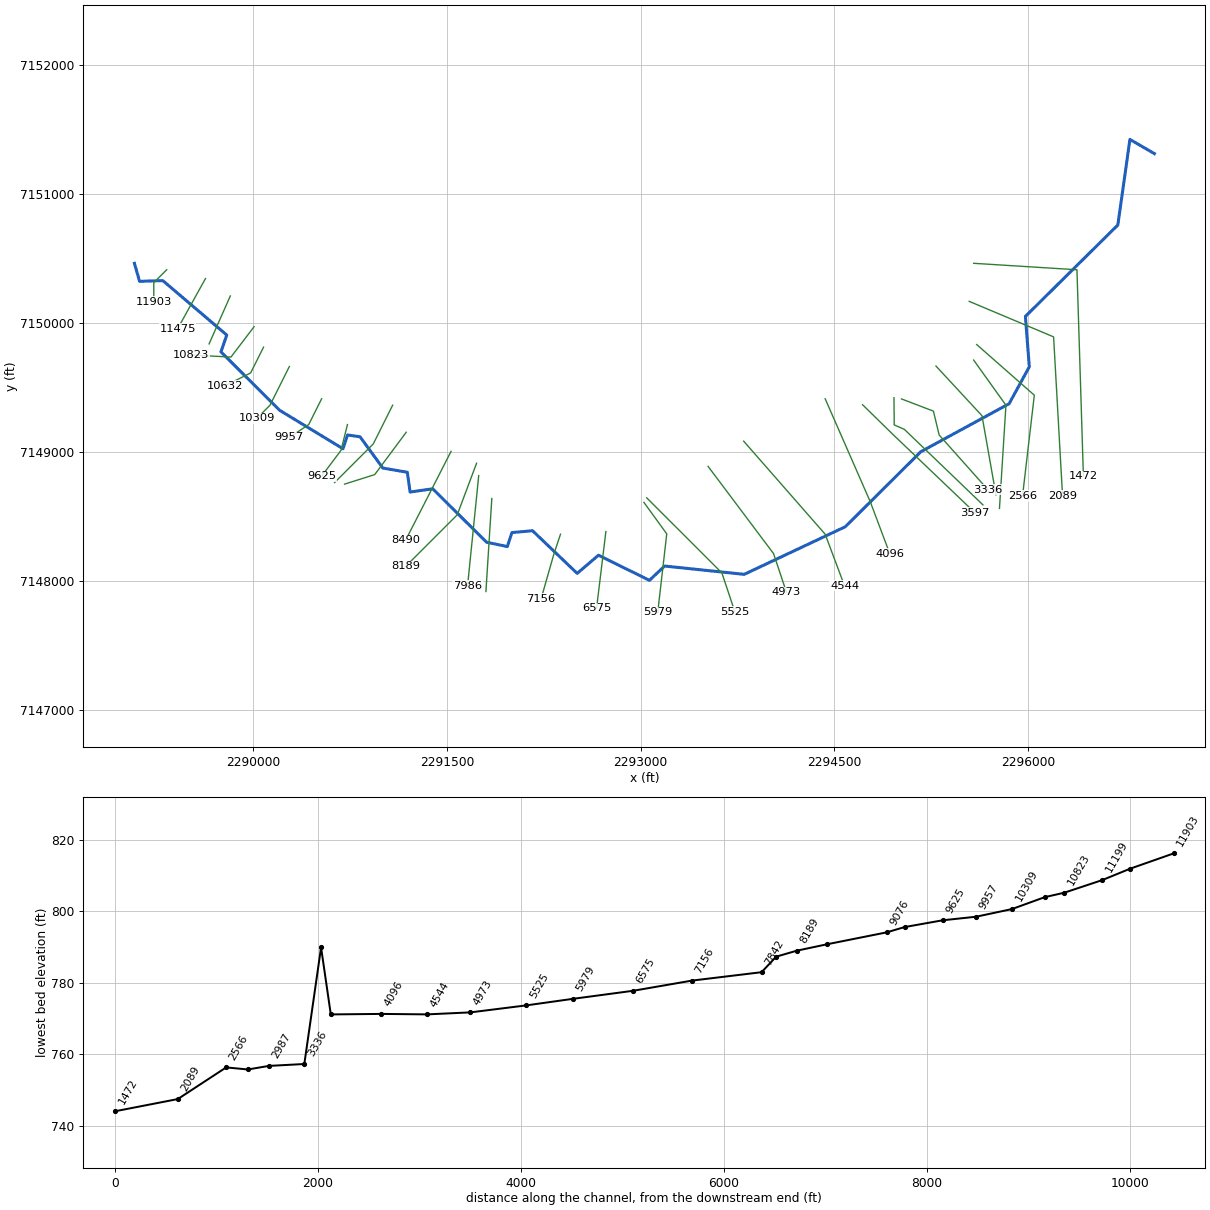
--- MDE S 010.prj (project) ---

Proj Title=MDE S 010 Base Level Engineering
Current Plan=p01
Default Exp/Contr=0.3,0.1
English Units
Geom File=g01
Flow File=f01
Plan File=p01
BEGIN DESCRIPTION:
MDE S 010
END DESCRIPTION:

--- MDE S 010.p01 (plan) ---

Plan Title=Multiple Run
Short Identifier=Multiple
Geom File=g01
Flow File=f01
Subcritical Flow
K Sum by GR= 0
Std Step Tol= 0.01
Critical Tol= 0.01
Num of Std Step Trials= 20
Max Error Tol= 0.3
Flow Tol Ratio= 0.001
Split Flow NTrial= 30
Split Flow Tol= 0.02
Split Flow Ratio= 0.02
Log Output Level= 0
Friction Slope Method= 1
Unsteady Friction Slope Method= 2
Unsteady Bridges Friction Slope Method= 1
Parabolic Critical Depth
Global Vel Dist=  1 , 1 , 1
Global Log Level= 0
CheckData=True
Encroach Param= -1, 0, 0, 0
BEGIN DESCRIPTION:
Multiple Run
END DESCRIPTION:

--- MDE S 010.f01 (steady flow) ---

Flow Title=Multiple
Number of Profiles=7
Profile Names=10-year,25-year,50-year,1pct_min,100-year,1pct_plu,500-year
River Rch & RM= MDE S 010,Reach-1,11903
     703     976    1204     738    1473    2939    2208
River Rch & RM= MDE S 010,Reach-1,8490
    1231    1757    2208    1376    2745    5478    4255
Boundary for River Rch & Prof#=MDE S 010,Reach-1,1
Up Type=0
Dn Type=3
Dn Slope=0.005
Boundary for River Rch & Prof#=MDE S 010,Reach-1,2
Up Type=0
Dn Type=3
Dn Slope=0.005
Boundary for River Rch & Prof#=MDE S 010,Reach-1,3
Up Type=0
Dn Type=3
Dn Slope=0.005
Boundary for River Rch & Prof#=MDE S 010,Reach-1,4
Up Type=0
Dn Type=3
Dn Slope=0.005
Boundary for River Rch & Prof#=MDE S 010,Reach-1,5
Up Type=0
Dn Type=3
Dn Slope=0.005
Boundary for River Rch & Prof#=MDE S 010,Reach-1,6
Up Type=0
Dn Type=3
Dn Slope=0.005
Boundary for River Rch & Prof#=MDE S 010,Reach-1,7
Up Type=0
Dn Type=3
Dn Slope=0.005

--- MDE S 010.g01 (geometry) ---

Geom Title=Existing Conditions

River Reach=MDE S 010,Reach-1
Reach XY= 30
      2289079.00      7150460.00      2289118.83      7150320.30
      2289299.12      7150325.82      2289794.21      7149903.94
      2289749.22      7149773.46      2290203.68      7149320.79
      2290694.59      7149022.55      2290729.73      7149129.61
      2290826.63      7149115.04      2291002.98      7148873.01
      2291192.66      7148840.29      2291214.38      7148687.16
      2291389.24      7148712.24      2291806.55      7148298.08
      2291967.16      7148264.37      2292002.87      7148372.85
      2292162.40      7148387.18      2292508.25      7148056.41
      2292673.03      7148197.29      2293067.96      7148002.70
      2293185.56      7148113.43      2293801.78      7148049.00
      2294585.06      7148418.14      2295169.32      7148999.24
      2295853.64      7149371.75      2296009.99      7149657.75
      2295979.82      7150048.34      2296695.78      7150756.92
      2296789.20      7151420.43      2296979.00      7151310.00

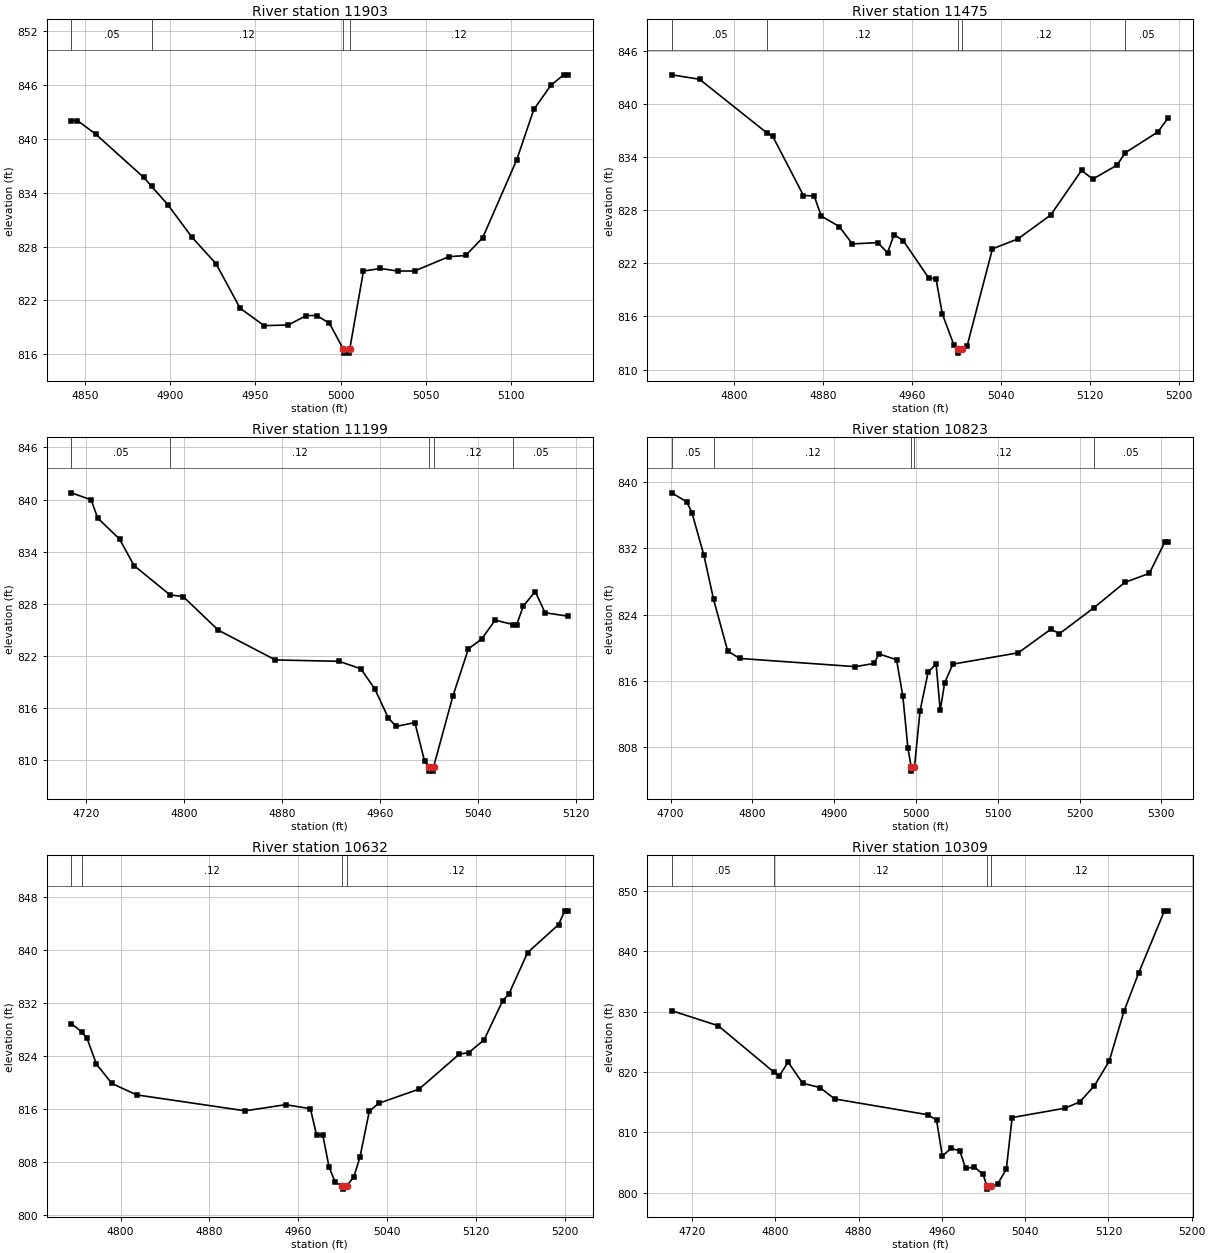
Type RM Length L Ch R = 1,11903,428,428,428
BEGIN DESCRIPTION:
MDE S 010 23.0
END DESCRIPTION:
XS GIS Cut Line= 3
      2289329.01      7150410.01      2289229.00      7150310.00
      2289229.00      7150160.03
#Sta/Elev= 30
  4842.0  842.03  4845.5  842.03  4856.1  840.54  4884.4  835.70  4889.1  834.69
  4898.6  832.65  4912.7  829.04  4926.9  826.07  4941.0  821.12  4955.1  819.18
  4969.3  819.26  4979.9  820.31  4985.9  820.31  4993.4  819.46  5001.4  816.62
  5001.7  816.12  5005.2  816.12  5005.4  816.62  5013.4  825.27  5023.4  825.55
  5033.4  825.27  5043.4  825.27  5063.4  826.86  5073.4  827.00  5083.4  828.98
  5103.4  837.68  5113.4  843.27  5123.4  845.95  5130.9  847.13  5133.4  847.13
#Mann=4,-1,0
  4842.0    0.05       0  4889.1    0.12       0  5001.4    0.07       0
  5005.4    0.12       0
Bank Sta=5001.4,5005.4
Exp/Cntr=0.3,0.1

Type RM Length L Ch R = 1,11475,276,276,276
BEGIN DESCRIPTION:
Mapping XS d00e2193
END DESCRIPTION:
XS GIS Cut Line= 2
      2289629.52      7150341.82      2289413.32      7149952.07
#Sta/Elev= 30
  4744.3  843.27  4769.3  842.77  4829.8  836.71  4835.1  836.31  4862.6  829.65
  4872.2  829.60  4878.6  827.33  4894.7  826.15  4906.5  824.19  4929.4  824.33
  4938.1  823.18  4943.9  825.23  4952.2  824.56  4975.1  820.33  4981.6  820.25
  4987.3  816.28  4997.7  812.77  5001.4  812.36  5001.6  811.86  5005.4  812.36
  5009.4  812.61  5032.3  823.63  5055.1  824.75  5084.6  827.45  5112.3  832.48
  5122.4  831.50  5144.1  833.07  5151.5  834.47  5180.9  836.83  5190.0  838.40
#Mann=5,-1,0
  4744.3    0.05       0  4829.8    0.12       0  5001.4    0.07       0
  5005.4    0.12       0  5151.5    0.05       0
Bank Sta=5001.4,5005.4
Exp/Cntr=0.3,0.1

Type RM Length L Ch R = 1,11199,376,376,376
BEGIN DESCRIPTION:
Mapping XS 639958e1
END DESCRIPTION:
XS GIS Cut Line= 2
      2289821.69      7150206.84      2289657.55      7149835.61
#Sta/Elev= 30
  4707.8  840.77  4723.8  839.96  4729.3  837.85  4747.1  835.43  4759.0  832.37
  4788.4  828.99  4799.1  828.80  4827.9  824.92  4874.5  821.49  4926.6  821.33
  4944.4  820.47  4955.8  818.15  4966.8  814.81  4973.2  813.82  4988.6  814.26
  4996.5  809.81  4999.9  809.16  5000.2  808.66  5003.7  808.66  5003.9  809.16
  5019.8  817.38  5032.4  822.78  5043.1  823.88  5054.2  826.08  5069.0  825.57
  5071.8  825.55  5077.3  827.71  5087.0  829.38  5095.1  826.93  5113.7  826.54
#Mann=5,-1,0
  4707.8    0.05       0  4788.4    0.12       0  4999.9    0.07       0
  5003.9    0.12       0  5069.0    0.05       0
Bank Sta=4999.9,5003.9
Exp/Cntr=0.3,0.1

Type RM Length L Ch R = 1,10823,191,191,191
BEGIN DESCRIPTION:
Mapping XS 74508072
END DESCRIPTION:
XS GIS Cut Line= 3
      2290005.99      7149968.74      2289826.78      7149733.35
      2289516.14      7149749.42
#Sta/Elev= 30
  4701.4  838.68  4719.9  837.58  4726.2  836.26  4740.8  831.14  4752.6  825.83
  4769.8  819.62  4784.4  818.71  4926.0  817.72  4948.6  818.10  4954.9  819.25
  4976.3  818.55  4984.0  814.16  4990.2  807.92  4994.2  805.62  4994.5  805.12
  4998.2  805.62  5005.0  812.36  5015.0  817.10  5024.7  818.00  5029.7  812.46
  5035.1  815.76  5045.1  818.02  5125.2  819.39  5165.2  822.25  5175.3  821.68
  5218.0  824.85  5255.4  827.88  5285.4  828.97  5304.4  832.77  5308.3  832.77
#Mann=5,-1,0
  4701.4    0.05       0  4752.6    0.12       0  4994.2    0.07       0
  4998.2    0.12       0  5218.0    0.05       0
Bank Sta=4994.2,4998.2
Exp/Cntr=0.3,0.1

Type RM Length L Ch R = 1,10632,323,323,323
BEGIN DESCRIPTION:
MDE S 010 20.0
END DESCRIPTION:
XS GIS Cut Line= 3
      2290079.00      7149810.00      2289979.00      7149610.00
      2289779.01      7149510.01
#Sta/Elev= 30
  4755.7  828.89  4764.9  827.68  4769.7  826.69  4778.1  822.82  4792.0  819.87
  4814.4  818.14  4912.2  815.73  4948.6  816.66  4970.9  816.05  4976.5  812.07
  4982.1  812.07  4987.7  807.27  4993.3  804.91  4999.7  804.39  4999.9  803.89
  5003.7  804.39  5010.1  805.76  5015.6  808.74  5024.0  815.67  5032.4  816.86
  5068.8  819.01  5105.1  824.30  5113.5  824.52  5127.4  826.45  5144.2  832.39
  5149.8  833.41  5166.6  839.65  5194.5  843.89  5200.1  845.97  5202.9  845.97
#Mann=4,-1,0
  4755.7    0.05       0  4764.9    0.12       0  4999.7    0.07       0
  5003.7    0.12       0
Bank Sta=4999.7,5003.7
Exp/Cntr=0.3,0.1

Type RM Length L Ch R = 1,10309,352,352,352
BEGIN DESCRIPTION:
MDE S 010 19.0
END DESCRIPTION:
XS GIS Cut Line= 3
      2290279.00      7149660.00      2290129.00      7149360.00
      2290029.02      7149260.02
#Sta/Elev= 30
  4700.5  830.14  4745.2  827.64  4798.8  819.94  4803.9  819.34  4812.3  821.62
  4826.3  818.11  4843.0  817.39  4857.0  815.51  4946.5  812.89  4954.9  812.01
  4960.4  806.04  4968.8  807.30  4977.2  806.92  4982.8  804.00  4991.2  804.21
  4999.6  803.02  5003.2  801.06  5003.4  800.56  5007.2  801.06  5013.5  801.40
  5021.9  803.85  5027.5  812.42  5078.3  813.98  5092.5  815.02  5106.6  817.72
  5120.8  821.81  5134.9  830.03  5149.0  836.38  5173.8  846.69  5177.3  846.69
#Mann=4,-1,0
  4700.5    0.05       0  4798.8    0.12       0  5003.2    0.07       0
  5007.2    0.12       0
Bank Sta=5003.2,5007.2
Exp/Cntr=0.3,0.1

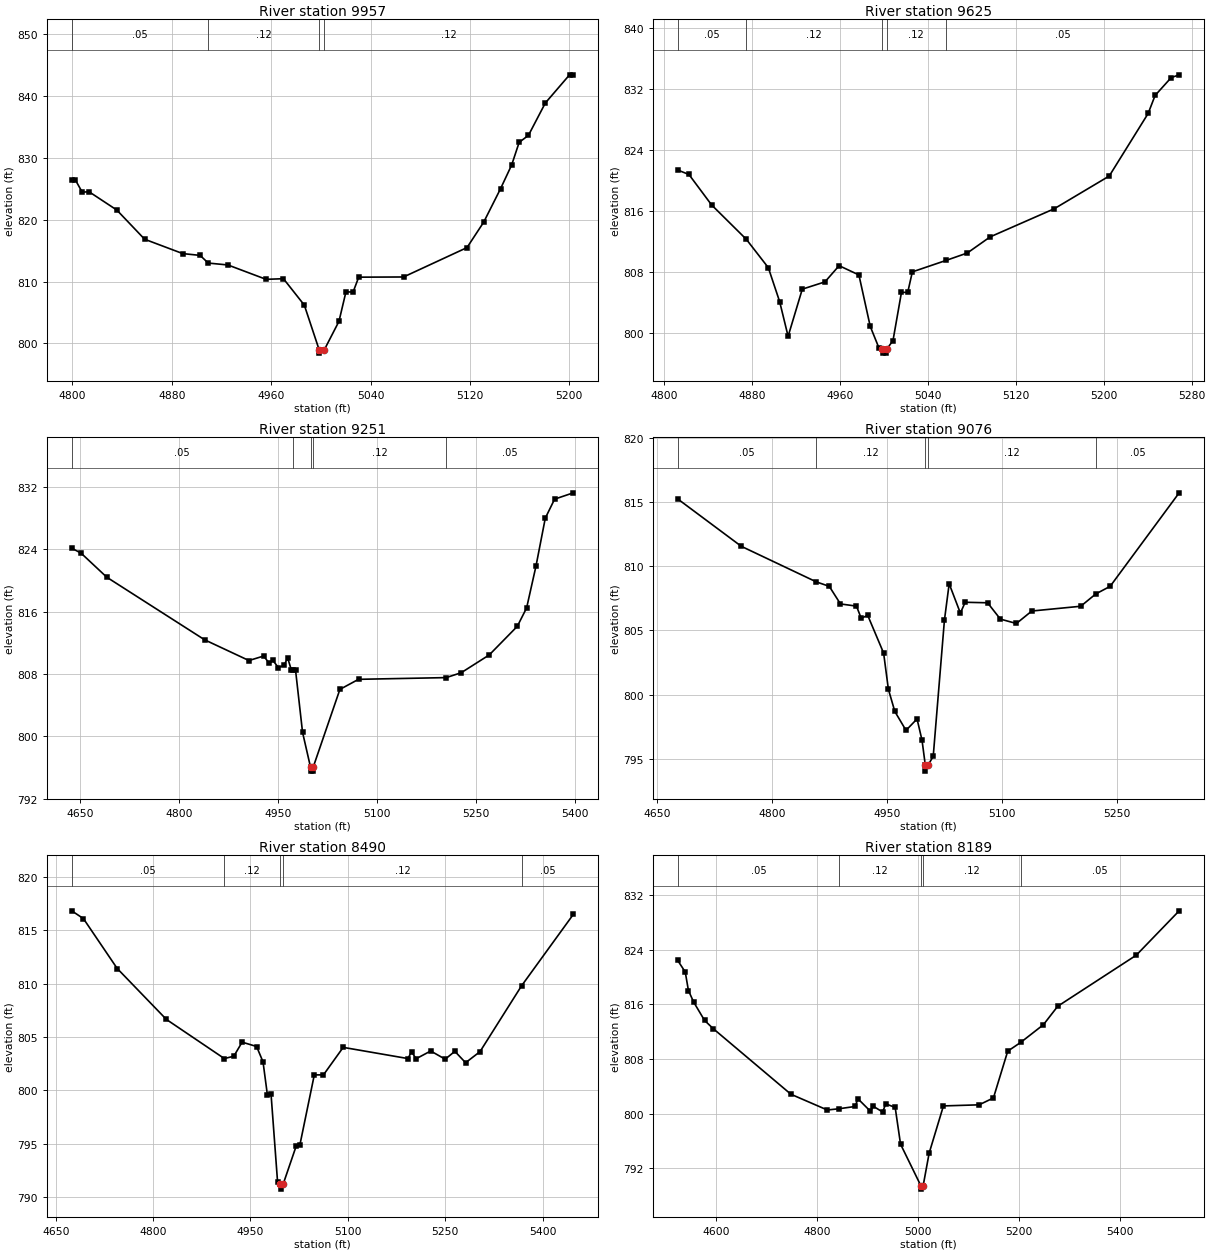
Type RM Length L Ch R = 1,9957,332,332,332
BEGIN DESCRIPTION:
MDE S 010 18.0
END DESCRIPTION:
XS GIS Cut Line= 3
      2290529.00      7149410.01      2290429.00      7149210.00
      2290278.99      7149110.00
#Sta/Elev= 30
  4799.4  826.47  4802.2  826.47  4807.8  824.46  4813.4  824.51  4835.7  821.56
  4858.1  816.84  4888.8  814.52  4902.8  814.23  4909.3  812.99  4925.2  812.68
  4955.9  810.36  4969.9  810.46  4986.7  806.19  4998.7  798.93  4998.9  798.43
  5002.7  798.93  5014.6  803.57  5020.2  808.32  5026.0  808.32  5030.5  810.71
  5066.6  810.74  5117.7  815.49  5131.2  819.62  5144.7  825.00  5153.7  828.86
  5159.7  832.50  5167.2  833.64  5180.8  838.87  5200.3  843.42  5203.3  843.42
#Mann=4,-1,0
  4799.4    0.05       0  4909.3    0.12       0  4998.7    0.07       0
  5002.7    0.12       0
Bank Sta=4998.7,5002.7
Exp/Cntr=0.3,0.1

Type RM Length L Ch R = 1,9625,374,374,374
BEGIN DESCRIPTION:
MDE S 010 17.0
END DESCRIPTION:
XS GIS Cut Line= 3
      2290729.00      7149210.01      2290679.00      7149010.00
      2290528.98      7148809.98
#Sta/Elev= 30
  4812.4  821.38  4822.7  820.79  4843.3  816.81  4874.9  812.31  4894.9  808.60
  4905.2  804.16  4912.9  799.62  4925.8  805.79  4946.4  806.74  4959.3  808.86
  4977.3  807.65  4987.6  800.92  4995.4  798.14  4998.5  797.92  4998.8  797.42
  5002.3  797.42  5002.5  797.92  5008.3  799.06  5016.0  805.37  5021.7  805.37
  5025.9  808.05  5056.6  809.55  5075.9  810.52  5096.7  812.63  5155.0  816.31
  5205.0  820.59  5240.4  828.78  5246.7  831.13  5261.3  833.46  5268.6  833.83
#Mann=5,-1,0
  4812.4    0.05       0  4874.9    0.12       0  4998.5    0.07       0
  5002.5    0.12       0  5056.6    0.05       0
Bank Sta=4998.5,5002.5
Exp/Cntr=0.3,0.1

Type RM Length L Ch R = 1,9251,175,175,175
BEGIN DESCRIPTION:
MDE S 010 16.0
END DESCRIPTION:
XS GIS Cut Line= 3
      2291079.02      7149360.04      2290929.00      7149060.00
      2290629.01      7148760.01
#Sta/Elev= 30
  4637.9  824.13  4651.9  823.51  4691.0  820.41  4839.2  812.38  4906.3  809.72
  4928.6  810.30  4937.0  809.37  4942.6  809.73  4951.0  808.81  4959.4  809.11
  4965.0  810.05  4970.6  808.49  4972.8  808.49  4976.9  808.49  4987.5  800.51
  4999.6  796.03  4999.9  795.53  5003.4  795.53  5003.6  796.03  5044.1  806.02
  5072.3  807.31  5205.1  807.53  5227.9  808.16  5270.3  810.44  5312.8  814.11
  5326.9  816.47  5341.0  821.80  5355.2  827.99  5369.3  830.43  5397.6  831.24
#Mann=5,-1,0
  4637.9    0.05       0  4972.8    0.12       0  4999.6    0.07       0
  5003.6    0.12       0  5205.1    0.05       0
Bank Sta=4999.6,5003.6
Exp/Cntr=0.3,0.1

Type RM Length L Ch R = 1,9076,586,586,586
BEGIN DESCRIPTION:
Mapping XS 957ae44f
END DESCRIPTION:
XS GIS Cut Line= 3
      2291184.32      7149150.64      2290940.14      7148822.18
      2290706.61      7148748.37
#Sta/Elev= 30
  4677.3  815.23  4760.4  811.54  4858.4  808.77  4875.1  808.43  4889.7  807.06
  4910.6  806.89  4916.8  805.94  4925.2  806.18  4946.0  803.24  4952.2  800.43
  4960.6  798.70  4975.2  797.23  4989.6  798.12  4996.1  796.46  5000.3  794.56
  5000.6  794.06  5004.3  794.56  5010.7  795.21  5025.3  805.79  5031.5  808.63
  5046.1  806.35  5052.4  807.19  5081.6  807.15  5098.3  805.88  5119.2  805.54
  5139.3  806.51  5203.1  806.88  5222.8  807.84  5241.5  808.43  5331.5  815.70
#Mann=5,-1,0
  4677.3    0.05       0  4858.4    0.12       0  5000.3    0.07       0
  5004.3    0.12       0  5222.8    0.05       0
Bank Sta=5000.3,5004.3
Exp/Cntr=0.3,0.1

Type RM Length L Ch R = 1,8490,301,301,301
BEGIN DESCRIPTION:
Mapping XS d676e96e
END DESCRIPTION:
XS GIS Cut Line= 3
      2291531.46      7149002.48      2291356.25      7148658.98
      2291179.91      7148314.38
#Sta/Elev= 30
  4674.7  816.83  4692.7  816.10  4744.8  811.42  4820.5  806.65  4909.8  802.98
  4924.4  803.20  4937.2  804.52  4959.5  804.11  4969.4  802.67  4976.1  799.59
  4981.7  799.69  4991.8  791.42  4996.0  791.24  4996.5  790.74  5000.6  791.24
  5020.5  794.78  5026.2  794.89  5048.4  801.45  5062.5  801.45  5092.9  804.03
  5192.6  802.98  5198.3  803.62  5205.2  802.96  5227.7  803.69  5250.1  802.92
  5264.9  803.66  5281.5  802.59  5303.7  803.63  5367.7  809.80  5447.4  816.49
#Mann=5,-1,0
  4674.7    0.05       0  4909.8    0.12       0  4996.0    0.07       0
  5000.6    0.12       0  5367.7    0.05       0
Bank Sta=4996,5000.6
Exp/Cntr=0.3,0.1

Type RM Length L Ch R = 1,8189,203,203,203
BEGIN DESCRIPTION:
MDE S 010 14.0
END DESCRIPTION:
XS GIS Cut Line= 3
      2291729.00      7148909.99      2291579.00      7148510.00
      2291178.98      7148109.98
#Sta/Elev= 30
  4523.8  822.45  4538.9  820.74  4545.2  818.02  4555.8  816.30  4577.2  813.64
  4594.1  812.45  4748.1  802.83  4820.2  800.52  4843.7  800.71  4875.3  801.04
  4880.7  802.17  4905.6  800.33  4910.9  801.08  4929.6  800.23  4935.9  801.42
  4954.5  800.90  4965.1  795.52  5005.3  789.43  5005.8  788.93  5009.9  789.43
  5021.7  794.19  5050.0  801.12  5120.7  801.28  5149.0  802.29  5177.3  809.14
  5203.1  810.43  5248.0  813.02  5276.3  815.72  5431.8  823.20  5516.7  829.70
#Mann=5,-1,0
  4523.8    0.05       0  4843.7    0.12       0  5005.3    0.07       0
  5009.9    0.12       0  5203.1    0.05       0
Bank Sta=5005.3,5009.9
Exp/Cntr=0.3,0.1

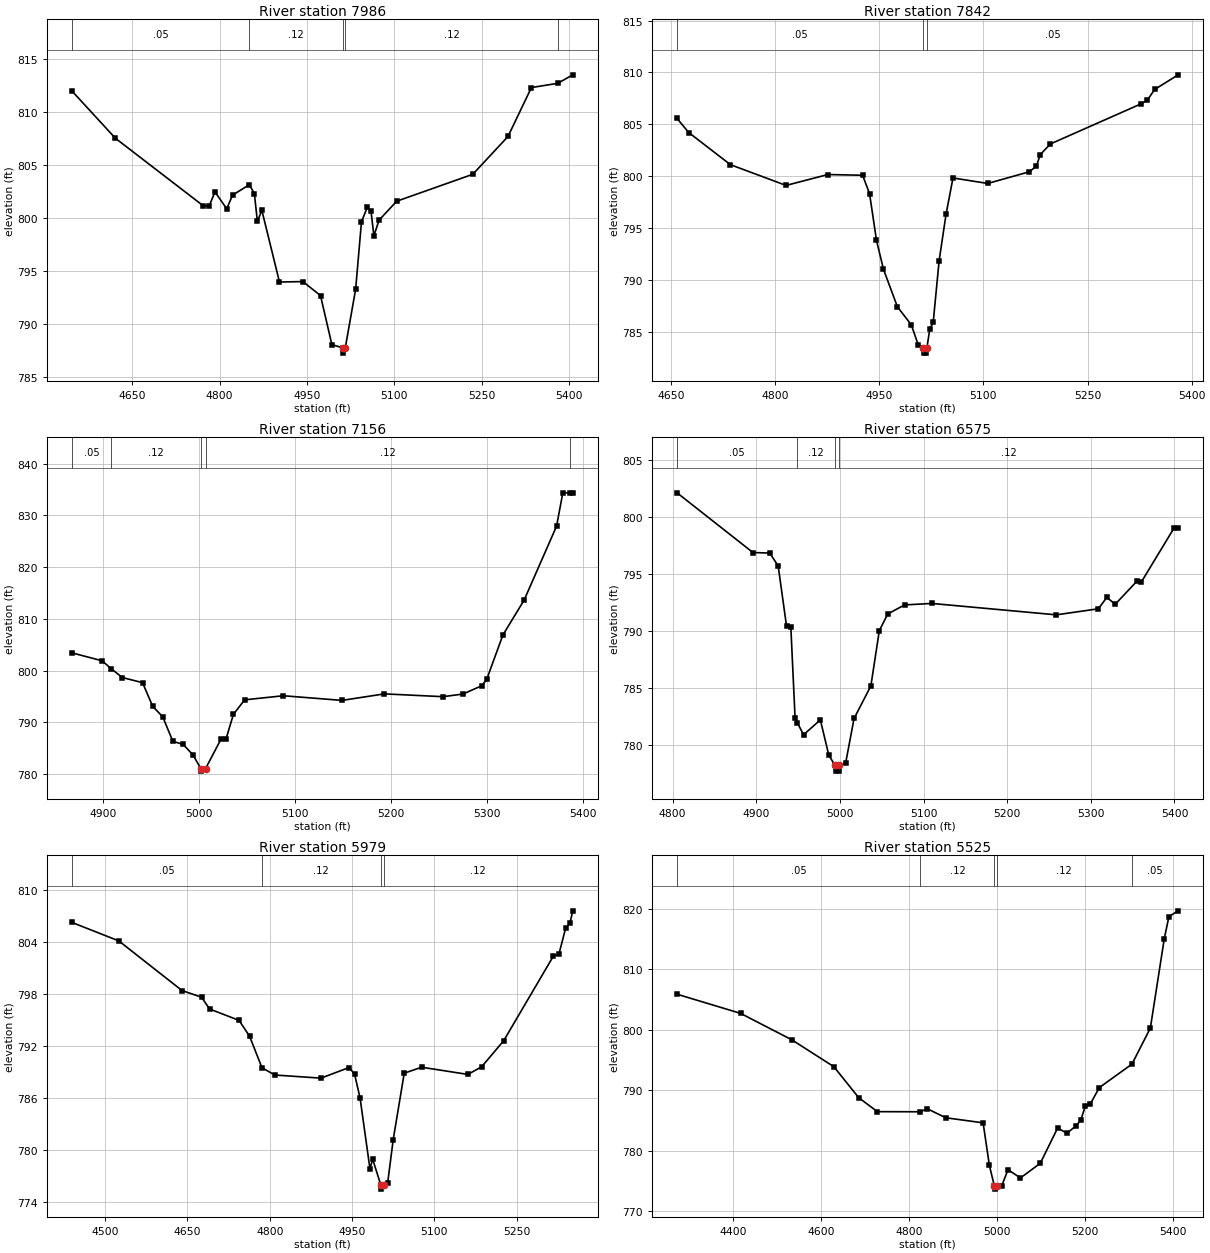
Type RM Length L Ch R = 1,7986,144,144,144
BEGIN DESCRIPTION:
Mapping XS 4f3759d4
END DESCRIPTION:
XS GIS Cut Line= 3
      2291745.71      7148814.60      2291700.43      7148366.05
      2291659.12      7147959.37
#Sta/Elev= 30
  4546.4  811.98  4621.4  807.50  4772.1  801.14  4782.2  801.12  4792.2  802.45
  4812.3  800.86  4822.4  802.15  4851.2  803.13  4859.8  802.28  4864.9  799.67
  4872.6  800.71  4902.8  793.96  4943.0  794.00  4973.2  792.68  4992.7  788.06
  5011.1  787.76  5011.5  787.26  5015.7  787.76  5033.5  793.29  5043.5  799.64
  5053.6  801.01  5059.7  800.69  5064.8  798.32  5073.7  799.79  5103.8  801.57
  5234.5  804.11  5294.8  807.67  5335.0  812.28  5380.2  812.68  5406.0  813.48
#Mann=5,-1,0
  4546.4    0.05       0  4851.2    0.12       0  5011.1    0.07       0
  5015.7    0.12       0  5380.2    0.05       0
Bank Sta=5011.1,5015.7
Exp/Cntr=0.3,0.1

Type RM Length L Ch R = 1,7842,686,686,686
BEGIN DESCRIPTION:
Mapping XS 6bb9ebf4
END DESCRIPTION:
XS GIS Cut Line= 2
      2291847.10      7148636.72      2291801.47      7147916.26
#Sta/Elev= 30
  4658.7  805.56  4675.5  804.20  4735.6  801.10  4815.7  799.10  4875.9  800.15
  4926.0  800.08  4936.0  798.31  4946.0  793.80  4956.0  791.02  4976.1  787.39
  4996.1  785.66  5006.1  783.72  5013.7  783.42  5014.3  782.92  5018.0  782.92
  5018.6  783.42  5022.7  785.21  5027.7  785.89  5036.2  791.82  5046.2  796.32
  5056.2  799.82  5106.3  799.29  5166.4  800.42  5176.5  800.97  5181.9  802.07
  5196.5  803.10  5326.8  806.96  5336.2  807.33  5346.8  808.36  5380.6  809.77
#Mann=3,-1,0
  4658.7    0.05       0  5013.7   0.033       0  5018.6    0.05       0
Bank Sta=5013.7,5018.6
Exp/Cntr=0.3,0.1

Type RM Length L Ch R = 1,7156,581,581,581
BEGIN DESCRIPTION:
MDE S 010 12.0
END DESCRIPTION:
XS GIS Cut Line= 3
      2292379.00      7148360.00      2292329.00      7148210.00
      2292229.01      7147860.02
#Sta/Elev= 30
  4867.3  803.44  4898.9  801.90  4908.3  800.39  4920.0  798.66  4941.1  797.67
  4951.6  793.12  4962.2  791.05  4972.7  786.31  4983.3  785.76  4993.8  783.67
  5001.8  781.07  5002.4  780.57  5006.8  781.07  5022.8  786.74  5028.0  786.74
  5035.8  791.55  5047.5  794.35  5087.8  795.14  5148.9  794.24  5193.1  795.50
  5254.2  794.96  5275.0  795.47  5294.5  797.07  5299.7  798.30  5316.6  806.89
  5338.7  813.63  5372.5  827.92  5379.0  834.36  5387.0  834.36  5389.4  834.36
#Mann=5,-1,0
  4867.3    0.05       0  4908.3    0.12       0  5001.8    0.07       0
  5006.8    0.12       0  5387.0    0.05       0
Bank Sta=5001.8,5006.8
Exp/Cntr=0.3,0.1

Type RM Length L Ch R = 1,6575,596,596,596
BEGIN DESCRIPTION:
Mapping XS 44dd13e6
END DESCRIPTION:
XS GIS Cut Line= 2
      2292730.37      7148380.06      2292658.20      7147785.32
#Sta/Elev= 30
  4805.3  802.15  4896.0  796.91  4916.2  796.86  4926.2  795.72  4936.2  790.43
  4941.3  790.39  4946.4  782.36  4949.1  781.97  4956.5  780.91  4976.6  782.22
  4986.7  779.12  4994.2  778.22  4994.9  777.72  4998.7  777.72  4999.3  778.22
  5006.8  778.41  5016.9  782.34  5037.0  785.20  5047.1  790.05  5057.2  791.52
  5077.3  792.31  5109.9  792.44  5258.7  791.44  5309.0  791.97  5319.1  792.97
  5329.2  792.37  5355.3  794.41  5360.3  794.31  5399.5  799.06  5404.4  799.06
#Mann=4,-1,0
  4805.3    0.05       0  4949.1    0.12       0  4994.2    0.07       0
  4999.3    0.12       0
Bank Sta=4994.2,4999.3
Exp/Cntr=0.3,0.1

Type RM Length L Ch R = 1,5979,454,454,454
BEGIN DESCRIPTION:
Mapping XS bae15561
END DESCRIPTION:
XS GIS Cut Line= 3
      2293025.28      7148606.74      2293201.93      7148362.94
      2293132.23      7147754.80
#Sta/Elev= 30
  4439.0  806.25  4524.8  804.11  4640.0  798.38  4675.6  797.61  4690.3  796.25
  4744.1  794.93  4763.2  793.10  4785.7  789.47  4809.1  788.63  4893.3  788.27
  4944.3  789.49  4954.4  788.75  4964.5  785.98  4982.5  777.82  4987.5  778.91
  5002.2  775.96  5002.8  775.46  5007.3  775.96  5014.8  776.17  5024.9  781.17
  5045.0  788.84  5076.7  789.53  5160.9  788.70  5185.9  789.57  5226.2  792.58
  5316.8  802.35  5326.8  802.55  5339.3  805.61  5347.0  806.15  5352.2  807.58
#Mann=4,-1,0
  4439.0    0.05       0  4785.7    0.12       0  5002.2    0.07       0
  5007.3    0.12       0
Bank Sta=5002.2,5007.3
Exp/Cntr=0.3,0.1

Type RM Length L Ch R = 1,5525,552,552,552
BEGIN DESCRIPTION:
MDE S 010 9.0
END DESCRIPTION:
XS GIS Cut Line= 4
      2293046.91      7148642.10      2293229.00      7148460.00
      2293629.00      7148060.00      2293728.99      7147760.04
#Sta/Elev= 30
  4273.2  805.85  4417.6  802.69  4534.3  798.31  4629.7  793.88  4686.3  788.75
  4728.7  786.45  4826.5  786.43  4841.9  786.94  4884.3  785.44  4969.1  784.60
  4983.3  777.59  4994.7  774.15  4995.5  773.65  5000.1  774.15  5011.6  774.23
  5025.7  776.86  5054.0  775.50  5099.0  777.91  5138.6  783.75  5159.7  782.88
  5180.7  784.13  5191.3  785.07  5201.8  787.43  5212.4  787.66  5233.4  790.43
  5307.5  794.30  5349.4  800.26  5381.0  815.01  5391.6  818.68  5412.6  819.63
#Mann=5,-1,0
  4273.2    0.05       0  4826.5    0.12       0  4994.7    0.07       0
  5000.1    0.12       0  5307.5    0.05       0
Bank Sta=4994.7,5000.1
Exp/Cntr=0.3,0.1

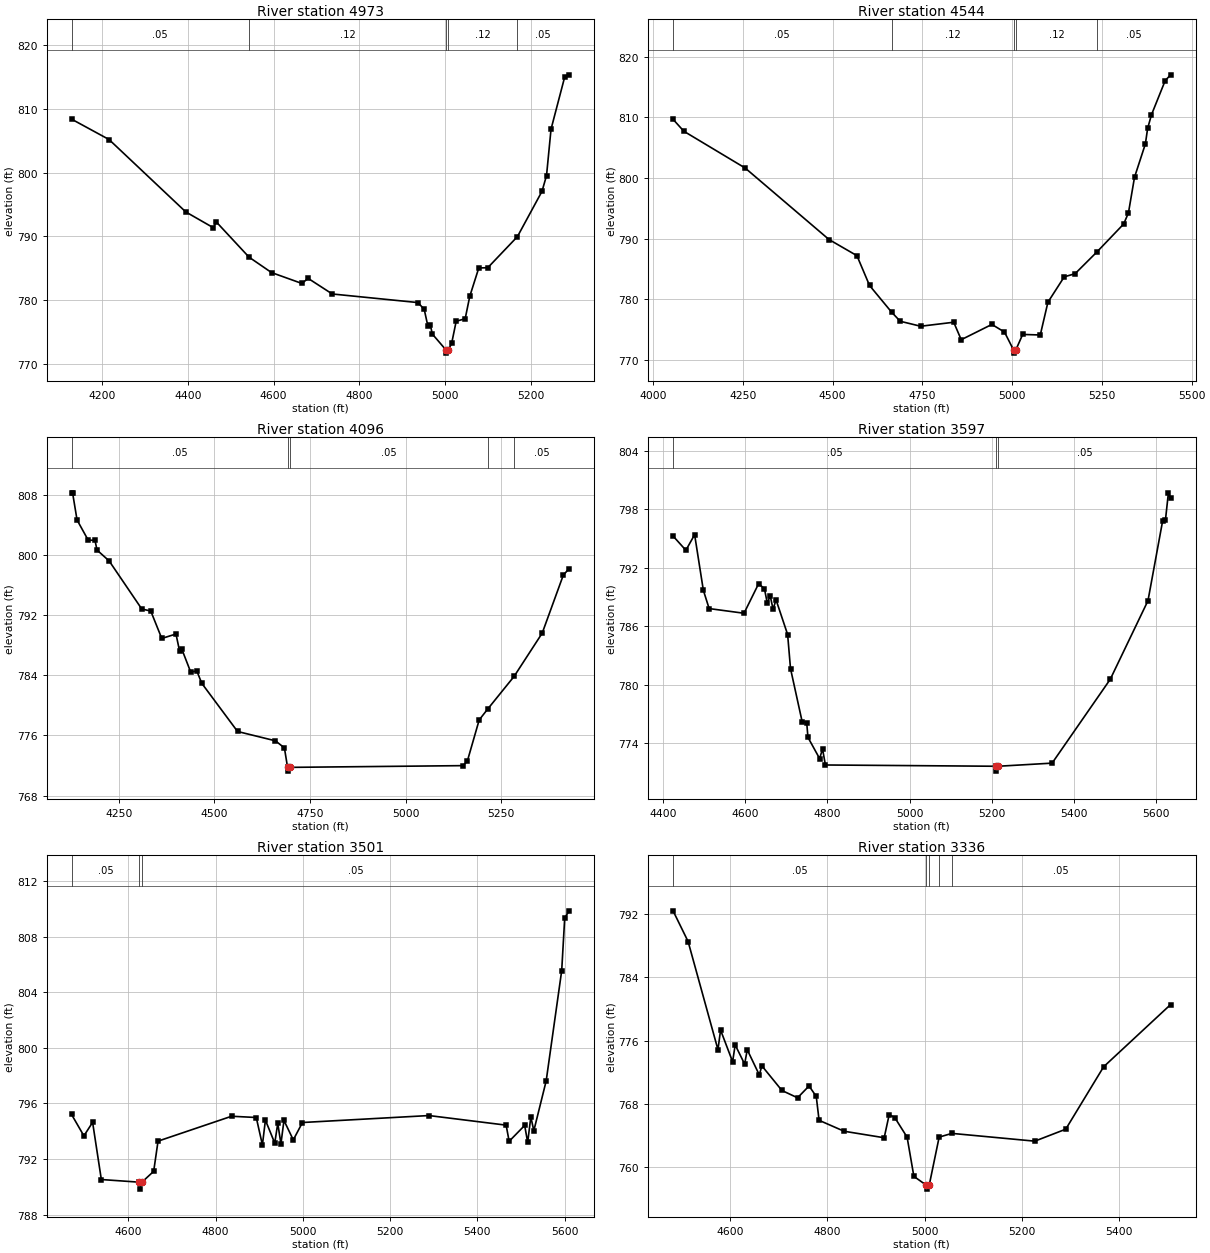
Type RM Length L Ch R = 1,4973,429,429,429
BEGIN DESCRIPTION:
MDE S 010 8.0
END DESCRIPTION:
XS GIS Cut Line= 4
      2293522.15      7148885.81      2293729.00      7148610.00
      2294029.00      7148210.00      2294129.00      7147909.99
#Sta/Elev= 30
  4128.6  808.40  4216.1  805.20  4395.2  793.84  4459.8  791.35  4466.1  792.29
  4542.7  786.75  4595.2  784.33  4666.1  782.62  4680.6  783.42  4736.9  780.97
  4936.9  779.62  4951.5  778.56  4959.8  776.00  4966.1  776.06  4970.2  774.70
  5002.3  772.19  5003.0  771.69  5007.7  772.19  5015.5  773.22  5026.1  776.69
  5047.1  777.09  5057.7  780.58  5078.8  785.05  5099.8  785.09  5169.0  789.97
  5226.3  797.07  5236.9  799.55  5247.4  806.82  5279.0  814.94  5289.6  815.35
#Mann=5,-1,0
  4128.6    0.05       0  4542.7    0.12       0  5002.3    0.07       0
  5007.7    0.12       0  5169.0    0.05       0
Bank Sta=5002.3,5007.7
Exp/Cntr=0.3,0.1

Type RM Length L Ch R = 1,4544,448,448,448
BEGIN DESCRIPTION:
MDE S 010 7.0
END DESCRIPTION:
XS GIS Cut Line= 4
      2293797.64      7149081.57      2294079.00      7148760.00
      2294429.00      7148360.00      2294579.00      7147959.99
#Sta/Elev= 30
  4055.4  809.66  4085.5  807.69  4256.3  801.63  4489.8  789.85  4567.6  787.19
  4602.7  782.28  4663.9  777.90  4688.2  776.38  4745.1  775.56  4837.2  776.22
  4858.1  773.34  4943.5  775.86  4978.6  774.60  5004.1  771.63  5005.1  771.13
  5010.0  771.63  5029.3  774.21  5078.3  774.12  5099.6  779.52  5145.0  783.70
  5175.3  784.22  5236.7  787.84  5310.6  792.41  5323.9  794.24  5340.8  800.11
  5371.1  805.61  5377.3  808.15  5388.0  810.40  5426.3  816.04  5441.4  816.99
#Mann=5,-1,0
  4055.4    0.05       0  4663.9    0.12       0  5004.1    0.07       0
  5010.0    0.12       0  5236.7    0.05       0
Bank Sta=5004.1,5010
Exp/Cntr=0.3,0.1

Type RM Length L Ch R = 1,4096,499,499,499
BEGIN DESCRIPTION:
MDE S 010 6.0
END DESCRIPTION:
XS GIS Cut Line= 3
      2294429.01      7149409.98      2294779.00      7148610.00
      2294929.00      7148209.99
#Sta/Elev= 30
  4126.8  808.26  4129.5  808.26  4141.2  804.65  4170.4  801.96  4188.0  801.96
  4193.4  800.65  4225.0  799.21  4310.4  792.81  4333.8  792.55  4362.6  788.90
  4399.7  789.49  4409.4  787.17  4414.9  787.49  4438.2  784.43  4454.2  784.58
  4467.1  782.94  4560.7  776.53  4659.7  775.29  4683.1  774.35  4691.4  771.76
  4692.4  771.26  4697.4  771.76  5149.5  771.99  5161.1  772.57  5192.2  778.07
  5213.9  779.48  5283.5  783.86  5356.9  789.61  5412.1  797.33  5427.2  798.18
#Mann=5,-1,0
  4126.8    0.05       0  4691.4   0.033       0  4697.4    0.05       0
  5213.9    0.12       0  5283.5    0.05       0
Bank Sta=4691.4,4697.4
Exp/Cntr=0.3,0.1

Type RM Length L Ch R = 1,3597,96,96,96
BEGIN DESCRIPTION:
Mapping XS 35bc4bca
END DESCRIPTION:
XS GIS Cut Line= 3
      2294718.57      7149363.83      2294950.84      7149136.22
      2295591.25      7148524.52
#Sta/Elev= 30
  4424.4  795.23  4455.6  793.77  4476.9  795.37  4498.1  789.67  4512.2  787.79
  4597.1  787.31  4632.5  790.33  4646.7  789.84  4653.7  788.35  4660.8  789.10
  4667.8  787.72  4675.0  788.69  4703.2  785.13  4710.2  781.64  4738.5  776.20
  4749.6  776.10  4752.7  774.58  4781.0  772.41  4788.2  773.39  4795.1  771.75
  5209.5  771.62  5210.5  771.12  5215.5  771.62  5346.8  771.94  5488.3  780.54
  5580.1  788.60  5615.7  796.77  5622.6  796.87  5629.8  799.66  5635.2  799.08
#Mann=3,-1,0
  4424.4    0.05       0  5209.5   0.033       0  5215.5    0.05       0
Bank Sta=5209.5,5215.5
Exp/Cntr=0.3,0.1

Type RM Length L Ch R = 1,3501,165,165,165
BEGIN DESCRIPTION:
Mapping XS bb5718ec
END DESCRIPTION:
XS GIS Cut Line= 4
      2294961.77      7149418.28      2294963.91      7149207.53
      2295042.45      7149172.74      2295650.88      7148587.61
#Sta/Elev= 30
  4469.6  795.21  4497.9  793.67  4517.9  794.64  4537.9  790.53  4624.8  790.34
  4625.9  789.84  4630.9  790.34  4657.9  791.12  4667.9  793.29  4836.5  795.08
  4893.1  794.99  4907.2  793.02  4914.1  794.80  4935.5  793.15  4942.4  794.57
  4949.7  793.10  4956.6  794.78  4978.0  793.38  4999.0  794.63  5289.0  795.13
  5466.0  794.44  5472.9  793.28  5508.5  794.42  5515.4  793.20  5522.6  795.03
  5529.5  794.04  5557.8  797.62  5593.4  805.55  5600.3  809.33  5610.4  809.85
#Mann=3,-1,0
  4469.6    0.05       0  4624.8   0.033       0  4630.9    0.05       0
Bank Sta=4624.8,4630.9
Exp/Cntr=0.3,0.1

Type RM Length L Ch R = 1,3336,349,349,349
BEGIN DESCRIPTION:
Mapping XS 5d5bf1ec
END DESCRIPTION:
XS GIS Cut Line= 4
      2295020.09      7149408.76      2295267.24      7149314.36
      2295311.92      7149128.95      2295688.71      7148705.77
#Sta/Elev= 30
  4483.5  792.36  4514.4  788.49  4575.7  774.85  4581.1  777.32  4605.8  773.33
  4611.1  775.45  4630.5  773.03  4635.9  774.84  4660.6  771.67  4665.9  772.81
  4707.1  769.70  4739.2  768.78  4762.8  770.27  4777.6  768.95  4783.4  765.94
  4834.8  764.56  4917.1  763.74  4927.4  766.66  4938.8  766.29  4964.2  763.81
  4978.1  758.87  5003.5  757.76  5004.5  757.26  5009.6  757.76  5030.0  763.82
  5056.2  764.29  5226.4  763.31  5290.0  764.82  5367.8  772.69  5505.4  780.54
#Mann=5,-1,0
  4483.5    0.05       0  5003.5   0.033       0  5009.6    0.05       0
  5030.0    0.12       0  5056.2    0.05       0
Bank Sta=5003.5,5009.6
Exp/Cntr=0.3,0.1

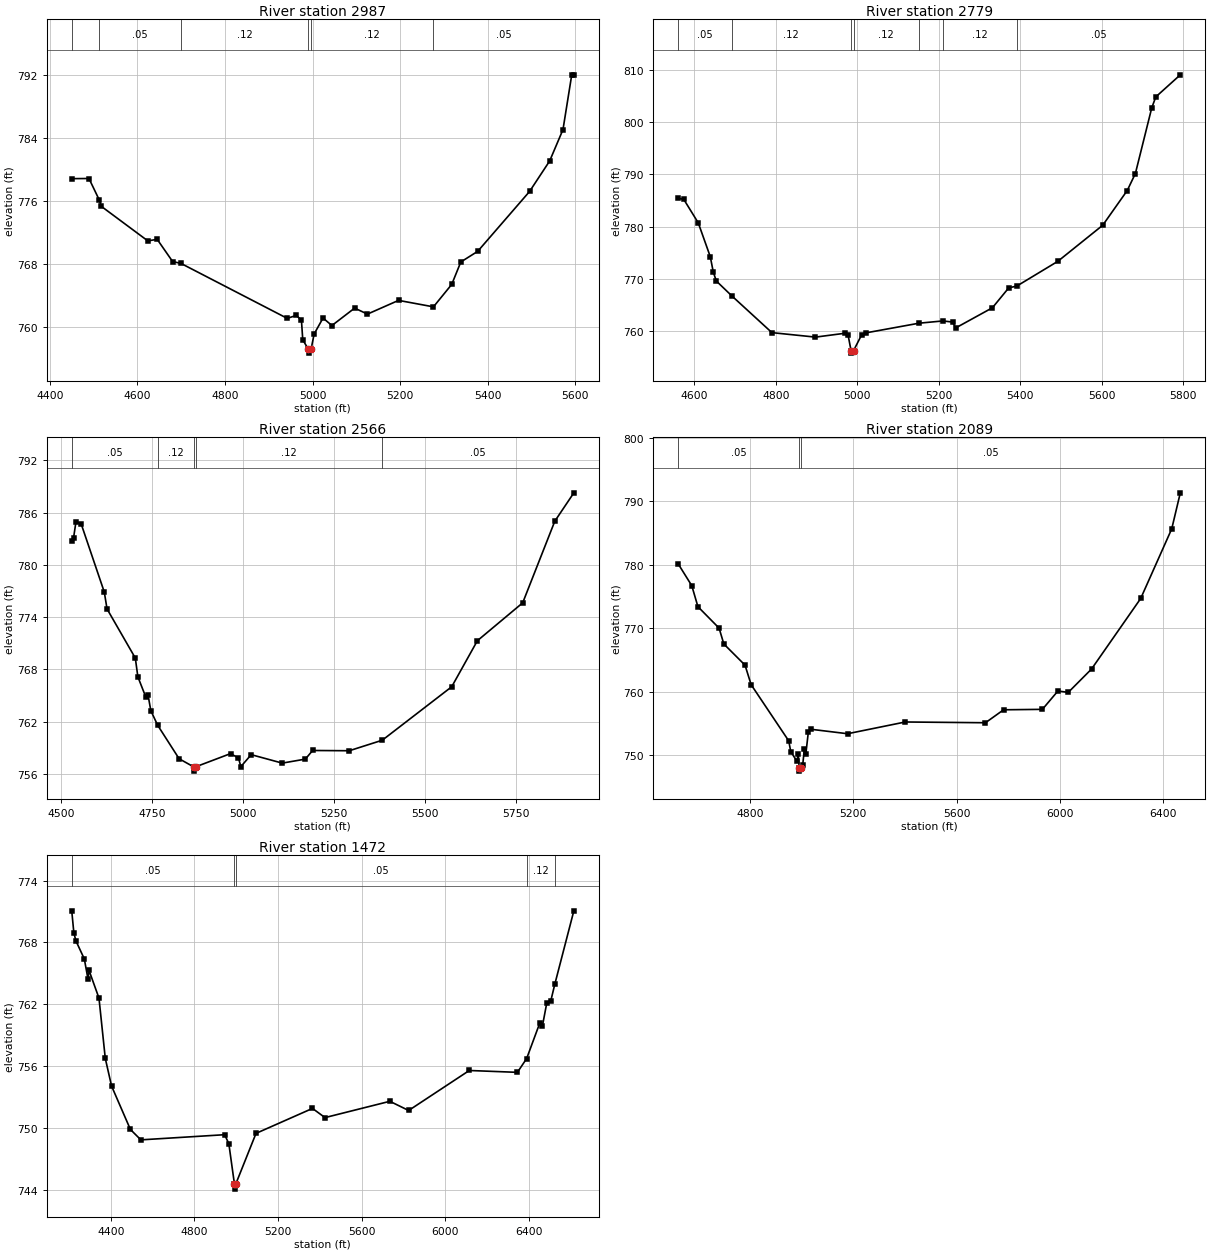
Type RM Length L Ch R = 1,2987,208,208,208
BEGIN DESCRIPTION:
Mapping XS 0b44665b
END DESCRIPTION:
XS GIS Cut Line= 3
      2295287.12      7149663.69      2295643.59      7149278.58
      2295751.58      7148665.59
#Sta/Elev= 30
  4449.9  778.86  4489.2  778.88  4512.7  776.16  4517.6  775.34  4623.6  770.97
  4645.1  771.16  4680.3  768.35  4699.7  768.10  4942.2  761.14  4963.2  761.52
  4974.7  760.89  4977.7  758.42  4990.4  757.23  4991.4  756.73  4996.7  757.23
  5003.7  759.16  5024.0  761.18  5044.3  760.23  5096.2  762.44  5125.5  761.68
  5196.6  763.42  5276.3  762.60  5318.1  765.45  5338.8  768.29  5377.4  769.64
  5496.0  777.24  5541.9  781.11  5572.3  785.09  5592.3  792.03  5597.1  792.03
#Mann=6,-1,0
  4449.9    0.12       0  4512.7    0.05       0  4699.7    0.12       0
  4990.4    0.07       0  4996.7    0.12       0  5276.3    0.05       0
Bank Sta=4990.4,4996.7
Exp/Cntr=0.3,0.1

Type RM Length L Ch R = 1,2779,213,213,213
BEGIN DESCRIPTION:
MDE S 010 3.0
END DESCRIPTION:
XS GIS Cut Line= 3
      2295579.02      7149709.97      2295829.00      7149360.00
      2295779.00      7148560.04
#Sta/Elev= 30
  4560.9  785.41  4574.4  785.22  4610.0  780.71  4639.5  774.22  4646.9  771.27
  4654.3  769.56  4692.0  766.73  4790.7  759.66  4897.6  758.80  4968.9  759.53
  4977.5  759.20  4984.8  756.23  4985.8  755.73  4991.1  756.23  5011.0  759.27
  5021.0  759.61  5151.6  761.47  5209.9  761.90  5234.0  761.69  5241.5  760.56
  5331.6  764.43  5371.7  768.25  5391.3  768.58  5492.0  773.33  5602.2  780.25
  5662.3  786.91  5682.3  790.17  5722.4  802.75  5732.4  804.86  5792.5  809.09
#Mann=7,-1,0
  4560.9    0.05       0  4692.0    0.12       0  4984.8    0.07       0
  4991.1    0.12       0  5151.6    0.05       0  5209.9    0.12       0
  5391.3    0.05       0
Bank Sta=4984.8,4991.1
Exp/Cntr=0.3,0.1

Type RM Length L Ch R = 1,2566,477,477,477
BEGIN DESCRIPTION:
Mapping XS d1c1642f
END DESCRIPTION:
XS GIS Cut Line= 3
      2295602.49      7149830.26      2296048.93      7149437.64
      2295957.52      7148656.39
#Sta/Elev= 30
  4528.3  782.74  4533.3  783.11  4539.9  784.95  4554.2  784.69  4617.8  776.86
  4625.3  774.93  4703.1  769.29  4710.1  767.14  4731.6  764.85  4738.3  765.00
  4745.8  763.25  4764.5  761.58  4823.6  757.73  4863.2  756.81  4864.2  756.31
  4869.5  756.81  4965.0  758.32  4986.8  757.82  4993.5  756.83  5021.9  758.20
  5107.3  757.23  5170.8  757.69  5190.9  758.68  5291.6  758.65  5382.5  759.86
  5573.5  766.00  5644.0  771.28  5768.7  775.63  5857.0  785.00  5909.4  788.26
#Mann=5,-1,0
  4528.3    0.05       0  4764.5    0.12       0  4863.2    0.07       0
  4869.5    0.12       0  5382.5    0.05       0
Bank Sta=4863.2,4869.5
Exp/Cntr=0.3,0.1

Type RM Length L Ch R = 1,2089,617,617,617
BEGIN DESCRIPTION:
Mapping XS a3e6fccb
END DESCRIPTION:
XS GIS Cut Line= 3
      2295544.63      7150164.89      2296198.11      7149889.86
      2296267.48      7148656.81
#Sta/Elev= 30
  4521.9  780.09  4574.3  776.67  4598.1  773.36  4680.1  769.98  4698.4  767.49
  4780.5  764.15  4804.2  761.07  4949.8  752.22  4957.5  750.54  4981.3  749.03
  4986.7  750.14  4990.0  747.96  4991.0  747.46  4996.4  747.96  5004.0  748.49
  5010.4  750.99  5015.9  750.16  5025.7  753.63  5034.2  754.06  5177.6  753.35
  5401.0  755.20  5711.5  755.08  5781.6  757.12  5931.9  757.19  5992.0  760.08
  6032.0  759.86  6122.2  763.54  6312.5  774.65  6432.7  785.62  6465.9  791.29
#Mann=3,-1,0
  4521.9    0.05       0  4990.0    0.04       0  4996.4    0.05       0
Bank Sta=4990,4996.4
Exp/Cntr=0.3,0.1

Type RM Length L Ch R = 1,1472,0,0,0
BEGIN DESCRIPTION:
MDE S 010 2.0
END DESCRIPTION:
XS GIS Cut Line= 3
      2295579.01      7150460.00      2296379.00      7150410.00
      2296429.00      7148810.03
#Sta/Elev= 30
  4213.4  771.03  4223.4  768.92  4233.4  768.14  4273.5  766.39  4291.0  764.44
  4296.0  765.28  4343.6  762.59  4373.7  756.75  4403.8  754.06  4493.9  749.85
  4544.0  748.84  4944.8  749.34  4964.9  748.47  4991.7  744.56  4992.7  744.06
  4998.2  744.56  5095.0  749.47  5365.1  751.89  5425.1  751.00  5735.3  752.58
  5825.3  751.69  6115.5  755.57  6345.6  755.39  6389.9  756.73  6453.2  760.20
  6465.7  759.93  6485.7  762.07  6505.7  762.35  6524.6  763.94  6615.7  771.06
#Mann=5,-1,0
  4213.4    0.05       0  4991.7    0.04       0  4998.2    0.05       0
  6389.9    0.12       0  6524.6    0.05       0
Bank Sta=4991.7,4998.2
Exp/Cntr=0.3,0.1

Chan Stop Cuts=-1