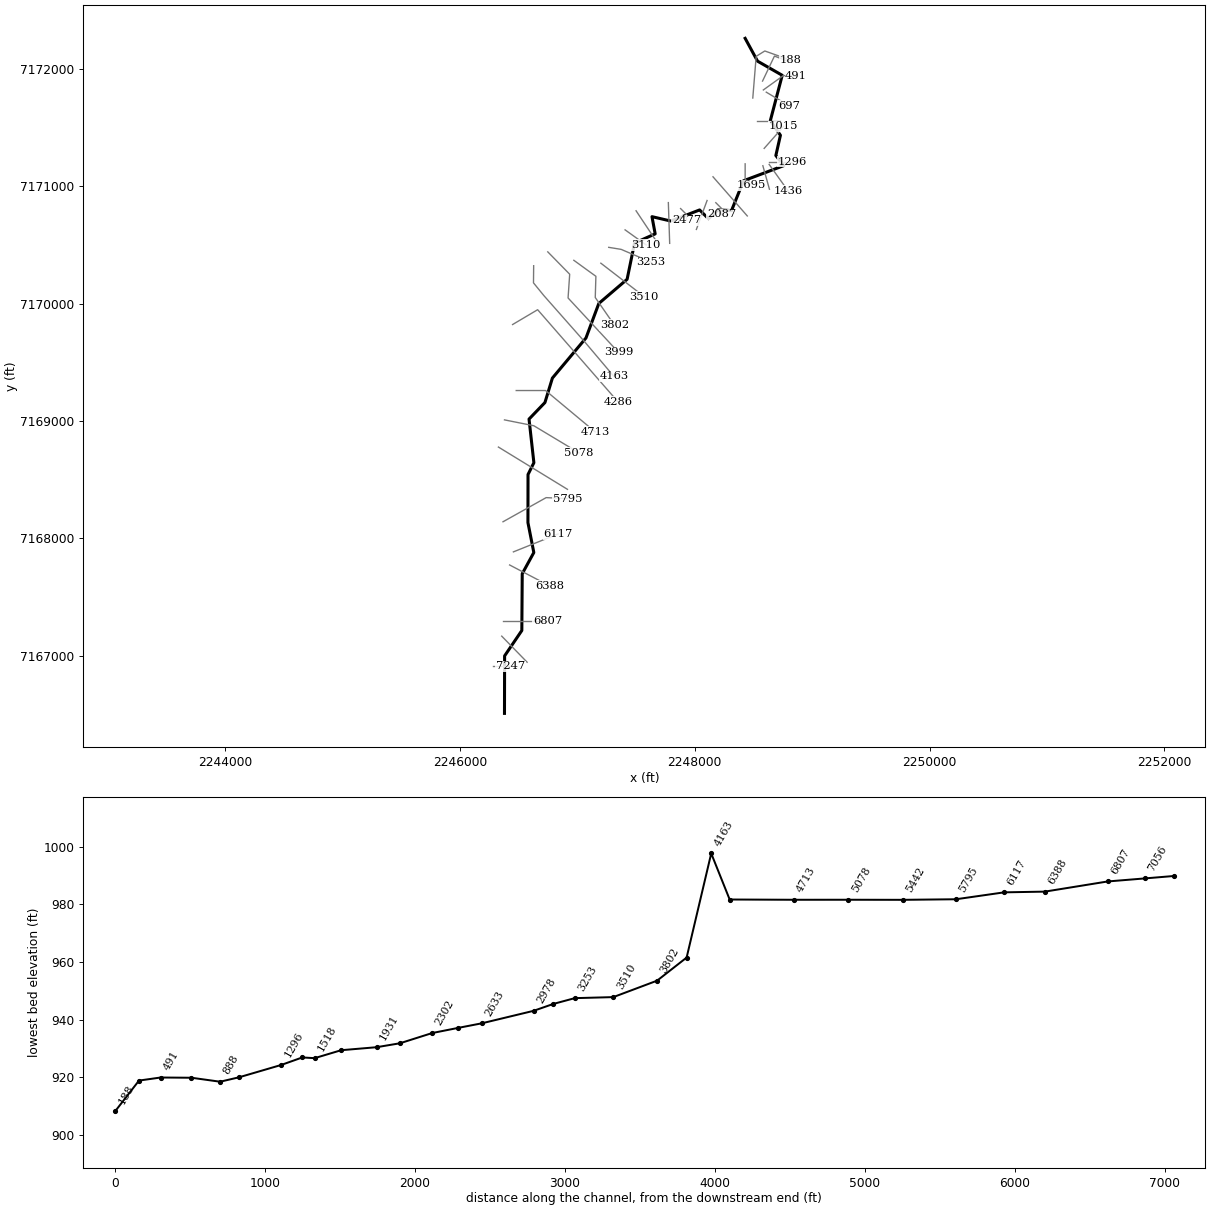
--- MDE S 019.prj (project) ---

Proj Title=MDE S 019 Base Level Engineering
Current Plan=p01
Default Exp/Contr=0.3,0.1
English Units
Geom File=g01
Flow File=f01
Plan File=p01
Y Axis Title=Elevation
X Axis Title(PF)=Main Channel Distance
X Axis Title(XS)=Station
BEGIN DESCRIPTION:
MDE S 019
END DESCRIPTION:
DSS Export Rating Curves= 0
DSS Export Rating Curve Sorted= 0
DSS Export Volume Flow Curves= 0
DXF OffsetX= 0
DXF OffsetY= 0
DXF ScaleX= 1
DXF ScaleY= 10

--- MDE S 019.p01 (plan) ---

Plan Title=Multiple Run
Short Identifier=Multiple
Geom File=g01
Flow File=f01
Subcritical Flow
K Sum by GR= 0
Std Step Tol= 0.01
Critical Tol= 0.01
Num of Std Step Trials= 20
Max Error Tol= 0.3
Flow Tol Ratio= 0.001
Split Flow NTrial= 30
Split Flow Tol= 0.02
Split Flow Ratio= 0.02
Log Output Level= 0
Friction Slope Method= 1
Unsteady Friction Slope Method= 2
Unsteady Bridges Friction Slope Method= 1
Parabolic Critical Depth
Global Vel Dist=  1 , 1 , 1
Global Log Level= 0
CheckData=True
Encroach Param= -1, 0, 0, 0
BEGIN DESCRIPTION:
Multiple Run
END DESCRIPTION:

--- MDE S 019.f01 (steady flow) ---

Flow Title=Multiple
Number of Profiles=7
Profile Names=10-year,25-year,50-year,1pct_min,100-year,1pct_plu,500-year
River Rch & RM= MDE S 019,Reach-1,7247
     677     941    1163     715    1427    2846    2148
River Rch & RM= MDE S 019,Reach-1,1015
     864    1219    1521     943    1881    3754    2884
Boundary for River Rch & Prof#=MDE S 019,Reach-1,1
Up Type=0
Dn Type=3
Dn Slope=0.007
Boundary for River Rch & Prof#=MDE S 019,Reach-1,2
Up Type=0
Dn Type=3
Dn Slope=0.007
Boundary for River Rch & Prof#=MDE S 019,Reach-1,3
Up Type=0
Dn Type=3
Dn Slope=0.007
Boundary for River Rch & Prof#=MDE S 019,Reach-1,4
Up Type=0
Dn Type=3
Dn Slope=0.007
Boundary for River Rch & Prof#=MDE S 019,Reach-1,5
Up Type=0
Dn Type=3
Dn Slope=0.007
Boundary for River Rch & Prof#=MDE S 019,Reach-1,6
Up Type=0
Dn Type=3
Dn Slope=0.007
Boundary for River Rch & Prof#=MDE S 019,Reach-1,7
Up Type=0
Dn Type=3
Dn Slope=0.007

--- MDE S 019.g01 (geometry) ---

Geom Title=Existing Conditions
Program Version=4.10

River Reach=MDE S 019       ,Reach-1
Reach XY= 30
        2246379.        7166510.      2246380.05      7166999.56
      2246526.76      7167215.93       2246530.2       7167699.5
      2246628.94      7167880.03       2246578.8      7168134.92
      2246579.52      7168544.78      2246629.43      7168644.82
      2246588.13      7169016.74      2246723.48      7169157.57
      2246787.14      7169366.06      2247073.17       7169707.7
      2247182.51      7170001.52      2247423.54      7170207.55
        2247487.      7170516.38      2247662.55      7170594.28
      2247635.43      7170741.04      2247795.82       7170703.7
      2248040.94      7170798.21      2248116.63      7170723.38
      2248196.84      7170798.57      2248312.77      7170792.63
      2248415.28      7171046.77      2248758.79      7171175.94
      2248690.51      7171261.75      2248729.52      7171434.33
      2248643.73      7171559.31      2248744.86      7171945.14
      2248534.61      7172065.59        2248429.        7172260.

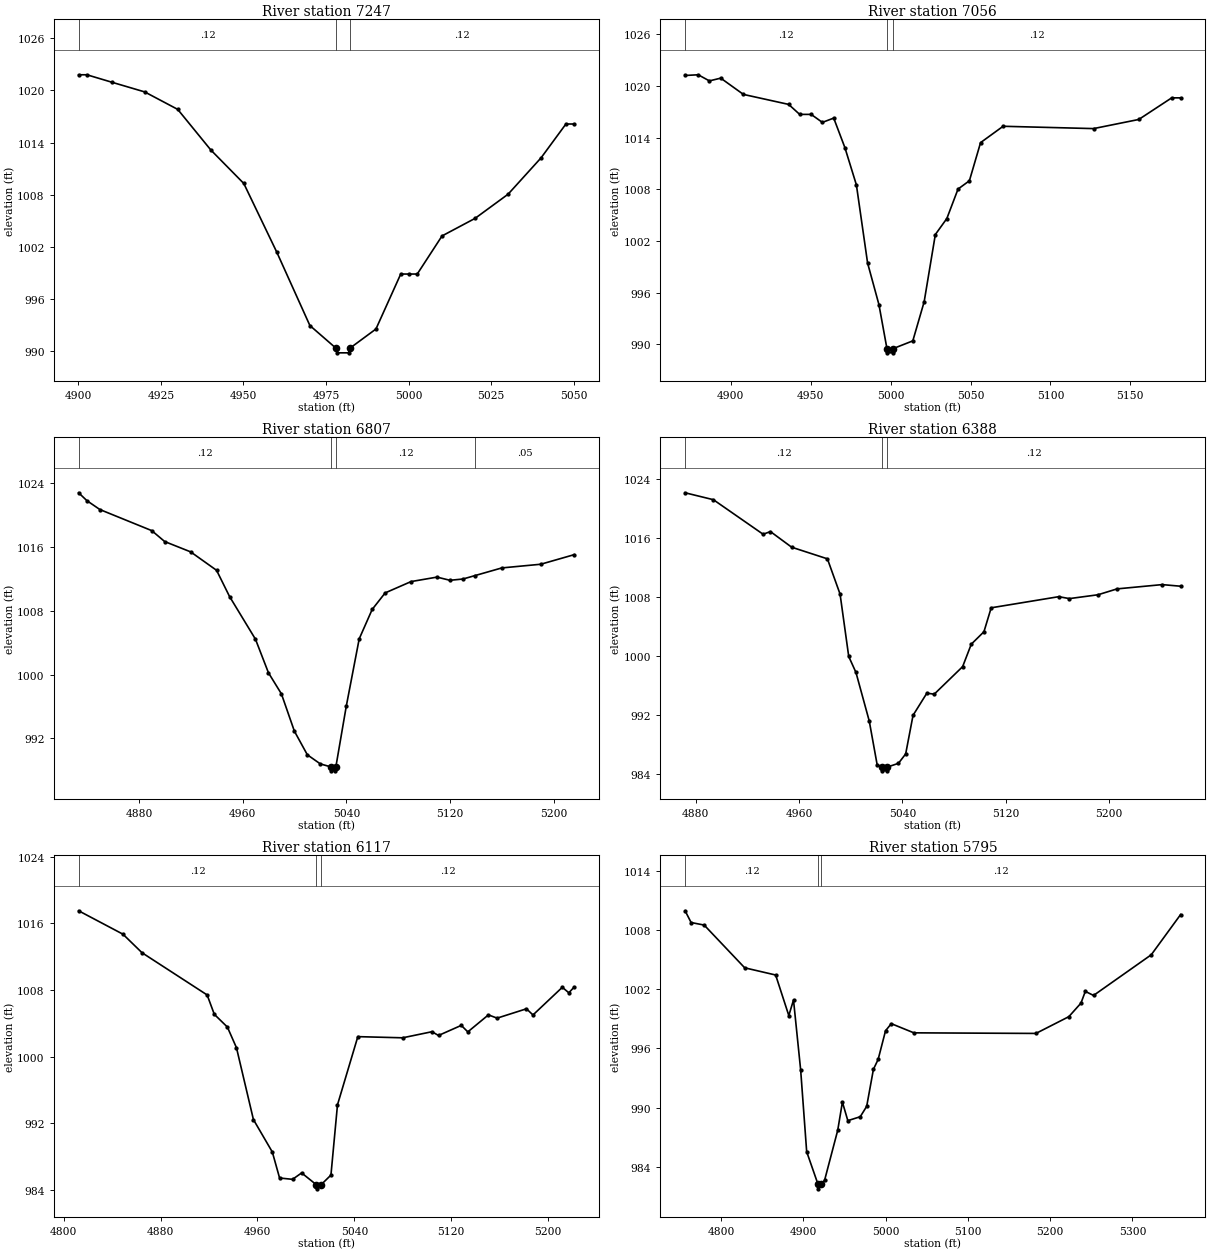
Type RM Length L Ch R = 1 ,7247    ,191,191,191
BEGIN DESCRIPTION:
MDE S 019 19.0
END DESCRIPTION:
XS GIS Cut Line= 3
      2246279.01        7166910.        2246379.        7166910.
      2246429.01        7166910.
#Sta/Elev= 23
  4900.1  1021.8  4902.6  1021.8  4910.1 1020.95  4920.1 1019.83  4930.1 1017.82
  4940.1 1013.16  4950.1  1009.3  4960.1 1001.39  4970.1  992.97  4978.1  990.33
  4978.3  989.83  4981.8  989.83  4982.1  990.33  4990.1  992.57  4997.6  998.89
  5000.1  998.89  5002.6  998.89  5010.1 1003.27  5020.1 1005.29  5030.1 1008.07
  5040.1 1012.26  5047.6 1016.14  5050.1 1016.14
#Mann= 3 ,-1 , 0
  4900.1     .12       0  4978.1     .07       0  4982.1     .12       0
Bank Sta=4978.1,4982.1
XS Rating Curve= 0 ,0
Exp/Cntr=0.3,0.1

Type RM Length L Ch R = 1 ,7056    ,249,249,249
BEGIN DESCRIPTION:
Mapping XS a1d73555
END DESCRIPTION:
XS GIS Cut Line= 2
      2246355.45      7167167.93      2246571.85      7166945.83
#Sta/Elev= 30
  4871.4 1021.21  4879.6 1021.29  4886.6 1020.58  4893.7  1020.9  4907.9 1019.01
  4936.2 1017.85  4943.1 1016.69  4950.3 1016.69  4957.3 1015.76  4964.4 1016.26
  4971.4 1012.83  4978.6  1008.5  4985.6  999.43  4992.7   994.6  4997.7   989.5
    4998     989  5001.5     989  5001.7   989.5  5013.9  990.39    5021  994.93
    5028 1002.74  5035.2  1004.6  5042.2 1008.02  5049.3 1008.98  5056.3 1013.41
  5070.4 1015.31    5127 1015.04  5155.3  1016.1  5175.9 1018.61  5181.5 1018.61
#Mann= 3 ,-1 , 0
  4871.4     .12       0  4997.7     .07       0  5001.7     .12       0
Bank Sta=4997.7,5001.7
XS Rating Curve= 0 ,0
Exp/Cntr=0.3,0.1

Type RM Length L Ch R = 1 ,6807    ,419,419,419
BEGIN DESCRIPTION:
Mapping XS 7a0313b1
END DESCRIPTION:
XS GIS Cut Line= 2
      2246362.63      7167297.44      2246744.83      7167297.44
#Sta/Elev= 30
  4833.5 1022.76  4839.9 1021.77  4849.9 1020.66  4889.9 1018.02  4899.9 1016.65
  4919.9 1015.36  4939.9 1013.05  4949.9 1009.77  4969.9 1004.42  4979.9 1000.22
  4989.9  997.58  4999.9  992.91  5009.9  989.95  5019.9  988.81  5027.9  988.44
  5028.1  987.94  5031.6  987.94  5031.9  988.44  5039.9  996.01  5049.9 1004.47
  5059.9 1008.15  5069.9 1010.22  5089.9 1011.64  5109.9  1012.2  5119.9  1011.8
  5129.9 1011.96  5139.4  1012.4  5159.9 1013.35  5189.9 1013.81  5215.7 1015.01
#Mann= 4 ,-1 , 0
  4833.5     .12       0  5027.9     .07       0  5031.9     .12       0
  5139.4     .05       0
Bank Sta=5027.9,5031.9
XS Rating Curve= 0 ,0
Exp/Cntr=0.3,0.1

Type RM Length L Ch R = 1 ,6388    ,271,271,271
BEGIN DESCRIPTION:
Mapping XS b02f80d9
END DESCRIPTION:
XS GIS Cut Line= 2
      2246422.65      7167774.18      2246762.62      7167596.29
#Sta/Elev= 30
  4871.8 1022.17  4893.7 1021.23  4932.2 1016.54  4937.9  1016.9  4954.3 1014.78
    4982  1013.2  4991.8 1008.41  4998.5  999.94  5004.1  997.77  5014.4  991.17
  5020.5  985.25  5024.2  984.91  5024.4  984.41  5027.9  984.41  5028.2  984.91
    5037  985.43  5042.6  986.71  5048.3  991.95    5059  994.96  5064.7  994.82
  5086.7  998.56  5093.4 1001.61  5103.2  1003.3  5108.8 1006.55  5161.1 1008.06
  5169.4  1007.8  5191.5 1008.32  5206.3 1009.12  5241.2  1009.7  5255.5 1009.48
#Mann= 3 ,-1 , 0
  4871.8     .12       0  5024.2     .07       0  5028.2     .12       0
Bank Sta=5024.2,5028.2
XS Rating Curve= 0 ,0
Exp/Cntr=0.3,0.1

Type RM Length L Ch R = 1 ,6117    ,322,322,322
BEGIN DESCRIPTION:
Mapping XS 804f7f90
END DESCRIPTION:
XS GIS Cut Line= 2
      2246455.06      7167885.65      2246834.73      7168038.02
#Sta/Elev= 30
  4812.4 1017.52    4849 1014.71  4864.7 1012.49  4918.5 1007.42  4924.4  1005.1
  4935.2 1003.57  4942.7 1001.09  4956.7  992.47  4972.3  988.58  4978.3  985.46
    4989   985.3  4996.5  986.07  5008.6  984.66  5008.8  984.16  5012.6  984.66
  5020.7  985.81  5026.1  994.24  5042.9 1002.42  5079.9 1002.28  5104.1 1003.01
  5109.5 1002.56  5128.3 1003.77  5133.7 1002.99  5150.7 1005.03  5157.9 1004.64
  5182.1 1005.76  5187.5 1005.02  5211.7 1008.34  5217.1 1007.68  5221.5 1008.37
#Mann= 3 ,-1 , 0
  4812.4     .12       0  5008.6     .07       0  5012.6     .12       0
Bank Sta=5008.6,5012.6
XS Rating Curve= 0 ,0
Exp/Cntr=0.3,0.1

Type RM Length L Ch R = 1 ,5795    ,353,353,353
BEGIN DESCRIPTION:
Mapping XS 575dedeb
END DESCRIPTION:
XS GIS Cut Line= 3
      2246366.49      7168142.09      2246733.85      7168347.73
      2246914.66      7168339.44
#Sta/Elev= 30
  4756.5 1009.94  4763.8 1008.75  4779.7 1008.49  4828.9 1004.16  4866.5 1003.43
  4882.5  999.32  4888.2  1000.9  4896.9   993.8  4904.2  985.52  4917.8  982.26
  4918.1  981.76  4921.8  982.26  4925.9  982.61  4941.9  987.69  4947.6  990.55
  4954.2  988.67  4969.3  989.07  4977.1  990.12  4985.3  993.88    4991  994.87
    5000  997.78    5007   998.5  5034.4  997.57  5182.7  997.51  5222.7  999.21
  5237.4 1000.58  5242.7 1001.77  5252.7 1001.36  5322.8 1005.48  5358.5 1009.56
#Mann= 3 ,-1 , 0
  4756.5     .12       0  4917.8     .07       0  4921.8     .12       0
Bank Sta=4917.8,4921.8
XS Rating Curve= 0 ,0
Exp/Cntr=0.3,0.1

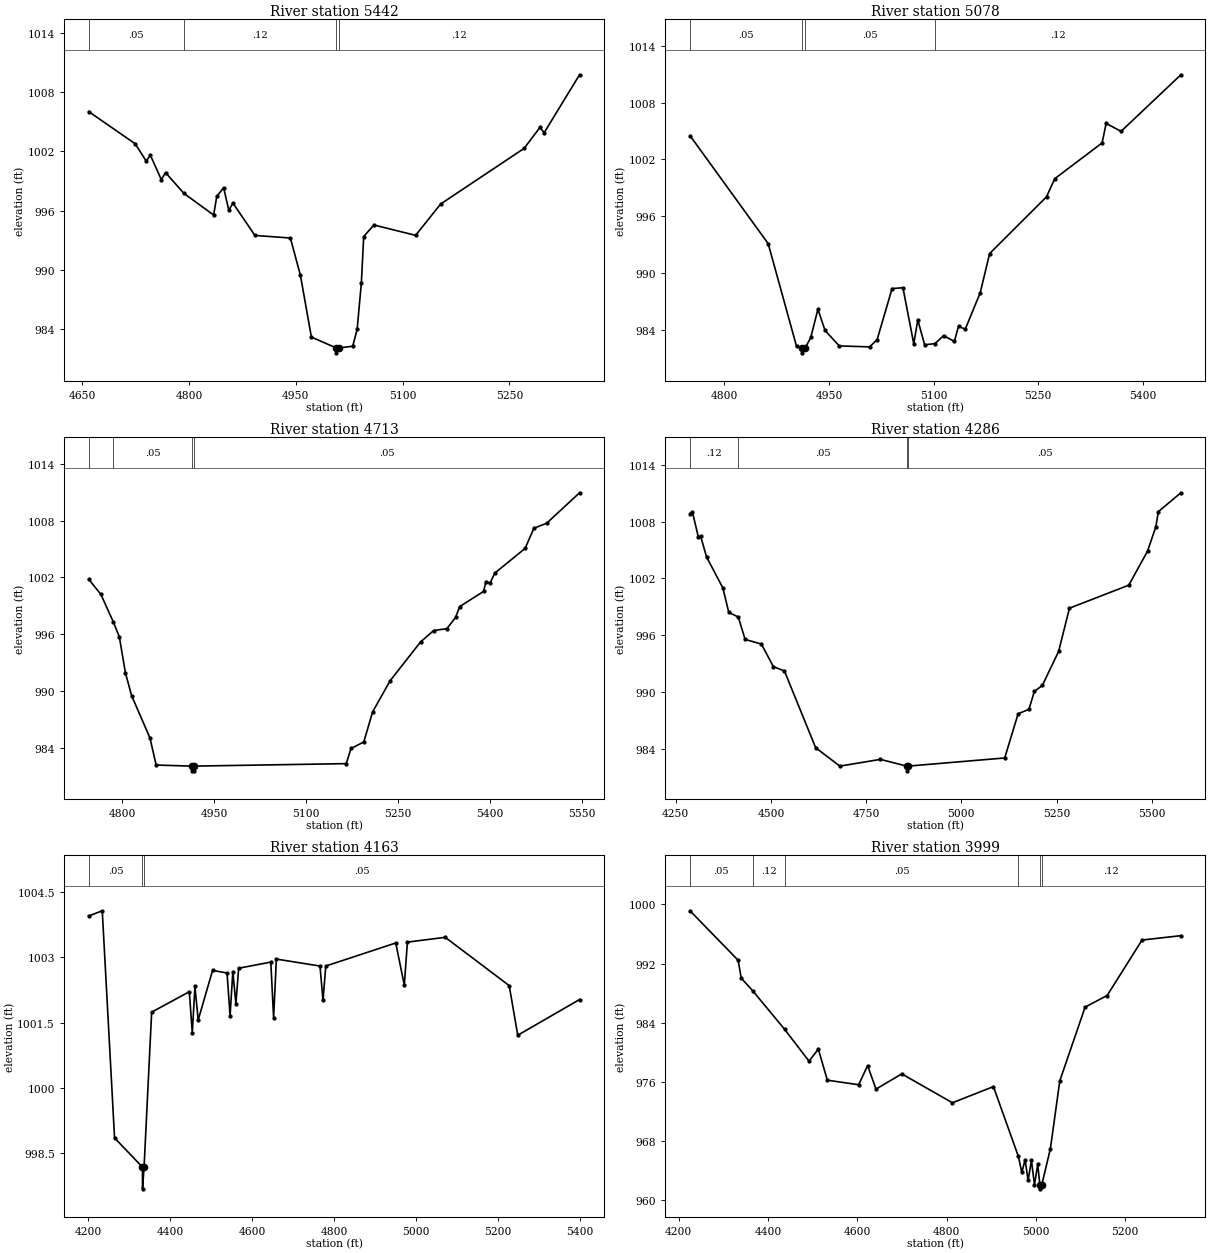
Type RM Length L Ch R = 1 ,5442    ,364,364,364
BEGIN DESCRIPTION:
Mapping XS d40fb923
END DESCRIPTION:
XS GIS Cut Line= 4
       2246327.3      7168778.54       2246481.6      7168684.05
      2246714.06       7168541.7      2246915.39      7168418.42
#Sta/Elev= 30
  4658.9 1006.04  4724.3 1002.77  4739.7 1001.02  4745.6 1001.61    4761  999.13
  4766.9  999.85  4792.7  997.74  4834.5  995.54  4838.9  997.43  4848.5  998.31
  4855.8  996.03  4861.6  996.75  4892.5  993.47  4942.3  993.21  4956.4  989.43
  4971.8  983.16  5006.6  982.06  5006.8  981.56  5010.6  982.06  5029.9  982.23
  5036.1  983.95    5042  988.65  5045.3  993.36  5059.6  994.53  5118.2  993.48
  5153.4  996.66  5270.6  1002.3  5292.9 1004.43  5298.8 1003.89  5348.5 1009.77
#Mann= 4 ,-1 , 0
  4658.9     .05       0  4792.7     .12       0  5006.6     .07       0
  5010.6     .12       0
Bank Sta=5006.6,5010.6
XS Rating Curve= 0 ,0
Exp/Cntr=0.3,0.1

Type RM Length L Ch R = 1 ,5078    ,365,365,365
BEGIN DESCRIPTION:
MDE S 019 13.0
END DESCRIPTION:
XS GIS Cut Line= 4
      2246379.02        7169010.        2246629.        7168960.
        2246879.        7168810.      2247014.25      7168728.85
#Sta/Elev= 30
  4750.5 1004.51  4862.7  993.11  4903.4  982.26  4911.6  982.09  4911.9  981.59
  4915.6  982.09  4923.8  983.21    4934  986.19  4944.2  983.96  4964.6  982.32
  5008.3  982.22    5019  982.99  5040.4  988.37    5056  988.46  5071.5  982.55
  5077.3  985.06  5087.1  982.44  5101.9  982.56  5114.3   983.4  5129.8   982.8
  5135.7  984.39  5145.4  984.09  5166.8  987.92  5180.4  992.07    5262  998.06
  5273.7  999.96  5341.7 1003.74  5347.5  1005.8  5368.9 1004.96  5454.7 1010.93
#Mann= 4 ,-1 , 0
  4750.5     .05       0  4911.6    .033       0  4915.6     .05       0
  5101.9     .12       0
Bank Sta=4911.6,4915.6
XS Rating Curve= 0 ,0
Exp/Cntr=0.3,0.1

Type RM Length L Ch R = 1 ,4713    ,427,427,427
BEGIN DESCRIPTION:
MDE S 019 12.0
END DESCRIPTION:
XS GIS Cut Line= 4
      2246479.03        7169260.        2246729.        7169260.
        2247029.        7169010.      2247151.62      7168907.82
#Sta/Elev= 30
  4745.6 1001.81  4765.6  1000.2    4786  997.27  4795.6  995.72  4805.6  991.91
  4815.6  989.52  4845.6  985.04  4855.6  982.19  4913.6  982.08  4913.8  981.58
  4917.3  981.58  4917.6  982.08  5165.4  982.34  5173.3  983.94  5194.1  984.63
  5208.4   987.8    5237  991.09  5286.5  995.18    5308  996.39  5329.5  996.59
  5343.8  997.79  5350.3  998.91  5389.3 1000.52  5393.2 1001.56  5399.8 1001.39
  5407.6 1002.45    5457 1005.06  5471.3 1007.18  5492.2 1007.72  5545.7 1010.93
#Mann= 4 ,-1 , 0
  4745.6     .12       0    4786     .05       0  4913.6    .033       0
  4917.6     .05       0
Bank Sta=4913.6,4917.6
XS Rating Curve= 0 ,0
Exp/Cntr=0.3,0.1

Type RM Length L Ch R = 1 ,4286    ,123,123,123
BEGIN DESCRIPTION:
Mapping XS 99b39308
END DESCRIPTION:
XS GIS Cut Line= 4
      2246448.03      7169822.09      2246661.47      7169948.41
      2247210.16      7169319.28      2247345.77       7169163.8
#Sta/Elev= 30
  4287.4 1008.84  4293.7 1009.03  4309.4 1006.35  4315.2 1006.49  4330.8 1004.27
  4373.7 1000.99  4389.3   998.4  4414.2  997.92  4432.2  995.55    4475  995.06
  4506.3  992.68  4535.4  992.22  4617.4  984.11    4681  982.17  4787.4  982.88
  4856.6  982.17  4856.8  981.67  4860.6  982.17  5113.9  983.03  5149.1   987.7
  5177.5  988.17  5191.8  990.06  5212.7  990.69  5255.4  994.28  5283.9  998.85
  5439.6 1001.28  5488.9 1004.87  5510.8 1007.46  5517.4 1009.05  5576.5 1011.04
#Mann= 4 ,-1 , 0
  4287.4     .12       0  4414.2     .05       0  4856.6    .033       0
  4860.6     .05       0
Bank Sta=4856.6,4860.6
XS Rating Curve= 0 ,0
Exp/Cntr=0.3,0.1

Type RM Length L Ch R = 1 ,4163    ,164,164,164
BEGIN DESCRIPTION:
Mapping XS a78e8a71
END DESCRIPTION:
XS GIS Cut Line= 5
      2246627.58      7170323.18      2246626.06       7170177.1
      2246714.75      7170068.35      2247062.21      7169674.77
      2247311.29      7169379.93
#Sta/Elev= 30
  4201.3 1003.95  4234.5 1004.07  4264.5  998.85  4332.5  998.18  4332.7  997.68
  4336.5  998.18    4355 1001.74  4446.9 1002.21  4454.1 1001.26  4460.6 1002.33
  4468.5 1001.56  4503.6  1002.7  4538.9 1002.64  4546.3 1001.66    4553 1002.67
  4560.5 1001.93  4567.2 1002.75  4645.6 1002.89  4652.5 1001.61  4659.2 1002.96
  4765.6  1002.8    4773 1002.01  4779.7  1002.8  4950.4 1003.33  4971.3 1002.36
  4978.8 1003.35  5071.1 1003.46  5227.2 1002.35    5248 1001.21  5398.7 1002.03
#Mann= 3 ,-1 , 0
  4201.3     .05       0  4332.5    .033       0  4336.5     .05       0
Bank Sta=4332.5,4336.5
XS Rating Curve= 0 ,0
Exp/Cntr=0.3,0.1

Type RM Length L Ch R = 1 ,3999    ,197,197,197
BEGIN DESCRIPTION:
MAPPING XS 92582
END DESCRIPTION:
XS GIS Cut Line= 4
      2246747.83      7170441.22      2246934.41      7170250.71
      2246920.66      7170048.39      2247348.88      7169586.77
#Sta/Elev= 30
  4225.3  999.15  4333.1  992.45  4340.1  990.03  4365.4  988.34  4437.1  983.11
  4491.7   978.8  4512.7  980.42  4532.8  976.22  4602.9   975.6    4623  978.19
  4641.8  975.01  4699.5  977.07  4812.9  973.16  4904.7  975.35  4960.6  965.89
  4968.3  963.73  4975.6  965.44  4982.4  962.66  4989.8  965.35  4996.6  962.06
  5003.9  964.82  5008.8  962.01    5009  961.51  5012.8  962.01  5032.3  966.96
  5053.3  976.13    5110  986.11  5159.3  987.68  5237.5  995.19  5324.4  995.78
#Mann= 6 ,-1 , 0
  4225.3     .05       0  4365.4     .12       0  4437.1     .05       0
  4960.6     .12       0  5008.8     .07       0  5012.8     .12       0
Bank Sta=5008.8,5012.8
XS Rating Curve= 0 ,0
Exp/Cntr=0.3,0.1

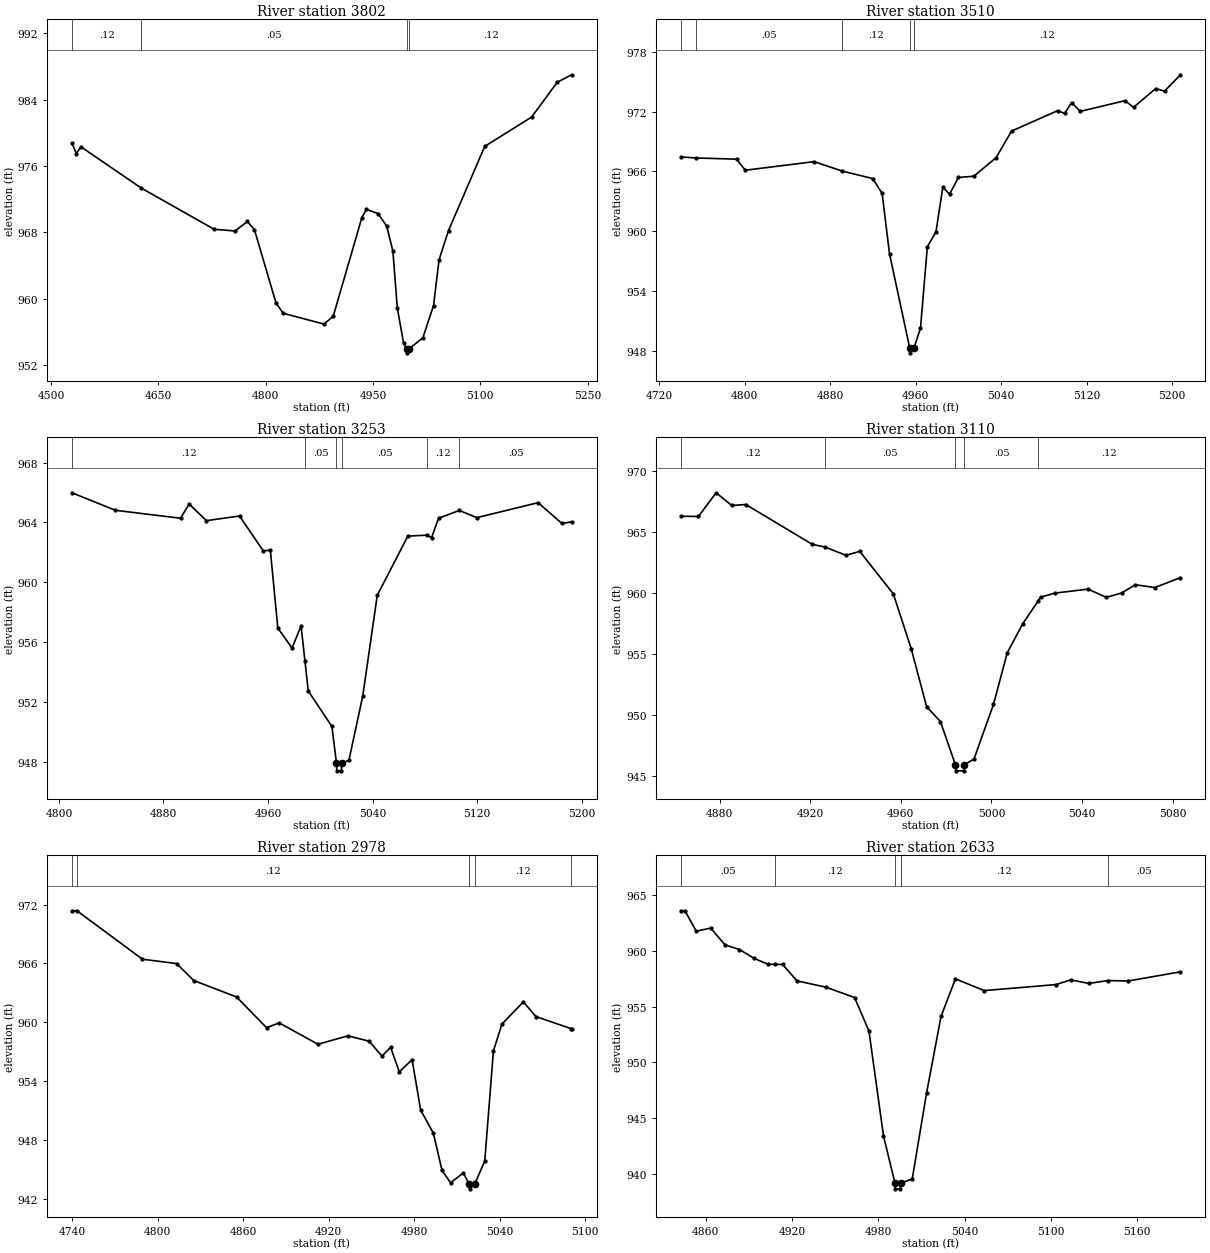
Type RM Length L Ch R = 1 ,3802    ,292,292,292
BEGIN DESCRIPTION:
Mapping XS fd678b75
END DESCRIPTION:
XS GIS Cut Line= 5
      2246969.81      7170369.26      2247102.99       7170272.5
      2247157.65      7170233.15      2247152.26      7170052.23
      2247314.94      7169817.71
#Sta/Elev= 30
  4529.3  978.73  4535.5  977.49  4541.7  978.31  4626.3  973.33    4728  968.37
  4757.4  968.17  4774.4  969.31  4784.4  968.32  4814.4  959.52  4824.5  958.26
  4881.6  956.95  4894.5   957.9  4934.5  969.78  4940.9  970.77    4957  970.27
  4969.3  968.74  4977.9  965.73    4984  958.94  4992.8  954.65  4996.9  953.99
  4997.1  953.49  5000.9  953.99  5019.8  955.31  5034.7  959.19  5042.4  964.69
  5055.6  968.22  5106.3  978.36  5171.8  981.89  5207.6  986.08  5227.7  986.98
#Mann= 4 ,-1 , 0
  4529.3     .12       0  4626.3     .05       0  4996.9     .07       0
  5000.9     .12       0
Bank Sta=4996.9,5000.9
XS Rating Curve= 0 ,0
Exp/Cntr=0.3,0.1

Type RM Length L Ch R = 1 ,3510    ,257,257,257
BEGIN DESCRIPTION:
Mapping XS 77f6728b
END DESCRIPTION:
XS GIS Cut Line= 2
      2247199.85       7170344.7      2247570.04       7170059.2
#Sta/Elev= 30
  4740.1  967.45  4754.2  967.34  4792.3  967.22  4800.5  966.11  4864.8  966.97
  4891.3  966.02  4919.7  965.27  4928.5  963.78  4935.4  957.72  4954.3  948.28
  4954.5  947.78  4958.3  948.28  4964.4  950.27  4970.8  958.42  4978.9  959.94
  4985.3  964.42  4991.6   963.7  4999.8  965.38  5014.3  965.51  5035.1  967.36
  5049.6  970.04  5092.6  972.08  5099.4  971.81  5105.7   972.9  5113.9  972.02
  5155.8  973.09  5163.7  972.42  5184.5  974.31  5192.7  974.04  5207.6  975.69
#Mann= 5 ,-1 , 0
  4740.1     .12       0  4754.2     .05       0  4891.3     .12       0
  4954.3     .07       0  4958.3     .12       0
Bank Sta=4954.3,4958.3
XS Rating Curve= 0 ,0
Exp/Cntr=0.3,0.1

Type RM Length L Ch R = 1 ,3253    ,143,143,143
BEGIN DESCRIPTION:
Mapping XS 897fd2a7
END DESCRIPTION:
XS GIS Cut Line= 3
      2247266.96      7170479.68      2247372.95      7170462.36
      2247625.66      7170354.14
#Sta/Elev= 30
    4810  965.98  4843.3  964.81  4893.1  964.28  4899.6  965.23  4912.9  964.12
  4938.2  964.43  4956.3  962.11  4961.8  962.14  4967.5  956.95  4978.4  955.62
  4985.3  957.09  4988.3  954.72  4990.8  952.75  5008.9  950.38  5012.4  947.92
  5012.6  947.42  5016.1  947.42  5016.4  947.92  5021.9  948.12  5032.5  952.42
  5043.6  959.14    5067  963.09  5081.9  963.15  5085.1  962.98  5090.5  964.28
  5106.4   964.8  5119.8  964.32  5166.7  965.32  5184.9  963.93  5192.3  964.04
#Mann= 6 ,-1 , 0
    4810     .12       0  4988.3     .05       0  5012.4    .033       0
  5016.4     .05       0  5081.9     .12       0  5106.4     .05       0
Bank Sta=5012.4,5016.4
XS Rating Curve= 0 ,0
Exp/Cntr=0.3,0.1

Type RM Length L Ch R = 1 ,3110    ,132,132,132
BEGIN DESCRIPTION:
Mapping XS c4516f7c
END DESCRIPTION:
XS GIS Cut Line= 2
      2247406.35      7170628.57       2247585.6      7170500.16
#Sta/Elev= 30
  4862.9  966.26  4870.7  966.24  4878.5  968.18  4885.4  967.14  4891.6  967.22
    4921  963.95  4926.5  963.74  4935.8  963.06  4941.9  963.38  4956.7   959.9
  4964.6  955.41  4971.4  950.66  4977.5  949.44  4984.1  945.91  4984.4  945.41
  4987.9  945.41  4988.1  945.91  4992.3  946.38  5000.9  950.85    5007  955.09
  5013.8  957.45  5020.7  959.35  5021.7  959.63  5027.9  959.96  5042.6  960.29
  5050.7  959.62  5057.4  959.97  5063.5  960.65  5072.1  960.42  5083.4  961.23
#Mann= 5 ,-1 , 0
  4862.9     .12       0  4926.5     .05       0  4984.1    .033       0
  4988.1     .05       0  5020.7     .12       0
Bank Sta=4984.1,4988.1
XS Rating Curve= 0 ,0
Exp/Cntr=0.3,0.1

Type RM Length L Ch R = 1 ,2978    ,345,345,345
BEGIN DESCRIPTION:
MAPPING XS D13809
END DESCRIPTION:
XS GIS Cut Line= 2
      2247499.83      7170791.09      2247694.42      7170499.21
#Sta/Elev= 30
  4739.8  971.36  4743.3  971.36  4789.3  966.42  4813.2  965.98  4825.3  964.25
  4855.4  962.57  4876.4  959.44  4885.3  959.93  4912.5  957.75  4933.5  958.61
  4948.5  958.06  4957.4  956.54  4963.5  957.44  4969.6  954.94  4978.6  956.18
  4984.6  951.04  4993.5  948.69  4999.6  944.89  5005.6  943.63  5014.6  944.63
  5018.6  943.51  5018.9  943.01  5022.6  943.51  5029.6  945.84  5035.7  957.08
  5041.7  959.81  5056.7  962.07  5065.6  960.57  5090.1  959.35  5090.6  959.26
#Mann= 5 ,-1 , 0
  4739.8     .05       0  4743.3     .12       0  5018.6     .07       0
  5022.6     .12       0  5090.1     .05       0
Bank Sta=5018.6,5022.6
XS Rating Curve= 0 ,0
Exp/Cntr=0.3,0.1

Type RM Length L Ch R = 1 ,2633    ,156,156,156
BEGIN DESCRIPTION:
Mapping XS e8363f94
END DESCRIPTION:
XS GIS Cut Line= 2
       2247774.8      7170860.78      2247786.15      7170513.67
#Sta/Elev= 30
  4842.7  963.59  4845.6  963.59  4853.5  961.76  4863.5  962.04  4873.5  960.53
  4883.5  960.12  4893.5  959.34  4903.5  958.79  4908.4  958.79  4913.5  958.78
  4923.5  957.31  4943.5  956.75  4963.5  955.82  4973.5  952.82  4983.6  943.43
  4991.6  939.18  4991.8  938.68  4995.3  938.68  4995.6  939.18  5003.6  939.58
  5013.6   947.3  5023.6  954.12  5033.6  957.49  5053.6  956.44  5103.6  956.98
  5113.6   957.4  5126.4  957.08  5139.5  957.34  5153.6   957.3    5190  958.12
#Mann= 5 ,-1 , 0
  4842.7     .05       0  4908.4     .12       0  4991.6     .07       0
  4995.6     .12       0  5139.5     .05       0
Bank Sta=4991.6,4995.6
XS Rating Curve= 0 ,0
Exp/Cntr=0.3,0.1

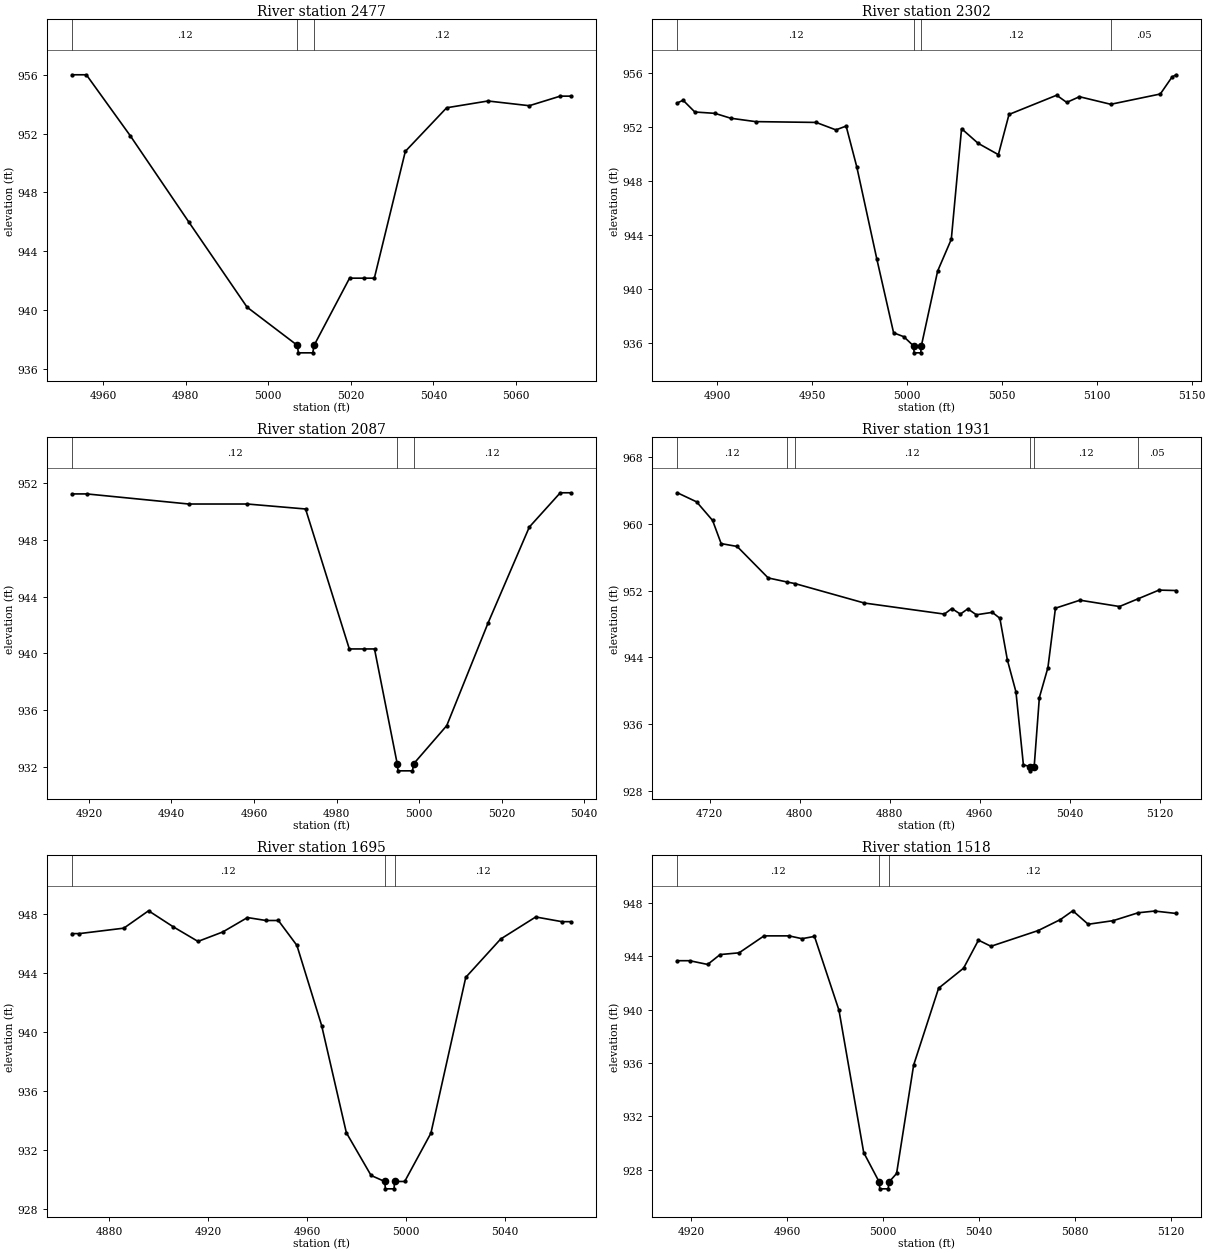
Type RM Length L Ch R = 1 ,2477    ,175,175,175
BEGIN DESCRIPTION:
MDE S 019 6.0
END DESCRIPTION:
XS GIS Cut Line= 3
        2247879.        7170810.        2247929.        7170760.
        2247929.      7170710.01
#Sta/Elev= 18
  4952.5  955.99    4956  955.99  4966.6  951.86  4980.8  945.99  4994.9  940.21
  5007.1  937.61  5007.3  937.11  5010.8  937.11  5011.1  937.61  5019.7  942.18
  5023.2  942.18  5025.7  942.18  5033.2  950.79  5043.2  953.75  5053.2  954.21
  5063.2  953.89  5070.7  954.54  5073.2  954.54
#Mann= 3 ,-1 , 0
  4952.5     .12       0  5007.1     .07       0  5011.1     .12       0
Bank Sta=5007.1,5011.1
XS Rating Curve= 0 ,0
Exp/Cntr=0.3,0.1

Type RM Length L Ch R = 1 ,2302    ,215,215,215
BEGIN DESCRIPTION:
Mapping XS ce398983
END DESCRIPTION:
XS GIS Cut Line= 2
      2248104.75       7170878.6      2248013.58      7170632.22
#Sta/Elev= 30
  4879.1  953.76  4882.1  953.96  4888.3  953.09  4898.9  952.99  4907.2  952.63
  4920.3  952.38  4952.2  952.32  4962.6  951.77    4968  952.05  4973.6  949.04
  4984.2  942.21    4993  936.78  4998.4  936.49  5003.6   935.8  5003.8   935.3
  5007.3   935.3  5007.6   935.8  5016.2  941.34  5023.4  943.69  5028.8  951.86
  5037.5  950.78  5048.2  949.94  5053.8  952.91  5078.9  954.33  5084.2   953.8
  5090.9  954.22  5107.4  953.66  5133.5  954.42  5139.7  955.68  5141.8  955.84
#Mann= 4 ,-1 , 0
  4879.1     .12       0  5003.6     .07       0  5007.6     .12       0
  5107.4     .05       0
Bank Sta=5003.6,5007.6
XS Rating Curve= 0 ,0
Exp/Cntr=0.3,0.1

Type RM Length L Ch R = 1 ,2087    ,156,156,156
BEGIN DESCRIPTION:
MDE S 019 5.0
END DESCRIPTION:
XS GIS Cut Line= 3
      2248178.97      7170860.03        2248229.        7170810.
        2248229.      7170759.95
#Sta/Elev= 17
  4915.9  951.22  4919.5  951.22  4944.2  950.51  4958.4  950.51  4972.5  950.16
  4983.1  940.32  4986.7  940.32  4989.2  940.32  4994.7  932.25  4994.9  931.75
  4998.4  931.75  4998.7  932.25  5006.7  934.93  5016.7  942.14  5026.7  948.89
  5034.2   951.3  5036.7   951.3
#Mann= 3 ,-1 , 0
  4915.9     .12       0  4994.7     .07       0  4998.7     .12       0
Bank Sta=4994.7,4998.7
XS Rating Curve= 0 ,0
Exp/Cntr=0.3,0.1

Type RM Length L Ch R = 1 ,1931    ,236,236,236
BEGIN DESCRIPTION:
Mapping XS 3e21738e
END DESCRIPTION:
XS GIS Cut Line= 3
      2248155.17      7171080.61       2248274.1      7170944.79
      2248447.14      7170747.18
#Sta/Elev= 30
  4691.3  963.75  4708.4  962.66  4722.6  960.43  4730.2  957.65  4744.4  957.31
    4772  953.53  4788.5  953.05  4795.9  952.85  4857.4  950.52  4928.6  949.19
  4935.2  949.86  4942.8  949.19  4949.4  949.82    4957  949.11  4971.2   949.4
  4977.9  948.69  4984.6  943.67  4992.2  939.86  4998.8  931.12  5004.4  930.88
  5004.6  930.38  5008.4  930.88    5013  939.17  5020.6  942.76  5027.3   949.9
  5049.1  950.86  5084.2   950.1  5100.8  951.03  5119.3  952.07  5134.5  952.02
#Mann= 6 ,-1 , 0
  4691.3     .12       0  4788.5     .05       0  4795.9     .12       0
  5004.4     .07       0  5008.4     .12       0  5100.8     .05       0
Bank Sta=5004.4,5008.4
XS Rating Curve= 0 ,0
Exp/Cntr=0.3,0.1

Type RM Length L Ch R = 1 ,1695    ,177,177,177
BEGIN DESCRIPTION:
MDE S 019 4.0
END DESCRIPTION:
XS GIS Cut Line= 4
        2248429.      7171191.02        2248429.        7171110.
        2248429.        7171060.      2248478.98      7171010.02
#Sta/Elev= 26
  4864.8  946.67  4867.8  946.67  4885.8  947.04  4895.8  948.22  4905.8  947.13
  4915.8  946.14  4925.8  946.78  4935.8  947.76  4943.3  947.56  4948.3  947.56
  4955.8  945.87  4965.8  940.43  4975.8  933.15  4985.8  930.25  4991.3  929.84
  4991.6  929.34  4995.1  929.34  4995.3  929.84  4995.8  929.84  4999.4  929.84
    5010  933.12  5024.1   943.7  5038.2   946.3  5052.4   947.8    5063  947.48
  5066.5  947.48
#Mann= 3 ,-1 , 0
  4864.8     .12       0  4991.3     .07       0  4995.3     .12       0
Bank Sta=4991.3,4995.3
XS Rating Curve= 0 ,0
Exp/Cntr=0.3,0.1

Type RM Length L Ch R = 1 ,1518    ,82,82,82
BEGIN DESCRIPTION:
Mapping XS 01197d3c
END DESCRIPTION:
XS GIS Cut Line= 2
      2248579.92      7171174.76      2248635.91      7170974.75
#Sta/Elev= 29
  4914.3  943.67  4919.4  943.67  4926.9  943.39  4932.1  944.13    4940  944.26
  4950.4  945.53  4960.8  945.53  4966.2  945.32  4971.4  945.49  4981.6  939.96
  4991.9   929.3  4998.4  927.08  4998.6  926.58  5002.1  926.58  5002.4  927.08
  5005.6  927.73  5012.7  935.85  5023.1  941.61  5033.5  943.11  5039.7  945.21
  5044.9  944.75  5064.6  945.93  5073.8  946.75    5079  947.41  5085.4   946.4
  5095.8  946.67  5106.2  947.26  5113.1  947.39    5122  947.21
#Mann= 3 ,-1 , 0
  4914.3     .12       0  4998.4     .07       0  5002.4     .12       0
Bank Sta=4998.4,5002.4
XS Rating Curve= 0 ,0
Exp/Cntr=0.3,0.1

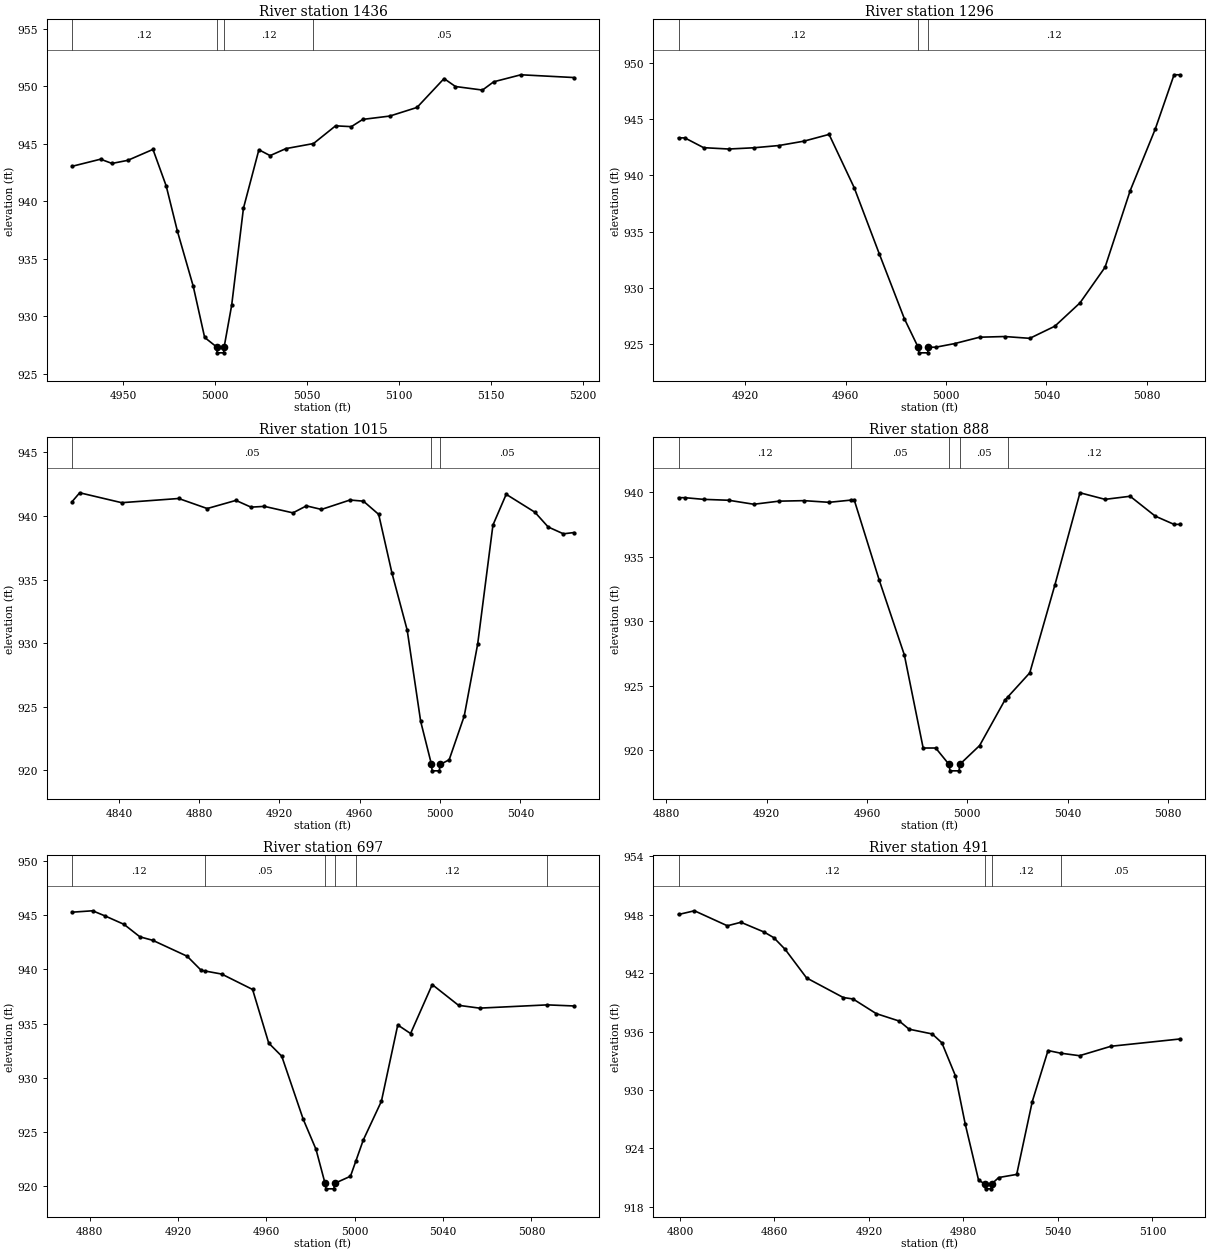
Type RM Length L Ch R = 1 ,1436    ,140,140,140
BEGIN DESCRIPTION:
Mapping XS afbe795e
END DESCRIPTION:
XS GIS Cut Line= 2
      2248633.63      7171185.79      2248792.37      7170963.81
#Sta/Elev= 30
  4922.1  943.05  4937.6  943.67  4943.8   943.3  4952.4  943.57  4966.1  944.52
  4973.3  941.34  4979.4   937.4    4988  932.62  4994.2  928.17  5000.8  927.33
    5001  926.83  5004.5  926.83  5004.8  927.33  5008.9  930.97  5015.3   939.4
  5023.7  944.49  5029.8  943.98  5038.4  944.59  5053.4  945.03  5065.4  946.57
    5074   946.5  5080.2  947.13  5094.9  947.42  5109.7  948.17  5124.4  950.68
  5130.6  949.99  5145.3  949.68  5151.4   950.4  5166.2  951.01    5195  950.77
#Mann= 4 ,-1 , 0
  4922.1     .12       0  5000.8     .07       0  5004.8     .12       0
  5053.4     .05       0
Bank Sta=5000.8,5004.8
XS Rating Curve= 0 ,0
Exp/Cntr=0.3,0.1

Type RM Length L Ch R = 1 ,1296    ,281,281,281
BEGIN DESCRIPTION:
MDE S 019 3.0
END DESCRIPTION:
XS GIS Cut Line= 3
        2248629.        7171210.        2248729.        7171210.
        2248829.        7171210.
#Sta/Elev= 27
  4893.4  943.34  4895.9  943.34  4903.4  942.47  4913.4  942.35  4923.4  942.46
  4933.4  942.66  4943.4  943.05  4953.4  943.65  4963.4  938.92  4973.4  933.04
  4983.4  927.27  4988.9  924.73  4989.2  924.23  4992.7  924.23  4992.9  924.73
  4995.9  924.73  5003.4  925.05  5013.4  925.62  5023.4  925.68  5033.4  925.52
  5043.4   926.6  5053.4  928.67  5063.4  931.84  5073.4  938.64  5083.4  944.12
  5090.9  948.95  5093.4  948.95
#Mann= 3 ,-1 , 0
  4893.4     .12       0  4988.9     .07       0  4992.9     .12       0
Bank Sta=4988.9,4992.9
XS Rating Curve= 0 ,0
Exp/Cntr=0.3,0.1

Type RM Length L Ch R = 1 ,1015    ,127,127,127
BEGIN DESCRIPTION:
Mapping XS c3d5d9d8
END DESCRIPTION:
XS GIS Cut Line= 2
      2248591.16      7171322.58      2248756.63      7171509.84
#Sta/Elev= 30
  4816.7  941.13  4820.5  941.83  4841.4  941.05  4869.8  941.38    4884  940.59
  4898.3  941.23  4905.8   940.7  4912.5  940.76  4926.7  940.25  4933.4   940.8
  4940.9  940.52  4955.1  941.26  4961.8  941.17  4969.4  940.13    4976  935.52
  4983.6  931.02  4990.3  923.85  4995.7  920.45    4996  919.95  4999.6  919.95
    5000  920.45  5004.5  920.82    5012  924.26  5018.7  929.93  5026.3  939.29
  5032.9  941.71  5047.2   940.3  5053.8  939.14  5061.4   938.6  5066.6   938.7
#Mann= 3 ,-1 , 0
  4816.7     .05       0  4995.7    .033       0    5000     .05       0
Bank Sta=4995.7,5000
XS Rating Curve= 0 ,0
Exp/Cntr=0.3,0.1

Type RM Length L Ch R = 1 ,888     ,191,191,191
BEGIN DESCRIPTION:
MDE S 019 2.0
END DESCRIPTION:
XS GIS Cut Line= 3
      2248529.01        7171560.        2248629.        7171560.
      2248729.01        7171560.
#Sta/Elev= 29
  4884.9  939.58  4887.4  939.58  4894.9  939.45  4904.9  939.38  4914.9  939.07
  4924.9  939.31  4934.9  939.35  4944.9  939.22  4953.5  939.39  4954.9  939.42
  4964.9  933.18  4974.9  927.39  4982.4  920.17  4987.4  920.17  4992.7   918.9
  4993.1   918.4  4996.7   918.4    4997   918.9  5004.9  920.36  5014.9  923.86
  5016.1  924.12  5024.9     926  5034.9  932.81  5044.9  939.96  5054.9  939.45
  5064.9  939.69  5074.9  938.15  5082.4  937.51  5084.9  937.51
#Mann= 5 ,-1 , 0
  4884.9     .12       0  4953.5     .05       0  4992.7    .033       0
    4997     .05       0  5016.1     .12       0
Bank Sta=4992.7,4997
XS Rating Curve= 0 ,0
Exp/Cntr=0.3,0.1

Type RM Length L Ch R = 1 ,697     ,206,206,206
BEGIN DESCRIPTION:
Mapping XS 0de5b9e0
END DESCRIPTION:
XS GIS Cut Line= 2
      2248608.87      7171801.49      2248803.77      7171684.91
#Sta/Elev= 30
  4872.1  945.27  4881.4   945.4  4887.2  944.91  4895.6  944.15  4902.8     943
  4908.6  942.68  4924.2  941.21  4930.5  939.92  4932.3  939.85  4939.8  939.57
  4953.8  938.15  4961.1  933.21    4967     932  4976.7   926.2  4982.5  923.42
  4986.6  920.28    4987  919.78  4990.6  919.78  4990.9  920.28  4998.1  920.94
  5000.5  922.32  5003.9  924.28  5012.1  927.85  5019.5  934.88  5025.3  934.09
  5035.1   938.6    5047  936.69  5056.5  936.43  5087.2  936.73  5099.2  936.63
#Mann= 6 ,-1 , 0
  4872.1     .12       0  4932.3     .05       0  4986.6    .033       0
  4990.9     .05       0  5000.5     .12       0  5087.2     .05       0
Bank Sta=4986.6,4990.9
XS Rating Curve= 0 ,0
Exp/Cntr=0.3,0.1

Type RM Length L Ch R = 1 ,491     ,144,144,144
BEGIN DESCRIPTION:
Mapping XS f3c65b97
END DESCRIPTION:
XS GIS Cut Line= 3
      2248584.03      7171820.33      2248754.27      7171942.95
      2248862.91      7171937.27
#Sta/Elev= 30
  4799.1  948.01  4809.2  948.39  4830.1  946.85  4838.7  947.21  4853.4  946.21
  4859.6  945.63  4866.8  944.43  4880.4   941.5  4903.7  939.49  4909.9  939.34
  4924.6  937.84  4939.3  937.07  4945.5  936.24  4960.2  935.75  4966.3  934.84
  4974.9  931.46  4981.1  926.53  4989.6  920.75  4993.6  920.36    4994  919.86
  4997.6  919.86  4997.9  920.36  5002.4  921.02  5013.8  921.34  5023.7  928.82
  5033.7  934.05  5041.7  933.78  5053.7  933.52  5073.7  934.49  5117.7  935.24
#Mann= 4 ,-1 , 0
  4799.1     .12       0  4993.6     .07       0  4997.9     .12       0
  5041.7     .05       0
Bank Sta=4993.6,4997.9
XS Rating Curve= 0 ,0
Exp/Cntr=0.3,0.1

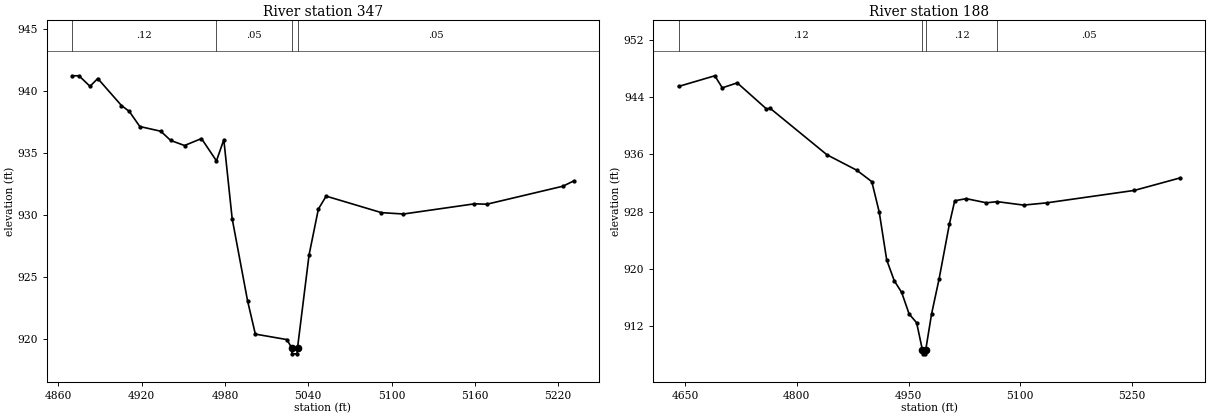
Type RM Length L Ch R = 1 ,347     ,159,159,159
BEGIN DESCRIPTION:
Mapping XS 01c0d2b0
END DESCRIPTION:
XS GIS Cut Line= 3
      2248577.22      7171895.89       2248678.6      7172108.83
      2248795.85      7172063.91
#Sta/Elev= 30
  4869.9  941.21  4874.9  941.21  4882.8  940.36  4888.4  940.99  4905.5  938.81
  4911.1  938.34  4918.7  937.12  4933.8  936.74  4940.9     936  4950.9  935.59
  4963.1  936.15  4973.9  934.35  4979.2  936.06  4985.2   929.7  4996.3  923.07
  5001.9  920.39  5024.6  919.95    5028   919.3  5028.3   918.8  5031.9   918.8
  5032.3   919.3  5040.6  926.78  5047.3  930.47  5052.9  931.51  5092.7  930.18
  5108.6  930.07  5159.7  930.89  5168.7  930.86  5223.4  932.31  5231.3  932.74
#Mann= 4 ,-1 , 0
  4869.9     .12       0  4973.9     .05       0    5028    .033       0
  5032.3     .05       0
Bank Sta=5028,5032.3
XS Rating Curve= 0 ,0
Exp/Cntr=0.3,0.1

Type RM Length L Ch R = 1 ,188     ,0,0,0
BEGIN DESCRIPTION:
MDE S 019 1.0
END DESCRIPTION:
XS GIS Cut Line= 4
       2248494.1       7171751.5      2248523.03      7172106.87
      2248596.45      7172152.32      2248813.65      7172074.84
#Sta/Elev= 30
  4641.3  945.45    4690  946.94    4700  945.26  4720.1  945.95  4759.3  942.32
  4764.3   942.4  4840.5  935.92  4880.6  933.76  4900.7  932.17  4910.7  927.91
  4920.7  921.25  4930.8  918.36  4940.8  916.71  4950.8  913.71  4960.9  912.48
  4968.7  908.65  4969.1  908.15  4972.7  908.15    4973  908.65  4980.9   913.7
    4991  918.59  5004.9  926.28    5012   929.5  5027.4   929.8  5054.5  929.22
  5069.1  929.38  5104.4   928.9  5135.2  929.21  5253.1  930.95  5314.8   932.7
#Mann= 4 ,-1 , 0
  4641.3     .12       0  4968.7     .07       0    4973     .12       0
  5069.1     .05       0
Bank Sta=4968.7,4973
XS Rating Curve= 0 ,0
Exp/Cntr=0.3,0.1

Chan Stop Cuts=-1
Use User Specified Reach Order=0
Composite Channel Slope=5