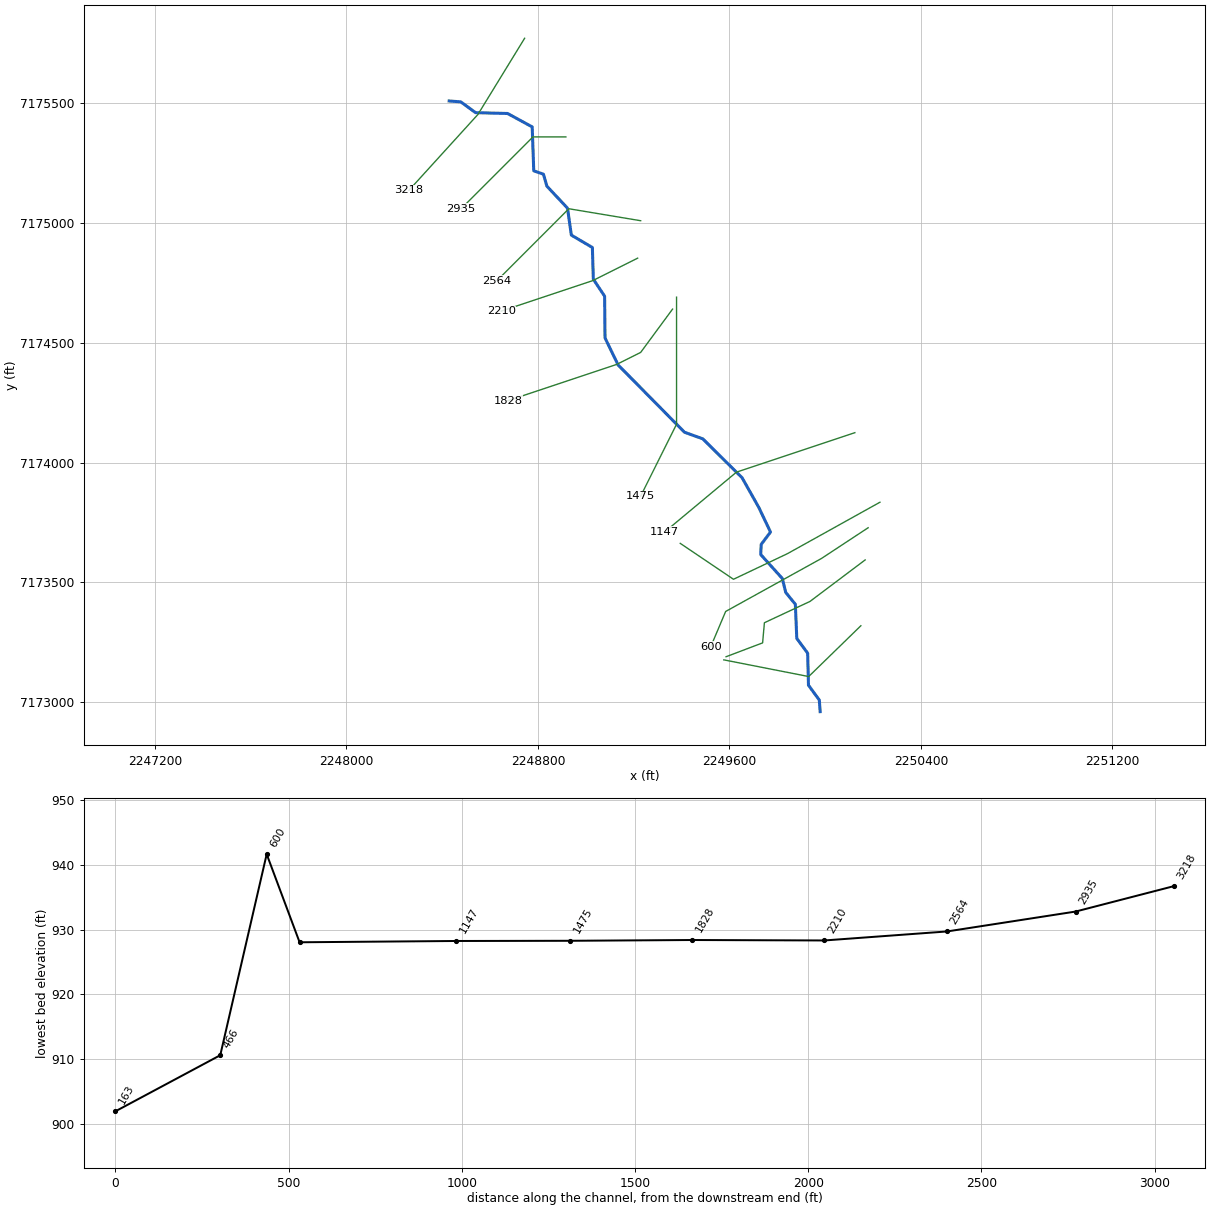
--- MDE S 020.prj (project) ---

Proj Title=MDE S 020 Base Level Engineering
Current Plan=p01
Default Exp/Contr=0.3,0.1
English Units
Geom File=g01
Flow File=f01
Plan File=p01
BEGIN DESCRIPTION:
MDE S 020
END DESCRIPTION:

--- MDE S 020.p01 (plan) ---

Plan Title=Multiple Run
Short Identifier=Multiple
Geom File=g01
Flow File=f01
Subcritical Flow
K Sum by GR= 0
Std Step Tol= 0.01
Critical Tol= 0.01
Num of Std Step Trials= 20
Max Error Tol= 0.3
Flow Tol Ratio= 0.001
Split Flow NTrial= 30
Split Flow Tol= 0.02
Split Flow Ratio= 0.02
Log Output Level= 0
Friction Slope Method= 1
Unsteady Friction Slope Method= 2
Unsteady Bridges Friction Slope Method= 1
Parabolic Critical Depth
Global Vel Dist=  1 , 1 , 1
Global Log Level= 0
CheckData=True
Encroach Param= -1, 0, 0, 0
BEGIN DESCRIPTION:
Multiple Run
END DESCRIPTION:

--- MDE S 020.f01 (steady flow) ---

Flow Title=Multiple
Number of Profiles=7
Profile Names=10-year,25-year,50-year,1pct_min,100-year,1pct_plu,500-year
River Rch & RM= MDE S 020,Reach-1,3218
     772    1090    1362     846    1688    3369    2599
Boundary for River Rch & Prof#=MDE S 020,Reach-1,1
Up Type=0
Dn Type=3
Dn Slope=0.009
Boundary for River Rch & Prof#=MDE S 020,Reach-1,2
Up Type=0
Dn Type=3
Dn Slope=0.009
Boundary for River Rch & Prof#=MDE S 020,Reach-1,3
Up Type=0
Dn Type=3
Dn Slope=0.009
Boundary for River Rch & Prof#=MDE S 020,Reach-1,4
Up Type=0
Dn Type=3
Dn Slope=0.009
Boundary for River Rch & Prof#=MDE S 020,Reach-1,5
Up Type=0
Dn Type=3
Dn Slope=0.009
Boundary for River Rch & Prof#=MDE S 020,Reach-1,6
Up Type=0
Dn Type=3
Dn Slope=0.009
Boundary for River Rch & Prof#=MDE S 020,Reach-1,7
Up Type=0
Dn Type=3
Dn Slope=0.009

--- MDE S 020.g01 (geometry) ---

Geom Title=Existing Conditions

River Reach=MDE S 020,Reach-1
Reach XY= 30
      2248429.00      7175510.00      2248477.49      7175506.35
      2248539.47      7175461.13      2248673.09      7175457.76
      2248775.94      7175401.72      2248782.40      7175218.44
      2248822.94      7175204.20      2248837.25      7175154.23
      2248923.46      7175062.42      2248939.45      7174949.92
      2249027.34      7174898.16      2249031.28      7174765.95
      2249078.48      7174694.78      2249080.20      7174520.50
      2249134.83      7174407.70      2249412.33      7174126.65
      2249488.68      7174099.22      2249652.71      7173936.82
      2249722.95      7173812.19      2249771.44      7173710.00
      2249732.58      7173658.35      2249730.66      7173616.05
      2249820.84      7173516.05      2249835.14      7173457.83
      2249875.24      7173408.44      2249881.27      7173265.94
      2249926.73      7173204.06      2249930.13      7173070.47
      2249975.35      7173008.49      2249979.00      7172960.00

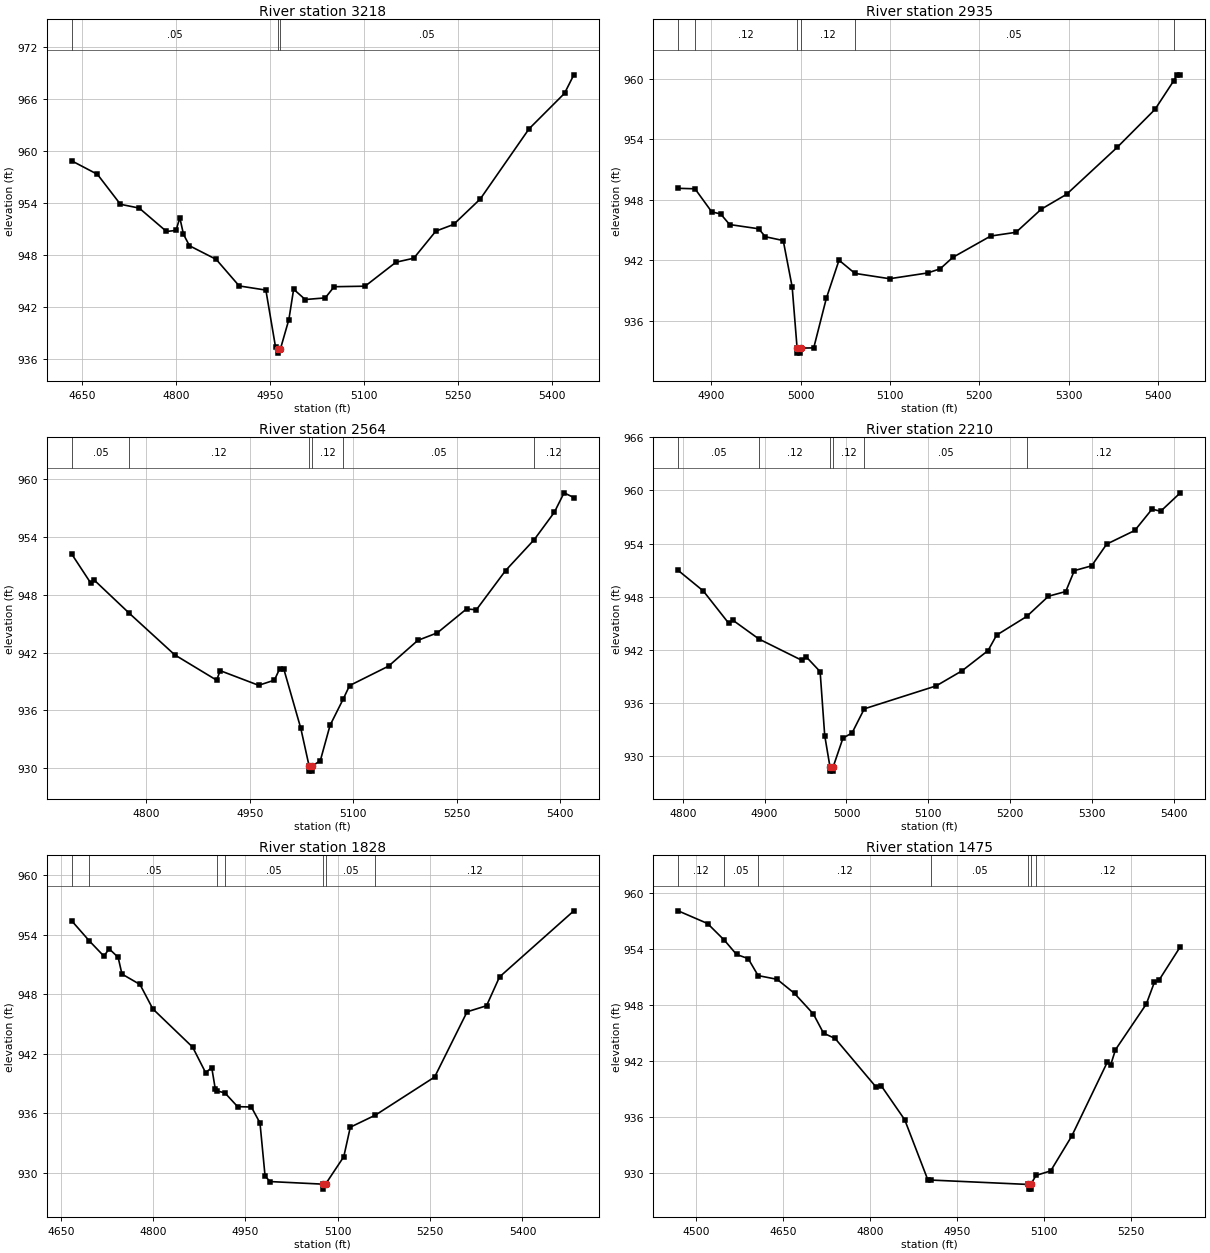
Type RM Length L Ch R = 1,3218,283,283,283
BEGIN DESCRIPTION:
MDE S 020 9.0
END DESCRIPTION:
XS GIS Cut Line= 4
      2248744.38      7175771.89      2248695.87      7175692.82
      2248549.01      7175453.45      2248261.15      7175137.12
#Sta/Elev= 30
  4633.9  958.90  4675.0  957.34  4711.7  953.88  4741.7  953.44  4785.2  950.74
  4800.4  950.86  4806.5  952.33  4812.3  950.42  4821.9  949.09  4864.5  947.52
  4901.2  944.45  4943.8  943.97  4959.2  937.40  4963.1  937.19  4963.3  936.69
  4967.1  937.19  4980.5  940.57  4988.1  944.07  5006.6  942.88  5038.6  943.07
  5052.7  944.36  5102.1  944.42  5151.4  947.19  5179.8  947.65  5215.0  950.78
  5243.3  951.55  5285.9  954.49  5363.7  962.59  5420.3  966.69  5435.2  968.83
#Mann=3,-1,0
  4633.9    0.05       0  4963.1   0.033       0  4967.1    0.05       0
Bank Sta=4963.1,4967.1
Exp/Cntr=0.3,0.1

Type RM Length L Ch R = 1,2935,371,371,371
BEGIN DESCRIPTION:
MDE S 020 8.0
END DESCRIPTION:
XS GIS Cut Line= 4
      2248916.56      7175360.00      2248829.00      7175360.00
      2248779.00      7175360.00      2248479.02      7175060.02
#Sta/Elev= 30
  4863.0  949.15  4881.9  949.10  4900.6  946.81  4910.6  946.60  4920.6  945.55
  4953.1  945.13  4960.6  944.34  4980.6  943.96  4990.6  939.35  4996.1  933.28
  4996.3  932.78  4999.8  932.78  5000.1  933.28  5014.7  933.30  5028.8  938.22
  5043.0  942.01  5060.8  940.70  5099.6  940.17  5142.0  940.74  5156.1  941.15
  5170.3  942.29  5212.7  944.41  5241.0  944.78  5269.3  947.08  5297.5  948.55
  5354.1  953.21  5396.5  956.99  5417.3  959.81  5421.3  960.42  5424.8  960.42
#Mann=6,-1,0
  4863.0    0.05       0  4881.9    0.12       0  4996.1    0.07       0
  5000.1    0.12       0  5060.8    0.05       0  5417.3    0.12       0
Bank Sta=4996.1,5000.1
Exp/Cntr=0.3,0.1

Type RM Length L Ch R = 1,2564,354,354,354
BEGIN DESCRIPTION:
MDE S 020 7.0
END DESCRIPTION:
XS GIS Cut Line= 3
      2249228.98      7175010.00      2248929.00      7175060.00
      2248628.99      7174759.99
#Sta/Elev= 30
  4691.5  952.23  4719.4  949.19  4724.4  949.51  4775.4  946.06  4841.0  941.77
  4901.8  939.14  4906.9  940.13  4962.7  938.61  4985.5  939.14  4993.1  940.30
  4999.2  940.30  5023.9  934.14  5036.0  930.21  5036.3  929.71  5039.8  929.71
  5040.0  930.21  5052.2  930.80  5066.3  934.46  5085.7  937.23  5094.6  938.58
  5151.2  940.60  5193.6  943.27  5221.9  944.05  5264.3  946.53  5278.5  946.44
  5320.9  950.51  5362.5  953.72  5391.6  956.55  5405.7  958.57  5419.9  958.08
#Mann=6,-1,0
  4691.5    0.05       0  4775.4    0.12       0  5036.0    0.07       0
  5040.0    0.12       0  5085.7    0.05       0  5362.5    0.12       0
Bank Sta=5036,5040
Exp/Cntr=0.3,0.1

Type RM Length L Ch R = 1,2210,382,382,382
BEGIN DESCRIPTION:
MDE S 020 6.0
END DESCRIPTION:
XS GIS Cut Line= 5
      2249216.59      7174853.80      2249129.00      7174810.00
      2249029.00      7174760.00      2248729.00      7174660.00
      2248646.24      7174632.41
#Sta/Elev= 30
  4794.4  950.98  4825.2  948.65  4856.0  945.03  4861.6  945.33  4893.1  943.23
  4945.4  940.83  4951.0  941.20  4967.8  939.55  4973.4  932.34  4979.8  928.82
  4980.0  928.32  4983.5  928.32  4983.8  928.82  4995.7  932.05  5006.8  932.63
  5021.7  935.35  5109.5  937.94  5141.2  939.65  5172.8  941.92  5183.3  943.67
  5220.1  945.78  5246.6  948.06  5267.7  948.59  5278.2  950.95  5299.3  951.49
  5317.7  953.94  5352.0  955.48  5373.1  957.89  5383.6  957.65  5407.6  959.73
#Mann=6,-1,0
  4794.4    0.05       0  4893.1    0.12       0  4979.8    0.07       0
  4983.8    0.12       0  5021.7    0.05       0  5220.1    0.12       0
Bank Sta=4979.8,4983.8
Exp/Cntr=0.3,0.1

Type RM Length L Ch R = 1,1828,353,353,353
BEGIN DESCRIPTION:
MDE S 020 5.0
END DESCRIPTION:
XS GIS Cut Line= 5
      2249362.34      7174640.98      2249229.00      7174460.00
      2249129.00      7174410.00      2248829.00      7174310.00
      2248674.49      7174258.50
#Sta/Elev= 30
  4667.7  955.39  4696.6  953.35  4720.1  951.83  4728.6  952.57  4743.2  951.71
  4749.4  950.03  4778.7  948.98  4799.6  946.52  4864.3  942.67  4885.2  940.12
  4895.3  940.60  4900.9  938.50  4904.6  938.26  4916.7  938.07  4937.2  936.69
  4959.6  936.65  4973.6  935.05  4981.9  929.68  4990.3  929.15  5076.1  928.89
  5076.3  928.39  5080.1  928.89  5109.7  931.65  5120.3  934.62  5161.2  935.84
  5257.3  939.67  5310.0  946.23  5341.6  946.84  5362.7  949.74  5483.4  956.39
#Mann=7,-1,0
  4667.7    0.12       0  4696.6    0.05       0  4904.6    0.12       0
  4916.7    0.05       0  5076.1   0.033       0  5080.1    0.05       0
  5161.2    0.12       0
Bank Sta=5076.1,5080.1
Exp/Cntr=0.3,0.1

Type RM Length L Ch R = 1,1475,328,328,328
BEGIN DESCRIPTION:
MDE S 020 4.0
END DESCRIPTION:
XS GIS Cut Line= 4
      2249379.00      7174690.75      2249379.00      7174460.00
      2249379.00      7174160.00      2249228.98      7173859.97
#Sta/Elev= 30
  4469.0  958.05  4519.8  956.69  4549.0  954.89  4569.8  953.38  4589.8  952.94
  4607.0  951.12  4639.8  950.72  4669.8  949.21  4702.3  947.01  4719.8  944.96
  4739.8  944.39  4809.8  939.24  4819.8  939.29  4859.8  935.70  4899.8  929.25
  4905.2  929.24  5073.2  928.77  5073.5  928.27  5077.0  928.27  5077.2  928.77
  5086.4  929.74  5111.6  930.22  5147.9  933.94  5209.4  941.87  5215.0  941.54
  5223.4  943.19  5276.5  948.07  5290.4  950.39  5298.8  950.66  5335.2  954.21
#Mann=7,-1,0
  4469.0    0.12       0  4549.0    0.05       0  4607.0    0.12       0
  4905.2    0.05       0  5073.2   0.033       0  5077.2    0.05       0
  5086.4    0.12       0
Bank Sta=5073.2,5077.2
Exp/Cntr=0.3,0.1

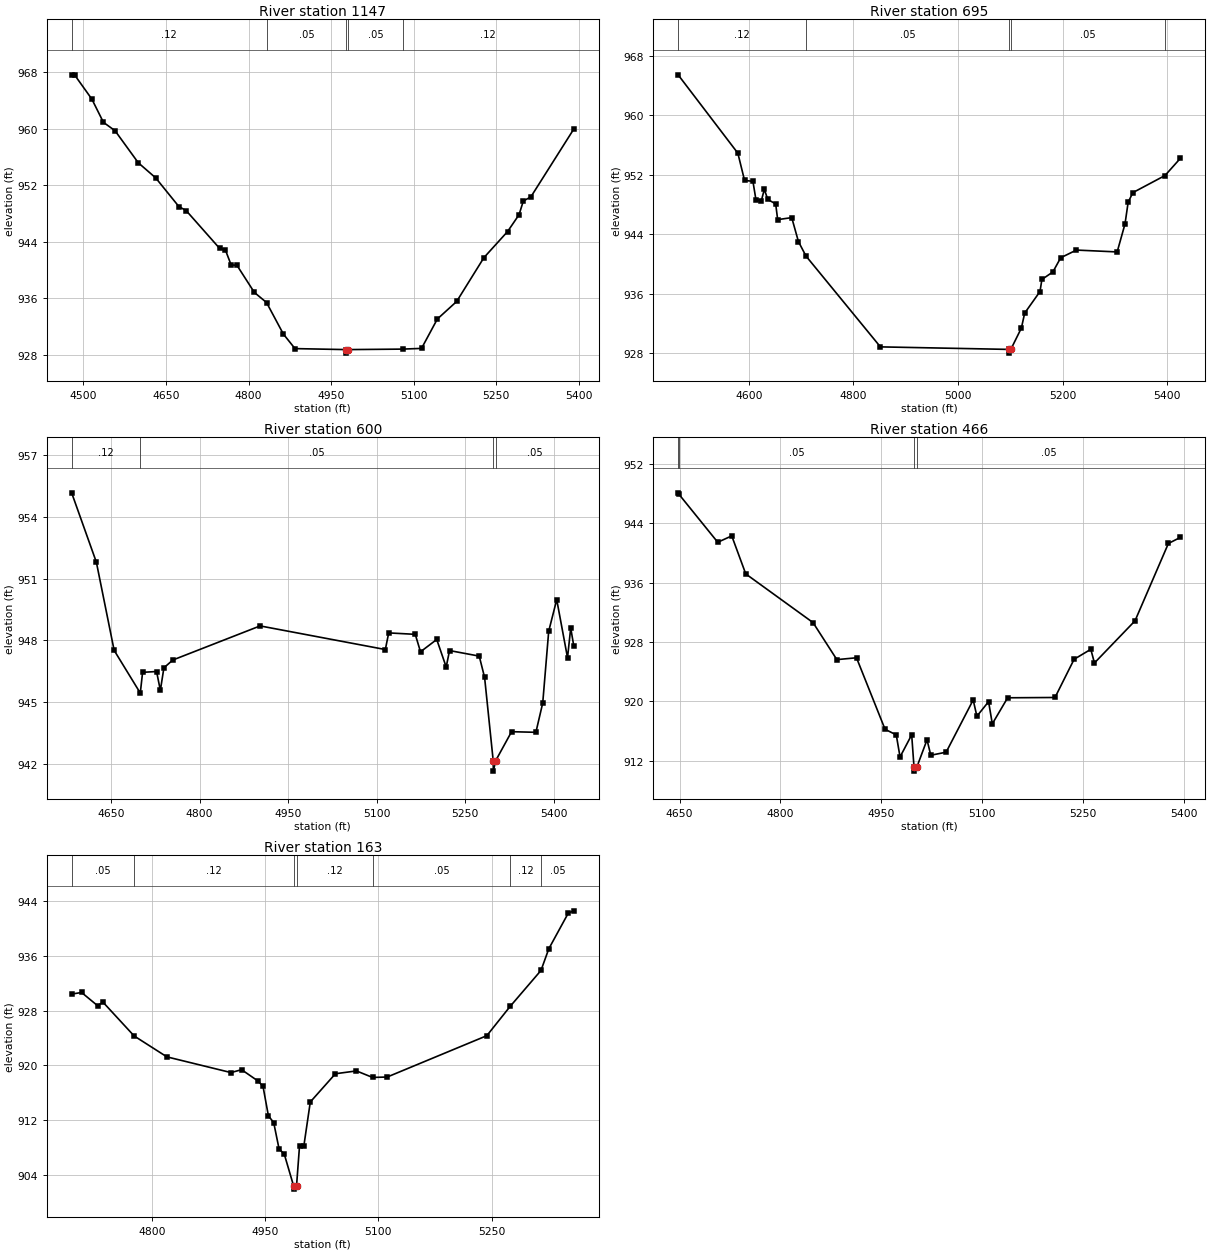
Type RM Length L Ch R = 1,1147,452,452,452
BEGIN DESCRIPTION:
MDE S 020 3.0
END DESCRIPTION:
XS GIS Cut Line= 4
      2250123.77      7174124.93      2249929.00      7174060.00
      2249629.00      7173960.00      2249329.04      7173710.03
#Sta/Elev= 30
  4478.7  967.67  4483.9  967.67  4515.4  964.23  4536.4  960.94  4557.5  959.75
  4599.7  955.21  4631.3  953.07  4673.5  949.00  4686.6  948.44  4747.3  943.09
  4757.8  942.88  4768.3  940.74  4778.9  940.68  4810.5  936.84  4832.6  935.41
  4863.2  930.94  4884.3  928.88  4977.2  928.74  4977.4  928.24  4981.2  928.74
  5079.7  928.81  5114.1  928.91  5142.8  933.07  5177.9  935.56  5227.4  941.77
  5270.3  945.46  5291.2  947.85  5299.0  949.80  5312.6  950.37  5390.7  960.00
#Mann=5,-1,0
  4478.7    0.12       0  4832.6    0.05       0  4977.2   0.033       0
  4981.2    0.05       0  5079.7    0.12       0
Bank Sta=4977.2,4981.2
Exp/Cntr=0.3,0.1

Type RM Length L Ch R = 1,695,95,95,95
BEGIN DESCRIPTION:
Mapping XS df0e6b5a
END DESCRIPTION:
XS GIS Cut Line= 5
      2250228.85      7173834.57      2250061.10      7173741.35
      2249842.43      7173619.84      2249616.85      7173512.82
      2249394.44      7173662.78
#Sta/Elev= 30
  4464.9  965.44  4579.1  954.91  4591.9  951.25  4607.9  951.13  4613.7  948.64
  4623.9  948.49  4629.7  950.05  4636.3  948.69  4651.4  948.09  4655.2  945.98
  4682.1  946.25  4694.9  943.03  4709.3  941.09  4851.6  928.88  5096.9  928.54
  5097.2  928.04  5100.9  928.54  5121.1  931.41  5127.4  933.42  5156.7  936.32
  5160.3  937.94  5181.3  938.95  5196.3  940.86  5226.3  941.89  5304.2  941.64
  5319.2  945.41  5325.2  948.32  5334.2  949.61  5395.7  951.91  5424.9  954.21
#Mann=5,-1,0
  4464.9    0.12       0  4709.3    0.05       0  5096.9   0.033       0
  5100.9    0.05       0  5395.7    0.12       0
Bank Sta=5096.9,5100.9
Exp/Cntr=0.3,0.1

Type RM Length L Ch R = 1,600,134,134,134
BEGIN DESCRIPTION:
Mapping XS 9c149cf8
END DESCRIPTION:
XS GIS Cut Line= 4
      2250179.24      7173727.85      2249985.03      7173600.08
      2249584.12      7173378.39      2249521.65      7173230.76
#Sta/Elev= 30
  4583.3  955.18  4625.2  951.80  4655.3  947.51  4699.6  945.43  4703.5  946.44
  4727.2  946.48  4733.6  945.56  4739.6  946.66  4754.7  947.04  4902.6  948.70
  5114.8  947.55  5120.5  948.36  5165.5  948.29  5174.4  947.44  5201.9  948.04
  5217.9  946.70  5223.6  947.50  5273.9  947.23  5283.0  946.19  5297.6  942.13
  5297.8  941.63  5301.6  942.13  5328.7  943.55  5369.9  943.52  5381.5  944.95
  5391.6  948.44  5405.2  949.98  5423.5  947.15  5428.9  948.60  5434.2  947.71
#Mann=4,-1,0
  4583.3    0.12       0  4699.6    0.05       0  5297.6   0.033       0
  5301.6    0.05       0
Bank Sta=5297.6,5301.6
Exp/Cntr=0.3,0.1

Type RM Length L Ch R = 1,466,303,303,303
BEGIN DESCRIPTION:
Mapping XS 30937213
END DESCRIPTION:
XS GIS Cut Line= 5
      2250166.82      7173593.58      2249936.42      7173420.27
      2249745.94      7173331.33      2249738.54      7173247.23
      2249585.80      7173189.33
#Sta/Elev= 30
  4647.9  948.11  4648.9  947.94  4706.8  941.45  4727.6  942.31  4748.4  937.19
  4848.4  930.63  4883.8  925.64  4913.0  925.89  4955.4  916.26  4972.1  915.50
  4977.7  912.53  4995.0  915.51  4998.5  911.12  4998.8  910.62  5002.5  911.12
  5017.8  914.84  5023.4  912.76  5046.2  913.17  5086.4  920.21  5091.9  918.02
  5109.3  919.98  5114.8  916.99  5137.6  920.50  5208.0  920.54  5236.4  925.69
  5261.2  927.03  5266.6  925.19  5326.9  930.87  5376.5  941.29  5394.2  942.10
#Mann=4,-1,0
  4647.9    0.12       0  4648.9    0.05       0  4998.5   0.033       0
  5002.5    0.05       0
Bank Sta=4998.5,5002.5
Exp/Cntr=0.3,0.1

Type RM Length L Ch R = 1,163,0,0,0
BEGIN DESCRIPTION:
MDE S 020 1.0
END DESCRIPTION:
XS GIS Cut Line= 3
      2250148.89      7173318.69      2249931.03      7173106.70
      2249576.38      7173176.31
#Sta/Elev= 30
  4693.6  930.41  4706.8  930.64  4727.9  928.72  4735.1  929.23  4776.4  924.30
  4819.8  921.25  4904.7  918.96  4918.8  919.38  4940.1  917.76  4947.1  916.98
  4954.3  912.65  4961.3  911.67  4968.4  907.84  4975.4  907.04  4987.6  902.46
  4987.8  901.96  4991.6  902.46  4995.5  908.21  5001.2  908.21  5009.8  914.67
  5043.1  918.79  5071.0  919.20  5092.3  918.25  5111.7  918.31  5243.7  924.34
  5274.6  928.61  5315.5  933.86  5325.8  937.01  5351.7  942.23  5359.0  942.55
#Mann=7,-1,0
  4693.6    0.05       0  4776.4    0.12       0  4987.6    0.07       0
  4991.6    0.12       0  5092.3    0.05       0  5274.6    0.12       0
  5315.5    0.05       0
Bank Sta=4987.6,4991.6
Exp/Cntr=0.3,0.1

Chan Stop Cuts=-1