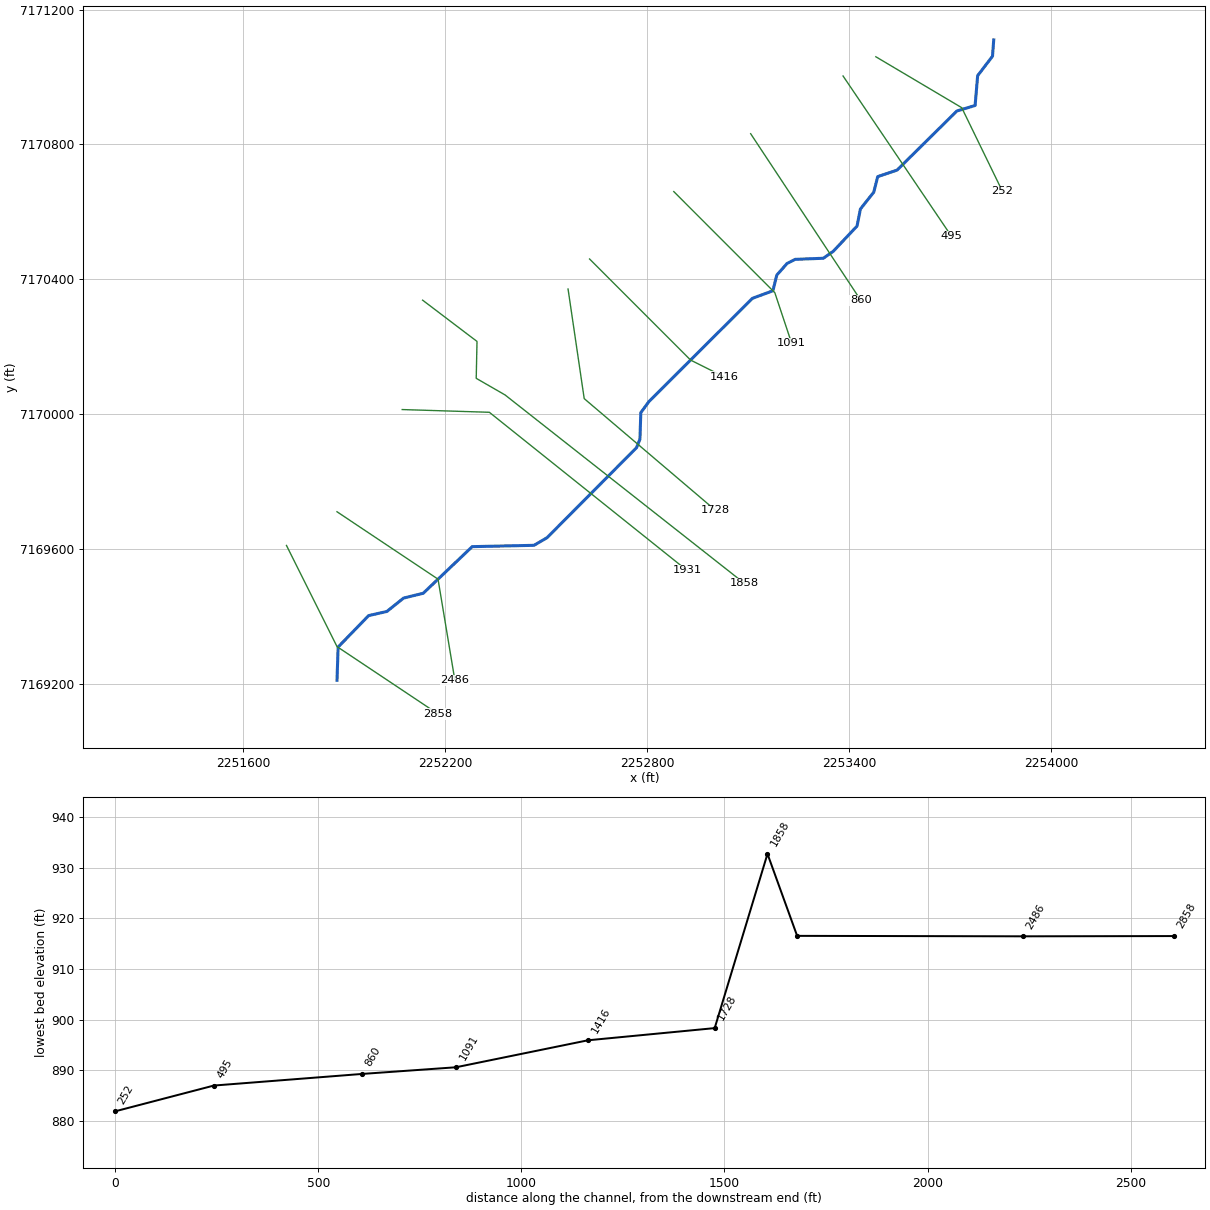
--- MDE S 021.prj (project) ---

Proj Title=MDE S 021 Base Level Engineering
Current Plan=p01
Default Exp/Contr=0.3,0.1
English Units
Geom File=g01
Flow File=f01
Plan File=p01
BEGIN DESCRIPTION:
MDE S 021
END DESCRIPTION:

--- MDE S 021.p01 (plan) ---

Plan Title=Multiple Run
Short Identifier=Multiple
Geom File=g01
Flow File=f01
Subcritical Flow
K Sum by GR= 0
Std Step Tol= 0.01
Critical Tol= 0.01
Num of Std Step Trials= 20
Max Error Tol= 0.3
Flow Tol Ratio= 0.001
Split Flow NTrial= 30
Split Flow Tol= 0.02
Split Flow Ratio= 0.02
Log Output Level= 0
Friction Slope Method= 1
Unsteady Friction Slope Method= 2
Unsteady Bridges Friction Slope Method= 1
Parabolic Critical Depth
Global Vel Dist=  1 , 1 , 1
Global Log Level= 0
CheckData=True
Encroach Param= -1, 0, 0, 0
BEGIN DESCRIPTION:
Multiple Run
END DESCRIPTION:

--- MDE S 021.f01 (steady flow) ---

Flow Title=Multiple
Number of Profiles=7
Profile Names=10-year,25-year,50-year,1pct_min,100-year,1pct_plu,500-year
River Rch & RM= MDE S 021,Reach-1,2858
     811    1143    1425     884    1763    3518    2702
Boundary for River Rch & Prof#=MDE S 021,Reach-1,1
Up Type=0
Dn Type=3
Dn Slope=0.007
Boundary for River Rch & Prof#=MDE S 021,Reach-1,2
Up Type=0
Dn Type=3
Dn Slope=0.007
Boundary for River Rch & Prof#=MDE S 021,Reach-1,3
Up Type=0
Dn Type=3
Dn Slope=0.007
Boundary for River Rch & Prof#=MDE S 021,Reach-1,4
Up Type=0
Dn Type=3
Dn Slope=0.007
Boundary for River Rch & Prof#=MDE S 021,Reach-1,5
Up Type=0
Dn Type=3
Dn Slope=0.007
Boundary for River Rch & Prof#=MDE S 021,Reach-1,6
Up Type=0
Dn Type=3
Dn Slope=0.007
Boundary for River Rch & Prof#=MDE S 021,Reach-1,7
Up Type=0
Dn Type=3
Dn Slope=0.007

--- MDE S 021.g01 (geometry) ---

Geom Title=Existing Conditions

River Reach=MDE S 021,Reach-1
Reach XY= 30
      2251879.00      7169210.00      2251882.38      7169308.61
      2251972.93      7169401.87      2252027.26      7169414.19
      2252076.81      7169453.90      2252135.06      7169468.14
      2252280.46      7169606.46      2252463.84      7169610.38
      2252502.53      7169632.86      2252768.48      7169900.21
      2252778.47      7169925.22      2252781.15      7170004.11
      2252805.18      7170036.87      2253112.52      7170343.27
      2253173.36      7170365.65      2253184.88      7170412.24
      2253215.37      7170446.67      2253239.34      7170458.88
      2253323.11      7170462.15      2253352.57      7170482.86
      2253423.17      7170557.69      2253433.18      7170608.29
      2253472.76      7170658.15      2253484.59      7170704.39
      2253541.98      7170723.73      2253719.62      7170899.10
      2253773.75      7170915.47      2253781.27      7171003.98
      2253825.36      7171061.50      2253829.00      7171110.00

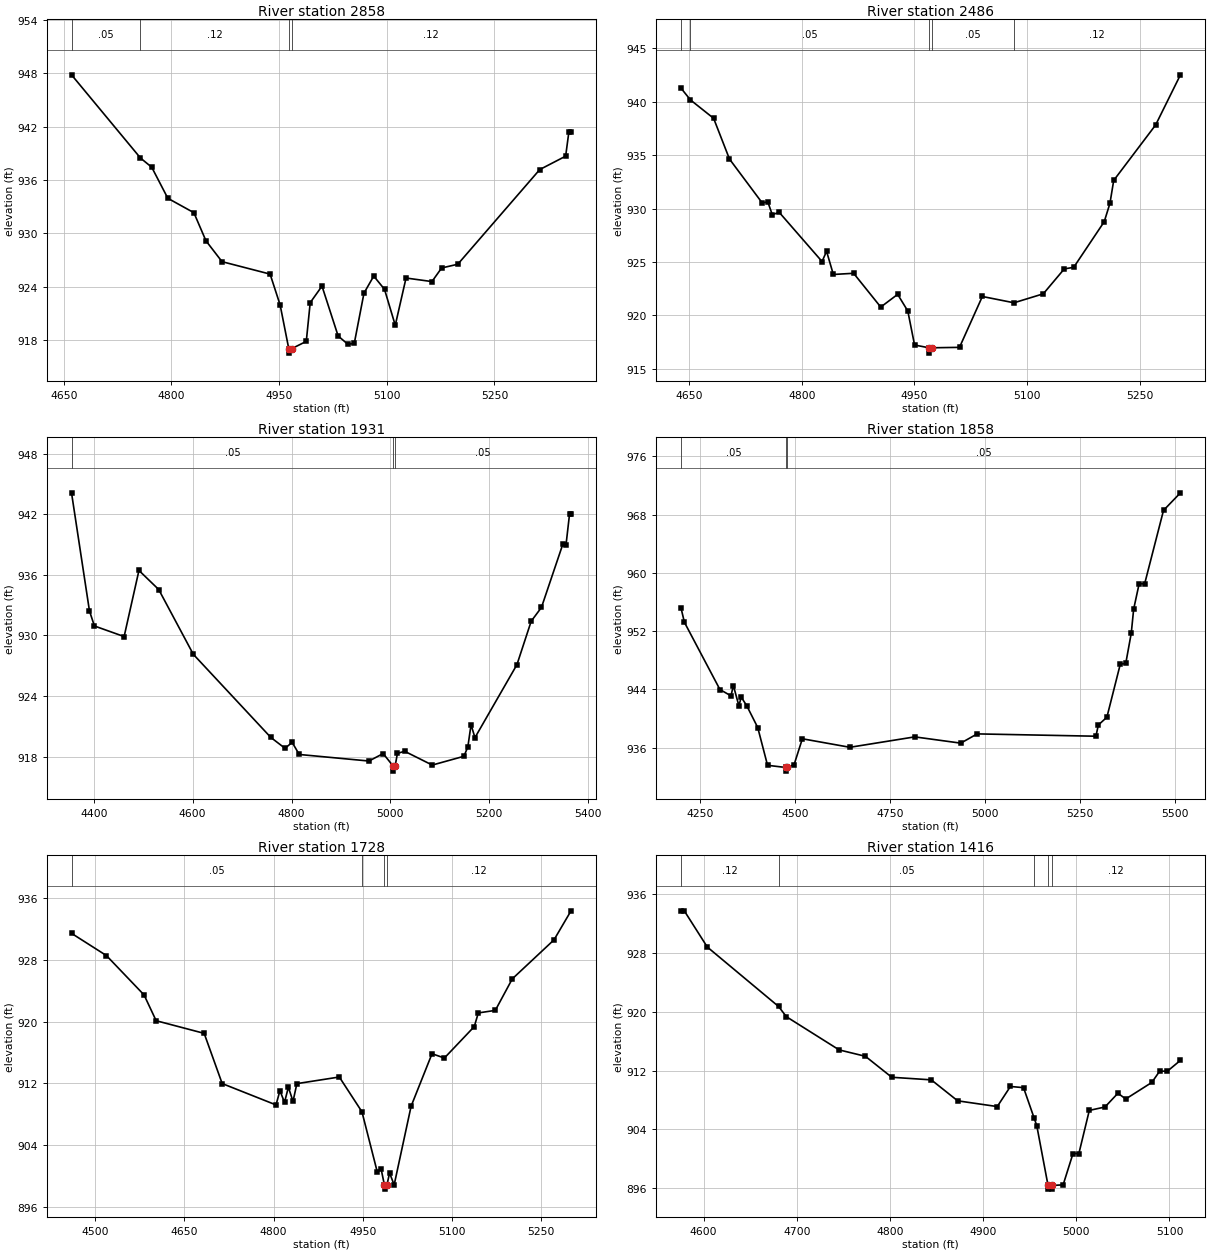
Type RM Length L Ch R = 1,2858,372,372,372
BEGIN DESCRIPTION:
MDE S 021 8.0
END DESCRIPTION:
XS GIS Cut Line= 3
      2251728.99      7169610.02      2251879.00      7169310.00
      2252179.01      7169110.00
#Sta/Elev= 30
  4660.8  947.83  4756.9  938.47  4772.6  937.43  4795.0  933.94  4831.3  932.32
  4848.1  929.16  4870.5  926.81  4937.5  925.41  4951.5  921.93  4963.5  917.02
  4963.7  916.52  4967.5  917.02  4987.9  917.84  4993.4  922.20  5009.8  924.06
  5032.3  918.45  5045.8  917.52  5054.8  917.62  5068.3  923.27  5081.9  925.19
  5096.9  923.70  5111.9  919.65  5126.9  924.97  5163.0  924.57  5176.5  926.10
  5199.0  926.52  5313.2  937.17  5349.3  938.68  5353.8  941.41  5356.8  941.41
#Mann=4,-1,0
  4660.8    0.05       0  4756.9    0.12       0  4963.5    0.07       0
  4967.5    0.12       0
Bank Sta=4963.5,4967.5
Exp/Cntr=0.3,0.1

Type RM Length L Ch R = 1,2486,555,555,555
BEGIN DESCRIPTION:
MDE S 021 7.0
END DESCRIPTION:
XS GIS Cut Line= 3
      2251879.03      7169709.98      2252179.00      7169510.00
      2252229.01      7169209.96
#Sta/Elev= 30
  4639.2  941.27  4651.9  940.16  4682.7  938.44  4703.8  934.63  4747.3  930.53
  4754.8  930.62  4760.8  929.42  4769.9  929.65  4827.0  925.04  4833.0  926.00
  4842.0  923.83  4869.0  923.94  4905.1  920.78  4927.6  921.97  4941.1  920.41
  4950.1  917.23  4969.2  916.97  4969.4  916.47  4973.2  916.97  5009.9  917.01
  5040.3  921.77  5082.4  921.18  5121.4  922.02  5149.3  924.35  5161.9  924.50
  5202.5  928.77  5210.1  930.49  5215.1  932.63  5270.9  937.82  5303.9  942.51
#Mann=5,-1,0
  4639.2    0.12       0  4651.9    0.05       0  4969.2   0.033       0
  4973.2    0.05       0  5082.4    0.12       0
Bank Sta=4969.2,4973.2
Exp/Cntr=0.3,0.1

Type RM Length L Ch R = 1,1931,73,73,73
BEGIN DESCRIPTION:
Mapping XS 7cb59613
END DESCRIPTION:
XS GIS Cut Line= 3
      2252072.68      7170013.23      2252331.43      7170005.13
      2252918.45      7169535.87
#Sta/Elev= 30
  4355.0  944.13  4391.3  932.43  4401.3  930.94  4461.4  929.89  4491.4  936.44
  4531.4  934.55  4601.4  928.13  4758.1  919.90  4786.9  918.82  4801.3  919.41
  4815.6  918.21  4956.6  917.56  4985.4  918.30  5005.6  917.06  5005.9  916.56
  5009.6  917.06  5014.2  918.31  5028.7  918.53  5084.7  917.16  5148.7  918.03
  5156.7  918.96  5163.1  921.15  5171.1  919.88  5256.0  927.11  5284.8  931.41
  5305.6  932.78  5348.8  939.04  5355.2  938.95  5362.5  942.07  5365.4  942.07
#Mann=3,-1,0
  4355.0    0.05       0  5005.6   0.033       0  5009.6    0.05       0
Bank Sta=5005.6,5009.6
Exp/Cntr=0.3,0.1

Type RM Length L Ch R = 1,1858,130,130,130
BEGIN DESCRIPTION:
Mapping XS 5315616a
END DESCRIPTION:
XS GIS Cut Line= 5
      2252133.20      7170337.85      2252294.75      7170215.35
      2252292.39      7170105.92      2252378.03      7170056.59
      2253088.92      7169497.38
#Sta/Elev= 30
  4199.0  955.23  4208.1  953.22  4301.7  943.99  4330.8  943.12  4337.1  944.53
  4351.6  941.77  4357.9  942.94  4372.5  941.75  4401.3  938.77  4427.1  933.59
  4475.1  933.29  4475.4  932.79  4479.1  933.29  4497.1  933.69  4518.8  937.23
  4644.0  936.06  4814.8  937.49  4935.9  936.63  4979.2  937.90  5291.9  937.58
  5298.3  939.12  5320.8  940.19  5356.1  947.47  5370.5  947.57  5385.0  951.73
  5391.3  955.02  5405.8  958.52  5420.2  958.49  5469.9  968.57  5514.5  970.98
#Mann=3,-1,0
  4199.0    0.05       0  4475.1   0.033       0  4479.1    0.05       0
Bank Sta=4475.1,4479.1
Exp/Cntr=0.3,0.1

Type RM Length L Ch R = 1,1728,312,312,312
BEGIN DESCRIPTION:
Mapping XS 116c7ec0
END DESCRIPTION:
XS GIS Cut Line= 3
      2252565.10      7170370.83      2252613.04      7170045.71
      2253003.01      7169714.15
#Sta/Elev= 30
  4460.0  931.47  4518.7  928.59  4582.1  923.48  4602.4  920.14  4683.2  918.50
  4713.5  911.99  4804.1  909.22  4810.7  911.07  4818.4  909.55  4824.9  911.52
  4832.7  909.68  4839.2  911.98  4910.6  912.84  4948.7  908.33  4974.3  900.58
  4980.9  900.92  4986.6  898.80  4986.9  898.30  4990.6  898.80  4995.2  900.39
  5002.9  898.85  5031.4  909.05  5066.6  915.86  5087.4  915.30  5137.7  919.38
  5144.5  921.15  5173.1  921.48  5201.7  925.57  5271.9  930.63  5300.5  934.39
#Mann=4,-1,0
  4460.0    0.05       0  4948.7    0.12       0  4986.6    0.07       0
  4990.6    0.12       0
Bank Sta=4986.6,4990.6
Exp/Cntr=0.3,0.1

Type RM Length L Ch R = 1,1416,325,325,325
BEGIN DESCRIPTION:
MDE S 021 4.0
END DESCRIPTION:
XS GIS Cut Line= 3
      2252628.97      7170460.03      2252929.00      7170160.00
      2253028.99      7170110.01
#Sta/Elev= 30
  4575.7  933.71  4579.3  933.71  4604.0  928.79  4680.5  920.71  4688.9  919.32
  4745.5  914.81  4773.7  913.94  4802.0  911.09  4844.4  910.74  4872.7  907.89
  4915.2  907.11  4929.3  909.84  4943.4  909.68  4954.8  905.54  4957.6  904.52
  4969.7  896.39  4970.0  895.89  4973.5  895.89  4973.7  896.39  4985.9  896.47
  4996.5  900.73  5002.8  900.73  5014.0  906.59  5030.8  907.05  5044.7  908.92
  5053.1  908.14  5081.1  910.39  5089.5  911.92  5097.8  911.92  5111.8  913.39
#Mann=5,-1,0
  4575.7    0.12       0  4680.5    0.05       0  4954.8    0.12       0
  4969.7    0.07       0  4973.7    0.12       0
Bank Sta=4969.7,4973.7
Exp/Cntr=0.3,0.1

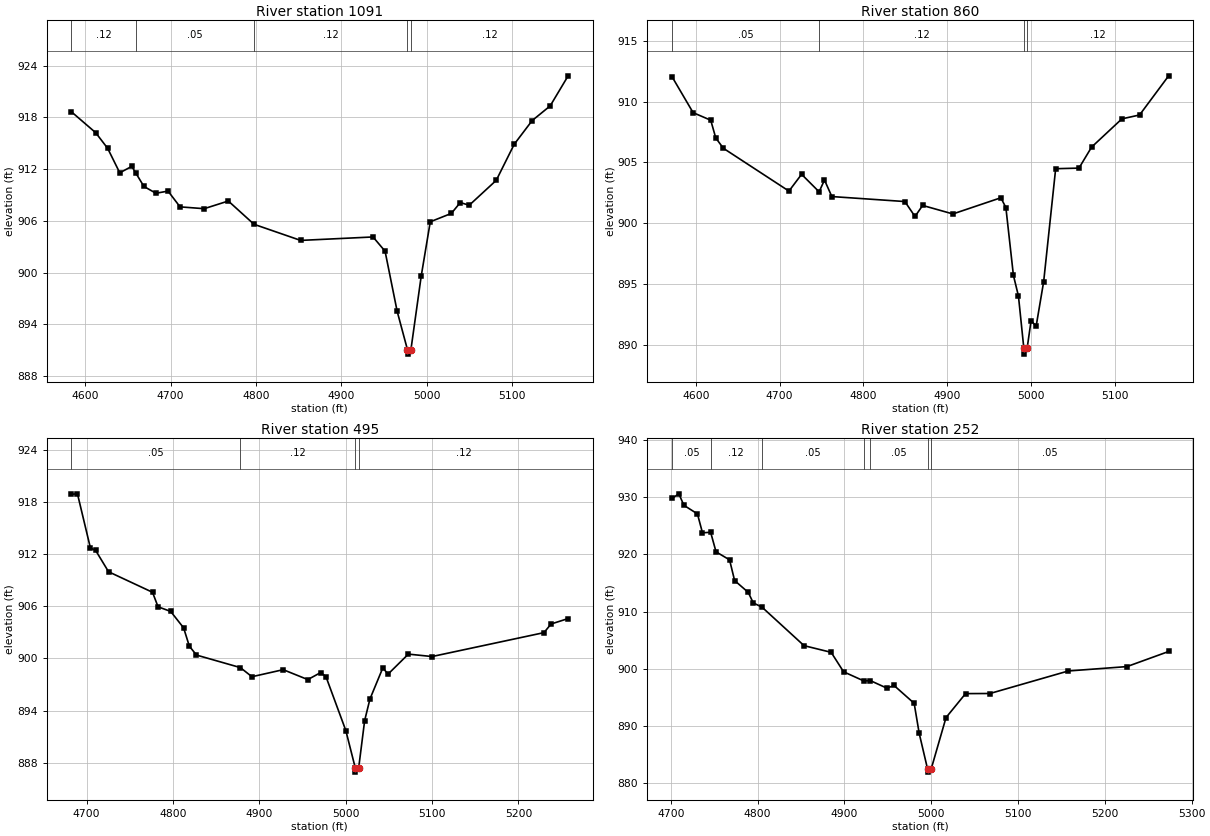
Type RM Length L Ch R = 1,1091,231,231,231
BEGIN DESCRIPTION:
MDE S 021 3.0
END DESCRIPTION:
XS GIS Cut Line= 3
      2252878.99      7170660.01      2253179.00      7170360.00
      2253229.00      7170210.00
#Sta/Elev= 30
  4583.7  918.65  4612.0  916.24  4626.1  914.42  4640.3  911.58  4654.4  912.33
  4658.9  911.59  4668.6  910.00  4682.7  909.21  4696.9  909.46  4711.0  907.63
  4739.3  907.42  4767.6  908.31  4797.7  905.61  4852.4  903.74  4937.3  904.14
  4951.4  902.49  4965.6  895.51  4977.7  891.05  4978.0  890.55  4981.7  891.05
  4993.8  899.61  5004.4  905.90  5029.1  906.87  5039.6  908.13  5050.1  907.82
  5081.8  910.71  5102.9  914.90  5123.9  917.64  5145.0  919.34  5166.1  922.83
#Mann=5,-1,0
  4583.7    0.12       0  4658.9    0.05       0  4797.7    0.12       0
  4977.7    0.07       0  4981.7    0.12       0
Bank Sta=4977.7,4981.7
Exp/Cntr=0.3,0.1

Type RM Length L Ch R = 1,860,365,365,365
BEGIN DESCRIPTION:
Mapping XS 183f73c9
END DESCRIPTION:
XS GIS Cut Line= 2
      2253107.28      7170831.71      2253434.18      7170337.56
#Sta/Elev= 30
  4571.7  912.05  4596.9  909.09  4617.9  908.47  4623.9  907.01  4633.0  906.16
  4711.2  902.64  4726.3  904.02  4747.2  902.58  4753.6  903.55  4762.4  902.19
  4849.5  901.78  4861.6  900.55  4870.7  901.46  4906.8  900.76  4964.0  902.09
  4970.0  901.29  4979.0  895.71  4985.0  894.01  4991.4  889.73  4991.7  889.23
  4995.4  889.73  5000.1  891.99  5006.1  891.52  5015.1  895.20  5029.4  904.48
  5057.2  904.53  5072.3  906.26  5108.4  908.58  5129.5  908.90  5164.2  912.12
#Mann=4,-1,0
  4571.7    0.05       0  4747.2    0.12       0  4991.4    0.07       0
  4995.4    0.12       0
Bank Sta=4991.4,4995.4
Exp/Cntr=0.3,0.1

Type RM Length L Ch R = 1,495,243,243,243
BEGIN DESCRIPTION:
MAPPING XS 916B019
END DESCRIPTION:
XS GIS Cut Line= 2
      2253381.62      7171002.99      2253703.93      7170526.82
#Sta/Elev= 30
  4682.6  918.88  4689.5  918.93  4704.5  912.70  4710.5  912.43  4725.5  909.97
  4776.4  907.61  4782.8  905.94  4797.4  905.41  4812.4  903.52  4819.0  901.42
  4827.3  900.39  4878.1  898.95  4891.5  897.90  4927.7  898.71  4956.2  897.57
  4971.1  898.38  4977.2  897.91  5000.2  891.71  5011.1  887.43  5011.4  886.93
  5015.1  887.43  5022.0  892.86  5028.1  895.33  5043.0  898.91  5049.1  898.20
  5072.6  900.50  5100.0  900.22  5229.6  902.97  5237.8  903.96  5257.6  904.59
#Mann=4,-1,0
  4682.6    0.05       0  4878.1    0.12       0  5011.1    0.07       0
  5015.1    0.12       0
Bank Sta=5011.1,5015.1
Exp/Cntr=0.3,0.1

Type RM Length L Ch R = 1,252,0,0,0
BEGIN DESCRIPTION:
MDE S 021 1.0
END DESCRIPTION:
XS GIS Cut Line= 3
      2253478.97      7171060.02      2253734.00      7170908.94
      2253854.65      7170661.18
#Sta/Elev= 30
  4701.5  929.84  4709.4  930.64  4715.2  928.63  4730.8  927.12  4736.6  923.80
  4746.0  923.90  4752.2  920.47  4767.8  919.06  4773.6  915.43  4789.3  913.36
  4795.1  911.51  4805.2  910.76  4853.6  904.01  4884.8  902.84  4899.1  899.43
  4922.2  897.84  4930.1  897.87  4949.1  896.55  4957.2  897.03  4980.4  893.90
  4986.2  888.63  4995.9  882.33  4996.2  881.83  4999.9  882.33  5017.1  891.40
  5039.6  895.60  5067.7  895.62  5157.9  899.57  5225.5  900.34  5273.5  902.99
#Mann=7,-1,0
  4701.5    0.05       0  4746.0    0.12       0  4805.2    0.05       0
  4922.2    0.12       0  4930.1    0.05       0  4995.9   0.033       0
  4999.9    0.05       0
Bank Sta=4995.9,4999.9
Exp/Cntr=0.3,0.1

Chan Stop Cuts=-1