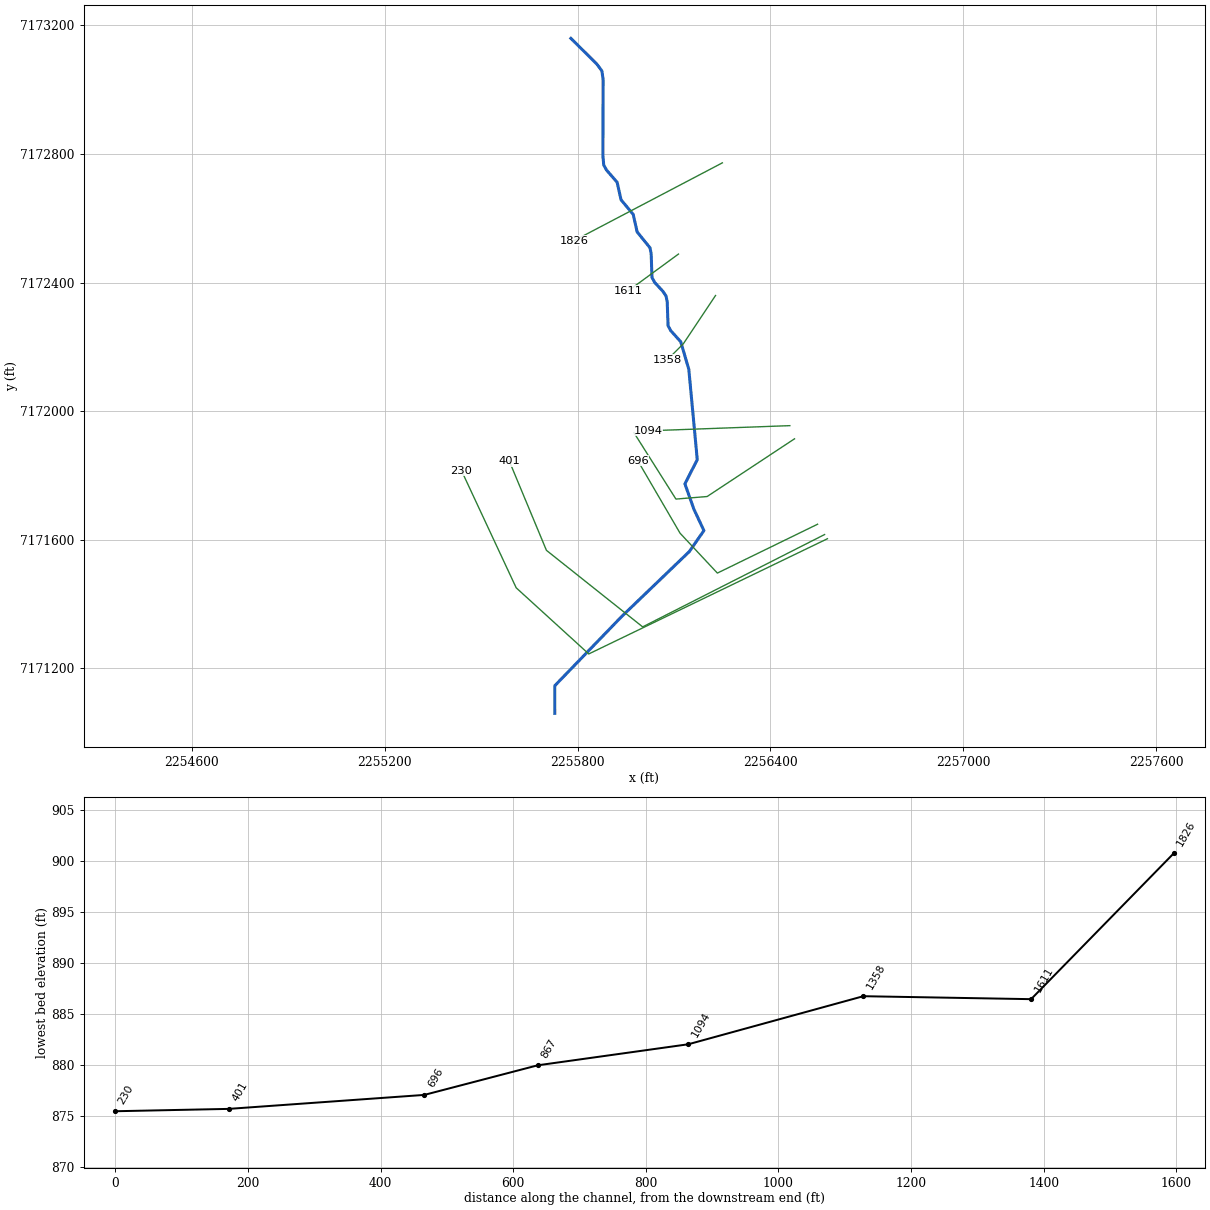
--- MDE S 022.prj (project) ---

Proj Title=MDE S 022 Base Level Engineering
Current Plan=p01
Default Exp/Contr=0.3,0.1
English Units
Geom File=g01
Flow File=f01
Plan File=p01
BEGIN DESCRIPTION:
MDE S 022
END DESCRIPTION:

--- MDE S 022.p01 (plan) ---

Plan Title=Multiple Run
Short Identifier=Multiple
Geom File=g01
Flow File=f01
Subcritical Flow
K Sum by GR= 0
Std Step Tol= 0.01
Critical Tol= 0.01
Num of Std Step Trials= 20
Max Error Tol= 0.3
Flow Tol Ratio= 0.001
Split Flow NTrial= 30
Split Flow Tol= 0.02
Split Flow Ratio= 0.02
Log Output Level= 0
Friction Slope Method= 1
Unsteady Friction Slope Method= 2
Unsteady Bridges Friction Slope Method= 1
Parabolic Critical Depth
Global Vel Dist=  1 , 1 , 1
Global Log Level= 0
CheckData=True
Encroach Param= -1, 0, 0, 0
BEGIN DESCRIPTION:
Multiple Run
END DESCRIPTION:

--- MDE S 022.f01 (steady flow) ---

Flow Title=Multiple
Number of Profiles=7
Profile Names=10-year,25-year,50-year,1pct_min,100-year,1pct_plu,500-year
River Rch & RM= MDE S 022,Reach-1,1826
     590     815    1002     613    1223    2440    1824
River Rch & RM= MDE S 022,Reach-1,401
     604     835    1028     629    1255    2505    1876
Boundary for River Rch & Prof#=MDE S 022,Reach-1,1
Up Type=0
Dn Type=3
Dn Slope=0.005
Boundary for River Rch & Prof#=MDE S 022,Reach-1,2
Up Type=0
Dn Type=3
Dn Slope=0.005
Boundary for River Rch & Prof#=MDE S 022,Reach-1,3
Up Type=0
Dn Type=3
Dn Slope=0.005
Boundary for River Rch & Prof#=MDE S 022,Reach-1,4
Up Type=0
Dn Type=3
Dn Slope=0.005
Boundary for River Rch & Prof#=MDE S 022,Reach-1,5
Up Type=0
Dn Type=3
Dn Slope=0.005
Boundary for River Rch & Prof#=MDE S 022,Reach-1,6
Up Type=0
Dn Type=3
Dn Slope=0.005
Boundary for River Rch & Prof#=MDE S 022,Reach-1,7
Up Type=0
Dn Type=3
Dn Slope=0.005

--- MDE S 022.g01 (geometry) ---

Geom Title=Existing Conditions

River Reach=MDE S 022,Reach-1
Reach XY= 30
      2255779.00      7173160.00      2255859.50      7173080.21
      2255875.52      7173058.56      2255879.43      7173030.18
      2255878.56      7172794.82      2255881.24      7172765.93
      2255889.80      7172750.33      2255922.88      7172712.18
      2255935.08      7172657.80      2255972.92      7172612.20
      2255985.12      7172557.82      2256025.17      7172508.42
      2256028.77      7172489.91      2256031.35      7172415.97
      2256039.89      7172400.37      2256065.18      7172373.13
      2256075.15      7172358.40      2256078.76      7172339.90
      2256081.36      7172265.98      2256089.89      7172250.37
      2256120.72      7172216.24      2256145.88      7172130.46
      2256172.19      7171849.24      2256133.78      7171773.97
      2256161.68      7171695.25      2256192.87      7171628.71
      2256147.56      7171563.51      2255936.92      7171361.16
      2255728.94      7171145.99      2255729.00      7171060.00

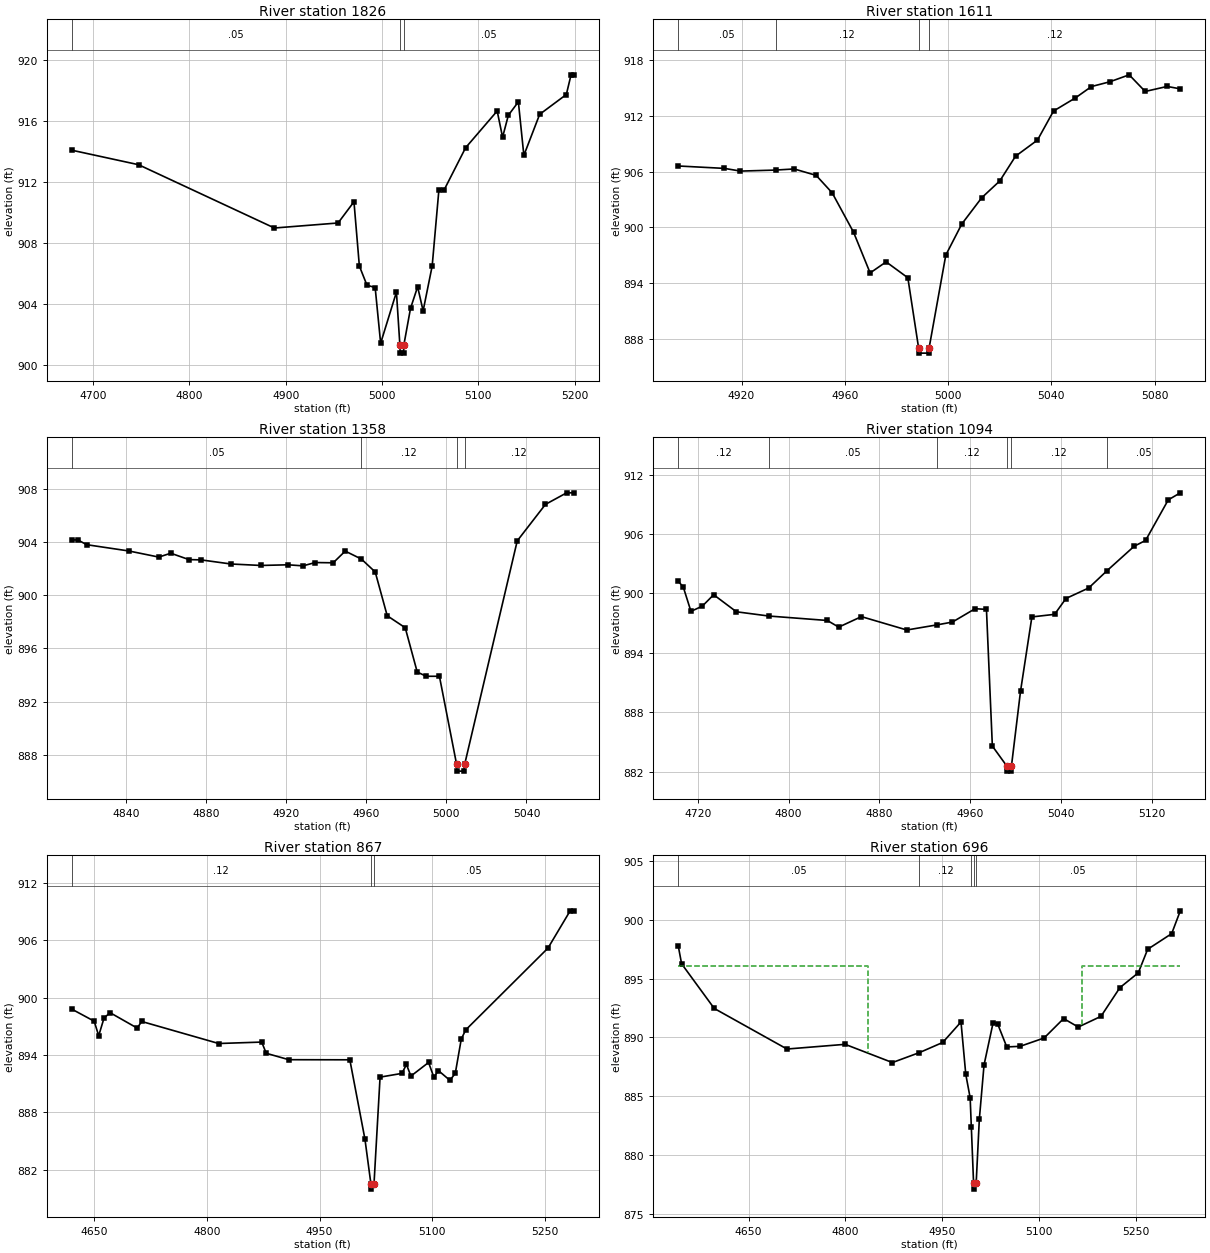
Type RM Length L Ch R = 1,1826,215,215,215
BEGIN DESCRIPTION:
Mapping XS d760ccd5
END DESCRIPTION:
XS GIS Cut Line= 2
      2256250.40      7172772.70      2255788.78      7172530.49
#Sta/Elev= 30
  4677.8  914.06  4747.1  913.11  4888.2  908.96  4954.3  909.29  4970.8  910.68
  4976.4  906.47  4984.3  905.21  4992.8  905.06  4998.5  901.41  5014.9  904.76
  5018.5  901.26  5018.8  900.76  5022.3  900.76  5022.5  901.26  5029.5  903.69
  5036.9  905.11  5042.6  903.53  5052.0  906.47  5059.0  911.47  5064.6  911.48
  5086.7  914.22  5119.5  916.63  5125.1  914.91  5131.1  916.35  5141.5  917.23
  5147.2  913.72  5163.6  916.41  5191.3  917.71  5196.2  919.00  5199.1  919.00
#Mann=3,-1,0
  4677.8    0.05       0  5018.5   0.033       0  5022.5    0.05       0
Bank Sta=5018.5,5022.5
Exp/Cntr=0.3,0.1

Type RM Length L Ch R = 1,1611,253,253,253
BEGIN DESCRIPTION:
Mapping XS 69714665
END DESCRIPTION:
XS GIS Cut Line= 2
      2256113.82      7172488.94      2255956.94      7172374.14
#Sta/Elev= 29
  4895.5  906.62  4913.4  906.36  4919.6  906.07  4933.2  906.18  4940.4  906.30
  4948.9  905.61  4955.1  903.73  4963.4  899.48  4969.8  895.11  4976.0  896.30
  4984.4  894.59  4988.6  886.98  4988.9  886.48  4992.4  886.48  4992.6  886.98
  4999.1  897.03  5005.3  900.38  5013.0  903.20  5020.0  905.01  5026.1  907.67
  5034.6  909.41  5040.8  912.53  5049.3  913.95  5055.5  915.17  5062.6  915.68
  5070.1  916.43  5076.3  914.64  5084.8  915.18  5089.9  914.92
#Mann=4,-1,0
  4895.5    0.05       0  4933.2    0.12       0  4988.6    0.07       0
  4992.6    0.12       0
Bank Sta=4988.6,4992.6
Exp/Cntr=0.3,0.1

Type RM Length L Ch R = 1,1358,264,264,264
BEGIN DESCRIPTION:
MDE S 022 2.0
END DESCRIPTION:
XS GIS Cut Line= 3
      2256228.98      7172359.97      2256129.00      7172210.00
      2256078.97      7172159.97
#Sta/Elev= 30
  4812.7  904.15  4815.7  904.15  4820.2  903.79  4841.2  903.32  4856.2  902.86
  4862.2  903.15  4871.3  902.67  4877.3  902.65  4892.3  902.34  4907.3  902.23
  4920.8  902.28  4928.3  902.20  4934.4  902.45  4943.4  902.43  4949.4  903.31
  4957.5  902.71  4964.4  901.74  4970.4  898.45  4979.4  897.55  4985.4  894.22
  4989.9  893.90  4996.5  893.90  5005.1  887.27  5005.3  886.77  5008.8  886.77
  5009.1  887.27  5035.4  904.08  5049.5  906.82  5060.1  907.69  5063.7  907.69
#Mann=4,-1,0
  4812.7    0.05       0  4957.5    0.12       0  5005.1    0.07       0
  5009.1    0.12       0
Bank Sta=5005.1,5009.1
Exp/Cntr=0.3,0.1

Type RM Length L Ch R = 1,1094,227,227,227
BEGIN DESCRIPTION:
Mapping XS 27da110d
END DESCRIPTION:
XS GIS Cut Line= 2
      2256460.20      7171955.09      2256018.40      7171938.98
#Sta/Elev= 30
  4702.9  901.23  4707.3  900.66  4714.1  898.19  4724.1  898.72  4734.1  899.87
  4754.1  898.15  4782.7  897.72  4834.2  897.27  4844.2  896.60  4864.2  897.66
  4904.2  896.31  4930.4  896.82  4944.3  897.11  4964.3  898.46  4974.3  898.39
  4979.5  884.59  4992.3  882.56  4992.5  882.06  4996.0  882.06  4996.3  882.56
  5004.3  890.13  5014.3  897.63  5034.3  897.89  5044.3  899.49  5064.3  900.55
  5080.4  902.29  5104.4  904.77  5114.4  905.35  5134.4  909.45  5145.0  910.16
#Mann=6,-1,0
  4702.9    0.12       0  4782.7    0.05       0  4930.4    0.12       0
  4992.3    0.07       0  4996.3    0.12       0  5080.4    0.05       0
Bank Sta=4992.3,4996.3
Exp/Cntr=0.3,0.1

Type RM Length L Ch R = 1,867,171,171,171
BEGIN DESCRIPTION:
Mapping XS f10fec47
END DESCRIPTION:
XS GIS Cut Line= 4
      2256474.77      7171914.16      2256202.87      7171734.62
      2256105.83      7171726.67      2255975.14      7171933.31
#Sta/Elev= 30
  4620.4  898.79  4650.2  897.53  4656.2  896.01  4663.3  897.86  4671.3  898.42
  4707.4  896.81  4713.4  897.50  4815.8  895.20  4873.0  895.35  4879.0  894.18
  4909.1  893.51  4990.2  893.50  5010.3  885.21  5018.3  880.50  5018.6  880.00
  5022.3  880.50  5030.4  891.69  5059.4  892.08  5065.5  893.01  5071.4  891.80
  5094.9  893.22  5102.0  891.67  5107.9  892.38  5123.2  891.36  5130.4  892.07
  5138.4  895.67  5144.3  896.62  5253.7  905.16  5283.2  909.05  5288.1  909.05
#Mann=3,-1,0
  4620.4    0.12       0  5018.3    0.07       0  5022.3    0.05       0
Bank Sta=5018.3,5022.3
Exp/Cntr=0.3,0.1

Type RM Length L Ch R = 1,696,295,295,295
BEGIN DESCRIPTION:
Mapping XS cbe8c36f
END DESCRIPTION:
XS GIS Cut Line= 4
      2256546.38      7171648.39      2256234.73      7171496.42
      2256118.67      7171620.53      2255987.06      7171846.21
#Sta/Elev= 30
  4540.9  897.78  4546.1  896.26  4596.7  892.46  4709.4  889.01  4799.5  889.41
  4872.7  887.86  4914.7  888.71  4950.7  889.57  4979.0  891.31  4986.4  886.86
  4993.2  884.86  4995.0  882.39  4998.5  877.60  4998.8  877.10  5002.5  877.60
  5007.4  883.03  5014.7  887.66  5028.8  891.26  5035.7  891.16  5049.9  889.19
  5070.6  889.24  5107.8  889.95  5138.0  891.60  5160.7  890.88  5195.9  891.79
  5225.2  894.23  5253.7  895.49  5268.2  897.49  5305.4  898.82  5318.8  900.76
#Mann=5,-1,0
  4540.9    0.05       0  4914.7    0.12       0  4995.0    0.05       0
  4998.5    0.07       0  5002.5    0.05       0
#XS Ineff=2,0
    0.00 4834.20  896.10 5165.80    0.00  896.10
Permanent Ineff=
       F       F
Bank Sta=4998.5,5002.5
Exp/Cntr=0.3,0.1

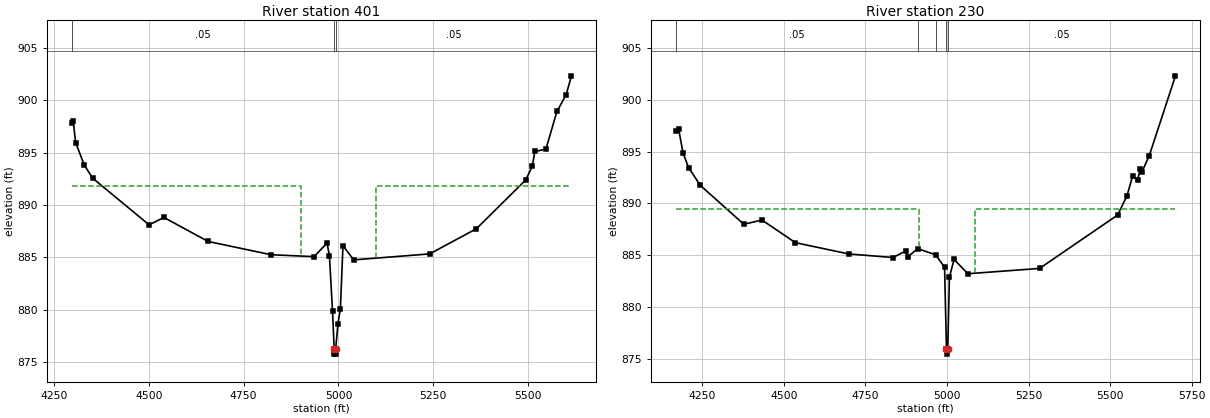
Type RM Length L Ch R = 1,401,171,171,171
BEGIN DESCRIPTION:
Mapping XS fb61e829
END DESCRIPTION:
XS GIS Cut Line= 4
      2256568.32      7171616.36      2256002.37      7171329.06
      2255702.95      7171567.22      2255587.22      7171845.32
#Sta/Elev= 30
  4296.2  897.82  4300.1  898.06  4306.7  895.98  4329.1  893.85  4351.5  892.57
  4500.5  888.10  4539.4  888.81  4656.3  886.51  4822.5  885.24  4935.7  885.06
  4969.9  886.36  4976.2  885.13  4984.3  879.87  4988.7  876.23  4988.9  875.73
  4992.4  875.73  4992.7  876.23  4998.7  878.64  5005.1  880.05  5011.9  886.11
  5040.3  884.75  5240.6  885.32  5364.0  887.73  5494.1  892.40  5511.5  893.72
  5517.9  895.12  5547.2  895.34  5576.4  898.96  5600.3  900.52  5614.7  902.36
#Mann=3,-1,0
  4296.2    0.05       0  4988.7    0.07       0  4992.7    0.05       0
#XS Ineff=2,0
    0.00 4901.40  891.83 5098.60    0.00  891.83
Permanent Ineff=
       F       F
Bank Sta=4988.7,4992.7
Exp/Cntr=0.3,0.1

Type RM Length L Ch R = 1,230,0,0,0
BEGIN DESCRIPTION:
MDE S 022 1.0
END DESCRIPTION:
XS GIS Cut Line= 4
      2256577.22      7171603.32      2255834.66      7171244.91
      2255608.86      7171450.68      2255438.76      7171815.11
#Sta/Elev= 30
  4168.2  897.01  4177.3  897.19  4190.7  894.88  4207.7  893.46  4244.0  891.74
  4377.2  888.00  4432.7  888.41  4535.3  886.23  4699.2  885.14  4834.8  884.80
  4874.4  885.45  4880.0  884.88  4910.3  885.65  4965.5  885.06  4992.6  883.85
  4998.4  876.00  4998.6  875.50  5002.4  876.00  5007.4  882.90  5021.6  884.61
  5064.2  883.24  5283.8  883.75  5523.1  888.89  5551.5  890.72  5568.8  892.61
  5584.4  892.24  5591.7  893.30  5597.2  893.01  5620.1  894.61  5700.4  902.29
#Mann=5,-1,0
  4168.2    0.05       0  4910.3    0.12       0  4965.5    0.05       0
  4998.4    0.07       0  5002.4    0.05       0
#XS Ineff=2,0
    0.00 4913.40  889.50 5086.60    0.00  889.50
Permanent Ineff=
       F       F
Bank Sta=4998.4,5002.4
Exp/Cntr=0.3,0.1

Chan Stop Cuts=-1