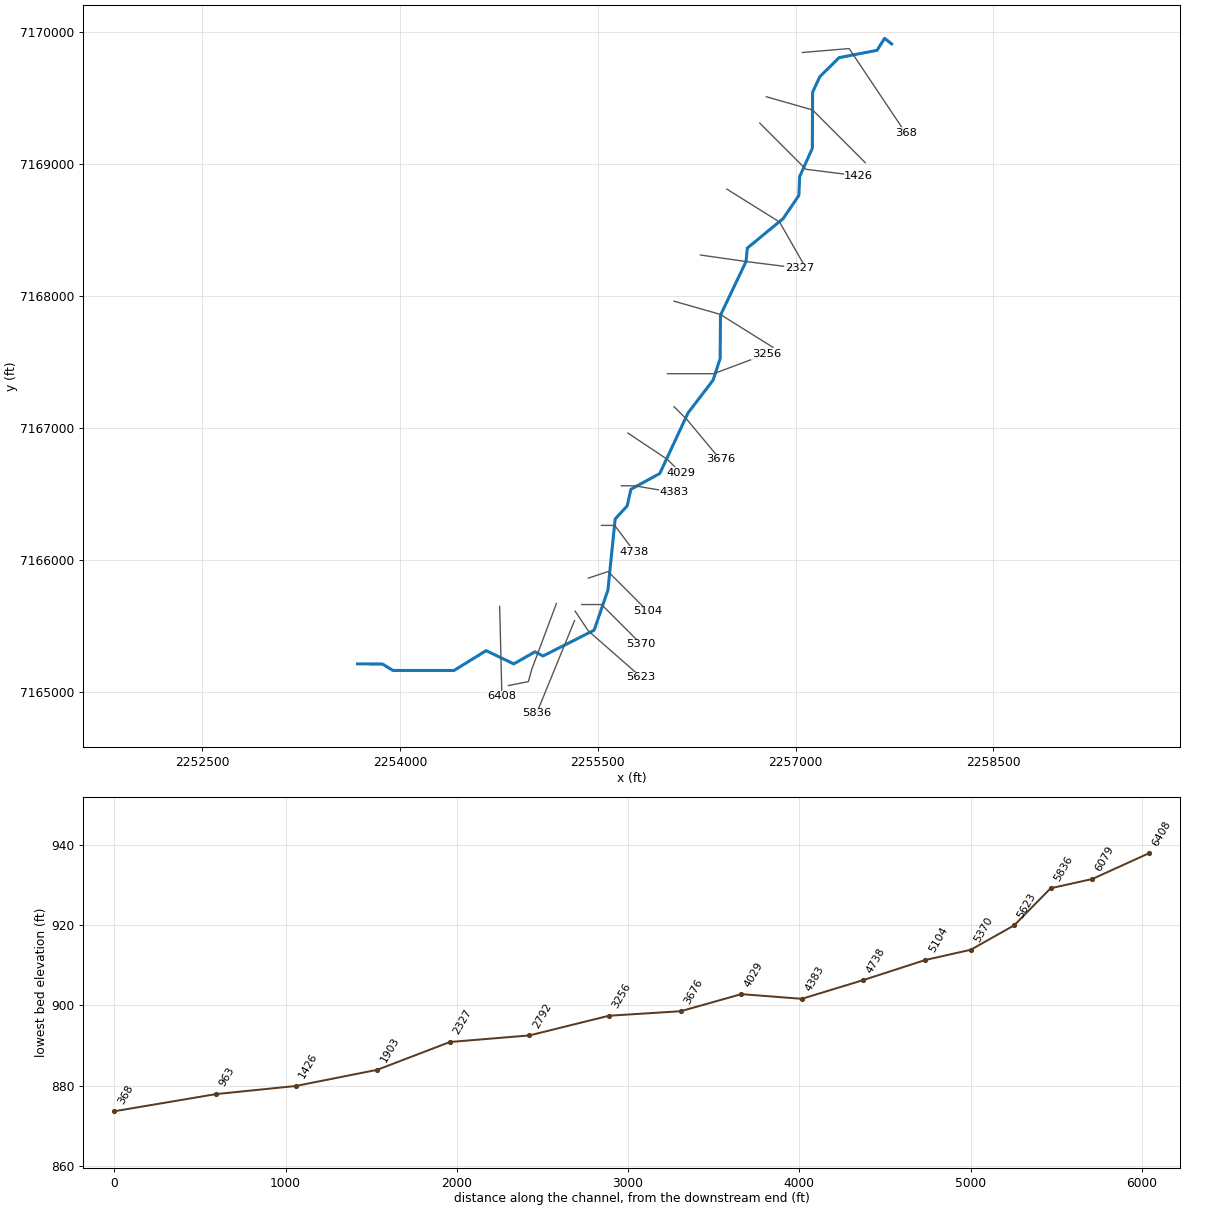
--- MDE S 023.prj (project) ---

Proj Title=MDE S 023 Base Level Engineering
Current Plan=p01
Default Exp/Contr=0.3,0.1
English Units
Geom File=g01
Flow File=f01
Plan File=p01
BEGIN DESCRIPTION:
MDE S 023
END DESCRIPTION:

--- MDE S 023.p01 (plan) ---

Plan Title=Multiple Run
Short Identifier=Multiple
Geom File=g01
Flow File=f01
Subcritical Flow
K Sum by GR= 0
Std Step Tol= 0.01
Critical Tol= 0.01
Num of Std Step Trials= 20
Max Error Tol= 0.3
Flow Tol Ratio= 0.001
Split Flow NTrial= 30
Split Flow Tol= 0.02
Split Flow Ratio= 0.02
Log Output Level= 0
Friction Slope Method= 1
Unsteady Friction Slope Method= 2
Unsteady Bridges Friction Slope Method= 1
Parabolic Critical Depth
Global Vel Dist=  1 , 1 , 1
Global Log Level= 0
CheckData=True
Encroach Param= -1, 0, 0, 0
BEGIN DESCRIPTION:
Multiple Run
END DESCRIPTION:

--- MDE S 023.f01 (steady flow) ---

Flow Title=Multiple
Number of Profiles=7
Profile Names=10-year,25-year,50-year,1pct_min,100-year,1pct_plu,500-year
River Rch & RM= MDE S 023,Reach-1,6408
     529     730     897     549    1096    2187    1638
River Rch & RM= MDE S 023,Reach-1,4738
     675     946    1175     727    1451    2895    2213
River Rch & RM= MDE S 023,Reach-1,3256
     780    1098    1369     849    1694    3381    2597
Boundary for River Rch & Prof#=MDE S 023,Reach-1,1
Up Type=0
Dn Type=3
Dn Slope=0.007
Boundary for River Rch & Prof#=MDE S 023,Reach-1,2
Up Type=0
Dn Type=3
Dn Slope=0.007
Boundary for River Rch & Prof#=MDE S 023,Reach-1,3
Up Type=0
Dn Type=3
Dn Slope=0.007
Boundary for River Rch & Prof#=MDE S 023,Reach-1,4
Up Type=0
Dn Type=3
Dn Slope=0.007
Boundary for River Rch & Prof#=MDE S 023,Reach-1,5
Up Type=0
Dn Type=3
Dn Slope=0.007
Boundary for River Rch & Prof#=MDE S 023,Reach-1,6
Up Type=0
Dn Type=3
Dn Slope=0.007
Boundary for River Rch & Prof#=MDE S 023,Reach-1,7
Up Type=0
Dn Type=3
Dn Slope=0.007

--- MDE S 023.g01 (geometry) ---

Geom Title=Existing Conditions

River Reach=MDE S 023,Reach-1
Reach XY= 30
      2253679.00      7165210.00      2253868.50      7165208.79
      2253947.27      7165160.21      2254410.78      7165160.09
      2254654.00      7165310.42      2254863.61      7165210.07
      2255025.77      7165301.76      2255085.55      7165269.58
      2255473.42      7165465.58      2255577.78      7165770.50
      2255632.55      7166308.53      2255723.46      7166407.58
      2255751.85      7166533.58      2255970.98      7166653.62
      2256184.83      7167112.30      2256375.18      7167361.58
      2256428.48      7167525.22      2256431.24      7167854.07
      2256625.17      7168261.59      2256634.52      7168362.43
      2256906.14      7168586.16      2257025.45      7168761.47
      2257031.39      7168904.47      2257127.62      7169119.66
      2257129.51      7169544.79      2257184.83      7169662.30
      2257330.47      7169806.46      2257617.82      7169861.99
      2257675.36      7169952.84      2257729.00      7169910.00

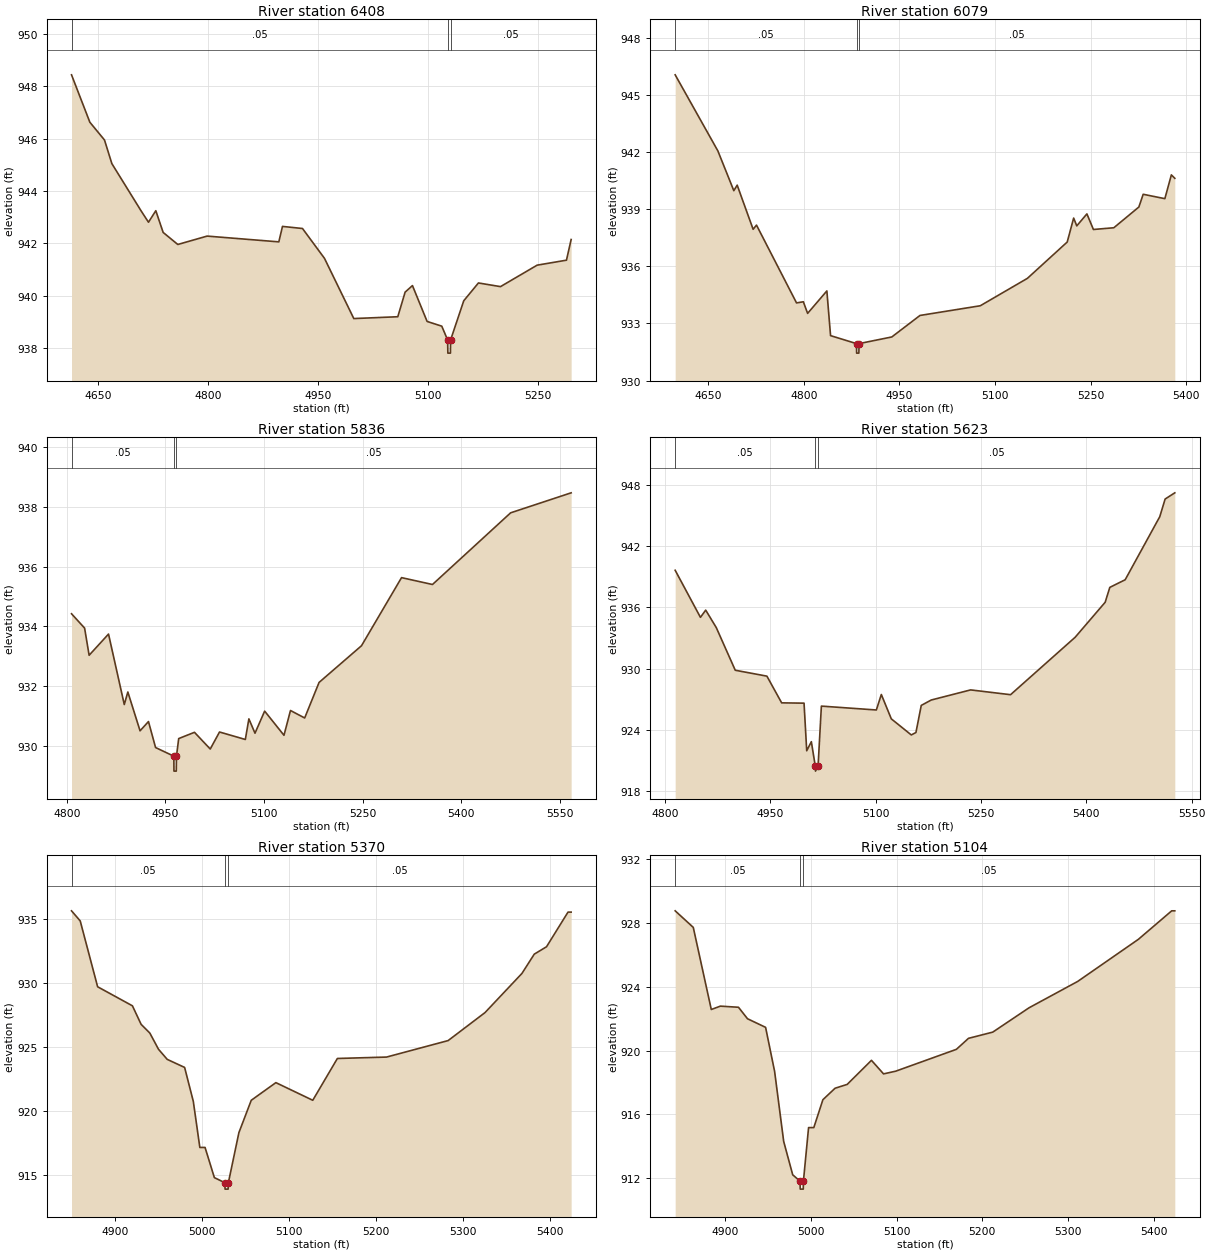
Type RM Length L Ch R = 1,6408,329,329,329
BEGIN DESCRIPTION:
Mapping XS 572ab195
END DESCRIPTION:
XS GIS Cut Line= 2
      2254756.90      7165644.98      2254773.85      7164963.59
#Sta/Elev= 30
  4613.5  948.44  4638.5  946.63  4658.5  945.95  4668.5  945.05  4708.5  943.24
  4718.5  942.81  4728.5  943.25  4738.5  942.42  4758.5  941.96  4798.5  942.28
  4896.3  942.06  4901.3  942.65  4928.6  942.57  4958.6  941.43  4998.6  939.13
  5058.6  939.20  5068.6  940.14  5078.6  940.39  5098.6  939.02  5118.6  938.84
  5126.6  938.31  5126.9  937.81  5130.4  937.81  5130.6  938.31  5148.6  939.81
  5168.6  940.49  5198.7  940.35  5248.7  941.17  5288.7  941.36  5295.1  942.15
#Mann=3,-1,0
  4613.5    0.05       0  5126.6    0.04       0  5130.6    0.05       0
Bank Sta=5126.6,5130.6
Exp/Cntr=0.3,0.1

Type RM Length L Ch R = 1,6079,243,243,243
BEGIN DESCRIPTION:
Mapping XS aa75ece9
END DESCRIPTION:
XS GIS Cut Line= 4
      2255187.32      7165668.30      2255000.99      7165170.60
      2254974.58      7165075.56      2254823.68      7165045.71
#Sta/Elev= 30
  4598.3  946.07  4665.3  942.07  4690.3  939.98  4695.6  940.27  4720.6  937.95
  4725.9  938.17  4788.7  934.08  4799.4  934.14  4806.1  933.53  4836.3  934.71
  4842.1  932.36  4882.8  931.94  4883.0  931.44  4886.5  931.44  4886.8  931.94
  4938.2  932.29  4982.4  933.42  5077.0  933.93  5150.9  935.37  5213.4  937.28
  5223.5  938.54  5228.4  938.13  5244.3  938.76  5254.5  937.94  5286.5  938.03
  5325.8  939.12  5332.6  939.79  5366.6  939.56  5376.8  940.81  5382.2  940.63
#Mann=3,-1,0
  4598.3    0.05       0  4882.8   0.033       0  4886.8    0.05       0
Bank Sta=4882.8,4886.8
Exp/Cntr=0.3,0.1

Type RM Length L Ch R = 1,5836,213,213,213
BEGIN DESCRIPTION:
Mapping XS ebb040bc
END DESCRIPTION:
XS GIS Cut Line= 2
      2255324.77      7165538.39      2255036.77      7164834.74
#Sta/Elev= 30
  4807.0  934.42  4826.9  933.94  4833.8  933.03  4863.3  933.74  4887.3  931.38
  4892.7  931.80  4911.3  930.50  4924.1  930.81  4934.9  929.94  4962.7  929.65
  4962.9  929.15  4966.4  929.15  4966.7  929.65  4970.1  930.24  4994.1  930.45
  5018.1  929.89  5032.2  930.46  5071.5  930.21  5076.9  930.90  5086.2  930.42
  5100.9  931.16  5130.3  930.35  5140.2  931.18  5161.8  930.93  5183.7  932.12
  5248.3  933.35  5309.2  935.63  5356.3  935.40  5475.2  937.80  5567.3  938.47
#Mann=3,-1,0
  4807.0    0.05       0  4962.7   0.033       0  4966.7    0.05       0
Bank Sta=4962.7,4966.7
Exp/Cntr=0.3,0.1

Type RM Length L Ch R = 1,5623,253,253,253
BEGIN DESCRIPTION:
MDE S 023 14.0
END DESCRIPTION:
XS GIS Cut Line= 3
      2255329.01      7165609.98      2255429.00      7165460.00
      2255829.03      7165109.97
#Sta/Elev= 30
  4814.2  939.64  4850.2  935.02  4857.7  935.73  4872.8  934.01  4899.8  929.83
  4944.9  929.25  4965.9  926.63  4997.8  926.60  5001.6  921.93  5008.2  922.82
  5013.8  920.43  5014.1  919.93  5017.8  920.43  5022.5  926.31  5100.8  925.93
  5107.9  927.45  5122.1  925.06  5150.6  923.48  5157.2  923.72  5164.8  926.38
  5179.1  926.91  5235.1  927.90  5292.0  927.43  5384.1  933.07  5426.8  936.50
  5433.4  937.96  5455.3  938.71  5504.6  944.90  5512.2  946.63  5526.0  947.24
#Mann=3,-1,0
  4814.2    0.05       0  5013.8   0.033       0  5017.8    0.05       0
Bank Sta=5013.8,5017.8
Exp/Cntr=0.3,0.1

Type RM Length L Ch R = 1,5370,266,266,266
BEGIN DESCRIPTION:
MDE S 023 13.0
END DESCRIPTION:
XS GIS Cut Line= 3
      2255378.99      7165660.00      2255529.00      7165660.00
      2255829.02      7165359.98
#Sta/Elev= 30
  4850.3  935.63  4860.3  934.84  4880.3  929.69  4920.3  928.20  4930.3  926.75
  4940.3  926.07  4950.3  924.80  4960.3  924.01  4980.3  923.38  4990.3  920.72
  4997.8  917.12  5003.8  917.12  5014.5  914.76  5026.6  914.36  5026.8  913.86
  5030.3  913.86  5030.6  914.36  5042.7  918.28  5056.9  920.81  5085.2  922.19
  5127.6  920.81  5155.9  924.08  5212.4  924.19  5283.2  925.48  5325.6  927.67
  5368.0  930.73  5382.2  932.24  5396.3  932.82  5421.0  935.53  5424.6  935.53
#Mann=3,-1,0
  4850.3    0.05       0  5026.6   0.033       0  5030.6    0.05       0
Bank Sta=5026.6,5030.6
Exp/Cntr=0.3,0.1

Type RM Length L Ch R = 1,5104,366,366,366
BEGIN DESCRIPTION:
MDE S 023 12.0
END DESCRIPTION:
XS GIS Cut Line= 3
      2255429.02      7165860.01      2255579.00      7165910.00
      2255879.03      7165609.97
#Sta/Elev= 30
  4842.0  928.77  4863.1  927.73  4884.1  922.58  4894.7  922.79  4915.8  922.72
  4926.3  922.00  4947.4  921.46  4957.9  918.70  4968.5  914.30  4979.0  912.21
  4987.5  911.81  4987.8  911.31  4991.3  911.31  4991.5  911.81  4997.5  915.17
  5003.6  915.17  5014.2  916.92  5028.4  917.64  5042.5  917.88  5070.8  919.39
  5084.9  918.54  5099.1  918.71  5169.8  920.08  5183.9  920.77  5212.2  921.16
  5254.6  922.69  5311.2  924.34  5381.9  926.98  5420.8  928.77  5424.4  928.77
#Mann=3,-1,0
  4842.0    0.05       0  4987.5   0.033       0  4991.5    0.05       0
Bank Sta=4987.5,4991.5
Exp/Cntr=0.3,0.1

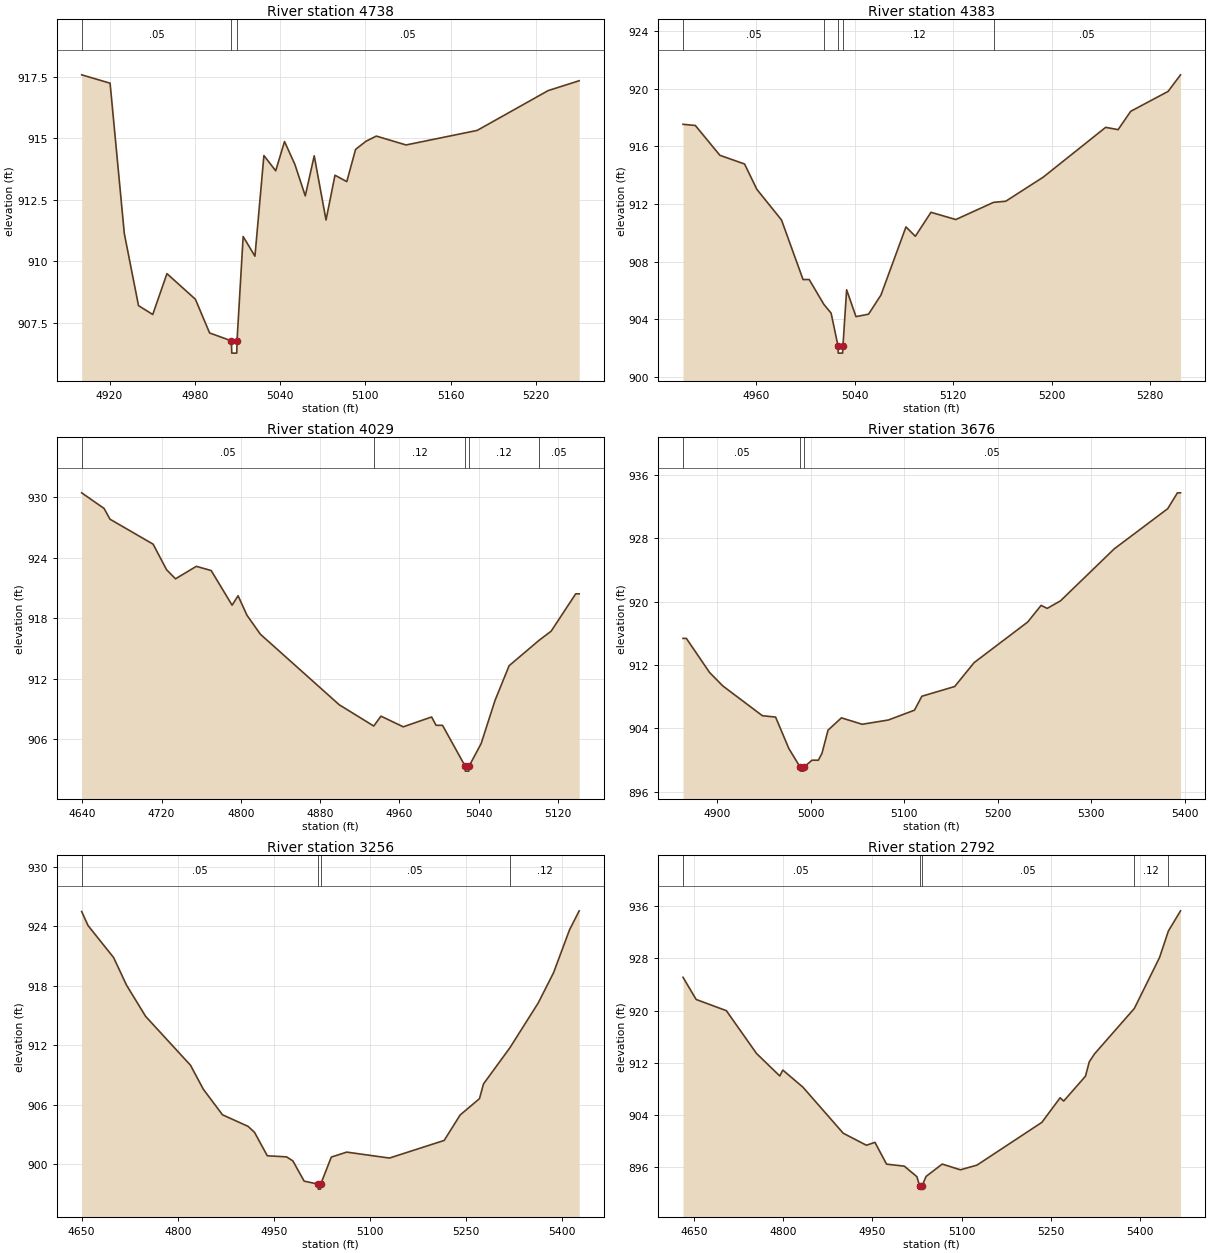
Type RM Length L Ch R = 1,4738,355,355,355
BEGIN DESCRIPTION:
MDE S 023 11.0
END DESCRIPTION:
XS GIS Cut Line= 3
      2255528.96      7166260.00      2255629.00      7166260.00
      2255778.98      7166060.03
#Sta/Elev= 30
  4900.4  917.58  4920.4  917.24  4930.4  911.13  4940.4  908.20  4950.4  907.84
  4960.4  909.50  4980.4  908.46  4990.4  907.09  5005.7  906.77  5006.0  906.27
  5009.5  906.27  5009.7  906.77  5014.0  911.01  5022.3  910.21  5028.6  914.30
  5036.9  913.68  5043.1  914.87  5050.4  913.94  5057.7  912.66  5064.0  914.29
  5072.3  911.68  5078.6  913.50  5086.9  913.24  5093.1  914.55  5100.4  914.88
  5107.7  915.09  5128.6  914.73  5178.6  915.32  5228.6  916.94  5250.4  917.34
#Mann=3,-1,0
  4900.4    0.05       0  5005.7   0.033       0  5009.7    0.05       0
Bank Sta=5005.7,5009.7
Exp/Cntr=0.3,0.1

Type RM Length L Ch R = 1,4383,354,354,354
BEGIN DESCRIPTION:
MDE S 023 10.0
END DESCRIPTION:
XS GIS Cut Line= 3
      2255679.01      7166560.00      2255779.00      7166560.00
      2256078.97      7166510.00
#Sta/Elev= 30
  4900.7  917.52  4910.7  917.44  4930.7  915.37  4950.7  914.77  4960.7  913.01
  4980.7  910.89  4998.2  906.76  5003.2  906.76  5015.1  905.04  5021.0  904.43
  5026.6  902.16  5026.8  901.66  5030.3  901.66  5030.6  902.16  5033.6  906.05
  5041.2  904.19  5051.4  904.36  5061.5  905.69  5081.8  910.41  5089.4  909.76
  5102.1  911.42  5122.3  910.92  5152.9  912.11  5162.9  912.19  5193.3  913.86
  5244.0  917.31  5254.1  917.15  5264.3  918.42  5294.7  919.80  5304.8  920.95
#Mann=5,-1,0
  4900.7    0.05       0  5015.1    0.12       0  5026.6   0.033       0
  5030.6    0.12       0  5152.9    0.05       0
Bank Sta=5026.6,5030.6
Exp/Cntr=0.3,0.1

Type RM Length L Ch R = 1,4029,353,353,353
BEGIN DESCRIPTION:
MDE S 023 9.0
END DESCRIPTION:
XS GIS Cut Line= 3
      2255728.98      7166960.01      2256029.00      7166760.00
      2256129.00      7166660.00
#Sta/Elev= 30
  4639.4  930.46  4662.0  928.91  4668.0  927.84  4711.5  925.36  4725.1  922.82
  4734.1  921.92  4755.1  923.16  4770.1  922.74  4791.2  919.30  4797.2  920.24
  4806.2  918.30  4819.7  916.42  4899.3  909.41  4934.1  907.30  4941.4  908.28
  4963.9  907.22  4992.5  908.20  4997.0  907.37  5003.5  907.37  5026.3  903.32
  5026.5  902.82  5030.0  902.82  5030.3  903.32  5042.4  905.54  5056.5  909.85
  5070.7  913.29  5100.5  915.78  5113.1  916.72  5137.9  920.43  5141.4  920.43
#Mann=5,-1,0
  4639.4    0.05       0  4934.1    0.12       0  5026.3    0.07       0
  5030.3    0.12       0  5100.5    0.05       0
Bank Sta=5026.3,5030.3
Exp/Cntr=0.3,0.1

Type RM Length L Ch R = 1,3676,420,420,420
BEGIN DESCRIPTION:
MDE S 023 8.0
END DESCRIPTION:
XS GIS Cut Line= 3
      2256078.98      7167160.02      2256179.00      7167060.00
      2256429.02      7166759.97
#Sta/Elev= 30
  4863.6  915.35  4867.2  915.35  4891.9  911.06  4906.1  909.35  4948.5  905.58
  4962.6  905.41  4976.8  901.43  4988.9  899.08  4989.2  898.58  4992.7  898.58
  4992.9  899.08  5001.5  899.96  5008.3  899.96  5012.2  900.83  5018.7  903.76
  5033.0  905.31  5055.2  904.50  5083.2  905.04  5111.1  906.28  5119.0  908.04
  5154.1  909.27  5174.9  912.29  5232.2  917.42  5246.5  919.52  5253.0  919.14
  5267.3  920.10  5324.6  926.65  5381.9  931.74  5392.3  933.74  5395.6  933.74
#Mann=3,-1,0
  4863.6    0.05       0  4988.9   0.033       0  4992.9    0.05       0
Bank Sta=4988.9,4992.9
Exp/Cntr=0.3,0.1

Type RM Length L Ch R = 1,3256,464,464,464
BEGIN DESCRIPTION:
MDE S 023 7.0
END DESCRIPTION:
XS GIS Cut Line= 3
      2256029.00      7167410.00      2256379.00      7167410.00
      2256779.00      7167560.00
#Sta/Elev= 30
  4650.0  925.50  4660.0  924.08  4700.0  920.84  4720.0  918.07  4750.0  914.90
  4820.0  909.97  4840.0  907.55  4870.0  904.96  4910.0  903.79  4920.0  903.19
  4940.0  900.82  4970.0  900.71  4980.0  900.30  4997.5  898.26  5019.4  897.95
  5019.6  897.45  5023.1  897.45  5023.4  897.95  5040.0  900.69  5064.1  901.19
  5130.8  900.59  5216.3  902.37  5241.2  904.94  5271.4  906.59  5277.7  908.08
  5318.9  911.73  5363.1  916.25  5387.1  919.31  5412.1  923.65  5427.2  925.57
#Mann=4,-1,0
  4650.0    0.05       0  5019.4   0.033       0  5023.4    0.05       0
  5318.9    0.12       0
Bank Sta=5019.4,5023.4
Exp/Cntr=0.3,0.1

Type RM Length L Ch R = 1,2792,465,465,465
BEGIN DESCRIPTION:
MDE S 023 6.0
END DESCRIPTION:
XS GIS Cut Line= 3
      2256078.96      7167960.01      2256429.00      7167860.00
      2256828.96      7167610.02
#Sta/Elev= 30
  4631.8  925.11  4653.9  921.70  4704.6  919.98  4755.3  913.40  4794.3  909.95
  4799.5  910.85  4833.3  908.22  4900.9  901.15  4939.9  899.30  4954.2  899.75
  4973.7  896.40  5003.5  896.09  5024.7  894.47  5029.2  893.06  5029.5  892.56
  5033.3  893.06  5040.1  894.51  5067.2  896.41  5097.8  895.53  5125.6  896.25
  5234.6  902.82  5265.3  906.60  5271.2  906.09  5307.8  909.91  5314.2  912.12
  5323.1  913.35  5389.9  920.32  5432.2  928.14  5447.1  932.22  5467.5  935.32
#Mann=5,-1,0
  4631.8    0.05       0  5029.2   0.033       0  5033.3    0.05       0
  5389.9    0.12       0  5447.1    0.05       0
Bank Sta=5029.2,5033.3
Exp/Cntr=0.3,0.1

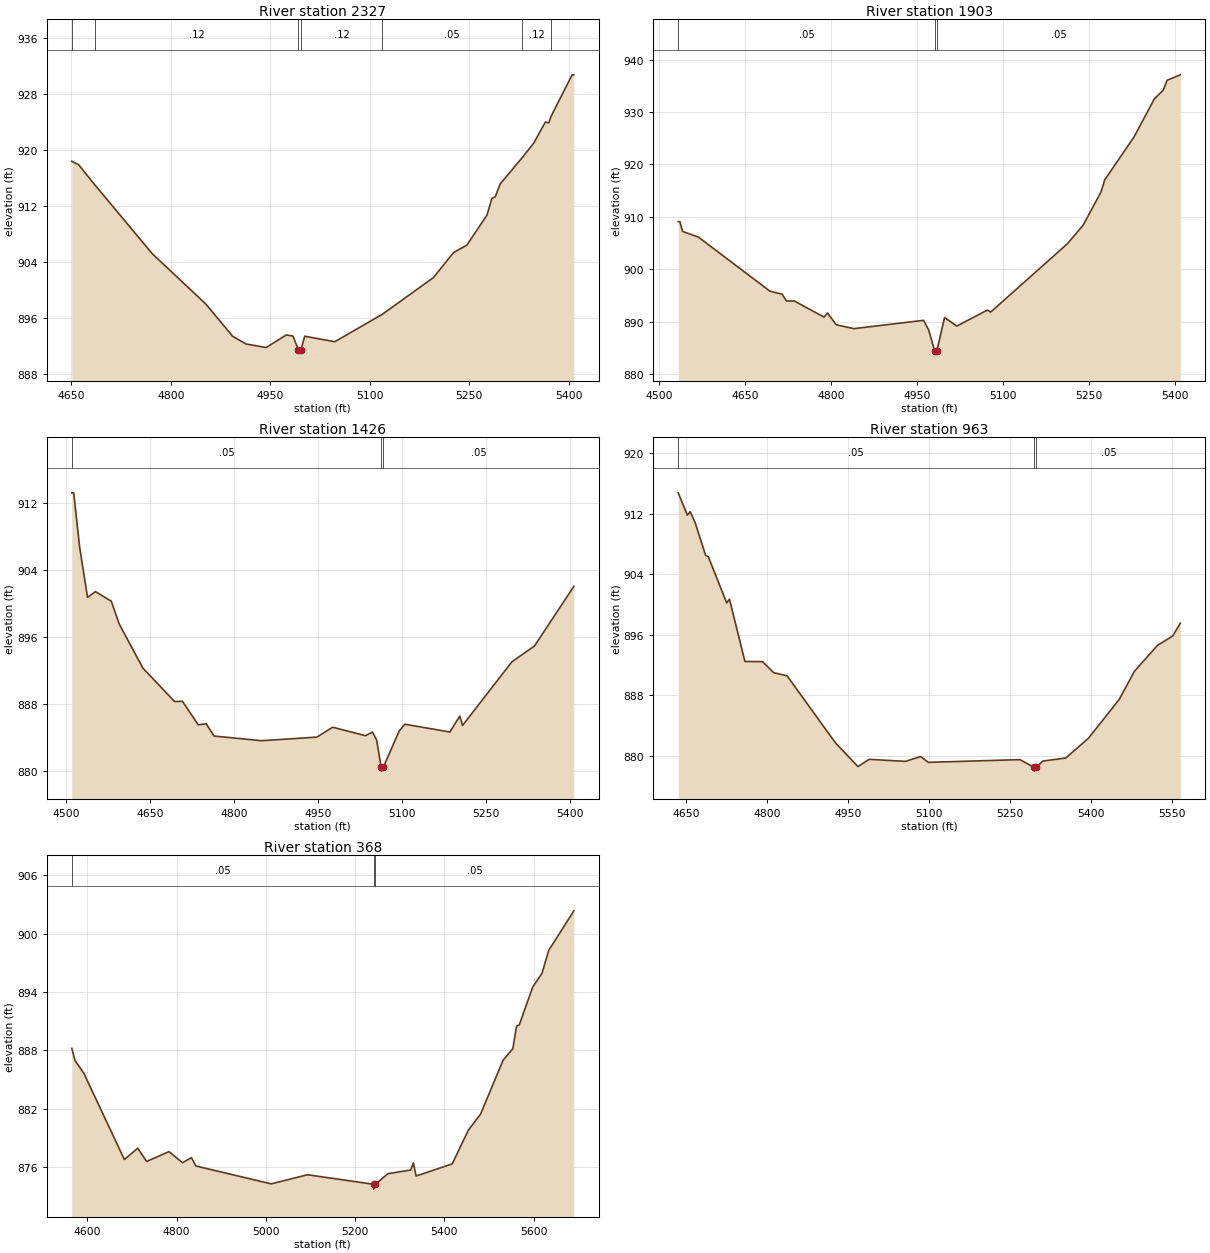
Type RM Length L Ch R = 1,2327,424,424,424
BEGIN DESCRIPTION:
MDE S 023 5.0
END DESCRIPTION:
XS GIS Cut Line= 3
      2256279.00      7168310.00      2256629.00      7168260.00
      2257029.03      7168210.00
#Sta/Elev= 30
  4650.8  918.36  4660.9  917.90  4685.4  915.02  4772.0  905.16  4852.8  897.95
  4893.2  893.34  4913.4  892.23  4943.7  891.72  4974.1  893.52  4984.2  893.36
  4992.2  891.42  4992.5  890.92  4996.4  891.42  5001.8  893.34  5047.2  892.55
  5118.7  896.47  5195.8  901.72  5226.1  905.30  5246.2  906.37  5276.5  910.65
  5284.0  913.06  5289.1  913.30  5296.6  915.14  5328.9  918.80  5347.0  920.96
  5364.6  923.99  5369.7  923.87  5373.2  924.81  5404.9  930.74  5407.5  930.74
#Mann=7,-1,0
  4650.8    0.05       0  4685.4    0.12       0  4992.2    0.07       0
  4996.4    0.12       0  5118.7    0.05       0  5328.9    0.12       0
  5373.2    0.05       0
Bank Sta=4992.2,4996.4
Exp/Cntr=0.3,0.1

Type RM Length L Ch R = 1,1903,477,477,477
BEGIN DESCRIPTION:
MDE S 023 4.0
END DESCRIPTION:
XS GIS Cut Line= 3
      2256479.00      7168810.00      2256879.00      7168560.00
      2257079.00      7168210.01
#Sta/Elev= 30
  4533.7  909.09  4536.6  909.09  4541.4  907.22  4569.1  906.13  4693.5  895.83
  4714.7  895.25  4722.4  893.94  4735.9  893.96  4787.8  890.88  4793.7  891.68
  4809.0  889.42  4839.7  888.68  4961.2  890.27  4970.0  888.43  4980.3  884.51
  4980.6  884.01  4984.5  884.51  4997.7  890.80  5019.1  889.17  5072.3  892.22
  5078.1  891.84  5212.0  904.90  5239.3  908.43  5270.3  914.76  5276.8  917.07
  5327.9  925.25  5363.2  932.50  5379.0  934.22  5385.5  936.06  5408.5  937.10
#Mann=3,-1,0
  4533.7    0.05       0  4980.3    0.04       0  4984.5    0.05       0
Bank Sta=4980.3,4984.5
Exp/Cntr=0.3,0.1

Type RM Length L Ch R = 1,1426,463,463,463
BEGIN DESCRIPTION:
MDE S 023 3.0
END DESCRIPTION:
XS GIS Cut Line= 3
      2256729.03      7169309.97      2257079.00      7168960.00
      2257478.96      7168910.00
#Sta/Elev= 30
  4509.7  913.20  4513.2  913.20  4523.8  906.71  4537.9  900.72  4552.1  901.41
  4580.4  900.26  4594.5  897.55  4636.9  892.28  4693.5  888.29  4707.6  888.32
  4735.9  885.51  4750.1  885.63  4764.2  884.17  4849.1  883.61  4948.1  884.04
  4976.3  885.22  5034.9  884.21  5047.5  884.64  5055.0  883.69  5063.0  880.48
  5063.3  879.98  5067.2  880.48  5095.3  884.77  5105.4  885.58  5186.0  884.65
  5203.7  886.55  5208.7  885.44  5296.9  893.03  5337.2  894.91  5407.7  902.03
#Mann=3,-1,0
  4509.7    0.05       0  5063.0    0.04       0  5067.2    0.05       0
Bank Sta=5063,5067.2
Exp/Cntr=0.3,0.1

Type RM Length L Ch R = 1,963,595,595,595
BEGIN DESCRIPTION:
MDE S 023 2.0
END DESCRIPTION:
XS GIS Cut Line= 3
      2256778.97      7169510.01      2257129.00      7169410.00
      2257528.98      7169010.02
#Sta/Elev= 30
  4636.0  914.76  4652.9  911.81  4658.1  912.27  4667.2  910.84  4686.7  906.51
  4691.9  906.29  4725.7  900.21  4730.9  900.70  4759.5  892.47  4792.0  892.45
  4812.8  890.99  4837.5  890.58  4927.2  881.71  4968.8  878.58  4989.6  879.54
  5056.6  879.27  5084.9  879.91  5099.0  879.14  5268.7  879.50  5294.9  878.48
  5295.2  877.98  5299.2  878.48  5311.2  879.31  5353.6  879.71  5396.0  882.36
  5452.6  887.46  5480.9  891.19  5523.3  894.59  5551.6  895.84  5565.7  897.53
#Mann=3,-1,0
  4636.0    0.05       0  5294.9    0.04       0  5299.2    0.05       0
Bank Sta=5294.9,5299.2
Exp/Cntr=0.3,0.1

Type RM Length L Ch R = 1,368,0,0,0
BEGIN DESCRIPTION:
MDE S 023 1.0
END DESCRIPTION:
XS GIS Cut Line= 3
      2257051.82      7169845.55      2257406.50      7169875.29
      2257834.04      7169236.37
#Sta/Elev= 30
  4565.2  888.20  4572.4  886.96  4592.5  885.61  4683.0  876.76  4712.9  877.92
  4733.0  876.56  4783.1  877.57  4813.2  876.43  4833.3  876.95  4843.4  876.09
  5012.1  874.25  5093.2  875.19  5241.2  874.21  5241.5  873.71  5245.5  874.21
  5273.3  875.30  5324.4  875.68  5330.4  876.41  5336.6  875.06  5417.5  876.31
  5453.5  879.77  5481.0  881.43  5531.6  886.99  5553.2  888.16  5561.6  890.49
  5567.6  890.60  5597.6  894.49  5618.6  895.93  5633.6  898.28  5689.9  902.35
#Mann=3,-1,0
  4565.2    0.05       0  5241.2    0.04       0  5245.5    0.05       0
Bank Sta=5241.2,5245.5
Exp/Cntr=0.3,0.1

Chan Stop Cuts=-1