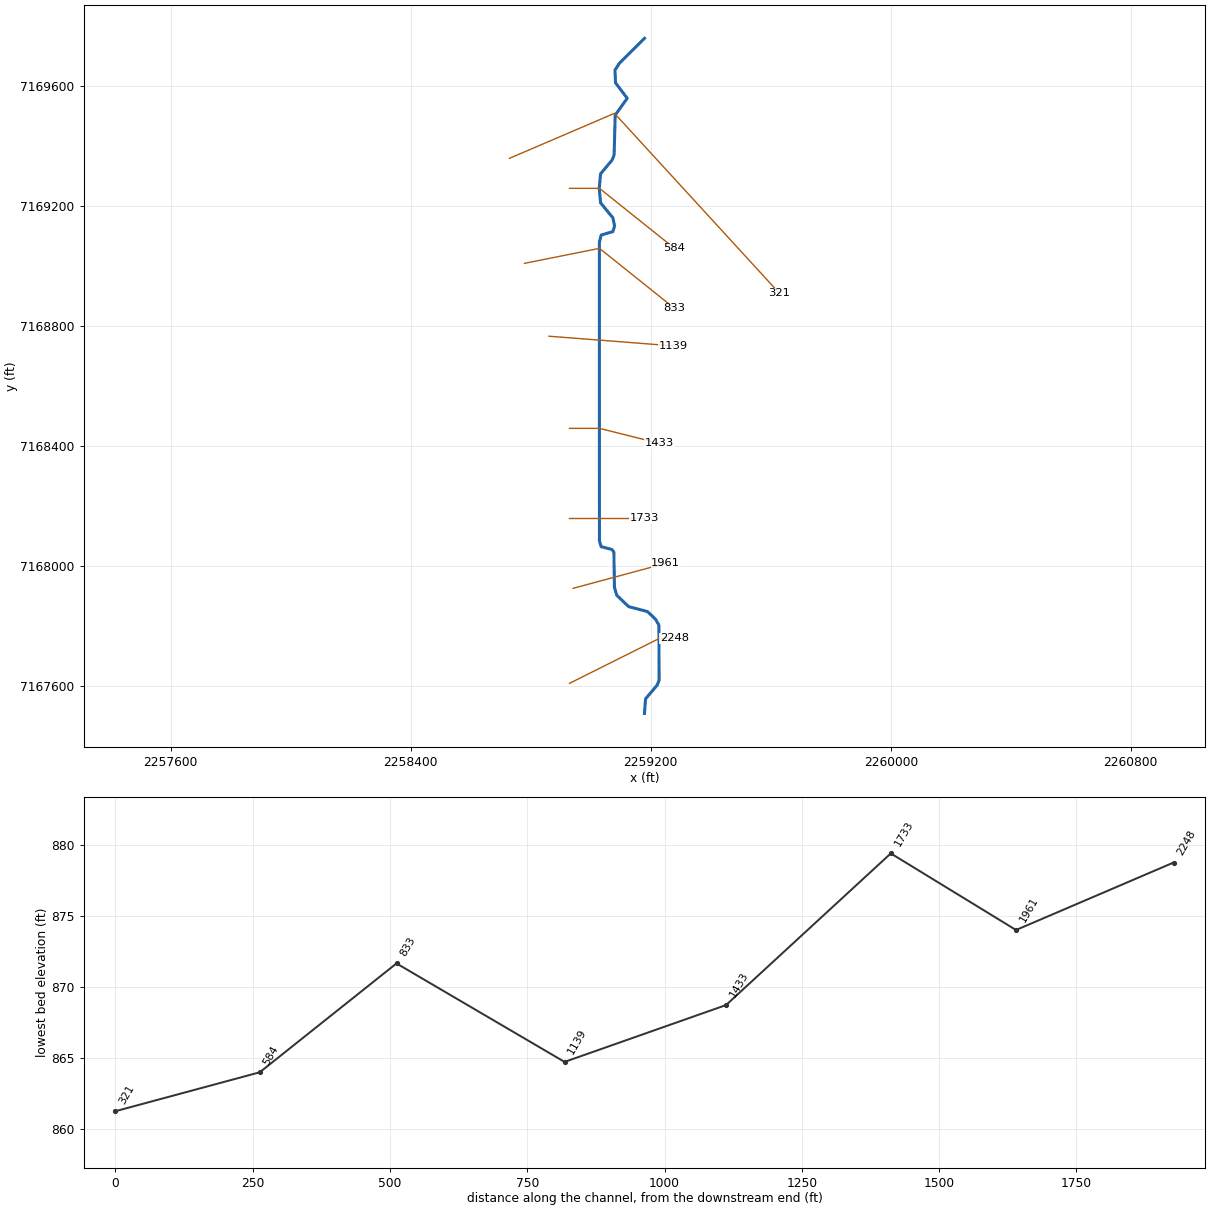
--- MDE S 024.prj (project) ---

Proj Title=MDE S 024 Base Level Engineering
Current Plan=p01
Default Exp/Contr=0.3,0.1
English Units
Geom File=g01
Flow File=f01
Plan File=p01
BEGIN DESCRIPTION:
MDE S 024
END DESCRIPTION:

--- MDE S 024.p01 (plan) ---

Plan Title=Multiple Run
Short Identifier=Multiple
Geom File=g01
Flow File=f01
Subcritical Flow
K Sum by GR= 0
Std Step Tol= 0.01
Critical Tol= 0.01
Num of Std Step Trials= 20
Max Error Tol= 0.3
Flow Tol Ratio= 0.001
Split Flow NTrial= 30
Split Flow Tol= 0.02
Split Flow Ratio= 0.02
Log Output Level= 0
Friction Slope Method= 1
Unsteady Friction Slope Method= 2
Unsteady Bridges Friction Slope Method= 1
Parabolic Critical Depth
Global Vel Dist=  1 , 1 , 1
Global Log Level= 0
CheckData=True
Encroach Param= -1, 0, 0, 0
BEGIN DESCRIPTION:
Multiple Run
END DESCRIPTION:

--- MDE S 024.f01 (steady flow) ---

Flow Title=Multiple
Number of Profiles=7
Profile Names=10-year,25-year,50-year,1pct_min,100-year,1pct_plu,500-year
River Rch & RM= MDE S 024,Reach-1,2248
     466     635     774     470     937    1870    1376
Boundary for River Rch & Prof#=MDE S 024,Reach-1,1
Up Type=0
Dn Type=3
Dn Slope=0.005
Boundary for River Rch & Prof#=MDE S 024,Reach-1,2
Up Type=0
Dn Type=3
Dn Slope=0.005
Boundary for River Rch & Prof#=MDE S 024,Reach-1,3
Up Type=0
Dn Type=3
Dn Slope=0.005
Boundary for River Rch & Prof#=MDE S 024,Reach-1,4
Up Type=0
Dn Type=3
Dn Slope=0.005
Boundary for River Rch & Prof#=MDE S 024,Reach-1,5
Up Type=0
Dn Type=3
Dn Slope=0.005
Boundary for River Rch & Prof#=MDE S 024,Reach-1,6
Up Type=0
Dn Type=3
Dn Slope=0.005
Boundary for River Rch & Prof#=MDE S 024,Reach-1,7
Up Type=0
Dn Type=3
Dn Slope=0.005

--- MDE S 024.g01 (geometry) ---

Geom Title=Existing Conditions

River Reach=MDE S 024,Reach-1
Reach XY= 30
      2259179.00      7167510.00      2259182.65      7167558.49
      2259221.11      7167603.84      2259227.88      7167620.46
      2259227.02      7167804.33      2259215.77      7167823.67
      2259189.04      7167849.37      2259126.45      7167865.75
      2259086.70      7167903.53      2259078.94      7167929.91
      2259077.02      7168048.03      2259070.41      7168056.41
      2259034.62      7168065.62      2259028.88      7168084.88
      2259028.66      7169080.37      2259034.70      7169104.41
      2259073.79      7169115.79      2259079.32      7169134.96
      2259073.72      7169161.87      2259032.75      7169211.56
      2259028.19      7169260.00      2259032.70      7169308.40
      2259070.85      7169353.94      2259077.77      7169370.51
      2259081.47      7169504.14      2259121.41      7169560.01
      2259082.57      7169611.65      2259080.60      7169653.96
      2259095.11      7169676.71      2259179.00      7169760.00

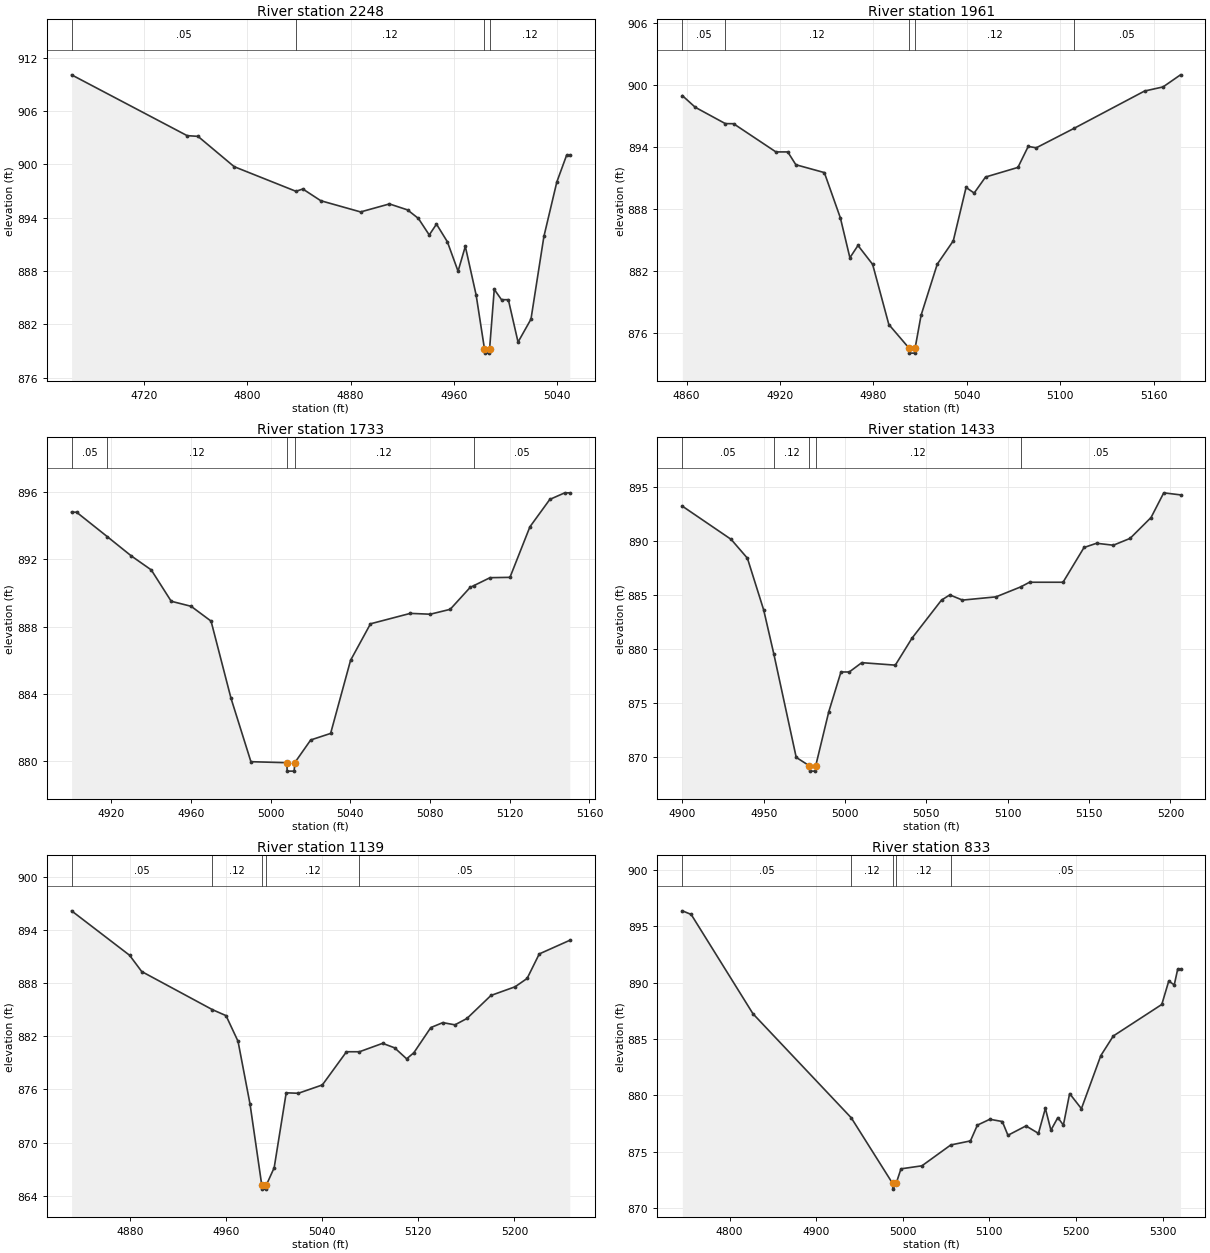
Type RM Length L Ch R = 1,2248,287,287,287
BEGIN DESCRIPTION:
MDE S 024 8.0
END DESCRIPTION:
XS GIS Cut Line= 3
      2258929.02      7167610.01      2259229.00      7167760.00
      2259279.01      7167760.00
#Sta/Elev= 30
  4664.2  910.07  4753.6  903.23  4762.0  903.15  4790.0  899.74  4837.8  896.97
  4843.1  897.23  4857.0  895.91  4887.8  894.65  4910.1  895.55  4924.1  894.88
  4932.5  893.92  4940.9  892.06  4946.5  893.28  4954.9  891.30  4963.2  887.98
  4968.8  890.78  4977.2  885.29  4983.6  879.27  4983.9  878.77  4987.4  878.77
  4987.6  879.27  4991.2  885.94  4996.8  884.78  5002.1  884.78  5009.6  880.01
  5019.6  882.59  5029.6  891.89  5039.6  898.02  5047.1  901.00  5049.6  901.00
#Mann=4,-1,0
  4664.2    0.05       0  4837.8    0.12       0  4983.6    0.07       0
  4987.6    0.12       0
Bank Sta=4983.6,4987.6
Exp/Cntr=0.3,0.1

Type RM Length L Ch R = 1,1961,228,228,228
BEGIN DESCRIPTION:
Mapping XS 5e68d046
END DESCRIPTION:
XS GIS Cut Line= 2
      2258940.98      7167926.75      2259249.84      7168010.07
#Sta/Elev= 30
  4857.3  898.94  4865.6  897.81  4884.9  896.23  4890.2  896.22  4917.4  893.49
  4925.0  893.49  4930.2  892.25  4948.5  891.49  4958.8  887.10  4964.9  883.25
  4970.1  884.44  4979.5  882.61  4989.9  876.79  5002.8  874.52  5003.1  874.02
  5006.6  874.02  5006.8  874.52  5010.6  877.68  5021.0  882.63  5031.3  884.89
  5039.5  890.05  5044.7  889.51  5052.0  891.06  5072.8  891.99  5079.4  894.02
  5084.6  893.89  5108.7  895.76  5154.1  899.38  5166.0  899.78  5177.2  900.95
#Mann=5,-1,0
  4857.3    0.05       0  4884.9    0.12       0  5002.8    0.07       0
  5006.8    0.12       0  5108.7    0.05       0
Bank Sta=5002.8,5006.8
Exp/Cntr=0.3,0.1

Type RM Length L Ch R = 1,1733,300,300,300
BEGIN DESCRIPTION:
MDE S 024 6.0
END DESCRIPTION:
XS GIS Cut Line= 3
      2258929.00      7168160.00      2259029.00      7168160.00
      2259179.00      7168160.00
#Sta/Elev= 29
  4900.1  894.79  4902.6  894.79  4918.1  893.33  4930.1  892.19  4940.1  891.36
  4950.1  889.50  4960.1  889.20  4970.1  888.32  4980.1  883.74  4990.1  879.97
  5008.1  879.91  5008.3  879.41  5011.8  879.41  5012.1  879.91  5020.1  881.26
  5030.1  881.65  5040.1  885.99  5050.1  888.16  5070.1  888.78  5080.1  888.73
  5090.1  889.02  5100.1  890.32  5102.0  890.43  5110.1  890.90  5120.1  890.92
  5130.1  893.92  5140.1  895.55  5147.6  895.94  5150.1  895.94
#Mann=5,-1,0
  4900.1    0.05       0  4918.1    0.12       0  5008.1    0.07       0
  5012.1    0.12       0  5102.0    0.05       0
Bank Sta=5008.1,5012.1
Exp/Cntr=0.3,0.1

Type RM Length L Ch R = 1,1433,294,294,294
BEGIN DESCRIPTION:
MDE S 024 5.0
END DESCRIPTION:
XS GIS Cut Line= 3
      2258928.99      7168460.00      2259029.00      7168460.00
      2259229.04      7168409.99
#Sta/Elev= 30
  4900.0  893.22  4930.0  890.15  4940.0  888.41  4950.0  883.63  4956.2  879.59
  4970.0  870.01  4978.0  869.24  4978.3  868.74  4981.8  868.74  4982.0  869.24
  4990.0  874.22  4997.5  877.90  5002.6  877.90  5010.3  878.76  5030.9  878.53
  5041.2  881.03  5059.3  884.54  5064.4  885.02  5072.2  884.54  5092.8  884.84
  5108.0  885.76  5113.4  886.19  5134.0  886.19  5146.9  889.40  5154.6  889.79
  5164.9  889.61  5175.2  890.24  5188.1  892.17  5195.9  894.45  5206.2  894.26
#Mann=5,-1,0
  4900.0    0.05       0  4956.2    0.12       0  4978.0    0.07       0
  4982.0    0.12       0  5108.0    0.05       0
Bank Sta=4978,4982
Exp/Cntr=0.3,0.1

Type RM Length L Ch R = 1,1139,306,306,306
BEGIN DESCRIPTION:
Mapping XS a3da19b2
END DESCRIPTION:
XS GIS Cut Line= 2
      2258860.80      7168767.15      2259274.35      7168735.02
#Sta/Elev= 30
  4831.3  896.18  4879.6  891.16  4889.7  889.32  4948.5  885.02  4959.9  884.34
  4969.9  881.44  4979.9  874.34  4989.6  865.24  4989.8  864.74  4993.3  864.74
  4993.6  865.24  5000.0  867.16  5010.0  875.62  5020.1  875.57  5040.1  876.51
  5060.2  880.26  5071.0  880.26  5090.3  881.21  5100.3  880.70  5110.3  879.46
  5116.3  880.15  5130.4  882.99  5140.4  883.55  5150.5  883.30  5160.5  884.02
  5180.5  886.62  5200.6  887.60  5210.6  888.54  5220.7  891.31  5246.1  892.85
#Mann=5,-1,0
  4831.3    0.05       0  4948.5    0.12       0  4989.6    0.07       0
  4993.6    0.12       0  5071.0    0.05       0
Bank Sta=4989.6,4993.6
Exp/Cntr=0.3,0.1

Type RM Length L Ch R = 1,833,249,249,249
BEGIN DESCRIPTION:
MDE S 024 3.0
END DESCRIPTION:
XS GIS Cut Line= 3
      2258778.96      7169009.99      2259029.00      7169060.00
      2259278.96      7168860.03
#Sta/Elev= 30
  4745.5  896.37  4755.7  896.05  4827.1  887.23  4940.5  878.00  4988.3  872.17
  4988.5  871.67  4992.3  872.17  4997.9  873.47  5022.1  873.74  5055.4  875.59
  5078.1  875.95  5086.1  877.35  5100.5  877.87  5114.9  877.67  5121.4  876.45
  5142.2  877.28  5156.6  876.62  5164.6  878.84  5171.0  876.90  5179.0  878.02
  5185.4  877.35  5192.6  880.15  5206.2  878.81  5228.6  883.52  5243.0  885.26
  5299.0  888.06  5307.0  890.13  5313.4  889.80  5317.4  891.21  5320.6  891.21
#Mann=5,-1,0
  4745.5    0.05       0  4940.5    0.12       0  4988.3    0.07       0
  4992.3    0.12       0  5055.4    0.05       0
Bank Sta=4988.3,4992.3
Exp/Cntr=0.3,0.1

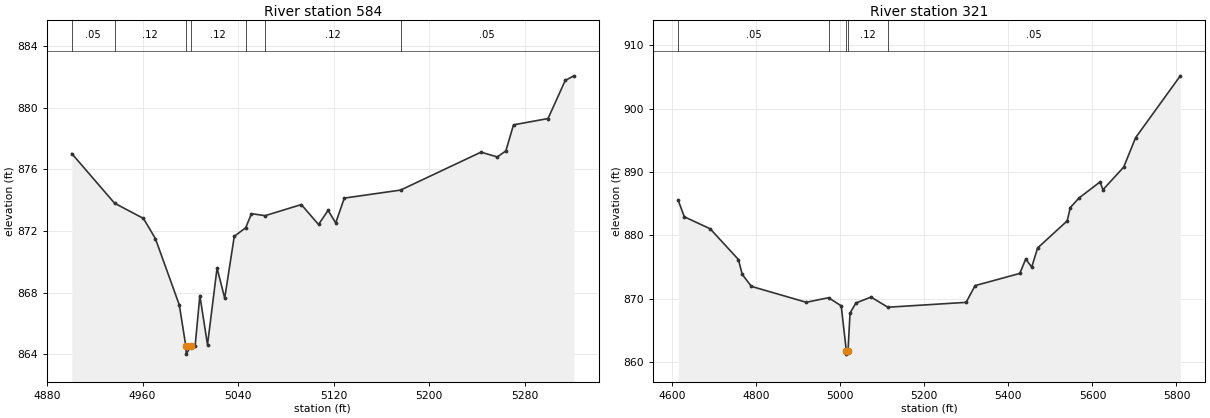
Type RM Length L Ch R = 1,584,263,263,263
BEGIN DESCRIPTION:
MDE S 024 2.0
END DESCRIPTION:
XS GIS Cut Line= 3
      2258928.99      7169260.00      2259029.00      7169260.00
      2259279.02      7169059.98
#Sta/Elev= 30
  4900.8  877.02  4936.6  873.80  4960.8  872.81  4970.8  871.50  4990.8  867.20
  4996.3  864.51  4996.6  864.01  5000.3  864.51  5004.0  864.51  5008.0  867.81
  5014.4  864.62  5022.4  869.59  5028.8  867.64  5036.8  871.65  5046.4  872.21
  5051.2  873.12  5062.6  872.99  5092.9  873.71  5107.3  872.42  5115.3  873.33
  5121.7  872.52  5128.9  874.13  5176.0  874.65  5243.3  877.11  5256.9  876.80
  5264.1  877.19  5270.5  878.88  5299.4  879.29  5313.8  881.76  5321.0  882.06
#Mann=7,-1,0
  4900.8    0.05       0  4936.6    0.12       0  4996.3    0.07       0
  5000.3    0.12       0  5046.4    0.05       0  5062.6    0.12       0
  5176.0    0.05       0
Bank Sta=4996.3,5000.3
Exp/Cntr=0.3,0.1

Type RM Length L Ch R = 1,321,0,0,0
BEGIN DESCRIPTION:
MDE S 024 1.0
END DESCRIPTION:
XS GIS Cut Line= 3
      2258729.03      7169360.01      2259079.00      7169510.00
      2259629.01      7168909.99
#Sta/Elev= 30
  4614.4  885.52  4628.9  882.94  4690.5  881.04  4757.6  876.20  4766.7  873.85
  4788.4  871.96  4919.0  869.45  4972.0  870.17  5002.2  868.89  5014.4  861.77
  5014.7  861.27  5018.4  861.77  5023.2  867.76  5037.4  869.35  5073.2  870.27
  5113.3  868.67  5299.5  869.44  5320.7  872.08  5427.1  874.00  5441.3  876.28
  5455.5  875.00  5469.6  878.02  5539.9  882.29  5547.3  884.39  5568.3  885.92
  5618.2  888.44  5625.0  887.21  5674.4  890.78  5702.7  895.42  5809.1  905.18
#Mann=5,-1,0
  4614.4    0.05       0  4972.0    0.12       0  5014.4    0.07       0
  5018.4    0.12       0  5113.3    0.05       0
Bank Sta=5014.4,5018.4
Exp/Cntr=0.3,0.1

Chan Stop Cuts=-1