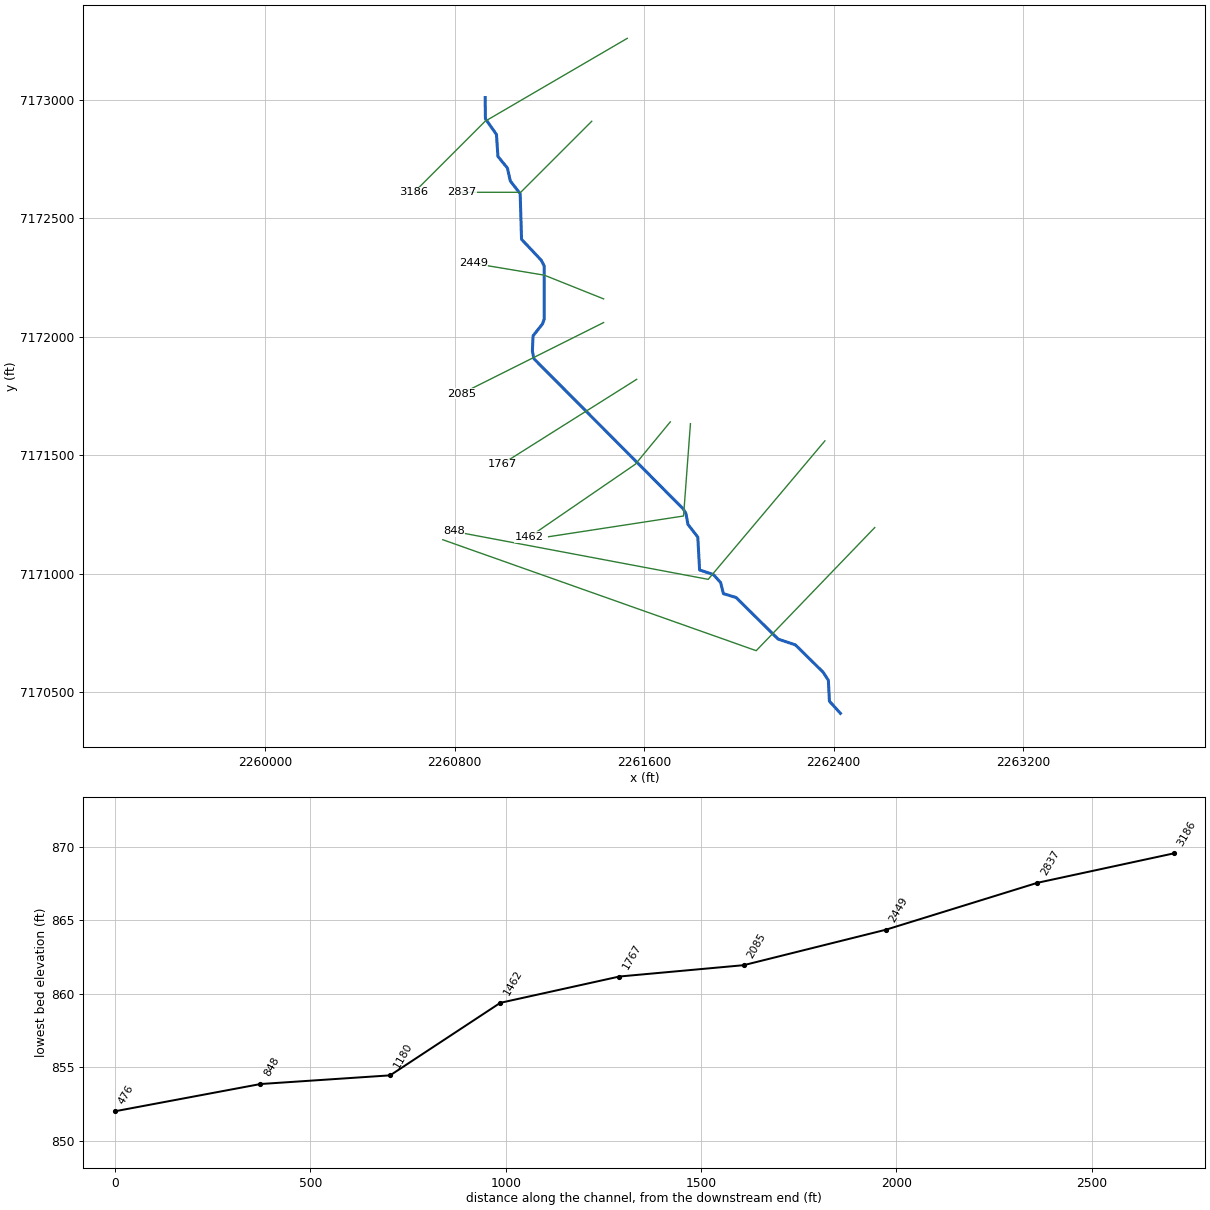
--- MDE S 025.prj (project) ---

Proj Title=MDE S 025 Base Level Engineering
Current Plan=p01
Default Exp/Contr=0.3,0.1
English Units
Geom File=g01
Flow File=f01
Plan File=p01
BEGIN DESCRIPTION:
MDE S 025
END DESCRIPTION:

--- MDE S 025.p01 (plan) ---

Plan Title=Multiple Run
Short Identifier=Multiple
Geom File=g01
Flow File=f01
Subcritical Flow
K Sum by GR= 0
Std Step Tol= 0.01
Critical Tol= 0.01
Num of Std Step Trials= 20
Max Error Tol= 0.3
Flow Tol Ratio= 0.001
Split Flow NTrial= 30
Split Flow Tol= 0.02
Split Flow Ratio= 0.02
Log Output Level= 0
Friction Slope Method= 1
Unsteady Friction Slope Method= 2
Unsteady Bridges Friction Slope Method= 1
Parabolic Critical Depth
Global Vel Dist=  1 , 1 , 1
Global Log Level= 0
CheckData=True
Encroach Param= -1, 0, 0, 0
BEGIN DESCRIPTION:
Multiple Run
END DESCRIPTION:

--- MDE S 025.f01 (steady flow) ---

Flow Title=Multiple
Number of Profiles=7
Profile Names=10-year,25-year,50-year,1pct_min,100-year,1pct_plu,500-year
River Rch & RM= MDE S 025,Reach-1,3186
     631     880    1089     671    1338    2670    2023
River Rch & RM= MDE S 025,Reach-1,848
     891    1268    1591     992    1979    3948    3069
Boundary for River Rch & Prof#=MDE S 025,Reach-1,1
Up Type=0
Dn Type=3
Dn Slope=0.005
Boundary for River Rch & Prof#=MDE S 025,Reach-1,2
Up Type=0
Dn Type=3
Dn Slope=0.005
Boundary for River Rch & Prof#=MDE S 025,Reach-1,3
Up Type=0
Dn Type=3
Dn Slope=0.005
Boundary for River Rch & Prof#=MDE S 025,Reach-1,4
Up Type=0
Dn Type=3
Dn Slope=0.005
Boundary for River Rch & Prof#=MDE S 025,Reach-1,5
Up Type=0
Dn Type=3
Dn Slope=0.005
Boundary for River Rch & Prof#=MDE S 025,Reach-1,6
Up Type=0
Dn Type=3
Dn Slope=0.005
Boundary for River Rch & Prof#=MDE S 025,Reach-1,7
Up Type=0
Dn Type=3
Dn Slope=0.005

--- MDE S 025.g01 (geometry) ---

Geom Title=Existing Conditions

River Reach=MDE S 025,Reach-1
Reach XY= 30
      2260929.00      7173010.00      2260930.02      7172920.42
      2260976.67      7172854.03      2260982.83      7172761.58
      2261022.89      7172712.18      2261035.12      7172657.82
      2261076.76      7172604.07      2261082.55      7172411.47
      2261165.60      7172323.31      2261177.94      7172299.56
      2261178.48      7172075.22      2261170.85      7172053.94
      2261131.16      7172004.02      2261128.33      7171939.92
      2261134.40      7171907.57      2261765.38      7171273.22
      2261776.50      7171253.97      2261785.14      7171207.83
      2261826.75      7171154.06      2261834.22      7171015.45
      2261892.27      7170996.34      2261923.07      7170962.19
      2261934.63      7170915.65      2261988.42      7170899.11
      2262165.79      7170723.63      2262238.68      7170699.22
      2262356.13      7170583.53      2262377.88      7170549.54
      2262382.39      7170461.41      2262429.00      7170410.00

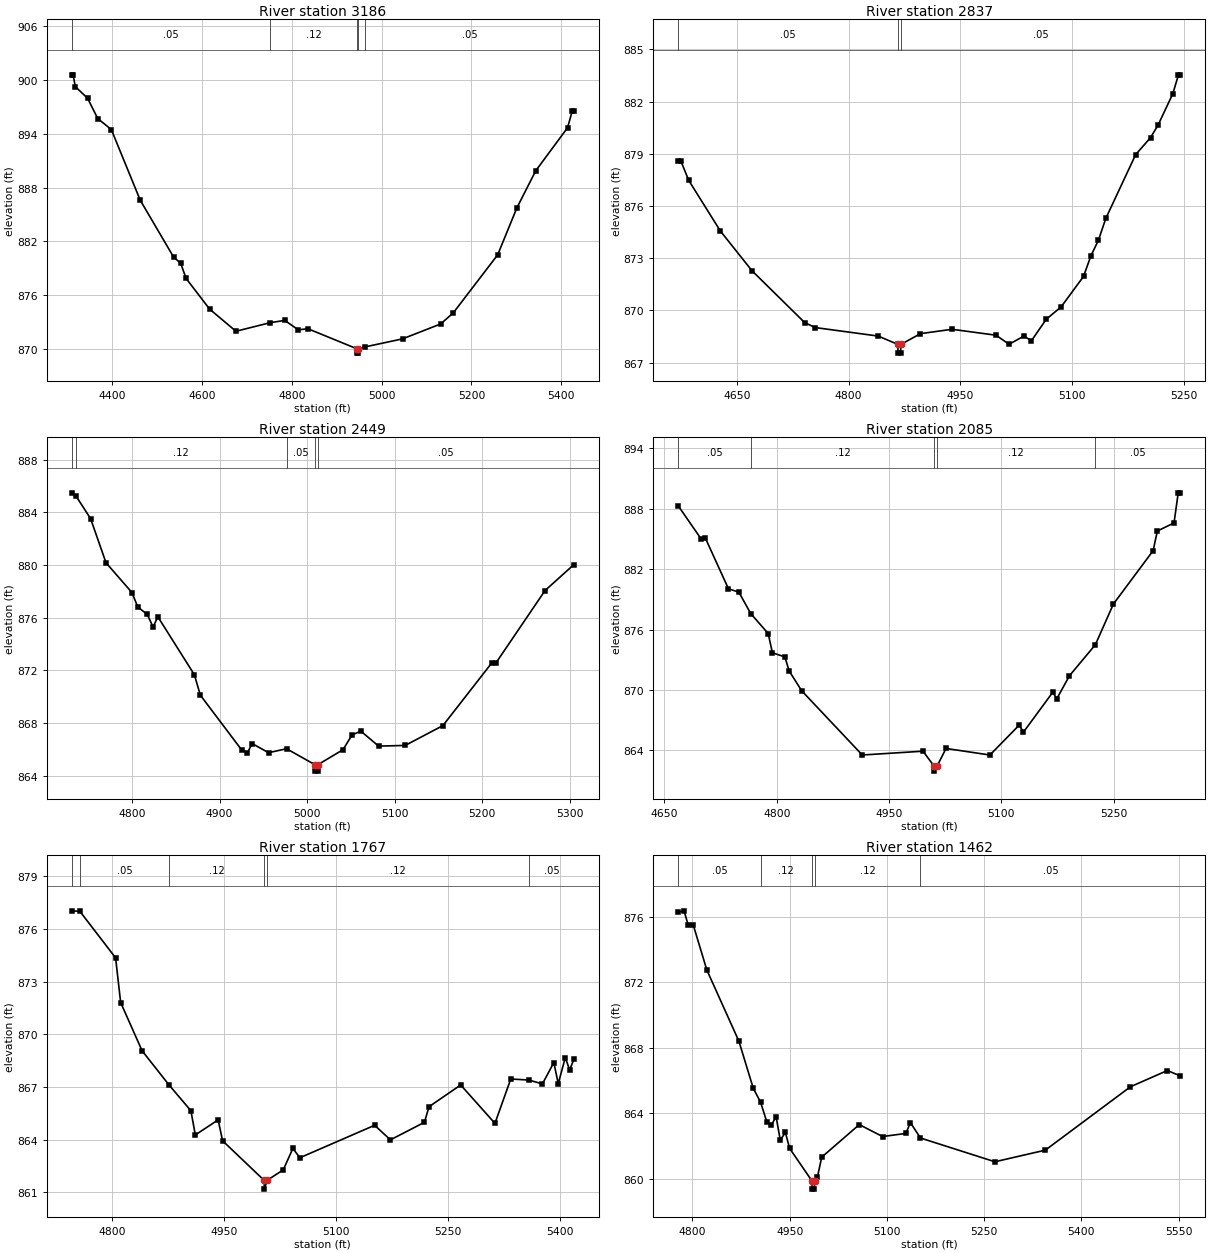
Type RM Length L Ch R = 1,3186,349,349,349
BEGIN DESCRIPTION:
MDE S 025 5.0
END DESCRIPTION:
XS GIS Cut Line= 3
      2261529.01      7173260.00      2260929.00      7172910.00
      2260629.00      7172610.00
#Sta/Elev= 30
  4309.4  900.59  4312.3  900.59  4317.3  899.27  4344.6  897.98  4367.3  895.71
  4397.5  894.49  4462.0  886.60  4536.4  880.25  4552.1  879.57  4564.1  877.88
  4616.6  874.45  4675.3  871.98  4751.7  872.94  4784.1  873.19  4814.2  872.14
  4835.7  872.26  4944.1  870.04  4944.4  869.54  4947.9  869.54  4948.1  870.04
  4963.5  870.24  5046.5  871.13  5131.3  872.79  5159.6  874.03  5258.6  880.51
  5301.0  885.71  5343.4  889.89  5414.2  894.68  5424.8  896.57  5428.3  896.57
#Mann=5,-1,0
  4309.4    0.05       0  4751.7    0.12       0  4944.1   0.033       0
  4948.1    0.12       0  4963.5    0.05       0
Bank Sta=4944.1,4948.1
Exp/Cntr=0.3,0.1

Type RM Length L Ch R = 1,2837,388,388,388
BEGIN DESCRIPTION:
MDE S 025 4.0
END DESCRIPTION:
XS GIS Cut Line= 3
      2261379.00      7172910.00      2261079.00      7172610.00
      2260828.97      7172610.00
#Sta/Elev= 30
  4571.2  878.59  4574.7  878.59  4585.3  877.47  4627.8  874.56  4670.2  872.28
  4740.9  869.30  4755.1  869.01  4839.9  868.52  4866.2  868.04  4866.4  867.54
  4869.9  867.54  4870.2  868.04  4896.5  868.66  4938.9  868.91  4998.0  868.57
  5015.5  868.05  5035.5  868.52  5045.5  868.25  5065.5  869.49  5085.5  870.20
  5115.5  871.95  5125.5  873.14  5135.5  874.03  5145.5  875.29  5185.5  878.95
  5205.5  879.93  5215.5  880.64  5235.5  882.46  5243.0  883.54  5245.5  883.54
#Mann=3,-1,0
  4571.2    0.05       0  4866.2   0.033       0  4870.2    0.05       0
Bank Sta=4866.2,4870.2
Exp/Cntr=0.3,0.1

Type RM Length L Ch R = 1,2449,364,364,364
BEGIN DESCRIPTION:
MDE S 025 3.0
END DESCRIPTION:
XS GIS Cut Line= 3
      2261429.01      7172160.00      2261179.00      7172260.00
      2260879.01      7172310.00
#Sta/Elev= 30
  4731.2  885.48  4735.7  885.27  4752.7  883.52  4770.3  880.17  4799.9  877.91
  4806.6  876.81  4817.4  876.25  4824.1  875.29  4829.5  876.07  4871.2  871.67
  4878.0  870.12  4925.1  865.97  4931.8  865.74  4937.2  866.44  4956.0  865.75
  4976.5  866.05  5008.6  864.85  5008.9  864.35  5012.4  864.35  5012.6  864.85
  5041.0  865.98  5051.2  867.09  5061.3  867.39  5081.6  866.25  5112.0  866.30
  5155.1  867.81  5210.8  872.56  5215.9  872.59  5271.7  878.06  5304.6  880.03
#Mann=5,-1,0
  4731.2    0.05       0  4735.7    0.12       0  4976.5    0.05       0
  5008.6   0.033       0  5012.6    0.05       0
Bank Sta=5008.6,5012.6
Exp/Cntr=0.3,0.1

Type RM Length L Ch R = 1,2085,318,318,318
BEGIN DESCRIPTION:
MDE S 025 2.0
END DESCRIPTION:
XS GIS Cut Line= 3
      2261428.98      7172059.99      2261129.00      7171910.00
      2260829.00      7171760.00
#Sta/Elev= 30
  4668.4  888.28  4699.1  884.98  4704.7  885.07  4735.5  880.04  4749.4  879.71
  4765.3  877.58  4788.6  875.60  4794.2  873.69  4810.9  873.28  4816.5  871.90
  4833.3  869.92  4914.3  863.54  4995.4  863.92  5010.2  862.44  5010.4  861.94
  5014.2  862.44  5026.2  864.19  5084.8  863.54  5124.0  866.51  5129.6  865.81
  5168.7  869.76  5174.3  869.14  5191.1  871.41  5225.7  874.49  5249.8  878.53
  5302.9  883.83  5308.5  885.78  5330.8  886.58  5336.4  889.57  5339.2  889.57
#Mann=5,-1,0
  4668.4    0.05       0  4765.3    0.12       0  5010.2    0.07       0
  5014.2    0.12       0  5225.7    0.05       0
Bank Sta=5010.2,5014.2
Exp/Cntr=0.3,0.1

Type RM Length L Ch R = 1,1767,305,305,305
BEGIN DESCRIPTION:
Mapping XS 3e2710fe
END DESCRIPTION:
XS GIS Cut Line= 2
      2261568.67      7171820.34      2260999.61      7171461.78
#Sta/Elev= 30
  4746.2  877.04  4757.1  877.01  4804.9  874.36  4811.7  871.81  4840.4  869.06
  4876.5  867.11  4905.8  865.64  4911.7  864.26  4942.3  865.12  4948.2  863.93
  5003.9  861.67  5004.2  861.17  5007.9  861.67  5029.5  862.27  5042.4  863.49
  5051.8  862.96  5151.9  864.81  5173.1  863.98  5218.6  864.98  5224.8  865.87
  5267.2  867.11  5313.1  864.92  5334.3  867.45  5358.6  867.39  5376.7  867.17
  5392.0  868.39  5397.9  867.18  5407.3  868.67  5413.2  867.97  5418.8  868.57
#Mann=6,-1,0
  4746.2    0.12       0  4757.1    0.05       0  4876.5    0.12       0
  5003.9    0.07       0  5007.9    0.12       0  5358.6    0.05       0
Bank Sta=5003.9,5007.9
Exp/Cntr=0.3,0.1

Type RM Length L Ch R = 1,1462,282,282,282
BEGIN DESCRIPTION:
Mapping XS b5a4d2ff
END DESCRIPTION:
XS GIS Cut Line= 3
      2261710.57      7171640.80      2261563.22      7171461.96
      2261115.61      7171154.95
#Sta/Elev= 30
  4778.1  876.29  4787.0  876.37  4793.5  875.50  4801.4  875.49  4822.2  872.76
  4871.7  868.41  4893.9  865.53  4905.0  864.70  4914.7  863.49  4921.7  863.29
  4929.1  863.80  4935.5  862.37  4943.4  862.84  4949.9  861.87  4984.4  859.88
  4984.7  859.38  4988.2  859.38  4988.4  859.88  4992.9  860.13  4999.4  861.33
  5057.4  863.32  5093.3  862.59  5129.2  862.78  5136.2  863.44  5151.8  862.50
  5266.6  861.05  5344.4  861.76  5475.7  865.63  5532.6  866.62  5552.6  866.29
#Mann=5,-1,0
  4778.1    0.05       0  4905.0    0.12       0  4984.4    0.07       0
  4988.4    0.12       0  5151.8    0.05       0
Bank Sta=4984.4,4988.4
Exp/Cntr=0.3,0.1

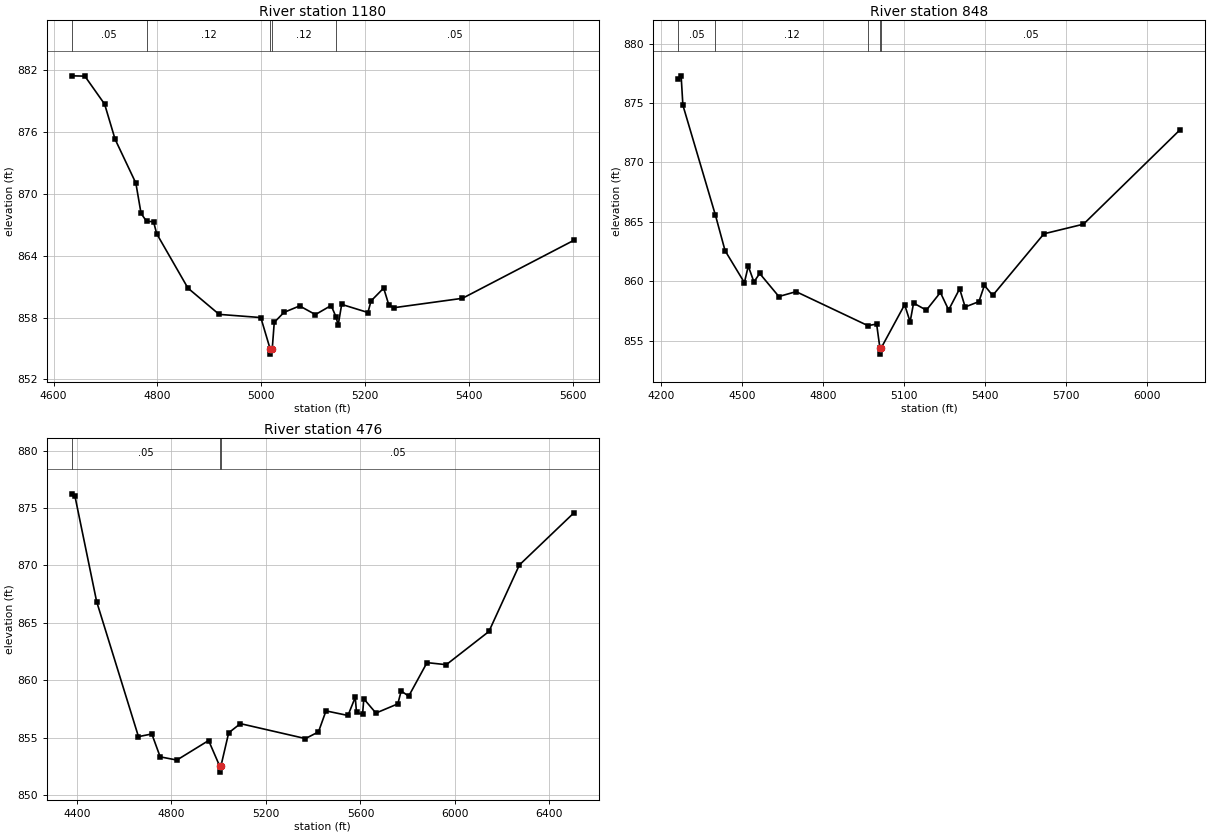
Type RM Length L Ch R = 1,1180,332,332,332
BEGIN DESCRIPTION:
Mapping XS 96a60de6
END DESCRIPTION:
XS GIS Cut Line= 3
      2261795.65      7171633.16      2261766.51      7171243.28
      2261196.85      7171155.83
#Sta/Elev= 30
  4635.2  881.47  4660.4  881.44  4698.5  878.72  4718.6  875.32  4758.7  871.05
  4768.7  868.11  4779.5  867.33  4792.7  867.32  4798.8  866.14  4859.0  860.86
  4919.1  858.31  4999.4  858.00  5017.4  854.95  5017.7  854.45  5021.4  854.95
  5025.3  857.53  5043.9  858.50  5074.2  859.13  5104.6  858.29  5134.9  859.17
  5144.5  858.04  5148.4  857.25  5155.2  859.28  5205.8  858.49  5211.7  859.61
  5236.1  860.86  5246.2  859.20  5256.3  858.96  5387.9  859.87  5602.5  865.50
#Mann=5,-1,0
  4635.2    0.05       0  4779.5    0.12       0  5017.4    0.07       0
  5021.4    0.12       0  5144.5    0.05       0
Bank Sta=5017.4,5021.4
Exp/Cntr=0.3,0.1

Type RM Length L Ch R = 1,848,372,372,372
BEGIN DESCRIPTION:
Mapping XS 3b79db57
END DESCRIPTION:
XS GIS Cut Line= 3
      2262363.15      7171560.43      2261870.70      7170975.84
      2260796.96      7171178.15
#Sta/Elev= 30
  4265.1  877.01  4275.8  877.29  4282.3  874.82  4402.9  865.54  4438.3  862.57
  4509.8  859.88  4524.1  861.27  4545.0  859.94  4566.4  860.65  4637.3  858.71
  4701.0  859.12  4966.4  856.26  4998.9  856.39  5011.1  854.36  5011.4  853.86
  5015.3  854.36  5102.4  858.02  5122.8  856.58  5135.5  858.16  5182.8  857.56
  5234.7  859.05  5265.2  857.58  5305.9  859.36  5326.3  857.83  5377.2  858.28
  5397.5  859.65  5428.1  858.80  5617.7  863.99  5763.9  864.80  6122.1  872.77
#Mann=5,-1,0
  4265.1    0.05       0  4402.9    0.12       0  4966.4    0.05       0
  5011.1   0.033       0  5015.3    0.05       0
Bank Sta=5011.1,5015.3
Exp/Cntr=0.3,0.1

Type RM Length L Ch R = 1,476,0,0,0
BEGIN DESCRIPTION:
MDE S 025 1.0
END DESCRIPTION:
XS GIS Cut Line= 3
      2262573.61      7171194.40      2262073.30      7170674.67
      2260750.07      7171143.09
#Sta/Elev= 30
  4378.0  876.23  4391.5  876.02  4483.3  866.85  4660.3  855.10  4716.9  855.33
  4752.1  853.34  4822.9  853.06  4957.2  854.76  5004.6  852.51  5005.0  852.01
  5009.0  852.51  5042.1  855.43  5091.7  856.23  5367.0  854.93  5422.2  855.51
  5454.0  857.34  5547.0  856.94  5577.9  858.52  5583.2  857.20  5608.8  857.04
  5614.1  858.39  5665.3  857.15  5758.0  857.95  5772.3  859.07  5804.1  858.62
  5881.6  861.54  5963.2  861.36  6143.6  864.25  6272.6  870.04  6503.1  874.57
#Mann=3,-1,0
  4378.0    0.05       0  5004.6   0.033       0  5009.0    0.05       0
Bank Sta=5004.6,5009
Exp/Cntr=0.3,0.1

Chan Stop Cuts=-1