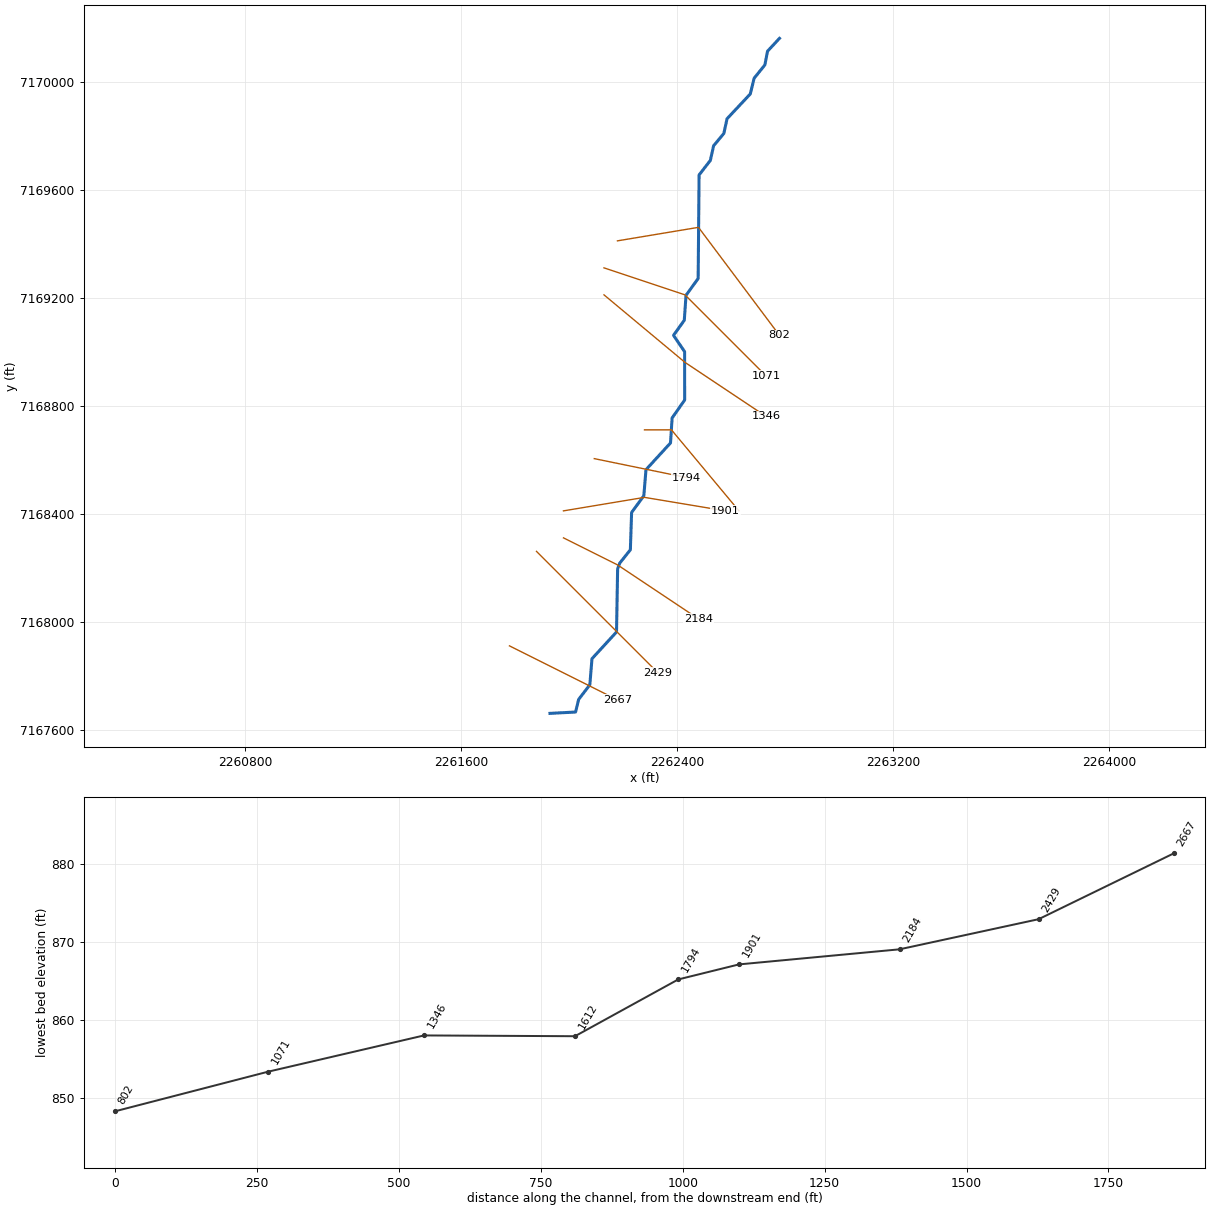
--- MDE S 026.prj (project) ---

Proj Title=MDE S 026 Base Level Engineering
Current Plan=p01
Default Exp/Contr=0.3,0.1
English Units
Geom File=g01
Flow File=f01
Plan File=p01
BEGIN DESCRIPTION:
MDE S 026
END DESCRIPTION:

--- MDE S 026.p01 (plan) ---

Plan Title=Multiple Run
Short Identifier=Multiple
Geom File=g01
Flow File=f01
Subcritical Flow
K Sum by GR= 0
Std Step Tol= 0.01
Critical Tol= 0.01
Num of Std Step Trials= 20
Max Error Tol= 0.3
Flow Tol Ratio= 0.001
Split Flow NTrial= 30
Split Flow Tol= 0.02
Split Flow Ratio= 0.02
Log Output Level= 0
Friction Slope Method= 1
Unsteady Friction Slope Method= 2
Unsteady Bridges Friction Slope Method= 1
Parabolic Critical Depth
Global Vel Dist=  1 , 1 , 1
Global Log Level= 0
CheckData=True
Encroach Param= -1, 0, 0, 0
BEGIN DESCRIPTION:
Multiple Run
END DESCRIPTION:

--- MDE S 026.f01 (steady flow) ---

Flow Title=Multiple
Number of Profiles=7
Profile Names=10-year,25-year,50-year,1pct_min,100-year,1pct_plu,500-year
River Rch & RM= MDE S 026,Reach-1,2667
     362     486     587     354     706    1410    1021
Boundary for River Rch & Prof#=MDE S 026,Reach-1,1
Up Type=0
Dn Type=3
Dn Slope=0.005
Boundary for River Rch & Prof#=MDE S 026,Reach-1,2
Up Type=0
Dn Type=3
Dn Slope=0.005
Boundary for River Rch & Prof#=MDE S 026,Reach-1,3
Up Type=0
Dn Type=3
Dn Slope=0.005
Boundary for River Rch & Prof#=MDE S 026,Reach-1,4
Up Type=0
Dn Type=3
Dn Slope=0.005
Boundary for River Rch & Prof#=MDE S 026,Reach-1,5
Up Type=0
Dn Type=3
Dn Slope=0.005
Boundary for River Rch & Prof#=MDE S 026,Reach-1,6
Up Type=0
Dn Type=3
Dn Slope=0.005
Boundary for River Rch & Prof#=MDE S 026,Reach-1,7
Up Type=0
Dn Type=3
Dn Slope=0.005

--- MDE S 026.g01 (geometry) ---

Geom Title=Existing Conditions

River Reach=MDE S 026,Reach-1
Reach XY= 30
      2261929.00      7167660.00      2262023.73      7167664.98
      2262035.25      7167711.81      2262076.68      7167765.94
      2262084.54      7167862.42      2262175.45      7167961.47
      2262179.52      7168194.78      2262187.14      7168216.06
      2262226.73      7168265.94      2262231.27      7168404.06
      2262276.64      7168465.98      2262284.54      7168562.42
      2262375.38      7168661.50      2262381.36      7168754.02
      2262427.78      7168820.50      2262427.62      7168999.56
      2262386.56      7169060.00      2262426.45      7169115.89
      2262432.85      7169208.40      2262477.78      7169270.50
      2262481.24      7169654.07      2262522.88      7169707.82
      2262535.08      7169762.20      2262572.90      7169807.81
      2262584.85      7169862.29      2262670.84      7169953.95
      2262685.09      7170012.19      2262724.96      7170061.67
      2262734.67      7170112.36      2262779.00      7170160.00

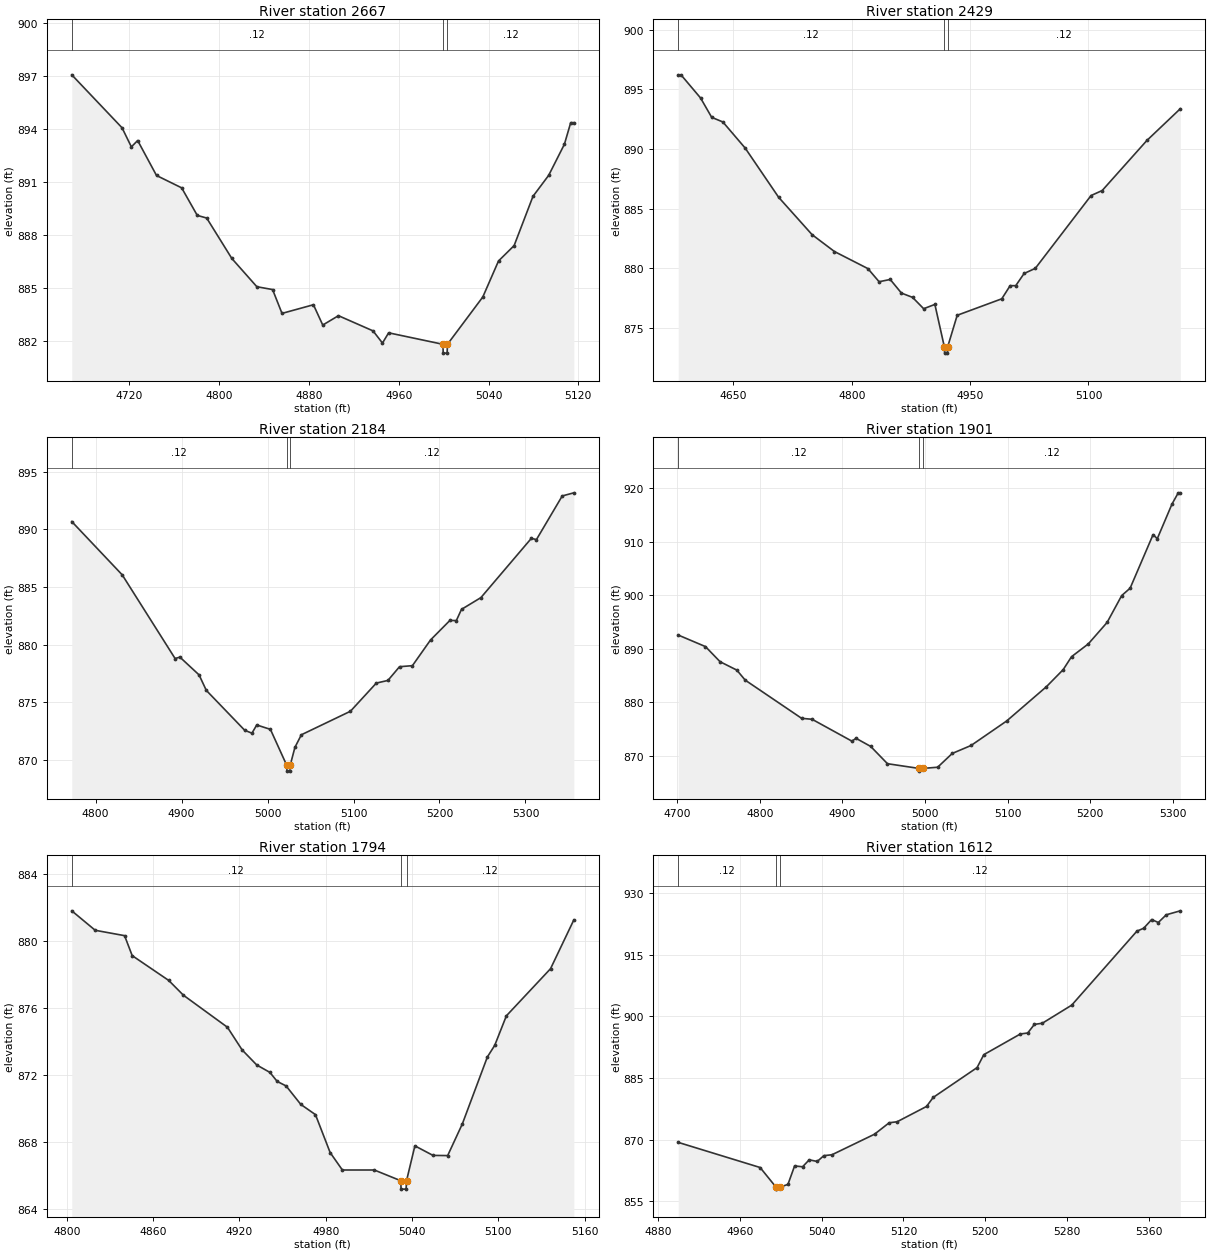
Type RM Length L Ch R = 1,2667,238,238,238
BEGIN DESCRIPTION:
MDE S 026 8.0
END DESCRIPTION:
XS GIS Cut Line= 3
      2261778.97      7167910.02      2262079.00      7167760.00
      2262179.04      7167709.98
#Sta/Elev= 30
  4668.7  897.07  4713.5  894.07  4721.8  892.99  4727.4  893.35  4744.2  891.37
  4766.6  890.67  4780.5  889.11  4788.9  888.96  4811.3  886.67  4833.6  885.07
  4847.6  884.91  4856.0  883.56  4884.0  884.05  4892.3  882.90  4906.3  883.43
  4937.1  882.57  4945.5  881.88  4951.0  882.46  4999.4  881.81  4999.6  881.31
  5003.1  881.31  5003.4  881.81  5034.9  884.49  5048.9  886.53  5062.8  887.40
  5079.6  890.19  5093.6  891.38  5107.6  893.14  5113.2  894.36  5116.0  894.36
#Mann=3,-1,0
  4668.7    0.12       0  4999.4    0.07       0  5003.4    0.12       0
Bank Sta=4999.4,5003.4
Exp/Cntr=0.3,0.1

Type RM Length L Ch R = 1,2429,245,245,245
BEGIN DESCRIPTION:
MDE S 026 7.0
END DESCRIPTION:
XS GIS Cut Line= 3
      2261878.99      7168260.01      2262179.00      7167960.00
      2262329.00      7167810.00
#Sta/Elev= 30
  4580.0  896.21  4583.5  896.21  4608.3  894.27  4622.4  892.65  4636.6  892.26
  4664.9  890.07  4707.3  885.95  4749.7  882.82  4778.0  881.41  4820.4  879.98
  4834.6  878.88  4848.7  879.07  4862.9  877.93  4877.0  877.57  4891.1  876.62
  4905.3  876.98  4917.4  873.40  4917.7  872.90  4921.2  872.90  4921.4  873.40
  4933.6  876.07  4990.1  877.45  5000.7  878.55  5007.8  878.55  5018.4  879.57
  5032.6  880.00  5103.3  886.10  5117.4  886.52  5174.0  890.71  5216.4  893.37
#Mann=3,-1,0
  4580.0    0.12       0  4917.4    0.07       0  4921.4    0.12       0
Bank Sta=4917.4,4921.4
Exp/Cntr=0.3,0.1

Type RM Length L Ch R = 1,2184,283,283,283
BEGIN DESCRIPTION:
MDE S 026 6.0
END DESCRIPTION:
XS GIS Cut Line= 3
      2261979.02      7168309.99      2262179.00      7168210.00
      2262478.97      7168010.02
#Sta/Elev= 30
  4772.2  890.68  4830.9  886.06  4892.4  878.81  4898.0  878.93  4920.3  877.39
  4928.7  876.05  4973.4  872.59  4981.8  872.34  4987.4  873.05  5003.3  872.67
  5022.3  869.55  5022.6  869.05  5026.1  869.05  5026.3  869.55  5031.8  871.11
  5039.3  872.20  5096.4  874.24  5126.5  876.68  5140.0  876.91  5153.5  878.10
  5168.5  878.19  5189.6  880.42  5212.1  882.11  5219.6  882.10  5225.6  883.07
  5248.2  884.09  5306.8  889.22  5312.8  889.12  5342.8  892.90  5356.3  893.17
#Mann=3,-1,0
  4772.2    0.12       0  5022.3    0.07       0  5026.3    0.12       0
Bank Sta=5022.3,5026.3
Exp/Cntr=0.3,0.1

Type RM Length L Ch R = 1,1901,107,107,107
BEGIN DESCRIPTION:
MDE S 026 5.0
END DESCRIPTION:
XS GIS Cut Line= 3
      2261978.99      7168410.00      2262279.00      7168460.00
      2262579.01      7168410.00
#Sta/Elev= 30
  4701.0  892.58  4734.0  890.42  4751.7  887.59  4772.0  886.02  4782.1  884.15
  4850.5  877.00  4863.2  876.82  4911.4  872.73  4916.4  873.26  4934.2  871.74
  4954.5  868.51  4993.0  867.62  4993.3  867.12  4997.0  867.62  5015.3  867.85
  5033.0  870.43  5055.8  871.92  5098.9  876.50  5147.1  882.92  5167.4  886.11
  5177.5  888.53  5197.8  890.92  5220.6  894.94  5238.3  899.97  5248.5  901.35
  5276.3  911.37  5281.4  910.61  5299.2  917.08  5306.8  919.19  5309.3  919.19
#Mann=3,-1,0
  4701.0    0.12       0  4993.0    0.07       0  4997.0    0.12       0
Bank Sta=4993,4997
Exp/Cntr=0.3,0.1

Type RM Length L Ch R = 1,1794,182,182,182
BEGIN DESCRIPTION:
Mapping XS f51a3fa5
END DESCRIPTION:
XS GIS Cut Line= 2
      2262093.02      7168603.46      2262434.90      7168533.34
#Sta/Elev= 30
  4803.5  881.79  4819.8  880.63  4840.2  880.31  4845.5  879.12  4870.9  877.64
  4881.1  876.76  4911.7  874.85  4921.9  873.50  4932.1  872.60  4941.2  872.16
  4946.3  871.62  4952.5  871.35  4962.7  870.25  4972.9  869.64  4983.1  867.38
  4991.6  866.34  5013.8  866.34  5032.2  865.70  5032.4  865.20  5035.9  865.20
  5036.2  865.70  5042.0  867.78  5054.6  867.21  5064.8  867.20  5075.0  869.09
  5092.4  873.08  5097.5  873.77  5105.6  875.53  5136.3  878.34  5152.5  881.25
#Mann=3,-1,0
  4803.5    0.12       0  5032.2    0.07       0  5036.2    0.12       0
Bank Sta=5032.2,5036.2
Exp/Cntr=0.3,0.1

Type RM Length L Ch R = 1,1612,266,266,266
BEGIN DESCRIPTION:
MDE S 026 4.0
END DESCRIPTION:
XS GIS Cut Line= 3
      2262278.96      7168710.00      2262379.00      7168710.00
      2262629.03      7168409.96
#Sta/Elev= 30
  4899.9  869.31  4979.9  863.20  4995.4  858.44  4995.7  857.94  4999.4  858.44
  5007.1  859.09  5013.6  863.58  5021.4  863.38  5027.9  865.07  5035.7  864.67
  5042.2  866.08  5050.1  866.30  5091.7  871.30  5106.0  874.08  5113.8  874.33
  5142.5  878.05  5149.0  880.24  5191.9  887.50  5198.5  890.65  5234.2  895.68
  5241.4  895.92  5247.9  898.01  5255.7  898.30  5284.4  902.70  5348.1  920.70
  5354.7  921.40  5362.5  923.52  5369.0  922.80  5376.8  924.68  5390.5  925.64
#Mann=3,-1,0
  4899.9    0.12       0  4995.4    0.07       0  4999.4    0.12       0
Bank Sta=4995.4,4999.4
Exp/Cntr=0.3,0.1

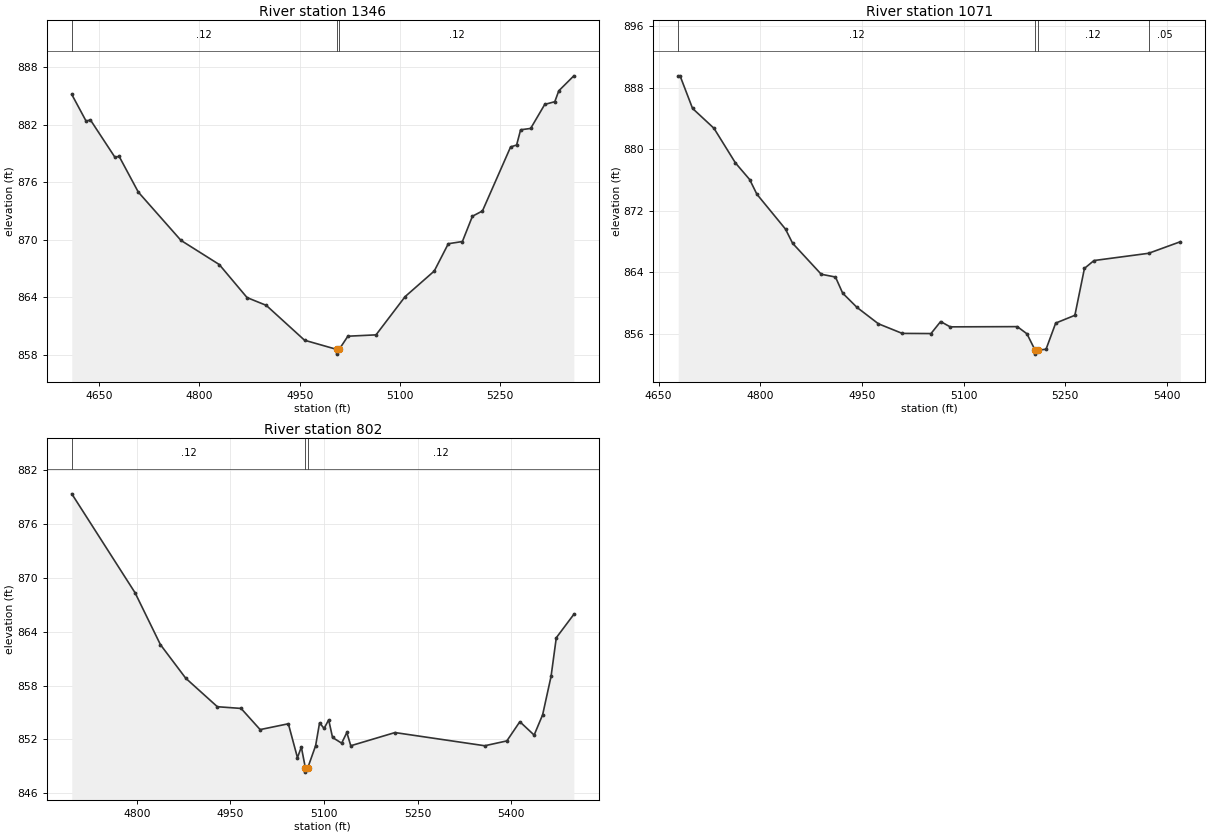
Type RM Length L Ch R = 1,1346,275,275,275
BEGIN DESCRIPTION:
MDE S 026 3.0
END DESCRIPTION:
XS GIS Cut Line= 3
      2262129.04      7169209.97      2262429.00      7168960.00
      2262728.98      7168760.01
#Sta/Elev= 30
  4609.1  885.14  4630.5  882.36  4637.0  882.48  4673.5  878.60  4680.0  878.67
  4708.6  874.95  4772.4  869.91  4829.7  867.39  4871.3  863.94  4900.0  863.13
  4957.3  859.49  5005.1  858.54  5005.3  858.04  5009.1  858.54  5022.1  859.91
  5064.2  860.05  5107.7  864.04  5151.3  866.71  5172.3  869.56  5193.4  869.79
  5208.4  872.43  5223.4  872.98  5265.5  879.66  5274.5  879.86  5280.5  881.45
  5295.5  881.59  5316.6  884.10  5331.6  884.38  5337.6  885.52  5360.1  887.08
#Mann=3,-1,0
  4609.1    0.12       0  5005.1    0.07       0  5009.1    0.12       0
Bank Sta=5005.1,5009.1
Exp/Cntr=0.3,0.1

Type RM Length L Ch R = 1,1071,269,269,269
BEGIN DESCRIPTION:
MDE S 026 2.0
END DESCRIPTION:
XS GIS Cut Line= 3
      2262128.97      7169310.01      2262429.00      7169210.00
      2262728.98      7168910.02
#Sta/Elev= 30
  4679.1  889.53  4681.8  889.53  4700.2  885.30  4731.8  882.72  4763.5  878.22
  4784.5  876.06  4795.1  874.16  4837.3  869.63  4847.8  867.79  4890.0  863.77
  4911.0  863.41  4921.6  861.32  4942.7  859.47  4974.3  857.34  5009.5  856.09
  5051.9  856.07  5066.1  857.63  5080.2  856.94  5179.2  856.97  5193.4  856.04
  5205.5  853.90  5205.7  853.40  5209.5  853.90  5221.6  854.04  5235.8  857.43
  5264.1  858.44  5278.2  864.53  5292.3  865.55  5372.8  866.49  5419.6  867.99
#Mann=4,-1,0
  4679.1    0.12       0  5205.5    0.07       0  5209.5    0.12       0
  5372.8    0.05       0
Bank Sta=5205.5,5209.5
Exp/Cntr=0.3,0.1

Type RM Length L Ch R = 1,802,0,0,0
BEGIN DESCRIPTION:
MDE S 026 1.0
END DESCRIPTION:
XS GIS Cut Line= 3
      2262178.95      7169409.99      2262479.00      7169460.00
      2262779.01      7169059.99
#Sta/Elev= 30
  4695.8  879.37  4797.2  868.34  4837.8  862.56  4878.3  858.82  4929.0  855.64
  4967.0  855.45  4997.5  853.09  5042.7  853.74  5057.3  849.96  5063.5  851.15
  5069.9  848.85  5070.1  848.35  5073.9  848.85  5086.4  851.30  5092.7  853.84
  5100.0  853.22  5107.3  854.18  5113.5  852.21  5128.1  851.58  5136.4  852.77
  5142.7  851.29  5213.5  852.76  5357.3  851.29  5392.7  851.83  5413.5  853.97
  5436.4  852.48  5450.0  854.74  5463.5  859.02  5471.9  863.33  5500.0  865.94
#Mann=3,-1,0
  4695.8    0.12       0  5069.9    0.07       0  5073.9    0.12       0
Bank Sta=5069.9,5073.9
Exp/Cntr=0.3,0.1

Chan Stop Cuts=-1