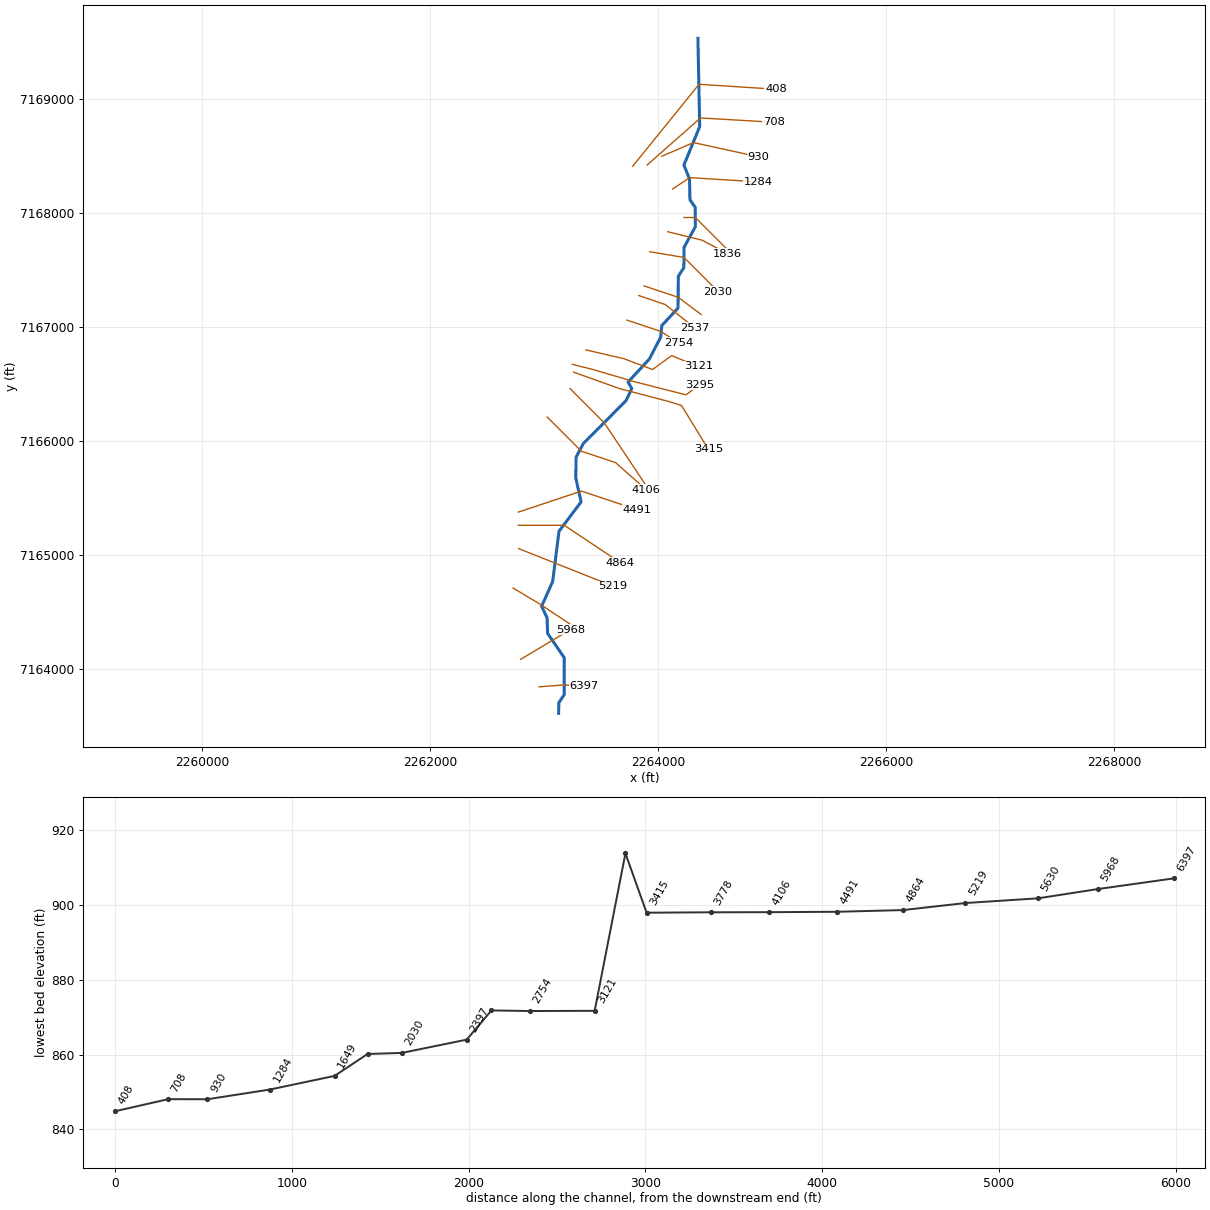
--- MDE S 027.prj (project) ---

Proj Title=MDE S 027 Base Level Engineering
Current Plan=p01
Default Exp/Contr=0.3,0.1
English Units
Geom File=g01
Flow File=f01
Plan File=p01
BEGIN DESCRIPTION:
MDE S 027
END DESCRIPTION:

--- MDE S 027.p01 (plan) ---

Plan Title=Multiple Run
Short Identifier=Multiple
Geom File=g01
Flow File=f01
Subcritical Flow
K Sum by GR= 0
Std Step Tol= 0.01
Critical Tol= 0.01
Num of Std Step Trials= 20
Max Error Tol= 0.3
Flow Tol Ratio= 0.001
Split Flow NTrial= 30
Split Flow Tol= 0.02
Split Flow Ratio= 0.02
Log Output Level= 0
Friction Slope Method= 1
Unsteady Friction Slope Method= 2
Unsteady Bridges Friction Slope Method= 1
Parabolic Critical Depth
Global Vel Dist=  1 , 1 , 1
Global Log Level= 0
CheckData=True
Encroach Param= -1, 0, 0, 0
BEGIN DESCRIPTION:
Multiple Run
END DESCRIPTION:

--- MDE S 027.f01 (steady flow) ---

Flow Title=Multiple
Number of Profiles=7
Profile Names=10-year,25-year,50-year,1pct_min,100-year,1pct_plu,500-year
River Rch & RM= MDE S 027,Reach-1,6397
     753    1054    1310     809    1614    3219    2453
Boundary for River Rch & Prof#=MDE S 027,Reach-1,1
Up Type=0
Dn Type=3
Dn Slope=0.005
Boundary for River Rch & Prof#=MDE S 027,Reach-1,2
Up Type=0
Dn Type=3
Dn Slope=0.005
Boundary for River Rch & Prof#=MDE S 027,Reach-1,3
Up Type=0
Dn Type=3
Dn Slope=0.005
Boundary for River Rch & Prof#=MDE S 027,Reach-1,4
Up Type=0
Dn Type=3
Dn Slope=0.005
Boundary for River Rch & Prof#=MDE S 027,Reach-1,5
Up Type=0
Dn Type=3
Dn Slope=0.005
Boundary for River Rch & Prof#=MDE S 027,Reach-1,6
Up Type=0
Dn Type=3
Dn Slope=0.005
Boundary for River Rch & Prof#=MDE S 027,Reach-1,7
Up Type=0
Dn Type=3
Dn Slope=0.005

--- MDE S 027.g01 (geometry) ---

Geom Title=Existing Conditions

River Reach=MDE S 027,Reach-1
Reach XY= 30
      2263129.00      7163610.00      2263131.10      7163704.13
      2263178.49      7163775.21      2263177.95      7164099.56
      2263032.76      7164311.56      2263027.75      7164449.50
      2262979.77      7164549.31      2263076.74      7164765.94
      2263132.75      7165208.45      2263326.78      7165465.91
      2263279.52      7165675.22      2263282.75      7165858.45
      2263345.64      7165976.68      2263720.88      7166353.95
      2263771.22      7166460.09      2263738.30      7166516.67
      2263925.16      7166718.62      2264025.17      7166911.59
      2264034.52      7167012.43      2264176.94      7167165.85
      2264179.52      7167444.78      2264227.78      7167520.51
      2264230.20      7167699.50      2264328.94      7167880.03
      2264327.78      7168049.49      2264281.26      7168115.94
      2264277.78      7168299.50      2264228.22      7168420.05
      2264366.97      7168758.07      2264351.27      7169532.22

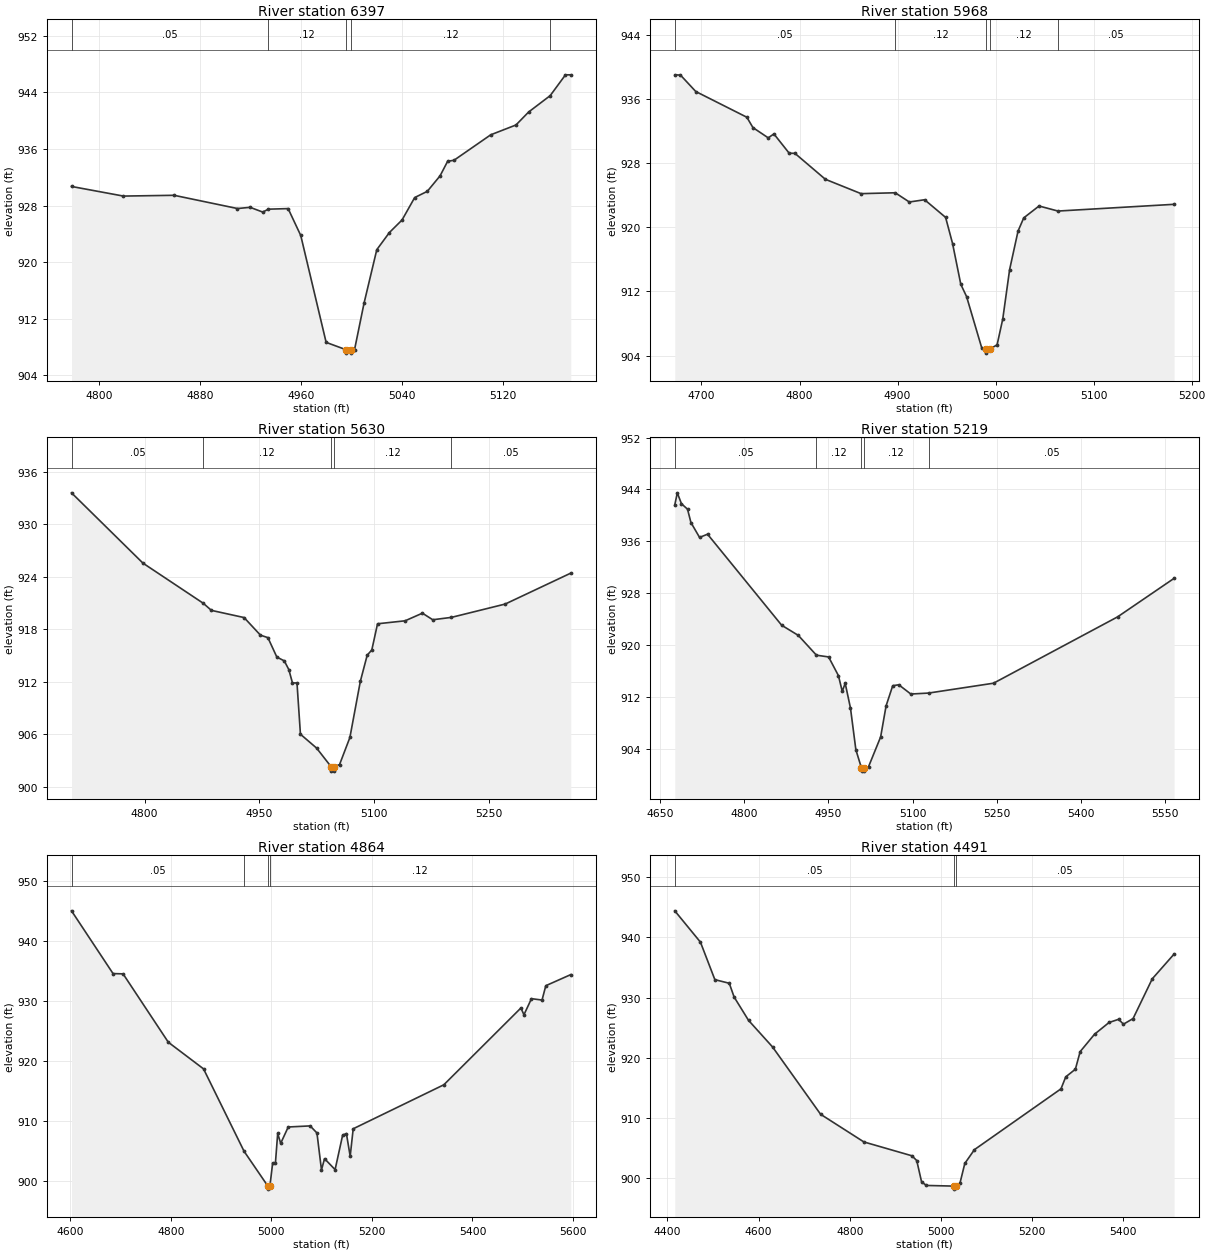
Type RM Length L Ch R = 1,6397,429,429,429
BEGIN DESCRIPTION:
MDE S 027 17.0
END DESCRIPTION:
XS GIS Cut Line= 3
      2262958.03      7163842.97      2263179.00      7163860.00
      2263352.31      7163848.75
#Sta/Elev= 30
  4778.3  930.71  4819.4  929.35  4859.5  929.46  4909.7  927.59  4919.7  927.76
  4929.7  927.09  4934.2  927.50  4949.8  927.58  4959.8  923.78  4979.9  908.67
  4995.4  907.65  4995.7  907.15  4999.2  907.15  4999.4  907.65  5002.4  907.65
  5009.9  914.20  5020.0  921.77  5030.0  924.20  5040.0  925.97  5050.0  929.14
  5060.0  930.02  5070.1  932.21  5076.1  934.27  5081.1  934.41  5110.2  938.01
  5130.2  939.40  5140.2  941.23  5157.3  943.55  5169.4  946.49  5173.6  946.49
#Mann=5,-1,0
  4778.3    0.05       0  4934.2    0.12       0  4995.4    0.07       0
  4999.4    0.12       0  5157.3    0.05       0
Bank Sta=4995.4,4999.4
Exp/Cntr=0.3,0.1

Type RM Length L Ch R = 1,5968,338,338,338
BEGIN DESCRIPTION:
Mapping XS c2daa382
END DESCRIPTION:
XS GIS Cut Line= 2
      2262795.91      7164083.89      2263232.91      7164345.26
#Sta/Elev= 30
  4672.8  939.01  4678.6  938.98  4694.2  936.93  4746.3  933.72  4752.5  932.43
  4768.1  931.15  4773.9  931.64  4789.5  929.23  4795.3  929.22  4826.4  925.98
  4862.8  924.19  4897.6  924.30  4912.0  923.15  4927.6  923.43  4949.0  921.23
  4956.1  917.97  4964.5  912.88  4970.4  911.35  4985.9  904.93  4989.8  904.80
  4990.0  904.30  4993.8  904.80  5001.5  905.33  5007.3  908.56  5014.3  914.73
  5022.9  919.53  5028.7  921.17  5044.3  922.65  5063.6  922.02  5182.0  922.86
#Mann=5,-1,0
  4672.8    0.05       0  4897.6    0.12       0  4989.8    0.07       0
  4993.8    0.12       0  5063.6    0.05       0
Bank Sta=4989.8,4993.8
Exp/Cntr=0.3,0.1

Type RM Length L Ch R = 1,5630,411,411,411
BEGIN DESCRIPTION:
MDE S 027 15.0
END DESCRIPTION:
XS GIS Cut Line= 3
      2262729.02      7164709.99      2262979.00      7164560.00
      2263279.02      7164359.99
#Sta/Elev= 30
  4704.6  933.57  4797.9  925.55  4876.7  920.97  4887.3  920.16  4930.0  919.34
  4951.4  917.33  4961.1  917.05  4972.8  914.83  4982.5  914.40  4988.4  913.41
  4993.2  911.88  4999.1  911.88  5003.6  906.03  5024.7  904.45  5043.7  902.32
  5044.0  901.82  5047.5  901.82  5047.7  902.32  5054.7  902.57  5068.2  905.66
  5081.8  912.05  5090.8  915.05  5096.8  915.64  5104.3  918.63  5140.3  918.97
  5162.9  919.84  5176.4  919.09  5200.8  919.36  5271.0  920.88  5356.7  924.41
#Mann=5,-1,0
  4704.6    0.05       0  4876.7    0.12       0  5043.7    0.07       0
  5047.7    0.12       0  5200.8    0.05       0
Bank Sta=5043.7,5047.7
Exp/Cntr=0.3,0.1

Type RM Length L Ch R = 1,5219,355,355,355
BEGIN DESCRIPTION:
Mapping XS 9e8866b2
END DESCRIPTION:
XS GIS Cut Line= 4
      2262777.90      7165055.89      2262932.95      7164994.21
      2263438.13      7164793.23      2263605.14      7164726.79
#Sta/Elev= 30
  4676.1  941.61  4680.6  943.48  4688.0  941.80  4698.8  940.96  4704.9  938.90
  4720.3  936.60  4734.5  937.10  4866.7  923.06  4896.4  921.49  4928.7  918.44
  4950.4  918.17  4967.9  915.29  4974.7  912.87  4980.0  914.10  4989.4  910.28
  4999.0  903.86  5008.9  901.06  5009.2  900.56  5012.7  900.56  5012.9  901.06
  5021.7  901.26  5043.2  905.84  5052.9  910.63  5064.7  913.73  5075.5  913.88
  5097.0  912.45  5128.7  912.60  5244.5  914.12  5465.7  924.35  5566.4  930.29
#Mann=5,-1,0
  4676.1    0.05       0  4928.7    0.12       0  5008.9    0.07       0
  5012.9    0.12       0  5128.7    0.05       0
Bank Sta=5008.9,5012.9
Exp/Cntr=0.3,0.1

Type RM Length L Ch R = 1,4864,373,373,373
BEGIN DESCRIPTION:
MDE S 027 13.0
END DESCRIPTION:
XS GIS Cut Line= 5
      2262776.40      7165260.00      2263029.00      7165260.00
      2263179.00      7165260.00      2263479.00      7165060.00
      2263670.33      7164932.45
#Sta/Elev= 30
  4602.5  945.02  4685.1  934.57  4705.1  934.52  4795.1  923.13  4865.1  918.70
  4945.7  904.98  4993.1  899.17  4993.3  898.67  4997.1  899.17  5002.6  903.01
  5008.1  903.01  5012.6  907.94  5018.6  906.30  5033.6  909.02  5077.2  909.20
  5090.7  908.02  5099.7  901.87  5105.8  903.74  5126.8  901.92  5141.8  907.66
  5149.3  907.92  5156.8  904.15  5162.8  908.72  5343.1  916.05  5496.4  928.84
  5502.4  927.71  5517.4  930.39  5538.4  930.16  5545.9  932.55  5595.6  934.40
#Mann=4,-1,0
  4602.5    0.05       0  4945.7    0.12       0  4993.1    0.07       0
  4997.1    0.12       0
Bank Sta=4993.1,4997.1
Exp/Cntr=0.3,0.1

Type RM Length L Ch R = 1,4491,385,385,385
BEGIN DESCRIPTION:
MDE S 027 12.0
END DESCRIPTION:
XS GIS Cut Line= 5
      2262775.60      7165375.54      2263029.00      7165460.00
      2263329.00      7165560.00      2263629.00      7165460.00
      2263814.32      7165398.23
#Sta/Elev= 30
  4416.2  944.40  4472.5  939.20  4504.1  932.98  4535.7  932.38  4546.3  930.10
  4577.9  926.23  4630.6  921.81  4736.0  910.64  4830.9  906.05  4936.3  903.75
  4946.8  902.96  4957.4  899.43  4967.9  898.83  5029.2  898.72  5029.4  898.22
  5033.2  898.72  5041.7  899.24  5052.2  902.48  5073.3  904.77  5263.1  914.86
  5273.6  916.85  5294.7  918.12  5305.2  921.04  5336.8  923.93  5368.5  925.87
  5389.5  926.40  5400.1  925.59  5421.2  926.52  5463.3  933.12  5511.1  937.22
#Mann=3,-1,0
  4416.2    0.05       0  5029.2   0.033       0  5033.2    0.05       0
Bank Sta=5029.2,5033.2
Exp/Cntr=0.3,0.1

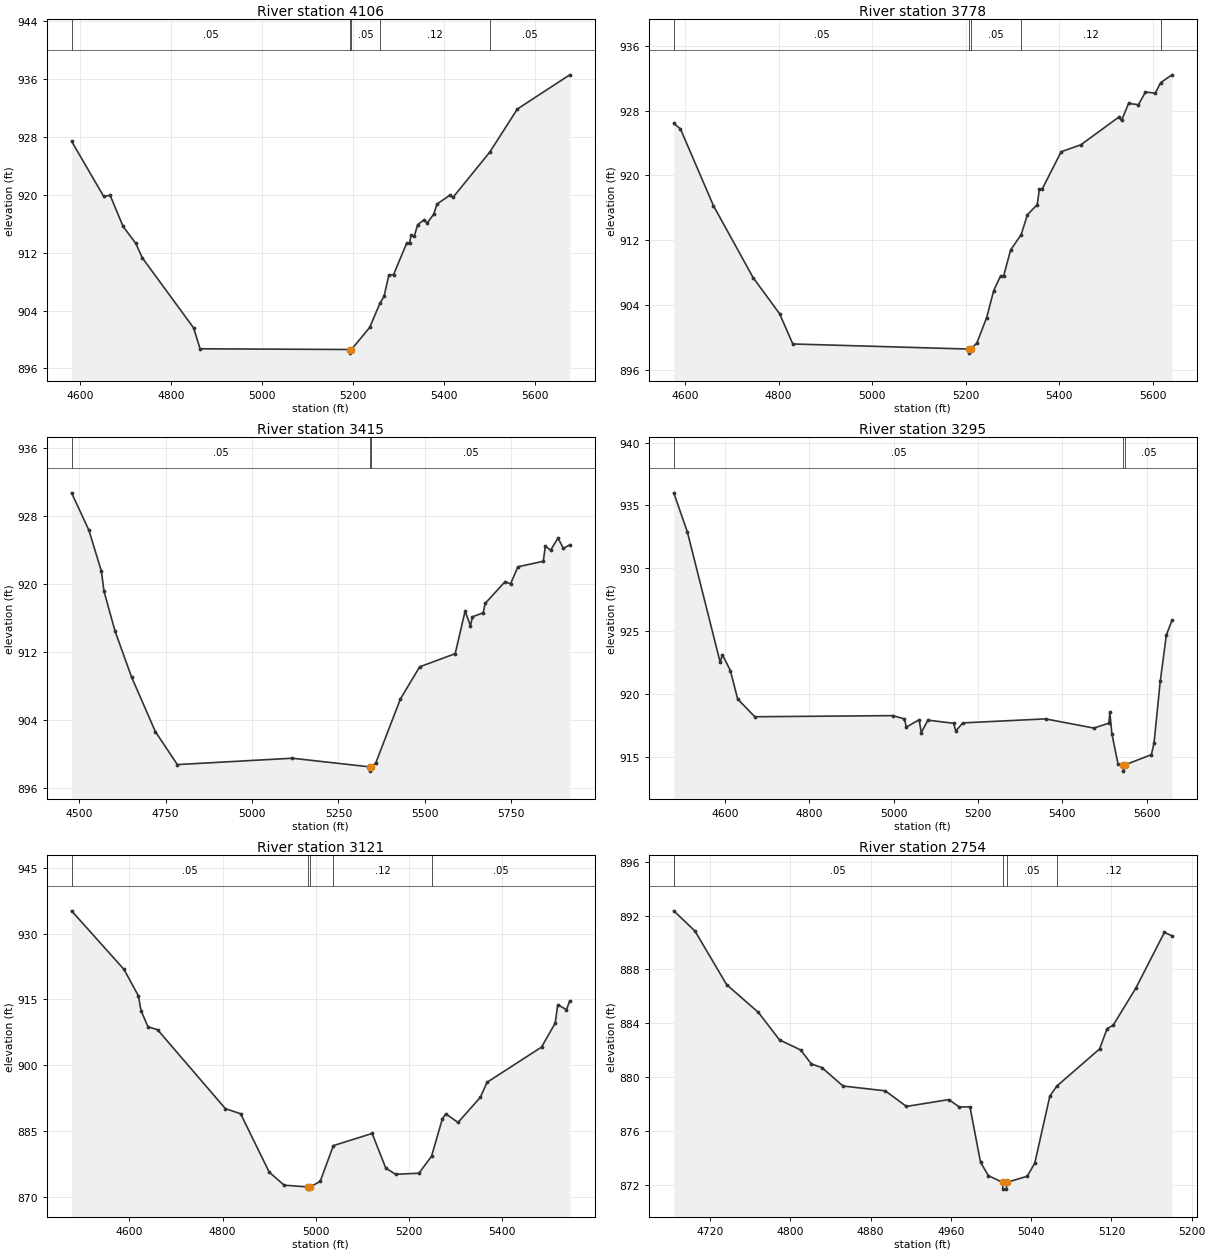
Type RM Length L Ch R = 1,4106,328,328,328
BEGIN DESCRIPTION:
MDE S 027 11.0
END DESCRIPTION:
XS GIS Cut Line= 4
      2263028.98      7166210.02      2263329.00      7165910.00
      2263629.00      7165810.00      2263895.27      7165573.43
#Sta/Elev= 30
  4580.8  927.41  4651.5  919.78  4665.7  919.93  4694.0  915.65  4722.2  913.28
  4736.4  911.30  4849.5  901.59  4863.7  898.71  5192.8  898.61  5193.1  898.11
  5196.8  898.61  5237.0  901.66  5259.6  905.00  5268.6  905.95  5279.2  908.88
  5289.7  908.98  5318.7  913.35  5324.7  913.35  5328.4  914.46  5335.1  914.24
  5342.6  915.87  5356.9  916.55  5363.5  916.08  5377.8  917.30  5385.3  918.72
  5413.7  919.95  5420.4  919.64  5501.6  925.92  5562.1  931.86  5677.5  936.59
#Mann=5,-1,0
  4580.8    0.05       0  5192.8   0.033       0  5196.8    0.05       0
  5259.6    0.12       0  5501.6    0.05       0
Bank Sta=5192.8,5196.8
Exp/Cntr=0.3,0.1

Type RM Length L Ch R = 1,3778,363,363,363
BEGIN DESCRIPTION:
MDE S 027 10.0
END DESCRIPTION:
XS GIS Cut Line= 4
      2263228.97      7166460.03      2263529.00      7166160.00
      2263729.00      7165860.00      2263884.62      7165626.58
#Sta/Elev= 30
  4575.7  926.41  4589.9  925.74  4660.6  916.26  4745.4  907.39  4802.0  902.94
  4830.3  899.21  5206.8  898.58  5207.1  898.08  5210.8  898.58  5223.8  899.32
  5244.9  902.47  5259.9  905.79  5274.9  907.64  5280.9  907.55  5296.0  910.79
  5318.7  912.70  5332.0  915.15  5353.0  916.39  5357.6  918.32  5363.6  918.32
  5404.1  922.91  5446.2  923.77  5527.3  927.18  5533.3  926.77  5548.3  928.87
  5569.4  928.72  5584.4  930.28  5605.4  930.14  5616.9  931.43  5641.1  932.40
#Mann=5,-1,0
  4575.7    0.05       0  5206.8   0.033       0  5210.8    0.05       0
  5318.7    0.12       0  5616.9    0.05       0
Bank Sta=5206.8,5210.8
Exp/Cntr=0.3,0.1

Type RM Length L Ch R = 1,3415,120,120,120
BEGIN DESCRIPTION:
Mapping XS 2d781af3
END DESCRIPTION:
XS GIS Cut Line= 6
      2263260.67      7166603.33      2263666.91      7166458.37
      2264088.83      7166347.87      2264207.60      7166310.84
      2264345.71      7166085.26      2264442.47      7165927.21
#Sta/Elev= 30
  4477.9  930.74  4528.2  926.32  4564.3  921.49  4571.7  919.16  4603.5  914.48
  4651.4  909.06  4720.3  902.63  4784.0  898.74  5116.4  899.49  5340.9  898.47
  5341.1  897.97  5344.9  898.47  5358.1  898.92  5429.4  906.46  5485.2  910.25
  5588.0  911.80  5616.7  916.81  5632.2  915.09  5638.0  916.14  5668.9  916.61
  5674.8  917.72  5732.6  920.29  5748.2  920.01  5769.5  922.03  5843.0  922.68
  5848.9  924.45  5864.3  923.99  5885.6  925.42  5901.1  924.19  5919.6  924.62
#Mann=3,-1,0
  4477.9    0.05       0  5340.9   0.033       0  5344.9    0.05       0
Bank Sta=5340.9,5344.9
Exp/Cntr=0.3,0.1

Type RM Length L Ch R = 1,3295,174,174,174
BEGIN DESCRIPTION:
Mapping XS d546780e
END DESCRIPTION:
XS GIS Cut Line= 5
      2263248.87      7166671.85      2263426.90      7166627.73
      2263784.75      7166522.36      2264246.74      7166404.61
      2264364.21      7166493.28
#Sta/Elev= 30
  4479.1  936.00  4511.4  932.88  4589.1  922.50  4594.2  923.11  4613.2  921.85
  4630.5  919.58  4671.1  918.17  4998.3  918.26  5025.3  918.00  5030.5  917.35
  5060.4  917.93  5065.6  916.91  5081.2  917.90  5142.2  917.65  5147.3  917.03
  5163.8  917.68  5359.9  918.00  5474.4  917.27  5510.1  917.66  5512.3  918.51
  5517.2  916.81  5531.8  914.40  5544.3  914.34  5544.6  913.84  5548.3  914.34
  5610.8  915.15  5617.1  916.10  5631.7  920.98  5646.2  924.67  5659.5  925.85
#Mann=3,-1,0
  4479.1    0.05       0  5544.3   0.033       0  5548.3    0.05       0
Bank Sta=5544.3,5548.3
Exp/Cntr=0.3,0.1

Type RM Length L Ch R = 1,3121,367,367,367
BEGIN DESCRIPTION:
Mapping XS aa66b30d
END DESCRIPTION:
XS GIS Cut Line= 5
      2263369.36      7166798.76      2263701.30      7166721.76
      2263953.43      7166626.86      2264120.34      7166748.49
      2264353.30      7166653.41
#Sta/Elev= 30
  4476.2  935.22  4588.7  921.84  4619.5  915.82  4625.1  912.45  4640.1  908.75
  4660.6  908.09  4806.0  890.08  4838.7  888.91  4900.0  875.59  4932.0  872.61
  4983.5  872.21  4983.7  871.71  4987.5  872.21  5009.3  873.47  5037.6  881.64
  5120.7  884.41  5150.0  876.51  5170.9  875.10  5221.1  875.34  5248.1  879.21
  5271.3  887.76  5278.8  888.89  5304.9  886.92  5352.9  892.69  5367.0  896.08
  5483.9  904.12  5513.3  909.59  5518.7  913.80  5537.4  912.66  5544.5  914.67
#Mann=5,-1,0
  4476.2    0.05       0  4983.5   0.033       0  4987.5    0.05       0
  5037.6    0.12       0  5248.1    0.05       0
Bank Sta=4983.5,4987.5
Exp/Cntr=0.3,0.1

Type RM Length L Ch R = 1,2754,217,217,217
BEGIN DESCRIPTION:
MDE S 027 7.0
END DESCRIPTION:
XS GIS Cut Line= 3
      2263728.98      7167060.01      2264029.00      7166960.00
      2264178.98      7166860.02
#Sta/Elev= 30
  4683.8  892.36  4704.9  890.86  4736.5  886.87  4768.2  884.80  4789.2  882.76
  4810.3  882.01  4820.9  880.97  4831.4  880.70  4852.5  879.33  4894.6  878.97
  4915.7  877.81  4957.9  878.32  4968.4  877.77  4979.0  877.78  4989.5  873.66
  4997.4  872.66  5011.6  872.16  5011.8  871.66  5015.3  871.66  5015.6  872.16
  5036.1  872.62  5043.6  873.60  5058.6  878.58  5065.5  879.32  5108.2  882.09
  5115.7  883.60  5121.7  883.85  5144.3  886.61  5172.8  890.76  5180.3  890.50
#Mann=4,-1,0
  4683.8    0.05       0  5011.6   0.033       0  5015.6    0.05       0
  5065.5    0.12       0
Bank Sta=5011.6,5015.6
Exp/Cntr=0.3,0.1

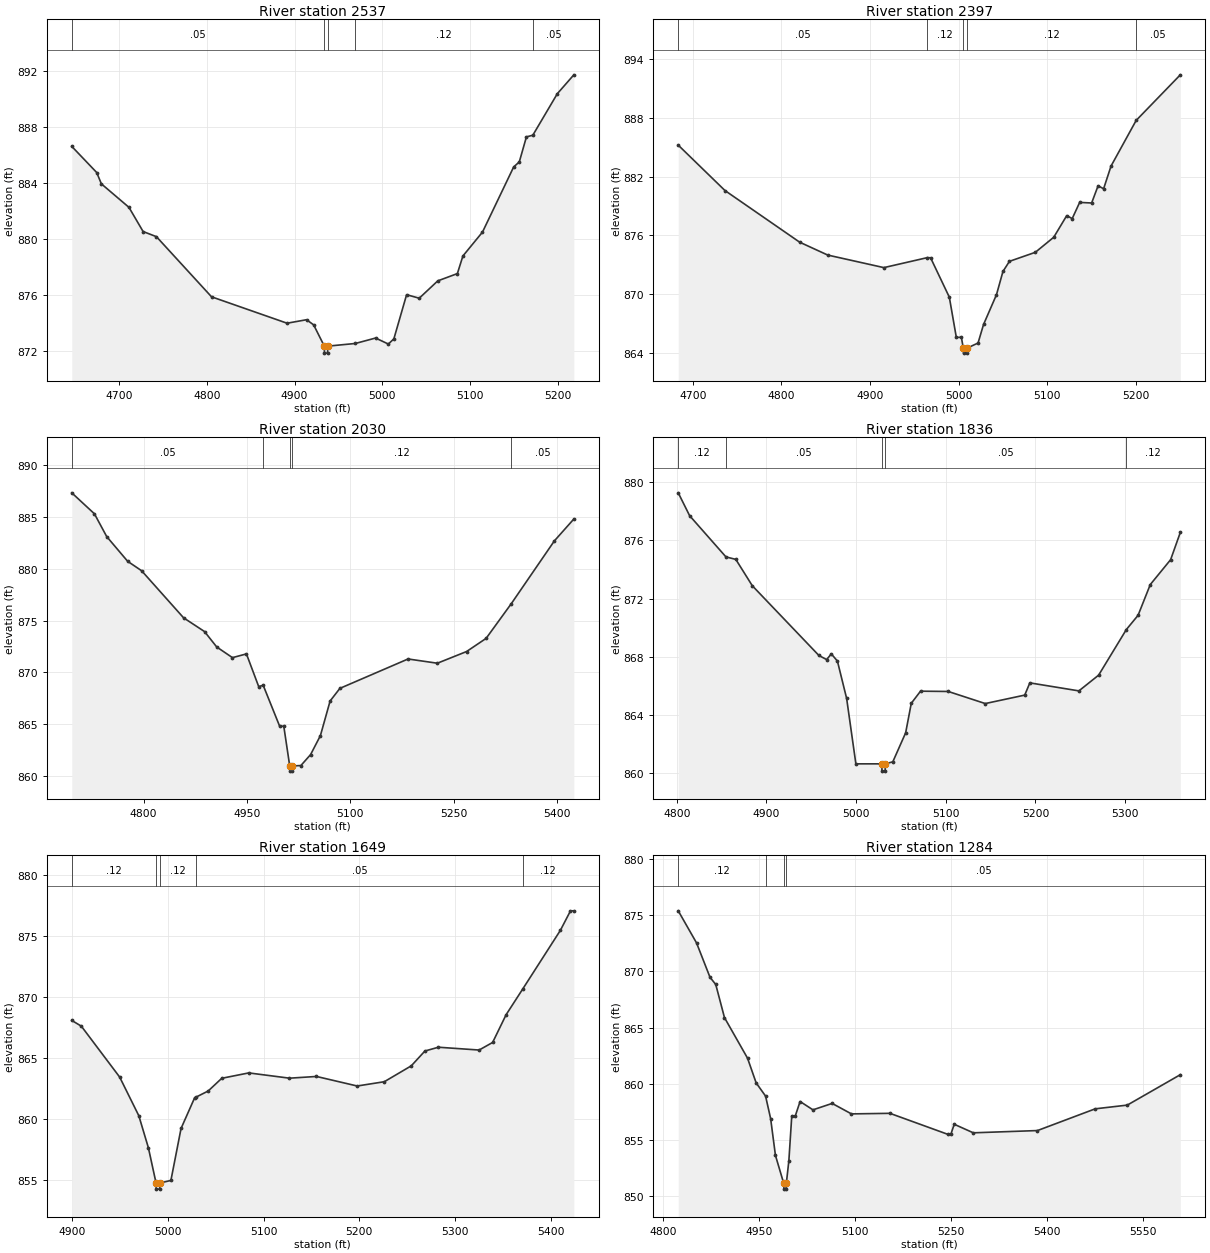
Type RM Length L Ch R = 1,2537,140,140,140
BEGIN DESCRIPTION:
Mapping XS f04835dc
END DESCRIPTION:
XS GIS Cut Line= 3
      2263832.14      7167275.92      2264064.25      7167196.76
      2264320.72      7166994.94
#Sta/Elev= 30
  4646.4  886.61  4674.8  884.74  4680.1  883.93  4711.5  882.25  4727.6  880.52
  4742.8  880.15  4805.5  875.85  4891.5  873.96  4913.7  874.21  4921.8  873.84
  4933.9  872.32  4934.1  871.82  4937.6  871.82  4937.9  872.32  4969.2  872.51
  4992.3  872.90  5006.8  872.47  5013.1  872.84  5027.6  876.00  5042.0  875.75
  5063.1  876.99  5085.4  877.51  5091.7  878.77  5114.0  880.48  5149.5  885.14
  5155.9  885.50  5164.0  887.29  5171.3  887.41  5199.2  890.38  5218.0  891.73
#Mann=5,-1,0
  4646.4    0.05       0  4933.9    0.07       0  4937.9    0.05       0
  4969.2    0.12       0  5171.3    0.05       0
Bank Sta=4933.9,4937.9
Exp/Cntr=0.3,0.1

Type RM Length L Ch R = 1,2397,367,367,367
BEGIN DESCRIPTION:
MDE S 027 6.0
END DESCRIPTION:
XS GIS Cut Line= 3
      2263879.03      7167359.99      2264179.00      7167260.00
      2264379.01      7167110.00
#Sta/Elev= 30
  4683.7  885.21  4736.4  880.58  4820.7  875.31  4852.3  874.00  4915.6  872.72
  4964.7  873.74  4968.3  873.72  4989.4  869.71  4997.3  865.61  5003.0  865.61
  5005.2  864.50  5005.4  864.00  5008.9  864.00  5009.2  864.50  5021.8  865.03
  5028.0  866.92  5042.6  869.96  5049.9  872.33  5057.2  873.36  5086.4  874.28
  5107.2  875.82  5121.8  878.02  5128.0  877.72  5136.4  879.37  5149.9  879.31
  5157.2  881.07  5163.4  880.76  5171.8  883.08  5200.1  887.73  5249.9  892.38
#Mann=5,-1,0
  4683.7    0.05       0  4964.7    0.12       0  5005.2    0.07       0
  5009.2    0.12       0  5200.1    0.05       0
Bank Sta=5005.2,5009.2
Exp/Cntr=0.3,0.1

Type RM Length L Ch R = 1,2030,194,194,194
BEGIN DESCRIPTION:
MDE S 027 5.0
END DESCRIPTION:
XS GIS Cut Line= 3
      2263929.04      7167659.99      2264229.00      7167610.00
      2264529.02      7167309.98
#Sta/Elev= 30
  4695.9  887.35  4728.8  885.32  4746.6  883.12  4777.0  880.73  4797.2  879.82
  4858.1  875.27  4888.5  873.94  4906.2  872.45  4929.0  871.42  4949.3  871.78
  4967.1  868.62  4973.6  868.75  4997.5  864.79  5003.5  864.79  5012.1  860.95
  5012.4  860.45  5015.9  860.45  5016.1  860.95  5028.3  860.99  5042.4  862.05
  5056.6  863.88  5070.7  867.23  5084.9  868.45  5183.8  871.29  5226.3  870.88
  5268.7  872.01  5297.0  873.28  5333.6  876.64  5396.0  882.70  5424.3  884.82
#Mann=5,-1,0
  4695.9    0.05       0  4973.6    0.12       0  5012.1    0.07       0
  5016.1    0.12       0  5333.6    0.05       0
Bank Sta=5012.1,5016.1
Exp/Cntr=0.3,0.1

Type RM Length L Ch R = 1,1836,187,187,187
BEGIN DESCRIPTION:
Mapping XS 1123c448
END DESCRIPTION:
XS GIS Cut Line= 3
      2264086.68      7167835.51      2264388.67      7167760.95
      2264608.57      7167644.49
#Sta/Elev= 30
  4801.6  879.27  4814.3  877.70  4854.8  874.87  4865.8  874.70  4884.2  872.89
  4958.5  868.10  4967.1  867.82  4972.3  868.21  4979.1  867.72  4989.4  865.15
  4999.7  860.66  5028.6  860.66  5028.8  860.16  5032.3  860.16  5032.6  860.66
  5040.9  860.80  5055.2  862.79  5061.5  864.82  5071.8  865.65  5102.7  865.63
  5144.0  864.80  5188.0  865.38  5193.7  866.22  5248.4  865.67  5270.4  866.75
  5301.3  869.88  5314.4  870.86  5328.0  872.97  5350.7  874.68  5361.5  876.55
#Mann=5,-1,0
  4801.6    0.12       0  4854.8    0.05       0  5028.6   0.033       0
  5032.6    0.05       0  5301.3    0.12       0
Bank Sta=5028.6,5032.6
Exp/Cntr=0.3,0.1

Type RM Length L Ch R = 1,1649,365,365,365
BEGIN DESCRIPTION:
MDE S 027 4.0
END DESCRIPTION:
XS GIS Cut Line= 3
      2264229.02      7167960.00      2264329.00      7167960.00
      2264628.97      7167660.03
#Sta/Elev= 30
  4899.8  868.08  4909.8  867.61  4949.8  863.45  4969.8  860.29  4979.8  857.67
  4987.8  854.79  4988.0  854.29  4991.5  854.29  4991.8  854.79  5003.3  855.00
  5013.9  859.25  5028.1  861.76  5030.0  861.83  5042.2  862.31  5056.4  863.35
  5084.6  863.79  5127.1  863.36  5155.3  863.50  5197.8  862.72  5226.1  863.07
  5254.3  864.37  5268.5  865.58  5282.6  865.89  5325.1  865.66  5339.2  866.28
  5353.3  868.55  5370.8  870.67  5409.9  875.44  5420.5  877.04  5424.0  877.04
#Mann=5,-1,0
  4899.8    0.12       0  4987.8    0.07       0  4991.8    0.12       0
  5030.0    0.05       0  5370.8    0.12       0
Bank Sta=4987.8,4991.8
Exp/Cntr=0.3,0.1

Type RM Length L Ch R = 1,1284,354,354,354
BEGIN DESCRIPTION:
MDE S 027 3.0
END DESCRIPTION:
XS GIS Cut Line= 3
      2264128.96      7168209.97      2264279.00      7168310.00
      2264881.65      7168273.17
#Sta/Elev= 30
  4823.9  875.36  4852.5  872.51  4873.5  869.46  4882.5  868.82  4896.1  865.88
  4932.1  862.28  4945.6  860.08  4960.3  858.91  4968.2  856.91  4975.7  853.65
  4988.7  851.15  4989.0  850.65  4992.5  850.65  4992.7  851.15  4996.7  853.19
  5001.2  857.15  5006.7  857.15  5014.2  858.43  5034.3  857.69  5064.3  858.26
  5094.4  857.33  5154.5  857.38  5244.7  855.52  5249.9  855.56  5254.9  856.41
  5284.7  855.65  5384.9  855.85  5475.1  857.78  5525.2  858.11  5608.0  860.81
#Mann=4,-1,0
  4823.9    0.12       0  4960.3    0.05       0  4988.7   0.033       0
  4992.7    0.05       0
Bank Sta=4988.7,4992.7
Exp/Cntr=0.3,0.1

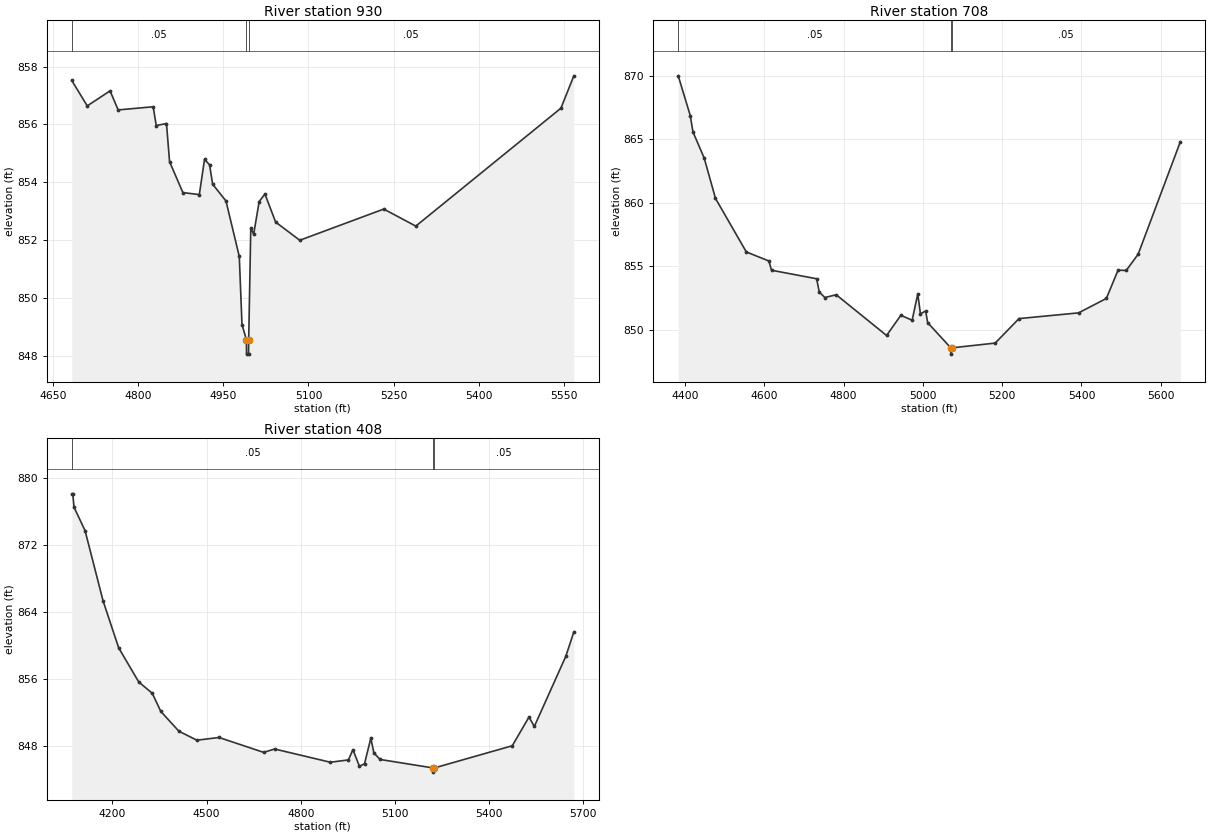
Type RM Length L Ch R = 1,930,222,222,222
BEGIN DESCRIPTION:
MDE S 027 2.0
END DESCRIPTION:
XS GIS Cut Line= 3
      2264033.93      7168497.35      2264312.79      7168617.70
      2264881.32      7168493.28
#Sta/Elev= 30
  4682.4  857.52  4709.7  856.64  4750.0  857.16  4764.2  856.50  4826.0  856.61
  4831.4  855.96  4849.5  856.03  4854.9  854.71  4878.4  853.64  4907.4  853.57
  4916.6  854.79  4925.5  854.60  4930.9  853.93  4954.4  853.35  4977.9  851.43
  4982.7  849.07  4990.5  848.55  4990.7  848.05  4994.2  848.05  4994.5  848.55
  4998.2  852.41  5003.3  852.20  5013.0  853.33  5023.2  853.59  5042.0  852.62
  5084.6  851.99  5232.8  853.07  5289.3  852.48  5545.3  856.56  5568.1  857.68
#Mann=3,-1,0
  4682.4    0.05       0  4990.5    0.04       0  4994.5    0.05       0
Bank Sta=4990.5,4994.5
Exp/Cntr=0.3,0.1

Type RM Length L Ch R = 1,708,300,300,300
BEGIN DESCRIPTION:
Mapping XS 5e72a961
END DESCRIPTION:
XS GIS Cut Line= 3
      2263905.66      7168420.98      2264373.78      7168833.65
      2265015.23      7168796.08
#Sta/Elev= 30
  4382.8  870.00  4413.2  866.86  4419.9  865.58  4448.3  863.52  4476.8  860.34
  4554.6  856.12  4611.5  855.41  4618.1  854.68  4731.9  854.01  4738.6  852.96
  4752.8  852.53  4781.3  852.75  4908.4  849.54  4944.4  851.13  4972.9  850.74
  4987.1  852.82  4993.8  851.24  5006.9  851.47  5012.1  850.55  5070.2  848.57
  5070.4  848.07  5074.2  848.57  5182.4  848.94  5242.5  850.87  5392.7  851.32
  5462.9  852.46  5492.4  854.69  5512.9  854.66  5543.0  855.94  5649.4  864.80
#Mann=3,-1,0
  4382.8    0.05       0  5070.2    0.04       0  5074.2    0.05       0
Bank Sta=5070.2,5074.2
Exp/Cntr=0.3,0.1

Type RM Length L Ch R = 1,408,0,0,0
BEGIN DESCRIPTION:
MDE S 027 1.0
END DESCRIPTION:
XS GIS Cut Line= 3
      2263778.99      7168409.99      2264361.07      7169129.01
      2265034.78      7169085.72
#Sta/Elev= 30
  4070.2  878.07  4073.4  878.07  4077.4  876.47  4112.6  873.67  4170.1  865.27
  4219.7  859.68  4283.6  855.61  4326.8  854.25  4354.0  852.09  4411.5  849.73
  4469.1  848.65  4539.4  848.98  4681.7  847.20  4716.9  847.60  4894.4  846.02
  4951.9  846.30  4966.3  847.52  4987.1  845.53  5003.2  845.84  5023.3  848.88
  5033.3  847.12  5053.1  846.35  5221.7  845.34  5221.9  844.84  5225.7  845.34
  5474.2  847.99  5527.5  851.42  5544.4  850.29  5644.6  858.65  5670.4  861.58
#Mann=3,-1,0
  4070.2    0.05       0  5221.7    0.04       0  5225.7    0.05       0
Bank Sta=5221.7,5225.7
Exp/Cntr=0.3,0.1

Chan Stop Cuts=-1