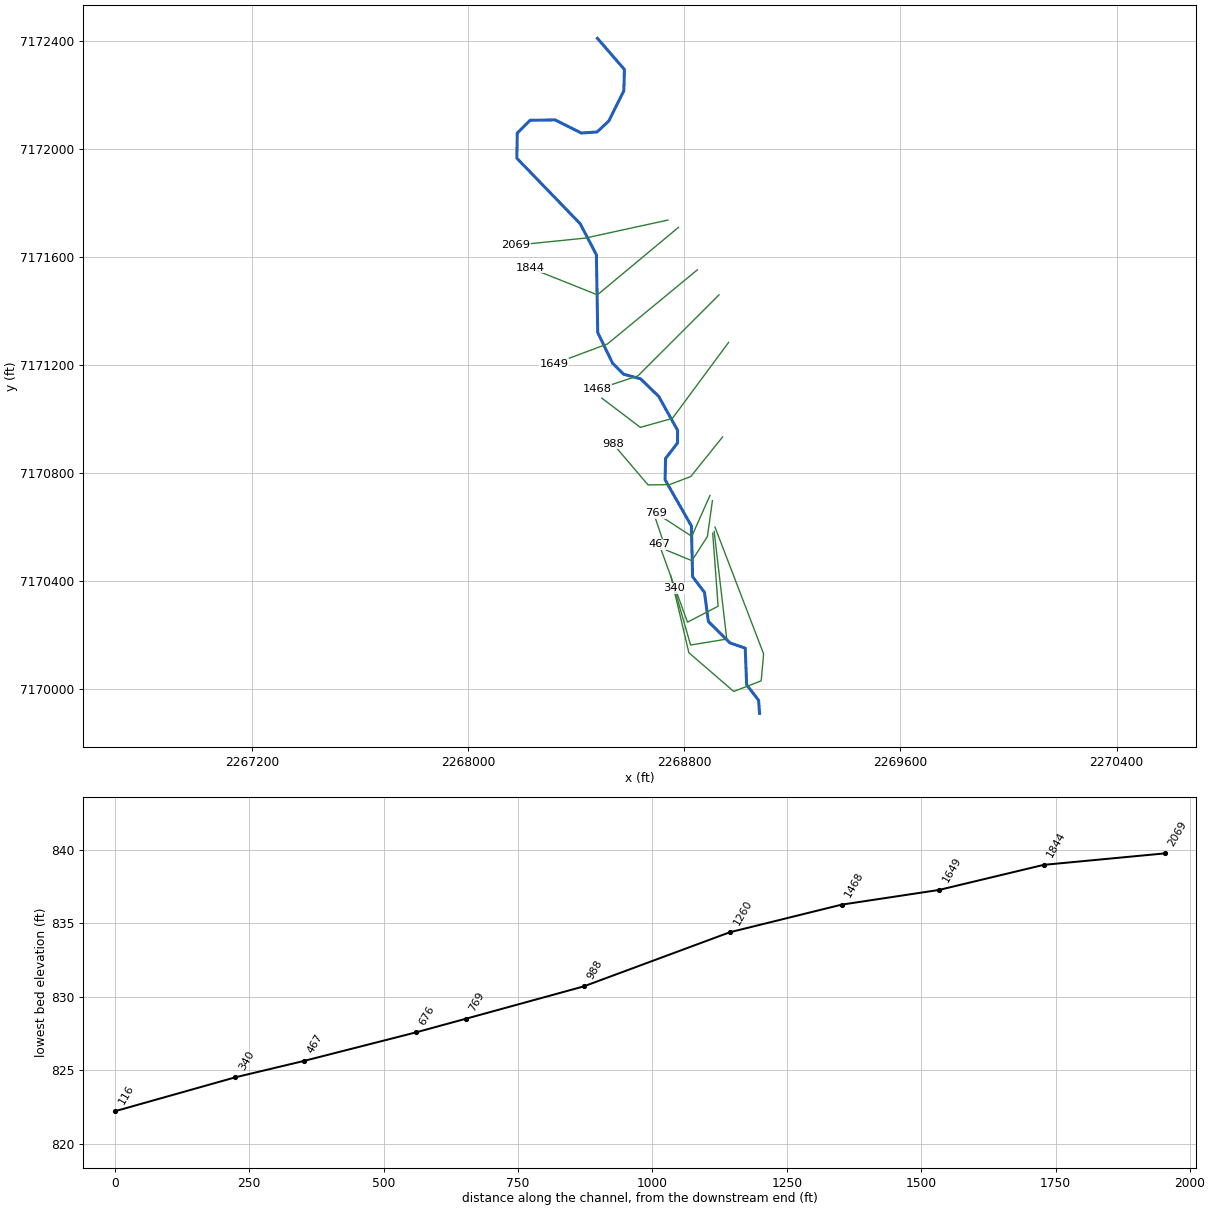
--- MDE S 028.prj (project) ---

Proj Title=MDE S 028 Base Level Engineering
Current Plan=p01
Default Exp/Contr=0.3,0.1
English Units
Geom File=g01
Flow File=f01
Plan File=p01
BEGIN DESCRIPTION:
MDE S 028
END DESCRIPTION:

--- MDE S 028.p01 (plan) ---

Plan Title=Multiple Run
Short Identifier=Multiple
Geom File=g01
Flow File=f01
Subcritical Flow
K Sum by GR= 0
Std Step Tol= 0.01
Critical Tol= 0.01
Num of Std Step Trials= 20
Max Error Tol= 0.3
Flow Tol Ratio= 0.001
Split Flow NTrial= 30
Split Flow Tol= 0.02
Split Flow Ratio= 0.02
Log Output Level= 0
Friction Slope Method= 1
Unsteady Friction Slope Method= 2
Unsteady Bridges Friction Slope Method= 1
Parabolic Critical Depth
Global Vel Dist=  1 , 1 , 1
Global Log Level= 0
CheckData=True
Encroach Param= -1, 0, 0, 0
BEGIN DESCRIPTION:
Multiple Run
END DESCRIPTION:

--- MDE S 028.f01 (steady flow) ---

Flow Title=Multiple
Number of Profiles=7
Profile Names=10-year,25-year,50-year,1pct_min,100-year,1pct_plu,500-year
River Rch & RM= MDE S 028,Reach-1,2069
     514     699     852     516    1030    2055    1507
Boundary for River Rch & Prof#=MDE S 028,Reach-1,1
Up Type=0
Dn Type=3
Dn Slope=0.02
Boundary for River Rch & Prof#=MDE S 028,Reach-1,2
Up Type=0
Dn Type=3
Dn Slope=0.02
Boundary for River Rch & Prof#=MDE S 028,Reach-1,3
Up Type=0
Dn Type=3
Dn Slope=0.02
Boundary for River Rch & Prof#=MDE S 028,Reach-1,4
Up Type=0
Dn Type=3
Dn Slope=0.02
Boundary for River Rch & Prof#=MDE S 028,Reach-1,5
Up Type=0
Dn Type=3
Dn Slope=0.02
Boundary for River Rch & Prof#=MDE S 028,Reach-1,6
Up Type=0
Dn Type=3
Dn Slope=0.02
Boundary for River Rch & Prof#=MDE S 028,Reach-1,7
Up Type=0
Dn Type=3
Dn Slope=0.02

--- MDE S 028.g01 (geometry) ---

Geom Title=Existing Conditions

River Reach=MDE S 028,Reach-1
Reach XY= 30
      2268479.00      7172410.00      2268578.78      7172294.79
      2268576.86      7172215.96      2268521.00      7172103.61
      2268477.72      7172063.37      2268418.97      7172059.20
      2268323.02      7172107.83      2268230.25      7172106.64
      2268182.36      7172058.75      2268180.96      7171965.90
      2268415.38      7171723.22      2268475.25      7171608.45
      2268480.20      7171320.50      2268534.73      7171207.45
      2268576.46      7171165.75      2268638.68      7171149.22
      2268706.01      7171083.52      2268775.66      7170958.28
      2268775.63      7170911.74      2268731.19      7170854.03
      2268729.37      7170775.27      2268826.76      7170604.07
      2268831.26      7170415.94      2268875.14      7170358.40
      2268889.51      7170250.19      2268969.60      7170170.90
      2269025.92      7170151.70      2269031.14      7170015.89
      2269075.35      7169958.49      2269079.00      7169910.00

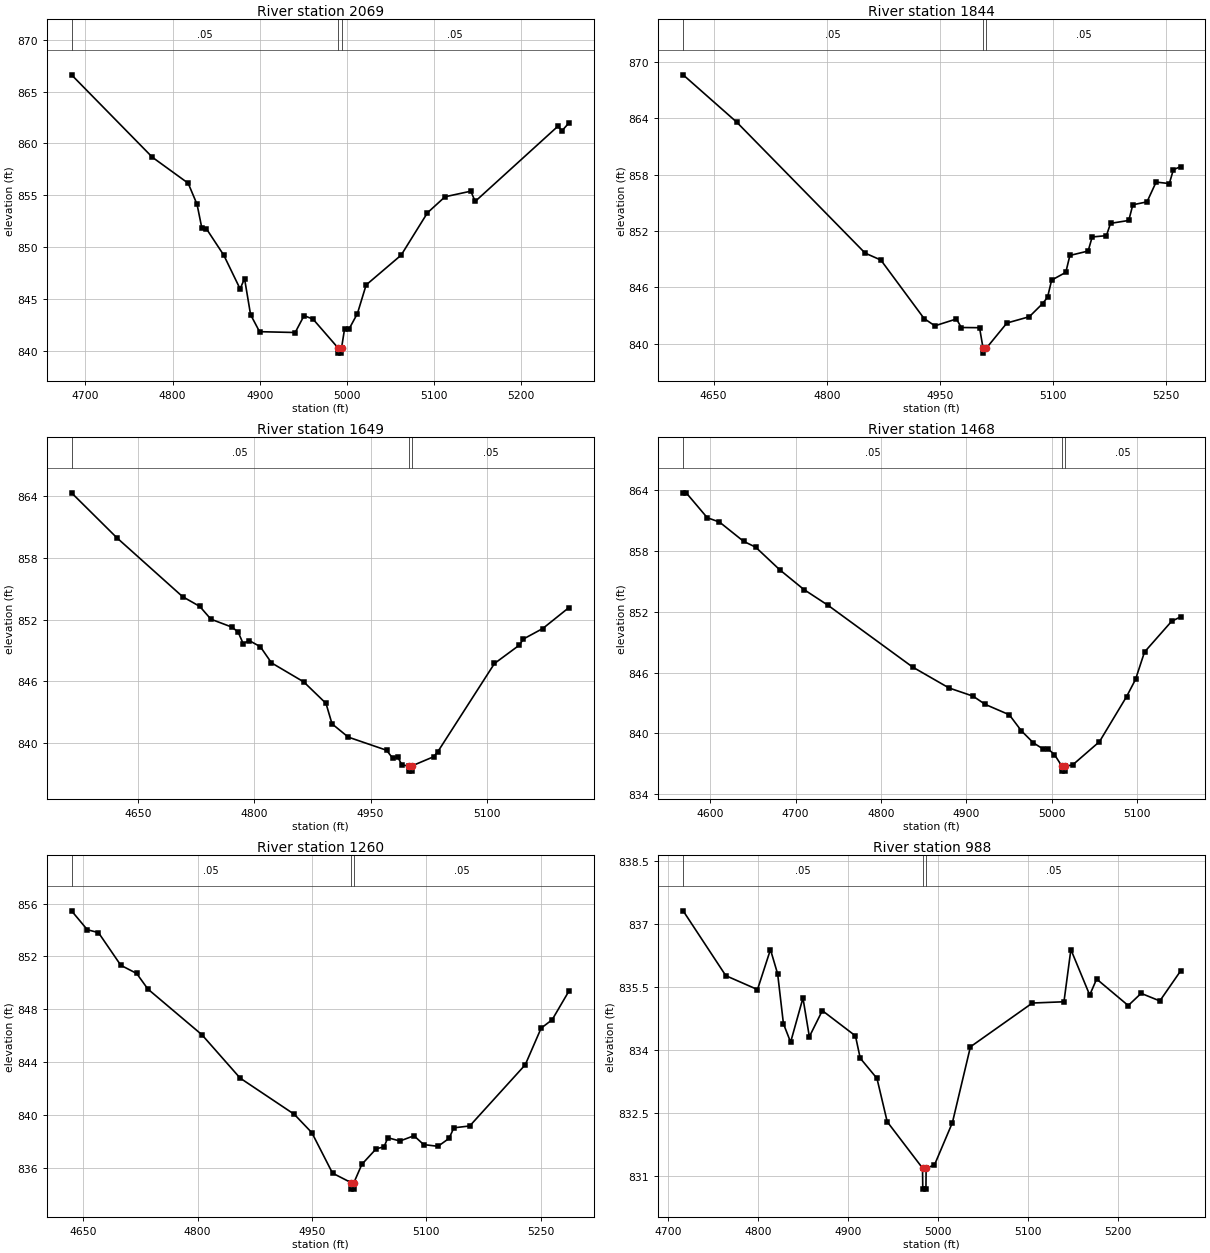
Type RM Length L Ch R = 1,2069,225,225,225
BEGIN DESCRIPTION:
MDE S 028 6.0
END DESCRIPTION:
XS GIS Cut Line= 3
      2268739.68      7171736.97      2268433.32      7171670.06
      2268177.52      7171644.07
#Sta/Elev= 30
  4684.0  866.62  4776.8  858.66  4817.8  856.16  4828.0  854.12  4833.5  851.83
  4838.6  851.78  4858.7  849.21  4877.4  845.96  4882.5  846.95  4889.4  843.48
  4899.7  841.83  4940.6  841.75  4950.8  843.38  4961.1  843.04  4989.8  840.26
  4990.0  839.76  4993.5  839.76  4993.8  840.26  4997.2  842.07  5002.3  842.07
  5012.0  843.58  5022.0  846.34  5062.2  849.22  5092.4  853.31  5112.5  854.85
  5142.1  855.39  5147.1  854.40  5241.8  861.64  5246.9  861.24  5254.7  861.98
#Mann=3,-1,0
  4684.0    0.05       0  4989.8   0.033       0  4993.8    0.05       0
Bank Sta=4989.8,4993.8
Exp/Cntr=0.3,0.1

Type RM Length L Ch R = 1,1844,195,195,195
BEGIN DESCRIPTION:
MDE S 028 5.0
END DESCRIPTION:
XS GIS Cut Line= 3
      2268778.99      7171709.99      2268479.00      7171460.00
      2268228.96      7171560.02
#Sta/Elev= 30
  4609.5  868.64  4680.4  863.61  4850.9  849.64  4871.8  848.90  4929.1  842.67
  4943.4  841.89  4972.0  842.62  4978.5  841.71  5002.7  841.69  5007.4  839.48
  5007.7  838.98  5011.4  839.48  5039.0  842.19  5068.7  842.86  5086.2  844.25
  5092.9  844.94  5098.3  846.76  5117.1  847.59  5122.5  849.39  5146.7  849.86
  5152.1  851.36  5171.0  851.50  5176.4  852.81  5200.6  853.12  5206.0  854.79
  5224.8  855.10  5236.9  857.21  5254.4  857.05  5259.8  858.53  5269.3  858.85
#Mann=3,-1,0
  4609.5    0.05       0  5007.4    0.04       0  5011.4    0.05       0
Bank Sta=5007.4,5011.4
Exp/Cntr=0.3,0.1

Type RM Length L Ch R = 1,1649,181,181,181
BEGIN DESCRIPTION:
Mapping XS 222a2fd9
END DESCRIPTION:
XS GIS Cut Line= 3
      2268848.85      7171552.58      2268516.20      7171278.17
      2268318.96      7171204.42
#Sta/Elev= 30
  4564.1  864.34  4622.7  859.96  4707.4  854.24  4729.6  853.29  4743.9  852.05
  4771.3  851.27  4779.1  850.79  4785.5  849.68  4793.4  849.97  4807.7  849.37
  4822.1  847.80  4863.7  845.95  4892.4  843.86  4900.2  841.87  4921.1  840.58
  4970.6  839.30  4978.4  838.53  4984.9  838.66  4990.3  837.88  4999.0  837.77
  4999.3  837.27  5002.8  837.27  5003.0  837.77  5031.3  838.67  5036.7  839.16
  5109.8  847.74  5141.8  849.52  5147.1  850.12  5172.1  851.14  5205.9  853.18
#Mann=3,-1,0
  4564.1    0.05       0  4999.0    0.04       0  5003.0    0.05       0
Bank Sta=4999,5003
Exp/Cntr=0.3,0.1

Type RM Length L Ch R = 1,1468,208,208,208
BEGIN DESCRIPTION:
MDE S 028 4.0
END DESCRIPTION:
XS GIS Cut Line= 3
      2268929.02      7171460.02      2268629.00      7171160.00
      2268479.00      7171110.00
#Sta/Elev= 30
  4568.3  863.73  4571.9  863.73  4596.6  861.27  4610.8  860.85  4639.0  858.95
  4653.2  858.37  4681.5  856.13  4709.7  854.19  4738.0  852.63  4837.0  846.54
  4879.5  844.48  4907.7  843.67  4921.9  842.86  4950.2  841.83  4964.3  840.25
  4978.4  839.06  4989.1  838.49  4995.2  838.49  5003.1  837.90  5011.7  836.77
  5011.9  836.27  5015.4  836.27  5015.7  836.77  5024.2  836.87  5055.8  839.18
  5087.5  843.62  5098.0  845.32  5108.5  848.02  5140.2  851.05  5150.7  851.49
#Mann=3,-1,0
  4568.3    0.05       0  5011.7    0.04       0  5015.7    0.05       0
Bank Sta=5011.7,5015.7
Exp/Cntr=0.3,0.1

Type RM Length L Ch R = 1,1260,272,272,272
BEGIN DESCRIPTION:
Mapping XS b7dba4e7
END DESCRIPTION:
XS GIS Cut Line= 4
      2268964.53      7171284.02      2268756.42      7171002.35
      2268637.91      7170969.22      2268495.42      7171077.45
#Sta/Elev= 30
  4634.8  855.45  4655.5  854.02  4670.1  853.80  4699.4  851.33  4720.2  850.71
  4734.9  849.53  4805.8  846.07  4855.9  842.79  4926.9  840.05  4949.9  838.66
  4977.0  835.60  5001.1  834.89  5001.3  834.39  5004.8  834.39  5005.1  834.89
  5015.5  836.27  5034.2  837.44  5044.5  837.59  5049.6  838.28  5065.4  838.03
  5083.8  838.43  5096.5  837.76  5115.3  837.63  5129.8  838.23  5136.1  839.03
  5156.9  839.17  5229.7  843.80  5250.5  846.57  5265.0  847.21  5287.0  849.38
#Mann=3,-1,0
  4634.8    0.05       0  5001.1    0.04       0  5005.1    0.05       0
Bank Sta=5001.1,5005.1
Exp/Cntr=0.3,0.1

Type RM Length L Ch R = 1,988,219,219,219
BEGIN DESCRIPTION:
Mapping XS 19b17dfb
END DESCRIPTION:
XS GIS Cut Line= 5
      2268942.26      7170933.75      2268824.46      7170787.27
      2268745.68      7170756.98      2268666.23      7170756.23
      2268536.18      7170909.06
#Sta/Elev= 30
  4717.1  837.31  4764.5  835.77  4799.7  835.44  4814.1  836.39  4822.1  835.81
  4828.5  834.63  4836.5  834.19  4850.2  835.24  4857.3  834.32  4871.7  834.94
  4908.5  834.34  4913.8  833.81  4932.4  833.33  4943.8  832.30  4983.0  831.20
  4983.3  830.70  4986.8  830.70  4987.0  831.20  4996.2  831.27  5016.2  832.28
  5036.2  834.08  5105.0  835.12  5140.1  835.15  5147.8  836.39  5168.7  835.31
  5176.4  835.69  5211.5  835.06  5225.8  835.35  5246.6  835.17  5269.6  835.88
#Mann=3,-1,0
  4717.1    0.05       0  4983.0   0.033       0  4987.0    0.05       0
Bank Sta=4983,4987
Exp/Cntr=0.3,0.1

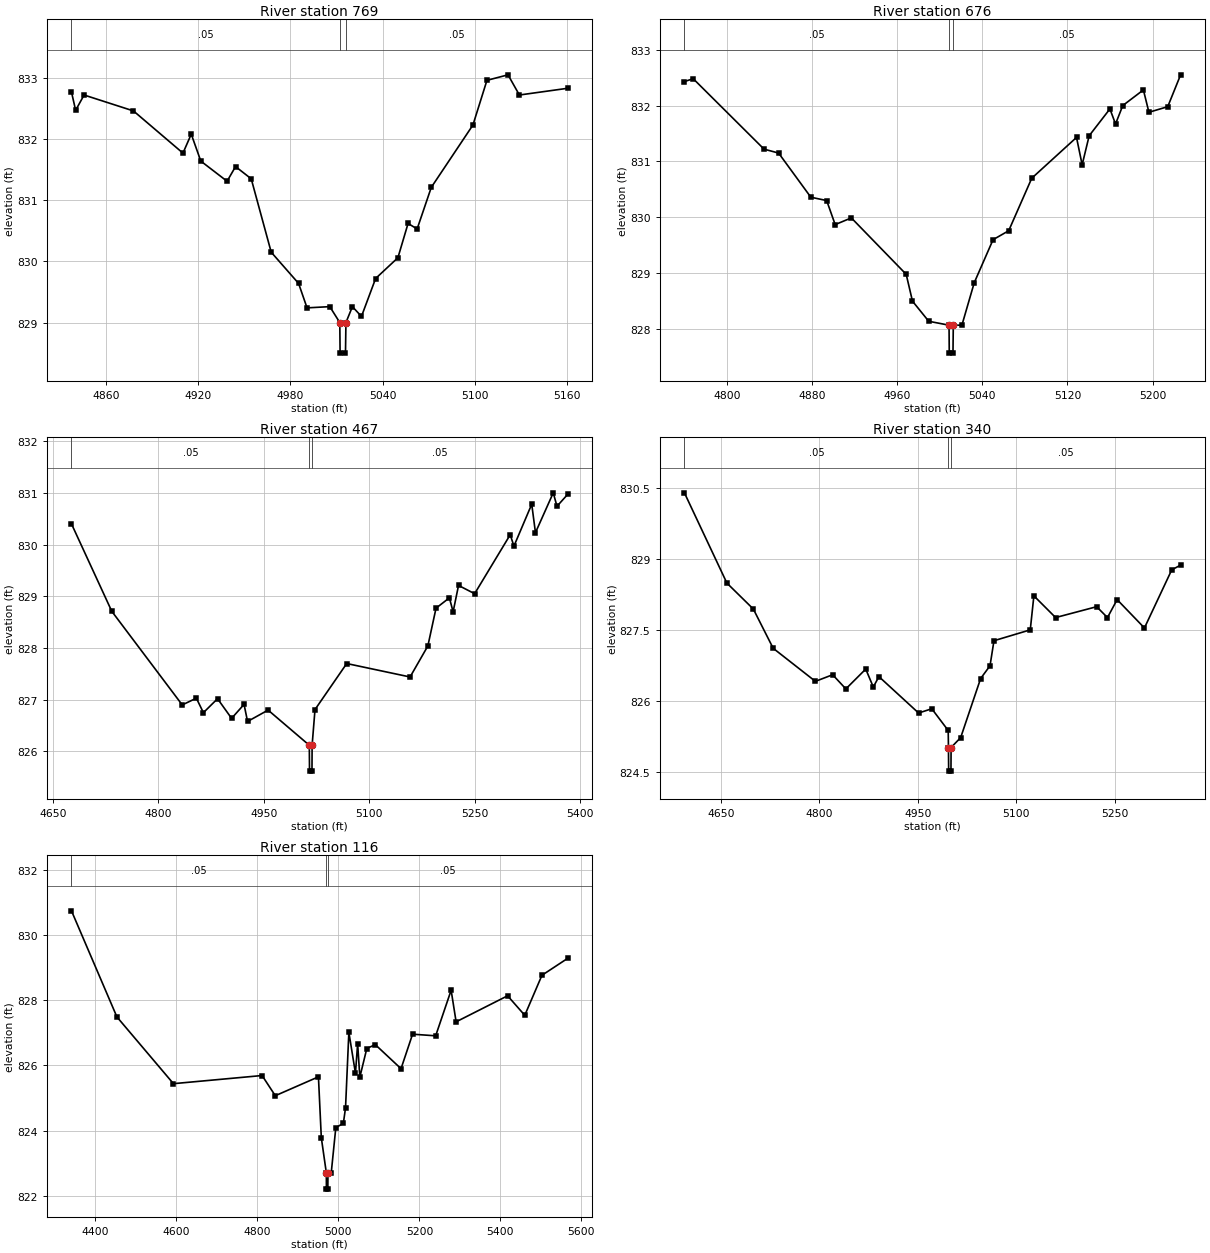
Type RM Length L Ch R = 1,769,93,93,93
BEGIN DESCRIPTION:
Mapping XS 94af567d
END DESCRIPTION:
XS GIS Cut Line= 3
      2268895.40      7170716.83      2268828.14      7170565.55
      2268696.49      7170651.35
#Sta/Elev= 30
  4837.6  832.77  4840.3  832.47  4845.8  832.72  4877.9  832.46  4910.1  831.77
  4915.5  832.08  4921.7  831.64  4938.8  831.31  4944.3  831.55  4954.5  831.35
  4967.5  830.15  4985.3  829.64  4990.8  829.24  5005.6  829.26  5012.1  829.00
  5012.3  828.50  5015.8  828.50  5016.1  829.00  5020.3  829.26  5026.2  829.10
  5035.4  829.72  5049.9  830.06  5056.5  830.62  5062.4  830.53  5071.6  831.21
  5098.7  832.23  5107.8  832.96  5121.5  833.05  5128.9  832.72  5160.3  832.83
#Mann=3,-1,0
  4837.6    0.05       0  5012.1   0.033       0  5016.1    0.05       0
Bank Sta=5012.1,5016.1
Exp/Cntr=0.3,0.1

Type RM Length L Ch R = 1,676,209,209,209
BEGIN DESCRIPTION:
Mapping XS b2fd8ae0
END DESCRIPTION:
XS GIS Cut Line= 5
      2268904.51      7170697.73      2268886.09      7170565.16
      2268828.65      7170475.35      2268733.37      7170514.90
      2268693.86      7170631.47
#Sta/Elev= 30
  4759.7  832.43  4768.0  832.48  4834.6  831.22  4848.3  831.15  4878.6  830.36
  4893.5  830.30  4901.5  829.87  4916.7  829.99  4968.3  828.98  4974.2  828.50
  4989.5  828.14  5008.6  828.07  5008.8  827.57  5012.3  827.57  5012.6  828.07
  5020.7  828.07  5032.3  828.83  5050.0  829.60  5064.7  829.76  5086.4  830.70
  5128.5  831.43  5133.8  830.94  5140.4  831.46  5159.9  831.94  5165.2  831.67
  5172.0  832.00  5191.4  832.28  5196.6  831.88  5214.3  831.98  5226.4  832.55
#Mann=3,-1,0
  4759.7    0.05       0  5008.6   0.033       0  5012.6    0.05       0
Bank Sta=5008.6,5012.6
Exp/Cntr=0.3,0.1

Type RM Length L Ch R = 1,467,127,127,127
BEGIN DESCRIPTION:
Mapping XS 94c9847a
END DESCRIPTION:
XS GIS Cut Line= 4
      2268905.64      7170577.10      2268925.71      7170306.79
      2268812.27      7170247.69      2268707.61      7170535.92
#Sta/Elev= 30
  4676.3  830.40  4733.6  828.71  4833.8  826.90  4853.9  827.03  4863.9  826.75
  4884.0  827.02  4904.0  826.64  4921.7  826.91  4926.7  826.58  4955.9  826.80
  5014.5  826.12  5014.8  825.62  5018.3  825.62  5018.5  826.12  5022.6  826.81
  5067.7  827.70  5157.8  827.44  5183.1  828.04  5194.7  828.77  5213.7  828.97
  5219.0  828.70  5226.7  829.21  5249.6  829.05  5300.2  830.19  5305.5  829.97
  5330.8  830.78  5336.1  830.23  5361.4  831.00  5366.7  830.74  5381.9  830.97
#Mann=3,-1,0
  4676.3    0.05       0  5014.5   0.035       0  5018.5    0.05       0
Bank Sta=5014.5,5018.5
Exp/Cntr=0.3,0.1

Type RM Length L Ch R = 1,340,224,224,224
BEGIN DESCRIPTION:
Mapping XS 35721454
END DESCRIPTION:
XS GIS Cut Line= 4
      2268910.90      7170584.27      2268957.70      7170185.17
      2268823.77      7170163.20      2268763.50      7170372.96
#Sta/Elev= 30
  4594.5  830.40  4659.2  828.49  4699.5  827.94  4729.7  827.11  4794.0  826.41
  4820.3  826.55  4840.4  826.25  4870.7  826.67  4882.2  826.29  4890.8  826.51
  4951.2  825.74  4971.3  825.83  4996.3  825.37  4996.7  825.01  4997.0  824.51
  5000.5  824.51  5000.7  825.01  5015.3  825.22  5045.7  826.47  5060.0  826.74
  5066.0  827.27  5121.3  827.50  5126.8  828.22  5159.9  827.76  5222.4  827.99
  5238.9  827.76  5253.6  828.14  5295.2  827.54  5336.8  828.77  5350.3  828.87
#Mann=3,-1,0
  4594.5    0.05       0  4996.7   0.035       0  5000.7    0.05       0
Bank Sta=4996.7,5000.7
Exp/Cntr=0.3,0.1

Type RM Length L Ch R = 1,116,0,0,0
BEGIN DESCRIPTION:
MDE S 028 3.0
END DESCRIPTION:
XS GIS Cut Line= 6
      2268913.94      7170600.08      2269094.01      7170130.22
      2269085.00      7170030.51      2268983.53      7169991.09
      2268817.41      7170134.54      2268750.24      7170420.10
#Sta/Elev= 30
  4341.1  830.75  4453.3  827.49  4592.8  825.44  4811.7  825.69  4844.3  825.07
  4950.8  825.65  4957.9  823.78  4970.3  822.70  4970.5  822.20  4974.0  822.20
  4974.3  822.70  4982.4  822.70  4993.7  824.09  5012.3  824.22  5017.7  824.70
  5025.9  827.02  5042.2  825.76  5047.6  826.67  5053.0  825.64  5070.2  826.52
  5091.1  826.64  5154.7  825.90  5183.2  826.96  5240.2  826.91  5278.4  828.31
  5290.7  827.34  5417.8  828.14  5460.2  827.54  5502.6  828.77  5566.1  829.29
#Mann=3,-1,0
  4341.1    0.05       0  4970.3    0.04       0  4974.3    0.05       0
Bank Sta=4970.3,4974.3
Exp/Cntr=0.3,0.1

Chan Stop Cuts=-1