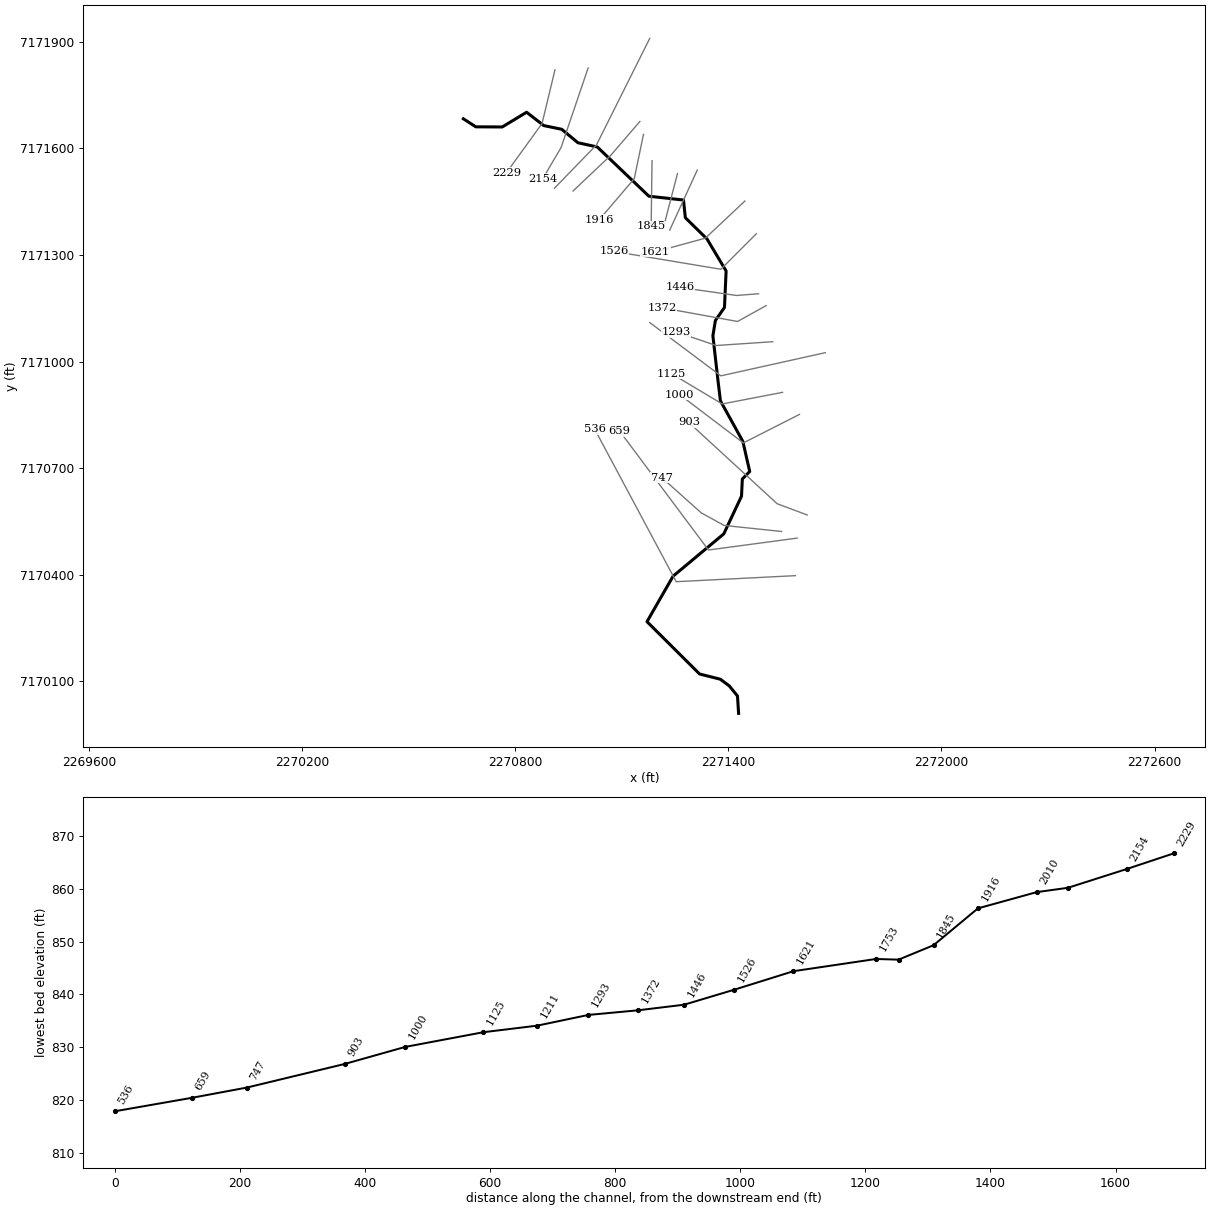
--- MDE S 029.prj (project) ---

Proj Title=MDE S 029 Base Level Engineering
Current Plan=p01
Default Exp/Contr=0.3,0.1
English Units
Geom File=g01
Flow File=f01
Plan File=p01
BEGIN DESCRIPTION:
MDE S 029
END DESCRIPTION:

--- MDE S 029.p01 (plan) ---

Plan Title=Multiple Run
Short Identifier=Multiple
Geom File=g01
Flow File=f01
Subcritical Flow
K Sum by GR= 0
Std Step Tol= 0.01
Critical Tol= 0.01
Num of Std Step Trials= 20
Max Error Tol= 0.3
Flow Tol Ratio= 0.001
Split Flow NTrial= 30
Split Flow Tol= 0.02
Split Flow Ratio= 0.02
Log Output Level= 0
Friction Slope Method= 1
Unsteady Friction Slope Method= 2
Unsteady Bridges Friction Slope Method= 1
Parabolic Critical Depth
Global Vel Dist=  1 , 1 , 1
Global Log Level= 0
CheckData=True
Encroach Param= -1, 0, 0, 0
BEGIN DESCRIPTION:
Multiple Run
END DESCRIPTION:

--- MDE S 029.f01 (steady flow) ---

Flow Title=Multiple
Number of Profiles=7
Profile Names=10-year,25-year,50-year,1pct_min,100-year,1pct_plu,500-year
River Rch & RM= MDE S 029,Reach-1,2229
      94     114     128      72     143     286     180
Boundary for River Rch & Prof#=MDE S 029,Reach-1,1
Up Type=0
Dn Type=3
Dn Slope=0.005
Boundary for River Rch & Prof#=MDE S 029,Reach-1,2
Up Type=0
Dn Type=3
Dn Slope=0.005
Boundary for River Rch & Prof#=MDE S 029,Reach-1,3
Up Type=0
Dn Type=3
Dn Slope=0.005
Boundary for River Rch & Prof#=MDE S 029,Reach-1,4
Up Type=0
Dn Type=3
Dn Slope=0.005
Boundary for River Rch & Prof#=MDE S 029,Reach-1,5
Up Type=0
Dn Type=3
Dn Slope=0.005
Boundary for River Rch & Prof#=MDE S 029,Reach-1,6
Up Type=0
Dn Type=3
Dn Slope=0.005
Boundary for River Rch & Prof#=MDE S 029,Reach-1,7
Up Type=0
Dn Type=3
Dn Slope=0.005

--- MDE S 029.g01 (geometry) ---

Geom Title=Existing Conditions

River Reach=MDE S 029,Reach-1
Reach XY= 30
      2270654.33      7171683.51      2270689.33      7171660.88
      2270763.77      7171660.51      2270832.32      7171701.95
      2270880.64      7171664.43      2270931.19      7171653.95
      2270976.81      7171616.11      2271031.30      7171604.17
      2271176.64      7171465.55      2271273.89      7171454.89
      2271279.08      7171405.15      2271340.21      7171345.11
      2271393.86      7171255.12      2271389.27      7171152.45
      2271363.68      7171115.79      2271356.68      7171072.68
      2271370.82      7170948.11      2271377.86      7170889.68
      2271441.00      7170775.50      2271460.31      7170690.75
      2271439.56      7170669.81      2271437.21      7170621.31
      2271387.34      7170515.22      2271244.58      7170396.12
      2271171.22      7170268.11      2271319.33      7170120.77
      2271377.54      7170106.14      2271402.85      7170087.27
      2271425.86      7170058.97      2271429.00      7170010.00

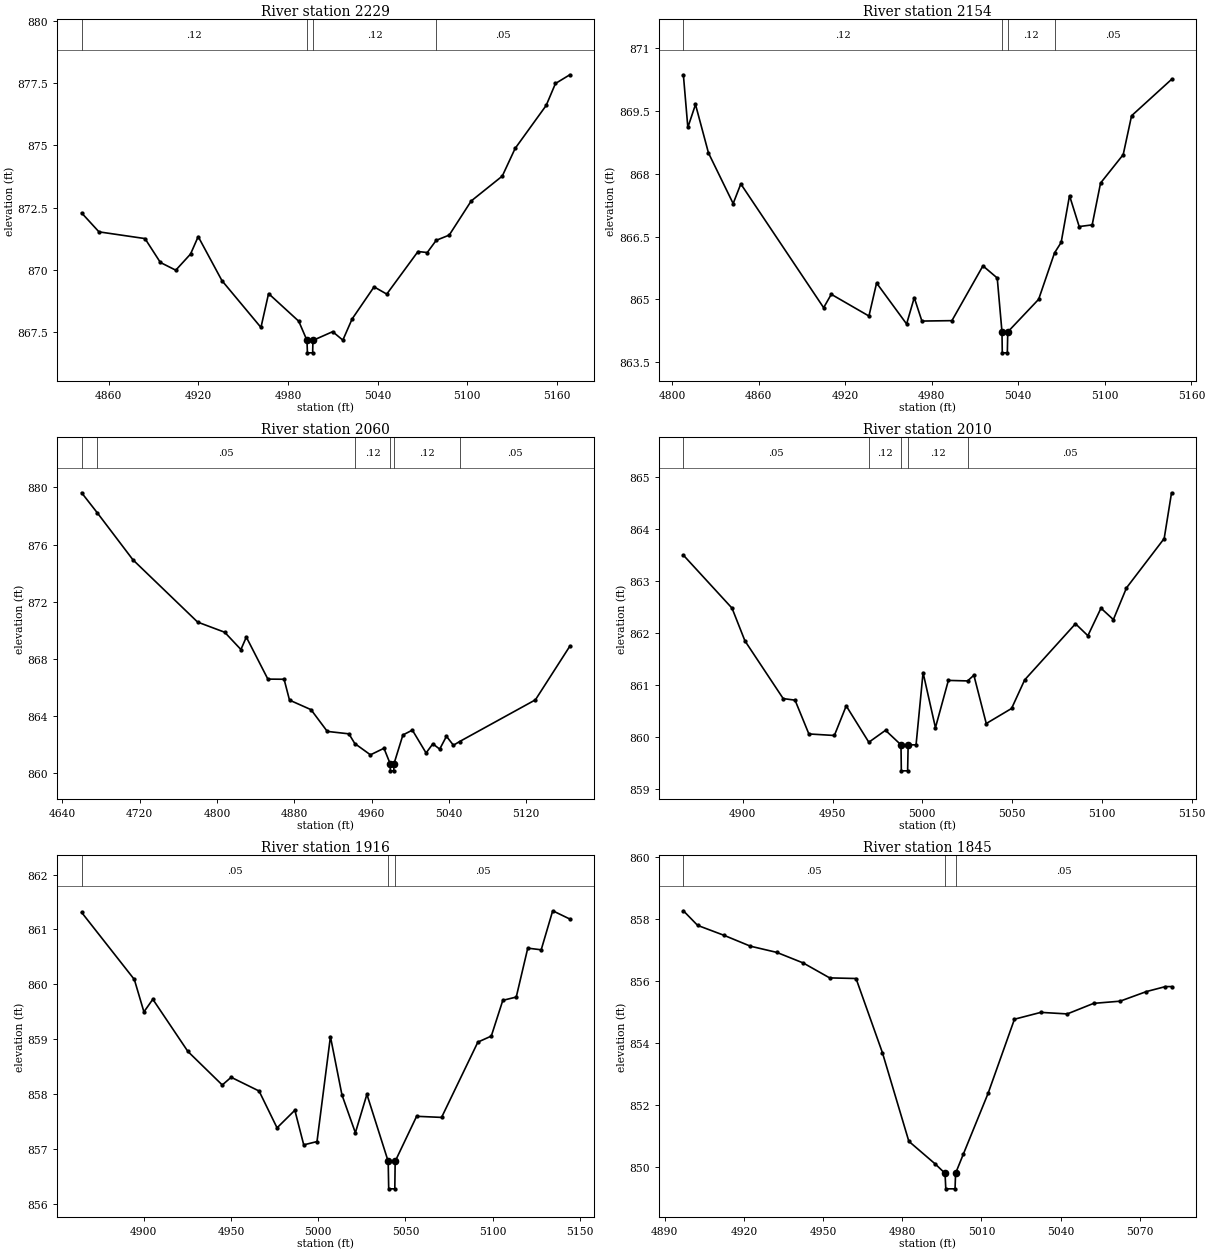
Type RM Length L Ch R = 1,2229,75,75,75
BEGIN DESCRIPTION:
Mapping XS 0ec9f2f7
END DESCRIPTION:
XS GIS Cut Line= 3
      2270912.16      7171821.26      2270875.84      7171670.33
      2270775.36      7171531.39
#Sta/Elev= 30
  4841.9  872.29  4853.5  871.53  4884.3  871.26  4894.6  870.30  4904.9  869.99
  4914.8  870.64  4919.9  871.34  4935.8  869.57  4961.9  867.69  4967.0  869.05
  4987.2  867.94  4992.7  867.17  4993.0  866.67  4996.5  866.67  4996.7  867.17
  5009.9  867.52  5016.7  867.18  5022.9  868.03  5037.6  869.32  5046.1  869.03
  5067.0  870.74  5073.2  870.70  5079.2  871.19  5087.9  871.40  5102.6  872.77
  5123.4  873.77  5132.0  874.88  5152.8  876.61  5159.0  877.49  5168.6  877.84
#Mann=4,-1,0
  4841.9    0.12       0  4992.7    0.07       0  4996.7    0.12       0
  5079.2    0.05       0
Bank Sta=4992.7,4996.7
Exp/Cntr=0.3,0.1

Type RM Length L Ch R = 1,2154,94,94,94
BEGIN DESCRIPTION:
Mapping XS a6b78c15
END DESCRIPTION:
XS GIS Cut Line= 3
      2271005.48      7171826.51      2270929.48      7171602.89
      2270877.70      7171514.87
#Sta/Elev= 30
  4807.9  870.37  4811.0  869.11  4816.3  869.66  4825.3  868.50  4842.4  867.29
  4847.7  867.76  4905.1  864.80  4910.4  865.12  4936.5  864.60  4941.8  865.39
  4962.6  864.41  4967.9  865.04  4973.2  864.48  4994.0  864.49  5015.5  865.80
  5025.4  865.51  5028.7  864.22  5028.9  863.72  5032.4  863.72  5032.7  864.22
  5054.1  865.00  5065.1  866.11  5069.7  866.36  5075.5  867.48  5082.2  866.74
  5091.2  866.78  5097.0  867.78  5112.7  868.46  5118.5  869.39  5146.2  870.26
#Mann=4,-1,0
  4807.9    0.12       0  5028.7    0.07       0  5032.7    0.12       0
  5065.1    0.05       0
Bank Sta=5028.7,5032.7
Exp/Cntr=0.3,0.1

Type RM Length L Ch R = 1,2060,50,50,50
BEGIN DESCRIPTION:
MDE S 029 6.0
END DESCRIPTION:
XS GIS Cut Line= 3
      2271178.98      7171909.96      2271029.00      7171610.00
      2270910.57      7171487.99
#Sta/Elev= 30
  4659.9  879.63  4676.2  878.22  4713.0  874.94  4780.0  870.58  4808.0  869.87
  4824.8  868.66  4830.4  869.53  4852.7  866.59  4869.5  866.58  4875.1  865.12
  4897.4  864.45  4914.2  862.93  4936.6  862.76  4942.7  862.08  4958.9  861.29
  4972.9  861.75  4979.3  860.67  4979.5  860.17  4983.0  860.17  4983.3  860.67
  4992.5  862.68  5002.3  863.02  5016.5  861.42  5023.5  862.06  5030.6  861.69
  5037.6  862.59  5044.8  861.96  5051.2  862.22  5129.7  865.14  5165.3  868.89
#Mann=6,-1,0
  4659.9    0.12       0  4676.2    0.05       0  4942.7    0.12       0
  4979.3    0.07       0  4983.3    0.12       0  5051.2    0.05       0
Bank Sta=4979.3,4983.3
Exp/Cntr=0.3,0.1

Type RM Length L Ch R = 1,2010,94,94,94
BEGIN DESCRIPTION:
Mapping XS fe9bcd44
END DESCRIPTION:
XS GIS Cut Line= 3
      2271151.20      7171676.03      2271068.87      7171580.29
      2270962.99      7171480.31
#Sta/Elev= 30
  4866.9  863.50  4894.0  862.48  4901.2  861.85  4922.5  860.74  4929.1  860.71
  4936.8  860.06  4951.0  860.03  4957.6  860.60  4970.2  859.90  4979.5  860.13
  4988.1  859.85  4988.3  859.35  4991.8  859.35  4992.1  859.85  4996.5  859.85
  5000.4  861.24  5007.3  860.18  5014.5  861.09  5025.2  861.08  5028.7  861.19
  5035.6  860.26  5049.7  860.55  5057.0  861.10  5085.3  862.18  5092.2  861.95
  5099.5  862.48  5106.4  862.26  5113.7  862.87  5134.7  863.82  5138.8  864.70
#Mann=5,-1,0
  4866.9    0.05       0  4970.2    0.12       0  4988.1    0.07       0
  4992.1    0.12       0  5025.2    0.05       0
Bank Sta=4988.1,4992.1
Exp/Cntr=0.3,0.1

Type RM Length L Ch R = 1,1916,71,71,71
BEGIN DESCRIPTION:
Mapping XS 45cf6e96
END DESCRIPTION:
XS GIS Cut Line= 3
      2271161.36      7171639.60      2271135.32      7171514.90
      2271036.38      7171398.97
#Sta/Elev= 30
  4864.4  861.31  4894.6  860.09  4900.1  859.50  4905.2  859.73  4925.3  858.78
  4945.0  858.17  4950.1  858.31  4966.1  858.06  4976.4  857.39  4986.6  857.71
  4991.7  857.08  4999.3  857.14  5007.0  859.05  5013.6  857.99  5021.3  857.30
  5027.9  858.00  5040.1  856.78  5040.4  856.28  5043.9  856.28  5044.1  856.78
  5056.4  857.60  5070.7  857.58  5091.5  858.95  5099.2  859.06  5105.8  859.71
  5113.5  859.77  5120.1  860.66  5127.8  860.63  5134.4  861.34  5144.2  861.19
#Mann=3,-1,0
  4864.4    0.05       0  5040.1   0.033       0  5044.1    0.05       0
Bank Sta=5040.1,5044.1
Exp/Cntr=0.3,0.1

Type RM Length L Ch R = 1,1845,56,56,56
BEGIN DESCRIPTION:
Mapping XS 7d3c0140
END DESCRIPTION:
XS GIS Cut Line= 2
      2271185.37      7171565.41      2271182.88      7171380.53
#Sta/Elev= 25
  4897.1  858.26  4902.5  857.79  4912.5  857.47  4922.5  857.12  4932.5  856.92
  4942.5  856.58  4952.5  856.10  4962.5  856.08  4972.5  853.69  4982.5  850.84
  4992.5  850.11  4996.2  849.81  4996.5  849.31  5000.0  849.31  5000.2  849.81
  5003.2  850.44  5012.5  852.38  5022.5  854.77  5032.5  854.99  5042.5  854.94
  5052.5  855.28  5062.5  855.35  5072.5  855.66  5079.7  855.82  5082.0  855.82
#Mann=3,-1,0
  4897.1    0.05       0  4996.2   0.033       0  5000.2    0.05       0
Bank Sta=4996.2,5000.2
Exp/Cntr=0.3,0.1

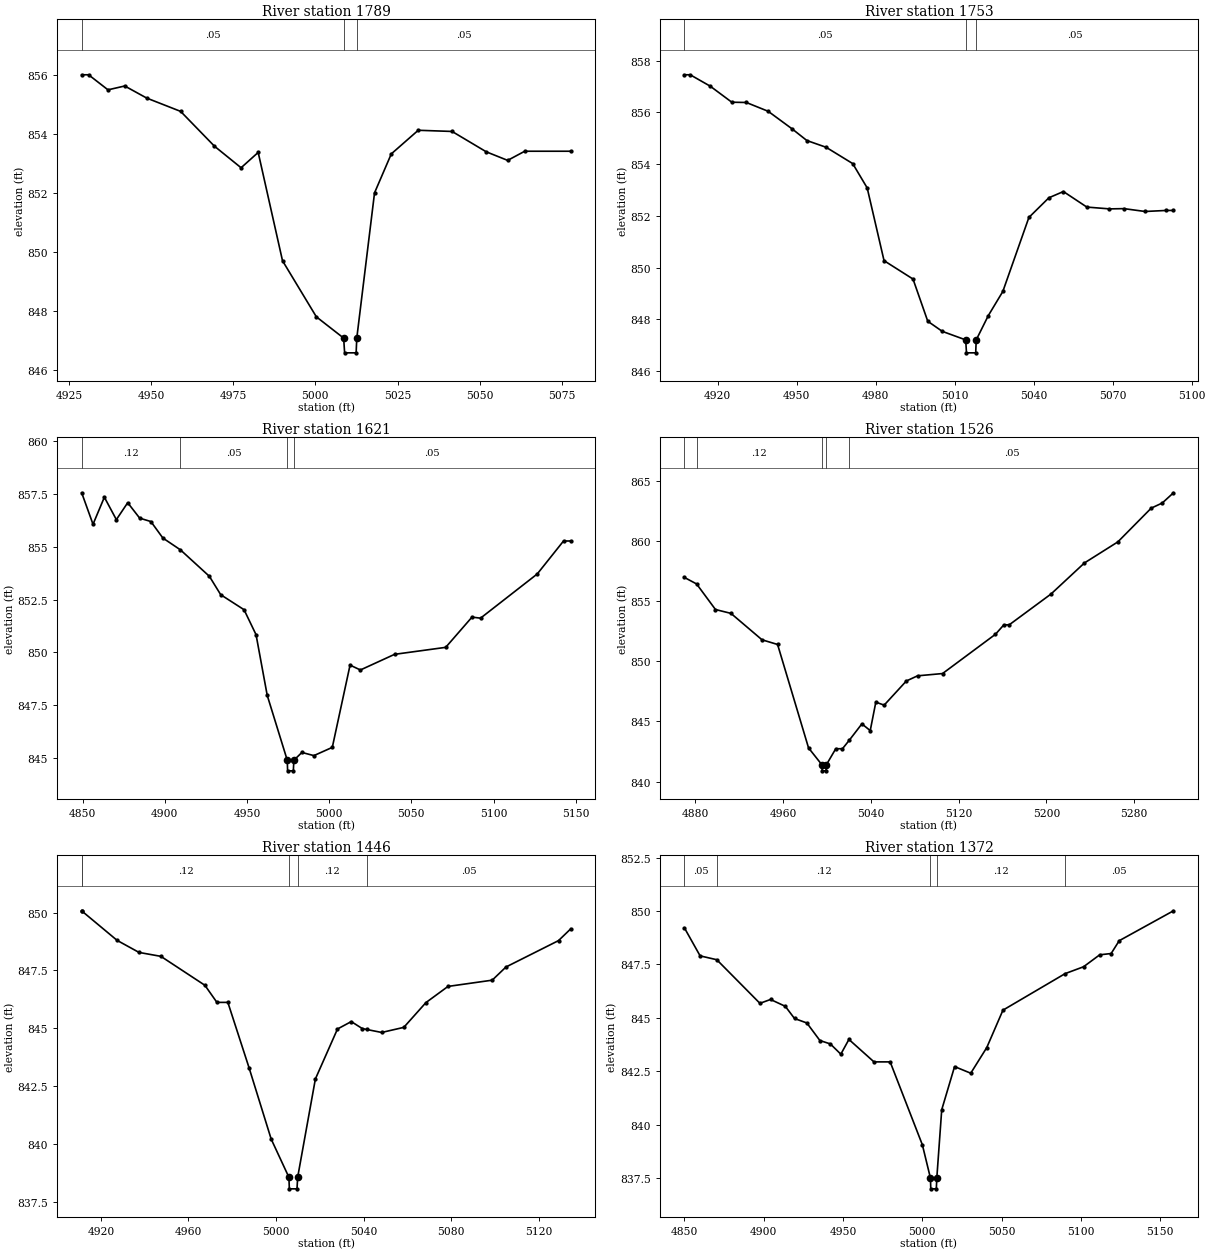
Type RM Length L Ch R = 1,1789,36,36,36
BEGIN DESCRIPTION:
Mapping XS 934a8699
END DESCRIPTION:
XS GIS Cut Line= 2
      2271256.94      7171529.12      2271219.51      7171385.11
#Sta/Elev= 23
  4928.9  856.00  4931.0  856.00  4936.9  855.49  4942.0  855.62  4948.7  855.21
  4959.0  854.76  4969.3  853.58  4977.4  852.85  4982.6  853.37  4990.0  849.70
  5000.3  847.80  5008.6  847.08  5008.9  846.58  5012.4  846.58  5012.6  847.08
  5018.0  852.00  5023.1  853.32  5031.3  854.12  5041.6  854.08  5052.0  853.39
  5058.5  853.10  5063.7  853.41  5077.7  853.41
#Mann=3,-1,0
  4928.9    0.05       0  5008.6   0.033       0  5012.6    0.05       0
Bank Sta=5008.6,5012.6
Exp/Cntr=0.3,0.1

Type RM Length L Ch R = 1,1753,132,132,132
BEGIN DESCRIPTION:
Mapping XS d9e92680
END DESCRIPTION:
XS GIS Cut Line= 2
      2271312.58      7171538.94      2271235.17      7171370.14
#Sta/Elev= 30
  4907.4  857.45  4909.6  857.45  4917.2  857.01  4925.4  856.39  4930.9  856.38
  4939.2  856.04  4948.3  855.36  4953.9  854.91  4961.2  854.65  4971.3  854.02
  4976.8  853.08  4983.2  850.27  4994.2  849.56  4999.8  847.93  5005.3  847.54
  5014.2  847.21  5014.5  846.71  5018.0  846.71  5018.2  847.21  5022.8  848.15
  5028.3  849.08  5038.2  851.94  5045.8  852.70  5051.3  852.94  5060.2  852.34
  5068.8  852.27  5074.3  852.28  5082.3  852.17  5090.4  852.21  5093.1  852.21
#Mann=3,-1,0
  4907.4    0.05       0  5014.2   0.033       0  5018.2    0.05       0
Bank Sta=5014.2,5018.2
Exp/Cntr=0.3,0.1

Type RM Length L Ch R = 1,1621,95,95,95
BEGIN DESCRIPTION:
Mapping XS 68420e90
END DESCRIPTION:
XS GIS Cut Line= 3
      2271446.69      7171451.96      2271335.52      7171347.56
      2271195.57      7171309.27
#Sta/Elev= 30
  4849.4  857.55  4856.3  856.06  4863.2  857.34  4870.5  856.28  4877.4  857.08
  4884.7  856.35  4891.5  856.19  4898.8  855.41  4909.5  854.85  4927.1  853.60
  4934.0  852.73  4948.2  852.02  4955.5  850.84  4962.3  847.97  4974.5  844.90
  4974.7  844.40  4978.2  844.40  4978.5  844.90  4983.4  845.27  4990.7  845.12
  5001.9  845.51  5012.7  849.40  5019.0  849.17  5039.8  849.91  5070.9  850.24
  5086.9  851.67  5092.1  851.62  5126.6  853.71  5142.6  855.27  5147.0  855.27
#Mann=4,-1,0
  4849.4    0.12       0  4909.5    0.05       0  4974.5   0.033       0
  4978.5    0.05       0
Bank Sta=4974.5,4978.5
Exp/Cntr=0.3,0.1

Type RM Length L Ch R = 1,1526,80,80,80
BEGIN DESCRIPTION:
MDE S 029 4.0
END DESCRIPTION:
XS GIS Cut Line= 3
      2271479.00      7171360.00      2271379.00      7171260.00
      2271078.96      7171310.01
#Sta/Elev= 30
  4870.1  856.99  4881.2  856.45  4898.4  854.32  4912.5  854.00  4940.8  851.80
  4955.0  851.41  4983.2  842.80  4995.4  841.39  4995.6  840.89  4999.1  840.89
  4999.4  841.39  5008.0  842.73  5014.1  842.73  5020.5  843.46  5031.8  844.80
  5039.4  844.24  5044.5  846.61  5052.1  846.36  5072.3  848.37  5082.5  848.80
  5105.3  848.99  5153.5  852.26  5161.1  853.04  5166.1  853.05  5204.1  855.61
  5234.6  858.20  5265.0  859.95  5295.4  862.76  5305.5  863.19  5315.7  864.04
#Mann=5,-1,0
  4870.1    0.05       0  4881.2    0.12       0  4995.4    0.07       0
  4999.4    0.12       0  5020.5    0.05       0
Bank Sta=4995.4,4999.4
Exp/Cntr=0.3,0.1

Type RM Length L Ch R = 1,1446,74,74,74
BEGIN DESCRIPTION:
Mapping XS 21a719b4
END DESCRIPTION:
XS GIS Cut Line= 3
      2271485.13      7171191.01      2271423.08      7171186.23
      2271263.43      7171208.99
#Sta/Elev= 27
  4911.2  850.08  4911.4  850.06  4927.4  848.80  4937.4  848.28  4947.4  848.11
  4967.5  846.86  4973.0  846.12  4978.0  846.12  4987.7  843.29  4997.8  840.21
  5005.9  838.56  5006.1  838.06  5009.6  838.06  5009.9  838.56  5018.0  842.81
  5028.1  844.97  5034.4  845.29  5039.4  844.99  5041.4  844.95  5048.3  844.82
  5058.4  845.04  5068.5  846.11  5078.6  846.81  5098.8  847.08  5105.1  847.65
  5129.1  848.79  5134.7  849.30
#Mann=5,-1,0
  4911.2    0.05       0  4911.4    0.12       0  5005.9    0.07       0
  5009.9    0.12       0  5041.4    0.05       0
Bank Sta=5005.9,5009.9
Exp/Cntr=0.3,0.1

Type RM Length L Ch R = 1,1372,79,79,79
BEGIN DESCRIPTION:
Mapping XS 34b88d81
END DESCRIPTION:
XS GIS Cut Line= 3
      2271506.45      7171157.70      2271426.09      7171113.01
      2271213.22      7171151.63
#Sta/Elev= 30
  4850.0  849.21  4859.9  847.90  4870.4  847.72  4897.6  845.68  4904.3  845.86
  4913.6  845.54  4919.4  844.97  4927.2  844.76  4935.4  843.94  4942.0  843.78
  4948.6  843.30  4953.7  843.99  4969.5  842.94  4979.7  842.94  5000.0  839.06
  5005.1  837.50  5005.3  837.00  5008.8  837.00  5009.1  837.50  5012.2  840.70
  5020.3  842.72  5030.5  842.41  5040.6  843.61  5050.8  845.36  5090.0  847.07
  5101.6  847.39  5111.8  847.95  5119.0  848.01  5124.1  848.61  5158.3  850.01
#Mann=5,-1,0
  4850.0    0.05       0  4870.4    0.12       0  5005.1    0.07       0
  5009.1    0.12       0  5090.0    0.05       0
Bank Sta=5005.1,5009.1
Exp/Cntr=0.3,0.1

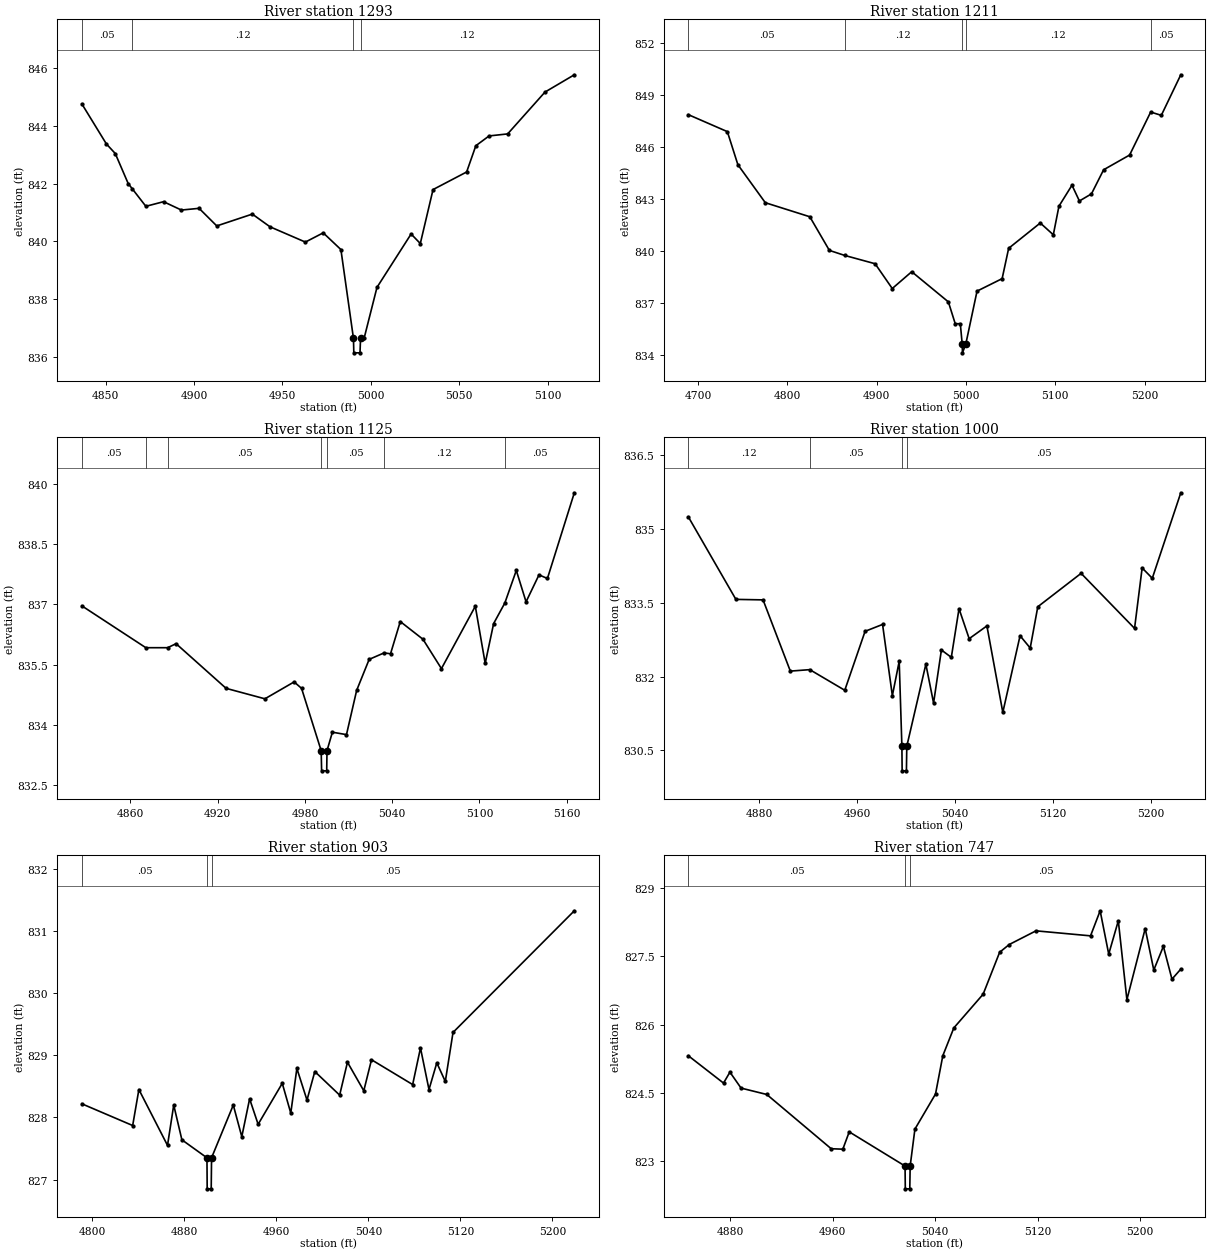
Type RM Length L Ch R = 1,1293,82,82,82
BEGIN DESCRIPTION:
Mapping XS afe03416
END DESCRIPTION:
XS GIS Cut Line= 3
      2271525.14      7171056.12      2271365.88      7171045.37
      2271253.31      7171083.58
#Sta/Elev= 30
  4836.6  844.76  4850.5  843.37  4855.5  843.04  4862.8  842.00  4865.2  841.81
  4872.8  841.21  4882.8  841.37  4892.9  841.08  4902.9  841.14  4912.9  840.53
  4933.0  840.94  4943.0  840.50  4963.0  839.97  4973.1  840.29  4983.1  839.71
  4990.2  836.63  4990.4  836.13  4993.9  836.13  4994.2  836.63  4996.2  836.63
  5003.5  838.40  5022.8  840.25  5028.0  839.92  5035.2  841.79  5054.2  842.40
  5059.4  843.31  5066.9  843.65  5077.4  843.72  5098.5  845.17  5115.1  845.77
#Mann=4,-1,0
  4836.6    0.05       0  4865.2    0.12       0  4990.2    0.07       0
  4994.2    0.12       0
Bank Sta=4990.2,4994.2
Exp/Cntr=0.3,0.1

Type RM Length L Ch R = 1,1211,86,86,86
BEGIN DESCRIPTION:
MDE S 029 3.0
END DESCRIPTION:
XS GIS Cut Line= 3
      2271673.19      7171025.26      2271379.00      7170960.00
      2271179.03      7171109.98
#Sta/Elev= 30
  4689.3  847.84  4733.0  846.86  4744.8  844.95  4775.5  842.76  4825.3  841.95
  4847.2  840.01  4864.3  839.72  4898.4  839.24  4917.6  837.81  4939.4  838.78
  4980.4  837.04  4988.1  835.78  4993.8  835.78  4995.9  834.60  4996.2  834.10
  4999.9  834.60  5012.5  837.66  5040.6  838.38  5047.9  840.13  5083.3  841.59
  5097.9  840.91  5104.2  842.56  5118.8  843.77  5127.1  842.86  5140.6  843.27
  5154.2  844.66  5183.3  845.51  5206.9  847.99  5218.8  847.80  5240.6  850.14
#Mann=5,-1,0
  4689.3    0.05       0  4864.3    0.12       0  4995.9    0.07       0
  4999.9    0.12       0  5206.9    0.05       0
Bank Sta=4995.9,4999.9
Exp/Cntr=0.3,0.1

Type RM Length L Ch R = 1,1125,125,125,125
BEGIN DESCRIPTION:
Mapping XS a1176ee8
END DESCRIPTION:
XS GIS Cut Line= 3
      2271552.62      7170913.55      2271382.95      7170880.86
      2271240.52      7170965.95
#Sta/Elev= 30
  4826.6  836.96  4870.6  835.92  4885.6  835.92  4891.4  836.02  4925.8  834.91
  4952.5  834.65  4972.6  835.07  4977.7  834.91  4991.2  833.36  4991.5  832.86
  4995.0  832.86  4995.2  833.36  4998.9  833.82  5008.6  833.76  5015.6  834.86
  5024.2  835.63  5034.4  835.79  5038.9  835.77  5045.6  836.57  5061.2  836.13
  5073.9  835.40  5097.2  836.95  5104.0  835.53  5109.8  836.52  5117.5  837.03
  5125.4  837.84  5132.1  837.06  5141.0  837.73  5146.8  837.64  5165.3  839.77
#Mann=7,-1,0
  4826.6    0.05       0  4870.6    0.12       0  4885.6    0.05       0
  4991.2   0.033       0  4995.2    0.05       0  5034.4    0.12       0
  5117.5    0.05       0
Bank Sta=4991.2,4995.2
Exp/Cntr=0.3,0.1

Type RM Length L Ch R = 1,1000,97,97,97
BEGIN DESCRIPTION:
Mapping XS 3eb79bad
END DESCRIPTION:
XS GIS Cut Line= 3
      2271600.58      7170851.66      2271442.39      7170771.18
      2271263.08      7170907.29
#Sta/Elev= 30
  4821.9  835.25  4860.8  833.57  4883.0  833.56  4905.3  832.11  4921.2  832.14
  4949.8  831.72  4966.4  832.92  4980.7  833.06  4988.7  831.61  4994.3  832.31
  4996.5  830.58  4996.7  830.08  5000.2  830.08  5000.5  830.58  5016.1  832.25
  5022.4  831.46  5028.8  832.54  5036.9  832.39  5043.2  833.38  5051.5  832.77
  5066.0  833.03  5079.0  831.27  5093.1  832.83  5101.4  832.58  5107.6  833.42
  5143.0  834.10  5186.7  832.98  5192.9  834.21  5201.2  834.00  5224.5  835.74
#Mann=4,-1,0
  4821.9    0.12       0  4921.2    0.05       0  4996.5   0.033       0
  5000.5    0.05       0
Bank Sta=4996.5,5000.5
Exp/Cntr=0.3,0.1

Type RM Length L Ch R = 1,903,156,156,156
BEGIN DESCRIPTION:
Mapping XS 3d12713a
END DESCRIPTION:
XS GIS Cut Line= 5
      2271622.32      7170568.35      2271537.57      7170600.01
      2271466.08      7170665.72      2271431.93      7170697.32
      2271288.93      7170828.72
#Sta/Elev= 30
  4790.8  828.22  4835.0  827.87  4840.4  828.45  4865.3  827.55  4870.7  828.20
  4877.8  827.64  4899.6  827.35  4899.8  826.85  4903.3  826.85  4903.6  827.35
  4922.5  828.20  4929.9  827.69  4936.7  828.30  4944.1  827.89  4965.1  828.55
  4972.5  828.07  4977.8  828.79  4986.6  828.28  4993.4  828.74  5015.0  828.36
  5021.8  828.89  5036.0  828.43  5042.7  828.93  5078.5  828.53  5085.3  829.12
  5092.7  828.45  5099.5  828.88  5106.9  828.58  5113.6  829.37  5219.1  831.33
#Mann=3,-1,0
  4790.8    0.05       0  4899.6   0.035       0  4903.6    0.05       0
Bank Sta=4899.6,4903.6
Exp/Cntr=0.3,0.1

Type RM Length L Ch R = 1,747,88,88,88
BEGIN DESCRIPTION:
Mapping XS 49370efa
END DESCRIPTION:
XS GIS Cut Line= 4
      2271549.99      7170521.99      2271388.29      7170538.95
      2271323.78      7170574.47      2271213.06      7170673.40
#Sta/Elev= 30
  4847.2  825.32  4874.7  824.72  4879.7  824.96  4888.4  824.61  4908.5  824.47
  4958.8  823.28  4967.9  823.27  4972.9  823.65  5016.5  822.90  5016.7  822.40
  5020.2  822.40  5020.5  822.90  5024.2  823.71  5040.3  824.48  5046.0  825.32
  5054.6  825.93  5077.5  826.67  5090.4  827.59  5097.9  827.76  5118.8  828.06
  5161.4  827.95  5168.9  828.50  5175.6  827.55  5183.1  828.28  5189.8  826.55
  5204.1  828.11  5210.8  827.20  5218.3  827.72  5225.0  827.00  5231.9  827.22
#Mann=3,-1,0
  4847.2    0.05       0  5016.5   0.035       0  5020.5    0.05       0
Bank Sta=5016.5,5020.5
Exp/Cntr=0.3,0.1

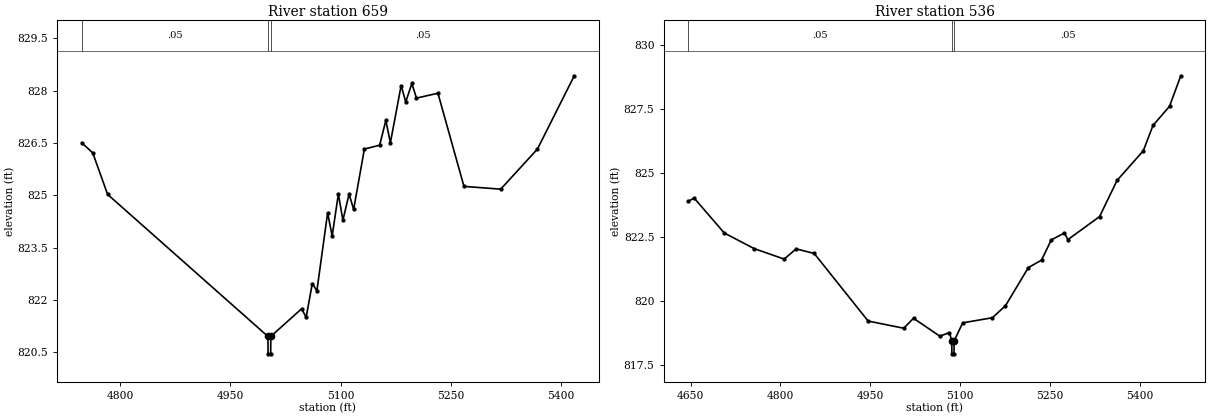
Type RM Length L Ch R = 1,659,123,123,123
BEGIN DESCRIPTION:
Mapping XS 0abf81e1
END DESCRIPTION:
XS GIS Cut Line= 3
      2271593.88      7170503.32      2271344.17      7170469.79
      2271093.88      7170804.88
#Sta/Elev= 30
  4747.6  826.51  4762.6  826.22  4782.8  825.03  5000.9  820.96  5001.2  820.46
  5004.7  820.46  5004.9  820.96  5046.7  821.75  5053.0  821.51  5061.3  822.47
  5067.6  822.27  5082.2  824.50  5088.4  823.84  5096.8  825.04  5103.0  824.29
  5111.4  825.04  5117.6  824.60  5132.2  826.33  5153.0  826.44  5161.4  827.15
  5167.6  826.51  5182.2  828.15  5188.5  827.68  5196.8  828.21  5203.1  827.79
  5232.3  827.93  5267.7  825.26  5317.7  825.18  5367.7  826.33  5417.8  828.43
#Mann=3,-1,0
  4747.6    0.05       0  5000.9   0.035       0  5004.9    0.05       0
Bank Sta=5000.9,5004.9
Exp/Cntr=0.3,0.1

Type RM Length L Ch R = 1,536,0,0,0
BEGIN DESCRIPTION:
Mapping XS 51d96b2c
END DESCRIPTION:
XS GIS Cut Line= 3
      2271588.98      7170397.64      2271253.44      7170380.62
      2271024.12      7170809.60
#Sta/Elev= 30
  4646.1  823.88  4656.1  824.00  4706.2  822.64  4756.2  822.03  4806.3  821.62
  4826.3  822.02  4856.4  821.84  4946.5  819.20  5005.9  818.92  5022.2  819.31
  5066.1  818.61  5082.3  818.75  5086.0  818.42  5086.3  817.92  5089.8  817.92
  5090.0  818.42  5104.3  819.13  5153.9  819.33  5175.8  819.80  5214.0  821.29
  5236.0  821.58  5252.2  822.37  5274.2  822.64  5279.9  822.38  5332.9  823.28
  5362.0  824.69  5405.9  825.85  5422.1  826.84  5449.7  827.59  5468.5  828.78
#Mann=3,-1,0
  4646.1    0.05       0  5086.0   0.035       0  5090.0    0.05       0
Bank Sta=5086,5090
Exp/Cntr=0.3,0.1

Chan Stop Cuts=-1