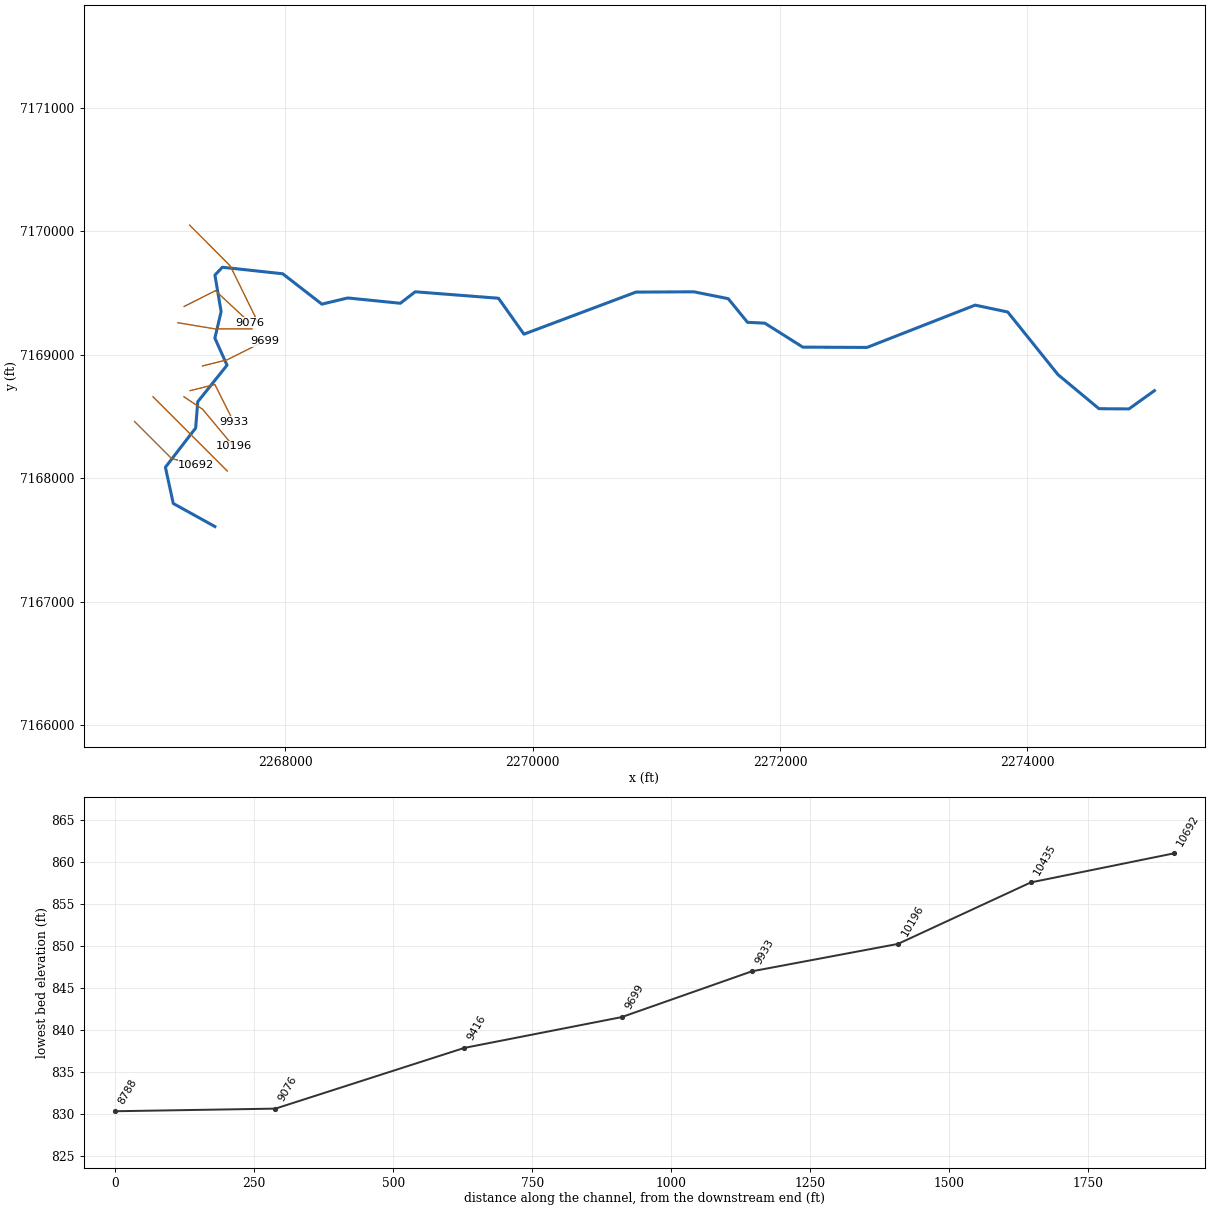
--- MDE S 030.prj (project) ---

Proj Title=MDE S 030 Base Level Engineering
Current Plan=p01
Default Exp/Contr=0.3,0.1
English Units
Geom File=g01
Flow File=f01
Plan File=p01
BEGIN DESCRIPTION:
MDE S 030
END DESCRIPTION:

--- MDE S 030.p01 (plan) ---

Plan Title=Multiple Run
Short Identifier=Multiple
Geom File=g01
Flow File=f01
Subcritical Flow
K Sum by GR= 0
Std Step Tol= 0.01
Critical Tol= 0.01
Num of Std Step Trials= 20
Max Error Tol= 0.3
Flow Tol Ratio= 0.001
Split Flow NTrial= 30
Split Flow Tol= 0.02
Split Flow Ratio= 0.02
Log Output Level= 0
Friction Slope Method= 1
Unsteady Friction Slope Method= 2
Unsteady Bridges Friction Slope Method= 1
Parabolic Critical Depth
Global Vel Dist=  1 , 1 , 1
Global Log Level= 0
CheckData=True
Encroach Param= -1, 0, 0, 0
BEGIN DESCRIPTION:
Multiple Run
END DESCRIPTION:

--- MDE S 030.f01 (steady flow) ---

Flow Title=Multiple
Number of Profiles=7
Profile Names=10-year,25-year,50-year,1pct_min,100-year,1pct_plu,500-year
River Rch & RM= MDE S 030,Reach-1,10692
     491     683     847     525    1047    2088    1596
River Rch & RM= MDE S 030,Reach-1,8788
    1030    1510    1936    1238    2469    4927    4020
Boundary for River Rch & Prof#=MDE S 030,Reach-1,1
Up Type=0
Dn Type=3
Dn Slope=0.009
Boundary for River Rch & Prof#=MDE S 030,Reach-1,2
Up Type=0
Dn Type=3
Dn Slope=0.009
Boundary for River Rch & Prof#=MDE S 030,Reach-1,3
Up Type=0
Dn Type=3
Dn Slope=0.009
Boundary for River Rch & Prof#=MDE S 030,Reach-1,4
Up Type=0
Dn Type=3
Dn Slope=0.009
Boundary for River Rch & Prof#=MDE S 030,Reach-1,5
Up Type=0
Dn Type=3
Dn Slope=0.009
Boundary for River Rch & Prof#=MDE S 030,Reach-1,6
Up Type=0
Dn Type=3
Dn Slope=0.009
Boundary for River Rch & Prof#=MDE S 030,Reach-1,7
Up Type=0
Dn Type=3
Dn Slope=0.009

--- MDE S 030.g01 (geometry) ---

Geom Title=Existing Conditions

River Reach=MDE S 030,Reach-1
Reach XY= 30
      2267429.00      7167610.00      2267092.36      7167796.65
      2267028.70      7168089.83      2267273.48      7168407.57
      2267290.24      7168620.00      2267527.21      7168916.11
      2267428.76      7169134.92      2267479.50      7169349.83
      2267429.31      7169644.98      2267489.26      7169709.02
      2267977.42      7169656.18      2268294.22      7169410.49
      2268504.04      7169460.31      2268929.10      7169417.33
      2269049.13      7169510.39      2269723.16      7169457.95
      2269928.89      7169167.31      2270834.93      7169507.76
      2271304.08      7169510.20      2271581.45      7169454.54
      2271737.31      7169263.08      2271877.46      7169256.25
      2272184.93      7169062.24      2272704.12      7169059.88
      2273579.00      7169402.44      2273842.34      7169346.64
      2274248.79      7168839.91      2274580.55      7168563.75
      2274823.07      7168562.24      2275029.00      7168710.00

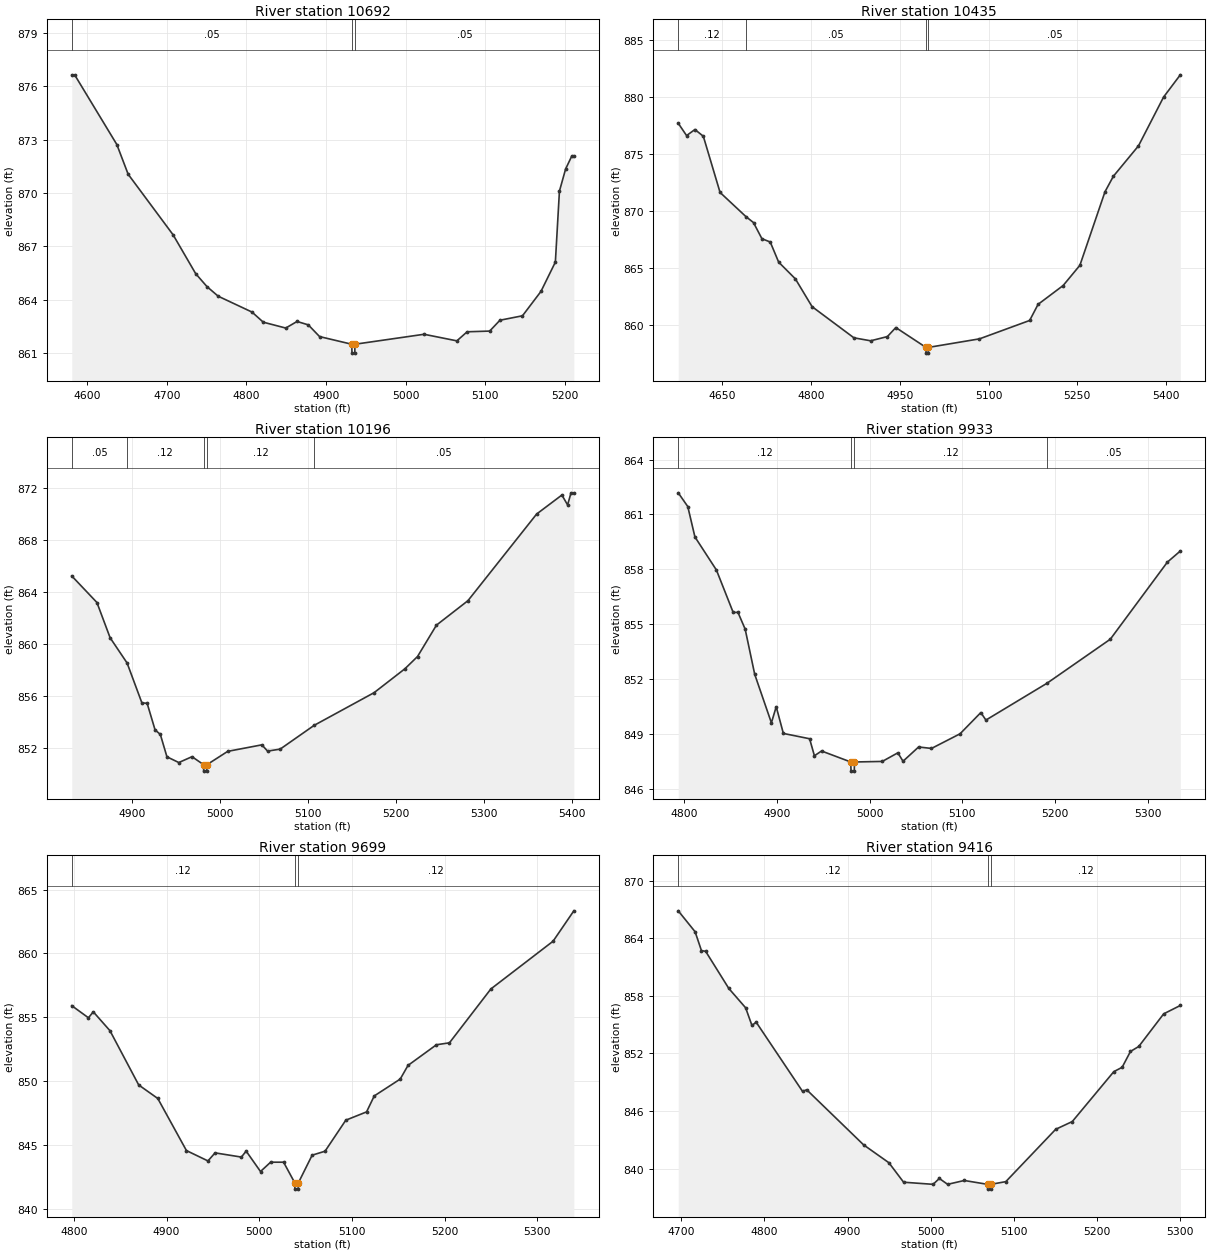
Type RM Length L Ch R = 1,10692,257,257,257
BEGIN DESCRIPTION:
MDE S 030 11.0
END DESCRIPTION:
XS GIS Cut Line= 3
      2266778.97      7168460.03      2267079.00      7168160.00
      2267279.03      7168109.99
#Sta/Elev= 30
  4580.8  876.64  4584.4  876.64  4637.4  872.72  4651.6  871.05  4708.1  867.64
  4736.4  865.46  4750.6  864.73  4764.7  864.19  4807.1  863.30  4821.3  862.73
  4849.5  862.40  4863.7  862.77  4877.8  862.58  4892.0  861.92  4932.4  861.49
  4932.7  860.99  4936.2  860.99  4936.4  861.49  5023.2  862.05  5064.4  861.68
  5077.3  862.19  5105.6  862.23  5118.5  862.84  5146.8  863.09  5170.0  864.46
  5188.1  866.11  5193.2  870.10  5201.0  871.35  5208.7  872.07  5211.3  872.07
#Mann=3,-1,0
  4580.8    0.05       0  4932.4   0.033       0  4936.4    0.05       0
Bank Sta=4932.4,4936.4
Exp/Cntr=0.3,0.1

Type RM Length L Ch R = 1,10435,239,239,239
BEGIN DESCRIPTION:
MDE S 030 10.0
END DESCRIPTION:
XS GIS Cut Line= 3
      2266929.03      7168659.97      2267229.00      7168360.00
      2267529.01      7168059.99
#Sta/Elev= 30
  4575.5  877.67  4589.6  876.59  4603.7  877.12  4617.9  876.53  4646.2  871.61
  4689.8  869.50  4702.7  868.97  4716.9  867.56  4731.0  867.27  4745.2  865.51
  4773.5  864.04  4801.7  861.61  4872.4  858.88  4900.7  858.62  4929.0  858.99
  4943.2  859.78  4994.2  858.04  4994.4  857.54  4997.9  857.54  4998.2  858.04
  5084.6  858.79  5169.4  860.40  5183.6  861.81  5226.0  863.46  5254.3  865.23
  5296.7  871.67  5310.9  873.03  5353.3  875.69  5395.7  879.96  5424.0  881.91
#Mann=4,-1,0
  4575.5    0.12       0  4689.8    0.05       0  4994.2   0.033       0
  4998.2    0.05       0
Bank Sta=4994.2,4998.2
Exp/Cntr=0.3,0.1

Type RM Length L Ch R = 1,10196,263,263,263
BEGIN DESCRIPTION:
MDE S 030 9.0
END DESCRIPTION:
XS GIS Cut Line= 3
      2267178.97      7168660.02      2267329.00      7168560.00
      2267578.98      7168260.02
#Sta/Elev= 30
  4831.3  865.23  4859.9  863.19  4874.9  860.48  4894.2  858.54  4911.0  855.48
  4917.0  855.44  4926.0  853.40  4932.0  853.05  4939.5  851.33  4953.0  850.89
  4968.0  851.34  4981.1  850.73  4981.3  850.23  4984.8  850.23  4985.1  850.73
  5008.6  851.75  5047.4  852.25  5053.9  851.77  5068.2  851.92  5106.9  853.75
  5175.0  856.26  5210.1  858.10  5224.4  859.04  5245.9  861.45  5281.7  863.33
  5359.8  869.99  5388.5  871.45  5395.0  870.69  5398.9  871.62  5402.1  871.62
#Mann=5,-1,0
  4831.3    0.05       0  4894.2    0.12       0  4981.1    0.07       0
  4985.1    0.12       0  5106.9    0.05       0
Bank Sta=4981.1,4985.1
Exp/Cntr=0.3,0.1

Type RM Length L Ch R = 1,9933,234,234,234
BEGIN DESCRIPTION:
MDE S 030 8.0
END DESCRIPTION:
XS GIS Cut Line= 3
      2267228.99      7168710.00      2267429.00      7168760.00
      2267579.01      7168459.98
#Sta/Elev= 30
  4793.6  862.18  4803.9  861.43  4811.6  859.77  4834.8  857.96  4852.9  855.64
  4858.0  855.65  4865.8  854.73  4876.1  852.26  4894.1  849.61  4899.3  850.49
  4907.0  849.03  4935.3  848.74  4940.5  847.81  4948.2  848.07  4979.7  847.47
  4980.0  846.97  4983.5  846.97  4983.7  847.47  5013.7  847.50  5030.5  847.97
  5036.1  847.51  5052.9  848.29  5066.8  848.21  5097.6  849.01  5120.0  850.17
  5125.5  849.76  5191.3  851.77  5259.7  854.18  5321.2  858.39  5335.2  859.00
#Mann=4,-1,0
  4793.6    0.12       0  4979.7    0.07       0  4983.7    0.12       0
  5191.3    0.05       0
Bank Sta=4979.7,4983.7
Exp/Cntr=0.3,0.1

Type RM Length L Ch R = 1,9699,283,283,283
BEGIN DESCRIPTION:
MDE S 030 7.0
END DESCRIPTION:
XS GIS Cut Line= 3
      2267329.00      7168910.00      2267529.00      7168960.00
      2267829.03      7169110.02
#Sta/Elev= 30
  4797.7  855.90  4815.7  854.95  4820.9  855.42  4838.9  853.94  4869.9  849.69
  4890.5  848.63  4921.4  844.55  4944.6  843.74  4952.3  844.37  4980.7  844.04
  4985.8  844.51  5001.3  842.91  5012.2  843.64  5026.2  843.64  5038.2  842.03
  5038.4  841.53  5041.9  841.53  5042.2  842.03  5057.0  844.19  5070.9  844.50
  5093.3  846.93  5115.7  847.58  5124.0  848.83  5152.0  850.15  5160.4  851.22
  5191.1  852.84  5205.1  852.99  5249.8  857.21  5316.9  860.95  5339.3  863.33
#Mann=3,-1,0
  4797.7    0.12       0  5038.2    0.07       0  5042.2    0.12       0
Bank Sta=5038.2,5042.2
Exp/Cntr=0.3,0.1

Type RM Length L Ch R = 1,9416,340,340,340
BEGIN DESCRIPTION:
MDE S 030 6.0
END DESCRIPTION:
XS GIS Cut Line= 3
      2267128.96      7169260.01      2267429.00      7169210.00
      2267729.02      7169210.00
#Sta/Elev= 30
  4696.3  866.86  4716.6  864.68  4724.2  862.72  4729.3  862.64  4757.2  858.77
  4777.4  856.76  4785.0  854.92  4790.1  855.26  4845.9  848.05  4850.9  848.22
  4919.4  842.48  4949.8  840.62  4967.5  838.59  5003.0  838.37  5010.5  838.98
  5020.5  838.37  5040.5  838.77  5068.5  838.37  5068.7  837.87  5072.2  837.87
  5072.5  838.37  5090.5  838.65  5150.5  844.10  5170.5  844.91  5220.5  850.11
  5230.5  850.56  5240.5  852.21  5250.5  852.73  5280.5  856.13  5300.5  857.00
#Mann=3,-1,0
  4696.3    0.12       0  5068.5    0.07       0  5072.5    0.12       0
Bank Sta=5068.5,5072.5
Exp/Cntr=0.3,0.1

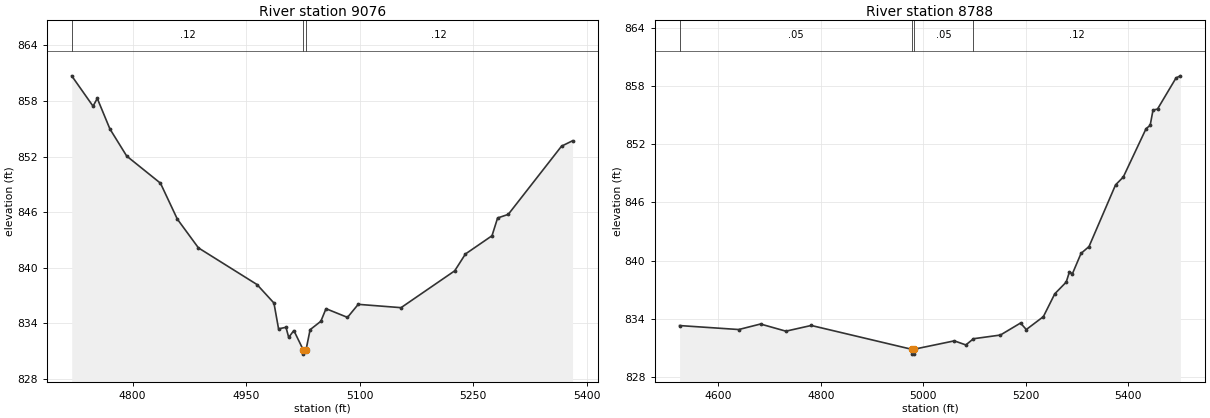
Type RM Length L Ch R = 1,9076,288,288,288
BEGIN DESCRIPTION:
Mapping XS 2b12b223
END DESCRIPTION:
XS GIS Cut Line= 3
      2267180.39      7169391.55      2267433.21      7169519.17
      2267710.64      7169261.41
#Sta/Elev= 30
  4719.5  860.72  4747.7  857.44  4753.3  858.28  4770.0  854.98  4792.2  852.05
  4836.8  849.12  4859.1  845.24  4887.0  842.13  4964.4  838.17  4986.8  836.17
  4992.9  833.38  5002.7  833.55  5006.3  832.46  5013.1  833.20  5025.3  831.15
  5025.6  830.65  5029.3  831.15  5034.6  833.29  5048.8  834.20  5055.6  835.56
  5084.0  834.62  5098.2  836.03  5154.8  835.67  5225.7  839.65  5239.9  841.47
  5275.0  843.44  5282.4  845.36  5296.5  845.75  5366.9  853.12  5381.4  853.70
#Mann=3,-1,0
  4719.5    0.12       0  5025.3    0.07       0  5029.3    0.12       0
Bank Sta=5025.3,5029.3
Exp/Cntr=0.3,0.1

Type RM Length L Ch R = 1,8788,0,0,0
BEGIN DESCRIPTION:
MDE S 030 5.0
END DESCRIPTION:
XS GIS Cut Line= 3
      2267225.15      7170049.56      2267553.20      7169719.72
      2267779.01      7169259.99
#Sta/Elev= 30
  4524.2  833.29  4639.7  832.88  4682.2  833.45  4731.7  832.71  4781.2  833.30
  4977.2  830.84  4977.4  830.34  4980.9  830.34  4981.2  830.84  5060.4  831.71
  5082.9  831.29  5097.8  831.93  5150.3  832.31  5189.6  833.55  5200.9  832.88
  5234.2  834.21  5256.5  836.57  5278.8  837.78  5285.2  838.85  5290.8  838.63
  5307.7  840.74  5323.3  841.45  5375.1  847.82  5390.2  848.63  5434.7  853.63
  5442.6  853.96  5448.2  855.54  5457.0  855.65  5493.1  858.86  5501.6  859.08
#Mann=4,-1,0
  4524.2    0.05       0  4977.2   0.033       0  4981.2    0.05       0
  5097.8    0.12       0
Bank Sta=4977.2,4981.2
Exp/Cntr=0.3,0.1

Chan Stop Cuts=-1