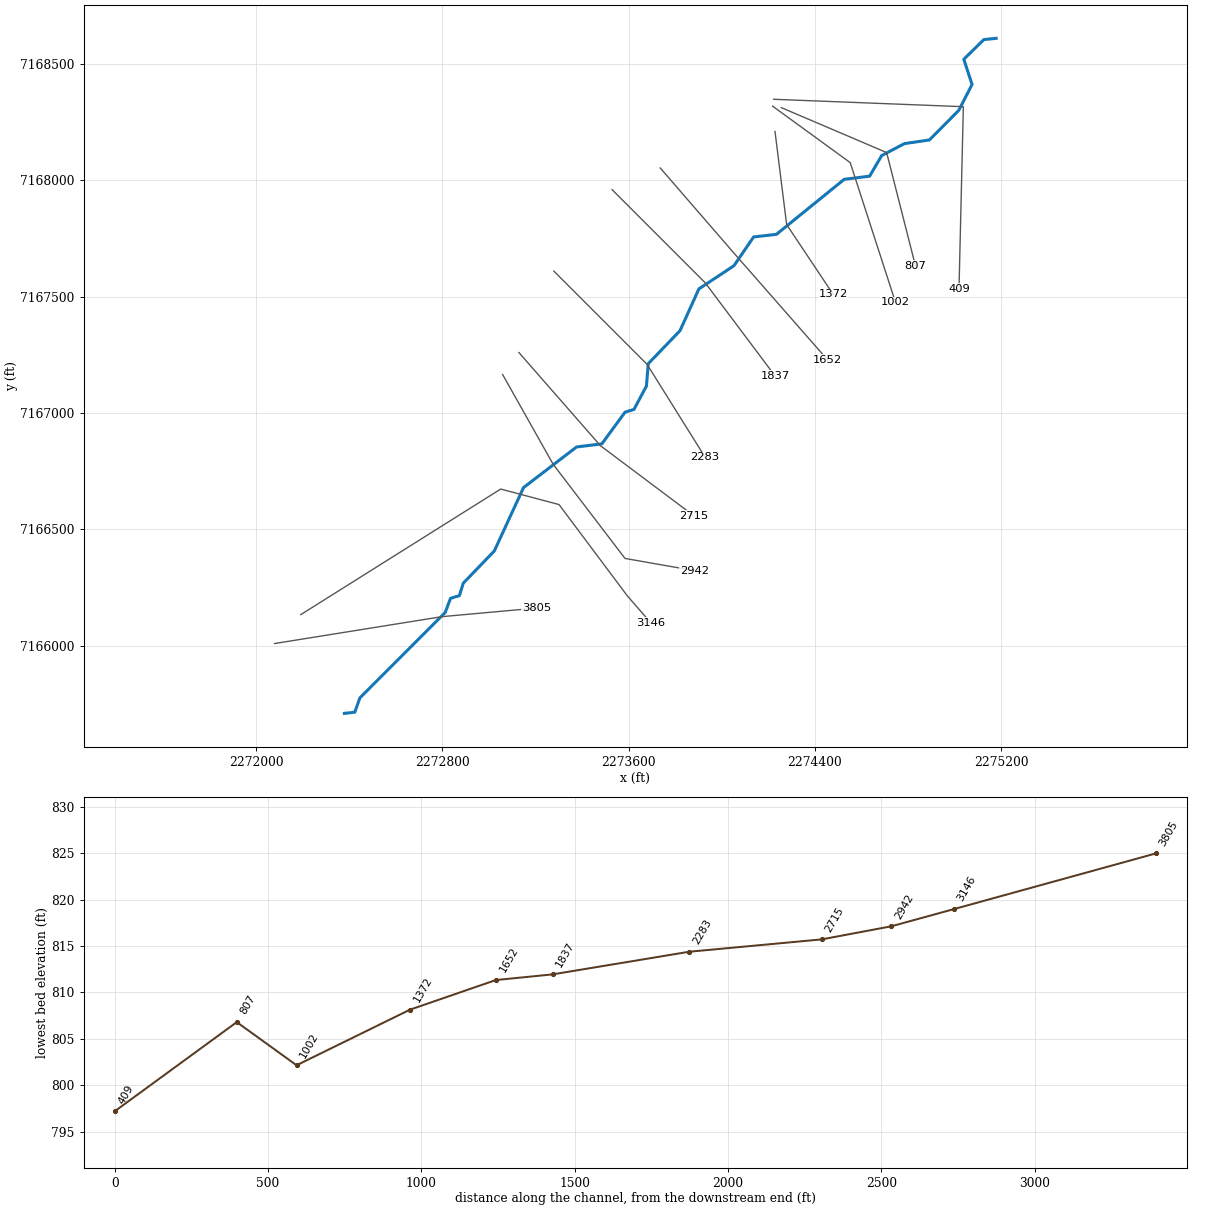
--- MDE S 031.prj (project) ---

Proj Title=MDE S 031 Base Level Engineering
Current Plan=p01
Default Exp/Contr=0.3,0.1
English Units
Geom File=g01
Flow File=f01
Plan File=p01
BEGIN DESCRIPTION:
MDE S 031
END DESCRIPTION:

--- MDE S 031.p01 (plan) ---

Plan Title=Multiple Run
Short Identifier=Multiple
Geom File=g01
Flow File=f01
Subcritical Flow
K Sum by GR= 0
Std Step Tol= 0.01
Critical Tol= 0.01
Num of Std Step Trials= 20
Max Error Tol= 0.3
Flow Tol Ratio= 0.001
Split Flow NTrial= 30
Split Flow Tol= 0.02
Split Flow Ratio= 0.02
Log Output Level= 0
Friction Slope Method= 1
Unsteady Friction Slope Method= 2
Unsteady Bridges Friction Slope Method= 1
Parabolic Critical Depth
Global Vel Dist=  1 , 1 , 1
Global Log Level= 0
CheckData=True
Encroach Param= -1, 0, 0, 0
BEGIN DESCRIPTION:
Multiple Run
END DESCRIPTION:

--- MDE S 031.f01 (steady flow) ---

Flow Title=Multiple
Number of Profiles=7
Profile Names=10-year,25-year,50-year,1pct_min,100-year,1pct_plu,500-year
River Rch & RM= MDE S 031,Reach-1,3805
     805    1132    1409     872    1739    3470    2654
River Rch & RM= MDE S 031,Reach-1,2942
    1382    2002    2544    1603    3197    6380    5066
Boundary for River Rch & Prof#=MDE S 031,Reach-1,1
Up Type=0
Dn Type=3
Dn Slope=0.005
Boundary for River Rch & Prof#=MDE S 031,Reach-1,2
Up Type=0
Dn Type=3
Dn Slope=0.005
Boundary for River Rch & Prof#=MDE S 031,Reach-1,3
Up Type=0
Dn Type=3
Dn Slope=0.005
Boundary for River Rch & Prof#=MDE S 031,Reach-1,4
Up Type=0
Dn Type=3
Dn Slope=0.005
Boundary for River Rch & Prof#=MDE S 031,Reach-1,5
Up Type=0
Dn Type=3
Dn Slope=0.005
Boundary for River Rch & Prof#=MDE S 031,Reach-1,6
Up Type=0
Dn Type=3
Dn Slope=0.005
Boundary for River Rch & Prof#=MDE S 031,Reach-1,7
Up Type=0
Dn Type=3
Dn Slope=0.005

--- MDE S 031.g01 (geometry) ---

Geom Title=Existing Conditions

River Reach=MDE S 031,Reach-1
Reach XY= 30
      2272379.00      7165710.00      2272423.67      7165714.92
      2272445.64      7165776.56      2272812.29      7166143.51
      2272834.98      7166204.23      2272873.02      7166215.77
      2272889.85      7166269.43      2273023.17      7166407.70
      2273148.70      7166680.13      2273376.57      7166854.48
      2273485.19      7166867.86      2273584.99      7167004.23
      2273623.05      7167015.76      2273676.67      7167115.94
      2273684.52      7167212.43      2273820.86      7167353.94
      2273901.99      7167533.52      2274052.51      7167633.00
      2274137.34      7167756.83      2274235.12      7167767.88
      2274526.58      7168004.46      2274635.44      7168017.79
      2274687.49      7168106.47      2274784.94      7168157.68
      2274892.30      7168173.40      2275018.24      7168300.32
      2275075.63      7168411.74      2275040.08      7168520.07
      2275126.44      7168604.69      2275179.00      7168610.00

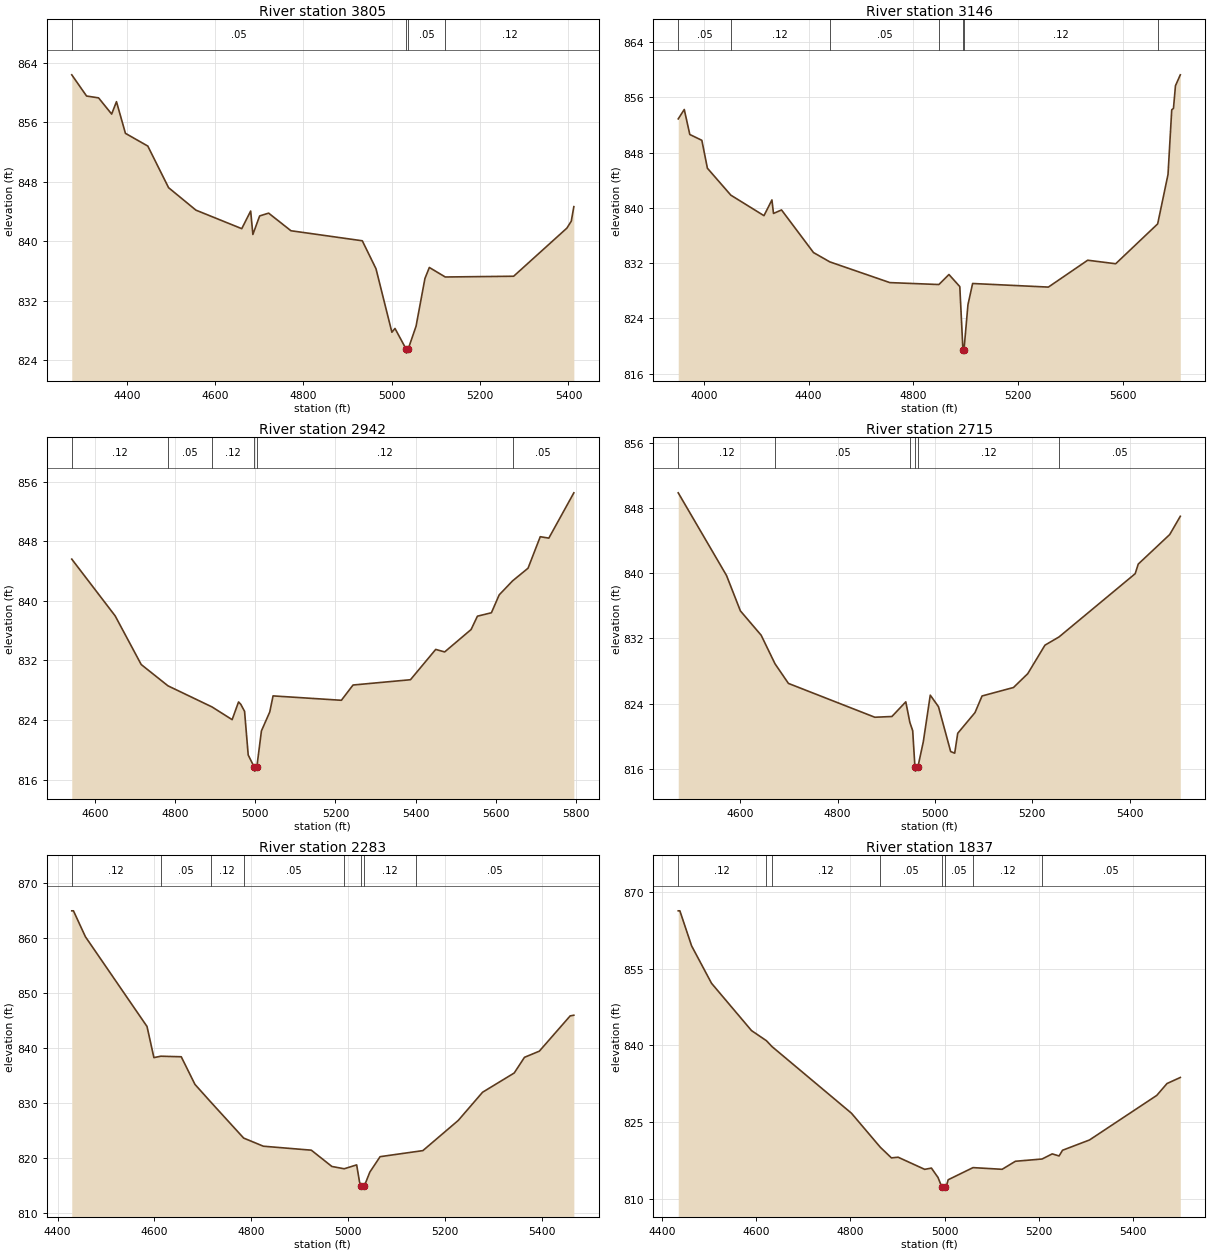
Type RM Length L Ch R = 1,3805,659,659,659
BEGIN DESCRIPTION:
MDE S 031 8.0
END DESCRIPTION:
XS GIS Cut Line= 3
      2272079.04      7166010.01      2272799.03      7166125.62
      2273204.75      7166162.38
#Sta/Elev= 30
  4275.6  862.41  4309.1  859.56  4336.3  859.31  4365.9  857.13  4376.8  858.80
  4397.1  854.54  4447.7  852.83  4494.8  847.23  4556.7  844.21  4660.4  841.72
  4680.6  844.09  4685.6  840.94  4700.9  843.43  4721.2  843.81  4771.8  841.44
  4933.3  840.09  4964.3  836.33  5000.3  827.79  5007.3  828.30  5032.9  825.48
  5033.2  824.98  5036.9  825.48  5055.0  828.60  5075.1  835.02  5085.1  836.50
  5121.1  835.22  5275.9  835.32  5396.4  841.79  5406.4  842.73  5412.2  844.68
#Mann=4,-1,0
  4275.6    0.05       0  5032.9   0.033       0  5036.9    0.05       0
  5121.1    0.12       0
Bank Sta=5032.9,5036.9
Exp/Cntr=0.3,0.1

Type RM Length L Ch R = 1,3146,204,204,204
BEGIN DESCRIPTION:
Mapping XS 793e4f93
END DESCRIPTION:
XS GIS Cut Line= 5
      2272191.93      7166134.39      2273050.67      7166673.70
      2273301.25      7166607.01      2273594.92      7166214.40
      2273695.01      7166099.79
#Sta/Elev= 30
  3902.7  852.89  3925.7  854.25  3946.9  850.63  3992.8  849.79  4014.0  845.75
  4103.4  841.85  4229.9  838.88  4260.2  841.16  4266.2  839.20  4296.8  839.71
  4418.8  833.54  4481.1  832.19  4710.2  829.19  4897.2  828.91  4935.7  830.36
  4977.1  828.61  4989.0  819.48  4989.3  818.98  4993.1  819.48  5008.2  825.99
  5026.0  829.06  5315.1  828.54  5465.1  832.43  5571.9  831.92  5732.1  837.69
  5771.6  844.85  5785.8  854.21  5792.4  854.41  5800.0  857.69  5818.5  859.27
#Mann=7,-1,0
  3902.7    0.05       0  4103.4    0.12       0  4481.1    0.05       0
  4897.2    0.12       0  4989.0    0.07       0  4993.1    0.12       0
  5732.1    0.05       0
Bank Sta=4989,4993.1
Exp/Cntr=0.3,0.1

Type RM Length L Ch R = 1,2942,227,227,227
BEGIN DESCRIPTION:
Mapping XS 05a66262
END DESCRIPTION:
XS GIS Cut Line= 4
      2273058.87      7167165.81      2273275.51      7166780.76
      2273584.59      7166375.63      2273881.58      7166323.52
#Sta/Elev= 30
  4542.0  845.59  4650.3  837.97  4715.3  831.44  4782.1  828.58  4891.9  825.75
  4942.2  824.04  4958.2  826.42  4963.9  826.09  4973.2  825.16  4982.3  819.30
  4997.7  817.63  4998.7  817.13  5003.7  817.63  5015.3  822.53  5036.1  825.08
  5044.3  827.23  5214.8  826.64  5243.9  828.69  5387.2  829.40  5450.2  833.47
  5472.5  833.13  5538.5  836.14  5554.3  837.93  5589.2  838.39  5608.6  840.79
  5642.0  842.67  5680.6  844.37  5711.1  848.60  5732.5  848.41  5794.9  854.49
#Mann=6,-1,0
  4542.0    0.12       0  4782.1    0.05       0  4891.9    0.12       0
  4997.7    0.07       0  5003.7    0.12       0  5642.0    0.05       0
Bank Sta=4997.7,5003.7
Exp/Cntr=0.3,0.1

Type RM Length L Ch R = 1,2715,432,432,432
BEGIN DESCRIPTION:
MDE S 031 5.0
END DESCRIPTION:
XS GIS Cut Line= 3
      2273128.99      7167260.01      2273479.00      7166860.00
      2273878.98      7166560.02
#Sta/Elev= 30
  4472.7  849.86  4571.9  839.72  4600.4  835.38  4643.1  832.39  4671.5  828.89
  4699.1  826.48  4876.6  822.33  4911.7  822.42  4940.2  824.22  4948.6  821.69
  4954.4  820.68  4959.0  816.22  4960.0  815.72  4965.0  816.22  4976.2  819.32
  4990.5  825.04  5007.4  823.62  5032.4  818.12  5040.7  817.92  5046.9  820.36
  5082.4  822.90  5096.9  824.94  5161.5  825.98  5190.7  827.67  5226.1  831.17
  5255.0  832.18  5411.5  839.94  5417.8  841.12  5482.4  844.74  5504.2  846.98
#Mann=6,-1,0
  4472.7    0.12       0  4671.5    0.05       0  4948.6    0.12       0
  4959.0    0.07       0  4965.0    0.12       0  5255.0    0.05       0
Bank Sta=4959,4965
Exp/Cntr=0.3,0.1

Type RM Length L Ch R = 1,2283,446,446,446
BEGIN DESCRIPTION:
MDE S 031 4.0
END DESCRIPTION:
XS GIS Cut Line= 3
      2273279.03      7167609.97      2273679.00      7167210.00
      2273928.98      7166810.03
#Sta/Elev= 30
  4429.3  864.98  4432.8  864.98  4457.5  860.27  4584.8  843.95  4599.0  838.30
  4613.5  838.55  4655.5  838.45  4683.8  833.43  4716.2  830.25  4784.4  823.67
  4825.2  822.19  4924.2  821.47  4966.7  818.51  4992.2  818.09  5017.9  818.80
  5023.8  815.71  5027.3  814.89  5028.3  814.39  5033.4  814.89  5045.1  817.48
  5066.3  820.29  5140.2  821.21  5154.7  821.39  5227.8  826.88  5278.0  832.00
  5343.4  835.50  5364.6  838.35  5395.3  839.47  5459.0  845.88  5466.6  846.00
#Mann=8,-1,0
  4429.3    0.12       0  4613.5    0.05       0  4716.2    0.12       0
  4784.4    0.05       0  4992.2    0.12       0  5027.3    0.07       0
  5033.4    0.12       0  5140.2    0.05       0
Bank Sta=5027.3,5033.4
Exp/Cntr=0.3,0.1

Type RM Length L Ch R = 1,1837,185,185,185
BEGIN DESCRIPTION:
MDE S 031 3.0
END DESCRIPTION:
XS GIS Cut Line= 3
      2273529.02      7167959.98      2273929.00      7167560.00
      2274229.02      7167159.97
#Sta/Elev= 30
  4434.8  866.29  4438.3  866.29  4463.1  859.46  4505.5  852.14  4590.3  842.91
  4622.0  840.93  4633.6  839.80  4802.5  826.77  4863.7  820.13  4887.3  818.05
  4901.5  818.18  4958.0  815.81  4972.2  816.06  4986.3  814.21  4993.9  812.45
  4994.9  811.95  5000.0  812.45  5003.6  812.45  5007.8  813.78  5060.5  816.15
  5122.3  815.82  5150.5  817.39  5207.1  817.83  5228.6  818.83  5243.2  818.43
  5250.5  819.54  5307.8  821.55  5450.5  830.25  5472.3  832.57  5500.5  833.75
#Mann=8,-1,0
  4434.8    0.12       0  4622.0    0.05       0  4633.6    0.12       0
  4863.7    0.05       0  4993.9   0.033       0  5000.0    0.05       0
  5060.5    0.12       0  5207.1    0.05       0
Bank Sta=4993.9,5000
Exp/Cntr=0.3,0.1

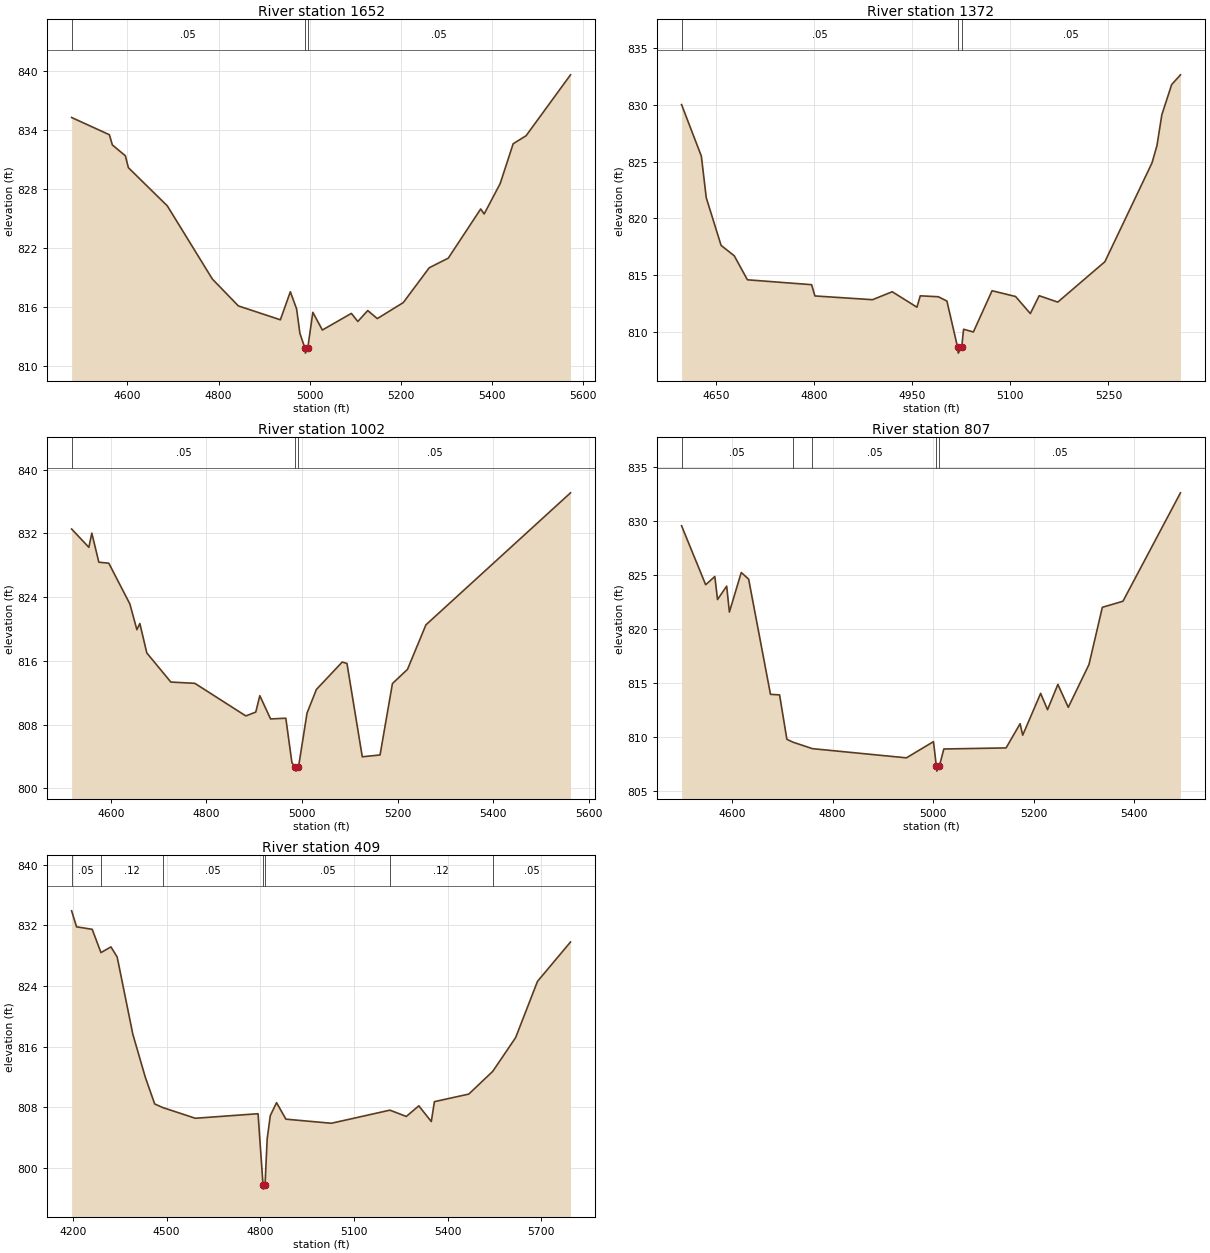
Type RM Length L Ch R = 1,1652,280,280,280
BEGIN DESCRIPTION:
Mapping XS b9af9fb3
END DESCRIPTION:
XS GIS Cut Line= 3
      2273735.93      7168053.10      2274064.28      7167673.93
      2274455.20      7167228.39
#Sta/Elev= 30
  4477.7  835.30  4560.5  833.55  4567.1  832.51  4595.6  831.41  4602.2  830.20
  4687.7  826.31  4786.5  818.87  4843.5  816.14  4935.6  814.73  4957.5  817.58
  4971.2  815.84  4978.4  813.36  4989.5  811.84  4990.5  811.34  4995.6  811.84
  5006.8  815.49  5027.7  813.69  5091.3  815.38  5105.5  814.56  5127.3  815.67
  5148.2  814.85  5205.2  816.48  5262.1  820.02  5303.9  821.00  5375.0  826.00
  5382.6  825.49  5417.7  828.58  5446.2  832.63  5474.6  833.45  5572.0  839.64
#Mann=3,-1,0
  4477.7    0.05       0  4989.5   0.033       0  4995.6    0.05       0
Bank Sta=4989.5,4995.6
Exp/Cntr=0.3,0.1

Type RM Length L Ch R = 1,1372,370,370,370
BEGIN DESCRIPTION:
MDE S 031 2.0
END DESCRIPTION:
XS GIS Cut Line= 3
      2274228.99      7168210.04      2274279.00      7167810.00
      2274479.00      7167510.01
#Sta/Elev= 30
  4596.6  830.01  4626.9  825.48  4634.4  821.82  4657.1  817.63  4677.3  816.71
  4697.4  814.60  4795.7  814.17  4800.7  813.18  4888.9  812.85  4919.1  813.55
  4956.9  812.19  4962.0  813.19  4989.7  813.11  5002.8  812.73  5019.2  808.65
  5020.2  808.15  5025.4  808.65  5028.3  810.25  5043.3  810.01  5071.9  813.64
  5107.9  813.13  5130.5  811.63  5144.0  813.20  5172.5  812.64  5244.6  816.19
  5316.7  824.88  5324.3  826.40  5331.8  829.12  5346.8  831.77  5360.3  832.63
#Mann=3,-1,0
  4596.6    0.05       0  5019.2   0.033       0  5025.4    0.05       0
Bank Sta=5019.2,5025.4
Exp/Cntr=0.3,0.1

Type RM Length L Ch R = 1,1002,195,195,195
BEGIN DESCRIPTION:
Mapping XS a50c38e4
END DESCRIPTION:
XS GIS Cut Line= 3
      2274218.38      7168318.84      2274552.06      7168076.17
      2274746.76      7167475.43
#Sta/Elev= 30
  4517.9  832.55  4554.0  830.25  4560.2  832.03  4574.9  828.38  4595.7  828.26
  4639.8  823.15  4654.5  819.91  4660.7  820.69  4675.3  816.99  4725.6  813.34
  4775.8  813.18  4882.5  809.09  4903.3  809.57  4911.8  811.63  4934.3  808.71
  4966.2  808.80  4979.0  803.21  4986.4  802.66  4987.4  802.16  4992.7  802.66
  5010.6  809.45  5030.2  812.41  5084.2  815.85  5094.2  815.67  5126.2  803.96
  5163.4  804.19  5189.3  813.15  5220.8  814.93  5259.4  820.52  5562.0  837.09
#Mann=3,-1,0
  4517.9    0.05       0  4986.4   0.033       0  4992.7    0.05       0
Bank Sta=4986.4,4992.7
Exp/Cntr=0.3,0.1

Type RM Length L Ch R = 1,807,398,398,398
BEGIN DESCRIPTION:
Mapping XS fdf34eb2
END DESCRIPTION:
XS GIS Cut Line= 3
      2274256.23      7168312.29      2274708.64      7168119.22
      2274832.11      7167633.56
#Sta/Elev= 30
  4499.5  829.53  4547.5  824.07  4565.7  824.83  4571.1  822.70  4589.3  823.94
  4594.7  821.54  4618.3  825.20  4633.0  824.59  4676.5  813.92  4694.6  813.87
  4709.1  809.76  4721.3  809.49  4760.1  808.89  4947.0  808.04  5000.9  809.54
  5006.5  807.31  5007.5  806.81  5012.8  807.31  5021.5  808.86  5145.4  808.96
  5173.3  811.20  5178.5  810.14  5214.2  814.01  5227.9  812.50  5248.5  814.84
  5269.2  812.72  5310.4  816.68  5337.0  821.98  5378.0  822.54  5492.5  832.58
#Mann=5,-1,0
  4499.5    0.05       0  4721.3    0.12       0  4760.1    0.05       0
  5006.5   0.033       0  5012.8    0.05       0
Bank Sta=5006.5,5012.8
Exp/Cntr=0.3,0.1

Type RM Length L Ch R = 1,409,0,0,0
BEGIN DESCRIPTION:
MDE S 031 1.0
END DESCRIPTION:
XS GIS Cut Line= 3
      2274223.08      7168348.17      2275038.16      7168316.30
      2275019.50      7167534.23
#Sta/Elev= 30
  4195.8  833.93  4211.7  831.82  4261.8  831.49  4289.8  828.42  4321.8  829.17
  4341.8  827.83  4391.9  817.65  4431.9  811.97  4461.9  808.45  4487.4  807.98
  4592.0  806.56  4793.0  807.16  4809.0  797.71  4810.1  797.21  4815.3  797.71
  4822.2  803.85  4832.2  806.91  4852.2  808.62  4882.2  806.44  5027.8  805.90
  5215.3  807.63  5267.9  806.80  5307.9  808.20  5347.9  806.13  5357.9  808.75
  5467.9  809.75  5544.7  812.75  5618.0  817.20  5688.0  824.62  5793.8  829.82
#Mann=7,-1,0
  4195.8    0.05       0  4289.8    0.12       0  4487.4    0.05       0
  4809.0   0.033       0  4815.3    0.05       0  5215.3    0.12       0
  5544.7    0.05       0
Bank Sta=4809,4815.3
Exp/Cntr=0.3,0.1

Chan Stop Cuts=-1