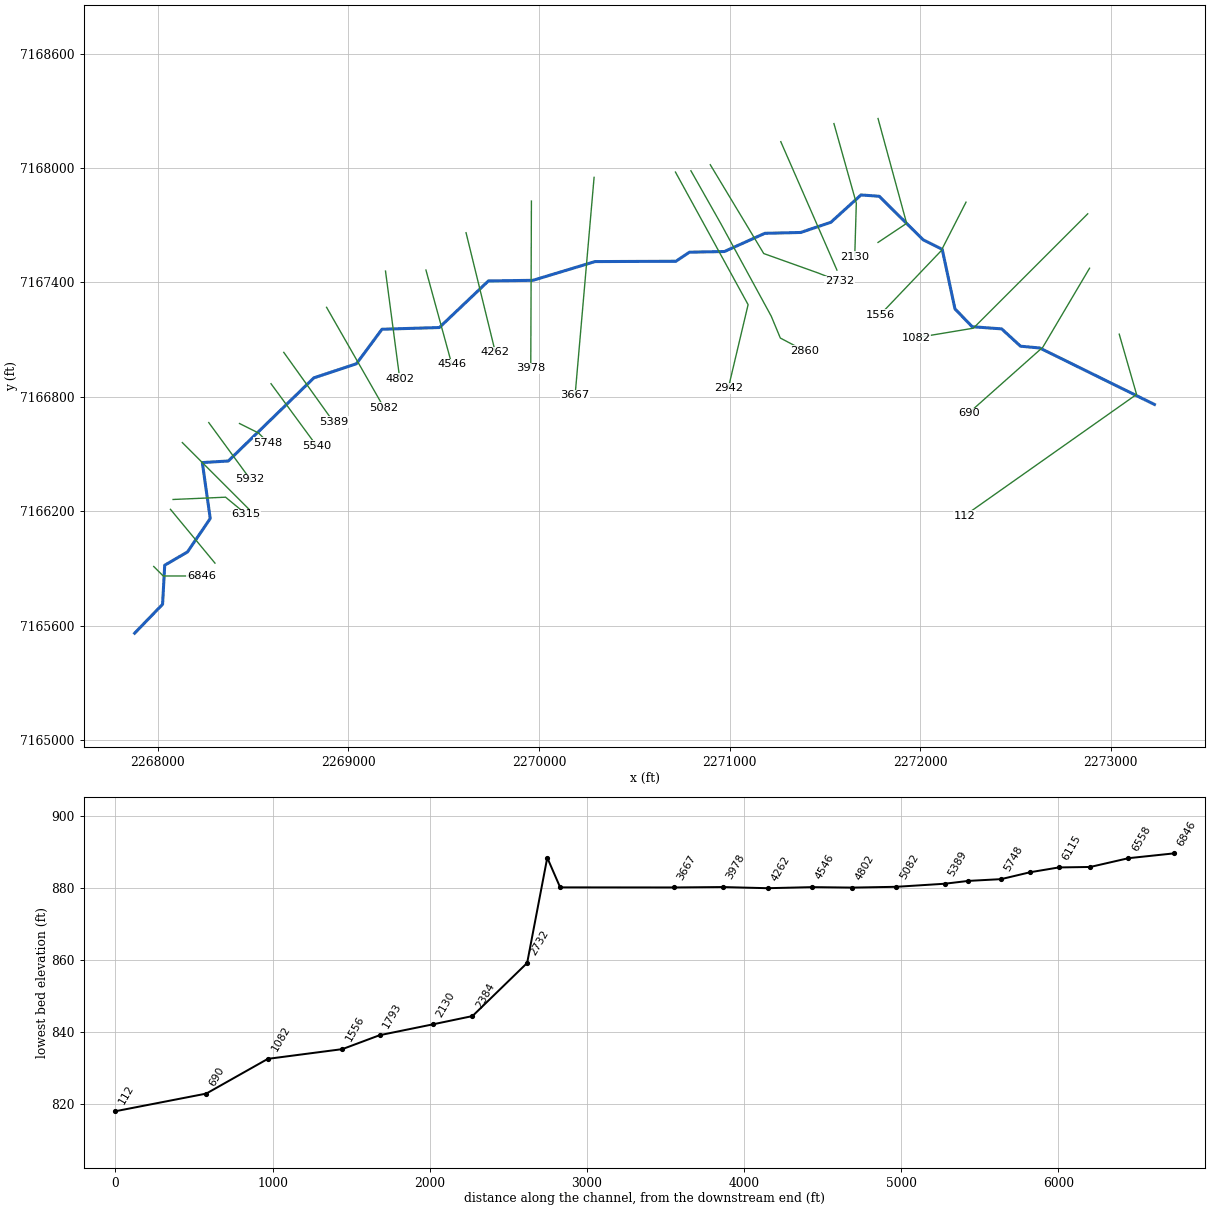
--- MDE S 032.prj (project) ---

Proj Title=MDE S 032 Base Level Engineering
Current Plan=p01
Default Exp/Contr=0.3,0.1
English Units
Geom File=g01
Flow File=f01
Plan File=p01
BEGIN DESCRIPTION:
MDE S 032
END DESCRIPTION:

--- MDE S 032.p01 (plan) ---

Plan Title=Multiple Run
Short Identifier=Multiple
Geom File=g01
Flow File=f01
Subcritical Flow
K Sum by GR= 0
Std Step Tol= 0.01
Critical Tol= 0.01
Num of Std Step Trials= 20
Max Error Tol= 0.3
Flow Tol Ratio= 0.001
Split Flow NTrial= 30
Split Flow Tol= 0.02
Split Flow Ratio= 0.02
Log Output Level= 0
Friction Slope Method= 1
Unsteady Friction Slope Method= 2
Unsteady Bridges Friction Slope Method= 1
Parabolic Critical Depth
Global Vel Dist=  1 , 1 , 1
Global Log Level= 0
CheckData=True
Encroach Param= -1, 0, 0, 0
BEGIN DESCRIPTION:
Multiple Run
END DESCRIPTION:

--- MDE S 032.f01 (steady flow) ---

Flow Title=Multiple
Number of Profiles=7
Profile Names=10-year,25-year,50-year,1pct_min,100-year,1pct_plu,500-year
River Rch & RM= MDE S 032,Reach-1,6846
     714     996    1234     760    1516    3025    2293
Boundary for River Rch & Prof#=MDE S 032,Reach-1,1
Up Type=0
Dn Type=3
Dn Slope=0.005
Boundary for River Rch & Prof#=MDE S 032,Reach-1,2
Up Type=0
Dn Type=3
Dn Slope=0.005
Boundary for River Rch & Prof#=MDE S 032,Reach-1,3
Up Type=0
Dn Type=3
Dn Slope=0.005
Boundary for River Rch & Prof#=MDE S 032,Reach-1,4
Up Type=0
Dn Type=3
Dn Slope=0.005
Boundary for River Rch & Prof#=MDE S 032,Reach-1,5
Up Type=0
Dn Type=3
Dn Slope=0.005
Boundary for River Rch & Prof#=MDE S 032,Reach-1,6
Up Type=0
Dn Type=3
Dn Slope=0.005
Boundary for River Rch & Prof#=MDE S 032,Reach-1,7
Up Type=0
Dn Type=3
Dn Slope=0.005

--- MDE S 032.g01 (geometry) ---

Geom Title=Existing Conditions

River Reach=MDE S 032,Reach-1
Reach XY= 30
      2267879.00      7165560.00      2268025.47      7165711.46
      2268036.70      7165916.48      2268156.13      7165986.17
      2268275.53      7166161.50      2268234.00      7166454.99
      2268370.55      7166463.41      2268819.21      7166899.48
      2269042.57      7166973.47      2269176.53      7167154.55
      2269477.54      7167163.54      2269734.85      7167407.94
      2269968.50      7167411.22      2270294.22      7167509.48
      2270718.50      7167511.22      2270789.51      7167558.78
      2270973.06      7167562.26      2271184.94      7167657.74
      2271373.06      7167662.26      2271531.43      7167715.52
      2271689.48      7167859.07      2271785.17      7167852.24
      2272015.80      7167623.64      2272115.74      7167573.65
      2272182.54      7167261.46      2272272.79      7167167.81
      2272427.53      7167156.44      2272526.58      7167065.54
      2272627.41      7167056.17      2273229.00      7166760.00

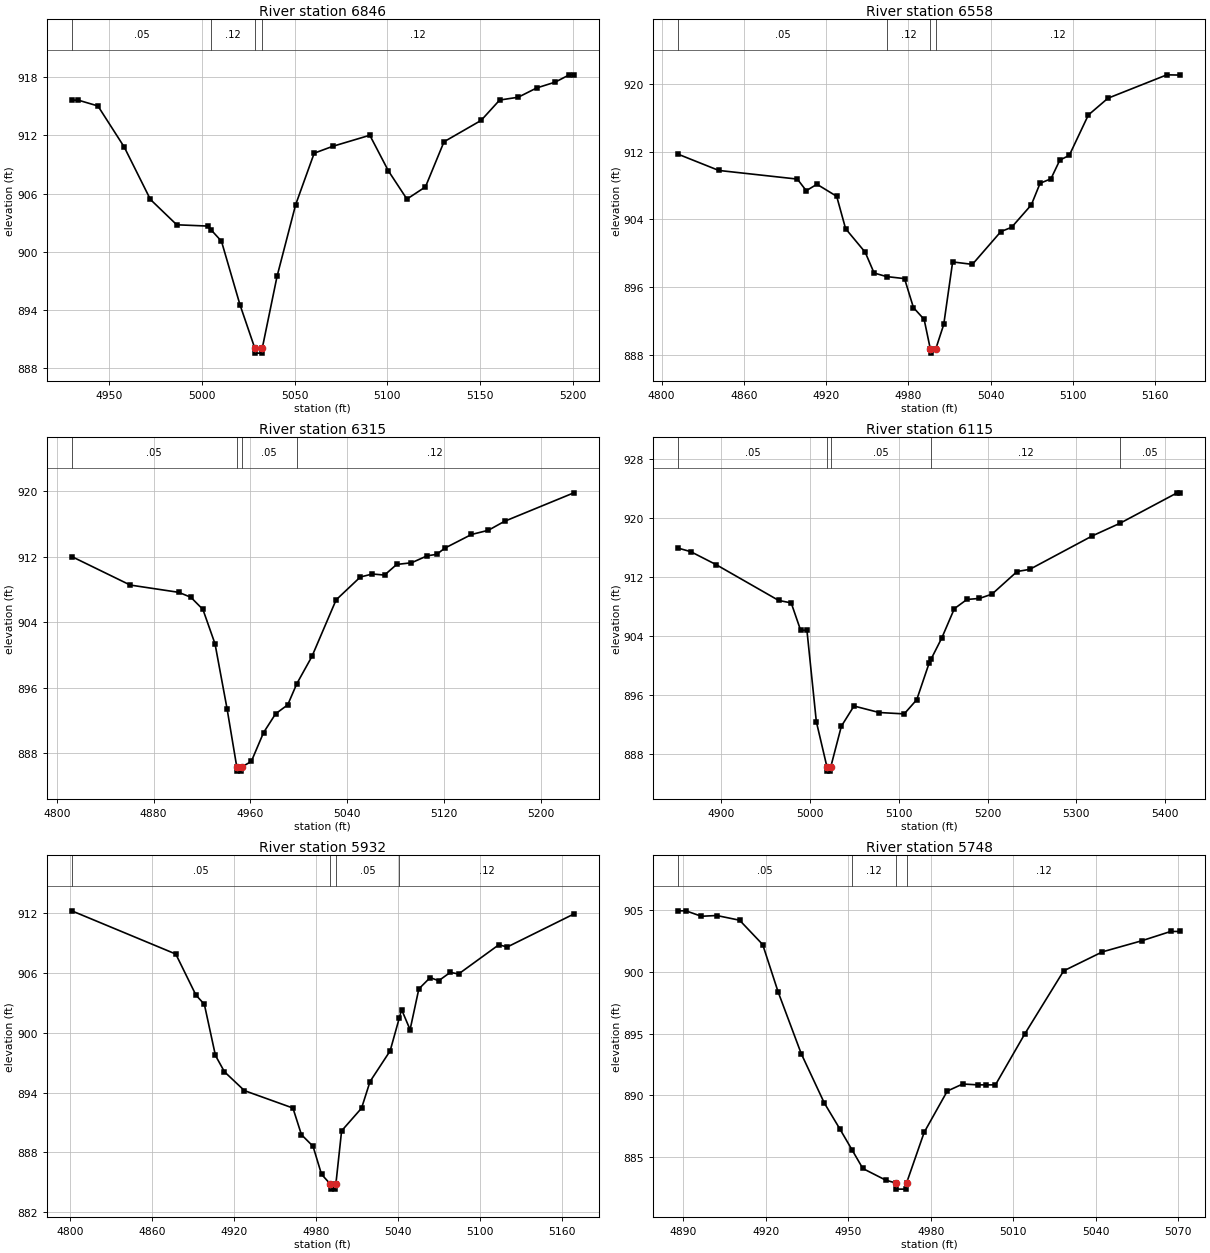
Type RM Length L Ch R = 1,6846,288,288,288
BEGIN DESCRIPTION:
MDE S 032 19.0
END DESCRIPTION:
XS GIS Cut Line= 3
      2267979.00      7165910.00      2268029.00      7165860.00
      2268228.99      7165860.00
#Sta/Elev= 30
  4929.9  915.64  4933.4  915.64  4944.0  915.04  4958.2  910.80  4972.3  905.40
  4986.5  902.79  5003.1  902.66  5004.9  902.29  5010.6  901.10  5020.6  894.54
  5028.6  890.06  5028.9  889.56  5032.4  889.56  5032.6  890.06  5040.6  897.49
  5050.6  904.86  5060.6  910.17  5070.6  910.88  5090.6  912.02  5100.6  908.35
  5110.6  905.44  5120.6  906.70  5130.6  911.35  5150.6  913.55  5160.6  915.65
  5170.6  915.94  5180.6  916.90  5190.6  917.50  5198.1  918.25  5200.6  918.25
#Mann=4,-1,0
  4929.9    0.05       0  5004.9    0.12       0  5028.6   0.033       0
  5032.6    0.12       0
Bank Sta=5028.6,5032.6
Exp/Cntr=0.3,0.1

Type RM Length L Ch R = 1,6558,243,243,243
BEGIN DESCRIPTION:
Mapping XS 6430c67b
END DESCRIPTION:
XS GIS Cut Line= 2
      2268066.78      7166209.77      2268300.29      7165927.56
#Sta/Elev= 30
  4812.1  911.69  4841.7  909.78  4899.0  908.76  4905.5  907.39  4913.3  908.15
  4927.7  906.73  4934.2  902.91  4948.5  900.13  4955.0  897.68  4964.1  897.26
  4977.2  897.02  4983.7  893.60  4991.5  892.21  4996.0  888.73  4996.2  888.23
  5000.0  888.73  5005.8  891.61  5012.3  898.99  5026.7  898.70  5047.5  902.57
  5055.3  903.07  5069.7  905.72  5076.1  908.27  5084.0  908.79  5090.5  911.00
  5097.4  911.56  5111.3  916.32  5125.6  918.30  5168.6  921.06  5178.4  921.03
#Mann=4,-1,0
  4812.1    0.05       0  4964.1    0.12       0  4996.0    0.07       0
  5000.0    0.12       0
Bank Sta=4996,5000
Exp/Cntr=0.3,0.1

Type RM Length L Ch R = 1,6315,200,200,200
BEGIN DESCRIPTION:
Mapping XS 0a7c6e74
END DESCRIPTION:
XS GIS Cut Line= 3
      2268080.70      7166261.45      2268356.09      7166273.40
      2268463.49      7166184.61
#Sta/Elev= 30
  4812.3  912.01  4860.6  908.53  4900.7  907.64  4910.7  907.04  4920.7  905.55
  4930.7  901.35  4940.7  893.38  4948.7  886.29  4949.0  885.79  4952.5  885.79
  4952.7  886.29  4960.7  886.97  4970.8  890.49  4980.8  892.80  4990.8  893.89
  4998.3  896.47  5010.8  899.80  5030.8  906.72  5050.8  909.51  5060.8  909.88
  5070.8  909.75  5080.9  911.05  5093.1  911.25  5106.2  912.11  5114.0  912.28
  5120.5  913.03  5142.7  914.71  5156.6  915.22  5170.0  916.32  5227.3  919.80
#Mann=4,-1,0
  4812.3    0.05       0  4948.7    0.07       0  4952.7    0.05       0
  4998.3    0.12       0
Bank Sta=4948.7,4952.7
Exp/Cntr=0.3,0.1

Type RM Length L Ch R = 1,6115,183,183,183
BEGIN DESCRIPTION:
MDE S 032 17.0
END DESCRIPTION:
XS GIS Cut Line= 3
      2268129.00      7166560.00      2268229.00      7166460.00
      2268529.01      7166159.99
#Sta/Elev= 30
  4851.5  915.90  4865.6  915.42  4893.9  913.68  4964.6  908.81  4978.8  908.47
  4989.4  904.76  4996.5  904.76  5007.1  892.37  5019.2  886.16  5019.5  885.66
  5023.0  885.66  5023.2  886.16  5035.3  891.75  5049.5  894.49  5077.8  893.61
  5106.1  893.42  5120.2  895.34  5134.3  900.35  5136.3  900.83  5148.5  903.73
  5162.6  907.69  5176.8  908.94  5190.9  909.08  5205.0  909.66  5233.3  912.73
  5247.5  913.02  5318.2  917.57  5349.2  919.27  5413.6  923.40  5417.2  923.40
#Mann=5,-1,0
  4851.5    0.05       0  5019.2   0.033       0  5023.2    0.05       0
  5136.3    0.12       0  5349.2    0.05       0
Bank Sta=5019.2,5023.2
Exp/Cntr=0.3,0.1

Type RM Length L Ch R = 1,5932,184,184,184
BEGIN DESCRIPTION:
Mapping XS 66009c55
END DESCRIPTION:
XS GIS Cut Line= 2
      2268267.81      7166664.80      2268484.85      7166368.48
#Sta/Elev= 30
  4801.1  912.26  4877.2  907.92  4891.9  903.81  4898.1  902.87  4906.2  897.74
  4912.8  896.10  4927.4  894.21  4962.9  892.46  4969.1  889.79  4977.6  888.62
  4983.8  885.81  4990.3  884.82  4990.5  884.32  4994.0  884.32  4994.3  884.82
  4998.5  890.17  5013.1  892.45  5019.3  895.12  5034.0  898.20  5040.7  901.50
  5042.4  902.34  5048.6  900.33  5055.0  904.42  5063.3  905.56  5069.5  905.24
  5078.0  906.08  5084.1  905.92  5113.5  908.85  5119.7  908.63  5168.4  911.94
#Mann=4,-1,0
  4801.1    0.05       0  4990.3   0.033       0  4994.3    0.05       0
  5040.7    0.12       0
Bank Sta=4990.3,4994.3
Exp/Cntr=0.3,0.1

Type RM Length L Ch R = 1,5748,208,208,208
BEGIN DESCRIPTION:
MDE S 032 16.0
END DESCRIPTION:
XS GIS Cut Line= 3
      2268429.02      7166659.99      2268529.00      7166610.00
      2268579.00      7166560.00
#Sta/Elev= 29
  4888.2  904.94  4891.0  904.94  4896.6  904.50  4902.2  904.56  4910.5  904.18
  4918.9  902.21  4924.5  898.38  4932.9  893.38  4941.3  889.38  4946.9  887.30
  4951.4  885.58  4955.3  884.08  4963.6  883.14  4967.2  882.91  4967.5  882.41
  4971.0  882.41  4971.2  882.91  4977.6  887.01  4986.0  890.35  4991.6  890.92
  4997.2  890.85  5000.0  890.85  5003.5  890.85  5014.1  894.95  5028.3  900.08
  5042.4  901.62  5056.6  902.51  5067.2  903.27  5070.7  903.27
#Mann=4,-1,0
  4888.2    0.05       0  4951.4    0.12       0  4967.2    0.07       0
  4971.2    0.12       0
Bank Sta=4967.2,4971.2
Exp/Cntr=0.3,0.1

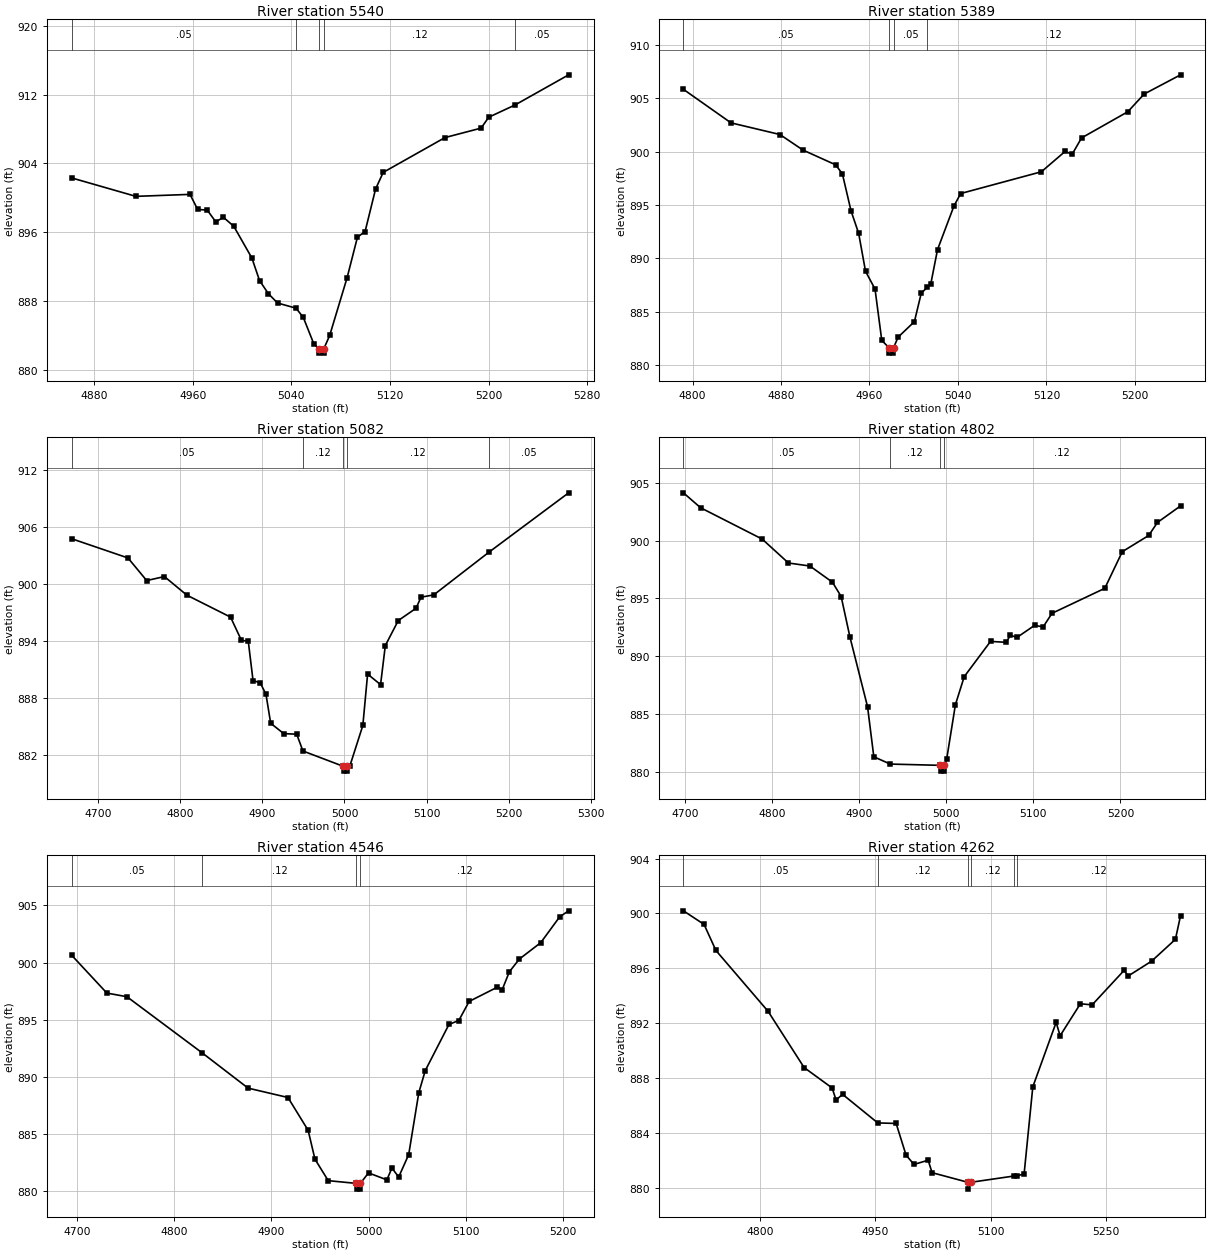
Type RM Length L Ch R = 1,5540,151,151,151
BEGIN DESCRIPTION:
Mapping XS 23d32d12
END DESCRIPTION:
XS GIS Cut Line= 2
      2268594.39      7166868.75      2268833.07      7166543.79
#Sta/Elev= 30
  4861.7  902.31  4913.9  900.16  4957.8  900.39  4964.0  898.64  4971.8  898.56
  4978.7  897.19  4984.9  897.72  4993.3  896.68  5008.0  892.98  5014.2  890.36
  5021.4  888.83  5028.8  887.75  5043.8  887.15  5049.7  886.07  5058.1  883.04
  5062.3  882.42  5062.6  881.92  5066.1  881.92  5066.3  882.42  5071.1  883.98
  5085.2  890.69  5093.6  895.41  5099.8  896.07  5108.3  901.01  5114.5  902.95
  5164.6  907.00  5193.9  908.10  5200.1  909.37  5221.4  910.79  5264.9  914.30
#Mann=5,-1,0
  4861.7    0.05       0  5043.8    0.12       0  5062.3   0.033       0
  5066.3    0.12       0  5221.4    0.05       0
Bank Sta=5062.3,5066.3
Exp/Cntr=0.3,0.1

Type RM Length L Ch R = 1,5389,307,307,307
BEGIN DESCRIPTION:
Mapping XS 4595b0c2
END DESCRIPTION:
XS GIS Cut Line= 2
      2268661.35      7167033.22      2268922.80      7166667.70
#Sta/Elev= 30
  4791.8  905.84  4834.8  902.70  4879.0  901.61  4899.9  900.15  4929.4  898.77
  4935.5  897.92  4943.3  894.46  4950.2  892.35  4956.4  888.80  4965.0  887.13
  4971.1  882.32  4977.7  881.63  4978.0  881.13  4981.5  881.13  4981.7  881.63
  4985.9  882.63  5000.6  884.08  5006.8  886.75  5012.3  887.30  5015.4  887.61
  5021.5  890.83  5036.3  894.90  5042.4  896.08  5115.4  898.12  5137.0  900.04
  5143.1  899.74  5151.7  901.29  5193.5  903.74  5208.3  905.40  5241.2  907.20
#Mann=4,-1,0
  4791.8    0.05       0  4977.7   0.033       0  4981.7    0.05       0
  5012.3    0.12       0
Bank Sta=4977.7,4981.7
Exp/Cntr=0.3,0.1

Type RM Length L Ch R = 1,5082,280,280,280
BEGIN DESCRIPTION:
Mapping XS 1e9d5b7d
END DESCRIPTION:
XS GIS Cut Line= 2
      2268885.74      7167269.69      2269186.54      7166743.84
#Sta/Elev= 30
  4667.4  904.76  4736.2  902.73  4759.0  900.35  4780.6  900.77  4808.0  898.81
  4861.2  896.50  4874.4  894.06  4882.8  893.95  4888.6  889.82  4897.4  889.58
  4904.4  888.36  4910.1  885.32  4926.0  884.23  4941.8  884.17  4949.4  882.40
  4998.8  880.78  4999.1  880.28  5002.6  880.28  5002.8  880.78  5006.6  880.83
  5022.4  885.09  5028.2  890.50  5044.0  889.39  5049.8  893.51  5065.6  896.14
  5087.2  897.43  5093.3  898.60  5108.8  898.84  5175.8  903.32  5273.2  909.59
#Mann=5,-1,0
  4667.4    0.05       0  4949.4    0.12       0  4998.8    0.07       0
  5002.8    0.12       0  5175.8    0.05       0
Bank Sta=4998.8,5002.8
Exp/Cntr=0.3,0.1

Type RM Length L Ch R = 1,4802,256,256,256
BEGIN DESCRIPTION:
Mapping XS f1841461
END DESCRIPTION:
XS GIS Cut Line= 2
      2269195.02      7167459.57      2269269.93      7166893.71
#Sta/Elev= 30
  4698.2  904.13  4717.9  902.84  4788.6  900.13  4818.8  898.06  4843.4  897.80
  4869.3  896.40  4879.3  895.16  4889.4  891.65  4909.6  885.63  4916.8  881.30
  4935.7  880.67  4993.3  880.56  4993.5  880.06  4997.0  880.06  4997.3  880.56
  5000.4  881.07  5010.5  885.81  5020.6  888.23  5050.8  891.28  5068.7  891.20
  5073.7  891.82  5081.1  891.62  5101.3  892.66  5111.3  892.54  5121.4  893.71
  5182.0  895.87  5202.1  899.04  5232.4  900.44  5242.5  901.57  5269.0  903.00
#Mann=4,-1,0
  4698.2    0.05       0  4935.7    0.12       0  4993.3    0.07       0
  4997.3    0.12       0
Bank Sta=4993.3,4997.3
Exp/Cntr=0.3,0.1

Type RM Length L Ch R = 1,4546,284,284,284
BEGIN DESCRIPTION:
Mapping XS 4f6799f3
END DESCRIPTION:
XS GIS Cut Line= 2
      2269407.19      7167465.07      2269542.65      7166971.11
#Sta/Elev= 30
  4694.0  900.65  4730.4  897.33  4751.1  897.01  4828.8  892.09  4875.9  889.02
  4917.0  888.20  4937.8  885.33  4944.8  882.81  4958.5  880.93  4987.6  880.69
  4987.9  880.19  4991.4  880.19  4991.6  880.69  5000.0  881.61  5018.9  881.00
  5024.1  882.03  5031.1  881.25  5041.4  883.21  5051.8  888.62  5058.5  890.56
  5082.9  894.59  5093.0  894.93  5103.7  896.60  5132.6  897.84  5137.8  897.64
  5145.1  899.19  5155.5  900.31  5177.5  901.74  5197.0  904.00  5206.2  904.52
#Mann=4,-1,0
  4694.0    0.05       0  4828.8    0.12       0  4987.6    0.07       0
  4991.6    0.12       0
Bank Sta=4987.6,4991.6
Exp/Cntr=0.3,0.1

Type RM Length L Ch R = 1,4262,284,284,284
BEGIN DESCRIPTION:
Mapping XS 26d3eb2a
END DESCRIPTION:
XS GIS Cut Line= 2
      2269617.58      7167660.95      2269771.40      7167033.53
#Sta/Elev= 30
  4700.8  900.19  4727.6  899.20  4743.0  897.30  4810.8  892.86  4857.6  888.76
  4894.0  887.27  4899.1  886.40  4907.7  886.80  4953.3  884.72  4977.2  884.68
  4990.1  882.37  5000.4  881.69  5018.8  882.00  5023.9  881.09  5070.4  880.39
  5070.7  879.89  5074.4  880.39  5130.8  880.85  5134.3  880.86  5143.5  881.00
  5154.8  887.35  5185.1  892.05  5190.3  891.08  5216.6  893.41  5231.9  893.33
  5273.5  895.85  5278.6  895.43  5309.2  896.52  5340.1  898.11  5346.8  899.84
#Mann=6,-1,0
  4700.8    0.05       0  4953.3    0.12       0  5070.4    0.07       0
  5074.4    0.12       0  5130.8    0.05       0  5134.3    0.12       0
Bank Sta=5070.4,5074.4
Exp/Cntr=0.3,0.1

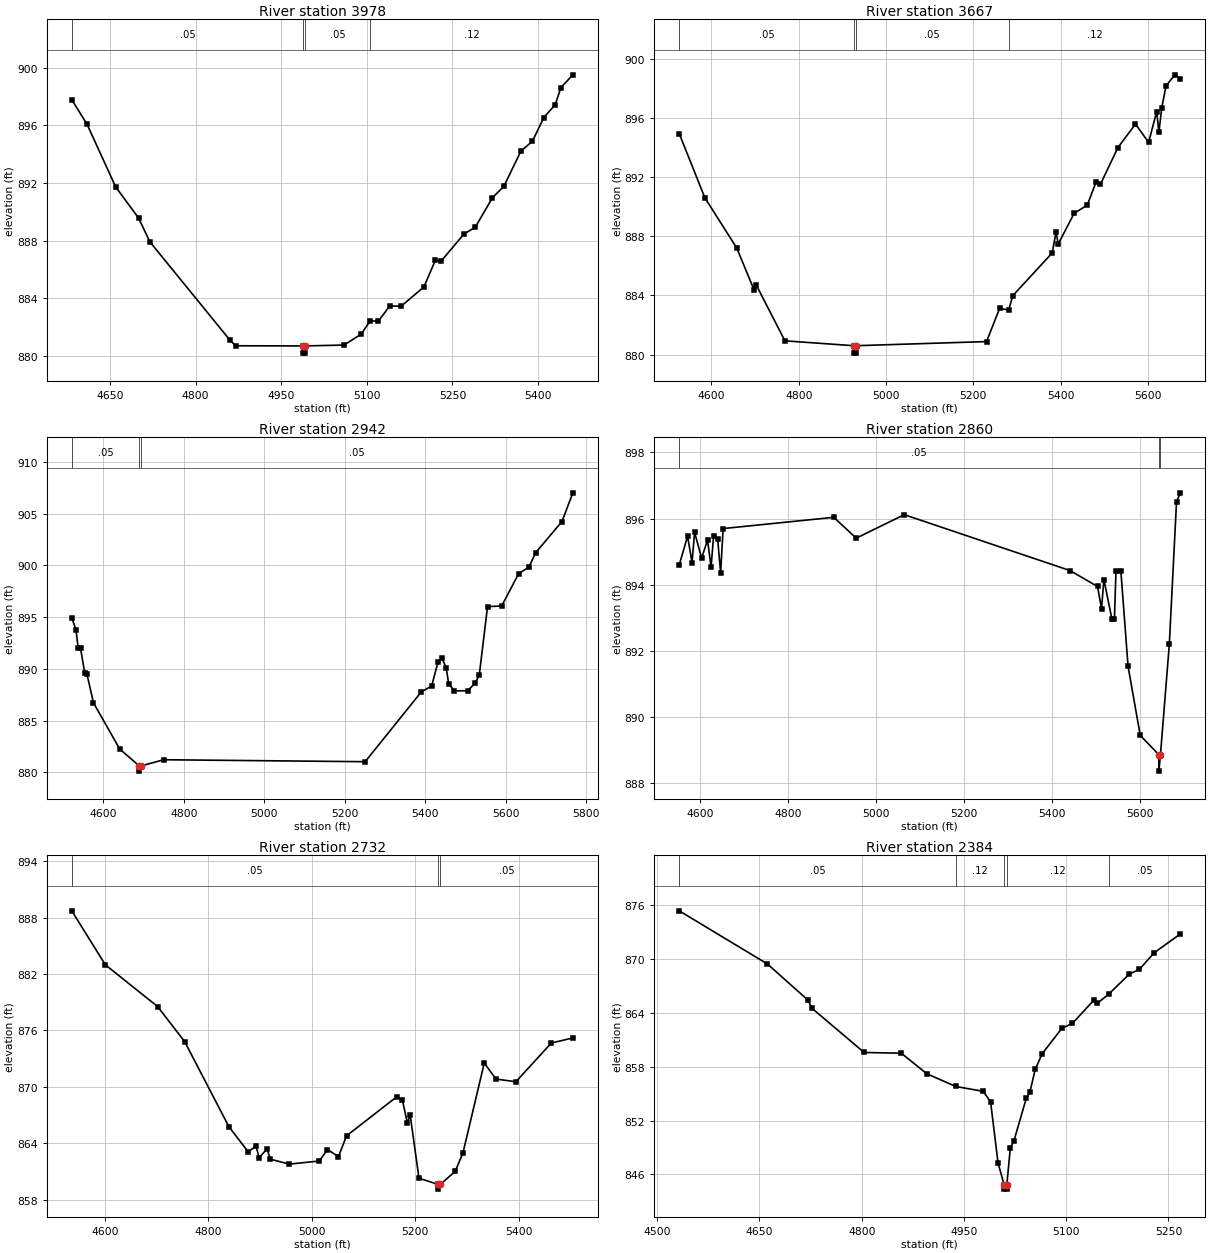
Type RM Length L Ch R = 1,3978,311,311,311
BEGIN DESCRIPTION:
Mapping XS 9a747a22
END DESCRIPTION:
XS GIS Cut Line= 2
      2269960.51      7167826.97      2269957.13      7166949.07
#Sta/Elev= 30
  4583.1  897.78  4610.1  896.06  4660.1  891.73  4700.1  889.58  4720.1  887.92
  4860.1  881.12  4870.1  880.72  4988.1  880.71  4988.3  880.21  4991.8  880.21
  4992.1  880.71  5060.1  880.77  5090.1  881.52  5106.2  882.46  5120.1  882.41
  5140.1  883.48  5160.1  883.46  5200.1  884.80  5220.1  886.64  5230.1  886.58
  5270.1  888.46  5290.1  888.94  5320.1  890.98  5340.1  891.77  5370.1  894.22
  5390.1  894.89  5410.1  896.54  5430.1  897.43  5440.1  898.62  5461.0  899.50
#Mann=4,-1,0
  4583.1    0.05       0  4988.1   0.033       0  4992.1    0.05       0
  5106.2    0.12       0
Bank Sta=4988.1,4992.1
Exp/Cntr=0.3,0.1

Type RM Length L Ch R = 1,3667,725,725,725
BEGIN DESCRIPTION:
Mapping XS 8f7faee8
END DESCRIPTION:
XS GIS Cut Line= 2
      2270289.30      7167951.30      2270189.59      7166807.54
#Sta/Elev= 30
  4526.3  894.93  4585.1  890.59  4658.1  887.20  4697.9  884.36  4702.9  884.69
  4768.5  880.93  4926.4  880.60  4926.7  880.10  4930.2  880.10  4930.4  880.60
  5230.3  880.88  5260.4  883.12  5281.0  883.01  5290.5  883.98  5380.8  886.87
  5389.6  888.28  5394.6  887.47  5431.0  889.54  5461.1  890.10  5481.2  891.65
  5491.2  891.50  5531.4  893.99  5571.6  895.57  5601.7  894.34  5620.2  896.42
  5625.2  895.01  5631.8  896.69  5641.8  898.17  5661.9  898.90  5674.4  898.65
#Mann=4,-1,0
  4526.3    0.05       0  4926.4   0.033       0  4930.4    0.05       0
  5281.0    0.12       0
Bank Sta=4926.4,4930.4
Exp/Cntr=0.3,0.1

Type RM Length L Ch R = 1,2942,82,82,82
BEGIN DESCRIPTION:
Mapping XS 20be928d
END DESCRIPTION:
XS GIS Cut Line= 3
      2270716.18      7167979.08      2271097.31      7167283.56
      2270993.01      7166843.76
#Sta/Elev= 30
  4521.7  894.95  4532.1  893.79  4537.9  891.97  4543.6  891.99  4554.0  889.61
  4559.7  889.46  4575.8  886.71  4641.2  882.24  4689.7  880.62  4689.9  880.12
  4693.7  880.62  4750.2  881.22  5250.8  881.03  5390.4  887.78  5416.0  888.34
  5431.5  890.62  5441.8  891.02  5452.1  890.10  5458.2  888.58  5472.6  887.87
  5505.5  887.88  5524.0  888.62  5534.3  889.40  5554.8  896.01  5590.0  896.07
  5632.2  899.20  5657.6  899.82  5674.4  901.22  5739.8  904.23  5766.8  907.00
#Mann=3,-1,0
  4521.7    0.05       0  4689.7   0.033       0  4693.7    0.05       0
Bank Sta=4689.7,4693.7
Exp/Cntr=0.3,0.1

Type RM Length L Ch R = 1,2860,128,128,128
BEGIN DESCRIPTION:
Mapping XS b2920ad2
END DESCRIPTION:
XS GIS Cut Line= 5
      2270797.23      7167986.05      2270953.47      7167709.92
      2271218.72      7167223.01      2271266.41      7167108.31
      2271393.07      7167041.64
#Sta/Elev= 30
  4552.9  894.60  4571.9  895.47  4582.0  894.67  4587.8  895.59  4603.7  894.81
  4617.3  895.35  4625.3  894.54  4631.1  895.49  4640.3  895.37  4647.0  894.37
  4652.7  895.70  4904.2  896.04  4955.2  895.41  5064.4  896.12  5441.3  894.43
  5503.7  893.95  5512.8  893.28  5518.2  894.16  5536.2  892.98  5542.1  892.96
  5545.7  894.43  5556.7  894.43  5573.1  891.54  5600.8  889.45  5642.8  888.87
  5643.1  888.37  5646.8  888.87  5666.9  892.20  5683.3  896.51  5692.0  896.78
#Mann=3,-1,0
  4552.9    0.05       0  5642.8   0.033       0  5646.8    0.05       0
Bank Sta=5642.8,5646.8
Exp/Cntr=0.3,0.1

Type RM Length L Ch R = 1,2732,348,348,348
BEGIN DESCRIPTION:
Mapping XS f7d703de
END DESCRIPTION:
XS GIS Cut Line= 4
      2270898.77      7168017.87      2271179.37      7167551.65
      2271465.16      7167449.48      2271577.75      7167405.32
#Sta/Elev= 30
  4536.1  888.71  4601.1  882.97  4702.1  878.53  4754.6  874.78  4840.0  865.74
  4876.9  863.10  4892.5  863.66  4898.3  862.46  4913.8  863.40  4919.7  862.30
  4956.6  861.77  5014.8  862.10  5030.4  863.32  5051.7  862.57  5067.3  864.78
  5164.8  868.95  5175.4  868.54  5184.9  866.13  5190.2  867.02  5207.3  860.27
  5244.5  859.61  5244.8  859.11  5248.5  859.61  5277.3  861.00  5292.3  862.96
  5333.5  872.53  5356.0  870.82  5394.6  870.53  5463.1  874.65  5504.7  875.19
#Mann=3,-1,0
  4536.1    0.05       0  5244.5   0.033       0  5248.5    0.05       0
Bank Sta=5244.5,5248.5
Exp/Cntr=0.3,0.1

Type RM Length L Ch R = 1,2384,254,254,254
BEGIN DESCRIPTION:
Mapping XS d9952485
END DESCRIPTION:
XS GIS Cut Line= 2
      2271268.78      7168138.54      2271563.35      7167464.93
#Sta/Elev= 30
  4532.3  875.39  4661.7  869.46  4720.9  865.45  4727.2  864.51  4803.6  859.59
  4858.1  859.51  4895.5  857.22  4937.9  855.80  4978.2  855.26  4989.1  854.08
  5000.0  847.28  5008.9  844.85  5009.2  844.35  5012.7  844.35  5012.9  844.85
  5018.0  848.90  5023.4  849.75  5041.4  854.47  5046.8  855.19  5054.6  857.72
  5064.8  859.45  5093.6  862.28  5109.2  862.84  5140.4  865.41  5145.8  865.08
  5162.8  866.13  5192.6  868.33  5207.4  868.86  5229.2  870.72  5267.5  872.81
#Mann=5,-1,0
  4532.3    0.05       0  4937.9    0.12       0  5008.9    0.07       0
  5012.9    0.12       0  5162.8    0.05       0
Bank Sta=5008.9,5012.9
Exp/Cntr=0.3,0.1

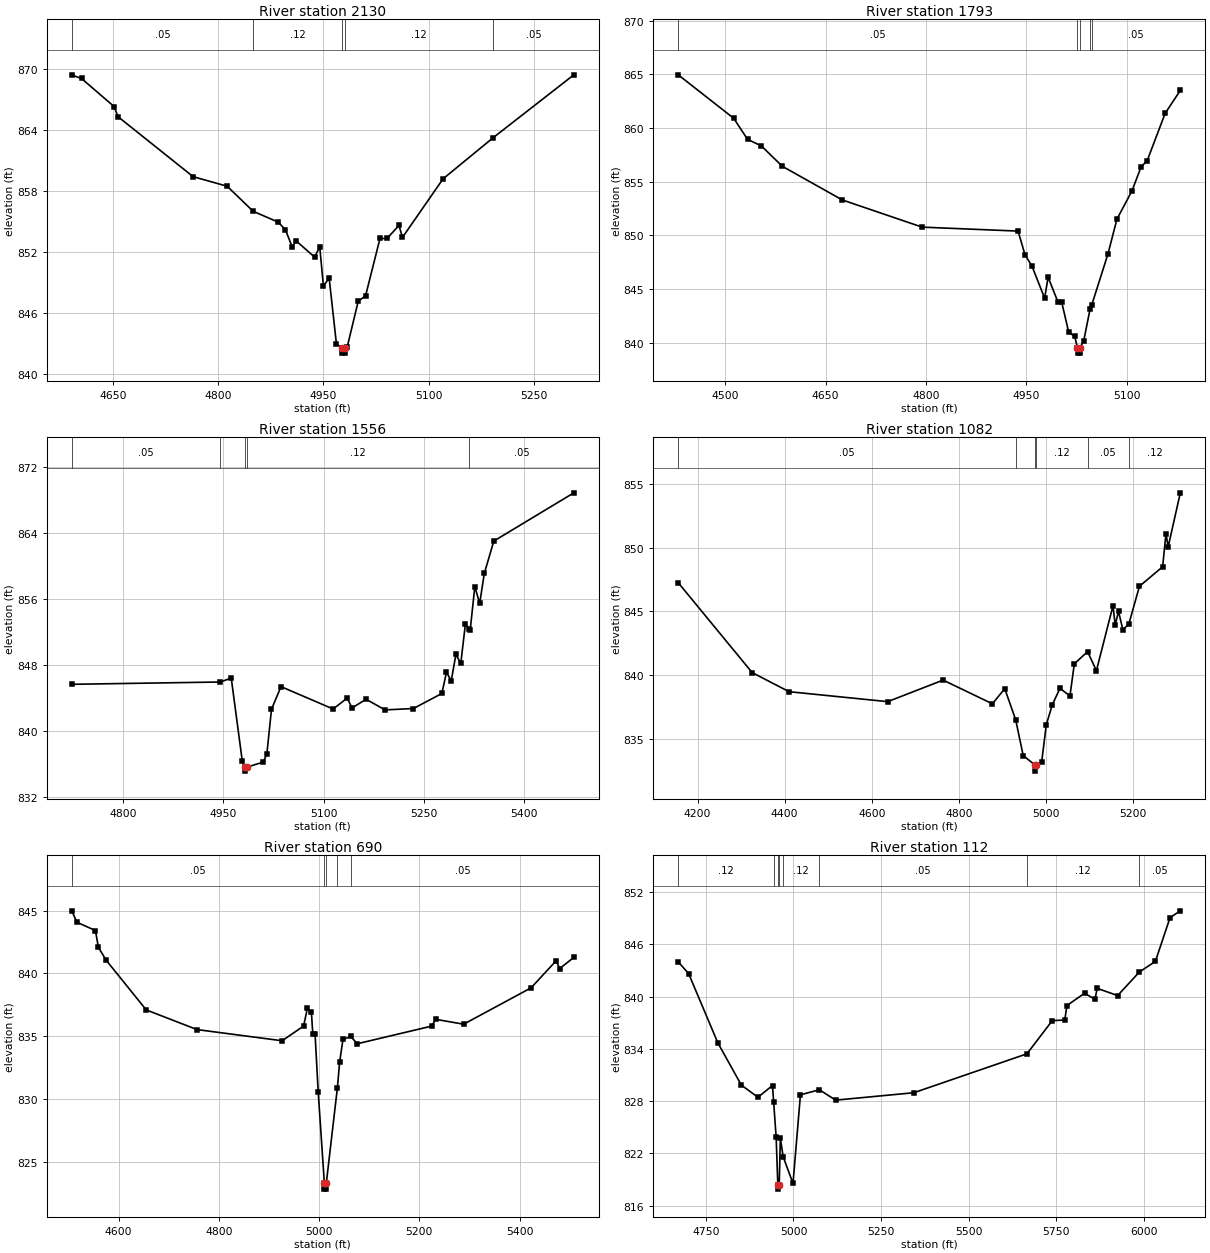
Type RM Length L Ch R = 1,2130,337,337,337
BEGIN DESCRIPTION:
Mapping XS 49ad31f9
END DESCRIPTION:
XS GIS Cut Line= 3
      2271547.64      7168233.38      2271665.04      7167815.84
      2271656.69      7167533.59
#Sta/Elev= 30
  4591.2  869.39  4605.1  869.05  4651.7  866.28  4657.0  865.30  4764.3  859.39
  4812.8  858.45  4850.0  855.98  4885.6  854.92  4896.0  854.16  4905.7  852.46
  4910.9  853.09  4937.5  851.48  4944.9  852.48  4950.1  848.63  4958.3  849.41
  4968.7  842.93  4977.0  842.53  4977.3  842.03  4980.8  842.03  4981.0  842.53
  4984.1  842.65  4999.8  847.15  5010.2  847.66  5030.8  853.31  5040.8  853.31
  5057.9  854.59  5062.9  853.42  5120.8  859.18  5192.5  863.24  5307.3  869.41
#Mann=5,-1,0
  4591.2    0.05       0  4850.0    0.12       0  4977.0    0.07       0
  4981.0    0.12       0  5192.5    0.05       0
Bank Sta=4977,4981
Exp/Cntr=0.3,0.1

Type RM Length L Ch R = 1,1793,237,237,237
BEGIN DESCRIPTION:
MDE S 032 5.0
END DESCRIPTION:
XS GIS Cut Line= 3
      2271779.00      7168259.99      2271929.00      7167710.00
      2271778.96      7167609.98
#Sta/Elev= 30
  4429.9  864.96  4512.8  860.91  4533.5  858.95  4554.3  858.33  4585.4  856.44
  4675.2  853.30  4794.4  850.77  4937.8  850.40  4948.2  848.19  4958.5  847.15
  4977.5  844.15  4982.7  846.11  4997.4  843.79  5003.0  843.79  5013.5  840.97
  5022.5  840.59  5026.5  839.53  5026.8  839.03  5030.3  839.03  5030.5  839.53
  5036.0  840.19  5045.4  843.13  5047.9  843.51  5072.1  848.26  5085.6  851.52
  5108.1  854.15  5121.7  856.39  5130.7  856.95  5157.7  861.38  5180.3  863.51
#Mann=5,-1,0
  4429.9    0.05       0  5026.5   0.033       0  5030.5    0.05       0
  5045.4    0.12       0  5047.9    0.05       0
Bank Sta=5026.5,5030.5
Exp/Cntr=0.3,0.1

Type RM Length L Ch R = 1,1556,474,474,474
BEGIN DESCRIPTION:
Mapping XS a62ee333
END DESCRIPTION:
XS GIS Cut Line= 3
      2272240.58      7167821.31      2272110.16      7167566.22
      2271789.55      7167230.24
#Sta/Elev= 30
  4723.3  845.67  4945.7  845.95  4961.8  846.43  4978.4  836.33  4982.0  835.66
  4982.3  835.16  4986.0  835.66  5009.8  836.26  5015.1  837.26  5022.0  842.64
  5036.2  845.39  5114.2  842.68  5135.2  844.00  5142.5  842.81  5163.5  843.86
  5191.9  842.57  5234.3  842.74  5276.8  844.56  5283.7  847.12  5290.9  846.11
  5297.8  849.28  5305.1  848.19  5312.0  852.97  5317.4  852.42  5319.2  852.24
  5326.1  857.49  5333.4  855.47  5340.3  859.10  5354.5  863.01  5474.2  868.85
#Mann=5,-1,0
  4723.3    0.05       0  4945.7    0.12       0  4982.0    0.07       0
  4986.0    0.12       0  5317.4    0.05       0
Bank Sta=4982,4986
Exp/Cntr=0.3,0.1

Type RM Length L Ch R = 1,1082,392,392,392
BEGIN DESCRIPTION:
MDE S 032 3.0
END DESCRIPTION:
XS GIS Cut Line= 3
      2272879.02      7167760.02      2272279.00      7167160.00
      2271979.00      7167110.00
#Sta/Elev= 30
  4155.7  847.24  4325.4  840.19  4410.3  838.69  4636.6  837.91  4763.8  839.60
  4877.0  837.74  4905.3  838.93  4930.5  836.48  4947.7  833.68  4974.0  832.96
  4974.2  832.46  4978.0  832.96  4990.1  833.18  5000.7  836.09  5014.4  837.66
  5032.1  838.95  5055.0  838.36  5065.1  840.88  5095.5  841.83  5115.8  840.34
  5153.8  845.43  5158.9  843.91  5166.5  845.00  5176.6  843.54  5190.3  844.01
  5214.6  846.96  5267.8  848.49  5275.5  851.09  5280.5  850.05  5308.4  854.29
#Mann=6,-1,0
  4155.7    0.05       0  4930.5    0.12       0  4974.0    0.07       0
  4978.0    0.12       0  5095.5    0.05       0  5190.3    0.12       0
Bank Sta=4974,4978
Exp/Cntr=0.3,0.1

Type RM Length L Ch R = 1,690,578,578,578
BEGIN DESCRIPTION:
Mapping XS c6a5baf4
END DESCRIPTION:
XS GIS Cut Line= 3
      2272888.62      7167474.71      2272643.50      7167060.33
      2272254.58      7166714.48
#Sta/Elev= 30
  4506.4  844.99  4516.6  844.08  4553.6  843.42  4559.5  842.08  4575.1  841.05
  4655.0  837.09  4756.4  835.52  4926.1  834.63  4969.0  835.80  4976.6  837.23
  4984.6  836.89  4987.4  835.17  4991.9  835.17  4998.2  830.52  5010.4  823.30
  5010.7  822.80  5014.2  822.80  5014.4  823.30  5036.5  830.90  5040.9  832.92
  5047.6  834.74  5063.2  834.97  5076.0  834.39  5224.8  835.80  5232.4  836.34
  5288.4  835.95  5423.0  838.85  5473.2  841.02  5479.9  840.38  5508.3  841.28
#Mann=5,-1,0
  4506.4    0.05       0  5010.4   0.033       0  5014.4    0.05       0
  5036.5    0.12       0  5063.2    0.05       0
Bank Sta=5010.4,5014.4
Exp/Cntr=0.3,0.1

Type RM Length L Ch R = 1,112,0,0,0
BEGIN DESCRIPTION:
MDE S 032 1.0
END DESCRIPTION:
XS GIS Cut Line= 3
      2273044.34      7167128.61      2273135.33      7166812.66
      2272232.80      7166176.14
#Sta/Elev= 30
  4671.0  844.00  4700.7  842.65  4784.0  834.70  4851.1  829.85  4898.5  828.45
  4940.1  829.80  4943.5  827.85  4950.5  823.84  4955.3  818.40  4955.5  817.90
  4959.3  818.40  4962.5  823.75  4970.4  821.64  4998.6  818.55  5019.8  828.73
  5073.7  829.31  5120.5  828.12  5343.4  828.97  5666.4  833.44  5738.7  837.25
  5774.4  837.32  5780.5  838.98  5831.0  840.40  5860.6  839.69  5866.8  840.96
  5925.3  840.13  5987.2  842.83  6033.0  844.05  6074.9  849.08  6104.2  849.86
#Mann=8,-1,0
  4671.0    0.12       0  4943.5    0.05       0  4955.3    0.07       0
  4959.3    0.05       0  4970.4    0.12       0  5073.7    0.05       0
  5666.4    0.12       0  5987.2    0.05       0
Bank Sta=4955.3,4959.3
Exp/Cntr=0.3,0.1

Chan Stop Cuts=-1