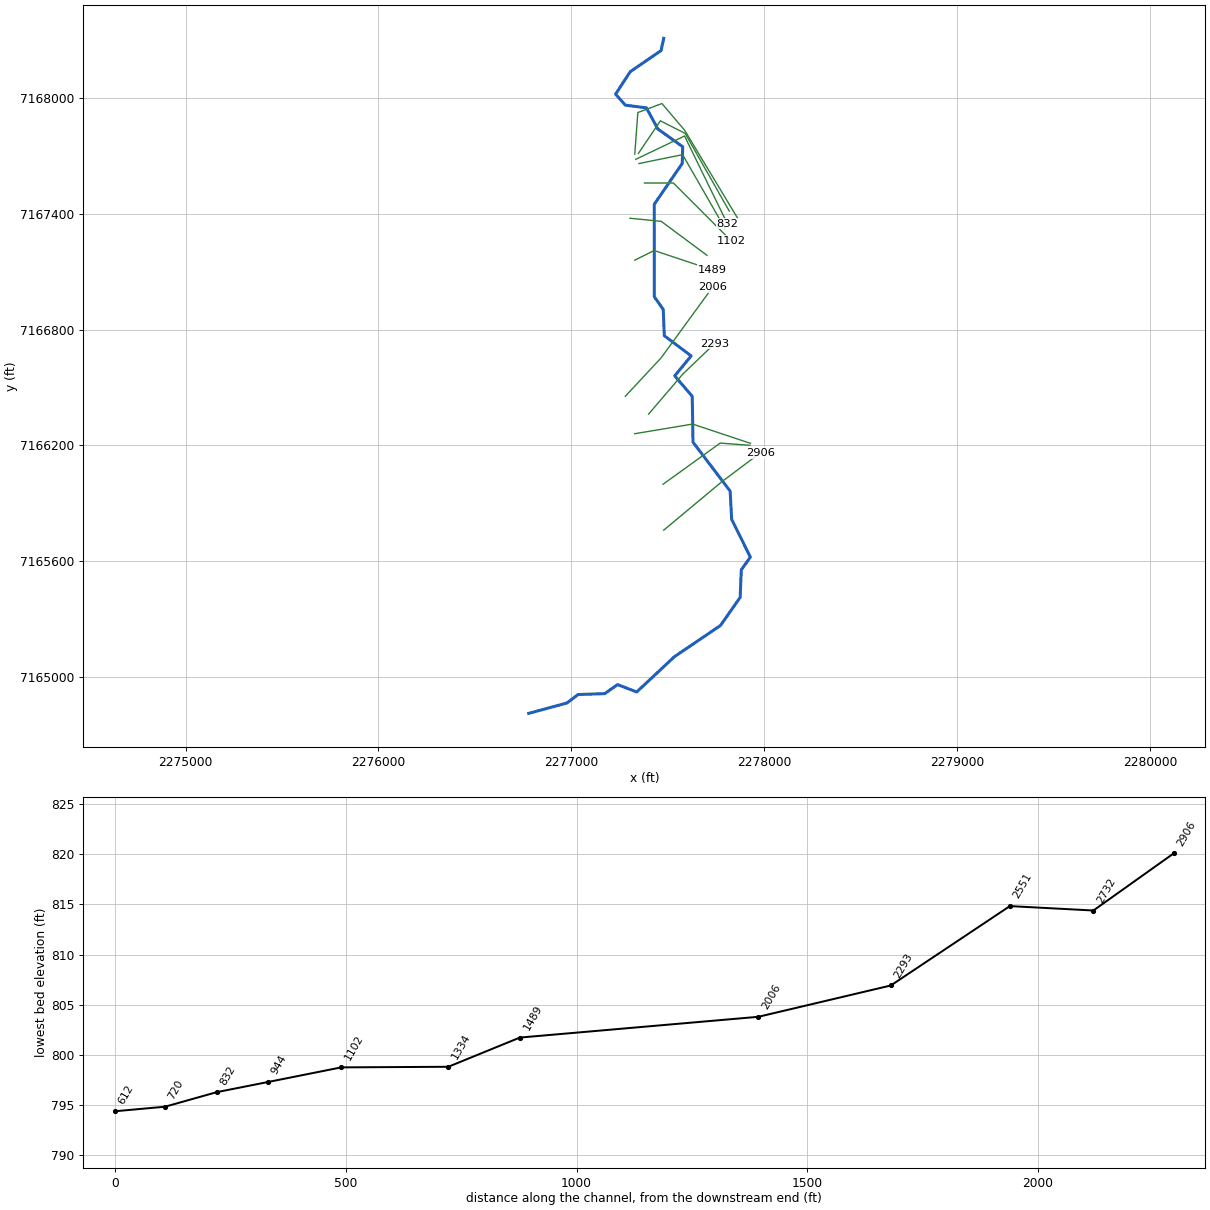
--- MDE S 033.prj (project) ---

Proj Title=MDE S 033 Base Level Engineering
Current Plan=p01
Default Exp/Contr=0.3,0.1
English Units
Geom File=g01
Flow File=f01
Plan File=p01
BEGIN DESCRIPTION:
MDE S 033
END DESCRIPTION:

--- MDE S 033.p01 (plan) ---

Plan Title=Multiple Run
Short Identifier=Multiple
Geom File=g01
Flow File=f01
Subcritical Flow
K Sum by GR= 0
Std Step Tol= 0.01
Critical Tol= 0.01
Num of Std Step Trials= 20
Max Error Tol= 0.3
Flow Tol Ratio= 0.001
Split Flow NTrial= 30
Split Flow Tol= 0.02
Split Flow Ratio= 0.02
Log Output Level= 0
Friction Slope Method= 1
Unsteady Friction Slope Method= 2
Unsteady Bridges Friction Slope Method= 1
Parabolic Critical Depth
Global Vel Dist=  1 , 1 , 1
Global Log Level= 0
CheckData=True
Encroach Param= -1, 0, 0, 0
BEGIN DESCRIPTION:
Multiple Run
END DESCRIPTION:

--- MDE S 033.f01 (steady flow) ---

Flow Title=Multiple
Number of Profiles=7
Profile Names=10-year,25-year,50-year,1pct_min,100-year,1pct_plu,500-year
River Rch & RM= MDE S 033,Reach-1,2906
     591     813     998     610    1216    2427    1807
River Rch & RM= MDE S 033,Reach-1,612
     714     995    1232     758    1512    3017    2281
Boundary for River Rch & Prof#=MDE S 033,Reach-1,1
Up Type=0
Dn Type=3
Dn Slope=0.009
Boundary for River Rch & Prof#=MDE S 033,Reach-1,2
Up Type=0
Dn Type=3
Dn Slope=0.009
Boundary for River Rch & Prof#=MDE S 033,Reach-1,3
Up Type=0
Dn Type=3
Dn Slope=0.009
Boundary for River Rch & Prof#=MDE S 033,Reach-1,4
Up Type=0
Dn Type=3
Dn Slope=0.009
Boundary for River Rch & Prof#=MDE S 033,Reach-1,5
Up Type=0
Dn Type=3
Dn Slope=0.009
Boundary for River Rch & Prof#=MDE S 033,Reach-1,6
Up Type=0
Dn Type=3
Dn Slope=0.009
Boundary for River Rch & Prof#=MDE S 033,Reach-1,7
Up Type=0
Dn Type=3
Dn Slope=0.009

--- MDE S 033.g01 (geometry) ---

Geom Title=Existing Conditions

River Reach=MDE S 033,Reach-1
Reach XY= 30
      2276779.00      7164810.00      2276977.40      7164863.85
      2277034.94      7164907.73      2277173.07      7164912.30
      2277239.71      7164959.18      2277339.05      7164921.11
      2277534.77      7165104.02      2277773.38      7165265.62
      2277875.45      7165411.47      2277881.30      7165554.07
      2277928.24      7165620.69      2277831.25      7165815.93
      2277823.52      7165962.44      2277631.06      7166215.86
      2277626.92      7166454.15      2277536.11      7166560.01
      2277621.40      7166663.35      2277482.08      7166768.30
      2277476.72      7166904.05      2277430.22      7166970.50
      2277430.05      7167449.56      2277575.36      7167661.66
      2277577.49      7167748.13      2277448.78      7167839.88
      2277389.10      7167949.61      2277280.22      7167963.53
      2277229.48      7168020.47      2277305.47      7168137.01
      2277465.54      7168246.69      2277479.00      7168310.00

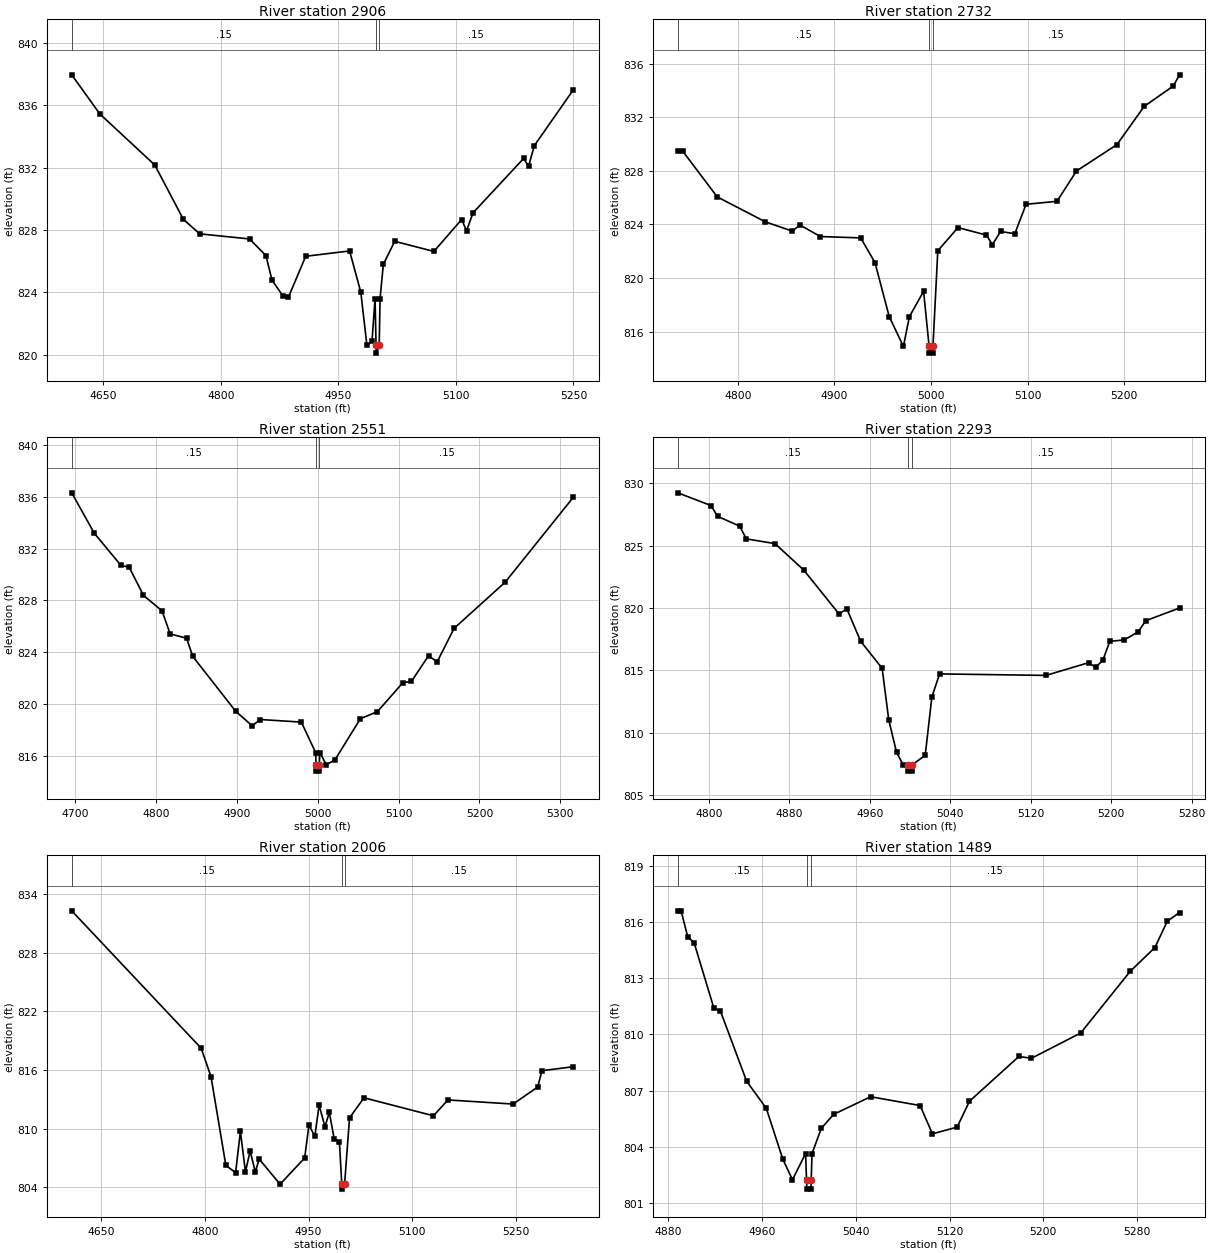
Type RM Length L Ch R = 1,2906,174,174,174
BEGIN DESCRIPTION:
MDE S 033 7.0
END DESCRIPTION:
XS GIS Cut Line= 3
      2277479.03      7165760.03      2277779.00      7166010.00
      2277979.02      7166160.02
#Sta/Elev= 30
  4609.5  837.96  4645.3  835.45  4715.5  832.17  4752.0  828.68  4772.8  827.75
  4836.6  827.42  4857.4  826.35  4865.2  824.77  4879.6  823.73  4886.1  823.68
  4908.2  826.31  4964.2  826.65  4978.5  824.01  4986.3  820.59  4992.8  820.84
  4996.7  823.59  4998.0  820.59  4998.3  820.09  5002.0  820.59  5003.1  823.59
  5007.3  825.79  5021.8  827.27  5071.8  826.62  5107.3  828.67  5113.5  827.95
  5121.8  829.10  5186.4  832.59  5192.7  832.09  5200.0  833.41  5250.0  837.01
#Mann=3,-1,0
  4609.5    0.15       0  4998.0    0.05       0  5002.0    0.15       0
Bank Sta=4998,5002
Exp/Cntr=0.3,0.1

Type RM Length L Ch R = 1,2732,181,181,181
BEGIN DESCRIPTION:
Mapping XS a0fcd0ad
END DESCRIPTION:
XS GIS Cut Line= 3
      2277475.50      7165997.84      2277772.02      7166211.45
      2277925.43      7166199.89
#Sta/Elev= 30
  4737.9  829.46  4743.1  829.46  4778.7  826.06  4828.5  824.20  4856.0  823.51
  4864.6  823.95  4885.5  823.10  4927.2  823.00  4942.0  821.15  4956.7  817.13
  4971.4  814.90  4977.6  817.12  4992.3  819.01  4998.0  814.90  4998.3  814.40
  5001.8  814.40  5002.0  814.90  5007.0  822.04  5027.9  823.77  5057.3  823.21
  5063.5  822.50  5072.0  823.48  5086.7  823.31  5098.4  825.51  5130.4  825.73
  5150.5  827.99  5192.4  829.96  5220.7  832.82  5250.7  834.33  5257.2  835.17
#Mann=3,-1,0
  4737.9    0.15       0  4998.0    0.05       0  5002.0    0.15       0
Bank Sta=4998,5002
Exp/Cntr=0.3,0.1

Type RM Length L Ch R = 1,2551,258,258,258
BEGIN DESCRIPTION:
MDE S 033 6.0
END DESCRIPTION:
XS GIS Cut Line= 3
      2277328.96      7166259.99      2277629.00      7166310.00
      2277928.99      7166210.00
#Sta/Elev= 30
  4695.9  836.30  4723.8  833.18  4756.8  830.70  4766.9  830.57  4784.6  828.39
  4807.5  827.20  4817.6  825.42  4837.9  825.09  4845.5  823.69  4898.7  819.45
  4919.0  818.34  4929.1  818.82  4979.8  818.62  4997.5  816.27  4998.0  815.34
  4998.3  814.84  5001.8  814.84  5002.0  815.34  5002.7  816.27  5010.6  815.34
  5021.2  815.69  5052.8  818.88  5073.9  819.43  5105.5  821.67  5116.0  821.76
  5137.1  823.74  5147.7  823.26  5168.7  825.85  5232.0  829.42  5316.3  835.97
#Mann=3,-1,0
  4695.9    0.15       0  4998.0    0.05       0  5002.0    0.15       0
Bank Sta=4998,5002
Exp/Cntr=0.3,0.1

Type RM Length L Ch R = 1,2293,287,287,287
BEGIN DESCRIPTION:
Mapping XS f6566284
END DESCRIPTION:
XS GIS Cut Line= 3
      2277400.92      7166361.88      2277577.70      7166568.74
      2277741.26      7166725.56
#Sta/Elev= 30
  4769.2  829.23  4802.2  828.21  4808.7  827.35  4830.7  826.56  4837.3  825.54
  4865.8  825.16  4894.4  823.04  4929.5  819.52  4937.2  819.94  4950.9  817.34
  4972.3  815.17  4978.9  811.02  4986.6  808.45  4993.2  807.43  4998.0  807.43
  4998.3  806.93  5001.8  806.93  5002.0  807.43  5015.1  808.19  5021.7  812.86
  5029.4  814.72  5135.1  814.60  5177.6  815.62  5184.5  815.24  5191.7  815.82
  5198.6  817.33  5212.8  817.44  5226.9  818.09  5234.2  818.98  5267.9  820.00
#Mann=3,-1,0
  4769.2    0.15       0  4998.0    0.05       0  5002.0    0.15       0
Bank Sta=4998,5002
Exp/Cntr=0.3,0.1

Type RM Length L Ch R = 1,2006,517,517,517
BEGIN DESCRIPTION:
Mapping XS f243fa57
END DESCRIPTION:
XS GIS Cut Line= 3
      2277280.09      7166454.20      2277465.68      7166653.38
      2277732.50      7167019.54
#Sta/Elev= 30
  4607.6  832.27  4794.7  818.22  4808.9  815.31  4830.4  806.23  4844.5  805.50
  4851.4  809.71  4858.7  805.58  4865.5  807.71  4872.9  805.57  4878.6  806.88
  4908.8  804.31  4944.3  807.00  4950.5  810.37  4959.0  809.21  4965.2  812.40
  4973.7  810.18  4979.9  811.67  4987.0  808.96  4994.5  808.67  4998.0  804.31
  4998.3  803.81  5002.0  804.31  5009.2  811.10  5030.1  813.15  5130.5  811.31
  5151.4  812.93  5245.6  812.51  5281.2  814.25  5287.3  815.92  5332.9  816.33
#Mann=3,-1,0
  4607.6    0.15       0  4998.0    0.05       0  5002.0    0.15       0
Bank Sta=4998,5002
Exp/Cntr=0.3,0.1

Type RM Length L Ch R = 1,1489,155,155,155
BEGIN DESCRIPTION:
MDE S 033 3.0
END DESCRIPTION:
XS GIS Cut Line= 3
      2277328.99      7167159.99      2277429.00      7167210.00
      2277728.96      7167110.01
#Sta/Elev= 30
  4888.2  816.59  4891.0  816.59  4896.6  815.22  4902.2  814.87  4919.0  811.39
  4924.5  811.25  4946.9  807.50  4963.7  806.05  4977.7  803.35  4986.0  802.24
  4997.2  803.64  4998.0  802.24  4998.3  801.74  5001.8  801.74  5002.0  802.24
  5002.7  803.64  5010.6  804.98  5021.1  805.73  5052.7  806.67  5094.9  806.20
  5105.4  804.69  5126.5  805.05  5137.0  806.43  5179.2  808.82  5189.8  808.72
  5231.9  810.07  5274.1  813.36  5295.2  814.63  5305.7  816.03  5316.2  816.50
#Mann=3,-1,0
  4888.2    0.15       0  4998.0    0.05       0  5002.0    0.15       0
Bank Sta=4998,5002
Exp/Cntr=0.3,0.1

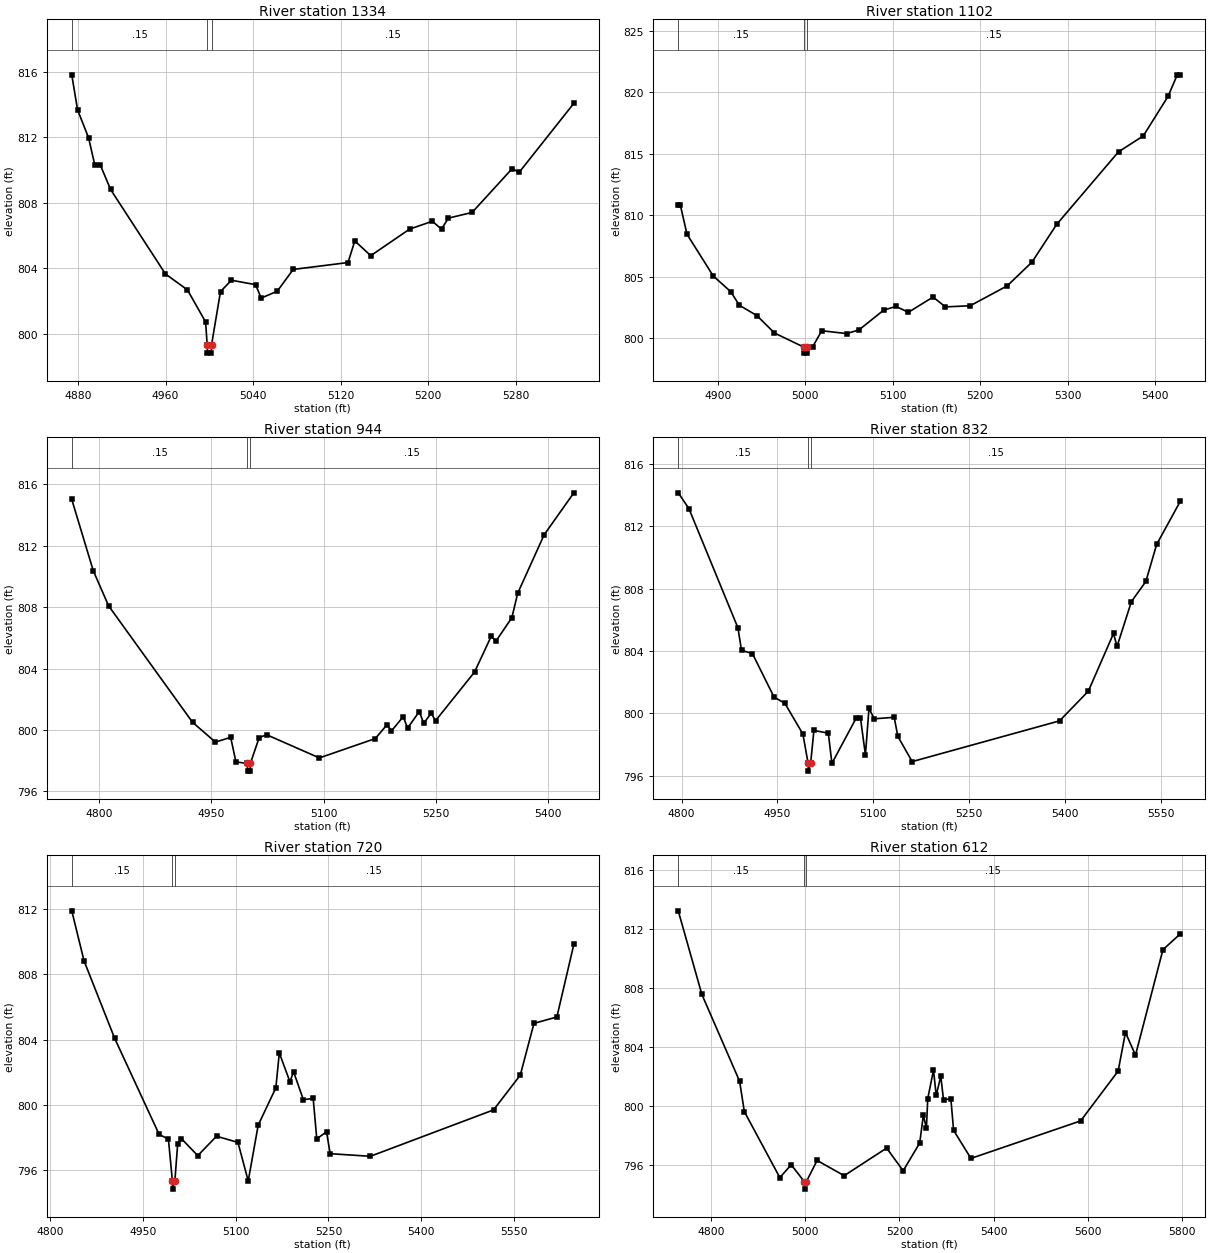
Type RM Length L Ch R = 1,1334,232,232,232
BEGIN DESCRIPTION:
Mapping XS f77f9d07
END DESCRIPTION:
XS GIS Cut Line= 3
      2277303.69      7167377.15      2277466.05      7167361.14
      2277703.71      7167184.76
#Sta/Elev= 30
  4874.2  815.82  4879.5  813.68  4889.6  811.97  4895.3  810.30  4900.4  810.30
  4909.7  808.82  4959.9  803.66  4980.0  802.69  4996.6  800.73  4998.0  799.33
  4998.3  798.83  5001.8  798.83  5002.0  799.33  5010.2  802.59  5020.2  803.28
  5042.3  803.01  5047.4  802.19  5062.1  802.61  5076.7  803.94  5126.8  804.36
  5133.0  805.68  5147.6  804.78  5183.1  806.40  5203.9  806.88  5212.3  806.40
  5218.5  807.07  5240.3  807.42  5277.0  810.10  5283.2  809.86  5333.3  814.08
#Mann=3,-1,0
  4874.2    0.15       0  4998.0    0.05       0  5002.0    0.15       0
Bank Sta=4998,5002
Exp/Cntr=0.3,0.1

Type RM Length L Ch R = 1,1102,158,158,158
BEGIN DESCRIPTION:
MDE S 033 2.0
END DESCRIPTION:
XS GIS Cut Line= 3
      2277378.96      7167560.00      2277529.00      7167560.00
      2277828.99      7167260.01
#Sta/Elev= 30
  4854.7  810.78  4857.2  810.78  4864.7  808.44  4894.7  805.05  4914.7  803.77
  4924.7  802.66  4944.7  801.82  4964.7  800.41  4998.0  799.27  4998.3  798.77
  5001.8  798.77  5002.0  799.27  5008.3  799.27  5018.9  800.59  5047.2  800.36
  5061.3  800.65  5089.6  802.26  5103.7  802.57  5117.9  802.09  5146.2  803.33
  5160.3  802.53  5188.6  802.62  5231.0  804.24  5259.3  806.17  5287.6  809.24
  5358.3  815.14  5386.6  816.43  5414.9  819.64  5425.5  821.40  5429.0  821.40
#Mann=3,-1,0
  4854.7    0.15       0  4998.0    0.05       0  5002.0    0.15       0
Bank Sta=4998,5002
Exp/Cntr=0.3,0.1

Type RM Length L Ch R = 1,944,112,112,112
BEGIN DESCRIPTION:
Mapping XS d771f015
END DESCRIPTION:
XS GIS Cut Line= 3
      2277350.74      7167660.82      2277576.99      7167706.91
      2277796.27      7167324.86
#Sta/Elev= 30
  4763.2  815.01  4792.0  810.36  4812.5  808.08  4924.7  800.50  4955.3  799.21
  4975.7  799.52  4982.7  797.92  4998.0  797.82  4998.3  797.32  5001.8  797.32
  5002.0  797.82  5013.8  799.50  5023.8  799.69  5094.3  798.18  5169.1  799.44
  5184.9  800.35  5190.6  799.93  5206.5  800.87  5212.2  800.12  5228.0  801.20
  5233.8  800.43  5243.8  801.09  5249.6  800.60  5301.8  803.77  5324.4  806.13
  5330.1  805.76  5351.7  807.31  5359.5  808.90  5394.9  812.71  5434.6  815.44
#Mann=3,-1,0
  4763.2    0.15       0  4998.0    0.05       0  5002.0    0.15       0
Bank Sta=4998,5002
Exp/Cntr=0.3,0.1

Type RM Length L Ch R = 1,832,112,112,112
BEGIN DESCRIPTION:
Mapping XS a1b5d084
END DESCRIPTION:
XS GIS Cut Line= 3
      2277333.93      7167682.61      2277587.11      7167803.61
      2277808.98      7167349.07
#Sta/Elev= 30
  4794.6  814.13  4811.3  813.12  4888.1  805.48  4893.7  804.04  4910.8  803.83
  4944.6  801.05  4961.7  800.64  4989.9  798.67  4998.0  796.80  4998.3  796.30
  5002.0  796.80  5007.1  798.91  5029.7  798.73  5035.3  796.80  5073.5  799.71
  5080.0  799.71  5087.8  797.34  5093.4  800.33  5101.5  799.65  5132.9  799.75
  5138.5  798.53  5161.0  796.91  5391.8  799.52  5436.9  801.42  5476.4  805.12
  5481.9  804.29  5504.4  807.16  5527.0  808.45  5543.9  810.82  5581.0  813.59
#Mann=3,-1,0
  4794.6    0.15       0  4998.0    0.05       0  5002.0    0.15       0
Bank Sta=4998,5002
Exp/Cntr=0.3,0.1

Type RM Length L Ch R = 1,720,108,108,108
BEGIN DESCRIPTION:
Mapping XS aaf1c3d8
END DESCRIPTION:
XS GIS Cut Line= 4
      2277348.01      7167713.61      2277461.93      7167882.21
      2277590.11      7167817.21      2277819.08      7167413.99
#Sta/Elev= 30
  4835.5  811.89  4855.3  808.83  4904.7  804.09  4976.6  798.20  4991.6  797.91
  4998.0  795.35  4998.3  794.85  5002.0  795.35  5006.5  797.59  5012.6  797.94
  5039.0  796.90  5069.3  798.09  5103.9  797.71  5120.5  795.35  5136.6  798.77
  5165.1  801.05  5170.7  803.19  5187.9  801.42  5193.7  802.04  5209.5  800.33
  5225.4  800.40  5231.2  797.93  5247.0  798.36  5252.8  797.02  5317.7  796.86
  5516.7  799.70  5559.9  801.83  5582.0  805.00  5619.0  805.39  5646.4  809.84
#Mann=3,-1,0
  4835.5    0.15       0  4998.0    0.05       0  5002.0    0.15       0
Bank Sta=4998,5002
Exp/Cntr=0.3,0.1

Type RM Length L Ch R = 1,612,0,0,0
BEGIN DESCRIPTION:
MDE S 033 1.0
END DESCRIPTION:
XS GIS Cut Line= 5
      2277329.00      7167709.95      2277344.87      7167925.24
      2277469.79      7167971.89      2277587.53      7167833.34
      2277863.82      7167374.67
#Sta/Elev= 30
  4730.0  813.24  4780.2  807.58  4860.4  801.70  4870.4  799.65  4945.8  795.18
  4970.0  796.05  4998.0  794.90  4998.3  794.40  5002.0  794.90  5025.0  796.34
  5082.5  795.31  5172.7  797.18  5207.8  795.64  5242.9  797.52  5250.7  799.40
  5257.2  798.52  5260.0  800.53  5272.2  802.45  5278.0  800.75  5287.7  802.04
  5293.5  800.45  5309.1  800.52  5314.9  798.38  5351.8  796.48  5584.8  799.02
  5664.4  802.39  5680.0  805.00  5701.3  803.47  5759.6  810.61  5796.5  811.68
#Mann=3,-1,0
  4730.0    0.15       0  4998.0    0.05       0  5002.0    0.15       0
Bank Sta=4998,5002
Exp/Cntr=0.3,0.1

Chan Stop Cuts=-1