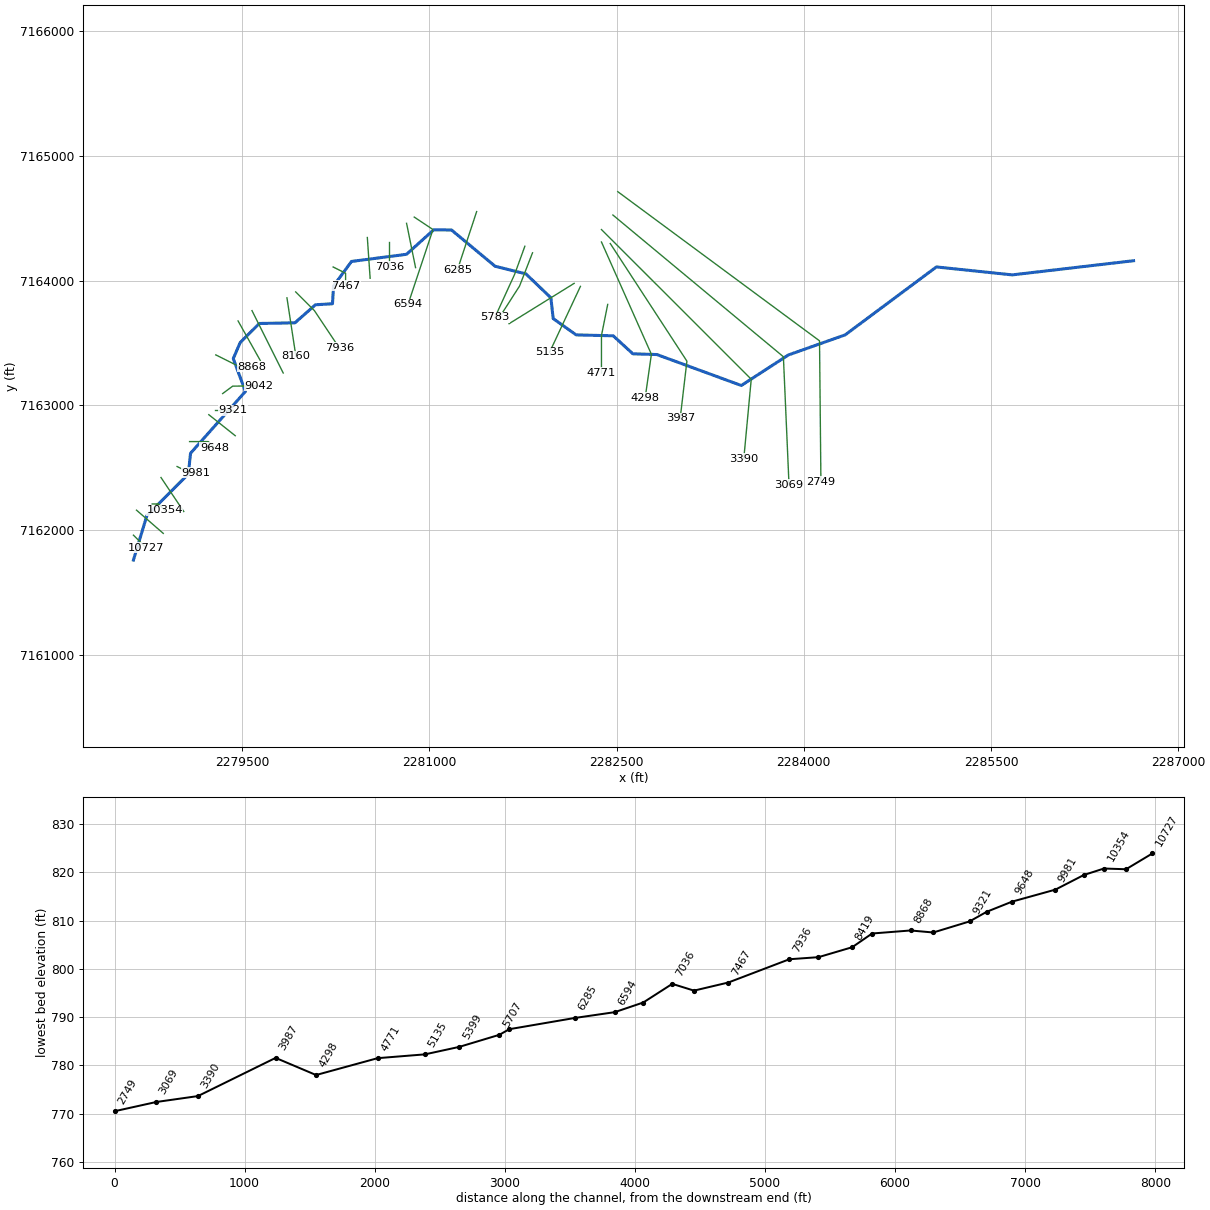
--- MDE S 034.prj (project) ---

Proj Title=MDE S 034 Base Level Engineering
Current Plan=p01
Default Exp/Contr=0.3,0.1
English Units
Geom File=g01
Flow File=f01
Plan File=p01
BEGIN DESCRIPTION:
MDE S 034
END DESCRIPTION:

--- MDE S 034.p01 (plan) ---

Plan Title=Multiple Run
Short Identifier=Multiple
Geom File=g01
Flow File=f01
Subcritical Flow
K Sum by GR= 0
Std Step Tol= 0.01
Critical Tol= 0.01
Num of Std Step Trials= 20
Max Error Tol= 0.3
Flow Tol Ratio= 0.001
Split Flow NTrial= 30
Split Flow Tol= 0.02
Split Flow Ratio= 0.02
Log Output Level= 0
Friction Slope Method= 1
Unsteady Friction Slope Method= 2
Unsteady Bridges Friction Slope Method= 1
Parabolic Critical Depth
Global Vel Dist=  1 , 1 , 1
Global Log Level= 0
CheckData=True
Encroach Param= -1, 0, 0, 0
BEGIN DESCRIPTION:
Multiple Run
END DESCRIPTION:

--- MDE S 034.f01 (steady flow) ---

Flow Title=Multiple
Number of Profiles=7
Profile Names=10-year,25-year,50-year,1pct_min,100-year,1pct_plu,500-year
River Rch & RM= MDE S 034,Reach-1,10727
     836    1177    1466     908    1812    3615    2770
River Rch & RM= MDE S 034,Reach-1,8868
    1173    1674    2104    1311    2616    5220    4057
Boundary for River Rch & Prof#=MDE S 034,Reach-1,1
Up Type=0
Dn Type=3
Dn Slope=0.005
Boundary for River Rch & Prof#=MDE S 034,Reach-1,2
Up Type=0
Dn Type=3
Dn Slope=0.005
Boundary for River Rch & Prof#=MDE S 034,Reach-1,3
Up Type=0
Dn Type=3
Dn Slope=0.005
Boundary for River Rch & Prof#=MDE S 034,Reach-1,4
Up Type=0
Dn Type=3
Dn Slope=0.005
Boundary for River Rch & Prof#=MDE S 034,Reach-1,5
Up Type=0
Dn Type=3
Dn Slope=0.005
Boundary for River Rch & Prof#=MDE S 034,Reach-1,6
Up Type=0
Dn Type=3
Dn Slope=0.005
Boundary for River Rch & Prof#=MDE S 034,Reach-1,7
Up Type=0
Dn Type=3
Dn Slope=0.005

--- MDE S 034.g01 (geometry) ---

Geom Title=Existing Conditions

River Reach=MDE S 034,Reach-1
Reach XY= 30
      2278629.00      7161760.00      2278736.74      7162116.46
      2279068.65      7162449.88      2279086.70      7162616.47
      2279525.96      7163111.42      2279429.08      7163375.40
      2279484.59      7163504.39      2279637.30      7163656.93
      2279923.07      7163662.24      2280087.32      7163806.89
      2280223.98      7163815.01      2280232.56      7163958.52
      2280376.45      7164154.27      2280817.17      7164211.64
      2281034.86      7164407.95      2281177.53      7164406.46
      2281526.70      7164115.83      2281773.56      7164054.81
      2281973.64      7163862.70      2281992.21      7163696.27
      2282176.32      7163565.40      2282473.32      7163558.00
      2282630.52      7163413.74      2282823.07      7163407.76
      2283499.40      7163159.68      2283876.57      7163404.48
      2284331.43      7163565.52      2285062.45      7164110.24
      2285670.51      7164046.58      2286642.22      7164160.12

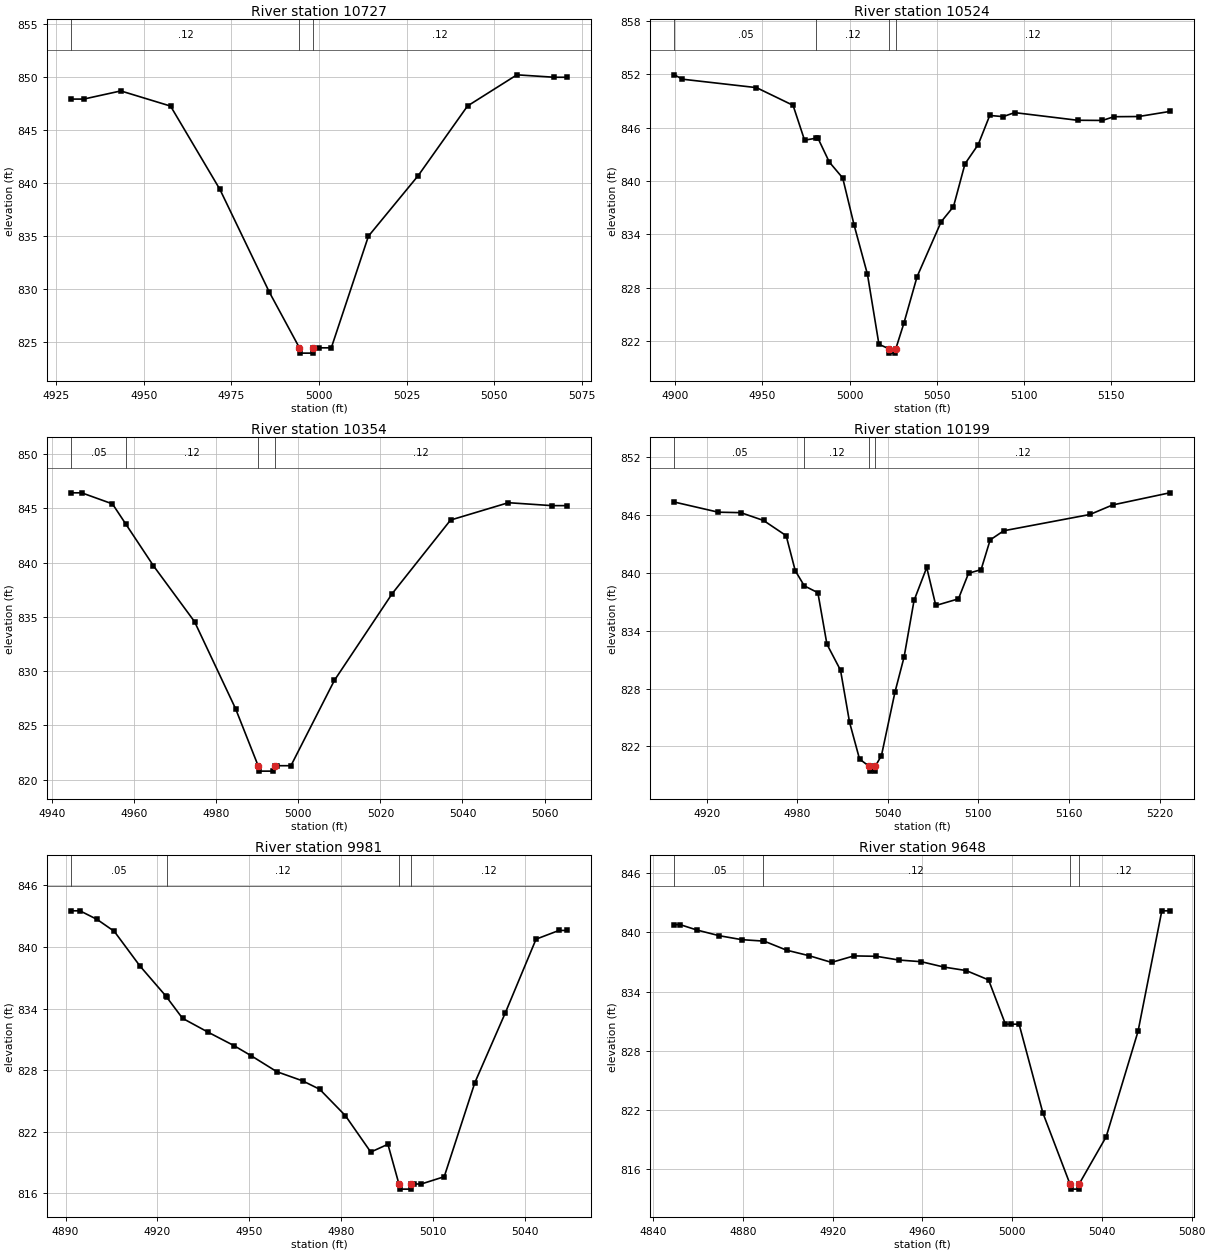
Type RM Length L Ch R = 1,10727,203,203,203
BEGIN DESCRIPTION:
MDE S 034 18.0
END DESCRIPTION:
XS GIS Cut Line= 3
      2278629.02      7161959.98      2278679.00      7161910.00
      2278729.01      7161859.99
#Sta/Elev= 18
  4929.3  847.89  4932.8  847.89  4943.4  848.66  4957.6  847.23  4971.7  839.36
  4985.8  829.67  4994.4  824.41  4994.7  823.91  4998.2  823.91  4998.4  824.41
  5000.0  824.41  5003.5  824.41  5014.1  834.95  5028.3  840.66  5042.4  847.24
  5056.5  850.18  5067.2  849.95  5070.7  849.95
#Mann=3,-1,0
  4929.3    0.12       0  4994.4    0.07       0  4998.4    0.12       0
Bank Sta=4994.4,4998.4
Exp/Cntr=0.3,0.1

Type RM Length L Ch R = 1,10524,170,170,170
BEGIN DESCRIPTION:
Mapping XS 3e34f28b
END DESCRIPTION:
XS GIS Cut Line= 2
      2278653.44      7162160.36      2278868.09      7161973.93
#Sta/Elev= 30
  4899.5  851.93  4904.0  851.44  4946.6  850.49  4967.6  848.50  4974.2  844.58
  4981.0  844.81  4981.8  844.84  4988.4  842.12  4996.1  840.33  5002.7  834.99
  5010.3  829.50  5016.9  821.62  5022.6  821.13  5022.8  820.63  5026.3  820.63
  5026.6  821.13  5031.2  823.98  5038.8  829.23  5052.6  835.40  5059.7  837.11
  5066.3  841.92  5073.9  844.09  5080.5  847.36  5088.2  847.23  5094.8  847.68
  5130.9  846.82  5145.2  846.80  5151.8  847.22  5166.0  847.24  5183.8  847.81
#Mann=4,-1,0
  4899.5    0.05       0  4981.0    0.12       0  5022.6    0.07       0
  5026.6    0.12       0
Bank Sta=5022.6,5026.6
Exp/Cntr=0.3,0.1

Type RM Length L Ch R = 1,10354,155,155,155
BEGIN DESCRIPTION:
MDE S 034 17.0
END DESCRIPTION:
XS GIS Cut Line= 3
      2278779.04      7162210.00      2278829.00      7162210.00
      2278879.02      7162159.98
#Sta/Elev= 19
  4944.7  846.43  4947.2  846.43  4954.7  845.41  4957.9  843.58  4964.7  839.70
  4974.7  834.56  4984.7  826.54  4990.2  821.28  4990.4  820.78  4993.9  820.78
  4994.2  821.28  4994.7  821.28  4998.2  821.28  5008.8  829.15  5022.9  837.15
  5037.1  843.92  5051.2  845.52  5061.8  845.25  5065.4  845.25
#Mann=4,-1,0
  4944.7    0.05       0  4957.9    0.12       0  4990.2    0.07       0
  4994.2    0.12       0
Bank Sta=4990.2,4994.2
Exp/Cntr=0.3,0.1

Type RM Length L Ch R = 1,10199,218,218,218
BEGIN DESCRIPTION:
Mapping XS 005961f5
END DESCRIPTION:
XS GIS Cut Line= 2
      2278849.84      7162421.96      2279032.14      7162149.29
#Sta/Elev= 30
  4898.7  847.37  4927.7  846.32  4942.7  846.27  4957.7  845.46  4972.7  843.88
  4978.7  840.25  4984.7  838.67  4993.7  837.96  4999.7  832.61  5008.7  829.91
  5014.7  824.49  5021.3  820.68  5027.7  819.93  5028.0  819.43  5031.5  819.43
  5031.7  819.93  5035.8  821.04  5044.8  827.66  5050.8  831.28  5057.4  837.15
  5065.8  840.58  5071.8  836.63  5086.8  837.32  5093.5  839.98  5101.8  840.35
  5107.8  843.44  5116.8  844.39  5173.9  846.08  5188.9  847.07  5226.7  848.33
#Mann=4,-1,0
  4898.7    0.05       0  4984.7    0.12       0  5027.7    0.07       0
  5031.7    0.12       0
Bank Sta=5027.7,5031.7
Exp/Cntr=0.3,0.1

Type RM Length L Ch R = 1,9981,333,333,333
BEGIN DESCRIPTION:
MDE S 034 16.0
END DESCRIPTION:
XS GIS Cut Line= 3
      2278978.99      7162510.00      2279079.00      7162460.00
      2279128.99      7162460.00
#Sta/Elev= 29
  4891.9  843.52  4894.7  843.52  4900.3  842.68  4905.9  841.52  4914.3  838.14
  4922.7  835.24  4923.0  835.12  4928.2  833.05  4936.6  831.69  4945.0  830.39
  4950.6  829.41  4959.0  827.85  4967.4  826.96  4973.0  826.14  4981.4  823.57
  4989.7  820.02  4995.3  820.78  4998.9  816.91  4999.2  816.41  5002.7  816.41
  5002.9  816.91  5003.7  816.91  5006.2  816.91  5013.7  817.62  5023.7  826.78
  5033.7  833.61  5043.7  840.76  5051.2  841.61  5053.7  841.61
#Mann=4,-1,0
  4891.9    0.05       0  4923.0    0.12       0  4998.9    0.07       0
  5002.9    0.12       0
Bank Sta=4998.9,5002.9
Exp/Cntr=0.3,0.1

Type RM Length L Ch R = 1,9648,195,195,195
BEGIN DESCRIPTION:
MDE S 034 15.0
END DESCRIPTION:
XS GIS Cut Line= 3
      2279078.98      7162710.00      2279229.00      7162710.00
      2279278.98      7162660.02
#Sta/Elev= 29
  4849.5  840.80  4852.0  840.80  4859.5  840.25  4869.5  839.67  4879.5  839.27
  4888.8  839.13  4889.5  839.12  4899.5  838.20  4909.5  837.64  4919.5  836.96
  4929.5  837.62  4939.5  837.58  4949.5  837.20  4959.5  837.03  4969.5  836.49
  4979.5  836.13  4989.5  835.18  4997.0  830.68  4999.5  830.68  5003.1  830.68
  5013.7  821.66  5025.8  814.42  5026.1  813.92  5029.6  813.92  5029.8  814.42
  5041.9  819.24  5056.1  829.95  5066.7  842.20  5070.2  842.20
#Mann=4,-1,0
  4849.5    0.05       0  4888.8    0.12       0  5025.8    0.07       0
  5029.8    0.12       0
Bank Sta=5025.8,5029.8
Exp/Cntr=0.3,0.1

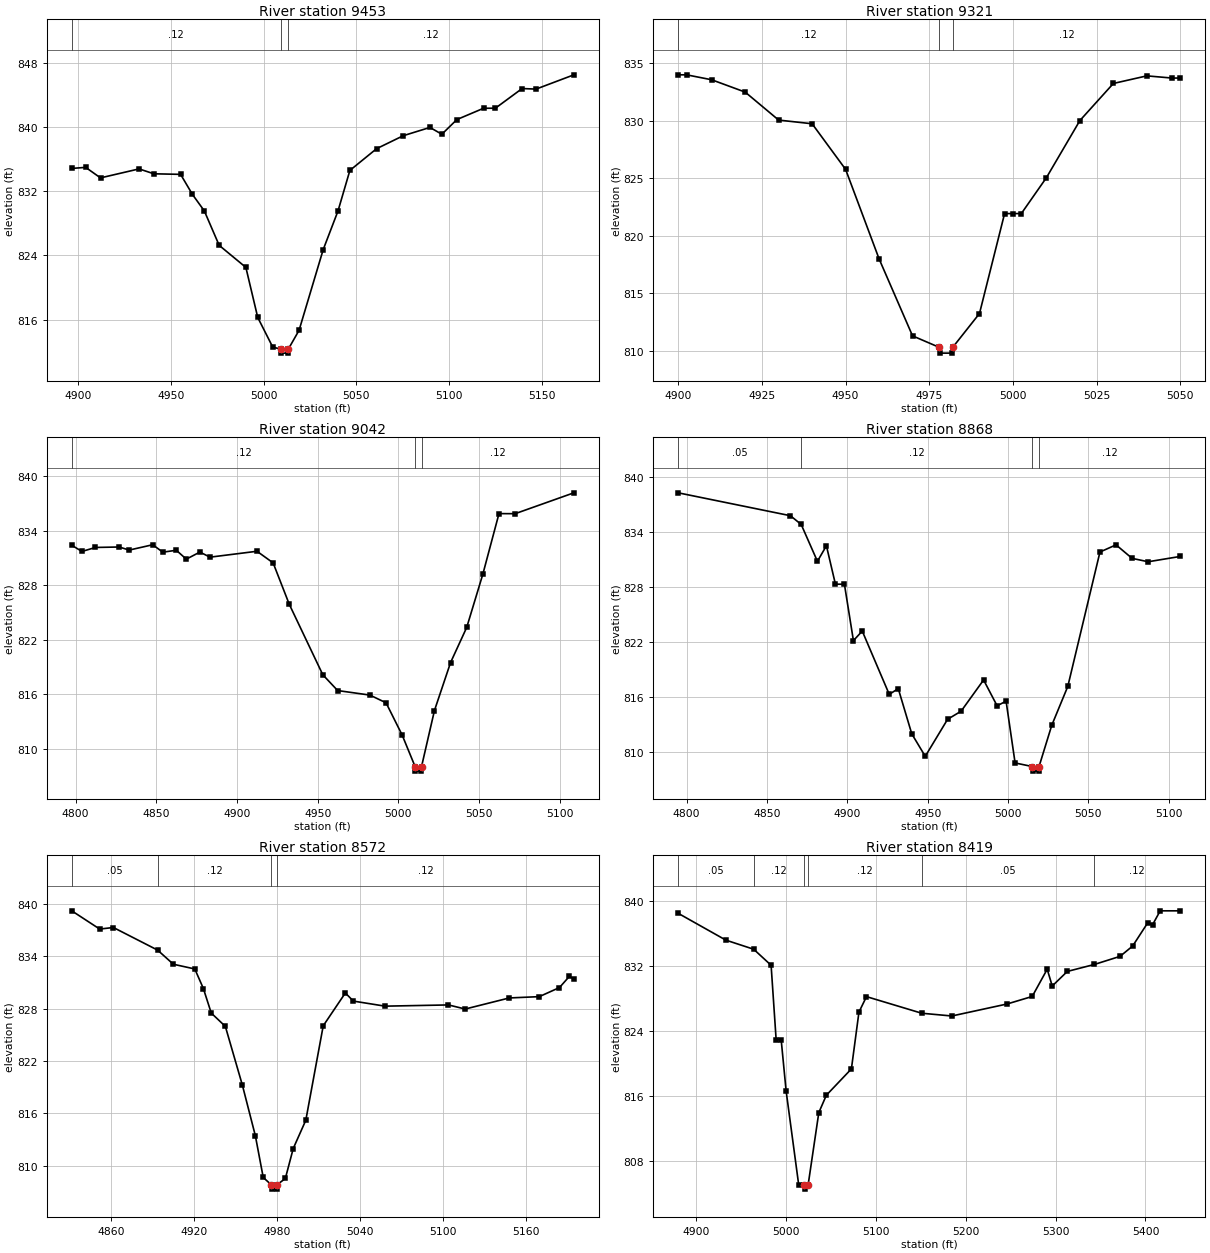
Type RM Length L Ch R = 1,9453,132,132,132
BEGIN DESCRIPTION:
Mapping XS 9f212482
END DESCRIPTION:
XS GIS Cut Line= 2
      2279233.10      7162925.58      2279444.96      7162756.92
#Sta/Elev= 30
  4896.5  834.85  4904.0  834.98  4912.0  833.67  4932.8  834.79  4940.8  834.18
  4955.2  834.11  4961.6  831.60  4968.0  829.55  4976.0  825.26  4990.4  822.51
  4996.8  816.27  5004.9  812.57  5009.3  812.32  5009.5  811.82  5013.0  811.82
  5013.3  812.32  5019.1  814.67  5032.1  824.72  5040.1  829.55  5046.5  834.60
  5060.9  837.31  5075.3  838.93  5089.7  839.96  5096.1  839.11  5104.2  840.94
  5118.6  842.35  5125.0  842.36  5139.4  844.81  5146.9  844.74  5167.3  846.52
#Mann=3,-1,0
  4896.5    0.12       0  5009.3    0.07       0  5013.3    0.12       0
Bank Sta=5009.3,5013.3
Exp/Cntr=0.3,0.1

Type RM Length L Ch R = 1,9321,279,279,279
BEGIN DESCRIPTION:
MDE S 034 14.0
END DESCRIPTION:
XS GIS Cut Line= 3
      2279278.98      7162960.00      2279379.00      7162960.00
      2279428.98      7162960.00
#Sta/Elev= 23
  4900.0  833.99  4902.5  833.99  4910.0  833.56  4920.0  832.49  4930.0  830.06
  4940.0  829.74  4950.0  825.78  4960.0  818.01  4970.0  811.32  4978.0  810.32
  4978.3  809.82  4981.8  809.82  4982.0  810.32  4990.0  813.26  4997.5  821.94
  5000.0  821.94  5002.5  821.94  5010.0  825.06  5020.0  830.02  5030.0  833.24
  5040.0  833.90  5047.5  833.71  5050.0  833.71
#Mann=3,-1,0
  4900.0    0.12       0  4978.0    0.07       0  4982.0    0.12       0
Bank Sta=4978,4982
Exp/Cntr=0.3,0.1

Type RM Length L Ch R = 1,9042,174,174,174
BEGIN DESCRIPTION:
Mapping XS 03255561
END DESCRIPTION:
XS GIS Cut Line= 3
      2279343.94      7163094.91      2279424.29      7163154.50
      2279635.44      7163156.55
#Sta/Elev= 30
  4797.6  832.42  4803.9  831.74  4812.3  832.18  4827.0  832.23  4833.2  831.89
  4847.8  832.48  4854.0  831.66  4862.4  831.87  4868.6  830.89  4877.0  831.67
  4883.3  831.11  4912.4  831.76  4922.4  830.48  4932.4  825.92  4953.2  818.15
  4962.4  816.41  4982.4  815.91  4992.4  815.06  5002.4  811.50  5010.4  808.03
  5010.6  807.53  5014.1  807.53  5014.4  808.03  5022.4  814.21  5032.4  819.50
  5042.4  823.37  5052.4  829.24  5062.4  835.91  5072.4  835.90  5108.8  838.20
#Mann=3,-1,0
  4797.6    0.12       0  5010.4    0.07       0  5014.4    0.12       0
Bank Sta=5010.4,5014.4
Exp/Cntr=0.3,0.1

Type RM Length L Ch R = 1,8868,296,296,296
BEGIN DESCRIPTION:
MDE S 034 13.0
END DESCRIPTION:
XS GIS Cut Line= 4
      2279289.05      7163404.97      2279379.00      7163360.00
      2279479.00      7163310.00      2279579.03      7163310.00
#Sta/Elev= 30
  4794.8  838.23  4864.6  835.74  4871.3  834.79  4881.4  830.78  4887.0  832.47
  4892.6  828.29  4898.2  828.29  4903.8  822.15  4909.3  823.19  4926.1  816.30
  4931.7  816.93  4940.1  812.01  4948.5  809.56  4962.4  813.59  4970.8  814.47
  4984.8  817.87  4993.2  815.06  4998.8  815.56  5004.4  808.84  5015.1  808.45
  5015.4  807.95  5019.0  807.95  5019.3  808.45  5027.2  812.93  5037.2  817.17
  5057.2  831.79  5067.2  832.57  5077.2  831.10  5087.2  830.73  5107.2  831.31
#Mann=4,-1,0
  4794.8    0.05       0  4871.3    0.12       0  5015.1    0.07       0
  5019.3    0.12       0
Bank Sta=5015.1,5019.3
Exp/Cntr=0.3,0.1

Type RM Length L Ch R = 1,8572,153,153,153
BEGIN DESCRIPTION:
Mapping XS 52a6509f
END DESCRIPTION:
XS GIS Cut Line= 2
      2279467.24      7163677.66      2279644.93      7163360.89
#Sta/Elev= 30
  4831.4  839.20  4851.6  837.11  4861.5  837.29  4893.5  834.70  4904.9  833.08
  4920.4  832.54  4926.6  830.30  4932.3  827.49  4942.5  825.96  4954.8  819.24
  4964.2  813.44  4969.9  808.66  4975.7  807.82  4976.0  807.32  4979.6  807.32
  4979.9  807.82  4985.9  808.54  4991.6  811.97  5000.7  815.21  5013.3  826.03
  5029.3  829.79  5035.1  828.86  5058.0  828.28  5103.9  828.42  5116.0  827.95
  5147.9  829.22  5169.6  829.37  5184.2  830.41  5191.3  831.68  5194.6  831.42
#Mann=4,-1,0
  4831.4    0.05       0  4893.5    0.12       0  4975.7    0.07       0
  4979.9    0.12       0
Bank Sta=4975.7,4979.9
Exp/Cntr=0.3,0.1

Type RM Length L Ch R = 1,8419,259,259,259
BEGIN DESCRIPTION:
MDE S 034 12.0
END DESCRIPTION:
XS GIS Cut Line= 3
      2279579.02      7163759.96      2279629.00      7163660.00
      2279829.01      7163259.97
#Sta/Elev= 30
  4879.8  838.52  4932.9  835.21  4963.8  834.09  4983.2  832.11  4988.8  822.93
  4994.4  822.93  4999.9  816.61  5013.9  805.03  5020.2  804.98  5020.5  804.48
  5024.4  804.98  5036.3  813.92  5044.7  816.07  5072.6  819.32  5081.0  826.33
  5089.4  828.24  5150.9  826.19  5184.4  825.85  5245.9  827.33  5273.9  828.26
  5290.6  831.62  5296.2  829.55  5313.0  831.35  5343.1  832.21  5371.7  833.21
  5385.7  834.48  5402.4  837.33  5408.0  837.13  5416.4  838.83  5438.8  838.83
#Mann=6,-1,0
  4879.8    0.05       0  4963.8    0.12       0  5020.2    0.07       0
  5024.4    0.12       0  5150.9    0.05       0  5343.1    0.12       0
Bank Sta=5020.2,5024.4
Exp/Cntr=0.3,0.1

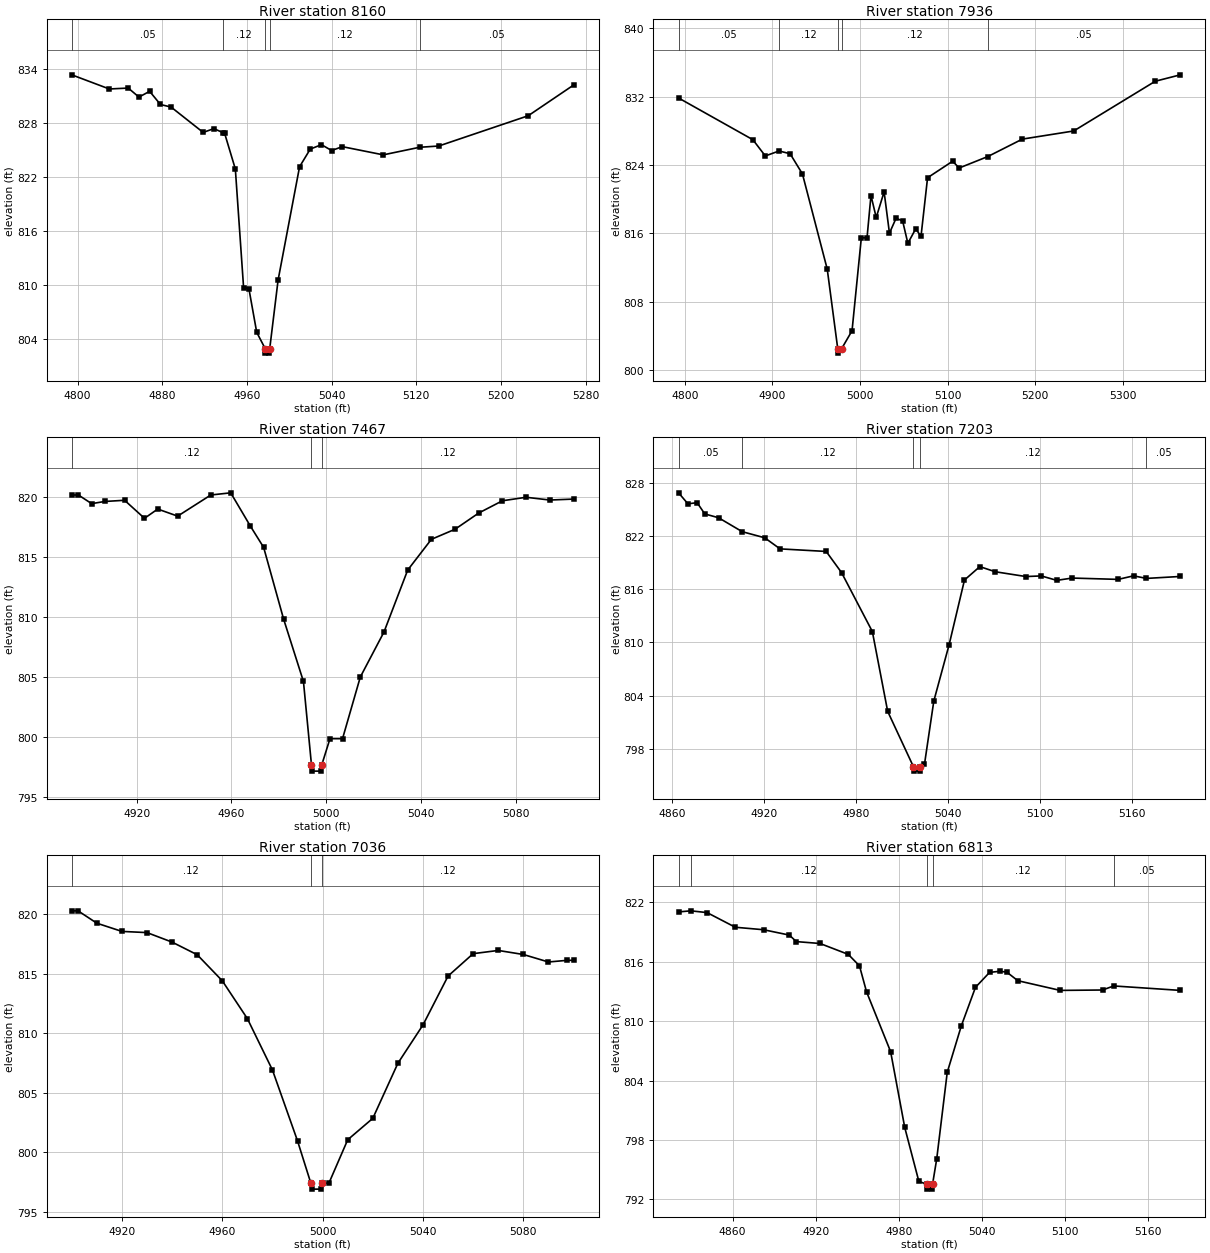
Type RM Length L Ch R = 1,8160,224,224,224
BEGIN DESCRIPTION:
Mapping XS 7552e745
END DESCRIPTION:
XS GIS Cut Line= 2
      2279859.06      7163862.80      2279930.67      7163394.04
#Sta/Elev= 30
  4794.4  833.30  4829.9  831.73  4847.8  831.83  4857.9  830.83  4868.0  831.47
  4878.2  830.01  4888.3  829.72  4918.6  826.91  4928.7  827.33  4937.6  826.87
  4938.9  826.80  4949.0  822.85  4956.8  809.69  4961.8  809.58  4969.2  804.73
  4977.2  802.92  4977.5  802.42  4981.1  802.42  4981.5  802.92  4989.4  810.52
  5009.7  823.10  5019.8  825.06  5030.4  825.55  5040.0  824.90  5050.1  825.33
  5088.8  824.42  5123.1  825.26  5141.2  825.40  5225.8  828.76  5268.6  832.16
#Mann=5,-1,0
  4794.4    0.05       0  4937.6    0.12       0  4977.2    0.07       0
  4981.5    0.12       0  5123.1    0.05       0
Bank Sta=4977.2,4981.5
Exp/Cntr=0.3,0.1

Type RM Length L Ch R = 1,7936,469,469,469
BEGIN DESCRIPTION:
MDE S 034 11.0
END DESCRIPTION:
XS GIS Cut Line= 3
      2279929.02      7163909.98      2280079.00      7163760.00
      2280279.02      7163459.97
#Sta/Elev= 30
  4792.9  831.84  4877.7  826.96  4891.9  825.06  4907.6  825.64  4920.2  825.32
  4934.3  822.95  4962.6  811.81  4974.6  802.49  4974.9  801.99  4978.9  802.49
  4990.9  804.61  5001.5  815.48  5008.0  815.48  5012.5  820.43  5018.5  817.86
  5027.5  820.86  5033.6  816.03  5041.1  817.76  5048.6  817.47  5054.6  814.84
  5063.6  816.54  5069.6  815.64  5077.1  822.51  5105.7  824.44  5113.2  823.65
  5145.9  824.99  5185.3  827.03  5243.9  827.98  5337.0  833.80  5365.6  834.55
#Mann=5,-1,0
  4792.9    0.05       0  4907.6    0.12       0  4974.6    0.07       0
  4978.9    0.12       0  5145.9    0.05       0
Bank Sta=4974.6,4978.9
Exp/Cntr=0.3,0.1

Type RM Length L Ch R = 1,7467,264,264,264
BEGIN DESCRIPTION:
MDE S 034 10.0
END DESCRIPTION:
XS GIS Cut Line= 3
      2280229.03      7164109.99      2280329.00      7164060.00
      2280329.00      7163959.97
#Sta/Elev= 30
  4892.6  820.15  4895.4  820.15  4901.0  819.43  4906.5  819.61  4914.9  819.71
  4923.3  818.21  4928.9  818.98  4937.3  818.39  4951.3  820.15  4959.7  820.33
  4968.0  817.56  4973.6  815.79  4982.0  809.84  4990.4  804.63  4993.8  797.67
  4994.2  797.17  4997.8  797.17  4998.1  797.67  5001.6  799.87  5006.9  799.87
  5014.4  805.00  5024.4  808.75  5034.4  813.90  5044.4  816.46  5054.4  817.30
  5064.4  818.65  5074.4  819.67  5084.4  819.96  5094.4  819.73  5104.4  819.81
#Mann=3,-1,0
  4892.6    0.12       0  4993.8    0.07       0  4998.1    0.12       0
Bank Sta=4993.8,4998.1
Exp/Cntr=0.3,0.1

Type RM Length L Ch R = 1,7203,167,167,167
BEGIN DESCRIPTION:
Mapping XS 3832dd8d
END DESCRIPTION:
XS GIS Cut Line= 2
      2280503.11      7164346.08      2280525.48      7164019.54
#Sta/Elev= 30
  4864.0  826.87  4870.1  825.63  4876.1  825.76  4881.1  824.49  4890.1  824.06
  4905.5  822.49  4920.2  821.80  4930.2  820.55  4960.3  820.26  4970.3  817.88
  4990.4  811.23  5000.4  802.23  5017.2  795.99  5017.6  795.49  5021.2  795.49
  5021.5  795.99  5024.4  796.25  5030.5  803.40  5040.5  809.76  5050.5  817.04
  5060.5  818.55  5070.6  817.97  5090.6  817.43  5100.6  817.50  5110.7  817.00
  5120.7  817.26  5150.7  817.11  5160.8  817.51  5169.2  817.22  5191.3  817.44
#Mann=5,-1,0
  4864.0    0.05       0  4905.5    0.12       0  5017.2    0.07       0
  5021.5    0.12       0  5169.2    0.05       0
Bank Sta=5017.2,5021.5
Exp/Cntr=0.3,0.1

Type RM Length L Ch R = 1,7036,223,223,223
BEGIN DESCRIPTION:
MDE S 034 9.0
END DESCRIPTION:
XS GIS Cut Line= 3
      2280679.00      7164309.96      2280679.00      7164210.00
      2280679.00      7164109.96
#Sta/Elev= 28
  4900.0  820.28  4902.5  820.28  4910.0  819.24  4920.0  818.55  4930.0  818.45
  4940.0  817.65  4950.0  816.59  4960.0  814.40  4970.0  811.22  4980.0  806.90
  4990.0  800.94  4995.3  797.39  4995.7  796.89  4999.3  796.89  4999.6  797.39
  5000.0  797.39  5002.5  797.39  5010.0  801.04  5020.0  802.84  5030.0  807.47
  5040.0  810.69  5050.0  814.80  5060.0  816.68  5070.0  816.95  5080.0  816.61
  5090.0  815.98  5097.5  816.12  5100.0  816.12
#Mann=3,-1,0
  4900.0    0.12       0  4995.3    0.07       0  4999.6    0.12       0
Bank Sta=4995.3,4999.6
Exp/Cntr=0.3,0.1

Type RM Length L Ch R = 1,6813,219,219,219
BEGIN DESCRIPTION:
Mapping XS e8f6008b
END DESCRIPTION:
XS GIS Cut Line= 2
      2280817.46      7164460.19      2280889.46      7164104.91
#Sta/Elev= 30
  4821.0  821.04  4829.9  821.15  4841.6  820.97  4862.0  819.49  4882.4  819.24
  4901.0  818.70  4906.1  818.04  4923.2  817.85  4943.6  816.75  4951.7  815.59
  4956.8  812.97  4974.2  806.92  4984.4  799.26  4994.6  793.81  5000.2  793.53
  5000.6  793.03  5004.2  793.03  5004.5  793.53  5007.5  796.08  5015.1  804.83
  5025.3  809.54  5035.5  813.42  5045.7  814.93  5053.0  815.04  5058.1  814.96
  5066.1  814.09  5096.7  813.11  5127.3  813.15  5135.4  813.56  5183.5  813.11
#Mann=5,-1,0
  4821.0    0.05       0  4829.9    0.12       0  5000.2    0.07       0
  5004.5    0.12       0  5135.4    0.05       0
Bank Sta=5000.2,5004.5
Exp/Cntr=0.3,0.1

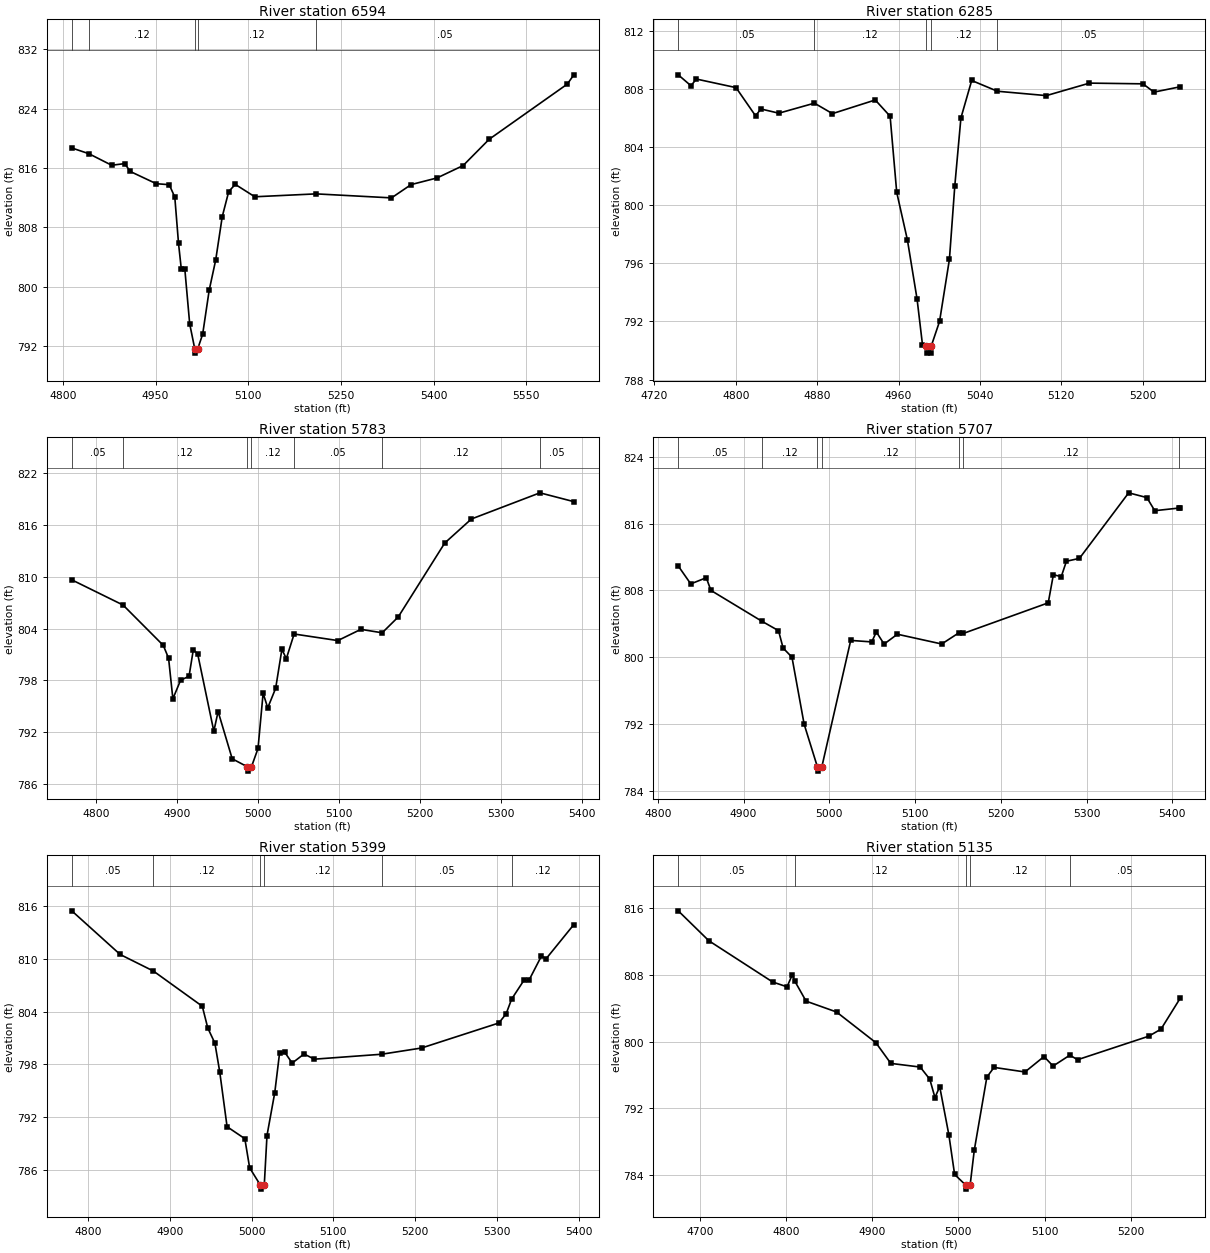
Type RM Length L Ch R = 1,6594,309,309,309
BEGIN DESCRIPTION:
MDE S 034 8.0
END DESCRIPTION:
XS GIS Cut Line= 3
      2280878.96      7164510.03      2281029.00      7164410.00
      2280828.99      7163809.98
#Sta/Elev= 30
  4814.3  818.69  4841.9  817.92  4878.9  816.36  4900.0  816.58  4909.0  815.52
  4951.1  813.87  4972.1  813.74  4981.1  812.06  4987.1  805.84  4991.6  802.37
  4997.3  802.37  5005.2  794.98  5013.6  791.53  5013.9  791.03  5017.9  791.53
  5026.2  793.58  5036.8  799.53  5047.3  803.58  5057.9  809.43  5068.4  812.82
  5079.0  813.78  5110.6  812.11  5209.9  812.50  5331.9  811.96  5363.6  813.75
  5405.7  814.65  5447.9  816.32  5490.0  819.86  5616.5  827.30  5627.1  828.55
#Mann=5,-1,0
  4814.3    0.05       0  4841.9    0.12       0  5013.6    0.07       0
  5017.9    0.12       0  5209.9    0.05       0
Bank Sta=5013.6,5017.9
Exp/Cntr=0.3,0.1

Type RM Length L Ch R = 1,6285,502,502,502
BEGIN DESCRIPTION:
Mapping XS 5b3f5cf6
END DESCRIPTION:
XS GIS Cut Line= 2
      2281378.87      7164553.95      2281224.32      7164085.17
#Sta/Elev= 30
  4743.4  808.97  4755.9  808.22  4761.2  808.68  4800.2  808.09  4819.4  806.15
  4824.7  806.62  4842.3  806.33  4877.3  807.02  4895.0  806.30  4937.1  807.24
  4951.7  806.12  4958.2  800.88  4968.7  797.61  4978.2  793.54  4983.5  790.41
  4987.2  790.32  4987.9  789.82  4991.6  789.82  4992.2  790.32  5000.3  792.00
  5010.0  796.27  5015.3  801.34  5021.3  806.00  5031.9  808.58  5057.2  807.84
  5105.3  807.54  5147.7  808.40  5200.3  808.35  5211.1  807.78  5237.0  808.15
#Mann=5,-1,0
  4743.4    0.05       0  4877.3    0.12       0  4987.2    0.07       0
  4992.2    0.12       0  5057.2    0.05       0
Bank Sta=4987.2,4992.2
Exp/Cntr=0.3,0.1

Type RM Length L Ch R = 1,5783,76,76,76
BEGIN DESCRIPTION:
Mapping XS f6647df0
END DESCRIPTION:
XS GIS Cut Line= 3
      2281765.25      7164276.28      2281684.22      7164053.24
      2281525.02      7163704.89
#Sta/Elev= 30
  4769.7  809.64  4833.1  806.72  4882.8  802.05  4889.3  800.57  4894.6  795.87
  4904.1  798.01  4914.6  798.49  4919.9  801.57  4925.3  801.04  4945.2  792.12
  4950.5  794.40  4967.9  788.93  4986.7  788.00  4987.3  787.50  4991.7  788.00
  4999.8  790.12  5006.1  796.52  5011.8  794.82  5021.6  797.09  5029.3  801.59
  5034.8  800.52  5044.4  803.37  5098.4  802.61  5126.9  803.91  5153.2  803.51
  5173.0  805.34  5230.5  813.90  5263.4  816.68  5348.1  819.71  5390.0  818.69
#Mann=7,-1,0
  4769.7    0.05       0  4833.1    0.12       0  4986.7    0.07       0
  4991.7    0.12       0  5044.4    0.05       0  5153.2    0.12       0
  5348.1    0.05       0
Bank Sta=4986.7,4991.7
Exp/Cntr=0.3,0.1

Type RM Length L Ch R = 1,5707,308,308,308
BEGIN DESCRIPTION:
Mapping XS 9f437e1f
END DESCRIPTION:
XS GIS Cut Line= 3
      2281826.62      7164223.56      2281722.60      7163956.83
      2281561.00      7163705.14
#Sta/Elev= 30
  4823.8  810.92  4838.4  808.77  4856.5  809.51  4861.9  807.99  4921.1  804.31
  4940.7  803.17  4946.1  801.08  4956.4  799.99  4970.6  791.96  4986.1  786.84
  4986.7  786.34  4991.2  786.84  5024.9  802.00  5049.4  801.82  5054.8  803.01
  5063.8  801.56  5079.3  802.74  5131.0  801.57  5151.2  802.92  5156.3  802.84
  5255.2  806.50  5261.2  809.87  5270.4  809.64  5276.4  811.48  5291.6  811.83
  5349.0  819.68  5370.2  819.11  5379.4  817.54  5407.1  817.85  5409.2  817.85
#Mann=7,-1,0
  4823.8    0.05       0  4921.1    0.12       0  4986.1    0.07       0
  4991.2    0.12       0  5151.2    0.05       0  5156.3    0.12       0
  5407.1    0.05       0
Bank Sta=4986.1,4991.2
Exp/Cntr=0.3,0.1

Type RM Length L Ch R = 1,5399,264,264,264
BEGIN DESCRIPTION:
Mapping XS ebc00514
END DESCRIPTION:
XS GIS Cut Line= 2
      2282160.35      7163978.67      2281638.63      7163655.13
#Sta/Elev= 30
  4780.2  815.45  4839.4  810.49  4880.0  808.61  4939.8  804.61  4946.5  802.14
  4955.2  800.42  4961.1  797.17  4970.1  790.93  4991.8  789.57  4997.7  786.26
  5010.5  784.34  5011.2  783.84  5015.6  784.34  5018.9  789.93  5028.4  794.80
  5034.3  799.31  5040.7  799.37  5049.7  798.16  5064.2  799.19  5076.8  798.60
  5159.0  799.16  5207.9  799.87  5302.4  802.71  5311.3  803.75  5318.0  805.42
  5333.2  807.58  5339.1  807.54  5354.4  810.30  5360.3  810.02  5394.1  813.89
#Mann=6,-1,0
  4780.2    0.05       0  4880.0    0.12       0  5010.5    0.07       0
  5015.6    0.12       0  5159.0    0.05       0  5318.0    0.12       0
Bank Sta=5010.5,5015.6
Exp/Cntr=0.3,0.1

Type RM Length L Ch R = 1,5135,364,364,364
BEGIN DESCRIPTION:
Mapping XS 76d7ce62
END DESCRIPTION:
XS GIS Cut Line= 2
      2282210.36      7163954.30      2281963.59      7163426.77
#Sta/Elev= 30
  4675.1  815.69  4710.6  812.10  4784.6  807.15  4801.3  806.57  4807.5  808.04
  4810.2  807.27  4823.4  804.85  4858.7  803.55  4904.3  799.87  4921.7  797.38
  4955.8  796.94  4966.9  795.48  4972.9  793.28  4978.4  794.59  4989.0  788.82
  4995.7  784.05  5008.4  782.79  5009.2  782.29  5013.7  782.79  5018.5  786.96
  5033.1  795.73  5041.4  796.90  5077.3  796.35  5099.4  798.20  5109.9  797.06
  5129.4  798.37  5138.3  797.82  5220.8  800.64  5235.1  801.49  5257.5  805.22
#Mann=5,-1,0
  4675.1    0.05       0  4810.2    0.12       0  5008.4    0.07       0
  5013.7    0.12       0  5129.4    0.05       0
Bank Sta=5008.4,5013.7
Exp/Cntr=0.3,0.1

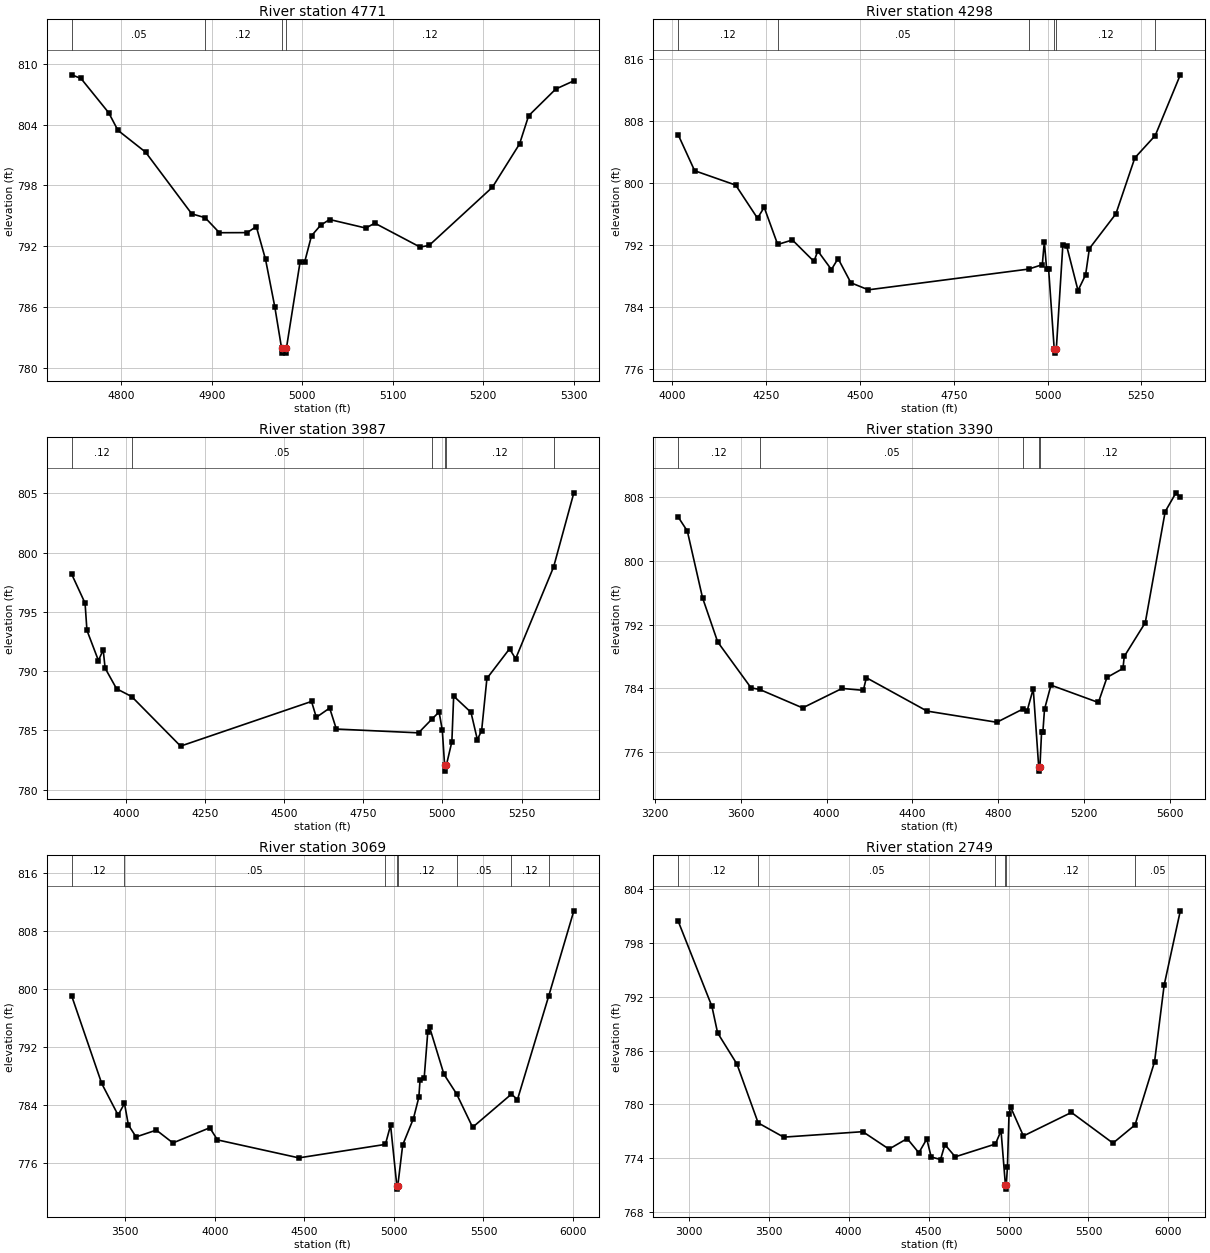
Type RM Length L Ch R = 1,4771,473,473,473
BEGIN DESCRIPTION:
MDE S 034 4.0
END DESCRIPTION:
XS GIS Cut Line= 3
      2282429.01      7163810.04      2282379.00      7163560.00
      2282379.00      7163259.99
#Sta/Elev= 30
  4745.1  808.89  4755.3  808.53  4785.9  805.16  4796.1  803.43  4826.7  801.28
  4877.7  795.21  4892.5  794.83  4908.3  793.35  4938.9  793.36  4949.1  793.95
  4959.3  790.72  4969.5  786.07  4977.0  782.00  4977.8  781.50  4981.6  781.50
  4982.4  782.00  4997.5  790.49  5002.6  790.49  5010.1  793.05  5020.1  794.08
  5030.1  794.65  5070.1  793.81  5080.1  794.29  5130.1  791.94  5140.1  792.10
  5210.1  797.83  5240.1  802.09  5250.1  804.86  5280.1  807.49  5300.1  808.30
#Mann=4,-1,0
  4745.1    0.05       0  4892.5    0.12       0  4977.0    0.07       0
  4982.4    0.12       0
Bank Sta=4977,4982.4
Exp/Cntr=0.3,0.1

Type RM Length L Ch R = 1,4298,311,311,311
BEGIN DESCRIPTION:
MDE S 034 3.0
END DESCRIPTION:
XS GIS Cut Line= 3
      2282379.02      7164309.96      2282779.00      7163410.00
      2282729.00      7163059.99
#Sta/Elev= 30
  4015.6  806.21  4059.3  801.58  4168.8  799.72  4226.9  795.44  4244.7  796.85
  4280.7  792.05  4319.9  792.63  4377.4  789.86  4387.6  791.22  4423.9  788.81
  4441.7  790.23  4475.8  787.10  4522.4  786.19  4949.6  788.87  4986.1  789.44
  4991.5  792.41  4997.7  788.83  5003.0  788.83  5017.9  778.51  5018.7  778.01
  5023.4  778.51  5040.8  791.92  5050.9  791.89  5081.3  786.10  5101.5  788.12
  5111.6  791.52  5182.3  796.01  5232.8  803.24  5287.2  806.13  5354.0  813.97
#Mann=6,-1,0
  4015.6    0.12       0  4280.7    0.05       0  4949.6    0.12       0
  5017.9    0.07       0  5023.4    0.12       0  5287.2    0.05       0
Bank Sta=5017.9,5023.4
Exp/Cntr=0.3,0.1

Type RM Length L Ch R = 1,3987,597,597,597
BEGIN DESCRIPTION:
Mapping XS de6db355
END DESCRIPTION:
XS GIS Cut Line= 3
      2282449.55      7164297.79      2283063.54      7163354.93
      2283009.87      7162897.32
#Sta/Elev= 30
  3829.4  798.16  3871.4  795.73  3877.3  793.44  3913.6  790.89  3928.7  791.79
  3934.7  790.25  3970.9  788.51  4018.7  787.85  4173.1  783.67  4586.7  787.44
  4601.8  786.10  4644.0  786.88  4665.1  785.11  4924.7  784.79  4967.0  785.95
  4989.7  786.55  4999.8  785.01  5007.1  782.06  5007.9  781.56  5012.6  782.06
  5030.0  784.04  5035.7  787.89  5090.4  786.52  5110.5  784.22  5124.0  784.97
  5140.7  789.38  5212.2  791.88  5231.4  791.04  5351.3  798.78  5415.3  805.04
#Mann=6,-1,0
  3829.4    0.12       0  4018.7    0.05       0  4967.0    0.12       0
  5007.1    0.07       0  5012.6    0.12       0  5351.3    0.05       0
Bank Sta=5007.1,5012.6
Exp/Cntr=0.3,0.1

Type RM Length L Ch R = 1,3390,321,321,321
BEGIN DESCRIPTION:
MDE S 034 2.0
END DESCRIPTION:
XS GIS Cut Line= 3
      2282378.99      7164410.01      2283579.00      7163210.00
      2283519.00      7162569.77
#Sta/Elev= 30
  3308.2  805.47  3350.6  803.72  3421.3  795.38  3492.1  789.83  3647.6  784.08
  3687.9  783.88  3888.0  781.57  4071.9  784.01  4170.9  783.77  4185.0  785.35
  4467.9  781.17  4793.1  779.77  4914.8  781.43  4934.6  781.22  4962.8  783.97
  4988.4  774.15  4989.2  773.65  4993.9  774.15  5001.7  778.56  5007.8  778.56
  5015.3  781.39  5045.4  784.42  5266.4  782.25  5306.6  785.39  5381.1  786.51
  5386.9  788.01  5485.0  792.25  5577.8  806.16  5628.0  808.51  5648.3  807.97
#Mann=5,-1,0
  3308.2    0.12       0  3687.9    0.05       0  4914.8    0.12       0
  4988.4    0.07       0  4993.9    0.12       0
Bank Sta=4988.4,4993.9
Exp/Cntr=0.3,0.1

Type RM Length L Ch R = 1,3069,320,320,320
BEGIN DESCRIPTION:
Mapping XS f54c2eb1
END DESCRIPTION:
XS GIS Cut Line= 3
      2282470.57      7164526.56      2283836.60      7163390.22
      2283881.56      7162365.59
#Sta/Elev= 30
  3201.9  799.03  3369.0  786.99  3460.5  782.63  3496.2  784.24  3517.8  781.27
  3560.8  779.62  3674.0  780.56  3766.5  778.79  3972.2  780.88  4015.1  779.21
  4469.5  776.73  4952.5  778.59  4981.4  781.23  5016.2  772.92  5017.1  772.42
  5021.8  772.92  5049.1  778.51  5109.1  782.16  5139.2  785.09  5145.9  787.49
  5169.2  787.81  5189.2  794.14  5199.2  794.74  5279.3  788.26  5349.5  785.57
  5439.4  780.95  5656.0  785.52  5689.7  784.77  5864.9  799.12  6004.4  810.80
#Mann=8,-1,0
  3201.9    0.12       0  3496.2    0.05       0  4952.5    0.12       0
  5016.2    0.07       0  5021.8    0.12       0  5349.5    0.05       0
  5656.0    0.12       0  5864.9    0.05       0
Bank Sta=5016.2,5021.8
Exp/Cntr=0.3,0.1

Type RM Length L Ch R = 1,2749,371,371,371
BEGIN DESCRIPTION:
Mapping XS 56ea3a85
END DESCRIPTION:
XS GIS Cut Line= 3
      2282509.44      7164713.95      2284126.10      7163517.74
      2284137.20      7162388.89
#Sta/Elev= 30
  2934.5  800.44  3145.2  790.93  3180.7  787.97  3301.8  784.48  3434.3  777.91
  3593.9  776.32  4088.7  776.93  4252.6  774.98  4366.3  776.16  4439.2  774.57
  4488.9  776.11  4516.6  774.10  4575.1  773.82  4602.1  775.49  4666.8  774.12
  4918.2  775.55  4953.3  777.03  4980.5  771.01  4981.4  770.51  4986.1  771.01
  4993.3  772.97  5003.3  778.95  5013.3  779.67  5093.3  776.45  5393.4  779.08
  5653.4  775.65  5791.5  777.69  5913.4  784.74  5973.4  793.30  6074.5  801.61
#Mann=6,-1,0
  2934.5    0.12       0  3434.3    0.05       0  4918.2    0.12       0
  4980.5    0.07       0  4986.1    0.12       0  5791.5    0.05       0
Bank Sta=4980.5,4986.1
Exp/Cntr=0.3,0.1