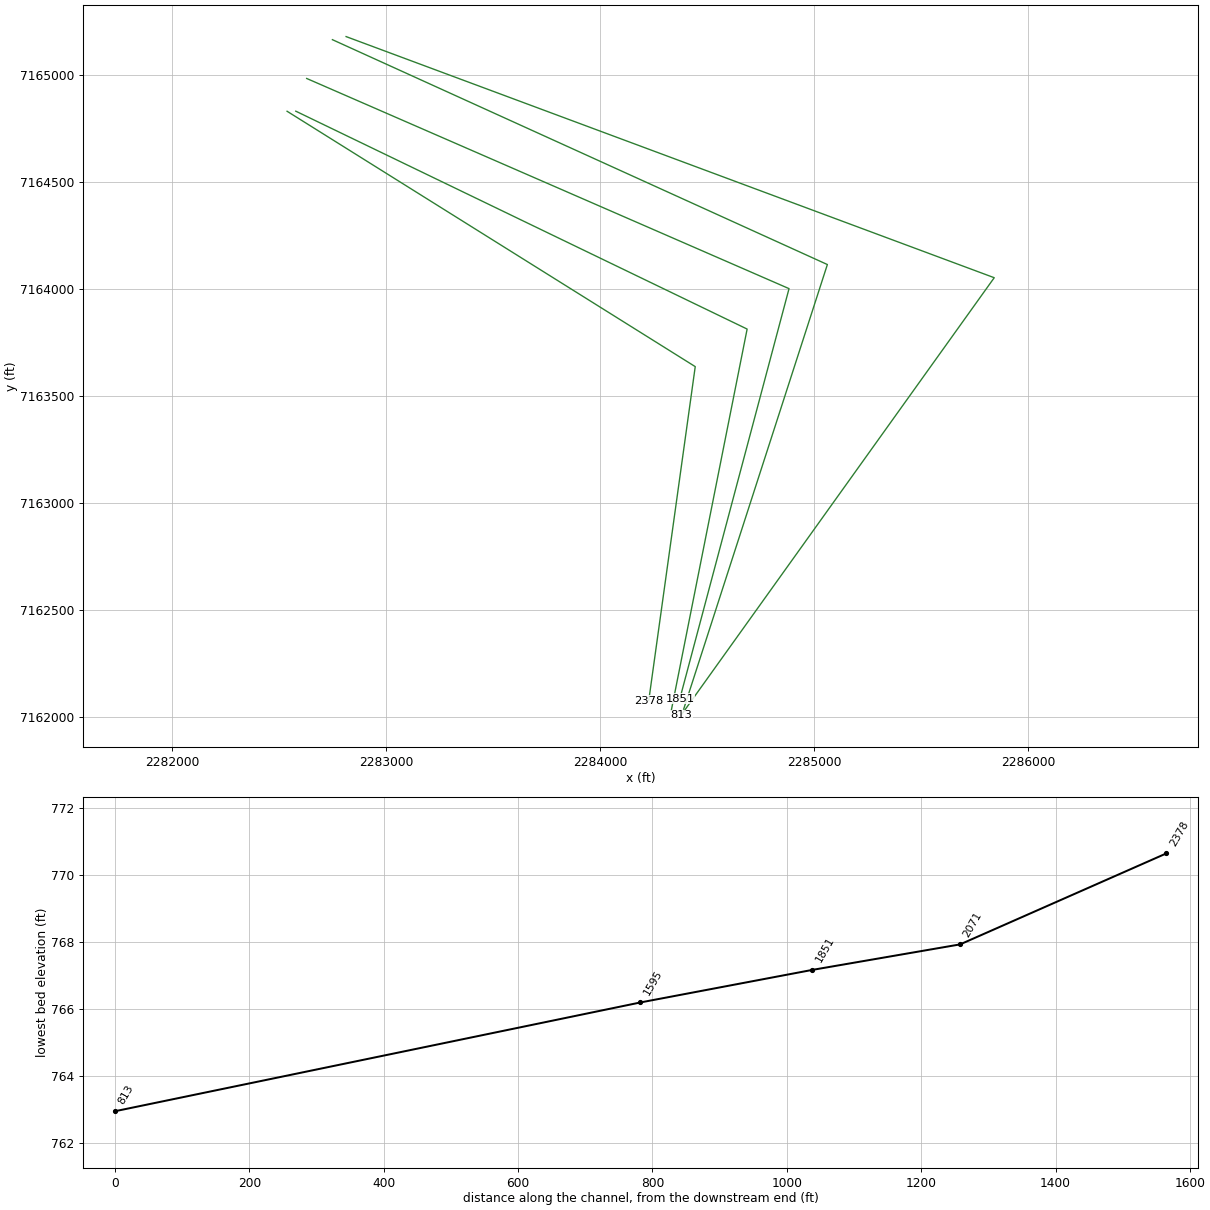
HEC-RAS study MDE S 034.prj: MDE S 034 Base Level Engineering

--- MDE S 034.g01 (geometry) --- (continued)

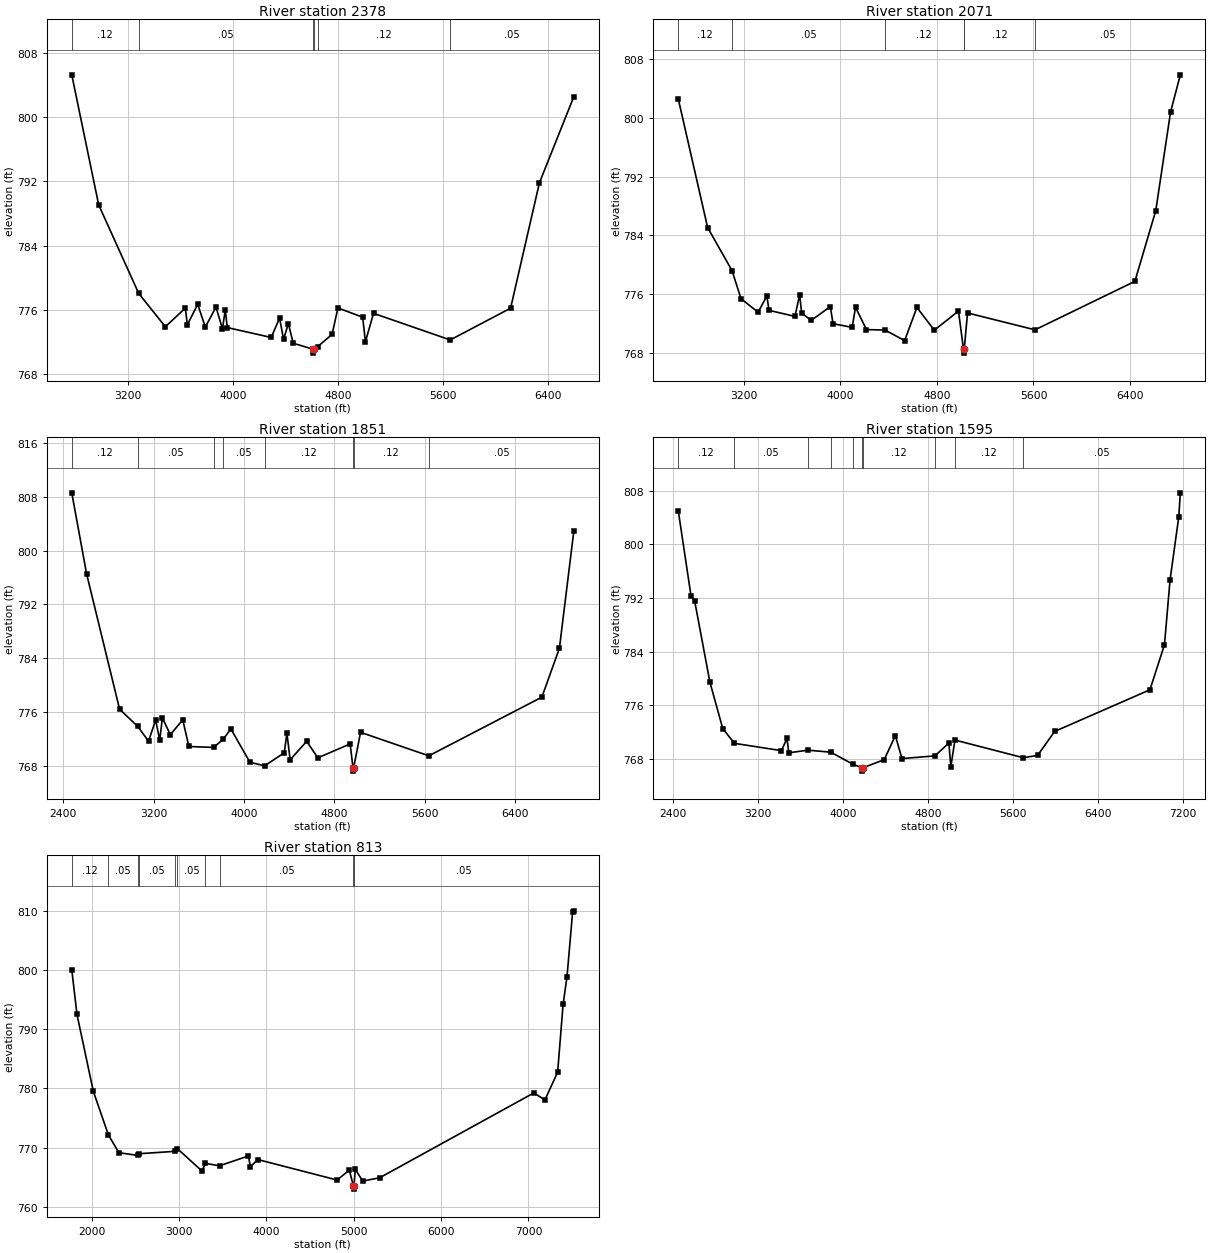
Type RM Length L Ch R = 1,2378,307,307,307
BEGIN DESCRIPTION:
Mapping XS f5d65cac
END DESCRIPTION:
XS GIS Cut Line= 3
      2282537.31      7164832.00      2284444.74      7163638.62
      2284227.49      7162078.06
#Sta/Elev= 30
  2770.5  805.26  2975.6  789.08  3280.4  778.07  3483.7  773.92  3635.8  776.24
  3651.1  774.16  3730.1  776.71  3787.9  773.89  3869.5  776.36  3918.8  773.66
  3940.3  776.04  3955.3  773.82  4290.1  772.59  4353.8  775.00  4384.5  772.36
  4421.0  774.32  4457.6  771.87  4606.8  771.14  4607.7  770.64  4612.4  771.14
  4642.9  771.43  4754.2  772.98  4798.3  776.26  4986.9  775.11  5008.1  772.06
  5069.6  775.59  5654.2  772.28  6114.1  776.23  6334.0  791.84  6596.1  802.55
#Mann=6,-1,0
  2770.5    0.12       0  3280.4    0.05       0  4606.8    0.07       0
  4612.4    0.05       0  4642.9    0.12       0  5654.2    0.05       0
Bank Sta=4606.8,4612.4
Exp/Cntr=0.3,0.1

Type RM Length L Ch R = 1,2071,220,220,220
BEGIN DESCRIPTION:
Mapping XS bdc47336
END DESCRIPTION:
XS GIS Cut Line= 3
      2282578.04      7164832.38      2284687.24      7163814.16
      2284332.64      7162030.69
#Sta/Elev= 30
  2656.1  802.64  2899.5  785.07  3101.4  779.20  3176.3  775.36  3317.5  773.51
  3390.9  775.73  3407.9  773.77  3623.2  772.94  3662.1  775.90  3678.8  773.41
  3758.1  772.39  3916.3  774.28  3939.0  771.95  4097.2  771.44  4125.3  774.19
  4215.8  771.14  4369.4  771.08  4532.2  769.64  4633.8  774.16  4778.1  771.06
  4978.4  773.67  5020.1  768.43  5020.9  767.93  5025.7  768.43  5053.4  773.41
  5612.4  771.11  6440.1  777.72  6613.4  787.38  6735.7  800.82  6816.6  805.90
#Mann=6,-1,0
  2656.1    0.12       0  3101.4    0.05       0  4369.4    0.12       0
  5020.1    0.07       0  5025.7    0.12       0  5612.4    0.05       0
Bank Sta=5020.1,5025.7
Exp/Cntr=0.3,0.1

Type RM Length L Ch R = 1,1851,256,256,256
BEGIN DESCRIPTION:
Mapping XS 6eaea219
END DESCRIPTION:
XS GIS Cut Line= 3
      2282628.92      7164985.24      2284883.09      7164003.10
      2284372.78      7162086.41
#Sta/Elev= 30
  2476.4  808.63  2607.5  796.56  2899.5  776.39  3058.9  773.85  3155.6  771.63
  3218.2  774.77  3254.7  771.81  3278.2  775.09  3348.5  772.61  3458.5  774.81
  3512.7  770.84  3730.5  770.70  3816.5  771.92  3884.0  773.46  4053.5  768.47
  4183.7  767.97  4356.4  769.90  4379.8  772.82  4408.7  768.86  4554.7  771.61
  4653.9  769.15  4939.4  771.22  4964.6  767.67  4965.5  767.17  4970.2  767.67
  5031.6  772.95  5635.5  769.45  6635.6  778.19  6790.8  785.46  6918.7  802.95
#Mann=8,-1,0
  2476.4    0.12       0  3058.9    0.05       0  3730.5    0.12       0
  3816.5    0.05       0  4183.7    0.12       0  4964.6    0.07       0
  4970.2    0.12       0  5635.5    0.05       0
Bank Sta=4964.6,4970.2
Exp/Cntr=0.3,0.1

Type RM Length L Ch R = 1,1595,782,782,782
BEGIN DESCRIPTION:
Mapping XS 65d71f22
END DESCRIPTION:
XS GIS Cut Line= 3
      2282749.21      7165166.52      2285062.25      7164115.69
      2284390.72      7162038.17
#Sta/Elev= 30
  2451.2  805.02  2571.0  792.35  2605.1  791.60  2749.0  779.47  2869.9  772.55
  2979.7  770.34  3422.5  769.25  3474.1  771.07  3491.7  768.93  3670.9  769.32
  3887.8  769.02  4097.2  767.20  4183.6  766.70  4184.4  766.20  4189.2  766.70
  4389.3  767.91  4493.9  771.49  4556.3  768.07  4865.8  768.47  4997.7  770.39
  5016.0  766.84  5054.4  770.83  5696.6  768.20  5832.3  768.54  5992.4  772.11
  6889.4  778.32  7026.0  785.03  7078.6  794.70  7160.9  804.11  7175.1  807.66
#Mann=10,-1,0
  2451.2    0.12       0  2979.7    0.05       0  3670.9    0.12       0
  3887.8    0.05       0  4097.2    0.12       0  4183.6    0.04       0
  4189.2    0.12       0  4865.8    0.05       0  5054.4    0.12       0
  5696.6    0.05       0
Bank Sta=4183.6,4189.2
Exp/Cntr=0.3,0.1

Type RM Length L Ch R = 1,813,0,0,0
BEGIN DESCRIPTION:
MDE S 034 1.0
END DESCRIPTION:
XS GIS Cut Line= 3
      2282813.06      7165180.98      2285842.06      7164054.13
      2284378.99      7162009.98
#Sta/Elev= 30
  1773.7  800.08  1833.4  792.51  2020.2  779.51  2193.4  772.11  2313.5  769.12
  2530.8  768.66  2543.1  768.95  2950.9  769.35  2983.6  769.79  3263.1  766.03
  3304.0  767.31  3464.4  766.91  3794.9  768.57  3817.9  766.76  3903.3  767.96
  4810.2  764.50  4949.9  766.18  4997.2  763.46  4998.0  762.96  5002.8  763.46
  5018.1  766.31  5104.0  764.32  5296.9  764.88  7061.0  779.23  7188.8  778.07
  7333.8  782.74  7396.4  794.23  7440.7  798.84  7505.8  809.92  7519.3  810.04
#Mann=10,-1,0
  1773.7    0.12       0  2193.4    0.05       0  2530.8    0.12       0
  2543.1    0.05       0  2950.9    0.12       0  2983.6    0.05       0
  3304.0    0.12       0  3464.4    0.05       0  4997.2    0.04       0
  5002.8    0.05       0
Bank Sta=4997.2,5002.8
Exp/Cntr=0.3,0.1

Chan Stop Cuts=-1