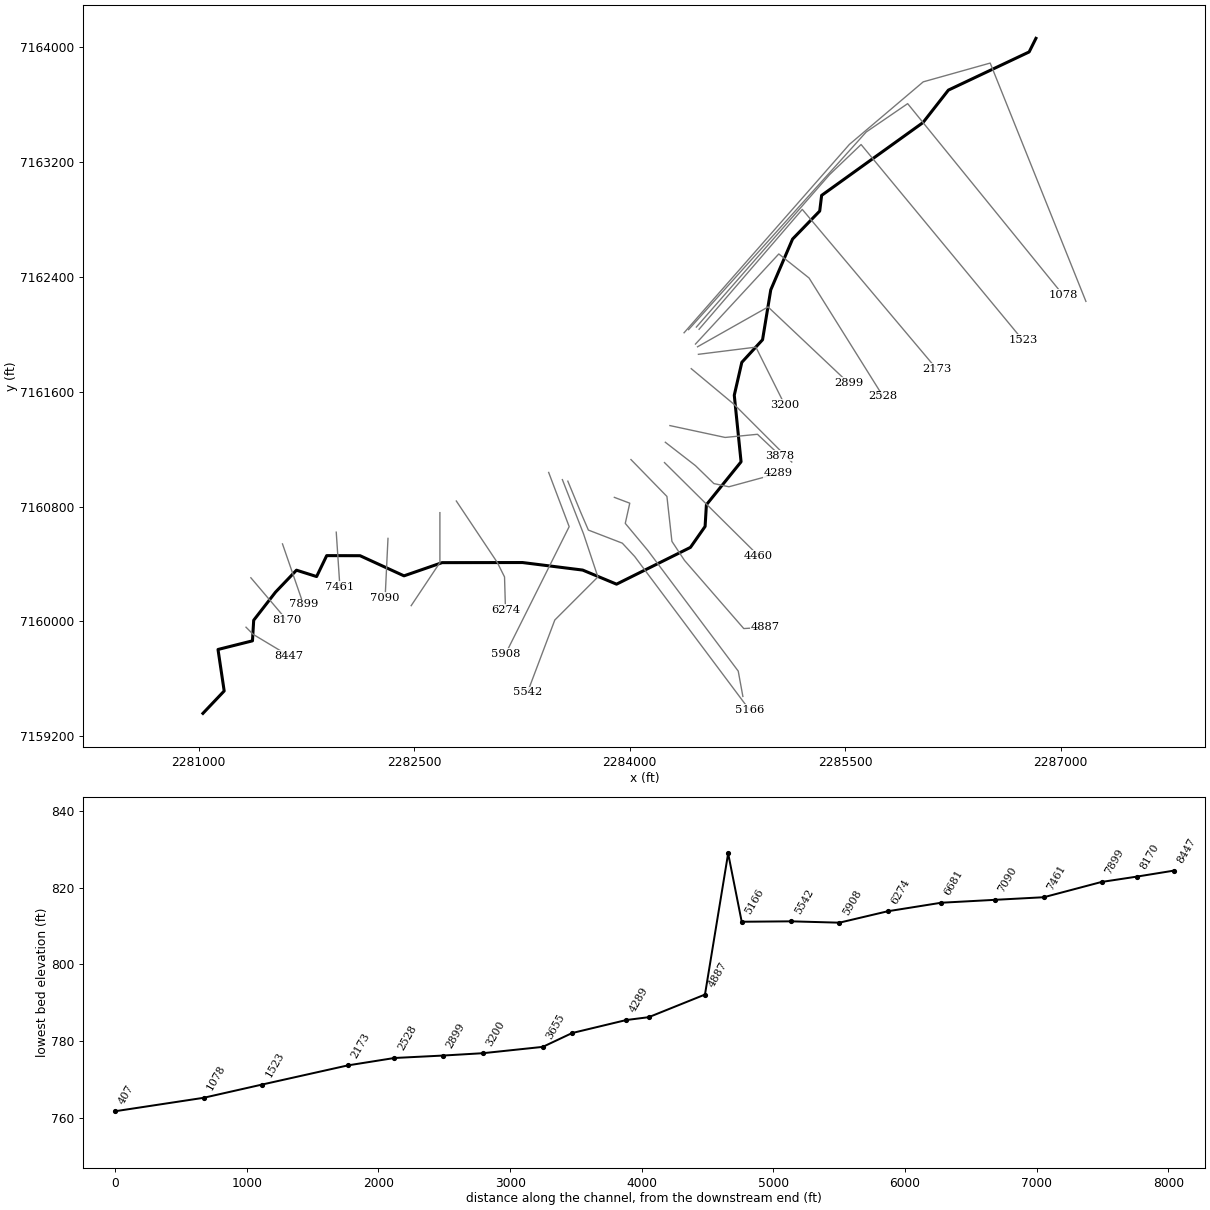
--- MDE S 035.prj (project) ---

Proj Title=MDE S 035 Base Level Engineering
Current Plan=p01
Default Exp/Contr=0.3,0.1
English Units
Geom File=g01
Flow File=f01
Plan File=p01
BEGIN DESCRIPTION:
MDE S 035
END DESCRIPTION:

--- MDE S 035.p01 (plan) ---

Plan Title=Multiple Run
Short Identifier=Multiple
Geom File=g01
Flow File=f01
Subcritical Flow
K Sum by GR= 0
Std Step Tol= 0.01
Critical Tol= 0.01
Num of Std Step Trials= 20
Max Error Tol= 0.3
Flow Tol Ratio= 0.001
Split Flow NTrial= 30
Split Flow Tol= 0.02
Split Flow Ratio= 0.02
Log Output Level= 0
Friction Slope Method= 1
Unsteady Friction Slope Method= 2
Unsteady Bridges Friction Slope Method= 1
Parabolic Critical Depth
Global Vel Dist=  1 , 1 , 1
Global Log Level= 0
CheckData=True
Encroach Param= -1, 0, 0, 0
BEGIN DESCRIPTION:
Multiple Run
END DESCRIPTION:

--- MDE S 035.f01 (steady flow) ---

Flow Title=Multiple
Number of Profiles=7
Profile Names=10-year,25-year,50-year,1pct_min,100-year,1pct_plu,500-year
River Rch & RM= MDE S 035,Reach-1,8447
     699     973    1204     741    1478    2948    2229
River Rch & RM= MDE S 035,Reach-1,5166
    1154    1653    2083    1303    2600    5187    4059
River Rch & RM= MDE S 035,Reach-1,1078
    1328    1916    2426    1524    3040    6065    4785
Boundary for River Rch & Prof#=MDE S 035,Reach-1,1
Up Type=0
Dn Type=3
Dn Slope=0.009
Boundary for River Rch & Prof#=MDE S 035,Reach-1,2
Up Type=0
Dn Type=3
Dn Slope=0.009
Boundary for River Rch & Prof#=MDE S 035,Reach-1,3
Up Type=0
Dn Type=3
Dn Slope=0.009
Boundary for River Rch & Prof#=MDE S 035,Reach-1,4
Up Type=0
Dn Type=3
Dn Slope=0.009
Boundary for River Rch & Prof#=MDE S 035,Reach-1,5
Up Type=0
Dn Type=3
Dn Slope=0.009
Boundary for River Rch & Prof#=MDE S 035,Reach-1,6
Up Type=0
Dn Type=3
Dn Slope=0.009
Boundary for River Rch & Prof#=MDE S 035,Reach-1,7
Up Type=0
Dn Type=3
Dn Slope=0.009

--- MDE S 035.g01 (geometry) ---

Geom Title=Existing Conditions

River Reach=MDE S 035,Reach-1
Reach XY= 30
      2281029.00      7159360.00      2281177.04      7159515.89
      2281134.02      7159804.92      2281373.96      7159865.08
      2281382.55      7160008.52      2281534.65      7160204.37
      2281680.42      7160356.96      2281820.54      7160312.63
      2281890.81      7160458.38      2282123.07      7160457.76
      2282429.00      7160317.56      2282694.22      7160409.48
      2283254.08      7160410.20      2283673.06      7160357.74
      2283908.83      7160259.63      2284423.39      7160515.59
      2284525.45      7160661.47      2284534.48      7160812.44
      2284775.87      7161111.63      2284728.57      7161575.18
      2284781.07      7161804.14      2284925.46      7161961.47
      2284982.55      7162308.53      2285134.47      7162662.45
      2285323.47      7162857.58      2285336.75      7162966.45
      2286042.56      7163473.49      2286219.25      7163699.47
      2286781.66      7163965.33      2286829.00      7164060.00

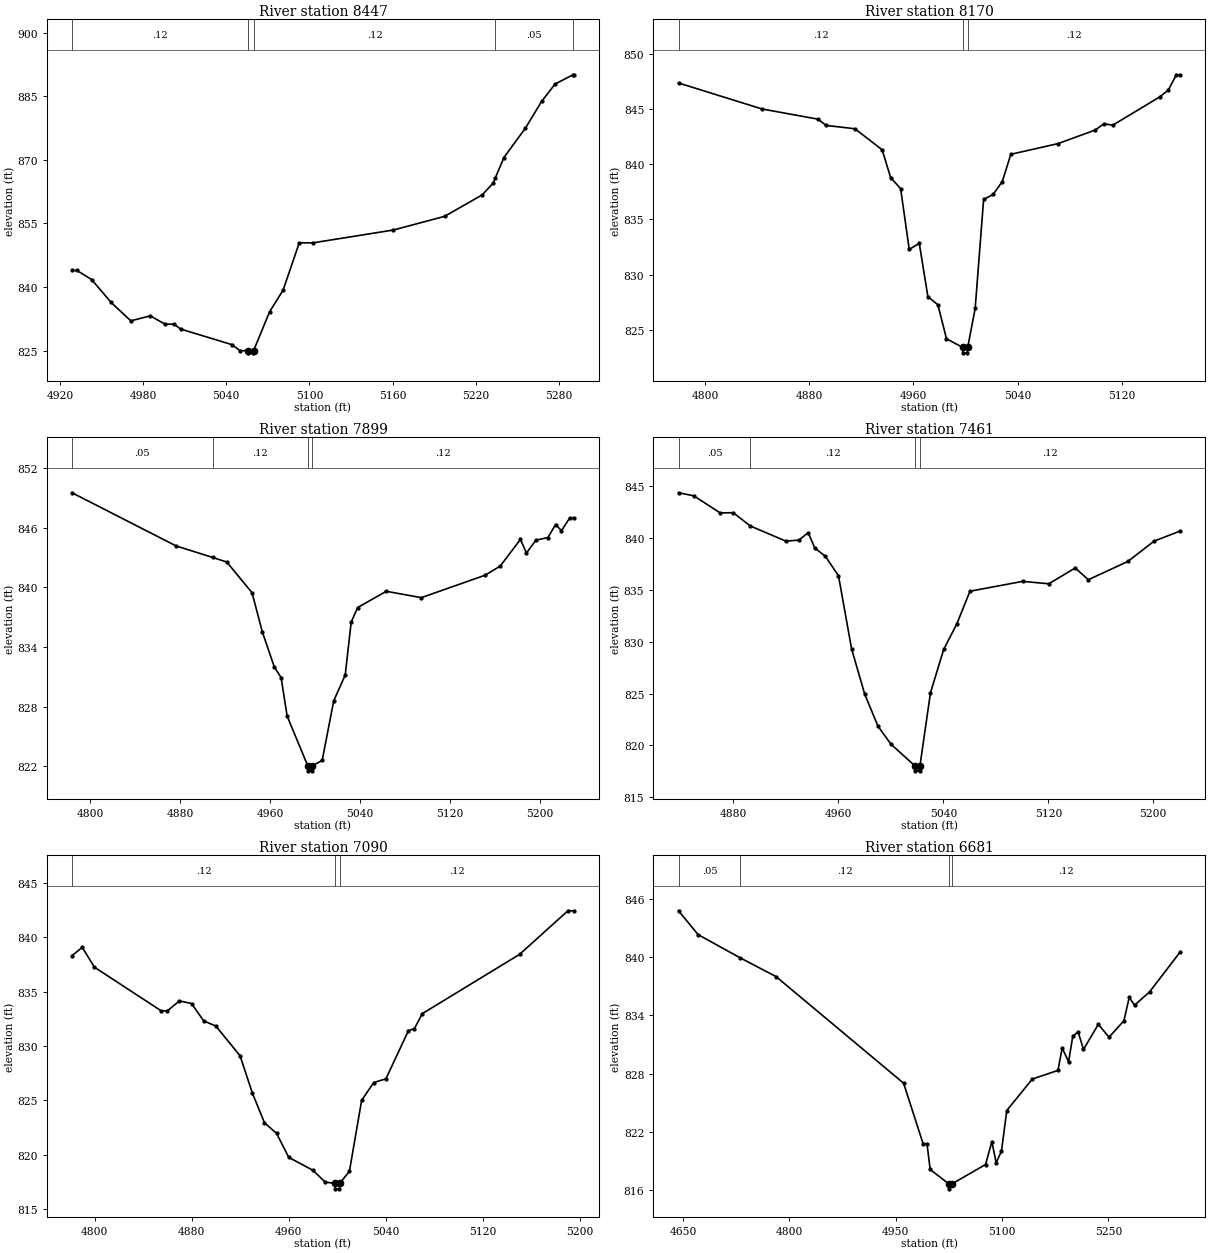
Type RM Length L Ch R = 1,8447,277,277,277
BEGIN DESCRIPTION:
MDE S 035 15.0
END DESCRIPTION:
XS GIS Cut Line= 3
      2281329.03      7159959.97      2281379.00      7159910.00
      2281628.98      7159760.01
#Sta/Elev= 30
  4928.7  843.91  4932.2  843.91  4942.8  841.78  4956.9  836.36  4971.1  832.03
  4985.2  833.20  4995.8  831.24  5002.3  831.24  5007.1  830.09  5044.1  826.41
  5049.9  824.99  5055.7  824.98  5055.9  824.48  5059.4  824.48  5059.7  824.98
  5071.3  834.18  5081.0  839.26  5092.7  850.44  5102.4  850.42  5160.7  853.46
  5197.6  856.68  5224.8  861.76  5232.6  864.50  5234.3  865.82  5240.4  870.55
  5255.9  877.48  5267.6  883.79  5277.3  887.88  5290.2  890.08  5290.9  890.08
#Mann=5,-1,0
  4928.7    0.12       0  5055.7    0.07       0  5059.7    0.12       0
  5234.3    0.05       0  5290.2    0.12       0
Bank Sta=5055.7,5059.7
Exp/Cntr=0.3,0.1

Type RM Length L Ch R = 1,8170,271,271,271
BEGIN DESCRIPTION:
Mapping XS 112f8c4b
END DESCRIPTION:
XS GIS Cut Line= 2
      2281362.85      7160304.10      2281612.14      7160010.45
#Sta/Elev= 30
  4779.7  847.34  4843.7  844.99  4886.6  844.07  4893.1  843.50  4915.1  843.20
  4936.0  841.30  4942.5  838.79  4950.2  837.78  4956.8  832.29  4964.5  832.84
  4971.1  828.03  4978.8  827.28  4985.4  824.21  4997.7  823.44  4997.9  822.94
  5001.4  822.94  5001.7  823.44  5007.4  826.95  5013.9  836.81  5021.2  837.26
  5028.2  838.42  5034.8  840.89  5071.1  841.86  5099.7  843.09  5106.2  843.65
  5113.0  843.52  5149.1  846.08  5155.6  846.69  5161.9  848.08  5164.9  848.08
#Mann=3,-1,0
  4779.7    0.12       0  4997.7    0.07       0  5001.7    0.12       0
Bank Sta=4997.7,5001.7
Exp/Cntr=0.3,0.1

Type RM Length L Ch R = 1,7899,438,438,438
BEGIN DESCRIPTION:
Mapping XS 3fb1a07f
END DESCRIPTION:
XS GIS Cut Line= 2
      2281582.97      7160540.03      2281728.83      7160118.14
#Sta/Elev= 30
  4783.9  849.53  4876.4  844.18  4908.9  843.02  4921.5  842.56  4944.0  839.47
  4953.2  835.51  4963.8  831.99  4969.9  830.91  4975.2  827.05  4993.6  822.03
  4993.8  821.53  4997.3  821.53  4997.6  822.03  5006.4  822.58  5016.7  828.59
  5026.9  831.18  5032.2  836.50  5037.9  837.97  5063.4  839.61  5094.6  838.97
  5151.6  841.24  5164.8  842.15  5182.8  844.84  5188.1  843.46  5196.6  844.76
  5207.2  845.02  5214.0  846.33  5219.3  845.72  5226.7  847.01  5230.3  847.01
#Mann=4,-1,0
  4783.9    0.05       0  4908.9    0.12       0  4993.6    0.07       0
  4997.6    0.12       0
Bank Sta=4993.6,4997.6
Exp/Cntr=0.3,0.1

Type RM Length L Ch R = 1,7461,371,371,371
BEGIN DESCRIPTION:
Mapping XS 002ab327
END DESCRIPTION:
XS GIS Cut Line= 2
      2281957.28      7160621.61      2281982.81      7160240.07
#Sta/Elev= 30
  4838.2  844.35  4849.8  844.06  4869.9  842.41  4879.9  842.43  4892.9  841.15
  4920.0  839.69  4930.0  839.79  4937.0  840.51  4942.0  839.03  4950.1  838.23
  4960.1  836.35  4970.1  829.29  4980.1  824.94  4990.2  821.85  5000.2  820.10
  5018.2  818.05  5018.5  817.55  5022.0  817.55  5022.2  818.05  5030.2  825.08
  5040.3  829.26  5050.3  831.72  5060.3  834.86  5100.4  835.81  5120.4  835.58
  5140.5  837.10  5150.5  835.97  5180.6  837.73  5200.6  839.69  5220.6  840.67
#Mann=4,-1,0
  4838.2    0.05       0  4892.9    0.12       0  5018.2    0.07       0
  5022.2    0.12       0
Bank Sta=5018.2,5022.2
Exp/Cntr=0.3,0.1

Type RM Length L Ch R = 1,7090,409,409,409
BEGIN DESCRIPTION:
Mapping XS 380e1de2
END DESCRIPTION:
XS GIS Cut Line= 2
      2282317.54      7160578.38      2282297.59      7160165.26
#Sta/Elev= 30
  4781.3  838.30  4789.7  839.06  4799.7  837.24  4854.7  833.23  4859.8  833.22
  4869.8  834.14  4879.8  833.90  4889.8  832.30  4899.8  831.83  4919.8  829.09
  4929.9  825.67  4939.9  822.94  4949.9  821.96  4959.9  819.76  4979.9  818.57
  4989.9  817.49  4997.9  817.37  4998.2  816.87  5001.7  816.87  5001.9  817.37
  5009.9  818.48  5020.0  825.01  5030.0  826.64  5040.0  826.98  5058.5  831.39
  5063.5  831.60  5070.0  832.97  5150.1  838.41  5190.0  842.42  5194.9  842.42
#Mann=3,-1,0
  4781.3    0.12       0  4997.9    0.07       0  5001.9    0.12       0
Bank Sta=4997.9,5001.9
Exp/Cntr=0.3,0.1

Type RM Length L Ch R = 1,6681,407,407,407
BEGIN DESCRIPTION:
MDE S 035 10.0
END DESCRIPTION:
XS GIS Cut Line= 4
      2282679.00      7160757.57      2282679.00      7160510.00
      2282679.00      7160410.00      2282479.01      7160110.02
#Sta/Elev= 30
  4643.5  844.80  4671.1  842.34  4730.9  839.93  4781.1  838.01  4961.1  827.01
  4988.6  820.77  4994.1  820.77  4998.6  818.11  5025.1  816.61  5025.4  816.11
  5029.1  816.61  5076.7  818.62  5085.7  820.98  5091.7  818.80  5099.2  820.00
  5106.7  824.19  5142.8  827.44  5178.9  828.33  5184.9  830.64  5193.9  829.23
  5199.9  831.87  5207.4  832.31  5214.9  830.49  5235.9  833.08  5251.0  831.76
  5272.0  833.45  5279.5  835.87  5287.0  835.06  5308.1  836.42  5351.6  840.57
#Mann=4,-1,0
  4643.5    0.05       0  4730.9    0.12       0  5025.1    0.07       0
  5029.1    0.12       0
Bank Sta=5025.1,5029.1
Exp/Cntr=0.3,0.1

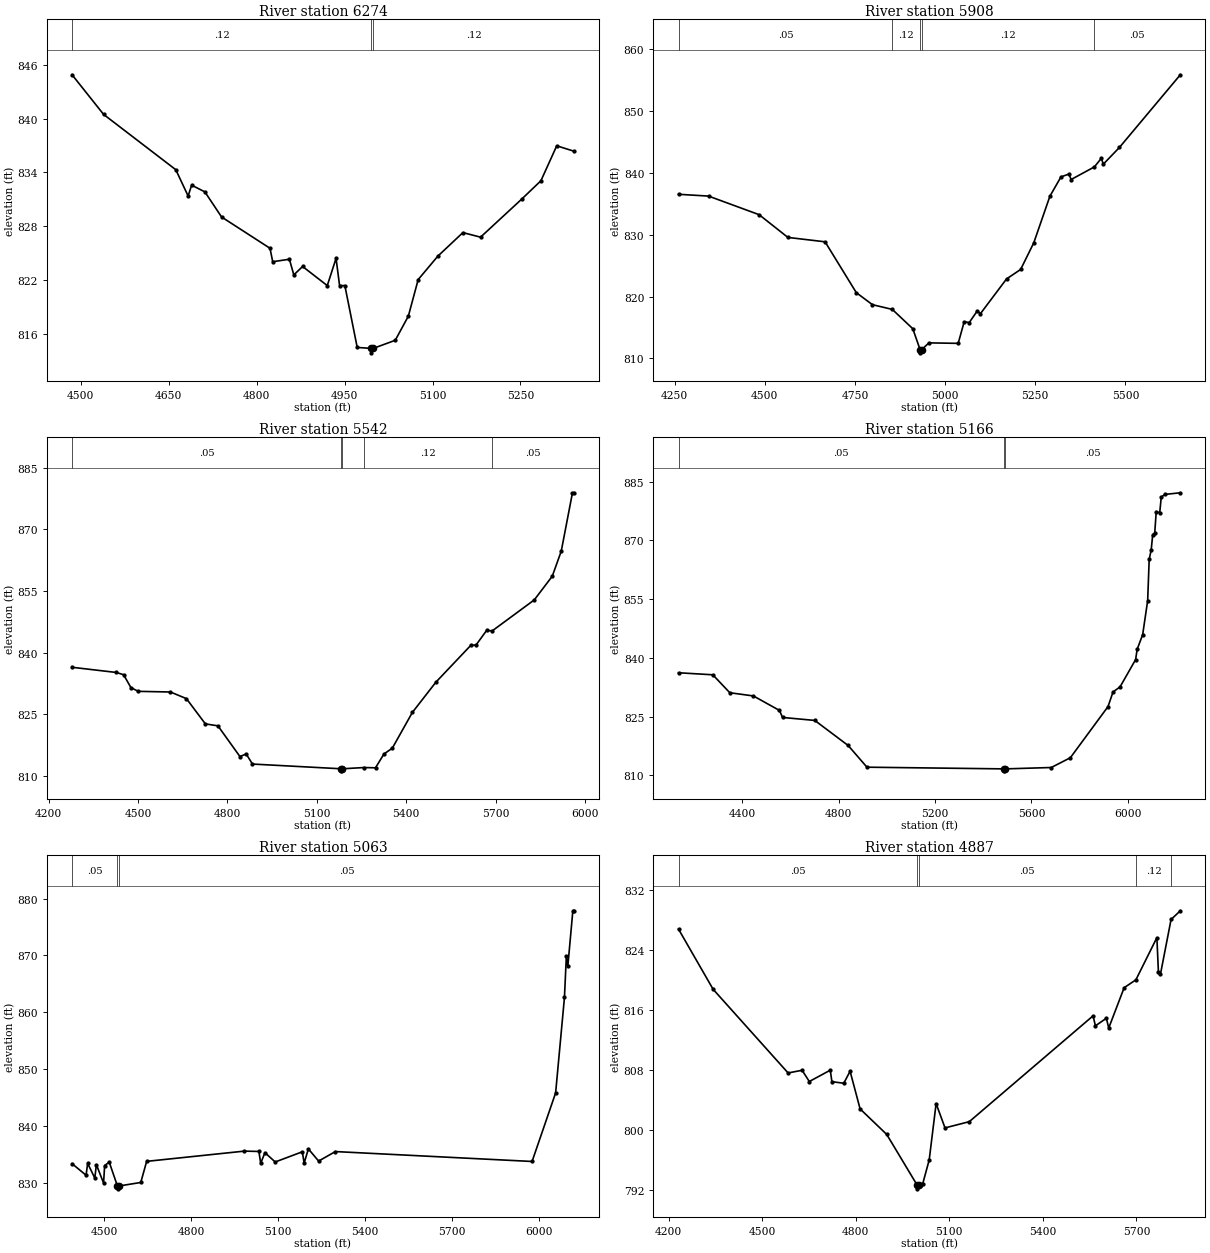
Type RM Length L Ch R = 1,6274,366,366,366
BEGIN DESCRIPTION:
MDE S 035 9.0
END DESCRIPTION:
XS GIS Cut Line= 5
      2282793.32      7160838.53      2282979.00      7160560.00
      2283079.00      7160410.00      2283129.00      7160310.00
      2283135.70      7160080.82
#Sta/Elev= 30
  4485.0  844.89  4538.8  840.47  4662.0  834.30  4683.0  831.37  4689.0  832.58
  4711.6  831.83  4740.1  829.03  4822.7  825.54  4827.3  824.04  4855.8  824.32
  4863.3  822.57  4878.3  823.51  4920.4  821.38  4935.4  824.42  4941.4  821.38
  4950.4  821.38  4971.5  814.48  4995.0  814.38  4995.3  813.88  4999.0  814.38
  5036.4  815.28  5058.7  817.97  5075.5  822.05  5109.0  824.66  5151.8  827.29
  5181.9  826.78  5251.9  831.01  5284.9  833.07  5311.9  836.97  5341.1  836.37
#Mann=3,-1,0
  4485.0    0.12       0  4995.0    0.07       0  4999.0    0.12       0
Bank Sta=4995,4999
Exp/Cntr=0.3,0.1

Type RM Length L Ch R = 1,5908,366,366,366
BEGIN DESCRIPTION:
MDE S 035 8.0
END DESCRIPTION:
XS GIS Cut Line= 5
      2283436.35      7161037.45      2283579.00      7160660.00
      2283429.00      7160360.00      2283279.00      7160060.00
      2283137.29      7159776.58
#Sta/Elev= 30
  4261.0  836.50  4344.2  836.21  4484.4  833.21  4564.2  829.54  4667.3  828.83
  4753.9  820.62  4798.7  818.68  4853.7  817.92  4910.5  814.80  4930.8  811.41
  4931.1  810.91  4934.8  811.41  4955.2  812.52  5036.3  812.44  5053.0  815.93
  5067.0  815.80  5089.4  817.69  5097.7  817.21  5170.4  822.84  5209.5  824.37
  5245.9  828.67  5290.6  836.19  5321.3  839.31  5343.7  839.77  5349.3  838.88
  5413.9  840.92  5433.2  842.31  5438.7  841.36  5483.5  844.07  5652.2  855.79
#Mann=5,-1,0
  4261.0    0.05       0  4853.7    0.12       0  4930.8    0.07       0
  4934.8    0.12       0  5413.9    0.05       0
Bank Sta=4930.8,4934.8
Exp/Cntr=0.3,0.1

Type RM Length L Ch R = 1,5542,376,376,376
BEGIN DESCRIPTION:
MDE S 035 7.0
END DESCRIPTION:
XS GIS Cut Line= 5
      2283531.68      7160987.54      2283679.00      7160610.00
      2283779.00      7160310.00      2283479.00      7160010.00
      2283288.77      7159506.17
#Sta/Elev= 30
  4278.5  836.44  4427.0  835.18  4451.5  834.63  4475.9  831.51  4500.4  830.59
  4608.6  830.43  4662.3  828.82  4725.9  822.68  4768.1  822.20  4841.9  814.74
  4863.0  815.36  4884.0  812.91  5181.8  811.76  5182.1  811.26  5185.8  811.76
  5258.0  812.06  5297.0  812.00  5325.3  815.35  5353.5  816.78  5420.7  825.46
  5499.7  832.82  5616.7  841.76  5634.6  841.87  5670.2  845.42  5688.6  845.28
  5829.9  852.82  5890.3  858.58  5920.5  864.68  5958.1  878.87  5962.8  878.87
#Mann=5,-1,0
  4278.5    0.05       0  5181.8   0.033       0  5185.8    0.05       0
  5258.0    0.12       0  5688.6    0.05       0
Bank Sta=5181.8,5185.8
Exp/Cntr=0.3,0.1

Type RM Length L Ch R = 1,5166,103,103,103
BEGIN DESCRIPTION:
Mapping XS 0704ef3c
END DESCRIPTION:
XS GIS Cut Line= 6
      2283569.71      7160976.65      2283661.39      7160755.19
      2283712.72      7160636.22      2283949.15      7160545.04
      2284035.11      7160452.38      2284834.02      7159385.01
#Sta/Elev= 30
  4135.4  836.19  4277.6  835.67  4348.2  831.09  4446.1  830.27  4554.3  826.57
  4567.0  824.78  4700.8  824.02  4839.3  817.62  4917.3  812.08  5485.7  811.65
  5486.4  811.15  5490.9  811.65  5682.1  812.00  5761.3  814.49  5917.6  827.55
  5938.4  831.28  5967.6  832.59  6032.2  839.56  6038.5  842.16  6061.4  845.91
  6082.2  854.63  6088.5  865.18  6096.8  867.50  6103.1  871.48  6111.4  871.76
  6117.7  877.35  6132.2  877.05  6138.5  881.02  6153.1  881.72  6217.7  882.14
#Mann=3,-1,0
  4135.4    0.05       0  5485.7   0.033       0  5490.9    0.05       0
Bank Sta=5485.7,5490.9
Exp/Cntr=0.3,0.1

Type RM Length L Ch R = 1,5063,176,176,176
BEGIN DESCRIPTION:
Mapping XS 83889bbf
END DESCRIPTION:
XS GIS Cut Line= 6
      2283893.65      7160863.97      2284000.93      7160823.46
      2283969.60      7160682.89      2284126.29      7160494.83
      2284756.12      7159654.31      2284788.39      7159478.02
#Sta/Elev= 30
  4388.7  833.40  4437.1  831.37  4442.5  833.45  4467.3  830.87  4472.6  833.24
  4497.5  830.00  4501.2  833.08  4517.2  833.66  4545.3  829.48  4546.0  828.98
  4550.5  829.48  4626.0  830.10  4646.3  833.81  4983.9  835.61  5033.9  835.55
  5040.2  833.48  5054.8  835.34  5090.2  833.70  5183.9  835.49  5190.2  833.51
  5204.8  836.00  5240.2  833.86  5298.1  835.53  5977.4  833.79  6058.7  845.84
  6089.2  862.61  6095.8  869.91  6100.9  868.12  6118.2  877.85  6121.7  877.85
#Mann=3,-1,0
  4388.7    0.05       0  4545.3   0.033       0  4550.5    0.05       0
Bank Sta=4545.3,4550.5
Exp/Cntr=0.3,0.1

Type RM Length L Ch R = 1,4887,427,427,427
BEGIN DESCRIPTION:
Mapping XS b0ee5b13
END DESCRIPTION:
XS GIS Cut Line= 6
      2284009.24      7161127.11      2284259.61      7160870.40
      2284294.42      7160557.56      2284381.87      7160425.23
      2284794.59      7159950.53      2284942.64      7159959.19
#Sta/Elev= 30
  4231.5  826.76  4342.4  818.75  4582.9  807.60  4627.8  807.96  4650.9  806.46
  4718.2  807.97  4723.3  806.44  4761.5  806.23  4781.7  807.83  4813.8  802.81
  4899.2  799.41  4996.7  792.66  4997.4  792.16  5001.9  792.66  5014.4  792.80
  5035.4  796.01  5057.6  803.52  5086.1  800.28  5164.0  801.11  5560.9  815.21
  5568.5  813.88  5603.6  814.89  5611.2  813.59  5660.6  818.96  5698.3  820.01
  5765.6  825.63  5770.6  821.00  5777.1  820.77  5811.1  828.05  5840.8  829.21
#Mann=5,-1,0
  4231.5    0.05       0  4996.7   0.033       0  5001.9    0.05       0
  5698.3    0.12       0  5811.1    0.05       0
Bank Sta=4996.7,5001.9
Exp/Cntr=0.3,0.1

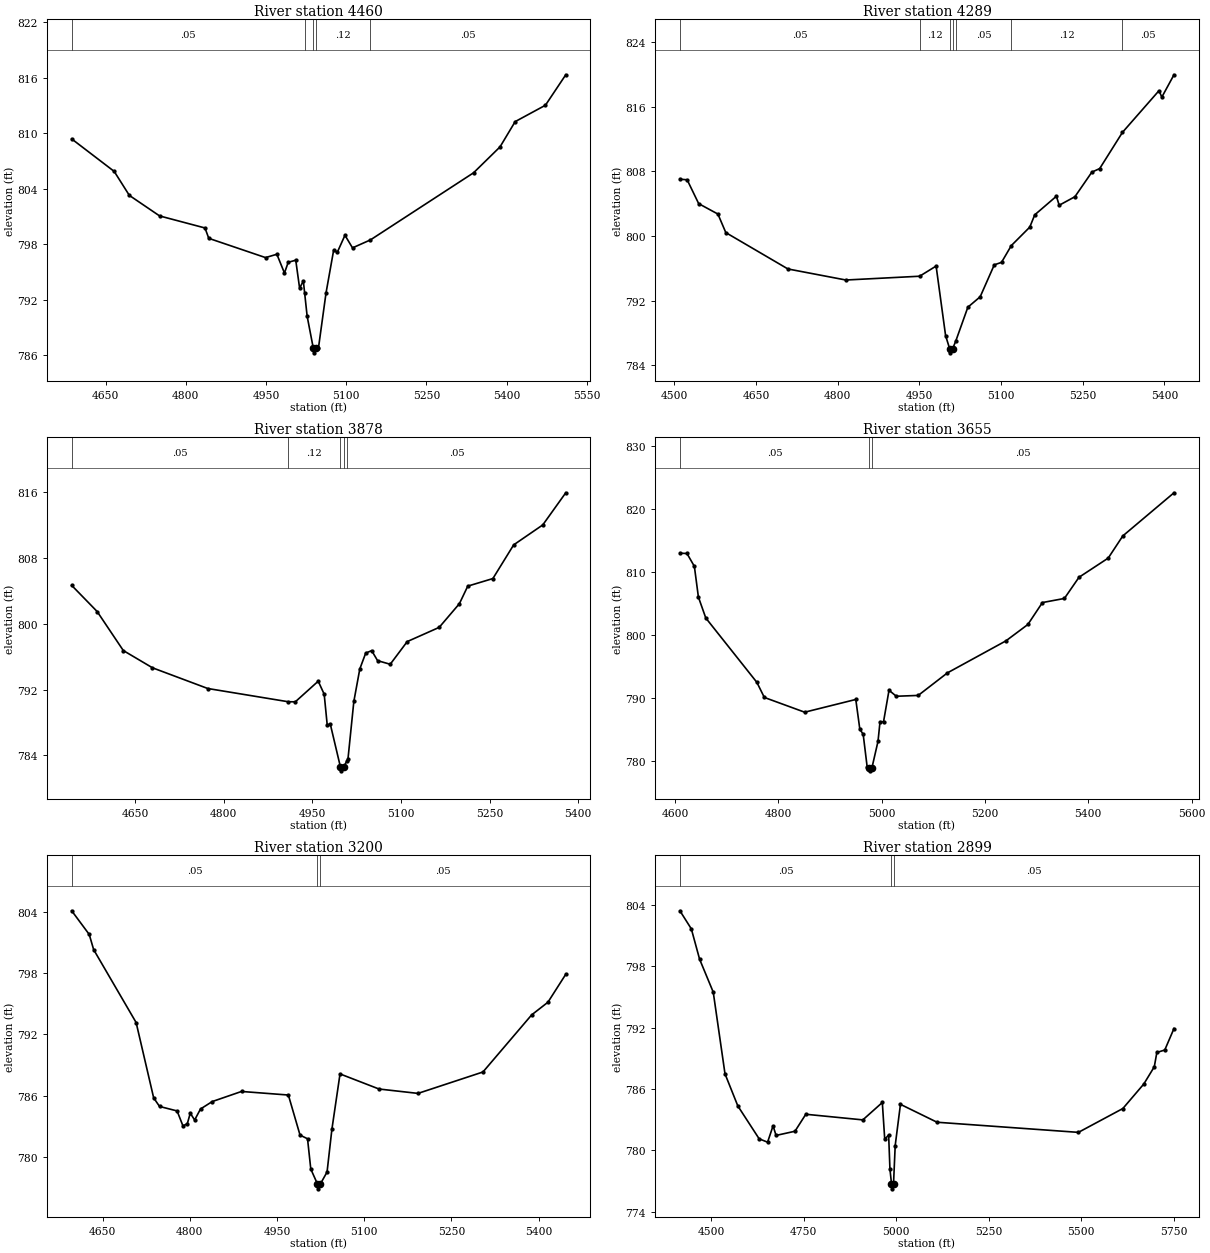
Type RM Length L Ch R = 1,4460,171,171,171
BEGIN DESCRIPTION:
Mapping XS ef34e16a
END DESCRIPTION:
XS GIS Cut Line= 2
      2284242.69      7161106.20      2284898.83      7160456.04
#Sta/Elev= 30
  4586.7  809.37  4666.2  805.86  4694.5  803.27  4751.1  801.05  4835.9  799.75
  4843.0  798.63  4949.1  796.55  4970.3  796.91  4984.5  794.88  4991.5  796.04
  5005.6  796.27  5012.8  793.25  5019.8  794.02  5022.2  792.74  5026.9  790.22
  5038.4  786.76  5039.1  786.26  5043.7  786.76  5048.1  786.80  5062.2  792.73
  5076.4  797.33  5083.5  797.15  5097.6  798.96  5111.7  797.60  5145.2  798.46
  5338.0  805.71  5387.5  808.51  5415.8  811.24  5472.4  813.01  5510.4  816.30
#Mann=5,-1,0
  4586.7    0.05       0  5022.2    0.12       0  5038.4   0.033       0
  5043.7    0.12       0  5145.2    0.05       0
Bank Sta=5038.4,5043.7
Exp/Cntr=0.3,0.1

Type RM Length L Ch R = 1,4289,411,411,411
BEGIN DESCRIPTION:
Mapping XS 96ce4e86
END DESCRIPTION:
XS GIS Cut Line= 5
      2284248.52      7161247.58      2284458.49      7161084.74
      2284586.67      7160960.01      2284691.17      7160937.64
      2285034.53      7161031.14
#Sta/Elev= 30
  4510.3  807.04  4523.6  806.97  4544.8  804.01  4580.1  802.72  4594.6  800.42
  4708.7  795.91  4815.1  794.54  4950.5  795.01  4980.8  796.27  4998.2  787.65
  5005.7  786.01  5006.5  785.51  5011.1  786.01  5017.0  786.99  5039.1  791.17
  5061.7  792.46  5087.6  796.42  5100.9  796.73  5118.9  798.81  5152.8  801.10
  5161.9  802.62  5201.7  804.93  5206.8  803.81  5235.7  804.87  5266.8  807.92
  5281.2  808.36  5323.0  812.85  5390.1  818.02  5395.3  817.22  5417.6  819.99
#Mann=7,-1,0
  4510.3    0.05       0  4950.5    0.12       0  5005.7    0.07       0
  5011.1    0.12       0  5017.0    0.05       0  5118.9    0.12       0
  5323.0    0.05       0
Bank Sta=5005.7,5011.1
Exp/Cntr=0.3,0.1

Type RM Length L Ch R = 1,3878,223,223,223
BEGIN DESCRIPTION:
Mapping XS da45984f
END DESCRIPTION:
XS GIS Cut Line= 4
      2284280.46      7161363.76      2284665.11      7161281.16
      2284890.07      7161303.18      2285047.97      7161154.26
#Sta/Elev= 30
  4542.6  804.69  4585.7  801.51  4630.0  796.76  4679.4  794.66  4773.0  792.14
  4909.1  790.53  4921.2  790.52  4960.0  793.03  4970.1  791.45  4975.3  787.65
  4980.3  787.85  4997.5  782.62  4998.3  782.12  5002.9  782.62  5009.1  783.37
  5010.3  783.51  5020.3  790.56  5030.4  794.52  5040.4  796.45  5050.5  796.75
  5060.5  795.53  5081.9  795.09  5110.7  797.85  5164.8  799.58  5199.0  802.46
  5213.2  804.60  5255.7  805.52  5290.9  809.62  5340.2  812.05  5379.1  815.96
#Mann=5,-1,0
  4542.6    0.05       0  4909.1    0.12       0  4997.5    0.07       0
  5002.9    0.12       0  5009.1    0.05       0
Bank Sta=4997.5,5002.9
Exp/Cntr=0.3,0.1

Type RM Length L Ch R = 1,3655,455,455,455
BEGIN DESCRIPTION:
MDE S 035 3.0
END DESCRIPTION:
XS GIS Cut Line= 3
      2284429.00      7161760.00      2284729.00      7161510.00
      2285129.00      7161110.00
#Sta/Elev= 30
  4609.6  813.03  4623.3  812.98  4637.6  810.94  4645.4  806.07  4659.7  802.75
  4758.6  792.54  4773.0  790.15  4851.1  787.81  4950.0  789.83  4957.8  785.12
  4964.3  784.31  4972.1  779.07  4975.9  779.01  4976.7  778.51  4981.3  779.01
  4993.0  783.19  4996.9  786.30  5003.7  786.30  5014.3  791.29  5028.4  790.34
  5070.8  790.47  5127.4  794.05  5240.5  799.12  5283.0  801.72  5311.2  805.20
  5353.7  805.85  5382.0  809.21  5438.5  812.25  5466.8  815.77  5565.8  822.61
#Mann=3,-1,0
  4609.6    0.05       0  4975.9   0.033       0  4981.3    0.05       0
Bank Sta=4975.9,4981.3
Exp/Cntr=0.3,0.1

Type RM Length L Ch R = 1,3200,301,301,301
BEGIN DESCRIPTION:
MDE S 035 2.0
END DESCRIPTION:
XS GIS Cut Line= 3
      2284479.00      7161860.00      2284879.00      7161910.00
      2285078.99      7161510.03
#Sta/Elev= 30
  4596.6  804.13  4626.8  801.81  4634.4  800.32  4707.5  793.17  4737.7  785.78
  4747.8  784.94  4778.0  784.50  4788.1  783.03  4795.6  783.25  4800.7  784.28
  4808.2  783.61  4818.3  784.69  4838.5  785.42  4888.9  786.41  4969.5  786.06
  4989.6  782.13  5002.5  781.77  5008.1  778.80  5019.4  777.36  5020.1  776.86
  5024.8  777.36  5036.1  778.51  5044.4  782.69  5058.4  788.13  5125.5  786.65
  5192.6  786.22  5304.4  788.32  5388.2  793.92  5416.2  795.16  5446.9  797.90
#Mann=3,-1,0
  4596.6    0.05       0  5019.4   0.033       0  5024.8    0.05       0
Bank Sta=5019.4,5024.8
Exp/Cntr=0.3,0.1

Type RM Length L Ch R = 1,2899,371,371,371
BEGIN DESCRIPTION:
Mapping XS c52b4556
END DESCRIPTION:
XS GIS Cut Line= 3
      2284472.68      7161912.35      2284963.88      7162189.81
      2285524.64      7161660.30
#Sta/Elev= 30
  4415.7  803.43  4446.6  801.66  4468.9  798.70  4505.8  795.48  4537.6  787.49
  4572.3  784.35  4629.9  781.14  4652.7  780.81  4667.5  782.41  4675.6  781.47
  4726.7  781.88  4756.0  783.54  4910.1  782.99  4962.8  784.69  4969.3  781.10
  4979.9  781.51  4983.4  778.18  4987.6  776.75  4988.4  776.25  4993.1  776.75
  4997.6  780.48  5011.8  784.51  5110.7  782.76  5492.8  781.77  5612.9  784.10
  5669.6  786.50  5697.9  788.18  5704.8  789.58  5726.2  789.82  5751.1  791.92
#Mann=3,-1,0
  4415.7    0.05       0  4987.6   0.033       0  4993.1    0.05       0
Bank Sta=4987.6,4993.1
Exp/Cntr=0.3,0.1

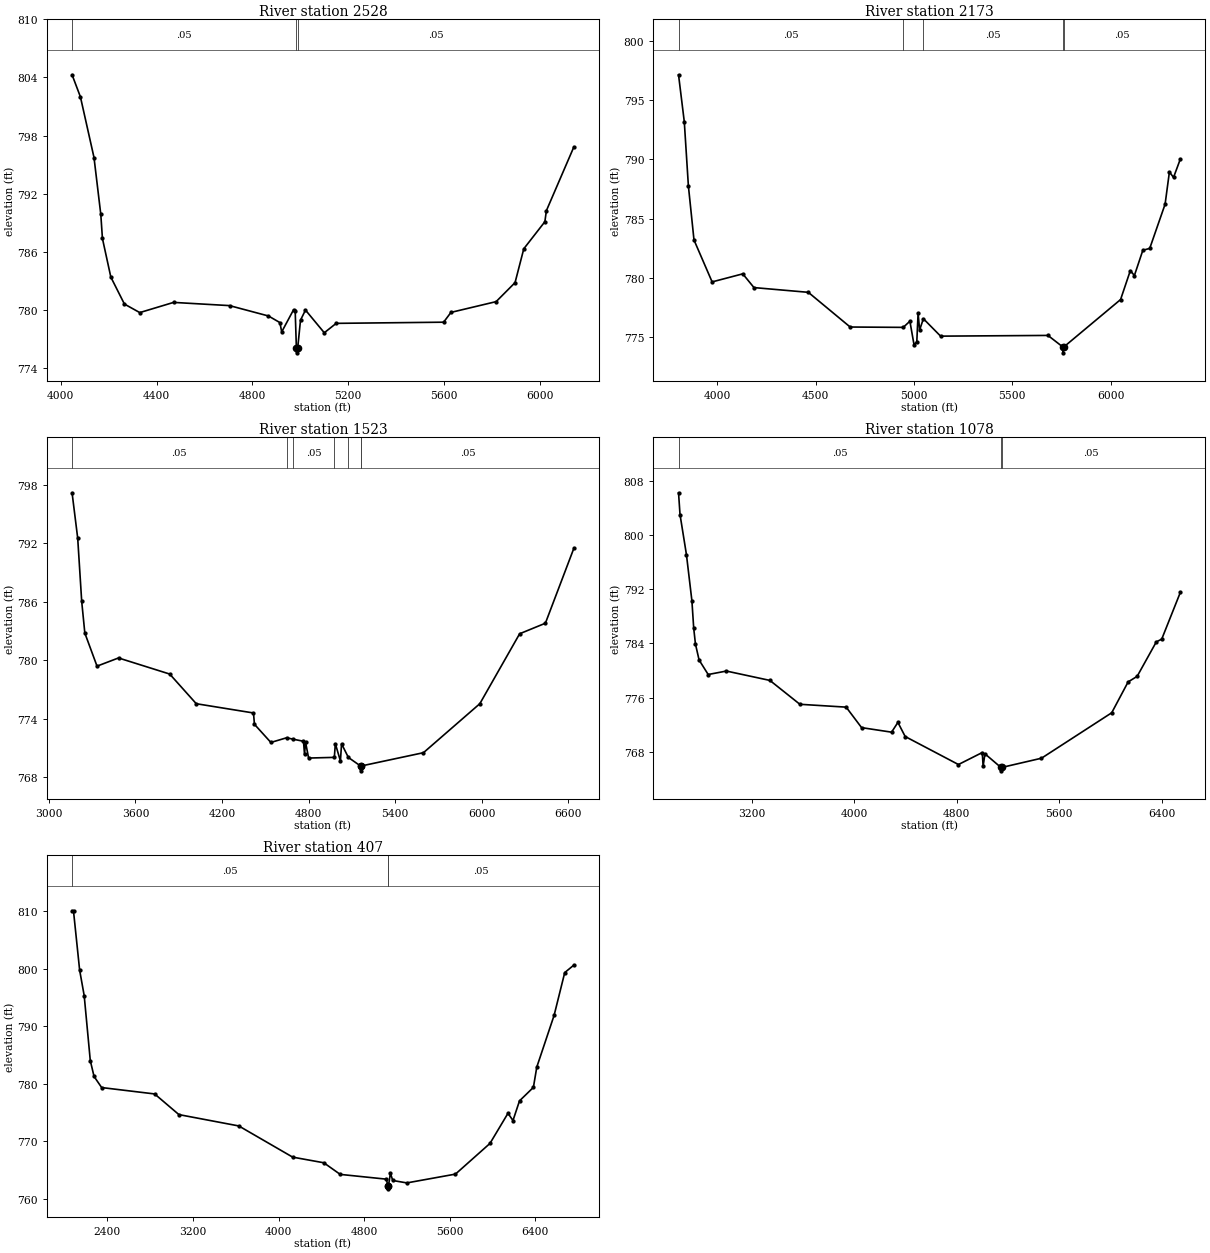
Type RM Length L Ch R = 1,2528,355,355,355
BEGIN DESCRIPTION:
Mapping XS aceccaf1
END DESCRIPTION:
XS GIS Cut Line= 4
      2284458.45      7161931.36      2285038.55      7162558.83
      2285249.18      7162391.39      2285764.60      7161567.31
#Sta/Elev= 30
  4046.8  804.28  4081.7  802.00  4138.4  795.75  4166.8  789.88  4173.6  787.40
  4208.7  783.42  4265.4  780.64  4329.5  779.76  4470.7  780.81  4704.3  780.48
  4867.0  779.41  4914.7  778.73  4922.3  777.77  4972.0  780.06  4978.6  779.95
  4983.6  776.11  4984.4  775.61  4989.1  776.11  5000.8  778.98  5021.6  780.02
  5100.1  777.68  5149.8  778.65  5598.5  778.77  5629.1  779.78  5817.8  780.89
  5896.8  782.85  5933.3  786.34  6021.3  789.13  6027.7  790.27  6142.4  796.84
#Mann=3,-1,0
  4046.8    0.05       0  4983.6   0.033       0  4989.1    0.05       0
Bank Sta=4983.6,4989.1
Exp/Cntr=0.3,0.1

Type RM Length L Ch R = 1,2173,650,650,650
BEGIN DESCRIPTION:
Mapping XS c77db38a
END DESCRIPTION:
XS GIS Cut Line= 3
      2284483.53      7162034.43      2285202.15      7162868.95
      2286136.74      7161759.00
#Sta/Elev= 30
  3802.2  797.15  3831.5  793.18  3852.3  787.77  3880.8  783.20  3973.0  779.66
  4128.8  780.34  4185.9  779.18  4462.3  778.78  4675.2  775.85  4945.0  775.82
  4979.0  776.34  4999.8  774.37  5014.1  774.60  5020.7  777.02  5028.4  775.60
  5047.6  776.55  5135.1  775.08  5681.3  775.14  5756.6  774.17  5757.4  773.67
  5762.1  774.17  6050.6  778.17  6100.1  780.61  6120.9  780.20  6163.8  782.33
  6198.9  782.49  6277.0  786.22  6299.0  788.95  6319.9  788.48  6354.5  790.03
#Mann=5,-1,0
  3802.2    0.05       0  4945.0    0.12       0  5047.6    0.05       0
  5756.6    0.07       0  5762.1    0.05       0
Bank Sta=5756.6,5762.1
Exp/Cntr=0.3,0.1

Type RM Length L Ch R = 1,1523,445,445,445
BEGIN DESCRIPTION:
Mapping XS 502ef379
END DESCRIPTION:
XS GIS Cut Line= 4
      2284464.60      7162049.72      2285391.86      7163110.79
      2285611.49      7163320.74      2286737.11      7161959.66
#Sta/Elev= 30
  3160.3  797.18  3199.4  792.52  3227.1  786.04  3248.8  782.80  3333.3  779.41
  3482.3  780.25  3837.3  778.60  4021.4  775.56  4418.2  774.61  4424.8  773.45
  4538.7  771.59  4648.2  772.07  4690.8  771.93  4764.9  771.71  4772.1  770.36
  4779.0  771.63  4800.4  769.99  4978.7  770.06  4985.8  771.46  5021.0  769.69
  5028.8  771.45  5076.2  770.05  5160.2  769.18  5161.0  768.68  5165.7  769.18
  5596.7  770.54  5987.5  775.56  6263.6  782.73  6442.1  783.81  6639.5  791.49
#Mann=7,-1,0
  3160.3    0.05       0  4648.2    0.12       0  4690.8    0.05       0
  4978.7    0.12       0  5076.2    0.05       0  5160.2    0.07       0
  5165.7    0.05       0
Bank Sta=5160.2,5165.7
Exp/Cntr=0.3,0.1

Type RM Length L Ch R = 1,1078,671,671,671
BEGIN DESCRIPTION:
Mapping XS a2fb3592
END DESCRIPTION:
XS GIS Cut Line= 4
      2284410.30      7162031.91      2285646.97      7163407.67
      2285935.77      7163605.32      2287017.15      7162274.53
#Sta/Elev= 30
  2630.5  806.21  2642.1  803.00  2692.2  797.09  2734.8  790.29  2748.9  786.24
  2762.4  783.92  2790.8  781.56  2861.8  779.42  3003.9  779.93  3343.2  778.55
  3577.2  775.03  3938.2  774.61  4058.5  771.59  4292.5  770.92  4341.8  772.36
  4398.6  770.28  4814.1  766.15  5000.1  767.92  5006.6  765.89  5020.9  767.73
  5145.6  765.72  5146.7  765.22  5151.9  765.72  5462.0  767.08  6009.8  773.78
  6137.9  778.33  6208.3  779.15  6357.7  784.23  6400.1  784.64  6545.1  791.52
#Mann=3,-1,0
  2630.5    0.05       0  5145.6    0.04       0  5151.9    0.05       0
Bank Sta=5145.6,5151.9
Exp/Cntr=0.3,0.1

Type RM Length L Ch R = 1,407,0,0,0
BEGIN DESCRIPTION:
MDE S 035 1.0
END DESCRIPTION:
XS GIS Cut Line= 5
      2284379.00      7162010.00      2285529.97      7163321.37
      2286044.22      7163757.07      2286510.35      7163887.82
      2287176.85      7162228.54
#Sta/Elev= 30
  2069.4  810.04  2083.2  809.92  2140.1  799.73  2182.8  795.29  2239.7  784.01
  2274.9  781.25  2346.0  779.32  2841.4  778.21  3068.2  774.62  3628.0  772.65
  4131.7  767.23  4422.8  766.25  4576.3  764.23  5008.4  763.40  5020.8  762.22
  5021.8  761.72  5027.1  762.22  5045.5  764.43  5067.5  763.17  5199.2  762.75
  5653.6  764.28  5976.2  769.61  6144.7  774.85  6191.3  773.59  6252.4  777.01
  6382.2  779.35  6414.1  782.89  6575.7  791.86  6675.2  799.30  6760.5  800.60
#Mann=3,-1,0
  2069.4    0.05       0  5020.8    0.04       0  5027.1    0.05       0
Bank Sta=5020.8,5027.1
Exp/Cntr=0.3,0.1

Chan Stop Cuts=-1