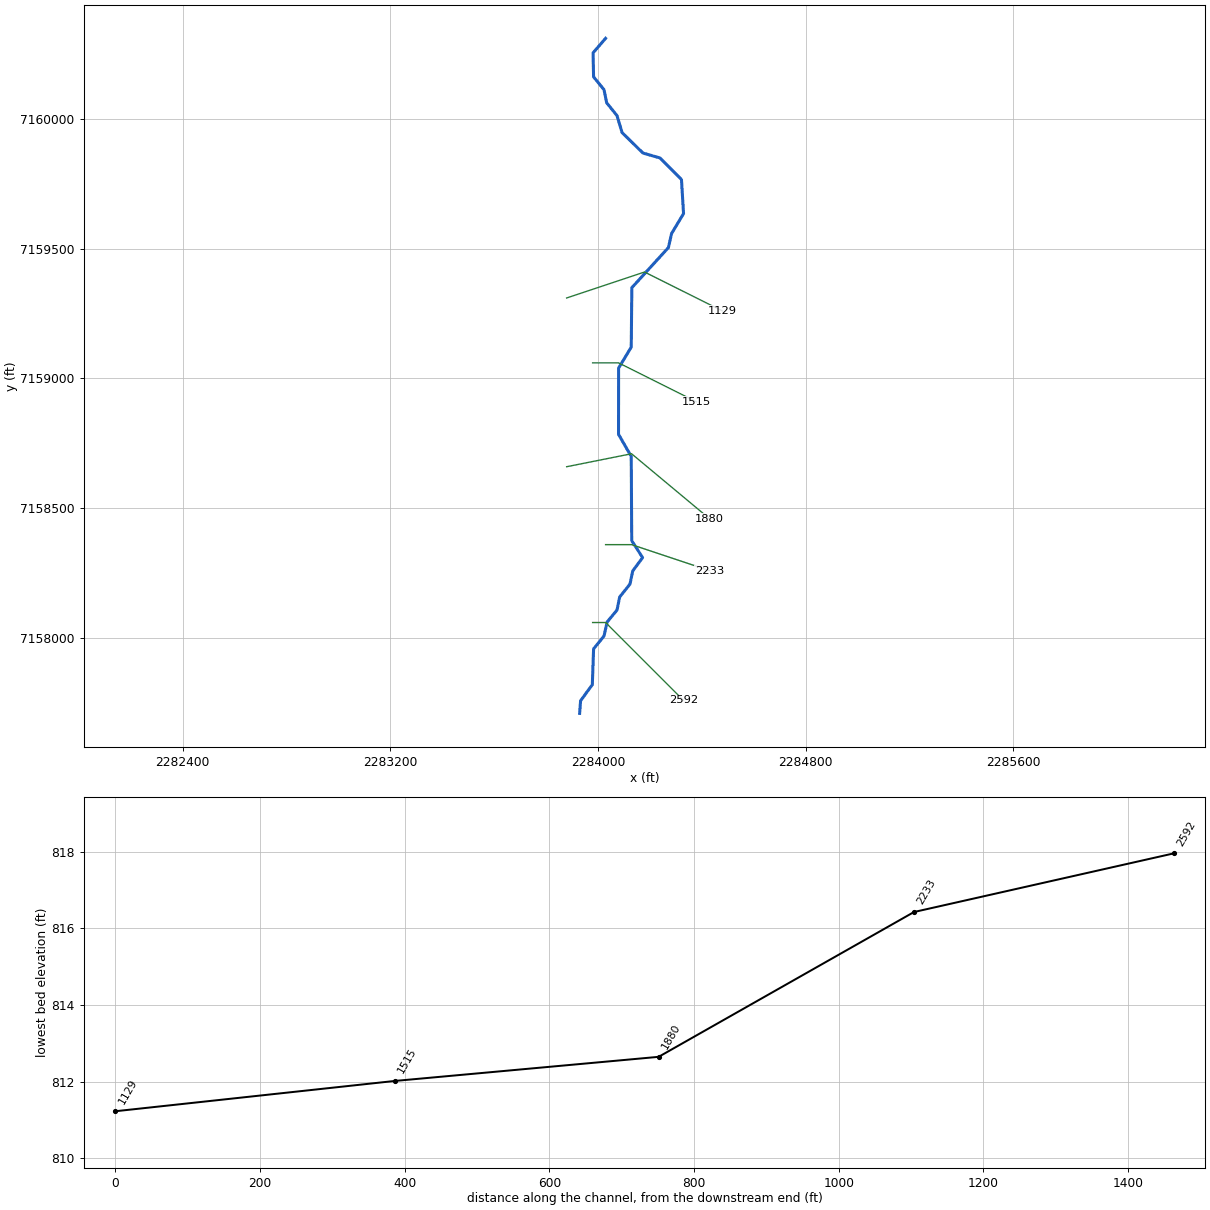
--- MDE S 036.prj (project) ---

Proj Title=MDE S 036 Base Level Engineering
Current Plan=p01
Default Exp/Contr=0.3,0.1
English Units
Geom File=g01
Flow File=f01
Plan File=p01
BEGIN DESCRIPTION:
MDE S 036
END DESCRIPTION:

--- MDE S 036.p01 (plan) ---

Plan Title=Multiple Run
Short Identifier=Multiple
Geom File=g01
Flow File=f01
Subcritical Flow
K Sum by GR= 0
Std Step Tol= 0.01
Critical Tol= 0.01
Num of Std Step Trials= 20
Max Error Tol= 0.3
Flow Tol Ratio= 0.001
Split Flow NTrial= 30
Split Flow Tol= 0.02
Split Flow Ratio= 0.02
Log Output Level= 0
Friction Slope Method= 1
Unsteady Friction Slope Method= 2
Unsteady Bridges Friction Slope Method= 1
Parabolic Critical Depth
Global Vel Dist=  1 , 1 , 1
Global Log Level= 0
CheckData=True
Encroach Param= -1, 0, 0, 0
BEGIN DESCRIPTION:
Multiple Run
END DESCRIPTION:

--- MDE S 036.f01 (steady flow) ---

Flow Title=Multiple
Number of Profiles=7
Profile Names=10-year,25-year,50-year,1pct_min,100-year,1pct_plu,500-year
River Rch & RM= MDE S 036,Reach-1,2592
     537     733     894     542    1082    2158    1586
Boundary for River Rch & Prof#=MDE S 036,Reach-1,1
Up Type=0
Dn Type=3
Dn Slope=0.005
Boundary for River Rch & Prof#=MDE S 036,Reach-1,2
Up Type=0
Dn Type=3
Dn Slope=0.005
Boundary for River Rch & Prof#=MDE S 036,Reach-1,3
Up Type=0
Dn Type=3
Dn Slope=0.005
Boundary for River Rch & Prof#=MDE S 036,Reach-1,4
Up Type=0
Dn Type=3
Dn Slope=0.005
Boundary for River Rch & Prof#=MDE S 036,Reach-1,5
Up Type=0
Dn Type=3
Dn Slope=0.005
Boundary for River Rch & Prof#=MDE S 036,Reach-1,6
Up Type=0
Dn Type=3
Dn Slope=0.005
Boundary for River Rch & Prof#=MDE S 036,Reach-1,7
Up Type=0
Dn Type=3
Dn Slope=0.005

--- MDE S 036.g01 (geometry) ---

Geom Title=Existing Conditions

River Reach=MDE S 036,Reach-1
Reach XY= 30
      2283929.00      7157710.00      2283932.65      7157758.49
      2283977.87      7157820.47      2283982.76      7157958.44
      2284022.88      7158007.82      2284035.08      7158062.20
      2284072.92      7158107.80      2284083.16      7158158.28
      2284122.95      7158207.81      2284133.43      7158258.36
      2284171.47      7158309.99      2284129.66      7158375.16
      2284127.78      7158699.50      2284078.80      7158784.92
      2284079.07      7159039.97      2284127.78      7159120.50
      2284130.05      7159349.57      2284270.86      7159503.94
      2284283.22      7159558.25      2284329.24      7159634.92
      2284321.20      7159766.21      2284238.70      7159849.23
      2284172.94      7159868.15      2284092.61      7159946.76
      2284072.90      7160012.18      2284033.16      7160061.72
      2284022.88      7160112.18      2283982.67      7160161.57
      2283980.77      7160254.17      2284029.00      7160310.00

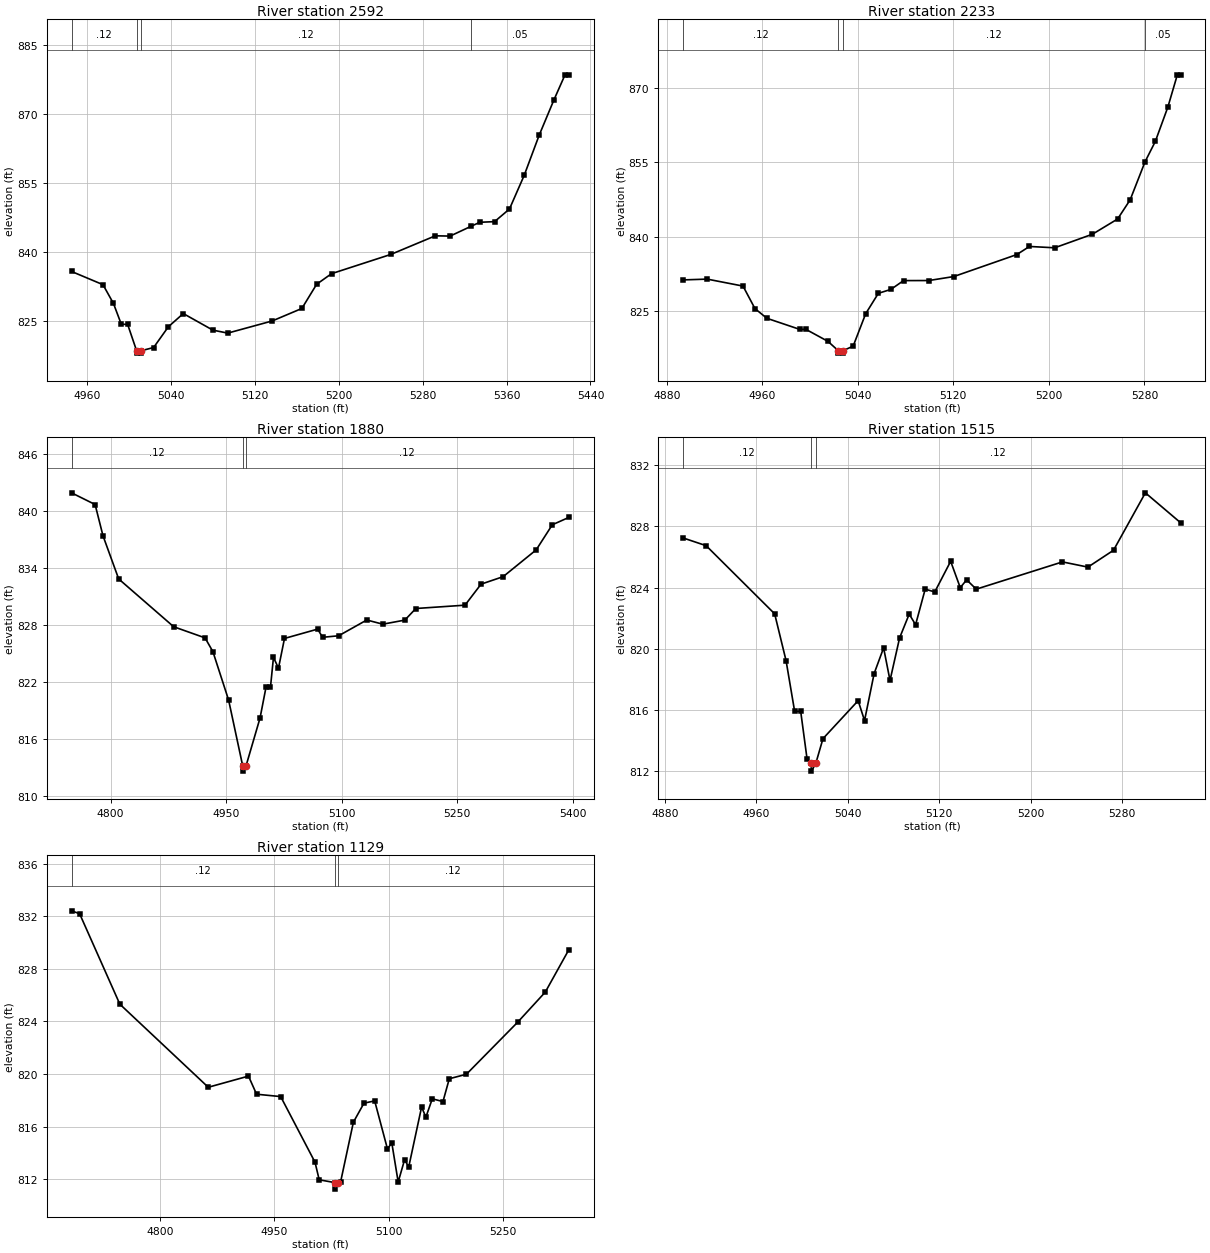
Type RM Length L Ch R = 1,2592,359,359,359
BEGIN DESCRIPTION:
MDE S 036 7.0
END DESCRIPTION:
XS GIS Cut Line= 3
      2283979.01      7158060.00      2284029.00      7158060.00
      2284329.03      7157759.97
#Sta/Elev= 30
  4945.0  835.71  4975.0  832.84  4985.0  828.75  4992.5  824.22  4998.5  824.22
  5007.1  818.46  5007.4  817.96  5010.9  817.96  5011.1  818.46  5023.3  819.18
  5037.4  823.70  5051.6  826.56  5079.8  822.96  5094.0  822.31  5136.4  824.95
  5164.7  827.67  5178.8  832.93  5193.0  835.23  5249.5  839.41  5292.0  843.46
  5306.1  843.40  5326.3  845.55  5334.4  846.40  5348.5  846.54  5362.7  849.28
  5376.8  856.62  5391.0  865.30  5405.1  872.99  5415.7  878.45  5419.3  878.45
#Mann=4,-1,0
  4945.0    0.12       0  5007.1    0.07       0  5011.1    0.12       0
  5326.3    0.05       0
Bank Sta=5007.1,5011.1
Exp/Cntr=0.3,0.1

Type RM Length L Ch R = 1,2233,353,353,353
BEGIN DESCRIPTION:
MDE S 036 6.0
END DESCRIPTION:
XS GIS Cut Line= 3
      2284028.96      7158360.00      2284129.00      7158360.00
      2284429.03      7158259.99
#Sta/Elev= 30
  4893.9  831.23  4913.9  831.39  4943.9  829.98  4953.9  825.43  4963.9  823.47
  4991.4  821.23  4996.6  821.23  5015.0  818.81  5023.6  816.93  5023.8  816.43
  5027.3  816.43  5027.6  816.93  5036.1  817.84  5046.6  824.40  5057.2  828.52
  5067.7  829.31  5078.3  831.09  5099.4  831.10  5120.4  831.91  5173.1  836.35
  5183.7  837.99  5204.8  837.72  5236.4  840.46  5257.5  843.54  5268.0  847.41
  5280.5  855.12  5289.1  859.23  5299.6  866.18  5307.5  872.68  5310.2  872.68
#Mann=4,-1,0
  4893.9    0.12       0  5023.6    0.07       0  5027.6    0.12       0
  5280.5    0.05       0
Bank Sta=5023.6,5027.6
Exp/Cntr=0.3,0.1

Type RM Length L Ch R = 1,1880,365,365,365
BEGIN DESCRIPTION:
MDE S 036 5.0
END DESCRIPTION:
XS GIS Cut Line= 3
      2283879.02      7158660.00      2284129.00      7158710.00
      2284428.96      7158460.03
#Sta/Elev= 30
  4749.3  841.93  4779.9  840.70  4790.1  837.42  4810.5  832.87  4881.9  827.84
  4922.6  826.67  4932.8  825.22  4953.2  820.12  4971.6  813.15  4971.9  812.65
  4975.6  813.15  4994.0  818.25  5001.7  821.47  5007.5  821.47  5011.4  824.62
  5017.9  823.48  5025.7  826.61  5068.7  827.59  5075.2  826.73  5096.0  826.89
  5132.5  828.55  5153.3  828.11  5181.9  828.54  5196.2  829.76  5260.0  830.11
  5280.8  832.32  5309.5  833.11  5352.4  835.93  5373.3  838.57  5394.7  839.34
#Mann=3,-1,0
  4749.3    0.12       0  4971.6    0.07       0  4975.6    0.12       0
Bank Sta=4971.6,4975.6
Exp/Cntr=0.3,0.1

Type RM Length L Ch R = 1,1515,386,386,386
BEGIN DESCRIPTION:
MDE S 036 4.0
END DESCRIPTION:
XS GIS Cut Line= 3
      2283979.02      7159060.00      2284079.00      7159060.00
      2284379.01      7158910.00
#Sta/Elev= 30
  4895.9  827.24  4915.9  826.74  4975.9  822.29  4985.9  819.23  4993.4  815.92
  4998.7  815.92  5004.3  812.80  5007.9  812.52  5008.1  812.02  5011.9  812.52
  5018.2  814.14  5049.0  816.62  5054.6  815.32  5063.0  818.39  5071.3  820.07
  5076.9  817.94  5085.3  820.72  5093.7  822.27  5099.3  821.58  5107.7  823.90
  5116.1  823.72  5130.0  825.72  5138.4  824.00  5144.0  824.51  5152.4  823.90
  5227.9  825.68  5250.2  825.34  5272.6  826.44  5300.5  830.19  5331.3  828.24
#Mann=3,-1,0
  4895.9    0.12       0  5007.9    0.07       0  5011.9    0.12       0
Bank Sta=5007.9,5011.9
Exp/Cntr=0.3,0.1

Type RM Length L Ch R = 1,1129,0,0,0
BEGIN DESCRIPTION:
MDE S 036 3.0
END DESCRIPTION:
XS GIS Cut Line= 3
      2283878.97      7159309.99      2284179.00      7159410.00
      2284479.03      7159259.99
#Sta/Elev= 30
  4684.3  832.43  4694.9  832.21  4747.6  825.32  4863.5  818.99  4916.2  819.84
  4926.8  818.46  4958.4  818.28  5003.4  813.28  5008.9  811.94  5029.3  811.73
  5029.6  811.23  5033.3  811.73  5036.9  811.77  5053.7  816.33  5067.6  817.78
  5081.6  817.95  5098.4  814.28  5104.0  814.77  5112.4  811.77  5120.7  813.45
  5126.3  812.94  5143.1  817.49  5148.7  816.71  5157.1  818.11  5171.1  817.90
  5179.4  819.64  5201.8  819.98  5268.9  823.94  5305.2  826.24  5336.0  829.46
#Mann=3,-1,0
  4684.3    0.12       0  5029.3    0.07       0  5033.3    0.12       0
Bank Sta=5029.3,5033.3
Exp/Cntr=0.3,0.1

Chan Stop Cuts=-1