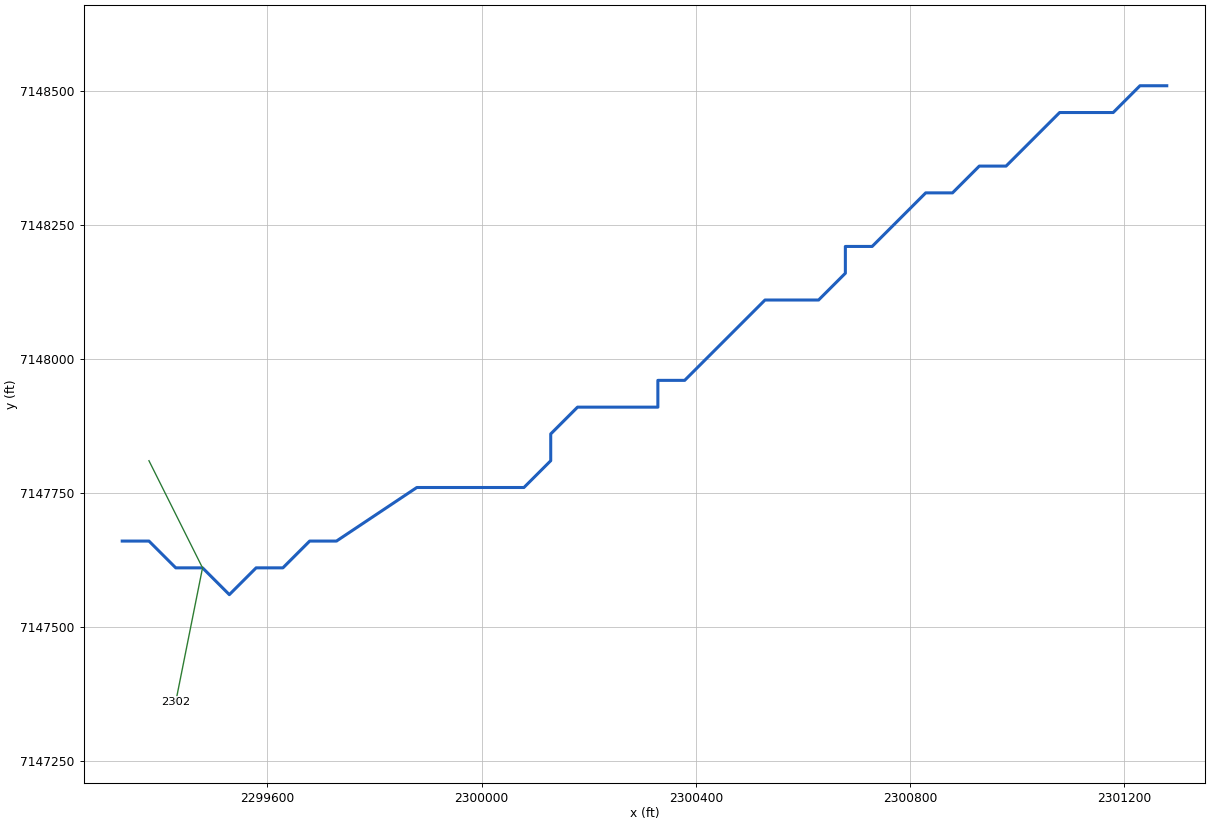
--- MDE S 037.prj (project) ---

Proj Title=MDE S 037 Base Level Engineering
Current Plan=p01
Default Exp/Contr=0.3,0.1
English Units
Geom File=g01
Flow File=f01
Plan File=p01
BEGIN DESCRIPTION:
MDE S 037
END DESCRIPTION:

--- MDE S 037.p01 (plan) ---

Plan Title=Multiple Run
Short Identifier=Multiple
Geom File=g01
Flow File=f01
Subcritical Flow
K Sum by GR= 0
Std Step Tol= 0.01
Critical Tol= 0.01
Num of Std Step Trials= 20
Max Error Tol= 0.3
Flow Tol Ratio= 0.001
Split Flow NTrial= 30
Split Flow Tol= 0.02
Split Flow Ratio= 0.02
Log Output Level= 0
Friction Slope Method= 1
Unsteady Friction Slope Method= 2
Unsteady Bridges Friction Slope Method= 1
Parabolic Critical Depth
Global Vel Dist=  1 , 1 , 1
Global Log Level= 0
CheckData=True
Encroach Param= -1, 0, 0, 0
BEGIN DESCRIPTION:
Multiple Run
END DESCRIPTION:

--- MDE S 037.f01 (steady flow) ---

Flow Title=Multiple
Number of Profiles=7
Profile Names=10-year,25-year,50-year,1pct_min,100-year,1pct_plu,500-year
River Rch & RM= MDE S 037,Reach-1,2302
     520     711     870     529    1056    2108    1559
Boundary for River Rch & Prof#=MDE S 037,Reach-1,1
Up Type=0
Dn Type=3
Dn Slope=0.005
Boundary for River Rch & Prof#=MDE S 037,Reach-1,2
Up Type=0
Dn Type=3
Dn Slope=0.005
Boundary for River Rch & Prof#=MDE S 037,Reach-1,3
Up Type=0
Dn Type=3
Dn Slope=0.005
Boundary for River Rch & Prof#=MDE S 037,Reach-1,4
Up Type=0
Dn Type=3
Dn Slope=0.005
Boundary for River Rch & Prof#=MDE S 037,Reach-1,5
Up Type=0
Dn Type=3
Dn Slope=0.005
Boundary for River Rch & Prof#=MDE S 037,Reach-1,6
Up Type=0
Dn Type=3
Dn Slope=0.005
Boundary for River Rch & Prof#=MDE S 037,Reach-1,7
Up Type=0
Dn Type=3
Dn Slope=0.005

--- MDE S 037.g01 (geometry) ---

Geom Title=Existing Conditions

River Reach=MDE S 037,Reach-1
Reach XY= 30
      2299329.00      7147660.00      2299379.00      7147660.00
      2299429.00      7147610.00      2299479.00      7147610.00
      2299529.00      7147560.00      2299579.00      7147610.00
      2299629.00      7147610.00      2299679.00      7147660.00
      2299729.00      7147660.00      2299879.00      7147760.00
      2300079.00      7147760.00      2300129.00      7147810.00
      2300129.00      7147860.00      2300179.00      7147910.00
      2300329.00      7147910.00      2300329.00      7147960.00
      2300379.00      7147960.00      2300529.00      7148110.00
      2300629.00      7148110.00      2300679.00      7148160.00
      2300679.00      7148210.00      2300729.00      7148210.00
      2300829.00      7148310.00      2300879.00      7148310.00
      2300929.00      7148360.00      2300979.00      7148360.00
      2301079.00      7148460.00      2301179.00      7148460.00
      2301229.00      7148510.00      2301279.00      7148510.00

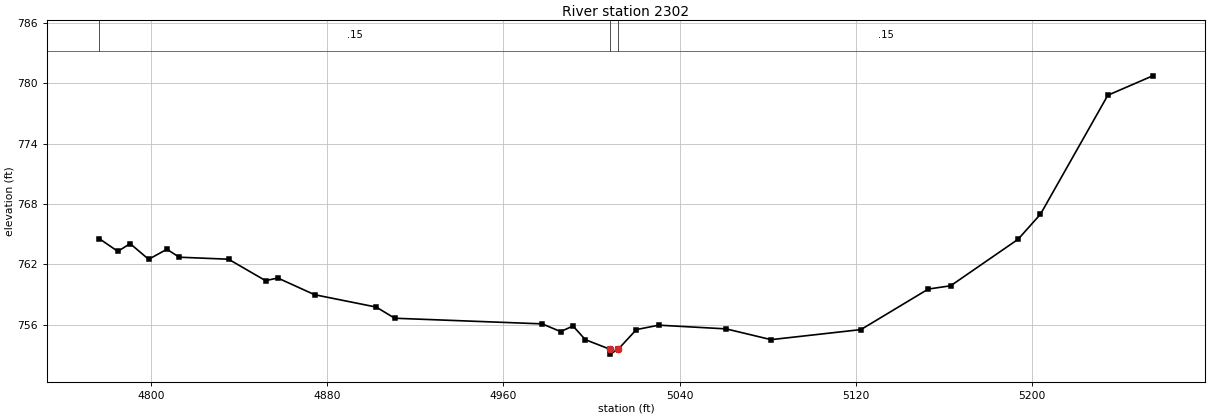
Type RM Length L Ch R = 1,2302,0,0,0
BEGIN DESCRIPTION:
MDE S 037 1.0
END DESCRIPTION:
XS GIS Cut Line= 3
      2299379.00      7147809.99      2299479.00      7147610.00
      2299428.99      7147359.95
#Sta/Elev= 30
  4776.4  764.54  4784.8  763.28  4790.4  764.05  4798.8  762.49  4807.1  763.49
  4812.7  762.70  4835.1  762.50  4851.9  760.37  4857.5  760.63  4874.2  758.97
  4902.2  757.74  4910.6  756.63  4977.6  756.07  4986.0  755.30  4991.6  755.86
  4997.2  754.50  5008.2  753.56  5008.4  753.06  5012.2  753.56  5020.4  755.50
  5030.6  755.94  5061.2  755.57  5081.6  754.50  5122.4  755.50  5153.0  759.53
  5163.2  759.86  5193.8  764.48  5204.0  766.98  5234.6  778.81  5255.0  780.74
#Mann=3,-1,0
  4776.4    0.15       0  5008.2    0.05       0  5012.2    0.15       0
Bank Sta=5008.2,5012.2
Exp/Cntr=0.3,0.1

Chan Stop Cuts=-1