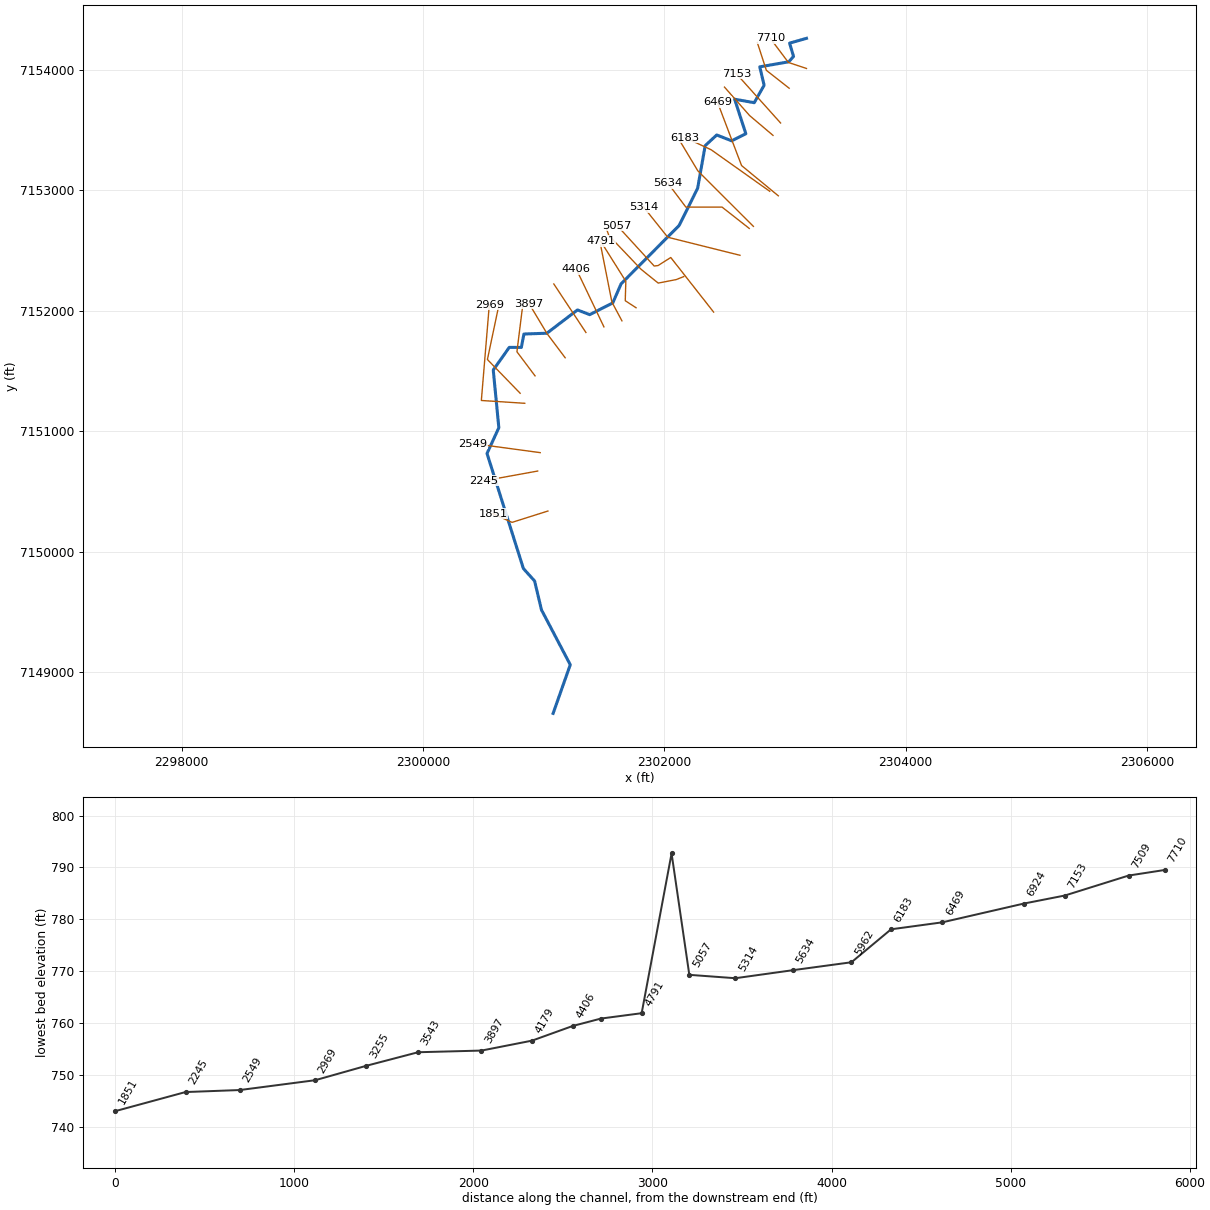
--- MDE S 038.prj (project) ---

Proj Title=MDE S 038 Base Level Engineering
Current Plan=p01
Default Exp/Contr=0.3,0.1
English Units
Geom File=g01
Flow File=f01
Plan File=p01
BEGIN DESCRIPTION:
MDE S 038
END DESCRIPTION:

--- MDE S 038.p01 (plan) ---

Plan Title=Multiple Run
Short Identifier=Multiple
Geom File=g01
Flow File=f01
Subcritical Flow
K Sum by GR= 0
Std Step Tol= 0.01
Critical Tol= 0.01
Num of Std Step Trials= 20
Max Error Tol= 0.3
Flow Tol Ratio= 0.001
Split Flow NTrial= 30
Split Flow Tol= 0.02
Split Flow Ratio= 0.02
Log Output Level= 0
Friction Slope Method= 1
Unsteady Friction Slope Method= 2
Unsteady Bridges Friction Slope Method= 1
Parabolic Critical Depth
Global Vel Dist=  1 , 1 , 1
Global Log Level= 0
CheckData=True
Encroach Param= -1, 0, 0, 0
BEGIN DESCRIPTION:
Multiple Run
END DESCRIPTION:

--- MDE S 038.f01 (steady flow) ---

Flow Title=Multiple
Number of Profiles=7
Profile Names=10-year,25-year,50-year,1pct_min,100-year,1pct_plu,500-year
River Rch & RM= MDE S 038,Reach-1,7710
     684     943    1158     707    1410    2814    2095
River Rch & RM= MDE S 038,Reach-1,2549
     668     922    1133     691    1379    2752    2050
Boundary for River Rch & Prof#=MDE S 038,Reach-1,1
Up Type=0
Dn Type=3
Dn Slope=0.00508
Boundary for River Rch & Prof#=MDE S 038,Reach-1,2
Up Type=0
Dn Type=3
Dn Slope=0.00508
Boundary for River Rch & Prof#=MDE S 038,Reach-1,3
Up Type=0
Dn Type=3
Dn Slope=0.00508
Boundary for River Rch & Prof#=MDE S 038,Reach-1,4
Up Type=0
Dn Type=3
Dn Slope=0.00508
Boundary for River Rch & Prof#=MDE S 038,Reach-1,5
Up Type=0
Dn Type=3
Dn Slope=0.00508
Boundary for River Rch & Prof#=MDE S 038,Reach-1,6
Up Type=0
Dn Type=3
Dn Slope=0.00508
Boundary for River Rch & Prof#=MDE S 038,Reach-1,7
Up Type=0
Dn Type=3
Dn Slope=0.00508

--- MDE S 038.g01 (geometry) ---

Geom Title=Existing Conditions

River Reach=MDE S 038,Reach-1
Reach XY= 30
      2303179.00      7154260.00      2303039.02      7154220.04
      2303071.75      7154109.67      2303032.01      7154065.45
      2302791.87      7154023.42      2302827.95      7153870.65
      2302746.08      7153726.14      2302583.62      7153754.90
      2302676.38      7153468.46      2302558.84      7153409.71
      2302435.03      7153458.38      2302339.47      7153369.83
      2302276.75      7153015.93      2302123.44      7152707.64
      2301642.47      7152223.56      2301573.56      7152065.25
      2301382.40      7151967.84      2301280.65      7152006.84
      2301027.45      7151813.75      2300836.97      7151807.06
      2300815.58      7151695.94      2300715.64      7151696.36
      2300582.75      7151508.45      2300629.06      7151029.99
      2300531.16      7150815.98      2300832.56      7149861.47
      2300925.38      7149758.50      2300982.55      7149518.50
      2301221.18      7149063.42      2301079.00      7148660.00

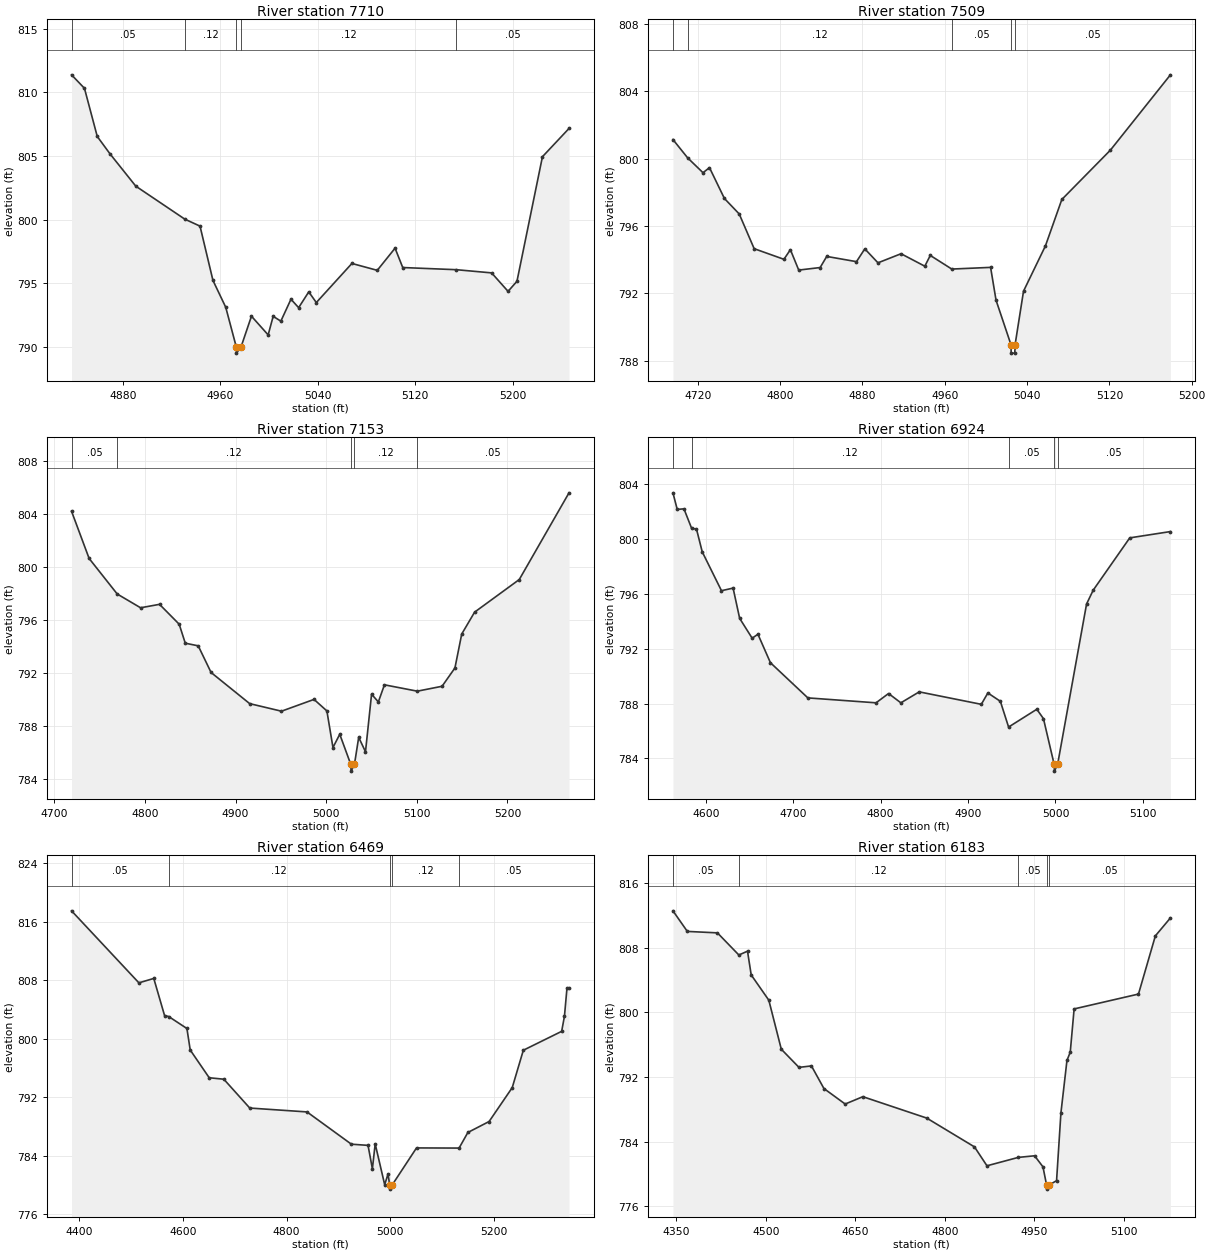
Type RM Length L Ch R = 1,7710,201,201,201
BEGIN DESCRIPTION:
MDE S 038 19.0
END DESCRIPTION:
XS GIS Cut Line= 3
      2303179.02      7154009.99      2303029.00      7154060.00
      2302879.02      7154259.97
#Sta/Elev= 30
  4838.0  811.37  4848.6  810.31  4859.1  806.53  4869.6  805.16  4890.7  802.63
  4930.9  800.04  4943.4  799.49  4954.0  795.23  4964.5  793.12  4973.1  790.02
  4973.3  789.52  4977.1  790.02  4985.6  792.42  4999.3  790.95  5003.4  792.41
  5009.7  792.03  5018.0  793.75  5024.3  793.09  5032.6  794.33  5038.8  793.49
  5068.0  796.56  5088.8  796.02  5103.4  797.76  5109.7  796.24  5153.7  796.07
  5182.6  795.82  5196.1  794.37  5203.4  795.16  5224.3  804.94  5246.1  807.16
#Mann=5,-1,0
  4838.0    0.05       0  4930.9    0.12       0  4973.1    0.07       0
  4977.1    0.12       0  5153.7    0.05       0
Bank Sta=4973.1,4977.1
Exp/Cntr=0.3,0.1

Type RM Length L Ch R = 1,7509,356,356,356
BEGIN DESCRIPTION:
Mapping XS df3aff9d
END DESCRIPTION:
XS GIS Cut Line= 3
      2303035.59      7153845.93      2302846.43      7153994.62
      2302771.45      7154225.44
#Sta/Elev= 30
  4696.0  801.13  4710.3  800.04  4725.2  799.16  4731.5  799.46  4746.0  797.63
  4760.4  796.71  4774.9  794.65  4803.8  794.02  4810.1  794.59  4818.2  793.38
  4839.0  793.53  4845.4  794.19  4874.3  793.88  4882.4  794.64  4895.2  793.81
  4917.6  794.35  4940.7  793.61  4946.0  794.25  4966.9  793.44  5004.6  793.54
  5009.9  791.59  5024.4  788.95  5024.6  788.45  5028.1  788.45  5028.4  788.95
  5036.6  792.13  5057.9  794.82  5073.8  797.57  5121.0  800.50  5179.3  804.97
#Mann=5,-1,0
  4696.0    0.05       0  4710.3    0.12       0  4966.9    0.05       0
  5024.4   0.033       0  5028.4    0.05       0
Bank Sta=5024.4,5028.4
Exp/Cntr=0.3,0.1

Type RM Length L Ch R = 1,7153,229,229,229
BEGIN DESCRIPTION:
Mapping XS 46f8baec
END DESCRIPTION:
XS GIS Cut Line= 2
      2302964.43      7153557.74      2302597.82      7153966.40
#Sta/Elev= 30
  4719.0  804.21  4738.4  800.65  4769.4  797.97  4795.2  796.93  4816.1  797.19
  4837.8  795.69  4844.5  794.26  4858.8  794.06  4873.0  792.05  4915.6  789.70
  4950.7  789.13  4986.6  790.02  5000.8  789.15  5007.5  786.39  5015.0  787.39
  5027.2  785.11  5027.5  784.61  5031.2  785.11  5035.9  787.16  5043.4  786.07
  5050.1  790.41  5057.6  789.83  5064.3  791.12  5100.6  790.64  5127.9  791.01
  5142.1  792.39  5149.6  794.95  5163.8  796.60  5213.1  799.06  5268.0  805.60
#Mann=5,-1,0
  4719.0    0.05       0  4769.4    0.12       0  5027.2    0.07       0
  5031.2    0.12       0  5100.6    0.05       0
Bank Sta=5027.2,5031.2
Exp/Cntr=0.3,0.1

Type RM Length L Ch R = 1,6924,455,455,455
BEGIN DESCRIPTION:
Mapping XS e2832c73
END DESCRIPTION:
XS GIS Cut Line= 3
      2302901.46      7153454.98      2302707.82      7153619.16
      2302499.30      7153855.43
#Sta/Elev= 30
  4562.5  803.39  4567.4  802.18  4575.1  802.22  4583.9  800.79  4589.4  800.75
  4596.0  799.08  4618.0  796.24  4631.3  796.43  4638.8  794.22  4653.1  792.77
  4659.7  793.06  4674.0  790.98  4716.8  788.41  4794.8  788.05  4809.1  788.73
  4823.2  788.05  4844.2  788.85  4915.2  787.94  4922.7  788.77  4937.0  788.16
  4946.4  786.28  4978.7  787.58  4986.3  786.89  4998.5  783.56  4998.8  783.06
  5002.5  783.56  5035.6  795.27  5043.2  796.28  5085.0  800.10  5131.5  800.56
#Mann=5,-1,0
  4562.5    0.05       0  4583.9    0.12       0  4946.4    0.05       0
  4998.5   0.033       0  5002.5    0.05       0
Bank Sta=4998.5,5002.5
Exp/Cntr=0.3,0.1

Type RM Length L Ch R = 1,6469,286,286,286
BEGIN DESCRIPTION:
Mapping XS 2aa601ec
END DESCRIPTION:
XS GIS Cut Line= 3
      2302945.59      7152953.43      2302640.88      7153204.62
      2302440.53      7153732.37
#Sta/Elev= 30
  4385.4  817.48  4515.3  807.64  4544.0  808.24  4564.8  803.17  4572.9  803.03
  4607.9  801.40  4614.3  798.46  4650.9  794.67  4679.1  794.47  4729.1  790.53
  4839.5  790.00  4925.1  785.59  4957.2  785.43  4965.6  782.23  4971.0  785.63
  4989.3  780.06  4995.8  781.52  4999.1  779.95  4999.4  779.45  5003.1  779.95
  5050.7  785.08  5132.8  785.06  5149.7  787.19  5190.7  788.69  5235.3  793.32
  5256.7  798.43  5330.6  801.01  5336.0  803.07  5340.9  806.94  5344.8  806.94
#Mann=5,-1,0
  4385.4    0.05       0  4572.9    0.12       0  4999.1    0.07       0
  5003.1    0.12       0  5132.8    0.05       0
Bank Sta=4999.1,5003.1
Exp/Cntr=0.3,0.1

Type RM Length L Ch R = 1,6183,221,221,221
BEGIN DESCRIPTION:
Mapping XS 2456f75d
END DESCRIPTION:
XS GIS Cut Line= 4
      2302874.10      7152991.42      2302678.01      7153130.55
      2302389.39      7153335.33      2302172.84      7153436.41
#Sta/Elev= 30
  4344.4  812.58  4368.5  810.03  4418.9  809.85  4454.8  807.11  4469.3  807.58
  4475.5  804.64  4505.0  801.51  4525.9  795.44  4555.5  793.19  4576.4  793.37
  4597.3  790.57  4632.9  788.65  4662.5  789.56  4769.5  786.91  4849.5  783.34
  4870.4  781.00  4922.9  782.04  4950.2  782.24  4964.2  780.87  4970.3  778.61
  4970.5  778.11  4974.3  778.61  4987.0  779.16  4994.3  787.56  5004.4  794.05
  5009.9  795.07  5016.4  800.43  5124.2  802.27  5152.5  809.48  5177.7  811.70
#Mann=5,-1,0
  4344.4    0.05       0  4454.8    0.12       0  4922.9    0.05       0
  4970.3   0.033       0  4974.3    0.05       0
Bank Sta=4970.3,4974.3
Exp/Cntr=0.3,0.1

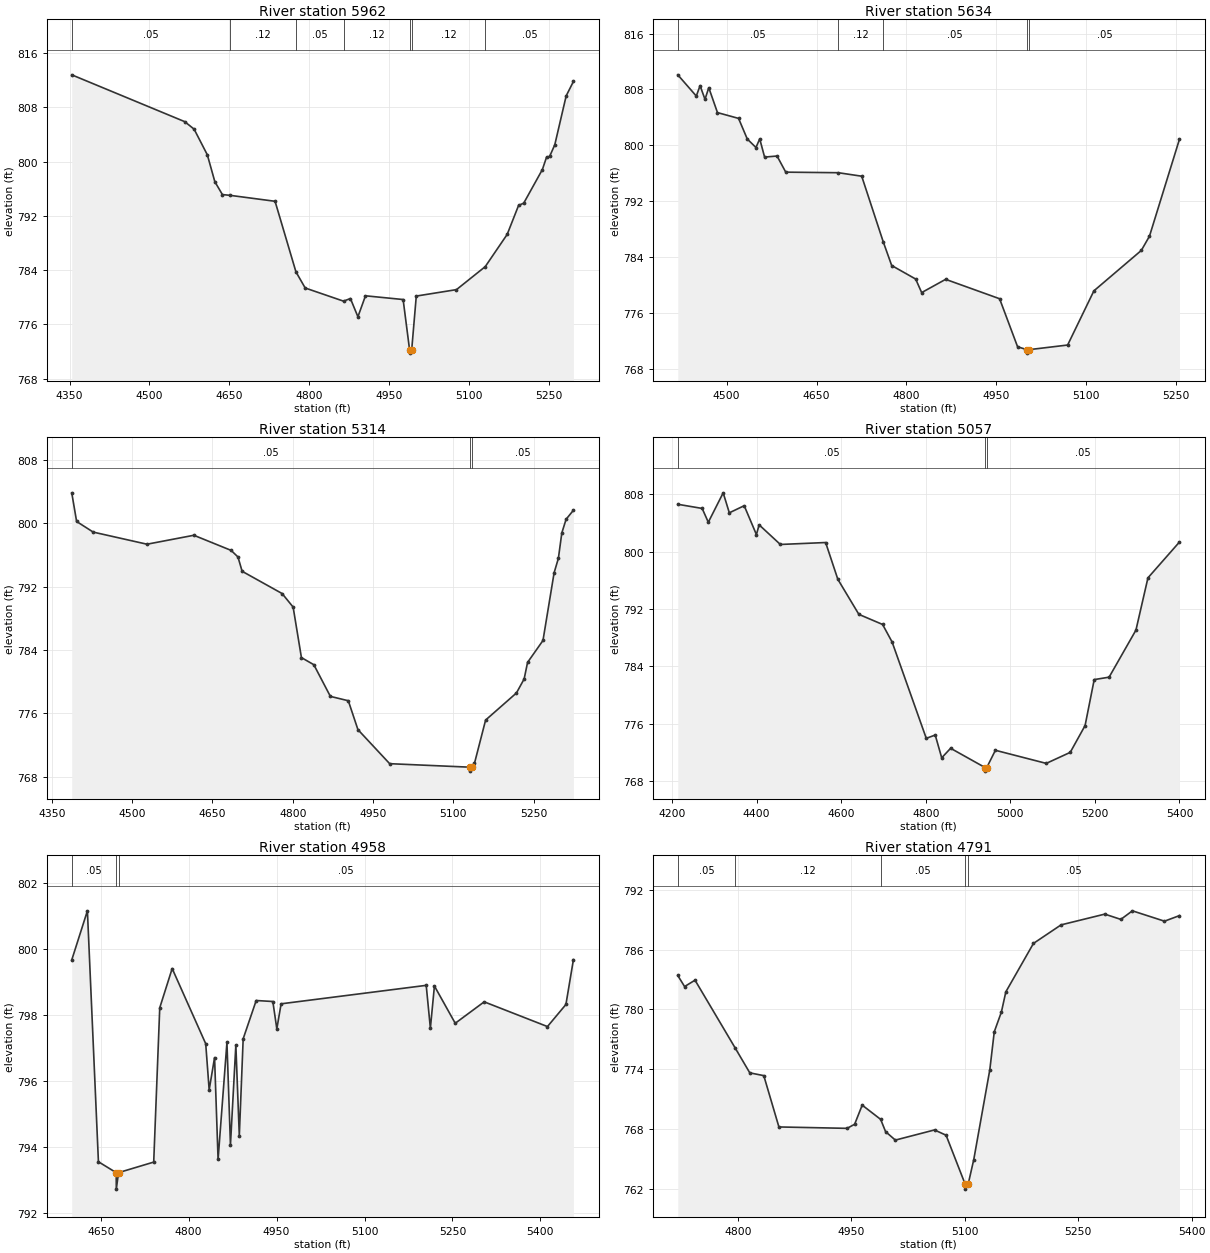
Type RM Length L Ch R = 1,5962,328,328,328
BEGIN DESCRIPTION:
MDE S 038 16.0
END DESCRIPTION:
XS GIS Cut Line= 4
      2302739.01      7152699.99      2302579.00      7152860.00
      2302279.00      7153160.00      2302129.00      7153410.00
#Sta/Elev= 30
  4354.0  812.79  4566.1  805.89  4583.8  804.78  4608.6  801.00  4622.7  797.04
  4636.9  795.14  4651.0  795.03  4735.8  794.15  4775.0  783.75  4792.4  781.37
  4864.4  779.43  4877.3  779.82  4891.4  777.13  4905.6  780.22  4976.3  779.67
  4988.4  772.27  4988.7  771.77  4992.4  772.27  5001.0  780.18  5076.5  781.13
  5130.5  784.52  5171.7  789.27  5193.1  793.54  5202.8  793.88  5237.8  798.83
  5245.6  800.65  5251.4  800.76  5261.1  802.48  5282.5  809.69  5296.1  811.81
#Mann=7,-1,0
  4354.0    0.05       0  4651.0    0.12       0  4775.0    0.05       0
  4864.4    0.12       0  4988.4    0.07       0  4992.4    0.12       0
  5130.5    0.05       0
Bank Sta=4988.4,4992.4
Exp/Cntr=0.3,0.1

Type RM Length L Ch R = 1,5634,320,320,320
BEGIN DESCRIPTION:
MDE S 038 15.0
END DESCRIPTION:
XS GIS Cut Line= 4
      2302704.72      7152683.12      2302479.00      7152860.00
      2302179.00      7152860.00      2302028.98      7153060.03
#Sta/Elev= 30
  4418.5  810.10  4449.4  807.06  4455.7  808.55  4463.9  806.59  4470.2  808.26
  4484.7  804.69  4519.9  803.86  4534.4  800.91  4548.9  799.69  4555.2  800.93
  4563.3  798.32  4584.1  798.47  4598.6  796.16  4686.3  796.08  4725.3  795.58
  4761.1  786.21  4775.3  782.79  4815.3  780.85  4825.3  778.91  4865.3  780.81
  4955.3  778.03  4985.3  771.15  5000.8  770.74  5001.0  770.24  5004.8  770.74
  5068.8  771.40  5112.6  779.16  5191.7  784.95  5205.3  786.99  5255.3  800.87
#Mann=5,-1,0
  4418.5    0.05       0  4686.3    0.12       0  4761.1    0.05       0
  5000.8   0.033       0  5004.8    0.05       0
Bank Sta=5000.8,5004.8
Exp/Cntr=0.3,0.1

Type RM Length L Ch R = 1,5314,257,257,257
BEGIN DESCRIPTION:
MDE S 038 14.0
END DESCRIPTION:
XS GIS Cut Line= 4
      2302627.87      7152460.29      2302229.00      7152560.00
      2302029.00      7152610.00      2301828.97      7152860.04
#Sta/Elev= 30
  4387.1  803.85  4396.2  800.23  4427.2  798.89  4527.7  797.36  4615.3  798.49
  4684.9  796.58  4697.7  795.75  4705.5  793.94  4780.2  791.13  4800.8  789.42
  4816.3  783.04  4839.5  782.14  4870.4  778.14  4903.9  777.59  4921.9  773.94
  4981.2  769.64  5130.5  769.20  5130.7  768.70  5134.5  769.20  5139.7  769.69
  5160.5  775.15  5218.1  778.57  5232.5  780.34  5238.9  782.43  5267.7  785.20
  5288.5  793.75  5296.5  795.58  5302.9  798.78  5310.9  800.51  5324.6  801.65
#Mann=3,-1,0
  4387.1    0.05       0  5130.5   0.033       0  5134.5    0.05       0
Bank Sta=5130.5,5134.5
Exp/Cntr=0.3,0.1

Type RM Length L Ch R = 1,5057,99,99,99
BEGIN DESCRIPTION:
Mapping XS b4ec2474
END DESCRIPTION:
XS GIS Cut Line= 6
      2302409.28      7151989.18      2302164.55      7152301.00
      2302054.02      7152441.83      2301948.55      7152374.94
      2301916.59      7152371.14      2301610.21      7152706.18
#Sta/Elev= 30
  4213.4  806.61  4271.1  806.03  4285.6  804.10  4320.8  808.21  4335.3  805.42
  4370.5  806.41  4399.4  802.38  4405.8  803.74  4456.0  801.00  4563.1  801.27
  4592.0  796.13  4641.7  791.24  4697.8  789.83  4720.3  787.38  4801.1  773.93
  4822.3  774.39  4837.6  771.21  4858.7  772.54  4940.2  769.85  4940.4  769.35
  4944.2  769.85  4964.6  772.26  5084.9  770.43  5141.6  771.97  5176.7  775.71
  5198.3  782.13  5233.5  782.47  5297.0  789.04  5325.4  796.34  5399.9  801.34
#Mann=3,-1,0
  4213.4    0.05       0  4940.2   0.033       0  4944.2    0.05       0
Bank Sta=4940.2,4944.2
Exp/Cntr=0.3,0.1

Type RM Length L Ch R = 1,4958,167,167,167
BEGIN DESCRIPTION:
Mapping XS fbf91492
END DESCRIPTION:
XS GIS Cut Line= 6
      2302161.87      7152283.67      2302099.55      7152258.76
      2301950.06      7152229.51      2301807.80      7152344.04
      2301540.20      7152625.24      2301519.59      7152686.21
#Sta/Elev= 30
  4600.6  799.66  4627.3  801.15  4646.1  793.54  4676.4  793.21  4676.6  792.71
  4680.4  793.21  4740.4  793.53  4750.7  798.21  4771.9  799.40  4829.1  797.12
  4835.0  795.72  4844.2  796.70  4850.2  793.61  4865.3  797.16  4871.3  794.05
  4880.5  797.08  4886.4  794.33  4893.0  797.27  4915.2  798.43  4943.6  798.40
  4950.4  797.57  4957.7  798.33  5205.2  798.89  5212.3  797.59  5219.2  798.87
  5254.7  797.74  5304.1  798.39  5412.0  797.64  5443.5  798.31  5456.3  799.67
#Mann=3,-1,0
  4600.6    0.05       0  4676.4   0.033       0  4680.4    0.05       0
Bank Sta=4676.4,4680.4
Exp/Cntr=0.3,0.1

Type RM Length L Ch R = 1,4791,227,227,227
BEGIN DESCRIPTION:
Mapping XS a0466f16
END DESCRIPTION:
XS GIS Cut Line= 4
      2301766.56      7152024.81      2301676.90      7152083.38
      2301681.59      7152244.68      2301471.80      7152579.06
#Sta/Elev= 30
  4720.7  783.41  4729.7  782.30  4743.5  782.94  4796.7  776.12  4815.9  773.64
  4834.4  773.36  4854.4  768.21  4944.5  768.07  4954.5  768.48  4964.5  770.40
  4988.9  768.97  4995.4  767.74  5008.3  766.89  5060.1  767.91  5075.4  767.38
  5100.6  762.47  5100.8  761.97  5104.6  762.47  5112.0  764.94  5133.2  773.95
  5139.1  777.76  5148.5  779.74  5154.4  781.77  5190.9  786.63  5227.4  788.49
  5285.2  789.57  5306.4  789.04  5321.7  789.90  5364.1  788.86  5383.9  789.42
#Mann=5,-1,0
  4720.7    0.05       0  4796.7    0.12       0  4988.9    0.05       0
  5100.6   0.033       0  5104.6    0.05       0
Bank Sta=5100.6,5104.6
Exp/Cntr=0.3,0.1

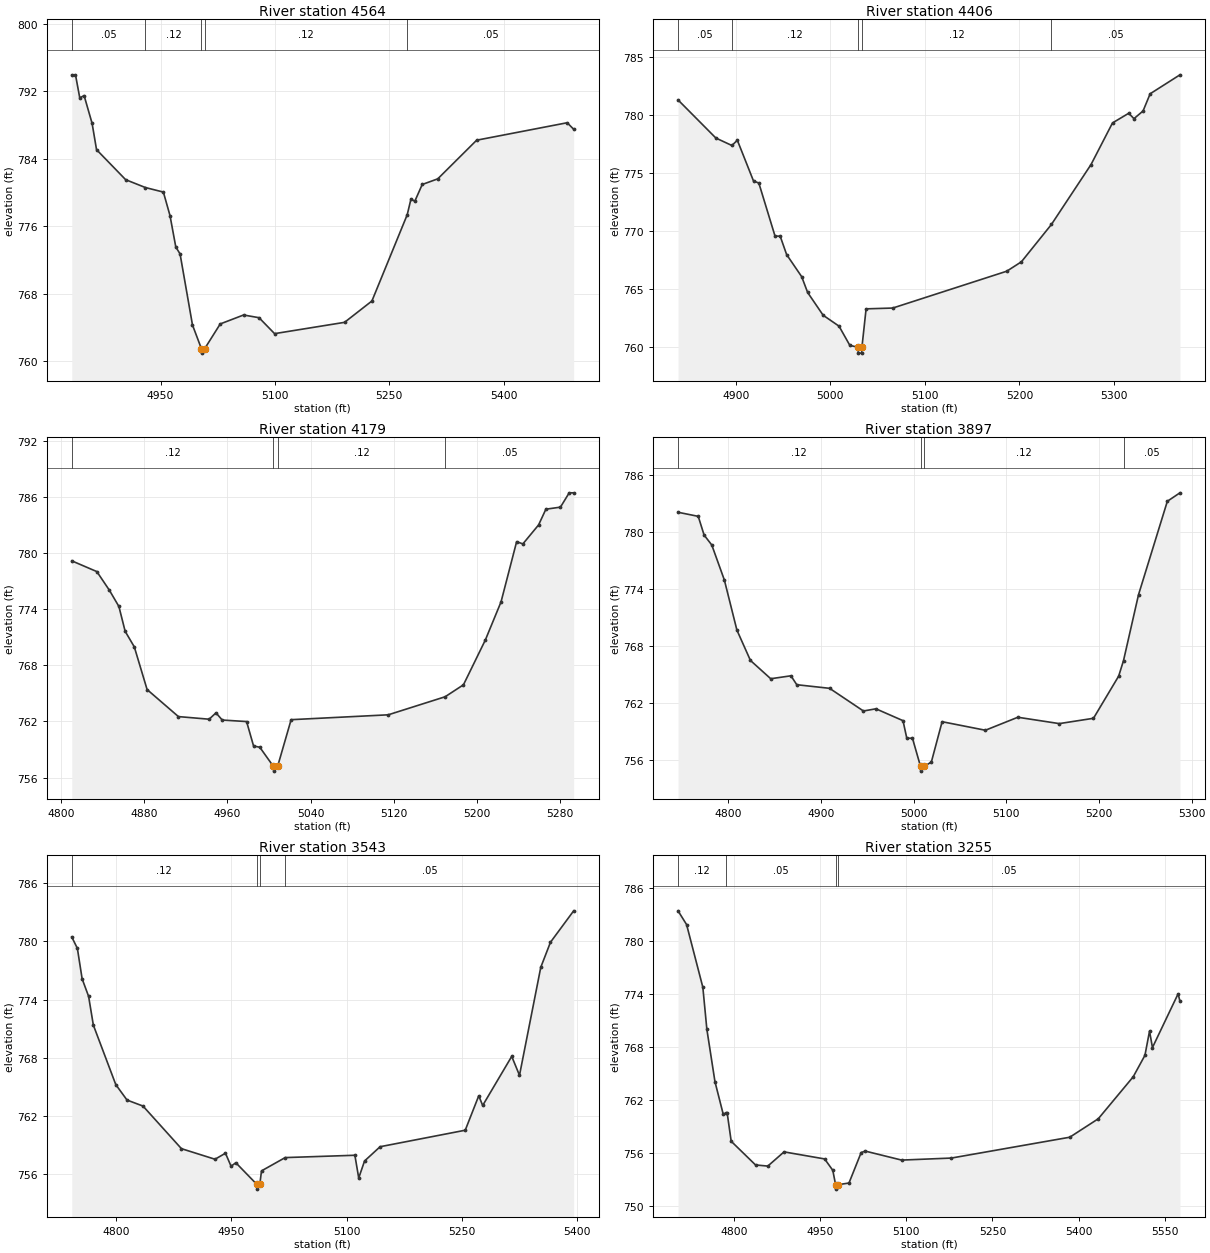
Type RM Length L Ch R = 1,4564,158,158,158
BEGIN DESCRIPTION:
Mapping XS d7a45fc0
END DESCRIPTION:
XS GIS Cut Line= 3
      2301649.36      7151916.43      2301566.31      7152071.41
      2301472.68      7152544.91
#Sta/Elev= 30
  4833.5  793.93  4838.4  793.93  4844.0  791.20  4849.7  791.47  4860.2  788.17
  4866.0  785.06  4904.2  781.50  4930.1  780.57  4953.7  780.03  4962.4  777.24
  4970.0  773.52  4975.6  772.70  4991.9  764.27  5003.7  761.44  5003.9  760.94
  5007.7  761.44  5028.3  764.40  5058.9  765.46  5079.2  765.14  5099.6  763.25
  5191.4  764.59  5227.3  767.12  5273.6  777.34  5278.5  779.19  5283.6  778.95
  5293.3  780.93  5313.7  781.60  5364.7  786.18  5483.5  788.25  5492.0  787.48
#Mann=5,-1,0
  4833.5    0.05       0  4930.1    0.12       0  5003.7    0.07       0
  5007.7    0.12       0  5273.6    0.05       0
Bank Sta=5003.7,5007.7
Exp/Cntr=0.3,0.1

Type RM Length L Ch R = 1,4406,227,227,227
BEGIN DESCRIPTION:
Mapping XS 70073000
END DESCRIPTION:
XS GIS Cut Line= 2
      2301500.07      7151866.43      2301271.27      7152345.17
#Sta/Elev= 30
  4839.1  781.30  4879.1  778.02  4896.0  777.38  4901.8  777.83  4918.9  774.32
  4924.5  774.15  4941.6  769.59  4947.1  769.57  4953.9  767.99  4969.8  766.09
  4976.1  764.73  4992.5  762.77  5009.3  761.83  5020.7  760.18  5029.5  760.01
  5029.7  759.51  5033.2  759.51  5033.5  760.01  5037.9  763.32  5066.1  763.39
  5186.6  766.56  5202.1  767.37  5233.8  770.58  5275.7  775.74  5298.4  779.32
  5315.5  780.15  5321.1  779.69  5330.7  780.35  5338.2  781.83  5369.7  783.46
#Mann=5,-1,0
  4839.1    0.05       0  4896.0    0.12       0  5029.5    0.07       0
  5033.5    0.12       0  5233.8    0.05       0
Bank Sta=5029.5,5033.5
Exp/Cntr=0.3,0.1

Type RM Length L Ch R = 1,4179,282,282,282
BEGIN DESCRIPTION:
Mapping XS 1138267d
END DESCRIPTION:
XS GIS Cut Line= 2
      2301350.75      7151819.87      2301084.84      7152222.25
#Sta/Elev= 30
  4810.5  779.17  4834.6  778.02  4846.7  776.02  4855.8  774.29  4861.8  771.64
  4870.6  769.97  4882.9  765.41  4913.0  762.52  4942.5  762.24  4949.1  762.92
  4955.1  762.15  4978.5  761.99  4985.2  759.38  4991.2  759.24  5004.3  757.19
  5004.5  756.69  5008.3  757.19  5021.3  762.19  5114.6  762.71  5169.3  764.64
  5186.9  765.92  5207.9  770.70  5223.0  774.78  5238.0  781.22  5244.0  780.98
  5259.1  783.01  5266.1  784.69  5280.1  784.91  5288.5  786.44  5292.8  786.44
#Mann=4,-1,0
  4810.5    0.12       0  5004.3    0.07       0  5008.3    0.12       0
  5169.3    0.05       0
Bank Sta=5004.3,5008.3
Exp/Cntr=0.3,0.1

Type RM Length L Ch R = 1,3897,354,354,354
BEGIN DESCRIPTION:
MDE S 038 10.0
END DESCRIPTION:
XS GIS Cut Line= 3
      2301178.98      7151610.03      2301029.00      7151810.00
      2300879.00      7152059.99
#Sta/Elev= 30
  4745.9  782.07  4767.7  781.64  4774.0  779.67  4782.3  778.62  4795.9  774.92
  4809.4  769.65  4824.0  766.45  4845.9  764.52  4867.7  764.83  4874.0  763.89
  4909.4  763.51  4945.9  761.12  4959.4  761.35  4988.6  760.10  4992.7  758.25
  4998.8  758.25  5007.5  755.28  5007.7  754.78  5011.5  755.28  5019.2  755.74
  5030.8  759.99  5077.5  759.09  5112.5  760.46  5157.2  759.79  5194.1  760.35
  5221.3  764.80  5226.5  766.43  5242.7  773.38  5273.8  783.23  5287.4  784.12
#Mann=4,-1,0
  4745.9    0.12       0  5007.5    0.07       0  5011.5    0.12       0
  5226.5    0.05       0
Bank Sta=5007.5,5011.5
Exp/Cntr=0.3,0.1

Type RM Length L Ch R = 1,3543,288,288,288
BEGIN DESCRIPTION:
MDE S 038 9.0
END DESCRIPTION:
XS GIS Cut Line= 3
      2300928.99      7151460.01      2300779.00      7151660.00
      2300829.00      7152060.00
#Sta/Elev= 30
  4742.4  780.45  4749.7  779.27  4755.9  776.13  4764.3  774.33  4770.5  771.36
  4799.7  765.23  4814.3  763.64  4835.1  763.02  4885.1  758.63  4928.8  757.54
  4942.4  758.16  4949.7  756.82  4955.9  757.18  4983.1  754.96  4983.3  754.46
  4987.1  754.96  4989.3  756.34  5020.1  757.71  5110.8  757.95  5115.8  755.61
  5123.4  757.36  5143.6  758.83  5254.4  760.53  5272.0  764.08  5277.1  763.08
  5314.9  768.14  5325.0  766.19  5352.7  777.32  5365.3  779.90  5395.5  783.14
#Mann=4,-1,0
  4742.4    0.12       0  4983.1    0.07       0  4987.1    0.12       0
  5020.1    0.05       0
Bank Sta=4983.1,4987.1
Exp/Cntr=0.3,0.1

Type RM Length L Ch R = 1,3255,286,286,286
BEGIN DESCRIPTION:
Mapping XS a52e3a41
END DESCRIPTION:
XS GIS Cut Line= 3
      2300805.69      7151315.66      2300534.28      7151595.65
      2300634.35      7152069.66
#Sta/Elev= 30
  4702.3  783.39  4717.2  781.83  4745.5  774.73  4752.5  769.97  4766.6  764.04
  4780.8  760.40  4785.9  760.46  4787.9  760.49  4794.9  757.28  4837.3  754.60
  4858.7  754.47  4887.0  756.08  4957.7  755.28  4971.9  753.99  4976.8  752.36
  4977.1  751.86  4980.8  752.36  5000.1  752.55  5021.3  756.00  5028.4  756.17
  5091.8  755.15  5178.5  755.38  5384.7  757.74  5434.4  759.83  5495.3  764.59
  5515.7  767.02  5523.7  769.76  5528.8  767.90  5573.5  773.99  5576.7  773.15
#Mann=4,-1,0
  4702.3    0.12       0  4785.9    0.05       0  4976.8   0.033       0
  4980.8    0.05       0
Bank Sta=4976.8,4980.8
Exp/Cntr=0.3,0.1

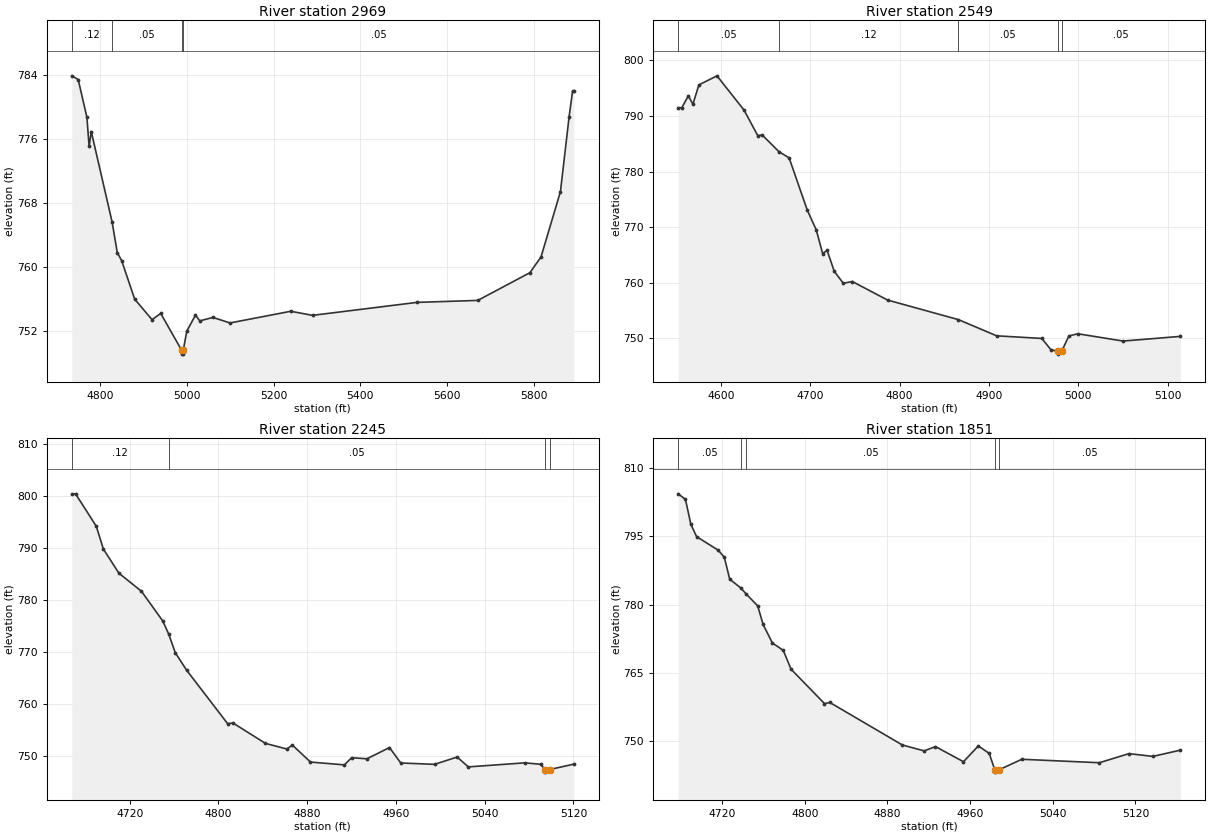
Type RM Length L Ch R = 1,2969,420,420,420
BEGIN DESCRIPTION:
Mapping XS b9bbd7f6
END DESCRIPTION:
XS GIS Cut Line= 3
      2300843.79      7151232.40      2300484.09      7151255.74
      2300550.23      7152050.83
#Sta/Elev= 30
  4734.2  783.89  4749.0  783.43  4769.1  778.71  4774.2  775.06  4779.2  776.92
  4827.2  765.62  4839.2  761.77  4849.2  760.79  4879.3  755.96  4919.4  753.39
  4939.4  754.17  4987.5  749.58  4987.8  749.08  4991.3  749.08  4991.5  749.58
  4999.6  751.96  5019.6  753.96  5029.6  753.24  5059.7  753.67  5099.3  752.98
  5239.4  754.44  5289.6  753.93  5530.4  755.55  5670.9  755.80  5791.3  759.27
  5816.8  761.24  5861.6  769.41  5881.6  778.78  5889.6  781.99  5892.5  781.99
#Mann=4,-1,0
  4734.2    0.12       0  4827.2    0.05       0  4987.5   0.033       0
  4991.5    0.05       0
Bank Sta=4987.5,4991.5
Exp/Cntr=0.3,0.1

Type RM Length L Ch R = 1,2549,304,304,304
BEGIN DESCRIPTION:
Mapping XS 49d7a04d
END DESCRIPTION:
XS GIS Cut Line= 2
      2300971.90      7150823.03      2300415.49      7150898.42
#Sta/Elev= 30
  4552.5  791.49  4556.5  791.49  4563.8  793.62  4568.9  792.11  4575.6  795.59
  4595.8  797.22  4626.1  791.06  4641.4  786.48  4646.5  786.57  4665.2  783.57
  4676.5  782.48  4696.7  773.12  4706.8  769.54  4714.0  765.27  4719.0  765.84
  4727.0  762.08  4737.1  759.93  4747.2  760.24  4786.6  756.91  4865.9  753.39
  4908.6  750.48  4959.1  750.01  4969.2  748.00  4977.3  747.69  4977.5  747.19
  4981.3  747.69  4989.4  750.46  4999.4  750.85  5049.9  749.54  5114.0  750.38
#Mann=5,-1,0
  4552.5    0.05       0  4665.2    0.12       0  4865.9    0.05       0
  4977.3   0.035       0  4981.3    0.05       0
Bank Sta=4977.3,4981.3
Exp/Cntr=0.3,0.1

Type RM Length L Ch R = 1,2245,394,394,394
BEGIN DESCRIPTION:
Mapping XS 262f46ae
END DESCRIPTION:
XS GIS Cut Line= 2
      2300950.79      7150670.32      2300505.47      7150589.48
#Sta/Elev= 30
  4667.8  800.45  4671.2  800.45  4689.9  794.20  4696.3  789.80  4710.3  785.15
  4730.6  781.67  4749.7  775.98  4755.1  773.46  4761.1  769.83  4771.3  766.46
  4808.2  756.17  4813.3  756.25  4842.4  752.34  4861.6  751.26  4866.7  752.01
  4883.0  748.74  4913.5  748.20  4920.1  749.58  4933.9  749.37  4954.2  751.54
  4964.4  748.56  4994.8  748.30  5015.2  749.71  5025.3  747.81  5076.2  748.59
  5090.4  748.31  5094.5  747.30  5094.7  746.80  5098.5  747.30  5120.4  748.34
#Mann=4,-1,0
  4667.8    0.12       0  4755.1    0.05       0  5094.5   0.033       0
  5098.5    0.05       0
Bank Sta=5094.5,5098.5
Exp/Cntr=0.3,0.1

Type RM Length L Ch R = 1,1851,0,0,0
BEGIN DESCRIPTION:
MDE S 038 8.0
END DESCRIPTION:
XS GIS Cut Line= 3
      2301035.85      7150338.64      2300738.66      7150244.65
      2300579.75      7150315.77
#Sta/Elev= 30
  4677.6  804.37  4684.6  803.14  4689.8  797.67  4695.3  794.96  4716.3  791.96
  4722.2  790.40  4727.4  785.59  4738.1  783.65  4743.4  782.31  4754.5  779.70
  4759.7  775.62  4768.7  771.54  4779.2  769.91  4786.8  765.76  4819.1  758.20
  4824.3  758.44  4894.5  749.08  4915.5  747.79  4926.5  748.73  4953.6  745.40
  4968.0  748.88  4978.5  747.23  4983.9  743.61  4984.2  743.11  4987.9  743.61
  5010.0  745.94  5085.1  745.18  5113.7  747.18  5136.9  746.57  5163.4  747.95
#Mann=5,-1,0
  4677.6    0.05       0  4738.1    0.12       0  4743.4    0.05       0
  4983.9    0.04       0  4987.9    0.05       0
Bank Sta=4983.9,4987.9
Exp/Cntr=0.3,0.1

Chan Stop Cuts=-1