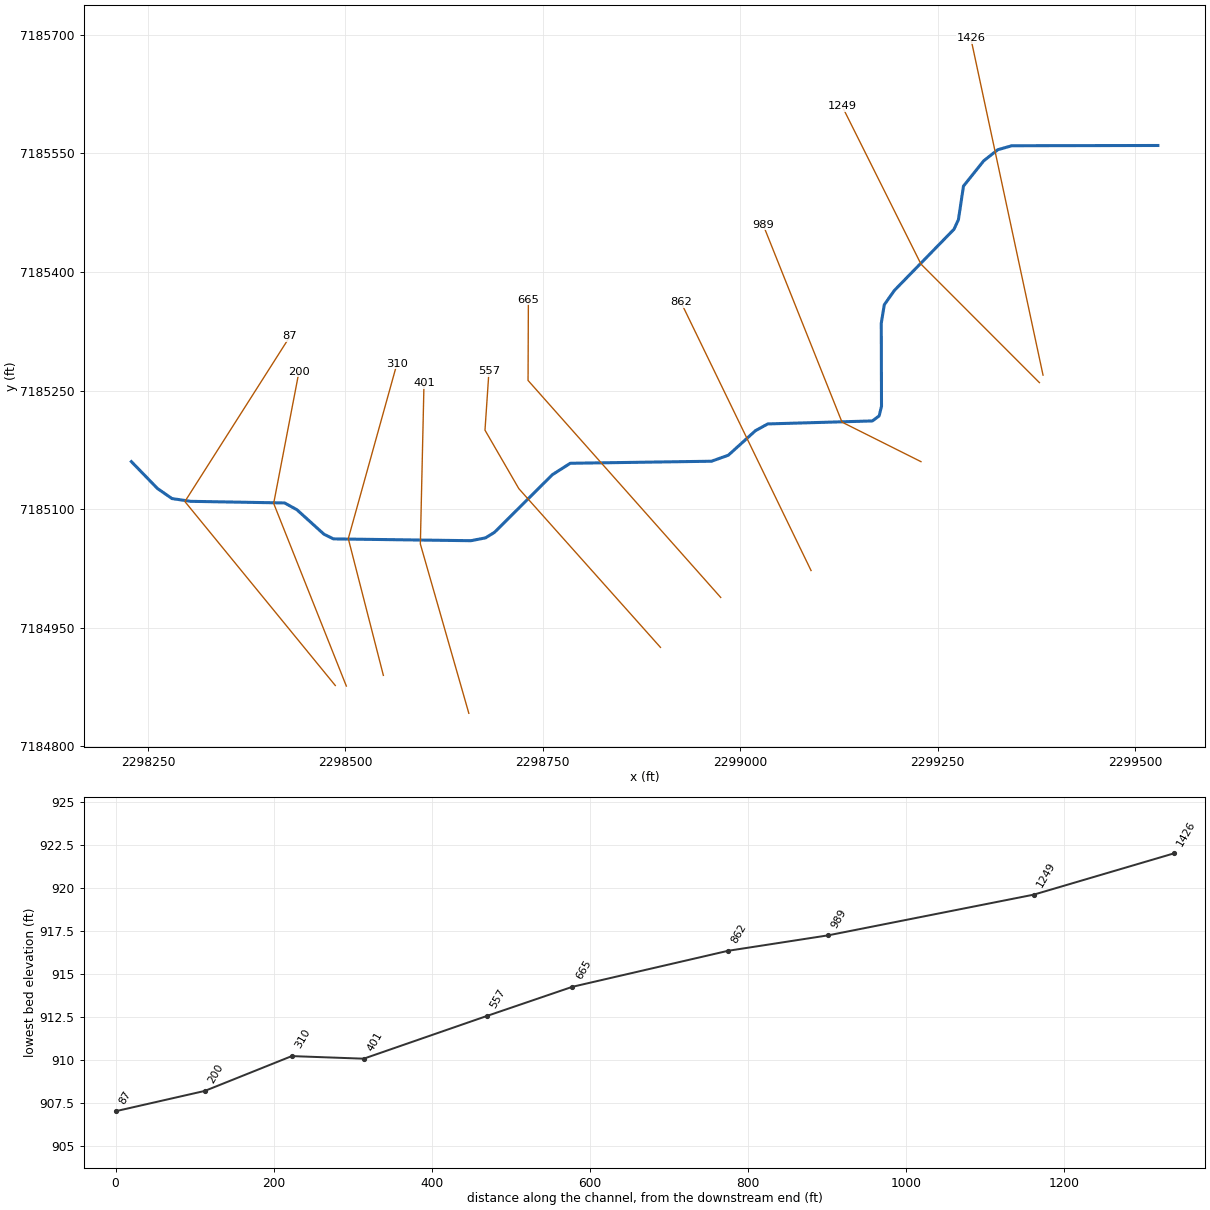
--- MDE S 041.prj (project) ---

Proj Title=MDE S 041 Base Level Engineering
Current Plan=p01
Default Exp/Contr=0.3,0.1
English Units
Geom File=g01
Flow File=f01
Plan File=p01
BEGIN DESCRIPTION:
MDE S 041
END DESCRIPTION:

--- MDE S 041.p01 (plan) ---

Plan Title=Multiple Run
Short Identifier=Multiple
Geom File=g01
Flow File=f01
Subcritical Flow
K Sum by GR= 0
Std Step Tol= 0.01
Critical Tol= 0.01
Num of Std Step Trials= 20
Max Error Tol= 0.3
Flow Tol Ratio= 0.001
Split Flow NTrial= 30
Split Flow Tol= 0.02
Split Flow Ratio= 0.02
Log Output Level= 0
Friction Slope Method= 1
Unsteady Friction Slope Method= 2
Unsteady Bridges Friction Slope Method= 1
Parabolic Critical Depth
Global Vel Dist=  1 , 1 , 1
Global Log Level= 0
CheckData=True
Encroach Param= -1, 0, 0, 0
BEGIN DESCRIPTION:
Multiple Run
END DESCRIPTION:

--- MDE S 041.f01 (steady flow) ---

Flow Title=Multiple
Number of Profiles=7
Profile Names=10-year,25-year,50-year,1pct_min,100-year,1pct_plu,500-year
River Rch & RM= MDE S 041,Reach-1,1426
     414     552     664     398     793    1583    1132
Boundary for River Rch & Prof#=MDE S 041,Reach-1,1
Up Type=0
Dn Type=3
Dn Slope=0.005
Boundary for River Rch & Prof#=MDE S 041,Reach-1,2
Up Type=0
Dn Type=3
Dn Slope=0.005
Boundary for River Rch & Prof#=MDE S 041,Reach-1,3
Up Type=0
Dn Type=3
Dn Slope=0.005
Boundary for River Rch & Prof#=MDE S 041,Reach-1,4
Up Type=0
Dn Type=3
Dn Slope=0.005
Boundary for River Rch & Prof#=MDE S 041,Reach-1,5
Up Type=0
Dn Type=3
Dn Slope=0.005
Boundary for River Rch & Prof#=MDE S 041,Reach-1,6
Up Type=0
Dn Type=3
Dn Slope=0.005
Boundary for River Rch & Prof#=MDE S 041,Reach-1,7
Up Type=0
Dn Type=3
Dn Slope=0.005

--- MDE S 041.g01 (geometry) ---

Geom Title=Existing Conditions

River Reach=MDE S 041,Reach-1
Reach XY= 30
      2299529.00      7185560.00      2299344.03      7185559.68
      2299326.30      7185554.65      2299308.45      7185540.56
      2299282.87      7185508.60      2299276.44      7185466.09
      2299270.81      7185453.98      2299195.47      7185376.75
      2299182.56      7185358.52      2299178.74      7185335.08
      2299179.04      7185229.95      2299176.08      7185217.92
      2299167.51      7185211.50      2299034.95      7185207.72
      2299019.36      7185199.14      2298985.06      7185168.14
      2298963.78      7185160.52      2298784.86      7185157.93
      2298762.25      7185143.53      2298688.79      7185070.50
      2298677.53      7185063.55      2298659.01      7185059.96
      2298484.94      7185062.26      2298472.94      7185068.14
      2298438.65      7185099.14      2298423.06      7185107.73
      2298303.91      7185109.79      2298280.37      7185113.30
      2298261.94      7185126.09      2298229.00      7185160.00

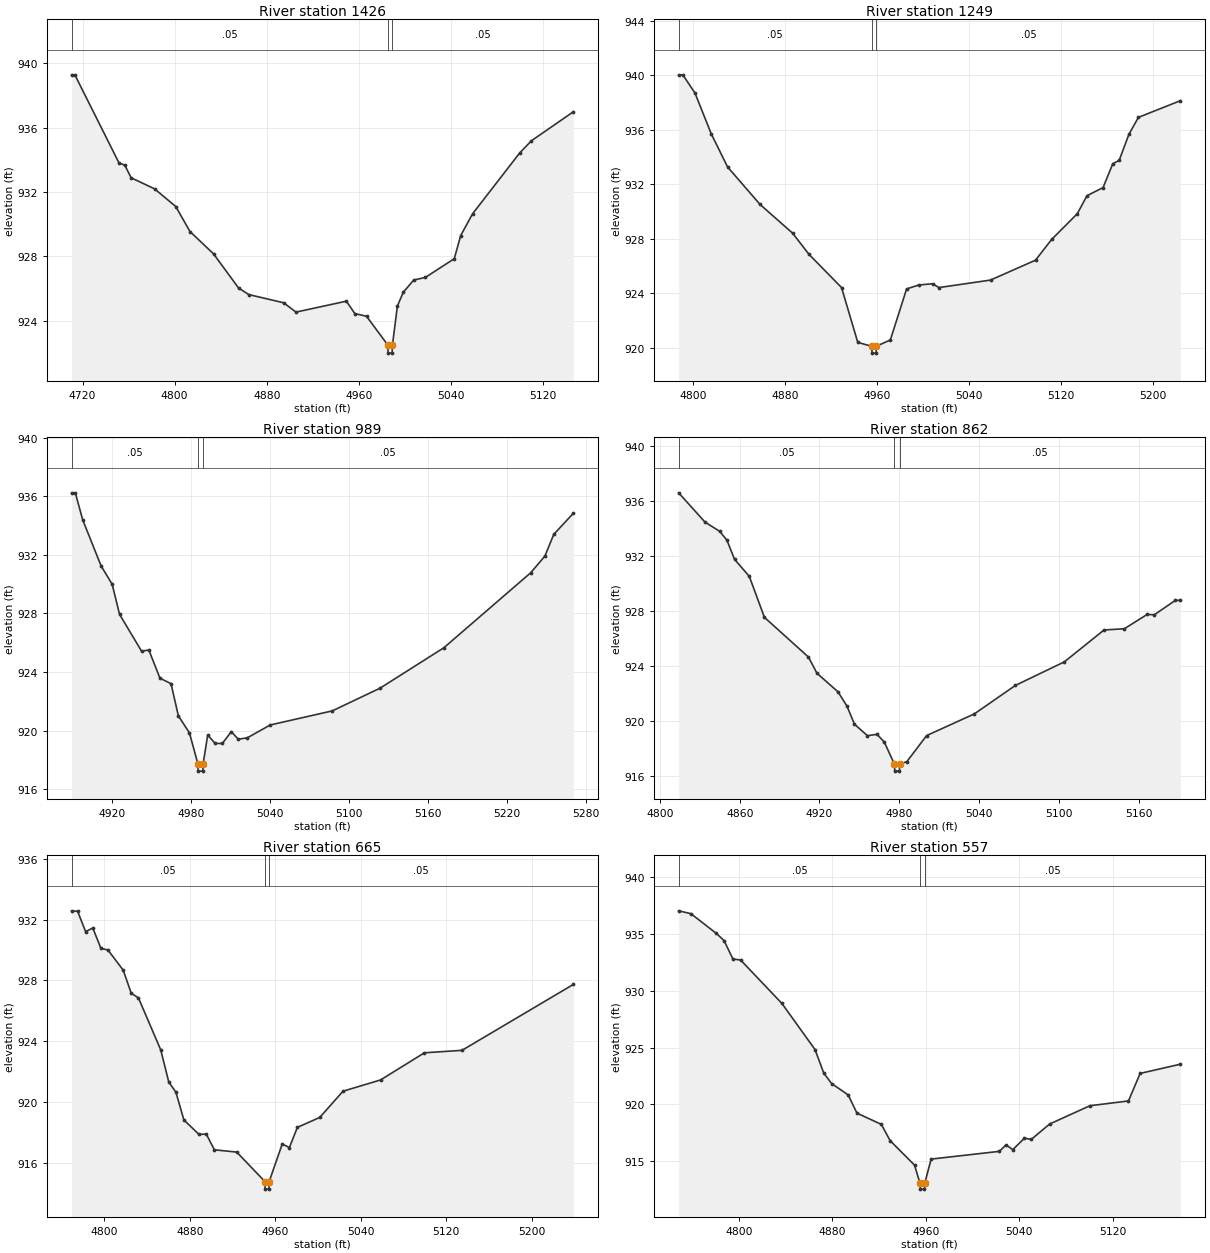
Type RM Length L Ch R = 1,1426,177,177,177
BEGIN DESCRIPTION:
Mapping XS af0fc81a
END DESCRIPTION:
XS GIS Cut Line= 2
      2299383.62      7185269.48      2299292.19      7185695.58
#Sta/Elev= 30
  4710.5  939.29  4713.3  939.29  4751.6  933.82  4756.7  933.67  4762.2  932.89
  4782.6  932.20  4801.0  931.10  4813.3  929.55  4833.8  928.16  4855.5  926.04
  4864.4  925.63  4894.7  925.12  4905.4  924.54  4949.2  925.22  4956.5  924.45
  4966.7  924.28  4985.2  922.49  4985.4  921.99  4988.9  921.99  4989.2  922.49
  4993.5  924.92  4998.6  925.77  5007.6  926.53  5017.9  926.70  5042.9  927.86
  5048.5  929.30  5058.8  930.65  5099.7  934.43  5109.9  935.19  5146.3  936.99
#Mann=3,-1,0
  4710.5    0.05       0  4985.2   0.033       0  4989.2    0.05       0
Bank Sta=4985.2,4989.2
Exp/Cntr=0.3,0.1

Type RM Length L Ch R = 1,1249,260,260,260
BEGIN DESCRIPTION:
MDE S 041 4.0
END DESCRIPTION:
XS GIS Cut Line= 3
      2299379.03      7185259.97      2299229.00      7185410.00
      2299128.99      7185610.02
#Sta/Elev= 30
  4787.8  940.02  4791.4  940.02  4802.0  938.68  4816.1  935.69  4830.3  933.26
  4858.5  930.51  4886.8  928.40  4901.0  926.85  4929.3  924.41  4943.4  920.39
  4955.5  920.10  4955.8  919.60  4959.3  919.60  4959.5  920.10  4971.7  920.57
  4985.8  924.31  4996.4  924.60  5008.4  924.69  5013.9  924.41  5058.7  924.96
  5097.8  926.42  5111.8  927.94  5134.1  929.83  5142.5  931.15  5156.5  931.75
  5164.9  933.49  5170.5  933.75  5178.9  935.65  5187.2  936.90  5223.6  938.12
#Mann=3,-1,0
  4787.8    0.05       0  4955.5   0.033       0  4959.5    0.05       0
Bank Sta=4955.5,4959.5
Exp/Cntr=0.3,0.1

Type RM Length L Ch R = 1,989,127,127,127
BEGIN DESCRIPTION:
MDE S 041 3.0
END DESCRIPTION:
XS GIS Cut Line= 3
      2299229.02      7185159.99      2299129.00      7185210.00
      2299029.00      7185460.01
#Sta/Elev= 30
  4889.4  936.23  4892.2  936.23  4897.8  934.39  4911.8  931.24  4920.2  929.99
  4925.8  927.94  4942.5  925.43  4948.1  925.50  4956.5  923.58  4964.9  923.21
  4970.5  921.01  4978.9  919.85  4985.3  917.74  4985.5  917.24  4989.0  917.24
  4989.3  917.74  4992.8  919.71  4998.4  919.13  5003.9  919.13  5010.7  919.93
  5016.0  919.42  5022.8  919.51  5040.3  920.39  5087.4  921.35  5123.7  922.90
  5172.2  925.66  5238.2  930.78  5248.9  931.91  5255.7  933.40  5270.5  934.83
#Mann=3,-1,0
  4889.4    0.05       0  4985.3   0.033       0  4989.3    0.05       0
Bank Sta=4985.3,4989.3
Exp/Cntr=0.3,0.1

Type RM Length L Ch R = 1,862,197,197,197
BEGIN DESCRIPTION:
Mapping XS 0dfe3145
END DESCRIPTION:
XS GIS Cut Line= 2
      2299089.82      7185022.22      2298925.06      7185361.65
#Sta/Elev= 30
  4814.1  936.61  4833.9  934.48  4844.9  933.81  4850.4  933.16  4856.1  931.77
  4867.2  930.53  4878.6  927.54  4911.7  924.65  4918.1  923.47  4933.9  922.12
  4940.7  921.07  4946.3  919.76  4956.1  918.92  4963.3  919.02  4968.8  918.45
  4976.4  916.84  4976.6  916.34  4980.1  916.34  4980.4  916.84  4985.8  917.04
  5000.6  918.93  5036.5  920.51  5067.3  922.58  5104.2  924.30  5134.0  926.62
  5149.3  926.71  5166.4  927.75  5171.9  927.73  5187.7  928.78  5191.4  928.78
#Mann=3,-1,0
  4814.1    0.05       0  4976.4   0.033       0  4980.4    0.05       0
Bank Sta=4976.4,4980.4
Exp/Cntr=0.3,0.1

Type RM Length L Ch R = 1,665,108,108,108
BEGIN DESCRIPTION:
Mapping XS 3b0aec70
END DESCRIPTION:
XS GIS Cut Line= 3
      2298975.39      7184988.18      2298731.39      7185262.72
      2298731.80      7185364.92
#Sta/Elev= 30
  4769.5  932.58  4775.1  932.55  4782.6  931.21  4789.3  931.45  4796.9  930.11
  4803.5  930.00  4817.8  928.67  4825.3  927.15  4832.0  926.85  4852.9  923.42
  4860.4  921.31  4867.1  920.63  4874.6  918.80  4888.8  917.85  4895.5  917.88
  4903.1  916.84  4924.0  916.69  4950.4  914.75  4950.6  914.25  4954.1  914.25
  4954.4  914.75  4966.6  917.22  4973.3  916.99  4980.8  918.32  5001.7  918.97
  5023.5  920.70  5058.6  921.44  5099.7  923.23  5134.8  923.39  5239.0  927.73
#Mann=3,-1,0
  4769.5    0.05       0  4950.4   0.033       0  4954.4    0.05       0
Bank Sta=4950.4,4954.4
Exp/Cntr=0.3,0.1

Type RM Length L Ch R = 1,557,156,156,156
BEGIN DESCRIPTION:
Mapping XS 7ed29e9b
END DESCRIPTION:
XS GIS Cut Line= 4
      2298899.07      7184925.02      2298719.73      7185125.80
      2298676.84      7185199.82      2298681.88      7185274.29
#Sta/Elev= 30
  4748.5  937.02  4759.0  936.77  4780.7  935.04  4787.4  934.40  4794.9  932.79
  4801.6  932.69  4836.8  928.89  4865.2  924.83  4872.7  922.76  4879.4  921.84
  4893.6  920.84  4901.1  919.24  4922.0  918.25  4929.5  916.82  4950.4  914.67
  4955.1  913.06  4955.4  912.56  4958.9  912.56  4959.1  913.06  4964.6  915.20
  5023.0  915.88  5028.7  916.45  5034.5  916.03  5044.5  917.04  5050.3  916.93
  5066.0  918.28  5100.5  919.89  5133.5  920.31  5143.5  922.73  5177.9  923.54
#Mann=3,-1,0
  4748.5    0.05       0  4955.1   0.033       0  4959.1    0.05       0
Bank Sta=4955.1,4959.1
Exp/Cntr=0.3,0.1

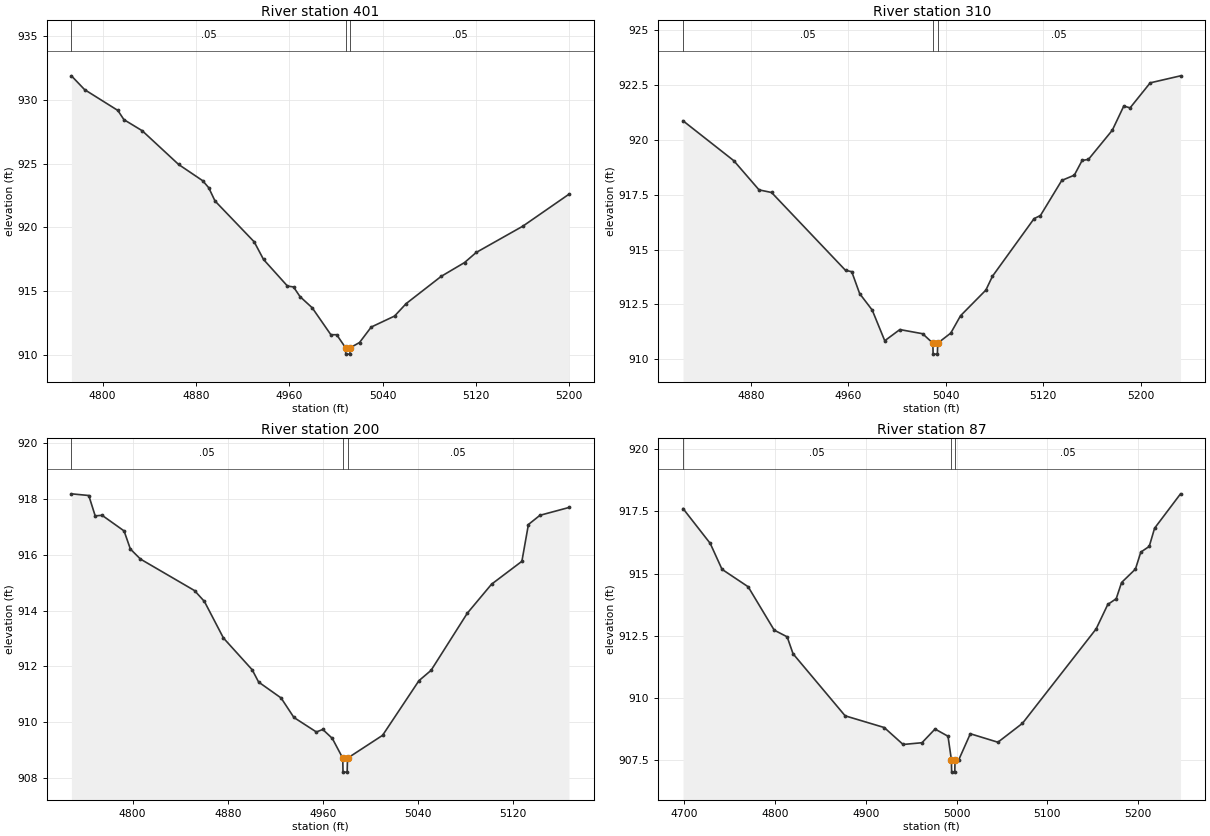
Type RM Length L Ch R = 1,401,91,91,91
BEGIN DESCRIPTION:
Mapping XS 62444a54
END DESCRIPTION:
XS GIS Cut Line= 3
      2298656.37      7184841.63      2298594.98      7185055.83
      2298599.61      7185259.45
#Sta/Elev= 30
  4773.2  931.87  4784.5  930.79  4813.0  929.16  4818.2  928.44  4833.9  927.57
  4865.1  924.93  4885.7  923.66  4890.9  923.11  4896.3  922.07  4929.9  918.87
  4937.9  917.49  4958.4  915.41  4963.6  915.34  4969.2  914.58  4979.6  913.71
  4995.6  911.60  5000.6  911.60  5008.2  910.58  5008.4  910.08  5011.9  910.08
  5012.2  910.58  5020.2  910.99  5030.2  912.20  5050.2  913.06  5060.2  914.04
  5090.2  916.17  5110.2  917.25  5120.2  918.04  5160.2  920.10  5199.7  922.60
#Mann=3,-1,0
  4773.2    0.05       0  5008.2   0.033       0  5012.2    0.05       0
Bank Sta=5008.2,5012.2
Exp/Cntr=0.3,0.1

Type RM Length L Ch R = 1,310,110,110,110
BEGIN DESCRIPTION:
Mapping XS 0ffe59b3
END DESCRIPTION:
XS GIS Cut Line= 3
      2298548.13      7184889.60      2298503.72      7185062.60
      2298565.38      7185283.97
#Sta/Elev= 30
  4824.3  920.87  4866.0  919.05  4886.7  917.72  4897.0  917.60  4957.7  914.05
  4962.8  913.99  4969.3  912.99  4979.6  912.24  4989.9  910.84  5002.3  911.35
  5021.0  911.16  5029.4  910.73  5029.6  910.23  5033.1  910.23  5033.4  910.73
  5044.1  911.19  5052.1  911.98  5072.9  913.15  5078.3  913.78  5112.5  916.41
  5117.7  916.55  5135.2  918.15  5145.5  918.39  5151.9  919.06  5157.1  919.11
  5176.7  920.44  5186.1  921.54  5191.3  921.46  5207.8  922.60  5232.7  922.92
#Mann=3,-1,0
  4824.3    0.05       0  5029.4   0.033       0  5033.4    0.05       0
Bank Sta=5029.4,5033.4
Exp/Cntr=0.3,0.1

Type RM Length L Ch R = 1,200,113,113,113
BEGIN DESCRIPTION:
Mapping XS cb5dfa2b
END DESCRIPTION:
XS GIS Cut Line= 3
      2298501.23      7184876.04      2298409.21      7185107.16
      2298441.30      7185273.93
#Sta/Elev= 30
  4748.5  918.19  4763.1  918.13  4768.5  917.40  4774.3  917.42  4792.8  916.86
  4798.1  916.21  4806.6  915.85  4852.1  914.72  4860.4  914.33  4876.4  913.02
  4900.6  911.88  4906.0  911.44  4924.9  910.87  4935.7  910.17  4954.6  909.65
  4960.0  909.74  4968.0  909.42  4976.8  908.71  4977.0  908.21  4980.5  908.21
  4980.8  908.71  5010.3  909.53  5040.9  911.49  5051.1  911.86  5081.6  913.91
  5102.0  914.95  5127.5  915.77  5133.0  917.09  5142.7  917.42  5167.1  917.70
#Mann=3,-1,0
  4748.5    0.05       0  4976.8   0.033       0  4980.8    0.05       0
Bank Sta=4976.8,4980.8
Exp/Cntr=0.3,0.1

Type RM Length L Ch R = 1,87,0,0,0
BEGIN DESCRIPTION:
MDE S 041 1.0
END DESCRIPTION:
XS GIS Cut Line= 3
      2298487.25      7184876.78      2298296.76      7185109.51
      2298429.79      7185318.40
#Sta/Elev= 30
  4698.5  917.61  4728.5  916.21  4741.5  915.17  4770.3  914.47  4799.0  912.73
  4813.3  912.46  4819.8  911.78  4877.2  909.29  4920.3  908.82  4941.1  908.14
  4961.9  908.21  4976.3  908.76  4990.6  908.47  4994.3  907.53  4994.6  907.03
  4998.1  907.03  4998.3  907.53  5002.5  907.53  5015.2  908.57  5045.6  908.23
  5072.7  908.99  5153.9  912.78  5166.7  913.76  5176.0  913.99  5181.9  914.64
  5197.2  915.18  5203.1  915.86  5212.4  916.09  5218.3  916.82  5246.9  918.20
#Mann=3,-1,0
  4698.5    0.05       0  4994.3   0.033       0  4998.3    0.05       0
Bank Sta=4994.3,4998.3
Exp/Cntr=0.3,0.1

Chan Stop Cuts=-1