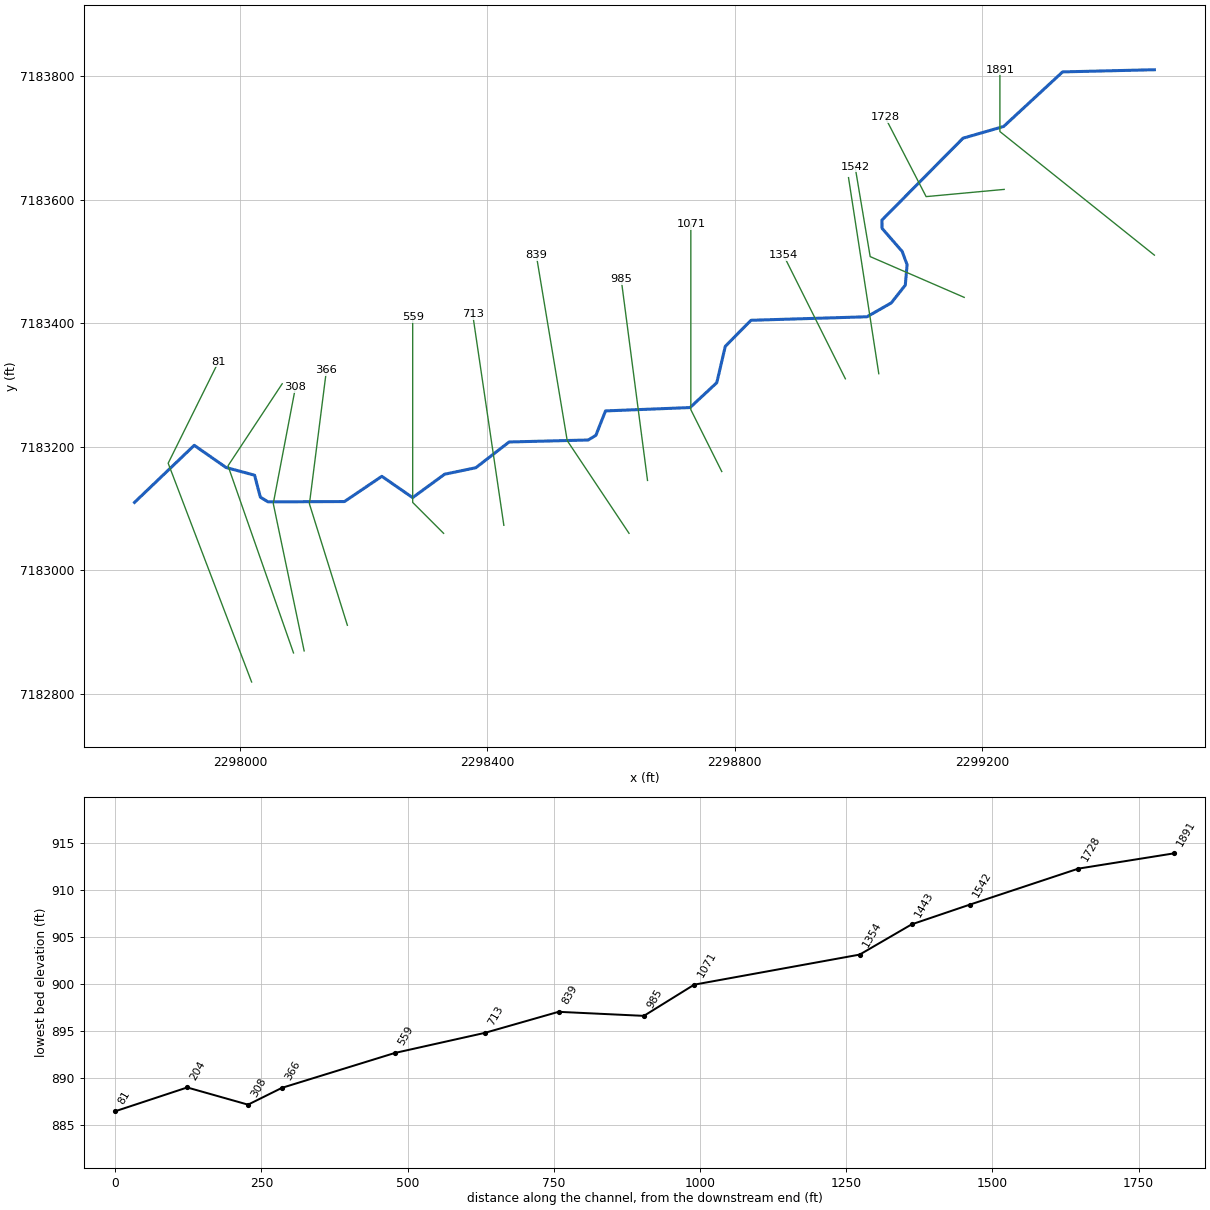
--- MDE S 042.prj (project) ---

Proj Title=MDE S 042 Base Level Engineering
Current Plan=p01
Default Exp/Contr=0.3,0.1
English Units
Geom File=g01
Flow File=f01
Plan File=p01
BEGIN DESCRIPTION:
MDE S 042
END DESCRIPTION:

--- MDE S 042.p01 (plan) ---

Plan Title=Multiple Run
Short Identifier=Multiple
Geom File=g01
Flow File=f01
Subcritical Flow
K Sum by GR= 0
Std Step Tol= 0.01
Critical Tol= 0.01
Num of Std Step Trials= 20
Max Error Tol= 0.3
Flow Tol Ratio= 0.001
Split Flow NTrial= 30
Split Flow Tol= 0.02
Split Flow Ratio= 0.02
Log Output Level= 0
Friction Slope Method= 1
Unsteady Friction Slope Method= 2
Unsteady Bridges Friction Slope Method= 1
Parabolic Critical Depth
Global Vel Dist=  1 , 1 , 1
Global Log Level= 0
CheckData=True
Encroach Param= -1, 0, 0, 0
BEGIN DESCRIPTION:
Multiple Run
END DESCRIPTION:

--- MDE S 042.f01 (steady flow) ---

Flow Title=Multiple
Number of Profiles=7
Profile Names=10-year,25-year,50-year,1pct_min,100-year,1pct_plu,500-year
River Rch & RM= MDE S 042,Reach-1,1891
     416     558     673     405     808    1611    1162
Boundary for River Rch & Prof#=MDE S 042,Reach-1,1
Up Type=0
Dn Type=3
Dn Slope=0.005
Boundary for River Rch & Prof#=MDE S 042,Reach-1,2
Up Type=0
Dn Type=3
Dn Slope=0.005
Boundary for River Rch & Prof#=MDE S 042,Reach-1,3
Up Type=0
Dn Type=3
Dn Slope=0.005
Boundary for River Rch & Prof#=MDE S 042,Reach-1,4
Up Type=0
Dn Type=3
Dn Slope=0.005
Boundary for River Rch & Prof#=MDE S 042,Reach-1,5
Up Type=0
Dn Type=3
Dn Slope=0.005
Boundary for River Rch & Prof#=MDE S 042,Reach-1,6
Up Type=0
Dn Type=3
Dn Slope=0.005
Boundary for River Rch & Prof#=MDE S 042,Reach-1,7
Up Type=0
Dn Type=3
Dn Slope=0.005

--- MDE S 042.g01 (geometry) ---

Geom Title=Existing Conditions

River Reach=MDE S 042,Reach-1
Reach XY= 30
      2299479.00      7183810.00      2299330.45      7183806.49
      2299235.04      7183718.18      2299169.32      7183699.22
      2299038.15      7183566.73      2299038.33      7183553.45
      2299070.88      7183516.03      2299078.85      7183494.58
      2299075.94      7183461.40      2299053.15      7183432.70
      2299014.00      7183410.33      2298826.30      7183404.64
      2298784.75      7183362.55      2298770.97      7183303.64
      2298727.74      7183263.46      2298590.97      7183258.02
      2298575.41      7183218.59      2298563.04      7183210.97
      2298434.94      7183207.75      2298381.17      7183166.09
      2298330.63      7183155.59      2298278.92      7183117.76
      2298229.10      7183152.20      2298168.55      7183111.36
      2298044.95      7183110.90      2298032.55      7183118.49
      2298023.20      7183154.00      2297977.02      7183166.49
      2297925.61      7183202.36      2297829.00      7183110.00

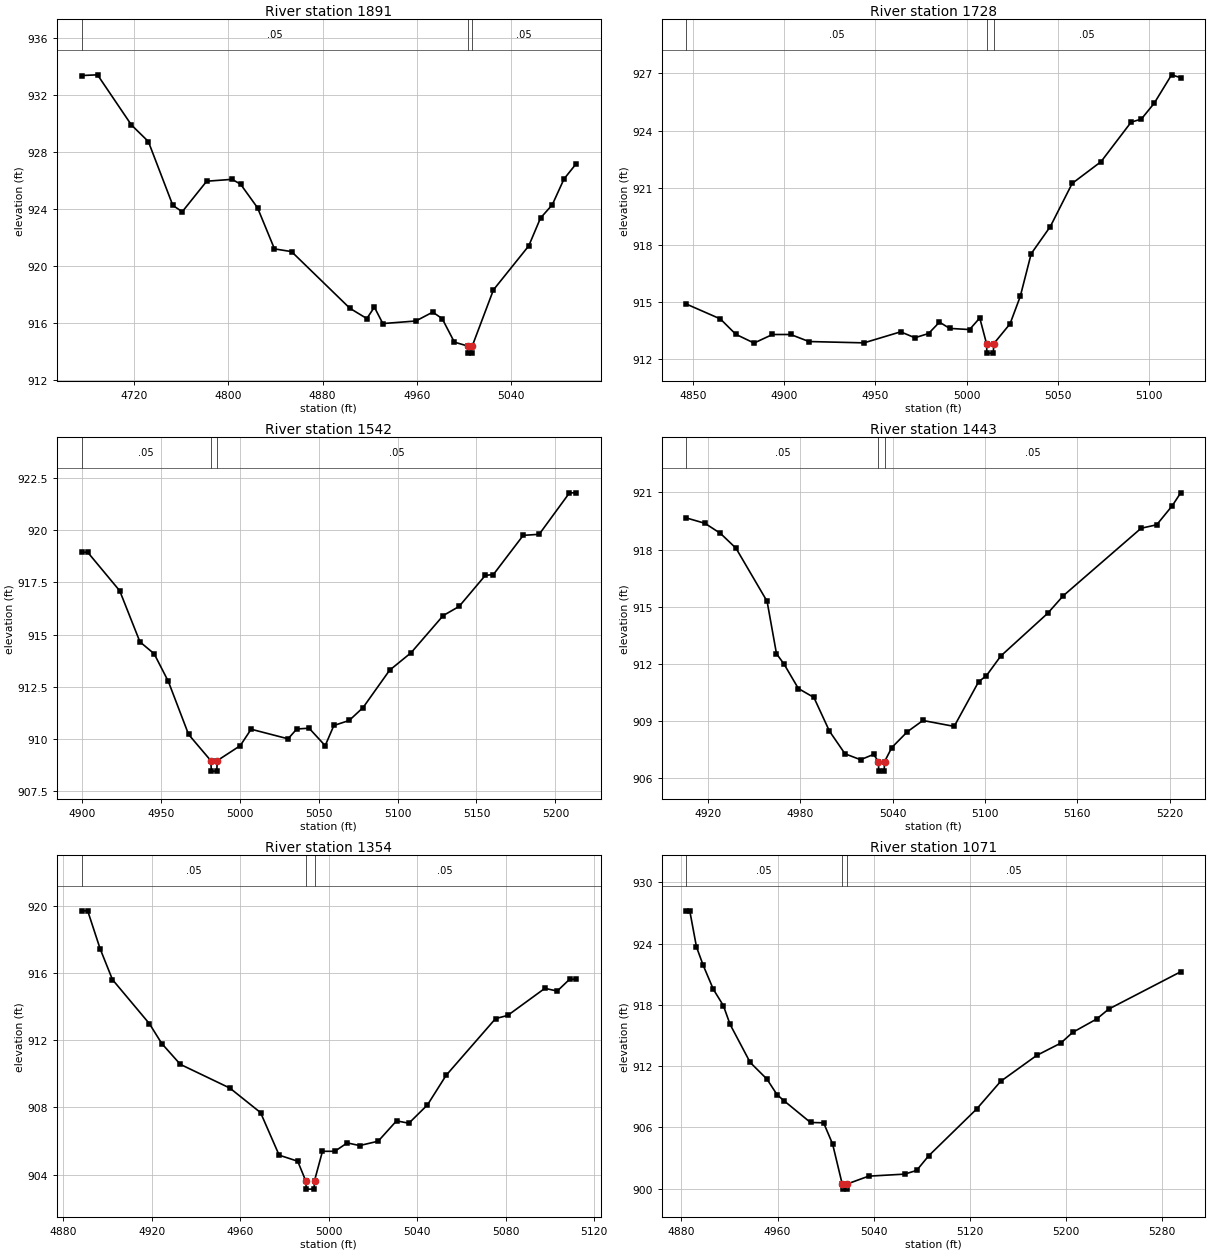
Type RM Length L Ch R = 1,1891,163,163,163
BEGIN DESCRIPTION:
MDE S 042 7.0
END DESCRIPTION:
XS GIS Cut Line= 3
      2299478.97      7183510.02      2299229.00      7183710.00
      2299229.00      7183809.98
#Sta/Elev= 30
  4675.1  933.35  4688.7  933.40  4717.5  929.89  4731.9  928.73  4752.7  924.26
  4760.7  923.81  4781.5  925.95  4803.1  926.08  4810.3  925.74  4824.7  924.09
  4839.1  921.21  4853.6  921.02  4903.2  917.05  4917.6  916.33  4924.0  917.13
  4931.2  915.98  4959.2  916.16  4973.6  916.78  4981.6  916.33  4992.0  914.68
  5003.2  914.41  5003.5  913.91  5007.0  913.91  5007.2  914.41  5025.2  918.34
  5055.2  921.42  5065.2  923.37  5075.2  924.30  5085.2  926.11  5095.2  927.14
#Mann=3,-1,0
  4675.1    0.05       0  5003.2   0.033       0  5007.2    0.05       0
Bank Sta=5003.2,5007.2
Exp/Cntr=0.3,0.1

Type RM Length L Ch R = 1,1728,186,186,186
BEGIN DESCRIPTION:
Mapping XS 7674ed8e
END DESCRIPTION:
XS GIS Cut Line= 3
      2299235.95      7183616.40      2299109.66      7183604.71
      2299043.46      7183732.89
#Sta/Elev= 30
  4846.3  914.87  4864.9  914.09  4873.4  913.28  4883.4  912.82  4893.5  913.27
  4903.5  913.27  4913.5  912.90  4943.7  912.83  4963.8  913.41  4971.6  913.10
  4979.1  913.32  4985.1  913.92  4990.7  913.59  5001.6  913.53  5007.2  914.14
  5010.9  912.79  5011.1  912.29  5014.6  912.29  5014.9  912.79  5023.8  913.83
  5029.4  915.27  5035.4  917.52  5045.9  918.95  5057.9  921.22  5073.7  922.36
  5090.2  924.44  5095.8  924.60  5102.9  925.44  5112.4  926.93  5117.4  926.78
#Mann=3,-1,0
  4846.3    0.05       0  5010.9   0.033       0  5014.9    0.05       0
Bank Sta=5010.9,5014.9
Exp/Cntr=0.3,0.1

Type RM Length L Ch R = 1,1542,99,99,99
BEGIN DESCRIPTION:
Mapping XS be168168
END DESCRIPTION:
XS GIS Cut Line= 3
      2299171.23      7183441.73      2299019.13      7183507.68
      2298994.75      7183652.86
#Sta/Elev= 30
  4899.9  918.95  4903.8  918.95  4924.1  917.10  4936.9  914.65  4945.9  914.08
  4954.9  912.75  4967.7  910.21  4981.8  908.95  4982.1  908.45  4985.6  908.45
  4985.8  908.95  5000.4  909.67  5007.3  910.46  5030.7  910.00  5036.2  910.47
  5044.0  910.51  5054.2  909.67  5059.7  910.64  5069.4  910.88  5078.2  911.50
  5095.0  913.29  5108.6  914.13  5128.9  915.91  5139.0  916.35  5155.6  917.84
  5160.7  917.88  5179.6  919.76  5189.7  919.81  5208.9  921.80  5212.9  921.80
#Mann=3,-1,0
  4899.9    0.05       0  4981.8   0.033       0  4985.8    0.05       0
Bank Sta=4981.8,4985.8
Exp/Cntr=0.3,0.1

Type RM Length L Ch R = 1,1443,89,89,89
BEGIN DESCRIPTION:
Mapping XS 6df089c1
END DESCRIPTION:
XS GIS Cut Line= 2
      2299033.07      7183318.18      2298984.10      7183635.43
#Sta/Elev= 30
  4906.1  919.66  4918.1  919.38  4928.2  918.85  4938.3  918.07  4958.5  915.28
  4964.6  912.53  4969.6  911.97  4978.8  910.70  4988.9  910.23  4999.0  908.46
  5009.1  907.27  5019.2  906.96  5027.7  907.24  5030.8  906.86  5031.0  906.36
  5034.5  906.36  5034.8  906.86  5039.5  907.60  5049.6  908.43  5059.7  909.02
  5080.0  908.71  5095.9  911.06  5100.9  911.37  5110.3  912.41  5140.7  914.65
  5150.8  915.57  5201.4  919.12  5211.5  919.30  5221.6  920.30  5227.1  920.98
#Mann=3,-1,0
  4906.1    0.05       0  5030.8   0.033       0  5034.8    0.05       0
Bank Sta=5030.8,5034.8
Exp/Cntr=0.3,0.1

Type RM Length L Ch R = 1,1354,283,283,283
BEGIN DESCRIPTION:
MDE S 042 5.0
END DESCRIPTION:
XS GIS Cut Line= 3
      2298978.99      7183310.01      2298929.00      7183410.00
      2298879.00      7183510.01
#Sta/Elev= 30
  4888.2  919.69  4891.0  919.69  4896.6  917.44  4902.2  915.60  4918.9  912.98
  4924.5  911.80  4932.9  910.56  4955.3  909.15  4969.2  907.69  4977.6  905.16
  4986.0  904.80  4989.6  903.64  4989.9  903.14  4993.4  903.14  4993.6  903.64
  4997.2  905.39  5002.8  905.39  5008.4  905.89  5014.0  905.73  5022.4  905.99
  5030.7  907.20  5036.3  907.06  5044.7  908.15  5053.1  909.90  5075.5  913.28
  5081.0  913.47  5097.8  915.08  5103.4  914.92  5109.0  915.62  5111.8  915.62
#Mann=3,-1,0
  4888.2    0.05       0  4989.6   0.033       0  4993.6    0.05       0
Bank Sta=4989.6,4993.6
Exp/Cntr=0.3,0.1

Type RM Length L Ch R = 1,1071,86,86,86
BEGIN DESCRIPTION:
MDE S 042 4.0
END DESCRIPTION:
XS GIS Cut Line= 3
      2298779.01      7183159.97      2298729.00      7183260.00
      2298729.00      7183559.97
#Sta/Elev= 30
  4884.1  927.21  4886.9  927.21  4892.5  923.67  4898.1  921.87  4906.5  919.53
  4914.9  917.92  4920.5  916.08  4937.2  912.36  4951.2  910.72  4959.6  909.20
  4965.2  908.62  4987.5  906.47  4998.4  906.44  5005.9  904.36  5013.9  900.44
  5014.2  899.94  5017.7  899.94  5017.9  900.44  5035.9  901.21  5065.9  901.41
  5075.9  901.77  5085.9  903.20  5125.9  907.79  5145.9  910.50  5175.9  913.04
  5195.9  914.24  5205.9  915.30  5225.9  916.61  5235.9  917.58  5295.9  921.24
#Mann=3,-1,0
  4884.1    0.05       0  5013.9   0.033       0  5017.9    0.05       0
Bank Sta=5013.9,5017.9
Exp/Cntr=0.3,0.1

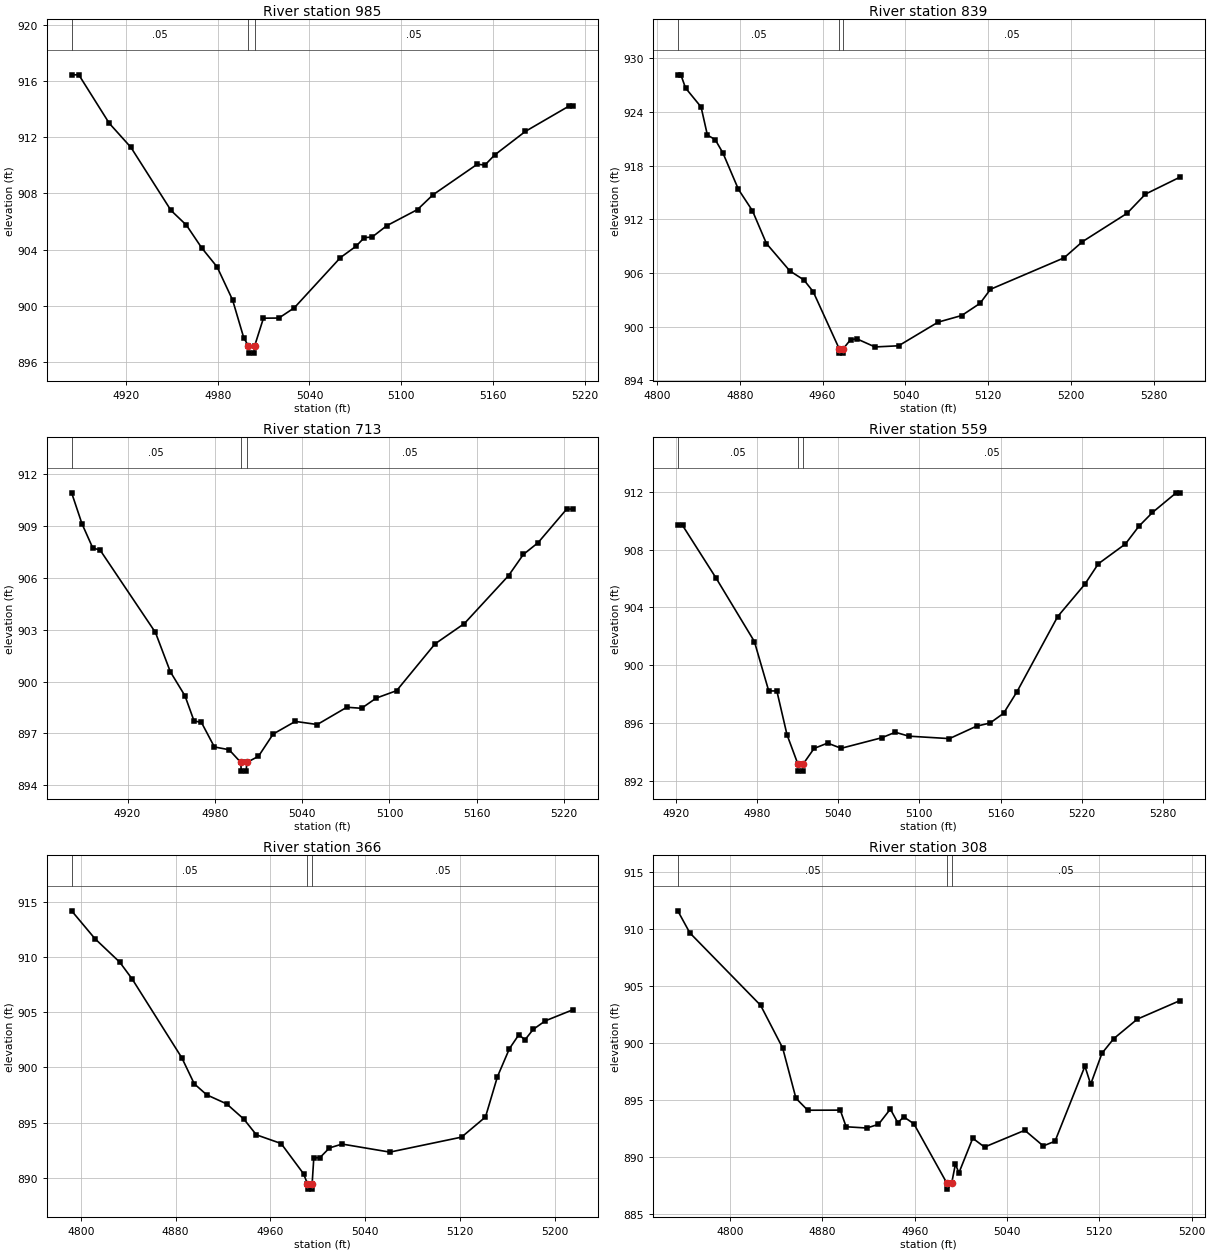
Type RM Length L Ch R = 1,985,146,146,146
BEGIN DESCRIPTION:
Mapping XS be4d9ba0
END DESCRIPTION:
XS GIS Cut Line= 2
      2298658.90      7183145.57      2298616.33      7183471.10
#Sta/Elev= 30
  4884.4  916.45  4889.1  916.45  4909.0  913.00  4923.2  911.28  4949.4  906.79
  4959.5  905.74  4969.5  904.12  4979.6  902.76  4989.7  900.41  4997.0  897.72
  5000.1  897.12  5000.3  896.62  5003.8  896.62  5004.1  897.12  5009.9  899.11
  5020.0  899.12  5030.1  899.85  5060.3  903.43  5070.4  904.23  5075.9  904.85
  5081.0  904.89  5090.6  905.70  5110.7  906.85  5120.8  907.90  5149.8  910.08
  5154.8  910.02  5161.2  910.74  5181.3  912.42  5209.6  914.21  5212.7  914.21
#Mann=3,-1,0
  4884.4    0.05       0  5000.1   0.033       0  5004.1    0.05       0
Bank Sta=5000.1,5004.1
Exp/Cntr=0.3,0.1

Type RM Length L Ch R = 1,839,126,126,126
BEGIN DESCRIPTION:
MDE S 042 3.0
END DESCRIPTION:
XS GIS Cut Line= 3
      2298629.01      7183059.99      2298529.00      7183210.00
      2298479.01      7183509.97
#Sta/Elev= 30
  4820.2  928.13  4823.2  928.13  4827.7  926.66  4842.7  924.54  4848.8  921.40
  4856.3  920.90  4863.8  919.40  4878.8  915.33  4892.3  912.95  4905.8  909.29
  4928.4  906.23  4941.9  905.23  4950.9  903.92  4976.0  897.55  4976.2  897.05
  4979.7  897.05  4980.0  897.55  4987.0  898.55  4993.0  898.65  5010.6  897.74
  5033.4  897.87  5071.5  900.51  5094.3  901.25  5112.0  902.61  5122.1  904.18
  5193.1  907.69  5210.9  909.50  5253.9  912.66  5271.7  914.81  5304.6  916.68
#Mann=3,-1,0
  4820.2    0.05       0  4976.0   0.033       0  4980.0    0.05       0
Bank Sta=4976,4980
Exp/Cntr=0.3,0.1

Type RM Length L Ch R = 1,713,154,154,154
BEGIN DESCRIPTION:
Mapping XS e702b8dc
END DESCRIPTION:
XS GIS Cut Line= 2
      2298426.47      7183072.98      2298376.10      7183414.08
#Sta/Elev= 30
  4881.6  910.93  4888.7  909.14  4896.1  907.74  4901.2  907.61  4939.2  902.84
  4949.4  900.57  4959.5  899.17  4965.7  897.72  4970.8  897.63  4979.7  896.21
  4989.8  896.05  4997.9  895.31  4998.1  894.81  5001.6  894.81  5001.9  895.31
  5010.0  895.67  5020.1  896.96  5035.3  897.69  5050.4  897.51  5070.7  898.51
  5080.8  898.45  5090.9  899.04  5104.9  899.47  5131.3  902.18  5151.5  903.36
  5181.8  906.13  5192.0  907.36  5202.1  908.04  5221.8  909.99  5226.4  909.99
#Mann=3,-1,0
  4881.6    0.05       0  4997.9   0.033       0  5001.9    0.05       0
Bank Sta=4997.9,5001.9
Exp/Cntr=0.3,0.1

Type RM Length L Ch R = 1,559,193,193,193
BEGIN DESCRIPTION:
MDE S 042 2.0
END DESCRIPTION:
XS GIS Cut Line= 3
      2298329.01      7183059.99      2298279.00      7183110.00
      2298279.00      7183409.98
#Sta/Elev= 30
  4921.5  909.68  4925.0  909.68  4949.8  906.03  4978.1  901.64  4988.7  898.22
  4994.7  898.22  5002.2  895.19  5010.2  893.17  5010.5  892.67  5014.0  892.67
  5014.2  893.17  5022.2  894.24  5032.2  894.61  5042.2  894.25  5072.2  894.98
  5082.2  895.36  5092.2  895.09  5122.2  894.92  5142.2  895.78  5152.2  896.00
  5162.2  896.67  5172.2  898.18  5202.2  903.37  5222.2  905.60  5232.2  907.02
  5252.2  908.39  5262.2  909.62  5272.2  910.57  5289.7  911.93  5292.2  911.93
#Mann=3,-1,0
  4921.5    0.05       0  5010.2   0.033       0  5014.2    0.05       0
Bank Sta=5010.2,5014.2
Exp/Cntr=0.3,0.1

Type RM Length L Ch R = 1,366,58,58,58
BEGIN DESCRIPTION:
Mapping XS 2daad5e5
END DESCRIPTION:
XS GIS Cut Line= 3
      2298173.33      7182911.22      2298111.95      7183107.67
      2298139.42      7183323.62
#Sta/Elev= 30
  4792.3  914.22  4812.0  911.69  4832.9  909.56  4843.4  908.03  4885.3  900.88
  4895.8  898.52  4906.3  897.52  4923.1  896.70  4937.7  895.31  4948.2  893.89
  4969.1  893.10  4988.0  890.36  4991.3  889.46  4991.5  888.96  4995.0  888.96
  4995.3  889.46  4996.7  891.81  5001.8  891.81  5009.9  892.70  5020.6  893.05
  5060.9  892.32  5121.4  893.68  5141.6  895.51  5151.7  899.17  5161.8  901.71
  5169.8  902.98  5174.9  902.51  5181.9  903.46  5192.0  904.23  5215.8  905.26
#Mann=3,-1,0
  4792.3    0.05       0  4991.3   0.033       0  4995.3    0.05       0
Bank Sta=4991.3,4995.3
Exp/Cntr=0.3,0.1

Type RM Length L Ch R = 1,308,104,104,104
BEGIN DESCRIPTION:
Mapping XS 347e8129
END DESCRIPTION:
XS GIS Cut Line= 3
      2298103.42      7182869.75      2298053.44      7183108.17
      2298089.32      7183295.97
#Sta/Elev= 30
  4754.7  911.58  4765.2  909.64  4826.5  903.29  4845.6  899.55  4857.1  895.14
  4867.3  894.09  4895.5  894.10  4900.6  892.64  4918.4  892.53  4928.6  892.85
  4938.9  894.19  4945.4  892.99  4950.5  893.51  4959.3  892.90  4988.0  887.67
  4988.2  887.17  4992.0  887.67  4995.3  889.37  4998.3  888.59  5010.3  891.63
  5020.5  890.86  5055.4  892.33  5071.4  890.96  5081.6  891.37  5107.5  897.95
  5112.5  896.37  5122.3  899.09  5132.5  900.37  5152.9  902.08  5189.5  903.69
#Mann=3,-1,0
  4754.7    0.05       0  4988.0   0.033       0  4992.0    0.05       0
Bank Sta=4988,4992
Exp/Cntr=0.3,0.1

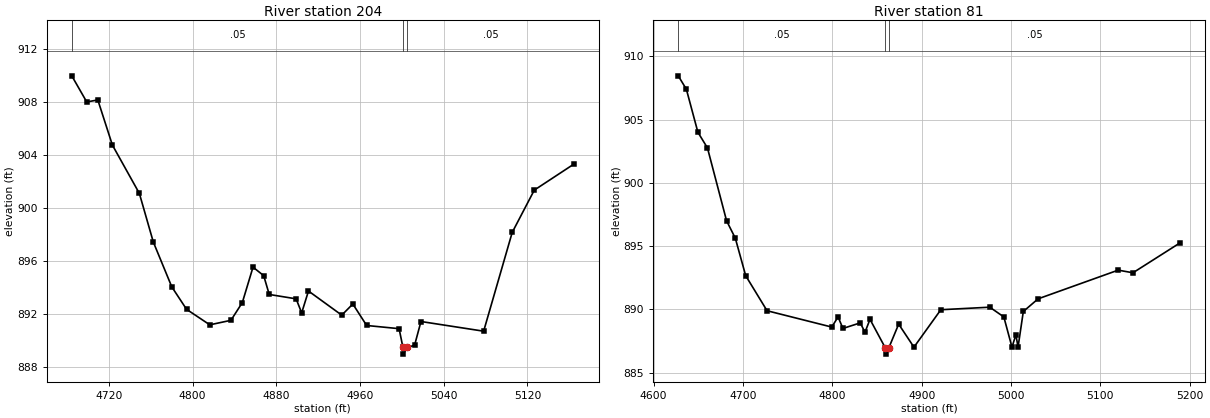
Type RM Length L Ch R = 1,204,123,123,123
BEGIN DESCRIPTION:
Mapping XS 466672ee
END DESCRIPTION:
XS GIS Cut Line= 3
      2298086.18      7182866.48      2297980.23      7183169.21
      2298067.89      7183301.95
#Sta/Elev= 30
  4684.6  909.99  4698.9  908.02  4709.5  908.17  4723.4  904.77  4749.2  901.12
  4762.5  897.46  4780.2  894.07  4794.3  892.38  4816.5  891.21  4836.7  891.55
  4847.6  892.89  4857.8  895.56  4868.0  894.92  4873.3  893.50  4899.0  893.17
  4904.3  892.11  4910.8  893.76  4942.6  891.94  4953.2  892.78  4966.4  891.16
  4997.4  890.92  5001.1  889.50  5001.3  889.00  5005.1  889.50  5012.2  889.67
  5018.3  891.46  5078.2  890.73  5105.5  898.18  5126.6  901.37  5164.4  903.33
#Mann=3,-1,0
  4684.6    0.05       0  5001.1   0.033       0  5005.1    0.05       0
Bank Sta=5001.1,5005.1
Exp/Cntr=0.3,0.1

Type RM Length L Ch R = 1,81,0,0,0
BEGIN DESCRIPTION:
MDE S 042 1.0
END DESCRIPTION:
XS GIS Cut Line= 3
      2298018.39      7182819.48      2297883.42      7183173.36
      2297964.78      7183337.45
#Sta/Elev= 30
  4627.5  908.47  4636.6  907.41  4649.5  904.01  4660.2  902.77  4681.6  897.01
  4691.4  895.63  4703.0  892.67  4726.9  889.90  4799.3  888.61  4806.4  889.41
  4811.8  888.50  4831.2  888.94  4836.5  888.20  4842.1  889.22  4859.2  886.97
  4859.5  886.47  4863.2  886.97  4874.2  888.84  4891.3  887.02  4921.4  889.98
  4976.2  890.18  4991.9  889.41  5001.0  887.02  5005.4  888.00  5007.8  887.02
  5013.7  889.84  5030.2  890.84  5119.9  893.11  5136.4  892.90  5189.4  895.28
#Mann=3,-1,0
  4627.5    0.05       0  4859.2   0.033       0  4863.2    0.05       0
Bank Sta=4859.2,4863.2
Exp/Cntr=0.3,0.1

Chan Stop Cuts=-1