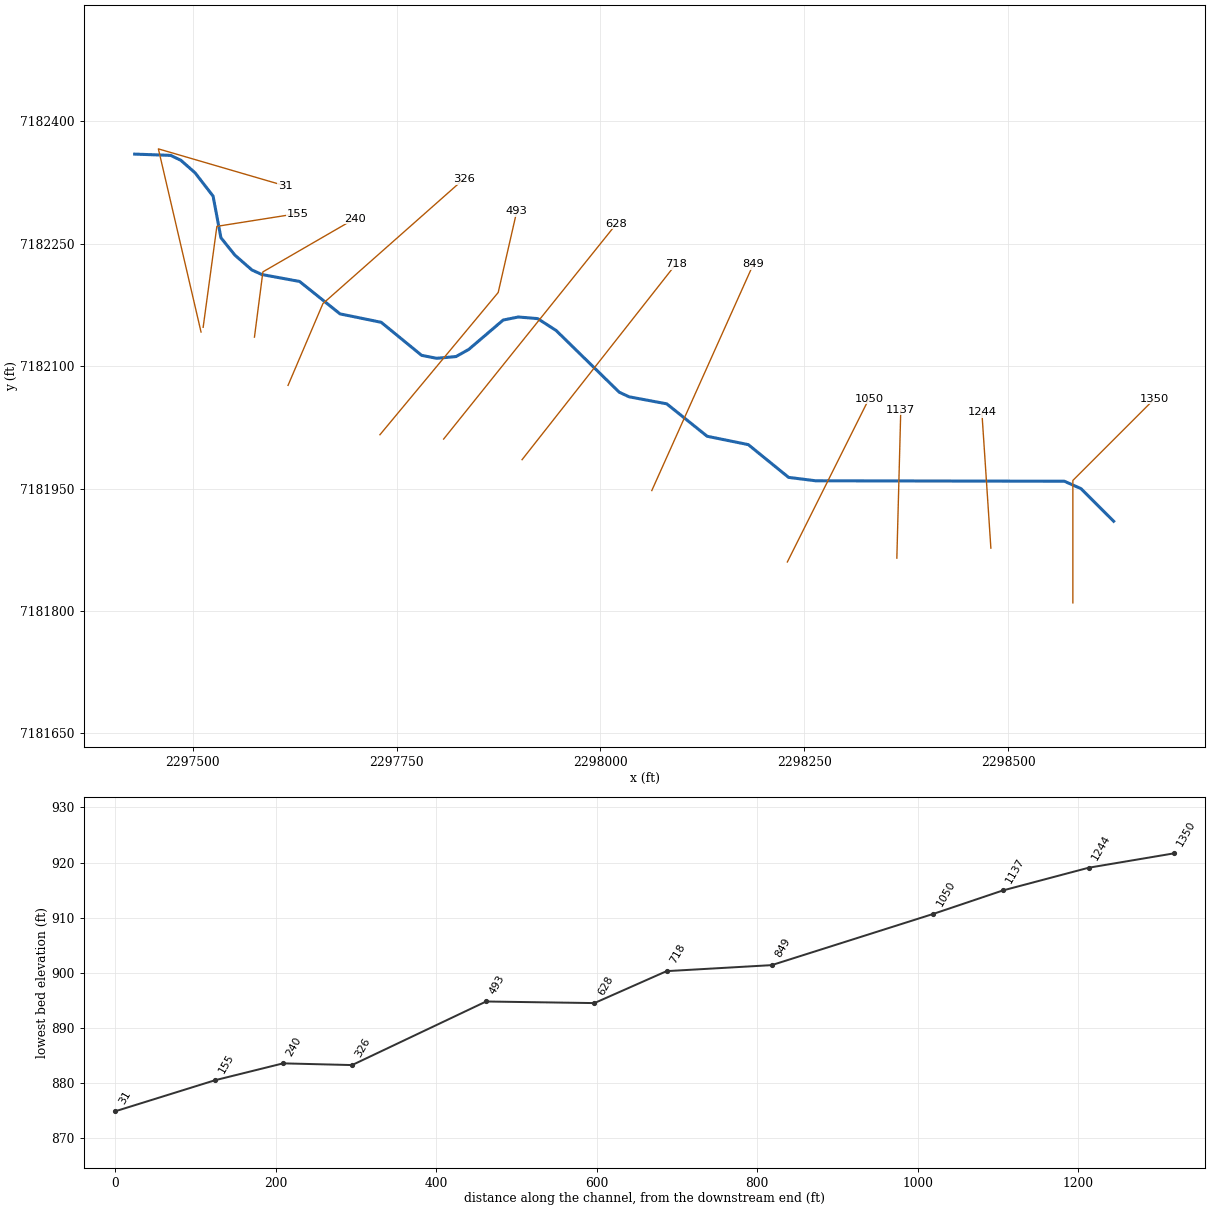
--- MDE S 043.prj (project) ---

Proj Title=MDE S 043 Base Level Engineering
Current Plan=p01
Default Exp/Contr=0.3,0.1
English Units
Geom File=g01
Flow File=f01
Plan File=p01
BEGIN DESCRIPTION:
MDE S 043
END DESCRIPTION:

--- MDE S 043.p01 (plan) ---

Plan Title=Multiple Run
Short Identifier=Multiple
Geom File=g01
Flow File=f01
Subcritical Flow
K Sum by GR= 0
Std Step Tol= 0.01
Critical Tol= 0.01
Num of Std Step Trials= 20
Max Error Tol= 0.3
Flow Tol Ratio= 0.001
Split Flow NTrial= 30
Split Flow Tol= 0.02
Split Flow Ratio= 0.02
Log Output Level= 0
Friction Slope Method= 1
Unsteady Friction Slope Method= 2
Unsteady Bridges Friction Slope Method= 1
Parabolic Critical Depth
Global Vel Dist=  1 , 1 , 1
Global Log Level= 0
CheckData=True
Encroach Param= -1, 0, 0, 0
BEGIN DESCRIPTION:
Multiple Run
END DESCRIPTION:

--- MDE S 043.f01 (steady flow) ---

Flow Title=Multiple
Number of Profiles=7
Profile Names=10-year,25-year,50-year,1pct_min,100-year,1pct_plu,500-year
River Rch & RM= MDE S 043,Reach-1,1350
     128     159     182     104     208     415     271
Boundary for River Rch & Prof#=MDE S 043,Reach-1,1
Up Type=0
Dn Type=3
Dn Slope=0.005
Boundary for River Rch & Prof#=MDE S 043,Reach-1,2
Up Type=0
Dn Type=3
Dn Slope=0.005
Boundary for River Rch & Prof#=MDE S 043,Reach-1,3
Up Type=0
Dn Type=3
Dn Slope=0.005
Boundary for River Rch & Prof#=MDE S 043,Reach-1,4
Up Type=0
Dn Type=3
Dn Slope=0.005
Boundary for River Rch & Prof#=MDE S 043,Reach-1,5
Up Type=0
Dn Type=3
Dn Slope=0.005
Boundary for River Rch & Prof#=MDE S 043,Reach-1,6
Up Type=0
Dn Type=3
Dn Slope=0.005
Boundary for River Rch & Prof#=MDE S 043,Reach-1,7
Up Type=0
Dn Type=3
Dn Slope=0.005

--- MDE S 043.g01 (geometry) ---

Geom Title=Existing Conditions

River Reach=MDE S 043,Reach-1
Reach XY= 30
      2298629.00      7181910.00      2298588.98      7181949.95
      2298568.60      7181959.04      2298263.82      7181959.56
      2298230.55      7181963.75      2298181.18      7182003.88
      2298130.72      7182014.16      2298081.19      7182053.90
      2298035.04      7182062.51      2298022.95      7182068.16
      2297945.66      7182143.75      2297922.96      7182158.37
      2297899.20      7182160.34      2297880.74      7182156.63
      2297838.55      7182120.62      2297822.89      7182111.84
      2297799.18      7182109.71      2297780.72      7182113.34
      2297731.20      7182153.84      2297680.72      7182164.15
      2297631.16      7182203.89      2297584.85      7182212.42
      2297572.66      7182218.02      2297551.86      7182236.16
      2297534.74      7182257.47      2297525.13      7182308.50
      2297502.98      7182337.17      2297485.63      7182352.41
      2297473.13      7182358.44      2297429.00      7182360.00

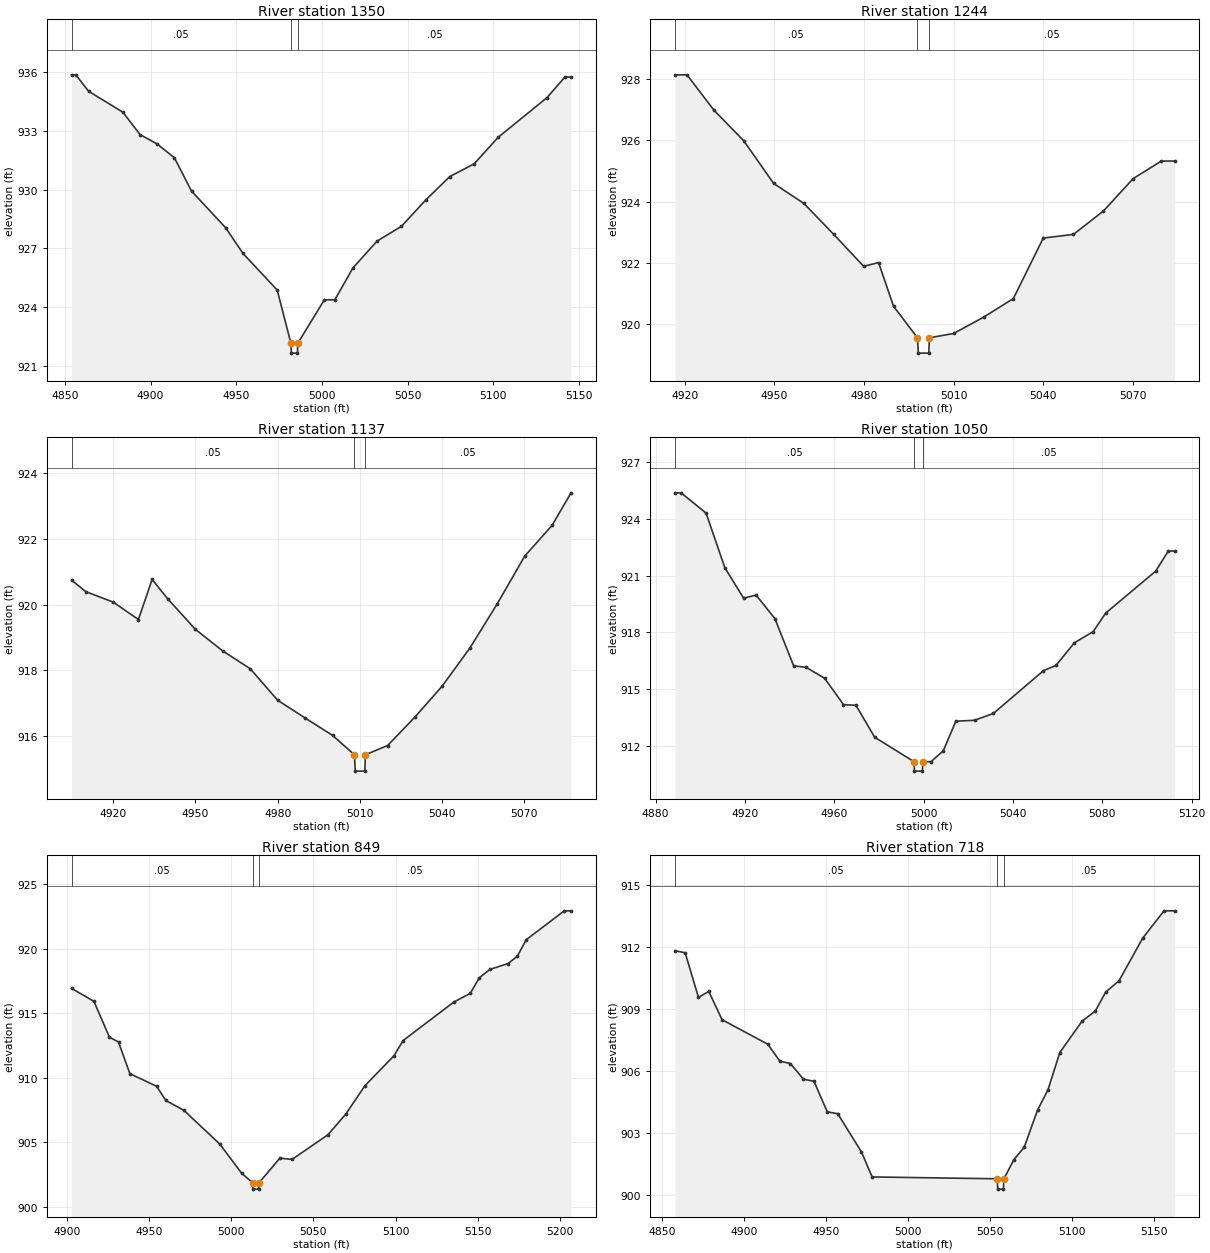
Type RM Length L Ch R = 1,1350,106,106,106
BEGIN DESCRIPTION:
MDE S 043 5.0
END DESCRIPTION:
XS GIS Cut Line= 3
      2298579.00      7181809.97      2298579.00      7181960.00
      2298678.97      7182059.97
#Sta/Elev= 27
  4853.9  935.86  4856.4  935.86  4863.9  935.02  4883.9  933.95  4893.9  932.81
  4903.9  932.33  4913.9  931.63  4923.9  929.93  4943.9  928.05  4953.9  926.75
  4973.9  924.88  4981.9  922.16  4982.2  921.66  4985.7  921.66  4985.9  922.16
  5001.4  924.38  5007.5  924.38  5018.1  926.01  5032.2  927.38  5046.4  928.13
  5060.5  929.47  5074.6  930.67  5088.8  931.32  5102.9  932.68  5131.2  934.69
  5141.8  935.75  5145.3  935.75
#Mann=3,-1,0
  4853.9    0.05       0  4981.9   0.033       0  4985.9    0.05       0
Bank Sta=4981.9,4985.9
Exp/Cntr=0.3,0.1

Type RM Length L Ch R = 1,1244,107,107,107
BEGIN DESCRIPTION:
Mapping XS 88331a4b
END DESCRIPTION:
XS GIS Cut Line= 2
      2298478.50      7181877.04      2298467.45      7182043.77
#Sta/Elev= 23
  4916.8  928.13  4920.8  928.13  4929.8  926.98  4939.8  925.98  4949.8  924.59
  4959.9  923.94  4969.9  922.93  4979.9  921.89  4984.9  922.01  4989.9  920.59
  4997.9  919.56  4998.2  919.06  5001.7  919.06  5001.9  919.56  5010.0  919.70
  5020.0  920.23  5030.0  920.84  5040.0  922.81  5050.1  922.93  5060.1  923.69
  5070.1  924.75  5079.5  925.32  5083.9  925.32
#Mann=3,-1,0
  4916.8    0.05       0  4997.9   0.033       0  5001.9    0.05       0
Bank Sta=4997.9,5001.9
Exp/Cntr=0.3,0.1

Type RM Length L Ch R = 1,1137,87,87,87
BEGIN DESCRIPTION:
Mapping XS 8fc6fdb6
END DESCRIPTION:
XS GIS Cut Line= 2
      2298363.24      7181864.79      2298368.08      7182046.93
#Sta/Elev= 24
  4904.8  920.75  4910.0  920.40  4920.0  920.08  4929.2  919.55  4934.2  920.77
  4940.0  920.17  4950.0  919.25  4960.0  918.59  4970.0  918.05  4980.0  917.09
  4990.0  916.55  5000.0  916.02  5008.0  915.43  5008.3  914.93  5011.8  914.93
  5012.0  915.43  5020.1  915.71  5030.1  916.58  5040.1  917.53  5050.1  918.68
  5060.1  920.03  5070.1  921.48  5080.1  922.42  5087.0  923.41
#Mann=3,-1,0
  4904.8    0.05       0  5008.0   0.033       0  5012.0    0.05       0
Bank Sta=5008,5012
Exp/Cntr=0.3,0.1

Type RM Length L Ch R = 1,1050,201,201,201
BEGIN DESCRIPTION:
MDE S 043 4.0
END DESCRIPTION:
XS GIS Cut Line= 3
      2298229.02      7181860.04      2298279.00      7181960.00
      2298329.02      7182060.03
#Sta/Elev= 30
  4888.7  925.38  4891.4  925.38  4902.6  924.31  4911.0  921.42  4919.4  919.81
  4925.0  919.97  4933.4  918.73  4941.8  916.23  4947.4  916.15  4955.7  915.57
  4964.1  914.18  4969.7  914.14  4978.1  912.45  4995.7  911.16  4995.9  910.66
  4999.4  910.66  4999.7  911.16  5003.3  911.16  5008.8  911.74  5014.4  913.30
  5022.8  913.35  5031.2  913.71  5053.6  915.97  5059.2  916.25  5067.5  917.45
  5075.9  918.04  5081.5  919.02  5103.9  921.24  5109.5  922.30  5112.3  922.30
#Mann=3,-1,0
  4888.7    0.05       0  4995.7   0.033       0  4999.7    0.05       0
Bank Sta=4995.7,4999.7
Exp/Cntr=0.3,0.1

Type RM Length L Ch R = 1,849,131,131,131
BEGIN DESCRIPTION:
Mapping XS 68b18b7d
END DESCRIPTION:
XS GIS Cut Line= 2
      2298062.88      7181947.60      2298187.32      7182224.96
#Sta/Elev= 30
  4902.8  916.92  4916.4  915.92  4925.9  913.14  4931.4  912.77  4938.3  910.32
  4954.6  909.34  4960.2  908.24  4971.2  907.48  4993.1  904.86  5006.4  902.60
  5013.0  901.88  5013.3  901.38  5016.8  901.38  5017.0  901.88  5029.6  903.78
  5037.0  903.68  5058.9  905.59  5069.8  907.20  5081.4  909.39  5099.1  911.71
  5104.6  912.88  5135.6  915.87  5145.5  916.53  5150.9  917.73  5157.5  918.39
  5168.5  918.84  5174.1  919.40  5179.6  920.69  5202.7  922.92  5206.8  922.92
#Mann=3,-1,0
  4902.8    0.05       0  5013.0   0.033       0  5017.0    0.05       0
Bank Sta=5013,5017
Exp/Cntr=0.3,0.1

Type RM Length L Ch R = 1,718,90,90,90
BEGIN DESCRIPTION:
Mapping XS 592cdd98
END DESCRIPTION:
XS GIS Cut Line= 2
      2297903.86      7181985.43      2298092.31      7182225.00
#Sta/Elev= 30
  4858.0  911.83  4864.2  911.73  4872.3  909.57  4878.6  909.86  4886.7  908.49
  4914.7  907.30  4922.0  906.48  4928.4  906.37  4936.4  905.61  4942.8  905.51
  4950.9  904.03  4957.3  903.94  4971.7  902.10  4978.3  900.88  5054.7  900.79
  5054.9  900.29  5058.4  900.29  5058.7  900.79  5064.8  901.72  5071.1  902.32
  5079.2  904.11  5085.6  905.10  5092.8  906.90  5106.4  908.42  5114.5  908.91
  5120.8  909.83  5128.9  910.37  5143.4  912.44  5156.4  913.76  5162.8  913.76
#Mann=3,-1,0
  4858.0    0.05       0  5054.7   0.033       0  5058.7    0.05       0
Bank Sta=5054.7,5058.7
Exp/Cntr=0.3,0.1

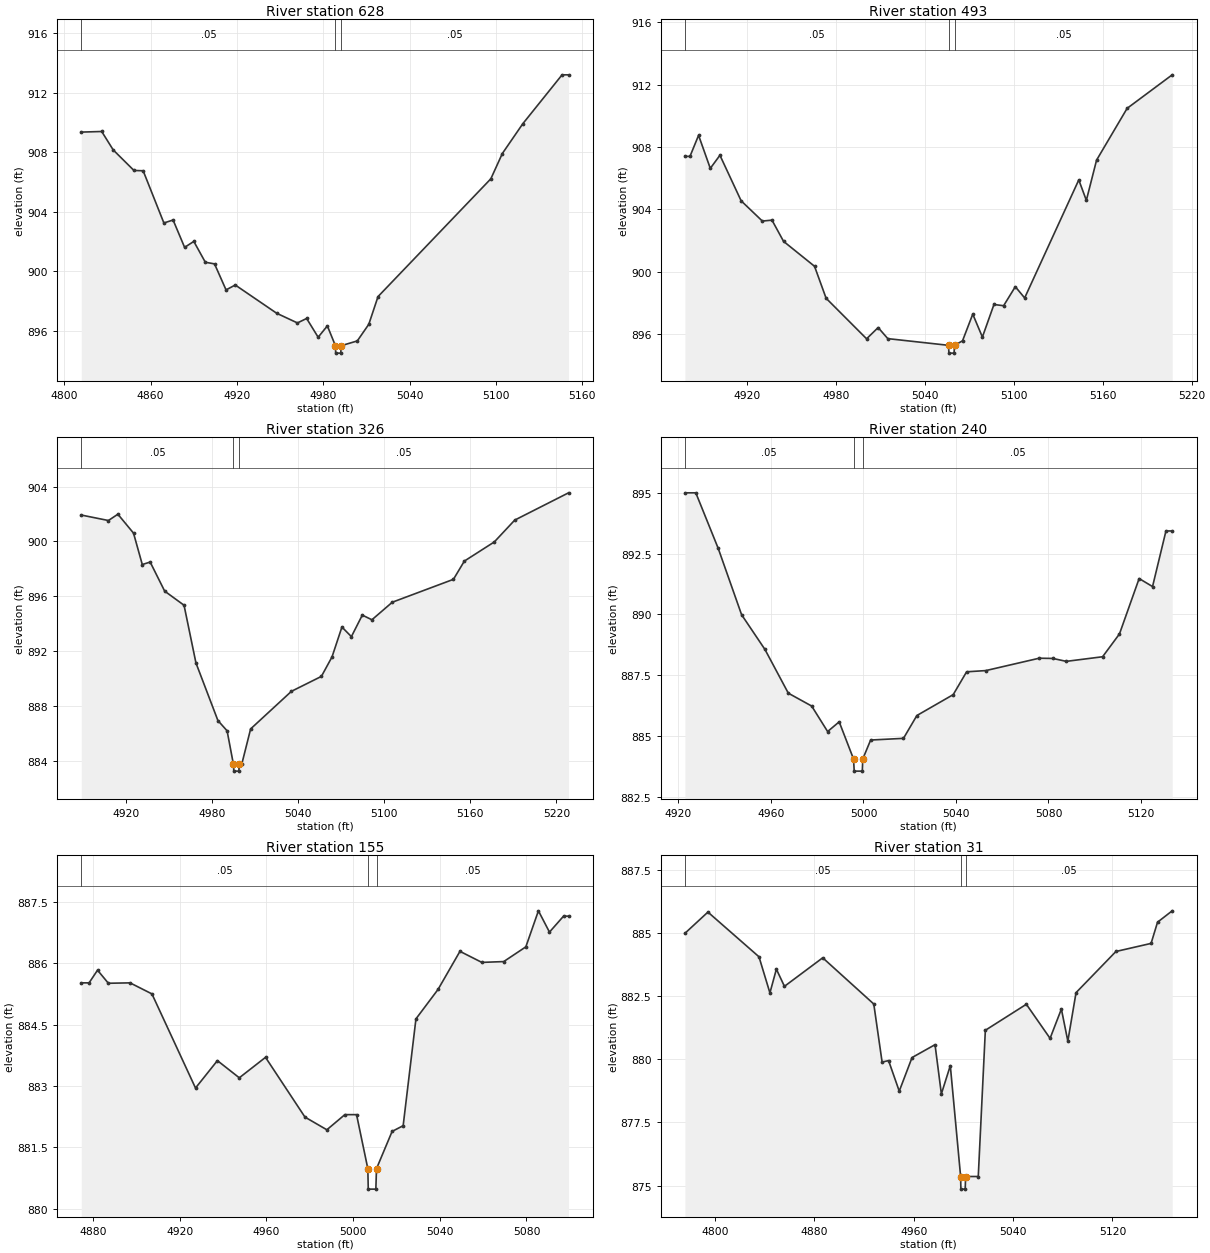
Type RM Length L Ch R = 1,628,135,135,135
BEGIN DESCRIPTION:
Mapping XS 8a860e4d
END DESCRIPTION:
XS GIS Cut Line= 2
      2297807.72      7182010.72      2298019.66      7182274.78
#Sta/Elev= 30
  4811.8  909.35  4826.0  909.39  4834.0  908.15  4848.4  906.77  4854.8  906.75
  4869.2  903.24  4875.6  903.44  4883.6  901.60  4890.0  902.00  4898.0  900.60
  4904.4  900.49  4912.4  898.74  4918.8  899.07  4947.6  897.17  4962.0  896.52
  4968.4  896.82  4976.4  895.56  4982.8  896.32  4988.4  894.99  4988.6  894.49
  4992.1  894.49  4992.4  894.99  5003.6  895.31  5011.6  896.43  5018.0  898.29
  5096.4  906.21  5104.4  907.91  5118.6  909.91  5145.9  913.20  5150.4  913.20
#Mann=3,-1,0
  4811.8    0.05       0  4988.4   0.033       0  4992.4    0.05       0
Bank Sta=4988.4,4992.4
Exp/Cntr=0.3,0.1

Type RM Length L Ch R = 1,493,167,167,167
BEGIN DESCRIPTION:
Mapping XS 1dc8a790
END DESCRIPTION:
XS GIS Cut Line= 3
      2297729.65      7182016.03      2297874.61      7182190.39
      2297897.33      7182289.67
#Sta/Elev= 30
  4878.2  907.40  4881.6  907.40  4887.4  908.75  4895.3  906.63  4901.8  907.47
  4916.1  904.55  4930.4  903.25  4936.9  903.31  4944.7  901.95  4965.6  900.35
  4973.4  898.30  5000.7  895.70  5008.5  896.42  5015.0  895.71  5056.0  895.28
  5056.2  894.78  5059.7  894.78  5060.0  895.28  5065.4  895.57  5072.3  897.28
  5078.8  895.81  5086.6  897.90  5093.1  897.82  5101.0  899.04  5107.3  898.32
  5143.8  905.89  5148.9  904.58  5155.8  907.16  5176.4  910.48  5206.8  912.63
#Mann=3,-1,0
  4878.2    0.05       0  5056.0   0.033       0  5060.0    0.05       0
Bank Sta=5056,5060
Exp/Cntr=0.3,0.1

Type RM Length L Ch R = 1,326,86,86,86
BEGIN DESCRIPTION:
Mapping XS 2b0fadf1
END DESCRIPTION:
XS GIS Cut Line= 3
      2297617.02      7182076.55      2297659.77      7182176.78
      2297832.47      7182329.50
#Sta/Elev= 30
  4889.0  901.92  4907.9  901.52  4914.5  901.98  4925.4  900.60  4931.5  898.31
  4937.0  898.49  4947.1  896.37  4960.6  895.34  4968.9  891.13  4984.2  886.93
  4990.6  886.18  4995.0  883.74  4995.3  883.24  4998.8  883.24  4999.0  883.74
  5000.8  883.74  5007.0  886.32  5035.4  889.06  5056.3  890.15  5063.7  891.57
  5070.6  893.75  5077.2  893.05  5084.8  894.62  5091.5  894.28  5105.7  895.56
  5148.3  897.23  5155.9  898.56  5176.8  899.96  5191.0  901.55  5228.5  903.54
#Mann=3,-1,0
  4889.0    0.05       0  4995.0   0.033       0  4999.0    0.05       0
Bank Sta=4995,4999
Exp/Cntr=0.3,0.1

Type RM Length L Ch R = 1,240,85,85,85
BEGIN DESCRIPTION:
Mapping XS 3ba14f1f
END DESCRIPTION:
XS GIS Cut Line= 3
      2297575.84      7182135.67      2297586.19      7182215.64
      2297698.77      7182280.79
#Sta/Elev= 28
  4922.8  895.01  4927.5  895.01  4937.2  892.72  4947.3  889.99  4957.4  888.56
  4967.5  886.76  4977.6  886.23  4984.5  885.18  4989.5  885.58  4995.7  884.05
  4996.0  883.55  4999.5  883.55  4999.7  884.05  5003.1  884.83  5017.3  884.90
  5023.1  885.84  5038.8  886.70  5044.6  887.64  5052.9  887.69  5076.0  888.20
  5081.9  888.19  5087.7  888.07  5103.4  888.26  5110.7  889.20  5119.2  891.48
  5125.0  891.15  5130.8  893.44  5133.5  893.44
#Mann=3,-1,0
  4922.8    0.05       0  4995.7   0.033       0  4999.7    0.05       0
Bank Sta=4995.7,4999.7
Exp/Cntr=0.3,0.1

Type RM Length L Ch R = 1,155,124,124,124
BEGIN DESCRIPTION:
Mapping XS 08b268a3
END DESCRIPTION:
XS GIS Cut Line= 3
      2297512.97      7182147.74      2297529.78      7182271.46
      2297628.50      7182287.05
#Sta/Elev= 30
  4874.6  885.52  4878.2  885.52  4882.1  885.83  4887.1  885.51  4897.1  885.52
  4907.2  885.25  4927.3  882.95  4937.4  883.62  4947.5  883.20  4959.6  883.70
  4977.8  882.24  4987.9  881.93  4996.2  882.30  5001.6  882.30  5006.8  880.98
  5007.0  880.48  5010.5  880.48  5010.8  880.98  5018.0  881.89  5023.1  882.03
  5029.0  884.64  5039.2  885.36  5049.3  886.29  5059.4  886.02  5069.5  886.04
  5079.7  886.40  5085.5  887.28  5090.6  886.76  5097.1  887.15  5099.4  887.15
#Mann=3,-1,0
  4874.6    0.05       0  5006.8   0.033       0  5010.8    0.05       0
Bank Sta=5006.8,5010.8
Exp/Cntr=0.3,0.1

Type RM Length L Ch R = 1,31,0,0,0
BEGIN DESCRIPTION:
MDE S 043 1.0
END DESCRIPTION:
XS GIS Cut Line= 3
      2297510.37      7182141.96      2297458.08      7182366.42
      2297613.33      7182321.10
#Sta/Elev= 30
  4775.9  884.99  4794.4  885.83  4835.5  884.06  4844.3  882.63  4849.5  883.57
  4856.0  882.89  4886.8  884.02  4927.9  882.19  4934.6  879.89  4939.8  879.95
  4948.4  878.74  4958.7  880.07  4977.2  880.58  4982.3  878.63  4989.5  879.75
  4997.8  875.36  4998.0  874.86  5001.5  874.86  5001.8  875.36  5012.0  875.36
  5017.7  881.15  5050.7  882.18  5069.8  880.83  5078.9  881.99  5084.1  880.72
  5090.7  882.64  5122.8  884.27  5151.1  884.59  5156.3  885.43  5168.1  885.88
#Mann=3,-1,0
  4775.9    0.05       0  4997.8   0.033       0  5001.8    0.05       0
Bank Sta=4997.8,5001.8
Exp/Cntr=0.3,0.1

Chan Stop Cuts=-1