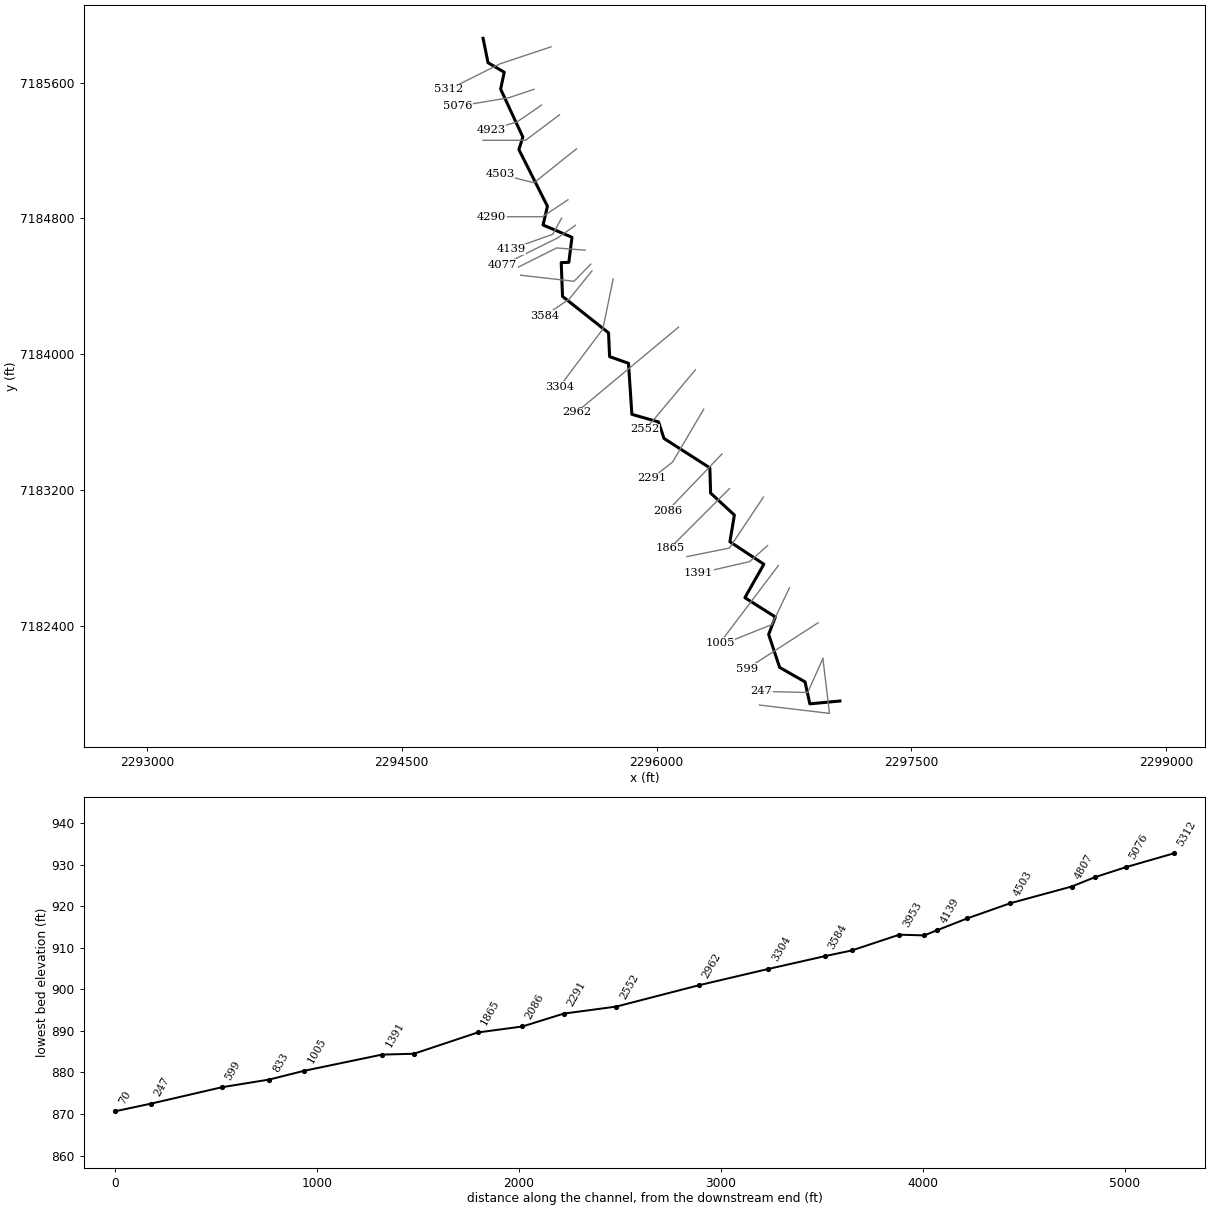
--- MDE S 044.prj (project) ---

Proj Title=MDE S 044 Base Level Engineering
Current Plan=p01
Default Exp/Contr=0.3,0.1
English Units
Geom File=g01
Flow File=f01
Plan File=p01
BEGIN DESCRIPTION:
MDE S 044
END DESCRIPTION:

--- MDE S 044.p01 (plan) ---

Plan Title=Multiple Run
Short Identifier=Multiple
Geom File=g01
Flow File=f01
Subcritical Flow
K Sum by GR= 0
Std Step Tol= 0.01
Critical Tol= 0.01
Num of Std Step Trials= 20
Max Error Tol= 0.3
Flow Tol Ratio= 0.001
Split Flow NTrial= 30
Split Flow Tol= 0.02
Split Flow Ratio= 0.02
Log Output Level= 0
Friction Slope Method= 1
Unsteady Friction Slope Method= 2
Unsteady Bridges Friction Slope Method= 1
Parabolic Critical Depth
Global Vel Dist=  1 , 1 , 1
Global Log Level= 0
CheckData=True
Encroach Param= -1, 0, 0, 0
BEGIN DESCRIPTION:
Multiple Run
END DESCRIPTION:

--- MDE S 044.f01 (steady flow) ---

Flow Title=Multiple
Number of Profiles=7
Profile Names=10-year,25-year,50-year,1pct_min,100-year,1pct_plu,500-year
River Rch & RM= MDE S 044,Reach-1,5312
     507     688     836     505    1008    2012    1469
Boundary for River Rch & Prof#=MDE S 044,Reach-1,1
Up Type=0
Dn Type=3
Dn Slope=0.01
Boundary for River Rch & Prof#=MDE S 044,Reach-1,2
Up Type=0
Dn Type=3
Dn Slope=0.01
Boundary for River Rch & Prof#=MDE S 044,Reach-1,3
Up Type=0
Dn Type=3
Dn Slope=0.01
Boundary for River Rch & Prof#=MDE S 044,Reach-1,4
Up Type=0
Dn Type=3
Dn Slope=0.01
Boundary for River Rch & Prof#=MDE S 044,Reach-1,5
Up Type=0
Dn Type=3
Dn Slope=0.01
Boundary for River Rch & Prof#=MDE S 044,Reach-1,6
Up Type=0
Dn Type=3
Dn Slope=0.01
Boundary for River Rch & Prof#=MDE S 044,Reach-1,7
Up Type=0
Dn Type=3
Dn Slope=0.01

--- MDE S 044.g01 (geometry) ---

Geom Title=Existing Conditions

River Reach=MDE S 044,Reach-1
Reach XY= 30
      2294979.00      7185860.00      2295008.30      7185716.68
      2295103.58      7185660.62      2295082.46      7185561.07
      2295213.13      7185279.14      2295189.96      7185205.23
      2295357.85      7184871.87      2295332.04      7184761.42
      2295502.27      7184689.17      2295483.84      7184541.65
      2295438.99      7184540.00      2295446.65      7184341.24
      2295717.36      7184126.97      2295723.77      7183986.83
      2295834.83      7183947.57      2295854.85      7183647.16
      2296011.83      7183602.42      2296043.72      7183505.31
      2296313.68      7183332.22      2296318.18      7183183.74
      2296458.01      7183054.36      2296431.78      7182897.36
      2296631.53      7182765.13      2296519.89      7182567.94
      2296699.51      7182454.52      2296659.68      7182351.93
      2296724.48      7182157.73      2296873.90      7182072.52
      2296902.15      7181943.30      2297079.00      7181960.00

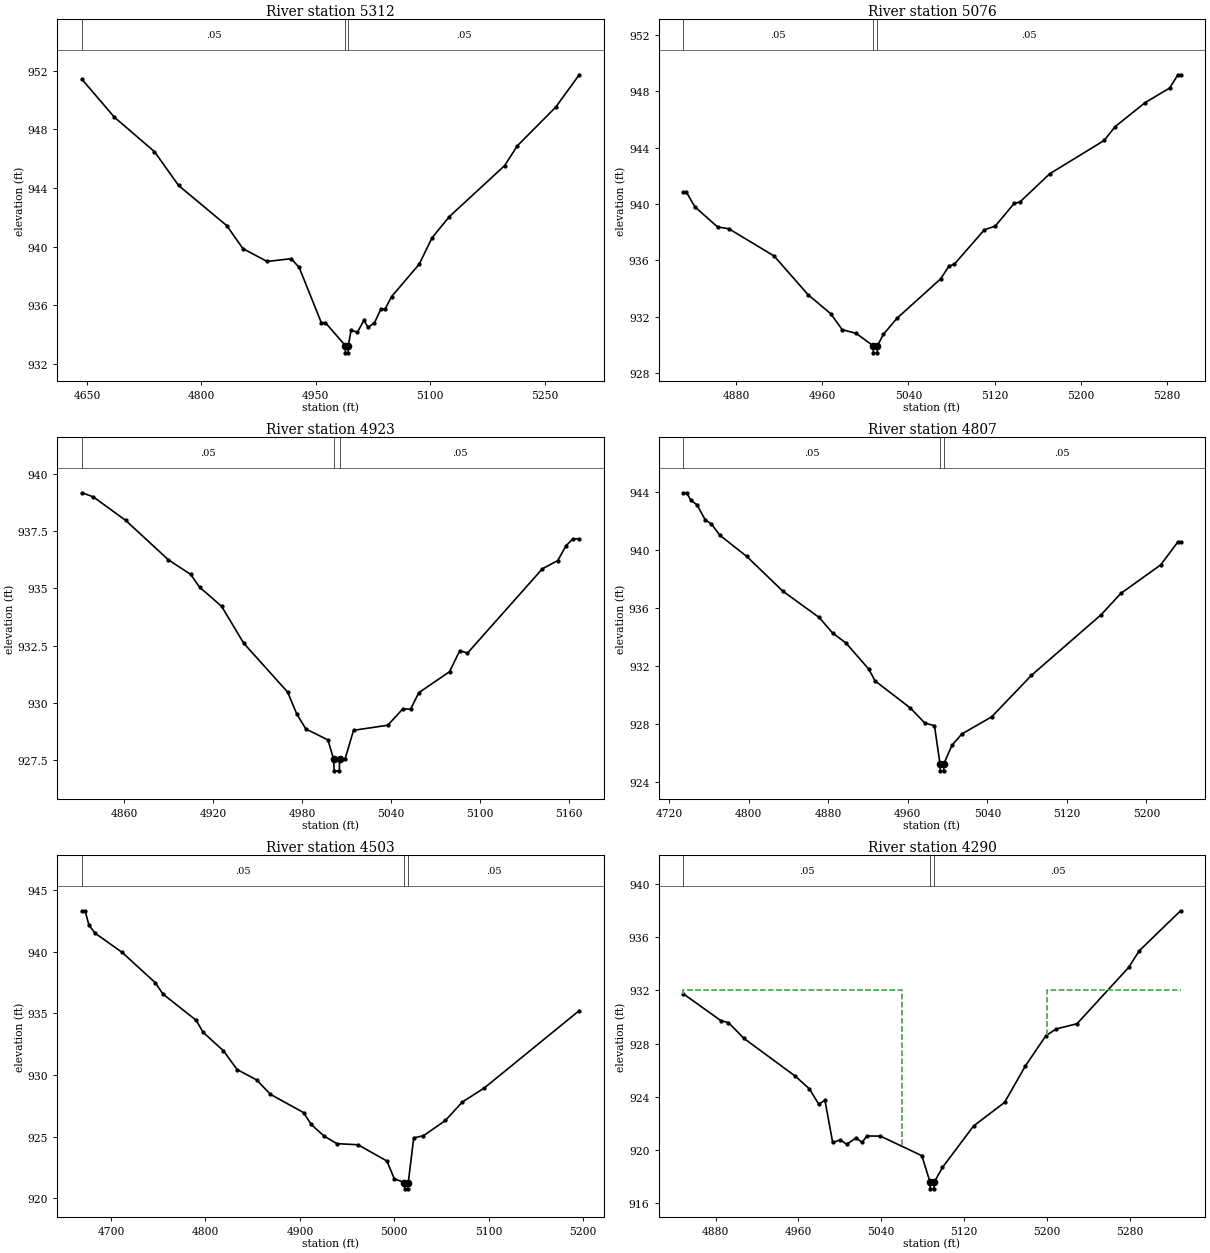
Type RM Length L Ch R = 1,5312,236,236,236
BEGIN DESCRIPTION:
MDE S 044 17.0
END DESCRIPTION:
XS GIS Cut Line= 3
      2295379.02      7185810.01      2295079.00      7185710.00
      2294778.96      7185559.98
#Sta/Elev= 30
  4643.6  951.41  4685.8  948.84  4738.5  946.48  4770.1  944.17  4833.4  941.42
  4854.4  939.86  4886.1  938.98  4917.7  939.17  4928.2  938.57  4957.2  934.80
  4962.6  934.80  4988.6  933.24  4988.8  932.74  4992.3  932.74  4992.6  933.24
  4996.2  934.28  5004.6  934.15  5013.0  934.96  5018.5  934.48  5026.9  934.79
  5035.3  935.73  5040.9  935.74  5049.3  936.58  5085.6  938.80  5102.4  940.60
  5124.8  942.03  5197.4  945.52  5214.2  946.88  5264.5  949.52  5295.3  951.73
#Mann=3,-1,0
  4643.6    0.05       0  4988.6   0.033       0  4992.6    0.05       0
Bank Sta=4988.6,4992.6
Exp/Cntr=0.3,0.1

Type RM Length L Ch R = 1,5076,153,153,153
BEGIN DESCRIPTION:
MDE S 044 16.0
END DESCRIPTION:
XS GIS Cut Line= 3
      2295279.04      7185560.01      2295129.00      7185510.00
      2294829.00      7185460.00
#Sta/Elev= 30
  4830.7  940.86  4833.4  940.86  4841.3  939.81  4862.4  938.38  4872.9  938.25
  4915.1  936.31  4946.7  933.56  4967.8  932.21  4978.3  931.09  4991.4  930.82
  5007.1  929.94  5007.4  929.44  5010.9  929.44  5011.1  929.94  5016.7  930.76
  5029.4  931.90  5070.0  934.70  5077.6  935.60  5082.6  935.73  5110.5  938.17
  5120.7  938.44  5138.4  940.06  5143.5  940.14  5171.3  942.15  5222.0  944.52
  5232.2  945.50  5260.0  947.20  5282.9  948.24  5290.5  949.18  5293.0  949.18
#Mann=3,-1,0
  4830.7    0.05       0  5007.1   0.033       0  5011.1    0.05       0
Bank Sta=5007.1,5011.1
Exp/Cntr=0.3,0.1

Type RM Length L Ch R = 1,4923,116,116,116
BEGIN DESCRIPTION:
Mapping XS dafa49a5
END DESCRIPTION:
XS GIS Cut Line= 3
      2295323.30      7185467.19      2295179.37      7185368.30
      2295025.13      7185322.58
#Sta/Elev= 30
  4831.5  939.17  4839.1  938.99  4861.0  937.96  4889.8  936.24  4904.7  935.61
  4910.8  935.05  4925.7  934.21  4940.6  932.60  4970.2  930.47  4976.4  929.51
  4982.5  928.86  4997.4  928.38  5001.3  927.53  5001.6  927.03  5005.1  927.03
  5005.3  927.53  5008.9  927.53  5014.7  928.80  5037.8  929.02  5048.0  929.74
  5053.2  929.72  5058.7  930.44  5079.5  931.36  5086.4  932.28  5091.6  932.17
  5142.1  935.85  5152.5  936.21  5158.1  936.86  5162.8  937.16  5167.0  937.16
#Mann=3,-1,0
  4831.5    0.05       0  5001.3   0.033       0  5005.3    0.05       0
Bank Sta=5001.3,5005.3
Exp/Cntr=0.3,0.1

Type RM Length L Ch R = 1,4807,304,304,304
BEGIN DESCRIPTION:
MDE S 044 15.0
END DESCRIPTION:
XS GIS Cut Line= 3
      2295429.02      7185410.02      2295229.00      7185260.00
      2294979.03      7185260.00
#Sta/Elev= 30
  4734.3  943.93  4737.5  943.93  4741.6  943.43  4747.9  943.10  4756.2  942.07
  4762.5  941.78  4770.8  941.01  4797.9  939.55  4834.3  937.15  4870.8  935.34
  4884.3  934.27  4897.9  933.57  4920.8  931.77  4927.0  930.97  4962.5  929.10
  4977.0  928.07  4986.8  927.88  4992.3  925.27  4992.6  924.77  4996.1  924.77
  4996.3  925.27  5004.3  926.52  5014.3  927.31  5044.3  928.49  5084.3  931.35
  5154.3  935.52  5174.3  937.00  5214.3  938.96  5231.8  940.56  5234.3  940.56
#Mann=3,-1,0
  4734.3    0.05       0  4992.3   0.033       0  4996.3    0.05       0
Bank Sta=4992.3,4996.3
Exp/Cntr=0.3,0.1

Type RM Length L Ch R = 1,4503,213,213,213
BEGIN DESCRIPTION:
MDE S 044 14.0
END DESCRIPTION:
XS GIS Cut Line= 3
      2295528.99      7185210.00      2295279.00      7185010.00
      2295079.00      7185060.00
#Sta/Elev= 30
  4669.4  943.33  4672.6  943.33  4676.6  942.18  4683.0  941.52  4711.8  939.95
  4747.0  937.48  4755.0  936.57  4790.3  934.43  4797.5  933.46  4819.1  931.96
  4833.5  930.44  4854.3  929.59  4868.7  928.43  4903.9  926.94  4911.9  925.98
  4925.5  925.04  4939.1  924.42  4961.5  924.33  4992.1  923.01  4999.9  921.57
  5010.7  921.25  5011.0  920.75  5014.5  920.75  5014.7  921.25  5020.5  924.89
  5030.8  925.06  5054.0  926.30  5072.0  927.80  5095.2  928.94  5195.7  935.22
#Mann=3,-1,0
  4669.4    0.05       0  5010.7   0.033       0  5014.7    0.05       0
Bank Sta=5010.7,5014.7
Exp/Cntr=0.3,0.1

Type RM Length L Ch R = 1,4290,151,151,151
BEGIN DESCRIPTION:
MDE S 044 13.0
END DESCRIPTION:
XS GIS Cut Line= 3
      2295478.98      7184909.99      2295329.00      7184810.00
      2295028.95      7184810.00
#Sta/Elev= 30
  4848.9  931.74  4884.9  929.74  4892.4  929.58  4907.5  928.39  4957.0  925.56
  4970.6  924.61  4979.6  923.46  4985.6  923.75  4993.1  920.58  5000.6  920.78
  5006.6  920.44  5015.6  920.92  5021.6  920.59  5026.1  921.07  5039.2  921.06
  5079.2  919.59  5087.2  917.60  5087.4  917.10  5090.9  917.10  5091.2  917.60
  5099.2  918.71  5129.2  921.82  5159.2  923.59  5179.2  926.32  5199.2  928.61
  5209.2  929.11  5229.2  929.50  5279.2  933.74  5289.2  934.97  5329.2  937.98
#Mann=3,-1,0
  4848.9    0.05       0  5087.2   0.033       0  5091.2    0.05       0
#XS Ineff=2,0
    0.00 5060.00  932.00 5200.00    0.00  932.00
Permanent Ineff=
       F       F
Bank Sta=5087.2,5091.2
Exp/Cntr=0.3,0.1

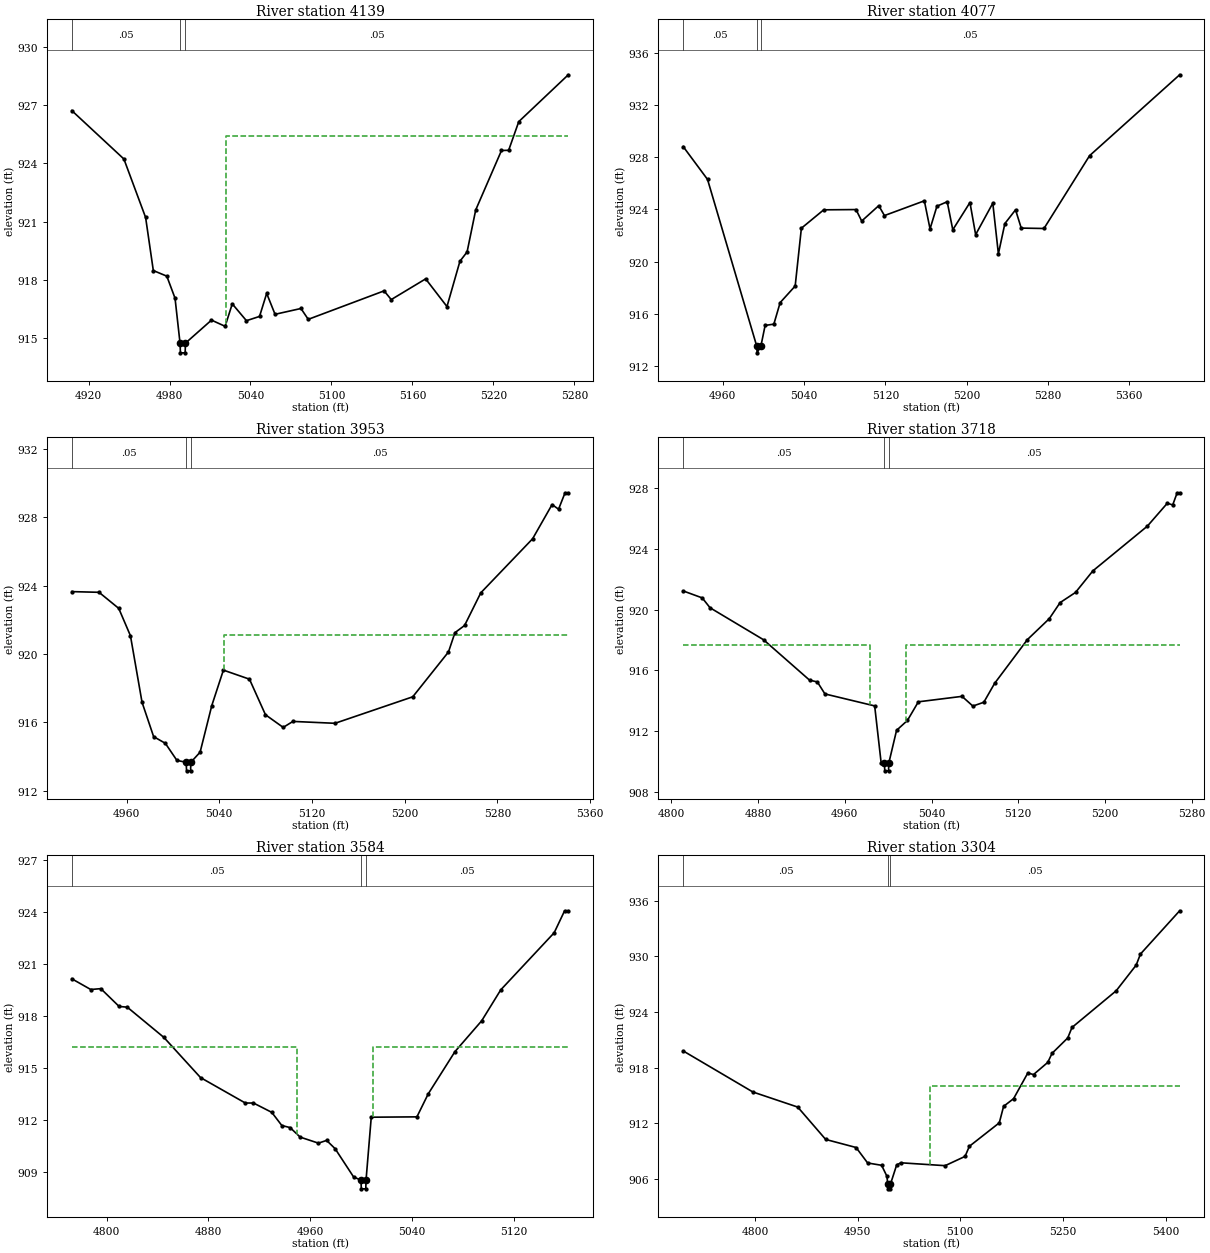
Type RM Length L Ch R = 1,4139,62,62,62
BEGIN DESCRIPTION:
Mapping XS 79e6d26b
END DESCRIPTION:
XS GIS Cut Line= 3
      2295441.02      7184801.69      2295389.02      7184706.92
      2295144.40      7184619.39
#Sta/Elev= 30
  4907.6  926.73  4946.2  924.23  4962.3  921.21  4968.0  918.47  4978.0  918.18
  4984.1  917.04  4987.8  914.72  4988.1  914.22  4991.6  914.22  4991.8  914.72
  5011.1  915.91  5021.2  915.59  5026.5  916.75  5037.0  915.88  5046.7  916.10
  5052.0  917.29  5058.2  916.21  5077.4  916.51  5082.8  915.95  5139.0  917.42
  5144.3  916.97  5169.8  918.04  5185.6  916.61  5195.2  918.95  5200.5  919.43
  5206.9  921.60  5226.0  924.67  5231.3  924.68  5238.8  926.16  5275.5  928.58
#Mann=3,-1,0
  4907.6    0.05       0  4987.8   0.033       0  4991.8    0.05       0
#XS Ineff=2,0
       0                 5021.80    0.00  925.42
Permanent Ineff=
       F       F
Bank Sta=4987.8,4991.8
Exp/Cntr=0.3,0.1

Type RM Length L Ch R = 1,4077,124,124,124
BEGIN DESCRIPTION:
Mapping XS 9e6161db
END DESCRIPTION:
XS GIS Cut Line= 3
      2295522.74      7184759.49      2295416.11      7184684.34
      2295094.72      7184525.61
#Sta/Elev= 30
  4920.9  928.81  4944.9  926.29  4993.4  913.50  4993.7  913.00  4997.4  913.50
  5001.6  915.10  5010.2  915.20  5016.4  916.85  5031.2  918.12  5037.3  922.55
  5059.3  923.96  5091.1  923.98  5096.7  923.10  5113.5  924.28  5119.1  923.52
  5158.4  924.65  5164.0  922.50  5170.8  924.24  5180.9  924.58  5186.4  922.43
  5203.3  924.52  5208.9  922.06  5225.8  924.47  5231.3  920.59  5237.7  922.91
  5248.2  923.96  5253.8  922.56  5276.2  922.53  5321.1  928.11  5409.8  934.31
#Mann=3,-1,0
  4920.9    0.05       0  4993.4   0.033       0  4997.4    0.05       0
Bank Sta=4993.4,4997.4
Exp/Cntr=0.3,0.1

Type RM Length L Ch R = 1,3953,235,235,235
BEGIN DESCRIPTION:
MDE S 044 12.0
END DESCRIPTION:
XS GIS Cut Line= 3
      2295579.41      7184613.34      2295411.69      7184626.35
      2295178.98      7184509.99
#Sta/Elev= 30
  4912.8  923.65  4936.3  923.61  4953.3  922.67  4963.4  921.07  4973.4  917.18
  4983.4  915.17  4993.5  914.78  5003.5  913.78  5011.5  913.67  5011.8  913.17
  5015.3  913.17  5015.5  913.67  5023.5  914.26  5033.6  916.99  5043.6  919.06
  5066.1  918.53  5079.9  916.45  5095.2  915.71  5103.6  916.06  5139.9  915.95
  5207.0  917.50  5237.8  920.12  5243.4  921.25  5251.7  921.67  5265.7  923.58
  5310.4  926.74  5327.2  928.74  5332.8  928.47  5338.4  929.43  5341.2  929.43
#Mann=3,-1,0
  4912.8    0.05       0  5011.5   0.033       0  5015.5    0.05       0
#XS Ineff=2,0
    0.00 4955.70  921.12 5044.30    0.00  921.12
Permanent Ineff=
       F       F
Bank Sta=5011.5,5015.5
Exp/Cntr=0.3,0.1

Type RM Length L Ch R = 1,3718,134,134,134
BEGIN DESCRIPTION:
Mapping XS e16eb4ae
END DESCRIPTION:
XS GIS Cut Line= 3
      2295612.83      7184531.15      2295514.73      7184430.18
      2295199.43      7184465.93
#Sta/Elev= 30
  4810.8  921.24  4828.4  920.78  4835.6  920.13  4885.0  918.02  4927.4  915.36
  4934.6  915.24  4941.6  914.45  4987.5  913.66  4993.5  909.89  4996.5  909.88
  4996.8  909.38  5000.3  909.38  5000.5  909.88  5007.7  912.05  5017.7  912.70
  5027.8  913.93  5068.1  914.29  5078.1  913.65  5088.2  913.90  5098.2  915.15
  5128.4  918.03  5148.6  919.41  5158.6  920.47  5172.8  921.14  5188.8  922.56
  5239.1  925.51  5257.5  927.02  5262.5  926.91  5266.6  927.71  5268.9  927.71
#Mann=3,-1,0
  4810.8    0.05       0  4996.5   0.033       0  5000.5    0.05       0
#XS Ineff=2,0
    0.00 4983.60  917.65 5016.40    0.00  917.65
Permanent Ineff=
       F       F
Bank Sta=4996.5,5000.5
Exp/Cntr=0.3,0.1

Type RM Length L Ch R = 1,3584,280,280,280
BEGIN DESCRIPTION:
Mapping XS 2c7ebc07
END DESCRIPTION:
XS GIS Cut Line= 3
      2295619.79      7184490.98      2295485.29      7184324.68
      2295339.19      7184225.79
#Sta/Elev= 30
  4772.6  920.14  4787.5  919.52  4795.4  919.57  4809.8  918.54  4816.2  918.50
  4845.0  916.75  4873.8  914.43  4909.0  912.96  4915.4  912.96  4929.8  912.42
  4937.7  911.66  4944.2  911.54  4952.1  910.99  4966.5  910.64  4972.9  910.80
  4979.6  910.32  4994.1  908.69  4999.9  908.50  5000.2  908.00  5003.7  908.00
  5003.9  908.50  5008.0  912.14  5043.9  912.16  5052.8  913.49  5073.8  915.93
  5094.8  917.71  5109.8  919.50  5151.8  922.80  5160.0  924.07  5162.9  924.07
#Mann=3,-1,0
  4772.6    0.05       0  4999.9   0.033       0  5003.9    0.05       0
#XS Ineff=2,0
    0.00 4950.00  916.22 5009.10    0.00  916.22
Permanent Ineff=
       F       F
Bank Sta=4999.9,5003.9
Exp/Cntr=0.3,0.1

Type RM Length L Ch R = 1,3304,342,342,342
BEGIN DESCRIPTION:
MDE S 044 9.0
END DESCRIPTION:
XS GIS Cut Line= 3
      2295744.76      7184443.93      2295683.84      7184148.92
      2295428.99      7183809.98
#Sta/Elev= 30
  4695.2  919.80  4797.0  915.37  4862.6  913.74  4903.4  910.25  4947.8  909.38
  4964.7  907.71  4985.1  907.46  4992.9  906.27  4994.0  905.42  4994.3  904.92
  4997.8  904.92  4998.0  905.42  5007.1  907.50  5013.3  907.73  5077.9  907.42
  5107.0  908.42  5113.3  909.51  5157.0  912.04  5163.3  913.82  5177.9  914.65
  5198.7  917.42  5207.0  917.25  5227.8  918.56  5234.1  919.54  5257.0  921.20
  5263.2  922.33  5327.8  926.29  5357.0  929.06  5363.2  930.25  5420.5  934.92
#Mann=3,-1,0
  4695.2    0.05       0  4994.0   0.033       0  4998.0    0.05       0
#XS Ineff=2,0
       0                 5055.40    0.00  915.99
Permanent Ineff=
       F       F
Bank Sta=4994,4998
Exp/Cntr=0.3,0.1

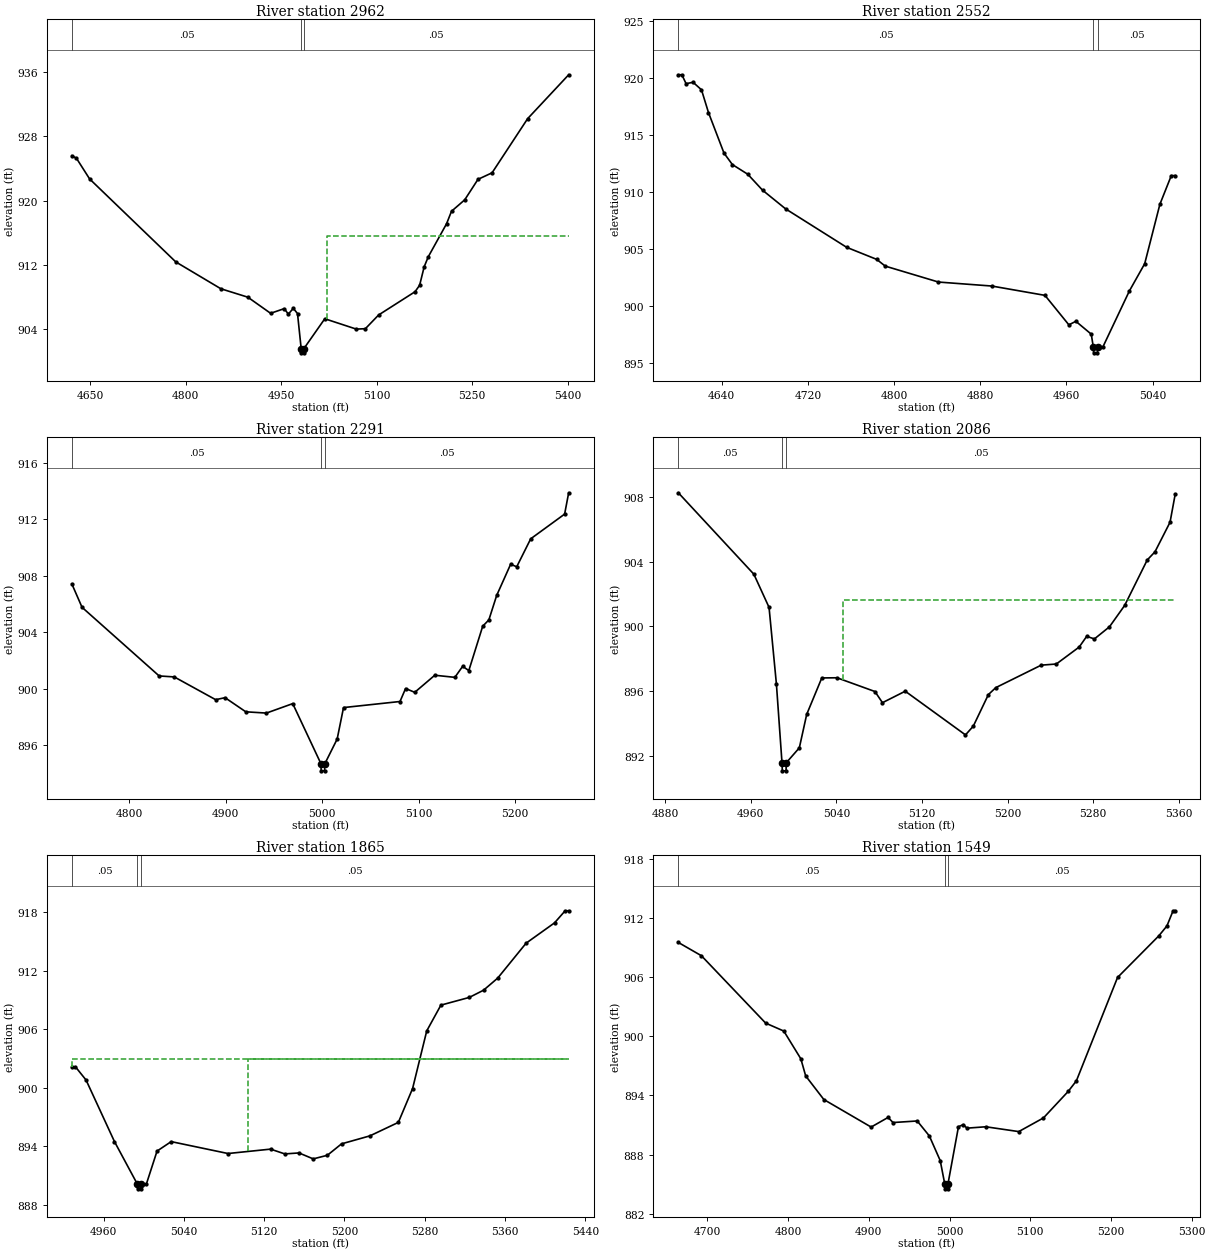
Type RM Length L Ch R = 1,2962,410,410,410
BEGIN DESCRIPTION:
MDE S 044 8.0
END DESCRIPTION:
XS GIS Cut Line= 3
      2296129.03      7184160.03      2295829.00      7183910.00
      2295528.97      7183659.98
#Sta/Elev= 30
  4620.7  925.59  4627.9  925.29  4648.7  922.70  4784.1  912.36  4855.0  909.01
  4897.4  907.96  4933.2  905.95  4954.6  906.53  4961.1  905.85  4968.9  906.57
  4975.5  905.92  4981.3  901.52  4981.5  901.02  4985.0  901.02  4985.3  901.52
  5018.4  905.27  5067.9  903.98  5082.2  904.03  5103.0  905.74  5160.3  908.64
  5167.5  909.45  5174.6  911.74  5181.1  913.00  5209.8  917.11  5217.6  918.67
  5238.4  920.10  5259.2  922.65  5281.4  923.47  5337.3  930.22  5401.8  935.69
#Mann=3,-1,0
  4620.7    0.05       0  4981.3   0.033       0  4985.3    0.05       0
#XS Ineff=2,0
       0                 5021.90    0.00  915.63
Permanent Ineff=
       F       F
Bank Sta=4981.3,4985.3
Exp/Cntr=0.3,0.1

Type RM Length L Ch R = 1,2552,261,261,261
BEGIN DESCRIPTION:
MDE S 044 7.0
END DESCRIPTION:
XS GIS Cut Line= 3
      2296229.03      7183910.04      2295979.00      7183610.00
      2295928.98      7183559.98
#Sta/Elev= 30
  4599.7  920.30  4603.0  920.30  4606.9  919.52  4613.4  919.64  4621.2  918.98
  4627.7  916.98  4642.1  913.42  4649.9  912.41  4664.2  911.56  4677.9  910.16
  4699.3  908.52  4756.0  905.14  4783.9  904.08  4791.8  903.49  4841.2  902.09
  4890.7  901.74  4940.1  900.92  4962.3  898.33  4968.8  898.64  4983.1  897.51
  4985.0  896.37  4985.3  895.87  4988.8  895.87  4989.0  896.37  4993.8  896.37
  5018.5  901.31  5032.7  903.70  5046.8  908.92  5057.4  911.44  5061.0  911.44
#Mann=3,-1,0
  4599.7    0.05       0  4985.0   0.033       0  4989.0    0.05       0
Bank Sta=4985,4989
Exp/Cntr=0.3,0.1

Type RM Length L Ch R = 1,2291,205,205,205
BEGIN DESCRIPTION:
Mapping XS 86207390
END DESCRIPTION:
XS GIS Cut Line= 3
      2296277.58      7183677.18      2296094.31      7183366.33
      2295972.52      7183271.03
#Sta/Elev= 30
  4740.3  907.41  4750.9  905.75  4830.9  900.89  4846.6  900.82  4889.5  899.21
  4899.3  899.35  4920.8  898.35  4942.2  898.26  4969.5  898.93  4998.8  894.67
  4999.0  894.17  5002.5  894.17  5002.8  894.67  5015.6  896.42  5022.2  898.65
  5080.8  899.08  5086.6  900.00  5096.1  899.73  5116.9  900.94  5137.7  900.79
  5145.8  901.57  5152.2  901.27  5166.6  904.41  5173.0  904.86  5181.1  906.59
  5195.6  908.80  5201.9  908.62  5216.4  910.60  5251.6  912.35  5255.8  913.86
#Mann=3,-1,0
  4740.3    0.05       0  4998.8   0.033       0  5002.8    0.05       0
Bank Sta=4998.8,5002.8
Exp/Cntr=0.3,0.1

Type RM Length L Ch R = 1,2086,221,221,221
BEGIN DESCRIPTION:
Mapping XS b9a14af6
END DESCRIPTION:
XS GIS Cut Line= 2
      2296385.02      7183413.72      2296063.72      7183078.41
#Sta/Elev= 30
  4892.2  908.25  4962.8  903.22  4977.0  901.17  4983.9  896.42  4989.1  891.57
  4989.4  891.07  4992.9  891.07  4993.1  891.57  5005.3  892.49  5012.2  894.56
  5026.3  896.81  5040.5  896.82  5076.0  895.97  5083.0  895.28  5104.3  895.99
  5160.6  893.29  5167.9  893.83  5182.0  895.78  5188.9  896.21  5231.4  897.60
  5245.5  897.67  5266.9  898.72  5273.9  899.38  5281.1  899.22  5295.2  899.97
  5309.4  901.29  5330.5  904.10  5337.7  904.60  5351.8  906.43  5356.6  908.15
#Mann=3,-1,0
  4892.2    0.05       0  4989.1   0.033       0  4993.1    0.05       0
#XS Ineff=2,0
    0.00 4954.10  901.65 5045.90    0.00  901.65
Permanent Ineff=
       F       F
Bank Sta=4989.1,4993.1
Exp/Cntr=0.3,0.1

Type RM Length L Ch R = 1,1865,316,316,316
BEGIN DESCRIPTION:
MDE S 044 5.0
END DESCRIPTION:
XS GIS Cut Line= 3
      2296429.03      7183210.03      2296379.00      7183160.00
      2296079.01      7182860.01
#Sta/Elev= 30
  4928.4  902.14  4932.0  902.14  4942.6  900.78  4970.9  894.47  4993.6  890.13
  4993.9  889.63  4997.4  889.63  4997.6  890.13  5002.7  890.13  5013.3  893.50
  5027.4  894.47  5084.0  893.25  5126.4  893.70  5140.6  893.21  5154.7  893.31
  5168.9  892.70  5183.0  893.07  5197.1  894.24  5225.4  895.06  5253.7  896.44
  5267.9  899.91  5282.0  905.82  5296.1  908.46  5324.4  909.25  5338.6  909.99
  5352.7  911.23  5381.0  914.81  5409.3  916.89  5419.9  918.13  5423.4  918.13
#Mann=3,-1,0
  4928.4    0.05       0  4993.6   0.033       0  4997.6    0.05       0
#XS Ineff=2,0
    0.00 4896.00  902.92 5104.00    0.00  902.92
Permanent Ineff=
       F       F
Bank Sta=4993.6,4997.6
Exp/Cntr=0.3,0.1

Type RM Length L Ch R = 1,1549,158,158,158
BEGIN DESCRIPTION:
MDE S 044 4.0
END DESCRIPTION:
XS GIS Cut Line= 3
      2296629.03      7183160.04      2296429.00      7182860.00
      2296178.95      7182809.99
#Sta/Elev= 30
  4664.0  909.56  4692.6  908.21  4772.2  901.36  4794.7  900.55  4815.8  897.73
  4821.8  895.99  4844.3  893.59  4902.9  890.79  4923.9  891.77  4930.0  891.25
  4960.0  891.41  4975.0  889.89  4988.5  887.38  4994.1  885.01  4994.3  884.51
  4997.8  884.51  4998.1  885.01  5011.1  890.83  5017.1  891.04  5021.6  890.68
  5045.0  890.82  5085.8  890.33  5116.4  891.72  5147.0  894.41  5157.2  895.49
  5208.2  906.00  5259.2  910.22  5269.4  911.24  5277.0  912.78  5279.6  912.78
#Mann=3,-1,0
  4664.0    0.05       0  4994.1   0.033       0  4998.1    0.05       0
Bank Sta=4994.1,4998.1
Exp/Cntr=0.3,0.1

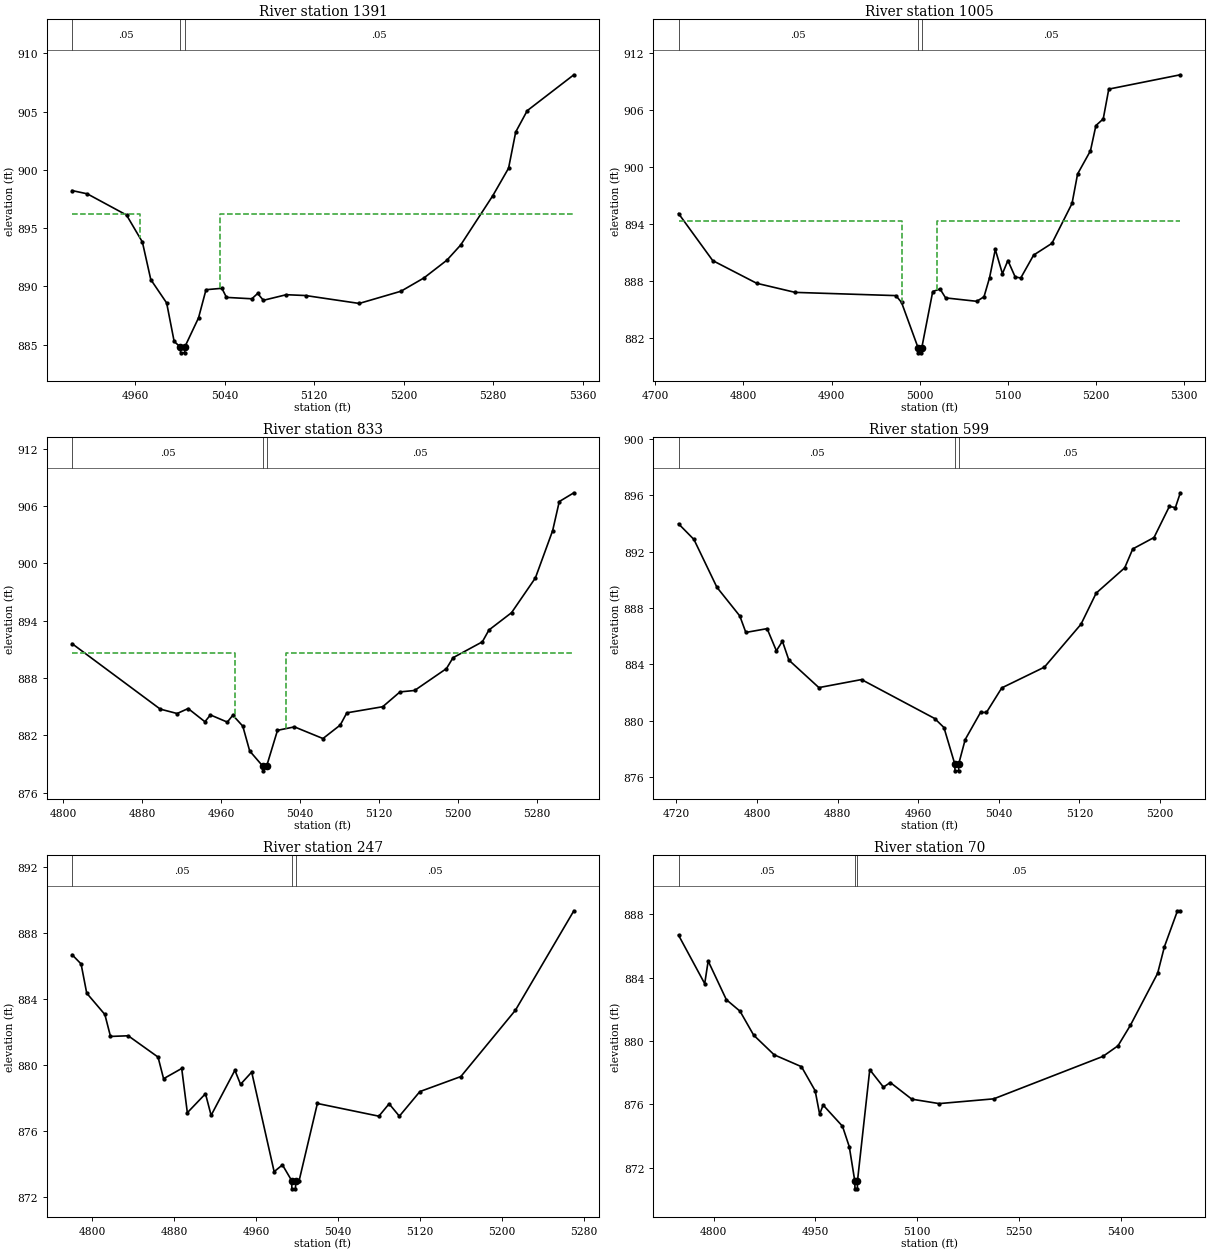
Type RM Length L Ch R = 1,1391,386,386,386
BEGIN DESCRIPTION:
Mapping XS 30e6f4ac
END DESCRIPTION:
XS GIS Cut Line= 3
      2296653.38      7182874.71      2296547.79      7182780.50
      2296248.32      7182711.62
#Sta/Elev= 30
  4903.4  898.23  4917.0  897.95  4952.1  896.13  4966.3  893.81  4973.8  890.59
  4988.0  888.58  4994.7  885.28  5000.2  884.80  5000.5  884.30  5004.0  884.30
  5004.2  884.80  5016.5  887.30  5023.2  889.72  5037.4  889.84  5041.5  889.06
  5064.2  888.94  5069.4  889.40  5074.5  888.81  5095.0  889.29  5112.2  889.22
  5160.2  888.54  5197.6  889.59  5218.1  890.73  5238.6  892.25  5251.0  893.56
  5279.7  897.79  5293.8  900.15  5300.2  903.26  5310.5  905.09  5352.2  908.17
#Mann=3,-1,0
  4903.4    0.05       0  5000.2   0.033       0  5004.2    0.05       0
#XS Ineff=2,0
    0.00 4964.20  896.24 5035.80    0.00  896.24
Permanent Ineff=
       F       F
Bank Sta=5000.2,5004.2
Exp/Cntr=0.3,0.1

Type RM Length L Ch R = 1,1005,172,172,172
BEGIN DESCRIPTION:
Mapping XS aab792ac
END DESCRIPTION:
XS GIS Cut Line= 2
      2296716.72      7182756.82      2296373.30      7182302.51
#Sta/Elev= 30
  4726.3  895.08  4765.1  890.12  4815.0  887.73  4858.7  886.77  4973.0  886.43
  4979.4  885.71  4998.3  880.90  4998.5  880.40  5002.0  880.40  5002.3  880.90
  5014.8  886.86  5023.1  887.13  5029.4  886.19  5064.8  885.83  5073.0  886.31
  5079.3  888.32  5085.8  891.29  5093.9  888.74  5100.1  890.13  5108.4  888.39
  5114.7  888.29  5129.3  890.70  5150.1  891.94  5172.9  896.14  5179.2  899.25
  5193.8  901.69  5200.0  904.35  5208.3  905.05  5214.6  908.19  5295.8  909.70
#Mann=3,-1,0
  4726.3    0.05       0  4998.3   0.033       0  5002.3    0.05       0
#XS Ineff=2,0
    0.00 4980.20  894.28 5019.80    0.00  894.28
Permanent Ineff=
       F       F
Bank Sta=4998.3,5002.3
Exp/Cntr=0.3,0.1

Type RM Length L Ch R = 1,833,234,234,234
BEGIN DESCRIPTION:
MDE S 044 2.0
END DESCRIPTION:
XS GIS Cut Line= 3
      2296782.26      7182626.19      2296679.00      7182410.00
      2296429.04      7182310.02
#Sta/Elev= 30
  4808.8  891.61  4898.2  884.76  4915.3  884.30  4926.5  884.82  4943.5  883.44
  4949.1  884.15  4966.2  883.40  4971.8  884.12  4981.9  882.98  4988.9  880.38
  5002.1  878.80  5002.3  878.30  5006.1  878.80  5017.1  882.54  5034.3  882.90
  5063.2  881.68  5080.7  883.09  5087.4  884.37  5123.8  885.01  5141.3  886.56
  5156.1  886.71  5188.4  889.00  5195.1  890.14  5224.8  891.80  5231.5  893.04
  5254.4  894.85  5278.6  898.49  5296.1  903.44  5302.8  906.48  5317.6  907.40
#Mann=3,-1,0
  4808.8    0.05       0  5002.1   0.033       0  5006.1    0.05       0
#XS Ineff=2,0
    0.00 4974.20  890.67 5025.80    0.00  890.67
Permanent Ineff=
       F       F
Bank Sta=5002.1,5006.1
Exp/Cntr=0.3,0.1

Type RM Length L Ch R = 1,599,352,352,352
BEGIN DESCRIPTION:
Mapping XS ab729d97
END DESCRIPTION:
XS GIS Cut Line= 2
      2296951.01      7182420.60      2296532.58      7182150.57
#Sta/Elev= 30
  4722.1  893.97  4737.4  892.86  4760.2  889.47  4782.9  887.44  4788.9  886.27
  4810.0  886.54  4819.2  884.97  4825.2  885.65  4831.6  884.31  4861.4  882.36
  4903.7  882.93  4976.3  880.17  4985.5  879.53  4996.2  876.96  4996.5  876.46
  5000.0  876.46  5000.2  876.96  5006.6  878.68  5021.8  880.60  5027.7  880.60
  5042.9  882.34  5085.2  883.81  5121.5  886.85  5136.6  889.06  5164.9  890.85
  5172.9  892.19  5194.0  893.00  5209.2  895.20  5215.2  895.12  5220.1  896.17
#Mann=3,-1,0
  4722.1    0.05       0  4996.2   0.033       0  5000.2    0.05       0
Bank Sta=4996.2,5000.2
Exp/Cntr=0.3,0.1

Type RM Length L Ch R = 1,247,177,177,177
BEGIN DESCRIPTION:
Mapping XS 1b267303
END DESCRIPTION:
XS GIS Cut Line= 3
      2296978.99      7182209.97      2296889.48      7182010.21
      2296618.75      7182016.33
#Sta/Elev= 30
  4780.2  886.68  4789.0  886.12  4794.5  884.35  4812.2  883.06  4817.7  881.73
  4835.0  881.77  4864.1  880.48  4869.5  879.17  4887.2  879.79  4892.7  877.11
  4910.4  878.26  4915.9  876.95  4939.1  879.68  4944.6  878.83  4955.5  879.57
  4977.4  873.54  4985.5  873.95  4994.5  873.00  4994.7  872.50  4998.2  872.50
  4998.5  873.00  5001.8  873.00  5019.6  877.67  5079.6  876.90  5089.6  877.65
  5099.6  876.90  5119.6  878.39  5159.6  879.30  5212.9  883.32  5269.9  889.34
#Mann=3,-1,0
  4780.2    0.05       0  4994.5   0.033       0  4998.5    0.05       0
Bank Sta=4994.5,4998.5
Exp/Cntr=0.3,0.1

Type RM Length L Ch R = 1,70,0,0,0
BEGIN DESCRIPTION:
MDE S 044 1.0
END DESCRIPTION:
XS GIS Cut Line= 3
      2296979.00      7182210.04      2297017.75      7181887.26
      2296605.74      7181936.20
#Sta/Elev= 30
  4748.1  886.68  4786.7  883.62  4791.8  885.05  4818.6  882.61  4838.8  881.88
  4858.9  880.37  4889.1  879.13  4929.4  878.38  4949.6  876.86  4956.2  875.38
  4961.3  875.96  4989.9  874.62  4999.9  873.33  5008.0  871.17  5008.3  870.67
  5011.8  870.67  5012.0  871.17  5030.1  878.19  5050.3  877.09  5060.4  877.38
  5092.1  876.33  5132.4  876.05  5212.9  876.35  5374.0  879.03  5396.2  879.70
  5414.3  880.98  5454.6  884.27  5464.7  885.96  5483.9  888.22  5488.1  888.22
#Mann=3,-1,0
  4748.1    0.05       0  5008.0   0.033       0  5012.0    0.05       0
Bank Sta=5008,5012
Exp/Cntr=0.3,0.1

Chan Stop Cuts=-1