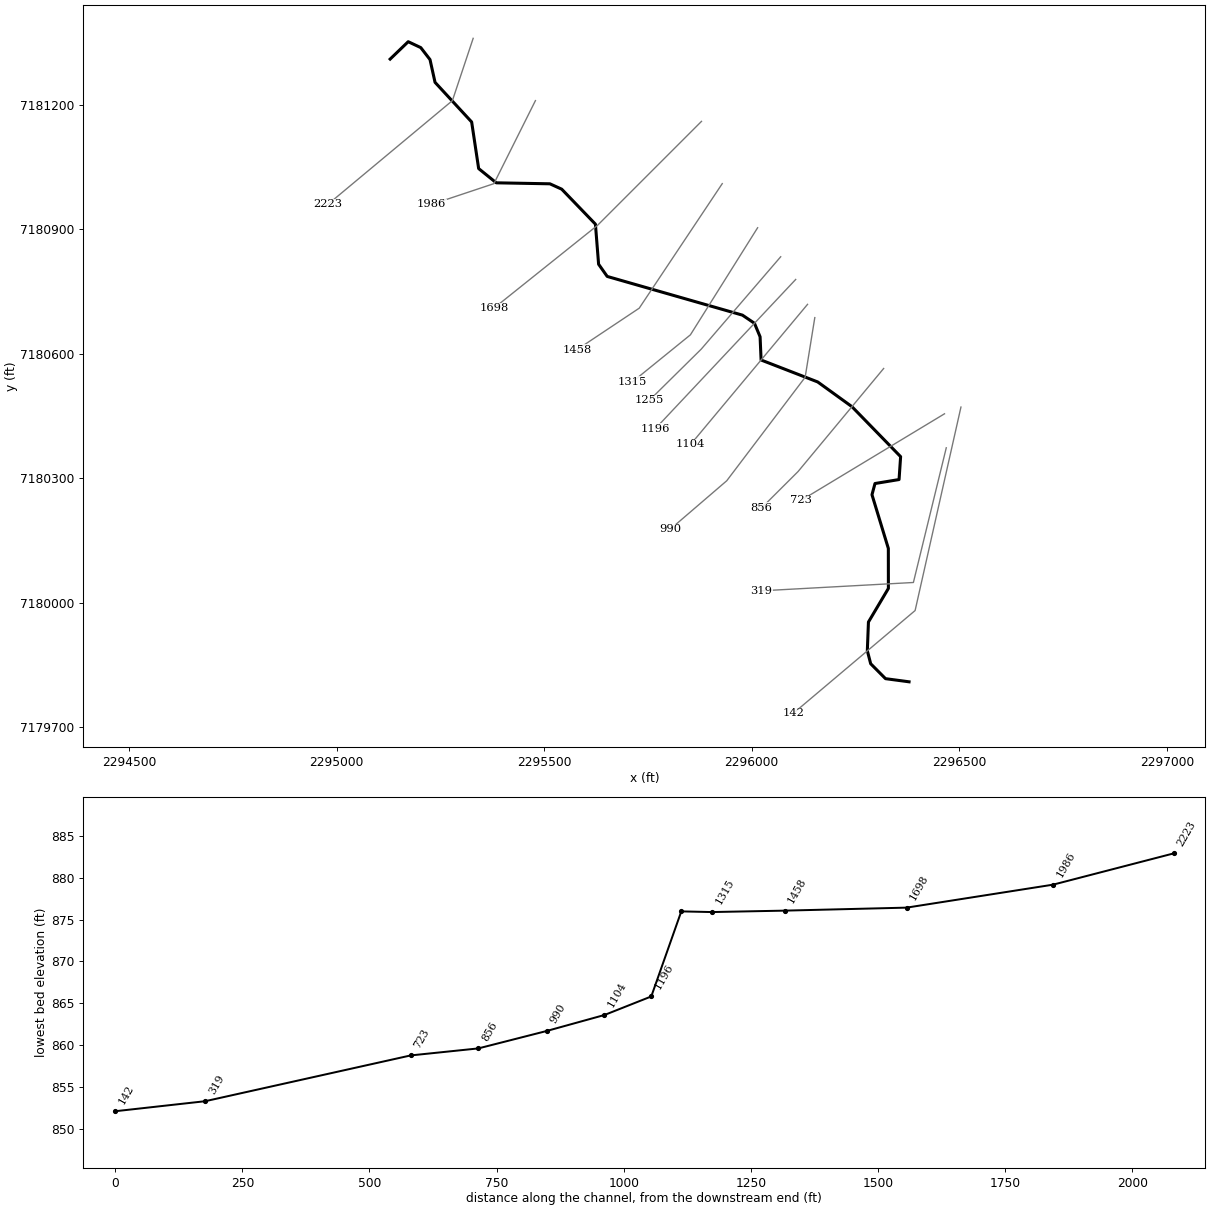
--- MDE S 045.prj (project) ---

Proj Title=MDE S 045 Base Level Engineering
Current Plan=p01
Default Exp/Contr=0.3,0.1
English Units
Geom File=g01
Flow File=f01
Plan File=p01
BEGIN DESCRIPTION:
MDE S 045
END DESCRIPTION:

--- MDE S 045.p01 (plan) ---

Plan Title=Multiple Run
Short Identifier=Multiple
Geom File=g01
Flow File=f01
Subcritical Flow
K Sum by GR= 0
Std Step Tol= 0.01
Critical Tol= 0.01
Num of Std Step Trials= 20
Max Error Tol= 0.3
Flow Tol Ratio= 0.001
Split Flow NTrial= 30
Split Flow Tol= 0.02
Split Flow Ratio= 0.02
Log Output Level= 0
Friction Slope Method= 1
Unsteady Friction Slope Method= 2
Unsteady Bridges Friction Slope Method= 1
Parabolic Critical Depth
Global Vel Dist=  1 , 1 , 1
Global Log Level= 0
CheckData=True
Encroach Param= -1, 0, 0, 0
BEGIN DESCRIPTION:
Multiple Run
END DESCRIPTION:

--- MDE S 045.f01 (steady flow) ---

Flow Title=Multiple
Number of Profiles=7
Profile Names=10-year,25-year,50-year,1pct_min,100-year,1pct_plu,500-year
River Rch & RM= MDE S 045,Reach-1,2223
     287     375     445     264     526    1050     734
Boundary for River Rch & Prof#=MDE S 045,Reach-1,1
Up Type=0
Dn Type=3
Dn Slope=0.005
Boundary for River Rch & Prof#=MDE S 045,Reach-1,2
Up Type=0
Dn Type=3
Dn Slope=0.005
Boundary for River Rch & Prof#=MDE S 045,Reach-1,3
Up Type=0
Dn Type=3
Dn Slope=0.005
Boundary for River Rch & Prof#=MDE S 045,Reach-1,4
Up Type=0
Dn Type=3
Dn Slope=0.005
Boundary for River Rch & Prof#=MDE S 045,Reach-1,5
Up Type=0
Dn Type=3
Dn Slope=0.005
Boundary for River Rch & Prof#=MDE S 045,Reach-1,6
Up Type=0
Dn Type=3
Dn Slope=0.005
Boundary for River Rch & Prof#=MDE S 045,Reach-1,7
Up Type=0
Dn Type=3
Dn Slope=0.005

--- MDE S 045.g01 (geometry) ---

Geom Title=Existing Conditions

River Reach=MDE S 045,Reach-1
Reach XY= 30
      2295129.00      7181310.00      2295172.55      7181351.90
      2295202.80      7181337.65      2295225.05      7181308.78
      2295237.17      7181253.99      2295325.37      7181158.50
      2295342.23      7181046.27      2295384.65      7181011.98
      2295513.84      7181009.60      2295542.35      7180996.64
      2295623.48      7180912.44      2295631.15      7180815.89
      2295651.88      7180786.48      2295977.66      7180693.24
      2296006.60      7180673.62      2296020.14      7180641.13
      2296022.58      7180585.17      2296158.91      7180532.32
      2296241.42      7180472.77      2296358.65      7180352.36
      2296354.91      7180297.21      2296296.93      7180287.64
      2296289.69      7180260.66      2296329.08      7180131.31
      2296329.20      7180034.92      2296281.16      7179954.02
      2296278.47      7179884.90      2296286.53      7179853.55
      2296322.29      7179817.56      2296379.00      7179810.00

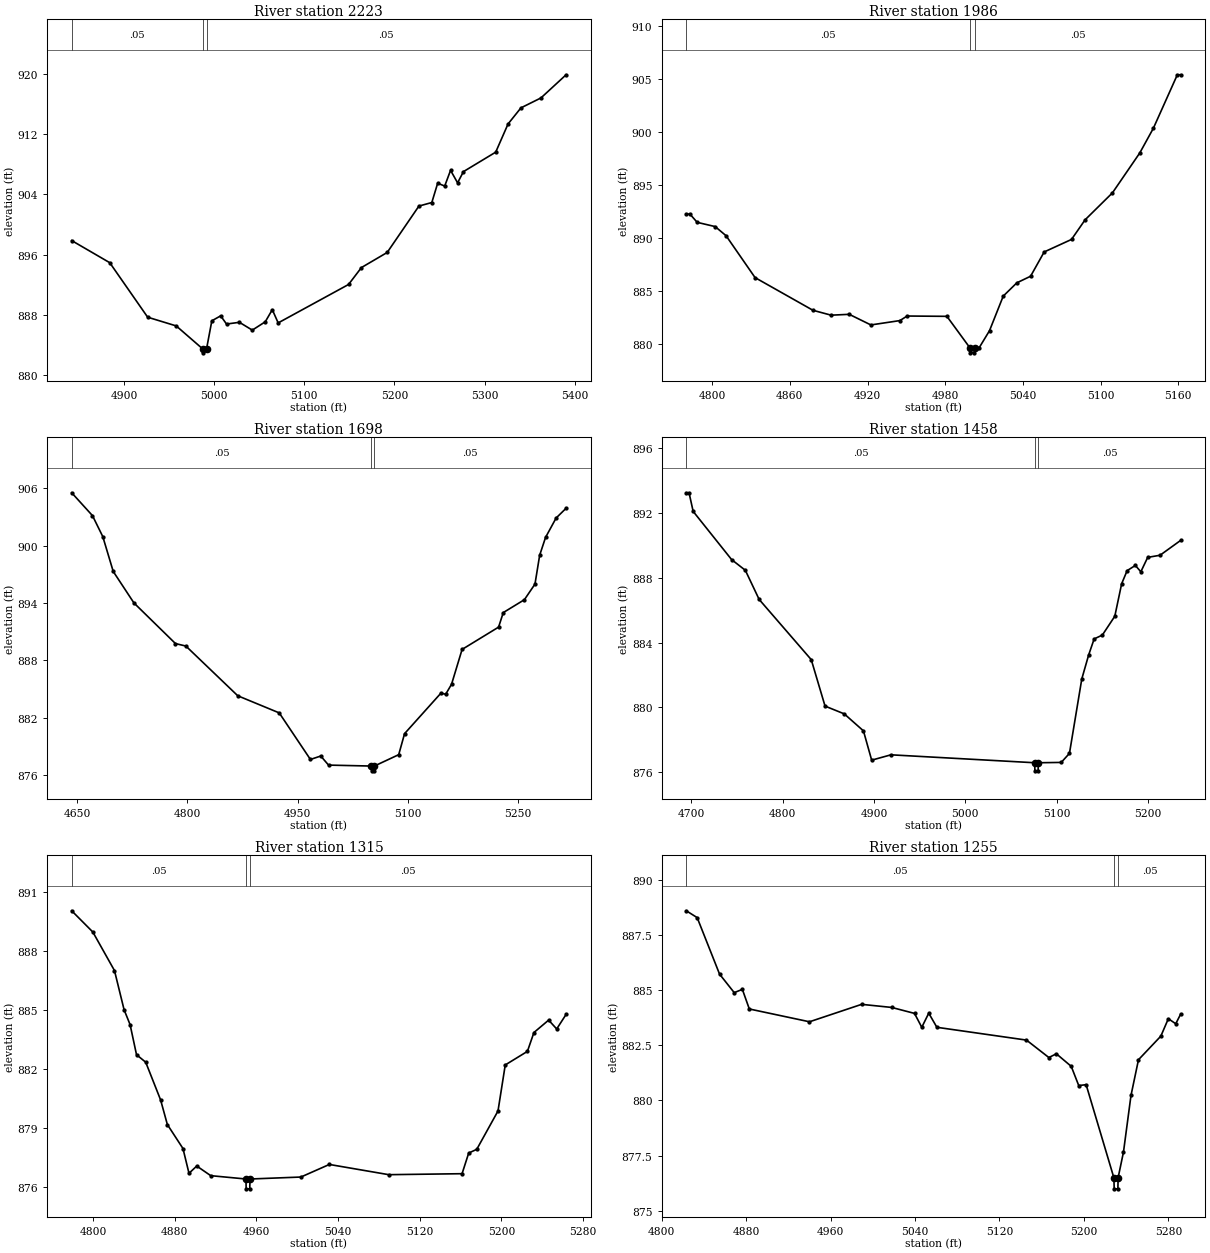
Type RM Length L Ch R = 1,2223,237,237,237
BEGIN DESCRIPTION:
MDE S 045 7.0
END DESCRIPTION:
XS GIS Cut Line= 3
      2295329.00      7181360.01      2295279.00      7181210.00
      2294979.03      7180960.03
#Sta/Elev= 30
  4841.9  897.86  4884.1  894.92  4926.2  887.67  4957.9  886.51  4987.5  883.43
  4987.7  882.93  4991.5  883.43  4997.4  887.19  5007.2  887.85  5013.7  886.76
  5028.0  886.99  5042.3  885.95  5056.7  887.06  5064.5  888.67  5071.0  886.91
  5149.1  892.02  5163.4  894.27  5192.0  896.28  5227.2  902.45  5241.5  902.92
  5248.0  905.49  5255.8  905.11  5262.3  907.20  5270.1  905.54  5276.6  907.03
  5312.4  909.62  5326.1  913.37  5340.4  915.51  5362.6  916.83  5390.5  919.91
#Mann=3,-1,0
  4841.9    0.05       0  4987.5   0.033       0  4991.5    0.05       0
Bank Sta=4987.5,4991.5
Exp/Cntr=0.3,0.1

Type RM Length L Ch R = 1,1986,288,288,288
BEGIN DESCRIPTION:
MDE S 045 6.0
END DESCRIPTION:
XS GIS Cut Line= 3
      2295478.99      7181209.99      2295379.00      7181010.00
      2295229.01      7180960.00
#Sta/Elev= 30
  4780.1  892.27  4782.9  892.27  4788.5  891.49  4802.4  891.09  4810.8  890.23
  4833.2  886.28  4877.9  883.20  4891.9  882.74  4905.9  882.82  4922.6  881.82
  4945.0  882.23  4950.6  882.66  4981.3  882.63  4998.9  879.69  4999.1  879.19
  5002.6  879.19  5002.9  879.69  5006.3  879.69  5014.2  881.28  5024.8  884.54
  5035.3  885.79  5045.9  886.41  5056.4  888.70  5077.5  889.88  5088.0  891.73
  5109.1  894.27  5130.2  898.03  5140.7  900.36  5159.2  905.40  5161.8  905.40
#Mann=3,-1,0
  4780.1    0.05       0  4998.9   0.033       0  5002.9    0.05       0
Bank Sta=4998.9,5002.9
Exp/Cntr=0.3,0.1

Type RM Length L Ch R = 1,1698,240,240,240
BEGIN DESCRIPTION:
MDE S 045 5.0
END DESCRIPTION:
XS GIS Cut Line= 3
      2295879.00      7181160.00      2295629.00      7180910.00
      2295379.00      7180710.00
#Sta/Elev= 30
  4642.3  905.52  4670.6  903.13  4684.7  900.93  4698.9  897.29  4727.1  894.00
  4783.7  889.75  4797.9  889.49  4868.6  884.29  4925.1  882.50  4967.6  877.63
  4981.7  877.99  4992.3  877.04  5050.7  876.94  5050.9  876.44  5054.4  876.44
  5054.7  876.94  5087.9  878.13  5095.9  880.33  5145.5  884.57  5151.9  884.45
  5159.9  885.49  5174.3  889.14  5224.0  891.47  5230.4  892.99  5259.2  894.34
  5273.6  895.97  5280.0  898.99  5288.0  900.85  5302.4  902.88  5316.0  903.90
#Mann=3,-1,0
  4642.3    0.05       0  5050.7   0.033       0  5054.7    0.05       0
Bank Sta=5050.7,5054.7
Exp/Cntr=0.3,0.1

Type RM Length L Ch R = 1,1458,143,143,143
BEGIN DESCRIPTION:
MDE S 045 4.0
END DESCRIPTION:
XS GIS Cut Line= 3
      2295929.02      7181010.03      2295729.00      7180710.00
      2295578.98      7180609.98
#Sta/Elev= 30
  4694.7  893.26  4697.7  893.26  4702.2  892.11  4744.3  889.13  4759.3  888.47
  4774.4  886.67  4831.4  882.95  4846.5  880.08  4867.5  879.60  4888.5  878.55
  4897.5  876.74  4918.6  877.07  5075.8  876.58  5076.1  876.08  5079.6  876.08
  5079.8  876.58  5104.9  876.60  5113.9  877.16  5127.4  881.76  5134.9  883.24
  5140.9  884.23  5149.9  884.47  5163.5  885.63  5171.0  887.64  5177.0  888.45
  5186.0  888.77  5192.0  888.38  5199.5  889.27  5213.0  889.40  5235.6  890.32
#Mann=3,-1,0
  4694.7    0.05       0  5075.8   0.033       0  5079.8    0.05       0
Bank Sta=5075.8,5079.8
Exp/Cntr=0.3,0.1

Type RM Length L Ch R = 1,1315,60,60,60
BEGIN DESCRIPTION:
Mapping XS dd9f5b6a
END DESCRIPTION:
XS GIS Cut Line= 3
      2296014.21      7180903.78      2295852.31      7180645.82
      2295712.72      7180532.58
#Sta/Elev= 30
  4779.0  890.05  4799.7  888.97  4820.9  887.01  4830.3  885.02  4836.2  884.26
  4842.5  882.73  4851.5  882.35  4866.1  880.43  4872.7  879.18  4888.0  877.96
  4893.9  876.70  4901.5  877.07  4915.2  876.58  4949.7  876.41  4949.9  875.91
  4953.4  875.91  4953.7  876.41  5003.5  876.51  5031.4  877.15  5089.6  876.63
  5161.4  876.68  5167.9  877.73  5175.8  877.92  5196.6  879.87  5203.7  882.21
  5225.4  882.90  5231.8  883.86  5246.2  884.49  5254.1  884.04  5263.3  884.78
#Mann=3,-1,0
  4779.0    0.05       0  4949.7   0.033       0  4953.7    0.05       0
Bank Sta=4949.7,4953.7
Exp/Cntr=0.3,0.1

Type RM Length L Ch R = 1,1255,59,59,59
BEGIN DESCRIPTION:
Mapping XS 3260ba92
END DESCRIPTION:
XS GIS Cut Line= 3
      2296069.77      7180833.87      2295878.47      7180611.48
      2295753.92      7180488.48
#Sta/Elev= 30
  4823.3  888.59  4833.6  888.28  4854.8  885.72  4868.7  884.88  4876.4  885.03
  4883.0  884.14  4940.0  883.56  4989.4  884.35  5017.9  884.21  5039.5  883.94
  5046.4  883.31  5053.0  883.95  5060.7  883.31  5145.6  882.73  5166.8  881.94
  5173.9  882.11  5188.0  881.54  5195.1  880.67  5202.1  880.71  5228.4  876.49
  5228.7  875.99  5232.2  875.99  5232.4  876.49  5237.5  877.66  5244.6  880.22
  5251.7  881.84  5272.9  882.91  5280.0  883.70  5287.0  883.47  5291.7  883.91
#Mann=3,-1,0
  4823.3    0.05       0  5228.4   0.033       0  5232.4    0.05       0
Bank Sta=5228.4,5232.4
Exp/Cntr=0.3,0.1

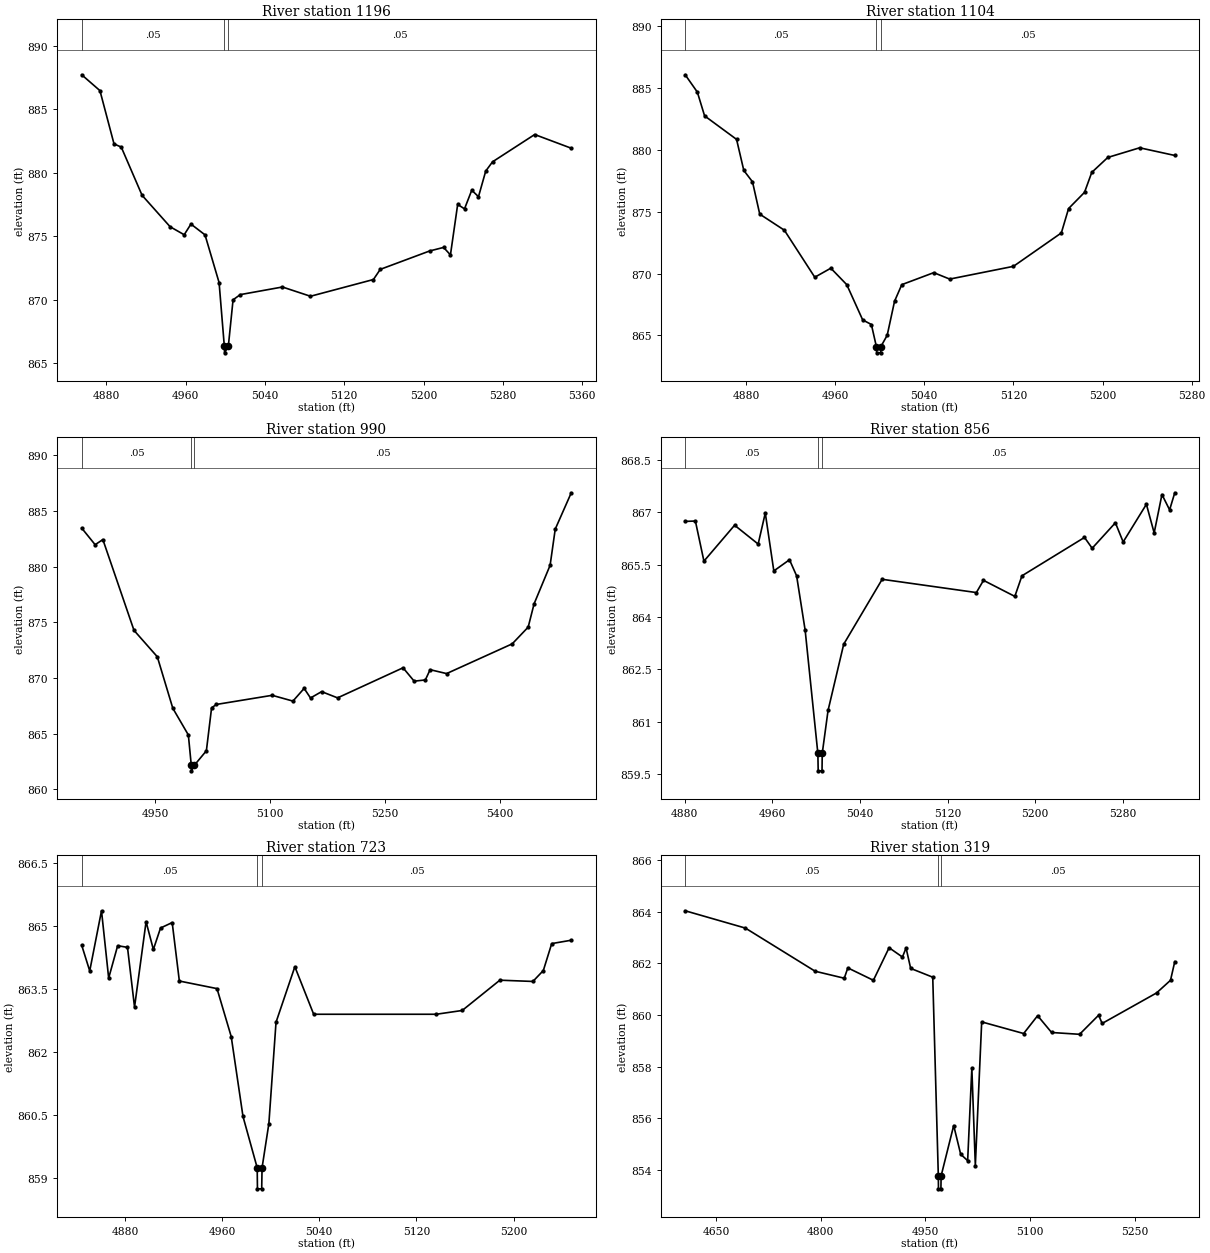
Type RM Length L Ch R = 1,1196,92,92,92
BEGIN DESCRIPTION:
Mapping XS e5388d28
END DESCRIPTION:
XS GIS Cut Line= 2
      2296105.87      7180779.17      2295767.51      7180419.38
#Sta/Elev= 30
  4855.1  887.73  4873.5  886.48  4887.7  882.28  4895.0  882.03  4916.0  878.23
  4944.3  875.75  4958.5  875.12  4965.3  875.96  4979.5  875.11  4993.7  871.35
  4999.0  866.31  4999.2  865.81  5003.0  866.31  5007.8  869.99  5015.1  870.40
  5057.6  871.00  5085.9  870.27  5149.4  871.59  5156.3  872.39  5206.1  873.84
  5220.2  874.12  5227.1  873.53  5234.4  877.51  5241.3  877.16  5248.6  878.63
  5255.4  878.12  5262.7  880.14  5269.6  880.87  5312.1  883.02  5349.0  881.94
#Mann=3,-1,0
  4855.1    0.05       0  4999.0   0.033       0  5003.0    0.05       0
Bank Sta=4999,5003
Exp/Cntr=0.3,0.1

Type RM Length L Ch R = 1,1104,114,114,114
BEGIN DESCRIPTION:
Mapping XS ca554635
END DESCRIPTION:
XS GIS Cut Line= 2
      2296134.45      7180719.23      2295852.92      7180381.86
#Sta/Elev= 30
  4825.4  886.06  4836.3  884.66  4842.8  882.74  4871.5  880.84  4878.0  878.33
  4885.8  877.41  4892.3  874.80  4914.4  873.50  4941.7  869.70  4956.1  870.43
  4970.4  869.10  4984.7  866.25  4992.5  865.88  4997.0  864.09  4997.3  863.59
  5000.8  863.59  5001.0  864.09  5006.7  865.01  5013.3  867.76  5019.8  869.10
  5048.5  870.07  5062.8  869.55  5120.0  870.58  5163.0  873.28  5169.5  875.25
  5183.8  876.56  5190.3  878.17  5204.7  879.38  5233.3  880.16  5264.8  879.54
#Mann=3,-1,0
  4825.4    0.05       0  4997.0   0.033       0  5001.0    0.05       0
Bank Sta=4997,5001
Exp/Cntr=0.3,0.1

Type RM Length L Ch R = 1,990,134,134,134
BEGIN DESCRIPTION:
Mapping XS eb71f55c
END DESCRIPTION:
XS GIS Cut Line= 4
      2296151.95      7180687.29      2296128.68      7180543.54
      2295939.79      7180294.25      2295803.11      7180176.95
#Sta/Elev= 30
  4854.4  883.46  4871.9  881.97  4882.0  882.43  4922.6  874.28  4953.0  871.91
  4973.2  867.29  4993.5  864.89  4997.3  862.17  4997.5  861.67  5001.3  862.17
  5017.0  863.47  5023.8  867.33  5030.1  867.63  5102.8  868.45  5129.9  867.93
  5144.5  869.07  5152.8  868.21  5167.3  868.78  5188.1  868.22  5273.5  870.92
  5288.0  869.72  5302.6  869.83  5308.8  870.75  5330.3  870.40  5415.9  873.07
  5436.7  874.57  5444.4  876.66  5465.3  880.12  5472.0  883.37  5492.9  886.63
#Mann=3,-1,0
  4854.4    0.05       0  4997.3   0.033       0  5001.3    0.05       0
Bank Sta=4997.3,5001.3
Exp/Cntr=0.3,0.1

Type RM Length L Ch R = 1,856,133,133,133
BEGIN DESCRIPTION:
Mapping XS 4f8e4ca0
END DESCRIPTION:
XS GIS Cut Line= 3
      2296317.76      7180564.71      2296111.64      7180316.51
      2296023.61      7180228.79
#Sta/Elev= 30
  4880.5  866.74  4889.8  866.75  4897.6  865.60  4925.6  866.63  4947.1  866.09
  4953.6  866.98  4961.4  865.32  4975.7  865.64  4982.2  865.18  4990.0  863.62
  5001.6  860.09  5001.9  859.59  5005.4  859.59  5005.6  860.09  5010.9  861.32
  5025.2  863.22  5060.3  865.08  5146.3  864.70  5152.8  865.05  5181.4  864.59
  5187.9  865.18  5245.0  866.28  5252.0  865.97  5273.2  866.70  5280.3  866.15
  5301.5  867.23  5308.6  866.41  5315.7  867.51  5322.7  867.07  5327.4  867.56
#Mann=3,-1,0
  4880.5    0.05       0  5001.6   0.033       0  5005.6    0.05       0
Bank Sta=5001.6,5005.6
Exp/Cntr=0.3,0.1

Type RM Length L Ch R = 1,723,404,404,404
BEGIN DESCRIPTION:
Mapping XS 07395397
END DESCRIPTION:
XS GIS Cut Line= 2
      2296464.37      7180455.61      2296119.30      7180247.25
#Sta/Elev= 30
  4844.4  864.54  4851.0  863.93  4860.7  865.36  4866.6  863.76  4874.0  864.53
  4882.1  864.49  4887.9  863.07  4897.4  865.10  4903.4  864.44  4909.3  864.95
  4918.9  865.08  4924.8  863.69  4955.8  863.51  4967.5  862.37  4977.2  860.47
  4988.9  859.25  4989.1  858.75  4992.6  858.75  4992.9  859.25  4998.5  860.30
  5004.4  862.71  5019.9  864.03  5035.4  862.90  5136.3  862.90  5157.7  862.99
  5188.7  863.71  5215.9  863.68  5224.5  863.94  5231.4  864.58  5247.5  864.66
#Mann=3,-1,0
  4844.4    0.05       0  4988.9   0.033       0  4992.9    0.05       0
Bank Sta=4988.9,4992.9
Exp/Cntr=0.3,0.1

Type RM Length L Ch R = 1,319,177,177,177
BEGIN DESCRIPTION:
Mapping XS a728a8e3
END DESCRIPTION:
XS GIS Cut Line= 3
      2296468.64      7180373.71      2296389.44      7180049.24
      2296022.89      7180029.16
#Sta/Elev= 30
  4605.9  864.03  4692.1  863.36  4792.0  861.69  4833.7  861.42  4838.8  861.82
  4875.4  861.34  4897.9  862.60  4917.0  862.24  4922.2  862.59  4928.8  861.80
  4960.4  861.46  4968.4  853.77  4968.6  853.27  4972.1  853.27  4972.4  853.77
  4990.4  855.72  5000.4  854.61  5010.4  854.36  5016.4  857.94  5021.4  854.17
  5030.5  859.73  5090.6  859.28  5110.6  859.97  5130.6  859.32  5170.7  859.25
  5198.0  859.99  5203.0  859.67  5280.9  860.85  5300.9  861.34  5307.0  862.06
#Mann=3,-1,0
  4605.9    0.05       0  4968.4   0.033       0  4972.4    0.05       0
Bank Sta=4968.4,4972.4
Exp/Cntr=0.3,0.1

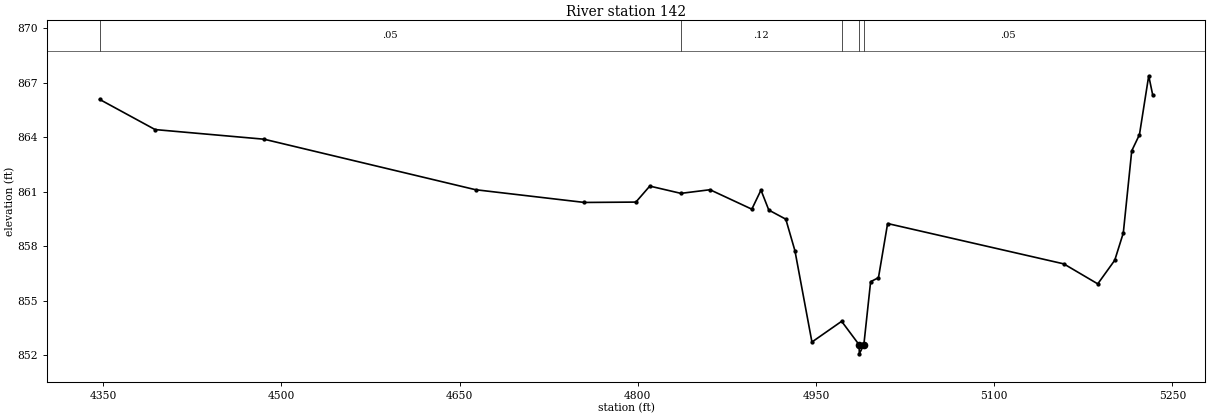
Type RM Length L Ch R = 1,142,0,0,0
BEGIN DESCRIPTION:
MDE S 045 1.0
END DESCRIPTION:
XS GIS Cut Line= 3
      2296504.00      7180471.80      2296393.57      7179981.68
      2296100.04      7179733.96
#Sta/Elev= 30
  4347.0  866.07  4393.7  864.41  4485.4  863.88  4663.5  861.10  4755.1  860.40
  4798.4  860.42  4810.1  861.30  4836.3  860.90  4860.8  861.10  4896.0  860.03
  4903.7  861.08  4910.3  859.98  4924.6  859.48  4932.3  857.74  4946.6  852.72
  4971.6  853.86  4986.3  852.57  4986.5  852.07  4990.3  852.57  4996.0  856.04
  5002.6  856.26  5010.3  859.24  5158.6  857.02  5187.2  855.92  5201.5  857.22
  5208.7  858.72  5215.8  863.24  5222.3  864.13  5230.1  867.37  5233.5  866.30
#Mann=5,-1,0
  4347.0    0.05       0  4836.3    0.12       0  4971.6    0.05       0
  4986.3   0.033       0  4990.3    0.05       0
Bank Sta=4986.3,4990.3
Exp/Cntr=0.3,0.1

Chan Stop Cuts=-1