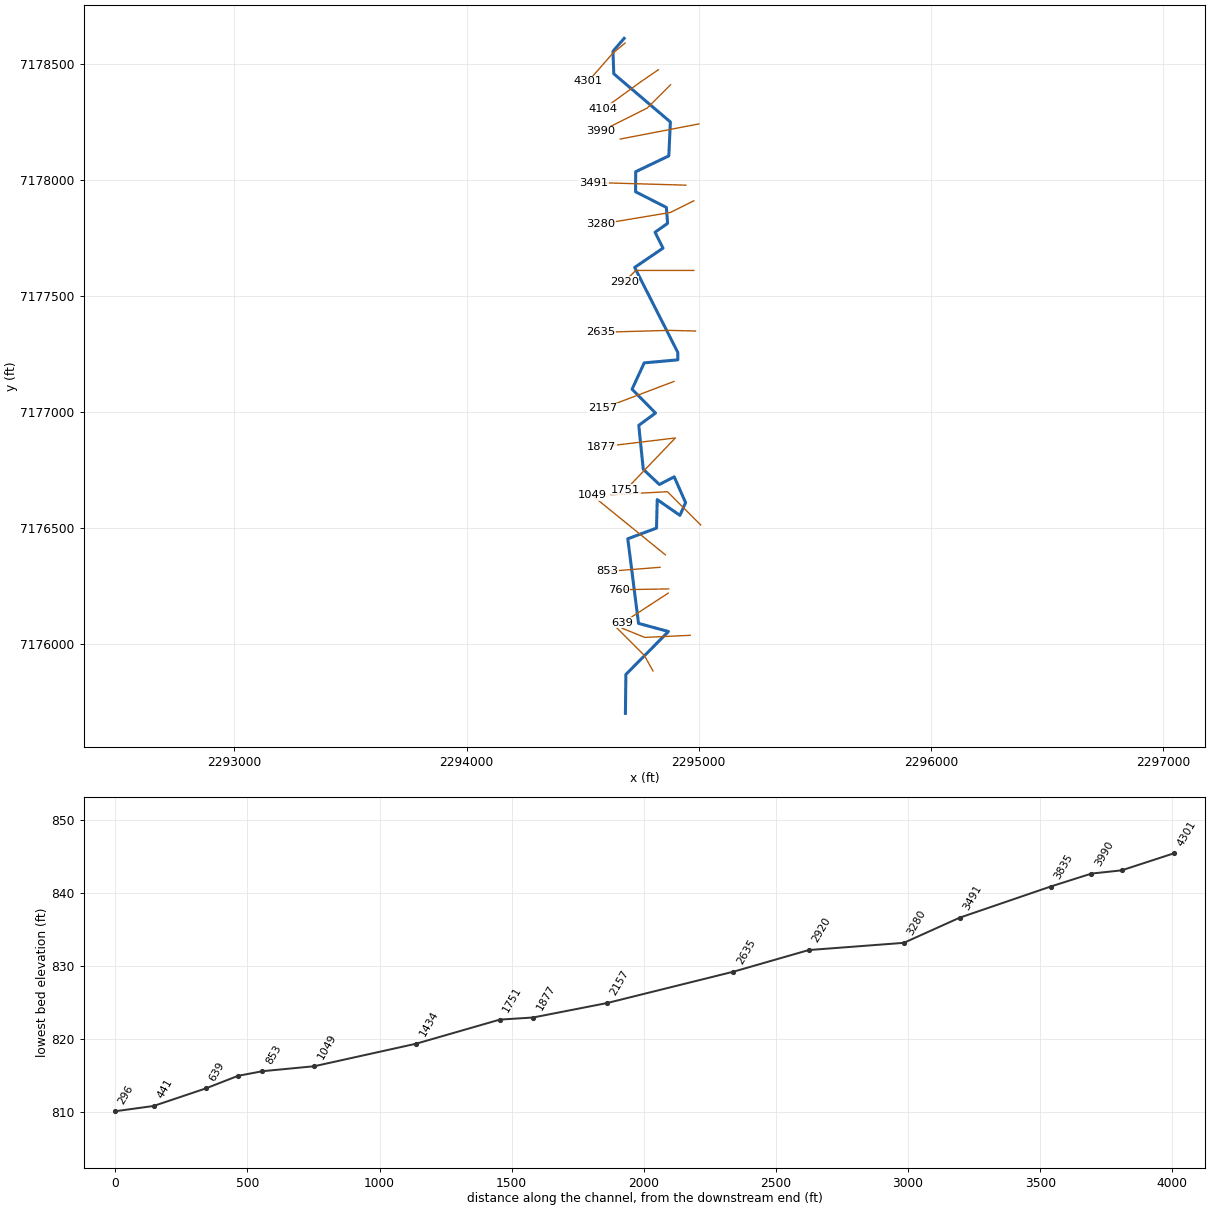
--- MDE S 046.prj (project) ---

Proj Title=MDE S 046 Base Level Engineering
Current Plan=p01
Default Exp/Contr=0.3,0.1
English Units
Geom File=g01
Flow File=f01
Plan File=p01
BEGIN DESCRIPTION:
MDE S 046
END DESCRIPTION:

--- MDE S 046.p01 (plan) ---

Plan Title=Multiple Run
Short Identifier=Multiple
Geom File=g01
Flow File=f01
Subcritical Flow
K Sum by GR= 0
Std Step Tol= 0.01
Critical Tol= 0.01
Num of Std Step Trials= 20
Max Error Tol= 0.3
Flow Tol Ratio= 0.001
Split Flow NTrial= 30
Split Flow Tol= 0.02
Split Flow Ratio= 0.02
Log Output Level= 0
Friction Slope Method= 1
Unsteady Friction Slope Method= 2
Unsteady Bridges Friction Slope Method= 1
Parabolic Critical Depth
Global Vel Dist=  1 , 1 , 1
Global Log Level= 0
CheckData=True
Encroach Param= -1, 0, 0, 0
BEGIN DESCRIPTION:
Multiple Run
END DESCRIPTION:

--- MDE S 046.f01 (steady flow) ---

Flow Title=Multiple
Number of Profiles=7
Profile Names=10-year,25-year,50-year,1pct_min,100-year,1pct_plu,500-year
River Rch & RM= MDE S 046,Reach-1,4301
     552     753     919     558    1113    2221    1634
Boundary for River Rch & Prof#=MDE S 046,Reach-1,1
Up Type=0
Dn Type=3
Dn Slope=0.005
Boundary for River Rch & Prof#=MDE S 046,Reach-1,2
Up Type=0
Dn Type=3
Dn Slope=0.005
Boundary for River Rch & Prof#=MDE S 046,Reach-1,3
Up Type=0
Dn Type=3
Dn Slope=0.005
Boundary for River Rch & Prof#=MDE S 046,Reach-1,4
Up Type=0
Dn Type=3
Dn Slope=0.005
Boundary for River Rch & Prof#=MDE S 046,Reach-1,5
Up Type=0
Dn Type=3
Dn Slope=0.005
Boundary for River Rch & Prof#=MDE S 046,Reach-1,6
Up Type=0
Dn Type=3
Dn Slope=0.005
Boundary for River Rch & Prof#=MDE S 046,Reach-1,7
Up Type=0
Dn Type=3
Dn Slope=0.005

--- MDE S 046.g01 (geometry) ---

Geom Title=Existing Conditions

River Reach=MDE S 046,Reach-1
Reach XY= 30
      2294679.00      7178610.00      2294630.76      7178554.16
      2294634.32      7178457.33      2294878.03      7178249.71
      2294871.33      7178103.48      2294728.56      7178035.36
      2294728.23      7177948.83      2294860.98      7177881.54
      2294866.04      7177812.76      2294811.93      7177774.55
      2294846.42      7177706.07      2294724.11      7177623.01
      2294909.83      7177257.37      2294910.16      7177224.91
      2294765.35      7177211.75      2294713.10      7177098.23
      2294814.07      7176995.63      2294741.93      7176942.68
      2294761.29      7176753.27      2294830.62      7176687.75
      2294894.59      7176720.86      2294943.67      7176609.68
      2294919.16      7176554.88      2294821.47      7176622.72
      2294818.34      7176500.02      2294694.58      7176453.90
      2294740.79      7176089.44      2294869.76      7176054.39
      2294686.36      7175869.41      2294684.37      7175701.74

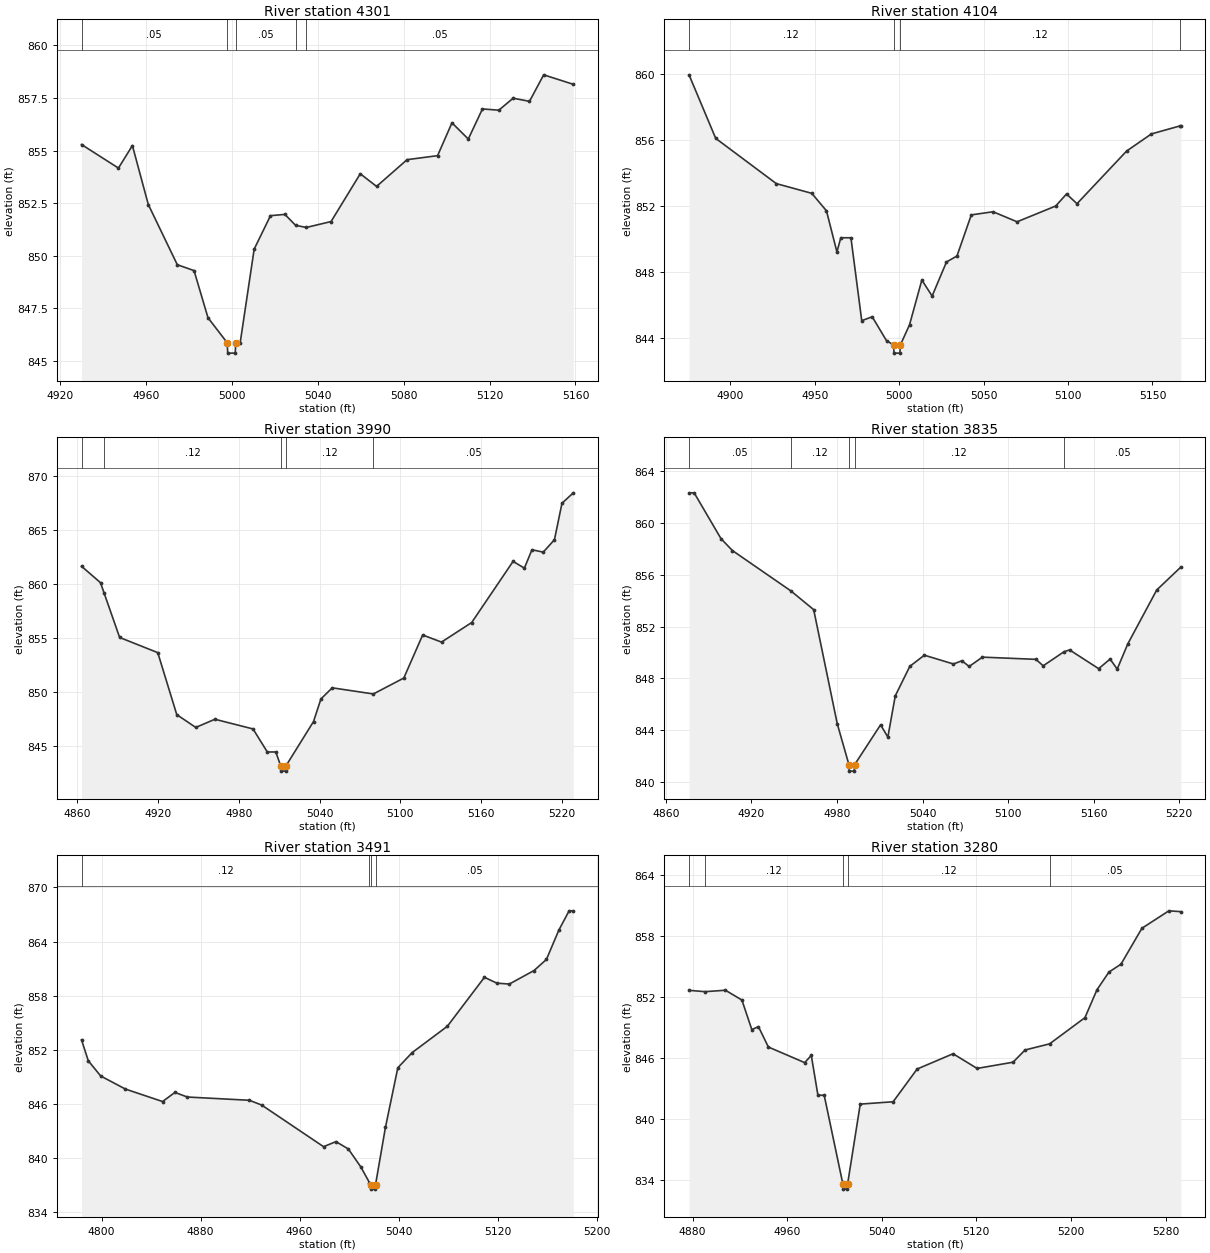
Type RM Length L Ch R = 1,4301,197,197,197
BEGIN DESCRIPTION:
MDE S 046 9.0
END DESCRIPTION:
XS GIS Cut Line= 3
      2294682.87      7178589.68      2294629.18      7178544.77
      2294524.52      7178425.07
#Sta/Elev= 30
  4930.0  855.29  4947.2  854.17  4953.7  855.24  4961.1  852.44  4974.6  849.58
  4982.4  849.30  4988.9  847.06  4997.8  845.88  4998.1  845.38  5001.6  845.38
  5001.8  845.88  5003.9  845.88  5010.4  850.32  5018.0  851.91  5024.7  851.97
  5029.7  851.45  5034.7  851.35  5046.2  851.63  5059.8  853.90  5067.4  853.30
  5081.6  854.57  5095.8  854.76  5102.5  856.32  5110.1  855.55  5116.7  856.98
  5124.3  856.92  5131.0  857.49  5138.6  857.34  5145.2  858.60  5159.0  858.15
#Mann=5,-1,0
  4930.0    0.05       0  4997.8   0.033       0  5001.8    0.05       0
  5029.7    0.12       0  5034.7    0.05       0
Bank Sta=4997.8,5001.8
Exp/Cntr=0.3,0.1

Type RM Length L Ch R = 1,4104,114,114,114
BEGIN DESCRIPTION:
Mapping XS 1562bf55
END DESCRIPTION:
XS GIS Cut Line= 3
      2294826.18      7178474.51      2294750.22      7178422.61
      2294589.07      7178305.35
#Sta/Elev= 30
  4875.5  859.97  4891.3  856.11  4927.2  853.36  4948.2  852.77  4956.9  851.71
  4963.1  849.21  4965.4  850.07  4971.4  850.07  4977.8  845.03  4984.0  845.27
  4992.5  843.81  4996.7  843.56  4996.9  843.06  5000.4  843.06  5000.7  843.56
  5006.1  844.78  5013.4  847.50  5019.5  846.53  5028.0  848.60  5034.2  848.96
  5042.7  851.46  5055.6  851.65  5069.8  851.04  5092.7  852.00  5099.1  852.73
  5105.3  852.14  5134.7  855.34  5149.4  856.38  5166.1  856.86  5166.8  856.86
#Mann=4,-1,0
  4875.5    0.12       0  4996.7    0.07       0  5000.7    0.12       0
  5166.1    0.05       0
Bank Sta=4996.7,5000.7
Exp/Cntr=0.3,0.1

Type RM Length L Ch R = 1,3990,155,155,155
BEGIN DESCRIPTION:
MDE S 046 8.0
END DESCRIPTION:
XS GIS Cut Line= 3
      2294878.99      7178409.99      2294779.00      7178310.00
      2294579.02      7178210.01
#Sta/Elev= 30
  4863.3  861.66  4877.4  860.13  4880.1  859.16  4891.6  855.04  4919.9  853.63
  4934.0  847.87  4948.1  846.68  4962.3  847.44  4990.6  846.54  5001.2  844.40
  5007.5  844.40  5011.1  843.12  5011.3  842.62  5014.8  842.62  5015.1  843.12
  5035.5  847.23  5041.0  849.33  5049.4  850.36  5079.9  849.79  5102.5  851.27
  5116.5  855.27  5130.5  854.61  5152.9  856.43  5183.6  862.11  5192.0  861.48
  5197.6  863.19  5206.0  862.97  5214.3  864.12  5219.9  867.51  5228.3  868.48
#Mann=5,-1,0
  4863.3    0.05       0  4880.1    0.12       0  5011.1    0.07       0
  5015.1    0.12       0  5079.9    0.05       0
Bank Sta=5011.1,5015.1
Exp/Cntr=0.3,0.1

Type RM Length L Ch R = 1,3835,344,344,344
BEGIN DESCRIPTION:
Mapping XS 8fa87651
END DESCRIPTION:
XS GIS Cut Line= 2
      2295001.04      7178241.28      2294662.44      7178176.17
#Sta/Elev= 30
  4876.3  862.35  4879.9  862.35  4898.7  858.81  4906.7  857.89  4947.7  854.77
  4963.7  853.32  4980.2  844.51  4988.4  841.34  4988.6  840.84  4992.1  840.84
  4992.4  841.34  5010.6  844.42  5015.7  843.47  5020.9  846.66  5031.1  848.94
  5041.3  849.80  5061.7  849.12  5067.6  849.37  5072.7  848.93  5082.0  849.65
  5119.5  849.48  5124.6  848.98  5139.1  850.06  5143.1  850.21  5163.5  848.76
  5171.5  849.50  5176.5  848.73  5183.9  850.67  5204.2  854.84  5221.1  856.61
#Mann=5,-1,0
  4876.3    0.05       0  4947.7    0.12       0  4988.4    0.07       0
  4992.4    0.12       0  5139.1    0.05       0
Bank Sta=4988.4,4992.4
Exp/Cntr=0.3,0.1

Type RM Length L Ch R = 1,3491,211,211,211
BEGIN DESCRIPTION:
Mapping XS 96fc42bd
END DESCRIPTION:
XS GIS Cut Line= 2
      2294944.51      7177977.41      2294547.27      7177988.86
#Sta/Elev= 30
  4783.8  853.12  4789.3  850.79  4799.3  849.11  4819.3  847.66  4849.3  846.28
  4859.3  847.29  4869.3  846.78  4919.4  846.42  4929.4  845.89  4979.4  841.28
  4989.4  841.84  4999.4  841.03  5009.4  839.06  5016.5  837.30  5017.4  837.08
  5017.7  836.58  5021.2  836.58  5021.4  837.08  5029.4  843.42  5039.4  850.02
  5050.9  851.69  5079.4  854.61  5109.4  860.04  5119.4  859.39  5129.5  859.29
  5149.5  860.79  5159.5  862.02  5169.5  865.26  5177.8  867.40  5181.2  867.40
#Mann=4,-1,0
  4783.8    0.12       0  5016.5    0.05       0  5017.4    0.07       0
  5021.4    0.05       0
Bank Sta=5017.4,5021.4
Exp/Cntr=0.3,0.1

Type RM Length L Ch R = 1,3280,360,360,360
BEGIN DESCRIPTION:
MDE S 046 6.0
END DESCRIPTION:
XS GIS Cut Line= 3
      2294979.01      7177910.00      2294879.00      7177860.00
      2294579.05      7177810.01
#Sta/Elev= 30
  4877.0  852.64  4890.5  852.51  4907.8  852.65  4921.7  851.69  4930.1  848.79
  4935.7  849.08  4944.1  847.08  4974.8  845.55  4980.4  846.26  4986.0  842.35
  4991.3  842.35  5007.1  833.64  5007.3  833.14  5010.8  833.14  5011.1  833.64
  5021.8  841.48  5049.6  841.71  5069.9  844.92  5100.3  846.42  5120.6  844.98
  5151.0  845.59  5161.2  846.79  5181.9  847.39  5211.8  849.96  5222.0  852.70
  5232.1  854.43  5242.3  855.21  5260.0  858.73  5282.8  860.44  5292.9  860.36
#Mann=5,-1,0
  4877.0    0.05       0  4890.5    0.12       0  5007.1    0.07       0
  5011.1    0.12       0  5181.9    0.05       0
Bank Sta=5007.1,5011.1
Exp/Cntr=0.3,0.1

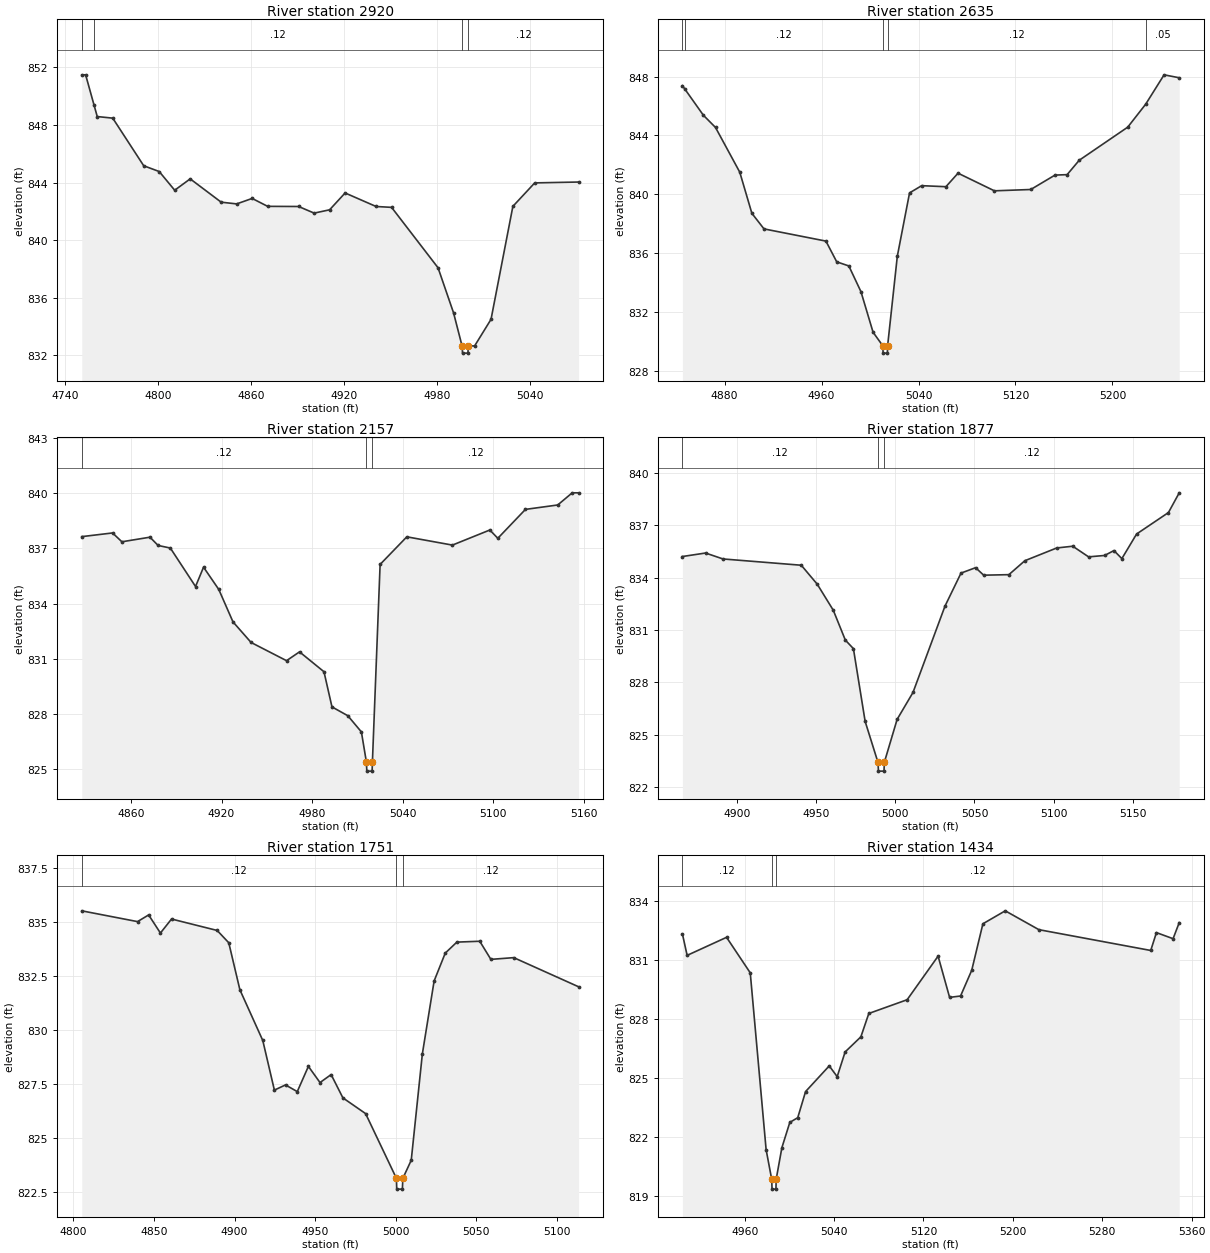
Type RM Length L Ch R = 1,2920,285,285,285
BEGIN DESCRIPTION:
MDE S 046 5.0
END DESCRIPTION:
XS GIS Cut Line= 3
      2294979.02      7177610.00      2294729.00      7177610.00
      2294679.02      7177560.02
#Sta/Elev= 30
  4750.7  851.49  4753.2  851.49  4758.6  849.40  4760.7  848.59  4770.7  848.48
  4790.7  845.17  4800.7  844.77  4810.7  843.47  4820.7  844.26  4840.7  842.64
  4850.7  842.52  4860.7  842.90  4870.7  842.35  4890.7  842.34  4900.7  841.88
  4910.7  842.11  4920.7  843.28  4940.7  842.34  4950.7  842.28  4980.7  838.08
  4990.7  834.95  4996.2  832.65  4996.5  832.15  5000.0  832.15  5000.2  832.65
  5004.3  832.65  5014.9  834.50  5029.0  842.35  5043.1  843.98  5071.4  844.04
#Mann=4,-1,0
  4750.7    0.05       0  4758.6    0.12       0  4996.2    0.07       0
  5000.2    0.12       0
Bank Sta=4996.2,5000.2
Exp/Cntr=0.3,0.1

Type RM Length L Ch R = 1,2635,478,478,478
BEGIN DESCRIPTION:
MDE S 046 4.0
END DESCRIPTION:
XS GIS Cut Line= 3
      2294986.29      7177349.06      2294871.82      7177351.79
      2294576.54      7177343.59
#Sta/Elev= 30
  4845.2  847.38  4847.3  847.14  4862.5  845.37  4872.5  844.54  4892.5  841.50
  4902.5  838.70  4912.5  837.64  4963.6  836.81  4972.5  835.40  4982.5  835.12
  4992.5  833.37  5002.5  830.61  5010.5  829.69  5010.8  829.19  5014.3  829.19
  5014.5  829.69  5022.5  835.78  5032.6  840.09  5042.6  840.58  5062.6  840.51
  5072.6  841.43  5102.6  840.23  5132.6  840.32  5152.6  841.30  5162.6  841.33
  5172.6  842.31  5212.6  844.56  5227.4  846.12  5242.6  848.12  5255.1  847.92
#Mann=5,-1,0
  4845.2    0.05       0  4847.3    0.12       0  5010.5    0.07       0
  5014.5    0.12       0  5227.4    0.05       0
Bank Sta=5010.5,5014.5
Exp/Cntr=0.3,0.1

Type RM Length L Ch R = 1,2157,280,280,280
BEGIN DESCRIPTION:
Mapping XS fde429ee
END DESCRIPTION:
XS GIS Cut Line= 2
      2294893.89      7177131.93      2294586.07      7177015.24
#Sta/Elev= 30
  4827.4  837.64  4847.8  837.84  4854.0  837.36  4872.6  837.61  4878.0  837.16
  4886.1  837.02  4902.8  834.93  4908.1  835.98  4918.2  834.77  4927.6  833.01
  4939.6  831.89  4963.1  830.90  4971.7  831.38  4987.9  830.30  4993.2  828.39
  5003.7  827.91  5012.7  827.03  5016.0  825.40  5016.3  824.90  5019.8  824.90
  5020.0  825.40  5025.1  836.13  5042.8  837.63  5073.0  837.18  5097.8  838.00
  5103.1  837.55  5121.4  839.12  5142.8  839.36  5152.4  840.02  5156.6  840.02
#Mann=3,-1,0
  4827.4    0.12       0  5016.0    0.07       0  5020.0    0.12       0
Bank Sta=5016,5020
Exp/Cntr=0.3,0.1

Type RM Length L Ch R = 1,1877,126,126,126
BEGIN DESCRIPTION:
Mapping XS cfa3f4c6
END DESCRIPTION:
XS GIS Cut Line= 2
      2294893.51      7176887.57      2294582.25      7176850.18
#Sta/Elev= 30
  4865.7  835.22  4880.3  835.42  4891.3  835.08  4940.7  834.72  4950.8  833.63
  4960.9  832.14  4968.5  830.43  4973.6  829.94  4981.0  825.77  4989.1  823.42
  4989.4  822.92  4992.9  822.92  4993.1  823.42  5001.2  825.89  5011.2  827.43
  5031.4  832.38  5041.5  834.27  5050.7  834.58  5055.8  834.15  5071.7  834.18
  5081.8  834.98  5101.9  835.71  5112.0  835.81  5122.0  835.20  5132.1  835.28
  5138.0  835.56  5143.0  835.10  5152.3  836.51  5172.4  837.74  5179.2  838.87
#Mann=3,-1,0
  4865.7    0.12       0  4989.1    0.07       0  4993.1    0.12       0
Bank Sta=4989.1,4993.1
Exp/Cntr=0.3,0.1

Type RM Length L Ch R = 1,1751,317,317,317
BEGIN DESCRIPTION:
Mapping XS 5c1b1993
END DESCRIPTION:
XS GIS Cut Line= 2
      2294899.51      7176888.34      2294686.35      7176665.74
#Sta/Elev= 30
  4805.2  835.53  4839.8  835.03  4846.7  835.34  4854.0  834.50  4860.9  835.15
  4889.2  834.62  4896.4  834.05  4903.3  831.87  4917.5  829.52  4924.7  827.22
  4931.6  827.46  4938.9  827.15  4945.8  828.32  4953.0  827.57  4959.9  827.94
  4967.2  826.86  4981.3  826.13  5000.4  823.13  5000.6  822.63  5004.1  822.63
  5004.4  823.13  5009.6  823.97  5016.5  828.90  5023.8  832.28  5030.7  833.57
  5037.9  834.08  5052.1  834.12  5059.0  833.28  5073.2  833.36  5113.4  832.01
#Mann=3,-1,0
  4805.2    0.12       0  5000.4    0.07       0  5004.4    0.12       0
Bank Sta=5000.4,5004.4
Exp/Cntr=0.3,0.1

Type RM Length L Ch R = 1,1434,385,385,385
BEGIN DESCRIPTION:
Mapping XS fca20ba4
END DESCRIPTION:
XS GIS Cut Line= 3
      2295008.50      7176513.61      2294865.53      7176656.69
      2294623.54      7176643.93
#Sta/Elev= 30
  4904.3  832.33  4908.5  831.24  4943.8  832.16  4965.0  830.35  4979.2  821.34
  4984.2  819.83  4984.5  819.33  4988.0  819.33  4988.2  819.83  4993.3  821.44
  5000.4  822.73  5007.5  822.97  5014.5  824.30  5035.7  825.61  5042.8  825.06
  5049.9  826.32  5064.0  827.09  5071.1  828.28  5105.4  828.98  5133.1  831.20
  5143.4  829.10  5153.2  829.17  5163.2  830.48  5173.2  832.85  5193.2  833.51
  5223.3  832.55  5323.4  831.49  5328.5  832.40  5343.4  832.09  5348.9  832.91
#Mann=3,-1,0
  4904.3    0.12       0  4984.2    0.07       0  4988.2    0.12       0
Bank Sta=4984.2,4988.2
Exp/Cntr=0.3,0.1

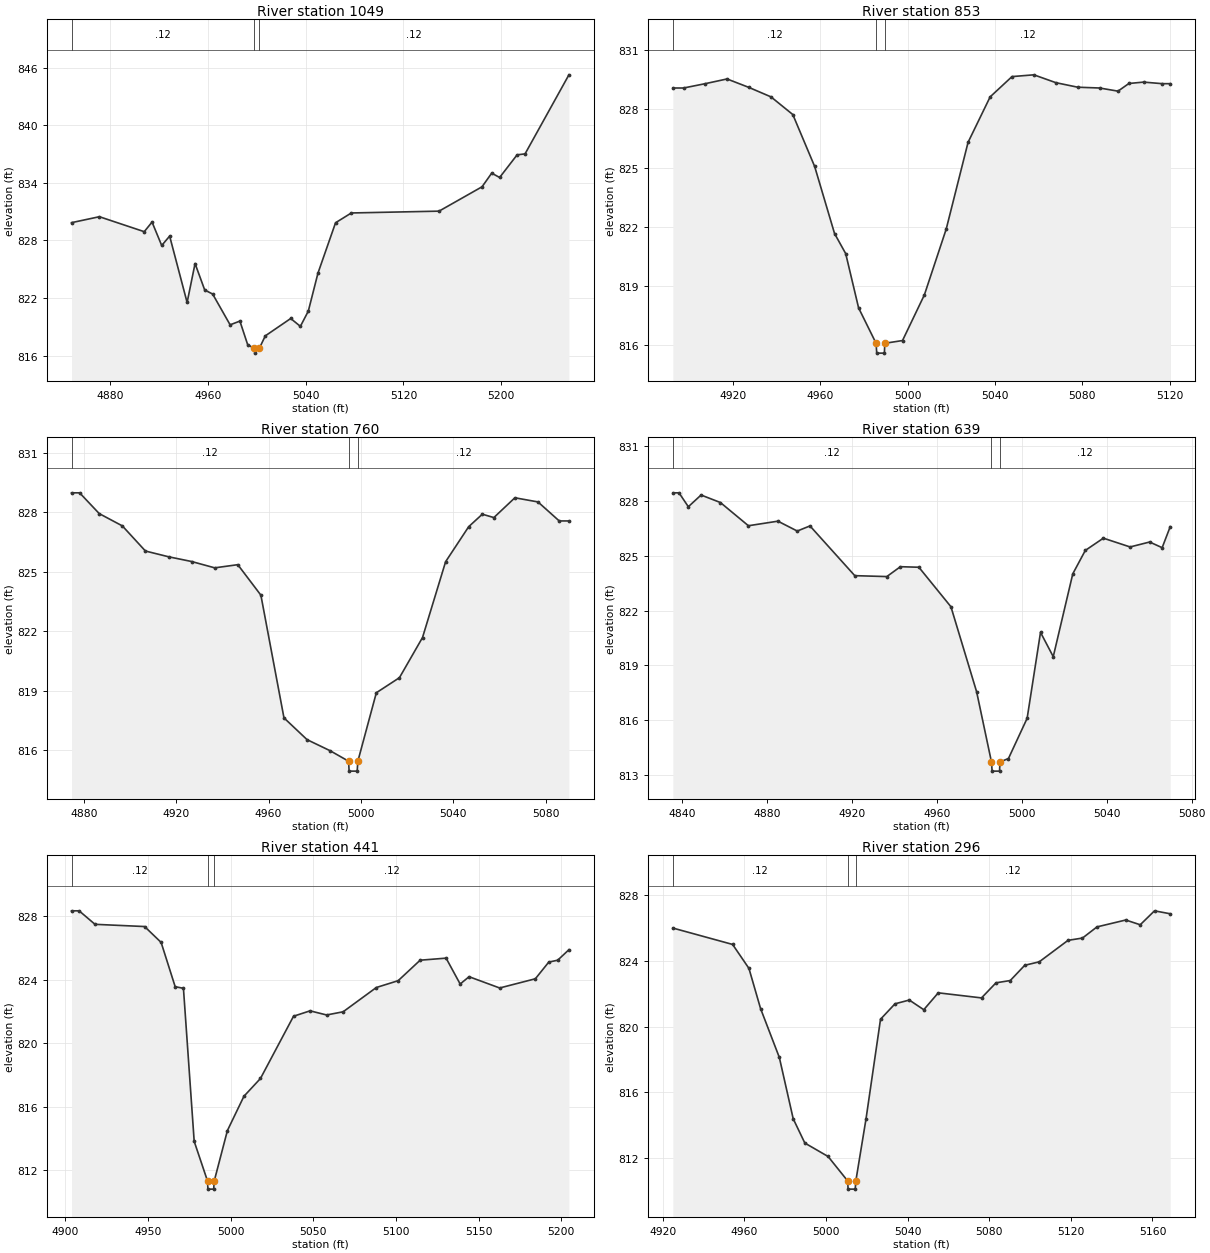
Type RM Length L Ch R = 1,1049,196,196,196
BEGIN DESCRIPTION:
Mapping XS 1dcacad1
END DESCRIPTION:
XS GIS Cut Line= 2
      2294856.72      7176384.72      2294540.71      7176641.37
#Sta/Elev= 30
  4848.3  829.85  4871.1  830.47  4907.8  828.91  4914.2  829.91  4922.1  827.47
  4928.6  828.45  4942.9  821.53  4949.4  825.59  4957.3  822.83  4963.8  822.41
  4978.1  819.20  4986.1  819.59  4992.5  817.12  4998.0  816.75  4998.2  816.25
  5002.0  816.75  5006.9  818.05  5027.7  819.86  5035.6  819.04  5042.1  820.63
  5050.0  824.59  5064.4  829.84  5077.3  830.86  5149.1  831.05  5184.3  833.59
  5192.2  835.01  5198.7  834.56  5213.0  836.92  5219.5  837.02  5255.4  845.26
#Mann=3,-1,0
  4848.3    0.12       0  4998.0    0.07       0  5002.0    0.12       0
Bank Sta=4998,5002
Exp/Cntr=0.3,0.1

Type RM Length L Ch R = 1,853,93,93,93
BEGIN DESCRIPTION:
Mapping XS 7322307e
END DESCRIPTION:
XS GIS Cut Line= 2
      2294833.73      7176331.06      2294606.82      7176313.41
#Sta/Elev= 30
  4892.6  829.05  4897.5  829.05  4907.4  829.27  4917.4  829.51  4927.4  829.08
  4937.5  828.60  4947.5  827.70  4957.5  825.06  4966.6  821.65  4971.7  820.63
  4977.6  817.87  4985.6  816.07  4985.9  815.57  4989.4  815.57  4989.6  816.07
  4997.7  816.21  5007.7  818.53  5017.7  821.88  5027.7  826.29  5037.8  828.60
  5047.8  829.63  5057.8  829.72  5067.9  829.32  5077.9  829.09  5087.9  829.05
  5096.3  828.89  5101.3  829.28  5108.0  829.35  5116.6  829.27  5120.2  829.27
#Mann=3,-1,0
  4892.6    0.12       0  4985.6    0.07       0  4989.6    0.12       0
Bank Sta=4985.6,4989.6
Exp/Cntr=0.3,0.1

Type RM Length L Ch R = 1,760,121,121,121
BEGIN DESCRIPTION:
Mapping XS 04a758d5
END DESCRIPTION:
XS GIS Cut Line= 2
      2294870.98      7176237.98      2294655.61      7176234.39
#Sta/Elev= 28
  4874.7  828.99  4878.2  828.99  4886.7  827.94  4896.7  827.32  4906.7  826.05
  4916.7  825.76  4926.7  825.52  4936.7  825.20  4946.7  825.36  4956.7  823.82
  4966.7  817.62  4976.7  816.52  4986.7  815.96  4994.7  815.43  4994.9  814.93
  4998.4  814.93  4998.7  815.43  5006.7  818.89  5016.7  819.65  5026.7  821.68
  5036.7  825.51  5046.7  827.28  5052.6  827.91  5057.6  827.74  5066.7  828.74
  5076.7  828.53  5085.9  827.57  5090.1  827.57
#Mann=3,-1,0
  4874.7    0.12       0  4994.7    0.07       0  4998.7    0.12       0
Bank Sta=4994.7,4998.7
Exp/Cntr=0.3,0.1

Type RM Length L Ch R = 1,639,198,198,198
BEGIN DESCRIPTION:
Mapping XS 0ffba344
END DESCRIPTION:
XS GIS Cut Line= 2
      2294868.83      7176219.81      2294672.58      7176091.81
#Sta/Elev= 30
  4835.6  828.44  4838.5  828.44  4842.9  827.68  4848.9  828.32  4858.0  827.91
  4871.2  826.64  4885.1  826.89  4894.2  826.35  4900.2  826.63  4921.3  823.91
  4936.4  823.86  4942.8  824.40  4951.5  824.37  4966.6  822.21  4978.7  817.56
  4985.7  813.72  4986.0  813.22  4989.5  813.22  4989.7  813.72  4993.7  813.91
  5002.5  816.11  5008.8  820.81  5014.8  819.48  5024.0  824.01  5029.9  825.29
  5038.4  825.96  5051.0  825.48  5060.2  825.75  5066.1  825.44  5069.9  826.59
#Mann=3,-1,0
  4835.6    0.12       0  4985.7    0.07       0  4989.7    0.12       0
Bank Sta=4985.7,4989.7
Exp/Cntr=0.3,0.1

Type RM Length L Ch R = 1,441,145,145,145
BEGIN DESCRIPTION:
Mapping XS 36078846
END DESCRIPTION:
XS GIS Cut Line= 3
      2294963.17      7176038.03      2294767.76      7176029.07
      2294670.16      7176068.55
#Sta/Elev= 30
  4903.8  828.34  4908.4  828.34  4918.0  827.49  4948.0  827.35  4958.0  826.35
  4966.5  823.56  4971.5  823.46  4978.0  813.82  4986.1  811.31  4986.3  810.81
  4989.8  810.81  4990.1  811.31  4998.1  814.50  5008.1  816.66  5018.1  817.78
  5038.1  821.70  5048.1  822.04  5058.1  821.78  5068.1  821.98  5088.2  823.51
  5101.4  823.94  5114.7  825.23  5130.4  825.36  5138.9  823.73  5144.3  824.19
  5162.8  823.48  5184.4  824.06  5192.5  825.11  5197.9  825.23  5204.7  825.89
#Mann=3,-1,0
  4903.8    0.12       0  4986.1    0.07       0  4990.1    0.12       0
Bank Sta=4986.1,4990.1
Exp/Cntr=0.3,0.1

Type RM Length L Ch R = 1,296,0,0,0
BEGIN DESCRIPTION:
MDE S 046 1.0
END DESCRIPTION:
XS GIS Cut Line= 3
      2294803.17      7175884.37      2294766.21      7175950.94
      2294647.90      7176069.73
#Sta/Elev= 30
  4924.9  826.01  4954.2  825.01  4962.2  823.55  4967.9  821.10  4977.1  818.12
  4983.9  814.38  4989.6  812.90  5001.0  812.08  5010.6  810.59  5010.8  810.09
  5014.3  810.09  5014.6  810.59  5019.6  814.38  5026.7  820.45  5033.8  821.39
  5040.8  821.62  5047.9  821.03  5055.0  822.06  5076.2  821.75  5083.3  822.67
  5090.3  822.81  5097.4  823.74  5104.5  823.95  5118.6  825.26  5125.7  825.40
  5132.8  826.08  5146.9  826.50  5154.0  826.21  5161.0  827.06  5168.7  826.88
#Mann=3,-1,0
  4924.9    0.12       0  5010.6    0.07       0  5014.6    0.12       0
Bank Sta=5010.6,5014.6
Exp/Cntr=0.3,0.1

Chan Stop Cuts=-1