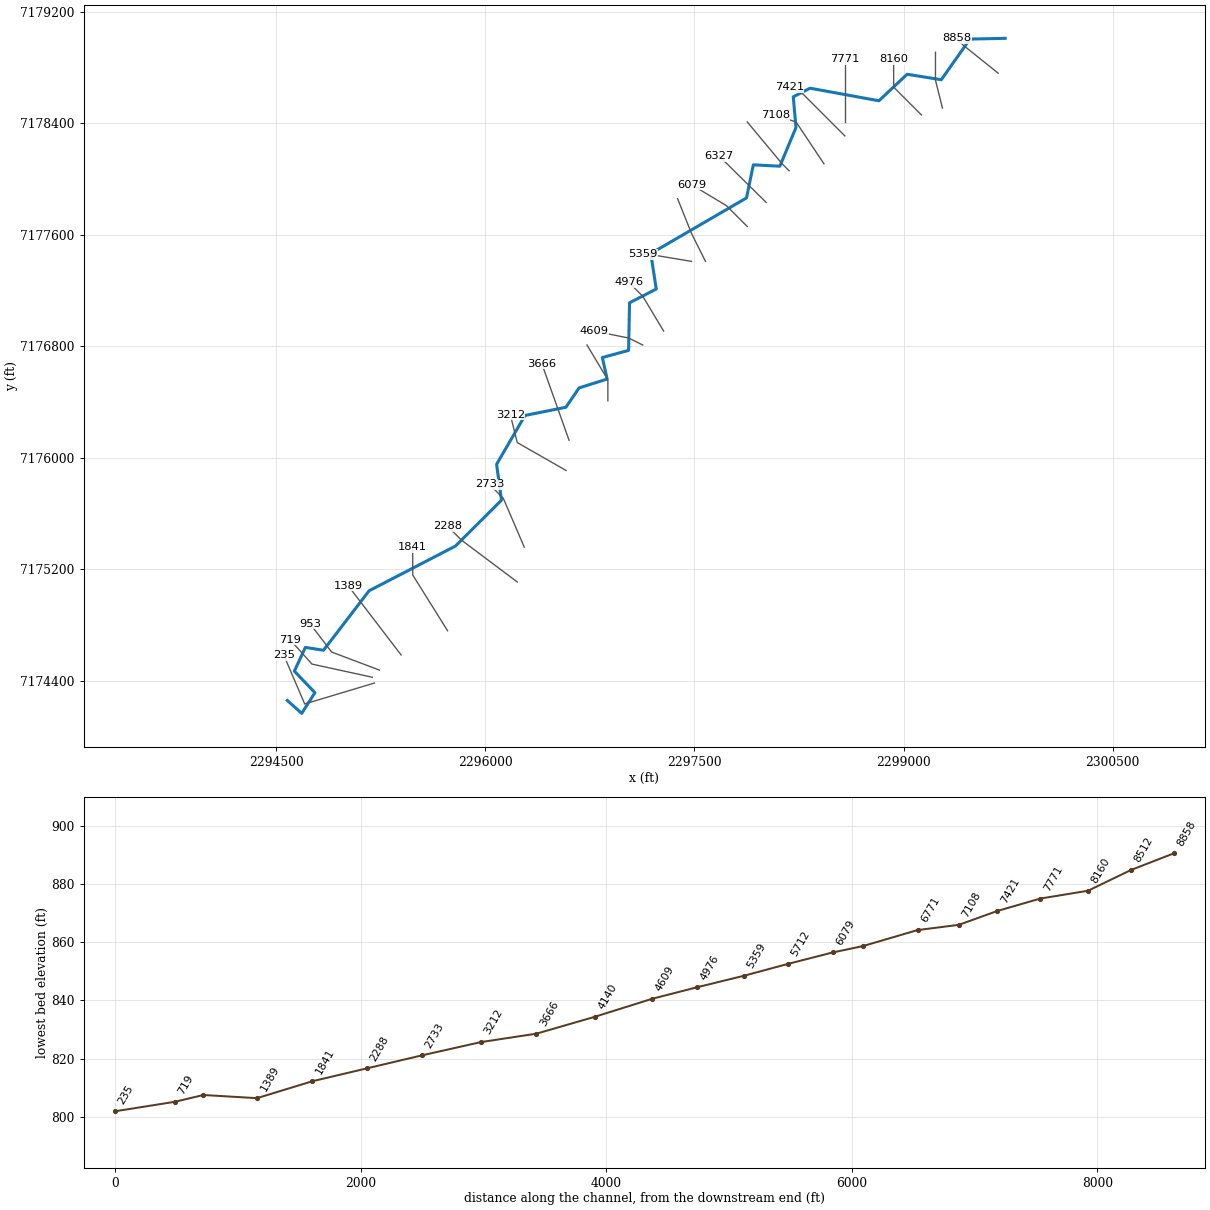
--- MDE S 047.prj (project) ---

Proj Title=MDE S 047 Base Level Engineering
Current Plan=p01
Default Exp/Contr=0.3,0.1
English Units
Geom File=g01
Flow File=f01
Plan File=p01
BEGIN DESCRIPTION:
MDE S 047
END DESCRIPTION:

--- MDE S 047.p01 (plan) ---

Plan Title=Multiple Run
Short Identifier=Multiple
Geom File=g01
Flow File=f01
Subcritical Flow
K Sum by GR= 0
Std Step Tol= 0.01
Critical Tol= 0.01
Num of Std Step Trials= 20
Max Error Tol= 0.3
Flow Tol Ratio= 0.001
Split Flow NTrial= 30
Split Flow Tol= 0.02
Split Flow Ratio= 0.02
Log Output Level= 0
Friction Slope Method= 1
Unsteady Friction Slope Method= 2
Unsteady Bridges Friction Slope Method= 1
Parabolic Critical Depth
Global Vel Dist=  1 , 1 , 1
Global Log Level= 0
CheckData=True
Encroach Param= -1, 0, 0, 0
BEGIN DESCRIPTION:
Multiple Run
END DESCRIPTION:

--- MDE S 047.f01 (steady flow) ---

Flow Title=Multiple
Number of Profiles=7
Profile Names=10-year,25-year,50-year,1pct_min,100-year,1pct_plu,500-year
River Rch & RM= MDE S 047,Reach-1,8858
     718     995    1226     751    1498    2988    2239
River Rch & RM= MDE S 047,Reach-1,4140
    1037    1464    1829    1134    2262    4513    3465
Boundary for River Rch & Prof#=MDE S 047,Reach-1,1
Up Type=0
Dn Type=3
Dn Slope=0.005
Boundary for River Rch & Prof#=MDE S 047,Reach-1,2
Up Type=0
Dn Type=3
Dn Slope=0.005
Boundary for River Rch & Prof#=MDE S 047,Reach-1,3
Up Type=0
Dn Type=3
Dn Slope=0.005
Boundary for River Rch & Prof#=MDE S 047,Reach-1,4
Up Type=0
Dn Type=3
Dn Slope=0.005
Boundary for River Rch & Prof#=MDE S 047,Reach-1,5
Up Type=0
Dn Type=3
Dn Slope=0.005
Boundary for River Rch & Prof#=MDE S 047,Reach-1,6
Up Type=0
Dn Type=3
Dn Slope=0.005
Boundary for River Rch & Prof#=MDE S 047,Reach-1,7
Up Type=0
Dn Type=3
Dn Slope=0.005

--- MDE S 047.g01 (geometry) ---

Geom Title=Existing Conditions

River Reach=MDE S 047,Reach-1
Reach XY= 30
      2299729.00      7179010.00      2299476.33      7179004.70
      2299270.70      7178713.07      2299025.58      7178752.21
      2298823.15      7178562.06      2298328.99      7178652.47
      2298208.82      7178590.23      2298228.44      7178370.64
      2298112.72      7178092.69      2297922.30      7178102.52
      2297873.56      7177865.25      2297186.80      7177466.21
      2297225.97      7177211.39      2297034.34      7177112.74
      2297027.52      7176771.49      2296839.03      7176720.06
      2296873.89      7176565.68      2296672.53      7176502.30
      2296577.75      7176363.46      2296284.44      7176304.75
      2296080.62      7175953.97      2296115.63      7175696.68
      2295785.45      7175367.75      2295165.68      7175046.63
      2294838.97      7174620.13      2294708.92      7174640.72
      2294629.87      7174470.33      2294777.26      7174316.16
      2294682.59      7174167.40      2294579.00      7174260.00

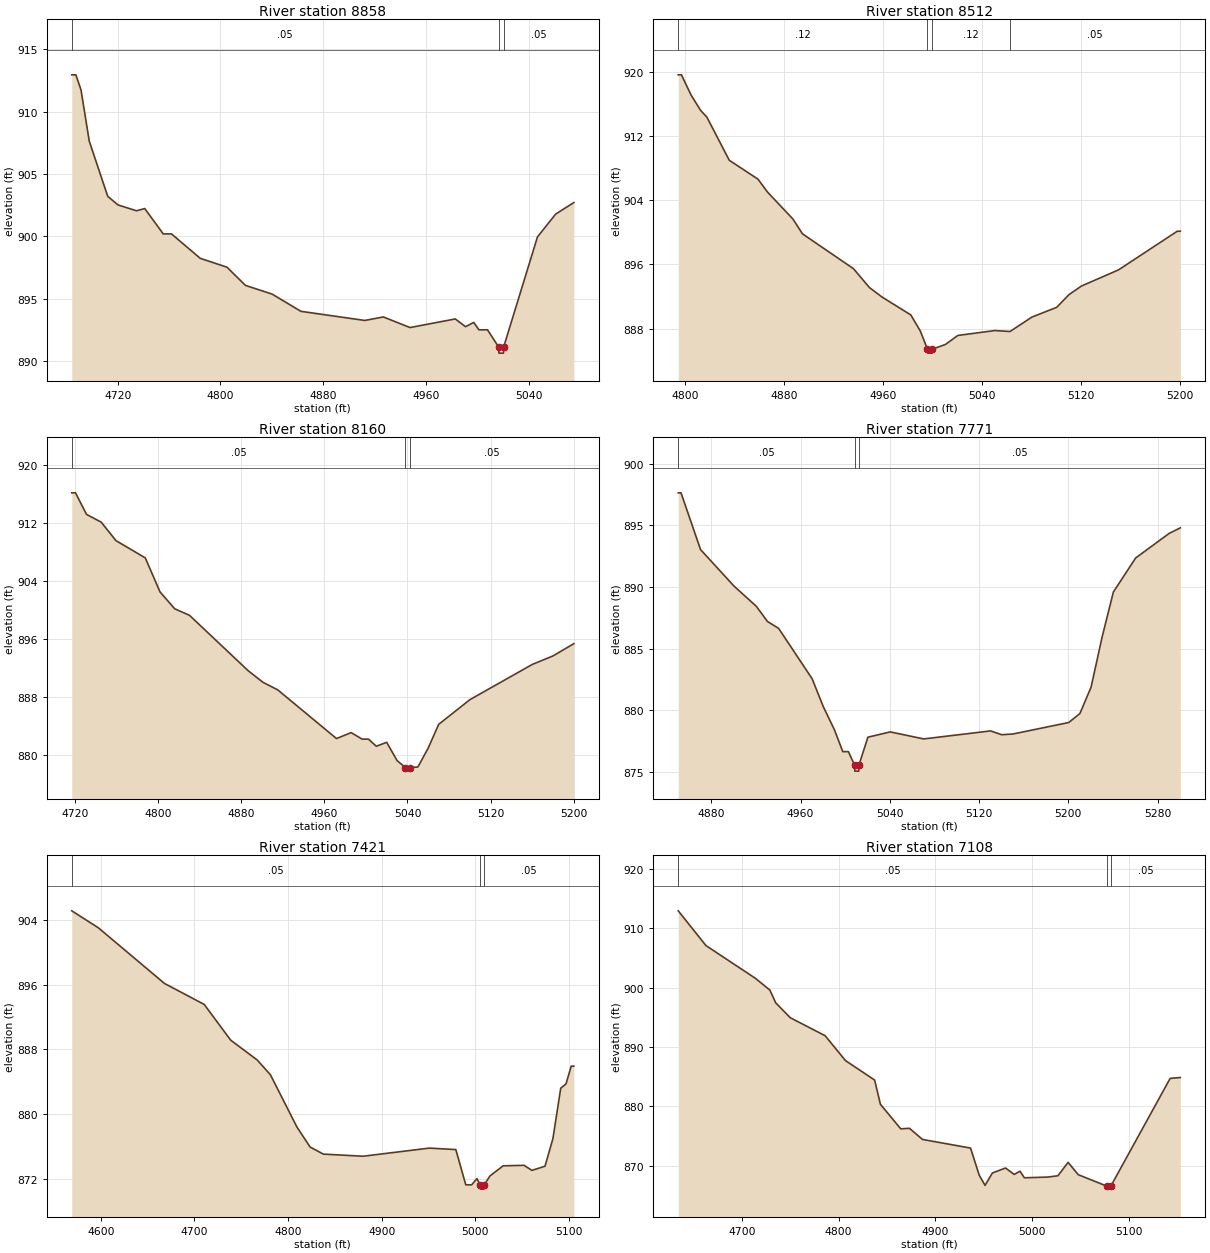
Type RM Length L Ch R = 1,8858,346,346,346
BEGIN DESCRIPTION:
MDE S 047 20.0
END DESCRIPTION:
XS GIS Cut Line= 3
      2299678.96      7178760.03      2299429.00      7178960.00
      2299379.01      7179009.99
#Sta/Elev= 30
  4684.3  912.94  4687.5  912.94  4691.5  911.73  4697.9  907.63  4712.3  903.20
  4720.3  902.51  4734.7  902.04  4741.1  902.22  4755.5  900.19  4761.9  900.19
  4784.3  898.23  4805.1  897.52  4819.5  896.06  4840.3  895.36  4862.7  893.98
  4912.4  893.25  4926.8  893.53  4947.6  892.68  4982.8  893.37  4990.8  892.75
  4997.2  893.09  5001.2  892.50  5007.9  892.50  5016.5  891.13  5016.8  890.63
  5020.3  890.63  5020.5  891.13  5046.8  899.95  5061.0  901.78  5075.1  902.70
#Mann=3,-1,0
  4684.3    0.05       0  5016.5   0.033       0  5020.5    0.05       0
Bank Sta=5016.5,5020.5
Exp/Cntr=0.3,0.1

Type RM Length L Ch R = 1,8512,352,352,352
BEGIN DESCRIPTION:
MDE S 047 19.0
END DESCRIPTION:
XS GIS Cut Line= 3
      2299279.01      7178509.96      2299229.00      7178710.00
      2299229.00      7178910.00
#Sta/Elev= 30
  4794.4  919.59  4797.0  919.59  4804.8  917.07  4812.5  915.17  4817.6  914.32
  4835.7  908.95  4858.9  906.61  4866.6  905.00  4887.2  901.64  4894.9  899.80
  4936.2  895.46  4949.1  893.11  4959.4  891.92  4982.6  889.70  4990.3  887.69
  4996.0  885.45  4996.3  884.95  4999.8  884.95  5000.0  885.45  5010.6  886.03
  5020.6  887.15  5050.6  887.76  5062.8  887.64  5080.6  889.44  5100.6  890.65
  5110.6  892.24  5120.6  893.30  5150.6  895.31  5198.1  900.12  5200.6  900.12
#Mann=4,-1,0
  4794.4    0.12       0  4996.0    0.07       0  5000.0    0.12       0
  5062.8    0.05       0
Bank Sta=4996,5000
Exp/Cntr=0.3,0.1

Type RM Length L Ch R = 1,8160,389,389,389
BEGIN DESCRIPTION:
MDE S 047 18.0
END DESCRIPTION:
XS GIS Cut Line= 3
      2299129.03      7178459.97      2298929.00      7178660.00
      2298929.00      7178860.02
#Sta/Elev= 30
  4717.1  916.22  4720.7  916.22  4731.3  913.24  4745.4  912.17  4759.6  909.62
  4787.8  907.23  4802.0  902.53  4816.1  900.20  4830.3  899.30  4886.8  891.64
  4901.0  890.04  4915.1  889.01  4971.7  882.27  4985.8  883.09  4996.4  882.19
  5002.5  882.19  5010.0  881.21  5020.0  881.75  5030.0  879.22  5038.0  878.27
  5038.2  877.77  5041.7  877.77  5042.0  878.27  5050.0  878.34  5060.0  880.98
  5070.0  884.23  5100.0  887.64  5160.0  892.51  5180.0  893.69  5200.0  895.38
#Mann=3,-1,0
  4717.1    0.05       0  5038.0   0.033       0  5042.0    0.05       0
Bank Sta=5038,5042
Exp/Cntr=0.3,0.1

Type RM Length L Ch R = 1,7771,350,350,350
BEGIN DESCRIPTION:
MDE S 047 17.0
END DESCRIPTION:
XS GIS Cut Line= 3
      2298579.00      7178409.99      2298579.00      7178560.00
      2298579.00      7178859.99
#Sta/Elev= 30
  4850.4  897.64  4852.9  897.64  4870.4  893.04  4900.4  890.08  4920.4  888.44
  4930.4  887.21  4940.4  886.65  4970.4  882.57  4980.4  880.31  4990.4  878.43
  4997.9  876.66  5002.9  876.66  5008.4  875.58  5008.7  875.08  5012.2  875.08
  5012.4  875.58  5020.4  877.83  5040.4  878.26  5070.4  877.69  5130.4  878.34
  5140.4  878.03  5150.4  878.09  5200.4  879.02  5210.4  879.75  5220.4  881.88
  5230.4  885.98  5240.4  889.60  5260.4  892.36  5290.4  894.35  5300.4  894.80
#Mann=3,-1,0
  4850.4    0.05       0  5008.4   0.033       0  5012.4    0.05       0
Bank Sta=5008.4,5012.4
Exp/Cntr=0.3,0.1

Type RM Length L Ch R = 1,7421,313,313,313
BEGIN DESCRIPTION:
MDE S 047 16.0
END DESCRIPTION:
XS GIS Cut Line= 3
      2298578.99      7178310.01      2298279.00      7178610.00
      2298178.96      7178660.02
#Sta/Elev= 30
  4569.1  905.07  4597.4  902.99  4668.1  896.13  4710.5  893.55  4738.8  889.15
  4767.1  886.71  4781.2  884.89  4809.5  878.46  4823.6  875.99  4837.8  875.12
  4880.2  874.86  4950.9  875.86  4979.2  875.68  4989.8  871.34  4996.1  871.34
  5001.7  872.11  5005.3  871.31  5005.6  870.81  5009.1  870.81  5009.3  871.31
  5015.7  872.44  5029.7  873.68  5052.0  873.74  5060.4  873.12  5074.4  873.63
  5082.8  877.00  5091.2  883.23  5096.8  883.76  5102.4  885.95  5105.2  885.95
#Mann=3,-1,0
  4569.1    0.05       0  5005.3   0.033       0  5009.3    0.05       0
Bank Sta=5005.3,5009.3
Exp/Cntr=0.3,0.1

Type RM Length L Ch R = 1,7108,337,337,337
BEGIN DESCRIPTION:
MDE S 047 15.0
END DESCRIPTION:
XS GIS Cut Line= 3
      2298429.03      7178109.96      2298229.00      7178410.00
      2298079.02      7178459.99
#Sta/Elev= 30
  4634.4  912.94  4663.0  907.09  4714.1  901.57  4729.1  899.58  4735.1  897.44
  4750.1  894.93  4786.2  891.89  4807.2  887.70  4837.3  884.42  4843.3  880.33
  4864.3  876.20  4873.3  876.29  4886.8  874.41  4936.4  872.96  4945.4  868.37
  4951.4  866.67  4958.9  868.75  4972.5  869.60  4981.5  868.52  4987.5  869.06
  4992.0  867.95  5016.1  868.07  5026.6  868.29  5037.2  870.55  5047.7  868.47
  5077.3  866.54  5077.6  866.04  5081.3  866.54  5142.6  884.70  5153.1  884.85
#Mann=3,-1,0
  4634.4    0.05       0  5077.3   0.033       0  5081.3    0.05       0
Bank Sta=5077.3,5081.3
Exp/Cntr=0.3,0.1

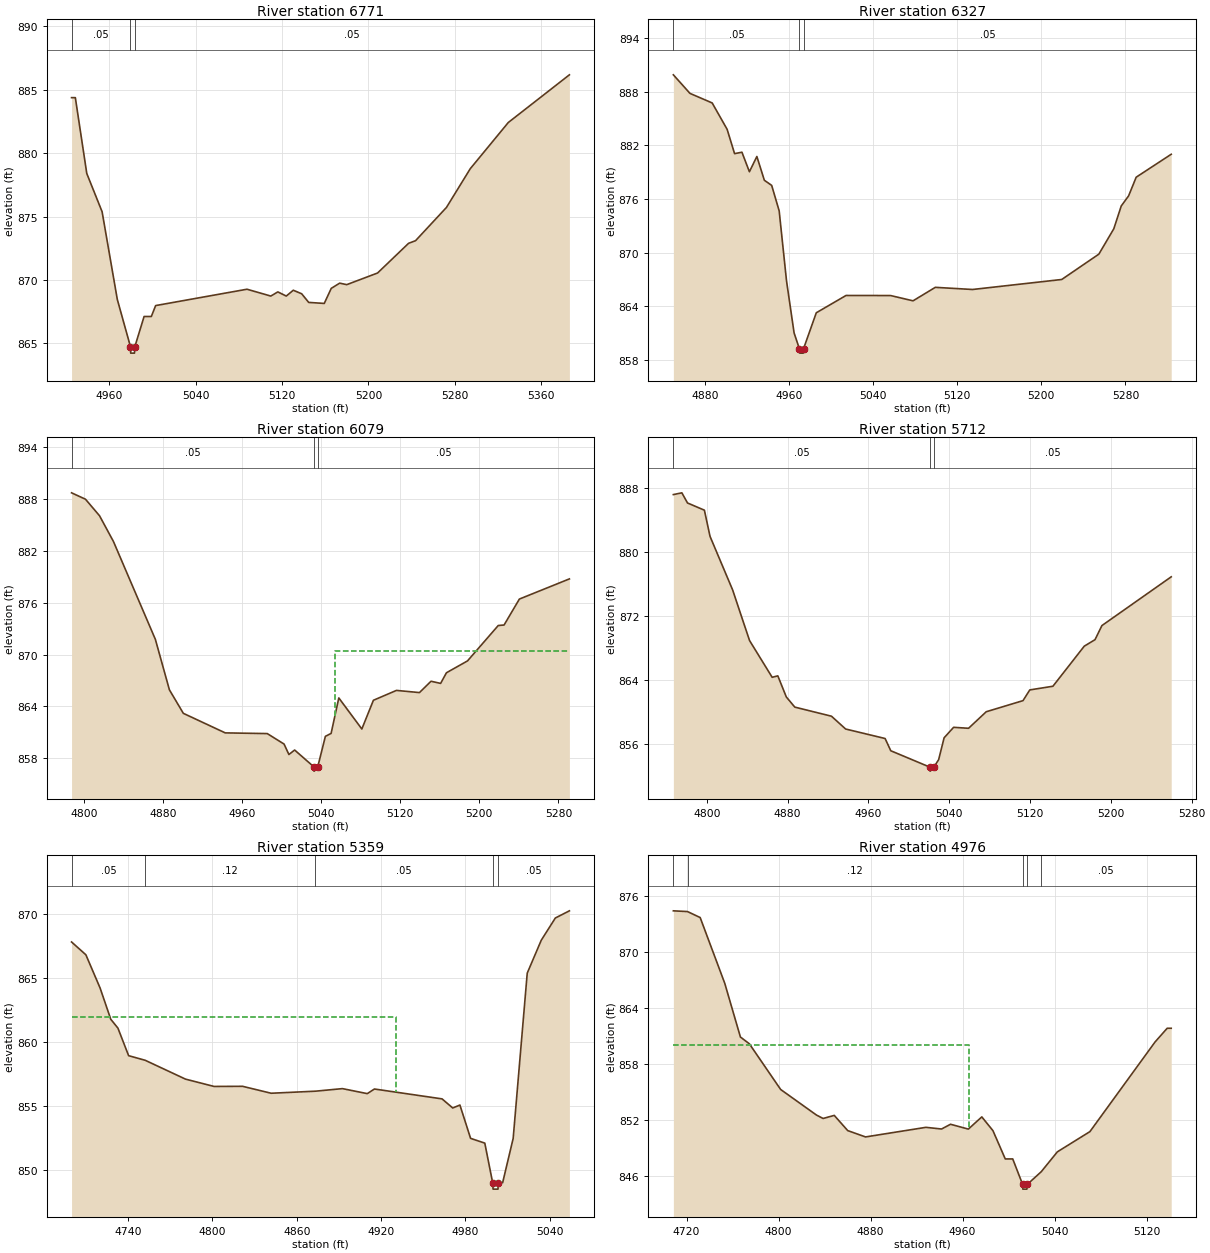
Type RM Length L Ch R = 1,6771,444,444,444
BEGIN DESCRIPTION:
MDE S 047 14.0
END DESCRIPTION:
XS GIS Cut Line= 3
      2298178.99      7178060.01      2298129.00      7178110.00
      2297879.00      7178409.99
#Sta/Elev= 30
  4925.0  884.38  4928.5  884.38  4939.1  878.40  4953.3  875.38  4967.4  868.46
  4979.6  864.73  4979.8  864.23  4983.3  864.23  4983.6  864.73  4992.2  867.12
  4998.9  867.12  5002.9  867.98  5087.5  869.27  5109.6  868.73  5116.1  869.06
  5123.9  868.73  5130.4  869.19  5138.2  868.91  5144.7  868.23  5159.1  868.15
  5165.6  869.34  5173.4  869.75  5179.9  869.63  5208.5  870.55  5237.2  872.89
  5243.7  873.10  5272.3  875.72  5294.4  878.78  5329.6  882.42  5386.2  886.18
#Mann=3,-1,0
  4925.0    0.05       0  4979.6   0.033       0  4983.6    0.05       0
Bank Sta=4979.6,4983.6
Exp/Cntr=0.3,0.1

Type RM Length L Ch R = 1,6327,248,248,248
BEGIN DESCRIPTION:
Mapping XS 77d4e660
END DESCRIPTION:
XS GIS Cut Line= 2
      2298014.39      7177833.12      2297677.17      7178165.36
#Sta/Elev= 30
  4850.1  889.91  4865.9  887.83  4887.0  886.76  4901.2  883.81  4908.3  881.08
  4915.3  881.24  4922.4  879.05  4929.5  880.76  4936.6  878.10  4943.6  877.52
  4950.7  874.67  4957.7  866.82  4964.9  860.99  4969.9  859.23  4970.1  858.73
  4973.6  858.73  4973.9  859.23  4986.0  863.25  5014.3  865.19  5056.7  865.18
  5078.0  864.59  5099.2  866.10  5134.6  865.86  5219.4  866.98  5254.7  869.82
  5268.9  872.66  5276.0  875.22  5283.0  876.35  5290.2  878.44  5323.5  881.01
#Mann=3,-1,0
  4850.1    0.05       0  4969.9   0.033       0  4973.9    0.05       0
Bank Sta=4969.9,4973.9
Exp/Cntr=0.3,0.1

Type RM Length L Ch R = 1,6079,367,367,367
BEGIN DESCRIPTION:
MDE S 047 12.0
END DESCRIPTION:
XS GIS Cut Line= 3
      2297878.98      7177660.02      2297729.00      7177810.00
      2297478.96      7177960.03
#Sta/Elev= 30
  4787.4  888.69  4801.5  887.95  4815.7  886.04  4829.8  883.06  4872.2  871.75
  4886.4  865.92  4900.5  863.20  4942.9  860.94  4985.4  860.86  5002.4  859.65
  5007.3  858.44  5013.1  858.96  5032.5  857.02  5032.7  856.52  5036.5  857.02
  5044.2  860.54  5050.0  860.88  5057.8  864.98  5081.1  861.39  5092.8  864.71
  5116.1  865.85  5139.4  865.60  5151.1  866.91  5160.8  866.66  5166.7  867.89
  5188.0  869.26  5219.1  873.35  5225.0  873.41  5240.5  876.41  5291.1  878.74
#Mann=3,-1,0
  4787.4    0.05       0  5032.5   0.033       0  5036.5    0.05       0
#XS Ineff=2,0
       0                 5053.90    0.00  870.44
Permanent Ineff=
       F       F
Bank Sta=5032.5,5036.5
Exp/Cntr=0.3,0.1

Type RM Length L Ch R = 1,5712,353,353,353
BEGIN DESCRIPTION:
MDE S 047 11.0
END DESCRIPTION:
XS GIS Cut Line= 3
      2297578.99      7177410.02      2297479.00      7177610.00
      2297379.01      7177859.96
#Sta/Elev= 30
  4766.9  887.15  4775.3  887.37  4780.9  886.10  4797.6  885.20  4803.2  881.92
  4825.6  875.21  4842.3  868.89  4864.7  864.29  4870.3  864.47  4878.7  861.83
  4887.1  860.56  4923.4  859.42  4937.4  857.82  4976.5  856.63  4982.1  855.10
  5020.8  853.05  5021.0  852.55  5024.8  853.05  5029.5  853.99  5034.9  856.72
  5044.3  858.03  5059.1  857.91  5076.6  859.98  5113.0  861.37  5119.7  862.71
  5142.6  863.17  5173.6  868.18  5184.3  869.00  5191.1  870.76  5259.7  876.86
#Mann=3,-1,0
  4766.9    0.05       0  5020.8   0.033       0  5024.8    0.05       0
Bank Sta=5020.8,5024.8
Exp/Cntr=0.3,0.1

Type RM Length L Ch R = 1,5359,383,383,383
BEGIN DESCRIPTION:
MDE S 047 10.0
END DESCRIPTION:
XS GIS Cut Line= 3
      2297479.03      7177409.99      2297179.00      7177460.00
      2297128.97      7177460.00
#Sta/Elev= 30
  4699.8  867.81  4710.0  866.81  4720.1  864.22  4727.7  861.78  4732.8  861.09
  4740.4  858.94  4752.2  858.58  4780.9  857.11  4801.2  856.54  4821.5  856.55
  4841.8  856.01  4873.3  856.17  4892.5  856.37  4910.2  855.98  4915.3  856.34
  4963.4  855.57  4971.0  854.86  4976.1  855.09  4983.7  852.49  4993.8  852.12
  4999.4  849.03  4999.7  848.53  5003.2  848.53  5003.4  849.03  5006.5  849.03
  5014.0  852.49  5024.0  865.38  5034.0  867.95  5044.0  869.68  5054.0  870.24
#Mann=5,-1,0
  4699.8    0.05       0  4752.2    0.12       0  4873.3    0.05       0
  4999.4   0.033       0  5003.4    0.05       0
#XS Ineff=2,0
    0.00 4930.70  861.98               0
Permanent Ineff=
       F       F
Bank Sta=4999.4,5003.4
Exp/Cntr=0.3,0.1

Type RM Length L Ch R = 1,4976,367,367,367
BEGIN DESCRIPTION:
MDE S 047 9.0
END DESCRIPTION:
XS GIS Cut Line= 3
      2297278.98      7176910.03      2297129.00      7177160.00
      2297029.03      7177259.97
#Sta/Elev= 30
  4708.5  874.42  4720.8  874.34  4731.8  873.70  4753.2  866.64  4766.8  860.88
  4774.6  860.15  4801.8  855.25  4832.9  852.51  4838.7  852.14  4848.4  852.47
  4860.1  850.84  4875.6  850.16  4928.1  851.19  4941.7  851.01  4949.5  851.52
  4965.0  851.00  4976.7  852.31  4986.4  850.83  4997.1  847.80  5003.6  847.80
  5012.2  845.06  5012.4  844.56  5015.9  844.56  5016.2  845.06  5028.4  846.43
  5042.4  848.56  5070.7  850.73  5127.3  860.34  5137.9  861.82  5141.4  861.82
#Mann=5,-1,0
  4708.5    0.05       0  4720.8    0.12       0  5012.2    0.07       0
  5016.2    0.12       0  5028.4    0.05       0
#XS Ineff=2,0
    0.00 4965.60  860.06               0
Permanent Ineff=
       F       F
Bank Sta=5012.2,5016.2
Exp/Cntr=0.3,0.1

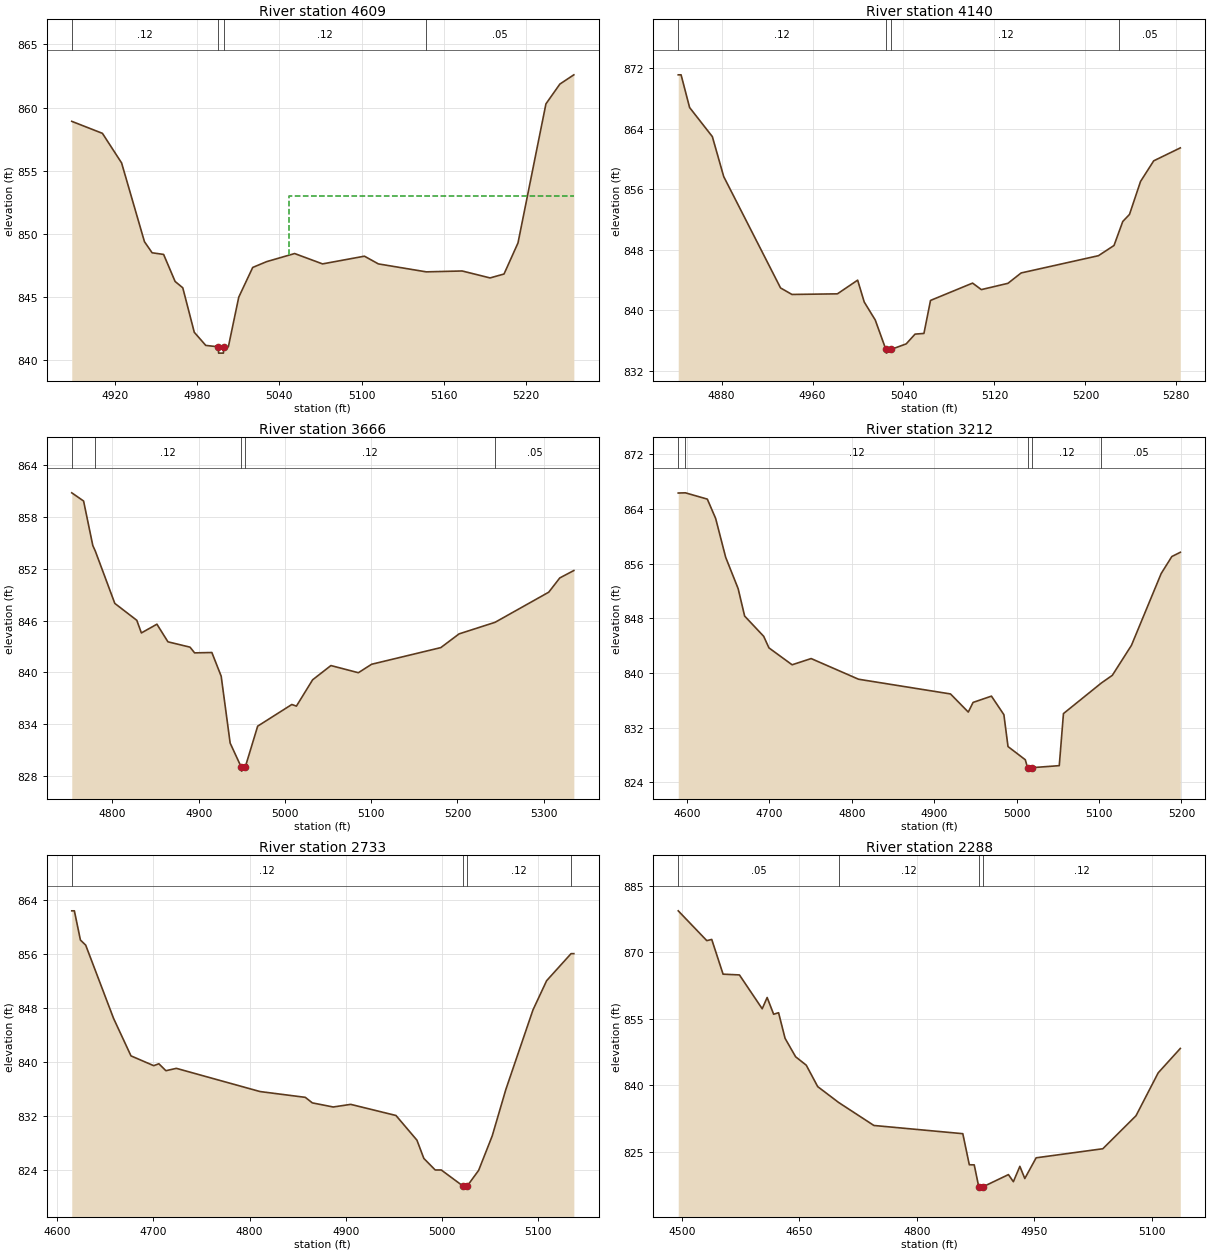
Type RM Length L Ch R = 1,4609,469,469,469
BEGIN DESCRIPTION:
MDE S 047 8.0
END DESCRIPTION:
XS GIS Cut Line= 3
      2297129.03      7176809.99      2297029.00      7176860.00
      2296778.99      7176910.00
#Sta/Elev= 30
  4888.3  858.92  4910.7  857.97  4924.7  855.63  4941.4  849.40  4947.0  848.52
  4955.4  848.39  4963.8  846.25  4969.4  845.75  4977.8  842.23  4986.2  841.19
  4995.3  841.08  4995.6  840.58  4999.1  840.58  4999.3  841.08  5002.7  841.08
  5010.3  845.01  5020.5  847.36  5030.7  847.82  5051.1  848.46  5071.5  847.64
  5102.1  848.25  5112.3  847.64  5147.3  847.01  5173.5  847.08  5193.9  846.53
  5204.1  846.84  5214.3  849.30  5234.7  860.30  5244.9  861.87  5255.1  862.60
#Mann=4,-1,0
  4888.3    0.12       0  4995.3    0.07       0  4999.3    0.12       0
  5147.3    0.05       0
#XS Ineff=2,0
       0                 5047.30    0.00  852.99
Permanent Ineff=
       F       F
Bank Sta=4995.3,4999.3
Exp/Cntr=0.3,0.1

Type RM Length L Ch R = 1,4140,474,474,474
BEGIN DESCRIPTION:
MDE S 047 7.0
END DESCRIPTION:
XS GIS Cut Line= 3
      2296879.00      7176409.99      2296879.00      7176560.00
      2296728.98      7176810.03
#Sta/Elev= 30
  4841.9  871.12  4844.4  871.12  4851.9  866.80  4871.9  862.96  4881.9  857.68
  4931.9  842.97  4941.9  842.11  4981.9  842.19  4999.7  844.00  5005.5  841.11
  5015.2  838.73  5024.5  834.86  5025.0  834.36  5029.3  834.86  5042.4  835.58
  5050.2  836.87  5058.0  836.96  5063.8  841.32  5100.8  843.61  5108.5  842.75
  5131.9  843.58  5143.5  844.95  5211.5  847.23  5225.2  848.58  5230.0  850.56
  5232.9  851.75  5238.8  852.68  5248.5  857.03  5260.1  859.76  5283.5  861.47
#Mann=4,-1,0
  4841.9    0.12       0  5024.5    0.07       0  5029.3    0.12       0
  5230.0    0.05       0
Bank Sta=5024.5,5029.3
Exp/Cntr=0.3,0.1

Type RM Length L Ch R = 1,3666,454,454,454
BEGIN DESCRIPTION:
Mapping XS 0288444c
END DESCRIPTION:
XS GIS Cut Line= 2
      2296600.35      7176126.99      2296405.27      7176675.32
#Sta/Elev= 30
  4752.9  860.81  4766.6  859.86  4777.3  854.70  4780.2  854.06  4802.8  848.00
  4828.3  846.04  4833.6  844.58  4851.6  845.59  4864.4  843.55  4890.0  842.93
  4895.3  842.27  4915.3  842.31  4926.1  839.57  4936.5  831.82  4949.2  829.07
  4949.8  828.57  4954.1  829.07  4968.4  833.78  5008.0  836.29  5013.3  836.10
  5032.1  839.15  5053.3  840.80  5085.1  839.97  5100.5  840.95  5180.7  842.88
  5201.9  844.47  5243.6  845.81  5305.8  849.30  5318.6  850.95  5334.9  851.81
#Mann=5,-1,0
  4752.9    0.05       0  4780.2    0.12       0  4949.2    0.07       0
  4954.1    0.12       0  5243.6    0.05       0
Bank Sta=4949.2,4954.1
Exp/Cntr=0.3,0.1

Type RM Length L Ch R = 1,3212,479,479,479
BEGIN DESCRIPTION:
MDE S 047 5.0
END DESCRIPTION:
XS GIS Cut Line= 3
      2296579.01      7175909.99      2296229.00      7176110.00
      2296179.00      7176310.02
#Sta/Elev= 30
  4589.3  866.30  4598.0  866.33  4624.6  865.41  4634.7  862.59  4646.9  856.90
  4662.0  852.33  4669.9  848.32  4693.0  845.36  4699.4  843.67  4727.5  841.20
  4750.6  842.11  4808.1  839.09  4919.7  836.94  4941.3  834.29  4947.1  835.70
  4969.4  836.62  4984.5  833.91  4989.5  829.25  5010.5  827.32  5013.2  826.16
  5013.8  825.66  5018.1  826.16  5051.7  826.46  5056.8  834.07  5102.7  838.53
  5116.1  839.66  5139.3  844.04  5175.4  854.54  5188.3  857.02  5198.6  857.64
#Mann=5,-1,0
  4589.3    0.05       0  4598.0    0.12       0  5013.2    0.07       0
  5018.1    0.12       0  5102.7    0.05       0
Bank Sta=5013.2,5018.1
Exp/Cntr=0.3,0.1

Type RM Length L Ch R = 1,2733,445,445,445
BEGIN DESCRIPTION:
MDE S 047 4.0
END DESCRIPTION:
XS GIS Cut Line= 3
      2296278.98      7175360.04      2296129.00      7175710.00
      2296028.98      7175810.02
#Sta/Elev= 30
  4615.0  862.37  4617.7  862.37  4624.0  858.04  4629.5  857.28  4658.5  846.41
  4676.6  840.86  4700.2  839.41  4705.6  839.69  4712.9  838.66  4723.8  839.01
  4810.8  835.57  4857.9  834.71  4865.2  833.89  4886.9  833.28  4905.1  833.67
  4952.2  832.02  4974.0  828.36  4981.2  825.65  4993.0  823.94  4999.3  823.94
  5021.5  821.60  5022.2  821.10  5026.5  821.60  5038.2  823.89  5052.3  828.99
  5066.5  835.89  5094.7  847.68  5108.9  852.01  5134.3  856.02  5137.2  856.02
#Mann=4,-1,0
  4615.0    0.12       0  5021.5    0.07       0  5026.5    0.12       0
  5134.3    0.05       0
Bank Sta=5021.5,5026.5
Exp/Cntr=0.3,0.1

Type RM Length L Ch R = 1,2288,447,447,447
BEGIN DESCRIPTION:
MDE S 047 3.0
END DESCRIPTION:
XS GIS Cut Line= 3
      2296229.03      7175109.97      2295829.00      7175410.00
      2295728.97      7175510.03
#Sta/Elev= 30
  4495.3  879.31  4531.8  872.60  4538.1  872.87  4552.6  865.05  4573.5  864.88
  4602.6  857.26  4608.9  859.80  4617.2  856.03  4623.5  856.37  4631.8  850.61
  4645.3  846.45  4658.9  844.56  4673.5  839.74  4700.3  836.16  4745.3  830.99
  4858.9  829.14  4867.2  822.15  4873.5  822.12  4879.3  817.16  4879.9  816.66
  4884.4  817.16  4917.2  819.93  4923.5  818.33  4931.8  821.79  4938.1  819.05
  4952.6  823.71  5037.8  825.75  5080.2  833.18  5108.5  842.83  5136.8  848.33
#Mann=4,-1,0
  4495.3    0.05       0  4700.3    0.12       0  4879.3    0.07       0
  4884.4    0.12       0
Bank Sta=4879.3,4884.4
Exp/Cntr=0.3,0.1

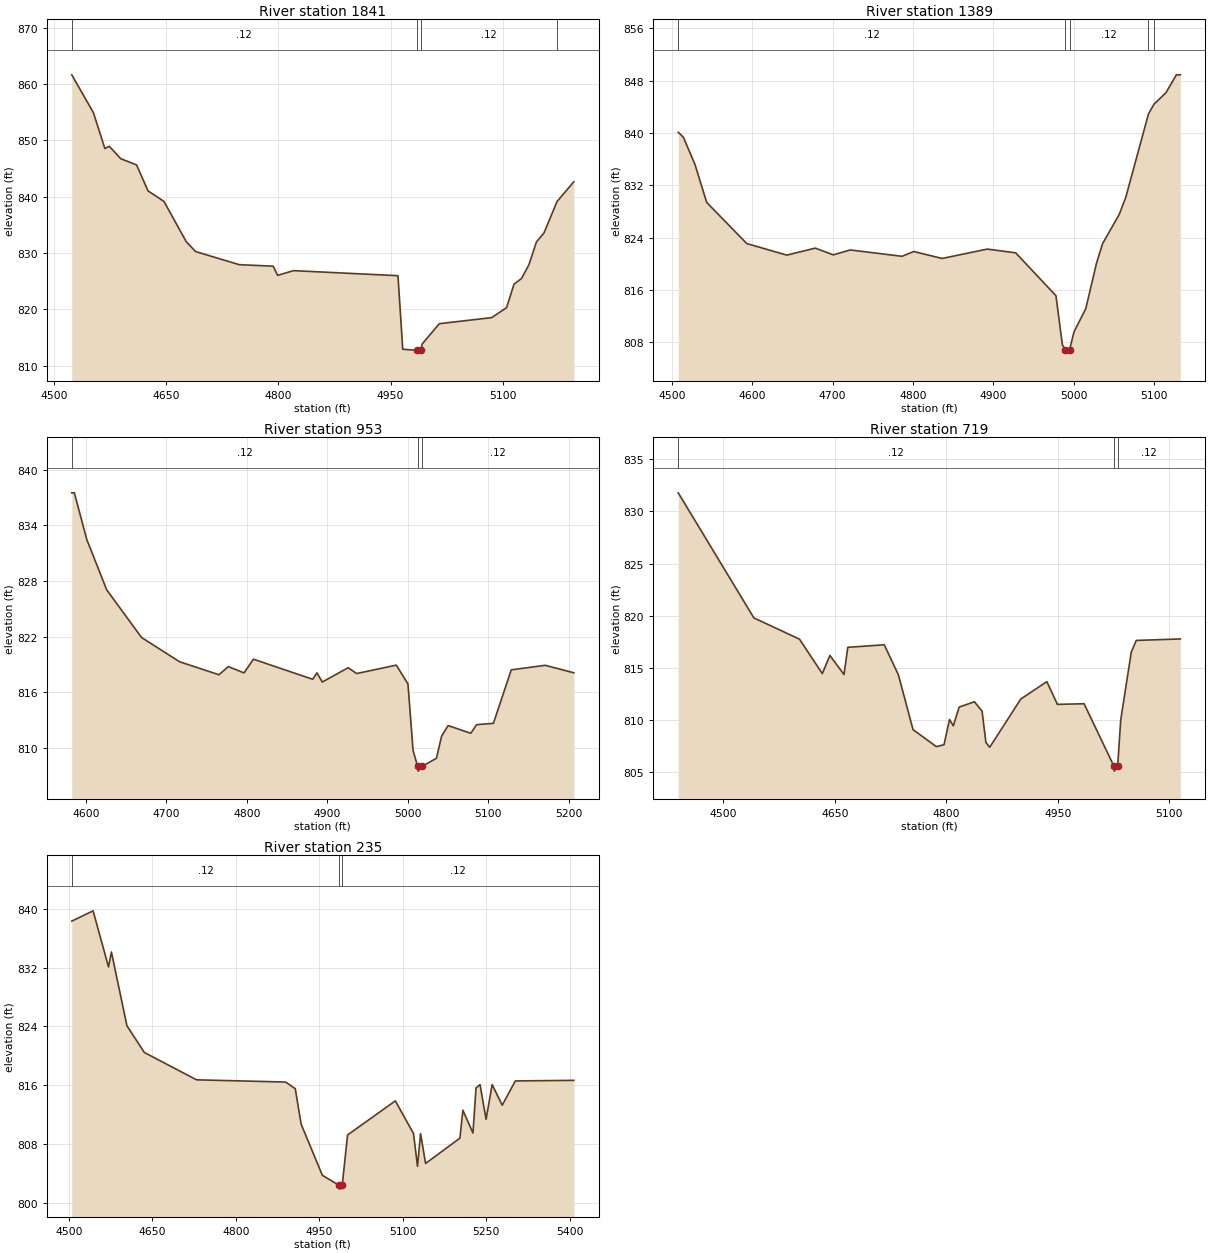
Type RM Length L Ch R = 1,1841,452,452,452
BEGIN DESCRIPTION:
MDE S 047 2.0
END DESCRIPTION:
XS GIS Cut Line= 3
      2295729.02      7174759.97      2295479.00      7175160.00
      2295479.00      7175359.96
#Sta/Elev= 30
  4523.5  861.66  4552.4  854.95  4567.8  848.56  4573.7  848.96  4589.0  846.76
  4610.2  845.65  4625.5  841.04  4646.8  839.17  4676.8  831.98  4689.2  830.25
  4747.6  827.92  4793.0  827.65  4798.9  826.02  4820.1  826.86  4959.9  825.96
  4966.3  812.89  4985.0  812.70  4985.7  812.20  4990.1  812.70  4992.3  813.82
  5015.2  817.43  5085.2  818.51  5105.2  820.28  5115.2  824.47  5125.2  825.46
  5135.2  827.94  5145.2  831.97  5155.2  833.54  5172.7  839.14  5195.2  842.66
#Mann=4,-1,0
  4523.5    0.12       0  4985.0    0.07       0  4990.1    0.12       0
  5172.7    0.05       0
Bank Sta=4985,4990.1
Exp/Cntr=0.3,0.1

Type RM Length L Ch R = 1,1389,436,436,436
BEGIN DESCRIPTION:
Mapping XS 25ec96d3
END DESCRIPTION:
XS GIS Cut Line= 2
      2295395.46      7174586.82      2295015.89      7175082.85
#Sta/Elev= 30
  4507.9  840.11  4514.3  839.35  4528.8  835.16  4543.3  829.39  4593.2  823.10
  4643.0  821.34  4678.4  822.41  4700.8  821.38  4721.9  822.13  4786.3  821.16
  4800.9  821.89  4836.2  820.83  4892.4  822.26  4927.7  821.69  4977.8  815.14
  4985.8  807.64  4989.5  806.87  4990.2  806.37  4994.7  806.87  5000.3  809.63
  5014.9  813.16  5028.2  820.08  5035.7  823.07  5056.5  827.55  5064.7  830.18
  5092.9  842.91  5099.8  844.40  5114.6  846.14  5127.6  848.88  5132.5  848.88
#Mann=5,-1,0
  4507.9    0.12       0  4989.5    0.07       0  4994.7    0.12       0
  5092.9    0.05       0  5099.8    0.12       0
Bank Sta=4989.5,4994.7
Exp/Cntr=0.3,0.1

Type RM Length L Ch R = 1,953,234,234,234
BEGIN DESCRIPTION:
Mapping XS 2ff4f7f8
END DESCRIPTION:
XS GIS Cut Line= 3
      2295240.08      7174477.97      2294897.48      7174607.20
      2294741.34      7174811.76
#Sta/Elev= 30
  4582.7  837.52  4585.9  837.52  4601.3  832.49  4626.1  827.04  4669.4  821.89
  4716.7  819.27  4765.5  817.87  4777.1  818.75  4796.6  818.07  4808.3  819.55
  4881.9  817.38  4887.2  818.08  4893.8  817.08  4925.9  818.63  4936.5  818.00
  4985.7  818.91  5000.2  816.88  5006.5  809.71  5012.2  807.96  5012.9  807.46
  5017.4  807.96  5035.6  808.85  5041.9  811.22  5050.1  812.38  5078.2  811.55
  5085.5  812.48  5106.3  812.62  5128.5  818.40  5170.7  818.89  5206.2  818.08
#Mann=3,-1,0
  4582.7    0.12       0  5012.2    0.07       0  5017.4    0.12       0
Bank Sta=5012.2,5017.4
Exp/Cntr=0.3,0.1

Type RM Length L Ch R = 1,719,484,484,484
BEGIN DESCRIPTION:
Mapping XS b384be06
END DESCRIPTION:
XS GIS Cut Line= 3
      2295188.44      7174426.61      2294756.14      7174521.04
      2294600.31      7174694.55
#Sta/Elev= 30
  4439.3  831.79  4541.1  819.80  4602.5  817.76  4633.2  814.46  4643.4  816.20
  4662.4  814.37  4667.5  816.98  4716.6  817.22  4735.6  814.34  4755.3  809.09
  4786.7  807.46  4797.0  807.64  4804.4  810.06  4809.5  809.45  4817.4  811.25
  4837.9  811.76  4848.2  810.86  4853.4  807.85  4858.5  807.40  4900.3  812.02
  4935.4  813.69  4949.6  811.51  4985.5  811.57  5025.5  805.61  5026.2  805.11
  5030.7  805.61  5034.8  810.00  5049.0  816.52  5055.7  817.64  5115.0  817.78
#Mann=3,-1,0
  4439.3    0.12       0  5025.5    0.07       0  5030.7    0.12       0
Bank Sta=5025.5,5030.7
Exp/Cntr=0.3,0.1

Type RM Length L Ch R = 1,235,0,0,0
BEGIN DESCRIPTION:
MDE S 047 1.0
END DESCRIPTION:
XS GIS Cut Line= 3
      2295203.97      7174384.99      2294704.00      7174235.00
      2294553.99      7174585.02
#Sta/Elev= 30
  4505.0  838.31  4543.3  839.71  4571.1  832.08  4576.3  834.11  4604.2  824.08
  4635.5  820.45  4729.4  816.73  4889.5  816.43  4906.9  815.53  4917.4  810.71
  4955.6  803.75  4986.1  802.37  4986.8  801.87  4991.3  802.37  5000.9  809.23
  5086.8  813.87  5119.5  809.43  5126.7  804.97  5132.2  809.42  5141.2  805.36
  5202.9  808.80  5208.3  812.59  5226.4  809.50  5231.9  815.62  5239.1  816.09
  5250.0  811.36  5260.9  816.09  5279.0  813.28  5302.6  816.58  5407.8  816.66
#Mann=3,-1,0
  4505.0    0.12       0  4986.1    0.07       0  4991.3    0.12       0
Bank Sta=4986.1,4991.3
Exp/Cntr=0.3,0.1

Chan Stop Cuts=-1