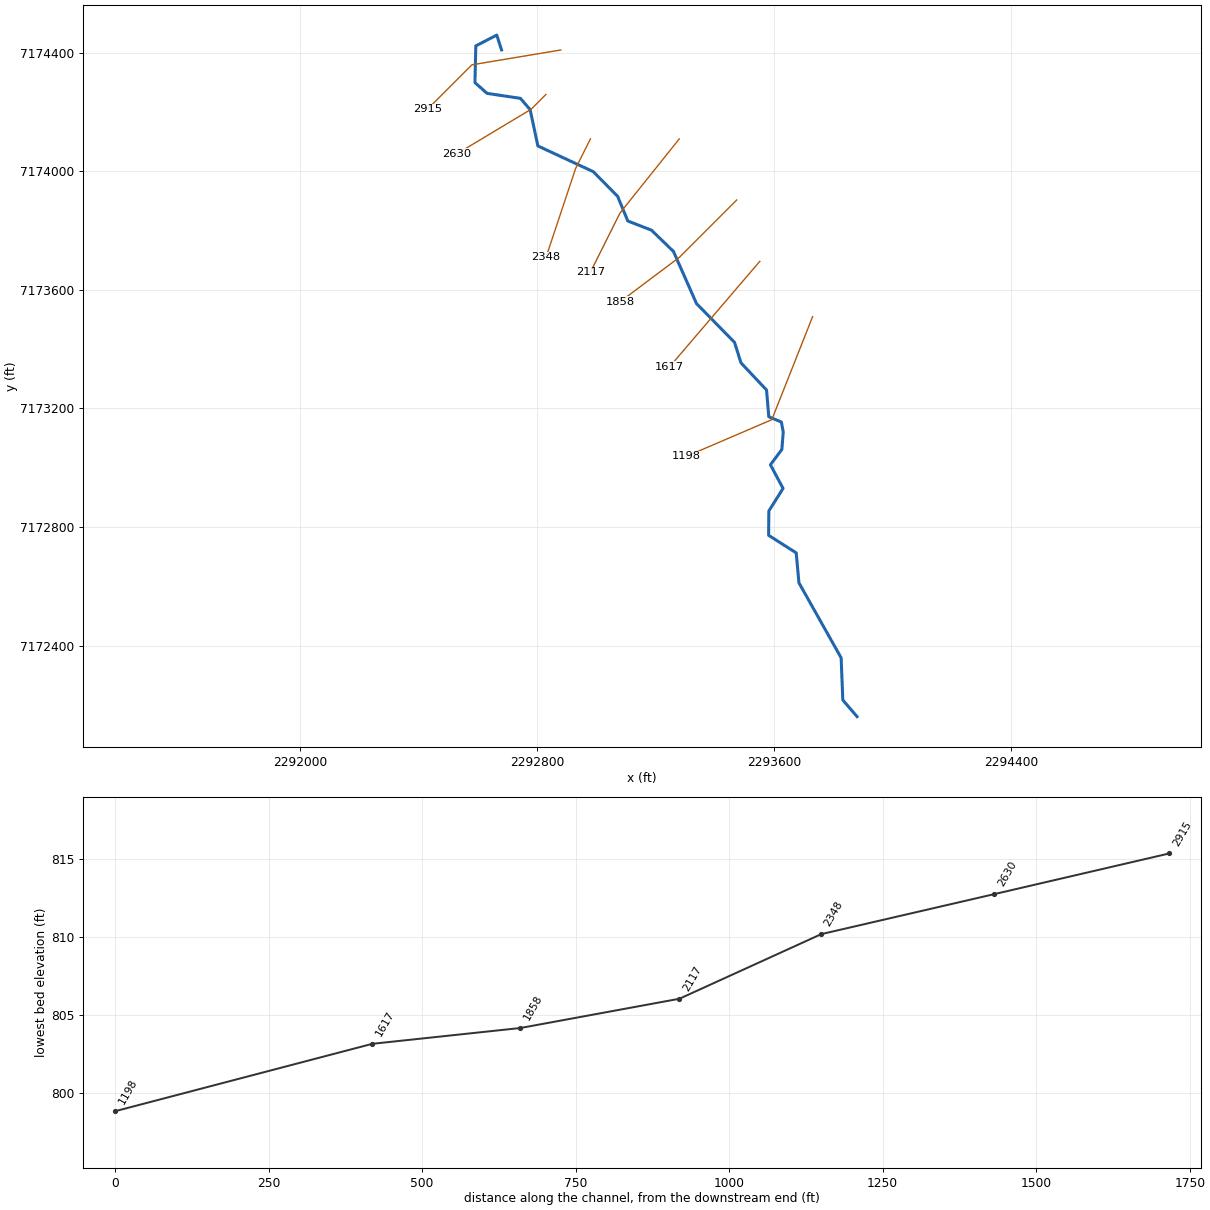
--- MDE S 048.prj (project) ---

Proj Title=MDE S 048 Base Level Engineering
Current Plan=p01
Default Exp/Contr=0.3,0.1
English Units
Geom File=g01
Flow File=f01
Plan File=p01
BEGIN DESCRIPTION:
MDE S 048
END DESCRIPTION:

--- MDE S 048.p01 (plan) ---

Plan Title=Multiple Run
Short Identifier=Multiple
Geom File=g01
Flow File=f01
Subcritical Flow
K Sum by GR= 0
Std Step Tol= 0.01
Critical Tol= 0.01
Num of Std Step Trials= 20
Max Error Tol= 0.3
Flow Tol Ratio= 0.001
Split Flow NTrial= 30
Split Flow Tol= 0.02
Split Flow Ratio= 0.02
Log Output Level= 0
Friction Slope Method= 1
Unsteady Friction Slope Method= 2
Unsteady Bridges Friction Slope Method= 1
Parabolic Critical Depth
Global Vel Dist=  1 , 1 , 1
Global Log Level= 0
CheckData=True
Encroach Param= -1, 0, 0, 0
BEGIN DESCRIPTION:
Multiple Run
END DESCRIPTION:

--- MDE S 048.f01 (steady flow) ---

Flow Title=Multiple
Number of Profiles=7
Profile Names=10-year,25-year,50-year,1pct_min,100-year,1pct_plu,500-year
River Rch & RM= MDE S 048,Reach-1,2915
     489     662     804     486     970    1935    1412
Boundary for River Rch & Prof#=MDE S 048,Reach-1,1
Up Type=0
Dn Type=3
Dn Slope=0.005
Boundary for River Rch & Prof#=MDE S 048,Reach-1,2
Up Type=0
Dn Type=3
Dn Slope=0.005
Boundary for River Rch & Prof#=MDE S 048,Reach-1,3
Up Type=0
Dn Type=3
Dn Slope=0.005
Boundary for River Rch & Prof#=MDE S 048,Reach-1,4
Up Type=0
Dn Type=3
Dn Slope=0.005
Boundary for River Rch & Prof#=MDE S 048,Reach-1,5
Up Type=0
Dn Type=3
Dn Slope=0.005
Boundary for River Rch & Prof#=MDE S 048,Reach-1,6
Up Type=0
Dn Type=3
Dn Slope=0.005
Boundary for River Rch & Prof#=MDE S 048,Reach-1,7
Up Type=0
Dn Type=3
Dn Slope=0.005

--- MDE S 048.g01 (geometry) ---

Geom Title=Existing Conditions

River Reach=MDE S 048,Reach-1
Reach XY= 30
      2292679.00      7174410.00      2292662.97      7174460.22
      2292592.20      7174423.79      2292589.28      7174299.84
      2292630.25      7174263.52      2292742.72      7174246.77
      2292775.48      7174208.74      2292801.72      7174086.10
      2292988.70      7173999.24      2293070.84      7173916.05
      2293105.16      7173832.86      2293185.05      7173801.84
      2293259.23      7173730.13      2293337.14      7173553.94
      2293465.37      7173423.21      2293487.18      7173353.96
      2293573.44      7173262.36      2293581.09      7173172.02
      2293623.46      7173154.35      2293629.84      7173120.40
      2293625.09      7173061.57      2293586.60      7173009.99
      2293629.21      7172930.21      2293581.15      7172853.95
      2293580.53      7172771.88      2293673.54      7172712.66
      2293682.83      7172611.59      2293825.25      7172358.44
      2293830.91      7172215.79      2293879.00      7172160.00

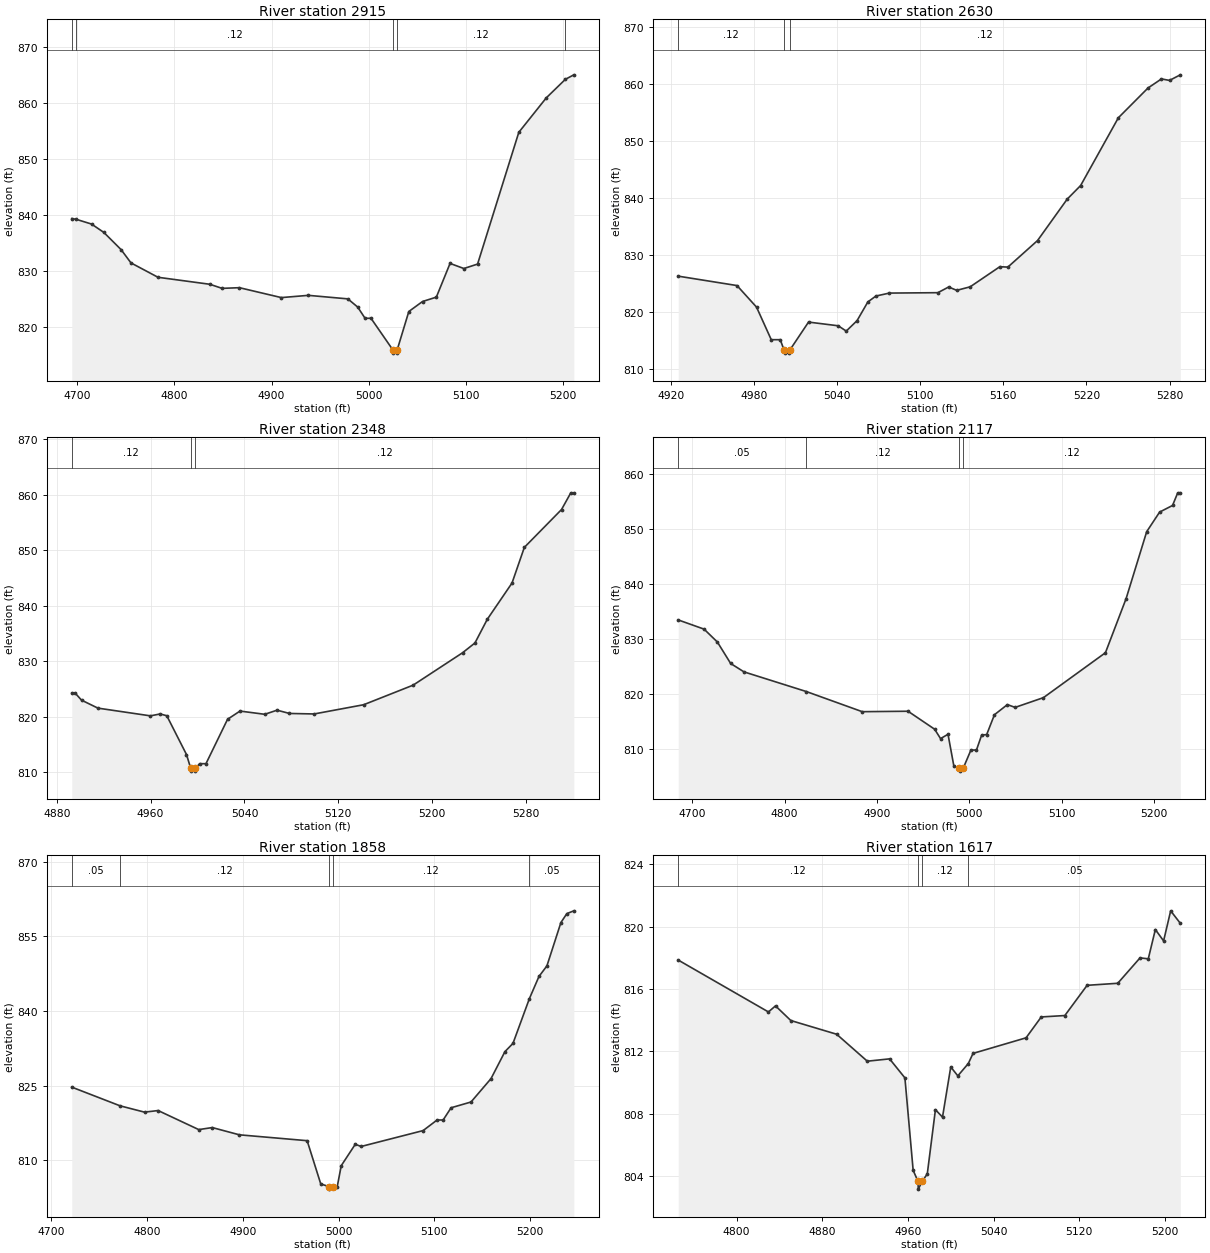
Type RM Length L Ch R = 1,2915,285,285,285
BEGIN DESCRIPTION:
MDE S 048 6.0
END DESCRIPTION:
XS GIS Cut Line= 3
      2292879.03      7174410.00      2292579.00      7174360.00
      2292429.00      7174210.00
#Sta/Elev= 30
  4694.6  839.38  4699.1  839.26  4714.9  838.41  4727.6  836.91  4745.3  833.84
  4755.5  831.46  4783.3  828.89  4836.6  827.64  4849.2  826.91  4867.0  827.03
  4910.1  825.26  4937.9  825.66  4978.5  825.03  4988.6  823.57  4996.2  821.56
  5002.3  821.56  5025.1  815.83  5025.3  815.33  5028.8  815.33  5029.1  815.83
  5041.2  822.77  5055.3  824.56  5069.5  825.34  5083.6  831.37  5097.8  830.46
  5111.9  831.25  5154.3  854.81  5182.6  860.98  5202.2  864.29  5210.9  865.09
#Mann=5,-1,0
  4694.6    0.05       0  4699.1    0.12       0  5025.1    0.07       0
  5029.1    0.12       0  5202.2    0.05       0
Bank Sta=5025.1,5029.1
Exp/Cntr=0.3,0.1

Type RM Length L Ch R = 1,2630,282,282,282
BEGIN DESCRIPTION:
MDE S 048 5.0
END DESCRIPTION:
XS GIS Cut Line= 3
      2292828.97      7174259.97      2292779.00      7174210.00
      2292529.02      7174060.01
#Sta/Elev= 30
  4925.5  826.24  4967.9  824.59  4982.0  820.80  4992.6  815.09  4999.1  815.09
  5001.9  813.23  5002.2  812.73  5005.7  812.73  5005.9  813.23  5019.5  818.18
  5040.9  817.53  5046.7  816.60  5054.5  818.43  5062.3  821.72  5068.1  822.75
  5077.8  823.27  5112.8  823.34  5120.6  824.34  5126.4  823.75  5136.1  824.37
  5157.5  827.90  5163.3  827.83  5184.7  832.49  5206.1  839.76  5215.8  842.15
  5243.0  854.04  5264.4  859.27  5274.1  860.86  5279.9  860.60  5287.7  861.58
#Mann=3,-1,0
  4925.5    0.12       0  5001.9    0.07       0  5005.9    0.12       0
Bank Sta=5001.9,5005.9
Exp/Cntr=0.3,0.1

Type RM Length L Ch R = 1,2348,231,231,231
BEGIN DESCRIPTION:
MDE S 048 4.0
END DESCRIPTION:
XS GIS Cut Line= 3
      2292978.98      7174109.97      2292929.00      7174010.00
      2292829.00      7173710.00
#Sta/Elev= 30
  4892.8  824.25  4895.6  824.25  4901.1  822.96  4915.1  821.52  4959.8  820.13
  4968.2  820.47  4973.8  820.15  4990.6  813.16  4994.2  810.67  4994.4  810.17
  4997.9  810.17  4998.2  810.67  5001.8  811.51  5007.2  811.51  5025.6  819.51
  5036.2  820.99  5057.3  820.41  5067.8  821.15  5078.4  820.56  5099.4  820.47
  5141.6  822.13  5183.8  825.66  5225.9  831.49  5236.5  833.26  5247.0  837.52
  5268.1  844.06  5278.6  850.48  5310.3  857.30  5318.2  860.31  5320.8  860.31
#Mann=3,-1,0
  4892.8    0.12       0  4994.2    0.07       0  4998.2    0.12       0
Bank Sta=4994.2,4998.2
Exp/Cntr=0.3,0.1

Type RM Length L Ch R = 1,2117,259,259,259
BEGIN DESCRIPTION:
MDE S 048 3.0
END DESCRIPTION:
XS GIS Cut Line= 3
      2293279.01      7174110.01      2293079.00      7173860.00
      2292978.99      7173659.98
#Sta/Elev= 30
  4684.8  833.46  4712.8  831.79  4727.2  829.45  4741.6  825.56  4756.0  824.04
  4823.4  820.48  4884.1  816.82  4933.7  816.90  4962.5  813.64  4968.9  811.94
  4977.0  812.72  4983.4  806.90  4989.4  806.54  4989.6  806.04  4993.4  806.54
  5001.8  809.86  5007.8  809.86  5013.4  812.56  5018.9  812.68  5027.3  816.27
  5041.3  818.10  5049.7  817.60  5080.4  819.37  5147.5  827.51  5169.9  837.33
  5192.2  849.47  5206.2  853.02  5220.2  854.22  5225.8  856.51  5228.6  856.51
#Mann=4,-1,0
  4684.8    0.05       0  4823.4    0.12       0  4989.4    0.07       0
  4993.4    0.12       0
Bank Sta=4989.4,4993.4
Exp/Cntr=0.3,0.1

Type RM Length L Ch R = 1,1858,241,241,241
BEGIN DESCRIPTION:
MDE S 048 2.0
END DESCRIPTION:
XS GIS Cut Line= 4
      2293472.68      7173903.69      2293329.00      7173760.00
      2293279.00      7173710.00      2293079.01      7173560.01
#Sta/Elev= 30
  4721.6  824.68  4772.0  820.92  4797.5  819.65  4811.7  819.97  4854.1  816.14
  4868.2  816.55  4896.5  815.09  4967.2  813.91  4981.4  805.22  4990.0  804.67
  4990.2  804.17  4994.0  804.67  4998.6  804.67  5002.8  808.89  5017.4  813.18
  5023.6  812.75  5088.2  815.94  5102.8  818.07  5109.1  818.07  5117.4  820.53
  5138.2  821.69  5159.1  826.40  5173.6  831.82  5182.0  833.48  5199.1  842.47
  5209.1  846.93  5217.4  849.06  5232.0  857.77  5238.2  859.57  5245.5  860.13
#Mann=5,-1,0
  4721.6    0.05       0  4772.0    0.12       0  4990.0    0.07       0
  4994.0    0.12       0  5199.1    0.05       0
Bank Sta=4990,4994
Exp/Cntr=0.3,0.1

Type RM Length L Ch R = 1,1617,419,419,419
BEGIN DESCRIPTION:
Mapping XS d51d7230
END DESCRIPTION:
XS GIS Cut Line= 2
      2293550.73      7173696.71      2293246.07      7173340.54
#Sta/Elev= 30
  4745.6  817.86  4829.8  814.53  4836.4  814.92  4850.7  813.98  4893.5  813.10
  4922.1  811.37  4942.9  811.52  4957.2  810.30  4964.9  804.37  4969.4  803.66
  4969.7  803.16  4973.4  803.66  4978.1  804.14  4985.7  808.26  4992.3  807.78
  5000.0  811.00  5006.6  810.43  5016.4  811.22  5020.8  811.87  5070.3  812.87
  5084.5  814.21  5106.5  814.30  5127.3  816.24  5155.9  816.37  5176.7  818.00
  5184.4  817.94  5191.0  819.82  5198.7  819.09  5205.3  821.02  5214.3  820.22
#Mann=4,-1,0
  4745.6    0.12       0  4969.4    0.07       0  4973.4    0.12       0
  5016.4    0.05       0
Bank Sta=4969.4,4973.4
Exp/Cntr=0.3,0.1

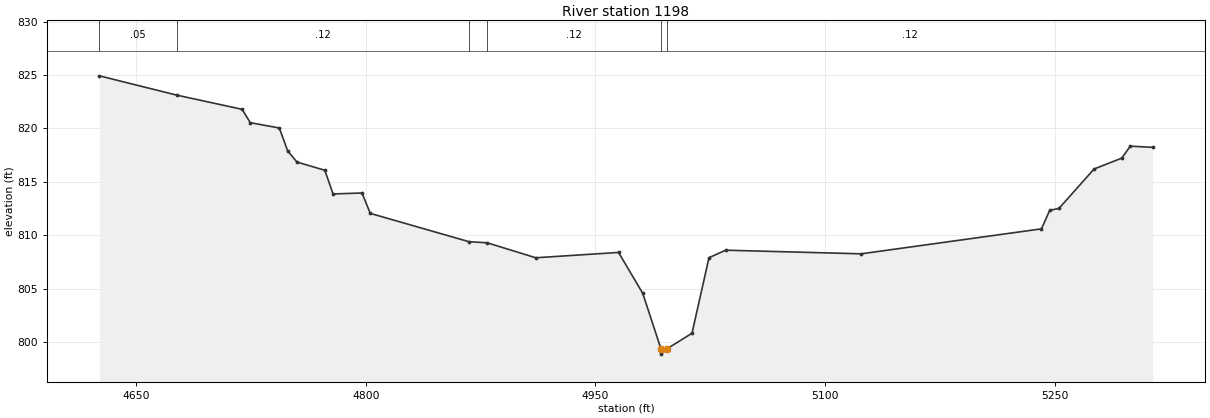
Type RM Length L Ch R = 1,1198,0,0,0
BEGIN DESCRIPTION:
MDE S 048 1.0
END DESCRIPTION:
XS GIS Cut Line= 3
      2293729.01      7173510.02      2293591.25      7173162.21
      2293302.64      7173038.27
#Sta/Elev= 30
  4625.9  824.93  4676.5  823.12  4719.2  821.79  4724.5  820.54  4743.5  820.04
  4748.9  817.91  4755.0  816.85  4773.2  816.08  4778.6  813.86  4797.5  813.95
  4802.9  812.04  4867.3  809.39  4879.4  809.28  4911.0  807.88  4965.1  808.38
  4980.9  804.55  4992.8  799.35  4993.0  798.85  4996.8  799.35  5013.1  800.81
  5024.2  807.89  5035.1  808.59  5123.6  808.25  5241.4  810.59  5246.8  812.33
  5252.8  812.50  5275.8  816.20  5293.9  817.22  5299.4  818.34  5314.1  818.23
#Mann=6,-1,0
  4625.9    0.05       0  4676.5    0.12       0  4867.3    0.05       0
  4879.4    0.12       0  4992.8    0.07       0  4996.8    0.12       0
Bank Sta=4992.8,4996.8
Exp/Cntr=0.3,0.1

Chan Stop Cuts=-1