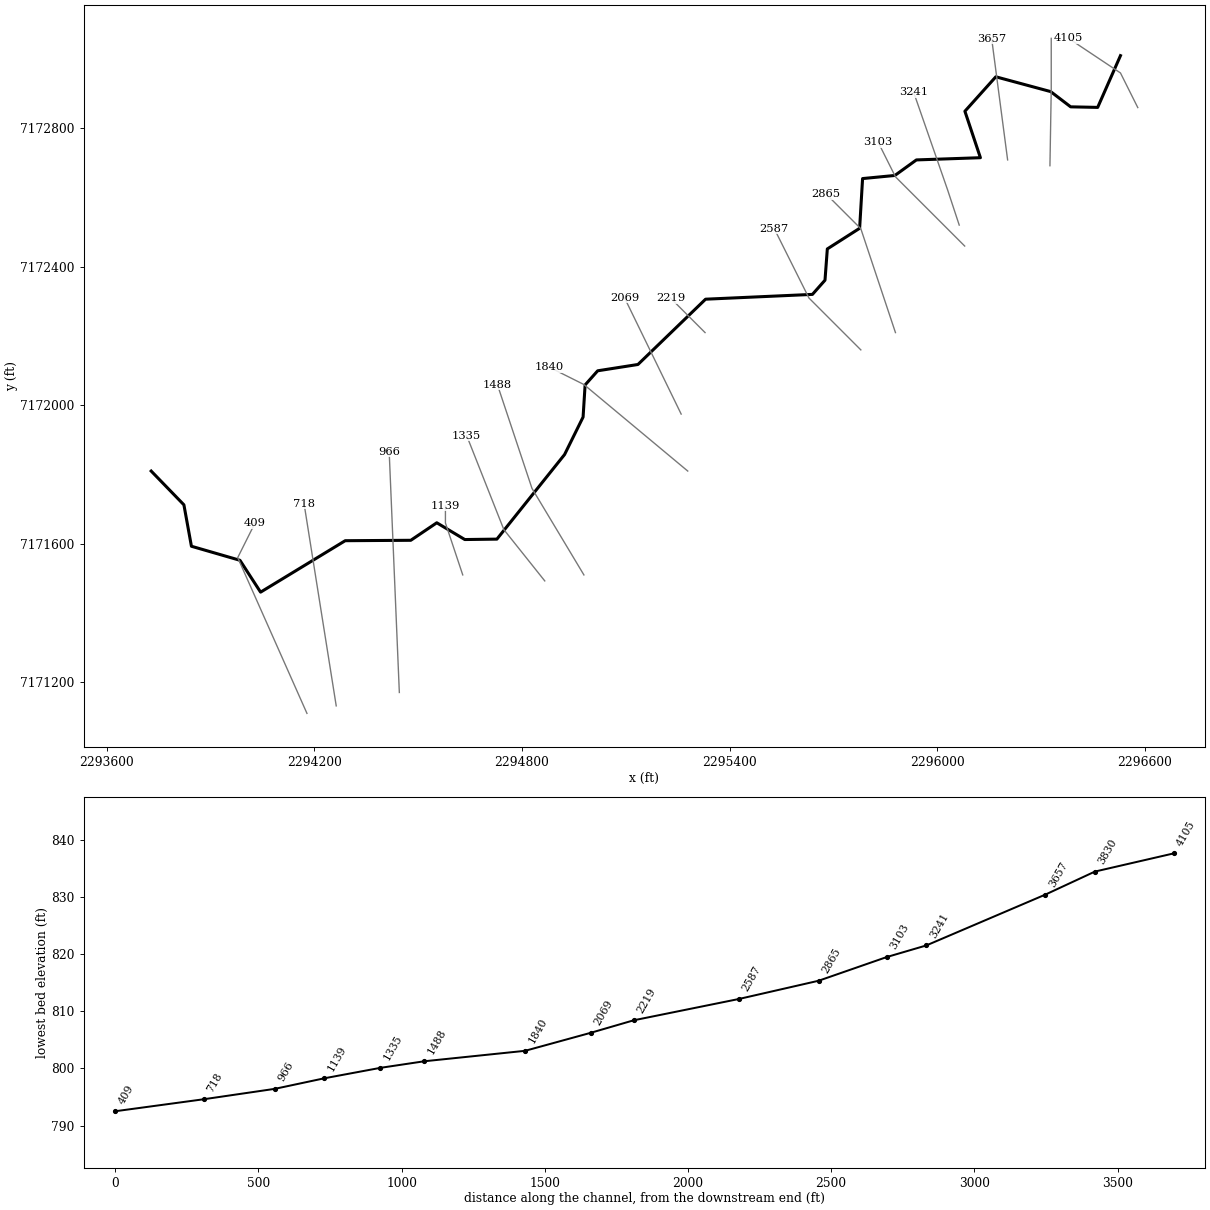
--- MDE S 049.prj (project) ---

Proj Title=MDE S 049 Base Level Engineering
Current Plan=p01
Default Exp/Contr=0.3,0.1
English Units
Geom File=g01
Flow File=f01
Plan File=p01
BEGIN DESCRIPTION:
MDE S 049
END DESCRIPTION:

--- MDE S 049.p01 (plan) ---

Plan Title=Multiple Run
Short Identifier=Multiple
Geom File=g01
Flow File=f01
Subcritical Flow
K Sum by GR= 0
Std Step Tol= 0.01
Critical Tol= 0.01
Num of Std Step Trials= 20
Max Error Tol= 0.3
Flow Tol Ratio= 0.001
Split Flow NTrial= 30
Split Flow Tol= 0.02
Split Flow Ratio= 0.02
Log Output Level= 0
Friction Slope Method= 1
Unsteady Friction Slope Method= 2
Unsteady Bridges Friction Slope Method= 1
Parabolic Critical Depth
Global Vel Dist=  1 , 1 , 1
Global Log Level= 0
CheckData=True
Encroach Param= -1, 0, 0, 0
BEGIN DESCRIPTION:
Multiple Run
END DESCRIPTION:

--- MDE S 049.f01 (steady flow) ---

Flow Title=Multiple
Number of Profiles=7
Profile Names=10-year,25-year,50-year,1pct_min,100-year,1pct_plu,500-year
River Rch & RM= MDE S 049,Reach-1,4105
     548     750     919     560    1118    2231    1655
River Rch & RM= MDE S 049,Reach-1,966
     684     950    1173     721    1438    2869    2162
Boundary for River Rch & Prof#=MDE S 049,Reach-1,1
Up Type=0
Dn Type=3
Dn Slope=0.005
Boundary for River Rch & Prof#=MDE S 049,Reach-1,2
Up Type=0
Dn Type=3
Dn Slope=0.005
Boundary for River Rch & Prof#=MDE S 049,Reach-1,3
Up Type=0
Dn Type=3
Dn Slope=0.005
Boundary for River Rch & Prof#=MDE S 049,Reach-1,4
Up Type=0
Dn Type=3
Dn Slope=0.005
Boundary for River Rch & Prof#=MDE S 049,Reach-1,5
Up Type=0
Dn Type=3
Dn Slope=0.005
Boundary for River Rch & Prof#=MDE S 049,Reach-1,6
Up Type=0
Dn Type=3
Dn Slope=0.005
Boundary for River Rch & Prof#=MDE S 049,Reach-1,7
Up Type=0
Dn Type=3
Dn Slope=0.005

--- MDE S 049.g01 (geometry) ---

Geom Title=Existing Conditions

River Reach=MDE S 049,Reach-1
Reach XY= 30
      2296529.00      7173010.00      2296463.13      7172860.50
      2296385.06      7172862.13      2296327.41      7172906.14
      2296168.91      7172948.91      2296079.60      7172849.39
      2296124.41      7172715.17      2295939.50      7172708.78
      2295877.32      7172663.89      2295784.04      7172654.92
      2295775.51      7172511.28      2295682.19      7172451.64
      2295675.46      7172361.32      2295639.17      7172320.33
      2295330.46      7172306.46      2295135.17      7172117.86
      2295018.84      7172099.64      2294982.51      7172058.75
      2294976.66      7171965.97      2294923.17      7171857.70
      2294727.72      7171613.37      2294634.97      7171612.17
      2294554.05      7171660.61      2294479.00      7171610.00
      2294289.49      7171608.81      2294045.04      7171460.19
      2293985.43      7171552.20      2293845.27      7171592.79
      2293823.54      7171712.45      2293729.00      7171810.00

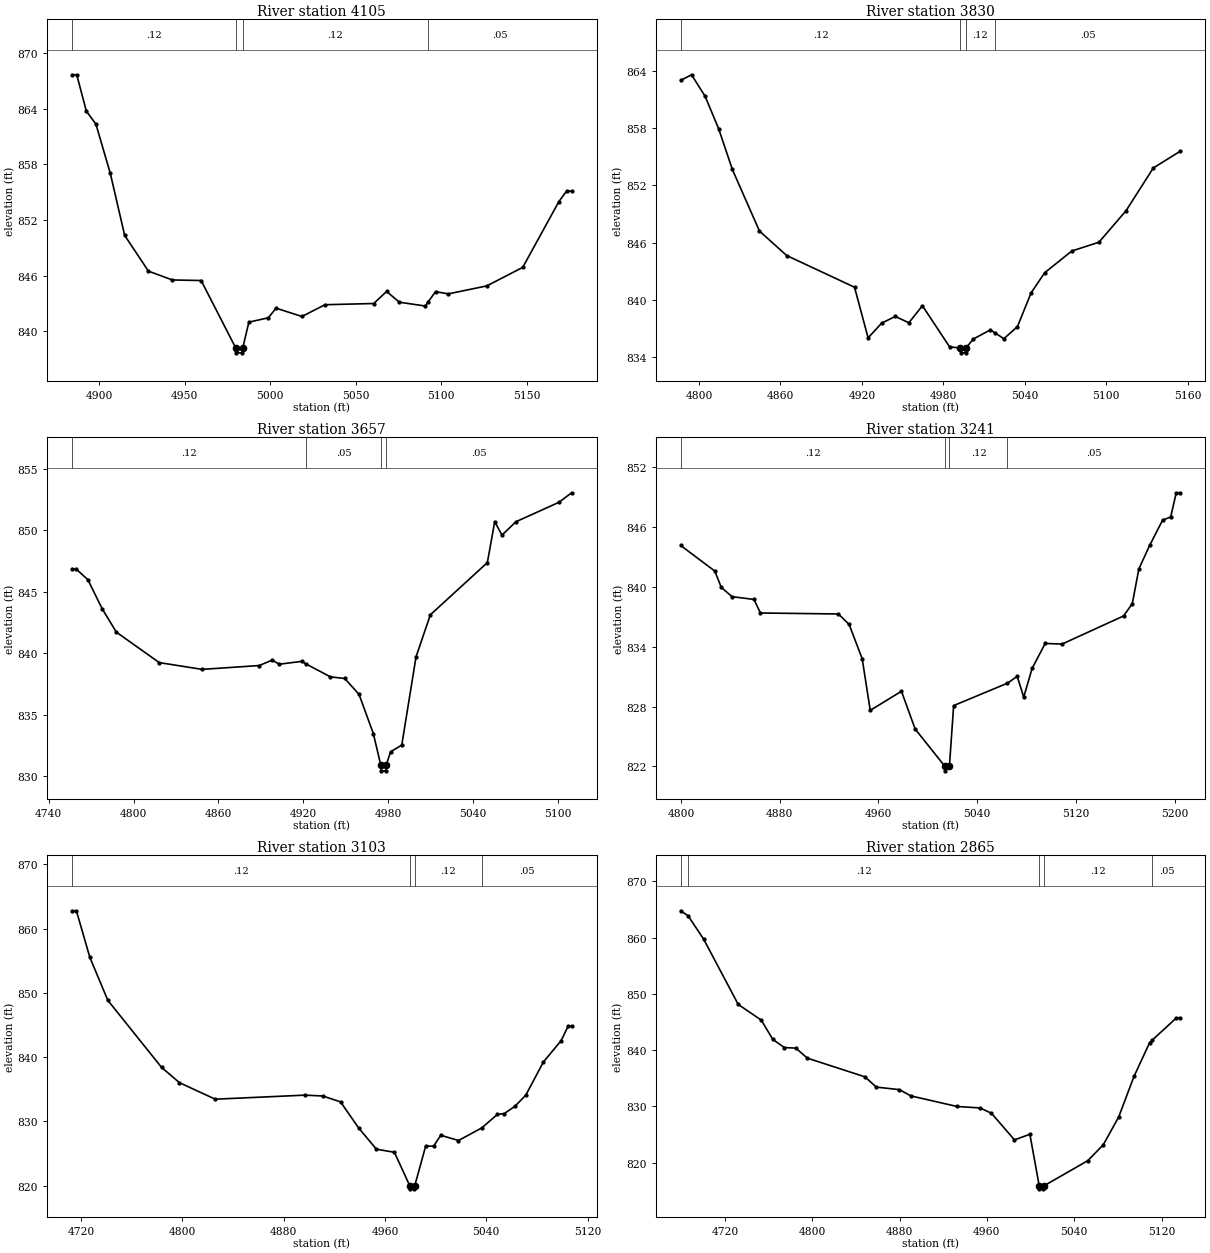
Type RM Length L Ch R = 1,4105,275,275,275
BEGIN DESCRIPTION:
MDE S 049 13.0
END DESCRIPTION:
XS GIS Cut Line= 3
      2296579.01      7172859.99      2296529.00      7172960.00
      2296378.99      7173060.00
#Sta/Elev= 30
  4884.2  867.65  4887.0  867.65  4892.6  863.73  4898.2  862.33  4906.6  857.02
  4915.0  850.33  4928.9  846.47  4942.9  845.52  4959.7  845.46  4980.0  838.16
  4980.3  837.66  4983.8  837.66  4984.0  838.16  4987.6  840.97  4999.0  841.44
  5003.5  842.48  5018.6  841.58  5032.1  842.85  5060.6  842.98  5068.1  844.28
  5075.6  843.12  5090.7  842.71  5092.4  843.15  5096.7  844.26  5104.2  844.02
  5126.7  844.88  5147.7  846.88  5168.8  853.97  5173.3  855.10  5176.3  855.10
#Mann=4,-1,0
  4884.2    0.12       0  4980.0    0.07       0  4984.0    0.12       0
  5092.4    0.05       0
Bank Sta=4980,4984
Exp/Cntr=0.3,0.1

Type RM Length L Ch R = 1,3830,173,173,173
BEGIN DESCRIPTION:
MDE S 049 12.0
END DESCRIPTION:
XS GIS Cut Line= 3
      2296325.26      7172692.02      2296329.00      7172910.00
      2296329.00      7173059.98
#Sta/Elev= 30
  4786.6  863.01  4794.6  863.59  4804.6  861.33  4814.6  857.92  4824.6  853.69
  4844.6  847.23  4864.6  844.67  4914.6  841.35  4924.6  836.05  4934.6  837.59
  4944.6  838.29  4954.6  837.63  4964.6  839.41  4984.6  835.11  4992.6  834.98
  4992.9  834.48  4996.4  834.48  4996.6  834.98  5002.1  835.93  5014.6  836.88
  5017.8  836.59  5024.6  835.96  5034.6  837.23  5044.6  840.75  5054.6  842.86
  5074.6  845.14  5094.6  846.06  5114.6  849.37  5134.6  853.83  5154.6  855.60
#Mann=4,-1,0
  4786.6    0.12       0  4992.6    0.07       0  4996.6    0.12       0
  5017.8    0.05       0
Bank Sta=4992.6,4996.6
Exp/Cntr=0.3,0.1

Type RM Length L Ch R = 1,3657,416,416,416
BEGIN DESCRIPTION:
Mapping XS 7ed33818
END DESCRIPTION:
XS GIS Cut Line= 2
      2296203.01      7172708.87      2296156.92      7173059.05
#Sta/Elev= 30
  4756.5  846.82  4759.6  846.82  4767.7  845.98  4777.8  843.62  4787.9  841.71
  4818.2  839.24  4848.4  838.69  4888.8  839.00  4898.0  839.44  4903.0  839.11
  4919.0  839.34  4922.1  839.12  4939.2  838.08  4949.3  837.95  4959.4  836.66
  4969.5  833.48  4974.7  830.95  4974.9  830.45  4978.4  830.45  4978.7  830.95
  4981.7  832.00  4989.6  832.54  4999.7  839.71  5009.8  843.12  5050.1  847.36
  5055.3  850.69  5060.4  849.59  5070.3  850.68  5100.6  852.25  5109.7  853.03
#Mann=4,-1,0
  4756.5    0.12       0  4922.1    0.05       0  4974.7   0.033       0
  4978.7    0.05       0
Bank Sta=4974.7,4978.7
Exp/Cntr=0.3,0.1

Type RM Length L Ch R = 1,3241,138,138,138
BEGIN DESCRIPTION:
Mapping XS 58aa9aca
END DESCRIPTION:
XS GIS Cut Line= 3
      2296063.22      7172520.49      2296029.48      7172622.72
      2295931.77      7172903.56
#Sta/Elev= 30
  4799.7  844.17  4827.3  841.60  4832.6  839.96  4841.3  839.03  4859.1  838.75
  4864.3  837.39  4927.5  837.29  4936.2  836.24  4946.8  832.79  4953.3  827.61
  4978.6  829.53  4989.7  825.74  5013.5  822.04  5013.7  821.54  5017.5  822.04
  5020.9  828.09  5064.5  830.34  5072.4  831.03  5077.7  828.94  5084.5  831.83
  5095.1  834.33  5108.8  834.27  5158.6  837.09  5165.7  838.33  5171.0  841.81
  5179.8  844.19  5190.3  846.72  5196.8  847.03  5201.3  849.46  5204.7  849.46
#Mann=4,-1,0
  4799.7    0.12       0  5013.5    0.07       0  5017.5    0.12       0
  5064.5    0.05       0
Bank Sta=5013.5,5017.5
Exp/Cntr=0.3,0.1

Type RM Length L Ch R = 1,3103,238,238,238
BEGIN DESCRIPTION:
MDE S 049 9.0
END DESCRIPTION:
XS GIS Cut Line= 3
      2296078.99      7172460.01      2295879.00      7172660.00
      2295829.02      7172759.97
#Sta/Elev= 30
  4712.9  862.78  4716.4  862.78  4727.0  855.54  4741.2  848.85  4783.6  838.42
  4797.7  836.04  4826.0  833.46  4896.7  834.09  4910.9  833.96  4925.0  833.04
  4939.2  829.00  4953.3  825.68  4967.5  825.20  4979.6  820.01  4979.8  819.51
  4983.3  819.51  4983.6  820.01  4992.2  826.16  4998.5  826.16  5004.1  827.85
  5018.1  827.03  5036.4  828.98  5048.8  831.08  5054.4  831.23  5062.8  832.38
  5071.2  834.07  5085.2  839.26  5099.2  842.58  5104.7  844.83  5107.5  844.83
#Mann=4,-1,0
  4712.9    0.12       0  4979.6    0.07       0  4983.6    0.12       0
  5036.4    0.05       0
Bank Sta=4979.6,4983.6
Exp/Cntr=0.3,0.1

Type RM Length L Ch R = 1,2865,278,278,278
BEGIN DESCRIPTION:
MDE S 049 8.0
END DESCRIPTION:
XS GIS Cut Line= 3
      2295879.01      7172209.98      2295779.00      7172510.00
      2295678.98      7172610.02
#Sta/Elev= 30
  4679.6  864.78  4686.4  863.88  4700.7  859.71  4732.3  848.13  4753.4  845.35
  4763.9  841.93  4774.5  840.47  4785.0  840.37  4795.6  838.59  4848.3  835.27
  4858.8  833.44  4879.9  832.99  4890.4  831.88  4932.6  830.00  4953.7  829.74
  4964.2  828.80  4985.3  824.06  4999.4  825.06  5008.0  815.86  5008.2  815.36
  5011.7  815.36  5012.0  815.86  5052.4  820.36  5066.6  823.18  5080.7  828.11
  5094.8  835.35  5109.0  841.30  5111.6  841.81  5133.7  845.76  5137.3  845.76
#Mann=5,-1,0
  4679.6    0.05       0  4686.4    0.12       0  5008.0    0.07       0
  5012.0    0.12       0  5111.6    0.05       0
Bank Sta=5008,5012
Exp/Cntr=0.3,0.1

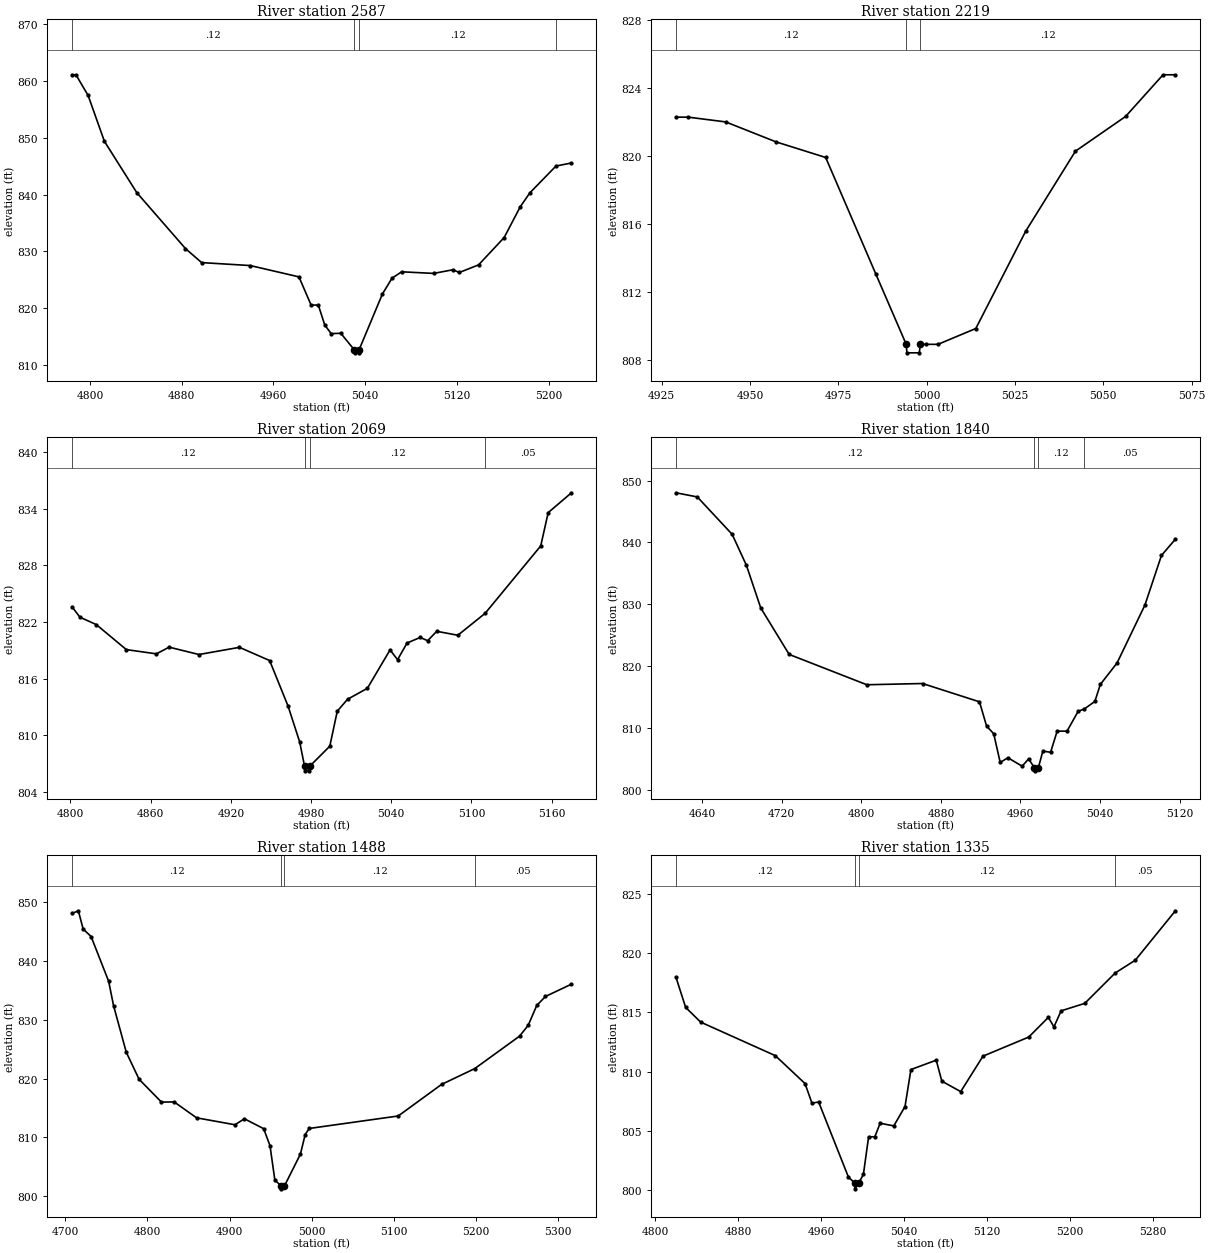
Type RM Length L Ch R = 1,2587,368,368,368
BEGIN DESCRIPTION:
MDE S 049 7.0
END DESCRIPTION:
XS GIS Cut Line= 3
      2295778.99      7172160.01      2295629.00      7172310.00
      2295529.01      7172509.98
#Sta/Elev= 30
  4784.2  861.07  4787.7  861.07  4798.3  857.43  4812.5  849.37  4840.8  840.33
  4883.2  830.51  4897.3  828.04  4939.7  827.52  4982.2  825.53  4992.8  820.57
  4999.1  820.57  5004.7  817.07  5010.3  815.55  5018.7  815.61  5030.6  812.67
  5030.9  812.17  5034.4  812.17  5034.6  812.67  5055.0  822.52  5063.4  825.30
  5071.8  826.42  5099.7  826.14  5116.5  826.78  5122.1  826.30  5138.9  827.64
  5161.2  832.45  5175.2  837.84  5183.6  840.30  5206.4  845.02  5219.9  845.56
#Mann=4,-1,0
  4784.2    0.12       0  5030.6    0.07       0  5034.6    0.12       0
  5206.4    0.05       0
Bank Sta=5030.6,5034.6
Exp/Cntr=0.3,0.1

Type RM Length L Ch R = 1,2219,150,150,150
BEGIN DESCRIPTION:
MDE S 049 6.0
END DESCRIPTION:
XS GIS Cut Line= 3
      2295329.00      7172210.00      2295279.00      7172260.00
      2295229.02      7172309.98
#Sta/Elev= 18
  4929.0  822.28  4932.5  822.28  4943.1  822.00  4957.3  820.83  4971.4  819.91
  4985.6  813.06  4994.2  808.93  4994.4  808.43  4997.9  808.43  4998.2  808.93
  4999.7  808.93  5003.2  808.93  5013.9  809.86  5028.0  815.57  5042.1  820.28
  5056.3  822.32  5066.9  824.77  5070.4  824.77
#Mann=3,-1,0
  4929.0    0.12       0  4994.2    0.07       0  4998.2    0.12       0
Bank Sta=4994.2,4998.2
Exp/Cntr=0.3,0.1

Type RM Length L Ch R = 1,2069,229,229,229
BEGIN DESCRIPTION:
Mapping XS 082f8d91
END DESCRIPTION:
XS GIS Cut Line= 2
      2295259.98      7171974.62      2295096.34      7172310.59
#Sta/Elev= 30
  4801.1  823.62  4807.1  822.51  4819.3  821.73  4841.8  819.08  4864.3  818.63
  4873.8  819.34  4896.1  818.56  4926.4  819.32  4949.0  817.92  4962.8  813.09
  4971.5  809.29  4975.1  806.74  4975.3  806.24  4978.8  806.24  4979.1  806.74
  4994.0  808.85  4999.6  812.56  5007.3  813.82  5022.1  814.98  5039.1  819.05
  5044.7  818.01  5051.8  819.78  5061.7  820.37  5067.2  820.02  5074.0  821.02
  5089.8  820.60  5110.2  822.92  5151.8  830.06  5157.4  833.59  5174.8  835.69
#Mann=4,-1,0
  4801.1    0.12       0  4975.1    0.07       0  4979.1    0.12       0
  5110.2    0.05       0
Bank Sta=4975.1,4979.1
Exp/Cntr=0.3,0.1

Type RM Length L Ch R = 1,1840,352,352,352
BEGIN DESCRIPTION:
MDE S 049 5.0
END DESCRIPTION:
XS GIS Cut Line= 3
      2295279.00      7171810.00      2294979.00      7172060.00
      2294879.01      7172109.99
#Sta/Elev= 30
  4613.5  848.02  4635.0  847.35  4670.1  841.30  4684.4  836.30  4698.8  829.42
  4727.4  821.90  4805.5  817.00  4861.5  817.20  4918.8  814.24  4925.9  810.33
  4933.1  809.08  4939.6  804.45  4947.4  805.20  4961.7  803.84  4968.2  805.02
  4974.0  803.59  4974.3  803.09  4978.0  803.59  4982.5  806.28  4990.3  806.09
  4996.9  809.51  5006.8  809.50  5018.0  812.70  5024.3  813.10  5034.8  814.30
  5040.3  817.05  5057.1  820.51  5085.1  829.86  5101.8  837.90  5115.8  840.52
#Mann=4,-1,0
  4613.5    0.12       0  4974.0    0.07       0  4978.0    0.12       0
  5024.3    0.05       0
Bank Sta=4974,4978
Exp/Cntr=0.3,0.1

Type RM Length L Ch R = 1,1488,153,153,153
BEGIN DESCRIPTION:
MDE S 049 4.0
END DESCRIPTION:
XS GIS Cut Line= 3
      2294979.01      7171509.98      2294829.00      7171760.00
      2294729.00      7172060.00
#Sta/Elev= 30
  4708.2  848.05  4716.0  848.51  4721.8  845.41  4731.5  844.13  4752.9  836.51
  4758.8  832.40  4774.3  824.47  4789.9  819.88  4817.1  816.00  4832.6  816.03
  4859.8  813.33  4906.5  812.15  4918.1  813.16  4941.5  811.48  4949.2  808.57
  4955.1  802.74  4962.8  801.76  4963.0  801.26  4966.8  801.76  4986.2  807.16
  4992.0  810.49  4996.9  811.52  5105.2  813.64  5157.9  819.00  5198.3  821.69
  5252.8  827.20  5263.3  829.03  5273.8  832.43  5284.4  833.95  5316.0  836.04
#Mann=4,-1,0
  4708.2    0.12       0  4962.8    0.07       0  4966.8    0.12       0
  5198.3    0.05       0
Bank Sta=4962.8,4966.8
Exp/Cntr=0.3,0.1

Type RM Length L Ch R = 1,1335,196,196,196
BEGIN DESCRIPTION:
Mapping XS 9cd3a567
END DESCRIPTION:
XS GIS Cut Line= 3
      2294865.95      7171492.67      2294747.78      7171640.85
      2294640.38      7171912.46
#Sta/Elev= 30
  4819.9  817.97  4829.3  815.41  4843.8  814.17  4915.8  811.34  4944.4  808.99
  4951.1  807.33  4957.5  807.44  4986.3  801.09  4992.3  800.61  4992.6  800.11
  4996.3  800.61  5000.7  801.34  5005.7  804.50  5011.7  804.50  5016.8  805.64
  5030.0  805.42  5040.8  807.05  5046.5  810.17  5070.9  810.96  5076.3  809.19
  5094.5  808.31  5116.0  811.30  5160.1  812.91  5179.0  814.57  5184.4  813.77
  5191.3  815.12  5214.1  815.75  5243.4  818.31  5262.8  819.39  5301.5  823.56
#Mann=4,-1,0
  4819.9    0.12       0  4992.3    0.07       0  4996.3    0.12       0
  5243.4    0.05       0
Bank Sta=4992.3,4996.3
Exp/Cntr=0.3,0.1

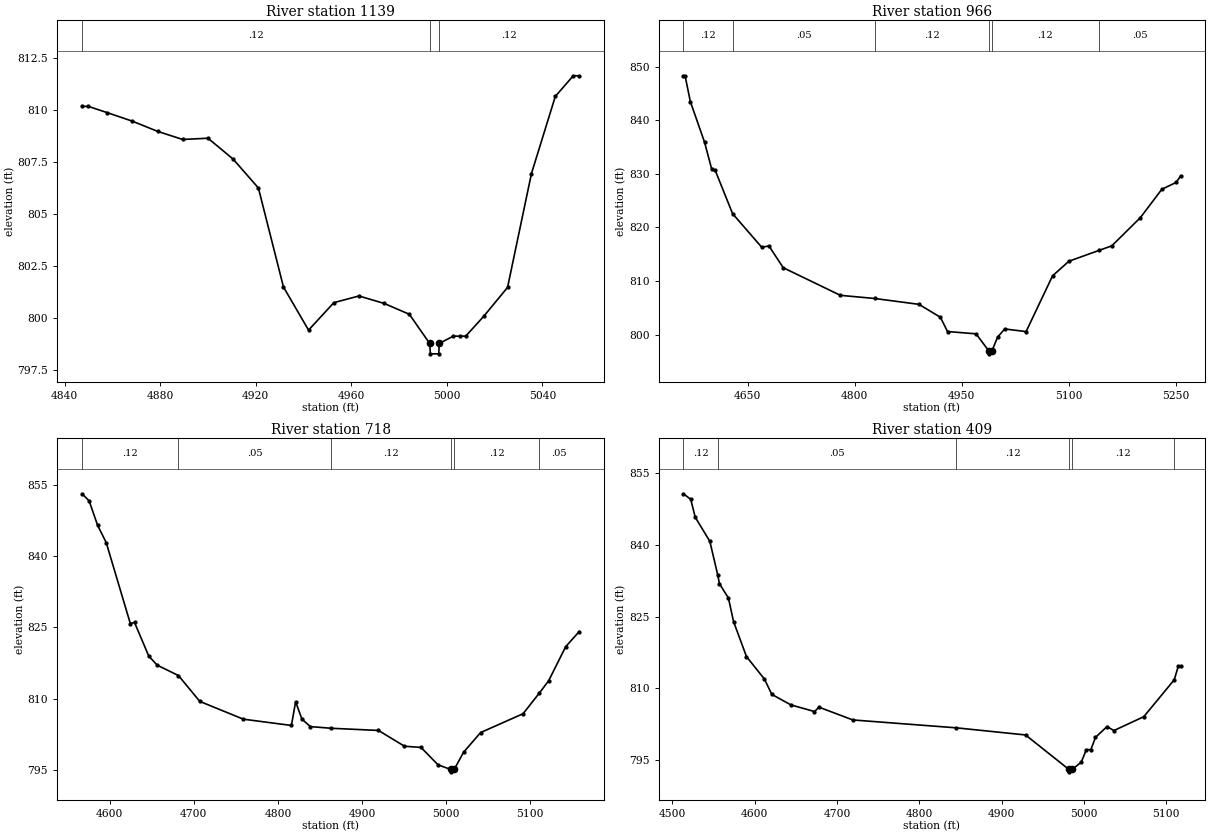
Type RM Length L Ch R = 1,1139,173,173,173
BEGIN DESCRIPTION:
MDE S 049 3.0
END DESCRIPTION:
XS GIS Cut Line= 3
      2294628.99      7171510.03      2294579.00      7171660.00
      2294579.00      7171710.02
#Sta/Elev= 28
  4847.3  810.17  4849.9  810.17  4857.8  809.87  4868.3  809.46  4878.9  808.97
  4889.4  808.58  4900.0  808.64  4910.5  807.64  4921.1  806.25  4931.6  801.49
  4942.1  799.42  4952.7  800.74  4963.2  801.06  4973.8  800.70  4984.3  800.18
  4992.8  798.78  4993.1  798.28  4996.6  798.28  4996.8  798.78  5002.7  799.13
  5005.4  799.13  5007.9  799.13  5015.4  800.08  5025.4  801.47  5035.4  806.94
  5045.4  810.65  5052.9  811.64  5055.4  811.64
#Mann=3,-1,0
  4847.3    0.12       0  4992.8    0.07       0  4996.8    0.12       0
Bank Sta=4992.8,4996.8
Exp/Cntr=0.3,0.1

Type RM Length L Ch R = 1,966,248,248,248
BEGIN DESCRIPTION:
Mapping XS 217b1606
END DESCRIPTION:
XS GIS Cut Line= 2
      2294445.87      7171170.33      2294416.53      7171866.21
#Sta/Elev= 30
  4559.9  848.28  4562.2  848.28  4569.6  843.47  4589.6  835.85  4599.5  830.87
  4604.5  830.62  4628.8  822.56  4669.7  816.29  4679.7  816.56  4699.7  812.49
  4779.8  807.34  4827.9  806.75  4889.9  805.66  4919.9  803.25  4929.9  800.59
  4969.9  800.16  4988.0  796.93  4988.2  796.43  4992.0  796.93  5000.0  799.53
  5010.0  801.07  5040.0  800.58  5077.1  810.98  5100.0  813.70  5142.0  815.71
  5160.1  816.57  5200.1  821.83  5230.2  827.12  5250.2  828.39  5256.4  829.58
#Mann=6,-1,0
  4559.9    0.12       0  4628.8    0.05       0  4827.9    0.12       0
  4988.0    0.07       0  4992.0    0.12       0  5142.0    0.05       0
Bank Sta=4988,4992
Exp/Cntr=0.3,0.1

Type RM Length L Ch R = 1,718,309,309,309
BEGIN DESCRIPTION:
Mapping XS 939903a3
END DESCRIPTION:
XS GIS Cut Line= 2
      2294263.54      7171131.68      2294170.62      7171715.94
#Sta/Elev= 30
  4567.0  853.12  4575.4  851.62  4585.5  846.47  4595.7  842.86  4624.4  825.81
  4629.4  826.05  4646.3  818.98  4656.4  817.06  4681.7  814.87  4707.1  809.43
  4758.9  805.69  4816.1  804.37  4821.1  809.36  4828.6  805.71  4838.7  804.13
  4863.2  803.78  4919.7  803.32  4950.6  800.00  4970.3  799.75  4990.6  796.08
  5005.8  795.11  5006.0  794.61  5009.8  795.11  5021.0  798.73  5041.2  802.87
  5091.8  806.84  5111.2  811.20  5122.2  813.77  5142.5  820.95  5158.6  824.13
#Mann=6,-1,0
  4567.0    0.12       0  4681.7    0.05       0  4863.2    0.12       0
  5005.8    0.07       0  5009.8    0.12       0  5111.2    0.05       0
Bank Sta=5005.8,5009.8
Exp/Cntr=0.3,0.1

Type RM Length L Ch R = 1,409,0,0,0
BEGIN DESCRIPTION:
MDE S 049 1.0
END DESCRIPTION:
XS GIS Cut Line= 3
      2294178.99      7171110.01      2293979.00      7171560.00
      2294028.99      7171659.97
#Sta/Elev= 30
  4513.4  850.70  4522.3  849.53  4527.7  845.81  4545.5  840.75  4555.0  833.78
  4557.2  831.87  4568.1  828.88  4574.3  823.97  4590.0  816.64  4611.9  811.91
  4620.8  808.72  4644.0  806.52  4672.7  805.13  4678.2  806.04  4719.3  803.37
  4845.0  801.72  4929.2  800.23  4981.9  793.01  4982.2  792.51  4985.9  793.01
  4996.9  794.54  5003.1  797.15  5008.6  797.15  5014.2  799.72  5028.2  801.98
  5036.6  801.15  5072.9  804.05  5109.9  811.77  5114.8  814.58  5117.6  814.58
#Mann=6,-1,0
  4513.4    0.12       0  4555.0    0.05       0  4845.0    0.12       0
  4981.9    0.07       0  4985.9    0.12       0  5109.9    0.05       0
Bank Sta=4981.9,4985.9
Exp/Cntr=0.3,0.1

Chan Stop Cuts=-1