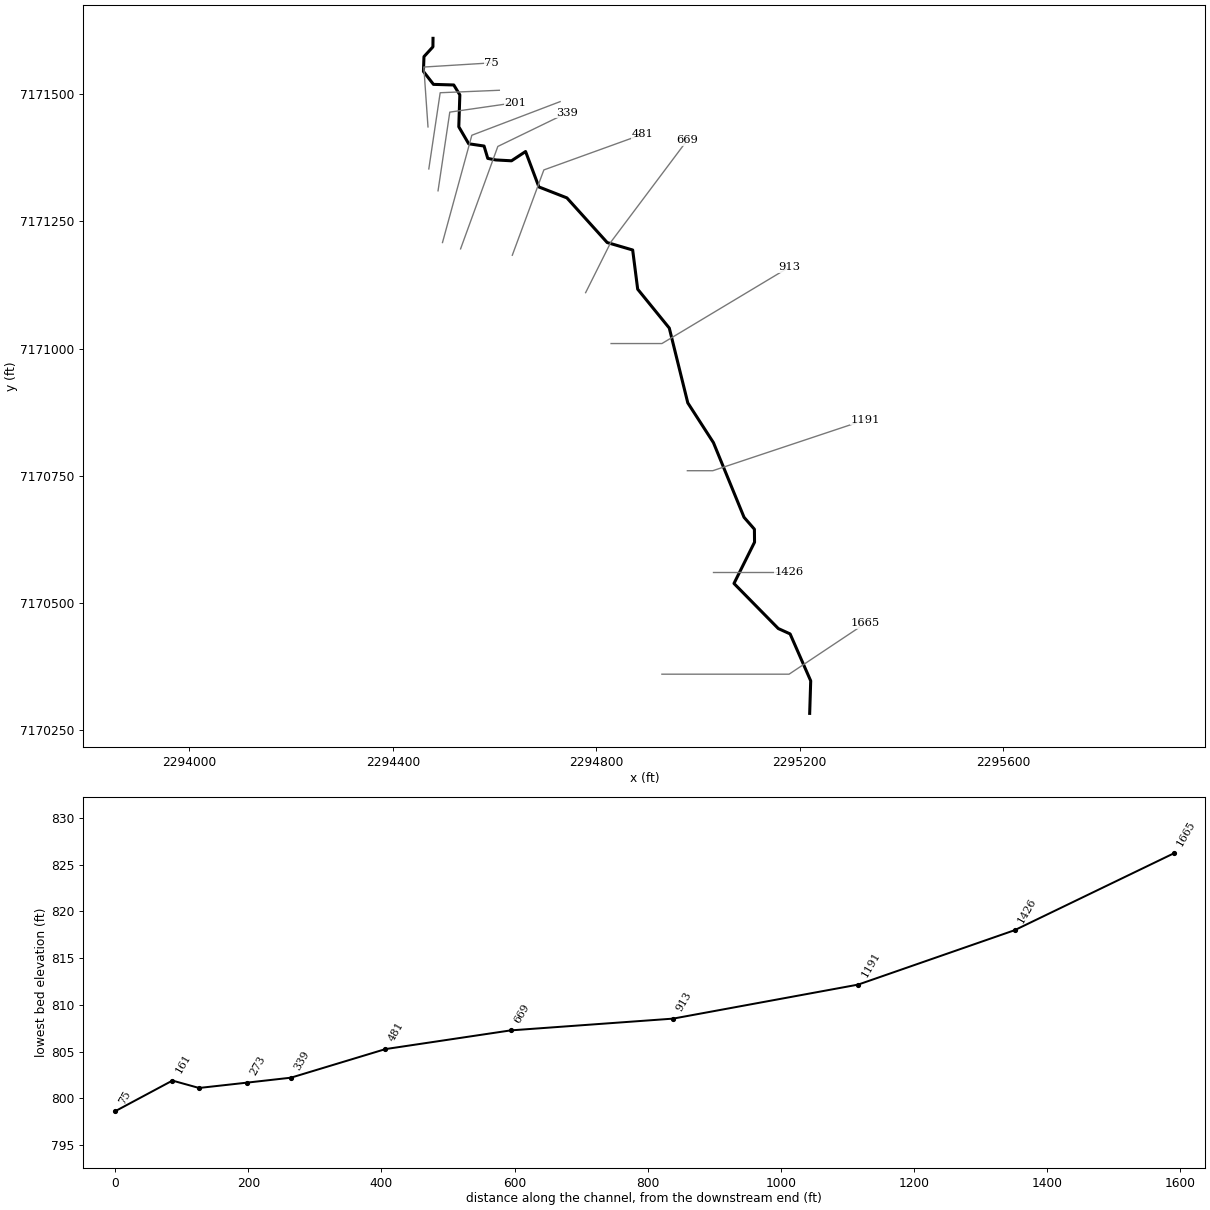
--- MDE S 050.prj (project) ---

Proj Title=MDE S 050 Base Level Engineering
Current Plan=p01
Default Exp/Contr=0.3,0.1
English Units
Geom File=g01
Flow File=f01
Plan File=p01
BEGIN DESCRIPTION:
MDE S 050
END DESCRIPTION:

--- MDE S 050.p01 (plan) ---

Plan Title=Multiple Run
Short Identifier=Multiple
Geom File=g01
Flow File=f01
Subcritical Flow
K Sum by GR= 0
Std Step Tol= 0.01
Critical Tol= 0.01
Num of Std Step Trials= 20
Max Error Tol= 0.3
Flow Tol Ratio= 0.001
Split Flow NTrial= 30
Split Flow Tol= 0.02
Split Flow Ratio= 0.02
Log Output Level= 0
Friction Slope Method= 1
Unsteady Friction Slope Method= 2
Unsteady Bridges Friction Slope Method= 1
Parabolic Critical Depth
Global Vel Dist=  1 , 1 , 1
Global Log Level= 0
CheckData=True
Encroach Param= -1, 0, 0, 0
BEGIN DESCRIPTION:
Multiple Run
END DESCRIPTION:

--- MDE S 050.f01 (steady flow) ---

Flow Title=Multiple
Number of Profiles=7
Profile Names=10-year,25-year,50-year,1pct_min,100-year,1pct_plu,500-year
River Rch & RM= MDE S 050,Reach-1,1665
     264     346     410     243     486     969     678
Boundary for River Rch & Prof#=MDE S 050,Reach-1,1
Up Type=0
Dn Type=3
Dn Slope=0.005
Boundary for River Rch & Prof#=MDE S 050,Reach-1,2
Up Type=0
Dn Type=3
Dn Slope=0.005
Boundary for River Rch & Prof#=MDE S 050,Reach-1,3
Up Type=0
Dn Type=3
Dn Slope=0.005
Boundary for River Rch & Prof#=MDE S 050,Reach-1,4
Up Type=0
Dn Type=3
Dn Slope=0.005
Boundary for River Rch & Prof#=MDE S 050,Reach-1,5
Up Type=0
Dn Type=3
Dn Slope=0.005
Boundary for River Rch & Prof#=MDE S 050,Reach-1,6
Up Type=0
Dn Type=3
Dn Slope=0.005
Boundary for River Rch & Prof#=MDE S 050,Reach-1,7
Up Type=0
Dn Type=3
Dn Slope=0.005

--- MDE S 050.g01 (geometry) ---

Geom Title=Existing Conditions

River Reach=MDE S 050,Reach-1
Reach XY= 30
      2295219.47      7170282.95      2295221.50      7170346.89
      2295180.99      7170439.17      2295157.74      7170449.72
      2295070.66      7170538.32      2295111.08      7170619.43
      2295110.82      7170645.00      2295090.46      7170668.36
      2295030.28      7170815.17      2294979.85      7170893.36
      2294943.48      7171040.41      2294881.34      7171116.88
      2294871.50      7171193.89      2294821.39      7171208.56
      2294742.20      7171296.34      2294687.14      7171317.86
      2294660.95      7171387.50      2294633.30      7171369.25
      2294602.43      7171370.93      2294586.64      7171373.96
      2294579.35      7171398.26      2294549.13      7171402.75
      2294529.67      7171436.11      2294531.72      7171498.85
      2294519.79      7171518.31      2294479.87      7171519.50
      2294460.16      7171544.87      2294461.21      7171574.04
      2294478.82      7171593.28      2294479.00      7171610.00

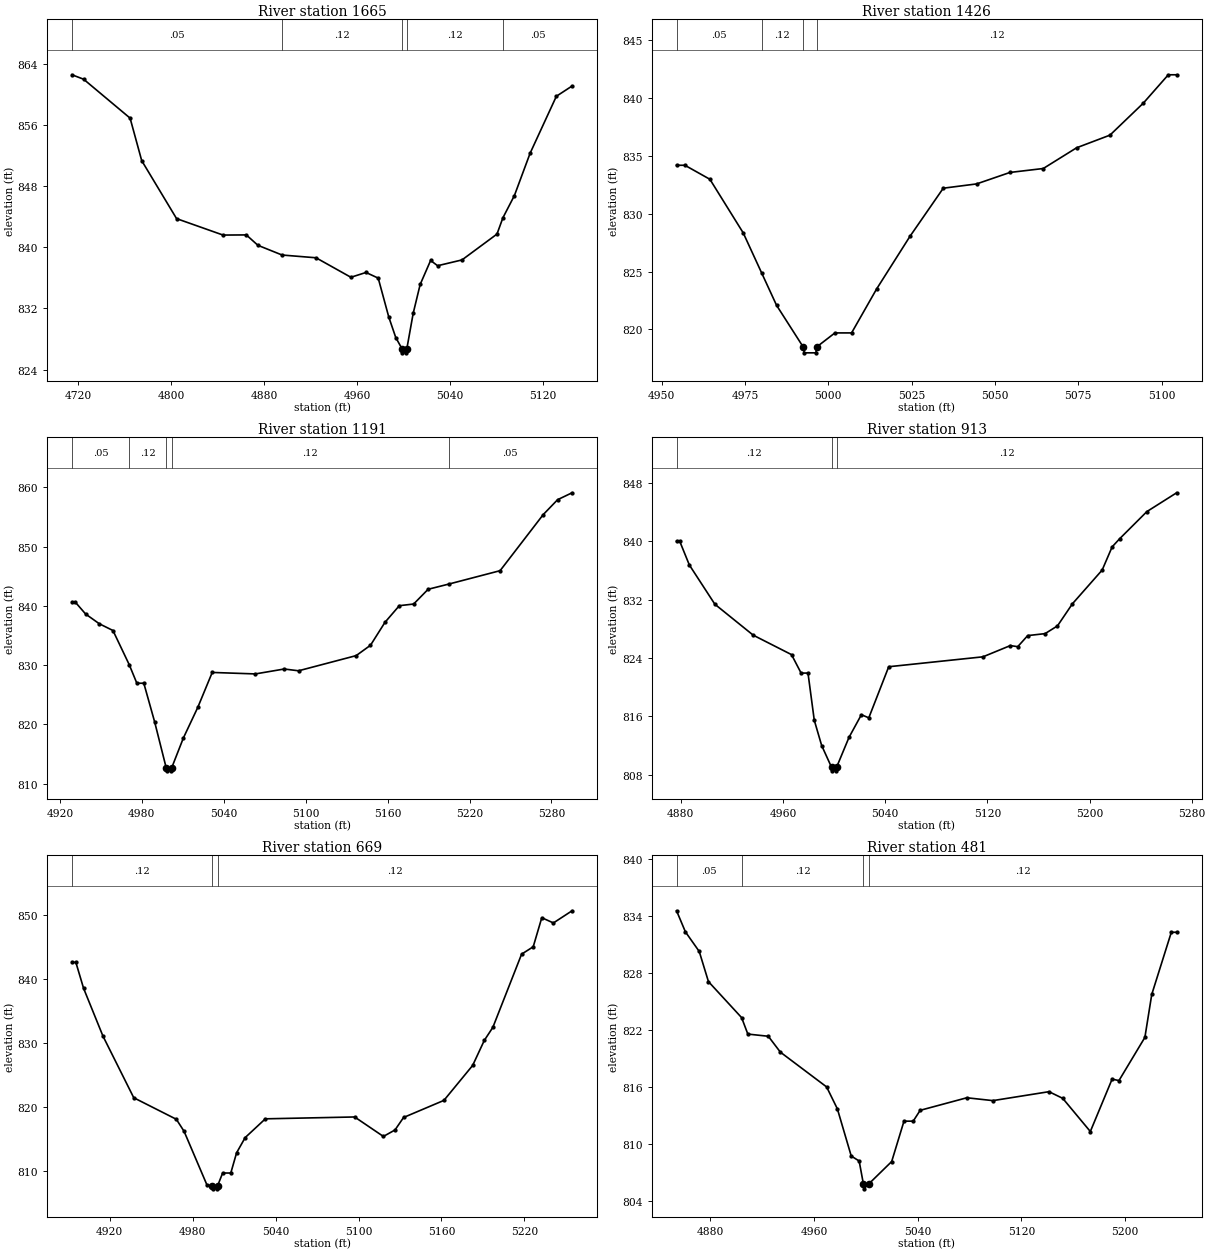
Type RM Length L Ch R = 1,1665,239,239,239
BEGIN DESCRIPTION:
MDE S 050 6.0
END DESCRIPTION:
XS GIS Cut Line= 3
      2294928.98      7170360.00      2295179.00      7170360.00
      2295329.00      7170460.00
#Sta/Elev= 30
  4714.5  862.56  4724.5  861.98  4764.5  856.89  4774.5  851.33  4804.5  843.75
  4844.5  841.60  4864.5  841.62  4874.5  840.26  4895.3  838.99  4924.5  838.63
  4954.5  836.08  4967.5  836.71  4978.0  835.97  4987.1  830.88  4993.1  828.20
  4998.6  826.70  4998.8  826.20  5002.3  826.20  5002.6  826.70  5008.1  831.37
  5014.1  835.14  5023.1  838.28  5029.1  837.59  5050.1  838.35  5080.2  841.73
  5085.3  843.86  5095.2  846.77  5108.7  852.30  5131.3  859.75  5144.8  861.09
#Mann=5,-1,0
  4714.5    0.05       0  4895.3    0.12       0  4998.6    0.07       0
  5002.6    0.12       0  5085.3    0.05       0
Bank Sta=4998.6,5002.6
Exp/Cntr=0.3,0.1

Type RM Length L Ch R = 1,1426,235,235,235
BEGIN DESCRIPTION:
MDE S 050 5.0
END DESCRIPTION:
XS GIS Cut Line= 3
      2295028.98      7170560.00      2295079.00      7170560.00
      2295178.98      7170560.00
#Sta/Elev= 23
  4954.5  834.17  4957.0  834.17  4964.5  832.96  4974.5  828.33  4980.0  824.89
  4984.5  822.08  4992.5  818.48  4992.8  817.98  4996.3  817.98  4996.5  818.48
  5002.0  819.70  5007.0  819.70  5014.5  823.49  5024.5  828.03  5034.5  832.19
  5044.5  832.56  5054.5  833.55  5064.5  833.89  5074.5  835.68  5084.5  836.77
  5094.5  839.53  5102.0  841.98  5104.5  841.98
#Mann=4,-1,0
  4954.5    0.05       0  4980.0    0.12       0  4992.5    0.07       0
  4996.5    0.12       0
Bank Sta=4992.5,4996.5
Exp/Cntr=0.3,0.1

Type RM Length L Ch R = 1,1191,278,278,278
BEGIN DESCRIPTION:
MDE S 050 4.0
END DESCRIPTION:
XS GIS Cut Line= 3
      2294979.04      7170760.00      2295029.00      7170760.00
      2295329.01      7170860.00
#Sta/Elev= 30
  4928.9  840.62  4931.4  840.62  4938.9  838.63  4948.9  836.99  4958.9  835.85
  4970.8  830.09  4976.4  826.95  4981.5  826.95  4989.4  820.45  4997.9  812.66
  4998.2  812.16  5001.7  812.16  5001.9  812.66  5010.5  817.72  5021.0  822.86
  5031.6  828.77  5063.2  828.52  5084.3  829.35  5094.8  829.05  5137.0  831.61
  5147.5  833.36  5158.1  837.23  5168.6  840.04  5179.1  840.32  5189.7  842.81
  5204.7  843.68  5242.4  845.95  5274.0  855.42  5284.5  857.93  5295.1  859.10
#Mann=5,-1,0
  4928.9    0.05       0  4970.8    0.12       0  4997.9    0.07       0
  5001.9    0.12       0  5204.7    0.05       0
Bank Sta=4997.9,5001.9
Exp/Cntr=0.3,0.1

Type RM Length L Ch R = 1,913,244,244,244
BEGIN DESCRIPTION:
MDE S 050 3.0
END DESCRIPTION:
XS GIS Cut Line= 3
      2294829.02      7171010.00      2294929.00      7171010.00
      2295178.98      7171159.99
#Sta/Elev= 30
  4876.7  840.00  4879.2  840.00  4886.7  836.76  4906.7  831.37  4936.7  827.13
  4966.7  824.46  4974.2  821.93  4979.6  821.93  4984.5  815.47  4990.3  811.99
  4998.0  809.02  4998.3  808.52  5001.8  808.52  5002.0  809.02  5011.7  813.11
  5021.4  816.22  5027.2  815.79  5042.8  822.80  5116.6  824.16  5138.0  825.70
  5143.8  825.55  5151.6  827.07  5165.2  827.34  5174.9  828.40  5186.6  831.43
  5209.9  836.06  5217.7  839.24  5223.5  840.34  5244.9  844.08  5268.2  846.66
#Mann=3,-1,0
  4876.7    0.12       0  4998.0    0.07       0  5002.0    0.12       0
Bank Sta=4998,5002
Exp/Cntr=0.3,0.1

Type RM Length L Ch R = 1,669,188,188,188
BEGIN DESCRIPTION:
MDE S 050 2.0
END DESCRIPTION:
XS GIS Cut Line= 3
      2294779.00      7171110.01      2294829.00      7171210.00
      2294979.00      7171410.00
#Sta/Elev= 30
  4892.7  842.62  4895.5  842.62  4901.1  838.56  4915.1  831.11  4937.4  821.48
  4968.2  818.12  4973.8  816.24  4990.5  807.79  4994.1  807.76  4994.4  807.26
  4997.9  807.26  4998.1  807.76  5001.7  809.73  5007.6  809.73  5011.8  812.89
  5018.0  815.26  5032.6  818.19  5097.2  818.48  5118.0  815.44  5126.4  816.45
  5132.6  818.40  5161.8  821.07  5182.6  826.53  5191.0  830.43  5197.2  832.47
  5218.0  843.90  5226.4  845.05  5232.6  849.59  5241.0  848.77  5254.5  850.67
#Mann=3,-1,0
  4892.7    0.12       0  4994.1    0.07       0  4998.1    0.12       0
Bank Sta=4994.1,4998.1
Exp/Cntr=0.3,0.1

Type RM Length L Ch R = 1,481,142,142,142
BEGIN DESCRIPTION:
Mapping XS acb6c34e
END DESCRIPTION:
XS GIS Cut Line= 3
      2294634.85      7171183.59      2294696.88      7171351.30
      2294891.66      7171421.63
#Sta/Elev= 30
  4853.9  834.51  4860.7  832.30  4871.4  830.23  4878.5  827.06  4904.1  823.27
  4908.9  821.54  4924.7  821.31  4934.0  819.64  4969.7  815.98  4978.0  813.67
  4988.7  808.71  4994.8  808.19  4998.1  805.76  4998.4  805.26  5002.1  805.76
  5019.9  808.13  5029.4  812.38  5036.5  812.38  5041.9  813.52  5077.9  814.84
  5098.0  814.54  5141.3  815.48  5151.9  814.78  5173.2  811.29  5190.0  816.80
  5195.3  816.65  5215.3  821.19  5220.6  825.71  5235.7  832.25  5239.8  832.25
#Mann=4,-1,0
  4853.9    0.05       0  4904.1    0.12       0  4998.1    0.07       0
  5002.1    0.12       0
Bank Sta=4998.1,5002.1
Exp/Cntr=0.3,0.1

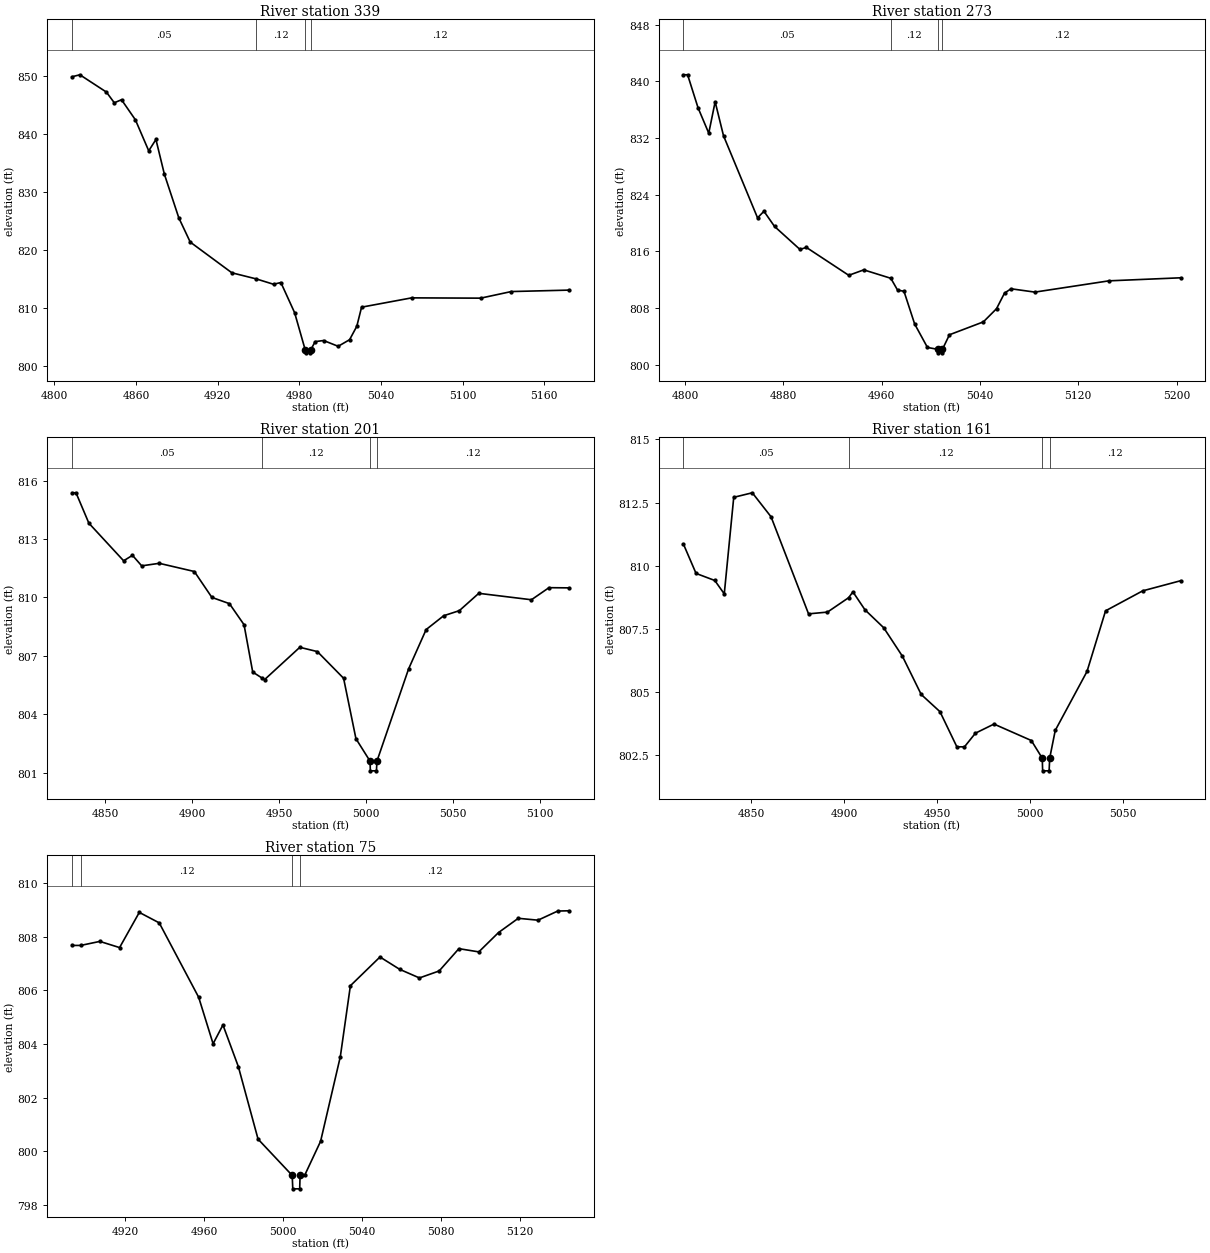
Type RM Length L Ch R = 1,339,66,66,66
BEGIN DESCRIPTION:
Mapping XS a27586b5
END DESCRIPTION:
XS GIS Cut Line= 3
      2294533.19      7171196.11      2294606.41      7171397.48
      2294742.30      7171463.39
#Sta/Elev= 30
  4812.9  849.90  4818.8  850.25  4838.3  847.26  4844.1  845.41  4849.4  845.94
  4859.6  842.47  4869.4  837.11  4874.7  839.07  4880.9  833.07  4891.5  825.53
  4899.9  821.34  4930.5  816.03  4948.5  814.97  4961.1  814.05  4966.5  814.35
  4976.6  809.14  4984.4  802.70  4984.7  802.20  4988.2  802.20  4988.4  802.70
  4991.7  804.14  4997.9  804.33  5008.6  803.33  5017.0  804.47  5022.3  806.79
  5025.8  810.09  5062.6  811.70  5113.3  811.65  5135.8  812.79  5178.2  813.04
#Mann=4,-1,0
  4812.9    0.05       0  4948.5    0.12       0  4984.4    0.07       0
  4988.4    0.12       0
Bank Sta=4984.4,4988.4
Exp/Cntr=0.3,0.1

Type RM Length L Ch R = 1,273,72,72,72
BEGIN DESCRIPTION:
Mapping XS 3d11f18d
END DESCRIPTION:
XS GIS Cut Line= 3
      2294497.62      7171208.54      2294555.31      7171419.47
      2294728.87      7171485.58
#Sta/Elev= 30
  4798.8  840.91  4802.2  840.91  4810.7  836.25  4819.4  832.67  4824.6  837.10
  4831.4  832.31  4859.1  820.72  4864.3  821.65  4872.9  819.51  4893.6  816.26
  4898.8  816.55  4933.3  812.61  4945.5  813.38  4967.5  812.19  4973.0  810.52
  4978.2  810.36  4986.9  805.74  4997.3  802.43  5005.5  802.17  5005.7  801.67
  5009.2  801.67  5009.5  802.17  5015.2  804.22  5042.8  806.04  5053.5  807.90
  5060.0  810.10  5065.3  810.71  5084.7  810.24  5144.9  811.83  5203.2  812.26
#Mann=4,-1,0
  4798.8    0.05       0  4967.5    0.12       0  5005.5    0.07       0
  5009.5    0.12       0
Bank Sta=5005.5,5009.5
Exp/Cntr=0.3,0.1

Type RM Length L Ch R = 1,201,40,40,40
BEGIN DESCRIPTION:
Mapping XS 6c8fcc52
END DESCRIPTION:
XS GIS Cut Line= 3
      2294488.88      7171310.27      2294511.97      7171464.92
      2294640.39      7171483.44
#Sta/Elev= 30
  4830.7  815.37  4833.1  815.37  4840.5  813.81  4860.5  811.88  4865.6  812.16
  4870.9  811.62  4881.0  811.75  4901.2  811.33  4911.3  810.00  4921.4  809.68
  4929.8  808.60  4934.8  806.17  4940.2  805.86  4941.6  805.78  4961.9  807.44
  4972.0  807.22  4987.1  805.85  4994.2  802.75  5002.3  801.60  5002.5  801.10
  5006.0  801.10  5006.3  801.60  5024.5  806.33  5034.6  808.35  5044.7  809.06
  5053.7  809.32  5064.9  810.21  5095.2  809.88  5105.3  810.50  5116.8  810.49
#Mann=4,-1,0
  4830.7    0.05       0  4940.2    0.12       0  5002.3    0.07       0
  5006.3    0.12       0
Bank Sta=5002.3,5006.3
Exp/Cntr=0.3,0.1

Type RM Length L Ch R = 1,161,86,86,86
BEGIN DESCRIPTION:
Mapping XS 207f38e0
END DESCRIPTION:
XS GIS Cut Line= 3
      2294470.74      7171353.29      2294493.09      7171503.05
      2294609.38      7171507.90
#Sta/Elev= 30
  4813.4  810.86  4820.2  809.70  4830.3  809.42  4835.4  808.89  4840.5  812.71
  4850.5  812.89  4860.6  811.94  4880.8  808.10  4891.0  808.17  4902.4  808.74
  4904.7  808.97  4911.2  808.26  4921.3  807.55  4931.4  806.42  4941.5  804.91
  4951.6  804.23  4960.7  802.84  4964.8  802.84  4970.7  803.38  4980.7  803.74
  5000.8  803.09  5006.7  802.39  5006.9  801.89  5010.4  801.89  5010.7  802.39
  5013.7  803.49  5030.8  805.82  5040.8  808.22  5060.8  809.01  5081.2  809.41
#Mann=4,-1,0
  4813.4    0.05       0  4902.4    0.12       0  5006.7    0.07       0
  5010.7    0.12       0
Bank Sta=5006.7,5010.7
Exp/Cntr=0.3,0.1

Type RM Length L Ch R = 1,75,0,0,0
BEGIN DESCRIPTION:
MDE S 050 1.0
END DESCRIPTION:
XS GIS Cut Line= 3
      2294469.13      7171435.83      2294460.93      7171553.57
      2294594.65      7171561.82
#Sta/Elev= 30
  4893.0  807.67  4897.5  807.67  4907.2  807.82  4917.2  807.59  4927.2  808.90
  4937.3  808.51  4957.3  805.74  4964.6  804.01  4969.6  804.71  4977.4  803.16
  4987.4  800.46  5004.7  799.11  5005.0  798.61  5008.5  798.61  5008.7  799.11
  5011.0  799.11  5019.1  800.38  5029.1  803.53  5034.2  806.17  5049.2  807.24
  5059.2  806.78  5069.2  806.46  5079.2  806.72  5089.2  807.55  5099.3  807.43
  5109.3  808.15  5119.3  808.68  5129.3  808.61  5139.3  808.95  5145.0  808.96
#Mann=4,-1,0
  4893.0    0.05       0  4897.5    0.12       0  5004.7    0.07       0
  5008.7    0.12       0
Bank Sta=5004.7,5008.7
Exp/Cntr=0.3,0.1

Chan Stop Cuts=-1