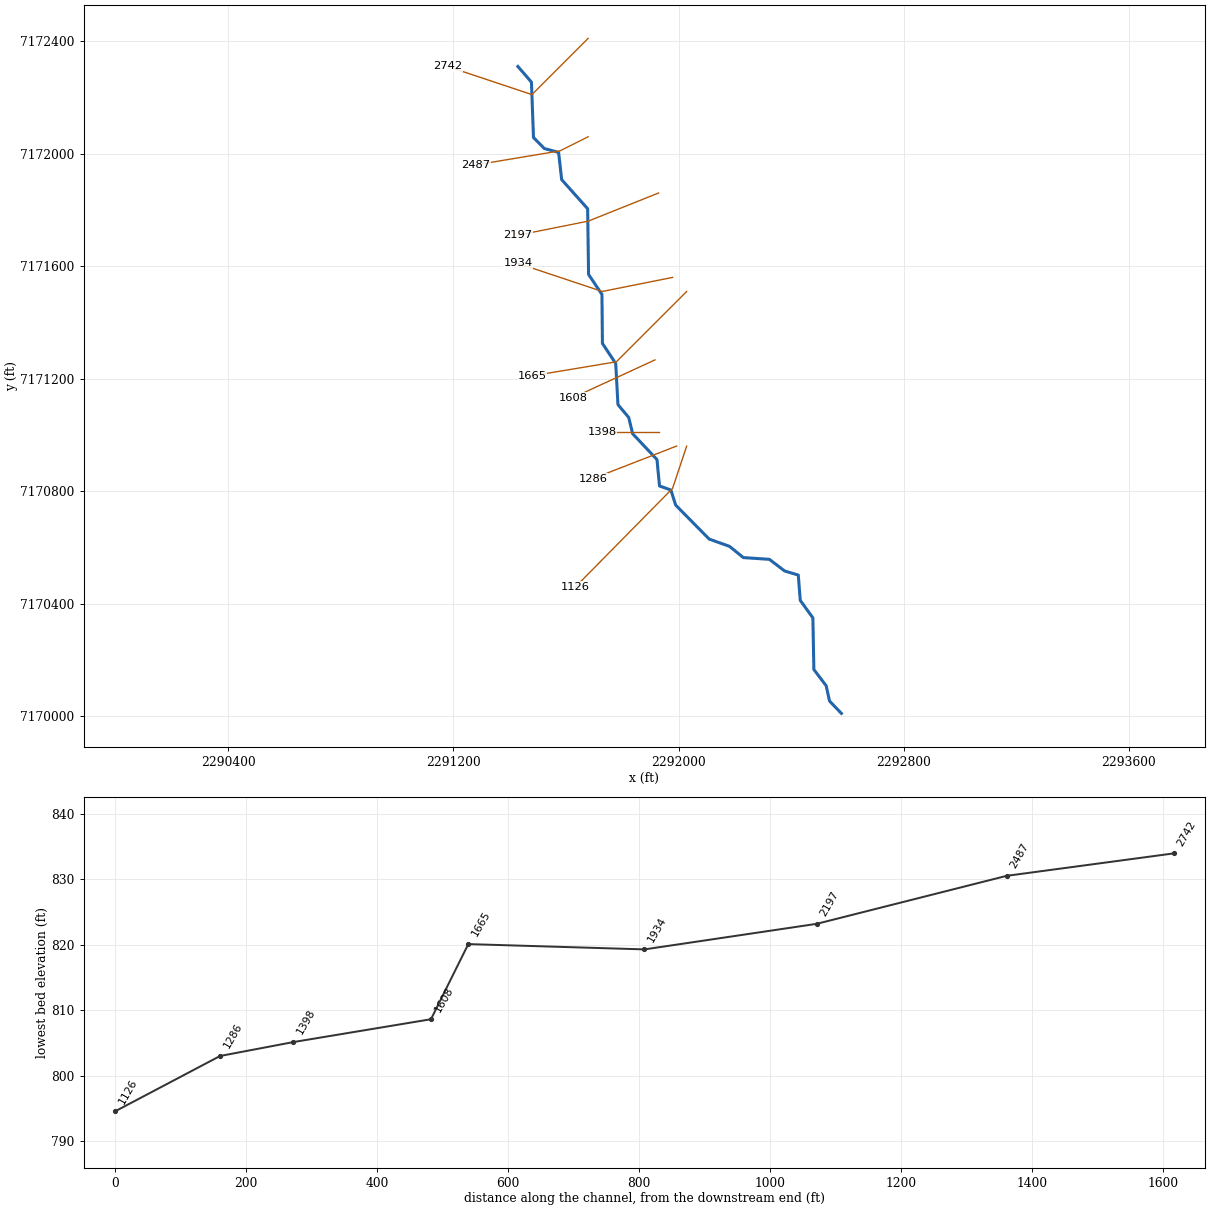
--- MDE S 051.prj (project) ---

Proj Title=MDE S 051 Base Level Engineering
Current Plan=p01
Default Exp/Contr=0.3,0.1
English Units
Geom File=g01
Flow File=f01
Plan File=p01
BEGIN DESCRIPTION:
MDE S 051
END DESCRIPTION:

--- MDE S 051.p01 (plan) ---

Plan Title=Multiple Run
Short Identifier=Multiple
Geom File=g01
Flow File=f01
Subcritical Flow
K Sum by GR= 0
Std Step Tol= 0.01
Critical Tol= 0.01
Num of Std Step Trials= 20
Max Error Tol= 0.3
Flow Tol Ratio= 0.001
Split Flow NTrial= 30
Split Flow Tol= 0.02
Split Flow Ratio= 0.02
Log Output Level= 0
Friction Slope Method= 1
Unsteady Friction Slope Method= 2
Unsteady Bridges Friction Slope Method= 1
Parabolic Critical Depth
Global Vel Dist=  1 , 1 , 1
Global Log Level= 0
CheckData=True
Encroach Param= -1, 0, 0, 0
BEGIN DESCRIPTION:
Multiple Run
END DESCRIPTION:

--- MDE S 051.f01 (steady flow) ---

Flow Title=Multiple
Number of Profiles=7
Profile Names=10-year,25-year,50-year,1pct_min,100-year,1pct_plu,500-year
River Rch & RM= MDE S 051,Reach-1,2742
     230     296     347     204     406     811     554
Boundary for River Rch & Prof#=MDE S 051,Reach-1,1
Up Type=0
Dn Type=3
Dn Slope=0.005
Boundary for River Rch & Prof#=MDE S 051,Reach-1,2
Up Type=0
Dn Type=3
Dn Slope=0.005
Boundary for River Rch & Prof#=MDE S 051,Reach-1,3
Up Type=0
Dn Type=3
Dn Slope=0.005
Boundary for River Rch & Prof#=MDE S 051,Reach-1,4
Up Type=0
Dn Type=3
Dn Slope=0.005
Boundary for River Rch & Prof#=MDE S 051,Reach-1,5
Up Type=0
Dn Type=3
Dn Slope=0.005
Boundary for River Rch & Prof#=MDE S 051,Reach-1,6
Up Type=0
Dn Type=3
Dn Slope=0.005
Boundary for River Rch & Prof#=MDE S 051,Reach-1,7
Up Type=0
Dn Type=3
Dn Slope=0.005

--- MDE S 051.g01 (geometry) ---

Geom Title=Existing Conditions

River Reach=MDE S 051,Reach-1
Reach XY= 30
      2291429.00      7172310.00      2291477.11      7172254.22
      2291484.40      7172057.32      2291522.96      7172018.17
      2291573.71      7172004.51      2291584.56      7171907.64
      2291676.93      7171804.14      2291680.22      7171570.50
      2291727.78      7171499.49      2291729.52      7171325.22
      2291776.73      7171254.06      2291784.71      7171107.65
      2291822.86      7171062.17      2291837.16      7171003.95
      2291923.44      7170912.36      2291932.50      7170818.48
      2291972.95      7170804.20      2291989.85      7170750.57
      2292108.91      7170629.78      2292181.17      7170603.86
      2292230.58      7170563.83      2292323.06      7170557.68
      2292377.22      7170516.30      2292425.85      7170501.69
      2292432.89      7170411.67      2292477.78      7170349.50
      2292481.23      7170165.92      2292524.92      7170108.31
      2292536.91      7170053.85      2292579.00      7170010.00

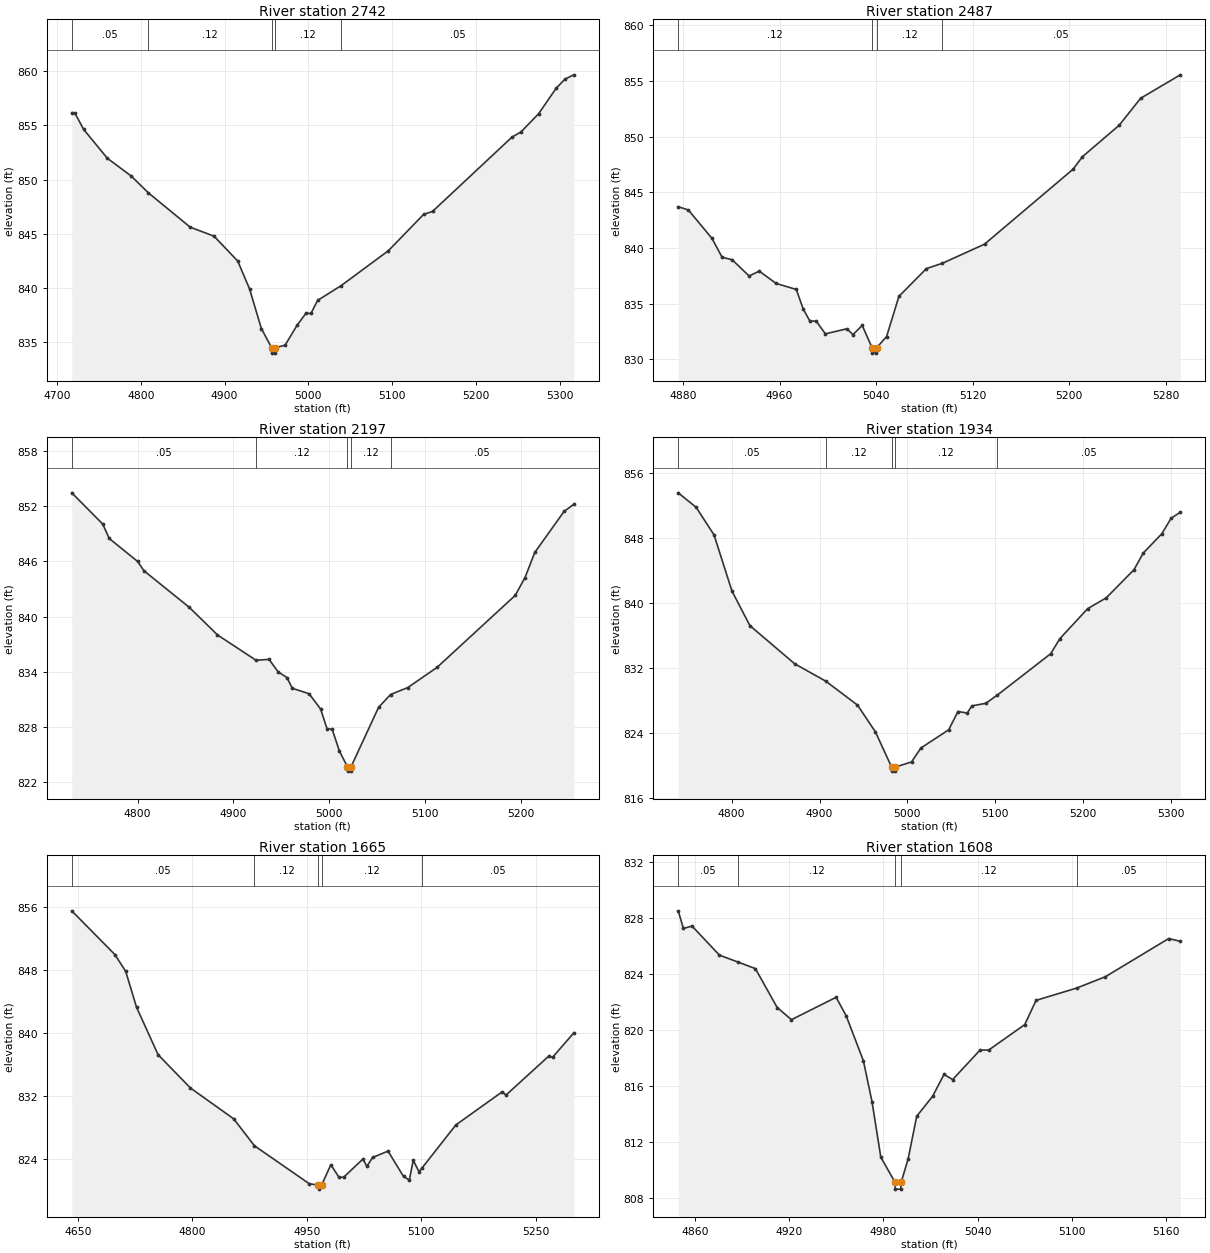
Type RM Length L Ch R = 1,2742,255,255,255
BEGIN DESCRIPTION:
MDE S 051 7.0
END DESCRIPTION:
XS GIS Cut Line= 3
      2291678.97      7172409.97      2291479.00      7172210.00
      2291179.03      7172309.99
#Sta/Elev= 30
  4717.7  856.17  4721.2  856.17  4731.8  854.64  4760.1  851.97  4788.4  850.34
  4809.2  848.77  4859.1  845.60  4887.4  844.78  4915.7  842.48  4929.8  839.91
  4943.9  836.25  4956.1  834.48  4956.3  833.98  4959.8  833.98  4960.1  834.48
  4972.2  834.71  4986.4  836.54  4997.0  837.65  5003.1  837.65  5011.0  838.85
  5038.7  840.19  5095.4  843.43  5137.5  846.79  5148.1  847.06  5242.9  853.92
  5253.5  854.39  5274.6  856.07  5295.7  858.44  5306.2  859.28  5316.7  859.67
#Mann=5,-1,0
  4717.7    0.05       0  4809.2    0.12       0  4956.1    0.07       0
  4960.1    0.12       0  5038.7    0.05       0
Bank Sta=4956.1,4960.1
Exp/Cntr=0.3,0.1

Type RM Length L Ch R = 1,2487,290,290,290
BEGIN DESCRIPTION:
MDE S 051 6.0
END DESCRIPTION:
XS GIS Cut Line= 3
      2291679.00      7172060.00      2291579.00      7172010.00
      2291279.04      7171960.01
#Sta/Elev= 30
  4876.1  843.71  4884.5  843.41  4904.0  840.87  4912.4  839.17  4920.8  838.94
  4934.8  837.48  4943.2  837.92  4957.2  836.81  4973.9  836.27  4979.5  834.55
  4985.1  833.43  4990.4  833.43  4998.0  832.28  5015.8  832.74  5020.8  832.21
  5028.5  833.04  5036.6  831.05  5036.8  830.55  5040.3  830.55  5040.6  831.05
  5048.7  832.04  5058.9  835.65  5081.7  838.15  5094.8  838.62  5129.8  840.34
  5203.3  847.09  5210.9  848.20  5241.3  851.02  5259.1  853.45  5292.0  855.56
#Mann=4,-1,0
  4876.1    0.12       0  5036.6    0.07       0  5040.6    0.12       0
  5094.8    0.05       0
Bank Sta=5036.6,5040.6
Exp/Cntr=0.3,0.1

Type RM Length L Ch R = 1,2197,263,263,263
BEGIN DESCRIPTION:
MDE S 051 5.0
END DESCRIPTION:
XS GIS Cut Line= 3
      2291929.01      7171860.00      2291679.00      7171760.00
      2291429.02      7171710.00
#Sta/Elev= 30
  4731.2  853.44  4763.5  850.05  4770.3  848.48  4799.9  845.99  4806.6  844.97
  4853.7  841.02  4883.3  838.01  4923.6  835.25  4937.2  835.35  4946.6  834.00
  4956.0  833.36  4961.4  832.21  4978.9  831.62  4991.0  829.96  4997.8  827.78
  5003.0  827.78  5010.7  825.37  5018.9  823.71  5019.1  823.21  5022.6  823.21
  5022.9  823.71  5051.5  830.13  5064.0  831.53  5082.1  832.29  5112.6  834.48
  5194.2  842.30  5204.4  844.23  5214.6  846.96  5245.2  851.42  5255.4  852.20
#Mann=5,-1,0
  4731.2    0.05       0  4923.6    0.12       0  5018.9    0.07       0
  5022.9    0.12       0  5064.0    0.05       0
Bank Sta=5018.9,5022.9
Exp/Cntr=0.3,0.1

Type RM Length L Ch R = 1,1934,269,269,269
BEGIN DESCRIPTION:
MDE S 051 4.0
END DESCRIPTION:
XS GIS Cut Line= 3
      2291978.96      7171559.99      2291729.00      7171510.00
      2291429.03      7171609.99
#Sta/Elev= 30
  4739.3  853.61  4759.7  851.82  4780.0  848.43  4800.4  841.50  4820.8  837.24
  4871.8  832.53  4907.3  830.38  4943.2  827.44  4963.6  824.14  4982.0  819.80
  4982.3  819.30  4985.8  819.30  4986.0  819.80  5004.7  820.43  5015.3  822.15
  5046.9  824.39  5057.5  826.65  5068.0  826.46  5073.3  827.34  5089.1  827.66
  5102.2  828.67  5162.9  833.77  5173.4  835.63  5205.0  839.33  5226.1  840.66
  5257.7  844.13  5268.3  846.19  5289.4  848.57  5299.9  850.47  5310.4  851.22
#Mann=5,-1,0
  4739.3    0.05       0  4907.3    0.12       0  4982.0    0.07       0
  4986.0    0.12       0  5102.2    0.05       0
Bank Sta=4982,4986
Exp/Cntr=0.3,0.1

Type RM Length L Ch R = 1,1665,57,57,57
BEGIN DESCRIPTION:
MDE S 051 3.0
END DESCRIPTION:
XS GIS Cut Line= 3
      2292028.97      7171509.97      2291779.00      7171260.00
      2291478.96      7171209.99
#Sta/Elev= 30
  4642.2  855.54  4698.7  849.97  4712.9  847.82  4727.0  843.27  4755.3  837.22
  4797.7  832.98  4854.3  829.06  4881.5  825.63  4953.3  820.80  4965.4  820.61
  4965.7  820.11  4969.4  820.61  4981.6  823.22  4992.2  821.62  4998.3  821.62
  5023.6  823.94  5028.7  823.01  5036.3  824.14  5056.5  824.95  5076.8  821.72
  5084.4  821.26  5089.5  823.77  5097.1  822.33  5101.5  822.86  5145.3  828.28
  5206.1  832.50  5211.1  832.09  5266.9  837.03  5272.0  836.89  5299.9  840.01
#Mann=5,-1,0
  4642.2    0.05       0  4881.5    0.12       0  4965.4    0.07       0
  4969.4    0.12       0  5101.5    0.05       0
Bank Sta=4965.4,4969.4
Exp/Cntr=0.3,0.1

Type RM Length L Ch R = 1,1608,210,210,210
BEGIN DESCRIPTION:
Mapping XS dd28c164
END DESCRIPTION:
XS GIS Cut Line= 2
      2291916.31      7171266.70      2291625.47      7171132.75
#Sta/Elev= 30
  4849.1  828.51  4852.4  827.25  4857.9  827.42  4875.4  825.34  4887.2  824.85
  4898.3  824.38  4912.2  821.60  4921.3  820.73  4949.8  822.33  4956.2  821.01
  4967.2  817.79  4972.7  814.86  4978.3  810.90  4987.3  809.12  4987.5  808.62
  4991.0  808.62  4991.3  809.12  4995.7  810.77  5001.2  813.83  5011.3  815.25
  5018.6  816.82  5024.1  816.45  5041.6  818.56  5047.1  818.56  5070.1  820.38
  5077.3  822.11  5103.2  822.99  5121.5  823.80  5161.9  826.53  5169.3  826.33
#Mann=5,-1,0
  4849.1    0.05       0  4887.2    0.12       0  4987.3    0.07       0
  4991.3    0.12       0  5103.2    0.05       0
Bank Sta=4987.3,4991.3
Exp/Cntr=0.3,0.1

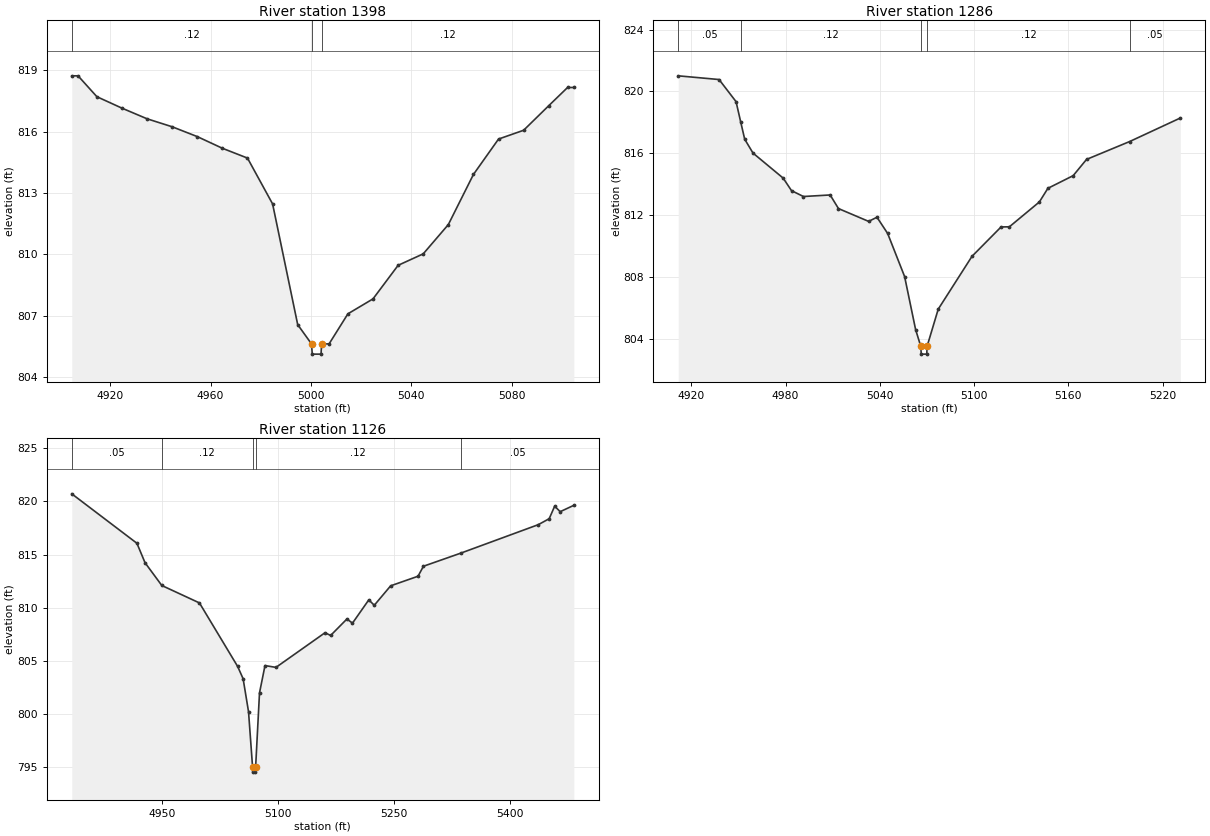
Type RM Length L Ch R = 1,1398,112,112,112
BEGIN DESCRIPTION:
MDE S 051 2.0
END DESCRIPTION:
XS GIS Cut Line= 3
      2291929.04      7171010.00      2291829.00      7171010.00
      2291729.04      7171010.00
#Sta/Elev= 27
  4904.7  818.73  4907.2  818.73  4914.7  817.71  4924.7  817.15  4934.7  816.63
  4944.7  816.24  4954.7  815.76  4964.7  815.19  4974.7  814.71  4984.7  812.47
  4994.7  806.57  5000.2  805.63  5000.5  805.13  5004.0  805.13  5004.2  805.63
  5007.2  805.63  5014.7  807.10  5024.7  807.83  5034.7  809.47  5044.7  810.03
  5054.7  811.46  5064.7  813.91  5074.7  815.64  5084.7  816.07  5094.7  817.27
  5102.2  818.16  5104.7  818.16
#Mann=3,-1,0
  4904.7    0.12       0  5000.2    0.07       0  5004.2    0.12       0
Bank Sta=5000.2,5004.2
Exp/Cntr=0.3,0.1

Type RM Length L Ch R = 1,1286,160,160,160
BEGIN DESCRIPTION:
Mapping XS 59093a64
END DESCRIPTION:
XS GIS Cut Line= 2
      2291993.26      7170960.38      2291695.42      7170844.47
#Sta/Elev= 30
  4911.7  821.01  4937.7  820.77  4948.5  819.34  4951.5  818.01  4954.0  816.91
  4959.3  816.01  4978.5  814.39  4983.8  813.58  4991.4  813.20  5008.4  813.30
  5013.7  812.42  5032.9  811.59  5038.2  811.86  5045.0  810.81  5055.8  808.02
  5062.8  804.59  5066.1  803.50  5066.4  803.00  5069.9  803.00  5070.1  803.50
  5077.2  805.91  5098.7  809.33  5117.2  811.23  5122.5  811.24  5141.6  812.85
  5147.0  813.73  5163.1  814.55  5171.6  815.60  5199.1  816.76  5231.3  818.28
#Mann=5,-1,0
  4911.7    0.05       0  4951.5    0.12       0  5066.1    0.07       0
  5070.1    0.12       0  5199.1    0.05       0
Bank Sta=5066.1,5070.1
Exp/Cntr=0.3,0.1

Type RM Length L Ch R = 1,1126,0,0,0
BEGIN DESCRIPTION:
MDE S 051 1.0
END DESCRIPTION:
XS GIS Cut Line= 3
      2292028.99      7170959.97      2291979.00      7170810.00
      2291633.91      7170460.00
#Sta/Elev= 30
  4833.5  820.72  4917.8  816.07  4928.3  814.24  4950.0  812.10  4998.7  810.46
  5048.1  804.49  5055.2  803.33  5062.2  800.23  5067.4  795.05  5067.6  794.55
  5071.1  794.55  5071.4  795.05  5076.4  802.00  5083.5  804.57  5097.7  804.40
  5161.2  807.66  5168.4  807.40  5189.5  808.95  5196.7  808.56  5217.8  810.75
  5224.9  810.24  5246.1  812.07  5281.5  812.97  5288.5  813.91  5337.1  815.15
  5437.1  817.82  5451.2  818.38  5458.3  819.56  5465.4  819.04  5483.1  819.64
#Mann=5,-1,0
  4833.5    0.05       0  4950.0    0.12       0  5067.4    0.07       0
  5071.4    0.12       0  5337.1    0.05       0
Bank Sta=5067.4,5071.4
Exp/Cntr=0.3,0.1

Chan Stop Cuts=-1