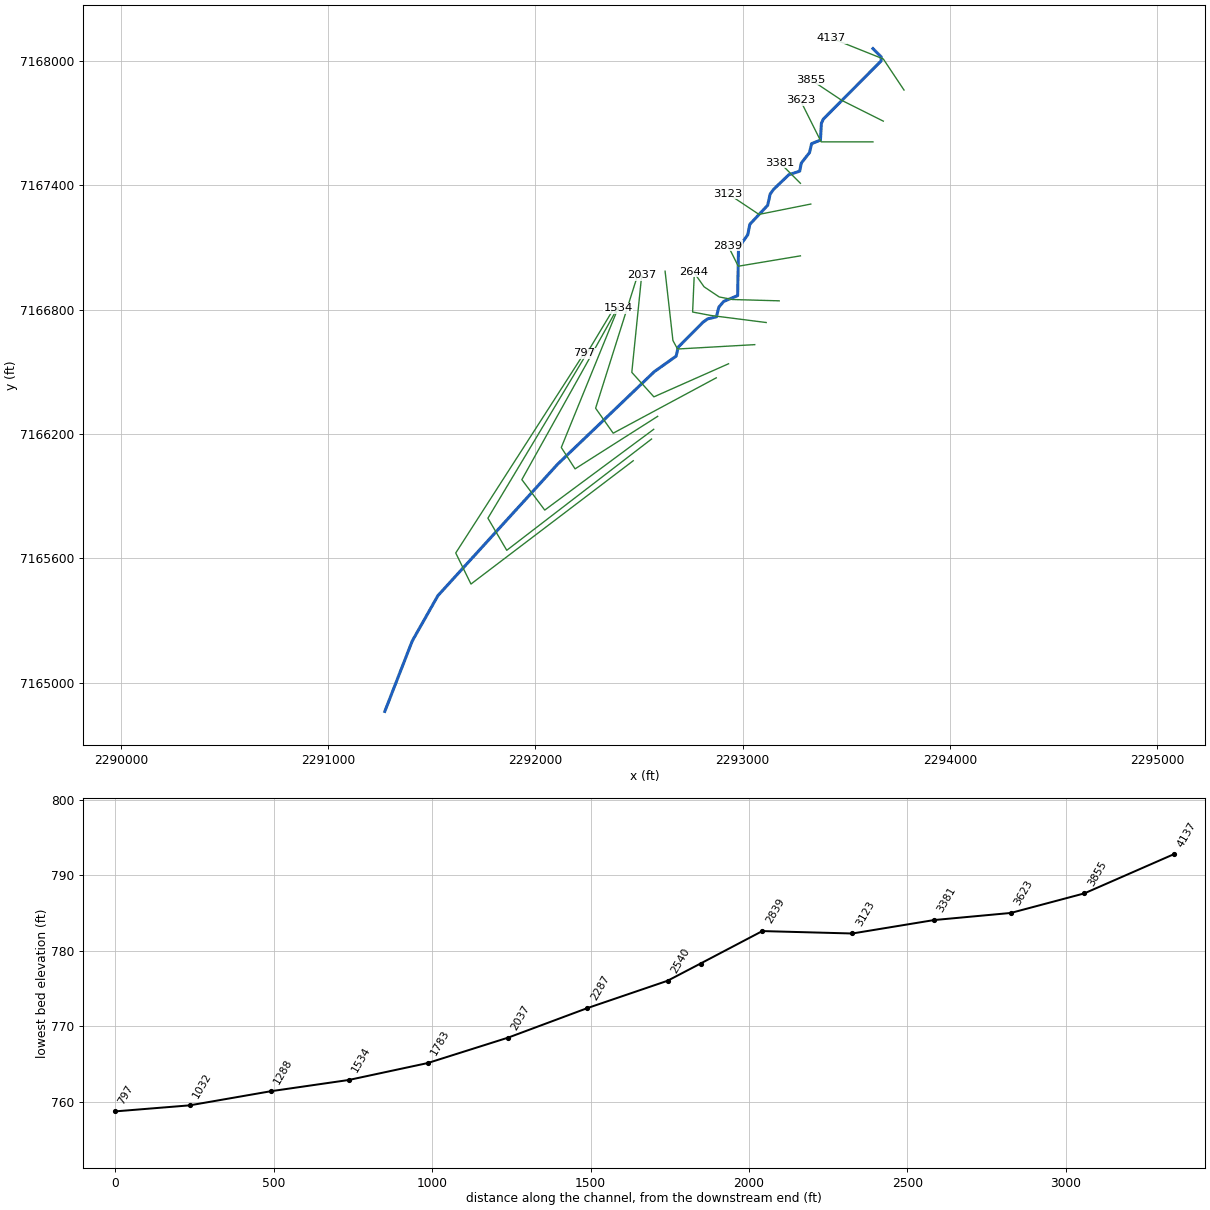
--- MDE S 052.prj (project) ---

Proj Title=MDE S 052 Base Level Engineering
Current Plan=p01
Default Exp/Contr=0.3,0.1
English Units
Geom File=g01
Flow File=f01
Plan File=p01
BEGIN DESCRIPTION:
MDE S 052
END DESCRIPTION:

--- MDE S 052.p01 (plan) ---

Plan Title=Multiple Run
Short Identifier=Multiple
Geom File=g01
Flow File=f01
Subcritical Flow
K Sum by GR= 0
Std Step Tol= 0.01
Critical Tol= 0.01
Num of Std Step Trials= 20
Max Error Tol= 0.3
Flow Tol Ratio= 0.001
Split Flow NTrial= 30
Split Flow Tol= 0.02
Split Flow Ratio= 0.02
Log Output Level= 0
Friction Slope Method= 1
Unsteady Friction Slope Method= 2
Unsteady Bridges Friction Slope Method= 1
Parabolic Critical Depth
Global Vel Dist=  1 , 1 , 1
Global Log Level= 0
CheckData=True
Encroach Param= -1, 0, 0, 0
BEGIN DESCRIPTION:
Multiple Run
END DESCRIPTION:

--- MDE S 052.f01 (steady flow) ---

Flow Title=Multiple
Number of Profiles=7
Profile Names=10-year,25-year,50-year,1pct_min,100-year,1pct_plu,500-year
River Rch & RM= MDE S 052,Reach-1,4137
     304     399     475     282     562    1121     787
River Rch & RM= MDE S 052,Reach-1,2540
     223     282     327     189     377     753     500
Boundary for River Rch & Prof#=MDE S 052,Reach-1,1
Up Type=0
Dn Type=3
Dn Slope=0.005
Boundary for River Rch & Prof#=MDE S 052,Reach-1,2
Up Type=0
Dn Type=3
Dn Slope=0.005
Boundary for River Rch & Prof#=MDE S 052,Reach-1,3
Up Type=0
Dn Type=3
Dn Slope=0.005
Boundary for River Rch & Prof#=MDE S 052,Reach-1,4
Up Type=0
Dn Type=3
Dn Slope=0.005
Boundary for River Rch & Prof#=MDE S 052,Reach-1,5
Up Type=0
Dn Type=3
Dn Slope=0.005
Boundary for River Rch & Prof#=MDE S 052,Reach-1,6
Up Type=0
Dn Type=3
Dn Slope=0.005
Boundary for River Rch & Prof#=MDE S 052,Reach-1,7
Up Type=0
Dn Type=3
Dn Slope=0.005

--- MDE S 052.g01 (geometry) ---

Geom Title=Existing Conditions

River Reach=MDE S 052,Reach-1
Reach XY= 30
      2293629.00      7168060.00      2293668.90      7168020.00
      2293668.11      7168000.00      2293389.53      7167719.75
      2293380.20      7167699.42      2293375.50      7167618.48
      2293332.90      7167601.35      2293322.84      7167558.08
      2293283.33      7167507.93      2293275.48      7167468.49
      2293223.23      7167451.72      2293148.78      7167380.13
      2293132.97      7167358.36      2293120.82      7167303.96
      2293034.84      7167212.29      2293024.78      7167161.75
      2292980.20      7167099.50      2292975.91      7166868.31
      2292908.76      7166840.19      2292884.93      7166812.19
      2292873.37      7166765.65      2292831.01      7166755.88
      2292809.08      7166740.14      2292689.19      7166619.68
      2292678.98      7166576.07      2292573.78      7166501.38
      2292107.30      7166055.13      2291529.32      7165420.75
      2291405.05      7165201.32      2291272.92      7164862.10

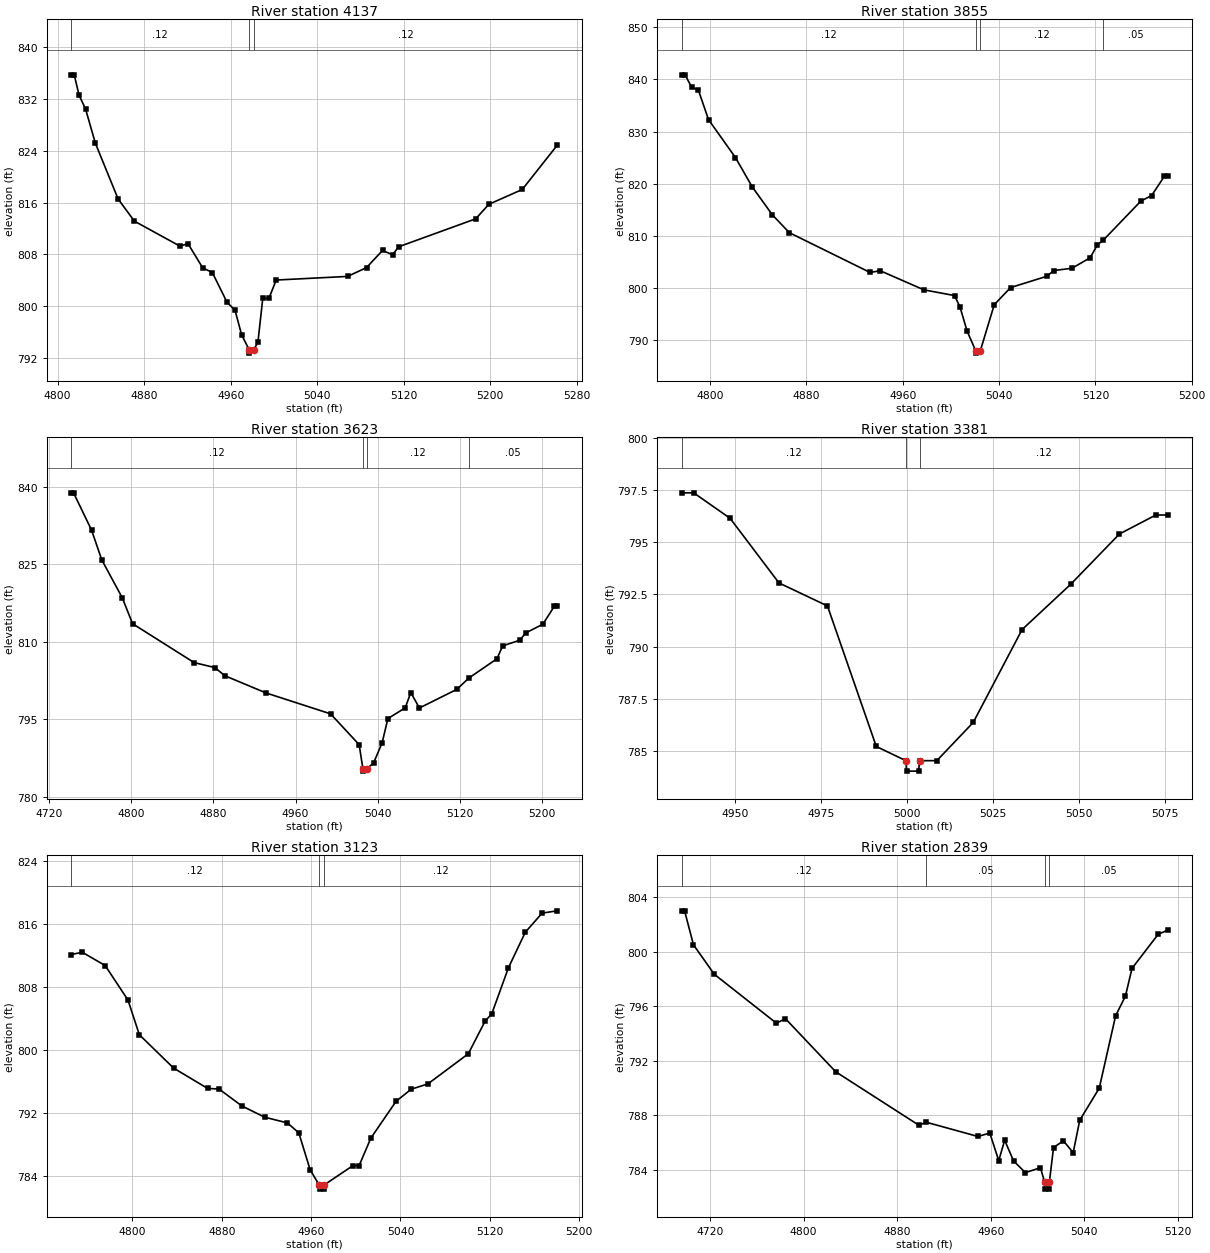
Type RM Length L Ch R = 1,4137,282,282,282
BEGIN DESCRIPTION:
MDE S 052 17.0
END DESCRIPTION:
XS GIS Cut Line= 3
      2293779.01      7167859.99      2293679.00      7168010.00
      2293429.05      7168109.98
#Sta/Elev= 30
  4812.3  835.75  4815.3  835.75  4819.8  832.59  4825.8  830.46  4834.8  825.21
  4855.9  816.56  4870.9  813.15  4913.0  809.29  4920.5  809.67  4934.0  805.95
  4943.0  805.20  4956.5  800.64  4964.0  799.36  4970.1  795.56  4977.1  793.26
  4977.3  792.76  4981.1  793.26  4985.1  794.43  4989.6  801.22  4995.3  801.22
  5002.0  804.05  5068.0  804.61  5085.5  805.97  5100.3  808.62  5109.7  807.95
  5115.1  809.18  5186.5  813.51  5198.6  815.75  5229.5  818.04  5261.8  824.87
#Mann=3,-1,0
  4812.3    0.12       0  4977.1    0.07       0  4981.1    0.12       0
Bank Sta=4977.1,4981.1
Exp/Cntr=0.3,0.1

Type RM Length L Ch R = 1,3855,232,232,232
BEGIN DESCRIPTION:
MDE S 052 16.0
END DESCRIPTION:
XS GIS Cut Line= 3
      2293678.97      7167710.02      2293479.00      7167810.00
      2293329.04      7167909.97
#Sta/Elev= 30
  4776.4  840.85  4779.2  840.85  4784.7  838.49  4790.3  837.92  4798.7  832.28
  4821.1  825.01  4835.1  819.37  4851.8  814.03  4865.8  810.64  4932.9  803.02
  4941.3  803.35  4977.6  799.69  5003.0  798.60  5007.5  796.45  5013.5  791.76
  5020.5  788.08  5020.8  787.58  5024.5  788.08  5036.0  796.85  5049.5  800.12
  5079.6  802.29  5085.6  803.39  5100.6  803.83  5115.6  805.83  5121.7  808.31
  5126.4  809.17  5157.7  816.67  5166.7  817.75  5177.2  821.40  5180.2  821.40
#Mann=4,-1,0
  4776.4    0.12       0  5020.5    0.07       0  5024.5    0.12       0
  5126.4    0.05       0
Bank Sta=5020.5,5024.5
Exp/Cntr=0.3,0.1

Type RM Length L Ch R = 1,3623,242,242,242
BEGIN DESCRIPTION:
MDE S 052 15.0
END DESCRIPTION:
XS GIS Cut Line= 3
      2293628.99      7167610.00      2293379.00      7167610.00
      2293279.00      7167810.01
#Sta/Elev= 30
  4741.2  838.85  4743.7  838.85  4761.2  831.66  4771.2  825.87  4791.2  818.52
  4801.2  813.52  4861.2  805.99  4881.2  805.04  4891.2  803.44  4931.2  800.12
  4994.0  796.08  5021.9  790.11  5025.5  785.49  5025.8  784.99  5029.5  785.49
  5035.9  786.55  5044.3  790.50  5049.9  795.16  5066.7  797.23  5072.2  800.19
  5080.6  797.21  5117.0  800.81  5128.9  803.03  5156.1  806.73  5161.7  809.24
  5178.5  810.33  5184.0  811.72  5200.8  813.42  5212.0  816.89  5214.8  816.89
#Mann=4,-1,0
  4741.2    0.12       0  5025.5    0.07       0  5029.5    0.12       0
  5128.9    0.05       0
Bank Sta=5025.5,5029.5
Exp/Cntr=0.3,0.1

Type RM Length L Ch R = 1,3381,258,258,258
BEGIN DESCRIPTION:
MDE S 052 14.0
END DESCRIPTION:
XS GIS Cut Line= 3
      2293278.99      7167410.01      2293229.00      7167460.00
      2293179.00      7167510.00
#Sta/Elev= 17
  4934.4  797.36  4937.9  797.36  4948.5  796.14  4962.7  793.05  4976.8  791.95
  4991.0  785.23  4999.6  784.55  4999.8  784.05  5003.3  784.05  5003.6  784.55
  5008.6  784.55  5019.2  786.38  5033.4  790.82  5047.5  792.98  5061.7  795.39
  5072.3  796.30  5075.8  796.30
#Mann=3,-1,0
  4934.4    0.12       0  4999.6    0.07       0  5003.6    0.12       0
Bank Sta=4999.6,5003.6
Exp/Cntr=0.3,0.1

Type RM Length L Ch R = 1,3123,284,284,284
BEGIN DESCRIPTION:
MDE S 052 13.0
END DESCRIPTION:
XS GIS Cut Line= 3
      2293328.97      7167309.99      2293079.00      7167260.00
      2292929.00      7167360.00
#Sta/Elev= 30
  4745.1  812.07  4755.3  812.35  4775.7  810.67  4796.1  806.29  4806.3  801.88
  4836.9  797.65  4867.4  795.06  4877.6  794.99  4898.0  792.84  4918.4  791.41
  4938.8  790.68  4949.0  789.42  4959.2  784.71  4967.4  782.77  4967.7  782.27
  4971.2  782.27  4971.4  782.77  4997.5  785.26  5003.0  785.26  5013.5  788.75
  5036.1  793.43  5049.6  794.96  5064.6  795.64  5100.7  799.46  5115.7  803.59
  5121.7  804.53  5136.7  810.41  5151.8  814.91  5166.8  817.33  5180.3  817.62
#Mann=3,-1,0
  4745.1    0.12       0  4967.4    0.07       0  4971.4    0.12       0
Bank Sta=4967.4,4971.4
Exp/Cntr=0.3,0.1

Type RM Length L Ch R = 1,2839,195,195,195
BEGIN DESCRIPTION:
MDE S 052 12.0
END DESCRIPTION:
XS GIS Cut Line= 3
      2293279.00      7167060.00      2292979.00      7167010.00
      2292929.02      7167109.96
#Sta/Elev= 30
  4695.7  802.99  4698.2  802.99  4705.8  800.50  4723.6  798.34  4776.8  794.75
  4784.4  795.09  4827.5  791.19  4898.5  787.28  4905.1  787.49  4949.1  786.45
  4959.3  786.70  4966.9  784.68  4972.0  786.17  4979.6  784.66  4989.7  783.80
  5002.6  784.16  5006.2  783.09  5006.5  782.59  5010.0  782.59  5010.2  783.09
  5013.8  785.64  5022.2  786.13  5030.6  785.27  5036.2  787.64  5052.9  789.99
  5066.9  795.30  5075.3  796.74  5080.9  798.77  5103.3  801.27  5111.6  801.58
#Mann=4,-1,0
  4695.7    0.12       0  4905.1    0.05       0  5006.2   0.033       0
  5010.2    0.05       0
Bank Sta=5006.2,5010.2
Exp/Cntr=0.3,0.1

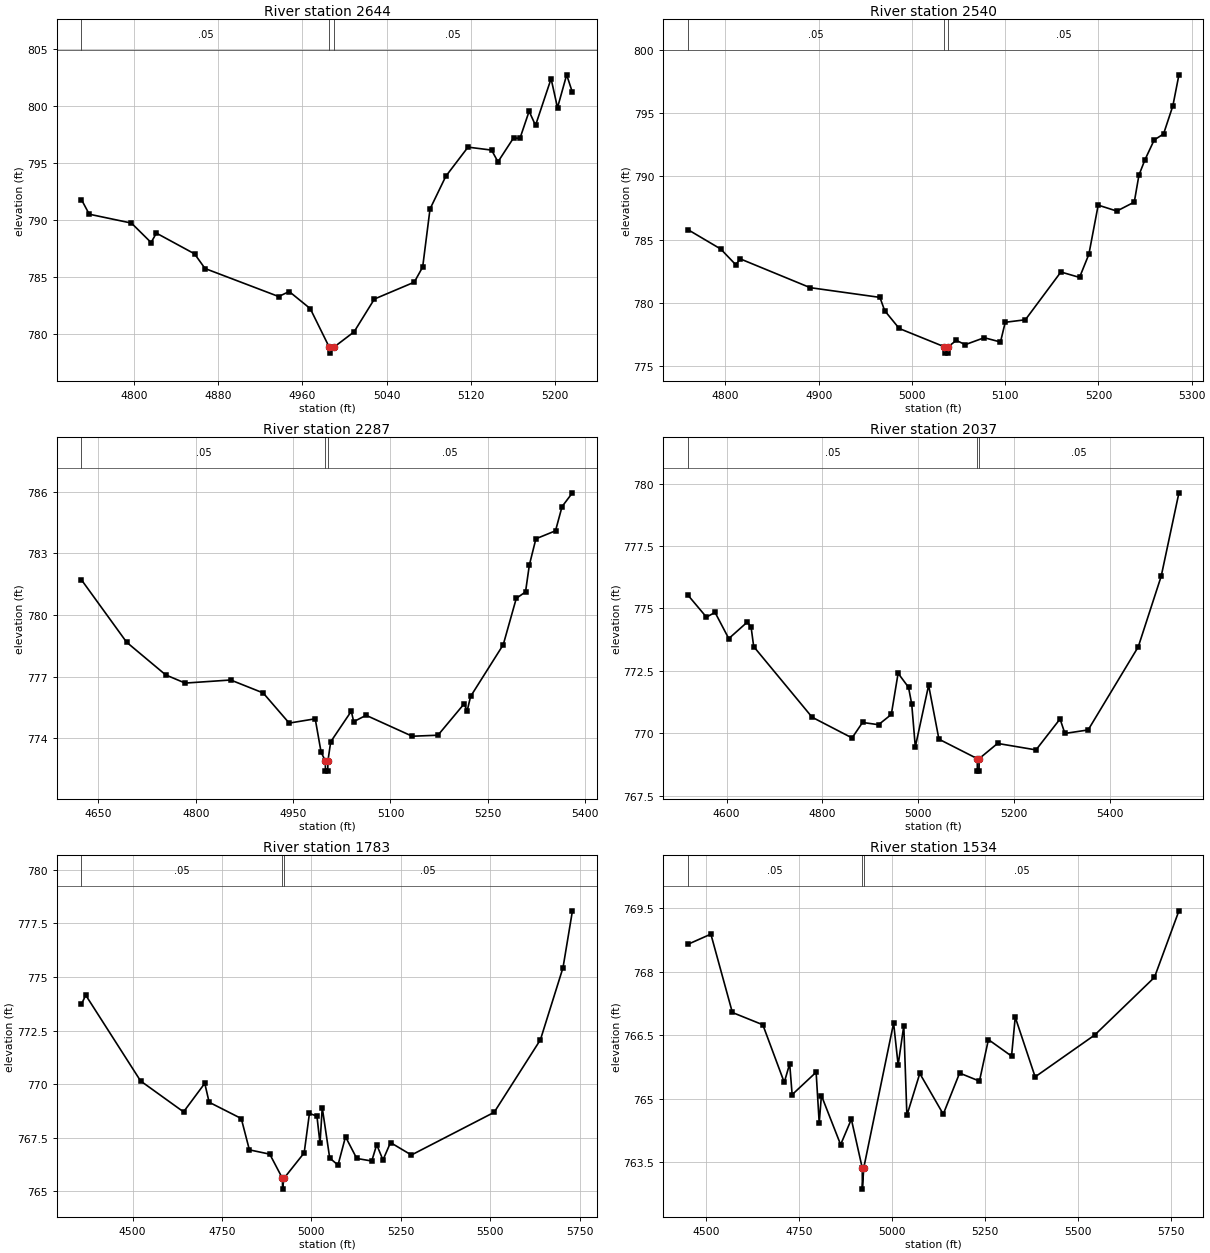
Type RM Length L Ch R = 1,2644,104,104,104
BEGIN DESCRIPTION:
Mapping XS 133b982a
END DESCRIPTION:
XS GIS Cut Line= 5
      2293176.43      7166843.02      2292950.80      7166849.41
      2292887.01      7166861.76      2292813.76      7166910.86
      2292763.03      7166982.67
#Sta/Elev= 30
  4749.9  791.77  4757.3  790.49  4797.4  789.71  4816.1  788.00  4821.1  788.83
  4857.4  787.01  4867.4  785.72  4937.4  783.26  4947.4  783.70  4967.4  782.20
  4985.6  778.79  4985.9  778.29  4989.6  778.79  5009.1  780.16  5028.4  783.04
  5066.3  784.52  5074.3  785.85  5081.3  790.95  5096.3  793.82  5117.4  796.38
  5139.8  796.12  5145.9  795.09  5160.7  797.19  5166.8  797.15  5175.5  799.53
  5181.6  798.29  5196.4  802.39  5202.5  799.84  5211.2  802.73  5216.7  801.18
#Mann=3,-1,0
  4749.9    0.05       0  4985.6   0.033       0  4989.6    0.05       0
Bank Sta=4985.6,4989.6
Exp/Cntr=0.3,0.1

Type RM Length L Ch R = 1,2540,253,253,253
BEGIN DESCRIPTION:
Mapping XS 6d15abde
END DESCRIPTION:
XS GIS Cut Line= 4
      2293113.80      7166738.39      2292846.08      7166772.52
      2292758.61      7166788.97      2292765.93      7166956.51
#Sta/Elev= 30
  4759.8  785.78  4794.9  784.25  4811.0  783.01  4816.1  783.46  4890.9  781.19
  4965.7  780.42  4970.8  779.37  4986.4  777.96  5034.9  776.51  5035.1  776.01
  5038.6  776.01  5038.9  776.51  5047.6  777.02  5057.2  776.68  5077.6  777.23
  5095.0  776.89  5100.1  778.45  5121.7  778.65  5159.8  782.43  5179.8  782.00
  5189.8  783.83  5199.8  787.72  5219.8  787.25  5238.5  787.96  5243.5  790.09
  5249.9  791.30  5259.9  792.88  5269.9  793.35  5279.9  795.58  5286.4  798.03
#Mann=3,-1,0
  4759.8    0.05       0  5034.9    0.04       0  5038.9    0.05       0
Bank Sta=5034.9,5038.9
Exp/Cntr=0.3,0.1

Type RM Length L Ch R = 1,2287,250,250,250
BEGIN DESCRIPTION:
Mapping XS f19e340f
END DESCRIPTION:
XS GIS Cut Line= 4
      2293058.49      7166631.66      2292685.84      7166610.56
      2292663.60      7166651.51      2292625.76      7166985.93
#Sta/Elev= 30
  4624.0  781.71  4693.6  778.67  4753.7  777.08  4783.7  776.68  4853.9  776.83
  4903.9  776.20  4944.0  774.73  4984.1  774.94  4993.2  773.31  4999.7  772.89
  4999.9  772.39  5003.4  772.39  5003.7  772.89  5008.0  773.82  5039.7  775.31
  5043.4  774.80  5062.5  775.11  5133.6  774.09  5173.2  774.14  5213.3  775.66
  5218.3  775.34  5223.5  776.03  5273.8  778.55  5293.9  780.81  5308.1  781.12
  5314.0  782.43  5324.1  783.71  5354.3  784.10  5364.4  785.28  5380.4  785.95
#Mann=3,-1,0
  4624.0    0.05       0  4999.7    0.04       0  5003.7    0.05       0
Bank Sta=4999.7,5003.7
Exp/Cntr=0.3,0.1

Type RM Length L Ch R = 1,2037,254,254,254
BEGIN DESCRIPTION:
Mapping XS ead92348
END DESCRIPTION:
XS GIS Cut Line= 4
      2292932.14      7166539.40      2292571.76      7166379.75
      2292465.07      7166497.83      2292512.89      7166966.79
#Sta/Elev= 30
  4519.3  775.53  4557.9  774.65  4575.8  774.84  4604.5  773.79  4643.1  774.45
  4651.1  774.25  4656.5  773.47  4778.4  770.64  4861.8  769.81  4883.7  770.43
  4917.0  770.34  4943.7  770.75  4957.9  772.40  4979.6  771.84  4986.3  771.17
  4993.8  769.45  5021.6  771.92  5043.1  769.76  5123.1  768.98  5123.3  768.48
  5126.8  768.48  5127.1  768.98  5165.5  769.59  5245.7  769.33  5295.9  770.57
  5306.0  769.99  5354.5  770.13  5459.1  773.46  5507.0  776.29  5544.0  779.63
#Mann=3,-1,0
  4519.3    0.05       0  5123.1   0.033       0  5127.1    0.05       0
Bank Sta=5123.1,5127.1
Exp/Cntr=0.3,0.1

Type RM Length L Ch R = 1,1783,249,249,249
BEGIN DESCRIPTION:
Mapping XS 3b616adc
END DESCRIPTION:
XS GIS Cut Line= 4
      2292872.74      7166471.60      2292375.26      7166204.43
      2292290.38      7166324.90      2292489.52      7166955.14
#Sta/Elev= 30
  4357.1  773.73  4369.0  774.15  4522.5  770.15  4642.6  768.71  4701.9  770.04
  4714.1  769.16  4804.0  768.40  4826.7  766.94  4883.7  766.74  4919.2  765.61
  4919.4  765.11  4923.2  765.61  4979.9  766.80  4994.6  768.64  5015.6  768.51
  5024.2  767.24  5030.4  768.91  5051.3  766.56  5074.5  766.23  5095.5  767.55
  5126.9  766.54  5168.9  766.42  5182.7  767.18  5200.3  766.47  5221.3  767.28
  5279.7  766.70  5511.2  768.69  5640.5  772.07  5703.7  775.43  5730.1  778.08
#Mann=3,-1,0
  4357.1    0.05       0  4919.2   0.035       0  4923.2    0.05       0
Bank Sta=4919.2,4923.2
Exp/Cntr=0.3,0.1

Type RM Length L Ch R = 1,1534,246,246,246
BEGIN DESCRIPTION:
Mapping XS 233e3e5e
END DESCRIPTION:
XS GIS Cut Line= 4
      2292589.79      7166285.61      2292191.17      7166032.26
      2292124.71      7166135.48      2292398.53      7166806.70
#Sta/Elev= 30
  4451.8  768.65  4513.4  768.89  4571.2  767.04  4653.1  766.75  4710.7  765.39
  4725.3  765.83  4731.9  765.10  4796.4  765.63  4804.7  764.43  4810.6  765.08
  4862.3  763.92  4891.1  764.52  4920.4  763.37  4920.7  762.87  4924.4  763.37
  5004.7  766.79  5016.9  765.80  5032.1  766.73  5040.4  764.61  5075.1  765.60
  5138.2  764.64  5182.1  765.61  5235.5  765.42  5259.6  766.40  5321.8  766.01
  5331.7  766.93  5385.2  765.52  5545.6  766.51  5706.0  767.87  5771.8  769.44
#Mann=3,-1,0
  4451.8    0.05       0  4920.4   0.033       0  4924.4    0.05       0
Bank Sta=4920.4,4924.4
Exp/Cntr=0.3,0.1

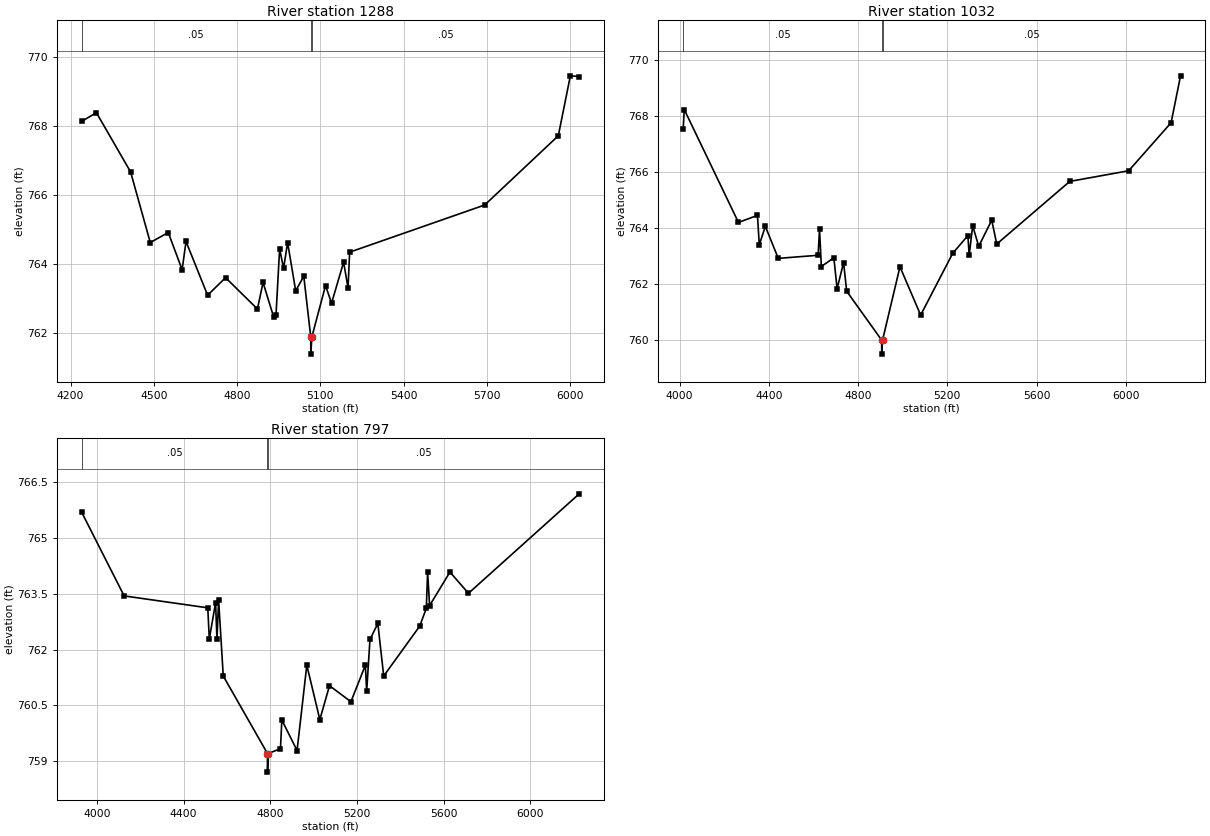
Type RM Length L Ch R = 1,1288,256,256,256
BEGIN DESCRIPTION:
Mapping XS 12421e36
END DESCRIPTION:
XS GIS Cut Line= 4
      2292570.81      7166223.09      2292044.90      7165833.39
      2291934.40      7165980.32      2292399.16      7166813.57
#Sta/Elev= 30
  4240.4  768.14  4293.1  768.39  4416.3  766.67  4487.2  764.62  4552.0  764.91
  4602.0  763.83  4616.0  764.65  4693.8  763.09  4758.5  763.60  4873.3  762.69
  4893.6  763.46  4932.1  762.45  4940.4  762.53  4953.3  764.44  4967.5  763.87
  4982.1  764.62  5011.2  763.22  5040.4  763.64  5065.5  761.88  5065.7  761.38
  5069.5  761.88  5118.8  763.37  5140.5  762.86  5183.9  764.05  5199.9  763.30
  5205.6  764.34  5692.4  765.71  5957.6  767.72  6001.0  769.46  6032.9  769.44
#Mann=3,-1,0
  4240.4    0.05       0  5065.5   0.035       0  5069.5    0.05       0
Bank Sta=5065.5,5069.5
Exp/Cntr=0.3,0.1

Type RM Length L Ch R = 1,1032,235,235,235
BEGIN DESCRIPTION:
Mapping XS 427b02a7
END DESCRIPTION:
XS GIS Cut Line= 4
      2292560.41      7166176.25      2291861.51      7165639.34
      2291770.55      7165794.26      2292372.34      7166796.37
#Sta/Elev= 30
  4015.7  767.51  4020.8  768.22  4263.7  764.20  4348.9  764.45  4357.1  763.40
  4384.2  764.06  4442.2  762.92  4620.8  763.03  4627.1  763.96  4635.3  762.63
  4691.4  762.94  4706.0  761.84  4735.0  762.77  4748.9  761.75  4905.7  760.01
  4906.0  759.51  4909.7  760.01  4987.8  762.62  5080.5  760.90  5224.3  763.10
  5292.3  763.73  5298.1  763.03  5313.7  764.08  5340.9  763.35  5399.2  764.28
  5421.6  763.43  5748.9  765.66  6013.2  766.04  6203.2  767.75  6245.6  769.42
#Mann=3,-1,0
  4015.7    0.05       0  4905.7   0.035       0  4909.7    0.05       0
Bank Sta=4905.7,4909.7
Exp/Cntr=0.3,0.1

Type RM Length L Ch R = 1,797,0,0,0
BEGIN DESCRIPTION:
MDE S 052 11.0
END DESCRIPTION:
XS GIS Cut Line= 4
      2292472.06      7166071.46      2291688.71      7165476.56
      2291615.24      7165626.47      2292234.85      7166589.84
#Sta/Elev= 30
  3930.1  765.68  4125.6  763.44  4511.6  763.12  4518.7  762.28  4547.7  763.26
  4554.0  762.27  4561.8  763.32  4583.1  761.29  4787.1  759.21  4787.3  758.71
  4791.1  759.21  4847.2  759.34  4853.5  760.11  4923.8  759.29  4968.8  761.58
  5028.9  760.12  5073.5  761.03  5172.4  760.60  5239.1  761.58  5245.1  760.88
  5260.3  762.27  5296.6  762.70  5323.7  761.29  5490.1  762.63  5520.4  763.11
  5526.4  764.07  5535.6  763.18  5629.4  764.08  5715.0  763.51  6226.1  766.18
#Mann=3,-1,0
  3930.1    0.05       0  4787.1   0.033       0  4791.1    0.05       0
Bank Sta=4787.1,4791.1
Exp/Cntr=0.3,0.1

Chan Stop Cuts=-1