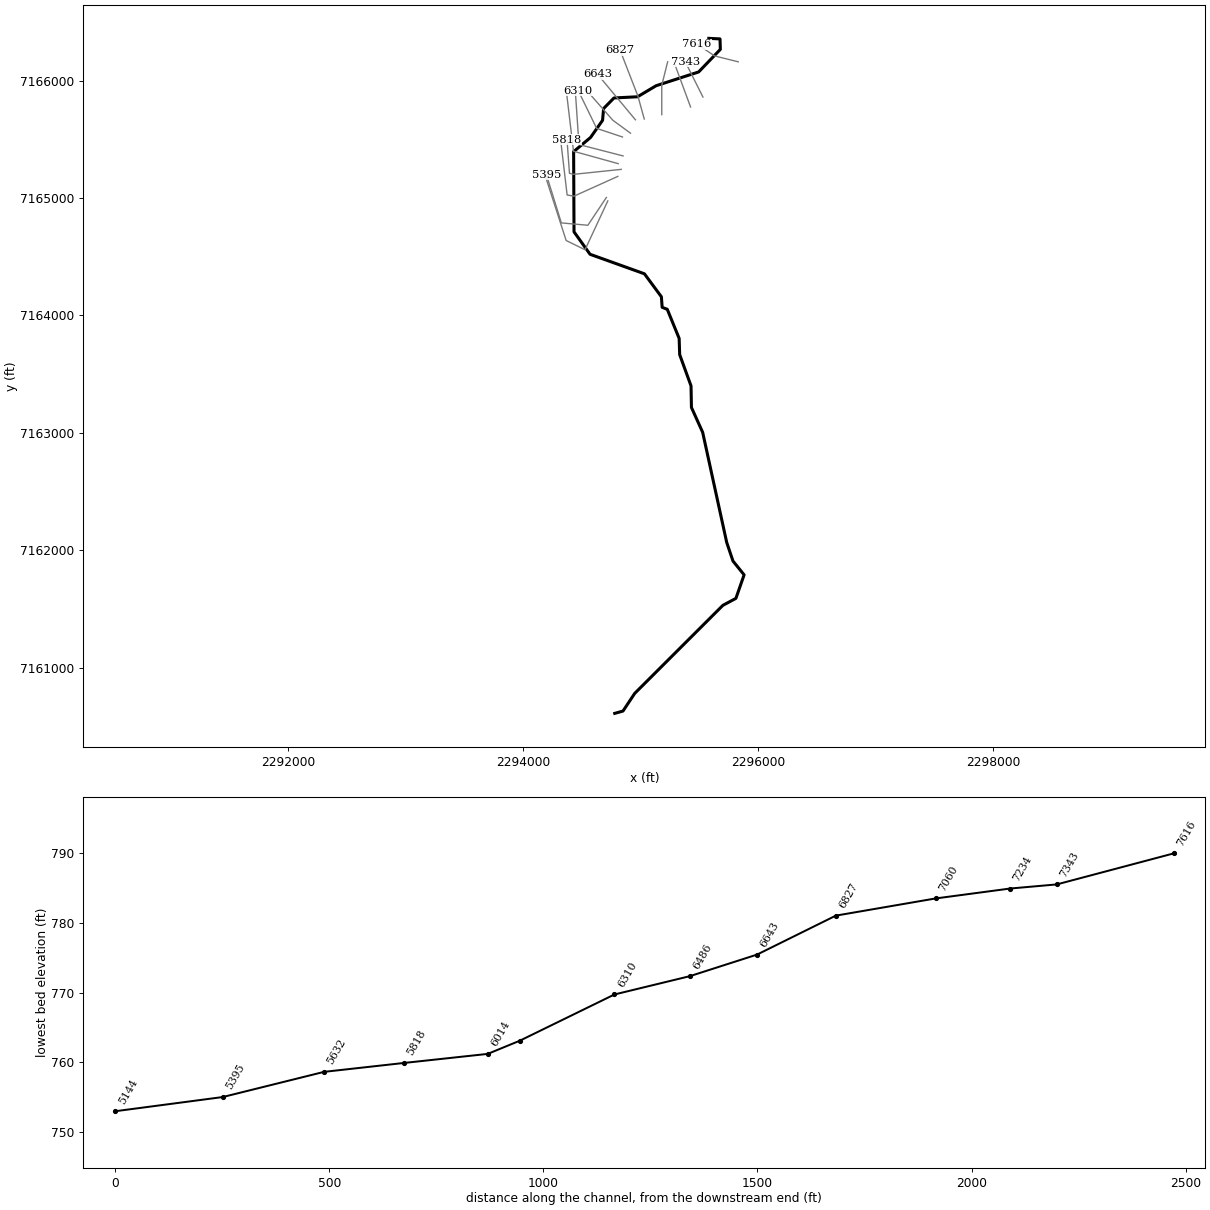
--- MDE S 053.prj (project) ---

Proj Title=MDE S 053 Base Level Engineering
Current Plan=p01
Default Exp/Contr=0.3,0.1
English Units
Geom File=g01
Flow File=f01
Plan File=p01
BEGIN DESCRIPTION:
MDE S 053
END DESCRIPTION:

--- MDE S 053.p01 (plan) ---

Plan Title=Multiple Run
Short Identifier=Multiple
Geom File=g01
Flow File=f01
Subcritical Flow
K Sum by GR= 0
Std Step Tol= 0.01
Critical Tol= 0.01
Num of Std Step Trials= 20
Max Error Tol= 0.3
Flow Tol Ratio= 0.001
Split Flow NTrial= 30
Split Flow Tol= 0.02
Split Flow Ratio= 0.02
Log Output Level= 0
Friction Slope Method= 1
Unsteady Friction Slope Method= 2
Unsteady Bridges Friction Slope Method= 1
Parabolic Critical Depth
Global Vel Dist=  1 , 1 , 1
Global Log Level= 0
CheckData=True
Encroach Param= -1, 0, 0, 0
BEGIN DESCRIPTION:
Multiple Run
END DESCRIPTION:

--- MDE S 053.f01 (steady flow) ---

Flow Title=Multiple
Number of Profiles=7
Profile Names=10-year,25-year,50-year,1pct_min,100-year,1pct_plu,500-year
River Rch & RM= MDE S 053,Reach-1,7616
     343     456     548     329     656    1309     938
Boundary for River Rch & Prof#=MDE S 053,Reach-1,1
Up Type=0
Dn Type=3
Dn Slope=0.005
Boundary for River Rch & Prof#=MDE S 053,Reach-1,2
Up Type=0
Dn Type=3
Dn Slope=0.005
Boundary for River Rch & Prof#=MDE S 053,Reach-1,3
Up Type=0
Dn Type=3
Dn Slope=0.005
Boundary for River Rch & Prof#=MDE S 053,Reach-1,4
Up Type=0
Dn Type=3
Dn Slope=0.005
Boundary for River Rch & Prof#=MDE S 053,Reach-1,5
Up Type=0
Dn Type=3
Dn Slope=0.005
Boundary for River Rch & Prof#=MDE S 053,Reach-1,6
Up Type=0
Dn Type=3
Dn Slope=0.005
Boundary for River Rch & Prof#=MDE S 053,Reach-1,7
Up Type=0
Dn Type=3
Dn Slope=0.005

--- MDE S 053.g01 (geometry) ---

Geom Title=Existing Conditions

River Reach=MDE S 053,Reach-1
Reach XY= 30
      2295579.00      7166360.00      2295674.31      7166355.18
      2295677.09      7166265.97      2295492.54      7166073.54
      2295130.56      7165956.24      2294973.07      7165862.24
      2294772.79      7165852.20      2294684.52      7165762.44
      2294675.37      7165661.50      2294573.38      7165515.62
      2294429.38      7165394.85      2294432.75      7164711.55
      2294569.19      7164520.51      2295031.55      7164354.27
      2295175.71      7164158.64      2295182.23      7164068.69
      2295225.78      7164051.84      2295326.75      7163804.07
      2295331.27      7163665.94      2295427.78      7163399.49
      2295431.26      7163215.94      2295526.73      7163004.06
      2295731.27      7162065.94      2295784.54      7161907.58
      2295879.21      7161789.95      2295809.38      7161589.53
      2295698.84      7161530.38      2294948.78      7160780.13
      2294849.14      7160629.76      2294779.00      7160610.00

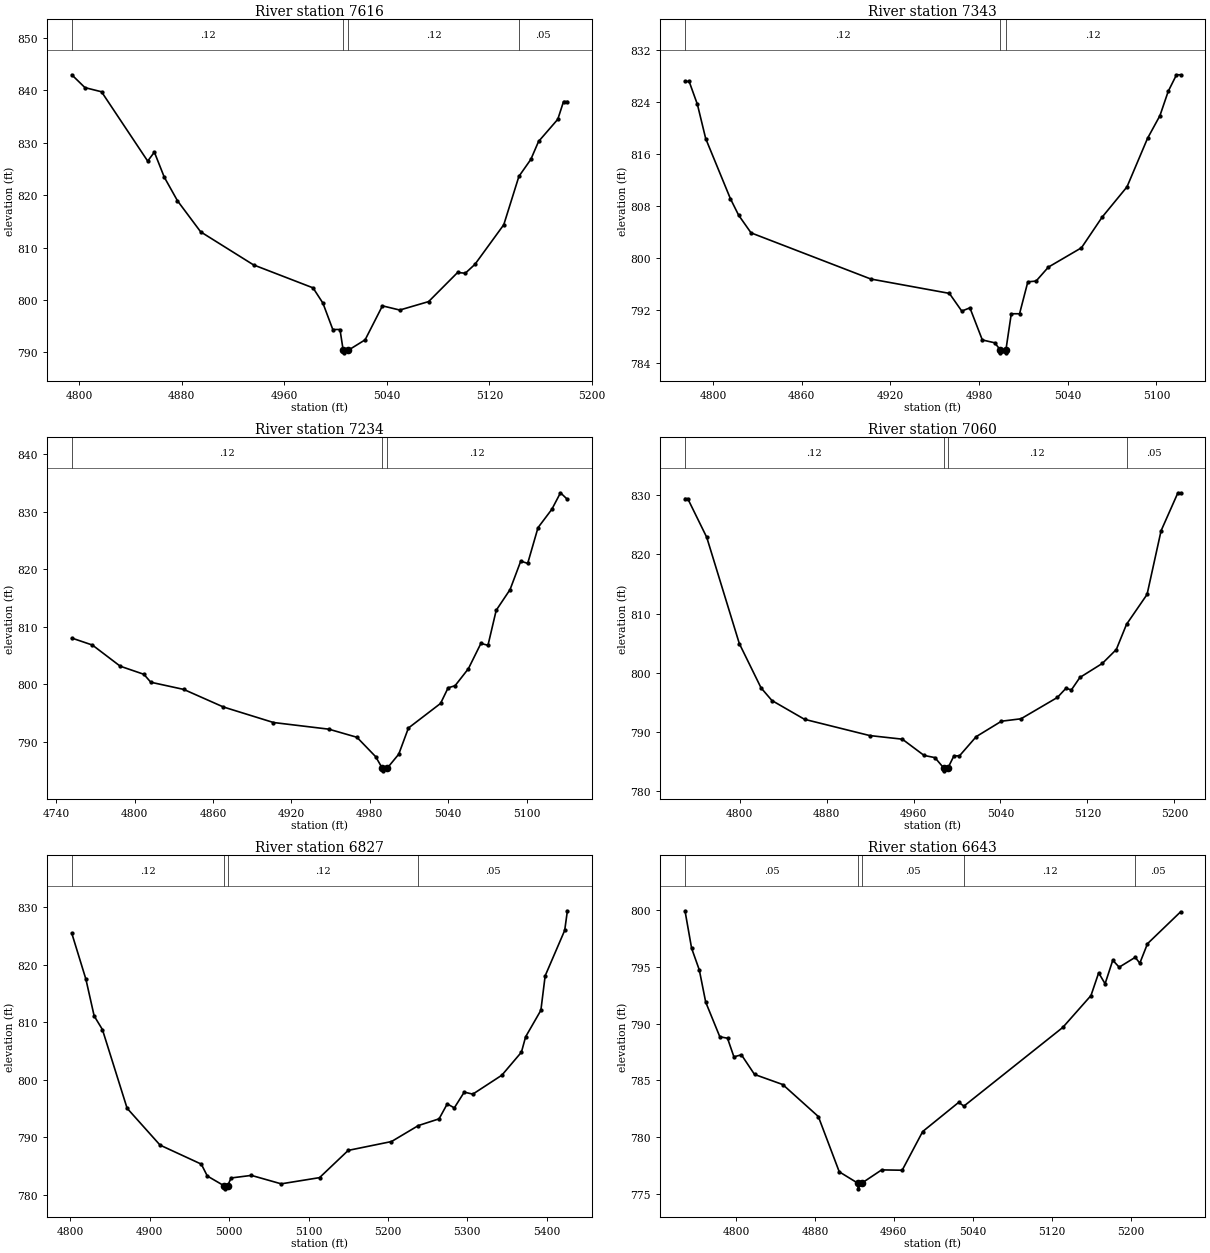
Type RM Length L Ch R = 1,7616,273,273,273
BEGIN DESCRIPTION:
MDE S 053 7.0
END DESCRIPTION:
XS GIS Cut Line= 3
      2295828.97      7166160.01      2295629.00      7166210.00
      2295479.00      7166310.00
#Sta/Elev= 30
  4794.4  842.95  4804.7  840.50  4817.6  839.71  4853.6  826.49  4858.8  828.20
  4866.5  823.44  4876.8  818.93  4894.9  813.00  4936.1  806.70  4982.5  802.32
  4990.2  799.41  4997.9  794.38  5003.5  794.38  5006.0  790.43  5006.3  789.93
  5010.0  790.43  5023.1  792.41  5036.6  798.89  5050.1  798.09  5072.6  799.70
  5095.2  805.25  5101.2  805.11  5108.7  806.80  5131.2  814.36  5143.0  823.58
  5152.3  826.82  5158.3  830.23  5173.3  834.46  5177.8  837.85  5180.8  837.85
#Mann=4,-1,0
  4794.4    0.12       0  5006.0    0.07       0  5010.0    0.12       0
  5143.0    0.05       0
Bank Sta=5006,5010
Exp/Cntr=0.3,0.1

Type RM Length L Ch R = 1,7343,109,109,109
BEGIN DESCRIPTION:
MDE S 053 6.0
END DESCRIPTION:
XS GIS Cut Line= 3
      2295528.99      7165860.02      2295429.00      7166060.00
      2295379.00      7166160.01
#Sta/Elev= 30
  4781.0  827.16  4783.8  827.16  4789.4  823.63  4795.0  818.39  4811.7  809.17
  4817.3  806.62  4825.7  803.91  4906.8  796.82  4959.9  794.62  4968.3  791.90
  4973.8  792.40  4982.2  787.47  4990.6  787.03  4994.2  785.99  4994.5  785.49
  4998.0  785.49  4998.2  785.99  5001.8  791.49  5007.4  791.49  5013.0  796.39
  5018.6  796.51  5026.9  798.65  5049.3  801.62  5063.3  806.33  5080.1  810.97
  5094.0  818.42  5102.4  821.91  5108.0  825.64  5113.6  828.18  5116.4  828.18
#Mann=3,-1,0
  4781.0    0.12       0  4994.2    0.07       0  4998.2    0.12       0
Bank Sta=4994.2,4998.2
Exp/Cntr=0.3,0.1

Type RM Length L Ch R = 1,7234,174,174,174
BEGIN DESCRIPTION:
Mapping XS 6480f83f
END DESCRIPTION:
XS GIS Cut Line= 2
      2295423.82      7165775.16      2295292.62      7166131.15
#Sta/Elev= 30
  4751.9  808.01  4767.7  806.79  4789.0  803.11  4807.1  801.70  4812.4  800.32
  4837.6  799.07  4868.0  796.01  4906.3  793.31  4948.7  792.15  4970.2  790.74
  4984.5  787.37  4989.5  785.40  4989.8  784.90  4993.5  785.40  5002.2  787.80
  5009.6  792.35  5034.2  796.63  5040.0  799.35  5045.3  799.71  5055.5  802.67
  5065.1  807.08  5070.5  806.74  5076.8  812.84  5087.4  816.44  5095.6  821.40
  5100.9  821.00  5108.8  827.22  5119.4  830.42  5126.0  833.29  5131.3  832.14
#Mann=3,-1,0
  4751.9    0.12       0  4989.5    0.07       0  4993.5    0.12       0
Bank Sta=4989.5,4993.5
Exp/Cntr=0.3,0.1

Type RM Length L Ch R = 1,7060,233,233,233
BEGIN DESCRIPTION:
MDE S 053 5.0
END DESCRIPTION:
XS GIS Cut Line= 3
      2295179.00      7165710.02      2295179.00      7165960.00
      2295228.99      7166159.97
#Sta/Elev= 30
  4749.7  829.40  4752.2  829.40  4769.7  822.87  4799.7  804.94  4819.7  797.47
  4829.7  795.34  4859.7  792.17  4919.7  789.43  4949.7  788.82  4969.7  786.08
  4979.7  785.71  4987.7  783.98  4987.9  783.48  4991.7  783.98  4997.2  786.01
  5002.3  786.01  5017.7  789.25  5040.9  791.85  5058.9  792.26  5092.4  795.86
  5100.2  797.39  5105.3  797.14  5113.1  799.23  5133.7  801.59  5146.6  803.94
  5156.0  808.19  5174.9  813.23  5187.8  823.97  5203.3  830.38  5205.8  830.38
#Mann=4,-1,0
  4749.7    0.12       0  4987.7    0.07       0  4991.7    0.12       0
  5156.0    0.05       0
Bank Sta=4987.7,4991.7
Exp/Cntr=0.3,0.1

Type RM Length L Ch R = 1,6827,184,184,184
BEGIN DESCRIPTION:
Mapping XS fd5dde0a
END DESCRIPTION:
XS GIS Cut Line= 3
      2295030.12      7165672.77      2294976.37      7165867.17
      2294823.88      7166261.10
#Sta/Elev= 30
  4801.9  825.51  4819.7  817.50  4830.1  811.11  4840.5  808.74  4871.6  795.04
  4913.1  788.63  4965.0  785.32  4972.6  783.25  4994.1  781.52  4994.4  781.02
  4998.1  781.52  5002.5  782.91  5028.1  783.36  5065.6  781.89  5113.9  782.97
  5150.0  787.71  5204.5  789.25  5238.3  792.03  5264.4  793.20  5274.7  795.80
  5283.6  795.11  5296.1  797.85  5306.9  797.50  5343.5  800.80  5368.1  804.80
  5373.4  807.48  5392.6  812.09  5398.0  818.09  5422.6  826.00  5426.0  829.41
#Mann=4,-1,0
  4801.9    0.12       0  4994.1    0.07       0  4998.1    0.12       0
  5238.3    0.05       0
Bank Sta=4994.1,4998.1
Exp/Cntr=0.3,0.1

Type RM Length L Ch R = 1,6643,157,157,157
BEGIN DESCRIPTION:
Mapping XS 974f03f9
END DESCRIPTION:
XS GIS Cut Line= 2
      2294955.05      7165666.03      2294633.92      7166052.53
#Sta/Elev= 30
  4748.3  799.94  4755.0  796.64  4762.8  794.73  4769.3  791.89  4783.6  788.84
  4791.4  788.71  4797.9  787.07  4805.5  787.25  4818.8  785.52  4847.4  784.63
  4883.5  781.81  4904.7  776.94  4923.5  775.94  4923.8  775.44  4927.5  775.94
  4947.7  777.11  4968.5  777.08  4989.3  780.49  5025.8  783.06  5031.1  782.73
  5131.3  789.66  5159.9  792.47  5167.7  794.47  5174.2  793.51  5182.0  795.58
  5188.5  794.97  5204.8  795.84  5209.4  795.32  5217.2  797.04  5250.8  799.85
#Mann=5,-1,0
  4748.3    0.05       0  4923.5    0.05       0  4927.5    0.05       0
  5031.1    0.12       0  5204.8    0.05       0
Bank Sta=4923.5,4927.5
Exp/Cntr=0.3,0.1

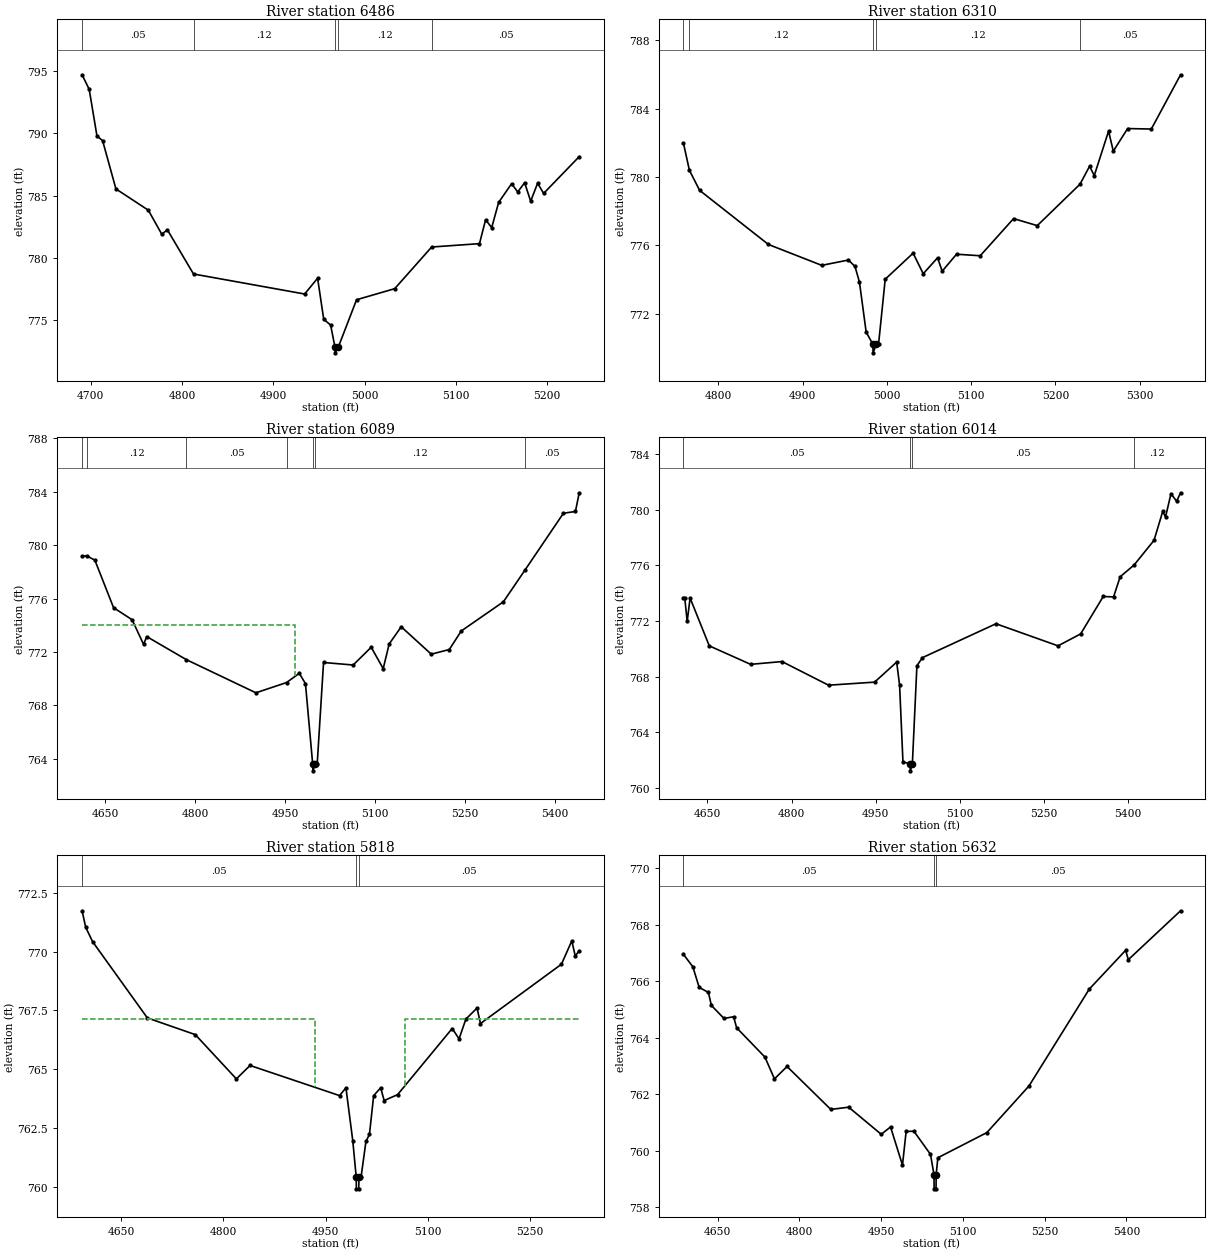
Type RM Length L Ch R = 1,6486,176,176,176
BEGIN DESCRIPTION:
Mapping XS b25546c7
END DESCRIPTION:
XS GIS Cut Line= 3
      2294912.80      7165552.22      2294763.03      7165662.10
      2294526.49      7165932.22
#Sta/Elev= 30
  4690.5  794.71  4698.3  793.54  4706.8  789.79  4713.0  789.41  4727.6  785.53
  4763.1  783.82  4777.8  781.89  4784.0  782.24  4812.6  778.69  4934.4  777.08
  4948.6  778.35  4955.3  775.05  4962.9  774.58  4967.5  772.85  4967.8  772.35
  4971.5  772.85  4991.3  776.62  5033.1  777.51  5073.6  780.86  5126.0  781.13
  5132.7  783.05  5139.4  782.42  5147.0  784.45  5161.2  785.95  5167.9  785.29
  5175.5  786.03  5182.1  784.54  5189.7  785.99  5196.3  785.17  5235.3  788.13
#Mann=5,-1,0
  4690.5    0.05       0  4812.6    0.12       0  4967.5    0.07       0
  4971.5    0.12       0  5073.6    0.05       0
Bank Sta=4967.5,4971.5
Exp/Cntr=0.3,0.1

Type RM Length L Ch R = 1,6310,221,221,221
BEGIN DESCRIPTION:
Mapping XS 020c39bc
END DESCRIPTION:
XS GIS Cut Line= 3
      2294844.65      7165519.71      2294625.12      7165593.07
      2294468.40      7165915.32
#Sta/Elev= 30
  4758.7  781.98  4765.8  780.39  4777.9  779.22  4859.5  776.06  4922.8  774.84
  4954.4  775.15  4962.2  774.78  4967.5  773.87  4975.5  770.94  4983.5  770.23
  4983.7  769.73  4987.5  770.23  4990.2  770.23  4998.1  774.03  5031.2  775.55
  5043.2  774.35  5060.2  775.28  5065.7  774.50  5082.7  775.49  5110.8  775.40
  5150.4  777.57  5178.5  777.16  5229.2  779.58  5240.6  780.63  5246.1  780.08
  5263.1  782.68  5268.7  781.51  5285.7  782.83  5313.8  782.80  5348.5  785.97
#Mann=5,-1,0
  4758.7    0.05       0  4765.8    0.12       0  4983.5    0.07       0
  4987.5    0.12       0  5229.2    0.05       0
Bank Sta=4983.5,4987.5
Exp/Cntr=0.3,0.1

Type RM Length L Ch R = 1,6089,75,75,75
BEGIN DESCRIPTION:
Mapping XS d4bdf9d6
END DESCRIPTION:
XS GIS Cut Line= 3
      2294849.78      7165358.41      2294474.76      7165455.30
      2294444.73      7165896.24
#Sta/Elev= 30
  4611.6  779.19  4619.6  779.19  4632.9  778.88  4664.1  775.32  4695.0  774.42
  4714.2  772.57  4719.4  773.16  4785.6  771.43  4901.6  768.95  4952.8  769.72
  4973.9  770.41  4984.2  769.64  4996.3  763.61  4996.6  763.11  5000.3  763.61
  5003.8  763.61  5014.4  771.22  5063.8  771.03  5093.9  772.36  5113.9  770.76
  5123.9  772.61  5144.0  773.89  5194.1  771.84  5224.2  772.19  5244.2  773.58
  5314.4  775.76  5350.8  778.16  5414.6  782.39  5434.6  782.52  5440.9  783.92
#Mann=7,-1,0
  4611.6    0.05       0  4619.6    0.12       0  4785.6    0.05       0
  4952.8    0.12       0  4996.3    0.07       0  5000.3    0.12       0
  5350.8    0.05       0
#XS Ineff=2,0
    0.00 4966.80  774.06               0
Permanent Ineff=
       F       F
Bank Sta=4996.3,5000.3
Exp/Cntr=0.3,0.1

Type RM Length L Ch R = 1,6014,196,196,196
BEGIN DESCRIPTION:
Mapping XS 18ae298d
END DESCRIPTION:
XS GIS Cut Line= 3
      2294808.36      7165292.64      2294428.30      7165398.21
      2294370.30      7165886.93
#Sta/Elev= 30
  4607.1  773.68  4609.4  773.68  4613.8  771.97  4619.0  773.65  4653.2  770.21
  4726.9  768.88  4782.9  769.08  4865.9  767.38  4948.0  767.60  4987.4  769.04
  4992.6  767.39  4998.6  761.87  5011.4  761.72  5011.7  761.22  5015.4  761.72
  5023.5  768.78  5033.3  769.36  5164.5  771.80  5275.2  770.21  5315.5  771.07
  5355.8  773.76  5374.2  773.73  5386.0  775.18  5410.7  776.02  5446.4  777.80
  5461.9  779.88  5466.9  779.48  5476.6  781.15  5486.7  780.61  5493.7  781.22
#Mann=4,-1,0
  4607.1    0.05       0  5011.4    0.07       0  5015.4    0.05       0
  5410.7    0.12       0
Bank Sta=5011.4,5015.4
Exp/Cntr=0.3,0.1

Type RM Length L Ch R = 1,5818,186,186,186
BEGIN DESCRIPTION:
Mapping XS 5fb3e960
END DESCRIPTION:
XS GIS Cut Line= 4
      2294834.27      7165243.83      2294429.95      7165201.58
      2294393.99      7165210.37      2294373.22      7165495.98
#Sta/Elev= 30
  4592.5  771.73  4597.8  771.03  4607.9  770.42  4688.3  767.18  4758.7  766.47
  4819.0  764.59  4839.1  765.16  4970.5  763.88  4979.9  764.21  4989.9  761.97
  4995.0  760.42  4995.2  759.92  4998.7  759.92  4999.0  760.42  5002.1  760.42
  5009.3  761.94  5014.4  762.23  5020.6  763.88  5030.9  764.21  5036.0  763.67
  5055.7  763.92  5135.9  766.73  5146.0  766.29  5156.0  767.13  5172.4  767.60
  5177.4  766.94  5296.3  769.46  5311.5  770.45  5316.6  769.81  5322.4  770.03
#Mann=3,-1,0
  4592.5    0.05       0  4995.0    0.04       0  4999.0    0.05       0
#XS Ineff=2,0
    0.00 4933.80  767.15 5066.20    0.00  767.15
Permanent Ineff=
       F       F
Bank Sta=4995,4999
Exp/Cntr=0.3,0.1

Type RM Length L Ch R = 1,5632,237,237,237
BEGIN DESCRIPTION:
Mapping XS e3785f8f
END DESCRIPTION:
XS GIS Cut Line= 4
      2294805.38      7165184.03      2294431.84      7165015.47
      2294374.10      7165025.57      2294322.37      7165466.22
#Sta/Elev= 30
  4587.3  766.95  4604.5  766.51  4616.2  765.78  4633.1  765.60  4638.6  765.14
  4661.7  764.68  4679.4  764.74  4684.9  764.35  4736.9  763.31  4754.3  762.54
  4777.4  762.98  4857.7  761.46  4890.5  761.54  4950.2  760.58  4967.3  760.84
  4989.2  759.49  4995.9  760.68  5010.1  760.69  5040.6  759.87  5047.0  759.15
  5047.3  758.65  5050.8  758.65  5051.0  759.15  5054.1  759.75  5144.0  760.64
  5221.3  762.29  5332.0  765.72  5398.6  767.09  5403.6  766.76  5499.4  768.49
#Mann=3,-1,0
  4587.3    0.05       0  5047.0    0.04       0  5051.0    0.05       0
Bank Sta=5047,5051
Exp/Cntr=0.3,0.1

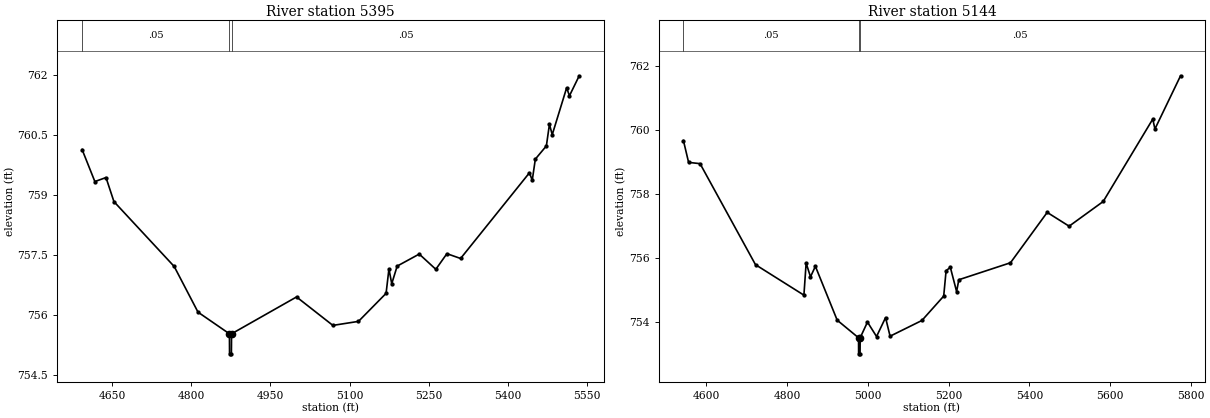
Type RM Length L Ch R = 1,5395,251,251,251
BEGIN DESCRIPTION:
Mapping XS ae483623
END DESCRIPTION:
XS GIS Cut Line= 4
      2294707.92      7165004.40      2294550.58      7164767.76
      2294324.88      7164787.85      2294197.51      7165199.42
#Sta/Elev= 30
  4593.5  760.14  4617.7  759.34  4638.8  759.44  4653.8  758.84  4768.0  757.22
  4813.1  756.08  4872.6  755.54  4872.8  755.04  4876.3  755.04  4876.6  755.54
  4999.7  756.46  5068.5  755.75  5117.0  755.85  5169.3  756.55  5174.7  757.16
  5180.0  756.79  5190.3  757.23  5232.1  757.53  5263.5  757.15  5284.5  757.54
  5310.4  757.42  5440.9  759.56  5446.1  759.37  5452.0  759.90  5472.9  760.23
  5478.7  760.77  5484.0  760.51  5511.3  761.68  5516.6  761.48  5535.1  761.98
#Mann=3,-1,0
  4593.5    0.05       0  4872.6   0.033       0  4876.6    0.05       0
Bank Sta=4872.6,4876.6
Exp/Cntr=0.3,0.1

Type RM Length L Ch R = 1,5144,0,0,0
BEGIN DESCRIPTION:
MDE S 053 1.0
END DESCRIPTION:
XS GIS Cut Line= 4
      2294720.05      7164975.27      2294526.36      7164559.13
      2294365.93      7164637.88      2294183.59      7165202.65
#Sta/Elev= 30
  4543.1  759.66  4555.9  758.98  4584.3  758.94  4721.6  755.79  4841.5  754.84
  4847.0  755.84  4857.8  755.41  4869.9  755.74  4923.9  754.06  4976.8  753.51
  4977.0  753.01  4980.5  753.01  4980.8  753.51  4998.9  754.00  5021.4  753.55
  5043.7  754.14  5054.9  753.56  5133.7  754.05  5187.7  754.81  5193.6  755.60
  5204.1  755.71  5219.7  754.95  5225.1  755.32  5353.1  755.85  5444.0  757.42
  5498.3  756.99  5582.7  757.76  5705.5  760.33  5710.8  760.02  5774.3  761.68
#Mann=3,-1,0
  4543.1    0.05       0  4976.8   0.033       0  4980.8    0.05       0
Bank Sta=4976.8,4980.8
Exp/Cntr=0.3,0.1

Chan Stop Cuts=-1