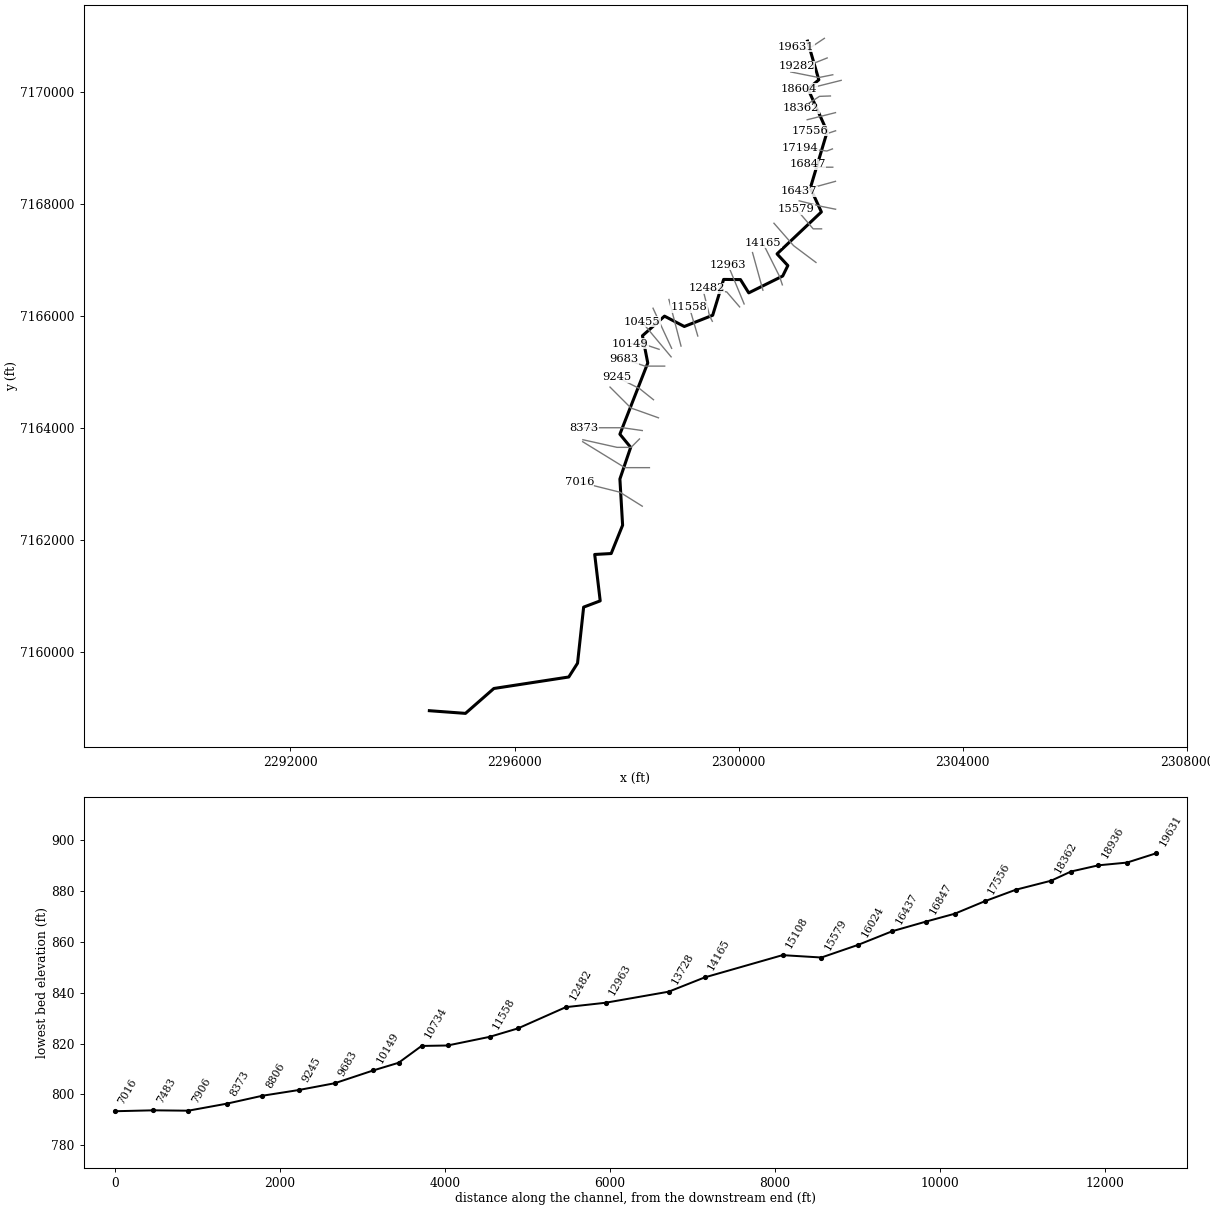
--- MDE S 054.prj (project) ---

Proj Title=MDE S 054 Base Level Engineering
Current Plan=p01
Default Exp/Contr=0.3,0.1
English Units
Geom File=g01
Flow File=f01
Plan File=p01
Y Axis Title=Elevation
X Axis Title(PF)=Main Channel Distance
X Axis Title(XS)=Station
BEGIN DESCRIPTION:
MDE S 054
END DESCRIPTION:
DSS Export Rating Curves= 0
DSS Export Rating Curve Sorted= 0
DSS Export Volume Flow Curves= 0
DXF OffsetX= 0
DXF OffsetY= 0
DXF ScaleX= 1
DXF ScaleY= 10

--- MDE S 054.p01 (plan) ---

Plan Title=Multiple Run
Short Identifier=Multiple
Geom File=g01
Flow File=f01
Subcritical Flow
K Sum by GR= 0
Std Step Tol= 0.01
Critical Tol= 0.01
Num of Std Step Trials= 20
Max Error Tol= 0.3
Flow Tol Ratio= 0.001
Split Flow NTrial= 30
Split Flow Tol= 0.02
Split Flow Ratio= 0.02
Log Output Level= 0
Friction Slope Method= 1
Unsteady Friction Slope Method= 2
Unsteady Bridges Friction Slope Method= 1
Parabolic Critical Depth
Global Vel Dist=  1 , 1 , 1
Global Log Level= 0
CheckData=True
Encroach Param= -1, 0, 0, 0
BEGIN DESCRIPTION:
Multiple Run
END DESCRIPTION:

--- MDE S 054.f01 (steady flow) ---

Flow Title=Multiple
Number of Profiles=7
Profile Names=10-year,25-year,50-year,1pct_min,100-year,1pct_plu,500-year
River Rch & RM= MDE S 054,Reach-1,19631
     716     989    1218     745    1487    2966    2217
River Rch & RM= MDE S 054,Reach-1,15579
    1126    1593    1991    1234    2463    4914    3776
River Rch & RM= MDE S 054,Reach-1,8373
    1285    1827    2290    1422    2838    5662    4369
Boundary for River Rch & Prof#=MDE S 054,Reach-1,1
Up Type=0
Dn Type=3
Dn Slope=0.005
Boundary for River Rch & Prof#=MDE S 054,Reach-1,2
Up Type=0
Dn Type=3
Dn Slope=0.005
Boundary for River Rch & Prof#=MDE S 054,Reach-1,3
Up Type=0
Dn Type=3
Dn Slope=0.005
Boundary for River Rch & Prof#=MDE S 054,Reach-1,4
Up Type=0
Dn Type=3
Dn Slope=0.005
Boundary for River Rch & Prof#=MDE S 054,Reach-1,5
Up Type=0
Dn Type=3
Dn Slope=0.005
Boundary for River Rch & Prof#=MDE S 054,Reach-1,6
Up Type=0
Dn Type=3
Dn Slope=0.005
Boundary for River Rch & Prof#=MDE S 054,Reach-1,7
Up Type=0
Dn Type=3
Dn Slope=0.005

--- MDE S 054.g01 (geometry) ---

Geom Title=Existing Conditions

River Reach=MDE S 054,Reach-1
Reach XY= 30
      2301229.00      7170910.00      2301429.87      7170220.09
      2301236.78      7170056.99      2301579.04      7169294.66
      2301278.71      7168289.81      2301475.33      7167861.58
      2300683.96      7167112.54      2300877.12      7166904.29
      2300785.21      7166717.81      2300178.98      7166417.07
      2300031.32      7166654.20      2299730.73      7166657.08
      2299535.52      7166017.68      2299029.01      7165817.07
      2298675.69      7166001.93      2298282.06      7165651.72
      2298376.94      7165165.86      2297879.38      7163894.72
      2298071.80      7163660.30      2297879.52      7163094.78
      2297927.95      7162270.43      2297723.99      7161765.00
      2297429.98      7161748.31      2297528.02      7160920.26
      2297232.43      7160808.78      2297123.53      7159807.56
      2296967.19      7159561.62      2295630.25      7159356.49
      2295123.07      7158912.26      2294479.00      7158960.00

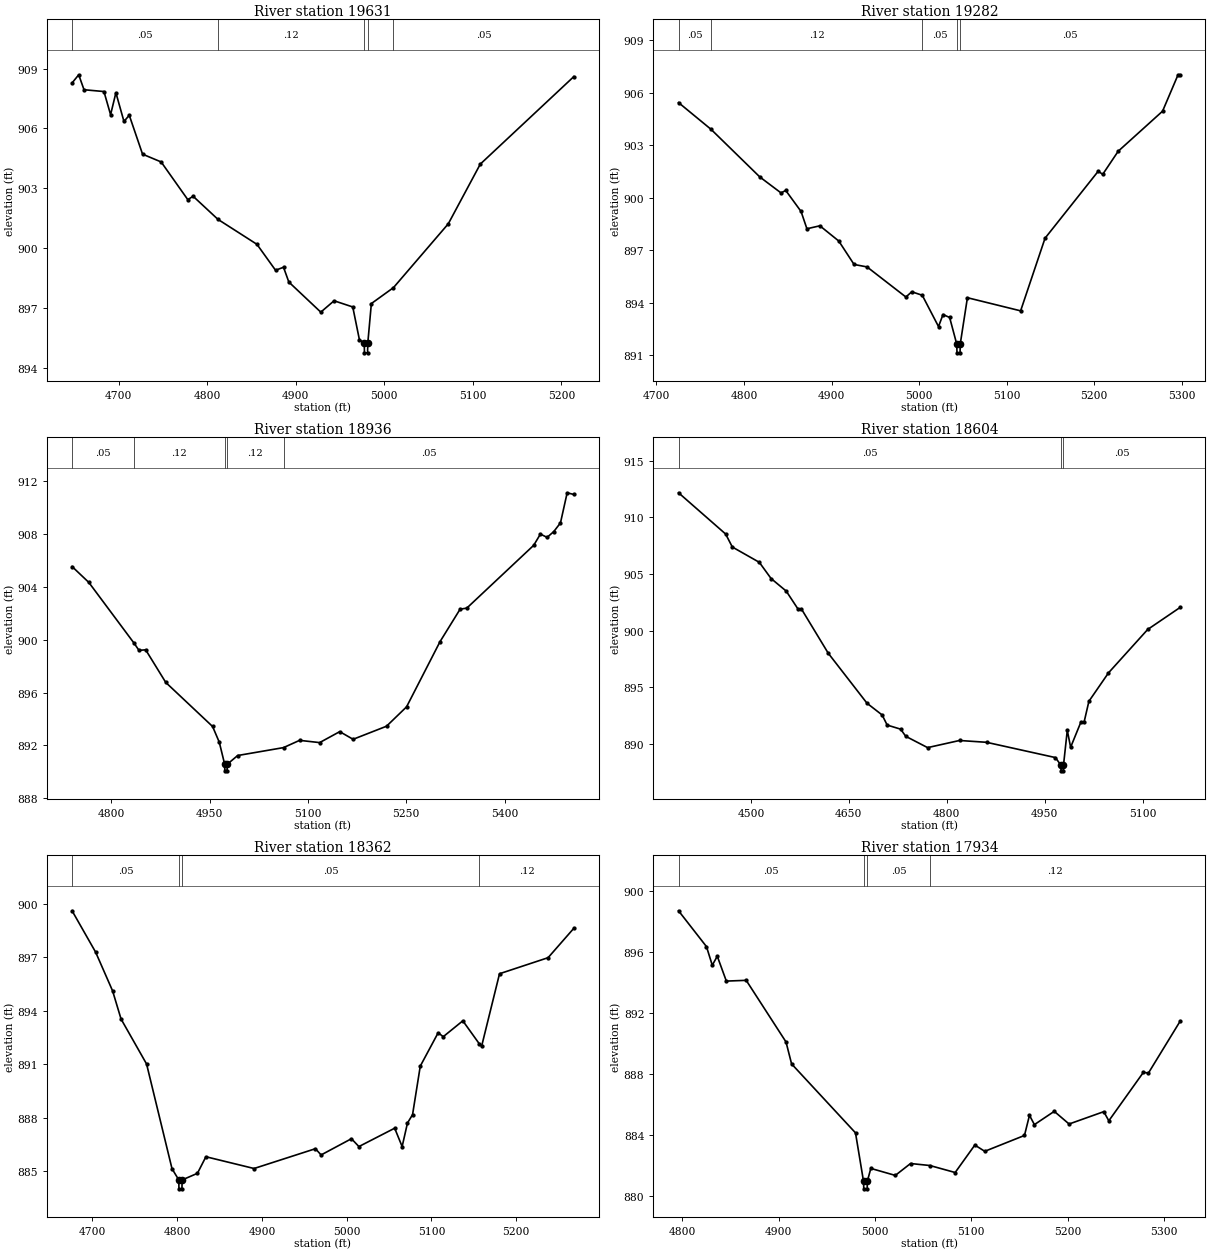
Type RM Length L Ch R = 1,19631,349,349,349
BEGIN DESCRIPTION:
MDE S 054 38.0
END DESCRIPTION:
XS GIS Cut Line= 3
      2301528.97      7170959.98      2301229.00      7170760.00
      2301028.98      7170810.01
#Sta/Elev= 30
  4647.4  908.28  4654.9  908.69  4660.9  907.94  4683.4  907.85  4690.9  906.69
  4696.9  907.79  4706.0  906.35  4712.0  906.66  4727.0  904.71  4748.0  904.32
  4778.1  902.43  4784.1  902.60  4812.2  901.44  4856.2  900.19  4877.2  898.89
  4886.2  899.04  4892.2  898.30  4928.3  896.79  4943.3  897.36  4964.4  897.05
  4971.9  895.41  4977.4  895.25  4977.6  894.75  4981.1  894.75  4981.4  895.25
  4985.4  897.22  5010.4  898.02  5072.3  901.22  5108.4  904.21  5214.1  908.60
#Mann=5,-1,0
  4647.4    0.05       0  4812.2    0.12       0  4977.4    0.07       0
  4981.4    0.12       0  5010.4    0.05       0
Bank Sta=4977.4,4981.4
Exp/Cntr=0.3,0.1

Type RM Length L Ch R = 1,19282,346,346,346
BEGIN DESCRIPTION:
MDE S 054 37.0
END DESCRIPTION:
XS GIS Cut Line= 3
      2301578.97      7170609.99      2301329.00      7170510.00
      2301028.97      7170459.99
#Sta/Elev= 30
  4725.2  905.44  4762.4  903.91  4818.1  901.19  4842.3  900.28  4847.7  900.42
  4865.2  899.22  4871.9  898.23  4886.7  898.40  4908.3  897.53  4925.8  896.19
  4940.6  896.05  4985.0  894.33  4991.7  894.63  5003.7  894.43  5022.3  892.64
  5027.4  893.33  5035.0  893.16  5043.1  891.64  5043.4  891.14  5046.9  891.14
  5047.1  891.64  5055.3  894.29  5116.1  893.54  5144.0  897.69  5204.8  901.52
  5209.9  901.34  5227.6  902.66  5278.3  904.95  5296.0  907.03  5298.6  907.03
#Mann=5,-1,0
  4725.2    0.05       0  4762.4    0.12       0  5003.7    0.05       0
  5043.1    0.07       0  5047.1    0.05       0
Bank Sta=5043.1,5047.1
Exp/Cntr=0.3,0.1

Type RM Length L Ch R = 1,18936,332,332,332
BEGIN DESCRIPTION:
MDE S 054 36.0
END DESCRIPTION:
XS GIS Cut Line= 3
      2301679.04      7170310.01      2301429.00      7170260.00
      2300928.99      7170360.00
#Sta/Elev= 30
  4740.5  905.55  4766.0  904.35  4835.2  899.73  4842.5  899.20  4852.7  899.24
  4883.3  896.77  4954.7  893.43  4964.9  892.24  4973.1  890.57  4973.3  890.07
  4976.8  890.07  4977.1  890.57  4992.9  891.23  5062.8  891.83  5087.3  892.38
  5117.9  892.21  5148.5  893.04  5168.9  892.46  5219.8  893.45  5250.4  894.92
  5301.4  899.86  5332.0  902.32  5342.2  902.40  5444.2  907.16  5454.4  908.01
  5464.6  907.76  5474.8  908.20  5485.0  908.86  5495.2  911.14  5505.4  911.01
#Mann=5,-1,0
  4740.5    0.05       0  4835.2    0.12       0  4973.1    0.07       0
  4977.1    0.12       0  5062.8    0.05       0
Bank Sta=4973.1,4977.1
Exp/Cntr=0.3,0.1

Type RM Length L Ch R = 1,18604,242,242,242
BEGIN DESCRIPTION:
MDE S 054 35.0
END DESCRIPTION:
XS GIS Cut Line= 3
      2301828.98      7170210.00      2301229.00      7170060.00
      2301079.05      7170060.00
#Sta/Elev= 30
  4389.2  912.18  4461.3  908.54  4471.6  907.39  4512.9  906.04  4530.9  904.61
  4554.1  903.50  4572.1  901.92  4577.3  901.93  4618.5  898.01  4677.8  893.60
  4701.0  892.56  4708.7  891.67  4729.3  891.31  4737.1  890.68  4770.6  889.68
  4819.5  890.31  4860.8  890.15  4966.4  888.80  4974.7  888.13  4975.0  887.63
  4978.5  887.63  4978.7  888.13  4984.5  891.21  4989.6  889.71  5005.1  891.90
  5010.1  891.90  5017.6  893.77  5047.6  896.28  5107.6  900.11  5157.6  902.07
#Mann=3,-1,0
  4389.2    0.05       0  4974.7   0.033       0  4978.7    0.05       0
Bank Sta=4974.7,4978.7
Exp/Cntr=0.3,0.1

Type RM Length L Ch R = 1,18362,428,428,428
BEGIN DESCRIPTION:
Mapping XS b3880558
END DESCRIPTION:
XS GIS Cut Line= 3
      2301636.79      7169931.50      2301440.64      7169924.27
      2301109.34      7169707.87
#Sta/Elev= 30
  4676.0  899.60  4703.8  897.28  4723.8  895.11  4733.8  893.53  4763.9  891.01
  4793.9  885.14  4801.9  884.51  4802.1  884.01  4805.6  884.01  4805.9  884.51
  4823.9  884.88  4833.9  885.81  4890.7  885.15  4963.1  886.26  4969.8  885.91
  5005.6  886.82  5014.4  886.38  5056.6  887.41  5065.4  886.38  5071.7  887.70
  5077.7  888.17  5086.8  890.89  5107.9  892.76  5113.9  892.54  5137.0  893.43
  5156.6  892.13  5159.2  892.01  5180.3  896.07  5237.6  896.97  5268.0  898.62
#Mann=4,-1,0
  4676.0    0.05       0  4801.9   0.033       0  4805.9    0.05       0
  5156.6    0.12       0
Bank Sta=4801.9,4805.9
Exp/Cntr=0.3,0.1

Type RM Length L Ch R = 1,17934,378,378,378
BEGIN DESCRIPTION:
Mapping XS acb569d5
END DESCRIPTION:
XS GIS Cut Line= 2
      2301727.09      7169633.74      2301222.19      7169506.86
#Sta/Elev= 30
  4796.2  898.69  4825.2  896.34  4831.2  895.12  4836.4  895.71  4845.8  894.08
  4866.4  894.13  4907.7  890.09  4913.5  888.65  4979.8  884.13  4988.1  880.96
  4988.4  880.46  4991.9  880.46  4992.1  880.96  4995.7  881.80  5021.1  881.34
  5036.9  882.12  5056.9  881.99  5083.2  881.53  5103.6  883.33  5113.9  882.92
  5155.1  883.96  5160.3  885.28  5165.4  884.67  5186.0  885.54  5201.4  884.71
  5237.4  885.52  5242.6  884.92  5278.5  888.10  5283.7  888.05  5316.8  891.47
#Mann=4,-1,0
  4796.2    0.05       0  4988.1   0.033       0  4992.1    0.05       0
  5056.9    0.12       0
Bank Sta=4988.1,4992.1
Exp/Cntr=0.3,0.1

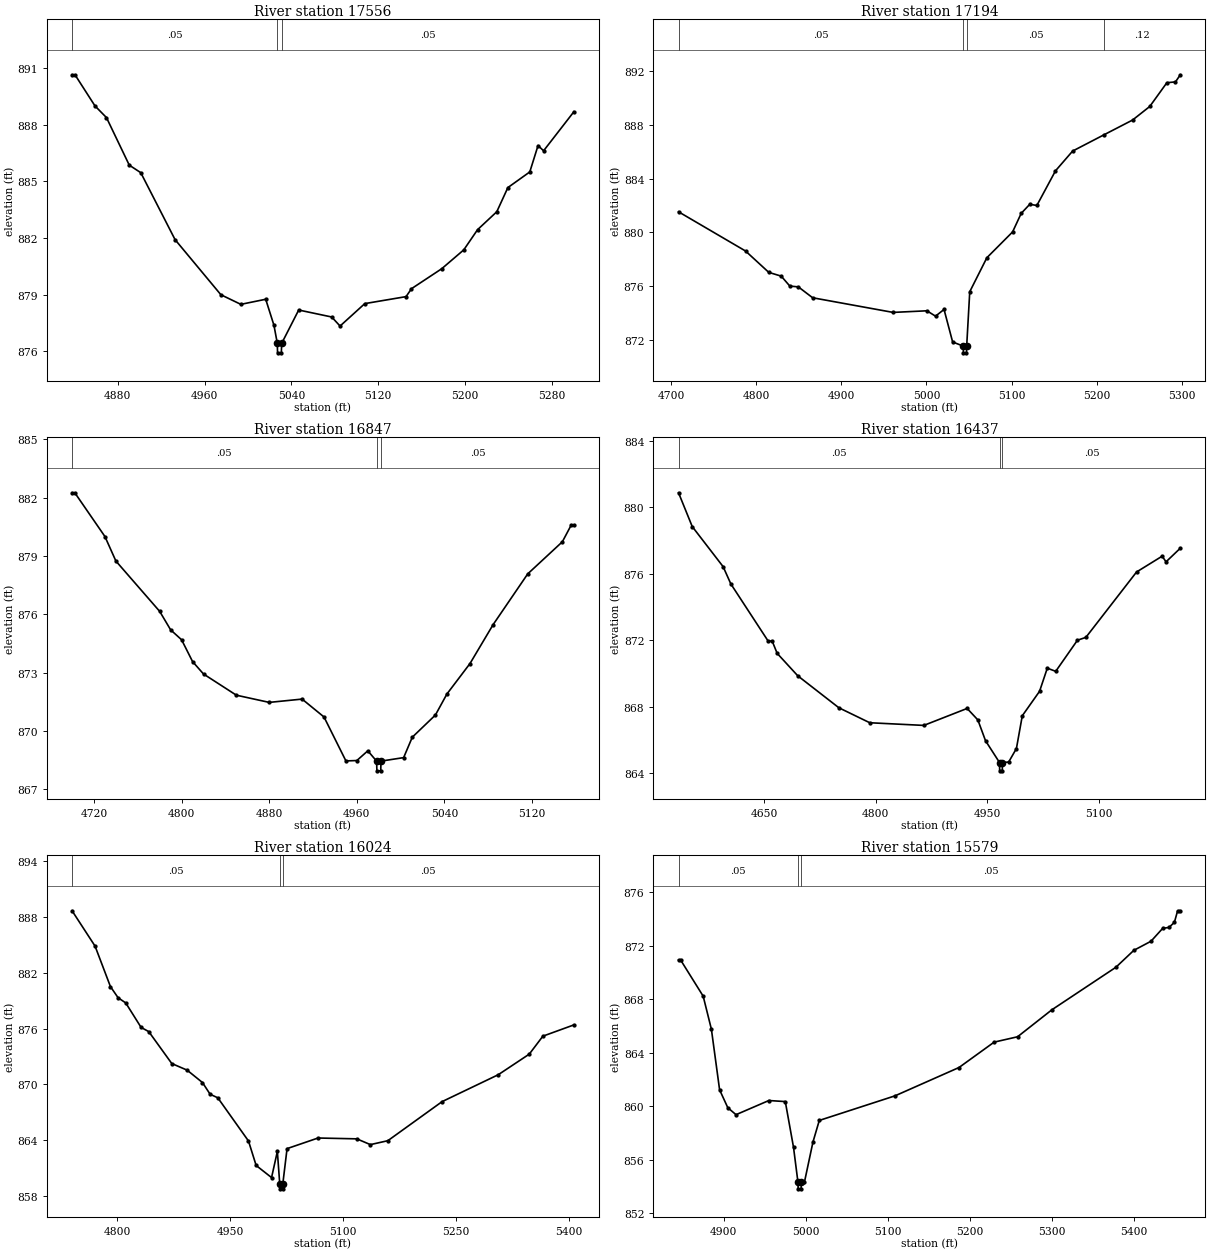
Type RM Length L Ch R = 1,17556,362,362,362
BEGIN DESCRIPTION:
MDE S 054 33.0
END DESCRIPTION:
XS GIS Cut Line= 3
      2301729.03      7169310.01      2301579.00      7169260.00
      2301278.98      7169310.00
#Sta/Elev= 30
  4837.9  890.65  4840.6  890.65  4859.0  889.00  4869.6  888.38  4890.6  885.86
  4901.2  885.46  4932.8  881.91  4975.0  878.99  4993.4  878.48  5016.3  878.75
  5023.9  877.37  5027.0  876.41  5027.2  875.91  5030.7  875.91  5031.0  876.41
  5046.7  878.18  5077.1  877.81  5084.8  877.33  5107.6  878.52  5145.6  878.89
  5150.6  879.31  5178.5  880.37  5198.8  881.37  5211.5  882.44  5229.2  883.39
  5239.4  884.67  5259.6  885.50  5267.2  886.90  5272.3  886.62  5300.2  888.69
#Mann=3,-1,0
  4837.9    0.05       0  5027.0   0.033       0  5031.0    0.05       0
Bank Sta=5027,5031
Exp/Cntr=0.3,0.1

Type RM Length L Ch R = 1,17194,347,347,347
BEGIN DESCRIPTION:
Mapping XS a917c653
END DESCRIPTION:
XS GIS Cut Line= 3
      2301672.73      7168986.43      2301572.86      7168949.04
      2301093.30      7169003.72
#Sta/Elev= 30
  4708.9  881.53  4787.6  878.61  4814.9  877.02  4829.5  876.74  4839.6  876.00
  4849.6  875.94  4866.4  875.13  4960.9  874.04  5000.6  874.16  5010.7  873.76
  5020.7  874.26  5030.8  871.84  5043.3  871.53  5043.5  871.03  5047.0  871.03
  5047.3  871.53  5050.9  875.58  5071.0  878.11  5101.2  880.03  5111.3  881.41
  5121.4  882.09  5129.7  882.00  5151.6  884.58  5171.7  886.05  5209.1  887.28
  5242.1  888.36  5262.3  889.37  5282.4  891.14  5292.5  891.20  5298.2  891.73
#Mann=4,-1,0
  4708.9    0.05       0  5043.3   0.033       0  5047.3    0.05       0
  5209.1    0.12       0
Bank Sta=5043.3,5047.3
Exp/Cntr=0.3,0.1

Type RM Length L Ch R = 1,16847,410,410,410
BEGIN DESCRIPTION:
MDE S 054 31.0
END DESCRIPTION:
XS GIS Cut Line= 3
      2301679.03      7168660.00      2301379.00      7168660.00
      2301229.05      7168709.98
#Sta/Elev= 30
  4700.0  882.25  4702.5  882.25  4730.0  880.00  4740.0  878.74  4780.0  876.15
  4790.0  875.20  4800.0  874.69  4810.0  873.57  4820.0  872.93  4850.0  871.84
  4880.0  871.47  4910.0  871.64  4930.0  870.72  4950.0  868.46  4960.0  868.48
  4970.0  868.98  4978.0  868.45  4978.3  867.95  4981.8  867.95  4982.0  868.45
  5002.7  868.63  5010.6  869.68  5031.7  870.82  5042.2  871.90  5063.3  873.47
  5084.4  875.47  5116.0  878.08  5147.6  879.73  5155.5  880.57  5158.1  880.57
#Mann=3,-1,0
  4700.0    0.05       0  4978.0   0.033       0  4982.0    0.05       0
Bank Sta=4978,4982
Exp/Cntr=0.3,0.1

Type RM Length L Ch R = 1,16437,413,413,413
BEGIN DESCRIPTION:
Mapping XS a065432e
END DESCRIPTION:
XS GIS Cut Line= 2
      2301726.76      7168407.80      2301076.63      7168229.61
#Sta/Elev= 30
  4535.3  880.86  4553.7  878.83  4595.2  876.42  4605.6  875.38  4655.8  871.94
  4661.0  871.96  4667.8  871.21  4695.5  869.86  4750.7  867.94  4792.2  867.04
  4864.8  866.88  4923.0  867.90  4937.4  867.21  4947.7  865.96  4966.5  864.65
  4966.7  864.15  4970.2  864.15  4970.5  864.65  4978.8  864.68  4989.2  865.49
  4997.1  867.46  5020.3  868.93  5030.7  870.32  5042.0  870.13  5071.2  872.00
  5082.5  872.17  5150.6  876.10  5185.0  877.05  5190.2  876.71  5209.4  877.53
#Mann=3,-1,0
  4535.3    0.05       0  4966.5   0.033       0  4970.5    0.05       0
Bank Sta=4966.5,4970.5
Exp/Cntr=0.3,0.1

Type RM Length L Ch R = 1,16024,445,445,445
BEGIN DESCRIPTION:
MDE S 054 29.0
END DESCRIPTION:
XS GIS Cut Line= 3
      2301729.03      7167909.99      2301479.00      7167960.00
      2301078.99      7168060.00
#Sta/Elev= 30
  4739.7  888.66  4770.3  884.86  4790.7  880.52  4800.9  879.32  4811.1  878.76
  4831.5  876.13  4841.7  875.68  4872.3  872.25  4892.7  871.54  4913.1  870.21
  4923.3  868.95  4933.5  868.57  4974.3  863.93  4984.5  861.30  5005.0  860.00
  5012.7  862.81  5015.9  859.29  5016.1  858.79  5019.6  858.79  5019.9  859.29
  5025.6  863.11  5066.8  864.25  5118.4  864.16  5136.4  863.54  5159.6  863.96
  5231.8  868.16  5306.5  871.05  5347.7  873.26  5365.8  875.19  5407.0  876.40
#Mann=3,-1,0
  4739.7    0.05       0  5015.9   0.033       0  5019.9    0.05       0
Bank Sta=5015.9,5019.9
Exp/Cntr=0.3,0.1

Type RM Length L Ch R = 1,15579,471,471,471
BEGIN DESCRIPTION:
MDE S 054 28.0
END DESCRIPTION:
XS GIS Cut Line= 3
      2301478.98      7167560.00      2301329.00      7167560.00
      2301028.97      7167910.03
#Sta/Elev= 30
  4845.2  870.95  4847.7  870.95  4875.2  868.24  4885.2  865.77  4895.2  861.23
  4905.2  859.89  4915.2  859.37  4955.2  860.43  4975.2  860.35  4985.2  856.93
  4990.6  854.32  4990.9  853.82  4994.4  853.82  4994.8  854.32  4998.5  854.32
  5008.9  857.33  5016.6  858.94  5108.8  860.78  5186.7  862.90  5229.5  864.80
  5258.0  865.20  5299.8  867.22  5377.7  870.40  5399.6  871.67  5420.5  872.35
  5434.8  873.32  5442.4  873.38  5449.0  873.77  5452.9  874.63  5456.2  874.63
#Mann=3,-1,0
  4845.2    0.05       0  4990.6   0.033       0  4994.8    0.05       0
Bank Sta=4990.6,4994.8
Exp/Cntr=0.3,0.1

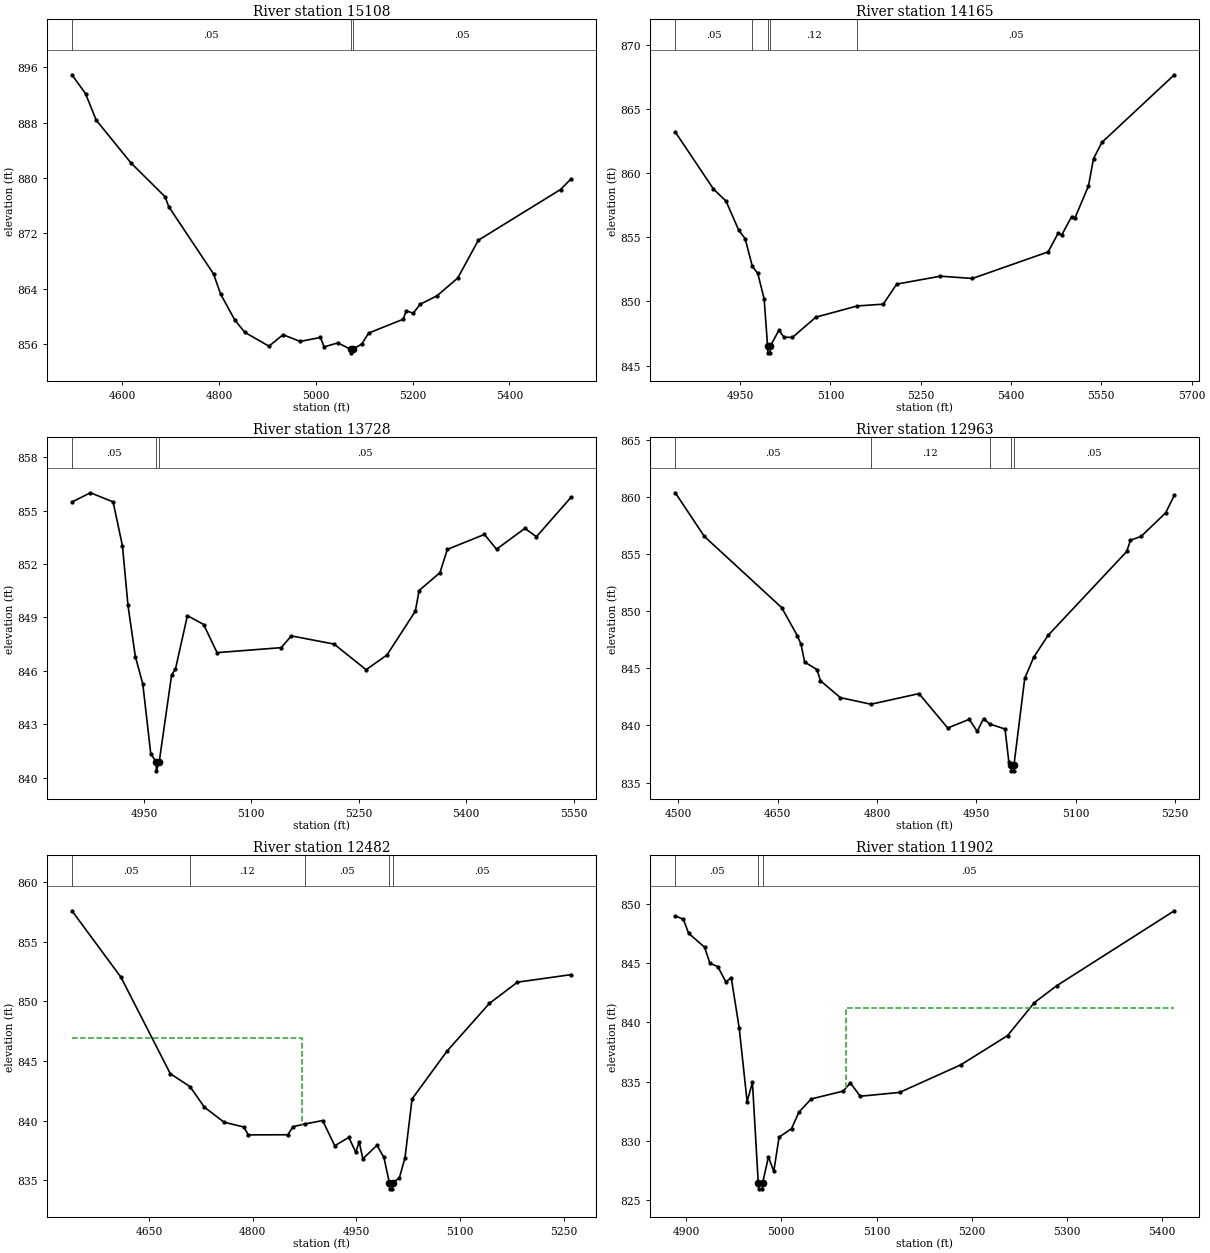
Type RM Length L Ch R = 1,15108,943,943,943
BEGIN DESCRIPTION:
MDE S 054 27.0
END DESCRIPTION:
XS GIS Cut Line= 3
      2301378.97      7166960.02      2300979.00      7167260.00
      2300628.98      7167660.02
#Sta/Elev= 30
  4495.8  894.93  4523.9  892.21  4545.8  888.40  4617.6  882.21  4688.5  877.29
  4695.8  875.89  4788.5  866.16  4803.1  863.25  4832.2  859.52  4853.1  857.72
  4903.1  855.71  4932.2  857.37  4967.6  856.40  5009.5  856.97  5017.1  855.61
  5045.6  856.19  5072.0  855.25  5072.3  854.75  5076.2  855.25  5095.0  856.03
  5109.2  857.61  5180.4  859.60  5187.0  860.83  5201.3  860.47  5215.5  861.76
  5250.6  863.00  5293.3  865.56  5336.0  871.03  5505.9  878.35  5527.3  879.88
#Mann=3,-1,0
  4495.8    0.05       0  5072.0   0.033       0  5076.2    0.05       0
Bank Sta=5072,5076.2
Exp/Cntr=0.3,0.1

Type RM Length L Ch R = 1,14165,437,437,437
BEGIN DESCRIPTION:
MDE S 054 26.0
END DESCRIPTION:
XS GIS Cut Line= 3
      2300779.01      7166559.98      2300729.00      7166710.00
      2300428.98      7167310.04
#Sta/Elev= 30
  4842.2  863.19  4905.5  858.76  4926.5  857.81  4947.6  855.54  4958.2  854.89
  4970.1  852.74  4979.2  852.18  4989.8  850.19  4995.5  846.50  4995.9  846.00
  4999.5  846.00  4999.8  846.50  5014.3  847.76  5022.7  847.22  5036.7  847.20
  5075.8  848.78  5144.5  849.65  5187.6  849.79  5210.0  851.35  5282.6  851.97
  5335.7  851.79  5461.5  853.86  5478.3  855.32  5483.9  855.16  5500.7  856.61
  5506.2  856.51  5528.6  859.00  5537.0  861.13  5551.0  862.39  5671.2  867.65
#Mann=5,-1,0
  4842.2    0.05       0  4970.1    0.12       0  4995.5    0.07       0
  4999.8    0.12       0  5144.5    0.05       0
Bank Sta=4995.5,4999.8
Exp/Cntr=0.3,0.1

Type RM Length L Ch R = 1,13728,765,765,765
BEGIN DESCRIPTION:
Mapping XS a105748f
END DESCRIPTION:
XS GIS Cut Line= 2
      2300432.09      7166464.55      2300246.74      7167136.45
#Sta/Elev= 30
  4849.4  855.48  4875.2  856.00  4906.9  855.49  4920.0  853.01  4927.7  849.67
  4938.0  846.80  4948.4  845.26  4959.5  841.34  4967.0  840.88  4967.4  840.38
  4971.3  840.88  4988.7  845.78  4993.9  846.08  5010.7  849.10  5033.4  848.60
  5052.1  847.02  5141.7  847.30  5155.9  847.96  5215.6  847.50  5260.3  846.06
  5289.5  846.89  5329.1  849.35  5334.3  850.51  5363.4  851.51  5373.8  852.82
  5425.6  853.66  5442.5  852.83  5482.1  854.00  5498.2  853.53  5546.4  855.74
#Mann=3,-1,0
  4849.4    0.05       0  4967.0   0.033       0  4971.3    0.05       0
Bank Sta=4967,4971.3
Exp/Cntr=0.3,0.1

Type RM Length L Ch R = 1,12963,481,481,481
BEGIN DESCRIPTION:
Mapping XS 427c5301
END DESCRIPTION:
XS GIS Cut Line= 2
      2300096.64      7166219.57      2299808.73      7166916.44
#Sta/Elev= 30
  4495.2  860.37  4538.9  856.56  4655.9  850.32  4679.6  847.86  4685.2  847.09
  4690.6  845.55  4709.1  844.90  4714.5  843.92  4744.5  842.44  4790.8  841.86
  4863.4  842.79  4906.8  839.78  4939.3  840.54  4951.4  839.48  4960.9  840.61
  4970.2  840.13  4993.4  839.69  4999.2  836.79  5002.4  836.53  5002.9  836.03
  5006.5  836.03  5006.9  836.53  5023.2  844.13  5036.7  845.97  5058.3  847.88
  5177.3  855.23  5182.9  856.22  5199.0  856.55  5236.1  858.61  5249.2  860.15
#Mann=5,-1,0
  4495.2    0.05       0  4790.8    0.12       0  4970.2    0.05       0
  5002.4   0.033       0  5006.9    0.05       0
Bank Sta=5002.4,5006.9
Exp/Cntr=0.3,0.1

Type RM Length L Ch R = 1,12482,580,580,580
BEGIN DESCRIPTION:
Mapping XS 6c8d0b55
END DESCRIPTION:
XS GIS Cut Line= 3
      2300016.50      7166166.78      2299787.17      7166433.42
      2299422.91      7166500.60
#Sta/Elev= 30
  4538.2  857.59  4609.2  852.02  4680.5  843.95  4709.1  842.86  4729.9  841.14
  4758.4  839.88  4786.9  839.48  4793.5  838.82  4850.6  838.83  4858.2  839.51
  4875.2  839.73  4901.0  840.02  4918.5  837.91  4938.9  838.61  4948.9  837.37
  4953.9  838.24  4959.2  836.81  4979.6  837.95  4989.7  836.93  4997.6  834.80
  4998.1  834.30  5001.7  834.30  5002.1  834.80  5012.0  835.21  5020.2  836.91
  5030.4  841.83  5081.2  845.85  5142.3  849.83  5182.9  851.61  5260.3  852.24
#Mann=5,-1,0
  4538.2    0.05       0  4709.1    0.12       0  4875.2    0.05       0
  4997.6   0.033       0  5002.1    0.05       0
#XS Ineff=2,0
    0.00 4870.90  846.90 5129.10    0.00  846.90
Permanent Ineff=
       F       F
Bank Sta=4997.6,5002.1
Exp/Cntr=0.3,0.1

Type RM Length L Ch R = 1,11902,344,344,344
BEGIN DESCRIPTION:
MDE S 054 22.0
END DESCRIPTION:
XS GIS Cut Line= 3
      2299528.99      7165910.02      2299479.00      7166010.00
      2299379.00      7166410.01
#Sta/Elev= 30
  4888.7  848.97  4897.1  848.68  4902.7  847.50  4919.4  846.33  4925.0  844.98
  4933.4  844.68  4941.8  843.40  4947.4  843.77  4955.8  839.51  4964.1  833.31
  4969.7  834.92  4975.8  826.45  4976.3  825.95  4979.9  825.95  4980.4  826.45
  4986.5  828.64  4992.1  827.43  4997.7  830.31  5010.8  831.03  5018.5  832.42
  5031.4  833.53  5064.9  834.19  5072.6  834.88  5082.9  833.76  5124.2  834.08
  5188.6  836.41  5237.6  838.87  5265.9  841.66  5289.1  843.07  5412.8  849.40
#Mann=3,-1,0
  4888.7    0.05       0  4975.8   0.033       0  4980.4    0.05       0
#XS Ineff=2,0
    0.00 4932.50  841.18 5067.50    0.00  841.18
Permanent Ineff=
       F       F
Bank Sta=4975.8,4980.4
Exp/Cntr=0.3,0.1

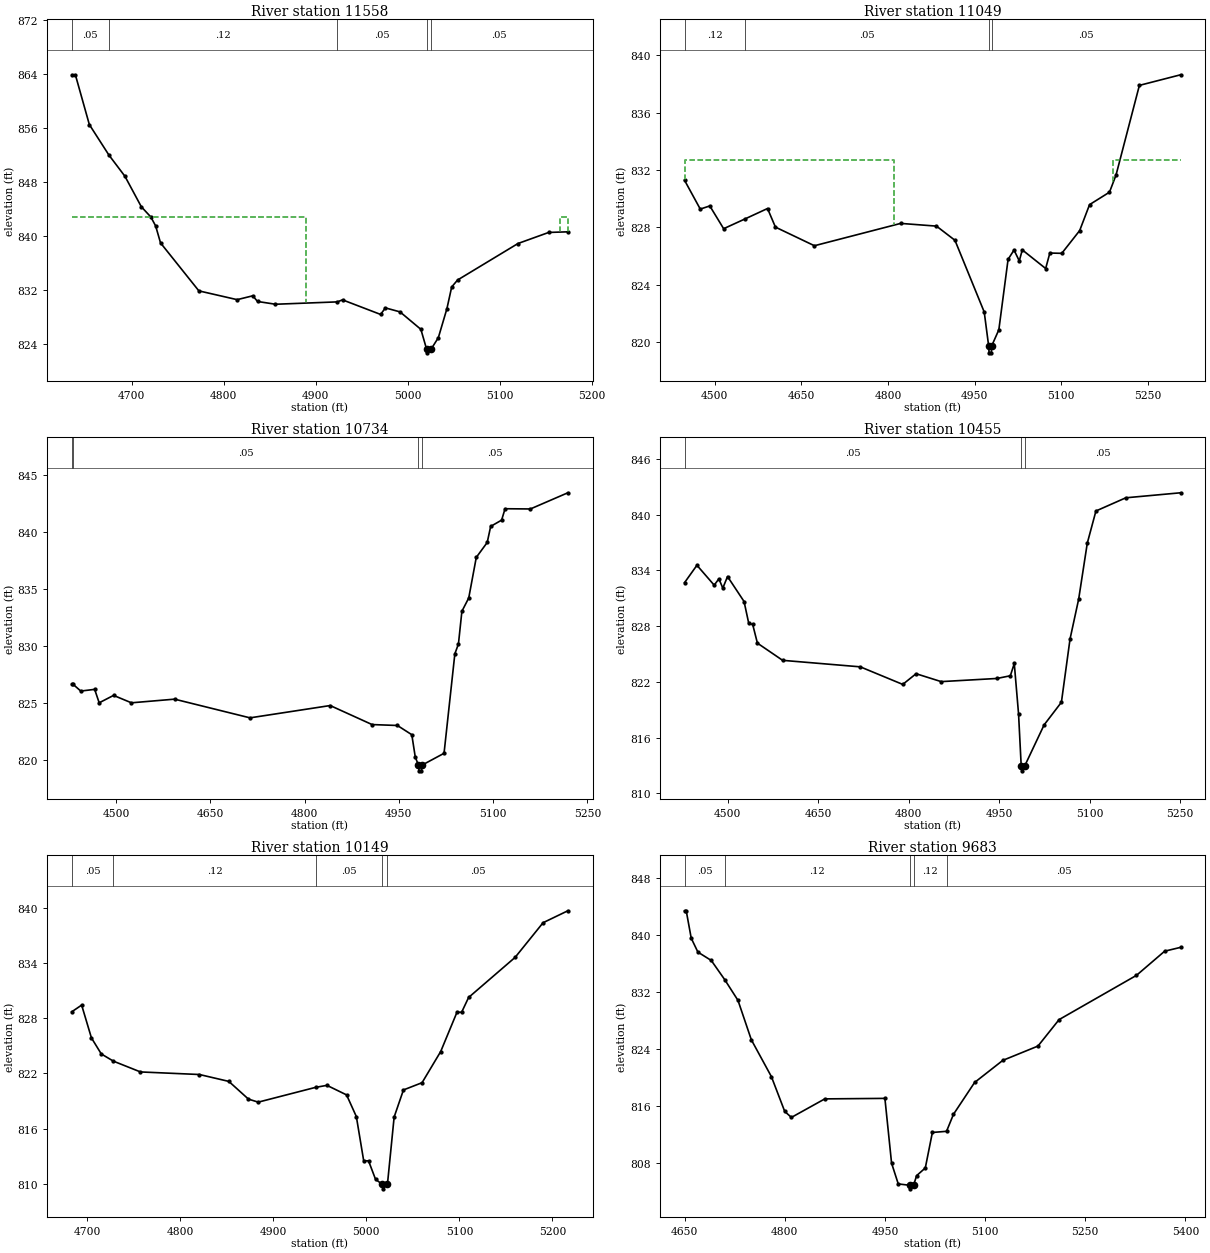
Type RM Length L Ch R = 1,11558,509,509,509
BEGIN DESCRIPTION:
Mapping XS c1ecadd9
END DESCRIPTION:
XS GIS Cut Line= 2
      2299269.59      7165647.40      2299118.21      7166165.12
#Sta/Elev= 30
  4634.8  863.82  4638.7  863.82  4653.9  856.44  4675.2  851.92  4692.6  848.78
  4710.4  844.27  4720.8  842.74  4726.0  841.42  4731.3  838.91  4773.0  831.80
  4814.6  830.50  4831.6  831.07  4836.8  830.23  4856.3  829.82  4923.5  830.17
  4929.2  830.47  4970.6  828.31  4975.8  829.28  4991.7  828.69  5014.4  826.10
  5020.7  823.12  5021.2  822.62  5025.3  823.12  5033.4  824.87  5042.7  829.16
  5047.9  832.38  5054.3  833.41  5120.0  838.82  5153.4  840.46  5174.2  840.55
#Mann=5,-1,0
  4634.8    0.05       0  4675.2    0.12       0  4923.5    0.05       0
  5020.7   0.033       0  5025.3    0.05       0
#XS Ineff=2,0
    0.00 4890.00  842.76 5165.30    0.00  842.76
Permanent Ineff=
       F       F
Bank Sta=5020.7,5025.3
Exp/Cntr=0.3,0.1

Type RM Length L Ch R = 1,11049,315,315,315
BEGIN DESCRIPTION:
Mapping XS e51890ac
END DESCRIPTION:
XS GIS Cut Line= 2
      2298970.54      7165467.66      2298754.82      7166299.23
#Sta/Elev= 30
  4447.7  831.28  4474.9  829.27  4491.4  829.49  4515.4  827.90  4552.8  828.59
  4591.4  829.31  4605.1  828.01  4672.6  826.71  4822.0  828.27  4884.0  828.08
  4916.0  827.09  4966.7  822.08  4974.3  819.73  4975.1  819.23  4979.0  819.23
  4979.8  819.73  4992.0  820.84  5008.0  825.76  5018.3  826.41  5027.4  825.65
  5032.6  826.42  5073.1  825.12  5080.3  826.20  5101.0  826.18  5132.0  827.77
  5149.1  829.58  5183.6  830.45  5194.9  831.64  5235.4  837.91  5306.8  838.65
#Mann=4,-1,0
  4447.7    0.12       0  4552.8    0.05       0  4974.3   0.033       0
  4979.8    0.05       0
#XS Ineff=2,0
    0.00 4809.70  832.72 5190.30    0.00  832.72
Permanent Ineff=
       F       F
Bank Sta=4974.3,4979.8
Exp/Cntr=0.3,0.1

Type RM Length L Ch R = 1,10734,279,279,279
BEGIN DESCRIPTION:
Mapping XS e79cc7cb
END DESCRIPTION:
XS GIS Cut Line= 2
      2298803.05      7165426.99      2298470.78      7166143.05
#Sta/Elev= 30
  4429.6  826.68  4430.9  826.68  4443.9  826.05  4466.0  826.20  4473.2  825.02
  4496.1  825.67  4524.5  825.02  4593.2  825.34  4713.2  823.70  4840.8  824.78
  4907.5  823.11  4947.8  823.03  4970.7  822.22  4976.2  820.26  4981.3  819.55
  4982.2  819.05  4986.1  819.05  4986.9  819.55  5022.0  820.59  5039.2  829.32
  5044.9  830.18  5050.4  833.05  5061.3  834.22  5073.3  837.78  5090.7  839.09
  5096.2  840.50  5113.6  841.05  5119.1  842.05  5159.4  842.03  5219.0  843.45
#Mann=4,-1,0
  4429.6    0.12       0  4430.9    0.05       0  4981.3   0.033       0
  4986.9    0.05       0
Bank Sta=4981.3,4986.9
Exp/Cntr=0.3,0.1

Type RM Length L Ch R = 1,10455,306,306,306
BEGIN DESCRIPTION:
Mapping XS e3ea5845
END DESCRIPTION:
XS GIS Cut Line= 3
      2298793.81      7165275.29      2298683.32      7165407.57
      2298266.95      7165906.11
#Sta/Elev= 30
  4428.6  832.68  4449.1  834.55  4477.7  832.41  4485.5  833.09  4492.0  832.09
  4499.8  833.34  4527.2  830.65  4535.0  828.29  4541.5  828.18  4549.3  826.17
  4591.1  824.32  4719.8  823.62  4790.1  821.73  4812.2  822.88  4853.8  822.03
  4946.2  822.37  4968.4  822.66  4974.9  823.98  4982.0  818.55  4986.4  812.93
  4987.2  812.43  4992.0  812.93  5024.3  817.37  5053.0  819.81  5067.3  826.62
  5081.6  830.91  5095.9  836.94  5110.2  840.39  5159.7  841.81  5250.5  842.35
#Mann=3,-1,0
  4428.6    0.05       0  4986.4   0.033       0  4992.0    0.05       0
Bank Sta=4986.4,4992
Exp/Cntr=0.3,0.1

Type RM Length L Ch R = 1,10149,466,466,466
BEGIN DESCRIPTION:
MDE S 054 18.0
END DESCRIPTION:
XS GIS Cut Line= 4
      2298579.03      7165409.99      2298279.00      7165510.00
      2298179.00      7165510.00      2298062.36      7165510.00
#Sta/Elev= 30
  4683.6  828.71  4694.2  829.44  4704.7  825.87  4715.3  824.12  4728.4  823.33
  4757.4  822.16  4820.7  821.88  4852.3  821.13  4873.4  819.20  4883.9  818.87
  4945.5  820.48  4957.7  820.70  4978.8  819.66  4989.3  817.30  4997.2  812.48
  5002.4  812.48  5009.9  810.47  5017.0  809.93  5017.9  809.43  5022.7  809.93
  5029.9  817.25  5039.9  820.20  5059.9  820.99  5079.9  824.38  5097.4  828.66
  5102.4  828.66  5109.9  830.27  5159.9  834.64  5189.9  838.41  5216.5  839.71
#Mann=5,-1,0
  4683.6    0.05       0  4728.4    0.12       0  4945.5    0.05       0
  5017.0   0.033       0  5022.7    0.05       0
Bank Sta=5017,5022.7
Exp/Cntr=0.3,0.1

Type RM Length L Ch R = 1,9683,438,438,438
BEGIN DESCRIPTION:
MDE S 054 17.0
END DESCRIPTION:
XS GIS Cut Line= 4
      2298678.98      7165110.00      2298329.00      7165110.00
      2298179.00      7165160.00      2297956.34      7165234.22
#Sta/Elev= 30
  4650.0  843.41  4652.5  843.41  4660.0  839.56  4670.0  837.61  4690.0  836.44
  4710.2  833.74  4730.0  830.84  4750.0  825.31  4780.0  820.15  4800.0  815.26
  4810.0  814.42  4860.0  817.02  4950.0  817.09  4960.0  808.00  4970.0  805.09
  4987.1  804.90  4988.0  804.40  4992.9  804.90  4997.5  806.25  5010.5  807.33
  5021.1  812.31  5042.3  812.47  5052.7  814.86  5084.3  819.32  5126.5  822.42
  5179.2  824.43  5210.8  828.14  5326.7  834.35  5368.9  837.74  5392.8  838.28
#Mann=5,-1,0
  4650.0    0.05       0  4710.2    0.12       0  4987.1    0.07       0
  4992.9    0.12       0  5042.3    0.05       0
Bank Sta=4987.1,4992.9
Exp/Cntr=0.3,0.1

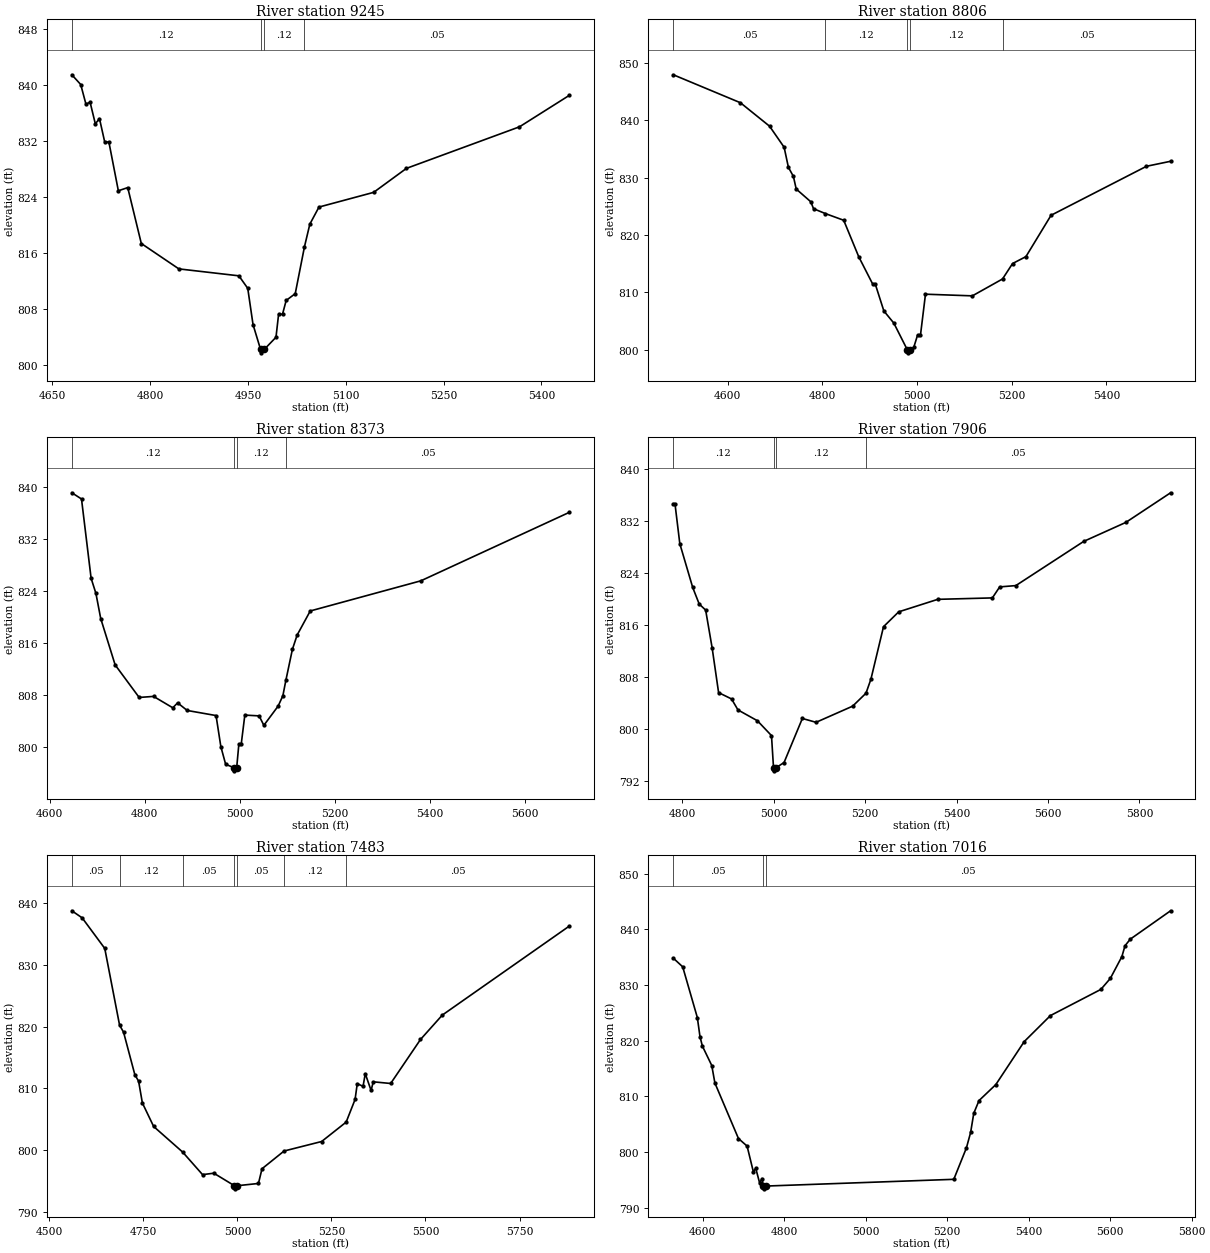
Type RM Length L Ch R = 1,9245,439,439,439
BEGIN DESCRIPTION:
MDE S 054 16.0
END DESCRIPTION:
XS GIS Cut Line= 4
      2298479.01      7164509.99      2298229.00      7164710.00
      2298129.00      7164760.00      2297833.46      7164907.77
#Sta/Elev= 30
  4680.1  841.47  4693.7  840.08  4701.7  837.28  4708.1  837.54  4716.1  834.46
  4722.5  835.20  4730.5  831.86  4736.9  831.86  4751.4  824.89  4765.8  825.34
  4786.6  817.35  4844.2  813.72  4936.2  812.73  4949.8  810.94  4957.9  805.76
  4969.4  802.22  4970.3  801.72  4975.2  802.22  4993.1  803.95  4997.1  807.24
  5003.1  807.24  5008.7  809.21  5022.6  810.18  5036.8  816.90  5045.0  820.12
  5059.0  822.56  5142.8  824.66  5193.1  828.09  5366.4  834.03  5442.5  838.51
#Mann=4,-1,0
  4680.1    0.12       0  4969.4    0.07       0  4975.2    0.12       0
  5036.8    0.05       0
Bank Sta=4969.4,4975.2
Exp/Cntr=0.3,0.1

Type RM Length L Ch R = 1,8806,433,433,433
BEGIN DESCRIPTION:
MDE S 054 15.0
END DESCRIPTION:
XS GIS Cut Line= 5
      2298567.79      7164187.46      2298167.94      7164330.35
      2298079.00      7164360.00      2297879.00      7164560.00
      2297703.01      7164736.00
#Sta/Elev= 30
  4485.6  847.89  4627.3  843.02  4688.8  838.94  4719.6  835.27  4728.6  831.78
  4739.2  830.19  4745.1  828.00  4775.9  825.78  4781.7  824.57  4806.9  823.72
  4845.4  822.56  4877.2  816.20  4907.0  811.39  4912.3  811.39  4930.2  806.77
  4951.3  804.65  4979.9  799.98  4980.9  799.48  4985.8  799.98  4993.4  800.45
  5001.3  802.55  5007.5  802.55  5018.1  809.69  5117.1  809.40  5180.8  812.34
  5202.0  815.03  5230.2  816.23  5283.3  823.43  5484.8  831.96  5535.7  832.83
#Mann=5,-1,0
  4485.6    0.05       0  4806.9    0.12       0  4979.9    0.07       0
  4985.8    0.12       0  5180.8    0.05       0
Bank Sta=4979.9,4985.8
Exp/Cntr=0.3,0.1

Type RM Length L Ch R = 1,8373,467,467,467
BEGIN DESCRIPTION:
MDE S 054 14.0
END DESCRIPTION:
XS GIS Cut Line= 4
      2298279.05      7163959.99      2297929.00      7164010.00
      2297779.00      7164010.00      2297237.40      7164010.01
#Sta/Elev= 30
  4646.8  839.05  4667.1  838.10  4687.3  825.92  4697.4  823.60  4707.5  819.74
  4737.8  812.62  4788.3  807.62  4818.6  807.78  4859.0  806.03  4869.1  806.79
  4889.3  805.62  4949.9  804.84  4960.0  800.07  4970.1  797.35  4987.3  796.85
  4988.3  796.35  4993.3  796.85  4997.9  800.49  5002.9  800.49  5010.4  804.91
  5040.4  804.79  5050.4  803.34  5080.4  806.29  5090.4  807.89  5096.6  810.23
  5110.4  815.01  5120.4  817.21  5147.9  820.90  5380.4  825.53  5692.0  836.03
#Mann=4,-1,0
  4646.8    0.12       0  4987.3    0.07       0  4993.3    0.12       0
  5096.6    0.05       0
Bank Sta=4987.3,4993.3
Exp/Cntr=0.3,0.1

Type RM Length L Ch R = 1,7906,423,423,423
BEGIN DESCRIPTION:
MDE S 054 13.0
END DESCRIPTION:
XS GIS Cut Line= 4
      2298229.01      7163810.01      2298079.00      7163660.00
      2297829.00      7163660.00      2297218.61      7163796.39
#Sta/Elev= 30
  4780.6  834.60  4784.2  834.60  4794.8  828.46  4823.0  821.74  4837.2  819.20
  4851.3  818.27  4865.5  812.46  4879.6  805.60  4907.9  804.63  4922.0  802.94
  4964.5  801.28  4995.3  799.00  4999.7  794.09  5000.7  793.59  5005.8  794.09
  5022.8  794.87  5062.8  801.63  5092.8  801.04  5172.8  803.52  5202.0  805.51
  5212.8  807.67  5240.3  815.72  5273.5  818.00  5359.0  819.92  5478.4  820.14
  5494.4  821.83  5529.7  822.03  5678.3  828.82  5770.3  831.73  5868.2  836.28
#Mann=4,-1,0
  4780.6    0.12       0  4999.7    0.07       0  5005.8    0.12       0
  5202.0    0.05       0
Bank Sta=4999.7,5005.8
Exp/Cntr=0.3,0.1

Type RM Length L Ch R = 1,7483,467,467,467
BEGIN DESCRIPTION:
Mapping XS fdc6e09b
END DESCRIPTION:
XS GIS Cut Line= 4
      2298406.48      7163297.67      2297967.91      7163297.91
      2297648.95      7163494.08      2297215.40      7163760.72
#Sta/Elev= 30
  4559.8  838.74  4587.3  837.59  4647.3  832.65  4686.7  820.23  4697.3  819.09
  4727.3  812.21  4737.3  811.16  4747.3  807.64  4777.3  803.83  4854.4  799.69
  4907.3  796.04  4937.3  796.27  4992.2  794.24  4993.2  793.74  4998.5  794.24
  5055.9  794.61  5065.4  796.99  5124.0  799.86  5223.9  801.40  5289.1  804.54
  5312.8  808.21  5318.6  810.76  5334.0  810.33  5339.9  812.38  5355.3  809.67
  5361.2  811.06  5407.4  810.79  5486.7  817.91  5544.7  821.86  5881.8  836.24
#Mann=7,-1,0
  4559.8    0.05       0  4686.7    0.12       0  4854.4    0.05       0
  4992.2   0.033       0  4998.5    0.05       0  5124.0    0.12       0
  5289.1    0.05       0
Bank Sta=4992.2,4998.5
Exp/Cntr=0.3,0.1

Type RM Length L Ch R = 1,7016,636,636,636
BEGIN DESCRIPTION:
MDE S 054 11.0
END DESCRIPTION:
XS GIS Cut Line= 4
      2298278.99      7162610.01      2297879.00      7162860.00
      2297479.00      7162960.00      2297153.03      7163041.50
#Sta/Elev= 30
  4528.3  834.82  4551.3  833.27  4587.2  824.16  4593.7  820.73  4599.6  819.03
  4622.6  815.54  4630.3  812.39  4688.1  802.42  4709.3  801.06  4724.6  796.45
  4730.5  797.08  4740.0  794.44  4745.9  795.23  4749.1  793.88  4750.2  793.38
  4755.5  793.88  5216.4  795.09  5247.4  800.74  5257.7  803.51  5265.4  806.95
  5278.3  809.24  5319.5  812.11  5389.1  819.83  5453.5  824.51  5577.2  829.21
  5600.4  831.18  5628.8  835.11  5636.5  837.06  5649.4  838.24  5748.3  843.34
#Mann=3,-1,0
  4528.3    0.05       0  4749.1   0.033       0  4755.5    0.05       0
Bank Sta=4749.1,4755.5
Exp/Cntr=0.3,0.1