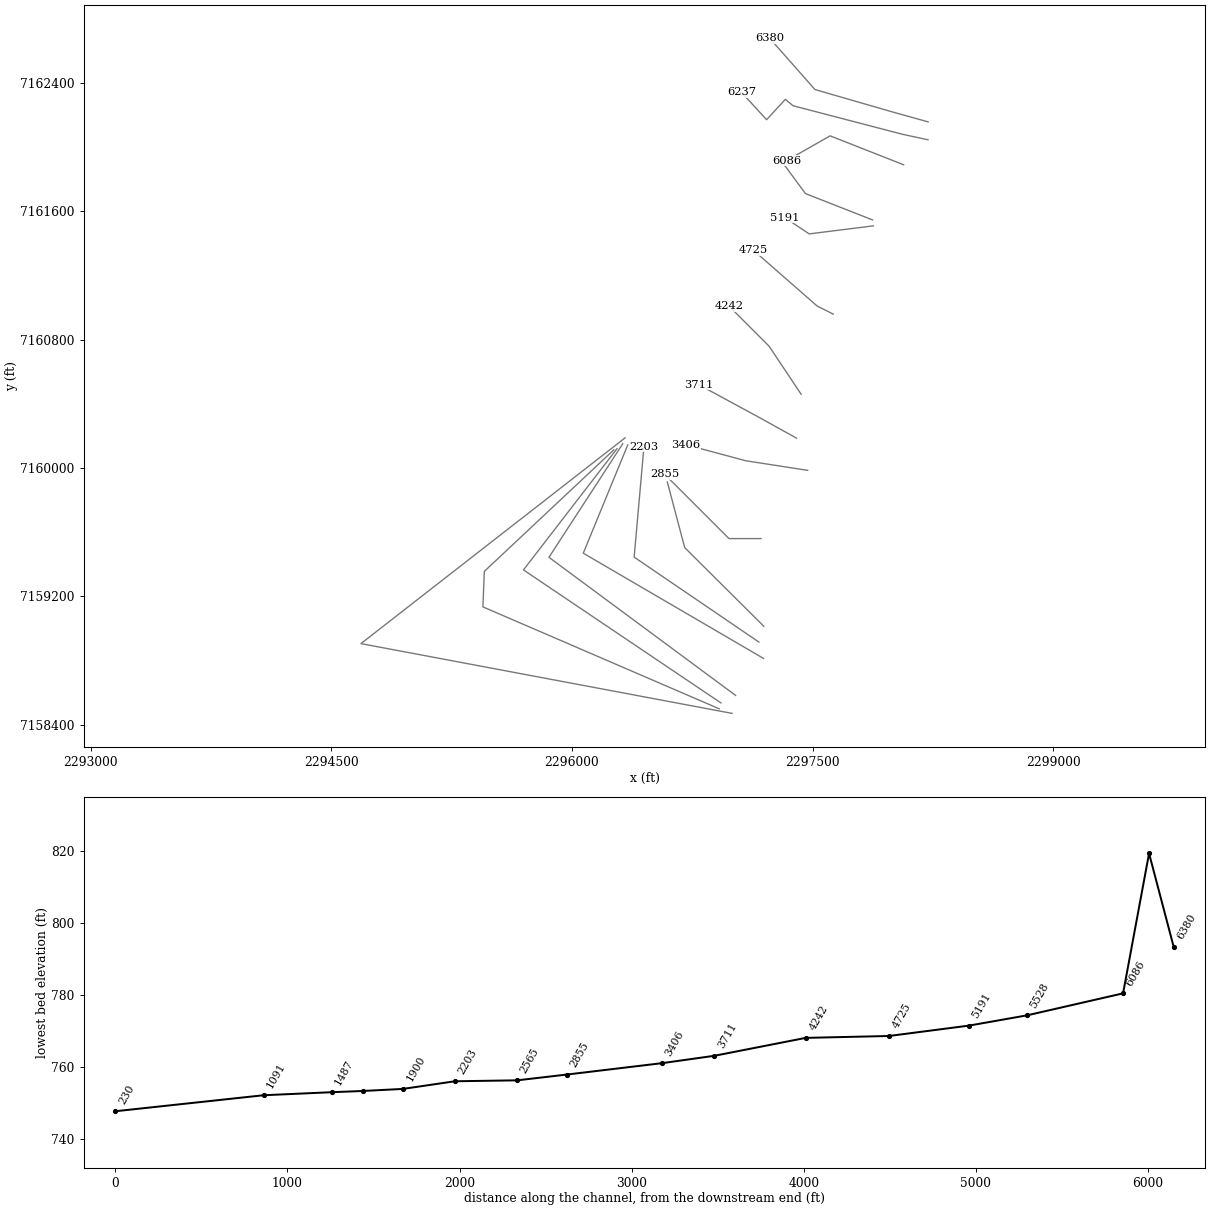
HEC-RAS study MDE S 054.prj: MDE S 054 Base Level Engineering

--- MDE S 054.g01 (geometry) --- (continued)

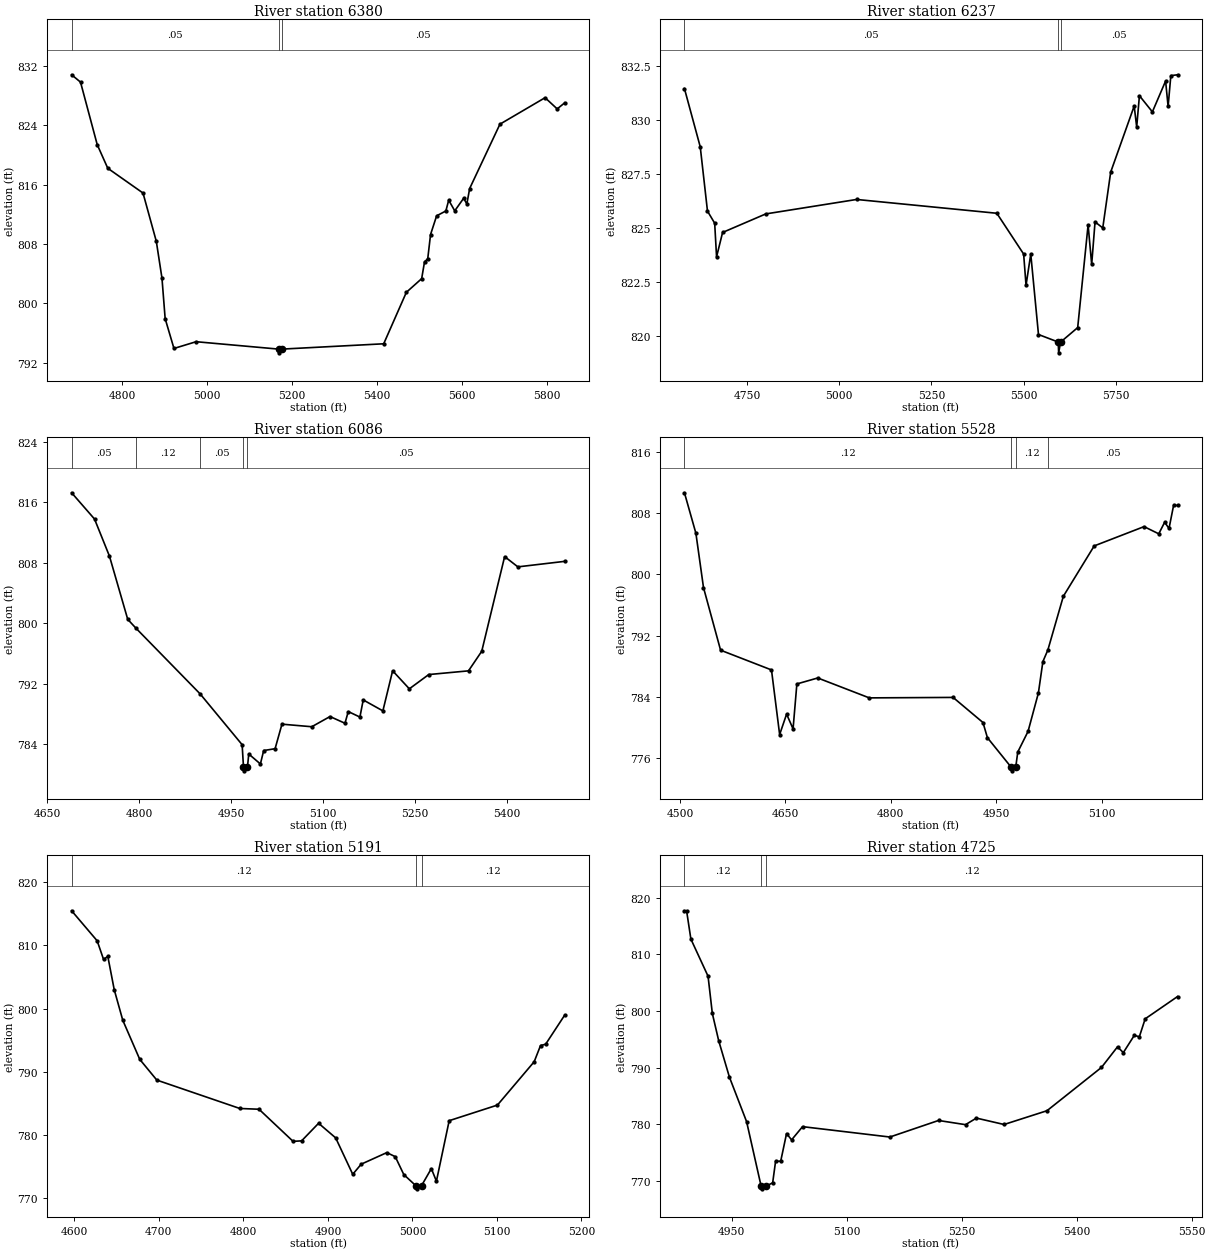
Type RM Length L Ch R = 1,6380,143,143,143
BEGIN DESCRIPTION:
Mapping XS 5ba89f21
END DESCRIPTION:
XS GIS Cut Line= 4
      2298220.87      7162158.48      2297982.92      7162224.90
      2297515.06      7162360.18      2297233.32      7162679.48
#Sta/Elev= 30
  4681.2  830.81  4702.1  829.82  4741.4  821.39  4766.2  818.21  4849.1  814.87
  4880.4  808.36  4893.7  803.40  4901.2  797.94  4921.9  793.92  4974.0  794.83
  5168.5  793.83  5169.5  793.33  5175.0  793.83  5415.3  794.55  5468.6  801.49
  5504.6  803.33  5511.3  805.59  5518.9  806.02  5525.5  809.28  5539.8  811.80
  5561.5  812.45  5568.2  813.91  5582.4  812.47  5603.3  814.16  5610.9  813.40
  5617.5  815.48  5688.7  824.15  5794.9  827.72  5823.4  826.21  5841.1  827.03
#Mann=3,-1,0
  4681.2    0.05       0  5168.5   0.033       0  5175.0    0.05       0
Bank Sta=5168.5,5175
Exp/Cntr=0.3,0.1

Type RM Length L Ch R = 1,6237,151,151,151
BEGIN DESCRIPTION:
Mapping XS 31ad3e92
END DESCRIPTION:
XS GIS Cut Line= 6
      2298220.02      7162046.88      2298062.14      7162080.88
      2297378.55      7162259.06      2297330.30      7162298.93
      2297213.60      7162172.11      2297056.28      7162343.31
#Sta/Elev= 30
  4580.9  831.45  4623.7  828.75  4643.3  825.77  4662.8  825.21  4667.9  823.65
  4684.2  824.78  4801.2  825.64  5047.2  826.31  5427.0  825.67  5499.6  823.78
  5506.1  822.33  5518.9  823.78  5539.8  820.05  5593.3  819.70  5594.4  819.20
  5599.8  819.70  5646.0  820.37  5674.2  825.13  5683.9  823.30  5693.0  825.27
  5713.9  824.99  5735.4  827.58  5799.0  830.64  5805.8  829.67  5813.2  831.12
  5848.3  830.37  5884.1  831.80  5890.9  830.62  5898.3  832.05  5916.4  832.09
#Mann=3,-1,0
  4580.9    0.05       0  5593.3   0.033       0  5599.8    0.05       0
Bank Sta=5593.3,5599.8
Exp/Cntr=0.3,0.1

Type RM Length L Ch R = 1,6086,558,558,558
BEGIN DESCRIPTION:
Mapping XS 4bea07a0
END DESCRIPTION:
XS GIS Cut Line= 3
      2298068.07      7161891.01      2297609.72      7162071.49
      2297338.22      7161916.77
#Sta/Elev= 30
  4689.7  817.26  4727.1  813.78  4751.5  808.86  4781.3  800.50  4794.7  799.33
  4899.5  790.63  4968.1  783.90  4970.3  780.94  4971.3  780.44  4976.8  780.94
  4978.9  782.67  4997.9  781.35  5003.3  783.13  5021.9  783.37  5033.1  786.62
  5081.8  786.28  5111.6  787.63  5136.0  786.74  5141.4  788.29  5160.4  787.56
  5165.8  789.83  5197.9  788.38  5213.8  793.69  5241.1  791.30  5272.8  793.19
  5337.7  793.68  5359.3  796.27  5396.7  808.81  5418.3  807.45  5494.8  808.18
#Mann=5,-1,0
  4689.7    0.05       0  4794.7    0.12       0  4899.5    0.05       0
  4970.3   0.033       0  4976.8    0.05       0
Bank Sta=4970.3,4976.8
Exp/Cntr=0.3,0.1

Type RM Length L Ch R = 1,5528,337,337,337
BEGIN DESCRIPTION:
Mapping XS 4d5b1a8c
END DESCRIPTION:
XS GIS Cut Line= 3
      2297874.23      7161547.13      2297455.93      7161711.40
      2297306.32      7161914.07
#Sta/Elev= 30
  4506.4  810.67  4522.7  805.38  4533.5  798.29  4557.8  790.11  4630.2  787.53
  4641.8  779.09  4651.7  781.76  4660.9  779.83  4666.3  785.70  4696.0  786.48
  4769.3  783.88  4888.5  783.94  4931.0  780.66  4937.3  778.68  4970.9  774.85
  4972.0  774.35  4977.6  774.85  4980.5  776.81  4995.1  779.50  5009.8  784.51
  5016.2  788.62  5023.3  790.14  5045.3  797.15  5089.2  803.73  5160.1  806.25
  5181.0  805.31  5189.4  806.82  5195.6  806.01  5202.1  809.02  5207.7  809.02
#Mann=4,-1,0
  4506.4    0.12       0  4970.9    0.07       0  4977.6    0.12       0
  5023.3    0.05       0
Bank Sta=4970.9,4977.6
Exp/Cntr=0.3,0.1

Type RM Length L Ch R = 1,5191,466,466,466
BEGIN DESCRIPTION:
MDE S 054 7.0
END DESCRIPTION:
XS GIS Cut Line= 3
      2297878.98      7161510.00      2297479.00      7161460.00
      2297328.98      7161560.01
#Sta/Elev= 30
  4596.8  815.49  4627.0  810.74  4634.6  807.79  4639.6  808.28  4647.2  803.01
  4657.3  798.18  4677.4  791.99  4697.6  788.71  4795.8  784.22  4818.5  784.10
  4858.8  779.02  4868.9  779.10  4889.0  781.88  4909.2  779.57  4929.4  773.81
  4939.4  775.41  4969.7  777.24  4979.7  776.60  4989.8  773.77  5004.0  772.01
  5005.1  771.51  5010.8  772.01  5022.4  774.71  5028.4  772.72  5043.5  782.29
  5100.6  784.76  5144.1  791.62  5151.6  794.18  5157.6  794.38  5180.2  798.99
#Mann=3,-1,0
  4596.8    0.12       0  5004.0    0.07       0  5010.8    0.12       0
Bank Sta=5004,5010.8
Exp/Cntr=0.3,0.1

Type RM Length L Ch R = 1,4725,483,483,483
BEGIN DESCRIPTION:
MDE S 054 6.0
END DESCRIPTION:
XS GIS Cut Line= 3
      2297629.02      7160959.99      2297529.00      7161010.00
      2297129.02      7161359.98
#Sta/Elev= 30
  4888.3  817.68  4891.1  817.68  4896.7  812.69  4919.1  806.14  4924.7  799.56
  4933.0  794.75  4947.0  788.33  4969.4  780.48  4988.3  769.13  4989.4  768.63
  4995.1  769.13  5003.4  769.69  5007.2  773.48  5013.9  773.51  5021.5  778.38
  5028.1  777.27  5042.4  779.60  5156.3  777.77  5219.8  780.69  5255.0  779.95
  5269.2  781.11  5305.3  779.98  5361.3  782.41  5432.4  790.05  5453.3  793.68
  5460.9  792.66  5475.2  795.70  5481.8  795.46  5489.4  798.62  5531.6  802.55
#Mann=3,-1,0
  4888.3    0.12       0  4988.3    0.07       0  4995.1    0.12       0
Bank Sta=4988.3,4995.1
Exp/Cntr=0.3,0.1

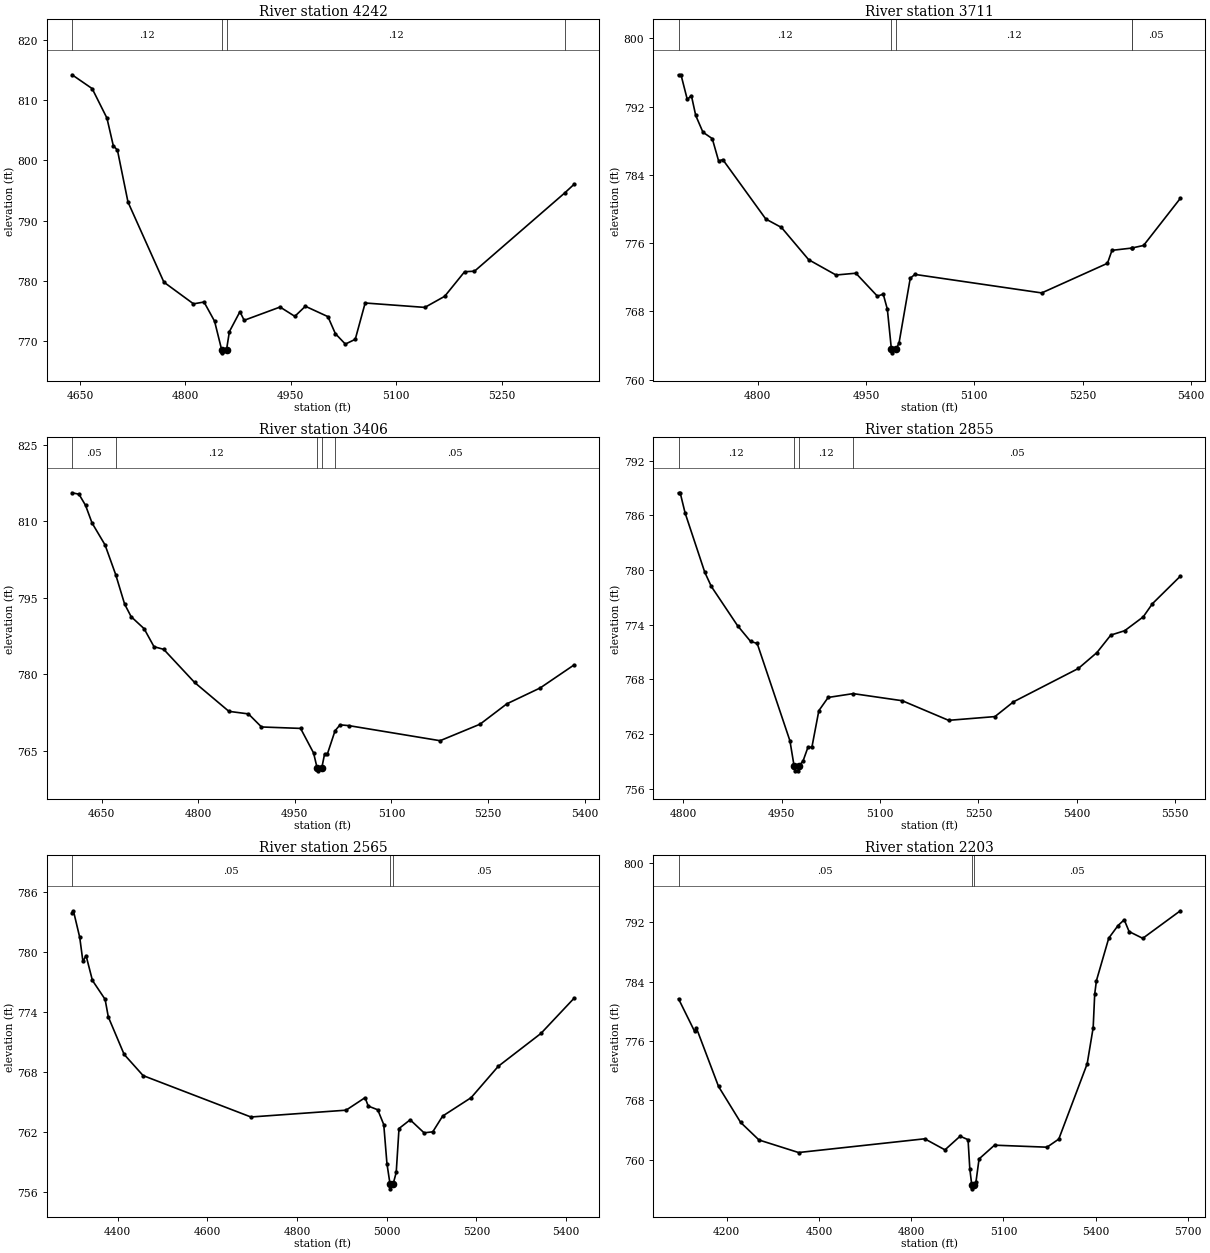
Type RM Length L Ch R = 1,4242,531,531,531
BEGIN DESCRIPTION:
MDE S 054 5.0
END DESCRIPTION:
XS GIS Cut Line= 3
      2297429.01      7160459.99      2297229.00      7160760.00
      2296979.02      7161009.98
#Sta/Elev= 30
  4638.8  814.19  4667.4  811.90  4688.4  807.02  4697.4  802.47  4703.4  801.68
  4718.4  793.09  4769.5  779.82  4811.6  776.23  4826.6  776.53  4841.6  773.35
  4851.7  768.61  4852.8  768.11  4858.6  768.61  4862.7  771.63  4877.7  774.93
  4883.7  773.50  4934.8  775.70  4955.8  774.16  4970.8  775.83  5002.9  774.11
  5013.5  771.29  5027.7  769.56  5041.8  770.35  5055.9  776.37  5140.8  775.64
  5169.1  777.48  5197.4  781.55  5211.5  781.64  5340.1  794.63  5352.9  796.01
#Mann=4,-1,0
  4638.8    0.12       0  4851.7    0.07       0  4858.6    0.12       0
  5340.1    0.05       0
Bank Sta=4851.7,4858.6
Exp/Cntr=0.3,0.1

Type RM Length L Ch R = 1,3711,305,305,305
BEGIN DESCRIPTION:
Mapping XS 606f46db
END DESCRIPTION:
XS GIS Cut Line= 3
      2297399.83      7160186.53      2297177.23      7160310.11
      2296790.32      7160519.84
#Sta/Elev= 30
  4690.5  795.73  4693.9  795.73  4702.6  792.84  4708.3  793.29  4714.3  790.96
  4724.3  789.00  4737.2  788.25  4746.0  785.63  4751.8  785.79  4811.3  778.83
  4833.0  777.84  4870.7  774.06  4908.5  772.27  4936.0  772.48  4965.8  769.79
  4973.9  770.03  4979.6  768.26  4985.1  763.65  4986.2  763.15  4992.1  763.65
  4995.8  764.32  5011.3  771.89  5017.7  772.34  5193.3  770.17  5284.3  773.64
  5290.6  775.16  5318.4  775.43  5318.5  775.44  5334.3  775.73  5385.2  781.25
#Mann=5,-1,0
  4690.5    0.12       0  4985.1   0.033       0  4992.1    0.12       0
  5318.4    0.12       0  5318.5    0.05       0
Bank Sta=4985.1,4992.1
Exp/Cntr=0.3,0.1

Type RM Length L Ch R = 1,3406,551,551,551
BEGIN DESCRIPTION:
Mapping XS 838b495d
END DESCRIPTION:
XS GIS Cut Line= 3
      2297469.61      7159985.46      2297082.25      7160045.60
      2296708.45      7160146.23
#Sta/Elev= 30
  4604.2  815.55  4614.9  815.27  4625.1  813.09  4635.2  809.64  4655.4  805.34
  4671.9  799.54  4685.8  793.75  4695.9  791.29  4716.1  788.93  4731.4  785.41
  4746.5  784.89  4794.4  778.41  4847.7  772.75  4878.0  772.25  4898.3  769.69
  4959.0  769.41  4979.2  764.59  4984.8  761.60  4985.9  761.10  4991.8  761.60
  4996.2  764.36  5000.5  764.36  5012.5  768.94  5020.3  770.11  5034.1  769.95
  5175.6  767.00  5237.7  770.24  5279.2  774.22  5331.0  777.33  5383.3  781.81
#Mann=5,-1,0
  4604.2    0.05       0  4671.9    0.12       0  4984.8    0.07       0
  4991.8    0.12       0  5012.5    0.05       0
Bank Sta=4984.8,4991.8
Exp/Cntr=0.3,0.1

Type RM Length L Ch R = 1,2855,290,290,290
BEGIN DESCRIPTION:
MDE S 054 2.0
END DESCRIPTION:
XS GIS Cut Line= 3
      2297178.99      7159560.00      2296979.00      7159560.00
      2296578.98      7159960.02
#Sta/Elev= 30
  4792.5  788.46  4795.0  788.46  4802.5  786.25  4832.5  779.75  4842.5  778.19
  4882.5  773.89  4902.5  772.15  4912.5  771.94  4962.5  761.25  4968.9  758.46
  4970.0  757.96  4974.9  757.96  4976.0  758.46  4982.5  759.04  4990.0  760.55
  4996.0  760.55  5006.6  764.56  5020.8  766.01  5059.0  766.43  5133.9  765.65
  5204.6  763.50  5275.3  763.91  5303.6  765.53  5402.6  769.19  5430.9  770.93
  5452.1  772.85  5473.3  773.33  5501.6  774.85  5515.7  776.30  5558.2  779.31
#Mann=4,-1,0
  4792.5    0.12       0  4968.9    0.07       0  4976.0    0.12       0
  5059.0    0.05       0
Bank Sta=4968.9,4976
Exp/Cntr=0.3,0.1

Type RM Length L Ch R = 1,2565,362,362,362
BEGIN DESCRIPTION:
Mapping XS 67a4cc38
END DESCRIPTION:
XS GIS Cut Line= 3
      2297196.28      7159013.09      2296702.74      7159503.98
      2296594.45      7159912.98
#Sta/Elev= 30
  4298.0  783.87  4301.0  784.10  4315.1  781.44  4322.2  779.04  4329.2  779.63
  4343.4  777.15  4371.7  775.26  4378.8  773.51  4414.1  769.77  4456.5  767.65
  4696.9  763.52  4909.1  764.20  4951.5  765.45  4958.6  764.61  4979.8  764.24
  4993.2  762.76  5000.3  758.87  5007.1  756.85  5008.2  756.35  5014.2  756.85
  5021.0  757.99  5027.2  762.37  5052.1  763.24  5083.1  761.94  5102.5  762.04
  5124.5  763.61  5188.1  765.45  5248.6  768.58  5343.8  771.86  5417.2  775.35
#Mann=3,-1,0
  4298.0    0.05       0  5007.1   0.033       0  5014.2    0.05       0
Bank Sta=5007.1,5014.2
Exp/Cntr=0.3,0.1

Type RM Length L Ch R = 1,2203,303,303,303
BEGIN DESCRIPTION:
Mapping XS cb821617
END DESCRIPTION:
XS GIS Cut Line= 3
      2297165.52      7158914.64      2296387.66      7159444.37
      2296448.63      7160131.66
#Sta/Elev= 30
  4043.7  781.68  4095.8  777.31  4101.8  777.75  4173.7  769.88  4245.5  765.04
  4305.2  762.67  4433.9  760.98  4843.9  762.83  4909.7  761.34  4959.0  763.18
  4984.8  762.71  4990.5  758.79  4996.9  756.59  4998.0  756.09  5004.0  756.59
  5010.5  757.01  5020.6  760.12  5070.8  761.97  5241.4  761.70  5279.7  762.79
  5372.0  772.93  5391.5  777.80  5396.5  782.32  5402.1  784.13  5442.2  789.86
  5472.3  791.55  5492.4  792.33  5508.3  790.74  5552.7  789.83  5674.8  793.54
#Mann=3,-1,0
  4043.7    0.05       0  4996.9   0.033       0  5004.0    0.05       0
Bank Sta=4996.9,5004
Exp/Cntr=0.3,0.1

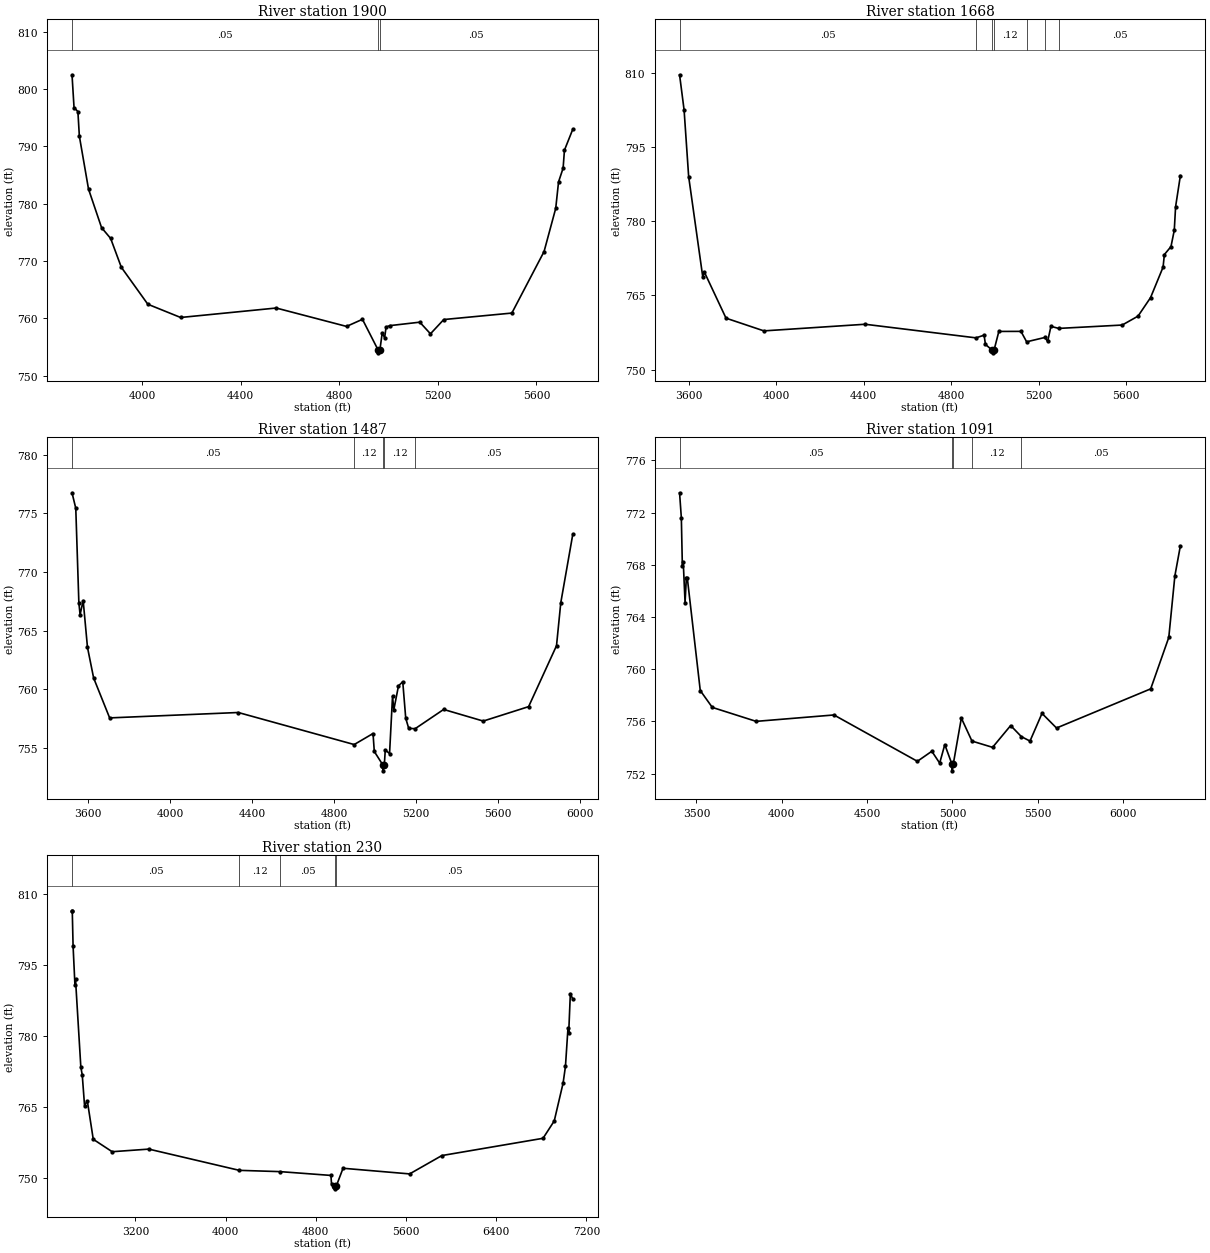
Type RM Length L Ch R = 1,1900,232,232,232
BEGIN DESCRIPTION:
Mapping XS b6ac547f
END DESCRIPTION:
XS GIS Cut Line= 3
      2297194.33      7158812.76      2296070.39      7159468.91
      2296347.81      7160144.19
#Sta/Elev= 30
  3716.2  802.49  3724.4  796.76  3740.1  796.07  3745.9  791.80  3783.1  782.55
  3836.0  775.82  3872.9  773.93  3916.2  768.90  4023.7  762.45  4156.8  760.14
  4544.5  761.79  4829.8  758.58  4894.3  759.82  4957.8  754.47  4958.9  753.97
  4965.0  754.47  4974.5  757.42  4984.4  756.61  4990.2  758.48  5005.9  758.72
  5126.9  759.32  5170.2  757.29  5224.2  759.78  5500.4  760.91  5631.0  771.64
  5678.3  779.18  5689.8  783.80  5708.3  786.20  5713.7  789.33  5747.7  793.00
#Mann=3,-1,0
  3716.2    0.05       0  4957.8   0.033       0  4965.0    0.05       0
Bank Sta=4957.8,4965
Exp/Cntr=0.3,0.1

Type RM Length L Ch R = 1,1668,181,181,181
BEGIN DESCRIPTION:
Mapping XS 62f66fbc
END DESCRIPTION:
XS GIS Cut Line= 3
      2297020.00      7158582.20      2295856.29      7159443.29
      2296316.89      7160151.90
#Sta/Elev= 30
  3556.7  809.63  3577.4  802.52  3598.3  789.04  3663.0  768.71  3669.9  769.76
  3769.4  760.41  3942.7  757.84  4406.0  759.18  4913.6  756.43  4950.9  756.97
  4957.1  755.10  4989.0  753.90  4990.1  753.40  4996.2  753.90  5018.4  757.73
  5119.7  757.74  5145.6  755.63  5229.2  756.51  5241.8  755.70  5256.9  758.76
  5292.3  758.34  5583.1  759.02  5655.6  760.82  5712.9  764.56  5770.3  770.73
  5776.2  773.27  5806.5  774.89  5821.6  778.19  5827.6  782.95  5849.5  789.24
#Mann=7,-1,0
  3556.7    0.05       0  4913.6    0.12       0  4989.0    0.07       0
  4996.2    0.12       0  5145.6    0.05       0  5229.2    0.12       0
  5292.3    0.05       0
Bank Sta=4989,4996.2
Exp/Cntr=0.3,0.1

Type RM Length L Ch R = 1,1487,396,396,396
BEGIN DESCRIPTION:
Mapping XS b5020931
END DESCRIPTION:
XS GIS Cut Line= 3
      2296929.23      7158534.80      2295697.39      7159364.65
      2296280.56      7160120.55
#Sta/Elev= 30
  3523.0  776.75  3541.3  775.43  3556.3  767.40  3562.3  766.36  3577.3  767.57
  3598.3  763.58  3628.3  760.97  3706.3  757.57  4333.0  758.03  4897.8  755.30
  4989.6  756.24  4995.7  754.71  5037.4  753.56  5038.6  753.06  5044.6  753.56
  5049.2  754.84  5070.1  754.53  5084.6  759.42  5090.9  758.27  5113.6  760.30
  5134.4  760.65  5148.9  757.54  5163.4  756.68  5194.7  756.65  5333.6  758.29
  5526.6  757.30  5747.6  758.53  5883.5  763.72  5904.3  767.38  5963.0  773.23
#Mann=5,-1,0
  3523.0    0.05       0  4897.8    0.12       0  5037.4    0.07       0
  5044.6    0.12       0  5194.7    0.05       0
Bank Sta=5037.4,5044.6
Exp/Cntr=0.3,0.1

Type RM Length L Ch R = 1,1091,861,861,861
BEGIN DESCRIPTION:
Mapping XS 6fbc53e1
END DESCRIPTION:
XS GIS Cut Line= 4
      2296918.52      7158498.35      2295444.53      7159134.12
      2295453.37      7159355.55      2296261.16      7160113.68
#Sta/Elev= 30
  3401.1  773.52  3411.5  771.60  3417.4  767.93  3422.8  768.19  3433.3  765.10
  3440.9  767.02  3446.4  767.00  3522.4  758.37  3592.9  757.08  3849.8  756.01
  4305.8  756.50  4794.6  752.95  4879.3  753.72  4925.3  752.81  4955.3  754.23
  4997.6  752.72  4998.8  752.22  5004.8  752.72  5052.3  756.26  5114.5  754.50
  5235.3  754.02  5341.3  755.69  5404.1  754.84  5454.6  754.50  5525.0  756.62
  5610.0  755.50  6161.9  758.50  6267.9  762.44  6303.5  767.15  6335.8  769.46
#Mann=5,-1,0
  3401.1    0.05       0  4997.6    0.04       0  5004.8    0.05       0
  5114.5    0.12       0  5404.1    0.05       0
Bank Sta=4997.6,5004.8
Exp/Cntr=0.3,0.1

Type RM Length L Ch R = 1,230,0,0,0
BEGIN DESCRIPTION:
MDE S 054 1.0
END DESCRIPTION:
XS GIS Cut Line= 3
      2296998.23      7158470.03      2294684.00      7158905.04
      2296331.49      7160188.36
#Sta/Elev= 30
  2637.2  806.44  2639.4  806.44  2646.6  799.02  2663.0  790.82  2668.1  792.00
  2715.5  773.45  2728.0  771.81  2748.3  765.36  2773.1  766.34  2825.6  758.24
  2993.3  755.62  3318.5  756.17  4121.4  751.69  4482.9  751.42  4934.3  750.62
  4939.3  748.86  4973.1  748.29  4974.2  747.79  4980.3  748.29  5041.7  752.13
  5632.5  750.94  5918.4  754.81  6815.9  758.45  6915.4  762.11  6994.1  770.11
  7014.9  773.62  7037.5  781.77  7043.9  780.76  7058.3  788.97  7080.3  787.78
#Mann=5,-1,0
  2637.2    0.05       0  4121.4    0.12       0  4482.9    0.05       0
  4973.1   0.033       0  4980.3    0.05       0
Bank Sta=4973.1,4980.3
Exp/Cntr=0.3,0.1

Chan Stop Cuts=-1