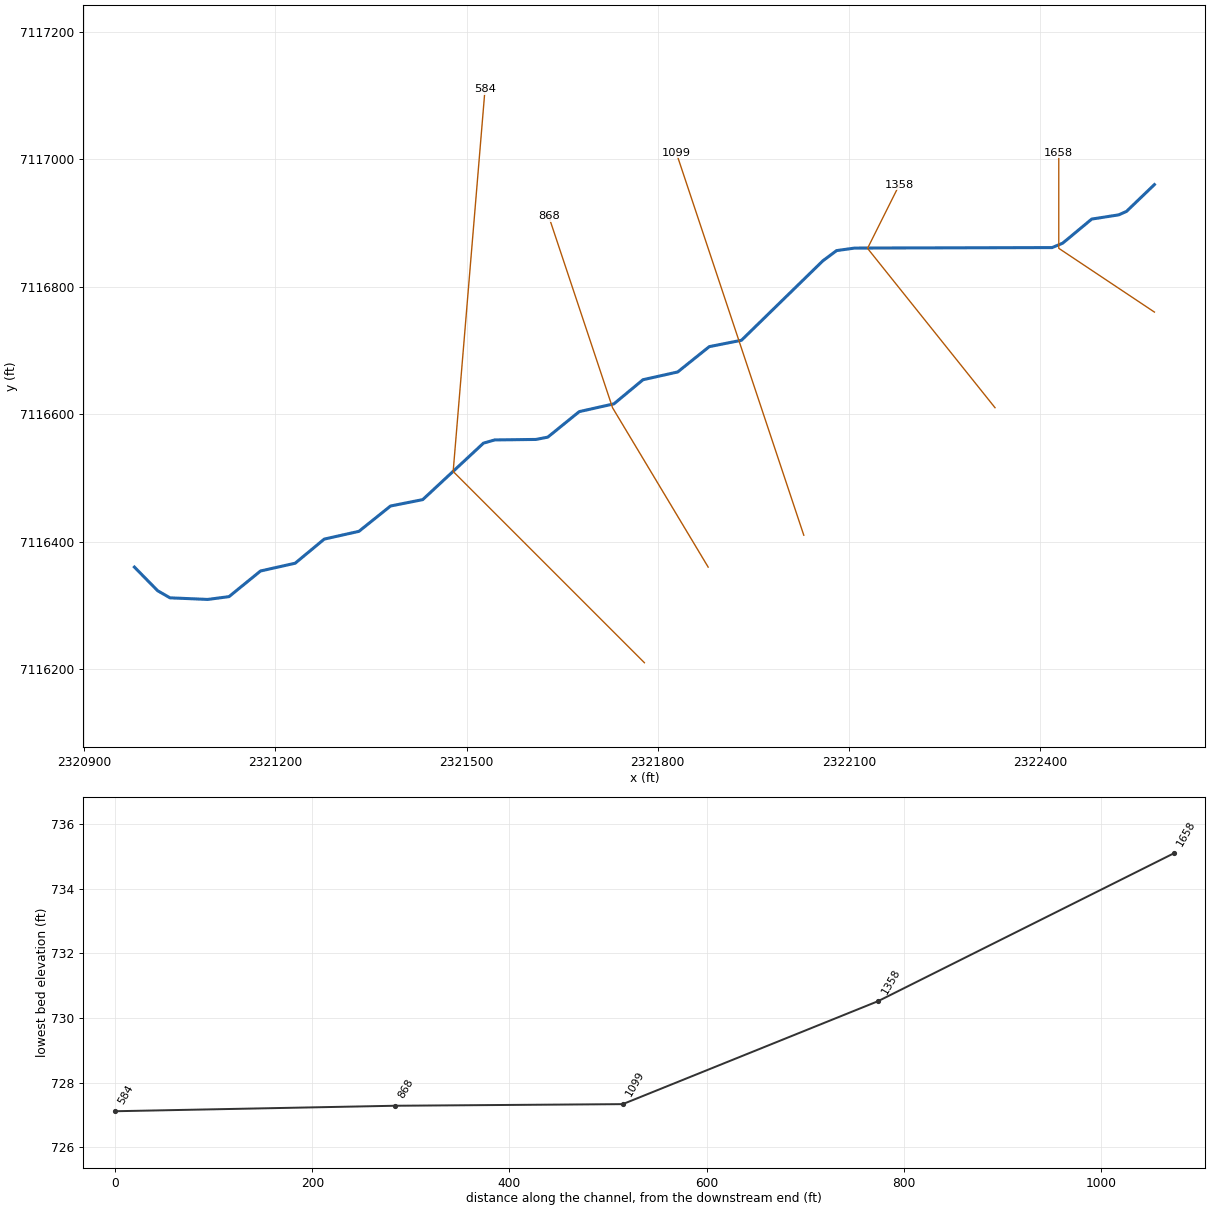
--- MDE S 061.prj (project) ---

Proj Title=MDE S 061 Base Level Engineering
Current Plan=p01
Default Exp/Contr=0.3,0.1
English Units
Geom File=g01
Flow File=f01
Plan File=p01
BEGIN DESCRIPTION:
MDE S 061
END DESCRIPTION:

--- MDE S 061.p01 (plan) ---

Plan Title=Multiple Run
Short Identifier=Multiple
Geom File=g01
Flow File=f01
Subcritical Flow
K Sum by GR= 0
Std Step Tol= 0.01
Critical Tol= 0.01
Num of Std Step Trials= 20
Max Error Tol= 0.3
Flow Tol Ratio= 0.001
Split Flow NTrial= 30
Split Flow Tol= 0.02
Split Flow Ratio= 0.02
Log Output Level= 0
Friction Slope Method= 1
Unsteady Friction Slope Method= 2
Unsteady Bridges Friction Slope Method= 1
Parabolic Critical Depth
Global Vel Dist=  1 , 1 , 1
Global Log Level= 0
CheckData=True
Encroach Param= -1, 0, 0, 0
BEGIN DESCRIPTION:
Multiple Run
END DESCRIPTION:

--- MDE S 061.f01 (steady flow) ---

Flow Title=Multiple
Number of Profiles=7
Profile Names=10-year,25-year,50-year,1pct_min,100-year,1pct_plu,500-year
River Rch & RM= MDE S 061,Reach-1,1658
     194     248     290     170     338     675     459
Boundary for River Rch & Prof#=MDE S 061,Reach-1,1
Up Type=0
Dn Type=3
Dn Slope=0.005
Boundary for River Rch & Prof#=MDE S 061,Reach-1,2
Up Type=0
Dn Type=3
Dn Slope=0.005
Boundary for River Rch & Prof#=MDE S 061,Reach-1,3
Up Type=0
Dn Type=3
Dn Slope=0.005
Boundary for River Rch & Prof#=MDE S 061,Reach-1,4
Up Type=0
Dn Type=3
Dn Slope=0.005
Boundary for River Rch & Prof#=MDE S 061,Reach-1,5
Up Type=0
Dn Type=3
Dn Slope=0.005
Boundary for River Rch & Prof#=MDE S 061,Reach-1,6
Up Type=0
Dn Type=3
Dn Slope=0.005
Boundary for River Rch & Prof#=MDE S 061,Reach-1,7
Up Type=0
Dn Type=3
Dn Slope=0.005

--- MDE S 061.g01 (geometry) ---

Geom Title=Existing Conditions

River Reach=MDE S 061,Reach-1
Reach XY= 30
      2322579.00      7116960.00      2322535.15      7116917.91
      2322522.96      7116912.51      2322480.69      7116905.92
      2322435.08      7116868.08      2322418.51      7116861.19
      2322108.82      7116860.43      2322080.46      7116856.46
      2322058.84      7116840.39      2321931.30      7116715.83
      2321880.74      7116705.81      2321831.20      7116666.08
      2321776.80      7116653.92      2321731.20      7116616.08
      2321676.82      7116603.88      2321627.41      7116563.83
      2321608.90      7116560.24      2321544.22      7116559.47
      2321526.58      7116554.46      2321431.29      7116465.85
      2321380.74      7116455.81      2321331.20      7116416.08
      2321276.80      7116403.92      2321231.20      7116366.08
      2321176.82      7116353.88      2321127.43      7116313.67
      2321094.10      7116309.27      2321034.83      7116311.77
      2321015.52      7116322.87      2320979.00      7116360.00

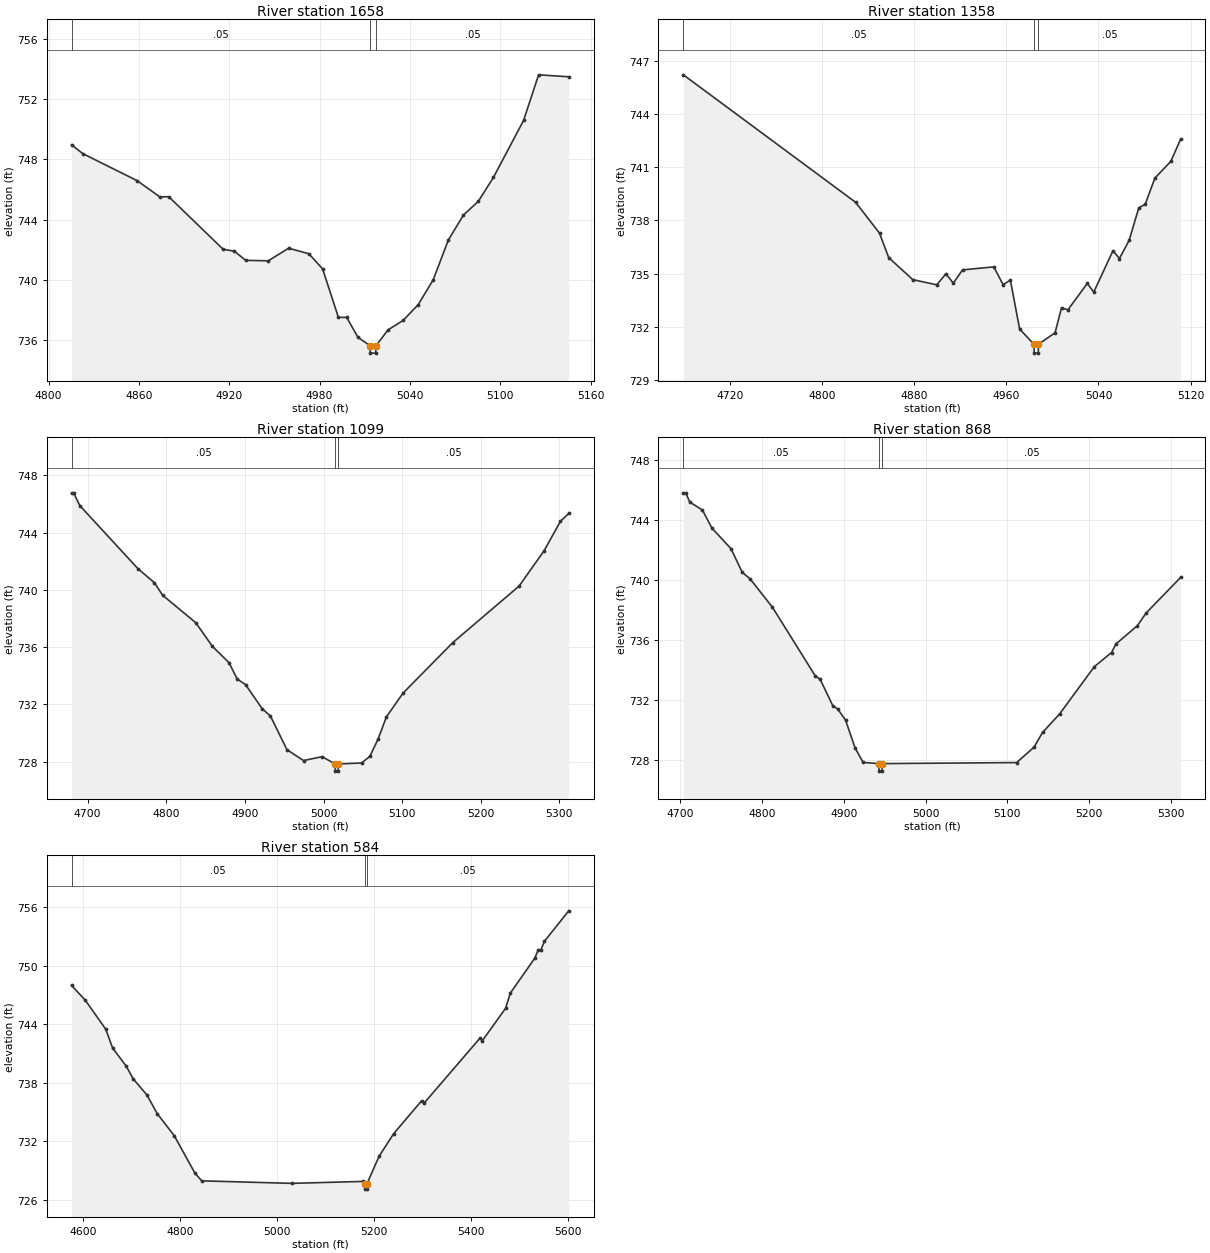
Type RM Length L Ch R = 1,1658,300,300,300
BEGIN DESCRIPTION:
MDE S 061 5.0
END DESCRIPTION:
XS GIS Cut Line= 3
      2322579.01      7116760.00      2322429.00      7116860.00
      2322429.00      7117010.02
#Sta/Elev= 30
  4815.2  748.98  4822.7  748.39  4858.8  746.59  4873.8  745.51  4879.8  745.52
  4915.9  742.02  4923.4  741.89  4930.9  741.28  4945.9  741.25  4959.4  742.09
  4972.9  741.72  4982.0  740.71  4992.5  737.48  4998.0  737.48  5005.5  736.15
  5013.5  735.60  5013.7  735.10  5017.2  735.10  5017.5  735.60  5025.5  736.65
  5035.5  737.28  5045.5  738.33  5055.5  739.99  5065.5  742.63  5075.5  744.29
  5085.5  745.22  5095.5  746.81  5115.5  750.60  5125.5  753.64  5145.5  753.51
#Mann=3,-1,0
  4815.2    0.05       0  5013.5   0.033       0  5017.5    0.05       0
Bank Sta=5013.5,5017.5
Exp/Cntr=0.3,0.1

Type RM Length L Ch R = 1,1358,259,259,259
BEGIN DESCRIPTION:
MDE S 061 4.0
END DESCRIPTION:
XS GIS Cut Line= 3
      2322328.98      7116610.03      2322129.00      7116860.00
      2322178.99      7116959.98
#Sta/Elev= 30
  4679.4  746.20  4829.0  739.02  4849.8  737.28  4857.8  735.90  4878.7  734.66
  4899.5  734.37  4907.5  734.99  4913.9  734.46  4921.9  735.21  4949.1  735.38
  4957.1  734.38  4963.5  734.63  4971.5  731.88  4983.9  731.02  4984.2  730.52
  4987.7  730.52  4987.9  731.02  5002.3  731.67  5007.9  733.07  5013.5  732.96
  5030.3  734.45  5035.9  733.96  5052.6  736.29  5058.2  735.85  5066.6  736.87
  5075.0  738.70  5080.6  738.91  5089.0  740.38  5102.9  741.33  5111.3  742.57
#Mann=3,-1,0
  4679.4    0.05       0  4983.9   0.033       0  4987.9    0.05       0
Bank Sta=4983.9,4987.9
Exp/Cntr=0.3,0.1

Type RM Length L Ch R = 1,1099,231,231,231
BEGIN DESCRIPTION:
MDE S 061 3.0
END DESCRIPTION:
XS GIS Cut Line= 3
      2322028.99      7116410.03      2321929.00      7116710.00
      2321829.01      7117009.97
#Sta/Elev= 30
  4679.5  746.78  4682.1  746.78  4690.0  745.89  4763.8  741.49  4784.9  740.50
  4795.4  739.62  4837.6  737.70  4858.7  736.05  4879.8  734.91  4890.3  733.76
  4900.8  733.38  4921.9  731.70  4932.5  731.18  4953.5  728.83  4974.6  728.07
  4998.3  728.34  5014.8  727.83  5015.0  727.33  5018.5  727.33  5018.8  727.83
  5048.4  727.90  5058.9  728.36  5069.5  729.58  5080.0  731.12  5101.1  732.78
  5164.4  736.31  5248.7  740.26  5280.3  742.71  5301.4  744.79  5311.9  745.34
#Mann=3,-1,0
  4679.5    0.05       0  5014.8   0.033       0  5018.8    0.05       0
Bank Sta=5014.8,5018.8
Exp/Cntr=0.3,0.1

Type RM Length L Ch R = 1,868,284,284,284
BEGIN DESCRIPTION:
MDE S 061 2.0
END DESCRIPTION:
XS GIS Cut Line= 3
      2321879.01      7116359.98      2321729.00      7116610.00
      2321629.00      7116910.00
#Sta/Elev= 30
  4703.9  745.79  4706.8  745.79  4711.7  745.18  4727.2  744.64  4738.9  743.44
  4762.2  742.07  4775.8  740.51  4785.6  740.06  4812.8  738.18  4865.2  733.61
  4871.1  733.39  4886.6  731.63  4892.5  731.42  4902.2  730.67  4913.8  728.83
  4923.6  727.86  4942.9  727.78  4943.2  727.28  4946.7  727.28  4946.9  727.78
  5111.4  727.85  5132.5  728.87  5143.0  729.85  5164.1  731.10  5206.3  734.23
  5227.4  735.17  5232.6  735.73  5259.0  736.96  5269.5  737.79  5311.7  740.16
#Mann=3,-1,0
  4703.9    0.05       0  4942.9   0.033       0  4946.9    0.05       0
Bank Sta=4942.9,4946.9
Exp/Cntr=0.3,0.1

Type RM Length L Ch R = 1,584,0,0,0
BEGIN DESCRIPTION:
MDE S 061 1.0
END DESCRIPTION:
XS GIS Cut Line= 3
      2321779.00      7116210.00      2321479.00      7116510.00
      2321529.00      7117109.96
#Sta/Elev= 30
  4575.7  747.98  4604.0  746.47  4646.4  743.49  4660.5  741.57  4688.8  739.69
  4703.0  738.41  4731.3  736.76  4752.5  734.85  4787.8  732.58  4830.3  728.76
  4844.4  727.96  5030.1  727.70  5178.1  727.90  5181.1  727.61  5181.3  727.11
  5184.8  727.11  5185.1  727.61  5210.7  730.49  5240.8  732.80  5298.5  736.17
  5303.5  735.92  5418.9  742.58  5423.9  742.33  5471.6  745.63  5481.6  747.20
  5531.8  750.76  5539.3  751.64  5544.3  751.60  5551.9  752.50  5602.0  755.62
#Mann=3,-1,0
  4575.7    0.05       0  5181.1   0.033       0  5185.1    0.05       0
Bank Sta=5181.1,5185.1
Exp/Cntr=0.3,0.1

Chan Stop Cuts=-1