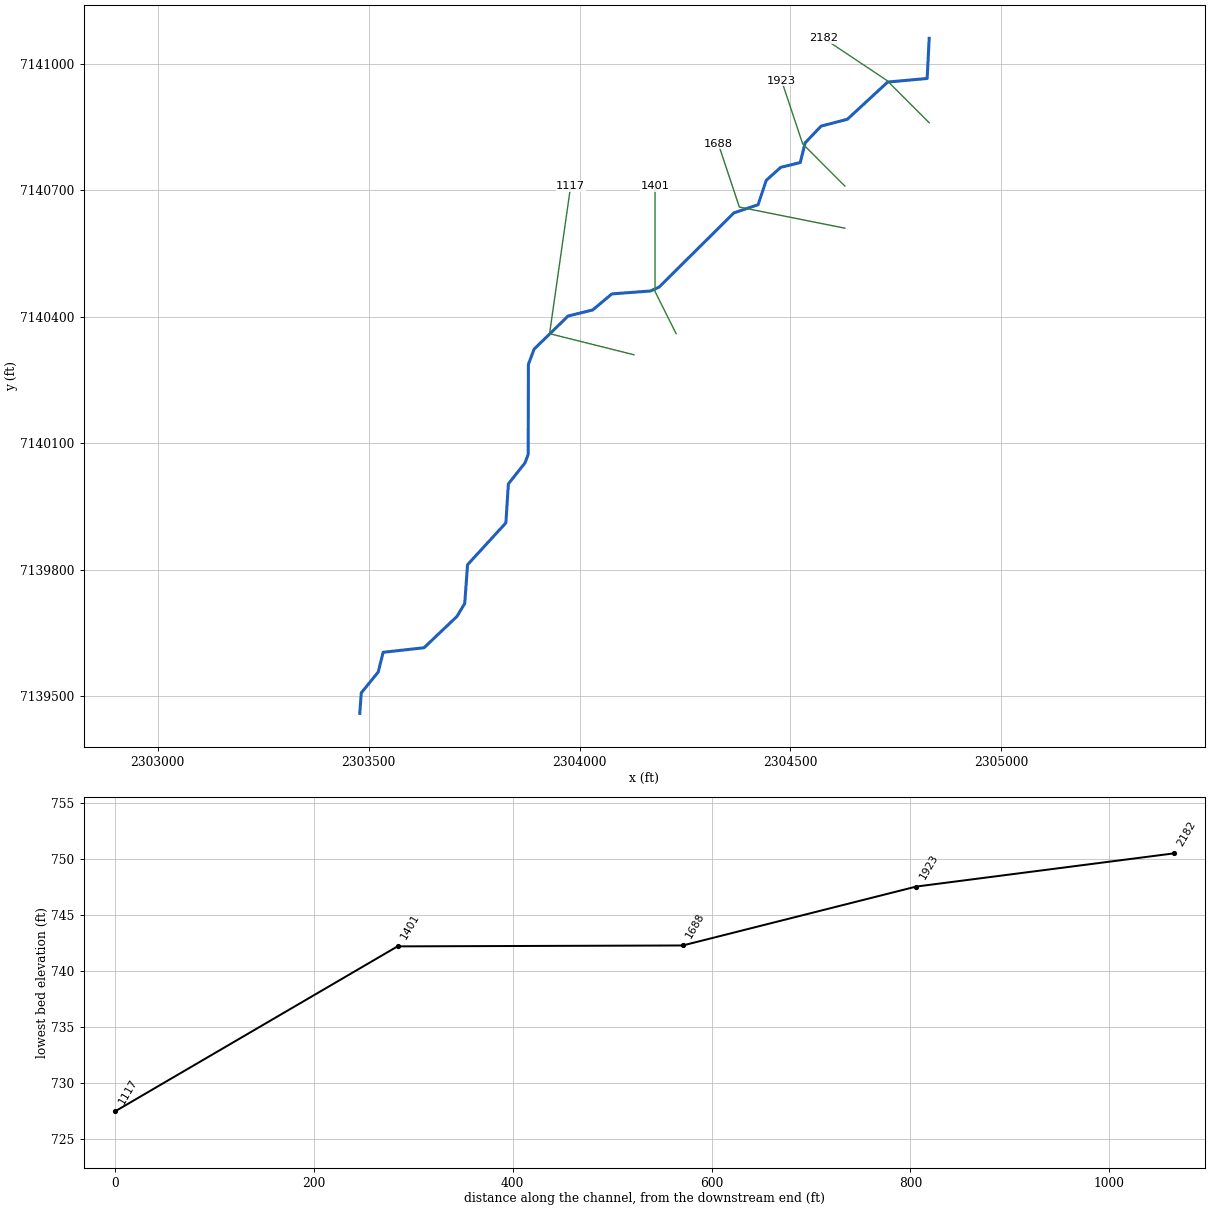
--- MDE S 068.prj (project) ---

Proj Title=MDE S 068 Base Level Engineering
Current Plan=p01
Default Exp/Contr=0.3,0.1
English Units
Geom File=g01
Flow File=f01
Plan File=p01
BEGIN DESCRIPTION:
MDE S 068
END DESCRIPTION:

--- MDE S 068.p01 (plan) ---

Plan Title=Multiple Run
Short Identifier=Multiple
Geom File=g01
Flow File=f01
Subcritical Flow
K Sum by GR= 0
Std Step Tol= 0.01
Critical Tol= 0.01
Num of Std Step Trials= 20
Max Error Tol= 0.3
Flow Tol Ratio= 0.001
Split Flow NTrial= 30
Split Flow Tol= 0.02
Split Flow Ratio= 0.02
Log Output Level= 0
Friction Slope Method= 1
Unsteady Friction Slope Method= 2
Unsteady Bridges Friction Slope Method= 1
Parabolic Critical Depth
Global Vel Dist=  1 , 1 , 1
Global Log Level= 0
CheckData=True
Encroach Param= -1, 0, 0, 0
BEGIN DESCRIPTION:
Multiple Run
END DESCRIPTION:

--- MDE S 068.f01 (steady flow) ---

Flow Title=Multiple
Number of Profiles=7
Profile Names=10-year,25-year,50-year,1pct_min,100-year,1pct_plu,500-year
River Rch & RM= MDE S 068,Reach-1,2182
     224     290     342     201     401     801     552
Boundary for River Rch & Prof#=MDE S 068,Reach-1,1
Up Type=0
Dn Type=3
Dn Slope=0.005
Boundary for River Rch & Prof#=MDE S 068,Reach-1,2
Up Type=0
Dn Type=3
Dn Slope=0.005
Boundary for River Rch & Prof#=MDE S 068,Reach-1,3
Up Type=0
Dn Type=3
Dn Slope=0.005
Boundary for River Rch & Prof#=MDE S 068,Reach-1,4
Up Type=0
Dn Type=3
Dn Slope=0.005
Boundary for River Rch & Prof#=MDE S 068,Reach-1,5
Up Type=0
Dn Type=3
Dn Slope=0.005
Boundary for River Rch & Prof#=MDE S 068,Reach-1,6
Up Type=0
Dn Type=3
Dn Slope=0.005
Boundary for River Rch & Prof#=MDE S 068,Reach-1,7
Up Type=0
Dn Type=3
Dn Slope=0.005

--- MDE S 068.g01 (geometry) ---

Geom Title=Existing Conditions

River Reach=MDE S 068,Reach-1
Reach XY= 30
      2304829.00      7141060.00      2304824.18      7140964.87
      2304730.57      7140956.35      2304635.02      7140868.18
      2304572.69      7140851.91      2304534.89      7140812.21
      2304523.34      7140765.66      2304476.81      7140754.08
      2304442.65      7140723.31      2304423.37      7140665.65
      2304366.02      7140646.28      2304188.79      7140470.52
      2304168.52      7140461.16      2304076.68      7140454.23
      2304031.17      7140416.14      2303972.92      7140401.87
      2303892.36      7140323.34      2303878.80      7140287.36
      2303878.32      7140073.92      2303870.86      7140053.94
      2303831.36      7140004.02      2303825.38      7139911.50
      2303734.54      7139812.42      2303727.84      7139720.48
      2303709.39      7139689.80      2303631.38      7139615.54
      2303534.42      7139604.78      2303522.84      7139558.20
      2303482.58      7139508.56      2303479.00      7139460.00

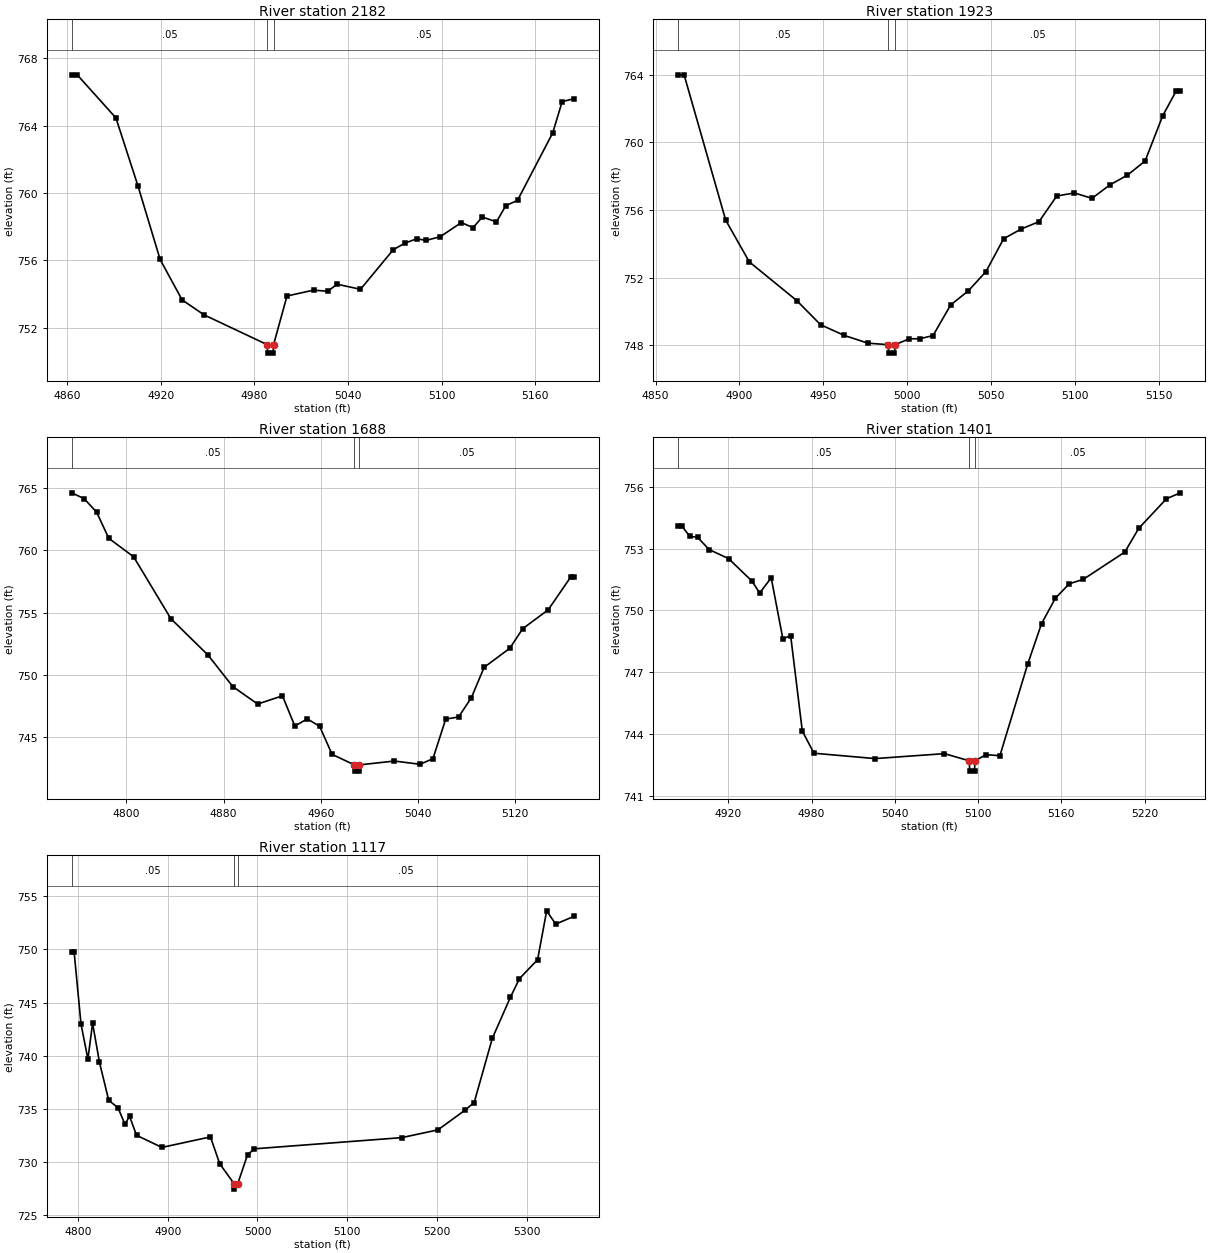
Type RM Length L Ch R = 1,2182,259,259,259
BEGIN DESCRIPTION:
MDE S 068 8.0
END DESCRIPTION:
XS GIS Cut Line= 3
      2304829.00      7140860.00      2304729.00      7140960.00
      2304579.00      7141060.00
#Sta/Elev= 30
  4863.0  767.01  4866.5  767.01  4891.3  764.45  4905.4  760.42  4919.6  756.05
  4933.7  753.65  4947.8  752.76  4988.3  750.99  4988.5  750.49  4992.0  750.49
  4992.3  750.99  5000.9  753.88  5017.9  754.23  5027.0  754.16  5033.0  754.58
  5048.0  754.28  5069.0  756.63  5076.5  757.02  5084.0  757.28  5090.0  757.18
  5099.1  757.40  5112.6  758.24  5120.1  757.94  5126.1  758.57  5135.1  758.28
  5141.1  759.24  5148.6  759.56  5171.2  763.57  5177.2  765.42  5184.7  765.59
#Mann=3,-1,0
  4863.0    0.05       0  4988.3    0.04       0  4992.3    0.05       0
Bank Sta=4988.3,4992.3
Exp/Cntr=0.3,0.1

Type RM Length L Ch R = 1,1923,235,235,235
BEGIN DESCRIPTION:
MDE S 068 7.0
END DESCRIPTION:
XS GIS Cut Line= 3
      2304629.01      7140709.99      2304529.00      7140810.00
      2304479.01      7140959.96
#Sta/Elev= 30
  4863.5  764.00  4867.0  764.00  4891.8  755.40  4905.9  752.93  4934.2  750.64
  4948.4  749.21  4962.5  748.58  4976.6  748.12  4988.8  748.03  4989.0  747.53
  4992.5  747.53  4992.8  748.03  5001.4  748.38  5007.6  748.38  5015.5  748.57
  5026.0  750.38  5036.6  751.22  5047.1  752.36  5057.6  754.30  5068.2  754.88
  5078.7  755.31  5089.3  756.83  5099.8  757.01  5110.3  756.69  5120.9  757.48
  5131.4  758.06  5142.0  758.90  5152.5  761.58  5160.4  763.02  5163.0  763.02
#Mann=3,-1,0
  4863.5    0.05       0  4988.8   0.033       0  4992.8    0.05       0
Bank Sta=4988.8,4992.8
Exp/Cntr=0.3,0.1

Type RM Length L Ch R = 1,1688,287,287,287
BEGIN DESCRIPTION:
MDE S 068 6.0
END DESCRIPTION:
XS GIS Cut Line= 3
      2304628.96      7140610.01      2304379.00      7140660.00
      2304329.01      7140809.98
#Sta/Elev= 30
  4755.1  764.63  4765.3  764.16  4775.5  763.08  4785.6  760.97  4806.0  759.49
  4836.6  754.52  4867.2  751.59  4887.6  749.06  4908.0  747.66  4928.4  748.32
  4938.6  745.89  4948.8  746.47  4959.0  745.87  4969.2  743.62  4987.6  742.77
  4987.9  742.27  4991.4  742.27  4991.6  742.77  5020.5  743.08  5041.6  742.82
  5052.2  743.27  5062.7  746.45  5073.3  746.62  5083.8  748.17  5094.3  750.61
  5115.4  752.14  5126.0  753.71  5147.0  755.23  5165.5  757.86  5168.1  757.86
#Mann=3,-1,0
  4755.1    0.05       0  4987.6   0.033       0  4991.6    0.05       0
Bank Sta=4987.6,4991.6
Exp/Cntr=0.3,0.1

Type RM Length L Ch R = 1,1401,284,284,284
BEGIN DESCRIPTION:
MDE S 068 5.0
END DESCRIPTION:
XS GIS Cut Line= 3
      2304228.98      7140360.04      2304179.00      7140460.00
      2304179.00      7140710.04
#Sta/Elev= 30
  4883.9  754.09  4886.7  754.09  4892.2  753.60  4897.8  753.56  4906.2  752.96
  4920.2  752.52  4937.0  751.43  4942.6  750.85  4950.9  751.59  4959.3  748.62
  4964.9  748.78  4973.3  744.14  4981.7  743.06  5025.7  742.80  5075.7  743.04
  5093.7  742.69  5093.9  742.19  5097.4  742.19  5097.7  742.69  5105.7  742.99
  5115.7  742.94  5135.7  747.39  5145.7  749.36  5155.7  750.60  5165.7  751.30
  5175.7  751.51  5205.7  752.84  5215.7  753.99  5235.7  755.43  5245.7  755.72
#Mann=3,-1,0
  4883.9    0.05       0  5093.7   0.033       0  5097.7    0.05       0
Bank Sta=5093.7,5097.7
Exp/Cntr=0.3,0.1

Type RM Length L Ch R = 1,1117,0,0,0
BEGIN DESCRIPTION:
MDE S 068 4.0
END DESCRIPTION:
XS GIS Cut Line= 3
      2304129.01      7140310.00      2303929.00      7140360.00
      2303979.00      7140709.98
#Sta/Elev= 30
  4793.0  749.78  4795.6  749.78  4803.3  742.98  4811.0  739.69  4816.2  743.06
  4823.9  739.38  4834.2  735.82  4844.5  735.12  4852.3  733.57  4857.4  734.32
  4865.2  732.53  4893.5  731.39  4947.6  732.38  4957.9  729.86  4974.0  727.97
  4974.2  727.47  4978.0  727.97  4988.9  730.69  4996.6  731.26  5160.8  732.31
  5201.2  733.04  5231.5  734.90  5241.6  735.61  5261.8  741.64  5282.0  745.51
  5292.1  747.26  5312.3  749.04  5322.4  753.63  5332.5  752.38  5352.7  753.11
#Mann=3,-1,0
  4793.0    0.05       0  4974.0   0.033       0  4978.0    0.05       0
Bank Sta=4974,4978
Exp/Cntr=0.3,0.1

Chan Stop Cuts=-1