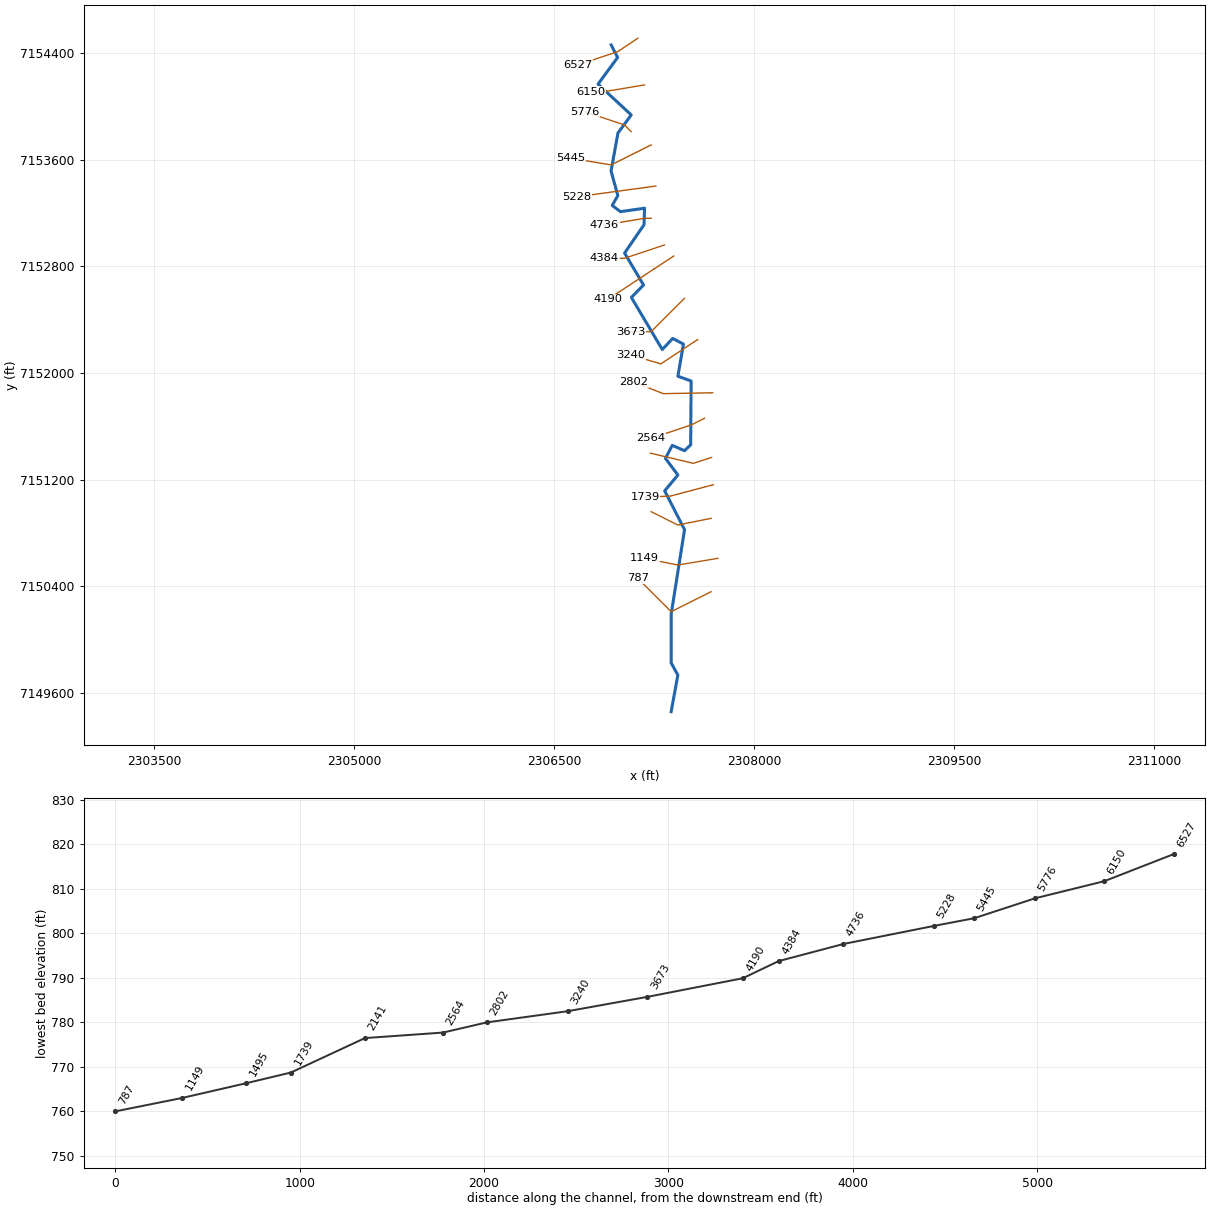
--- MDE S 071.prj (project) ---

Proj Title=MDE S 071 Base Level Engineering
Current Plan=p01
Default Exp/Contr=0.3,0.1
English Units
Geom File=g01
Flow File=f01
Plan File=p01
BEGIN DESCRIPTION:
MDE S 071
END DESCRIPTION:

--- MDE S 071.p01 (plan) ---

Plan Title=Multiple Run
Short Identifier=Multiple
Geom File=g01
Flow File=f01
Subcritical Flow
K Sum by GR= 0
Std Step Tol= 0.01
Critical Tol= 0.01
Num of Std Step Trials= 20
Max Error Tol= 0.3
Flow Tol Ratio= 0.001
Split Flow NTrial= 30
Split Flow Tol= 0.02
Split Flow Ratio= 0.02
Log Output Level= 0
Friction Slope Method= 1
Unsteady Friction Slope Method= 2
Unsteady Bridges Friction Slope Method= 1
Parabolic Critical Depth
Global Vel Dist=  1 , 1 , 1
Global Log Level= 0
CheckData=True
Encroach Param= -1, 0, 0, 0
BEGIN DESCRIPTION:
Multiple Run
END DESCRIPTION:

--- MDE S 071.f01 (steady flow) ---

Flow Title=Multiple
Number of Profiles=7
Profile Names=10-year,25-year,50-year,1pct_min,100-year,1pct_plu,500-year
River Rch & RM= MDE S 071,Reach-1,6527
     676     931    1143     698    1392    2777    2066
Boundary for River Rch & Prof#=MDE S 071,Reach-1,1
Up Type=0
Dn Type=3
Dn Slope=0.005
Boundary for River Rch & Prof#=MDE S 071,Reach-1,2
Up Type=0
Dn Type=3
Dn Slope=0.005
Boundary for River Rch & Prof#=MDE S 071,Reach-1,3
Up Type=0
Dn Type=3
Dn Slope=0.005
Boundary for River Rch & Prof#=MDE S 071,Reach-1,4
Up Type=0
Dn Type=3
Dn Slope=0.005
Boundary for River Rch & Prof#=MDE S 071,Reach-1,5
Up Type=0
Dn Type=3
Dn Slope=0.005
Boundary for River Rch & Prof#=MDE S 071,Reach-1,6
Up Type=0
Dn Type=3
Dn Slope=0.005
Boundary for River Rch & Prof#=MDE S 071,Reach-1,7
Up Type=0
Dn Type=3
Dn Slope=0.005

--- MDE S 071.g01 (geometry) ---

Geom Title=Existing Conditions

River Reach=MDE S 071,Reach-1
Reach XY= 30
      2306929.00      7154460.00      2306977.46      7154365.97
      2306830.57      7154166.04      2307079.59      7153935.00
      2306980.06      7153799.56      2306928.19      7153515.03
      2306978.98      7153330.05      2306936.68      7153256.29
      2306998.83      7153209.79      2307179.36      7153235.61
      2307175.46      7153111.48      2307029.74      7152899.31
      2307171.97      7152659.79      2307080.61      7152566.51
      2307312.38      7152176.15      2307391.08      7152258.86
      2307471.31      7152216.57      2307429.46      7151975.65
      2307529.01      7151940.01      2307525.47      7151460.99
      2307479.30      7151417.26      2307387.45      7151457.33
      2307336.29      7151359.95      2307429.61      7151234.92
      2307330.58      7151116.09      2307479.49      7150825.49
      2307379.07      7150189.97      2307379.54      7149825.21
      2307429.40      7149735.00      2307379.00      7149460.00

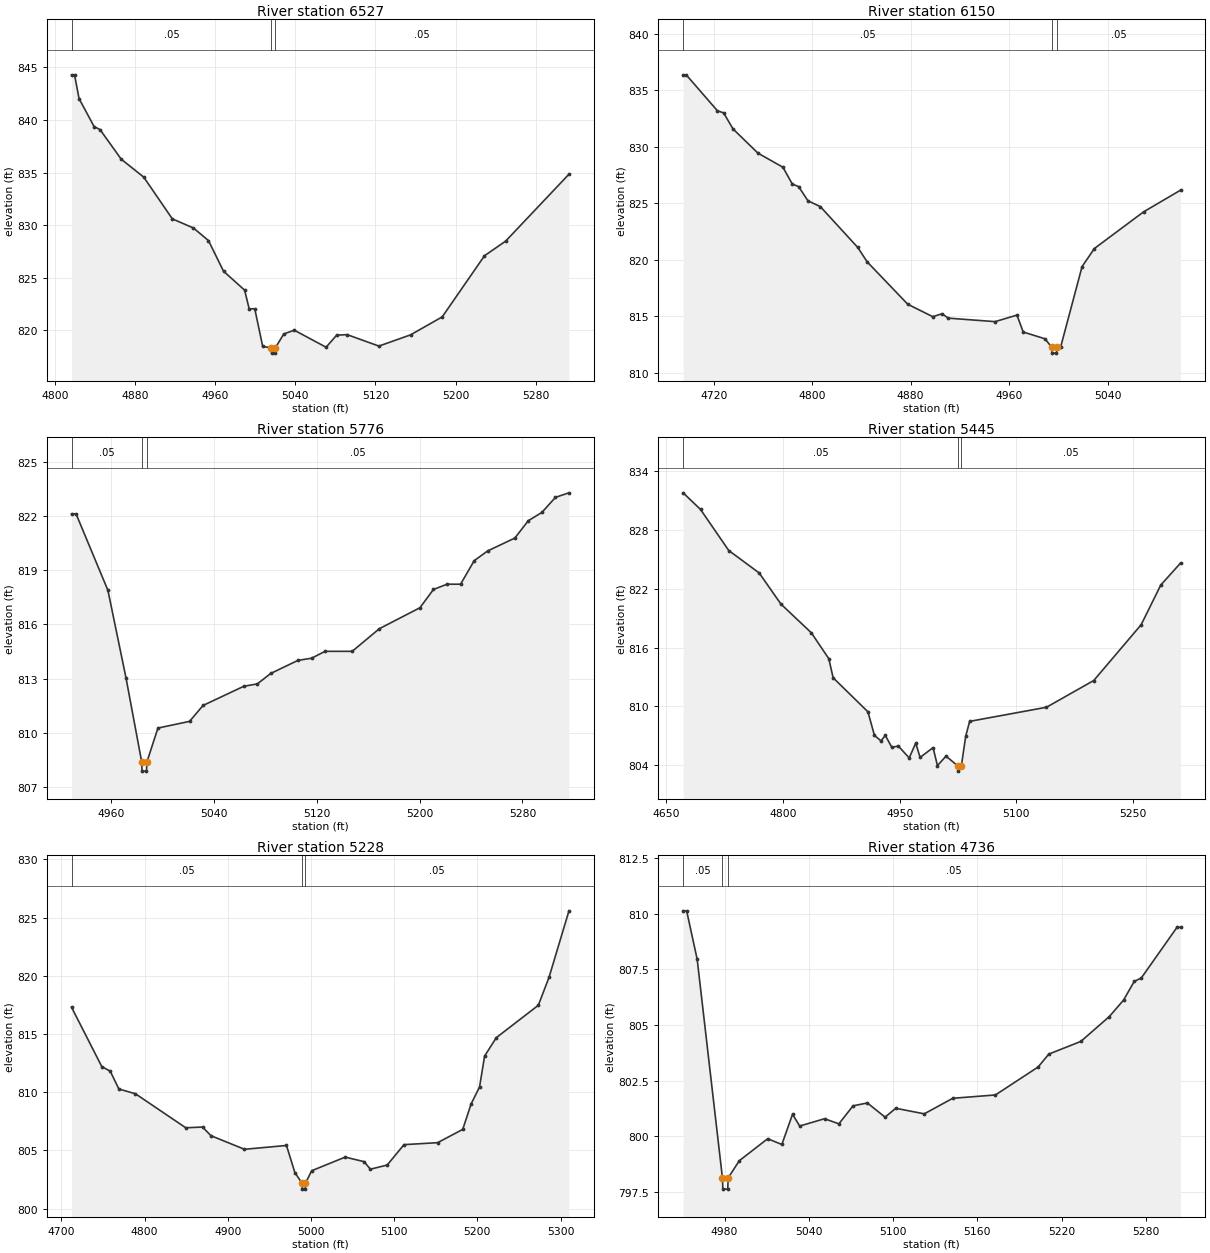
Type RM Length L Ch R = 1,6527,377,377,377
BEGIN DESCRIPTION:
MDE S 071 17.0
END DESCRIPTION:
XS GIS Cut Line= 3
      2307128.99      7154510.00      2306979.00      7154410.00
      2306679.00      7154310.00
#Sta/Elev= 30
  4816.6  844.30  4819.6  844.30  4824.1  842.04  4839.1  839.38  4845.1  839.08
  4866.2  836.27  4888.7  834.56  4917.2  830.59  4938.3  829.72  4953.3  828.52
  4968.3  825.61  4989.4  823.80  4993.9  822.03  4999.5  822.03  5007.4  818.45
  5016.0  818.31  5016.2  817.81  5019.7  817.81  5020.0  818.31  5028.5  819.64
  5039.0  819.99  5070.7  818.37  5081.2  819.52  5091.7  819.57  5123.4  818.48
  5155.0  819.55  5186.6  821.26  5228.8  827.08  5249.9  828.47  5313.1  834.84
#Mann=3,-1,0
  4816.6    0.05       0  5016.0   0.033       0  5020.0    0.05       0
Bank Sta=5016,5020
Exp/Cntr=0.3,0.1

Type RM Length L Ch R = 1,6150,374,374,374
BEGIN DESCRIPTION:
MDE S 071 16.0
END DESCRIPTION:
XS GIS Cut Line= 3
      2307178.99      7154160.00      2306879.00      7154110.00
      2306779.03      7154110.00
#Sta/Elev= 30
  4695.2  836.38  4697.7  836.38  4723.1  833.19  4728.1  833.01  4735.7  831.59
  4756.0  829.44  4776.3  828.19  4783.9  826.70  4789.0  826.48  4796.6  825.22
  4806.7  824.70  4837.1  821.08  4844.7  819.81  4877.7  816.05  4898.0  814.95
  4905.6  815.21  4910.6  814.82  4948.6  814.51  4966.4  815.09  4971.5  813.59
  4989.2  812.99  4994.8  812.22  4995.0  811.72  4998.5  811.72  4998.8  812.22
  5001.8  812.22  5019.3  819.39  5029.3  820.99  5069.3  824.24  5099.3  826.16
#Mann=3,-1,0
  4695.2    0.05       0  4994.8   0.033       0  4998.8    0.05       0
Bank Sta=4994.8,4998.8
Exp/Cntr=0.3,0.1

Type RM Length L Ch R = 1,5776,331,331,331
BEGIN DESCRIPTION:
MDE S 071 15.0
END DESCRIPTION:
XS GIS Cut Line= 3
      2307079.00      7153810.00      2307029.00      7153860.00
      2306729.04      7153959.99
#Sta/Elev= 30
  4929.3  822.11  4932.8  822.11  4957.6  817.88  4971.7  813.03  4983.9  808.39
  4984.1  807.89  4987.6  807.89  4987.9  808.39  4996.5  810.27  5021.1  810.64
  5031.6  811.52  5063.3  812.58  5073.8  812.71  5084.3  813.29  5105.4  814.01
  5116.0  814.13  5126.5  814.51  5147.6  814.51  5168.7  815.76  5200.3  816.92
  5210.8  817.93  5221.4  818.22  5231.9  818.22  5242.5  819.52  5253.0  820.06
  5274.1  820.77  5284.6  821.73  5295.2  822.19  5305.7  823.02  5316.2  823.27
#Mann=3,-1,0
  4929.3    0.05       0  4983.9   0.033       0  4987.9    0.05       0
Bank Sta=4983.9,4987.9
Exp/Cntr=0.3,0.1

Type RM Length L Ch R = 1,5445,217,217,217
BEGIN DESCRIPTION:
MDE S 071 14.0
END DESCRIPTION:
XS GIS Cut Line= 3
      2307229.01      7153710.01      2306929.00      7153560.00
      2306628.96      7153610.01
#Sta/Elev= 30
  4671.5  831.81  4693.9  830.11  4730.2  825.92  4769.3  823.63  4797.3  820.45
  4836.4  817.52  4858.8  814.88  4864.4  812.93  4909.1  809.46  4917.5  807.05
  4925.9  806.49  4931.5  807.05  4939.8  805.83  4948.2  805.96  4962.2  804.75
  4970.6  806.26  4976.2  804.80  4992.9  805.80  4998.5  803.96  5009.5  804.93
  5025.2  803.90  5025.5  803.40  5029.2  803.90  5034.8  806.94  5039.9  808.48
  5138.7  809.92  5199.5  812.65  5260.4  818.34  5285.7  822.40  5311.1  824.64
#Mann=3,-1,0
  4671.5    0.05       0  5025.2   0.033       0  5029.2    0.05       0
Bank Sta=5025.2,5029.2
Exp/Cntr=0.3,0.1

Type RM Length L Ch R = 1,5228,492,492,492
BEGIN DESCRIPTION:
Mapping XS e09ed212
END DESCRIPTION:
XS GIS Cut Line= 2
      2307265.05      7153402.01      2306672.50      7153321.48
#Sta/Elev= 30
  4712.1  817.30  4748.5  812.20  4758.6  811.81  4769.0  810.28  4788.9  809.87
  4849.4  806.95  4869.6  807.01  4879.7  806.27  4920.0  805.10  4970.5  805.43
  4980.6  803.10  4989.3  802.18  4989.6  801.68  4993.1  801.68  4993.3  802.18
  5000.8  803.26  5041.1  804.43  5063.8  804.04  5071.4  803.39  5091.6  803.75
  5111.8  805.50  5152.2  805.67  5182.4  806.81  5192.5  809.00  5202.6  810.45
  5208.7  813.11  5222.8  814.69  5273.3  817.47  5286.2  819.88  5310.1  825.58
#Mann=3,-1,0
  4712.1    0.05       0  4989.3   0.033       0  4993.3    0.05       0
Bank Sta=4989.3,4993.3
Exp/Cntr=0.3,0.1

Type RM Length L Ch R = 1,4736,352,352,352
BEGIN DESCRIPTION:
MDE S 071 12.0
END DESCRIPTION:
XS GIS Cut Line= 3
      2307229.05      7153160.00      2307179.00      7153160.00
      2306878.99      7153110.00
#Sta/Elev= 30
  4950.5  810.14  4953.0  810.14  4960.5  807.96  4978.5  798.11  4978.8  797.61
  4982.3  797.61  4982.5  798.11  4990.5  798.89  5010.7  799.88  5020.8  799.62
  5028.4  800.98  5033.5  800.45  5051.2  800.78  5061.4  800.55  5071.5  801.36
  5081.7  801.49  5094.3  800.85  5101.9  801.25  5122.2  801.00  5142.5  801.70
  5172.9  801.85  5203.3  803.11  5210.9  803.69  5233.7  804.26  5254.0  805.38
  5264.1  806.12  5271.7  806.96  5276.8  807.12  5302.2  809.40  5304.7  809.40
#Mann=3,-1,0
  4950.5    0.05       0  4978.5   0.033       0  4982.5    0.05       0
Bank Sta=4978.5,4982.5
Exp/Cntr=0.3,0.1

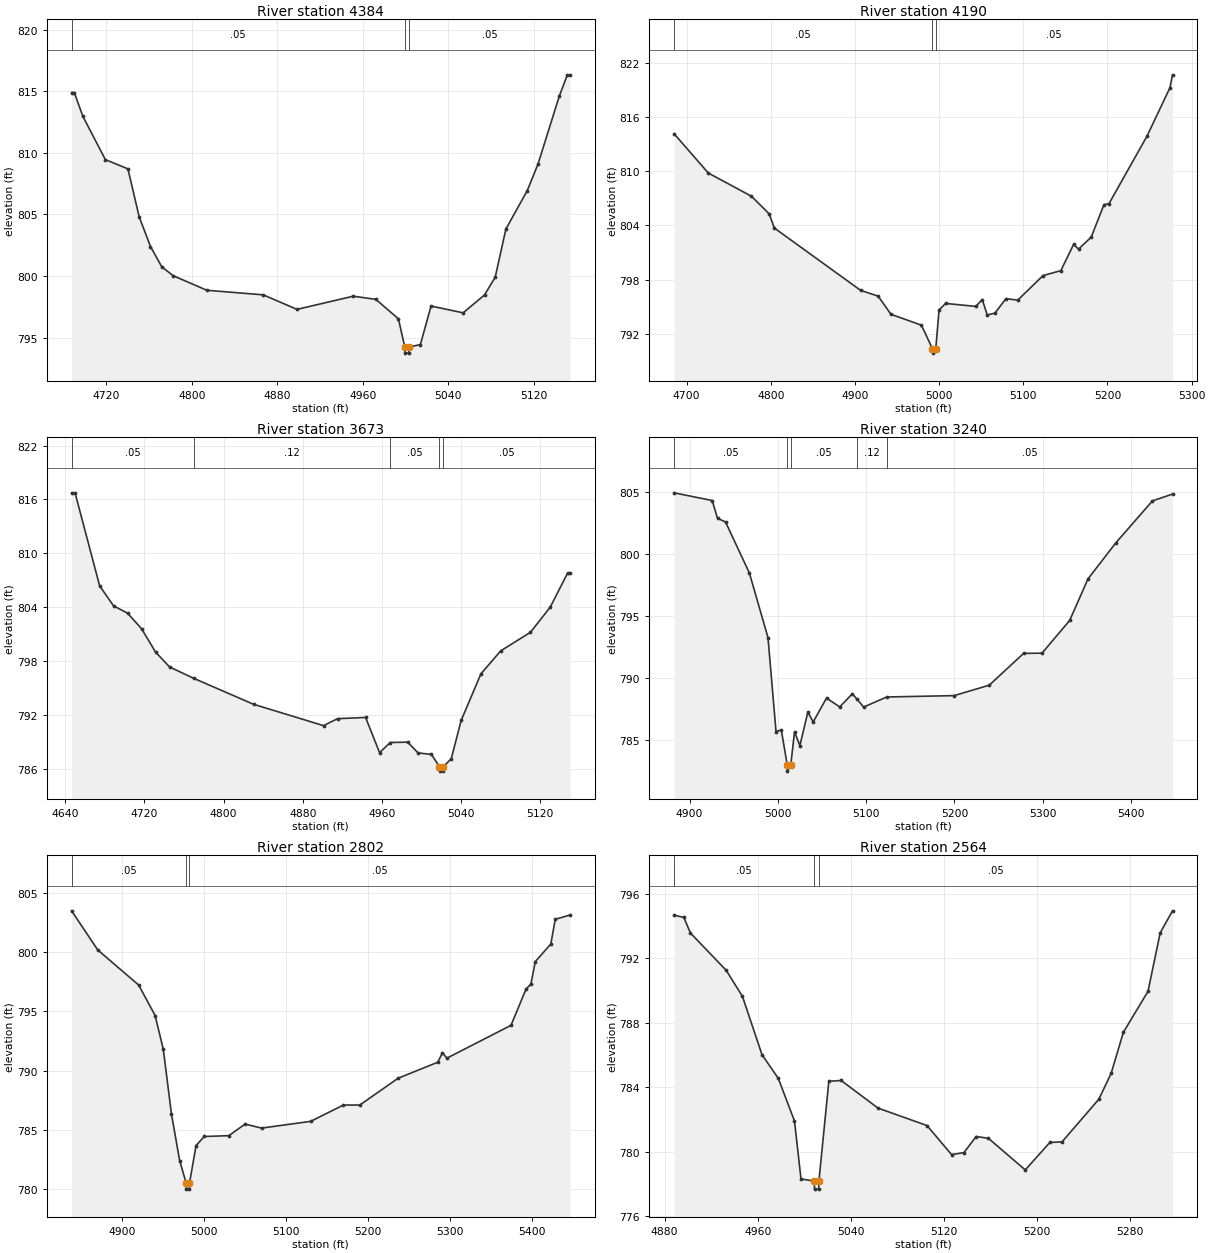
Type RM Length L Ch R = 1,4384,194,194,194
BEGIN DESCRIPTION:
MDE S 071 11.0
END DESCRIPTION:
XS GIS Cut Line= 3
      2307328.97      7152959.99      2307029.00      7152860.00
      2306879.00      7152860.00
#Sta/Elev= 30
  4687.6  814.88  4690.2  814.88  4698.1  812.97  4719.2  809.45  4740.3  808.70
  4750.8  804.81  4761.4  802.40  4771.9  800.76  4782.4  800.04  4814.1  798.85
  4866.8  798.48  4898.4  797.30  4951.1  798.37  4972.2  798.11  4993.3  796.53
  4999.2  794.25  4999.4  793.75  5002.9  793.75  5003.2  794.25  5013.8  794.44
  5023.8  797.57  5053.8  797.02  5073.8  798.47  5083.8  799.91  5093.8  803.82
  5113.8  806.94  5123.8  809.08  5143.8  814.62  5151.3  816.33  5153.8  816.33
#Mann=3,-1,0
  4687.6    0.05       0  4999.2   0.033       0  5003.2    0.05       0
Bank Sta=4999.2,5003.2
Exp/Cntr=0.3,0.1

Type RM Length L Ch R = 1,4190,517,517,517
BEGIN DESCRIPTION:
Mapping XS 4fa65126
END DESCRIPTION:
XS GIS Cut Line= 2
      2307398.49      7152877.01      2306903.60      7152551.77
#Sta/Elev= 30
  4685.1  814.13  4725.8  809.79  4777.0  807.23  4798.1  805.28  4804.2  803.72
  4906.6  796.84  4927.6  796.19  4942.7  794.19  4978.9  792.99  4992.0  790.40
  4992.2  789.90  4996.0  790.40  4999.9  794.66  5007.6  795.39  5043.5  795.06
  5051.2  795.81  5057.2  794.11  5066.3  794.32  5079.4  795.92  5093.3  795.75
  5123.5  798.47  5144.6  799.01  5159.7  801.90  5165.6  801.39  5180.7  802.72
  5195.8  806.30  5201.8  806.41  5246.9  813.86  5274.1  819.19  5277.3  820.64
#Mann=3,-1,0
  4685.1    0.05       0  4992.0   0.033       0  4996.0    0.05       0
Bank Sta=4992,4996
Exp/Cntr=0.3,0.1

Type RM Length L Ch R = 1,3673,433,433,433
BEGIN DESCRIPTION:
MDE S 071 9.0
END DESCRIPTION:
XS GIS Cut Line= 3
      2307478.98      7152559.98      2307229.00      7152310.00
      2307079.02      7152310.00
#Sta/Elev= 30
  4646.5  816.74  4650.0  816.74  4674.8  806.38  4688.9  804.14  4703.0  803.33
  4717.2  801.59  4731.3  798.99  4745.5  797.33  4769.7  796.07  4830.3  793.17
  4901.0  790.79  4915.2  791.57  4943.5  791.70  4957.6  787.78  4968.4  788.91
  4985.9  788.95  4996.5  787.75  5010.0  787.58  5018.0  786.22  5018.3  785.72
  5021.8  785.72  5022.0  786.22  5030.0  787.10  5040.0  791.37  5060.0  796.57
  5080.0  799.13  5110.0  801.19  5130.0  804.00  5147.5  807.79  5150.0  807.79
#Mann=5,-1,0
  4646.5    0.05       0  4769.7    0.12       0  4968.4    0.05       0
  5018.0   0.033       0  5022.0    0.05       0
Bank Sta=5018,5022
Exp/Cntr=0.3,0.1

Type RM Length L Ch R = 1,3240,438,438,438
BEGIN DESCRIPTION:
Mapping XS 93ea7604
END DESCRIPTION:
XS GIS Cut Line= 3
      2307577.67      7152250.38      2307301.44      7152068.24
      2307077.16      7152134.69
#Sta/Elev= 30
  4882.4  804.90  4925.6  804.28  4931.6  802.85  4940.7  802.55  4967.7  798.45
  4988.8  793.24  4997.9  785.68  5003.9  785.80  5010.6  782.99  5010.8  782.49
  5014.6  782.99  5018.9  785.66  5024.9  784.54  5034.0  787.24  5040.0  786.45
  5055.1  788.37  5070.1  787.66  5084.4  788.72  5089.6  788.29  5097.2  787.65
  5123.4  788.46  5199.6  788.57  5239.5  789.41  5278.4  791.97  5299.3  791.99
  5330.6  794.62  5351.4  797.97  5382.9  800.87  5424.4  804.25  5447.2  804.80
#Mann=5,-1,0
  4882.4    0.05       0  5010.6   0.033       0  5014.6    0.05       0
  5089.6    0.12       0  5123.4    0.05       0
Bank Sta=5010.6,5014.6
Exp/Cntr=0.3,0.1

Type RM Length L Ch R = 1,2802,238,238,238
BEGIN DESCRIPTION:
Mapping XS 29e755ce
END DESCRIPTION:
XS GIS Cut Line= 3
      2307690.98      7151851.58      2307319.07      7151845.05
      2307098.91      7151932.34
#Sta/Elev= 30
  4838.1  803.51  4870.1  800.20  4920.1  797.23  4940.1  794.66  4950.1  791.80
  4960.1  786.32  4970.1  782.39  4978.1  780.48  4978.3  779.98  4981.8  779.98
  4982.1  780.48  4990.1  783.66  5000.1  784.43  5030.1  784.50  5050.1  785.48
  5070.1  785.14  5130.1  785.71  5170.1  787.09  5190.1  787.09  5237.0  789.36
  5285.4  790.71  5291.1  791.52  5296.4  791.05  5374.8  793.83  5393.0  796.87
  5399.1  797.33  5404.5  799.22  5423.4  800.70  5428.8  802.79  5446.9  803.16
#Mann=3,-1,0
  4838.1    0.05       0  4978.1   0.033       0  4982.1    0.05       0
Bank Sta=4978.1,4982.1
Exp/Cntr=0.3,0.1

Type RM Length L Ch R = 1,2564,423,423,423
BEGIN DESCRIPTION:
MDE S 071 6.0
END DESCRIPTION:
XS GIS Cut Line= 3
      2307629.03      7151660.01      2307529.00      7151610.00
      2307228.96      7151509.99
#Sta/Elev= 30
  4888.2  794.66  4896.6  794.52  4902.2  793.56  4933.0  791.24  4946.9  789.63
  4963.7  786.02  4977.7  784.55  4991.6  781.91  4997.2  778.32  5008.6  778.19
  5008.8  777.69  5012.3  777.69  5012.6  778.19  5021.1  784.37  5031.7  784.42
  5063.3  782.71  5105.4  781.63  5126.5  779.83  5137.1  779.95  5147.6  780.95
  5158.1  780.84  5189.8  778.88  5210.9  780.58  5221.4  780.62  5253.0  783.26
  5263.6  784.87  5274.1  787.41  5295.2  789.94  5305.7  793.57  5316.3  794.93
#Mann=3,-1,0
  4888.2    0.05       0  5008.6   0.033       0  5012.6    0.05       0
Bank Sta=5008.6,5012.6
Exp/Cntr=0.3,0.1

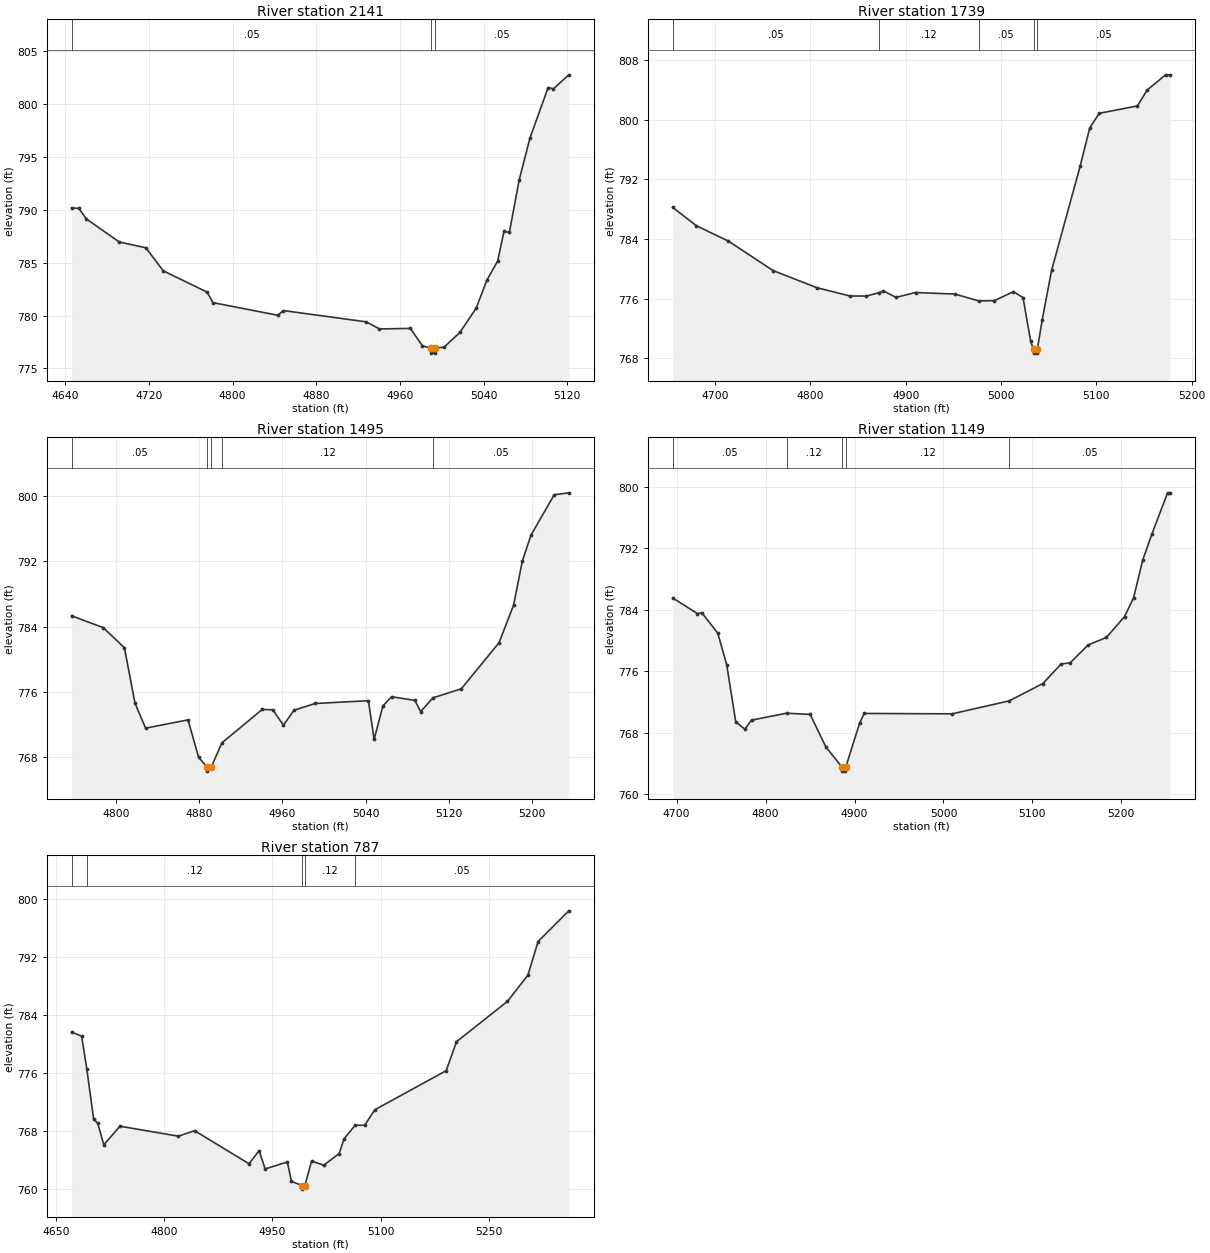
Type RM Length L Ch R = 1,2141,402,402,402
BEGIN DESCRIPTION:
Mapping XS 37136ac0
END DESCRIPTION:
XS GIS Cut Line= 3
      2307682.41      7151366.66      2307545.73      7151322.45
      2307222.86      7151399.09
#Sta/Elev= 30
  4646.0  790.20  4653.1  790.14  4660.1  789.16  4691.6  786.97  4717.1  786.42
  4733.7  784.24  4775.7  782.22  4781.2  781.23  4843.4  780.03  4848.5  780.48
  4927.8  779.41  4940.5  778.74  4970.0  778.79  4981.6  777.13  4989.9  776.95
  4990.1  776.45  4993.6  776.45  4993.9  776.95  5002.1  777.00  5017.4  778.41
  5033.0  780.71  5043.2  783.36  5053.5  785.16  5059.6  787.99  5064.7  787.87
  5074.1  792.85  5084.4  796.81  5101.8  801.59  5106.9  801.47  5121.5  802.79
#Mann=3,-1,0
  4646.0    0.05       0  4989.9   0.033       0  4993.9    0.05       0
Bank Sta=4989.9,4993.9
Exp/Cntr=0.3,0.1

Type RM Length L Ch R = 1,1739,244,244,244
BEGIN DESCRIPTION:
Mapping XS c778db0d
END DESCRIPTION:
XS GIS Cut Line= 3
      2307695.46      7151162.10      2307374.22      7151077.08
      2307185.01      7151068.60
#Sta/Elev= 30
  4655.4  788.25  4680.4  785.78  4713.8  783.73  4760.8  779.77  4806.9  777.47
  4841.3  776.37  4858.6  776.35  4871.6  776.80  4876.4  777.05  4889.7  776.18
  4910.3  776.83  4951.6  776.62  4976.5  775.70  4992.9  775.74  5012.9  776.94
  5023.0  776.15  5031.0  770.31  5034.0  769.20  5034.3  768.70  5037.8  768.70
  5038.0  769.20  5043.0  773.09  5053.0  779.82  5083.0  793.81  5093.0  798.92
  5103.0  800.87  5143.1  801.86  5153.1  803.97  5172.6  806.03  5177.1  806.03
#Mann=5,-1,0
  4655.4    0.05       0  4871.6    0.12       0  4976.5    0.05       0
  5034.0   0.033       0  5038.0    0.05       0
Bank Sta=5034,5038
Exp/Cntr=0.3,0.1

Type RM Length L Ch R = 1,1495,346,346,346
BEGIN DESCRIPTION:
MDE S 071 3.0
END DESCRIPTION:
XS GIS Cut Line= 3
      2307678.96      7150909.99      2307429.00      7150860.00
      2307229.01      7150959.99
#Sta/Elev= 30
  4757.1  785.32  4787.6  783.87  4808.0  781.40  4818.2  774.59  4828.4  771.55
  4869.2  772.56  4879.4  767.97  4887.6  766.78  4887.9  766.28  4891.6  766.78
  4901.8  769.74  4940.6  773.84  4950.8  773.80  4961.0  771.91  4971.2  773.75
  4991.6  774.57  5042.8  774.91  5048.3  770.17  5056.7  774.26  5065.1  775.40
  5087.5  774.95  5093.1  773.58  5105.0  775.27  5132.2  776.37  5168.5  782.02
  5182.5  786.62  5190.9  792.01  5199.3  795.22  5221.6  800.15  5235.6  800.39
#Mann=5,-1,0
  4757.1    0.05       0  4887.6    0.07       0  4891.6    0.05       0
  4901.8    0.12       0  5105.0    0.05       0
Bank Sta=4887.6,4891.6
Exp/Cntr=0.3,0.1

Type RM Length L Ch R = 1,1149,362,362,362
BEGIN DESCRIPTION:
MDE S 071 2.0
END DESCRIPTION:
XS GIS Cut Line= 3
      2307728.96      7150609.99      2307429.00      7150560.00
      2307178.95      7150610.01
#Sta/Elev= 30
  4695.5  785.53  4723.3  783.50  4728.4  783.60  4746.2  780.95  4756.3  776.82
  4766.4  769.40  4776.6  768.44  4784.2  769.62  4823.5  770.52  4850.1  770.37
  4867.8  766.12  4886.1  763.48  4886.3  762.98  4889.8  762.98  4890.1  763.48
  4905.8  769.27  4910.9  770.49  5009.8  770.44  5073.9  772.13  5111.8  774.39
  5132.2  776.93  5142.4  777.08  5162.8  779.42  5183.2  780.39  5203.6  783.10
  5213.8  785.57  5224.0  790.45  5234.2  793.80  5252.0  799.22  5254.6  799.22
#Mann=5,-1,0
  4695.5    0.05       0  4823.5    0.12       0  4886.1    0.07       0
  4890.1    0.12       0  5073.9    0.05       0
Bank Sta=4886.1,4890.1
Exp/Cntr=0.3,0.1

Type RM Length L Ch R = 1,787,0,0,0
BEGIN DESCRIPTION:
MDE S 071 1.0
END DESCRIPTION:
XS GIS Cut Line= 3
      2307678.99      7150359.99      2307379.00      7150210.00
      2307128.97      7150460.03
#Sta/Elev= 30
  4671.6  781.65  4685.6  781.09  4692.7  776.62  4702.3  769.61  4707.9  769.08
  4716.3  766.09  4738.7  768.66  4819.7  767.28  4842.1  768.04  4917.6  763.47
  4931.5  765.29  4939.9  762.76  4970.7  763.72  4976.3  761.04  4991.0  760.47
  4991.3  759.97  4995.0  760.47  5004.2  763.85  5021.1  763.27  5042.4  764.88
  5049.4  766.94  5064.7  768.80  5077.7  768.78  5091.9  770.93  5190.8  776.33
  5205.0  780.32  5275.7  785.90  5304.0  789.52  5318.1  794.16  5360.6  798.40
#Mann=5,-1,0
  4671.6    0.05       0  4692.7    0.12       0  4991.0    0.07       0
  4995.0    0.12       0  5064.7    0.05       0
Bank Sta=4991,4995
Exp/Cntr=0.3,0.1

Chan Stop Cuts=-1