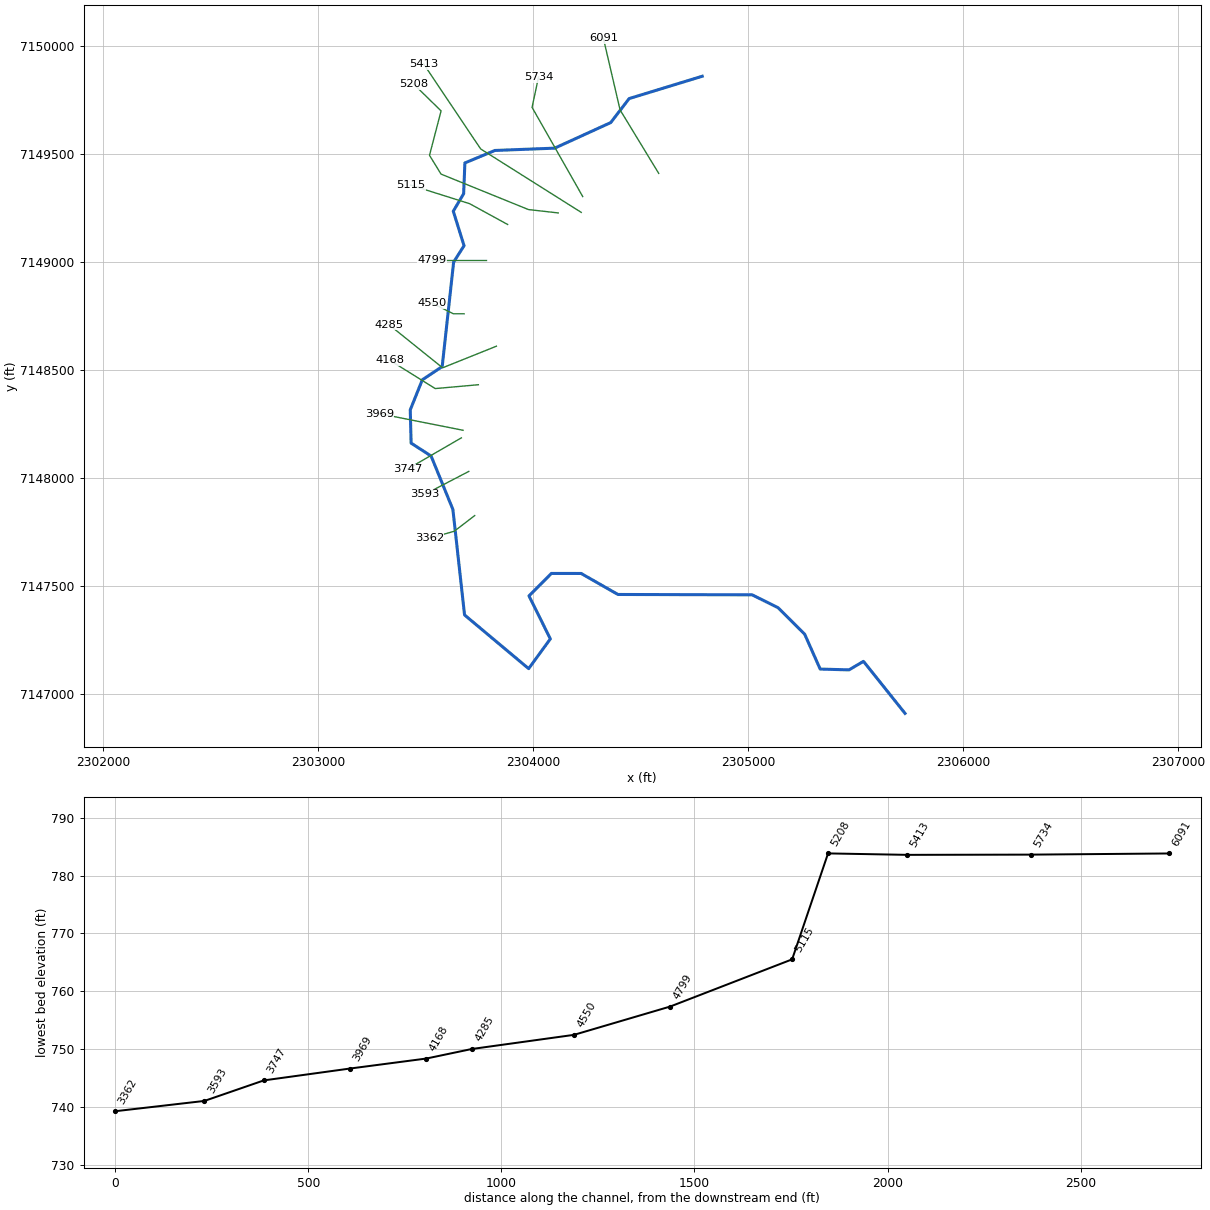
--- MDE S 072.prj (project) ---

Proj Title=MDE S 072 Base Level Engineering
Current Plan=p01
Default Exp/Contr=0.3,0.1
English Units
Geom File=g01
Flow File=f01
Plan File=p01
BEGIN DESCRIPTION:
MDE S 072
END DESCRIPTION:

--- MDE S 072.p01 (plan) ---

Plan Title=Multiple Run
Short Identifier=Multiple
Geom File=g01
Flow File=f01
Subcritical Flow
K Sum by GR= 0
Std Step Tol= 0.01
Critical Tol= 0.01
Num of Std Step Trials= 20
Max Error Tol= 0.3
Flow Tol Ratio= 0.001
Split Flow NTrial= 30
Split Flow Tol= 0.02
Split Flow Ratio= 0.02
Log Output Level= 0
Friction Slope Method= 1
Unsteady Friction Slope Method= 2
Unsteady Bridges Friction Slope Method= 1
Parabolic Critical Depth
Global Vel Dist=  1 , 1 , 1
Global Log Level= 0
CheckData=True
Encroach Param= -1, 0, 0, 0
BEGIN DESCRIPTION:
Multiple Run
END DESCRIPTION:

--- MDE S 072.f01 (steady flow) ---

Flow Title=Multiple
Number of Profiles=7
Profile Names=10-year,25-year,50-year,1pct_min,100-year,1pct_plu,500-year
River Rch & RM= MDE S 072,Reach-1,6091
     298     393     469     279     557    1112     786
Boundary for River Rch & Prof#=MDE S 072,Reach-1,1
Up Type=0
Dn Type=3
Dn Slope=0.00508
Boundary for River Rch & Prof#=MDE S 072,Reach-1,2
Up Type=0
Dn Type=3
Dn Slope=0.00508
Boundary for River Rch & Prof#=MDE S 072,Reach-1,3
Up Type=0
Dn Type=3
Dn Slope=0.00508
Boundary for River Rch & Prof#=MDE S 072,Reach-1,4
Up Type=0
Dn Type=3
Dn Slope=0.00508
Boundary for River Rch & Prof#=MDE S 072,Reach-1,5
Up Type=0
Dn Type=3
Dn Slope=0.00508
Boundary for River Rch & Prof#=MDE S 072,Reach-1,6
Up Type=0
Dn Type=3
Dn Slope=0.00508
Boundary for River Rch & Prof#=MDE S 072,Reach-1,7
Up Type=0
Dn Type=3
Dn Slope=0.00508

--- MDE S 072.g01 (geometry) ---

Geom Title=Existing Conditions

River Reach=MDE S 072,Reach-1
Reach XY= 30
      2304786.05      7149859.82      2304446.29      7149756.44
      2304360.51      7149645.20      2304099.95      7149526.89
      2303821.91      7149516.20      2303682.56      7149458.53
      2303676.70      7149315.93      2303628.60      7149235.00
      2303678.62      7149075.27      2303630.22      7148999.50
      2303576.99      7148515.68      2303484.62      7148454.38
      2303428.55      7148315.18      2303432.48      7148161.26
      2303525.46      7148101.51      2303626.74      7147854.06
      2303680.98      7147365.67      2303979.01      7147117.07
      2304079.87      7147254.96      2303980.57      7147453.96
      2304084.85      7147557.96      2304223.07      7147557.77
      2304394.21      7147460.51      2305018.50      7147458.80
      2305138.68      7147399.24      2305262.36      7147276.68
      2305334.41      7147115.16      2305468.55      7147111.37
      2305535.74      7147150.87      2305729.00      7146910.00

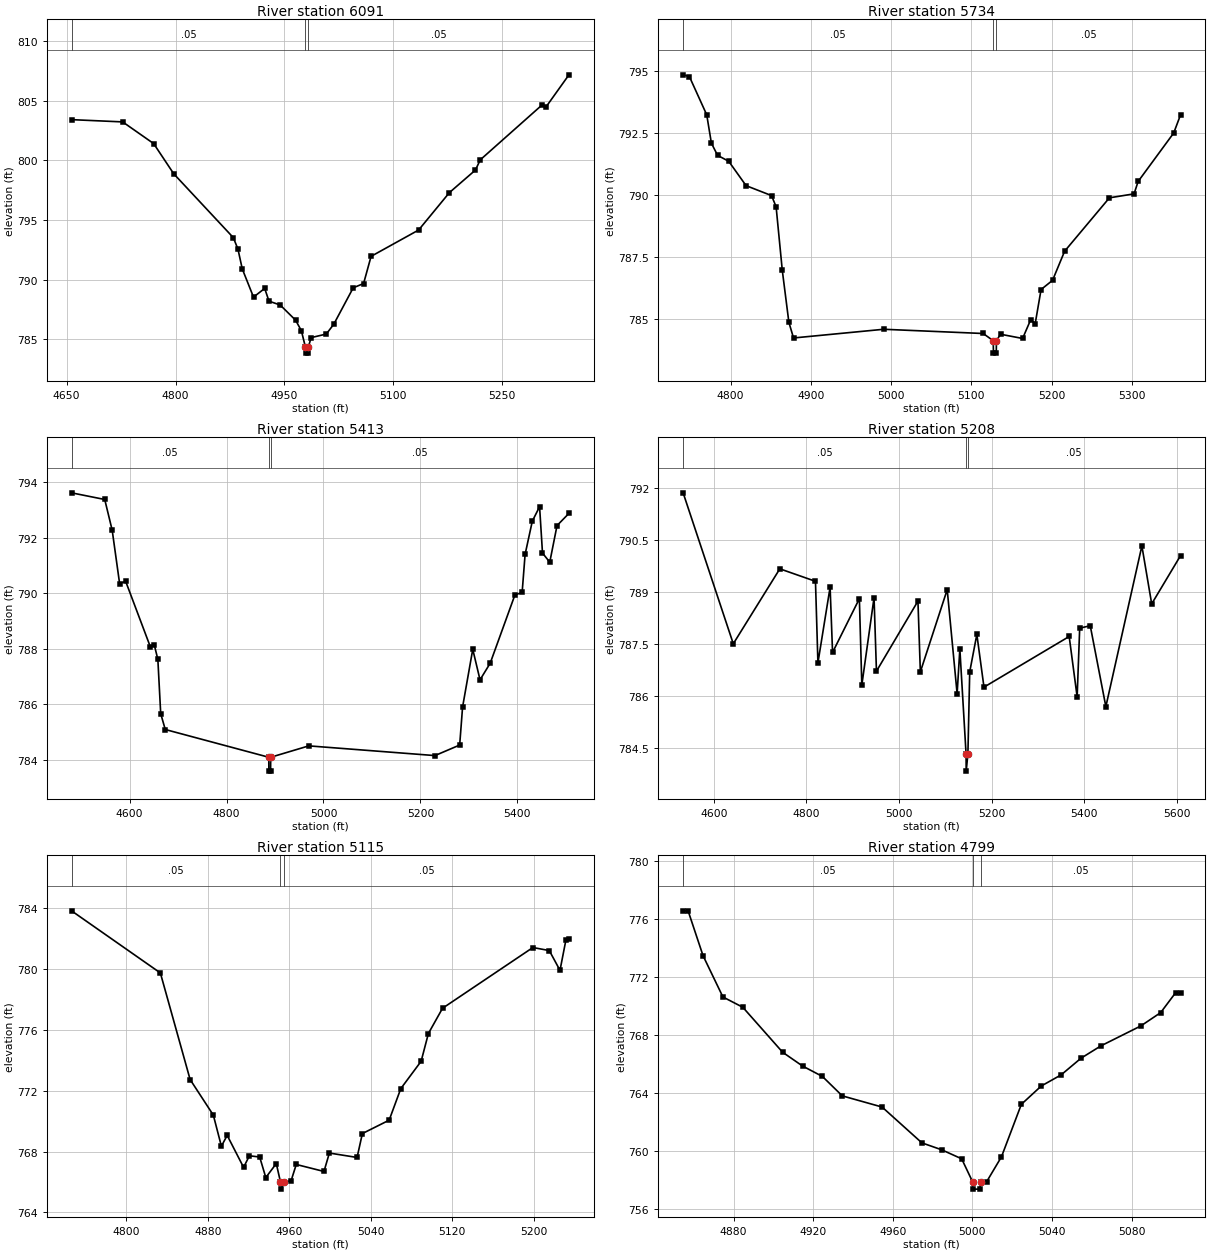
Type RM Length L Ch R = 1,6091,357,357,357
BEGIN DESCRIPTION:
MDE S 072 17.0
END DESCRIPTION:
XS GIS Cut Line= 3
      2304583.85      7149409.91      2304404.08      7149704.09
      2304326.52      7150035.37
#Sta/Elev= 30
  4656.8  803.42  4727.2  803.23  4769.9  801.41  4797.5  798.88  4879.6  793.52
  4886.0  792.55  4891.9  790.90  4907.4  788.53  4922.8  789.26  4928.7  788.19
  4944.1  787.87  4965.4  786.59  4973.3  785.71  4978.9  784.33  4979.1  783.83
  4982.6  783.83  4982.9  784.33  4986.7  785.13  5007.6  785.43  5017.9  786.25
  5044.7  789.31  5059.0  789.67  5069.3  791.95  5134.8  794.16  5177.2  797.30
  5213.0  799.19  5219.7  800.05  5304.7  804.65  5309.8  804.45  5341.8  807.18
#Mann=3,-1,0
  4656.8    0.05       0  4978.9   0.033       0  4982.9    0.05       0
Bank Sta=4978.9,4982.9
Exp/Cntr=0.3,0.1

Type RM Length L Ch R = 1,5734,321,321,321
BEGIN DESCRIPTION:
Mapping XS d5ad6e31
END DESCRIPTION:
XS GIS Cut Line= 3
      2304230.46      7149302.74      2303994.90      7149715.83
      2304025.08      7149856.60
#Sta/Elev= 30
  4741.0  794.83  4748.8  794.76  4770.4  793.22  4776.2  792.08  4783.9  791.59
  4797.8  791.35  4819.4  790.37  4851.1  789.97  4856.8  789.52  4864.5  786.96
  4872.7  784.87  4878.5  784.24  4990.8  784.59  5114.7  784.42  5127.2  784.13
  5127.5  783.63  5131.0  783.63  5131.2  784.13  5136.3  784.39  5163.8  784.22
  5173.8  784.97  5179.5  784.82  5186.8  786.19  5201.1  786.56  5216.1  787.73
  5271.9  789.88  5302.6  790.04  5307.7  790.54  5352.0  792.49  5360.5  793.22
#Mann=3,-1,0
  4741.0    0.05       0  5127.2   0.033       0  5131.2    0.05       0
Bank Sta=5127.2,5131.2
Exp/Cntr=0.3,0.1

Type RM Length L Ch R = 1,5413,205,205,205
BEGIN DESCRIPTION:
Mapping XS db88f20e
END DESCRIPTION:
XS GIS Cut Line= 3
      2304223.58      7149229.51      2303755.84      7149523.30
      2303490.93      7149916.42
#Sta/Elev= 30
  4480.1  793.62  4548.6  793.38  4564.0  792.27  4579.3  790.35  4591.8  790.43
  4642.9  788.06  4650.8  788.14  4658.2  787.62  4664.1  785.66  4673.5  785.09
  4887.1  784.09  4887.3  783.59  4890.8  783.59  4891.1  784.09  4969.7  784.50
  5230.0  784.15  5281.0  784.53  5287.0  785.90  5308.0  787.98  5323.0  786.88
  5344.0  787.48  5395.0  789.94  5409.9  790.03  5416.0  791.40  5430.9  792.60
  5445.9  793.12  5451.9  791.45  5466.9  791.12  5481.9  792.44  5506.5  792.88
#Mann=3,-1,0
  4480.1    0.05       0  4887.1   0.033       0  4891.1    0.05       0
Bank Sta=4887.1,4891.1
Exp/Cntr=0.3,0.1

Type RM Length L Ch R = 1,5208,93,93,93
BEGIN DESCRIPTION:
Mapping XS ff65b9f6
END DESCRIPTION:
XS GIS Cut Line= 6
      2304116.61      7149227.02      2303978.17      7149242.56
      2303571.61      7149406.81      2303518.03      7149493.77
      2303571.84      7149699.40      2303444.35      7149823.49
#Sta/Elev= 30
  4533.7  791.86  4642.0  787.51  4742.5  789.67  4819.5  789.31  4824.8  786.96
  4851.1  789.14  4856.4  787.26  4914.3  788.81  4919.6  786.32  4946.0  788.84
  4951.2  786.72  5040.8  788.74  5046.0  786.70  5104.0  789.07  5125.4  786.07
  5131.3  787.36  5144.7  784.34  5145.0  783.84  5148.7  784.34  5152.6  786.70
  5168.0  787.78  5183.4  786.26  5367.4  787.72  5384.6  785.98  5390.1  787.96
  5412.9  788.03  5446.6  785.70  5524.4  790.33  5545.6  788.66  5607.9  790.05
#Mann=3,-1,0
  4533.7    0.05       0  5144.7   0.033       0  5148.7    0.05       0
Bank Sta=5144.7,5148.7
Exp/Cntr=0.3,0.1

Type RM Length L Ch R = 1,5115,316,316,316
BEGIN DESCRIPTION:
Mapping XS 15090c2f
END DESCRIPTION:
XS GIS Cut Line= 3
      2303881.23      7149173.63      2303704.70      7149269.74
      2303430.56      7149355.72
#Sta/Elev= 30
  4746.3  783.81  4833.5  779.73  4862.7  772.73  4885.5  770.39  4893.4  768.35
  4899.1  769.06  4915.2  766.96  4920.9  767.72  4931.0  767.64  4937.0  766.29
  4947.3  767.21  4951.3  766.03  4951.5  765.53  4955.3  766.03  4961.7  766.05
  4966.9  767.15  4994.1  766.69  4999.4  767.90  5026.6  767.61  5031.8  769.18
  5058.1  770.06  5069.5  772.13  5089.5  773.93  5096.6  775.75  5110.5  777.41
  5199.2  781.40  5215.3  781.20  5225.8  779.90  5231.6  781.89  5234.6  781.96
#Mann=3,-1,0
  4746.3    0.05       0  4951.3   0.033       0  4955.3    0.05       0
Bank Sta=4951.3,4955.3
Exp/Cntr=0.3,0.1

Type RM Length L Ch R = 1,4799,249,249,249
BEGIN DESCRIPTION:
MDE S 072 15.0
END DESCRIPTION:
XS GIS Cut Line= 3
      2303778.97      7149010.00      2303629.00      7149010.00
      2303528.97      7149010.00
#Sta/Elev= 28
  4854.6  776.56  4857.1  776.56  4864.6  773.47  4874.6  770.62  4884.6  769.91
  4904.6  766.81  4914.6  765.86  4924.6  765.14  4934.6  763.80  4954.6  763.03
  4974.6  760.56  4984.6  760.08  4994.6  759.46  5000.1  757.87  5000.3  757.37
  5003.8  757.37  5004.1  757.87  5007.1  757.87  5014.6  759.60  5024.6  763.22
  5034.6  764.48  5044.6  765.25  5054.6  766.40  5064.6  767.25  5084.6  768.62
  5094.6  769.54  5102.1  770.91  5104.6  770.91
#Mann=3,-1,0
  4854.6    0.05       0  5000.1   0.033       0  5004.1    0.05       0
Bank Sta=5000.1,5004.1
Exp/Cntr=0.3,0.1

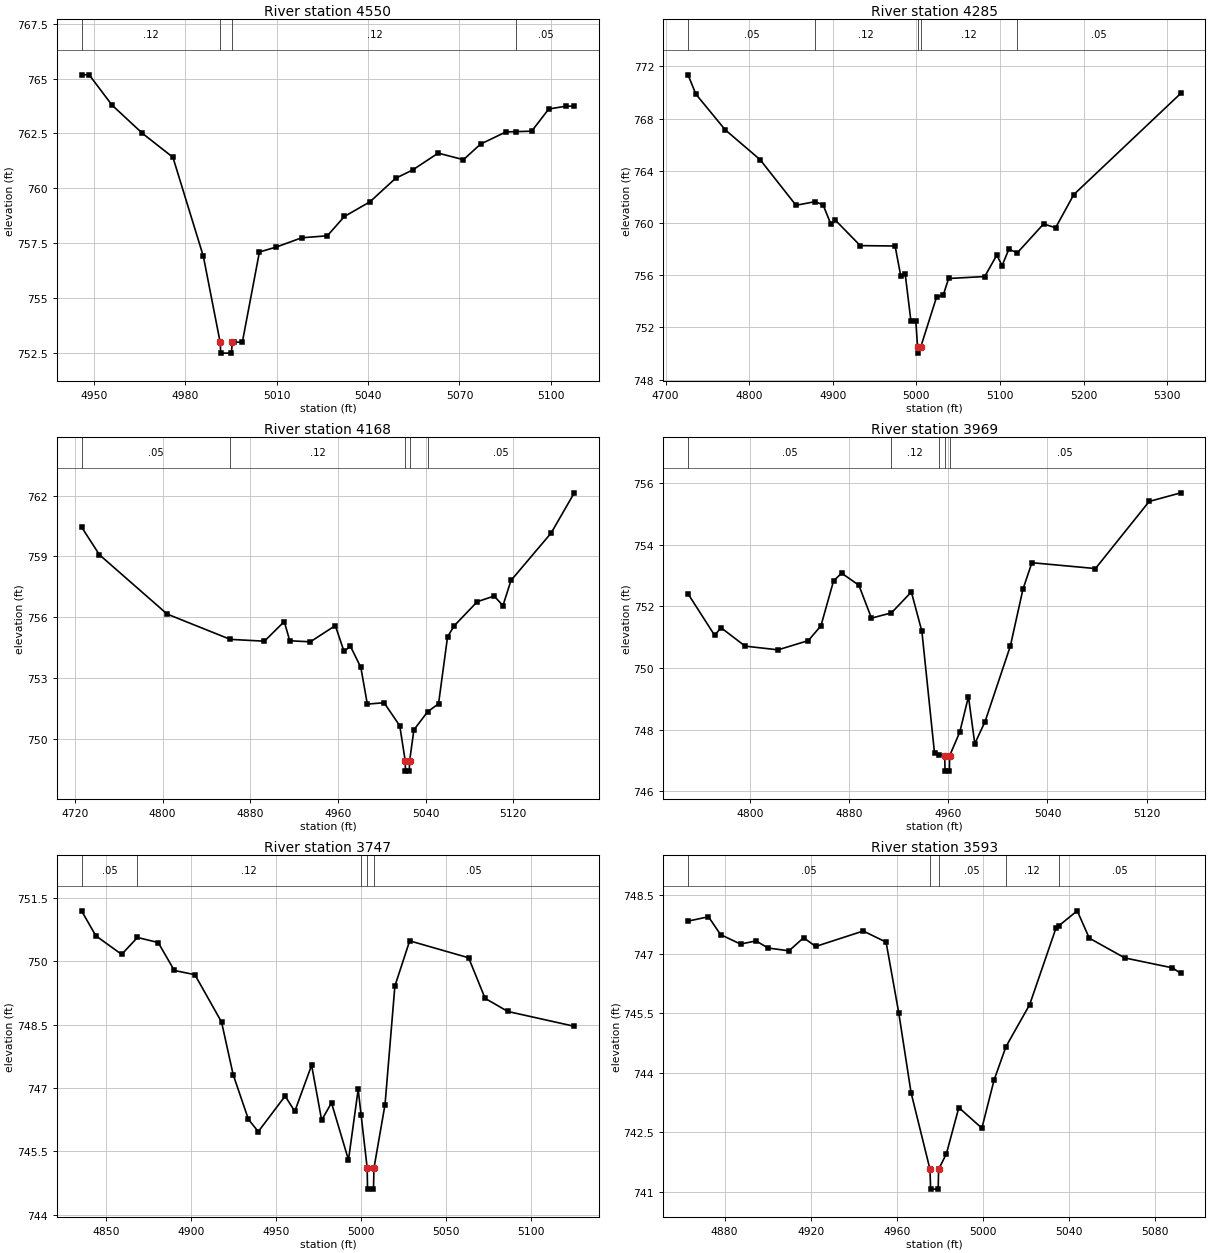
Type RM Length L Ch R = 1,4550,265,265,265
BEGIN DESCRIPTION:
MDE S 072 14.0
END DESCRIPTION:
XS GIS Cut Line= 3
      2303678.98      7148760.00      2303629.00      7148760.00
      2303528.99      7148810.01
#Sta/Elev= 29
  4945.9  765.17  4948.4  765.17  4955.9  763.79  4965.9  762.50  4975.9  761.41
  4985.9  756.89  4991.4  752.98  4991.6  752.48  4995.1  752.48  4995.4  752.98
  4995.9  752.98  4998.7  752.98  5004.3  757.09  5009.9  757.32  5018.2  757.74
  5026.6  757.83  5032.2  758.71  5040.6  759.38  5049.0  760.45  5054.6  760.83
  5063.0  761.60  5071.3  761.30  5076.9  762.01  5085.3  762.57  5088.7  762.58
  5093.7  762.60  5099.3  763.61  5104.9  763.74  5107.7  763.74
#Mann=4,-1,0
  4945.9    0.12       0  4991.4    0.07       0  4995.4    0.12       0
  5088.7    0.05       0
Bank Sta=4991.4,4995.4
Exp/Cntr=0.3,0.1

Type RM Length L Ch R = 1,4285,117,117,117
BEGIN DESCRIPTION:
MDE S 072 13.0
END DESCRIPTION:
XS GIS Cut Line= 3
      2303829.00      7148610.00      2303579.00      7148510.00
      2303329.01      7148709.99
#Sta/Elev= 30
  4726.8  771.36  4736.2  769.88  4771.2  767.15  4813.0  764.86  4856.0  761.36
  4878.8  761.64  4888.4  761.39  4897.8  759.89  4903.2  760.21  4932.8  758.27
  4974.5  758.24  4981.2  755.96  4986.6  756.08  4993.4  752.50  4999.3  752.50
  5001.3  750.53  5001.5  750.03  5005.3  750.53  5024.1  754.33  5032.1  754.48
  5038.5  755.75  5081.7  755.90  5096.1  757.54  5102.5  756.74  5110.5  757.99
  5120.7  757.72  5152.1  759.93  5166.5  759.64  5188.2  762.18  5316.2  769.94
#Mann=5,-1,0
  4726.8    0.05       0  4878.8    0.12       0  5001.3    0.07       0
  5005.3    0.12       0  5120.7    0.05       0
Bank Sta=5001.3,5005.3
Exp/Cntr=0.3,0.1

Type RM Length L Ch R = 1,4168,199,199,199
BEGIN DESCRIPTION:
Mapping XS 0fa5a6d6
END DESCRIPTION:
XS GIS Cut Line= 3
      2303745.27      7148431.58      2303544.67      7148413.81
      2303333.70      7148544.78
#Sta/Elev= 30
  4726.0  760.45  4742.3  759.08  4804.1  756.15  4861.7  754.90  4892.9  754.81
  4911.0  755.78  4916.0  754.83  4934.8  754.78  4957.6  755.58  4965.5  754.31
  4971.4  754.56  4980.9  753.51  4986.8  751.70  5002.1  751.77  5016.4  750.63
  5021.4  748.89  5021.6  748.39  5025.1  748.39  5025.4  748.89  5029.3  750.43
  5041.8  751.32  5051.8  751.72  5060.0  755.02  5065.9  755.56  5087.1  756.76
  5102.5  757.04  5110.6  756.57  5117.9  757.81  5154.5  760.15  5175.7  762.14
#Mann=5,-1,0
  4726.0    0.05       0  4861.7    0.12       0  5021.4    0.07       0
  5025.4    0.12       0  5041.8    0.05       0
Bank Sta=5021.4,5025.4
Exp/Cntr=0.3,0.1

Type RM Length L Ch R = 1,3969,222,222,222
BEGIN DESCRIPTION:
Mapping XS 57bf55cb
END DESCRIPTION:
XS GIS Cut Line= 2
      2303674.25      7148220.66      2303284.03      7148297.92
#Sta/Elev= 30
  4749.8  752.41  4771.3  751.06  4776.4  751.31  4795.9  750.71  4822.5  750.59
  4846.9  750.89  4857.1  751.37  4867.3  752.83  4873.8  753.08  4887.7  752.69
  4897.9  751.62  4914.0  751.79  4930.1  752.47  4938.6  751.19  4948.8  747.23
  4952.6  747.19  4957.0  747.15  4957.3  746.65  4960.8  746.65  4961.0  747.15
  4969.2  747.92  4976.2  749.07  4981.3  747.54  4989.6  748.26  5010.0  750.71
  5020.2  752.56  5027.4  753.42  5078.7  753.23  5122.1  755.41  5147.6  755.69
#Mann=5,-1,0
  4749.8    0.05       0  4914.0    0.12       0  4952.6    0.05       0
  4957.0   0.033       0  4961.0    0.05       0
Bank Sta=4957,4961
Exp/Cntr=0.3,0.1

Type RM Length L Ch R = 1,3747,154,154,154
BEGIN DESCRIPTION:
Mapping XS 7038a4fa
END DESCRIPTION:
XS GIS Cut Line= 2
      2303666.24      7148185.74      2303415.14      7148040.67
#Sta/Elev= 30
  4835.7  751.19  4844.1  750.60  4859.3  750.16  4868.6  750.56  4880.8  750.44
  4890.3  749.78  4902.4  749.68  4918.1  748.56  4924.9  747.32  4933.9  746.26
  4939.7  745.97  4955.5  746.81  4961.2  746.45  4971.1  747.54  4977.0  746.24
  4982.8  746.65  4992.8  745.30  4998.5  746.97  5000.2  746.37  5003.8  745.11
  5004.0  744.61  5007.5  744.61  5007.8  745.11  5014.3  746.61  5020.1  749.41
  5028.8  750.48  5063.5  750.08  5073.2  749.12  5086.6  748.81  5125.7  748.46
#Mann=5,-1,0
  4835.7    0.05       0  4868.6    0.12       0  5000.2    0.05       0
  5003.8    0.07       0  5007.8    0.05       0
Bank Sta=5003.8,5007.8
Exp/Cntr=0.3,0.1

Type RM Length L Ch R = 1,3593,231,231,231
BEGIN DESCRIPTION:
Mapping XS 61e896ec
END DESCRIPTION:
XS GIS Cut Line= 2
      2303700.67      7148030.25      2303497.51      7147924.78
#Sta/Elev= 30
  4863.0  747.83  4872.5  747.94  4878.1  747.49  4887.4  747.25  4894.6  747.33
  4900.2  747.15  4909.9  747.08  4916.7  747.41  4922.3  747.19  4944.4  747.58
  4955.0  747.30  4960.9  745.51  4966.6  743.50  4975.4  741.56  4975.7  741.06
  4979.2  741.06  4979.4  741.56  4983.0  741.95  4988.8  743.12  4999.5  742.60
  5005.2  743.82  5010.7  744.66  5021.7  745.72  5033.9  747.65  5035.2  747.71
  5043.8  748.09  5049.4  747.40  5065.9  746.90  5088.0  746.65  5091.9  746.51
#Mann=5,-1,0
  4863.0    0.05       0  4975.4   0.033       0  4979.4    0.05       0
  5010.7    0.12       0  5035.2    0.05       0
Bank Sta=4975.4,4979.4
Exp/Cntr=0.3,0.1

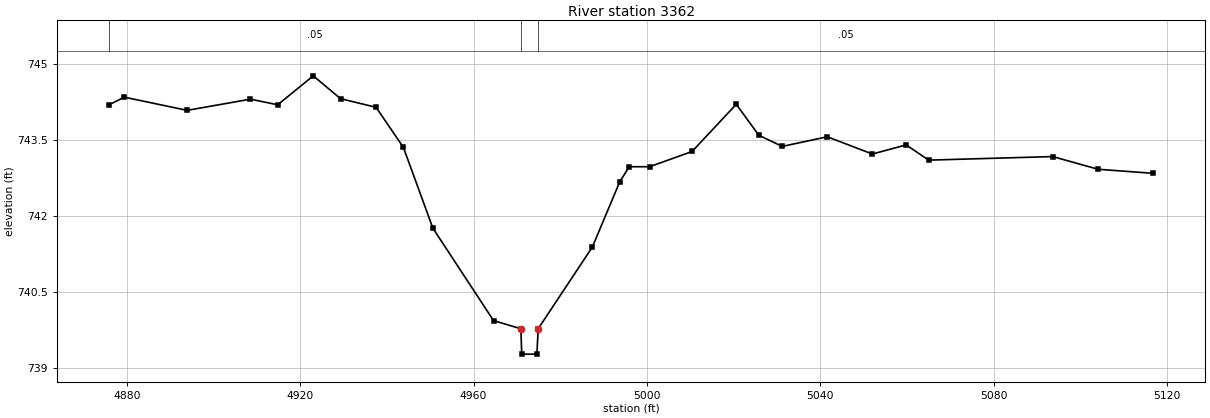
Type RM Length L Ch R = 1,3362,0,0,0
BEGIN DESCRIPTION:
MDE S 072 12.0
END DESCRIPTION:
XS GIS Cut Line= 3
      2303728.36      7147825.92      2303632.95      7147753.07
      2303516.65      7147720.19
#Sta/Elev= 30
  4875.9  744.19  4879.4  744.34  4893.9  744.08  4908.5  744.30  4914.8  744.19
  4923.0  744.76  4929.3  744.31  4937.5  744.14  4943.8  743.35  4950.6  741.76
  4964.6  739.94  4970.9  739.78  4971.1  739.28  4974.6  739.28  4974.9  739.78
  4987.4  741.39  4993.7  742.67  4995.9  742.97  5000.6  742.97  5010.4  743.27
  5020.6  744.20  5025.8  743.59  5031.2  743.37  5041.6  743.56  5052.0  743.22
  5059.8  743.40  5065.0  743.10  5093.6  743.17  5104.1  742.92  5116.8  742.84
#Mann=3,-1,0
  4875.9    0.05       0  4970.9   0.033       0  4974.9    0.05       0
Bank Sta=4970.9,4974.9
Exp/Cntr=0.3,0.1

Chan Stop Cuts=-1