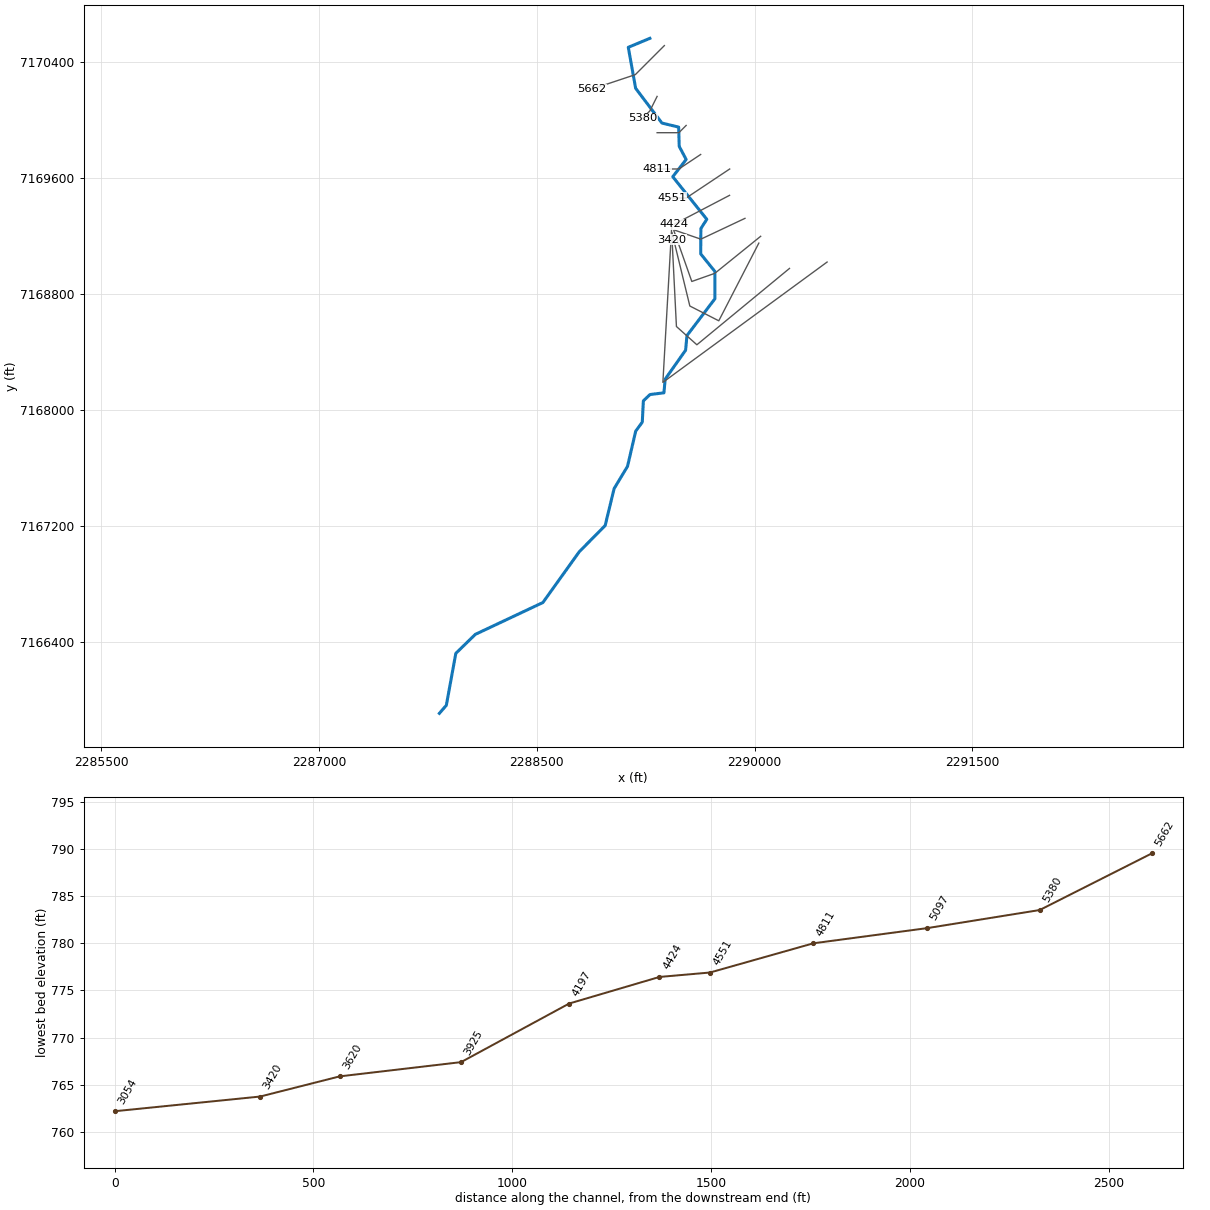
--- MDE S 073.prj (project) ---

Proj Title=MDE S 073 Base Level Engineering
Current Plan=p01
Default Exp/Contr=0.3,0.1
English Units
Geom File=g01
Flow File=f01
Plan File=p01
BEGIN DESCRIPTION:
MDE S 073
END DESCRIPTION:

--- MDE S 073.p01 (plan) ---

Plan Title=Multiple Run
Short Identifier=Multiple
Geom File=g01
Flow File=f01
Subcritical Flow
K Sum by GR= 0
Std Step Tol= 0.01
Critical Tol= 0.01
Num of Std Step Trials= 20
Max Error Tol= 0.3
Flow Tol Ratio= 0.001
Split Flow NTrial= 30
Split Flow Tol= 0.02
Split Flow Ratio= 0.02
Log Output Level= 0
Friction Slope Method= 1
Unsteady Friction Slope Method= 2
Unsteady Bridges Friction Slope Method= 1
Parabolic Critical Depth
Global Vel Dist=  1 , 1 , 1
Global Log Level= 0
CheckData=True
Encroach Param= -1, 0, 0, 0
BEGIN DESCRIPTION:
Multiple Run
END DESCRIPTION:

--- MDE S 073.f01 (steady flow) ---

Flow Title=Multiple
Number of Profiles=7
Profile Names=10-year,25-year,50-year,1pct_min,100-year,1pct_plu,500-year
River Rch & RM= MDE S 073,Reach-1,5662
     281     367     436     258     514    1027     717
Boundary for River Rch & Prof#=MDE S 073,Reach-1,1
Up Type=0
Dn Type=3
Dn Slope=0.005
Boundary for River Rch & Prof#=MDE S 073,Reach-1,2
Up Type=0
Dn Type=3
Dn Slope=0.005
Boundary for River Rch & Prof#=MDE S 073,Reach-1,3
Up Type=0
Dn Type=3
Dn Slope=0.005
Boundary for River Rch & Prof#=MDE S 073,Reach-1,4
Up Type=0
Dn Type=3
Dn Slope=0.005
Boundary for River Rch & Prof#=MDE S 073,Reach-1,5
Up Type=0
Dn Type=3
Dn Slope=0.005
Boundary for River Rch & Prof#=MDE S 073,Reach-1,6
Up Type=0
Dn Type=3
Dn Slope=0.005
Boundary for River Rch & Prof#=MDE S 073,Reach-1,7
Up Type=0
Dn Type=3
Dn Slope=0.005

--- MDE S 073.g01 (geometry) ---

Geom Title=Existing Conditions

River Reach=MDE S 073,Reach-1
Reach XY= 30
      2289279.00      7170560.00      2289130.49      7170498.16
      2289181.07      7170215.86      2289362.24      7169976.46
      2289477.48      7169948.46      2289481.30      7169815.94
      2289529.04      7169725.34      2289436.83      7169606.73
      2289671.21      7169313.42      2289630.39      7169249.57
      2289629.39      7169075.16      2289726.94      7168954.14
      2289726.94      7168765.86      2289534.54      7168512.42
      2289525.17      7168411.59      2289384.56      7168212.36
      2289375.97      7168118.01      2289280.33      7168106.45
      2289234.35      7168062.73      2289226.73      7167915.94
      2289181.36      7167854.02      2289125.17      7167611.58
      2289032.83      7167458.42      2288971.14      7167203.83
      2288792.63      7167023.21      2288542.24      7166673.61
      2288076.70      7166454.17      2287942.37      7166323.32
      2287877.09      7165965.79      2287829.00      7165910.00

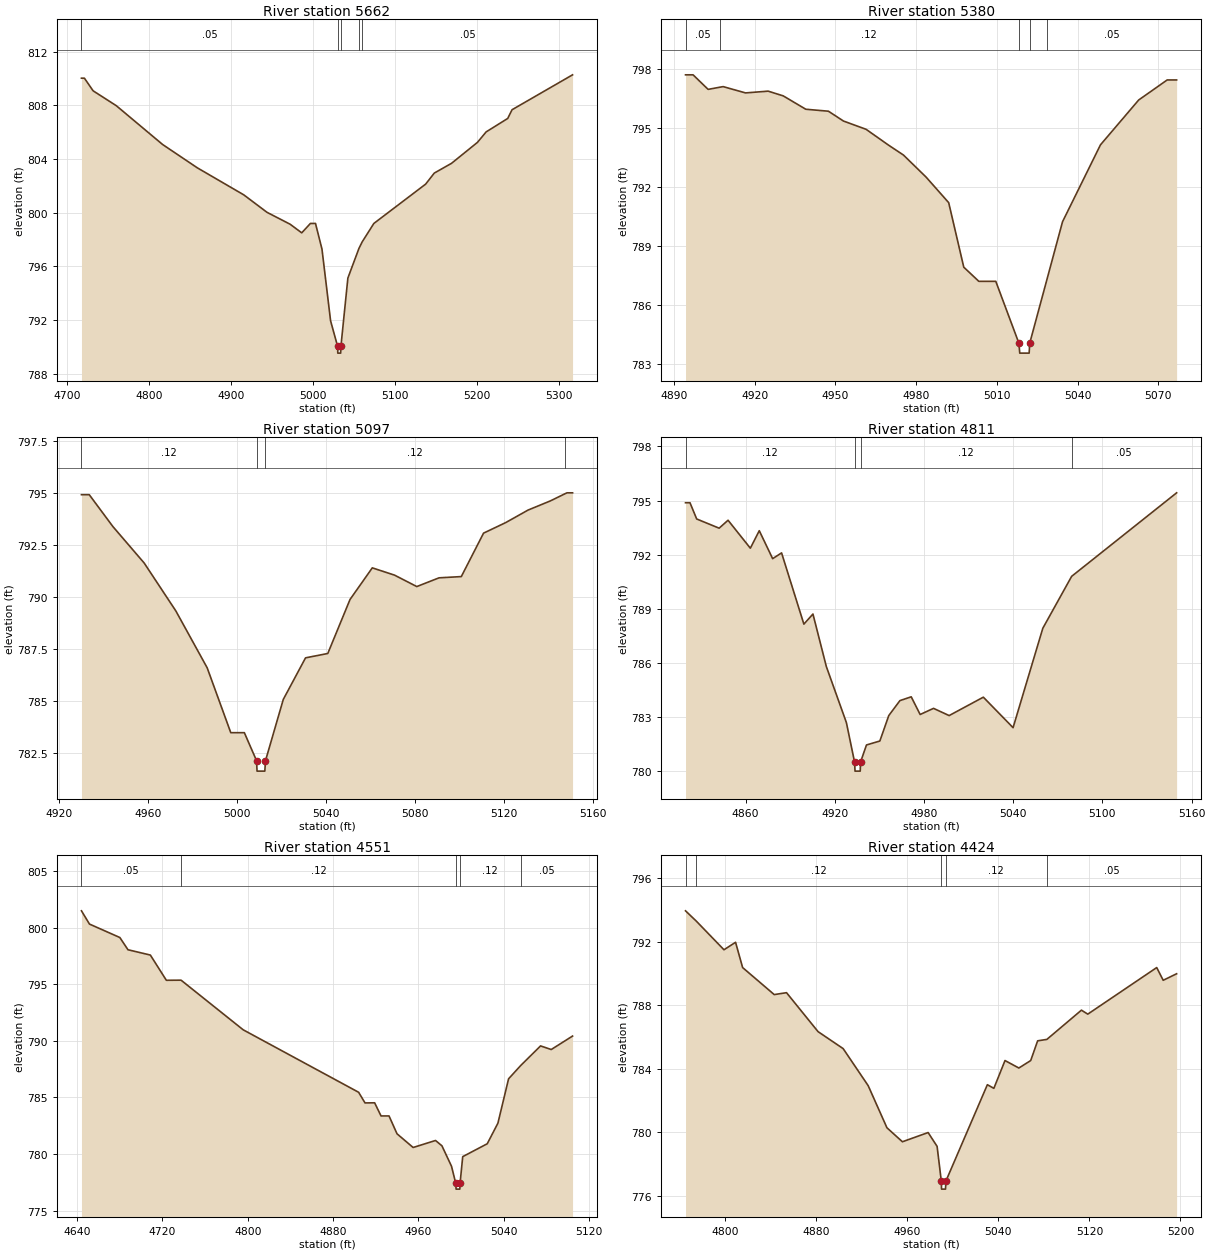
Type RM Length L Ch R = 1,5662,282,282,282
BEGIN DESCRIPTION:
MDE S 073 13.0
END DESCRIPTION:
XS GIS Cut Line= 3
      2289379.02      7170510.02      2289179.00      7170310.00
      2288878.99      7170210.00
#Sta/Elev= 30
  4717.6  810.02  4721.2  810.02  4731.8  809.08  4760.1  807.97  4816.6  805.08
  4859.0  803.34  4915.6  801.33  4943.9  800.03  4972.2  799.14  4986.3  798.50
  4996.9  799.20  5003.1  799.20  5011.0  797.29  5021.5  791.95  5030.1  790.04
  5030.3  789.54  5033.8  789.54  5034.1  790.04  5042.6  795.13  5056.1  797.34
  5060.0  797.82  5074.3  799.20  5137.5  802.13  5148.0  802.95  5169.1  803.68
  5200.7  805.24  5211.3  806.02  5237.6  807.02  5242.9  807.67  5316.7  810.27
#Mann=5,-1,0
  4717.6    0.05       0  5030.1   0.033       0  5034.1    0.05       0
  5056.1    0.12       0  5060.0    0.05       0
Bank Sta=5030.1,5034.1
Exp/Cntr=0.3,0.1

Type RM Length L Ch R = 1,5380,283,283,283
BEGIN DESCRIPTION:
MDE S 073 12.0
END DESCRIPTION:
XS GIS Cut Line= 3
      2289328.99      7170159.99      2289279.00      7170060.00
      2289229.00      7170010.00
#Sta/Elev= 30
  4894.3  797.68  4897.1  797.68  4902.7  796.94  4907.0  797.05  4908.3  797.08
  4916.6  796.76  4925.0  796.85  4930.6  796.61  4939.0  795.93  4947.4  795.83
  4953.0  795.33  4961.4  794.91  4969.8  794.10  4975.3  793.60  4983.7  792.48
  4992.1  791.18  4997.7  787.90  5003.3  787.18  5006.1  787.18  5009.6  787.18
  5018.2  784.03  5018.5  783.53  5022.0  783.53  5022.2  784.03  5028.5  787.22
  5034.4  790.21  5048.5  794.12  5062.7  796.40  5073.3  797.42  5076.8  797.42
#Mann=5,-1,0
  4894.3    0.05       0  4907.0    0.12       0  5018.2    0.07       0
  5022.2    0.12       0  5028.5    0.05       0
Bank Sta=5018.2,5022.2
Exp/Cntr=0.3,0.1

Type RM Length L Ch R = 1,5097,286,286,286
BEGIN DESCRIPTION:
MDE S 073 11.0
END DESCRIPTION:
XS GIS Cut Line= 3
      2289528.97      7169959.97      2289479.00      7169910.00
      2289328.97      7169910.00
#Sta/Elev= 29
  4930.1  794.91  4933.6  794.91  4944.2  793.38  4958.3  791.62  4972.5  789.32
  4986.6  786.58  4997.2  783.46  5000.8  783.46  5003.3  783.46  5008.8  782.11
  5009.0  781.61  5012.5  781.61  5012.8  782.11  5020.8  785.06  5030.8  787.06
  5040.8  787.27  5050.8  789.87  5060.8  791.39  5070.8  791.04  5080.8  790.49
  5090.8  790.91  5100.8  790.97  5110.8  793.06  5120.8  793.57  5130.8  794.17
  5140.8  794.61  5147.3  794.95  5148.3  795.00  5150.8  795.00
#Mann=4,-1,0
  4930.1    0.12       0  5008.8    0.07       0  5012.8    0.12       0
  5147.3    0.05       0
Bank Sta=5008.8,5012.8
Exp/Cntr=0.3,0.1

Type RM Length L Ch R = 1,4811,260,260,260
BEGIN DESCRIPTION:
MDE S 073 10.0
END DESCRIPTION:
XS GIS Cut Line= 3
      2289629.02      7169760.01      2289479.00      7169660.00
      2289329.00      7169660.00
#Sta/Elev= 30
  4819.6  794.88  4822.6  794.88  4827.1  793.98  4842.2  793.47  4848.2  793.91
  4863.2  792.36  4869.2  793.33  4878.2  791.78  4884.2  792.10  4899.2  788.15
  4905.3  788.71  4914.3  785.80  4927.8  782.69  4933.3  780.50  4933.6  780.00
  4937.1  780.00  4937.3  780.50  4941.3  781.45  4950.3  781.67  4956.3  783.08
  4963.8  783.91  4971.4  784.12  4977.4  783.14  4986.4  783.48  4996.9  783.08
  5019.9  784.10  5039.9  782.41  5059.9  787.92  5079.3  790.80  5149.9  795.43
#Mann=4,-1,0
  4819.6    0.12       0  4933.3    0.07       0  4937.3    0.12       0
  5079.3    0.05       0
Bank Sta=4933.3,4937.3
Exp/Cntr=0.3,0.1

Type RM Length L Ch R = 1,4551,127,127,127
BEGIN DESCRIPTION:
MDE S 073 9.0
END DESCRIPTION:
XS GIS Cut Line= 3
      2289828.99      7169659.99      2289529.00      7169460.00
      2289429.04      7169460.00
#Sta/Elev= 30
  4644.1  801.50  4651.6  800.33  4680.1  799.14  4687.7  798.06  4708.7  797.59
  4723.7  795.36  4737.5  795.37  4795.8  790.98  4904.0  785.46  4910.0  784.52
  4919.0  784.53  4925.0  783.37  4932.5  783.37  4940.0  781.79  4955.1  780.58
  4976.1  781.20  4982.1  780.73  4991.1  778.92  4995.1  777.40  4995.4  776.90
  4998.9  776.90  4999.1  777.40  5001.6  779.77  5024.6  780.91  5034.6  782.73
  5044.6  786.65  5055.8  787.81  5074.6  789.56  5084.6  789.24  5104.6  790.43
#Mann=5,-1,0
  4644.1    0.05       0  4737.5    0.12       0  4995.1    0.07       0
  4999.1    0.12       0  5055.8    0.05       0
Bank Sta=4995.1,4999.1
Exp/Cntr=0.3,0.1

Type RM Length L Ch R = 1,4424,227,227,227
BEGIN DESCRIPTION:
Mapping XS 532b2167
END DESCRIPTION:
XS GIS Cut Line= 2
      2289828.02      7169478.52      2289445.28      7169278.61
#Sta/Elev= 30
  4764.9  793.94  4774.4  793.29  4798.7  791.49  4808.9  791.96  4815.1  790.37
  4842.9  788.67  4853.7  788.79  4881.4  786.34  4903.5  785.27  4925.5  782.94
  4942.0  780.29  4955.6  779.41  4978.2  779.99  4986.1  779.12  4989.8  776.93
  4990.0  776.43  4993.5  776.43  4993.8  776.93  5030.3  783.00  5036.0  782.77
  5045.8  784.52  5058.0  784.05  5068.4  784.52  5074.5  785.76  5082.6  785.85
  5113.0  787.69  5118.6  787.44  5179.2  790.37  5184.9  789.57  5196.7  789.98
#Mann=5,-1,0
  4764.9    0.05       0  4774.4    0.12       0  4989.8    0.07       0
  4993.8    0.12       0  5082.6    0.05       0
Bank Sta=4989.8,4993.8
Exp/Cntr=0.3,0.1

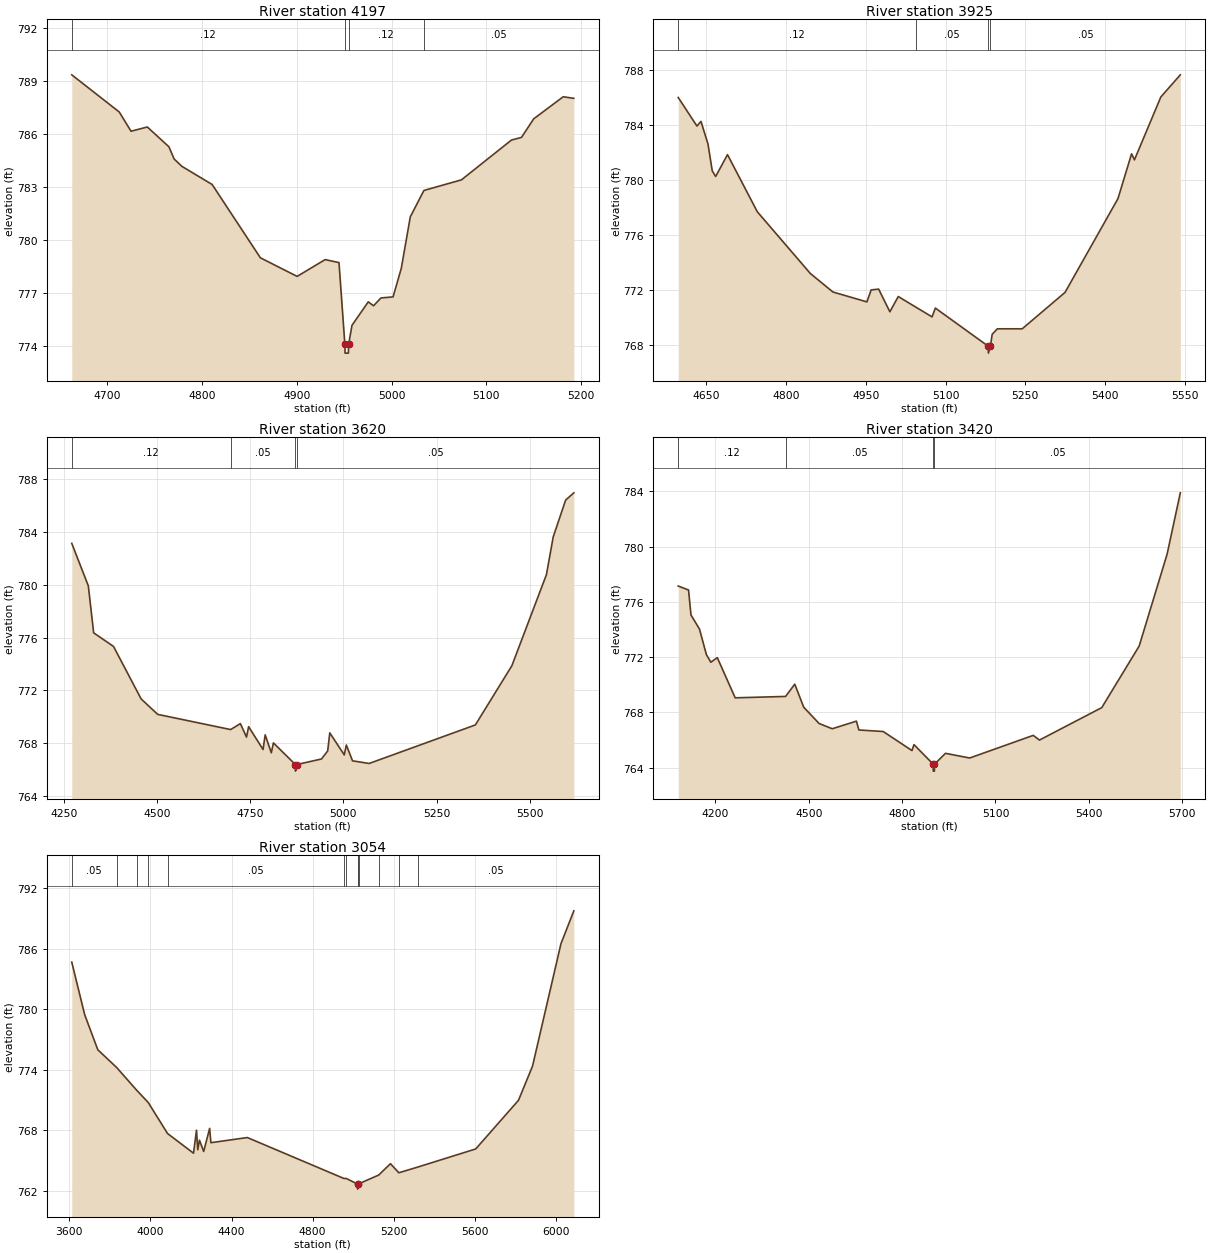
Type RM Length L Ch R = 1,4197,272,272,272
BEGIN DESCRIPTION:
Mapping XS 77398392
END DESCRIPTION:
XS GIS Cut Line= 3
      2289934.28      7169319.97      2289630.46      7169176.66
      2289446.71      7169239.75
#Sta/Elev= 30
  4662.3  789.35  4712.4  787.25  4724.9  786.16  4742.1  786.40  4764.9  785.28
  4770.4  784.59  4778.7  784.17  4810.5  783.15  4861.5  779.00  4900.3  777.95
  4929.9  778.90  4944.5  778.73  4950.7  774.11  4950.9  773.61  4954.4  773.61
  4954.7  774.11  4958.2  775.18  4975.4  776.51  4981.0  776.29  4988.8  776.73
  5001.6  776.79  5010.3  778.41  5019.8  781.32  5034.2  782.81  5073.8  783.41
  5126.6  785.66  5137.2  785.81  5150.1  786.86  5181.3  788.11  5192.5  788.02
#Mann=4,-1,0
  4662.3    0.12       0  4950.7    0.07       0  4954.7    0.12       0
  5034.2    0.05       0
Bank Sta=4950.7,4954.7
Exp/Cntr=0.3,0.1

Type RM Length L Ch R = 1,3925,305,305,305
BEGIN DESCRIPTION:
Mapping XS 10d96a79
END DESCRIPTION:
XS GIS Cut Line= 4
      2290042.33      7169196.37      2289726.57      7168941.27
      2289567.97      7168885.13      2289444.57      7169234.51
#Sta/Elev= 30
  4596.9  786.00  4632.1  783.92  4639.7  784.26  4652.9  782.61  4660.9  780.66
  4667.3  780.25  4689.6  781.84  4745.7  777.68  4845.4  773.19  4888.0  771.84
  4951.9  771.12  4959.9  771.99  4974.0  772.05  4995.1  770.40  5010.9  771.51
  5044.3  770.73  5074.5  770.03  5080.7  770.67  5180.3  767.89  5180.5  767.39
  5184.3  767.89  5187.6  768.76  5197.4  769.16  5244.1  769.16  5324.7  771.81
  5424.3  778.64  5449.9  781.90  5455.3  781.46  5505.0  786.04  5541.6  787.65
#Mann=4,-1,0
  4596.9    0.12       0  5044.3    0.05       0  5180.3    0.07       0
  5184.3    0.05       0
Bank Sta=5180.3,5184.3
Exp/Cntr=0.3,0.1

Type RM Length L Ch R = 1,3620,200,200,200
BEGIN DESCRIPTION:
Mapping XS f7680468
END DESCRIPTION:
XS GIS Cut Line= 4
      2290029.70      7169149.45      2289753.83      7168614.27
      2289554.40      7168716.17      2289431.61      7169221.41
#Sta/Elev= 30
  4271.7  783.14  4316.1  779.92  4330.4  776.36  4383.6  775.33  4457.7  771.35
  4502.1  770.18  4697.6  769.03  4723.7  769.48  4740.2  768.46  4745.8  769.25
  4784.5  767.52  4790.2  768.63  4806.7  767.27  4812.3  768.02  4871.2  766.38
  4871.5  765.88  4875.2  766.38  4941.2  766.80  4957.8  767.41  4963.4  768.78
  5002.2  767.11  5007.8  767.86  5024.4  766.66  5068.9  766.46  5353.7  769.38
  5451.6  773.87  5544.2  780.77  5562.4  783.63  5595.7  786.42  5617.7  786.97
#Mann=4,-1,0
  4271.7    0.12       0  4697.6    0.05       0  4871.2   0.033       0
  4875.2    0.05       0
Bank Sta=4871.2,4875.2
Exp/Cntr=0.3,0.1

Type RM Length L Ch R = 1,3420,366,366,366
BEGIN DESCRIPTION:
Mapping XS 762926c3
END DESCRIPTION:
XS GIS Cut Line= 4
      2290240.80      7168975.01      2289602.86      7168449.13
      2289462.06      7168574.99      2289432.10      7169172.04
#Sta/Elev= 30
  4080.6  777.15  4113.7  776.86  4121.6  775.05  4148.9  774.03  4171.1  772.18
  4185.4  771.63  4206.2  771.96  4263.6  769.05  4425.6  769.15  4455.1  770.04
  4483.8  768.37  4533.3  767.19  4575.4  766.81  4653.2  767.36  4661.0  766.72
  4739.2  766.61  4831.7  765.23  4838.2  765.66  4900.0  764.24  4900.2  763.74
  4903.7  763.74  4904.0  764.24  4939.4  765.03  5017.2  764.69  5221.4  766.33
  5241.4  765.99  5441.6  768.34  5561.8  772.80  5651.5  779.45  5694.0  783.90
#Mann=4,-1,0
  4080.6    0.12       0  4425.6    0.05       0  4900.0   0.033       0
  4904.0    0.05       0
Bank Sta=4900,4904
Exp/Cntr=0.3,0.1

Type RM Length L Ch R = 1,3054,0,0,0
BEGIN DESCRIPTION:
Mapping XS eee2e607
END DESCRIPTION:
XS GIS Cut Line= 3
      2290500.06      7169019.07      2289368.74      7168190.17
      2289429.73      7169263.46
#Sta/Elev= 30
  3611.6  784.67  3675.2  779.47  3740.0  775.99  3833.5  774.22  3931.4  771.99
  3989.0  770.76  4084.2  767.69  4212.4  765.74  4227.1  768.02  4233.3  766.08
  4241.7  767.03  4262.6  765.91  4291.9  768.20  4298.1  766.78  4478.0  767.29
  4955.2  763.23  4965.9  763.24  5021.9  762.68  5022.2  762.18  5025.9  762.68
  5026.8  762.70  5125.8  763.57  5184.2  764.70  5225.6  763.80  5318.1  764.36
  5604.9  766.16  5816.0  770.98  5885.3  774.37  6025.5  786.49  6089.1  789.75
#Mann=13,-1,0
  3611.6    0.05       0  3833.5    0.12       0  3931.4    0.05       0
  3989.0    0.12       0  4084.2    0.05       0  4955.2    0.12       0
  4965.9    0.05       0  5021.9   0.033       0  5025.9    0.05       0
  5026.8    0.12       0  5125.8    0.05       0  5225.6    0.12       0
  5318.1    0.05       0
Bank Sta=5021.9,5025.9
Exp/Cntr=0.3,0.1

Chan Stop Cuts=-1