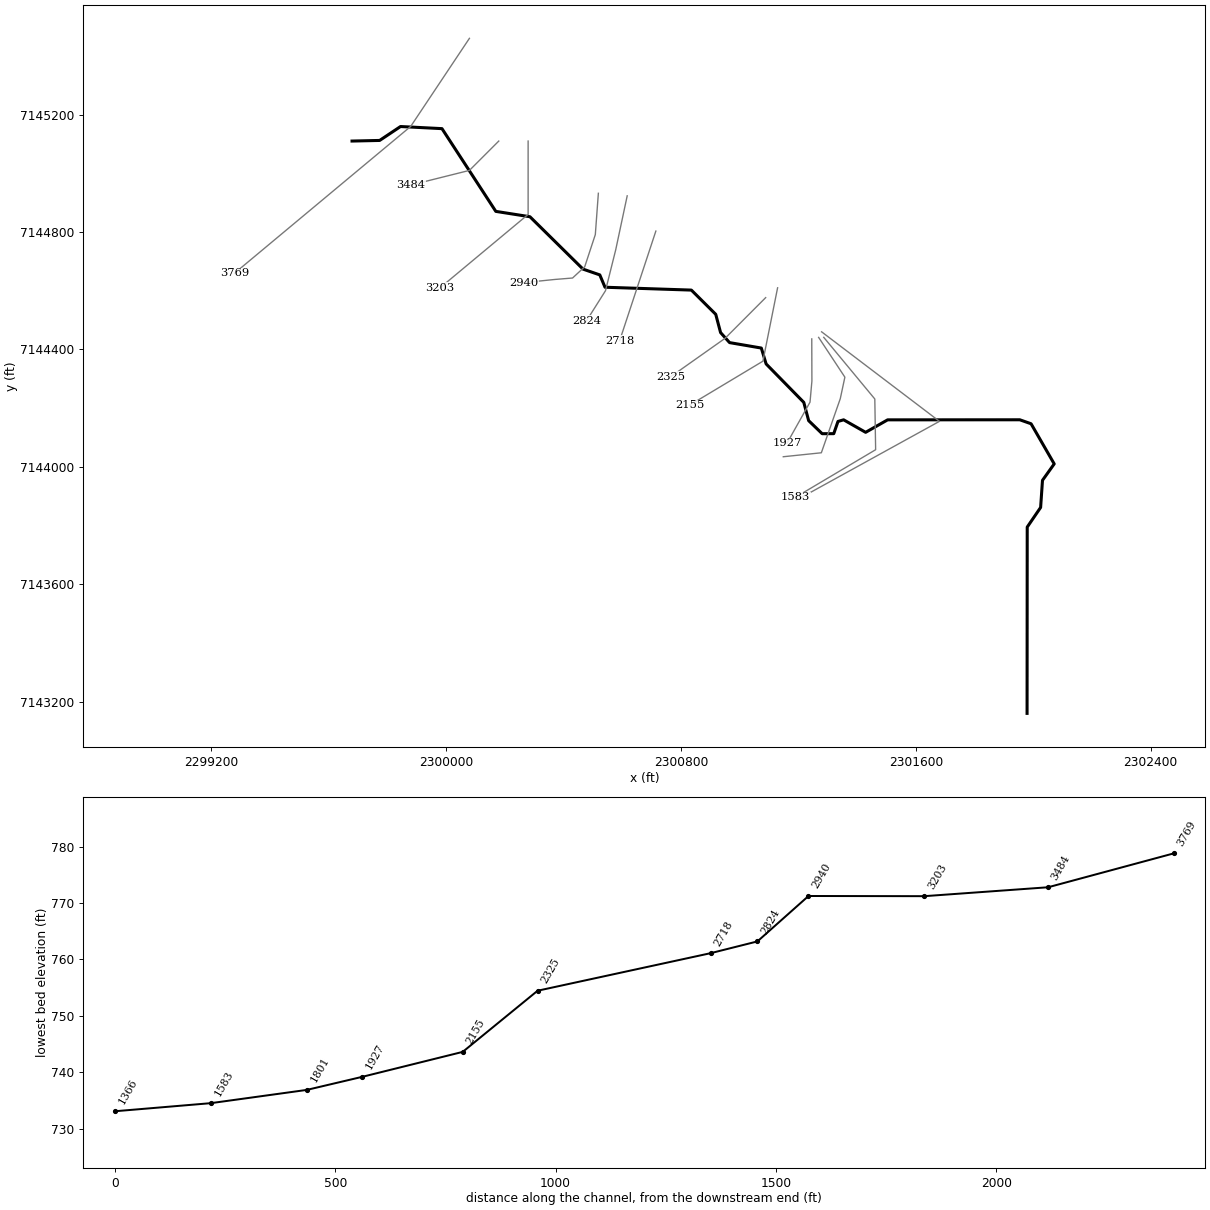
--- MDE S 074.prj (project) ---

Proj Title=MDE S 074 Base Level Engineering
Current Plan=p01
Default Exp/Contr=0.3,0.1
English Units
Geom File=g01
Flow File=f01
Plan File=p01
BEGIN DESCRIPTION:
MDE S 074
END DESCRIPTION:

--- MDE S 074.p01 (plan) ---

Plan Title=Multiple Run
Short Identifier=Multiple
Geom File=g01
Flow File=f01
Subcritical Flow
K Sum by GR= 0
Std Step Tol= 0.01
Critical Tol= 0.01
Num of Std Step Trials= 20
Max Error Tol= 0.3
Flow Tol Ratio= 0.001
Split Flow NTrial= 30
Split Flow Tol= 0.02
Split Flow Ratio= 0.02
Log Output Level= 0
Friction Slope Method= 1
Unsteady Friction Slope Method= 2
Unsteady Bridges Friction Slope Method= 1
Parabolic Critical Depth
Global Vel Dist=  1 , 1 , 1
Global Log Level= 0
CheckData=True
Encroach Param= -1, 0, 0, 0
BEGIN DESCRIPTION:
Multiple Run
END DESCRIPTION:

--- MDE S 074.f01 (steady flow) ---

Flow Title=Multiple
Number of Profiles=7
Profile Names=10-year,25-year,50-year,1pct_min,100-year,1pct_plu,500-year
River Rch & RM= MDE S 074,Reach-1,3769
     173     218     252     146     290     580     386
Boundary for River Rch & Prof#=MDE S 074,Reach-1,1
Up Type=0
Dn Type=3
Dn Slope=0.005
Boundary for River Rch & Prof#=MDE S 074,Reach-1,2
Up Type=0
Dn Type=3
Dn Slope=0.005
Boundary for River Rch & Prof#=MDE S 074,Reach-1,3
Up Type=0
Dn Type=3
Dn Slope=0.005
Boundary for River Rch & Prof#=MDE S 074,Reach-1,4
Up Type=0
Dn Type=3
Dn Slope=0.005
Boundary for River Rch & Prof#=MDE S 074,Reach-1,5
Up Type=0
Dn Type=3
Dn Slope=0.005
Boundary for River Rch & Prof#=MDE S 074,Reach-1,6
Up Type=0
Dn Type=3
Dn Slope=0.005
Boundary for River Rch & Prof#=MDE S 074,Reach-1,7
Up Type=0
Dn Type=3
Dn Slope=0.005

--- MDE S 074.g01 (geometry) ---

Geom Title=Existing Conditions

River Reach=MDE S 074,Reach-1
Reach XY= 30
      2299679.00      7145110.00      2299773.13      7145112.10
      2299844.22      7145159.51      2299985.47      7145152.31
      2300168.90      7144870.39      2300285.17      7144852.14
      2300466.00      7144673.69      2300523.20      7144653.94
      2300540.95      7144611.92      2300835.21      7144602.20
      2300918.22      7144519.68      2300934.74      7144457.43
      2300965.38      7144423.27      2301073.52      7144404.74
      2301089.90      7144350.62      2301218.21      7144219.66
      2301234.79      7144157.37      2301280.77      7144112.94
      2301320.33      7144113.03      2301334.77      7144154.68
      2301353.99      7144160.20      2301428.96      7144117.60
      2301503.88      7144160.11      2301954.21      7144160.33
      2301992.67      7144146.77      2302071.47      7144010.01
      2302031.55      7143954.11      2302025.15      7143861.60
      2301979.52      7143794.78      2301979.00      7143160.00

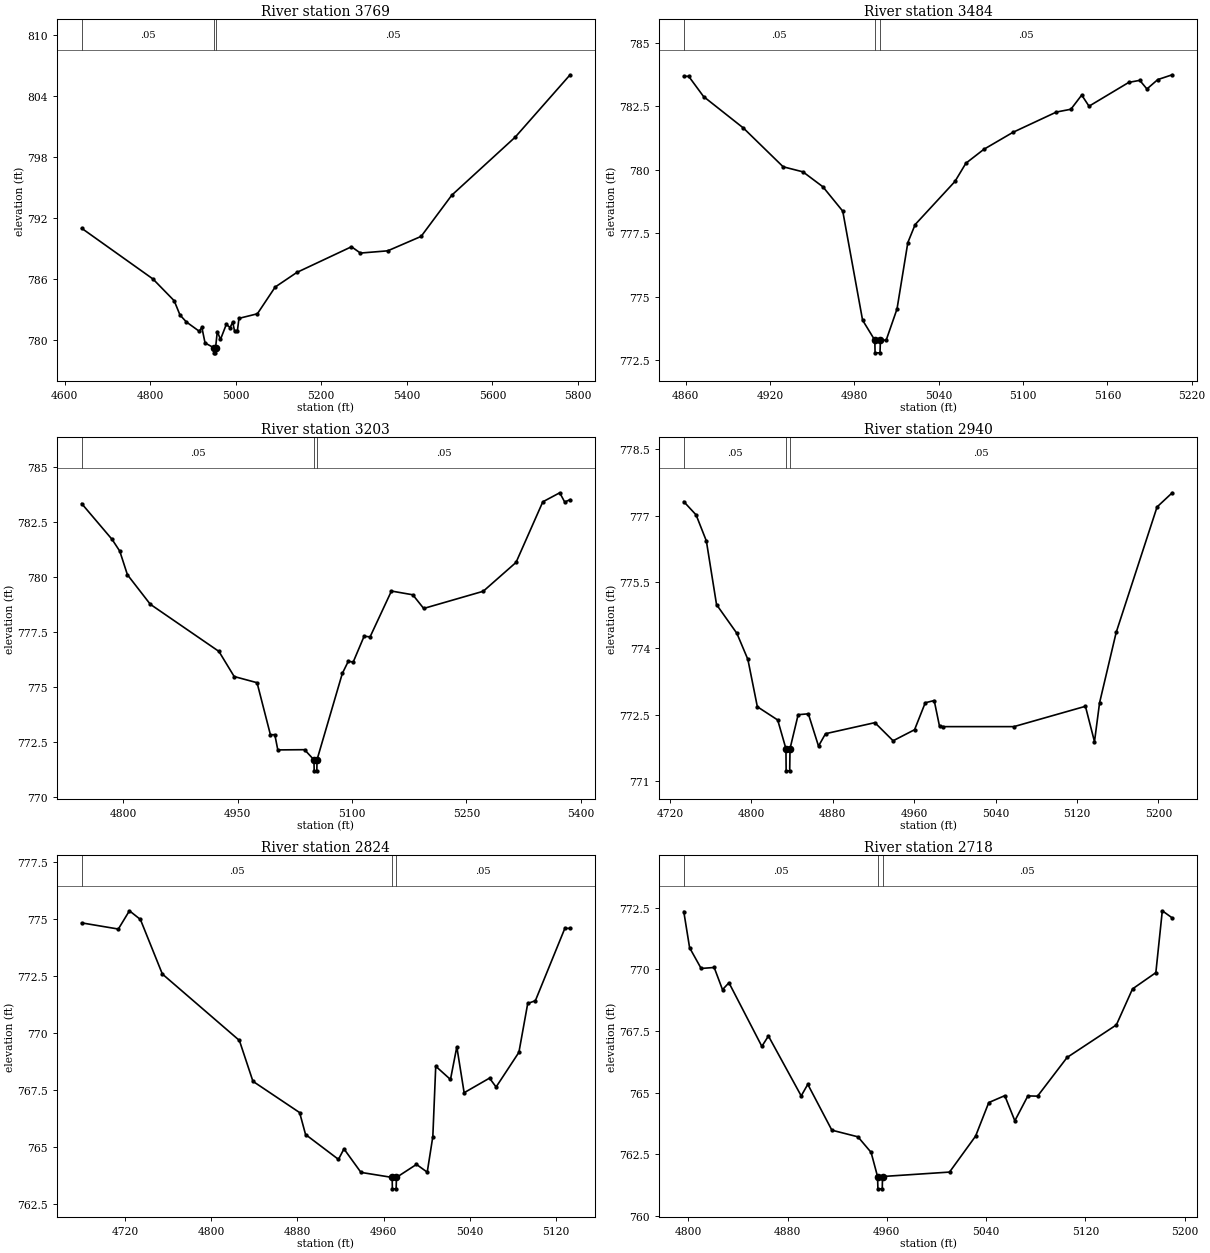
Type RM Length L Ch R = 1,3769,285,285,285
BEGIN DESCRIPTION:
MDE S 074 10.0
END DESCRIPTION:
XS GIS Cut Line= 3
      2300078.99      7145459.99      2299879.00      7145160.00
      2299278.98      7144659.98
#Sta/Elev= 30
  4640.0  791.03  4806.7  786.04  4856.3  783.90  4869.8  782.50  4884.9  781.81
  4914.9  780.90  4920.9  781.29  4928.4  779.75  4949.0  779.28  4949.2  778.78
  4952.7  778.78  4953.0  779.28  4957.0  780.87  4964.5  780.10  4978.0  781.57
  4987.0  781.27  4993.0  781.80  4997.5  780.90  5003.8  780.90  5007.7  782.17
  5050.7  782.62  5092.3  785.25  5143.1  786.69  5270.6  789.21  5291.5  788.59
  5355.3  788.81  5433.4  790.23  5505.0  794.28  5653.3  799.99  5781.6  806.12
#Mann=3,-1,0
  4640.0    0.05       0  4949.0   0.033       0  4953.0    0.05       0
Bank Sta=4949,4953
Exp/Cntr=0.3,0.1

Type RM Length L Ch R = 1,3484,281,281,281
BEGIN DESCRIPTION:
MDE S 074 9.0
END DESCRIPTION:
XS GIS Cut Line= 3
      2300178.98      7145109.98      2300079.00      7145010.00
      2299879.04      7144960.01
#Sta/Elev= 30
  4858.6  783.69  4862.1  783.69  4872.7  782.89  4901.0  781.65  4929.3  780.12
  4943.4  779.92  4957.6  779.33  4971.7  778.37  4985.8  774.07  4994.5  773.28
  4994.7  772.78  4998.2  772.78  4998.5  773.28  5002.6  773.28  5010.3  774.51
  5018.0  777.13  5023.2  777.84  5051.5  779.54  5059.3  780.26  5072.1  780.81
  5092.8  781.48  5123.7  782.28  5134.0  782.39  5141.7  782.95  5146.9  782.51
  5175.2  783.45  5183.0  783.53  5188.1  783.19  5195.8  783.56  5206.1  783.75
#Mann=3,-1,0
  4858.6    0.05       0  4994.5   0.033       0  4998.5    0.05       0
Bank Sta=4994.5,4998.5
Exp/Cntr=0.3,0.1

Type RM Length L Ch R = 1,3203,263,263,263
BEGIN DESCRIPTION:
MDE S 074 8.0
END DESCRIPTION:
XS GIS Cut Line= 3
      2300279.00      7145110.01      2300279.00      7144860.00
      2299979.01      7144610.01
#Sta/Elev= 30
  4745.4  783.33  4785.4  781.70  4795.4  781.17  4805.4  780.10  4835.4  778.76
  4925.4  776.62  4945.4  775.48  4975.4  775.20  4992.9  772.84  4998.7  772.84
  5002.6  772.15  5037.7  772.16  5050.0  771.70  5050.3  771.20  5053.8  771.20
  5054.0  771.70  5087.2  775.62  5095.0  776.17  5101.5  776.14  5115.8  777.31
  5123.6  777.28  5151.6  779.36  5179.6  779.19  5193.9  778.57  5272.0  779.35
  5315.0  780.66  5350.1  783.41  5372.3  783.82  5378.8  783.40  5385.9  783.51
#Mann=3,-1,0
  4745.4    0.05       0  5050.0   0.033       0  5054.0    0.05       0
Bank Sta=5050,5054
Exp/Cntr=0.3,0.1

Type RM Length L Ch R = 1,2940,116,116,116
BEGIN DESCRIPTION:
Mapping XS b37e3352
END DESCRIPTION:
XS GIS Cut Line= 6
      2300518.31      7144932.09      2300507.95      7144791.34
      2300471.81      7144681.66      2300430.38      7144643.36
      2300369.52      7144638.40      2300264.17      7144627.57
#Sta/Elev= 30
  4733.5  777.32  4745.6  777.02  4755.7  776.43  4765.7  774.99  4785.7  774.34
  4796.5  773.75  4805.8  772.68  4825.8  772.38  4833.9  771.73  4834.1  771.23
  4837.6  771.23  4837.9  771.73  4845.9  772.50  4855.9  772.52  4865.9  771.79
  4872.8  772.07  4921.3  772.32  4939.2  771.91  4960.3  772.16  4970.8  772.77
  4979.6  772.82  4984.8  772.24  4988.4  772.23  5057.9  772.23  5128.2  772.69
  5137.1  771.89  5142.1  772.77  5158.4  774.36  5198.6  777.20  5213.5  777.52
#Mann=3,-1,0
  4733.5    0.05       0  4833.9   0.033       0  4837.9    0.05       0
Bank Sta=4833.9,4837.9
Exp/Cntr=0.3,0.1

Type RM Length L Ch R = 1,2824,106,106,106
BEGIN DESCRIPTION:
Mapping XS 86fd04e3
END DESCRIPTION:
XS GIS Cut Line= 4
      2300616.58      7144923.39      2300577.57      7144740.12
      2300542.65      7144600.15      2300477.36      7144496.67
#Sta/Elev= 30
  4679.4  774.83  4713.5  774.56  4723.8  775.36  4734.0  774.98  4754.4  772.59
  4826.0  769.68  4838.6  767.89  4882.0  766.52  4887.5  765.56  4918.1  764.47
  4923.2  764.93  4939.0  763.90  4968.0  763.68  4968.2  763.18  4971.7  763.18
  4972.0  763.68  4990.6  764.25  5000.6  763.91  5005.8  765.47  5008.5  768.55
  5022.2  767.97  5028.1  769.40  5034.9  767.39  5058.5  768.03  5064.6  767.64
  5085.8  769.16  5094.0  771.30  5101.1  771.42  5128.5  774.59  5133.4  774.59
#Mann=3,-1,0
  4679.4    0.05       0  4968.0   0.033       0  4972.0    0.05       0
Bank Sta=4968,4972
Exp/Cntr=0.3,0.1

Type RM Length L Ch R = 1,2718,393,393,393
BEGIN DESCRIPTION:
Mapping XS afdf910a
END DESCRIPTION:
XS GIS Cut Line= 2
      2300714.21      7144803.25      2300590.77      7144429.62
#Sta/Elev= 30
  4796.4  772.35  4801.1  770.88  4810.4  770.04  4820.9  770.08  4827.6  769.18
  4832.8  769.46  4859.3  766.88  4864.6  767.30  4891.0  764.87  4896.3  765.34
  4915.7  763.48  4936.7  763.21  4947.3  762.58  4952.5  761.60  4952.8  761.10
  4956.3  761.10  4956.5  761.60  5010.5  761.78  5031.5  763.24  5042.1  764.60
  5055.0  764.88  5063.1  763.86  5073.6  764.87  5081.4  764.86  5105.2  766.43
  5144.9  767.75  5157.9  769.21  5176.7  769.87  5181.9  772.38  5189.9  772.09
#Mann=3,-1,0
  4796.4    0.05       0  4952.5   0.033       0  4956.5    0.05       0
Bank Sta=4952.5,4956.5
Exp/Cntr=0.3,0.1

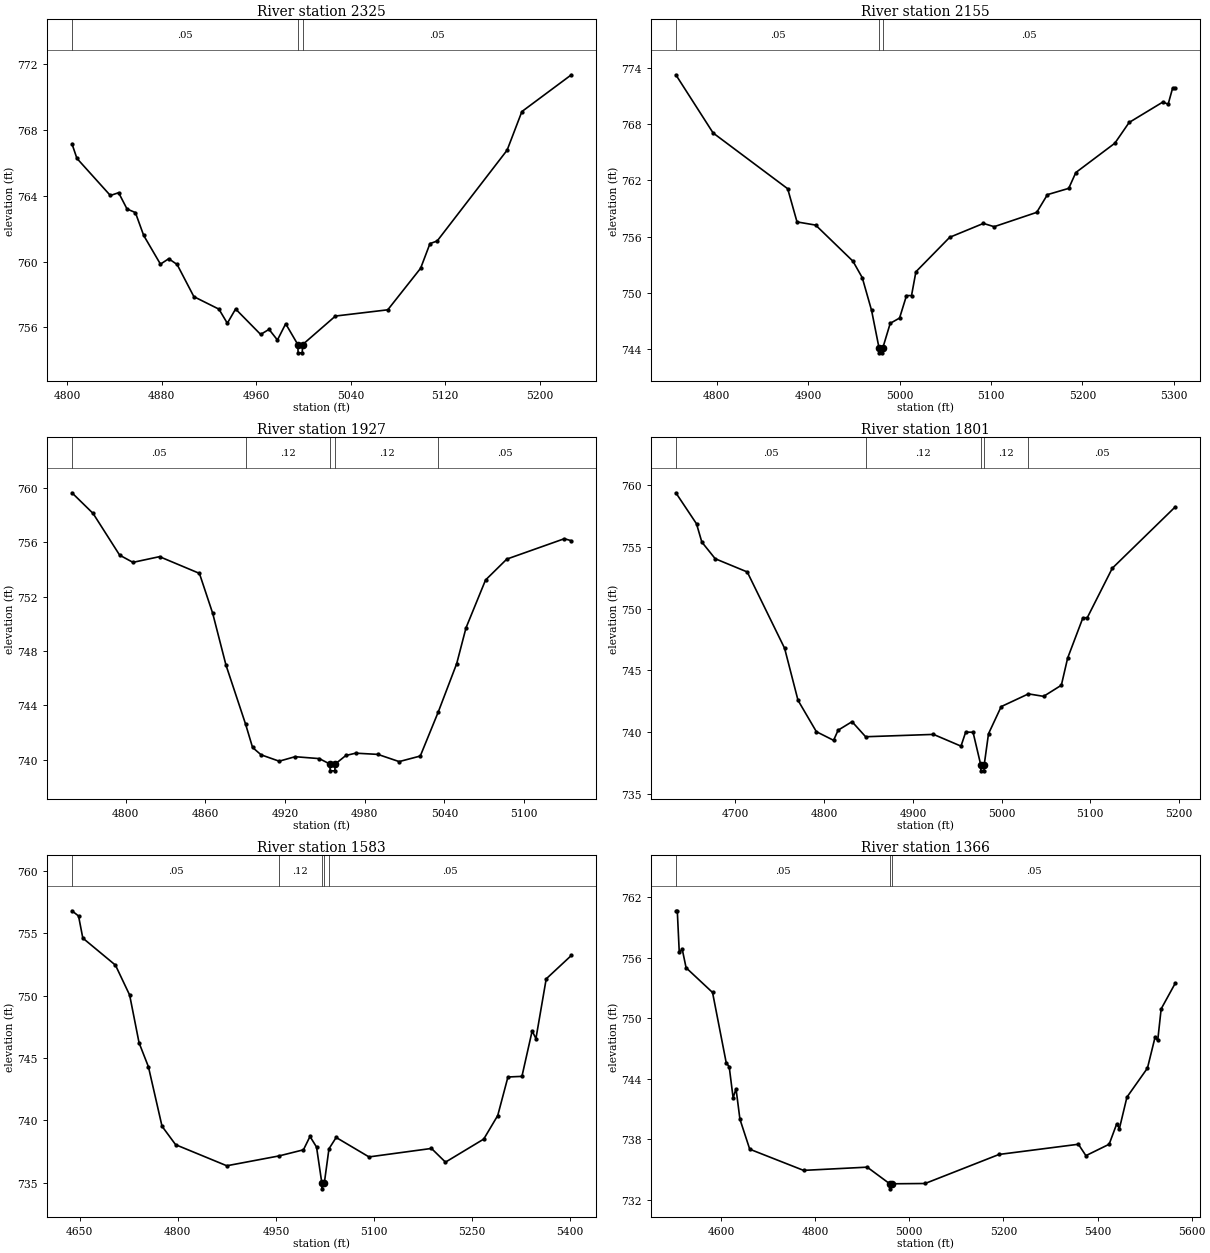
Type RM Length L Ch R = 1,2325,170,170,170
BEGIN DESCRIPTION:
Mapping XS 9bae7ada
END DESCRIPTION:
XS GIS Cut Line= 3
      2301088.36      7144576.54      2300949.82      7144437.70
      2300764.77      7144306.99
#Sta/Elev= 30
  4804.2  767.17  4808.4  766.28  4836.7  764.02  4843.7  764.19  4850.8  763.20
  4857.9  762.98  4864.9  761.59  4879.1  759.84  4886.1  760.17  4893.2  759.82
  4907.4  757.86  4928.6  757.10  4935.7  756.24  4942.7  757.11  4963.9  755.56
  4971.0  755.87  4978.1  755.22  4985.1  756.21  4995.4  754.94  4995.6  754.44
  4999.1  754.44  4999.4  754.94  5027.2  756.68  5071.5  757.06  5099.3  759.59
  5107.2  761.09  5113.3  761.25  5172.5  766.78  5185.0  769.13  5226.9  771.37
#Mann=3,-1,0
  4804.2    0.05       0  4995.4   0.033       0  4999.4    0.05       0
Bank Sta=4995.4,4999.4
Exp/Cntr=0.3,0.1

Type RM Length L Ch R = 1,2155,228,228,228
BEGIN DESCRIPTION:
MDE S 074 4.0
END DESCRIPTION:
XS GIS Cut Line= 3
      2301129.00      7144610.02      2301079.00      7144360.00
      2300829.02      7144210.01
#Sta/Elev= 30
  4755.2  773.27  4796.0  767.06  4877.6  761.11  4887.8  757.57  4908.2  757.23
  4949.0  753.38  4959.2  751.62  4969.4  748.12  4977.6  744.10  4977.8  743.60
  4981.3  743.60  4981.6  744.10  4989.8  746.75  5000.0  747.31  5007.6  749.71
  5013.1  749.71  5017.9  752.25  5054.9  755.93  5091.8  757.41  5103.5  757.06
  5150.1  758.59  5161.8  760.48  5185.1  761.15  5192.9  762.84  5235.6  765.97
  5251.2  768.18  5288.1  770.36  5293.9  770.13  5298.8  771.85  5301.7  771.85
#Mann=3,-1,0
  4755.2    0.05       0  4977.6   0.033       0  4981.6    0.05       0
Bank Sta=4977.6,4981.6
Exp/Cntr=0.3,0.1

Type RM Length L Ch R = 1,1927,126,126,126
BEGIN DESCRIPTION:
Mapping XS 51d311e8
END DESCRIPTION:
XS GIS Cut Line= 4
      2301245.41      7144435.89      2301245.88      7144292.25
      2301239.47      7144220.37      2301161.17      7144080.84
#Sta/Elev= 30
  4759.7  759.64  4775.6  758.12  4795.6  755.05  4805.6  754.52  4825.6  754.94
  4855.6  753.71  4865.6  750.77  4875.6  746.96  4890.4  742.60  4895.6  740.90
  4902.0  740.36  4915.6  739.89  4927.6  740.22  4945.8  740.08  4953.8  739.68
  4954.0  739.18  4957.5  739.18  4957.8  739.68  4965.8  740.31  4973.2  740.48
  4989.9  740.39  5005.9  739.86  5021.8  740.27  5035.4  743.53  5049.2  747.07
  5056.2  749.70  5070.9  753.22  5086.9  754.76  5130.2  756.26  5135.5  756.11
#Mann=5,-1,0
  4759.7    0.05       0  4890.4    0.12       0  4953.8    0.07       0
  4957.8    0.12       0  5035.4    0.05       0
Bank Sta=4953.8,4957.8
Exp/Cntr=0.3,0.1

Type RM Length L Ch R = 1,1801,218,218,218
BEGIN DESCRIPTION:
Mapping XS f1c7ad1b
END DESCRIPTION:
XS GIS Cut Line= 5
      2301268.87      7144441.00      2301358.22      7144305.58
      2301342.62      7144232.39      2301278.07      7144047.93
      2301148.37      7144034.42
#Sta/Elev= 30
  4632.8  759.37  4656.1  756.86  4662.1  755.38  4677.2  754.03  4713.3  752.96
  4755.4  746.78  4770.5  742.57  4791.2  740.03  4810.6  739.33  4815.7  740.15
  4831.4  740.84  4846.7  739.62  4923.2  739.81  4954.2  738.86  4959.5  740.00
  4967.8  739.98  4976.4  737.36  4976.6  736.86  4980.1  736.86  4980.4  737.36
  4985.2  739.86  4999.5  742.06  5030.2  743.09  5047.3  742.89  5067.3  743.79
  5074.4  745.99  5091.5  749.23  5096.6  749.27  5124.7  753.26  5195.7  758.23
#Mann=5,-1,0
  4632.8    0.05       0  4846.7    0.12       0  4976.4    0.07       0
  4980.4    0.12       0  5030.2    0.05       0
Bank Sta=4976.4,4980.4
Exp/Cntr=0.3,0.1

Type RM Length L Ch R = 1,1583,217,217,217
BEGIN DESCRIPTION:
Mapping XS c908c60f
END DESCRIPTION:
XS GIS Cut Line= 4
      2301286.25      7144441.17      2301460.22      7144231.18
      2301463.04      7144058.37      2301189.61      7143896.06
#Sta/Elev= 30
  4638.2  756.81  4648.3  756.39  4654.8  754.62  4704.7  752.45  4726.4  750.05
  4740.8  746.22  4755.1  744.30  4775.9  739.53  4796.7  738.05  4874.9  736.36
  4954.8  737.15  4992.1  737.64  5002.1  738.71  5012.1  737.86  5020.1  735.01
  5020.3  734.51  5024.1  735.01  5031.1  737.72  5042.1  738.63  5092.3  737.07
  5187.8  737.75  5209.2  736.65  5267.7  738.50  5289.1  740.39  5304.7  743.48
  5326.1  743.53  5341.7  747.17  5347.5  746.56  5363.2  751.35  5401.7  753.23
#Mann=5,-1,0
  4638.2    0.05       0  4954.8    0.12       0  5020.1    0.07       0
  5024.1    0.12       0  5031.1    0.05       0
Bank Sta=5020.1,5024.1
Exp/Cntr=0.3,0.1

Type RM Length L Ch R = 1,1366,0,0,0
BEGIN DESCRIPTION:
MDE S 074 3.0
END DESCRIPTION:
XS GIS Cut Line= 3
      2301278.99      7144460.01      2301680.45      7144155.00
      2301192.68      7143886.23
#Sta/Elev= 30
  4504.1  760.65  4507.2  760.65  4511.4  756.52  4517.7  756.84  4525.9  755.00
  4582.1  752.55  4611.2  745.57  4617.5  745.19  4625.8  742.10  4632.0  743.00
  4640.3  739.98  4661.1  737.01  4775.5  734.91  4910.7  735.23  4958.6  733.58
  4958.8  733.08  4962.6  733.58  5033.7  733.61  5190.8  736.49  5359.4  737.50
  5375.3  736.37  5424.7  737.50  5440.8  739.52  5446.5  739.05  5462.5  742.17
  5506.1  745.05  5522.2  748.10  5527.9  747.79  5535.2  750.92  5565.2  753.47
#Mann=3,-1,0
  4504.1    0.05       0  4958.6    0.04       0  4962.6    0.05       0
Bank Sta=4958.6,4962.6
Exp/Cntr=0.3,0.1

Chan Stop Cuts=-1