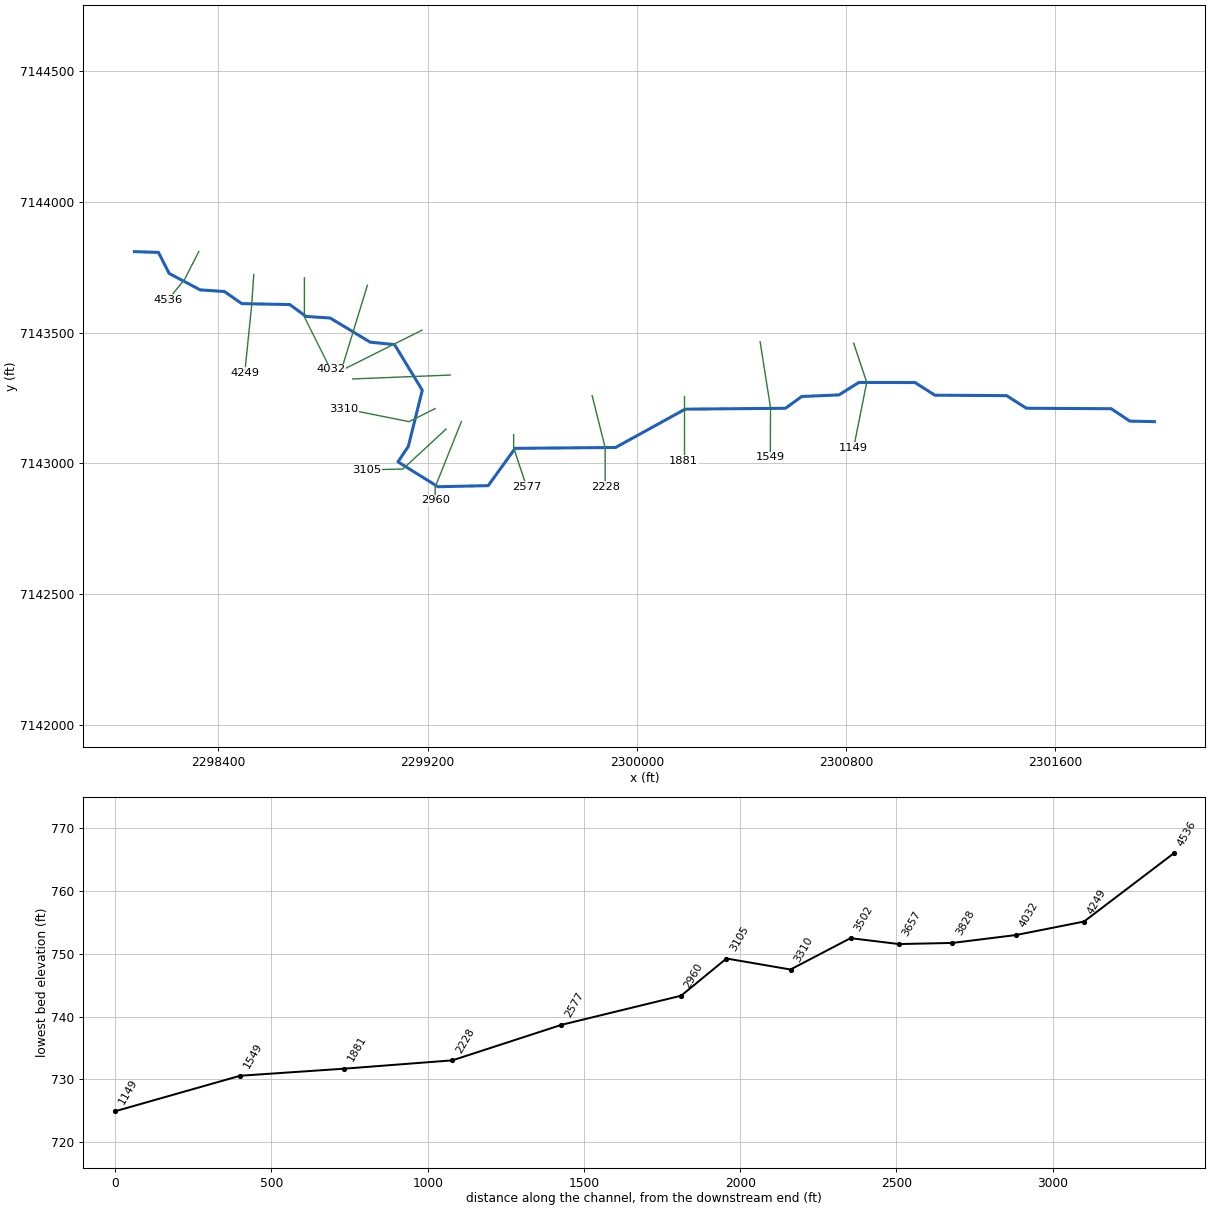
--- MDE S 075.prj (project) ---

Proj Title=MDE S 075 Base Level Engineering
Current Plan=p01
Default Exp/Contr=0.3,0.1
English Units
Geom File=g01
Flow File=f01
Plan File=p01
BEGIN DESCRIPTION:
MDE S 075
END DESCRIPTION:

--- MDE S 075.p01 (plan) ---

Plan Title=Multiple Run
Short Identifier=Multiple
Geom File=g01
Flow File=f01
Subcritical Flow
K Sum by GR= 0
Std Step Tol= 0.01
Critical Tol= 0.01
Num of Std Step Trials= 20
Max Error Tol= 0.3
Flow Tol Ratio= 0.001
Split Flow NTrial= 30
Split Flow Tol= 0.02
Split Flow Ratio= 0.02
Log Output Level= 0
Friction Slope Method= 1
Unsteady Friction Slope Method= 2
Unsteady Bridges Friction Slope Method= 1
Parabolic Critical Depth
Global Vel Dist=  1 , 1 , 1
Global Log Level= 0
CheckData=True
Encroach Param= -1, 0, 0, 0
BEGIN DESCRIPTION:
Multiple Run
END DESCRIPTION:

--- MDE S 075.f01 (steady flow) ---

Flow Title=Multiple
Number of Profiles=7
Profile Names=10-year,25-year,50-year,1pct_min,100-year,1pct_plu,500-year
River Rch & RM= MDE S 075,Reach-1,4536
     600     824    1011     616    1230    2453    1822
Boundary for River Rch & Prof#=MDE S 075,Reach-1,1
Up Type=0
Dn Type=3
Dn Slope=0.005
Boundary for River Rch & Prof#=MDE S 075,Reach-1,2
Up Type=0
Dn Type=3
Dn Slope=0.005
Boundary for River Rch & Prof#=MDE S 075,Reach-1,3
Up Type=0
Dn Type=3
Dn Slope=0.005
Boundary for River Rch & Prof#=MDE S 075,Reach-1,4
Up Type=0
Dn Type=3
Dn Slope=0.005
Boundary for River Rch & Prof#=MDE S 075,Reach-1,5
Up Type=0
Dn Type=3
Dn Slope=0.005
Boundary for River Rch & Prof#=MDE S 075,Reach-1,6
Up Type=0
Dn Type=3
Dn Slope=0.005
Boundary for River Rch & Prof#=MDE S 075,Reach-1,7
Up Type=0
Dn Type=3
Dn Slope=0.005

--- MDE S 075.g01 (geometry) ---

Geom Title=Existing Conditions

River Reach=MDE S 075,Reach-1
Reach XY= 30
      2298079.00      7143810.00      2298170.88      7143807.15
      2298211.98      7143726.56      2298330.58      7143663.82
      2298423.02      7143657.64      2298489.50      7143611.22
      2298673.06      7143607.74      2298734.98      7143562.36
      2298827.42      7143556.17      2298980.66      7143463.86
      2299073.53      7143454.74      2299179.67      7143280.08
      2299126.44      7143065.88      2299086.69      7143006.33
      2299239.50      7142911.20      2299431.70      7142915.36
      2299534.67      7143058.02      2299918.50      7143061.20
      2300184.93      7143207.76      2300568.50      7143211.22
      2300630.57      7143256.21      2300773.06      7143262.27
      2300849.03      7143309.93      2301063.78      7143309.48
      2301139.50      7143261.22      2301413.78      7143259.48
      2301489.50      7143211.22      2301813.79      7143209.49
      2301884.87      7143162.10      2301979.00      7143160.00

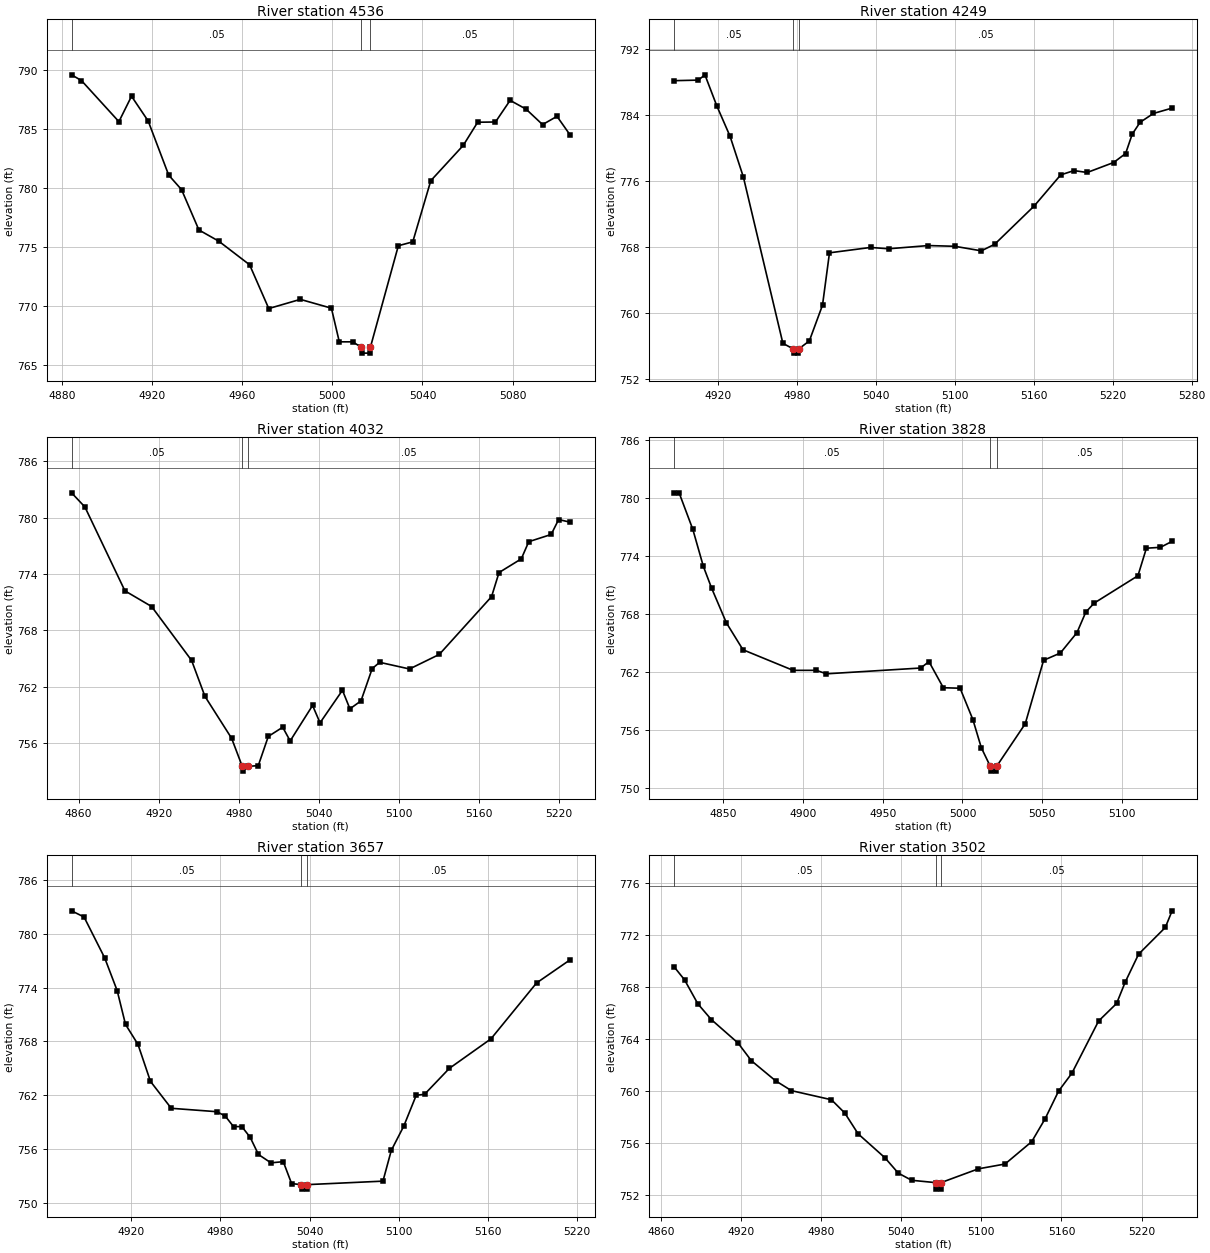
Type RM Length L Ch R = 1,4536,287,287,287
BEGIN DESCRIPTION:
MDE S 075 13.0
END DESCRIPTION:
XS GIS Cut Line= 3
      2298325.31      7143810.25      2298270.84      7143704.19
      2298206.90      7143624.89
#Sta/Elev= 30
  4884.3  789.63  4888.7  789.14  4905.3  785.65  4910.9  787.81  4918.3  785.70
  4927.4  781.10  4933.1  779.87  4940.8  776.44  4949.6  775.49  4963.3  773.48
  4971.8  769.76  4985.8  770.54  4999.6  769.79  5003.1  766.93  5009.0  766.93
  5012.9  766.47  5013.1  765.97  5016.6  765.97  5016.9  766.47  5029.3  775.10
  5035.7  775.43  5043.7  780.63  5058.1  783.63  5064.5  785.60  5072.4  785.62
  5078.9  787.46  5086.0  786.71  5093.3  785.40  5099.7  786.10  5105.4  784.55
#Mann=3,-1,0
  4884.3    0.05       0  5012.9   0.033       0  5016.9    0.05       0
Bank Sta=5012.9,5016.9
Exp/Cntr=0.3,0.1

Type RM Length L Ch R = 1,4249,217,217,217
BEGIN DESCRIPTION:
MDE S 075 12.0
END DESCRIPTION:
XS GIS Cut Line= 3
      2298535.32      7143722.64      2298527.28      7143604.43
      2298500.82      7143345.86
#Sta/Elev= 30
  4886.7  788.12  4905.3  788.19  4910.3  788.83  4919.4  785.04  4929.4  781.38
  4939.5  776.45  4969.5  756.31  4977.5  755.62  4977.8  755.12  4981.3  755.12
  4981.5  755.62  4989.6  756.60  4999.6  760.93  5004.9  767.27  5036.1  767.92
  5049.8  767.76  5080.0  768.15  5100.1  768.06  5120.2  767.51  5130.3  768.30
  5160.4  772.95  5180.5  776.71  5190.6  777.23  5200.6  777.00  5220.7  778.21
  5229.8  779.30  5234.8  781.64  5240.8  783.08  5250.9  784.15  5265.1  784.80
#Mann=3,-1,0
  4886.7    0.05       0  4977.5   0.033       0  4981.5    0.05       0
Bank Sta=4977.5,4981.5
Exp/Cntr=0.3,0.1

Type RM Length L Ch R = 1,4032,204,204,204
BEGIN DESCRIPTION:
MDE S 075 11.0
END DESCRIPTION:
XS GIS Cut Line= 3
      2298729.00      7143709.96      2298729.00      7143560.00
      2298829.02      7143359.97
#Sta/Elev= 30
  4854.7  782.65  4864.7  781.14  4894.7  772.20  4914.7  770.53  4944.7  764.78
  4954.7  760.95  4974.7  756.48  4982.7  753.48  4982.9  752.98  4986.7  753.48
  4994.7  753.57  5002.2  756.68  5013.0  757.66  5018.6  756.20  5035.4  759.98
  5041.0  758.13  5057.8  761.60  5063.4  759.62  5071.7  760.47  5080.1  763.91
  5085.7  764.58  5108.1  763.87  5130.4  765.42  5169.6  771.58  5175.2  774.15
  5191.9  775.61  5197.5  777.44  5214.3  778.21  5219.9  779.80  5228.3  779.53
#Mann=3,-1,0
  4854.7    0.05       0  4982.7   0.033       0  4986.7    0.05       0
Bank Sta=4982.7,4986.7
Exp/Cntr=0.3,0.1

Type RM Length L Ch R = 1,3828,171,171,171
BEGIN DESCRIPTION:
Mapping XS 95dbb49c
END DESCRIPTION:
XS GIS Cut Line= 2
      2298969.81      7143681.41      2298878.19      7143383.06
#Sta/Elev= 30
  4819.2  780.52  4822.5  780.52  4831.1  776.73  4837.7  772.90  4842.9  770.64
  4852.1  767.07  4862.5  764.28  4893.9  762.15  4908.4  762.15  4914.8  761.79
  4973.8  762.39  4979.0  763.05  4988.0  760.35  4998.5  760.30  5006.5  757.06
  5011.8  754.14  5017.4  752.22  5017.7  751.72  5021.2  751.72  5021.4  752.22
  5039.3  756.62  5050.8  763.19  5061.3  763.94  5071.7  766.05  5077.2  768.16
  5082.4  769.10  5109.9  771.94  5115.2  774.79  5124.0  774.88  5131.3  775.50
#Mann=3,-1,0
  4819.2    0.05       0  5017.4   0.033       0  5021.4    0.05       0
Bank Sta=5017.4,5021.4
Exp/Cntr=0.3,0.1

Type RM Length L Ch R = 1,3657,155,155,155
BEGIN DESCRIPTION:
MDE S 075 10.0
END DESCRIPTION:
XS GIS Cut Line= 3
      2299178.99      7143509.99      2299079.00      7143460.00
      2298879.00      7143360.00
#Sta/Elev= 30
  4879.8  782.56  4888.2  781.87  4902.1  777.31  4910.5  773.66  4916.1  769.90
  4924.5  767.67  4932.9  763.55  4946.9  760.55  4977.6  760.17  4983.2  759.69
  4988.8  758.51  4994.4  758.51  5000.0  757.32  5005.6  755.40  5014.0  754.47
  5022.3  754.60  5027.9  752.16  5034.3  752.04  5034.6  751.54  5038.1  751.54
  5038.3  752.04  5089.4  752.43  5095.0  755.85  5103.4  758.56  5111.8  762.00
  5117.4  762.11  5134.1  765.00  5162.1  768.29  5192.8  774.52  5215.2  777.08
#Mann=3,-1,0
  4879.8    0.05       0  5034.3   0.033       0  5038.3    0.05       0
Bank Sta=5034.3,5038.3
Exp/Cntr=0.3,0.1

Type RM Length L Ch R = 1,3502,192,192,192
BEGIN DESCRIPTION:
Mapping XS c4bd701d
END DESCRIPTION:
XS GIS Cut Line= 2
      2299287.03      7143338.16      2298913.93      7143323.29
#Sta/Elev= 30
  4869.5  769.59  4877.5  768.57  4887.5  766.72  4897.6  765.51  4917.6  763.71
  4927.6  762.35  4945.7  760.81  4957.6  760.05  4987.6  759.35  4997.6  758.33
  5007.6  756.73  5027.7  754.89  5037.7  753.71  5047.7  753.16  5065.7  752.98
  5065.9  752.48  5069.4  752.48  5069.7  752.98  5097.7  754.04  5117.7  754.41
  5137.7  756.13  5147.8  757.90  5157.8  760.01  5167.8  761.39  5187.8  765.40
  5201.3  766.75  5207.8  768.40  5217.8  770.54  5237.8  772.59  5242.9  773.87
#Mann=3,-1,0
  4869.5    0.05       0  5065.7   0.033       0  5069.7    0.05       0
Bank Sta=5065.7,5069.7
Exp/Cntr=0.3,0.1

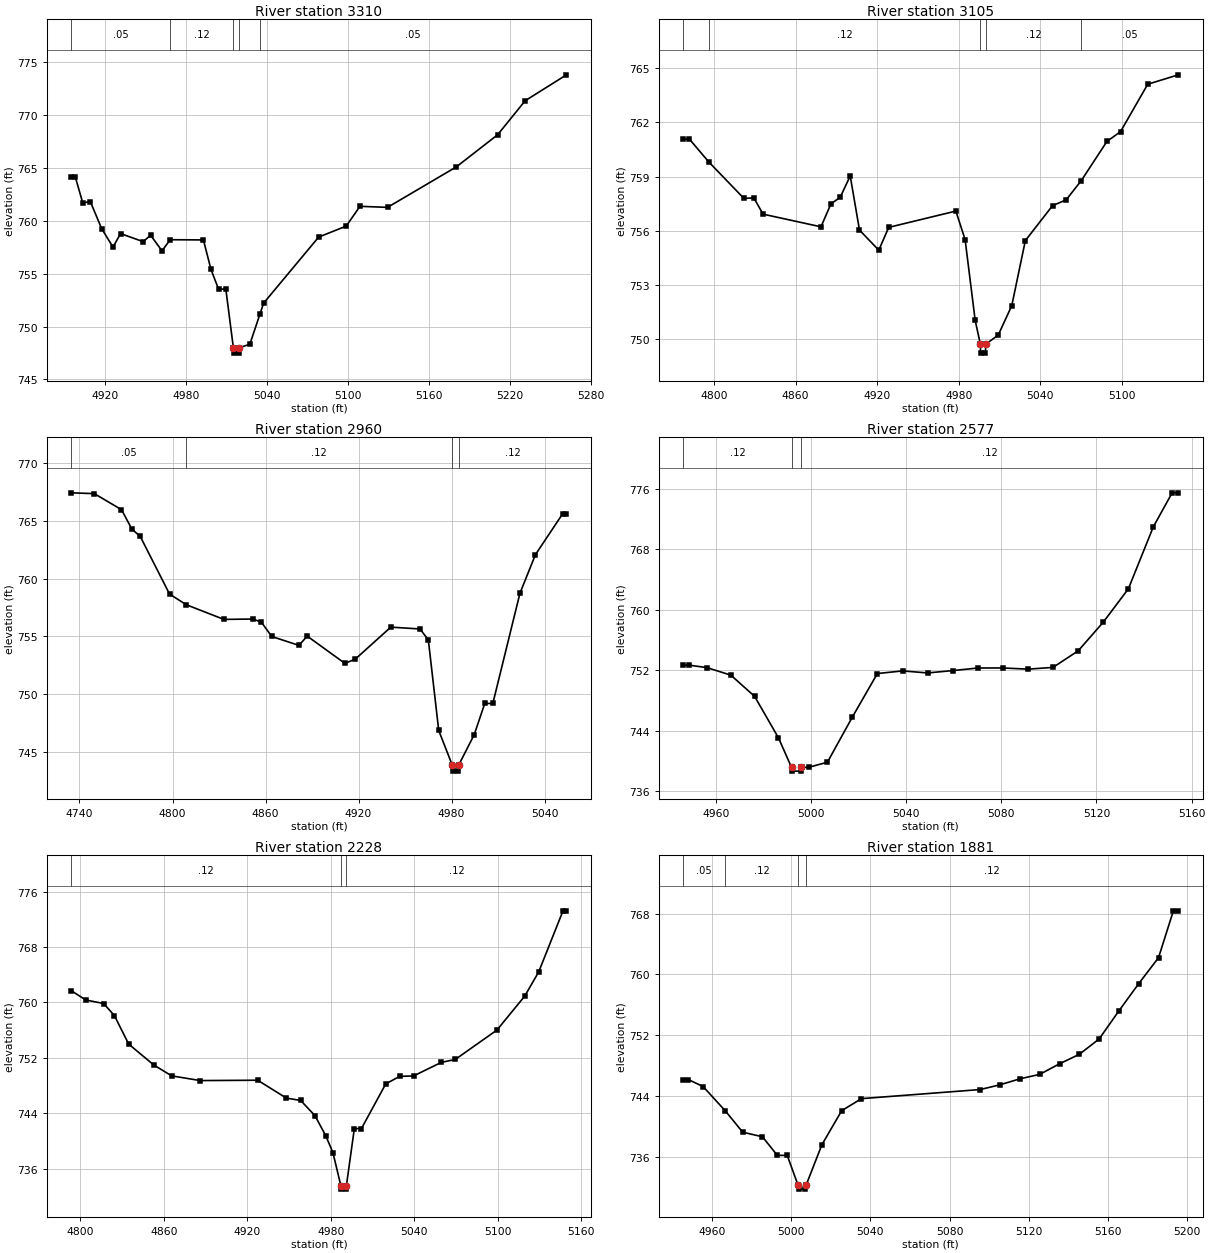
Type RM Length L Ch R = 1,3310,205,205,205
BEGIN DESCRIPTION:
MDE S 075 9.0
END DESCRIPTION:
XS GIS Cut Line= 3
      2299229.02      7143210.01      2299129.00      7143160.00
      2298878.98      7143210.00
#Sta/Elev= 30
  4895.3  764.19  4898.1  764.19  4903.7  761.70  4909.3  761.83  4917.7  759.27
  4926.1  757.52  4931.7  758.80  4948.4  758.04  4954.0  758.64  4962.4  757.17
  4968.5  758.22  4993.1  758.20  4998.7  755.41  5004.3  753.55  5009.7  753.55
  5015.3  747.99  5015.6  747.49  5019.1  747.49  5019.3  747.99  5027.5  748.33
  5035.0  751.19  5037.7  752.22  5078.5  758.47  5098.9  759.51  5109.1  761.38
  5129.5  761.28  5180.5  765.11  5211.1  768.15  5231.5  771.37  5262.1  773.82
#Mann=5,-1,0
  4895.3    0.05       0  4968.5    0.12       0  5015.3    0.07       0
  5019.3    0.12       0  5035.0    0.05       0
Bank Sta=5015.3,5019.3
Exp/Cntr=0.3,0.1

Type RM Length L Ch R = 1,3105,145,145,145
BEGIN DESCRIPTION:
Mapping XS 8270667a
END DESCRIPTION:
XS GIS Cut Line= 3
      2299270.62      7143131.65      2299105.42      7142978.70
      2298966.48      7142975.70
#Sta/Elev= 30
  4777.4  761.07  4781.9  761.07  4796.0  759.82  4822.0  757.79  4829.3  757.82
  4836.1  756.92  4878.7  756.22  4886.0  757.49  4892.8  757.85  4900.2  759.03
  4907.0  756.04  4921.2  754.93  4928.5  756.19  4977.9  757.09  4984.7  755.51
  4992.1  751.05  4995.9  749.74  4996.1  749.24  4999.6  749.24  4999.9  749.74
  5009.0  750.23  5019.0  751.86  5029.0  755.46  5049.0  757.39  5059.0  757.71
  5070.2  758.78  5089.0  760.94  5099.0  761.48  5119.0  764.10  5141.5  764.62
#Mann=5,-1,0
  4777.4    0.05       0  4796.0    0.12       0  4995.9    0.07       0
  4999.9    0.12       0  5070.2    0.05       0
Bank Sta=4995.9,4999.9
Exp/Cntr=0.3,0.1

Type RM Length L Ch R = 1,2960,383,383,383
BEGIN DESCRIPTION:
MDE S 075 8.0
END DESCRIPTION:
XS GIS Cut Line= 3
      2299329.00      7143160.00      2299229.00      7142910.00
      2299229.00      7142859.96
#Sta/Elev= 30
  4734.8  767.42  4749.6  767.35  4767.1  765.96  4773.8  764.28  4779.2  763.64
  4798.1  758.65  4808.9  757.73  4833.1  756.46  4851.9  756.49  4857.3  756.22
  4864.0  754.98  4881.5  754.21  4886.9  755.01  4911.2  752.65  4917.9  753.02
  4940.8  755.79  4959.6  755.63  4965.0  754.69  4971.7  746.84  4980.5  743.82
  4980.8  743.32  4984.3  743.32  4984.5  743.82  4994.6  746.48  5001.4  749.18
  5006.6  749.18  5024.1  758.73  5034.1  762.07  5051.6  765.60  5054.1  765.60
#Mann=4,-1,0
  4734.8    0.05       0  4808.9    0.12       0  4980.5    0.07       0
  4984.5    0.12       0
Bank Sta=4980.5,4984.5
Exp/Cntr=0.3,0.1

Type RM Length L Ch R = 1,2577,349,349,349
BEGIN DESCRIPTION:
MDE S 075 7.0
END DESCRIPTION:
XS GIS Cut Line= 3
      2299529.00      7143110.02      2299529.00      7143060.00
      2299578.99      7142910.03
#Sta/Elev= 28
  4946.3  752.69  4948.8  752.69  4956.3  752.36  4966.3  751.37  4976.3  748.56
  4986.3  743.09  4991.8  739.18  4992.1  738.68  4995.6  738.68  4995.8  739.18
  4996.3  739.18  4999.0  739.18  5006.9  739.86  5017.4  745.84  5027.9  751.58
  5038.5  751.93  5049.0  751.66  5059.6  751.97  5070.1  752.31  5080.6  752.32
  5091.2  752.16  5101.7  752.39  5112.3  754.58  5122.8  758.35  5133.4  762.78
  5143.9  770.98  5151.8  775.47  5154.4  775.47
#Mann=3,-1,0
  4946.3    0.12       0  4991.8    0.07       0  4995.8    0.12       0
Bank Sta=4991.8,4995.8
Exp/Cntr=0.3,0.1

Type RM Length L Ch R = 1,2228,347,347,347
BEGIN DESCRIPTION:
MDE S 075 6.0
END DESCRIPTION:
XS GIS Cut Line= 3
      2299829.01      7143259.96      2299879.00      7143060.00
      2299879.00      7142910.02
#Sta/Elev= 30
  4793.5  761.68  4803.8  760.35  4816.7  759.84  4824.4  758.10  4834.7  753.98
  4852.7  750.97  4865.6  749.39  4886.2  748.71  4927.5  748.76  4948.1  746.18
  4958.4  745.84  4968.7  743.64  4976.4  740.76  4981.6  738.31  4987.3  733.53
  4987.6  733.03  4991.1  733.03  4991.3  733.53  4997.0  741.77  5002.1  741.77
  5019.6  748.23  5029.6  749.32  5039.6  749.38  5059.6  751.34  5069.6  751.76
  5099.6  756.01  5119.6  760.92  5129.6  764.40  5147.1  773.23  5149.6  773.23
#Mann=3,-1,0
  4793.5    0.12       0  4987.3    0.07       0  4991.3    0.12       0
Bank Sta=4987.3,4991.3
Exp/Cntr=0.3,0.1

Type RM Length L Ch R = 1,1881,332,332,332
BEGIN DESCRIPTION:
MDE S 075 5.0
END DESCRIPTION:
XS GIS Cut Line= 3
      2300179.00      7143259.97      2300179.00      7143210.00
      2300179.00      7143009.97
#Sta/Elev= 27
  4945.5  746.15  4948.0  746.15  4955.5  745.23  4966.7  742.03  4975.5  739.21
  4985.5  738.60  4993.0  736.15  4998.0  736.15  5003.5  732.20  5003.7  731.70
  5007.2  731.70  5007.5  732.20  5015.5  737.55  5025.5  742.04  5035.5  743.63
  5095.5  744.83  5105.5  745.46  5115.5  746.24  5125.5  746.83  5135.5  748.22
  5145.5  749.47  5155.5  751.49  5165.5  755.20  5175.5  758.79  5185.5  762.21
  5193.0  768.39  5195.5  768.39
#Mann=4,-1,0
  4945.5    0.05       0  4966.7    0.12       0  5003.5    0.07       0
  5007.5    0.12       0
Bank Sta=5003.5,5007.5
Exp/Cntr=0.3,0.1

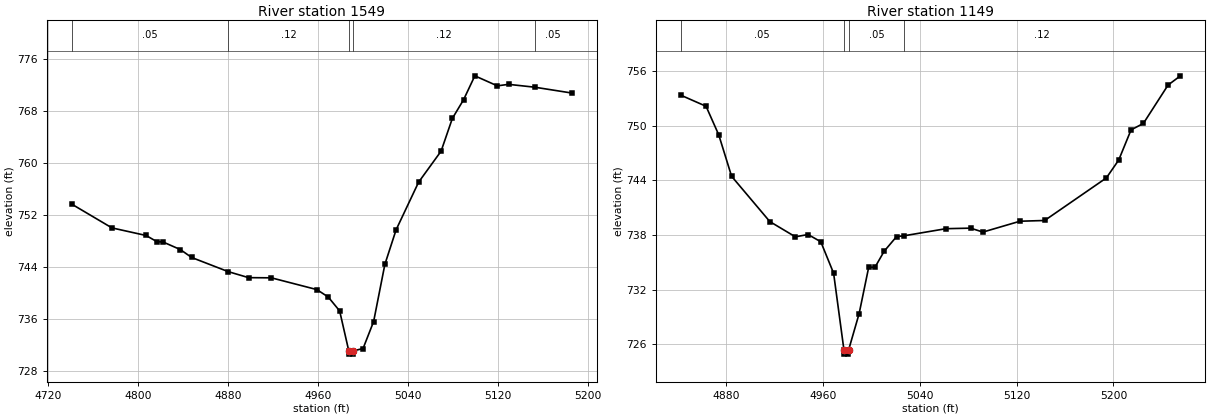
Type RM Length L Ch R = 1,1549,400,400,400
BEGIN DESCRIPTION:
Mapping XS c4bdc276
END DESCRIPTION:
XS GIS Cut Line= 3
      2300471.45      7143465.41      2300511.11      7143213.74
      2300510.44      7143024.02
#Sta/Elev= 30
  4741.2  753.65  4777.0  749.99  4807.4  748.82  4817.2  747.85  4822.2  747.84
  4837.8  746.66  4847.9  745.44  4880.3  743.27  4898.5  742.34  4918.8  742.31
  4959.3  740.50  4969.4  739.35  4979.5  737.22  4987.6  731.08  4987.9  730.58
  4991.4  730.58  4991.6  731.08  5000.3  731.44  5009.7  735.59  5019.7  744.38
  5029.7  749.70  5049.7  757.02  5069.7  761.79  5079.7  766.82  5089.7  769.70
  5099.7  773.37  5119.7  771.83  5129.7  772.06  5153.0  771.62  5185.7  770.73
#Mann=5,-1,0
  4741.2    0.05       0  4880.3    0.12       0  4987.6    0.07       0
  4991.6    0.12       0  5153.0    0.05       0
Bank Sta=4987.6,4991.6
Exp/Cntr=0.3,0.1

Type RM Length L Ch R = 1,1149,0,0,0
BEGIN DESCRIPTION:
MDE S 075 3.0
END DESCRIPTION:
XS GIS Cut Line= 3
      2300829.00      7143459.99      2300879.00      7143310.00
      2300828.99      7143059.96
#Sta/Elev= 30
  4842.3  753.35  4863.4  752.12  4873.9  748.98  4884.5  744.44  4916.1  739.47
  4937.2  737.80  4947.7  738.05  4958.2  737.26  4968.8  733.81  4977.3  725.43
  4977.6  724.93  4981.1  724.93  4981.3  725.43  4989.9  729.38  4997.8  734.46
  5003.0  734.46  5010.6  736.22  5020.8  737.82  5026.9  737.91  5061.6  738.69
  5082.0  738.75  5092.2  738.32  5122.8  739.51  5143.2  739.59  5194.2  744.26
  5204.4  746.22  5214.6  749.53  5224.8  750.24  5245.2  754.45  5255.4  755.46
#Mann=4,-1,0
  4842.3    0.05       0  4977.3   0.033       0  4981.3    0.05       0
  5026.9    0.12       0
Bank Sta=4977.3,4981.3
Exp/Cntr=0.3,0.1

Chan Stop Cuts=-1