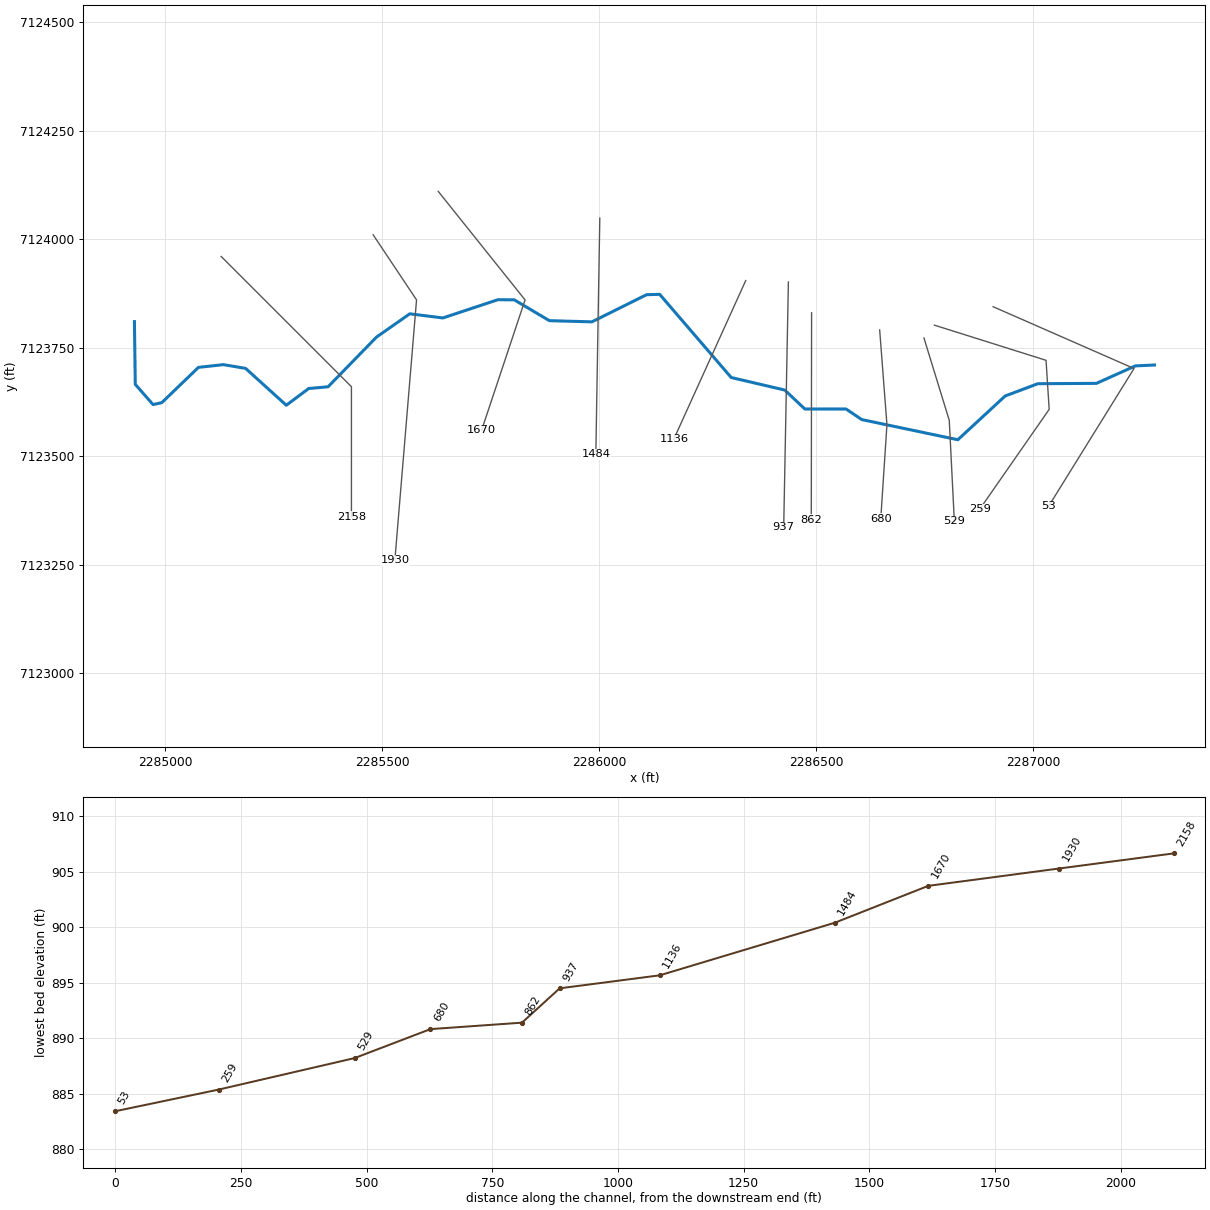
--- MDE S 086.prj (project) ---

Proj Title=MDE S 086 Base Level Engineering
Current Plan=p01
Default Exp/Contr=0.3,0.1
English Units
Geom File=g01
Flow File=f01
Plan File=p01
BEGIN DESCRIPTION:
MDE S 086
END DESCRIPTION:

--- MDE S 086.p01 (plan) ---

Plan Title=Multiple Run
Short Identifier=Multiple
Geom File=g01
Flow File=f01
Subcritical Flow
K Sum by GR= 0
Std Step Tol= 0.01
Critical Tol= 0.01
Num of Std Step Trials= 20
Max Error Tol= 0.3
Flow Tol Ratio= 0.001
Split Flow NTrial= 30
Split Flow Tol= 0.02
Split Flow Ratio= 0.02
Log Output Level= 0
Friction Slope Method= 1
Unsteady Friction Slope Method= 2
Unsteady Bridges Friction Slope Method= 1
Parabolic Critical Depth
Global Vel Dist=  1 , 1 , 1
Global Log Level= 0
CheckData=True
Encroach Param= -1, 0, 0, 0
BEGIN DESCRIPTION:
Multiple Run
END DESCRIPTION:

--- MDE S 086.f01 (steady flow) ---

Flow Title=Multiple
Number of Profiles=7
Profile Names=10-year,25-year,50-year,1pct_min,100-year,1pct_plu,500-year
River Rch & RM= MDE S 086,Reach-1,2158
     301     397     473     282     562    1121     791
Boundary for River Rch & Prof#=MDE S 086,Reach-1,1
Up Type=0
Dn Type=3
Dn Slope=0.008
Boundary for River Rch & Prof#=MDE S 086,Reach-1,2
Up Type=0
Dn Type=3
Dn Slope=0.008
Boundary for River Rch & Prof#=MDE S 086,Reach-1,3
Up Type=0
Dn Type=3
Dn Slope=0.008
Boundary for River Rch & Prof#=MDE S 086,Reach-1,4
Up Type=0
Dn Type=3
Dn Slope=0.008
Boundary for River Rch & Prof#=MDE S 086,Reach-1,5
Up Type=0
Dn Type=3
Dn Slope=0.008
Boundary for River Rch & Prof#=MDE S 086,Reach-1,6
Up Type=0
Dn Type=3
Dn Slope=0.008
Boundary for River Rch & Prof#=MDE S 086,Reach-1,7
Up Type=0
Dn Type=3
Dn Slope=0.008

--- MDE S 086.g01 (geometry) ---

Geom Title=Existing Conditions

River Reach=MDE S 086,Reach-1
Reach XY= 30
      2284929.00      7123810.00      2284931.01      7123665.40
      2284972.00      7123618.82      2284992.20      7123623.39
      2285076.57      7123704.57      2285134.04      7123710.87
      2285185.17      7123702.20      2285278.91      7123617.32
      2285330.57      7123655.87      2285375.15      7123659.83
      2285486.80      7123774.38      2285563.44      7123827.96
      2285639.84      7123818.45      2285766.30      7123860.43
      2285804.07      7123860.23      2285884.98      7123812.17
      2285983.02      7123809.46      2286109.04      7123872.00
      2286139.16      7123872.82      2286303.93      7123681.21
      2286427.36      7123652.31      2286473.64      7123608.61
      2286568.45      7123608.67      2286604.70      7123584.30
      2286826.09      7123537.82      2286935.13      7123638.63
      2287010.39      7123666.91      2287145.32      7123667.73
      2287235.27      7123708.01      2287279.00      7123710.00

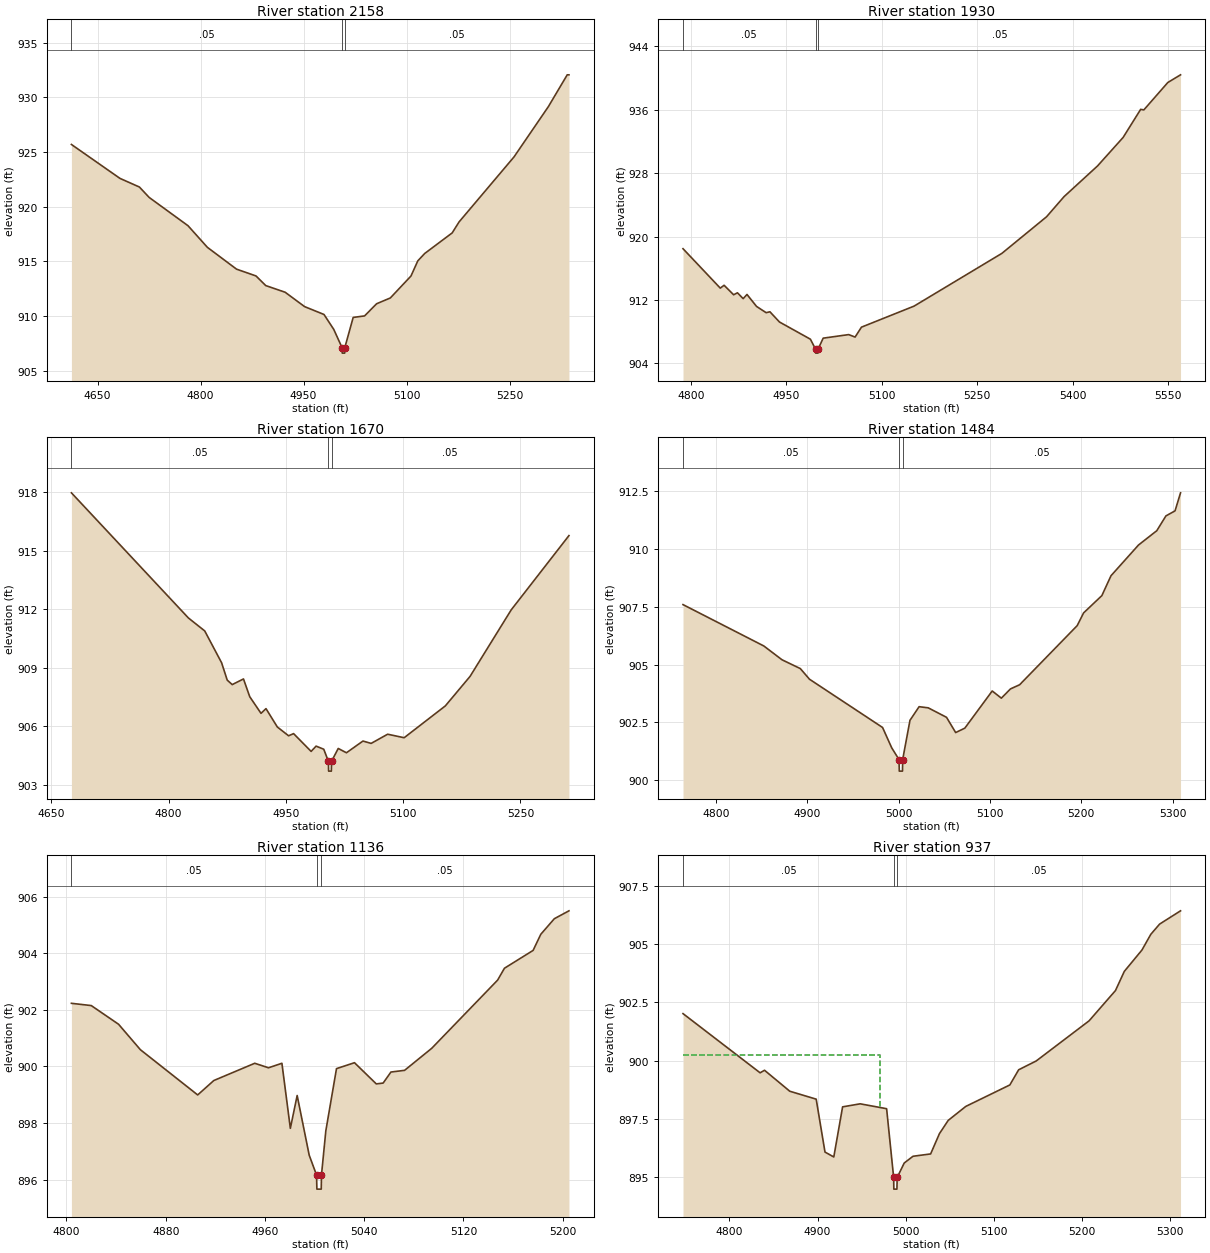
Type RM Length L Ch R = 1,2158,228,228,228
BEGIN DESCRIPTION:
MDE S 086 5.0
END DESCRIPTION:
XS GIS Cut Line= 3
      2285128.98      7123960.02      2285429.00      7123660.00
      2285429.00      7123359.99
#Sta/Elev= 30
  4612.0  925.69  4682.7  922.59  4711.0  921.80  4725.2  920.85  4781.7  918.27
  4810.0  916.29  4852.4  914.30  4880.7  913.68  4894.9  912.80  4923.2  912.19
  4951.4  910.88  4979.7  910.16  4993.9  908.80  5006.0  907.13  5006.3  906.63
  5009.8  906.63  5010.0  907.13  5022.2  909.89  5038.8  910.03  5056.3  911.14
  5076.3  911.67  5106.3  913.67  5116.3  915.06  5126.3  915.73  5166.3  917.61
  5176.3  918.61  5256.3  924.55  5306.3  929.14  5333.8  932.05  5336.3  932.05
#Mann=3,-1,0
  4612.0    0.05       0  5006.0   0.033       0  5010.0    0.05       0
Bank Sta=5006,5010
Exp/Cntr=0.3,0.1

Type RM Length L Ch R = 1,1930,260,260,260
BEGIN DESCRIPTION:
MDE S 086 4.0
END DESCRIPTION:
XS GIS Cut Line= 3
      2285479.02      7124009.97      2285579.00      7123860.00
      2285529.00      7123260.03
#Sta/Elev= 30
  4787.5  918.46  4846.1  913.48  4852.1  913.84  4867.1  912.64  4873.1  912.89
  4882.1  912.15  4888.1  912.68  4903.1  911.17  4918.2  910.38  4924.2  910.49
  4939.2  909.20  4987.8  907.03  4995.9  905.77  4996.1  905.27  4999.6  905.27
  4999.9  905.77  5007.9  907.16  5048.0  907.61  5058.1  907.30  5068.1  908.55
  5150.9  911.21  5288.9  917.87  5359.1  922.49  5386.7  925.04  5439.4  928.92
  5479.5  932.51  5507.1  936.06  5512.1  935.99  5549.8  939.45  5569.8  940.42
#Mann=3,-1,0
  4787.5    0.05       0  4995.9   0.033       0  4999.9    0.05       0
Bank Sta=4995.9,4999.9
Exp/Cntr=0.3,0.1

Type RM Length L Ch R = 1,1670,186,186,186
BEGIN DESCRIPTION:
MDE S 086 3.0
END DESCRIPTION:
XS GIS Cut Line= 3
      2285628.99      7124110.02      2285829.00      7123860.00
      2285729.00      7123560.01
#Sta/Elev= 30
  4675.7  917.96  4825.4  911.55  4846.2  910.89  4867.8  909.26  4875.0  908.37
  4881.4  908.14  4895.8  908.43  4903.8  907.52  4918.2  906.67  4924.6  906.91
  4939.1  905.97  4953.5  905.52  4959.9  905.63  4982.3  904.72  4988.7  904.99
  4998.5  904.83  5004.4  904.21  5004.7  903.71  5008.2  903.71  5008.4  904.21
  5017.0  904.87  5027.5  904.65  5048.6  905.25  5059.1  905.13  5080.2  905.60
  5101.3  905.42  5154.0  907.05  5185.6  908.56  5238.3  911.97  5312.1  915.77
#Mann=3,-1,0
  4675.7    0.05       0  5004.4   0.033       0  5008.4    0.05       0
Bank Sta=5004.4,5008.4
Exp/Cntr=0.3,0.1

Type RM Length L Ch R = 1,1484,348,348,348
BEGIN DESCRIPTION:
Mapping XS ffe7ec44
END DESCRIPTION:
XS GIS Cut Line= 2
      2286001.21      7124048.38      2285992.06      7123503.96
#Sta/Elev= 30
  4764.1  907.60  4852.5  905.81  4872.5  905.21  4892.5  904.83  4902.5  904.37
  4982.5  902.28  4992.5  901.40  5000.5  900.89  5000.8  900.39  5004.3  900.39
  5004.5  900.89  5012.5  902.59  5022.5  903.18  5032.5  903.13  5052.5  902.72
  5062.5  902.06  5072.5  902.25  5102.5  903.86  5112.5  903.55  5122.5  903.95
  5132.5  904.13  5195.5  906.69  5202.5  907.24  5222.5  907.99  5232.5  908.85
  5262.6  910.18  5282.6  910.80  5292.6  911.44  5302.6  911.66  5308.6  912.44
#Mann=3,-1,0
  4764.1    0.05       0  5000.5   0.033       0  5004.5    0.05       0
Bank Sta=5000.5,5004.5
Exp/Cntr=0.3,0.1

Type RM Length L Ch R = 1,1136,199,199,199
BEGIN DESCRIPTION:
Mapping XS 751221d6
END DESCRIPTION:
XS GIS Cut Line= 2
      2286337.43      7123904.60      2286171.80      7123539.29
#Sta/Elev= 30
  4804.0  902.23  4820.0  902.15  4842.0  901.49  4859.6  900.59  4905.8  898.99
  4918.8  899.50  4951.8  900.11  4962.9  899.95  4973.7  900.11  4980.5  897.81
  4986.0  898.97  4995.7  896.86  5001.6  896.16  5001.9  895.66  5005.4  895.66
  5005.6  896.16  5009.1  897.72  5017.7  899.92  5032.2  900.13  5049.8  899.38
  5055.3  899.41  5061.6  899.80  5072.6  899.86  5094.5  900.64  5147.6  903.05
  5153.1  903.47  5176.2  904.10  5182.4  904.67  5193.3  905.22  5205.1  905.50
#Mann=3,-1,0
  4804.0    0.05       0  5001.6   0.033       0  5005.6    0.05       0
Bank Sta=5001.6,5005.6
Exp/Cntr=0.3,0.1

Type RM Length L Ch R = 1,937,75,75,75
BEGIN DESCRIPTION:
Mapping XS a7138d06
END DESCRIPTION:
XS GIS Cut Line= 2
      2286435.70      7123901.26      2286424.91      7123336.16
#Sta/Elev= 30
  4747.2  902.02  4834.8  899.48  4839.8  899.59  4868.5  898.69  4898.5  898.35
  4908.5  896.08  4918.5  895.87  4928.5  898.02  4948.5  898.15  4978.5  897.94
  4986.5  894.99  4986.7  894.49  4990.2  894.49  4990.5  894.99  4998.5  895.61
  5008.5  895.90  5028.5  896.00  5038.5  896.87  5048.5  897.44  5068.5  898.04
  5118.5  898.96  5128.5  899.61  5148.5  899.99  5208.5  901.71  5238.5  903.01
  5248.5  903.83  5268.6  904.75  5278.6  905.42  5288.6  905.86  5312.4  906.43
#Mann=3,-1,0
  4747.2    0.05       0  4986.5   0.033       0  4990.5    0.05       0
#XS Ineff=2,0
    0.00 4970.90  900.24               0
Permanent Ineff=
       F       F
Bank Sta=4986.5,4990.5
Exp/Cntr=0.3,0.1

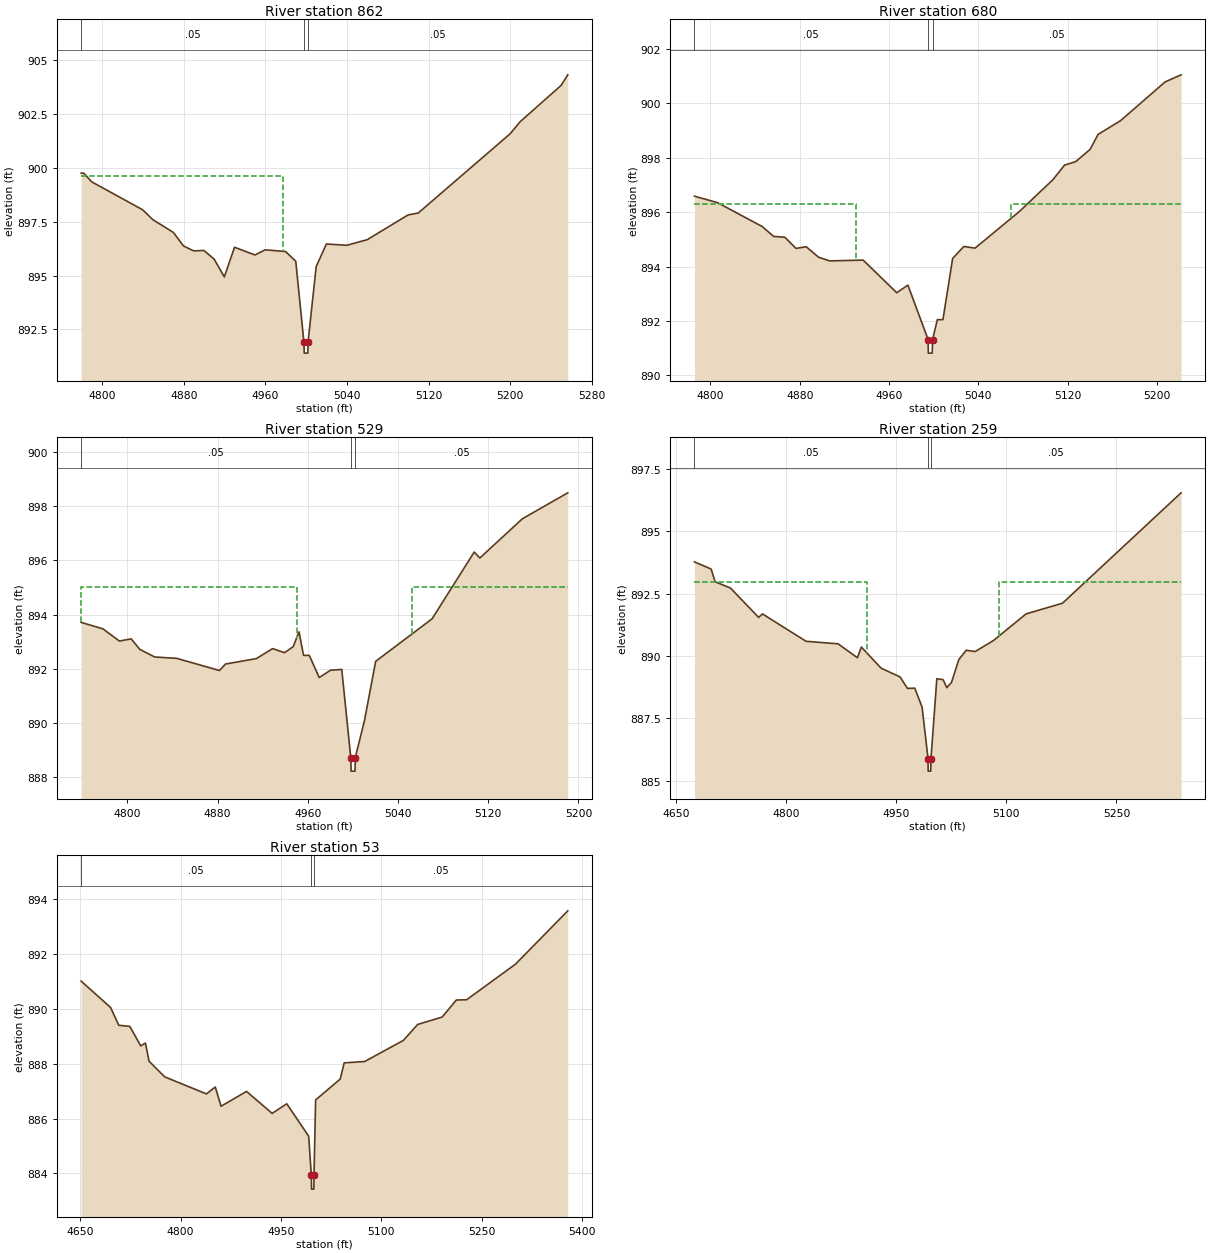
Type RM Length L Ch R = 1,862,182,182,182
BEGIN DESCRIPTION:
Mapping XS c9be21ae
END DESCRIPTION:
XS GIS Cut Line= 2
      2286489.16      7123830.31      2286488.44      7123353.51
#Sta/Elev= 30
  4779.5  899.76  4782.2  899.76  4789.8  899.36  4839.8  898.06  4849.8  897.60
  4869.8  897.01  4879.8  896.38  4889.8  896.15  4899.8  896.17  4909.8  895.77
  4919.8  894.94  4929.8  896.32  4949.8  895.96  4959.8  896.20  4979.8  896.12
  4989.8  895.67  4997.8  891.90  4998.1  891.40  5001.6  891.40  5001.8  891.90
  5009.8  895.42  5019.8  896.47  5039.8  896.41  5059.8  896.67  5099.8  897.82
  5109.8  897.91  5199.8  901.59  5209.8  902.16  5249.8  903.84  5256.3  904.33
#Mann=3,-1,0
  4779.5    0.05       0  4997.8   0.033       0  5001.8    0.05       0
#XS Ineff=2,0
    0.00 4977.20  899.65               0
Permanent Ineff=
       F       F
Bank Sta=4997.8,5001.8
Exp/Cntr=0.3,0.1

Type RM Length L Ch R = 1,680,151,151,151
BEGIN DESCRIPTION:
Mapping XS b8d1dcd0
END DESCRIPTION:
XS GIS Cut Line= 3
      2286646.03      7123790.76      2286662.75      7123572.31
      2286648.52      7123355.76
#Sta/Elev= 30
  4785.6  896.59  4806.4  896.35  4846.5  895.47  4856.6  895.11  4866.6  895.08
  4876.6  894.67  4885.8  894.73  4896.7  894.35  4906.7  894.21  4936.8  894.24
  4966.9  893.04  4976.9  893.32  4995.0  891.32  4995.2  890.82  4998.7  890.82
  4999.0  891.32  5003.3  892.05  5008.3  892.05  5017.0  894.30  5027.0  894.74
  5037.1  894.68  5077.2  896.04  5107.2  897.21  5117.2  897.73  5127.3  897.86
  5140.2  898.31  5147.3  898.86  5167.3  899.36  5207.4  900.79  5221.7  901.05
#Mann=3,-1,0
  4785.6    0.05       0  4995.0   0.033       0  4999.0    0.05       0
#XS Ineff=2,0
    0.00 4930.70  896.32 5069.30    0.00  896.32
Permanent Ineff=
       F       F
Bank Sta=4995,4999
Exp/Cntr=0.3,0.1

Type RM Length L Ch R = 1,529,270,270,270
BEGIN DESCRIPTION:
Mapping XS 5a9d377e
END DESCRIPTION:
XS GIS Cut Line= 3
      2286747.98      7123772.42      2286806.34      7123582.65
      2286818.06      7123349.79
#Sta/Elev= 30
  4758.9  893.71  4778.3  893.47  4792.8  893.02  4803.3  893.10  4811.0  892.71
  4824.2  892.43  4843.7  892.38  4881.6  891.93  4887.0  892.17  4914.3  892.37
  4928.8  892.74  4939.3  892.59  4947.0  892.81  4952.2  893.36  4956.2  892.49
  4961.3  892.49  4970.1  891.67  4980.1  891.94  4990.1  891.97  4998.1  888.71
  4998.4  888.21  5001.9  888.21  5002.1  888.71  5010.2  890.07  5020.2  892.27
  5070.2  893.84  5107.6  896.31  5112.6  896.09  5150.3  897.54  5190.6  898.50
#Mann=3,-1,0
  4758.9    0.05       0  4998.1   0.033       0  5002.1    0.05       0
#XS Ineff=2,0
    0.00 4950.00  895.01 5052.50    0.00  895.01
Permanent Ineff=
       F       F
Bank Sta=4998.1,5002.1
Exp/Cntr=0.3,0.1

Type RM Length L Ch R = 1,259,206,206,206
BEGIN DESCRIPTION:
Mapping XS f2d31b58
END DESCRIPTION:
XS GIS Cut Line= 4
      2286772.14      7123801.82      2287029.29      7123720.86
      2287036.57      7123607.80      2286876.17      7123377.31
#Sta/Elev= 30
  4674.5  893.78  4697.3  893.49  4702.7  892.98  4723.6  892.73  4762.1  891.55
  4767.3  891.69  4826.8  890.59  4870.4  890.49  4896.8  889.93  4902.1  890.36
  4929.2  889.51  4955.0  889.16  4965.0  888.70  4975.0  888.71  4985.0  887.95
  4993.1  885.88  4993.3  885.38  4996.8  885.38  4997.1  885.88  5005.1  889.09
  5013.7  889.05  5018.7  888.73  5025.1  888.94  5035.1  889.86  5045.2  890.23
  5057.4  890.18  5082.3  890.62  5126.8  891.69  5176.5  892.12  5338.2  896.55
#Mann=3,-1,0
  4674.5    0.05       0  4993.1   0.033       0  4997.1    0.05       0
#XS Ineff=2,0
    0.00 4910.00  892.97 5090.00    0.00  892.97
Permanent Ineff=
       F       F
Bank Sta=4993.1,4997.1
Exp/Cntr=0.3,0.1

Type RM Length L Ch R = 1,53,0,0,0
BEGIN DESCRIPTION:
MDE S 086 1.0
END DESCRIPTION:
XS GIS Cut Line= 3
      2286907.44      7123844.31      2287232.02      7123701.92
      2287035.35      7123384.79
#Sta/Elev= 30
  4651.4  891.01  4695.4  890.05  4707.7  889.40  4724.2  889.36  4740.5  888.65
  4747.6  888.75  4753.0  888.09  4776.4  887.52  4838.7  886.90  4852.0  887.15
  4860.6  886.45  4898.7  886.99  4937.0  886.19  4958.9  886.54  4991.6  885.36
  4995.6  883.93  4995.9  883.43  4999.4  883.43  4999.6  883.93  5002.0  886.68
  5038.8  887.44  5044.7  888.03  5075.4  888.08  5133.3  888.85  5154.5  889.43
  5191.2  889.70  5212.4  890.32  5227.8  890.33  5301.0  891.63  5379.0  893.57
#Mann=3,-1,0
  4651.4    0.05       0  4995.6   0.033       0  4999.6    0.05       0
Bank Sta=4995.6,4999.6
Exp/Cntr=0.3,0.1

Chan Stop Cuts=-1