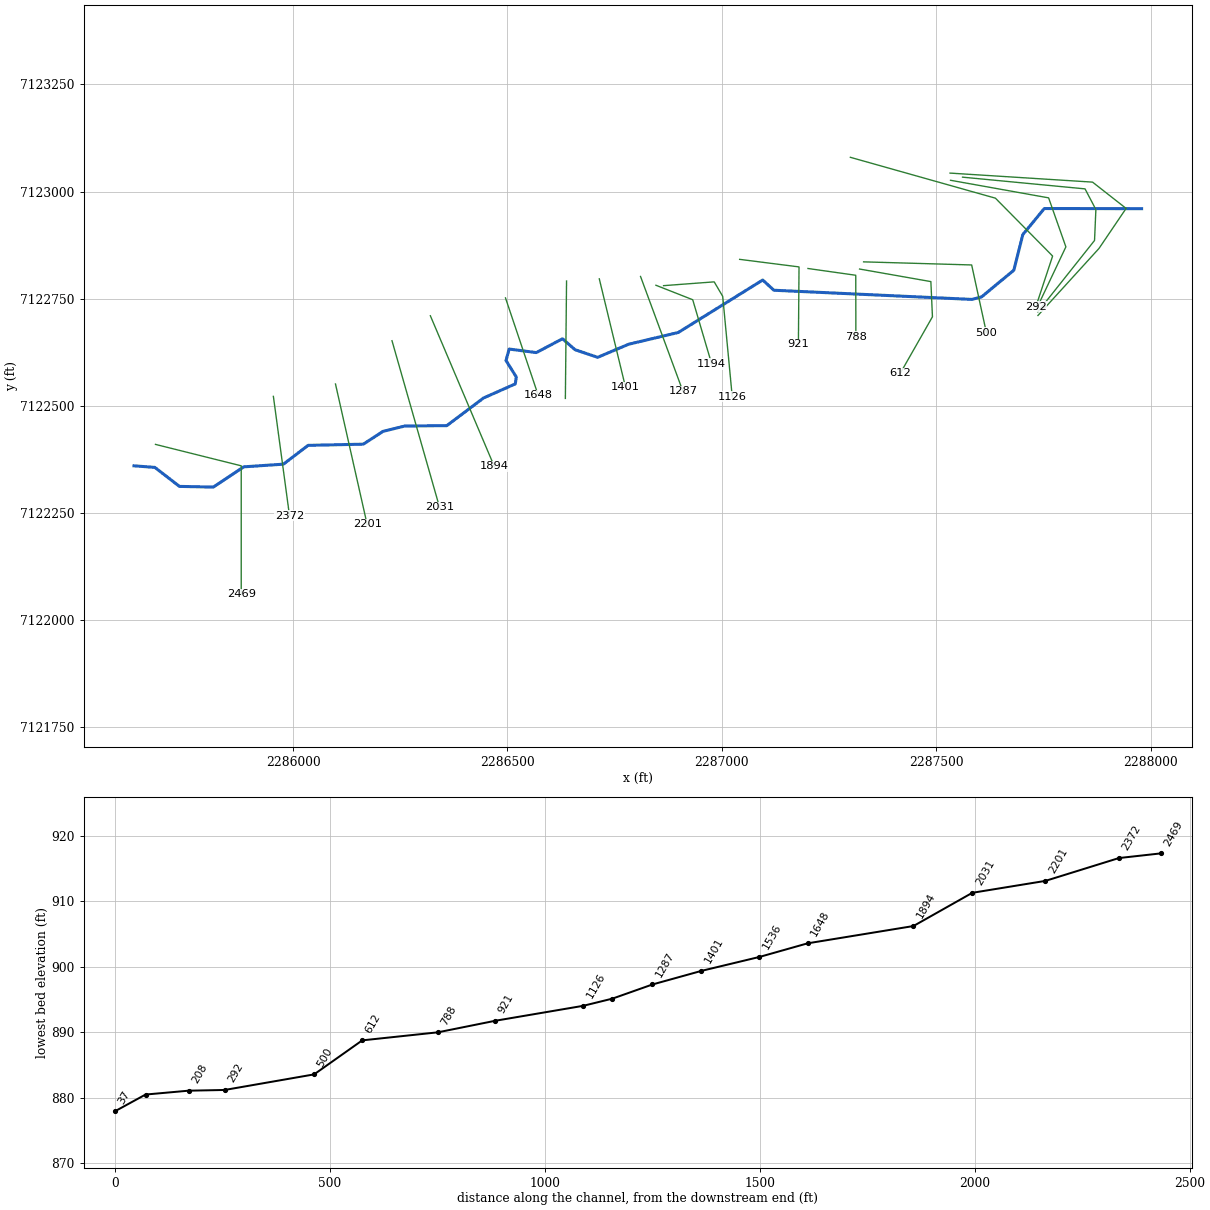
--- MDE S 087.prj (project) ---

Proj Title=MDE S 087 Base Level Engineering
Current Plan=p01
Default Exp/Contr=0.3,0.1
English Units
Geom File=g01
Flow File=f01
Plan File=p01
BEGIN DESCRIPTION:
MDE S 087
END DESCRIPTION:

--- MDE S 087.p01 (plan) ---

Plan Title=Multiple Run
Short Identifier=Multiple
Geom File=g01
Flow File=f01
Subcritical Flow
K Sum by GR= 0
Std Step Tol= 0.01
Critical Tol= 0.01
Num of Std Step Trials= 20
Max Error Tol= 0.3
Flow Tol Ratio= 0.001
Split Flow NTrial= 30
Split Flow Tol= 0.02
Split Flow Ratio= 0.02
Log Output Level= 0
Friction Slope Method= 1
Unsteady Friction Slope Method= 2
Unsteady Bridges Friction Slope Method= 1
Parabolic Critical Depth
Global Vel Dist=  1 , 1 , 1
Global Log Level= 0
CheckData=True
Encroach Param= -1, 0, 0, 0
BEGIN DESCRIPTION:
Multiple Run
END DESCRIPTION:

--- MDE S 087.f01 (steady flow) ---

Flow Title=Multiple
Number of Profiles=7
Profile Names=10-year,25-year,50-year,1pct_min,100-year,1pct_plu,500-year
River Rch & RM= MDE S 087,Reach-1,2469
     146     183     210     121     242     483     319
Boundary for River Rch & Prof#=MDE S 087,Reach-1,1
Up Type=0
Dn Type=3
Dn Slope=0.01
Boundary for River Rch & Prof#=MDE S 087,Reach-1,2
Up Type=0
Dn Type=3
Dn Slope=0.01
Boundary for River Rch & Prof#=MDE S 087,Reach-1,3
Up Type=0
Dn Type=3
Dn Slope=0.01
Boundary for River Rch & Prof#=MDE S 087,Reach-1,4
Up Type=0
Dn Type=3
Dn Slope=0.01
Boundary for River Rch & Prof#=MDE S 087,Reach-1,5
Up Type=0
Dn Type=3
Dn Slope=0.01
Boundary for River Rch & Prof#=MDE S 087,Reach-1,6
Up Type=0
Dn Type=3
Dn Slope=0.01
Boundary for River Rch & Prof#=MDE S 087,Reach-1,7
Up Type=0
Dn Type=3
Dn Slope=0.01

--- MDE S 087.g01 (geometry) ---

Geom Title=Existing Conditions

River Reach=MDE S 087,Reach-1
Reach XY= 30
      2285629.00      7122360.00      2285677.49      7122356.35
      2285734.92      7122312.02      2285813.73      7122310.38
      2285884.97      7122357.64      2285977.40      7122363.86
      2286034.94      7122407.73      2286163.78      7122410.54
      2286209.58      7122440.36      2286260.45      7122452.87
      2286358.48      7122453.80      2286444.32      7122518.33
      2286518.11      7122551.12      2286520.58      7122567.18
      2286496.61      7122605.68      2286503.83      7122632.47
      2286567.18      7122624.19      2286628.25      7122656.41
      2286657.71      7122630.88      2286710.29      7122613.14
      2286782.61      7122643.69      2286898.39      7122671.11
      2287095.27      7122793.52      2287121.27      7122769.65
      2287583.25      7122748.26      2287606.03      7122754.28
      2287681.03      7122816.47      2287701.92      7122899.51
      2287752.06      7122960.25      2287979.00      7122960.00

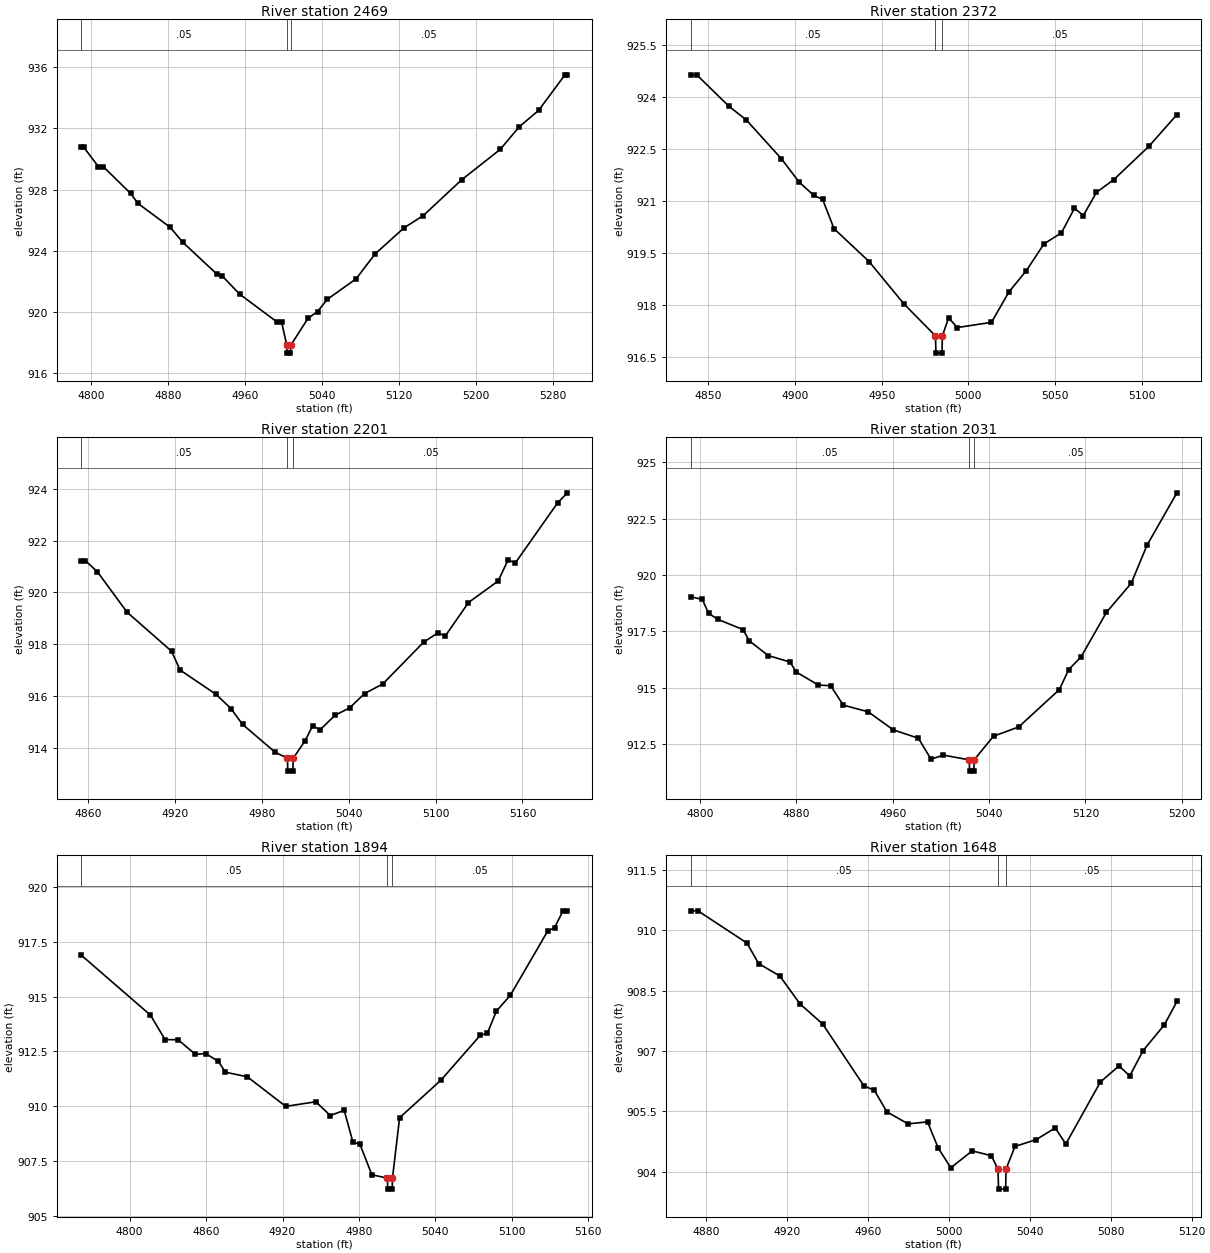
Type RM Length L Ch R = 1,2469,97,97,97
BEGIN DESCRIPTION:
MDE S 087 6.0
END DESCRIPTION:
XS GIS Cut Line= 3
      2285679.01      7122410.00      2285879.00      7122360.00
      2285879.00      7122060.04
#Sta/Elev= 30
  4789.2  930.78  4791.8  930.78  4807.2  929.50  4812.4  929.49  4840.7  927.75
  4848.5  927.09  4882.0  925.53  4894.8  924.57  4930.9  922.45  4936.1  922.35
  4954.1  921.17  4992.8  919.36  4997.8  919.36  5003.3  917.81  5003.6  917.31
  5007.1  917.31  5007.3  917.81  5025.3  919.58  5035.3  920.03  5045.3  920.82
  5075.3  922.16  5095.3  923.80  5125.3  925.50  5145.3  926.30  5185.3  928.64
  5225.3  930.62  5245.3  932.11  5265.3  933.17  5292.8  935.50  5295.3  935.50
#Mann=3,-1,0
  4789.2    0.05       0  5003.3   0.033       0  5007.3    0.05       0
Bank Sta=5003.3,5007.3
Exp/Cntr=0.3,0.1

Type RM Length L Ch R = 1,2372,171,171,171
BEGIN DESCRIPTION:
Mapping XS 542a25dc
END DESCRIPTION:
XS GIS Cut Line= 2
      2285954.00      7122521.95      2285991.57      7122243.97
#Sta/Elev= 28
  4839.8  924.65  4843.3  924.65  4861.9  923.74  4872.0  923.34  4892.2  922.22
  4902.3  921.55  4910.9  921.16  4915.9  921.05  4922.5  920.20  4942.7  919.25
  4962.9  918.02  4981.0  917.10  4981.3  916.60  4984.8  916.60  4985.0  917.10
  4988.6  917.62  4993.6  917.34  5013.3  917.49  5023.4  918.37  5033.5  918.99
  5043.6  919.76  5053.7  920.08  5061.2  920.79  5066.3  920.58  5073.9  921.25
  5083.9  921.62  5104.1  922.58  5120.3  923.50
#Mann=3,-1,0
  4839.8    0.05       0  4981.0   0.033       0  4985.0    0.05       0
Bank Sta=4981,4985
Exp/Cntr=0.3,0.1

Type RM Length L Ch R = 1,2201,170,170,170
BEGIN DESCRIPTION:
Mapping XS 3a2b3914
END DESCRIPTION:
XS GIS Cut Line= 2
      2286098.83      7122550.92      2286172.66      7122223.34
#Sta/Elev= 30
  4855.2  921.22  4858.2  921.22  4866.4  920.80  4886.9  919.24  4917.7  917.73
  4923.5  917.01  4948.4  916.07  4958.7  915.52  4966.7  914.91  4989.4  913.83
  4997.7  913.61  4997.9  913.11  5001.4  913.11  5001.7  913.61  5009.9  914.28
  5015.1  914.86  5020.2  914.70  5030.4  915.26  5040.7  915.55  5050.9  916.10
  5063.5  916.47  5091.9  918.09  5101.6  918.44  5106.7  918.32  5122.7  919.61
  5143.2  920.44  5150.0  921.25  5155.1  921.14  5184.2  923.45  5191.0  923.84
#Mann=3,-1,0
  4855.2    0.05       0  4997.7   0.033       0  5001.7    0.05       0
Bank Sta=4997.7,5001.7
Exp/Cntr=0.3,0.1

Type RM Length L Ch R = 1,2031,137,137,137
BEGIN DESCRIPTION:
Mapping XS 17d9b467
END DESCRIPTION:
XS GIS Cut Line= 2
      2286230.64      7122651.88      2286341.48      7122263.59
#Sta/Elev= 30
  4792.2  919.03  4801.9  918.91  4807.1  918.29  4815.0  918.02  4835.7  917.57
  4840.9  917.07  4856.6  916.42  4874.7  916.13  4879.9  915.69  4898.2  915.11
  4908.5  915.08  4918.9  914.22  4939.7  913.92  4960.5  913.12  4981.3  912.75
  4991.8  911.82  5002.1  912.00  5023.6  911.79  5023.8  911.29  5027.3  911.29
  5027.6  911.79  5043.7  912.84  5064.6  913.25  5098.4  914.91  5106.1  915.79
  5116.5  916.37  5137.4  918.33  5158.1  919.63  5171.2  921.32  5196.0  923.64
#Mann=3,-1,0
  4792.2    0.05       0  5023.6   0.033       0  5027.6    0.05       0
Bank Sta=5023.6,5027.6
Exp/Cntr=0.3,0.1

Type RM Length L Ch R = 1,1894,246,246,246
BEGIN DESCRIPTION:
Mapping XS 88916cc8
END DESCRIPTION:
XS GIS Cut Line= 2
      2286320.13      7122710.11      2286469.19      7122358.72
#Sta/Elev= 30
  4761.9  916.90  4816.3  914.16  4827.8  913.04  4838.1  913.03  4851.5  912.37
  4859.8  912.40  4869.7  912.04  4875.2  911.55  4892.4  911.34  4922.5  909.99
  4946.2  910.20  4957.5  909.57  4968.4  909.81  4975.3  908.35  4980.7  908.27
  4990.1  906.87  5002.3  906.71  5002.6  906.21  5006.1  906.21  5006.3  906.71
  5011.9  909.47  5044.4  911.19  5075.3  913.24  5080.8  913.33  5087.9  914.34
  5098.8  915.06  5128.1  917.99  5133.5  918.15  5140.2  918.92  5143.6  918.92
#Mann=3,-1,0
  4761.9    0.05       0  5002.3   0.033       0  5006.3    0.05       0
Bank Sta=5002.3,5006.3
Exp/Cntr=0.3,0.1

Type RM Length L Ch R = 1,1648,112,112,112
BEGIN DESCRIPTION:
Mapping XS 3b0c26f9
END DESCRIPTION:
XS GIS Cut Line= 2
      2286495.32      7122751.81      2286571.86      7122524.13
#Sta/Elev= 30
  4872.5  910.48  4876.1  910.48  4900.3  909.68  4906.1  909.17  4916.6  908.86
  4926.5  908.17  4937.7  907.67  4958.0  906.14  4963.3  906.02  4969.4  905.49
  4979.9  905.19  4989.5  905.24  4994.8  904.59  5001.0  904.10  5011.6  904.52
  5021.0  904.40  5024.3  904.07  5024.6  903.57  5028.1  903.57  5028.3  904.07
  5032.7  904.63  5043.2  904.80  5052.6  905.09  5057.8  904.69  5074.9  906.23
  5084.1  906.63  5089.4  906.38  5096.0  907.01  5106.5  907.65  5112.7  908.23
#Mann=3,-1,0
  4872.5    0.05       0  5024.3   0.033       0  5028.3    0.05       0
Bank Sta=5024.3,5028.3
Exp/Cntr=0.3,0.1

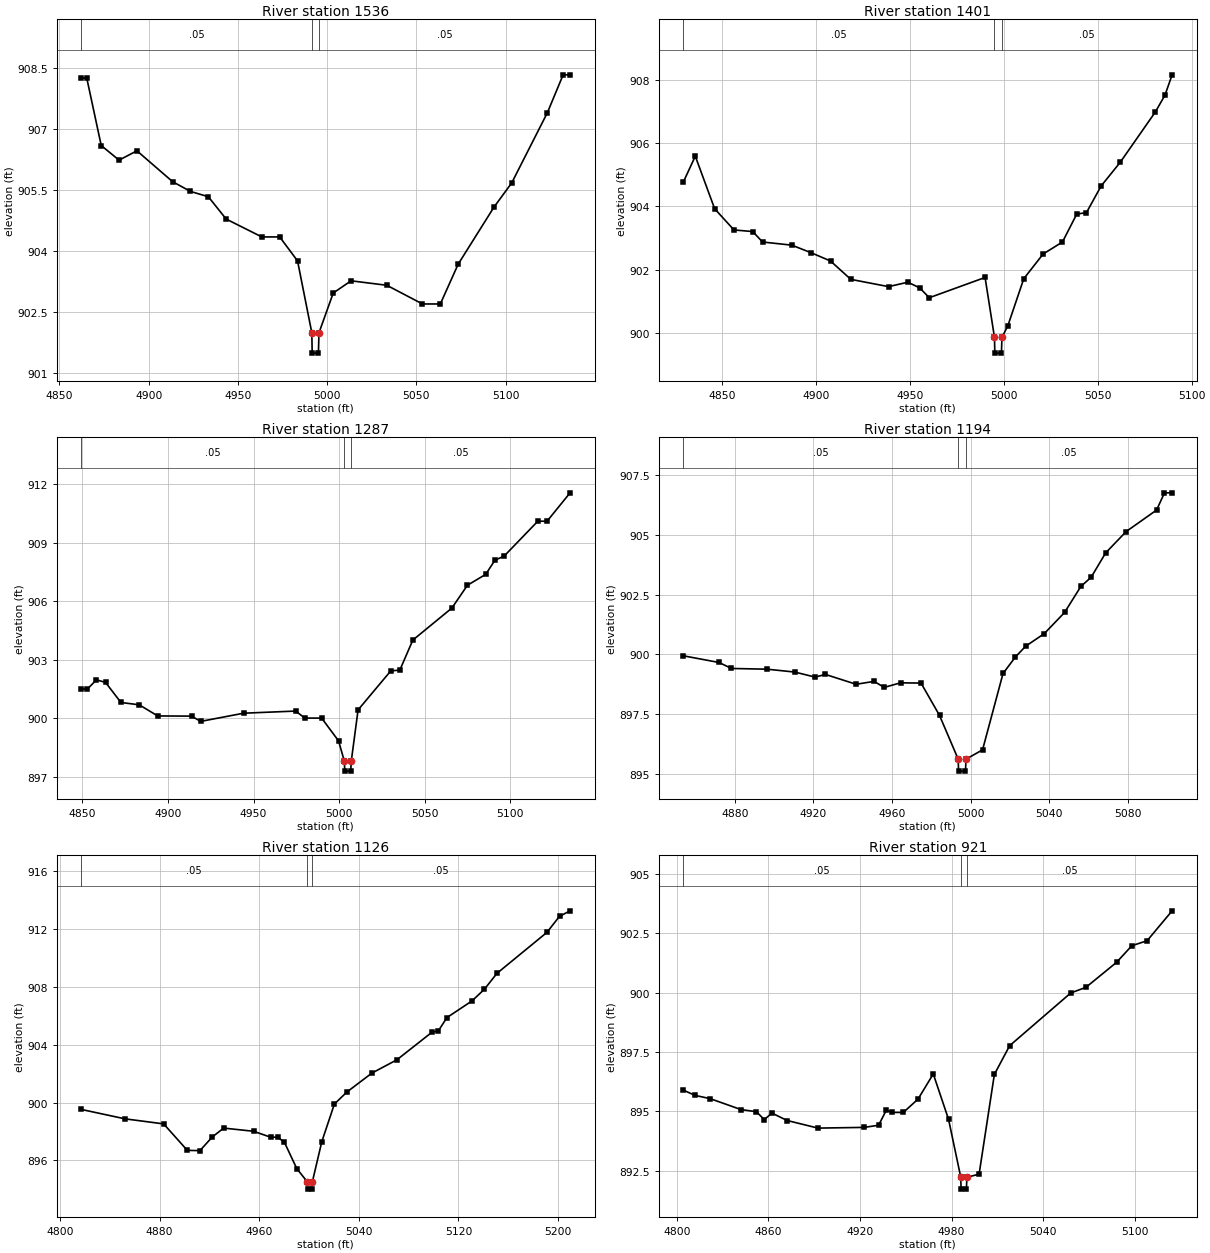
Type RM Length L Ch R = 1,1536,135,135,135
BEGIN DESCRIPTION:
Mapping XS 2eb29308
END DESCRIPTION:
XS GIS Cut Line= 2
      2286637.76      7122791.16      2286635.01      7122517.27
#Sta/Elev= 27
  4862.2  908.26  4865.3  908.26  4873.4  906.60  4883.4  906.24  4893.4  906.47
  4913.4  905.71  4923.4  905.47  4933.4  905.34  4943.4  904.79  4963.4  904.35
  4973.4  904.35  4983.4  903.76  4991.4  901.99  4991.6  901.49  4995.1  901.49
  4995.4  901.99  5003.4  902.97  5013.4  903.27  5033.4  903.16  5053.4  902.70
  5063.4  902.70  5073.4  903.68  5093.4  905.08  5103.4  905.68  5123.4  907.41
  5132.2  908.34  5136.1  908.34
#Mann=3,-1,0
  4862.2    0.05       0  4991.4   0.033       0  4995.4    0.05       0
Bank Sta=4991.4,4995.4
Exp/Cntr=0.3,0.1

Type RM Length L Ch R = 1,1401,114,114,114
BEGIN DESCRIPTION:
Mapping XS 1b87dfcd
END DESCRIPTION:
XS GIS Cut Line= 2
      2286714.13      7122796.21      2286775.35      7122543.22
#Sta/Elev= 30
  4829.3  904.76  4835.7  905.58  4846.0  903.92  4856.3  903.25  4866.3  903.20
  4871.5  902.87  4887.1  902.77  4897.4  902.53  4907.7  902.27  4918.5  901.69
  4938.6  901.46  4948.9  901.60  4955.2  901.42  4960.3  901.11  4990.0  901.75
  4995.0  899.86  4995.2  899.36  4998.7  899.36  4999.0  899.86  5002.1  900.22
  5010.6  901.71  5020.9  902.49  5031.2  902.87  5038.8  903.75  5044.0  903.80
  5051.8  904.64  5062.0  905.39  5080.7  906.98  5085.8  907.51  5089.6  908.15
#Mann=3,-1,0
  4829.3    0.05       0  4995.0   0.033       0  4999.0    0.05       0
Bank Sta=4995,4999
Exp/Cntr=0.3,0.1

Type RM Length L Ch R = 1,1287,93,93,93
BEGIN DESCRIPTION:
Mapping XS 35ff173b
END DESCRIPTION:
XS GIS Cut Line= 2
      2286810.34      7122801.79      2286909.20      7122533.74
#Sta/Elev= 30
  4849.3  901.49  4852.9  901.49  4858.2  901.96  4863.5  901.83  4872.5  900.80
  4883.2  900.68  4894.0  900.11  4913.8  900.10  4919.1  899.83  4944.2  900.25
  4974.6  900.36  4980.0  900.00  4989.8  900.00  4999.7  898.83  5003.1  897.78
  5003.3  897.28  5006.8  897.28  5007.1  897.78  5011.1  900.42  5030.2  902.42
  5035.5  902.46  5043.1  904.00  5065.9  905.64  5075.0  906.81  5085.7  907.37
  5091.1  908.10  5096.4  908.30  5116.2  910.10  5121.5  910.09  5135.0  911.55
#Mann=3,-1,0
  4849.3    0.05       0  5003.1   0.033       0  5007.1    0.05       0
Bank Sta=5003.1,5007.1
Exp/Cntr=0.3,0.1

Type RM Length L Ch R = 1,1194,68,68,68
BEGIN DESCRIPTION:
Mapping XS 3b0a24c6
END DESCRIPTION:
XS GIS Cut Line= 3
      2286846.19      7122781.30      2286932.04      7122747.52
      2286976.28      7122597.56
#Sta/Elev= 30
  4853.8  899.94  4872.0  899.66  4878.3  899.41  4896.4  899.38  4910.5  899.26
  4920.8  899.05  4926.1  899.16  4941.7  898.75  4950.8  898.87  4956.0  898.62
  4964.3  898.81  4974.7  898.80  4984.1  897.45  4993.6  895.62  4993.8  895.12
  4997.3  895.12  4997.6  895.62  5006.0  896.01  5016.4  899.20  5022.7  899.89
  5027.9  900.34  5037.3  900.86  5047.7  901.75  5056.0  902.84  5061.2  903.22
  5068.6  904.24  5079.0  905.13  5094.5  906.03  5098.5  906.75  5102.4  906.75
#Mann=3,-1,0
  4853.8    0.05       0  4993.6   0.033       0  4997.6    0.05       0
Bank Sta=4993.6,4997.6
Exp/Cntr=0.3,0.1

Type RM Length L Ch R = 1,1126,205,205,205
BEGIN DESCRIPTION:
Mapping XS 62c3d35d
END DESCRIPTION:
XS GIS Cut Line= 4
      2286864.00      7122780.35      2286982.13      7122789.21
      2287001.99      7122755.37      2287024.17      7122521.52
#Sta/Elev= 30
  4817.1  899.53  4852.2  898.88  4883.3  898.53  4902.3  896.70  4912.4  896.68
  4922.4  897.63  4931.5  898.24  4955.5  898.02  4969.2  897.61  4974.8  897.61
  4980.2  897.27  4990.2  895.44  4998.7  894.52  4998.9  894.02  5002.4  894.02
  5002.7  894.52  5010.3  897.30  5020.4  899.90  5030.4  900.73  5050.5  902.04
  5070.6  902.96  5098.8  904.87  5103.9  904.96  5110.8  905.88  5130.9  907.03
  5140.9  907.84  5151.0  908.94  5191.1  911.77  5201.2  912.88  5209.7  913.26
#Mann=3,-1,0
  4817.1    0.05       0  4998.7   0.033       0  5002.7    0.05       0
Bank Sta=4998.7,5002.7
Exp/Cntr=0.3,0.1

Type RM Length L Ch R = 1,921,133,133,133
BEGIN DESCRIPTION:
Mapping XS 39bccddb
END DESCRIPTION:
XS GIS Cut Line= 3
      2287041.50      7122841.71      2287179.98      7122824.08
      2287178.52      7122643.58
#Sta/Elev= 30
  4804.3  895.90  4811.9  895.68  4821.9  895.54  4842.1  895.08  4852.2  894.99
  4857.3  894.66  4862.4  894.93  4872.3  894.62  4892.5  894.30  4922.7  894.33
  4932.2  894.42  4937.2  895.05  4940.9  894.96  4948.4  894.96  4958.0  895.52
  4968.0  896.58  4978.0  894.67  4986.0  892.23  4986.2  891.73  4989.7  891.73
  4990.0  892.23  4998.0  892.36  5008.0  896.56  5018.0  897.77  5058.0  899.99
  5068.0  900.23  5088.0  901.28  5098.0  901.98  5108.0  902.19  5124.4  903.45
#Mann=3,-1,0
  4804.3    0.05       0  4986.0   0.033       0  4990.0    0.05       0
Bank Sta=4986,4990
Exp/Cntr=0.3,0.1

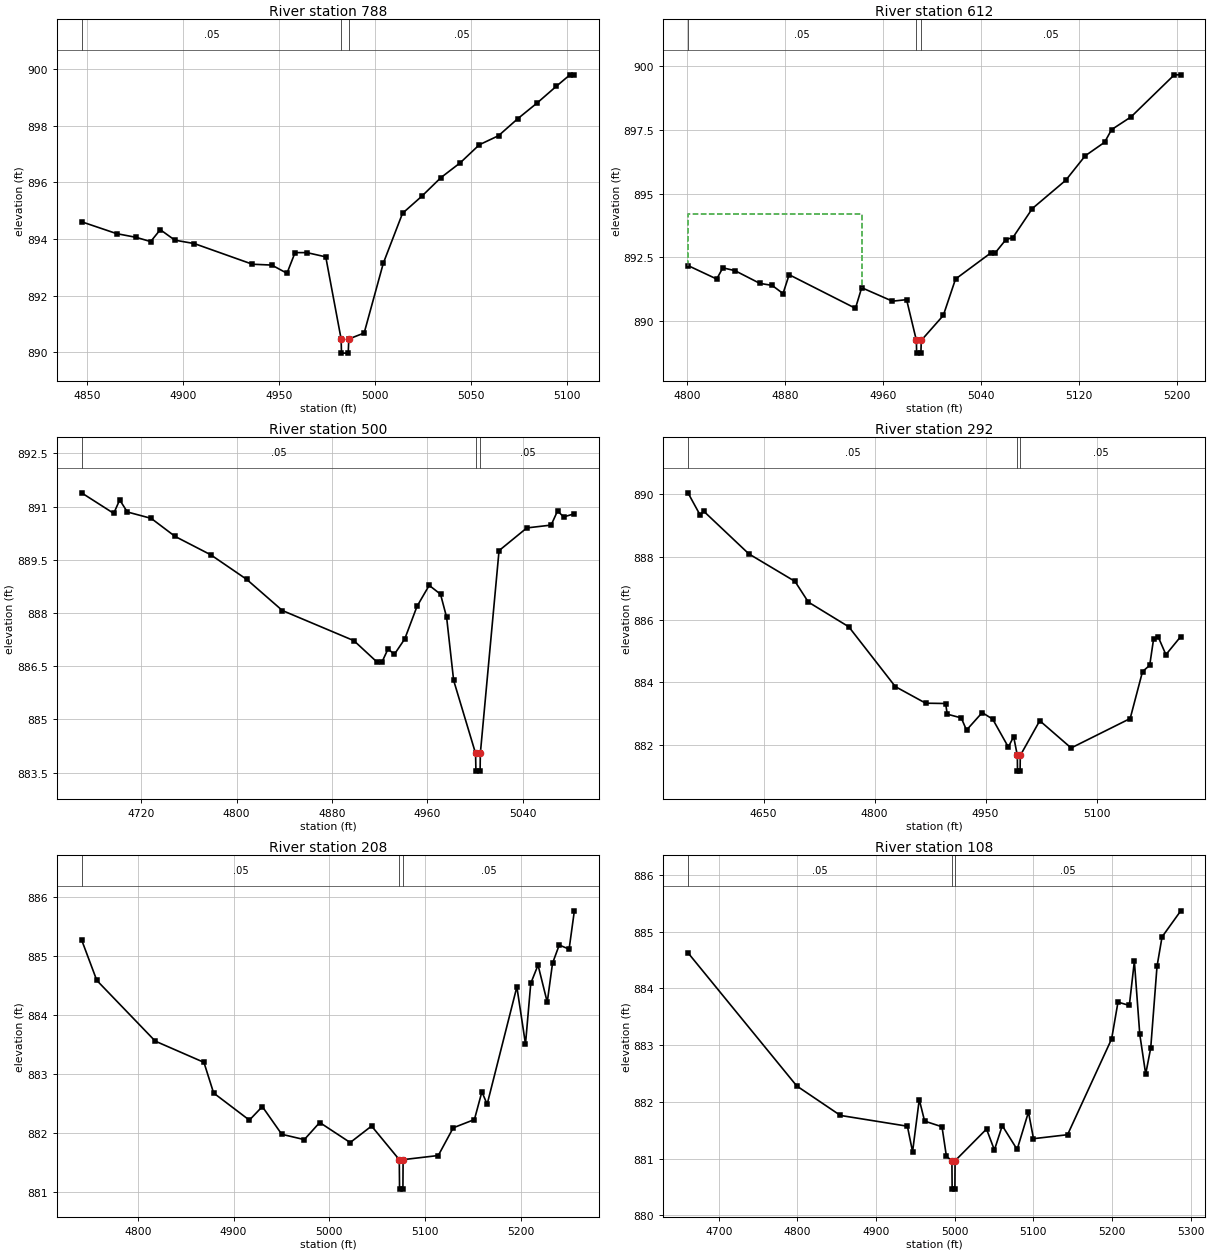
Type RM Length L Ch R = 1,788,176,176,176
BEGIN DESCRIPTION:
Mapping XS e79448a0
END DESCRIPTION:
XS GIS Cut Line= 3
      2287200.83      7122820.39      2287312.27      7122804.61
      2287312.61      7122660.46
#Sta/Elev= 30
  4847.0  894.61  4865.3  894.19  4875.4  894.06  4883.0  893.91  4888.0  894.33
  4895.6  893.96  4905.7  893.84  4936.0  893.11  4946.1  893.08  4954.0  892.79
  4958.2  893.52  4964.4  893.52  4974.2  893.37  4982.2  890.47  4982.4  889.97
  4985.9  889.97  4986.2  890.47  4994.2  890.68  5004.2  893.15  5014.2  894.91
  5024.2  895.51  5034.2  896.17  5044.2  896.69  5054.2  897.33  5064.2  897.65
  5074.2  898.25  5084.2  898.80  5094.2  899.39  5101.4  899.80  5103.7  899.80
#Mann=3,-1,0
  4847.0    0.05       0  4982.2   0.033       0  4986.2    0.05       0
Bank Sta=4982.2,4986.2
Exp/Cntr=0.3,0.1

Type RM Length L Ch R = 1,612,112,112,112
BEGIN DESCRIPTION:
Mapping XS d9db1e79
END DESCRIPTION:
XS GIS Cut Line= 4
      2287321.22      7122819.13      2287487.49      7122789.82
      2287491.18      7122707.69      2287416.09      7122575.82
#Sta/Elev= 30
  4800.4  892.18  4823.9  891.65  4828.9  892.09  4838.8  891.98  4859.1  891.48
  4869.2  891.40  4878.1  891.08  4883.1  891.82  4937.3  890.50  4942.4  891.31
  4967.5  890.78  4979.1  890.84  4987.1  889.24  4987.3  888.74  4990.8  888.74
  4991.1  889.24  5009.1  890.22  5019.1  891.65  5047.8  892.67  5051.4  892.67
  5060.3  893.20  5066.0  893.28  5081.9  894.42  5109.2  895.53  5125.1  896.49
  5140.9  897.02  5146.7  897.52  5162.6  898.02  5197.9  899.67  5203.2  899.67
#Mann=3,-1,0
  4800.4    0.05       0  4987.1   0.033       0  4991.1    0.05       0
#XS Ineff=2,0
    0.00 4942.60  894.21               0
Permanent Ineff=
       F       F
Bank Sta=4987.1,4991.1
Exp/Cntr=0.3,0.1

Type RM Length L Ch R = 1,500,208,208,208
BEGIN DESCRIPTION:
Mapping XS e6035ea4
END DESCRIPTION:
XS GIS Cut Line= 3
      2287330.58      7122835.88      2287582.63      7122828.64
      2287616.94      7122670.98
#Sta/Elev= 30
  4669.9  891.39  4696.9  890.81  4701.9  891.19  4708.3  890.85  4728.3  890.67
  4748.4  890.16  4778.4  889.64  4808.4  888.95  4838.4  888.07  4898.4  887.22
  4917.7  886.62  4922.0  886.62  4927.1  886.99  4932.3  886.83  4941.1  887.27
  4951.4  888.19  4961.6  888.78  4971.1  888.53  4976.2  887.88  4982.1  886.10
  5000.5  884.04  5000.8  883.54  5004.3  883.54  5004.5  884.04  5020.2  889.76
  5043.5  890.40  5063.9  890.48  5069.3  890.88  5074.4  890.71  5083.4  890.80
#Mann=3,-1,0
  4669.9    0.05       0  5000.5   0.033       0  5004.5    0.05       0
Bank Sta=5000.5,5004.5
Exp/Cntr=0.3,0.1

Type RM Length L Ch R = 1,292,84,84,84
BEGIN DESCRIPTION:
Mapping XS 2fb52e28
END DESCRIPTION:
XS GIS Cut Line= 4
      2287299.76      7123079.78      2287638.00      7122984.46
      2287771.44      7122849.43      2287732.23      7122730.90
#Sta/Elev= 30
  4547.7  890.05  4563.9  889.35  4569.1  889.46  4630.0  888.10  4692.4  887.22
  4710.4  886.56  4765.1  885.77  4828.0  883.86  4869.0  883.33  4896.0  883.32
  4898.1  882.98  4917.1  882.86  4924.2  882.47  4945.4  883.03  4959.6  882.82
  4980.7  881.93  4987.9  882.26  4992.9  881.66  4993.1  881.16  4996.6  881.16
  4996.9  881.66  5023.2  882.77  5065.6  881.90  5145.4  882.84  5162.1  884.34
  5171.8  884.54  5177.1  885.39  5183.1  885.46  5193.7  884.88  5213.8  885.46
#Mann=3,-1,0
  4547.7    0.05       0  4992.9   0.035       0  4996.9    0.05       0
Bank Sta=4992.9,4996.9
Exp/Cntr=0.3,0.1

Type RM Length L Ch R = 1,208,100,100,100
BEGIN DESCRIPTION:
Mapping XS 60e5fff4
END DESCRIPTION:
XS GIS Cut Line= 4
      2287533.34      7123026.20      2287762.11      7122985.18
      2287802.37      7122870.87      2287733.65      7122725.73
#Sta/Elev= 30
  4741.4  885.28  4757.3  884.59  4818.3  883.56  4869.1  883.20  4879.2  882.68
  4916.5  882.22  4930.0  882.45  4950.3  881.98  4973.8  881.89  4989.9  882.18
  5021.7  881.84  5044.0  882.12  5072.9  881.55  5073.2  881.05  5076.7  881.05
  5076.9  881.55  5113.6  881.62  5129.2  882.09  5151.3  882.23  5159.1  882.70
  5164.6  882.49  5195.6  884.48  5204.6  883.51  5210.1  884.54  5217.7  884.85
  5227.3  884.22  5232.8  884.88  5239.8  885.19  5250.1  885.12  5255.6  885.77
#Mann=3,-1,0
  4741.4    0.05       0  5072.9   0.035       0  5076.9    0.05       0
Bank Sta=5072.9,5076.9
Exp/Cntr=0.3,0.1

Type RM Length L Ch R = 1,108,71,71,71
BEGIN DESCRIPTION:
Mapping XS 2fbe43e8
END DESCRIPTION:
XS GIS Cut Line= 5
      2287561.32      7123033.47      2287847.07      7123006.15
      2287872.35      7122957.89      2287869.21      7122885.75
      2287736.93      7122719.23
#Sta/Elev= 30
  4660.9  884.63  4799.2  882.28  4854.7  881.76  4939.8  881.57  4946.4  881.12
  4954.9  882.04  4961.7  881.66  4983.8  881.56  4989.4  881.04  4996.4  880.96
  4996.7  880.46  5000.2  880.46  5000.4  880.96  5040.4  881.52  5050.4  881.15
  5060.4  881.58  5079.3  881.16  5093.7  881.82  5100.1  881.35  5143.4  881.42
  5199.4  883.11  5207.5  883.76  5221.9  883.70  5228.3  884.48  5235.2  883.19
  5242.7  882.49  5249.1  882.95  5257.1  884.39  5263.5  884.91  5287.3  885.37
#Mann=3,-1,0
  4660.9    0.05       0  4996.4   0.033       0  5000.4    0.05       0
Bank Sta=4996.4,5000.4
Exp/Cntr=0.3,0.1

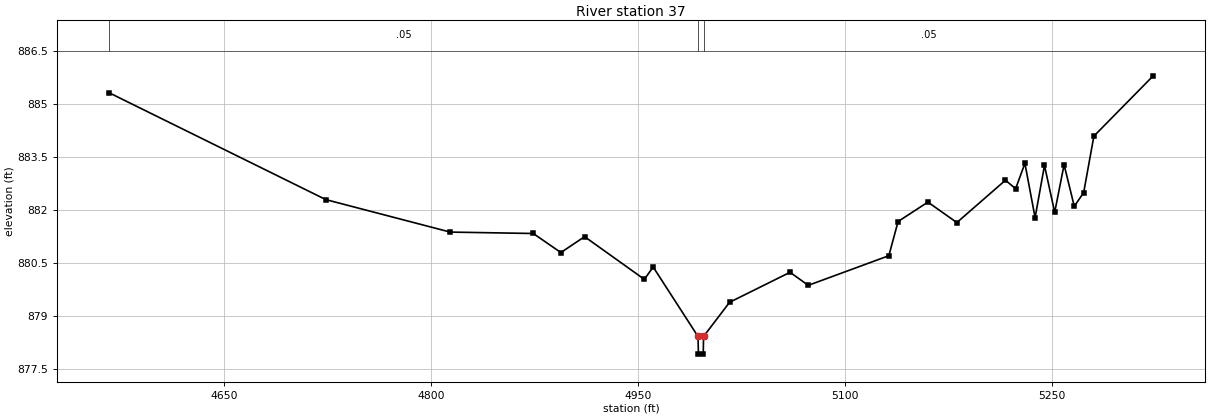
Type RM Length L Ch R = 1,37,0,0,0
BEGIN DESCRIPTION:
MDE S 087 1.0
END DESCRIPTION:
XS GIS Cut Line= 5
      2287532.25      7123042.95      2287864.55      7123021.91
      2287942.86      7122960.56      2287879.73      7122867.31
      2287737.27      7122710.79
#Sta/Elev= 30
  4566.9  885.32  4724.0  882.29  4814.1  881.37  4874.3  881.33  4894.3  880.79
  4911.5  881.24  4954.8  880.03  4961.2  880.38  4993.7  878.41  4994.0  877.91
  4997.5  877.91  4997.7  878.41  5016.6  879.38  5060.4  880.23  5073.6  879.86
  5132.0  880.70  5138.7  881.67  5160.3  882.22  5181.3  881.64  5216.5  882.84
  5223.9  882.60  5230.6  883.32  5238.0  881.78  5244.8  883.26  5252.2  881.93
  5259.0  883.28  5266.4  882.10  5273.2  882.49  5280.6  884.09  5323.6  885.80
#Mann=3,-1,0
  4566.9    0.05       0  4993.7   0.033       0  4997.7    0.05       0
Bank Sta=4993.7,4997.7
Exp/Cntr=0.3,0.1

Chan Stop Cuts=-1