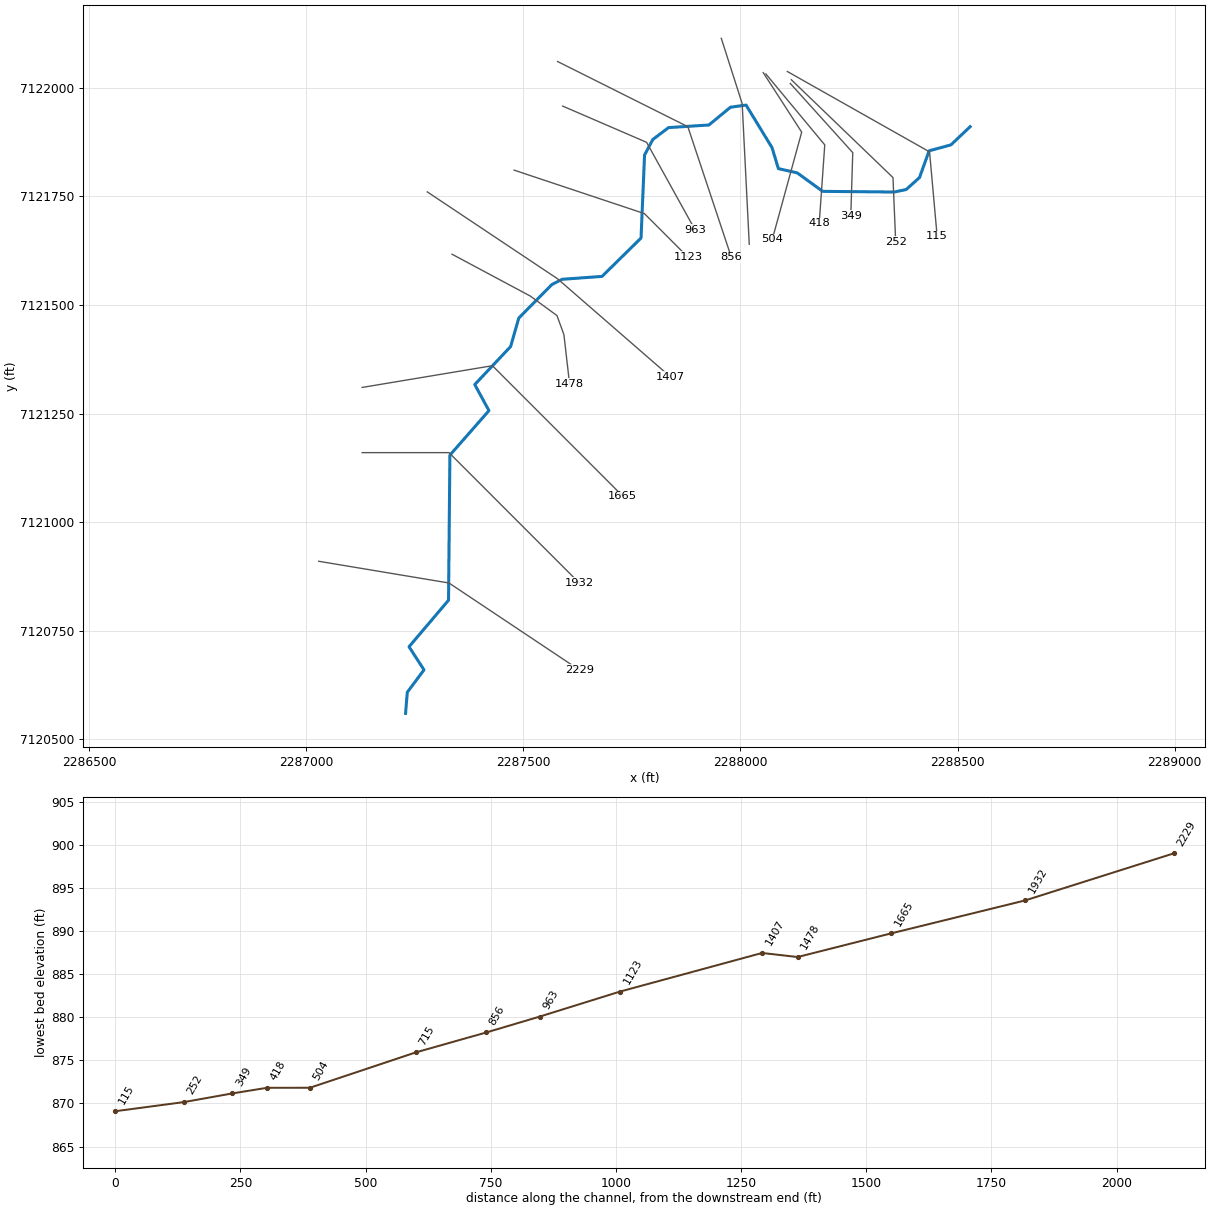
--- MDE S 088.prj (project) ---

Proj Title=MDE S 088 Base Level Engineering
Current Plan=p01
Default Exp/Contr=0.3,0.1
English Units
Geom File=g01
Flow File=f01
Plan File=p01
BEGIN DESCRIPTION:
MDE S 088
END DESCRIPTION:

--- MDE S 088.p01 (plan) ---

Plan Title=Multiple Run
Short Identifier=Multiple
Geom File=g01
Flow File=f01
Subcritical Flow
K Sum by GR= 0
Std Step Tol= 0.01
Critical Tol= 0.01
Num of Std Step Trials= 20
Max Error Tol= 0.3
Flow Tol Ratio= 0.001
Split Flow NTrial= 30
Split Flow Tol= 0.02
Split Flow Ratio= 0.02
Log Output Level= 0
Friction Slope Method= 1
Unsteady Friction Slope Method= 2
Unsteady Bridges Friction Slope Method= 1
Parabolic Critical Depth
Global Vel Dist=  1 , 1 , 1
Global Log Level= 0
CheckData=True
Encroach Param= -1, 0, 0, 0
BEGIN DESCRIPTION:
Multiple Run
END DESCRIPTION:

--- MDE S 088.f01 (steady flow) ---

Flow Title=Multiple
Number of Profiles=7
Profile Names=10-year,25-year,50-year,1pct_min,100-year,1pct_plu,500-year
River Rch & RM= MDE S 088,Reach-1,2229
     211     272     320     188     376     750     516
Boundary for River Rch & Prof#=MDE S 088,Reach-1,1
Up Type=0
Dn Type=3
Dn Slope=0.009
Boundary for River Rch & Prof#=MDE S 088,Reach-1,2
Up Type=0
Dn Type=3
Dn Slope=0.009
Boundary for River Rch & Prof#=MDE S 088,Reach-1,3
Up Type=0
Dn Type=3
Dn Slope=0.009
Boundary for River Rch & Prof#=MDE S 088,Reach-1,4
Up Type=0
Dn Type=3
Dn Slope=0.009
Boundary for River Rch & Prof#=MDE S 088,Reach-1,5
Up Type=0
Dn Type=3
Dn Slope=0.009
Boundary for River Rch & Prof#=MDE S 088,Reach-1,6
Up Type=0
Dn Type=3
Dn Slope=0.009
Boundary for River Rch & Prof#=MDE S 088,Reach-1,7
Up Type=0
Dn Type=3
Dn Slope=0.009

--- MDE S 088.g01 (geometry) ---

Geom Title=Existing Conditions

River Reach=MDE S 088,Reach-1
Reach XY= 30
      2287229.00      7120560.00      2287232.98      7120608.64
      2287271.42      7120660.07      2287236.99      7120713.33
      2287327.94      7120820.43      2287331.07      7121154.15
      2287420.98      7121256.67      2287388.32      7121316.66
      2287470.80      7121403.95      2287489.77      7121469.70
      2287565.67      7121546.61      2287589.48      7121558.84
      2287681.44      7121565.52      2287771.20      7121653.79
      2287779.32      7121844.98      2287798.40      7121880.65
      2287834.68      7121907.94      2287927.44      7121913.90
      2287977.16      7121954.79      2288013.00      7121959.77
      2288072.77      7121861.90      2288087.46      7121813.50
      2288130.84      7121803.72      2288189.48      7121761.19
      2288354.20      7121759.68      2288381.69      7121765.39
      2288412.47      7121793.05      2288434.52      7121854.53
      2288484.70      7121868.12      2288529.00      7121910.00

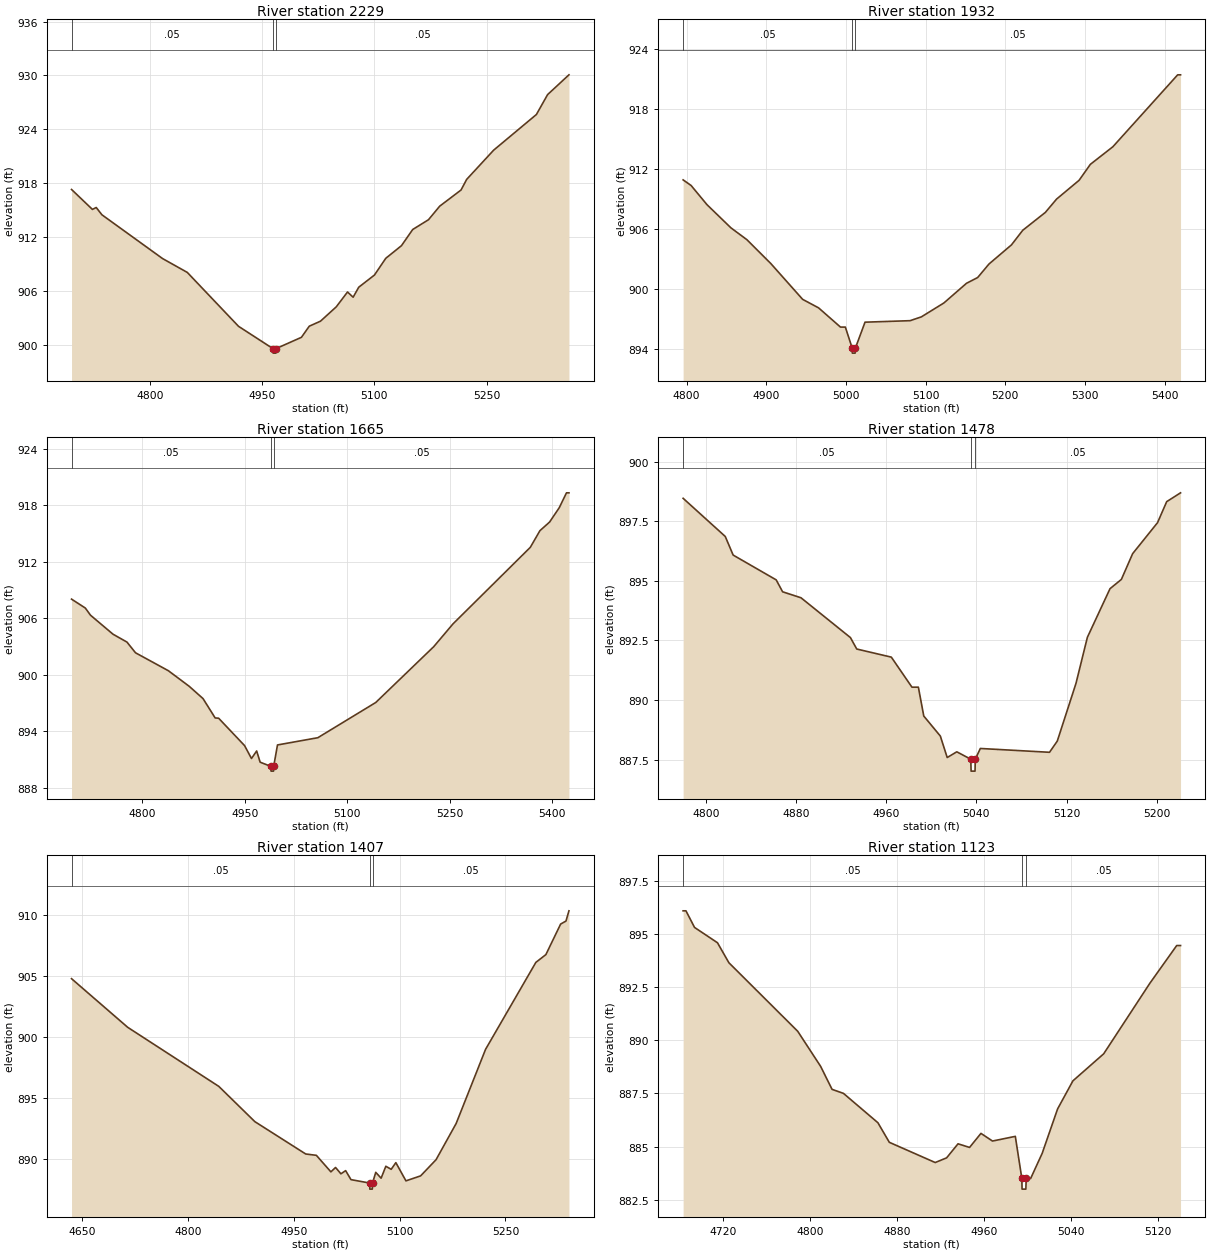
Type RM Length L Ch R = 1,2229,297,297,297
BEGIN DESCRIPTION:
MDE S 088 7.0
END DESCRIPTION:
XS GIS Cut Line= 3
      2287028.95      7120910.01      2287329.00      7120860.00
      2287628.97      7120660.02
#Sta/Elev= 30
  4695.3  917.29  4723.2  915.07  4728.3  915.28  4735.9  914.47  4817.0  909.59
  4850.0  908.05  4918.4  902.05  4964.5  899.56  4964.8  899.06  4968.3  899.06
  4968.5  899.56  5002.5  900.82  5013.0  902.06  5028.0  902.62  5049.1  904.22
  5064.1  905.87  5071.6  905.29  5079.1  906.40  5100.1  907.76  5115.2  909.62
  5136.2  911.03  5151.2  912.83  5172.3  913.92  5187.3  915.43  5215.8  917.23
  5223.3  918.41  5259.4  921.67  5316.5  925.64  5331.5  927.86  5360.0  930.06
#Mann=3,-1,0
  4695.3    0.05       0  4964.5   0.033       0  4968.5    0.05       0
Bank Sta=4964.5,4968.5
Exp/Cntr=0.3,0.1

Type RM Length L Ch R = 1,1932,267,267,267
BEGIN DESCRIPTION:
MDE S 088 6.0
END DESCRIPTION:
XS GIS Cut Line= 3
      2287128.98      7121160.00      2287329.00      7121160.00
      2287629.01      7120859.99
#Sta/Elev= 30
  4795.7  910.89  4805.7  910.33  4825.7  908.41  4855.7  906.10  4875.7  904.92
  4905.7  902.54  4945.7  898.96  4965.7  898.11  4993.2  896.19  4999.3  896.19
  5007.9  894.09  5008.1  893.59  5011.6  893.59  5011.9  894.09  5024.0  896.68
  5080.6  896.83  5094.7  897.21  5123.0  898.60  5151.3  900.56  5165.4  901.14
  5179.6  902.49  5207.8  904.40  5222.0  905.86  5250.3  907.64  5264.4  908.97
  5292.7  910.85  5306.8  912.44  5335.1  914.20  5416.4  921.38  5420.0  921.38
#Mann=3,-1,0
  4795.7    0.05       0  5007.9   0.033       0  5011.9    0.05       0
Bank Sta=5007.9,5011.9
Exp/Cntr=0.3,0.1

Type RM Length L Ch R = 1,1665,187,187,187
BEGIN DESCRIPTION:
MDE S 088 5.0
END DESCRIPTION:
XS GIS Cut Line= 3
      2287129.05      7121310.01      2287429.00      7121360.00
      2287729.03      7121059.97
#Sta/Elev= 30
  4696.1  908.04  4716.3  907.09  4723.9  906.33  4756.9  904.31  4777.2  903.48
  4789.8  902.34  4838.0  900.43  4868.4  898.78  4888.7  897.47  4906.4  895.42
  4911.5  895.39  4949.5  892.48  4959.6  891.11  4967.2  891.91  4972.3  890.72
  4988.1  890.27  4988.3  889.77  4991.8  889.77  4992.1  890.27  4997.7  892.55
  5056.8  893.32  5141.6  897.06  5226.5  902.99  5254.7  905.41  5367.9  913.54
  5382.0  915.31  5396.2  916.23  5410.3  917.75  5420.9  919.33  5424.5  919.33
#Mann=3,-1,0
  4696.1    0.05       0  4988.1   0.033       0  4992.1    0.05       0
Bank Sta=4988.1,4992.1
Exp/Cntr=0.3,0.1

Type RM Length L Ch R = 1,1478,71,71,71
BEGIN DESCRIPTION:
Mapping XS f745bc86
END DESCRIPTION:
XS GIS Cut Line= 5
      2287336.02      7121616.54      2287516.24      7121520.24
      2287577.64      7121475.36      2287593.61      7121431.45
      2287606.69      7121317.82
#Sta/Elev= 30
  4779.7  898.46  4817.1  896.86  4824.1  896.08  4862.3  895.04  4868.0  894.54
  4884.3  894.29  4928.2  892.62  4933.8  892.14  4964.5  891.80  4982.8  890.54
  4988.5  890.54  4993.3  889.33  5008.0  888.49  5014.1  887.59  5022.6  887.83
  5035.0  887.52  5035.3  887.02  5038.8  887.02  5039.0  887.52  5043.5  887.97
  5104.9  887.81  5111.8  888.28  5128.4  890.70  5138.5  892.63  5158.6  894.67
  5168.7  895.06  5178.7  896.14  5200.8  897.44  5208.9  898.32  5221.2  898.69
#Mann=3,-1,0
  4779.7    0.05       0  5035.0   0.033       0  5039.0    0.05       0
Bank Sta=5035,5039
Exp/Cntr=0.3,0.1

Type RM Length L Ch R = 1,1407,284,284,284
BEGIN DESCRIPTION:
MDE S 088 4.0
END DESCRIPTION:
XS GIS Cut Line= 3
      2287278.99      7121760.01      2287579.00      7121560.00
      2287839.21      7121334.04
#Sta/Elev= 30
  4634.9  904.80  4714.5  900.80  4843.7  895.94  4894.8  893.04  4966.9  890.38
  4982.0  890.27  5002.6  888.91  5009.2  889.27  5016.8  888.75  5023.5  889.01
  5031.1  888.27  5057.6  887.99  5057.8  887.49  5061.3  887.49  5061.6  887.99
  5066.2  888.87  5073.8  888.39  5080.5  889.37  5088.1  889.12  5094.7  889.67
  5109.0  888.17  5129.8  888.58  5151.7  889.91  5180.2  892.89  5221.9  898.99
  5293.2  906.14  5307.4  906.78  5328.3  909.29  5335.9  909.54  5340.1  910.38
#Mann=3,-1,0
  4634.9    0.05       0  5057.6   0.033       0  5061.6    0.05       0
Bank Sta=5057.6,5061.6
Exp/Cntr=0.3,0.1

Type RM Length L Ch R = 1,1123,160,160,160
BEGIN DESCRIPTION:
MDE S 088 3.0
END DESCRIPTION:
XS GIS Cut Line= 3
      2287479.04      7121809.99      2287779.00      7121710.00
      2287878.99      7121610.01
#Sta/Elev= 30
  4683.2  896.08  4685.8  896.08  4693.7  895.30  4714.8  894.58  4725.3  893.64
  4788.6  890.42  4809.7  888.77  4820.2  887.69  4830.7  887.50  4862.4  886.12
  4872.9  885.20  4915.1  884.25  4925.6  884.47  4936.1  885.13  4946.7  884.96
  4957.2  885.62  4967.8  885.26  4988.8  885.48  4994.8  883.50  4995.0  883.00
  4998.5  883.00  4998.8  883.50  5002.9  883.50  5013.5  884.68  5027.7  886.77
  5041.8  888.09  5070.1  889.36  5112.5  892.67  5137.3  894.45  5140.8  894.45
#Mann=3,-1,0
  4683.2    0.05       0  4994.8   0.033       0  4998.8    0.05       0
Bank Sta=4994.8,4998.8
Exp/Cntr=0.3,0.1

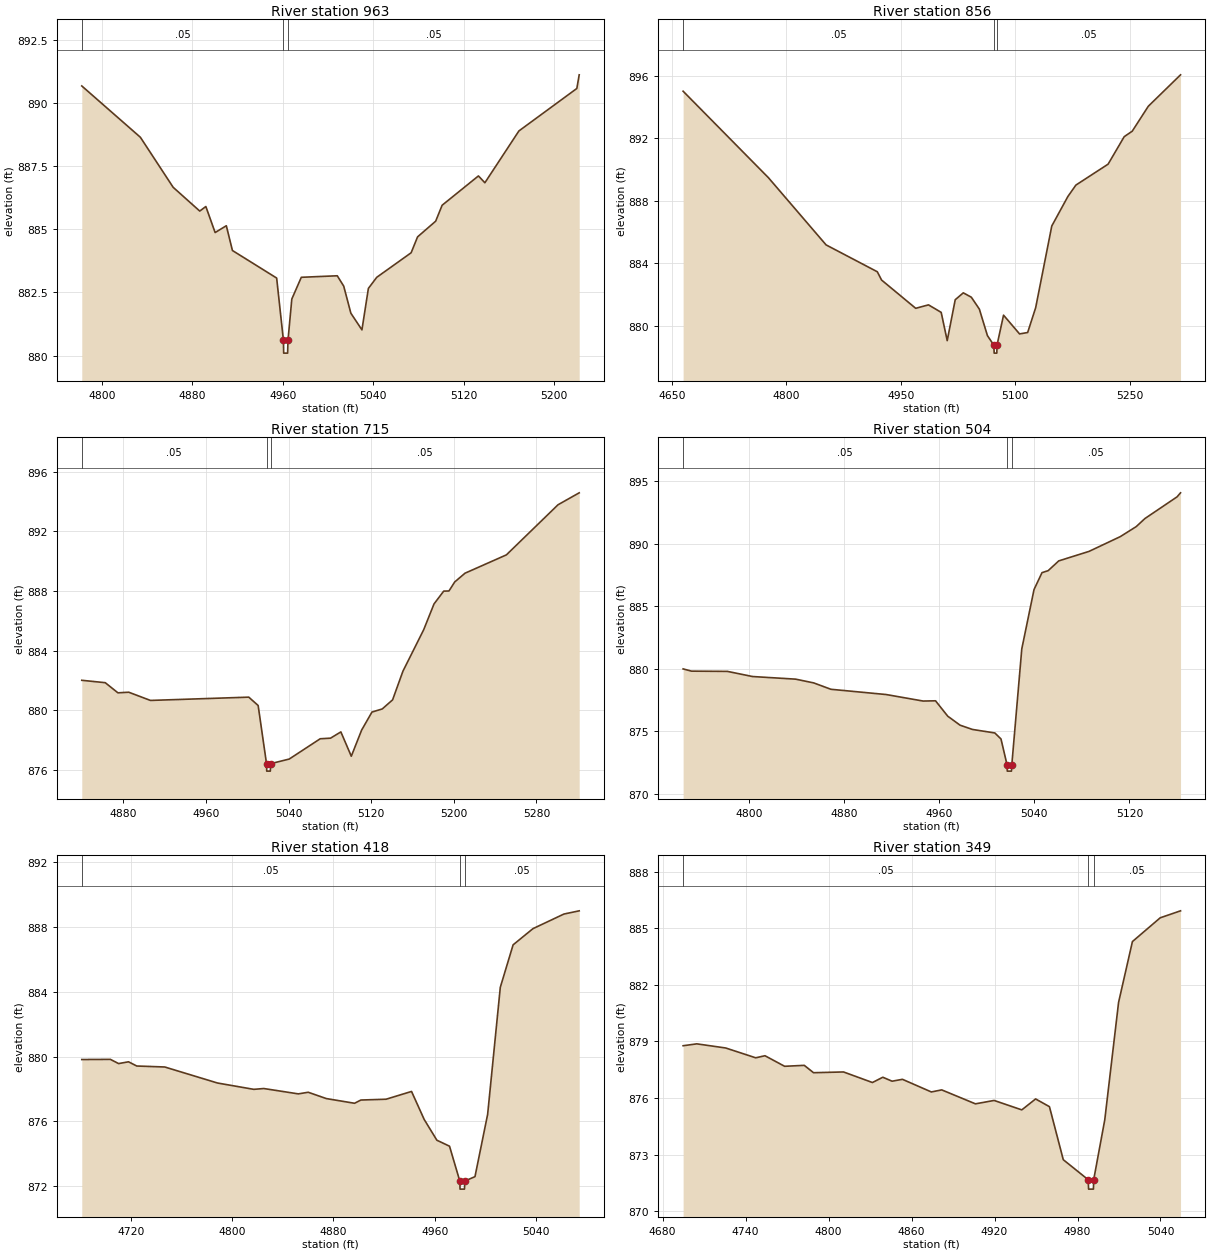
Type RM Length L Ch R = 1,963,107,107,107
BEGIN DESCRIPTION:
Mapping XS 29bf2a85
END DESCRIPTION:
XS GIS Cut Line= 3
      2287590.78      7121957.40      2287784.02      7121874.02
      2287895.12      7121673.39
#Sta/Elev= 30
  4782.3  890.67  4834.1  888.64  4863.1  886.66  4886.6  885.72  4892.0  885.90
  4900.2  884.87  4910.1  885.14  4915.5  884.16  4954.6  883.07  4960.6  880.60
  4960.8  880.10  4964.3  880.10  4964.6  880.60  4968.0  882.24  4976.4  883.10
  5008.2  883.16  5013.9  882.75  5020.2  881.68  5030.0  881.02  5035.7  882.66
  5043.1  883.10  5073.5  884.07  5079.2  884.70  5095.2  885.32  5100.9  885.95
  5133.0  887.11  5138.7  886.84  5168.8  888.89  5220.0  890.57  5222.1  891.11
#Mann=3,-1,0
  4782.3    0.05       0  4960.6   0.033       0  4964.6    0.05       0
Bank Sta=4960.6,4964.6
Exp/Cntr=0.3,0.1

Type RM Length L Ch R = 1,856,141,141,141
BEGIN DESCRIPTION:
MDE S 088 2.0
END DESCRIPTION:
XS GIS Cut Line= 3
      2287578.98      7122060.01      2287879.00      7121910.00
      2287979.01      7121609.97
#Sta/Elev= 30
  4664.7  895.02  4776.5  889.48  4852.0  885.18  4919.1  883.46  4924.7  882.93
  4969.4  881.12  4986.2  881.34  5002.8  880.86  5010.7  879.05  5021.2  881.67
  5031.8  882.11  5042.3  881.83  5052.8  881.07  5063.4  879.37  5071.9  878.75
  5072.2  878.25  5075.7  878.25  5075.9  878.75  5084.5  880.68  5105.5  879.48
  5116.1  879.57  5126.6  881.16  5147.7  886.39  5168.8  888.28  5179.3  889.01
  5221.5  890.35  5242.6  892.11  5253.1  892.46  5274.2  894.06  5316.4  896.07
#Mann=3,-1,0
  4664.7    0.05       0  5071.9   0.033       0  5075.9    0.05       0
Bank Sta=5071.9,5075.9
Exp/Cntr=0.3,0.1

Type RM Length L Ch R = 1,715,211,211,211
BEGIN DESCRIPTION:
Mapping XS 3a351ce2
END DESCRIPTION:
XS GIS Cut Line= 3
      2287956.00      7122113.32      2288004.06      7121963.20
      2288020.38      7121639.54
#Sta/Elev= 30
  4839.7  882.02  4862.4  881.86  4874.7  881.18  4885.2  881.22  4906.2  880.67
  5001.4  880.89  5010.5  880.33  5018.6  876.43  5018.8  875.93  5022.3  875.93
  5022.6  876.43  5040.6  876.74  5070.6  878.10  5080.6  878.14  5090.6  878.56
  5100.7  876.93  5110.7  878.68  5120.7  879.89  5130.7  880.10  5140.7  880.71
  5150.7  882.63  5170.8  885.41  5180.8  887.14  5190.2  888.00  5195.3  888.01
  5200.8  888.61  5210.8  889.20  5250.9  890.43  5300.9  893.79  5321.4  894.59
#Mann=3,-1,0
  4839.7    0.05       0  5018.6   0.033       0  5022.6    0.05       0
Bank Sta=5018.6,5022.6
Exp/Cntr=0.3,0.1

Type RM Length L Ch R = 1,504,86,86,86
BEGIN DESCRIPTION:
Mapping XS fb645932
END DESCRIPTION:
XS GIS Cut Line= 3
      2288052.52      7122034.47      2288141.12      7121897.48
      2288073.53      7121651.12
#Sta/Elev= 30
  4744.4  880.00  4751.4  879.82  4781.7  879.80  4802.8  879.39  4839.1  879.18
  4854.3  878.88  4868.8  878.37  4915.3  877.95  4946.4  877.43  4956.8  877.45
  4967.1  876.22  4977.5  875.50  4987.9  875.16  5006.7  874.88  5011.9  874.40
  5017.0  872.33  5017.2  871.83  5020.7  871.83  5021.0  872.33  5029.4  881.60
  5039.7  886.34  5046.4  887.69  5051.6  887.85  5060.5  888.63  5086.0  889.39
  5112.3  890.57  5125.7  891.37  5133.1  892.02  5160.1  893.75  5163.0  894.07
#Mann=3,-1,0
  4744.4    0.05       0  5017.0   0.033       0  5021.0    0.05       0
Bank Sta=5017,5021
Exp/Cntr=0.3,0.1

Type RM Length L Ch R = 1,418,69,69,69
BEGIN DESCRIPTION:
Mapping XS 34f85267
END DESCRIPTION:
XS GIS Cut Line= 3
      2288058.69      7122031.29      2288194.24      7121868.13
      2288181.48      7121687.90
#Sta/Elev= 30
  4681.3  879.82  4703.9  879.83  4710.4  879.57  4718.2  879.68  4724.7  879.42
  4746.8  879.36  4788.5  878.37  4817.1  877.98  4825.0  878.03  4852.3  877.70
  4860.1  877.80  4874.4  877.41  4896.7  877.12  4901.7  877.32  4921.6  877.37
  4941.7  877.85  4951.7  876.12  4961.7  874.84  4971.7  874.47  4979.8  872.32
  4980.0  871.82  4983.5  871.82  4983.8  872.32  4991.8  872.59  5001.8  876.44
  5011.8  884.28  5021.9  886.90  5037.6  887.90  5062.0  888.80  5074.1  889.00
#Mann=3,-1,0
  4681.3    0.05       0  4979.8   0.033       0  4983.8    0.05       0
Bank Sta=4979.8,4983.8
Exp/Cntr=0.3,0.1

Type RM Length L Ch R = 1,349,97,97,97
BEGIN DESCRIPTION:
Mapping XS db6a3ca4
END DESCRIPTION:
XS GIS Cut Line= 3
      2288114.88      7122009.55      2288258.70      7121850.31
      2288254.17      7121705.26
#Sta/Elev= 30
  4694.8  878.77  4704.7  878.87  4725.6  878.65  4747.3  878.13  4754.0  878.24
  4768.2  877.68  4782.4  877.73  4789.1  877.34  4810.8  877.38  4831.7  876.82
  4839.2  877.10  4845.9  876.89  4853.4  876.99  4874.3  876.32  4881.8  876.43
  4906.2  875.69  4919.7  875.87  4939.7  875.37  4949.7  875.95  4959.7  875.54
  4969.7  872.73  4987.7  871.67  4988.0  871.17  4991.5  871.17  4991.7  871.67
  4999.7  874.84  5009.7  881.07  5019.7  884.29  5039.8  885.55  5054.5  885.92
#Mann=3,-1,0
  4694.8    0.05       0  4987.7   0.033       0  4991.7    0.05       0
Bank Sta=4987.7,4991.7
Exp/Cntr=0.3,0.1

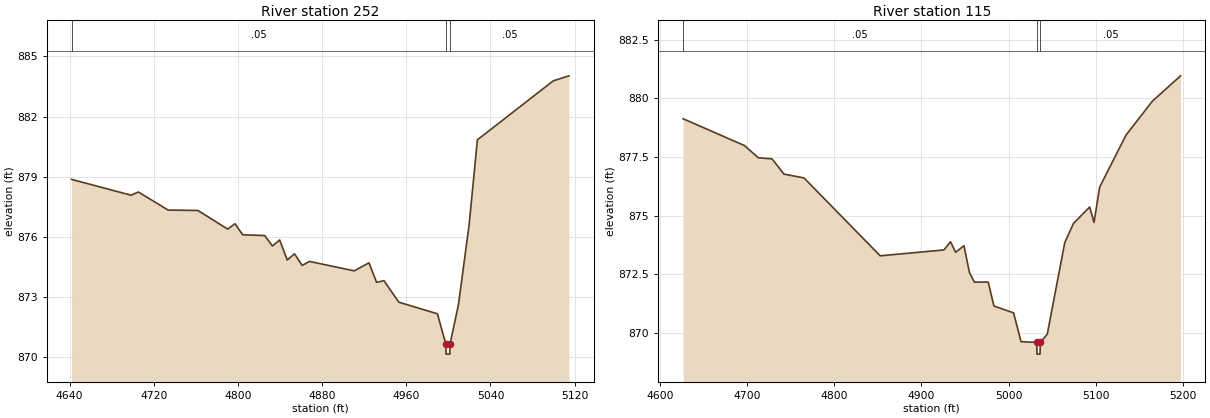
Type RM Length L Ch R = 1,252,137,137,137
BEGIN DESCRIPTION:
Mapping XS 253c43f1
END DESCRIPTION:
XS GIS Cut Line= 3
      2288117.22      7122018.06      2288351.30      7121792.95
      2288357.55      7121645.14
#Sta/Elev= 30
  4641.9  878.87  4698.5  878.08  4705.4  878.24  4733.7  877.34  4762.0  877.32
  4790.3  876.39  4797.2  876.66  4804.5  876.11  4825.5  876.07  4832.8  875.55
  4839.7  875.85  4846.9  874.85  4853.8  875.16  4861.1  874.58  4868.0  874.78
  4910.5  874.31  4924.6  874.71  4931.8  873.74  4938.8  873.82  4952.9  872.75
  4989.6  872.17  4997.6  870.66  4997.9  870.16  5001.4  870.16  5001.6  870.66
  5009.6  872.63  5019.7  876.59  5027.6  880.84  5099.7  883.78  5114.6  884.03
#Mann=3,-1,0
  4641.9    0.05       0  4997.6   0.033       0  5001.6    0.05       0
Bank Sta=4997.6,5001.6
Exp/Cntr=0.3,0.1

Type RM Length L Ch R = 1,115,0,0,0
BEGIN DESCRIPTION:
MDE S 088 1.0
END DESCRIPTION:
XS GIS Cut Line= 3
      2288108.10      7122036.98      2288435.56      7121852.07
      2288453.03      7121657.52
#Sta/Elev= 30
  4626.2  879.13  4696.6  877.99  4712.5  877.47  4728.4  877.42  4742.1  876.77
  4765.0  876.61  4852.6  873.29  4925.8  873.54  4933.4  873.89  4939.2  873.44
  4948.8  873.72  4955.1  872.58  4960.8  872.17  4976.7  872.17  4983.2  871.15
  5005.8  870.86  5014.4  869.63  5032.5  869.60  5032.7  869.10  5036.2  869.10
  5036.5  869.60  5044.5  869.95  5064.6  873.85  5074.6  874.67  5093.2  875.37
  5098.2  874.71  5104.7  876.22  5134.9  878.43  5165.0  879.87  5197.6  880.96
#Mann=3,-1,0
  4626.2    0.05       0  5032.5   0.033       0  5036.5    0.05       0
Bank Sta=5032.5,5036.5
Exp/Cntr=0.3,0.1

Chan Stop Cuts=-1