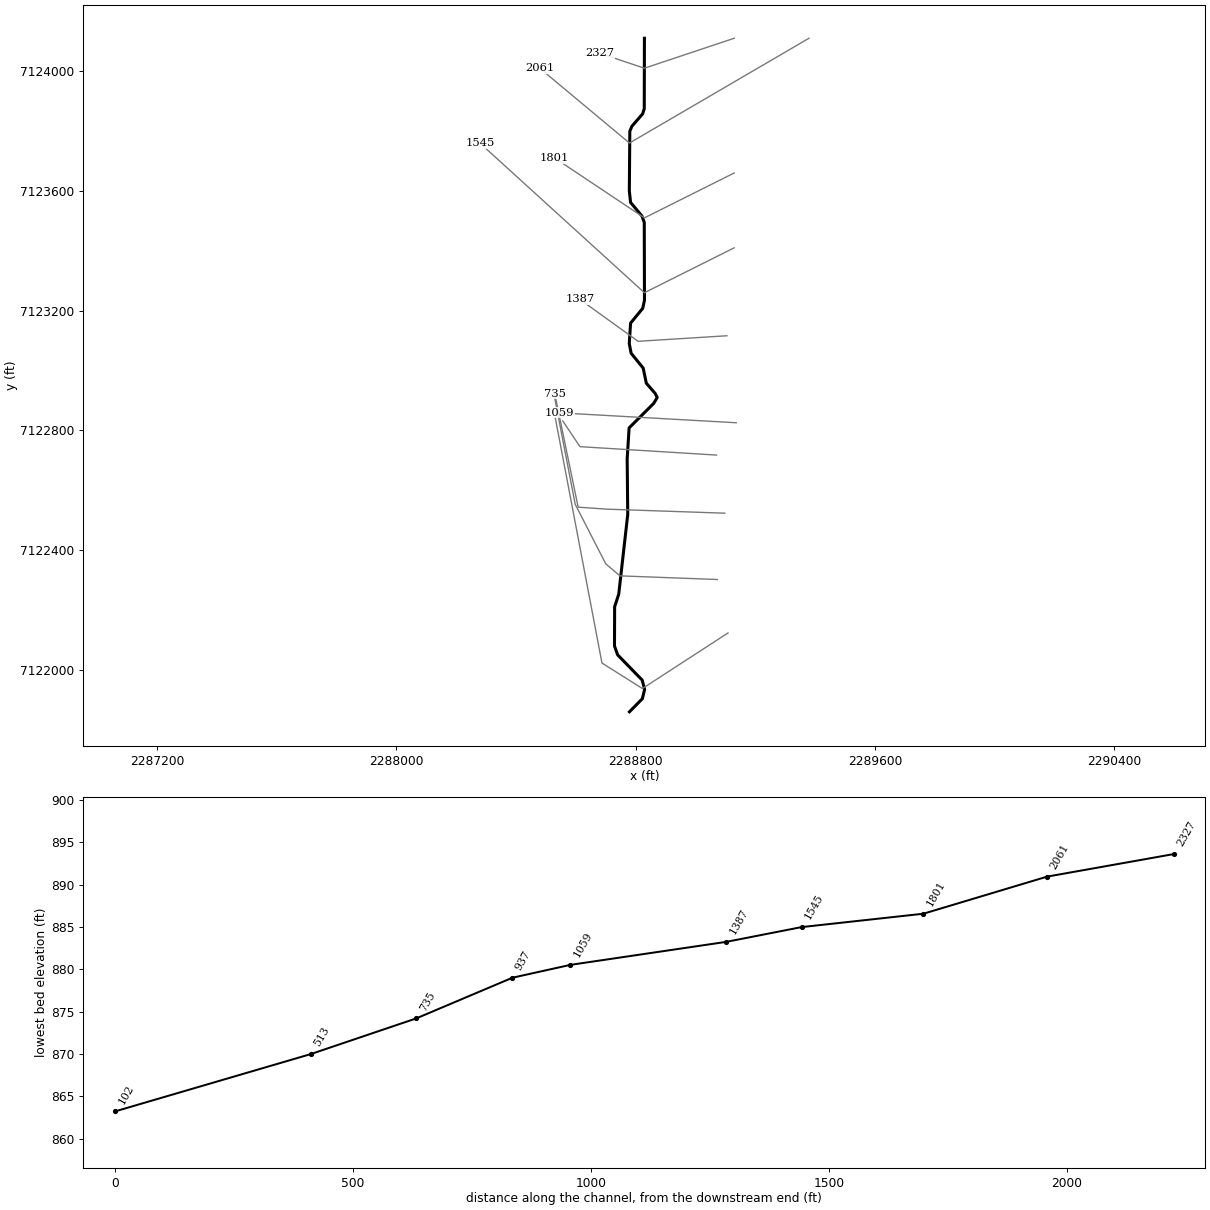
--- MDE S 089.prj (project) ---

Proj Title=MDE S 089 Base Level Engineering
Current Plan=p01
Default Exp/Contr=0.3,0.1
English Units
Geom File=g01
Flow File=f01
Plan File=p01
BEGIN DESCRIPTION:
MDE S 089
END DESCRIPTION:

--- MDE S 089.p01 (plan) ---

Plan Title=Multiple Run
Short Identifier=Multiple
Geom File=g01
Flow File=f01
Subcritical Flow
K Sum by GR= 0
Std Step Tol= 0.01
Critical Tol= 0.01
Num of Std Step Trials= 20
Max Error Tol= 0.3
Flow Tol Ratio= 0.001
Split Flow NTrial= 30
Split Flow Tol= 0.02
Split Flow Ratio= 0.02
Log Output Level= 0
Friction Slope Method= 1
Unsteady Friction Slope Method= 2
Unsteady Bridges Friction Slope Method= 1
Parabolic Critical Depth
Global Vel Dist=  1 , 1 , 1
Global Log Level= 0
CheckData=True
Encroach Param= -1, 0, 0, 0
BEGIN DESCRIPTION:
Multiple Run
END DESCRIPTION:

--- MDE S 089.f01 (steady flow) ---

Flow Title=Multiple
Number of Profiles=7
Profile Names=10-year,25-year,50-year,1pct_min,100-year,1pct_plu,500-year
River Rch & RM= MDE S 089,Reach-1,2327
     210     270     316     185     370     737     504
Boundary for River Rch & Prof#=MDE S 089,Reach-1,1
Up Type=0
Dn Type=3
Dn Slope=0.009
Boundary for River Rch & Prof#=MDE S 089,Reach-1,2
Up Type=0
Dn Type=3
Dn Slope=0.009
Boundary for River Rch & Prof#=MDE S 089,Reach-1,3
Up Type=0
Dn Type=3
Dn Slope=0.009
Boundary for River Rch & Prof#=MDE S 089,Reach-1,4
Up Type=0
Dn Type=3
Dn Slope=0.009
Boundary for River Rch & Prof#=MDE S 089,Reach-1,5
Up Type=0
Dn Type=3
Dn Slope=0.009
Boundary for River Rch & Prof#=MDE S 089,Reach-1,6
Up Type=0
Dn Type=3
Dn Slope=0.009
Boundary for River Rch & Prof#=MDE S 089,Reach-1,7
Up Type=0
Dn Type=3
Dn Slope=0.009

--- MDE S 089.g01 (geometry) ---

Geom Title=Existing Conditions

River Reach=MDE S 089,Reach-1
Reach XY= 30
      2288829.00      7124110.00      2288828.48      7123875.22
      2288823.25      7123857.67      2288787.14      7123816.06
      2288780.22      7123799.50      2288778.55      7123599.81
      2288782.78      7123561.57      2288820.86      7123516.06
      2288828.48      7123494.78      2288829.20      7123234.92
      2288823.25      7123207.66      2288782.70      7123158.40
      2288778.40      7123089.95      2288784.65      7123057.68
      2288824.84      7123008.25      2288835.40      7122957.70
      2288865.24      7122923.19      2288871.71      7122909.91
      2288859.72      7122889.97      2288777.84      7122808.42
      2288771.38      7122705.36      2288773.24      7122519.24
      2288743.14      7122252.72      2288729.45      7122211.07
      2288728.96      7122079.98      2288739.50      7122050.21
      2288821.51      7121966.08      2288829.72      7121935.10
      2288822.08      7121903.86      2288779.00      7121860.00

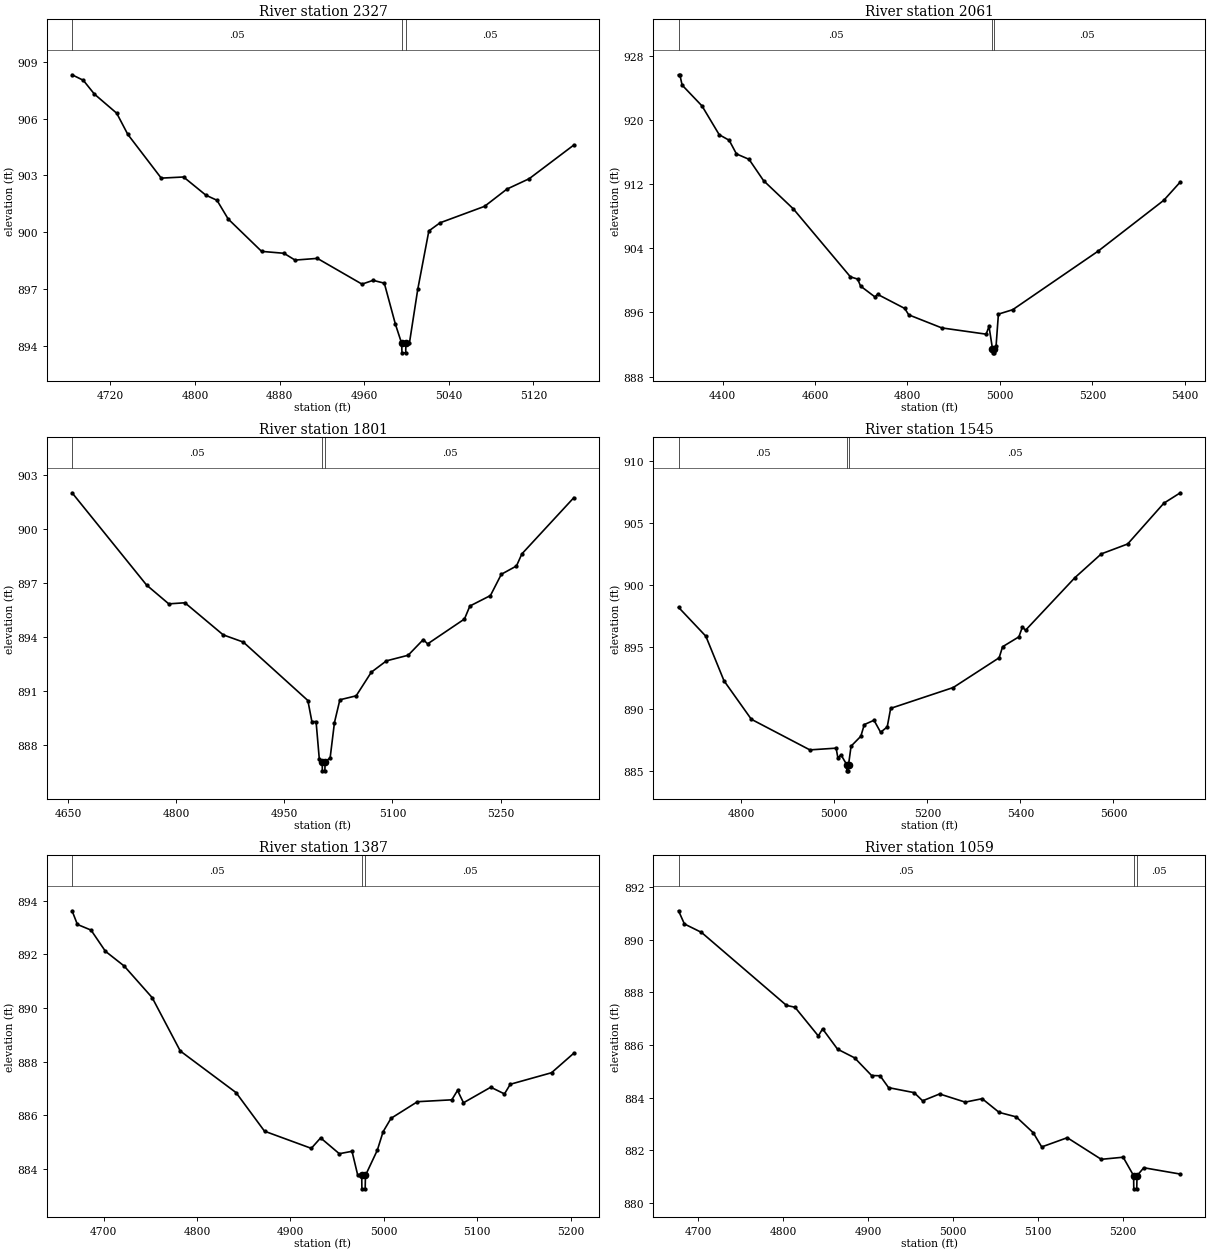
Type RM Length L Ch R = 1,2327,266,266,266
BEGIN DESCRIPTION:
MDE S 089 5.0
END DESCRIPTION:
XS GIS Cut Line= 3
      2289129.01      7124110.00      2288829.00      7124010.00
      2288678.96      7124060.01
#Sta/Elev= 30
  4683.8  908.31  4694.4  908.02  4704.9  907.29  4726.0  906.28  4736.5  905.16
  4768.1  902.85  4789.2  902.91  4810.3  901.95  4820.8  901.68  4831.4  900.69
  4863.0  898.98  4884.1  898.88  4894.6  898.52  4915.7  898.61  4957.9  897.25
  4968.4  897.45  4979.0  897.30  4989.5  895.13  4995.4  894.12  4995.7  893.62
  4999.2  893.62  4999.4  894.12  5002.7  894.12  5010.6  896.97  5021.1  900.06
  5031.7  900.49  5073.8  901.36  5094.9  902.27  5116.0  902.82  5158.2  904.60
#Mann=3,-1,0
  4683.8    0.05       0  4995.4   0.033       0  4999.4    0.05       0
Bank Sta=4995.4,4999.4
Exp/Cntr=0.3,0.1

Type RM Length L Ch R = 1,2061,260,260,260
BEGIN DESCRIPTION:
MDE S 089 4.0
END DESCRIPTION:
XS GIS Cut Line= 3
      2289378.96      7124109.98      2288779.00      7123760.00
      2288478.99      7124010.01
#Sta/Elev= 30
  4304.9  925.65  4307.7  925.65  4312.7  924.36  4355.7  921.76  4392.9  918.17
  4414.4  917.48  4430.1  915.78  4457.4  915.10  4488.8  912.44  4553.3  908.91
  4676.6  900.44  4692.3  900.16  4698.5  899.29  4729.5  897.94  4735.3  898.26
  4794.0  896.50  4802.7  895.70  4874.2  894.07  4970.1  893.29  4976.3  894.26
  4983.8  891.46  4984.1  890.96  4987.6  890.96  4987.8  891.46  4991.6  891.84
  4996.6  895.79  5027.5  896.34  5212.3  903.65  5354.2  909.99  5390.0  912.28
#Mann=3,-1,0
  4304.9    0.05       0  4983.8   0.033       0  4987.8    0.05       0
Bank Sta=4983.8,4987.8
Exp/Cntr=0.3,0.1

Type RM Length L Ch R = 1,1801,256,256,256
BEGIN DESCRIPTION:
MDE S 089 3.0
END DESCRIPTION:
XS GIS Cut Line= 3
      2289128.96      7123659.98      2288829.00      7123510.00
      2288529.02      7123709.99
#Sta/Elev= 30
  4655.7  902.00  4759.1  896.88  4789.8  895.84  4812.2  895.90  4865.3  894.12
  4893.2  893.72  4982.7  890.48  4988.3  889.31  4994.1  889.31  4998.6  887.22
  5002.6  887.08  5002.8  886.58  5006.3  886.58  5006.6  887.08  5013.6  887.30
  5019.6  889.26  5027.1  890.52  5049.7  890.74  5070.7  892.05  5091.7  892.68
  5121.8  892.99  5142.8  893.86  5148.8  893.62  5199.9  895.00  5207.4  895.72
  5235.9  896.30  5251.0  897.48  5272.0  897.94  5279.5  898.61  5351.6  901.73
#Mann=3,-1,0
  4655.7    0.05       0  5002.6   0.033       0  5006.6    0.05       0
Bank Sta=5002.6,5006.6
Exp/Cntr=0.3,0.1

Type RM Length L Ch R = 1,1545,158,158,158
BEGIN DESCRIPTION:
MDE S 089 2.0
END DESCRIPTION:
XS GIS Cut Line= 3
      2289129.02      7123410.01      2288829.00      7123260.00
      2288279.03      7123759.98
#Sta/Elev= 30
  4665.0  898.19  4723.7  895.86  4762.8  892.26  4821.5  889.16  4947.3  886.69
  5003.8  886.83  5007.5  886.05  5014.3  886.29  5026.5  885.50  5026.7  885.00
  5030.2  885.00  5030.5  885.50  5035.9  886.99  5056.9  887.79  5064.3  888.73
  5085.2  889.08  5099.4  888.11  5113.6  888.54  5121.0  890.04  5255.5  891.72
  5354.2  894.12  5361.6  895.01  5396.7  895.81  5404.2  896.61  5410.9  896.34
  5517.0  900.58  5573.8  902.50  5630.5  903.30  5708.3  906.59  5743.7  907.43
#Mann=3,-1,0
  4665.0    0.05       0  5026.5   0.033       0  5030.5    0.05       0
Bank Sta=5026.5,5030.5
Exp/Cntr=0.3,0.1

Type RM Length L Ch R = 1,1387,328,328,328
BEGIN DESCRIPTION:
Mapping XS da5d4731
END DESCRIPTION:
XS GIS Cut Line= 3
      2289104.67      7123116.24      2288807.87      7123097.69
      2288613.07      7123237.92
#Sta/Elev= 30
  4666.1  893.63  4671.8  893.12  4686.4  892.91  4701.8  892.12  4721.9  891.57
  4751.9  890.39  4782.0  888.40  4841.7  886.85  4872.2  885.41  4922.3  884.77
  4932.3  885.16  4952.3  884.57  4965.9  884.66  4972.1  883.76  4976.3  883.76
  4976.5  883.26  4980.0  883.26  4980.3  883.76  4993.0  884.70  4999.2  885.39
  5007.7  885.89  5036.0  886.51  5072.8  886.58  5078.9  886.93  5085.3  886.47
  5114.5  887.05  5129.2  886.80  5135.4  887.16  5179.6  887.59  5203.5  888.32
#Mann=3,-1,0
  4666.1    0.05       0  4976.3   0.033       0  4980.3    0.05       0
Bank Sta=4976.3,4980.3
Exp/Cntr=0.3,0.1

Type RM Length L Ch R = 1,1059,122,122,122
BEGIN DESCRIPTION:
Mapping XS db36f917
END DESCRIPTION:
XS GIS Cut Line= 2
      2289135.93      7122825.65      2288546.06      7122858.73
#Sta/Elev= 30
  4676.6  891.09  4683.5  890.59  4703.6  890.27  4803.7  887.50  4813.7  887.43
  4841.2  886.34  4846.2  886.61  4863.8  885.84  4883.9  885.51  4903.9  884.84
  4913.9  884.83  4923.9  884.38  4954.0  884.19  4964.0  883.88  4984.0  884.14
  5014.1  883.83  5034.1  883.96  5054.1  883.44  5074.2  883.27  5094.2  882.67
  5104.2  882.13  5134.3  882.48  5174.3  881.66  5200.1  881.74  5212.4  881.04
  5212.6  880.54  5216.1  880.54  5216.4  881.04  5224.4  881.34  5267.4  881.10
#Mann=3,-1,0
  4676.6    0.05       0  5212.4   0.033       0  5216.4    0.05       0
Bank Sta=5212.4,5216.4
Exp/Cntr=0.3,0.1

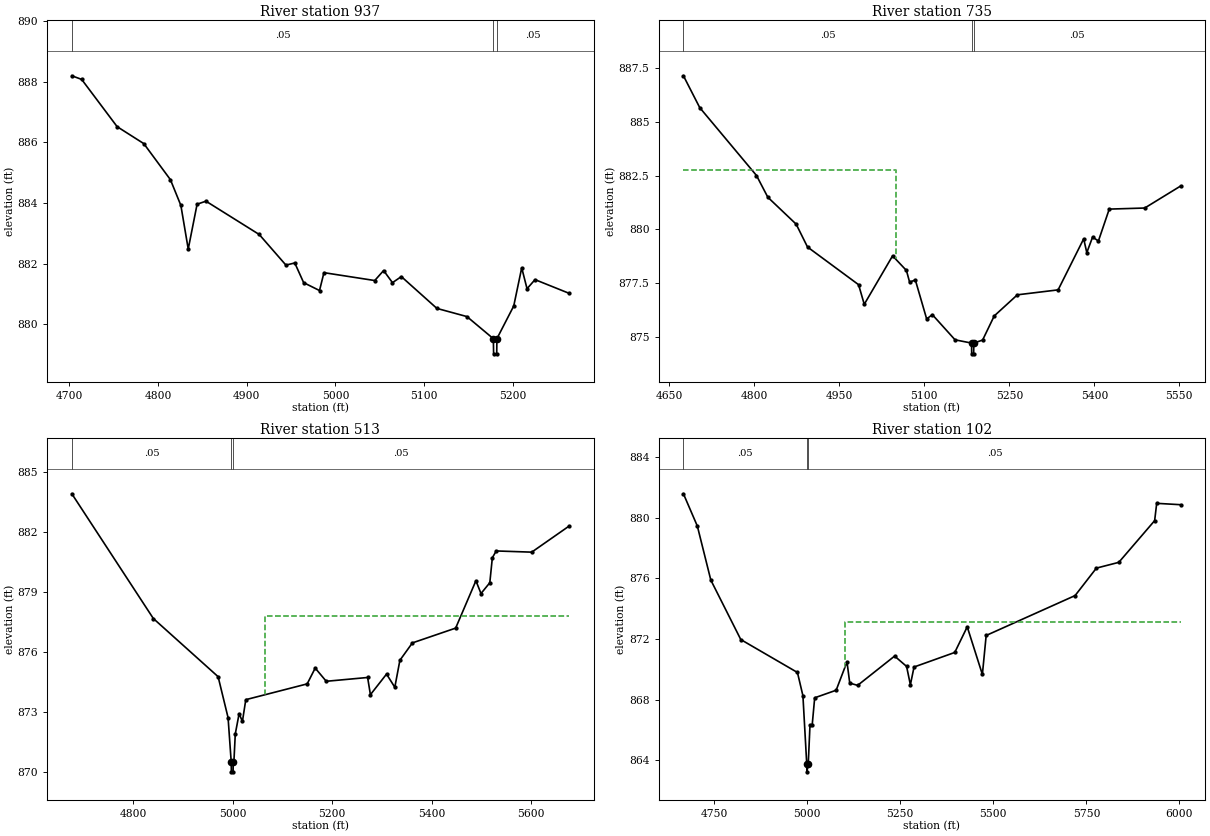
Type RM Length L Ch R = 1,937,202,202,202
BEGIN DESCRIPTION:
Mapping XS 91002283
END DESCRIPTION:
XS GIS Cut Line= 3
      2289070.03      7122717.62      2288613.58      7122745.78
      2288556.09      7122831.82
#Sta/Elev= 30
  4702.7  888.20  4713.8  888.08  4753.8  886.52  4783.9  885.96  4813.9  884.77
  4825.7  883.92  4834.0  882.48  4844.0  883.96  4854.0  884.06  4914.1  882.96
  4944.2  881.95  4954.2  882.02  4964.2  881.37  4982.1  881.11  4987.1  881.70
  5044.4  881.44  5054.4  881.77  5064.4  881.37  5074.4  881.57  5114.5  880.52
  5148.4  880.25  5178.2  879.52  5178.5  879.02  5182.0  879.02  5182.2  879.52
  5201.2  880.60  5210.2  881.86  5216.2  881.17  5225.2  881.47  5263.5  881.02
#Mann=3,-1,0
  4702.7    0.05       0  5178.2   0.033       0  5182.2    0.05       0
Bank Sta=5178.2,5182.2
Exp/Cntr=0.3,0.1

Type RM Length L Ch R = 1,735,222,222,222
BEGIN DESCRIPTION:
Mapping XS 2b3356a8
END DESCRIPTION:
XS GIS Cut Line= 4
      2289097.80      7122523.56      2288704.63      7122536.96
      2288607.50      7122543.69      2288529.33      7122921.94
#Sta/Elev= 30
  4675.1  887.13  4703.9  885.65  4804.0  882.50  4824.0  881.49  4874.0  880.24
  4894.0  879.18  4984.1  877.43  4994.1  876.52  5044.1  878.77  5068.5  878.09
  5074.1  877.55  5084.2  877.65  5104.2  875.84  5114.2  876.04  5154.3  874.87
  5183.4  874.72  5183.6  874.22  5187.1  874.22  5187.4  874.72  5202.9  874.86
  5223.4  875.98  5264.2  876.96  5336.1  877.19  5381.2  879.56  5386.7  878.92
  5396.9  879.64  5407.2  879.46  5426.3  880.94  5488.9  880.99  5552.1  882.01
#Mann=3,-1,0
  4675.1    0.05       0  5183.4   0.033       0  5187.4    0.05       0
#XS Ineff=2,0
    0.00 5050.00  882.75               0
Permanent Ineff=
       F       F
Bank Sta=5183.4,5187.4
Exp/Cntr=0.3,0.1

Type RM Length L Ch R = 1,513,411,411,411
BEGIN DESCRIPTION:
Mapping XS a8d37c92
END DESCRIPTION:
XS GIS Cut Line= 5
      2289072.55      7122302.03      2288747.29      7122314.18
      2288699.98      7122354.12      2288597.70      7122553.21
      2288524.36      7122933.48
#Sta/Elev= 30
  4677.3  883.91  4841.0  877.67  4971.1  874.76  4991.1  872.71  4997.4  870.50
  4997.7  870.00  5001.2  870.00  5001.4  870.50  5002.8  870.50  5005.6  871.90
  5013.3  872.91  5019.9  872.52  5026.7  873.61  5150.0  874.40  5166.1  875.19
  5188.3  874.53  5271.4  874.72  5277.0  873.86  5309.4  874.89  5326.0  874.23
  5336.2  875.58  5361.3  876.45  5448.2  877.19  5488.9  879.56  5499.1  878.92
  5516.8  879.46  5521.9  880.71  5529.7  881.05  5601.0  880.99  5675.8  882.29
#Mann=3,-1,0
  4677.3    0.05       0  4997.4   0.033       0  5001.4    0.05       0
#XS Ineff=2,0
       0                 5065.70    0.00  877.79
Permanent Ineff=
       F       F
Bank Sta=4997.4,5001.4
Exp/Cntr=0.3,0.1

Type RM Length L Ch R = 1,102,0,0,0
BEGIN DESCRIPTION:
MDE S 089 1.0
END DESCRIPTION:
XS GIS Cut Line= 4
      2289108.29      7122123.44      2288822.21      7121937.80
      2288687.10      7122023.04      2288530.92      7122843.02
#Sta/Elev= 30
  4667.5  881.57  4704.9  879.44  4741.1  875.88  4821.6  871.96  4973.8  869.79
  4988.5  868.26  4998.8  863.74  4999.1  863.24  5002.8  863.74  5007.5  866.32
  5013.4  866.32  5020.1  868.12  5077.8  868.62  5106.9  870.49  5114.3  869.09
  5135.5  868.94  5234.8  870.87  5267.0  870.19  5277.2  868.98  5287.0  870.15
  5396.4  871.11  5429.9  872.80  5470.6  869.66  5480.8  872.23  5719.7  874.86
  5776.9  876.67  5837.1  877.05  5933.4  879.80  5938.9  880.94  6003.0  880.85
#Mann=3,-1,0
  4667.5    0.05       0  4998.8   0.033       0  5002.8    0.05       0
#XS Ineff=2,0
       0                 5100.30    0.00  873.09
Permanent Ineff=
       F       F
Bank Sta=4998.8,5002.8
Exp/Cntr=0.3,0.1

Chan Stop Cuts=-1