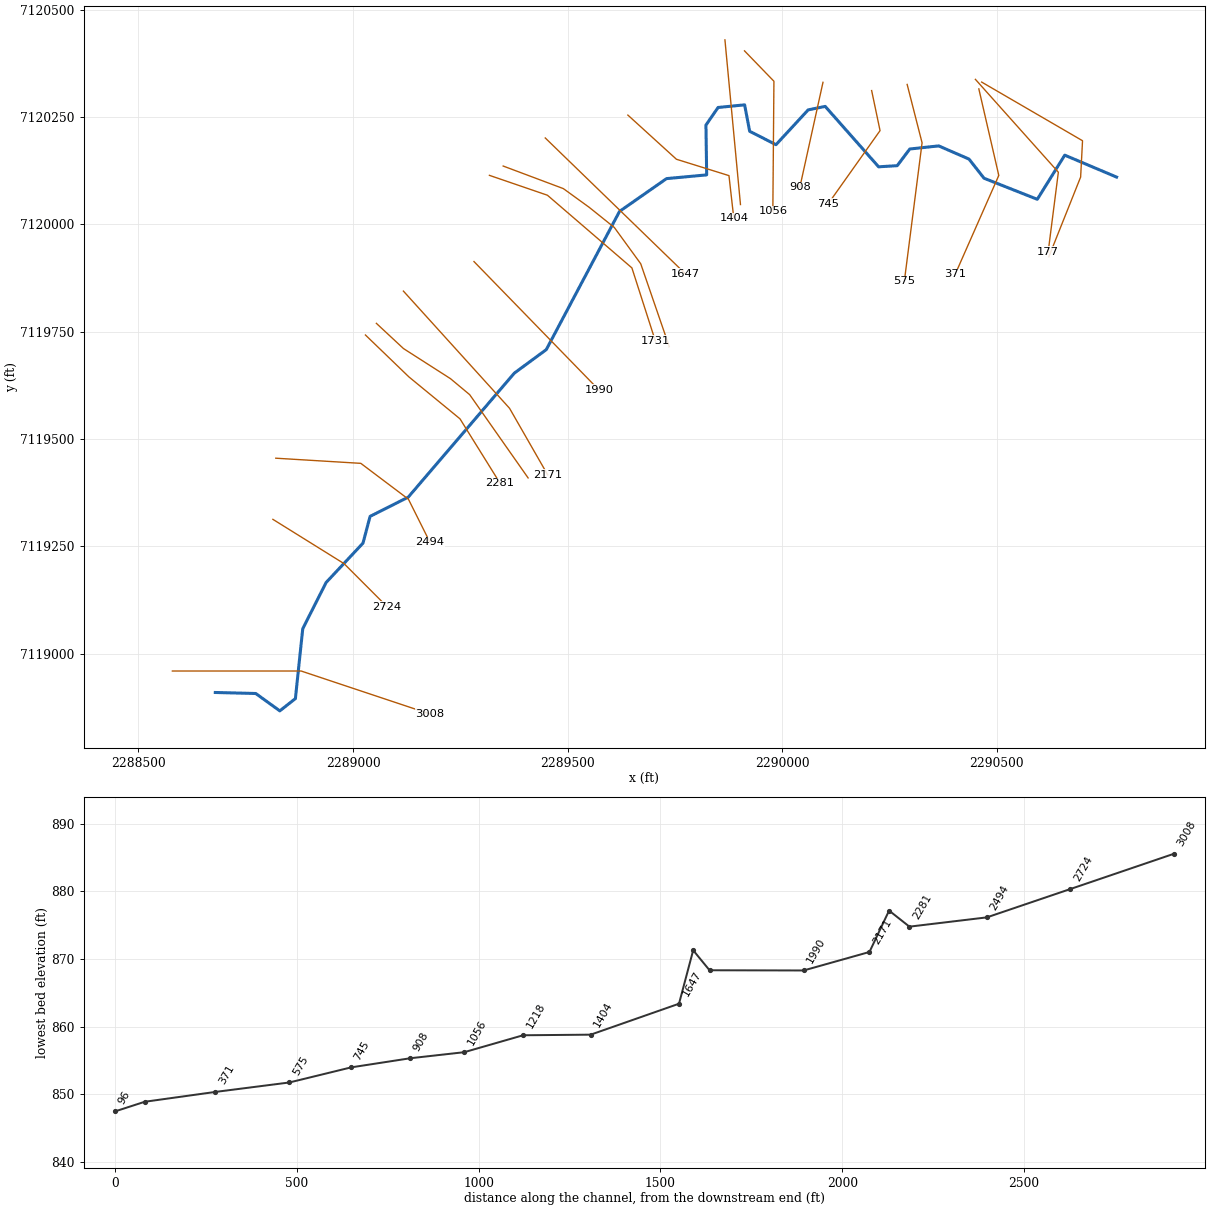
--- MDE S 090.prj (project) ---

Proj Title=MDE S 090 Base Level Engineering
Current Plan=p01
Default Exp/Contr=0.3,0.1
English Units
Geom File=g01
Flow File=f01
Plan File=p01
Y Axis Title=Elevation
X Axis Title(PF)=Main Channel Distance
X Axis Title(XS)=Station
BEGIN DESCRIPTION:
MDE S 090
END DESCRIPTION:
DSS Export Rating Curves= 0
DSS Export Rating Curve Sorted= 0
DSS Export Volume Flow Curves= 0
DXF OffsetX= 0
DXF OffsetY= 0
DXF ScaleX= 1
DXF ScaleY= 10

--- MDE S 090.p01 (plan) ---

Plan Title=Multiple Run
Short Identifier=Multiple
Geom File=g01
Flow File=f01
Subcritical Flow
K Sum by GR= 0
Std Step Tol= 0.01
Critical Tol= 0.01
Num of Std Step Trials= 20
Max Error Tol= 0.3
Flow Tol Ratio= 0.001
Split Flow NTrial= 30
Split Flow Tol= 0.02
Split Flow Ratio= 0.02
Log Output Level= 0
Friction Slope Method= 1
Unsteady Friction Slope Method= 2
Unsteady Bridges Friction Slope Method= 1
Parabolic Critical Depth
Global Vel Dist=  1 , 1 , 1
Global Log Level= 0
CheckData=True
Encroach Param= -1, 0, 0, 0
BEGIN DESCRIPTION:
Multiple Run
END DESCRIPTION:

--- MDE S 090.f01 (steady flow) ---

Flow Title=Multiple
Number of Profiles=7
Profile Names=10-year,25-year,50-year,1pct_min,100-year,1pct_plu,500-year
River Rch & RM= MDE S 090,Reach-1,3008
     257     336     398     235     470     937     653
Boundary for River Rch & Prof#=MDE S 090,Reach-1,1
Up Type=0
Dn Type=3
Dn Slope=0.005
Boundary for River Rch & Prof#=MDE S 090,Reach-1,2
Up Type=0
Dn Type=3
Dn Slope=0.005
Boundary for River Rch & Prof#=MDE S 090,Reach-1,3
Up Type=0
Dn Type=3
Dn Slope=0.005
Boundary for River Rch & Prof#=MDE S 090,Reach-1,4
Up Type=0
Dn Type=3
Dn Slope=0.005
Boundary for River Rch & Prof#=MDE S 090,Reach-1,5
Up Type=0
Dn Type=3
Dn Slope=0.005
Boundary for River Rch & Prof#=MDE S 090,Reach-1,6
Up Type=0
Dn Type=3
Dn Slope=0.005
Boundary for River Rch & Prof#=MDE S 090,Reach-1,7
Up Type=0
Dn Type=3
Dn Slope=0.005

--- MDE S 090.g01 (geometry) ---

Geom Title=Existing Conditions

River Reach=MDE S 090,Reach-1
Reach XY= 30
      2288679.00      7118910.00      2288773.24      7118907.65
      2288829.35      7118867.16      2288865.64      7118895.87
      2288882.76      7119058.44      2288937.16      7119166.05
      2289023.12      7119257.74      2289039.65      7119320.00
      2289128.60      7119364.86      2289375.83      7119653.65
      2289450.18      7119708.28      2289620.80      7120030.03
      2289730.33      7120106.45      2289823.89      7120115.12
      2289822.21      7120231.10      2289850.46      7120272.08
      2289912.35      7120278.20      2289924.06      7120216.72
      2289985.40      7120185.44      2290060.41      7120266.48
      2290100.09      7120274.58      2290224.47      7120133.95
      2290267.90      7120136.58      2290297.10      7120175.37
      2290364.53      7120182.64      2290435.12      7120151.92
      2290470.14      7120107.34      2290594.24      7120058.28
      2290658.26      7120161.06      2290779.00      7120110.00

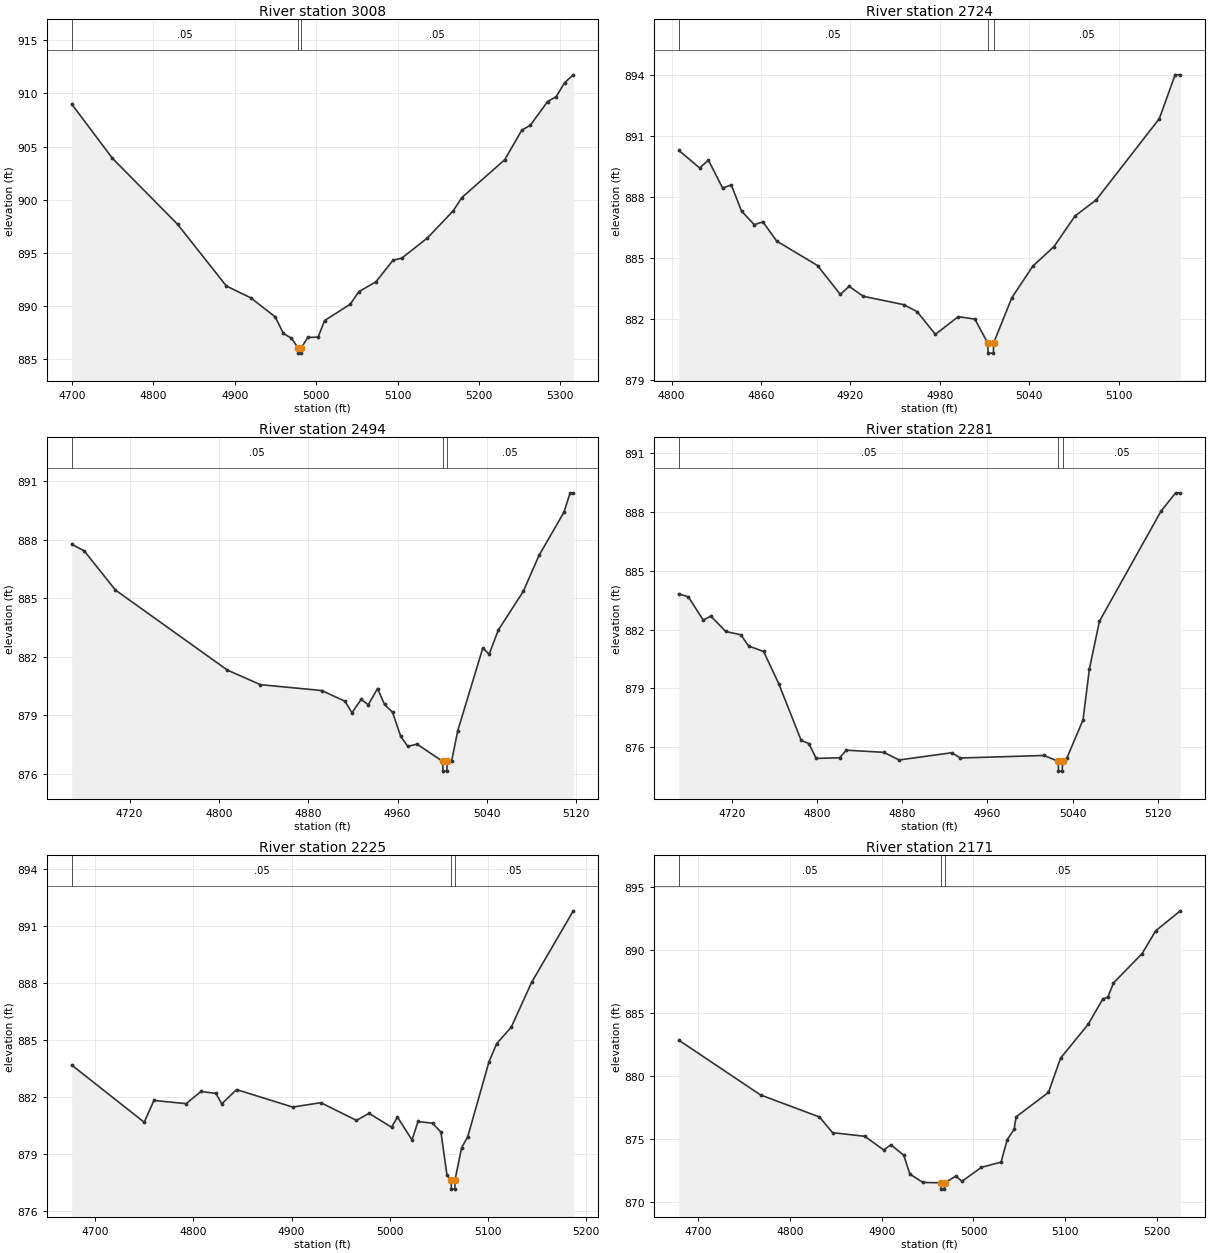
Type RM Length L Ch R = 1,3008,284,284,284
BEGIN DESCRIPTION:
MDE S 090 5.0
END DESCRIPTION:
XS GIS Cut Line= 3
      2288578.98      7118960.00      2288879.00      7118960.00
      2289178.96      7118860.01
#Sta/Elev= 30
  4699.6  909.00  4749.6  903.89  4829.6  897.67  4889.6  891.85  4919.6  890.73
  4949.6  888.94  4959.6  887.38  4969.6  886.92  4977.6  886.02  4977.9  885.52
  4981.4  885.52  4981.6  886.02  4989.6  887.00  5002.3  887.03  5010.2  888.59
  5041.8  890.13  5052.3  891.31  5073.4  892.25  5094.5  894.29  5105.0  894.47
  5136.6  896.38  5168.3  898.94  5178.8  900.18  5231.5  903.75  5252.6  906.54
  5263.1  907.01  5284.2  909.24  5294.8  909.70  5305.3  911.03  5315.8  911.76
#Mann=3,-1,0
  4699.6    0.05       0  4977.6   0.033       0  4981.6    0.05       0
Bank Sta=4977.6,4981.6
Exp/Cntr=0.3,0.1

Type RM Length L Ch R = 1,2724,230,230,230
BEGIN DESCRIPTION:
MDE S 090 4.0
END DESCRIPTION:
XS GIS Cut Line= 3
      2288813.24      7119313.10      2288979.00      7119210.00
      2289078.98      7119110.02
#Sta/Elev= 30
  4804.8  890.28  4818.8  889.42  4824.7  889.80  4834.2  888.43  4840.0  888.59
  4846.9  887.30  4855.4  886.64  4861.3  886.77  4870.5  885.83  4897.9  884.63
  4913.2  883.21  4919.1  883.61  4928.6  883.12  4955.7  882.71  4964.7  882.37
  4977.0  881.25  4992.3  882.12  5003.5  882.00  5012.1  880.83  5012.4  880.33
  5015.9  880.33  5016.1  880.83  5028.3  883.05  5042.4  884.60  5056.6  885.56
  5070.7  887.06  5084.9  887.85  5127.3  891.84  5137.9  893.99  5141.4  893.99
#Mann=3,-1,0
  4804.8    0.05       0  5012.1   0.033       0  5016.1    0.05       0
Bank Sta=5012.1,5016.1
Exp/Cntr=0.3,0.1

Type RM Length L Ch R = 1,2494,213,213,213
BEGIN DESCRIPTION:
MDE S 090 3.0
END DESCRIPTION:
XS GIS Cut Line= 4
      2288819.96      7119455.49      2289018.06      7119443.50
      2289129.00      7119360.00      2289178.99      7119260.02
#Sta/Elev= 30
  4668.2  887.76  4679.3  887.43  4707.3  885.42  4807.5  881.32  4837.2  880.57
  4892.0  880.27  4912.9  879.72  4919.1  879.13  4927.4  879.82  4933.7  879.54
  4942.0  880.37  4948.3  879.56  4955.5  879.15  4962.8  877.92  4969.1  877.41
  4977.4  877.52  5000.4  876.64  5000.6  876.14  5004.1  876.14  5004.4  876.64
  5008.3  876.64  5013.9  878.22  5036.3  882.45  5041.9  882.13  5050.2  883.37
  5072.6  885.36  5086.6  887.19  5108.9  889.40  5114.5  890.40  5117.3  890.40
#Mann=3,-1,0
  4668.2    0.05       0  5000.4   0.033       0  5004.4    0.05       0
Bank Sta=5000.4,5004.4
Exp/Cntr=0.3,0.1

Type RM Length L Ch R = 1,2281,56,56,56
BEGIN DESCRIPTION:
Mapping XS a8faa5b5
END DESCRIPTION:
XS GIS Cut Line= 4
      2289028.82      7119742.34      2289130.22      7119644.68
      2289249.11      7119547.17      2289342.32      7119397.46
#Sta/Elev= 30
  4670.2  883.82  4679.1  883.67  4693.2  882.48  4700.2  882.69  4714.3  881.90
  4728.5  881.73  4735.7  881.16  4749.8  880.88  4764.0  879.24  4785.1  876.34
  4792.3  876.18  4799.2  875.42  4821.1  875.45  4827.5  875.84  4862.7  875.73
  4877.0  875.34  4926.6  875.71  4934.5  875.44  5013.1  875.57  5026.5  875.27
  5026.7  874.77  5030.2  874.77  5030.5  875.27  5034.4  875.42  5049.7  877.38
  5055.7  879.98  5065.1  882.42  5122.9  888.04  5136.7  888.98  5141.1  888.98
#Mann=3,-1,0
  4670.2    0.05       0  5026.5   0.033       0  5030.5    0.05       0
Bank Sta=5026.5,5030.5
Exp/Cntr=0.3,0.1

Type RM Length L Ch R = 1,2225,54,54,54
BEGIN DESCRIPTION:
Mapping XS f0469584
END DESCRIPTION:
XS GIS Cut Line= 5
      2289054.32      7119769.44      2289117.48      7119710.74
      2289226.95      7119640.68      2289271.74      7119603.39
      2289407.85      7119409.58
#Sta/Elev= 30
  4675.9  883.67  4749.8  880.66  4759.7  881.81  4792.5  881.64  4807.7  882.28
  4822.9  882.18  4828.8  881.63  4844.0  882.38  4901.1  881.46  4929.8  881.69
  4966.2  880.76  4979.0  881.13  5001.9  880.40  5008.0  880.93  5022.8  879.73
  5028.9  880.70  5043.7  880.61  5052.3  880.14  5058.5  877.86  5062.7  877.64
  5062.9  877.14  5066.4  877.14  5066.7  877.64  5073.4  879.33  5079.5  879.88
  5101.2  883.83  5109.1  884.80  5123.9  885.66  5144.8  888.03  5187.2  891.79
#Mann=3,-1,0
  4675.9    0.05       0  5062.7   0.033       0  5066.7    0.05       0
Bank Sta=5062.7,5066.7
Exp/Cntr=0.3,0.1

Type RM Length L Ch R = 1,2171,181,181,181
BEGIN DESCRIPTION:
MDE S 090 2.0
END DESCRIPTION:
XS GIS Cut Line= 3
      2289117.30      7119844.55      2289364.60      7119571.70
      2289453.50      7119416.74
#Sta/Elev= 30
  4678.7  882.84  4767.8  878.50  4832.1  876.75  4846.3  875.51  4881.4  875.22
  4902.3  874.13  4909.8  874.55  4924.0  873.72  4930.7  872.22  4944.9  871.56
  4964.6  871.53  4964.8  871.03  4968.3  871.03  4968.6  871.53  4980.8  872.06
  4987.5  871.65  5008.7  872.76  5030.1  873.17  5036.8  874.96  5044.3  875.76
  5046.5  876.76  5081.8  878.70  5095.0  881.42  5125.0  884.09  5140.8  886.08
  5146.6  886.27  5152.7  887.38  5183.9  889.71  5198.8  891.52  5225.6  893.10
#Mann=3,-1,0
  4678.7    0.05       0  4964.6   0.033       0  4968.6    0.05       0
Bank Sta=4964.6,4968.6
Exp/Cntr=0.3,0.1

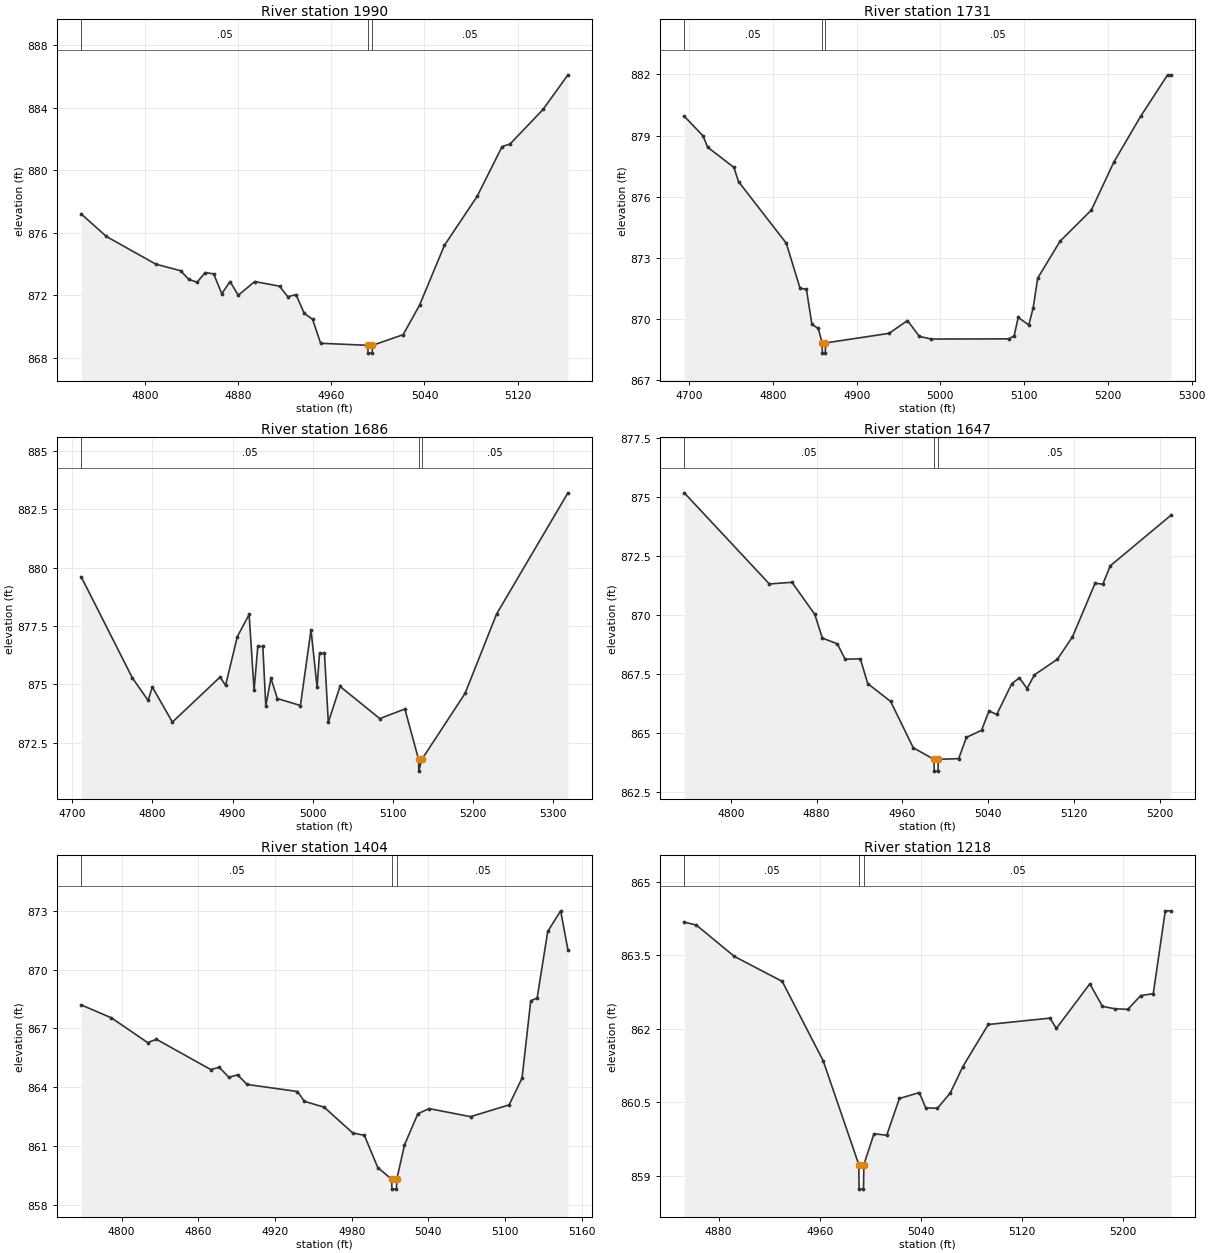
Type RM Length L Ch R = 1,1990,259,259,259
BEGIN DESCRIPTION:
Mapping XS f4944f07
END DESCRIPTION:
XS GIS Cut Line= 2
      2289281.75      7119913.30      2289573.10      7119614.13
#Sta/Elev= 30
  4745.5  877.20  4767.1  875.76  4809.5  873.99  4830.8  873.57  4837.8  873.01
  4844.9  872.84  4851.9  873.45  4859.1  873.37  4866.1  872.10  4873.2  872.88
  4880.2  872.00  4894.4  872.88  4915.7  872.58  4922.7  871.91  4929.8  872.04
  4936.8  870.85  4944.0  870.46  4950.9  868.93  4991.4  868.80  4991.6  868.30
  4995.1  868.30  4995.4  868.80  5021.7  869.48  5035.8  871.37  5057.1  875.19
  5085.2  878.33  5106.6  881.51  5113.5  881.68  5141.8  883.89  5163.1  886.10
#Mann=3,-1,0
  4745.5    0.05       0  4991.4   0.033       0  4995.4    0.05       0
Bank Sta=4991.4,4995.4
Exp/Cntr=0.3,0.1

Type RM Length L Ch R = 1,1731,45,45,45
BEGIN DESCRIPTION:
Mapping XS eaa10c8e
END DESCRIPTION:
XS GIS Cut Line= 4
      2289317.67      7120114.07      2289452.93      7120067.73
      2289649.69      7119898.56      2289704.35      7119728.49
#Sta/Elev= 30
  4694.2  879.95  4716.7  878.98  4722.1  878.43  4753.4  877.44  4759.0  876.74
  4816.0  873.72  4832.5  871.50  4840.0  871.47  4846.6  869.74  4854.2  869.54
  4858.8  868.83  4859.1  868.33  4862.6  868.33  4862.8  868.83  4938.7  869.30
  4960.7  869.93  4974.9  869.15  4989.2  869.02  5081.4  869.03  5088.0  869.17
  5092.9  870.08  5105.6  869.71  5110.8  870.56  5116.2  872.01  5142.9  873.82
  5180.3  875.35  5207.1  877.70  5239.2  879.95  5271.3  881.98  5275.3  881.96
#Mann=3,-1,0
  4694.2    0.05       0  4858.8   0.033       0  4862.8    0.05       0
Bank Sta=4858.8,4862.8
Exp/Cntr=0.3,0.1

Type RM Length L Ch R = 1,1686,39,39,39
BEGIN DESCRIPTION:
Mapping XS eeffcd04
END DESCRIPTION:
XS GIS Cut Line= 6
      2289349.79      7120135.72      2289489.94      7120083.20
      2289550.20      7120039.59      2289608.69      7119992.74
      2289670.26      7119908.18      2289736.55      7119715.84
#Sta/Elev= 30
  4711.2  879.60  4775.0  875.27  4794.6  874.31  4799.9  874.88  4824.9  873.38
  4884.4  875.31  4891.2  874.95  4905.9  877.04  4920.6  877.99  4926.8  874.74
  4931.4  876.62  4937.7  876.62  4941.4  874.07  4947.8  875.26  4955.8  874.39
  4984.6  874.09  4997.8  877.33  5005.4  874.87  5008.4  876.32  5014.6  876.32
  5019.4  873.37  5034.0  874.91  5083.6  873.53  5114.9  873.94  5132.0  871.78
  5132.3  871.28  5136.0  871.78  5190.0  874.61  5229.3  878.01  5318.3  883.20
#Mann=3,-1,0
  4711.2    0.05       0  5132.0   0.033       0  5136.0    0.05       0
Bank Sta=5132,5136
Exp/Cntr=0.3,0.1

Type RM Length L Ch R = 1,1647,243,243,243
BEGIN DESCRIPTION:
Mapping XS fb815e68
END DESCRIPTION:
XS GIS Cut Line= 2
      2289447.84      7120201.06      2289774.04      7119885.00
#Sta/Elev= 30
  4756.5  875.18  4835.9  871.32  4857.0  871.39  4878.3  870.03  4885.3  869.03
  4899.4  868.78  4906.6  868.13  4920.8  868.15  4927.7  867.10  4949.1  866.34
  4970.2  864.38  4989.5  863.89  4989.8  863.39  4993.3  863.39  4993.5  863.89
  5012.6  863.92  5019.8  864.82  5033.9  865.12  5040.9  865.94  5048.1  865.79
  5062.2  867.10  5069.2  867.34  5076.4  866.89  5083.3  867.47  5104.7  868.13
  5118.8  869.08  5139.9  871.35  5147.1  871.31  5154.1  872.09  5210.7  874.23
#Mann=3,-1,0
  4756.5    0.05       0  4989.5   0.033       0  4993.5    0.05       0
Bank Sta=4989.5,4993.5
Exp/Cntr=0.3,0.1

Type RM Length L Ch R = 1,1404,186,186,186
BEGIN DESCRIPTION:
Mapping XS be96a36f
END DESCRIPTION:
XS GIS Cut Line= 4
      2289640.32      7120254.34      2289753.43      7120151.53
      2289875.83      7120113.42      2289887.08      7120014.30
#Sta/Elev= 30
  4768.4  868.20  4792.0  867.54  4820.4  866.28  4827.2  866.45  4869.7  864.91
  4876.5  865.02  4883.9  864.51  4890.7  864.64  4898.1  864.15  4937.6  863.79
  4943.0  863.29  4958.5  862.99  4980.8  861.68  4989.9  861.56  5000.4  859.92
  5011.3  859.32  5011.5  858.82  5015.0  858.82  5015.3  859.32  5021.3  861.07
  5031.8  862.66  5040.6  862.92  5073.0  862.51  5103.2  863.11  5113.3  864.47
  5120.1  868.41  5125.1  868.55  5133.4  871.94  5143.5  872.99  5149.2  871.00
#Mann=3,-1,0
  4768.4    0.05       0  5011.3   0.033       0  5015.3    0.05       0
Bank Sta=5011.3,5015.3
Exp/Cntr=0.3,0.1

Type RM Length L Ch R = 1,1218,162,162,162
BEGIN DESCRIPTION:
Mapping XS 96db91aa
END DESCRIPTION:
XS GIS Cut Line= 2
      2289866.46      7120429.46      2289902.65      7120046.06
#Sta/Elev= 28
  4852.9  864.18  4862.4  864.12  4892.5  863.48  4930.4  862.97  4962.8  861.35
  4991.0  859.23  4991.2  858.73  4994.7  858.73  4995.0  859.23  5003.0  859.86
  5013.1  859.83  5023.1  860.58  5038.9  860.70  5043.9  860.39  5053.2  860.38
  5063.3  860.69  5073.3  861.23  5093.4  862.09  5142.3  862.22  5147.3  862.01
  5173.8  862.92  5183.8  862.46  5193.9  862.41  5203.9  862.40  5214.0  862.68
  5224.0  862.72  5233.5  864.41  5238.0  864.41
#Mann=3,-1,0
  4852.9    0.05       0  4991.0   0.033       0  4995.0    0.05       0
Bank Sta=4991,4995
Exp/Cntr=0.3,0.1

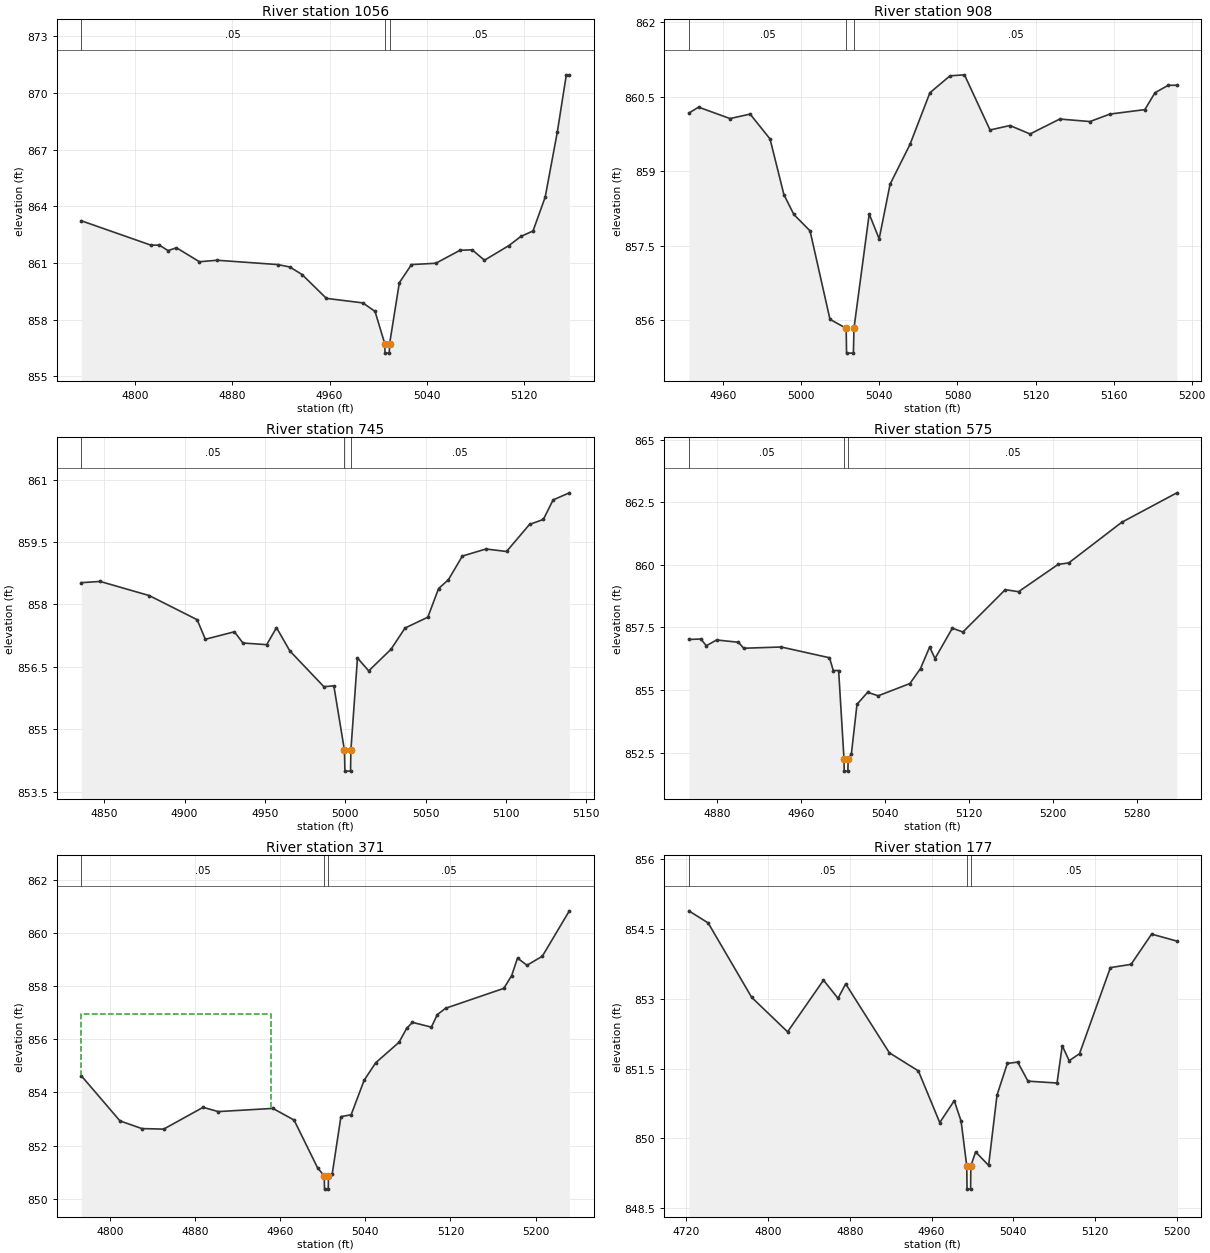
Type RM Length L Ch R = 1,1056,148,148,148
BEGIN DESCRIPTION:
Mapping XS ef2078d1
END DESCRIPTION:
XS GIS Cut Line= 3
      2289912.05      7120403.91      2289980.60      7120333.16
      2289978.07      7120030.09
#Sta/Elev= 30
  4755.7  863.24  4812.9  861.95  4819.9  861.95  4827.1  861.66  4834.0  861.81
  4852.9  861.07  4867.4  861.15  4917.4  860.92  4927.4  860.79  4937.4  860.39
  4957.4  859.13  4987.4  858.89  4997.4  858.44  5005.4  856.73  5005.6  856.23
  5009.1  856.23  5009.4  856.73  5017.4  859.96  5027.4  860.92  5047.4  860.99
  5067.4  861.68  5077.4  861.70  5087.4  861.15  5107.4  861.92  5117.4  862.41
  5127.4  862.70  5137.4  864.49  5147.4  867.94  5154.8  870.97  5157.3  870.97
#Mann=3,-1,0
  4755.7    0.05       0  5005.4   0.033       0  5009.4    0.05       0
Bank Sta=5005.4,5009.4
Exp/Cntr=0.3,0.1

Type RM Length L Ch R = 1,908,163,163,163
BEGIN DESCRIPTION:
Mapping XS 8f2be3df
END DESCRIPTION:
XS GIS Cut Line= 2
      2290094.91      7120330.65      2290041.03      7120086.52
#Sta/Elev= 30
  4942.4  860.17  4947.4  860.29  4963.5  860.06  4973.8  860.15  4984.0  859.65
  4991.1  858.53  4996.2  858.13  5004.5  857.80  5014.7  856.02  5023.0  855.84
  5023.2  855.34  5026.7  855.34  5027.0  855.84  5034.8  858.14  5039.9  857.64
  5045.5  858.74  5055.7  859.54  5065.9  860.58  5076.2  860.92  5083.6  860.94
  5096.7  859.83  5106.9  859.92  5117.2  859.75  5132.4  860.05  5147.9  860.00
  5158.1  860.15  5176.0  860.24  5181.2  860.58  5188.0  860.73  5192.4  860.73
#Mann=3,-1,0
  4942.4    0.05       0  5023.0    0.04       0  5027.0    0.05       0
Bank Sta=5023,5027
Exp/Cntr=0.3,0.1

Type RM Length L Ch R = 1,745,170,170,170
BEGIN DESCRIPTION:
Mapping XS 56764955
END DESCRIPTION:
XS GIS Cut Line= 3
      2290208.29      7120311.43      2290227.88      7120218.19
      2290107.23      7120048.12
#Sta/Elev= 30
  4835.7  858.52  4847.4  858.55  4878.0  858.21  4907.8  857.63  4912.9  857.16
  4931.0  857.34  4936.3  857.07  4951.1  857.03  4957.2  857.44  4965.5  856.88
  4986.7  856.02  4992.9  856.04  4999.5  854.49  4999.8  853.99  5003.3  853.99
  5003.5  854.49  5007.6  856.71  5014.6  856.40  5028.5  856.92  5037.2  857.43
  5051.4  857.69  5058.1  858.38  5064.2  858.59  5072.9  859.16  5087.6  859.33
  5100.4  859.27  5114.7  859.92  5123.3  860.04  5129.4  860.51  5139.5  860.68
#Mann=3,-1,0
  4835.7    0.05       0  4999.5    0.04       0  5003.5    0.05       0
Bank Sta=4999.5,5003.5
Exp/Cntr=0.3,0.1

Type RM Length L Ch R = 1,575,204,204,204
BEGIN DESCRIPTION:
Mapping XS 62930cc8
END DESCRIPTION:
XS GIS Cut Line= 3
      2290291.05      7120325.70      2290325.79      7120189.74
      2290284.52      7119867.81
#Sta/Elev= 30
  4853.1  857.02  4864.6  857.04  4869.7  856.77  4879.6  857.00  4900.3  856.91
  4905.4  856.67  4941.1  856.72  4987.1  856.29  4990.7  855.78  4995.8  855.78
  5000.9  852.26  5001.1  851.76  5004.6  851.76  5004.9  852.26  5007.9  852.43
  5013.3  854.43  5023.4  854.91  5033.5  854.77  5063.7  855.26  5073.8  855.86
  5082.5  856.72  5087.6  856.26  5104.1  857.47  5114.2  857.32  5154.5  859.01
  5167.2  858.93  5204.9  860.02  5215.0  860.08  5265.4  861.70  5318.0  862.88
#Mann=3,-1,0
  4853.1    0.05       0  5000.9    0.04       0  5004.9    0.05       0
Bank Sta=5000.9,5004.9
Exp/Cntr=0.3,0.1

Type RM Length L Ch R = 1,371,194,194,194
BEGIN DESCRIPTION:
Mapping XS 8c8477de
END DESCRIPTION:
XS GIS Cut Line= 3
      2290458.04      7120315.40      2290504.56      7120113.87
      2290402.93      7119883.63
#Sta/Elev= 30
  4773.2  854.63  4809.5  852.93  4830.1  852.64  4850.6  852.62  4887.6  853.44
  4901.9  853.28  4953.2  853.40  4973.1  852.96  4995.2  851.16  5001.4  850.86
  5001.7  850.36  5005.2  850.36  5005.4  850.86  5008.9  850.93  5017.1  853.09
  5026.7  853.16  5038.9  854.46  5049.8  855.12  5071.7  855.89  5078.8  856.41
  5084.3  856.64  5102.1  856.46  5107.6  856.93  5115.4  857.17  5170.1  857.92
  5177.5  858.40  5183.0  859.06  5191.9  858.79  5206.3  859.13  5231.7  860.84
#Mann=3,-1,0
  4773.2    0.05       0  5001.4    0.04       0  5005.4    0.05       0
#XS Ineff=2,0
    0.00 4951.50  856.97               0
Permanent Ineff=
       F       F
Bank Sta=5001.4,5005.4
Exp/Cntr=0.3,0.1

Type RM Length L Ch R = 1,177,81,81,81
BEGIN DESCRIPTION:
Mapping XS 9706e8f0
END DESCRIPTION:
XS GIS Cut Line= 3
      2290450.06      7120337.54      2290643.32      7120121.37
      2290619.56      7119935.54
#Sta/Elev= 30
  4722.6  854.89  4741.5  854.63  4784.1  853.03  4819.2  852.29  4854.3  853.40
  4868.5  853.01  4876.0  853.32  4918.7  851.84  4947.1  851.45  4968.0  850.34
  4982.2  850.81  4988.9  850.37  4994.4  849.41  4994.7  848.91  4998.2  848.91
  4998.4  849.41  5003.1  849.71  5015.8  849.42  5024.0  850.93  5034.1  851.61
  5044.2  851.64  5054.3  851.23  5082.7  851.19  5087.8  851.99  5094.6  851.67
  5104.7  851.82  5134.9  853.67  5155.1  853.74  5175.2  854.39  5199.9  854.24
#Mann=3,-1,0
  4722.6    0.05       0  4994.4    0.04       0  4998.4    0.05       0
Bank Sta=4994.4,4998.4
Exp/Cntr=0.3,0.1

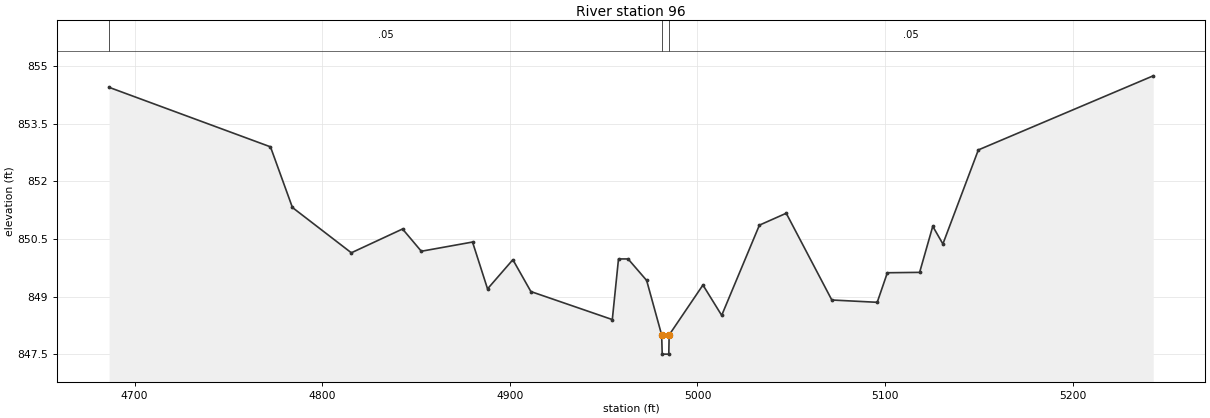
Type RM Length L Ch R = 1,96,0,0,0
BEGIN DESCRIPTION:
MDE S 090 1.0
END DESCRIPTION:
XS GIS Cut Line= 4
      2290464.63      7120331.22      2290699.65      7120194.66
      2290695.25      7120110.12      2290621.08      7119924.34
#Sta/Elev= 30
  4686.4  854.45  4772.4  852.90  4784.1  851.32  4815.5  850.14  4842.8  850.76
  4852.8  850.18  4880.1  850.42  4888.1  849.20  4901.6  849.96  4911.2  849.13
  4954.6  848.40  4957.9  849.98  4963.0  849.98  4972.9  849.42  4980.9  848.00
  4981.2  847.50  4984.7  847.50  4984.9  848.00  5002.9  849.30  5012.9  848.51
  5033.0  850.86  5047.3  851.17  5071.6  848.91  5095.8  848.85  5101.2  849.62
  5118.4  849.63  5125.4  850.83  5130.8  850.37  5149.7  852.82  5242.9  854.75
#Mann=3,-1,0
  4686.4    0.05       0  4980.9    0.04       0  4984.9    0.05       0
Bank Sta=4980.9,4984.9
Exp/Cntr=0.3,0.1

Chan Stop Cuts=-1