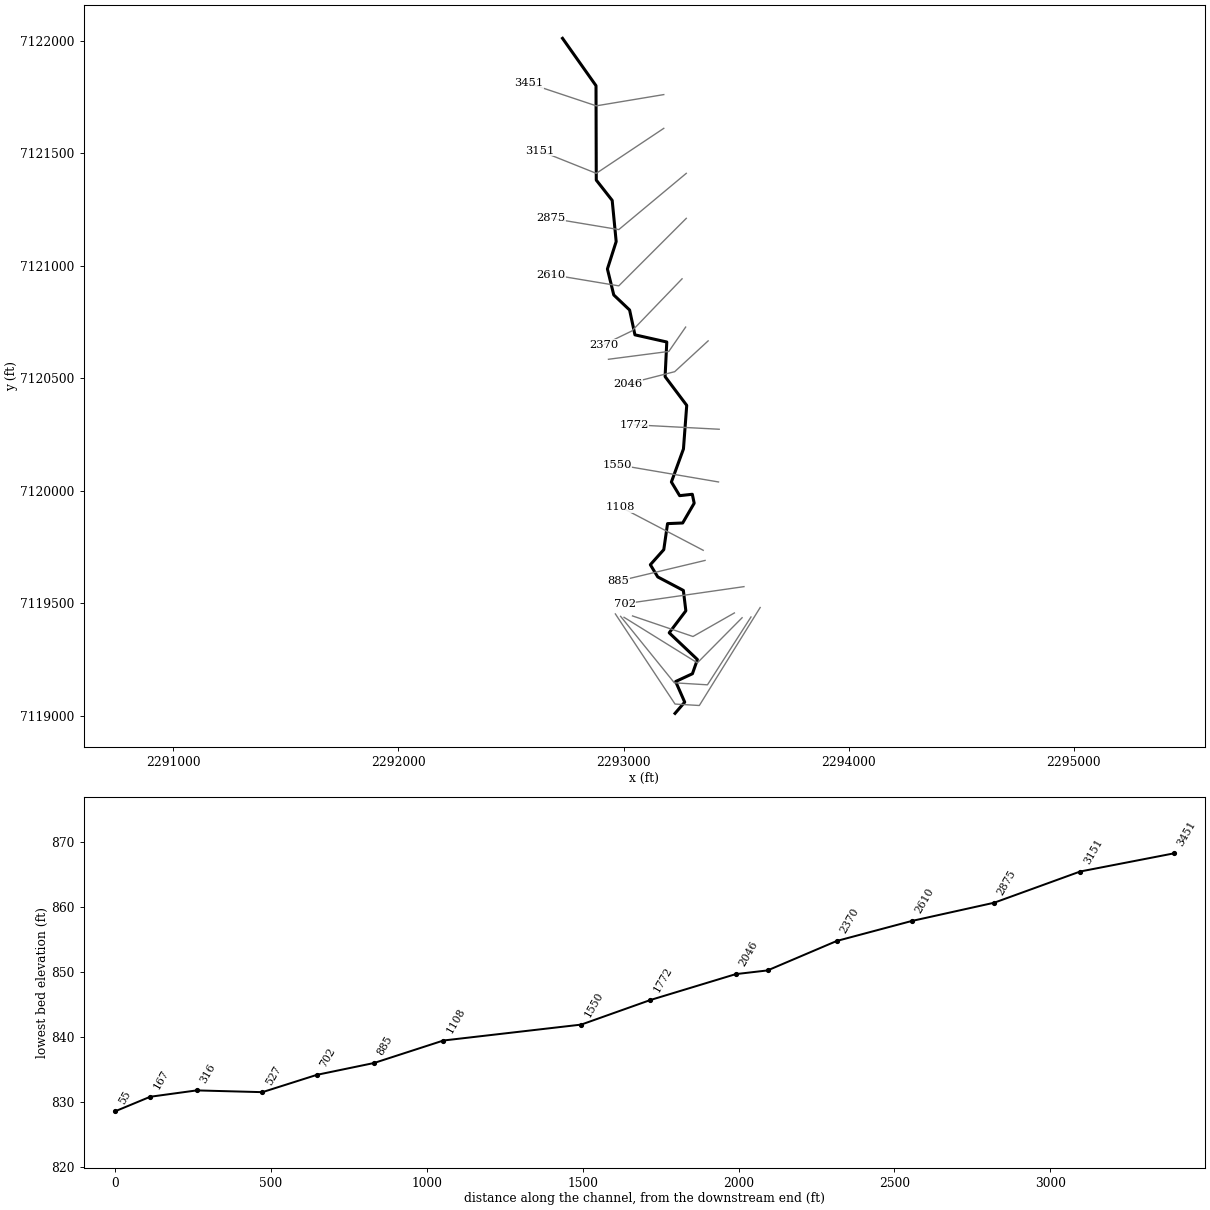
--- MDE S 091.prj (project) ---

Proj Title=MDE S 091 Base Level Engineering
Current Plan=p01
Default Exp/Contr=0.3,0.1
English Units
Geom File=g01
Flow File=f01
Plan File=p01
BEGIN DESCRIPTION:
MDE S 091
END DESCRIPTION:

--- MDE S 091.p01 (plan) ---

Plan Title=Multiple Run
Short Identifier=Multiple
Geom File=g01
Flow File=f01
Subcritical Flow
K Sum by GR= 0
Std Step Tol= 0.01
Critical Tol= 0.01
Num of Std Step Trials= 20
Max Error Tol= 0.3
Flow Tol Ratio= 0.001
Split Flow NTrial= 30
Split Flow Tol= 0.02
Split Flow Ratio= 0.02
Log Output Level= 0
Friction Slope Method= 1
Unsteady Friction Slope Method= 2
Unsteady Bridges Friction Slope Method= 1
Parabolic Critical Depth
Global Vel Dist=  1 , 1 , 1
Global Log Level= 0
CheckData=True
Encroach Param= -1, 0, 0, 0
BEGIN DESCRIPTION:
Multiple Run
END DESCRIPTION:

--- MDE S 091.f01 (steady flow) ---

Flow Title=Multiple
Number of Profiles=7
Profile Names=10-year,25-year,50-year,1pct_min,100-year,1pct_plu,500-year
River Rch & RM= MDE S 091,Reach-1,3451
     277     364     432     256     511    1019     713
Boundary for River Rch & Prof#=MDE S 091,Reach-1,1
Up Type=0
Dn Type=3
Dn Slope=0.008
Boundary for River Rch & Prof#=MDE S 091,Reach-1,2
Up Type=0
Dn Type=3
Dn Slope=0.008
Boundary for River Rch & Prof#=MDE S 091,Reach-1,3
Up Type=0
Dn Type=3
Dn Slope=0.008
Boundary for River Rch & Prof#=MDE S 091,Reach-1,4
Up Type=0
Dn Type=3
Dn Slope=0.008
Boundary for River Rch & Prof#=MDE S 091,Reach-1,5
Up Type=0
Dn Type=3
Dn Slope=0.008
Boundary for River Rch & Prof#=MDE S 091,Reach-1,6
Up Type=0
Dn Type=3
Dn Slope=0.008
Boundary for River Rch & Prof#=MDE S 091,Reach-1,7
Up Type=0
Dn Type=3
Dn Slope=0.008

--- MDE S 091.g01 (geometry) ---

Geom Title=Existing Conditions

River Reach=MDE S 091,Reach-1
Reach XY= 30
      2292729.00      7122010.00      2292877.80      7121799.50
      2292878.96      7121379.98      2292949.70      7121289.84
      2292967.42      7121106.80      2292928.51      7120984.96
      2292956.68      7120869.59      2293027.09      7120802.63
      2293050.84      7120692.27      2293192.34      7120660.45
      2293184.86      7120506.62      2293280.97      7120378.79
      2293266.41      7120185.09      2293212.84      7120038.29
      2293249.55      7119977.53      2293305.82      7119983.79
      2293314.12      7119943.99      2293263.01      7119856.15
      2293195.74      7119853.29      2293179.01      7119737.68
      2293119.28      7119670.60      2293152.25      7119616.36
      2293266.04      7119556.39      2293277.08      7119465.82
      2293203.09      7119368.02      2293328.46      7119249.31
      2293306.31      7119186.21      2293231.68      7119151.50
      2293272.03      7119059.92      2293229.00      7119010.00

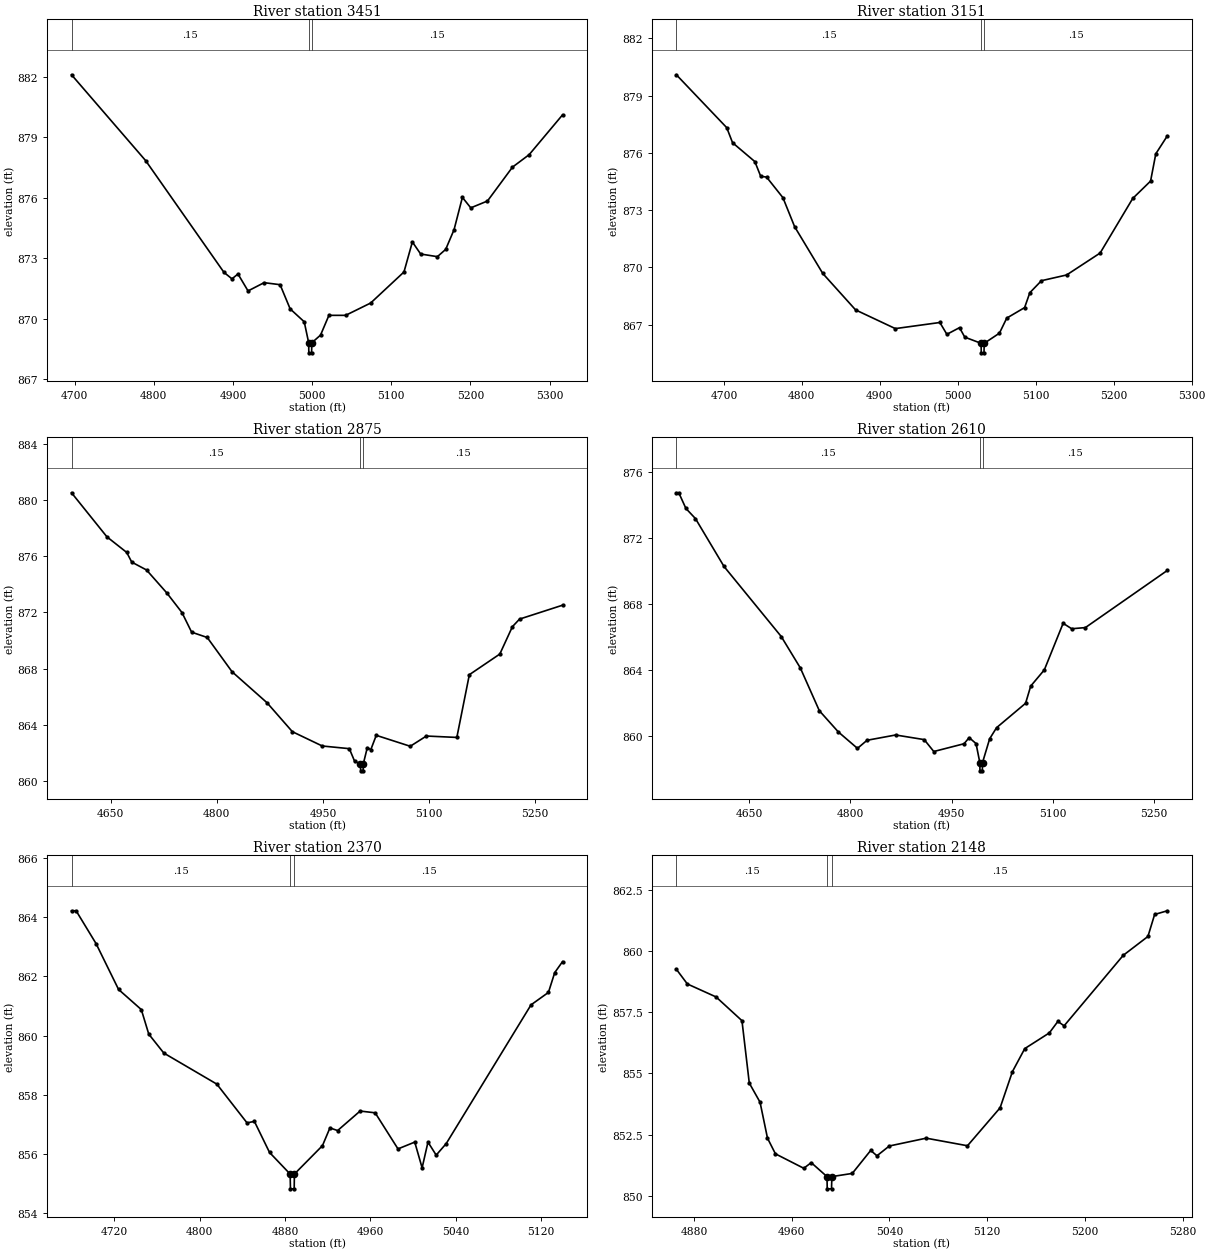
Type RM Length L Ch R = 1,3451,300,300,300
BEGIN DESCRIPTION:
MDE S 091 9.0
END DESCRIPTION:
XS GIS Cut Line= 3
      2293178.95      7121759.99      2292879.00      7121710.00
      2292579.02      7121809.99
#Sta/Elev= 30
  4696.0  882.10  4789.7  877.84  4888.6  872.30  4898.7  871.98  4906.3  872.22
  4919.0  871.38  4939.3  871.79  4959.5  871.69  4972.2  870.49  4990.0  869.85
  4995.6  868.81  4995.8  868.31  4999.3  868.31  4999.6  868.81  5010.6  869.19
  5021.2  870.17  5042.3  870.17  5073.9  870.78  5116.0  872.32  5126.6  873.81
  5137.1  873.21  5158.2  873.08  5168.7  873.44  5179.3  874.42  5189.8  876.02
  5200.4  875.50  5221.5  875.84  5253.1  877.52  5274.2  878.14  5316.3  880.11
#Mann=3,-1,0
  4696.0    0.15       0  4995.6    0.05       0  4999.6    0.15       0
Bank Sta=4995.6,4999.6
Exp/Cntr=0.3,0.1

Type RM Length L Ch R = 1,3151,276,276,276
BEGIN DESCRIPTION:
MDE S 091 8.0
END DESCRIPTION:
XS GIS Cut Line= 3
      2293179.00      7121610.00      2292879.00      7121410.00
      2292629.01      7121510.00
#Sta/Elev= 30
  4639.0  880.09  4703.6  877.32  4711.1  876.53  4739.7  875.54  4747.2  874.77
  4754.7  874.73  4775.7  873.65  4790.7  872.13  4826.8  869.68  4868.9  867.77
  4919.9  866.79  4977.0  867.11  4986.0  866.49  5002.2  866.84  5009.0  866.34
  5029.9  866.02  5030.1  865.52  5033.6  865.52  5033.9  866.02  5053.4  866.55
  5062.8  867.34  5085.7  867.89  5092.4  868.67  5107.3  869.30  5139.6  869.60
  5182.6  870.75  5224.4  873.61  5247.3  874.52  5254.0  875.95  5268.8  876.89
#Mann=3,-1,0
  4639.0    0.15       0  5029.9    0.05       0  5033.9    0.15       0
Bank Sta=5029.9,5033.9
Exp/Cntr=0.3,0.1

Type RM Length L Ch R = 1,2875,265,265,265
BEGIN DESCRIPTION:
MDE S 091 7.0
END DESCRIPTION:
XS GIS Cut Line= 3
      2293278.99      7121409.99      2292979.00      7121160.00
      2292679.04      7121209.99
#Sta/Elev= 30
  4594.4  880.52  4644.5  877.38  4672.5  876.27  4679.6  875.58  4700.5  875.02
  4729.1  873.39  4750.6  871.99  4764.3  870.59  4786.4  870.21  4821.5  867.77
  4871.0  865.56  4906.8  863.50  4949.1  862.48  4987.4  862.29  4995.0  861.38
  5003.2  861.21  5003.4  860.71  5006.9  860.71  5007.2  861.21  5012.8  862.36
  5017.8  862.22  5025.5  863.24  5073.6  862.46  5096.4  863.19  5139.5  863.09
  5157.2  867.56  5200.3  869.03  5218.1  870.98  5228.2  871.52  5289.0  872.51
#Mann=3,-1,0
  4594.4    0.15       0  5003.2    0.05       0  5007.2    0.15       0
Bank Sta=5003.2,5007.2
Exp/Cntr=0.3,0.1

Type RM Length L Ch R = 1,2610,240,240,240
BEGIN DESCRIPTION:
MDE S 091 6.0
END DESCRIPTION:
XS GIS Cut Line= 3
      2293279.01      7121210.01      2292979.00      7120910.00
      2292679.02      7120960.00
#Sta/Elev= 30
  4541.8  874.72  4545.4  874.72  4556.0  873.77  4570.1  873.16  4612.5  870.26
  4697.4  866.02  4725.7  864.12  4753.9  861.53  4782.2  860.24  4810.5  859.25
  4824.7  859.74  4867.1  860.06  4909.5  859.78  4923.7  859.06  4968.6  859.53
  4976.2  859.90  4986.4  859.54  4992.0  858.39  4992.2  857.89  4995.7  857.89
  4996.0  858.39  5006.6  859.83  5016.8  860.50  5059.9  861.98  5067.5  863.02
  5087.7  864.00  5115.6  866.82  5128.3  866.49  5148.6  866.56  5270.2  870.02
#Mann=3,-1,0
  4541.8    0.15       0  4992.0    0.05       0  4996.0    0.15       0
Bank Sta=4992,4996
Exp/Cntr=0.3,0.1

Type RM Length L Ch R = 1,2370,222,222,222
BEGIN DESCRIPTION:
Mapping XS 9474e1db
END DESCRIPTION:
XS GIS Cut Line= 3
      2293260.22      7120941.25      2293037.09      7120709.48
      2292912.45      7120649.12
#Sta/Elev= 30
  4679.9  864.22  4684.2  864.22  4702.9  863.11  4724.0  861.56  4745.3  860.88
  4752.3  860.05  4766.4  859.41  4816.1  858.36  4844.4  857.05  4851.3  857.10
  4865.5  856.05  4884.8  855.32  4885.1  854.82  4888.6  854.82  4888.8  855.32
  4915.1  856.28  4922.1  856.88  4929.3  856.79  4950.4  857.45  4964.5  857.39
  4985.9  856.17  5001.6  856.40  5008.5  855.53  5014.0  856.40  5021.7  855.96
  5031.1  856.35  5110.6  861.04  5126.9  861.46  5132.8  862.13  5140.1  862.50
#Mann=3,-1,0
  4679.9    0.15       0  4884.8    0.05       0  4888.8    0.15       0
Bank Sta=4884.8,4888.8
Exp/Cntr=0.3,0.1

Type RM Length L Ch R = 1,2148,102,102,102
BEGIN DESCRIPTION:
Mapping XS 7b2fc229
END DESCRIPTION:
XS GIS Cut Line= 3
      2293276.16      7120726.75      2293201.38      7120618.57
      2292933.25      7120583.71
#Sta/Elev= 30
  4865.6  859.25  4874.6  858.65  4898.1  858.12  4919.3  857.15  4925.3  854.60
  4934.1  853.82  4940.2  852.35  4946.7  851.71  4969.9  851.12  4976.0  851.35
  4988.9  850.78  4989.1  850.28  4992.6  850.28  4992.9  850.78  5009.6  850.91
  5024.7  851.85  5029.8  851.63  5039.9  852.03  5070.1  852.35  5103.9  852.04
  5130.6  853.59  5140.7  855.07  5150.8  856.01  5170.9  856.65  5177.9  857.12
  5183.0  856.94  5231.4  859.82  5251.6  860.59  5257.1  861.49  5267.5  861.64
#Mann=3,-1,0
  4865.6    0.15       0  4988.9    0.05       0  4992.9    0.15       0
Bank Sta=4988.9,4992.9
Exp/Cntr=0.3,0.1

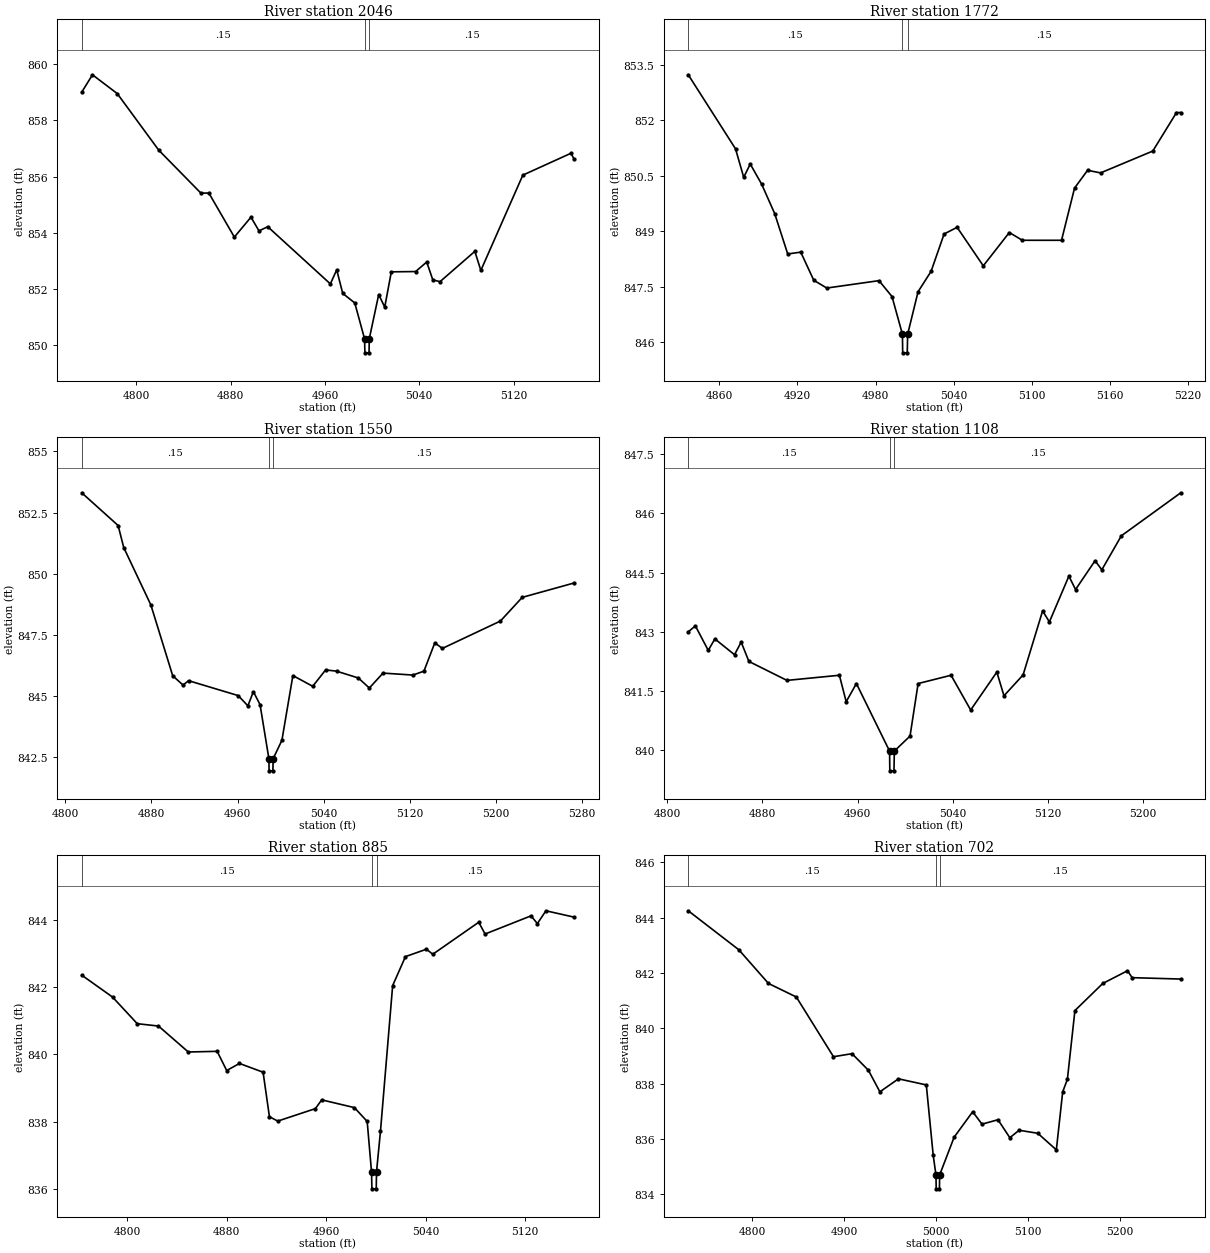
Type RM Length L Ch R = 1,2046,274,274,274
BEGIN DESCRIPTION:
Mapping XS 7d78b1ae
END DESCRIPTION:
XS GIS Cut Line= 3
      2293376.12      7120665.43      2293227.58      7120528.58
      2293018.74      7120474.94
#Sta/Elev= 30
  4753.8  859.01  4762.9  859.63  4783.9  858.96  4819.1  856.94  4854.8  855.41
  4861.6  855.41  4883.2  853.84  4897.3  854.55  4904.1  854.06  4911.5  854.21
  4964.6  852.17  4970.0  852.67  4975.1  851.83  4985.3  851.49  4993.6  850.21
  4993.9  849.71  4997.4  849.71  4997.6  850.21  5005.6  851.79  5010.7  851.34
  5016.3  852.60  5036.9  852.61  5046.3  852.95  5051.5  852.31  5057.6  852.25
  5087.1  853.33  5092.2  852.65  5127.8  856.05  5168.6  856.83  5171.4  856.61
#Mann=3,-1,0
  4753.8    0.15       0  4993.6    0.05       0  4997.6    0.15       0
Bank Sta=4993.6,4997.6
Exp/Cntr=0.3,0.1

Type RM Length L Ch R = 1,1772,222,222,222
BEGIN DESCRIPTION:
Mapping XS 15e971ce
END DESCRIPTION:
XS GIS Cut Line= 2
      2293425.27      7120272.71      2293047.49      7120292.52
#Sta/Elev= 30
  4836.1  853.23  4872.4  851.23  4878.7  850.46  4883.7  850.82  4892.4  850.28
  4902.5  849.48  4912.5  848.39  4922.5  848.44  4932.5  847.68  4942.5  847.47
  4982.6  847.67  4992.6  847.24  5000.6  846.22  5000.8  845.72  5004.3  845.72
  5004.6  846.22  5012.6  847.37  5022.6  847.92  5032.6  848.93  5042.6  849.11
  5062.7  848.07  5082.7  848.97  5092.7  848.76  5122.8  848.76  5132.8  850.17
  5142.8  850.65  5152.8  850.58  5192.9  851.17  5211.1  852.21  5214.4  852.21
#Mann=3,-1,0
  4836.1    0.15       0  5000.6    0.05       0  5004.6    0.15       0
Bank Sta=5000.6,5004.6
Exp/Cntr=0.3,0.1

Type RM Length L Ch R = 1,1550,442,442,442
BEGIN DESCRIPTION:
Mapping XS 3fba4cfe
END DESCRIPTION:
XS GIS Cut Line= 2
      2293422.27      7120038.44      2292971.37      7120115.26
#Sta/Elev= 30
  4815.3  853.31  4849.1  851.97  4854.3  851.07  4879.5  848.72  4899.8  845.82
  4909.4  845.44  4914.5  845.62  4960.6  845.01  4969.6  844.59  4974.7  845.17
  4980.9  844.64  4989.1  842.43  4989.3  841.93  4992.8  841.93  4993.1  842.43
  5001.2  843.18  5011.4  845.83  5029.8  845.39  5041.8  846.06  5051.9  846.01
  5072.2  845.73  5082.4  845.32  5095.1  845.93  5122.9  845.85  5133.1  846.01
  5143.2  847.17  5150.2  846.94  5204.1  848.06  5224.4  849.03  5272.7  849.62
#Mann=3,-1,0
  4815.3    0.15       0  4989.1    0.05       0  4993.1    0.15       0
Bank Sta=4989.1,4993.1
Exp/Cntr=0.3,0.1

Type RM Length L Ch R = 1,1108,223,223,223
BEGIN DESCRIPTION:
Mapping XS 3636d8a6
END DESCRIPTION:
XS GIS Cut Line= 2
      2293354.22      7119734.77      2292987.29      7119926.92
#Sta/Elev= 30
  4817.6  843.00  4823.6  843.15  4834.4  842.53  4840.0  842.82  4856.5  842.42
  4862.1  842.74  4868.6  842.25  4900.6  841.77  4944.7  841.90  4950.4  841.23
  4959.0  841.69  4986.9  839.98  4987.1  839.48  4990.6  839.48  4990.9  839.98
  5004.1  840.36  5010.9  841.69  5038.6  841.90  5055.1  841.02  5077.1  841.98
  5083.1  841.38  5099.2  841.91  5115.6  843.53  5121.3  843.25  5137.7  844.41
  5143.3  844.07  5159.7  844.80  5165.4  844.57  5181.8  845.43  5231.8  846.52
#Mann=3,-1,0
  4817.6    0.15       0  4986.9    0.05       0  4990.9    0.15       0
Bank Sta=4986.9,4990.9
Exp/Cntr=0.3,0.1

Type RM Length L Ch R = 1,885,183,183,183
BEGIN DESCRIPTION:
Mapping XS 30af5c33
END DESCRIPTION:
XS GIS Cut Line= 2
      2293362.50      7119689.70      2292976.82      7119597.71
#Sta/Elev= 30
  4763.2  842.35  4788.0  841.70  4807.9  840.91  4825.0  840.84  4849.0  840.07
  4872.2  840.09  4879.9  839.52  4890.2  839.73  4909.2  839.47  4914.3  838.15
  4921.0  838.02  4951.3  838.39  4956.4  838.65  4982.7  838.42  4993.0  838.01
  4996.5  836.51  4996.8  836.01  5000.3  836.01  5000.5  836.51  5003.7  837.72
  5013.5  842.04  5023.8  842.90  5040.7  843.12  5045.8  842.97  5082.8  843.92
  5087.9  843.57  5124.9  844.11  5130.0  843.88  5136.9  844.26  5159.7  844.07
#Mann=3,-1,0
  4763.2    0.15       0  4996.5    0.05       0  5000.5    0.15       0
Bank Sta=4996.5,5000.5
Exp/Cntr=0.3,0.1

Type RM Length L Ch R = 1,702,175,175,175
BEGIN DESCRIPTION:
Mapping XS 13d0d36e
END DESCRIPTION:
XS GIS Cut Line= 2
      2293535.38      7119573.27      2293004.94      7119496.99
#Sta/Elev= 30
  4730.2  844.25  4785.2  842.84  4817.5  841.62  4847.8  841.13  4888.2  838.97
  4908.4  839.08  4926.2  838.48  4938.7  837.70  4958.9  838.17  4989.2  837.95
  4996.7  835.41  4999.7  834.69  5000.0  834.19  5003.5  834.19  5003.7  834.69
  5019.5  836.06  5039.7  836.98  5049.8  836.53  5067.2  836.69  5080.1  836.04
  5090.2  836.31  5110.5  836.20  5130.7  835.60  5137.6  837.70  5142.7  838.15
  5150.9  840.64  5181.2  841.62  5208.1  842.08  5213.2  841.83  5266.1  841.78
#Mann=3,-1,0
  4730.2    0.15       0  4999.7    0.05       0  5003.7    0.15       0
Bank Sta=4999.7,5003.7
Exp/Cntr=0.3,0.1

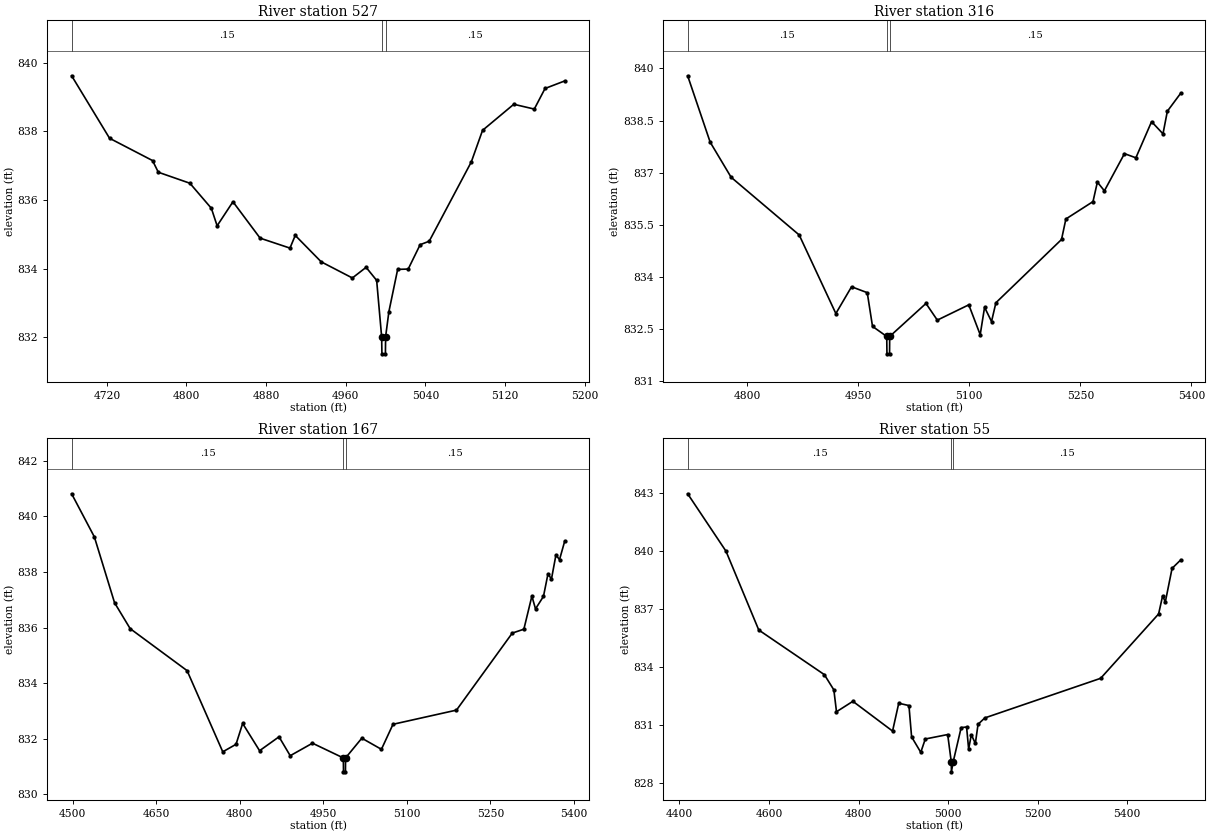
Type RM Length L Ch R = 1,527,211,211,211
BEGIN DESCRIPTION:
Mapping XS eeef3cab
END DESCRIPTION:
XS GIS Cut Line= 3
      2293492.76      7119456.33      2293308.76      7119351.65
      2293040.06      7119443.04
#Sta/Elev= 30
  4684.6  839.62  4722.7  837.80  4765.9  837.15  4771.7  836.81  4803.4  836.49
  4825.0  835.76  4830.8  835.25  4846.7  835.95  4874.0  834.89  4904.0  834.60
  4909.3  834.97  4935.4  834.20  4966.7  833.73  4980.5  834.04  4991.1  833.66
  4996.1  832.02  4996.4  831.52  4999.9  831.52  5000.1  832.02  5003.4  832.75
  5012.2  833.98  5022.8  833.99  5034.8  834.70  5043.9  834.80  5086.2  837.11
  5097.5  838.03  5128.9  838.79  5149.5  838.65  5160.3  839.25  5180.1  839.47
#Mann=3,-1,0
  4684.6    0.15       0  4996.1    0.05       0  5000.1    0.15       0
Bank Sta=4996.1,5000.1
Exp/Cntr=0.3,0.1

Type RM Length L Ch R = 1,316,149,149,149
BEGIN DESCRIPTION:
Mapping XS 53911848
END DESCRIPTION:
XS GIS Cut Line= 3
      2293527.02      7119434.94      2293328.20      7119234.58
      2293002.36      7119436.88
#Sta/Elev= 30
  4719.7  839.79  4750.1  837.88  4778.4  836.87  4870.3  835.21  4919.8  832.95
  4941.0  833.72  4962.2  833.55  4969.3  832.58  4988.5  832.29  4988.8  831.79
  4992.3  831.79  4992.5  832.29  5041.5  833.24  5056.8  832.76  5099.3  833.20
  5114.7  832.34  5120.6  833.13  5130.0  832.72  5135.9  833.26  5224.5  835.08
  5230.4  835.67  5267.0  836.17  5272.9  836.73  5282.4  836.48  5309.5  837.55
  5324.9  837.43  5346.1  838.47  5361.5  838.12  5367.4  838.77  5385.5  839.29
#Mann=3,-1,0
  4719.7    0.15       0  4988.5    0.05       0  4992.5    0.15       0
Bank Sta=4988.5,4992.5
Exp/Cntr=0.3,0.1

Type RM Length L Ch R = 1,167,112,112,112
BEGIN DESCRIPTION:
Mapping XS 5a14fa05
END DESCRIPTION:
XS GIS Cut Line= 4
      2293566.61      7119438.45      2293373.11      7119136.91
      2293225.98      7119145.81      2292987.19      7119441.18
#Sta/Elev= 30
  4498.0  840.81  4538.8  839.26  4575.1  836.89  4603.1  835.96  4705.3  834.45
  4769.4  831.53  4793.2  831.80  4805.1  832.55  4835.5  831.57  4870.4  832.07
  4890.5  831.39  4930.5  831.84  4985.9  831.31  4986.2  830.81  4989.7  830.81
  4989.9  831.31  5019.1  832.02  5054.3  831.62  5075.1  832.52  5189.1  833.03
  5289.3  835.80  5310.1  835.94  5324.5  837.13  5331.0  836.67  5345.3  837.12
  5353.3  837.92  5359.7  837.75  5367.7  838.61  5374.1  838.44  5383.5  839.11
#Mann=3,-1,0
  4498.0    0.15       0  4985.9    0.05       0  4989.9    0.15       0
Bank Sta=4985.9,4989.9
Exp/Cntr=0.3,0.1

Type RM Length L Ch R = 1,55,0,0,0
BEGIN DESCRIPTION:
MDE S 091 1.0
END DESCRIPTION:
XS GIS Cut Line= 4
      2293607.41      7119480.49      2293336.97      7119044.98
      2293229.05      7119051.40      2292963.78      7119451.97
#Sta/Elev= 30
  4418.3  842.97  4503.9  840.00  4577.1  835.92  4723.6  833.61  4744.8  832.82
  4750.7  831.69  4787.3  832.23  4875.9  830.69  4889.7  832.13  4912.5  832.01
  4918.4  830.39  4938.9  829.59  4949.0  830.28  4999.0  830.51  5007.1  829.08
  5007.3  828.58  5011.1  829.08  5029.1  830.87  5041.2  830.90  5045.8  829.76
  5051.8  830.50  5060.8  830.05  5066.8  831.04  5081.9  831.37  5340.6  833.42
  5470.0  836.75  5479.0  837.69  5485.0  837.37  5500.1  839.11  5519.5  839.55
#Mann=3,-1,0
  4418.3    0.15       0  5007.1    0.05       0  5011.1    0.15       0
Bank Sta=5007.1,5011.1
Exp/Cntr=0.3,0.1

Chan Stop Cuts=-1