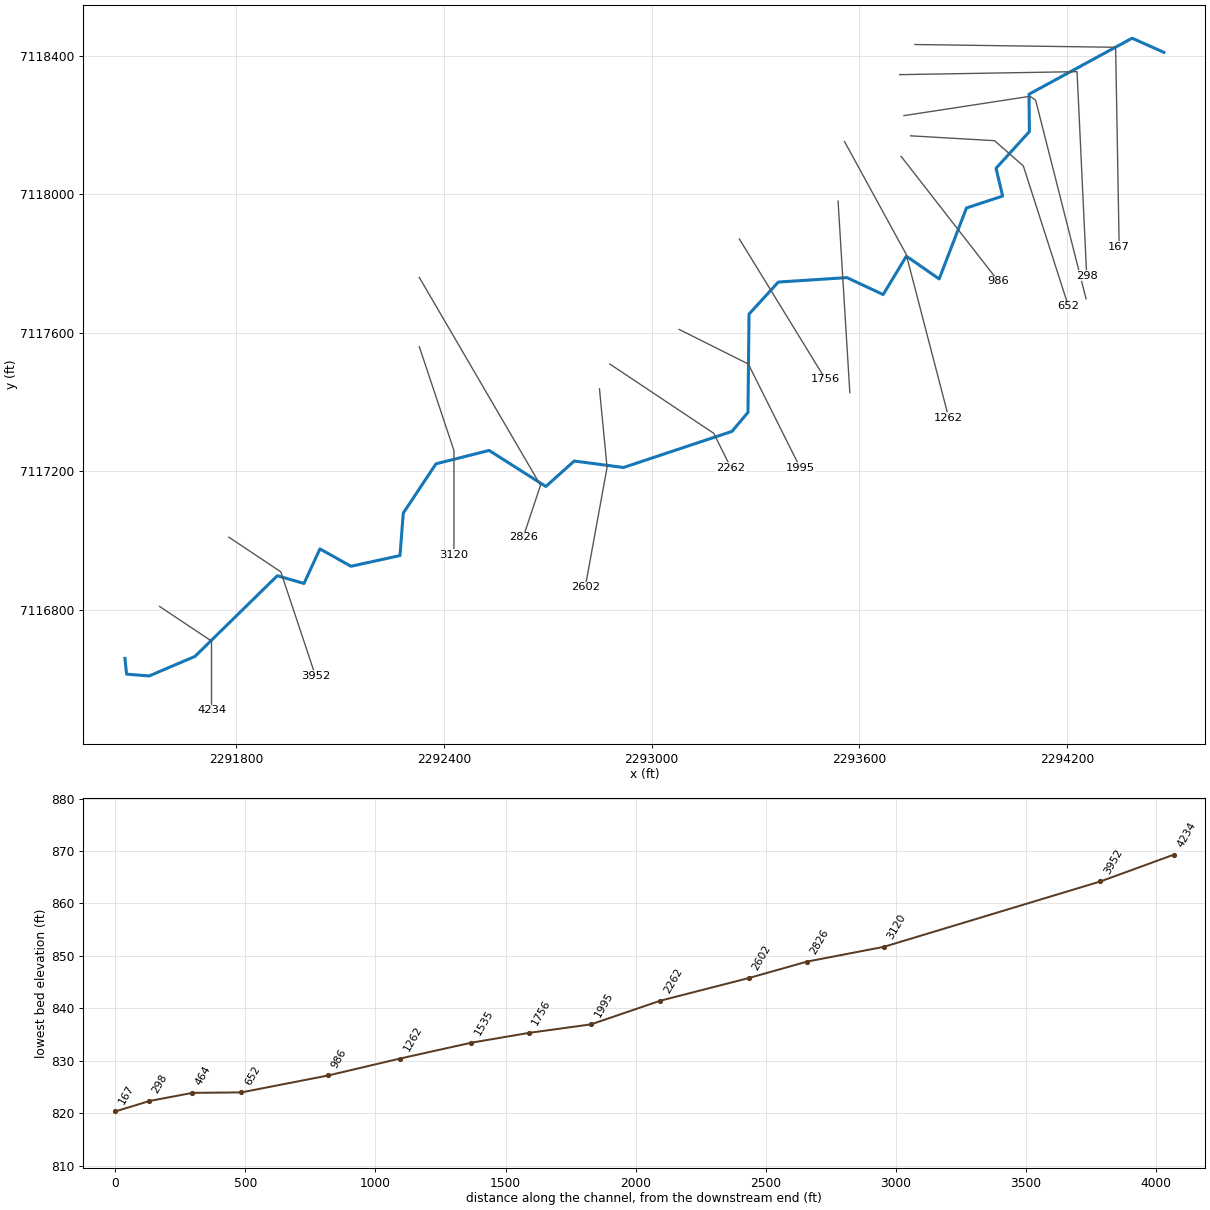
--- MDE S 092.prj (project) ---

Proj Title=MDE S 092 Base Level Engineering
Current Plan=p01
Default Exp/Contr=0.3,0.1
English Units
Geom File=g01
Flow File=f01
Plan File=p01
BEGIN DESCRIPTION:
MDE S 092
END DESCRIPTION:

--- MDE S 092.p01 (plan) ---

Plan Title=Multiple Run
Short Identifier=Multiple
Geom File=g01
Flow File=f01
Subcritical Flow
K Sum by GR= 0
Std Step Tol= 0.01
Critical Tol= 0.01
Num of Std Step Trials= 20
Max Error Tol= 0.3
Flow Tol Ratio= 0.001
Split Flow NTrial= 30
Split Flow Tol= 0.02
Split Flow Ratio= 0.02
Log Output Level= 0
Friction Slope Method= 1
Unsteady Friction Slope Method= 2
Unsteady Bridges Friction Slope Method= 1
Parabolic Critical Depth
Global Vel Dist=  1 , 1 , 1
Global Log Level= 0
CheckData=True
Encroach Param= -1, 0, 0, 0
BEGIN DESCRIPTION:
Multiple Run
END DESCRIPTION:

--- MDE S 092.f01 (steady flow) ---

Flow Title=Multiple
Number of Profiles=7
Profile Names=10-year,25-year,50-year,1pct_min,100-year,1pct_plu,500-year
River Rch & RM= MDE S 092,Reach-1,4234
     322     427     513     307     612    1220     870
Boundary for River Rch & Prof#=MDE S 092,Reach-1,1
Up Type=0
Dn Type=3
Dn Slope=0.005
Boundary for River Rch & Prof#=MDE S 092,Reach-1,2
Up Type=0
Dn Type=3
Dn Slope=0.005
Boundary for River Rch & Prof#=MDE S 092,Reach-1,3
Up Type=0
Dn Type=3
Dn Slope=0.005
Boundary for River Rch & Prof#=MDE S 092,Reach-1,4
Up Type=0
Dn Type=3
Dn Slope=0.005
Boundary for River Rch & Prof#=MDE S 092,Reach-1,5
Up Type=0
Dn Type=3
Dn Slope=0.005
Boundary for River Rch & Prof#=MDE S 092,Reach-1,6
Up Type=0
Dn Type=3
Dn Slope=0.005
Boundary for River Rch & Prof#=MDE S 092,Reach-1,7
Up Type=0
Dn Type=3
Dn Slope=0.005

--- MDE S 092.g01 (geometry) ---

Geom Title=Existing Conditions

River Reach=MDE S 092,Reach-1
Reach XY= 30
      2291479.00      7116660.00      2291483.68      7116614.51
      2291548.95      7116609.32      2291681.30      7116665.83
      2291919.01      7116898.75      2291996.00      7116876.33
      2292042.01      7116976.16      2292131.61      7116926.04
      2292273.20      7116956.90      2292282.69      7117079.65
      2292377.19      7117221.86      2292530.53      7117260.46
      2292694.42      7117156.41      2292776.18      7117229.84
      2292918.50      7117211.22      2293231.71      7117315.40
      2293278.02      7117370.26      2293281.05      7117654.16
      2293365.65      7117746.64      2293563.79      7117759.46
      2293668.38      7117710.60      2293735.44      7117821.38
      2293830.15      7117755.61      2293908.92      7117960.50
      2294013.35      7117994.92      2293994.38      7118075.18
      2294090.66      7118181.14      2294089.56      7118289.06
      2294387.29      7118450.78      2294479.00      7118410.00

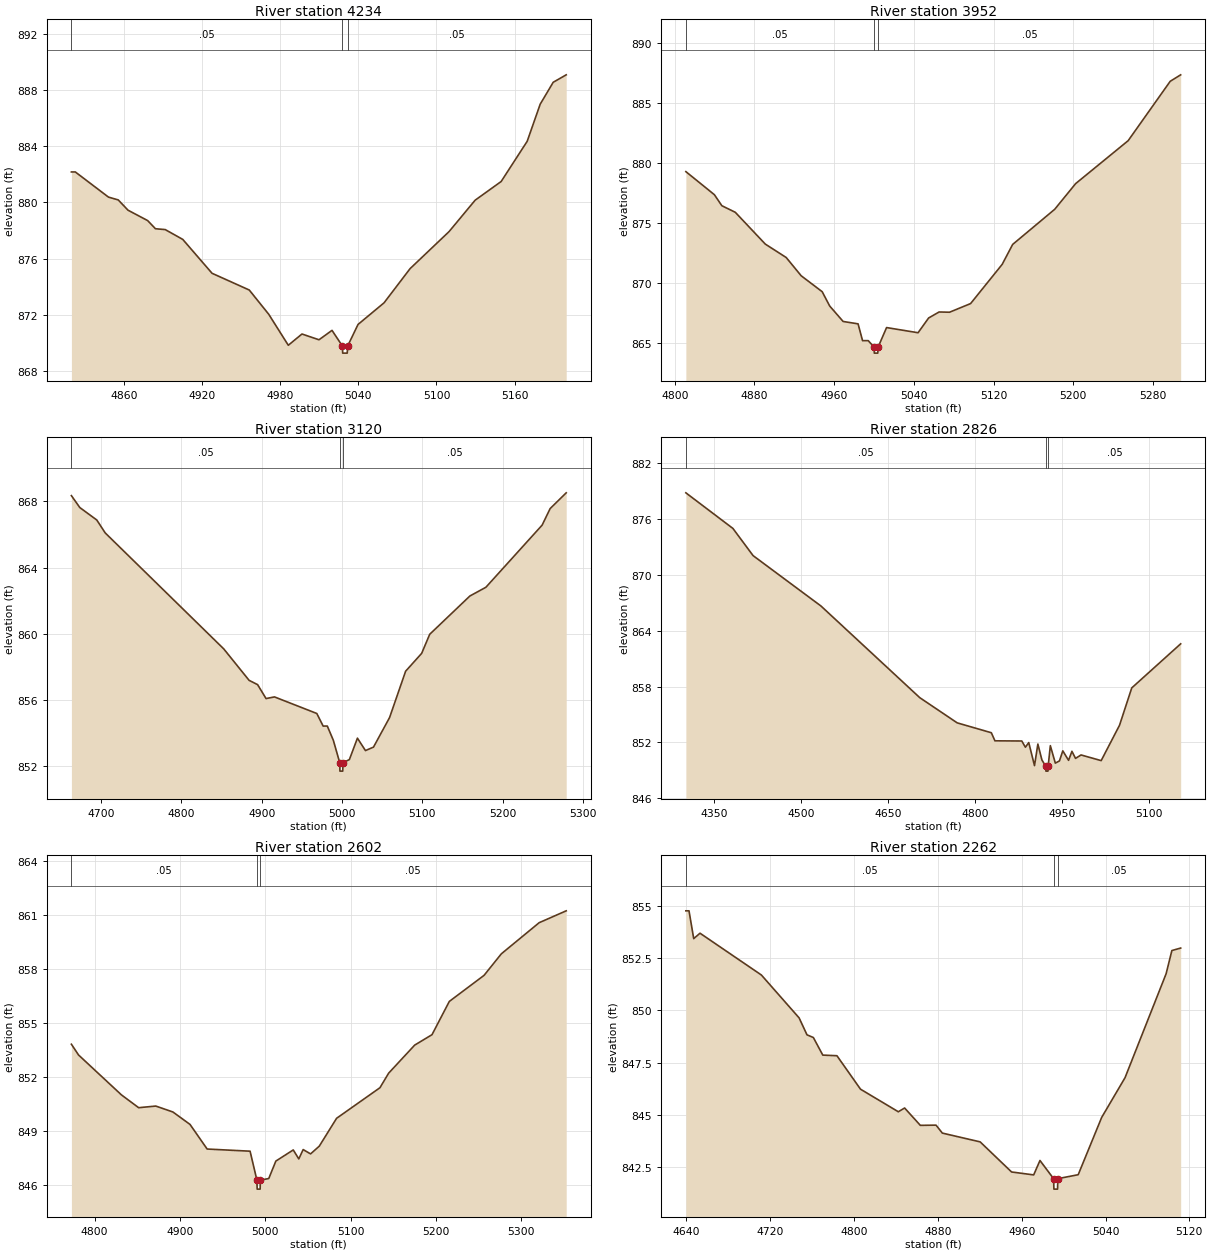
Type RM Length L Ch R = 1,4234,282,282,282
BEGIN DESCRIPTION:
MDE S 092 11.0
END DESCRIPTION:
XS GIS Cut Line= 3
      2291579.02      7116809.99      2291729.00      7116710.00
      2291729.00      7116509.95
#Sta/Elev= 30
  4819.4  882.17  4822.4  882.17  4847.9  880.38  4855.4  880.18  4862.9  879.45
  4878.0  878.71  4884.0  878.13  4891.5  878.07  4905.0  877.37  4927.5  874.96
  4956.1  873.77  4971.1  872.04  4986.1  869.84  4996.6  870.64  5009.7  870.23
  5019.7  870.90  5027.7  869.78  5027.9  869.28  5031.4  869.28  5031.7  869.78
  5039.7  871.32  5059.7  872.86  5079.7  875.29  5109.7  877.93  5129.7  880.16
  5149.7  881.49  5169.7  884.35  5179.7  886.99  5189.7  888.55  5199.7  889.08
#Mann=3,-1,0
  4819.4    0.05       0  5027.7   0.033       0  5031.7    0.05       0
Bank Sta=5027.7,5031.7
Exp/Cntr=0.3,0.1

Type RM Length L Ch R = 1,3952,832,832,832
BEGIN DESCRIPTION:
MDE S 092 10.0
END DESCRIPTION:
XS GIS Cut Line= 3
      2291778.96      7117010.02      2291929.00      7116910.00
      2292028.98      7116610.05
#Sta/Elev= 30
  4811.2  879.31  4839.8  877.39  4847.3  876.47  4860.8  875.92  4890.9  873.27
  4911.9  872.15  4926.9  870.63  4948.0  869.30  4955.5  868.11  4969.0  866.82
  4984.0  866.62  4988.5  865.22  4994.2  865.22  5000.1  864.68  5000.3  864.18
  5003.8  864.18  5004.1  864.68  5012.6  866.31  5044.2  865.88  5054.8  867.11
  5065.3  867.61  5075.8  867.59  5096.9  868.31  5128.6  871.58  5139.1  873.24
  5181.3  876.17  5202.3  878.31  5255.0  881.89  5297.2  886.84  5307.7  887.38
#Mann=3,-1,0
  4811.2    0.05       0  5000.1   0.033       0  5004.1    0.05       0
Bank Sta=5000.1,5004.1
Exp/Cntr=0.3,0.1

Type RM Length L Ch R = 1,3120,294,294,294
BEGIN DESCRIPTION:
MDE S 092 7.0
END DESCRIPTION:
XS GIS Cut Line= 3
      2292329.01      7117559.96      2292429.00      7117260.00
      2292429.00      7116959.98
#Sta/Elev= 30
  4663.0  868.34  4673.5  867.62  4694.6  866.87  4705.1  866.09  4852.7  859.09
  4884.3  857.19  4894.9  856.93  4905.4  856.09  4915.9  856.19  4968.6  855.19
  4976.5  854.43  4981.7  854.43  4989.2  853.57  4997.2  852.21  4997.4  851.71
  5000.9  851.71  5001.2  852.21  5009.2  852.41  5019.2  853.70  5029.2  852.95
  5039.2  853.16  5059.2  854.94  5079.2  857.74  5099.2  858.82  5109.2  859.97
  5159.2  862.28  5179.2  862.81  5249.2  866.56  5259.2  867.56  5279.2  868.51
#Mann=3,-1,0
  4663.0    0.05       0  4997.2   0.033       0  5001.2    0.05       0
Bank Sta=4997.2,5001.2
Exp/Cntr=0.3,0.1

Type RM Length L Ch R = 1,2826,224,224,224
BEGIN DESCRIPTION:
MDE S 092 6.0
END DESCRIPTION:
XS GIS Cut Line= 3
      2292328.99      7117760.01      2292679.00      7117160.00
      2292629.02      7117010.05
#Sta/Elev= 30
  4301.4  878.84  4382.5  875.01  4417.2  872.09  4534.2  866.67  4704.5  856.81
  4769.0  854.10  4827.8  853.04  4834.0  852.17  4880.3  852.15  4886.5  851.48
  4892.3  851.98  4902.2  849.50  4908.0  851.82  4915.0  850.11  4921.7  849.41
  4921.9  848.91  4925.4  848.91  4925.7  849.41  4929.5  851.65  4938.1  849.77
  4945.2  850.01  4951.0  851.09  4960.9  850.07  4966.7  851.04  4972.9  850.28
  4982.4  850.65  5017.1  850.04  5048.7  853.84  5069.8  857.86  5154.1  862.60
#Mann=3,-1,0
  4301.4    0.05       0  4921.7   0.033       0  4925.7    0.05       0
Bank Sta=4921.7,4925.7
Exp/Cntr=0.3,0.1

Type RM Length L Ch R = 1,2602,340,340,340
BEGIN DESCRIPTION:
Mapping XS d8d8c744
END DESCRIPTION:
XS GIS Cut Line= 3
      2292849.20      7117438.40      2292871.15      7117211.33
      2292808.03      7116865.27
#Sta/Elev= 30
  4772.9  853.83  4781.3  853.23  4831.6  851.01  4851.7  850.30  4871.8  850.39
  4891.9  850.06  4911.9  849.37  4932.0  848.00  4982.3  847.88  4990.3  846.27
  4990.6  845.77  4994.1  845.77  4994.3  846.27  5004.2  846.36  5012.5  847.33
  5032.9  847.95  5039.4  847.45  5044.5  847.97  5053.2  847.73  5063.4  848.16
  5083.7  849.71  5134.5  851.41  5144.7  852.22  5175.2  853.78  5195.5  854.36
  5215.8  856.21  5256.5  857.66  5276.8  858.86  5321.1  860.59  5352.8  861.25
#Mann=3,-1,0
  4772.9    0.05       0  4990.3   0.033       0  4994.3    0.05       0
Bank Sta=4990.3,4994.3
Exp/Cntr=0.3,0.1

Type RM Length L Ch R = 1,2262,267,267,267
BEGIN DESCRIPTION:
MDE S 092 4.0
END DESCRIPTION:
XS GIS Cut Line= 3
      2292879.02      7117509.98      2293179.00      7117310.00
      2293228.99      7117210.03
#Sta/Elev= 30
  4639.4  854.76  4642.4  854.76  4646.9  853.43  4652.9  853.69  4711.5  851.69
  4747.5  849.64  4755.0  848.83  4761.1  848.70  4770.1  847.86  4783.6  847.83
  4806.1  846.23  4842.2  845.15  4848.2  845.33  4863.2  844.50  4878.2  844.51
  4884.2  844.13  4920.3  843.71  4950.3  842.27  4971.4  842.13  4977.4  842.82
  4990.4  841.95  4990.7  841.45  4994.2  841.45  4994.4  841.95  5013.9  842.14
  5036.3  844.88  5058.6  846.78  5097.8  851.75  5103.3  852.86  5111.7  852.98
#Mann=3,-1,0
  4639.4    0.05       0  4990.4   0.033       0  4994.4    0.05       0
Bank Sta=4990.4,4994.4
Exp/Cntr=0.3,0.1

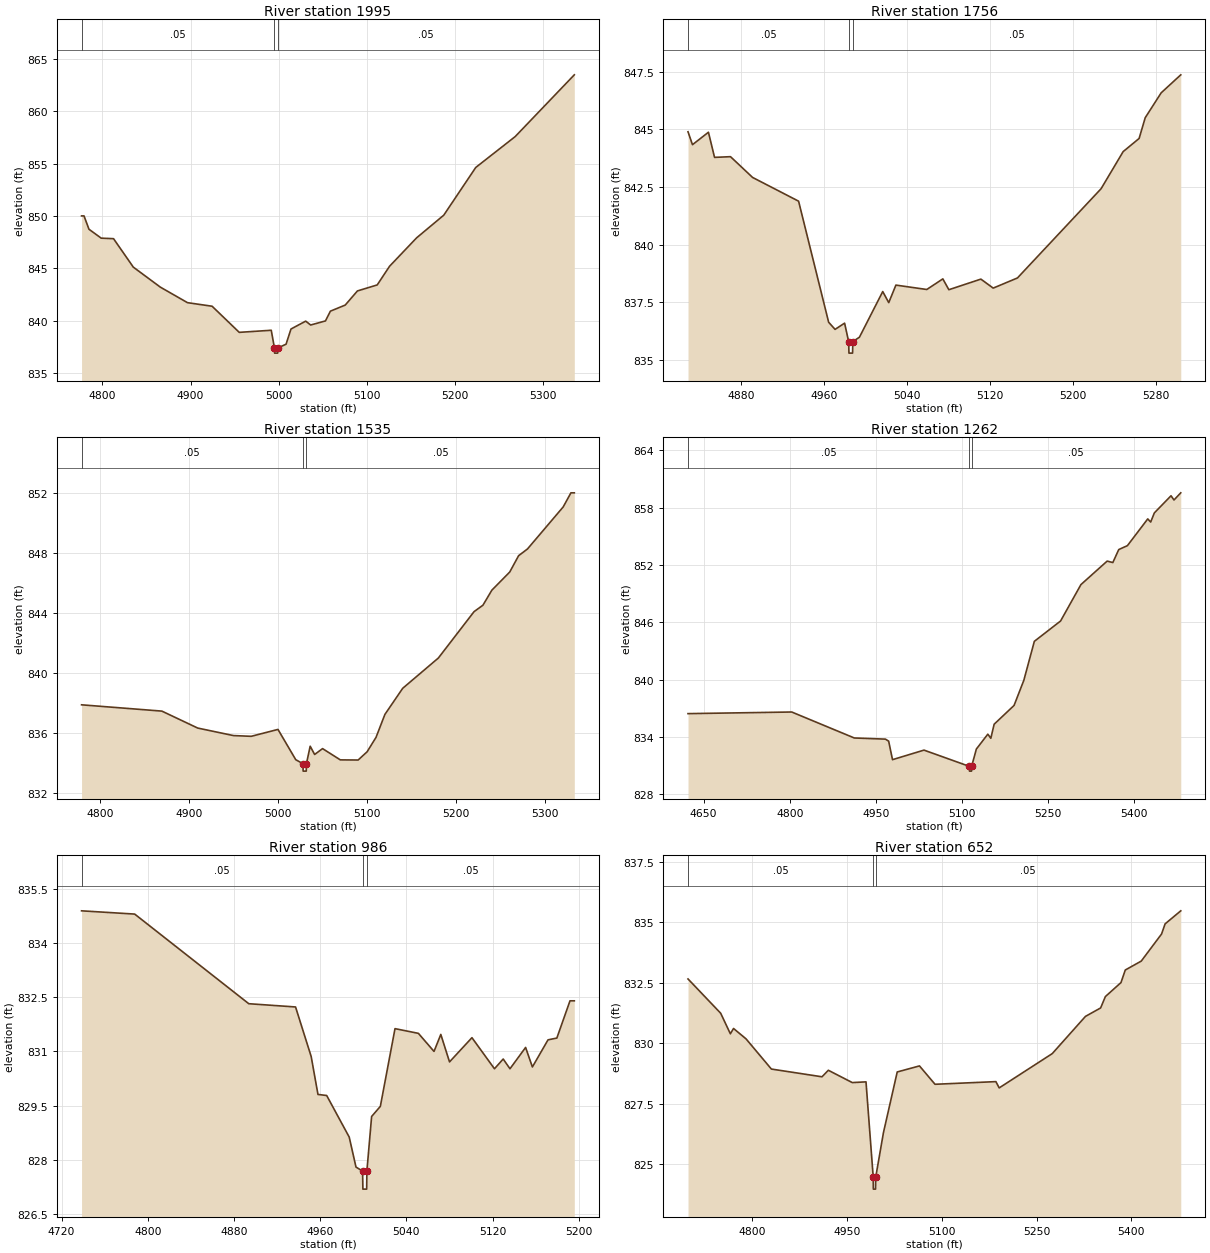
Type RM Length L Ch R = 1,1995,239,239,239
BEGIN DESCRIPTION:
MDE S 092 3.0
END DESCRIPTION:
XS GIS Cut Line= 3
      2293079.02      7117609.99      2293279.00      7117510.00
      2293429.00      7117210.00
#Sta/Elev= 30
  4776.4  850.01  4779.2  850.01  4784.8  848.74  4798.7  847.89  4812.7  847.84
  4835.1  845.13  4865.8  843.22  4896.6  841.74  4924.5  841.40  4955.3  838.91
  4991.6  839.11  4995.2  837.43  4995.4  836.93  4998.9  836.93  4999.2  837.43
  5008.4  837.78  5014.0  839.23  5030.7  839.98  5036.3  839.61  5053.1  840.00
  5058.7  840.93  5075.5  841.51  5089.4  842.86  5111.8  843.43  5125.8  845.21
  5156.5  847.92  5187.3  850.08  5223.6  854.63  5268.3  857.57  5335.4  863.46
#Mann=3,-1,0
  4776.4    0.05       0  4995.2   0.033       0  4999.2    0.05       0
Bank Sta=4995.2,4999.2
Exp/Cntr=0.3,0.1

Type RM Length L Ch R = 1,1756,221,221,221
BEGIN DESCRIPTION:
Mapping XS 1016e039
END DESCRIPTION:
XS GIS Cut Line= 2
      2293253.21      7117870.98      2293501.90      7117465.70
#Sta/Elev= 30
  4828.4  844.90  4832.7  844.34  4848.1  844.88  4854.0  843.79  4869.4  843.82
  4890.7  842.92  4935.1  841.89  4964.1  836.64  4970.3  836.33  4979.5  836.60
  4983.4  835.80  4983.7  835.30  4987.2  835.30  4987.4  835.80  4993.8  835.99
  5016.3  837.97  5022.1  837.49  5029.0  838.25  5058.8  838.06  5074.3  838.52
  5080.1  838.05  5111.0  838.51  5122.9  838.12  5146.3  838.56  5227.0  842.43
  5248.3  844.04  5263.7  844.61  5269.6  845.51  5285.0  846.59  5303.9  847.37
#Mann=3,-1,0
  4828.4    0.05       0  4983.4   0.033       0  4987.4    0.05       0
Bank Sta=4983.4,4987.4
Exp/Cntr=0.3,0.1

Type RM Length L Ch R = 1,1535,273,273,273
BEGIN DESCRIPTION:
Mapping XS a061f941
END DESCRIPTION:
XS GIS Cut Line= 2
      2293538.17      7117980.35      2293572.15      7117427.50
#Sta/Elev= 30
  4779.5  837.85  4869.8  837.43  4910.1  836.30  4950.2  835.80  4970.2  835.75
  5000.3  836.21  5020.3  834.19  5028.3  833.93  5028.6  833.43  5032.1  833.43
  5032.3  833.93  5036.5  835.09  5041.5  834.54  5050.4  834.93  5070.4  834.18
  5090.4  834.17  5100.5  834.72  5110.5  835.68  5120.5  837.21  5140.5  838.95
  5180.6  840.97  5220.7  844.06  5230.7  844.49  5240.7  845.49  5260.8  846.70
  5270.8  847.79  5280.8  848.24  5320.9  851.04  5329.6  851.98  5333.4  851.98
#Mann=3,-1,0
  4779.5    0.05       0  5028.3   0.033       0  5032.3    0.05       0
Bank Sta=5028.3,5032.3
Exp/Cntr=0.3,0.1

Type RM Length L Ch R = 1,1262,276,276,276
BEGIN DESCRIPTION:
Mapping XS fceec718
END DESCRIPTION:
XS GIS Cut Line= 3
      2293556.81      7118152.40      2293734.80      7117826.95
      2293857.50      7117355.50
#Sta/Elev= 30
  4622.9  836.44  4803.5  836.61  4912.5  833.89  4966.6  833.77  4972.3  833.56
  4979.0  831.62  5033.8  832.62  5112.8  830.92  5113.1  830.42  5116.6  830.42
  5116.8  830.92  5125.0  832.73  5145.0  834.29  5150.2  833.86  5156.0  835.33
  5190.7  837.30  5207.7  839.93  5226.0  844.01  5271.7  846.14  5307.1  849.95
  5352.8  852.41  5362.7  852.26  5373.0  853.62  5388.1  854.03  5423.5  856.83
  5428.6  856.50  5435.0  857.46  5464.0  859.25  5469.2  858.81  5481.0  859.56
#Mann=3,-1,0
  4622.9    0.05       0  5112.8   0.035       0  5116.8    0.05       0
Bank Sta=5112.8,5116.8
Exp/Cntr=0.3,0.1

Type RM Length L Ch R = 1,986,334,334,334
BEGIN DESCRIPTION:
Mapping XS 08461589
END DESCRIPTION:
XS GIS Cut Line= 2
      2293720.27      7118109.50      2294001.27      7117748.72
#Sta/Elev= 30
  4738.6  834.89  4787.9  834.80  4893.8  832.32  4937.2  832.23  4951.7  830.86
  4958.0  829.81  4966.1  829.78  4987.0  828.63  4993.3  827.80  4999.4  827.69
  4999.7  827.19  5003.2  827.19  5003.4  827.69  5007.8  829.20  5015.9  829.48
  5029.5  831.63  5051.2  831.50  5065.7  831.00  5072.0  831.47  5080.1  830.71
  5100.9  831.38  5121.8  830.52  5129.9  830.79  5136.2  830.52  5150.7  831.11
  5157.0  830.57  5171.5  831.32  5179.7  831.37  5191.9  832.40  5195.9  832.40
#Mann=3,-1,0
  4738.6    0.05       0  4999.4   0.033       0  5003.4    0.05       0
Bank Sta=4999.4,5003.4
Exp/Cntr=0.3,0.1

Type RM Length L Ch R = 1,652,188,188,188
BEGIN DESCRIPTION:
Mapping XS a32b3d6c
END DESCRIPTION:
XS GIS Cut Line= 4
      2293747.36      7118168.89      2293990.14      7118154.82
      2294073.20      7118081.92      2294203.44      7117676.42
#Sta/Elev= 30
  4698.5  832.66  4750.2  831.24  4765.5  830.39  4770.5  830.61  4790.3  830.18
  4830.4  828.93  4910.5  828.61  4920.5  828.88  4958.4  828.37  4980.1  828.40
  4991.5  824.46  4991.7  823.96  4995.2  823.96  4995.5  824.46  5007.7  826.30
  5029.5  828.81  5064.7  829.06  5089.3  828.30  5185.6  828.41  5190.8  828.15
  5274.8  829.57  5327.3  831.11  5351.3  831.46  5358.8  831.93  5383.5  832.51
  5390.3  833.03  5415.6  833.40  5447.7  834.52  5453.3  834.94  5478.1  835.48
#Mann=3,-1,0
  4698.5    0.05       0  4991.5   0.035       0  4995.5    0.05       0
Bank Sta=4991.5,4995.5
Exp/Cntr=0.3,0.1

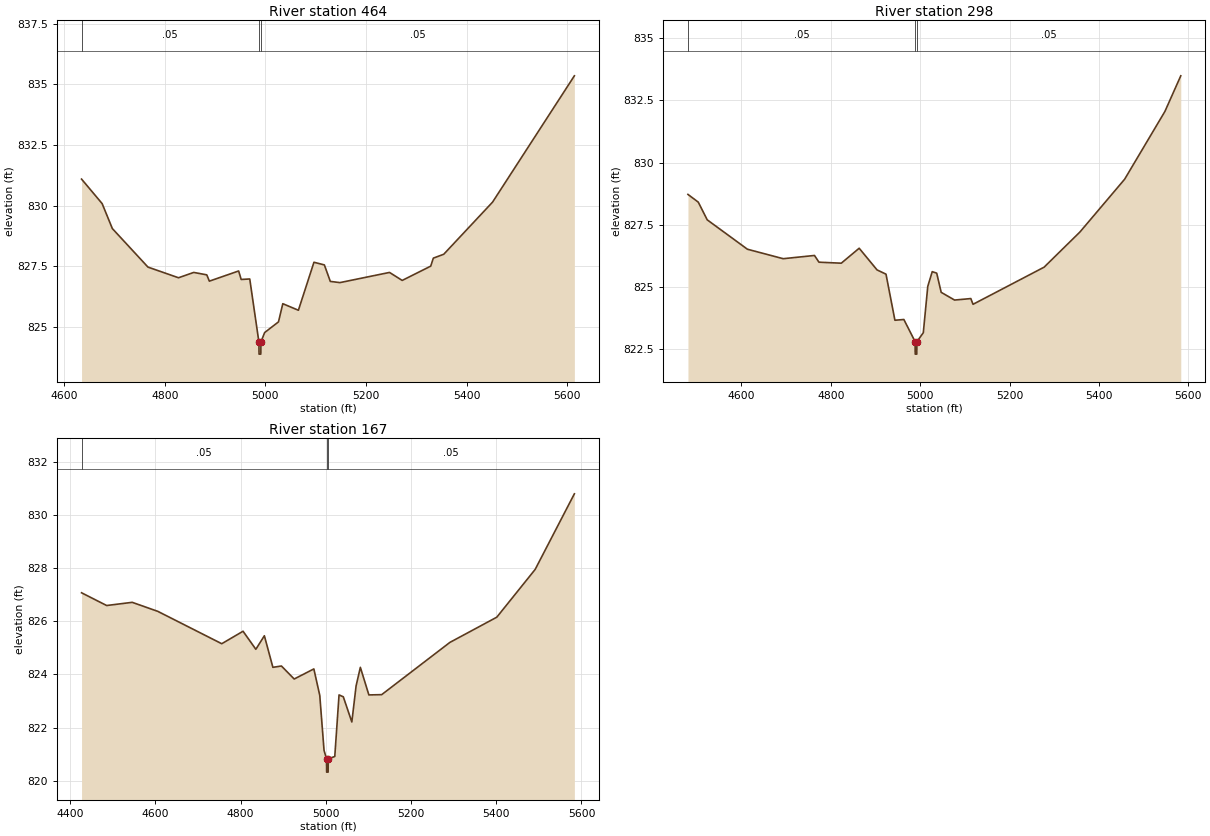
Type RM Length L Ch R = 1,464,166,166,166
BEGIN DESCRIPTION:
Mapping XS f47108cc
END DESCRIPTION:
XS GIS Cut Line= 4
      2293728.55      7118227.19      2294092.54      7118283.00
      2294108.69      7118271.72      2294254.27      7117698.36
#Sta/Elev= 30
  4634.7  831.09  4675.6  830.08  4695.9  829.05  4766.7  827.46  4827.4  827.02
  4857.7  827.24  4883.6  827.14  4888.7  826.88  4946.9  827.30  4952.0  826.95
  4969.0  826.97  4987.2  824.37  4987.5  823.87  4991.0  823.87  4991.2  824.37
  4998.6  824.76  5026.1  825.20  5034.7  825.95  5065.7  825.68  5096.6  827.66
  5117.3  827.55  5129.1  826.87  5148.2  826.82  5246.8  827.24  5272.0  826.91
  5328.7  827.50  5333.9  827.83  5354.6  827.99  5451.6  830.14  5614.2  835.35
#Mann=3,-1,0
  4634.7    0.05       0  4987.2   0.035       0  4991.2    0.05       0
Bank Sta=4987.2,4991.2
Exp/Cntr=0.3,0.1

Type RM Length L Ch R = 1,298,131,131,131
BEGIN DESCRIPTION:
Mapping XS b2b3cd4e
END DESCRIPTION:
XS GIS Cut Line= 3
      2293715.94      7118345.50      2294228.27      7118354.15
      2294256.06      7117764.51
#Sta/Elev= 30
  4480.3  828.72  4503.4  828.41  4523.4  827.70  4613.4  826.52  4693.4  826.14
  4763.4  826.27  4773.4  826.00  4823.4  825.96  4863.4  826.56  4903.4  825.69
  4923.4  825.52  4943.4  823.67  4963.4  823.70  4988.6  822.81  4988.8  822.31
  4992.3  822.31  4992.6  822.81  5006.9  823.17  5016.9  825.03  5026.9  825.62
  5036.9  825.56  5046.9  824.79  5076.9  824.48  5113.2  824.54  5118.2  824.31
  5277.2  825.80  5357.3  827.21  5457.4  829.33  5547.5  832.05  5583.0  833.48
#Mann=3,-1,0
  4480.3    0.05       0  4988.6   0.033       0  4992.6    0.05       0
Bank Sta=4988.6,4992.6
Exp/Cntr=0.3,0.1

Type RM Length L Ch R = 1,167,0,0,0
BEGIN DESCRIPTION:
MDE S 092 1.0
END DESCRIPTION:
XS GIS Cut Line= 3
      2293760.13      7118432.52      2294339.65      7118424.54
      2294349.87      7117848.01
#Sta/Elev= 30
  4427.1  827.08  4486.0  826.60  4546.0  826.72  4606.0  826.38  4756.0  825.16
  4806.0  825.63  4836.0  824.95  4856.0  825.46  4876.0  824.27  4896.0  824.32
  4926.0  823.83  4972.1  824.21  4986.0  823.21  4996.0  821.14  5001.8  820.82
  5002.1  820.32  5005.6  820.32  5005.8  820.82  5021.2  820.91  5031.2  823.23
  5041.2  823.16  5061.2  822.21  5071.2  823.57  5081.2  824.27  5101.2  823.23
  5131.2  823.24  5291.3  825.21  5401.3  826.16  5491.3  827.96  5583.3  830.81
#Mann=3,-1,0
  4427.1    0.05       0  5001.8   0.033       0  5005.8    0.05       0
Bank Sta=5001.8,5005.8
Exp/Cntr=0.3,0.1

Chan Stop Cuts=-1