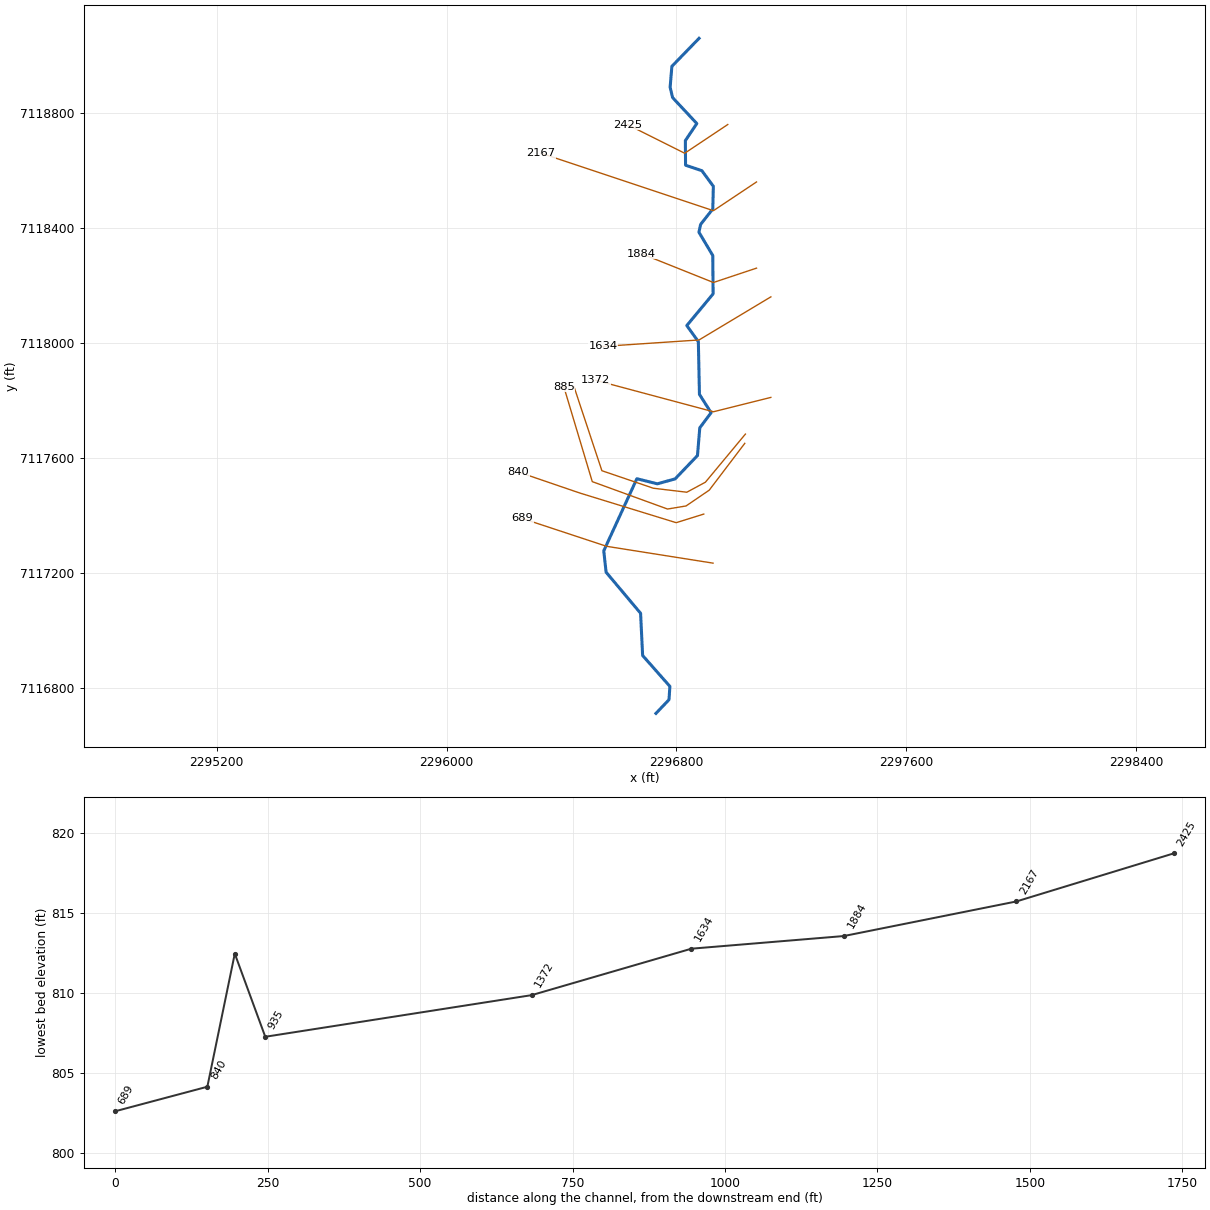
--- MDE S 093.prj (project) ---

Proj Title=MDE S 093 Base Level Engineering
Current Plan=p01
Default Exp/Contr=0.3,0.1
English Units
Geom File=g01
Flow File=f01
Plan File=p01
BEGIN DESCRIPTION:
MDE S 093
END DESCRIPTION:

--- MDE S 093.p01 (plan) ---

Plan Title=Multiple Run
Short Identifier=Multiple
Geom File=g01
Flow File=f01
Subcritical Flow
K Sum by GR= 0
Std Step Tol= 0.01
Critical Tol= 0.01
Num of Std Step Trials= 20
Max Error Tol= 0.3
Flow Tol Ratio= 0.001
Split Flow NTrial= 30
Split Flow Tol= 0.02
Split Flow Ratio= 0.02
Log Output Level= 0
Friction Slope Method= 1
Unsteady Friction Slope Method= 2
Unsteady Bridges Friction Slope Method= 1
Parabolic Critical Depth
Global Vel Dist=  1 , 1 , 1
Global Log Level= 0
CheckData=True
Encroach Param= -1, 0, 0, 0
BEGIN DESCRIPTION:
Multiple Run
END DESCRIPTION:

--- MDE S 093.f01 (steady flow) ---

Flow Title=Multiple
Number of Profiles=7
Profile Names=10-year,25-year,50-year,1pct_min,100-year,1pct_plu,500-year
River Rch & RM= MDE S 093,Reach-1,2425
     338     448     536     319     637    1272     901
Boundary for River Rch & Prof#=MDE S 093,Reach-1,1
Up Type=0
Dn Type=3
Dn Slope=0.005
Boundary for River Rch & Prof#=MDE S 093,Reach-1,2
Up Type=0
Dn Type=3
Dn Slope=0.005
Boundary for River Rch & Prof#=MDE S 093,Reach-1,3
Up Type=0
Dn Type=3
Dn Slope=0.005
Boundary for River Rch & Prof#=MDE S 093,Reach-1,4
Up Type=0
Dn Type=3
Dn Slope=0.005
Boundary for River Rch & Prof#=MDE S 093,Reach-1,5
Up Type=0
Dn Type=3
Dn Slope=0.005
Boundary for River Rch & Prof#=MDE S 093,Reach-1,6
Up Type=0
Dn Type=3
Dn Slope=0.005
Boundary for River Rch & Prof#=MDE S 093,Reach-1,7
Up Type=0
Dn Type=3
Dn Slope=0.005

--- MDE S 093.g01 (geometry) ---

Geom Title=Existing Conditions

River Reach=MDE S 093,Reach-1
Reach XY= 30
      2296879.00      7119060.00      2296784.33      7118962.45
      2296778.32      7118889.92      2296786.79      7118853.83
      2296871.19      7118763.41      2296831.33      7118704.02
      2296832.01      7118618.35      2296888.75      7118599.25
      2296928.79      7118544.90      2296926.81      7118465.97
      2296884.38      7118412.18      2296878.60      7118385.00
      2296926.72      7118304.07      2296927.95      7118170.44
      2296836.33      7118060.10      2296876.53      7118004.15
      2296880.38      7117820.44      2296920.92      7117756.70
      2296881.56      7117704.10      2296873.49      7117607.56
      2296795.79      7117526.39      2296734.05      7117509.15
      2296662.44      7117526.87      2296547.30      7117275.88
      2296555.34      7117201.51      2296675.44      7117058.53
      2296682.56      7116911.47      2296777.45      7116804.03
      2296774.43      7116757.65      2296729.00      7116710.00

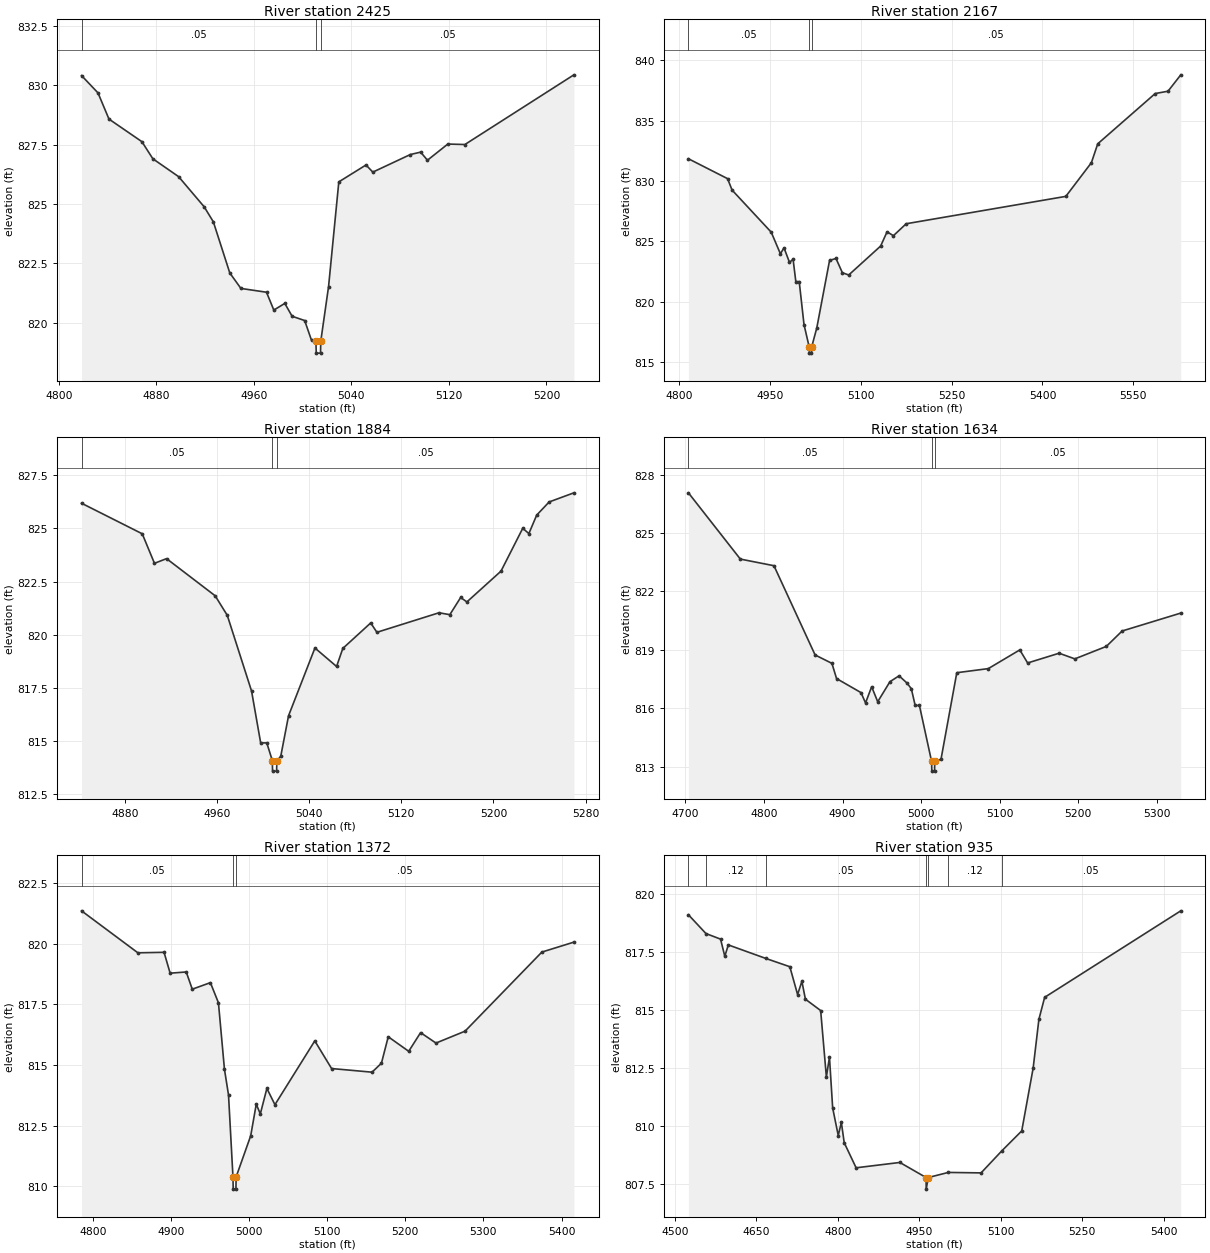
Type RM Length L Ch R = 1,2425,258,258,258
BEGIN DESCRIPTION:
MDE S 093 6.0
END DESCRIPTION:
XS GIS Cut Line= 3
      2296978.96      7118759.97      2296829.00      7118660.00
      2296629.03      7118759.98
#Sta/Elev= 30
  4818.7  830.40  4832.2  829.67  4841.2  828.57  4868.2  827.62  4877.2  826.90
  4898.3  826.15  4919.3  824.88  4926.8  824.25  4940.3  822.10  4949.4  821.45
  4970.4  821.29  4976.4  820.54  4985.4  820.82  4991.4  820.28  5001.7  820.10
  5007.3  819.27  5010.9  819.23  5011.2  818.73  5014.7  818.73  5014.9  819.23
  5021.3  821.53  5029.7  825.93  5052.0  826.64  5057.6  826.34  5088.4  827.08
  5096.8  827.18  5102.4  826.84  5119.1  827.52  5133.1  827.50  5222.5  830.43
#Mann=3,-1,0
  4818.7    0.05       0  5010.9   0.033       0  5014.9    0.05       0
Bank Sta=5010.9,5014.9
Exp/Cntr=0.3,0.1

Type RM Length L Ch R = 1,2167,283,283,283
BEGIN DESCRIPTION:
MDE S 093 5.0
END DESCRIPTION:
XS GIS Cut Line= 3
      2297079.03      7118560.02      2296929.00      7118460.00
      2296328.97      7118660.01
#Sta/Elev= 30
  4815.6  831.85  4880.2  830.20  4887.7  829.25  4952.3  825.76  4967.4  823.97
  4973.4  824.46  4982.4  823.26  4988.4  823.51  4992.9  821.66  4998.5  821.66
  5006.4  818.10  5015.0  816.23  5015.2  815.73  5018.7  815.73  5019.0  816.23
  5027.5  817.82  5048.6  823.42  5059.2  823.58  5069.7  822.40  5080.2  822.21
  5132.9  824.61  5143.5  825.79  5154.0  825.47  5175.1  826.46  5438.6  828.73
  5480.8  831.52  5491.3  833.09  5586.2  837.26  5607.3  837.45  5628.4  838.81
#Mann=3,-1,0
  4815.6    0.05       0  5015.0   0.033       0  5019.0    0.05       0
Bank Sta=5015,5019
Exp/Cntr=0.3,0.1

Type RM Length L Ch R = 1,1884,250,250,250
BEGIN DESCRIPTION:
MDE S 093 4.0
END DESCRIPTION:
XS GIS Cut Line= 3
      2297079.02      7118260.01      2296929.00      7118210.00
      2296678.99      7118310.00
#Sta/Elev= 30
  4842.4  826.19  4895.1  824.75  4905.7  823.36  4916.2  823.58  4958.4  821.83
  4968.9  820.91  4990.0  817.34  4997.9  814.90  5003.2  814.90  5008.0  814.07
  5008.2  813.57  5011.7  813.57  5012.0  814.07  5015.3  814.26  5022.1  816.18
  5045.0  819.37  5063.8  818.50  5069.2  819.35  5093.4  820.55  5098.8  820.11
  5152.7  821.03  5162.1  820.94  5171.5  821.75  5176.9  821.54  5206.5  822.99
  5225.4  825.01  5230.7  824.76  5237.5  825.63  5248.3  826.25  5269.8  826.68
#Mann=3,-1,0
  4842.4    0.05       0  5008.0   0.033       0  5012.0    0.05       0
Bank Sta=5008,5012
Exp/Cntr=0.3,0.1

Type RM Length L Ch R = 1,1634,262,262,262
BEGIN DESCRIPTION:
MDE S 093 3.0
END DESCRIPTION:
XS GIS Cut Line= 3
      2297129.02      7118160.01      2296879.00      7118010.00
      2296544.43      7117987.50
#Sta/Elev= 30
  4703.8  827.06  4769.9  823.66  4812.7  823.32  4865.1  818.74  4886.5  818.31
  4892.4  817.53  4923.5  816.81  4929.3  816.28  4937.1  817.11  4944.8  816.34
  4960.4  817.37  4972.0  817.67  4981.8  817.31  4987.6  817.01  4992.5  816.15
  4997.9  816.15  5013.4  813.28  5013.7  812.78  5017.2  812.78  5017.4  813.28
  5025.4  813.39  5045.5  817.83  5085.6  818.04  5125.7  819.00  5135.7  818.33
  5175.8  818.83  5195.8  818.54  5235.9  819.18  5256.0  819.97  5330.7  820.89
#Mann=3,-1,0
  4703.8    0.05       0  5013.4   0.035       0  5017.4    0.05       0
Bank Sta=5013.4,5017.4
Exp/Cntr=0.3,0.1

Type RM Length L Ch R = 1,1372,437,437,437
BEGIN DESCRIPTION:
MDE S 093 2.0
END DESCRIPTION:
XS GIS Cut Line= 3
      2297128.98      7117809.99      2296929.00      7117760.00
      2296519.42      7117869.50
#Sta/Elev= 30
  4785.7  821.35  4857.8  819.62  4891.3  819.64  4899.1  818.78  4919.7  818.83
  4927.4  818.12  4950.6  818.39  4960.9  817.56  4968.6  814.82  4973.8  813.76
  4979.5  810.38  4979.8  809.88  4983.3  809.88  4983.5  810.38  5002.2  812.08
  5009.3  813.38  5014.5  812.98  5022.9  814.03  5033.2  813.36  5084.2  815.99
  5105.7  814.85  5157.5  814.70  5169.5  815.07  5178.2  816.16  5204.4  815.56
  5219.6  816.33  5239.3  815.90  5276.5  816.39  5374.8  819.65  5415.8  820.06
#Mann=3,-1,0
  4785.7    0.05       0  4979.5   0.035       0  4983.5    0.05       0
Bank Sta=4979.5,4983.5
Exp/Cntr=0.3,0.1

Type RM Length L Ch R = 1,935,50,50,50
BEGIN DESCRIPTION:
Mapping XS 09cac82a
END DESCRIPTION:
XS GIS Cut Line= 6
      2297040.37      7117682.31      2296901.21      7117514.87
      2296836.43      7117479.88      2296719.99      7117493.78
      2296540.70      7117554.81      2296443.40      7117848.09
#Sta/Elev= 30
  4524.8  819.11  4557.1  818.30  4584.0  818.06  4591.8  817.32  4598.3  817.81
  4667.0  817.23  4711.6  816.87  4725.9  815.67  4733.8  816.24  4740.3  815.47
  4768.4  814.98  4778.9  812.12  4784.6  812.97  4790.5  810.78  4800.8  809.59
  4806.5  810.16  4811.8  809.28  4833.7  808.20  4914.3  808.43  4962.6  807.78
  4962.8  807.28  4966.6  807.78  5003.5  808.00  5063.9  807.98  5102.1  808.93
  5138.8  809.79  5159.9  812.51  5170.4  814.60  5181.0  815.55  5431.8  819.28
#Mann=7,-1,0
  4524.8    0.05       0  4557.1    0.12       0  4667.0    0.05       0
  4962.6   0.033       0  4966.6    0.05       0  5003.5    0.12       0
  5102.1    0.05       0
Bank Sta=4962.6,4966.6
Exp/Cntr=0.3,0.1

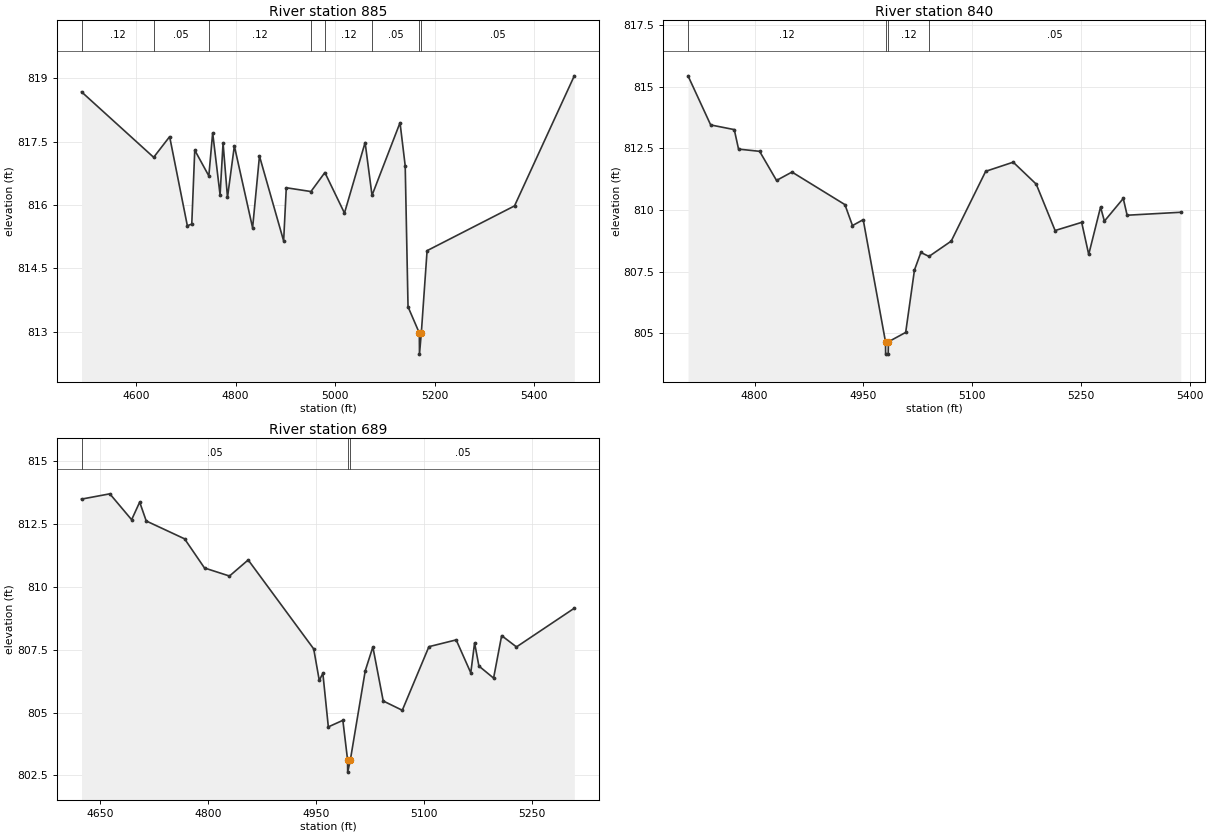
Type RM Length L Ch R = 1,885,45,45,45
BEGIN DESCRIPTION:
Mapping XS 4a5f4a98
END DESCRIPTION:
XS GIS Cut Line= 6
      2297038.13      7117650.01      2296914.40      7117487.03
      2296833.75      7117432.07      2296769.37      7117421.35
      2296507.25      7117516.75      2296408.37      7117846.52
#Sta/Elev= 30
  4490.2  818.68  4635.2  817.13  4667.3  817.62  4702.9  815.51  4711.8  815.55
  4717.8  817.30  4746.1  816.69  4753.8  817.71  4768.7  816.24  4774.7  817.47
  4783.6  816.18  4797.4  817.40  4834.1  815.46  4847.9  817.16  4896.5  815.15
  4901.8  816.41  4951.4  816.32  4979.4  816.77  5018.8  815.81  5060.3  817.48
  5074.2  816.23  5130.5  817.95  5140.9  816.93  5146.6  813.59  5169.3  812.97
  5169.6  812.47  5173.3  812.97  5184.9  814.92  5360.7  815.98  5480.9  819.06
#Mann=8,-1,0
  4490.2    0.12       0  4635.2    0.05       0  4746.1    0.12       0
  4951.4    0.05       0  4979.4    0.12       0  5074.2    0.05       0
  5169.3    0.07       0  5173.3    0.05       0
Bank Sta=5169.3,5173.3
Exp/Cntr=0.3,0.1

Type RM Length L Ch R = 1,840,151,151,151
BEGIN DESCRIPTION:
Mapping XS 1f40ae3f
END DESCRIPTION:
XS GIS Cut Line= 4
      2296895.40      7117403.79      2296799.45      7117373.88
      2296463.25      7117477.32      2296248.99      7117550.57
#Sta/Elev= 30
  4708.4  815.44  4739.6  813.45  4772.1  813.26  4778.0  812.47  4807.0  812.38
  4830.3  811.20  4851.6  811.54  4924.5  810.22  4934.9  809.37  4949.7  809.61
  4980.4  804.66  4980.6  804.16  4984.1  804.16  4984.4  804.66  5008.2  805.04
  5020.3  807.57  5029.1  808.28  5040.3  808.12  5070.9  808.74  5118.4  811.57
  5156.3  811.94  5188.0  811.05  5214.0  809.17  5250.6  809.50  5260.3  808.20
  5276.6  810.12  5281.9  809.55  5307.9  810.47  5313.2  809.79  5387.1  809.91
#Mann=4,-1,0
  4708.4    0.12       0  4980.4    0.07       0  4984.4    0.12       0
  5040.3    0.05       0
Bank Sta=4980.4,4984.4
Exp/Cntr=0.3,0.1

Type RM Length L Ch R = 1,689,0,0,0
BEGIN DESCRIPTION:
MDE S 093 1.0
END DESCRIPTION:
XS GIS Cut Line= 3
      2296927.77      7117233.01      2296557.34      7117291.57
      2296263.09      7117388.71
#Sta/Elev= 30
  4624.1  813.49  4663.4  813.70  4693.7  812.67  4704.9  813.37  4714.0  812.62
  4767.3  811.91  4795.0  810.75  4829.7  810.43  4855.7  811.07  4946.8  807.53
  4954.5  806.28  4959.5  806.56  4967.1  804.43  4987.3  804.69  4993.8  803.13
  4994.0  802.63  4997.8  803.13  5018.4  806.66  5029.0  807.61  5043.4  805.46
  5069.9  805.09  5106.9  807.62  5144.8  807.89  5165.1  806.58  5170.4  807.77
  5176.4  806.85  5196.8  806.37  5208.0  808.06  5228.6  807.61  5309.0  809.15
#Mann=3,-1,0
  4624.1    0.05       0  4993.8   0.033       0  4997.8    0.05       0
Bank Sta=4993.8,4997.8
Exp/Cntr=0.3,0.1

Chan Stop Cuts=-1