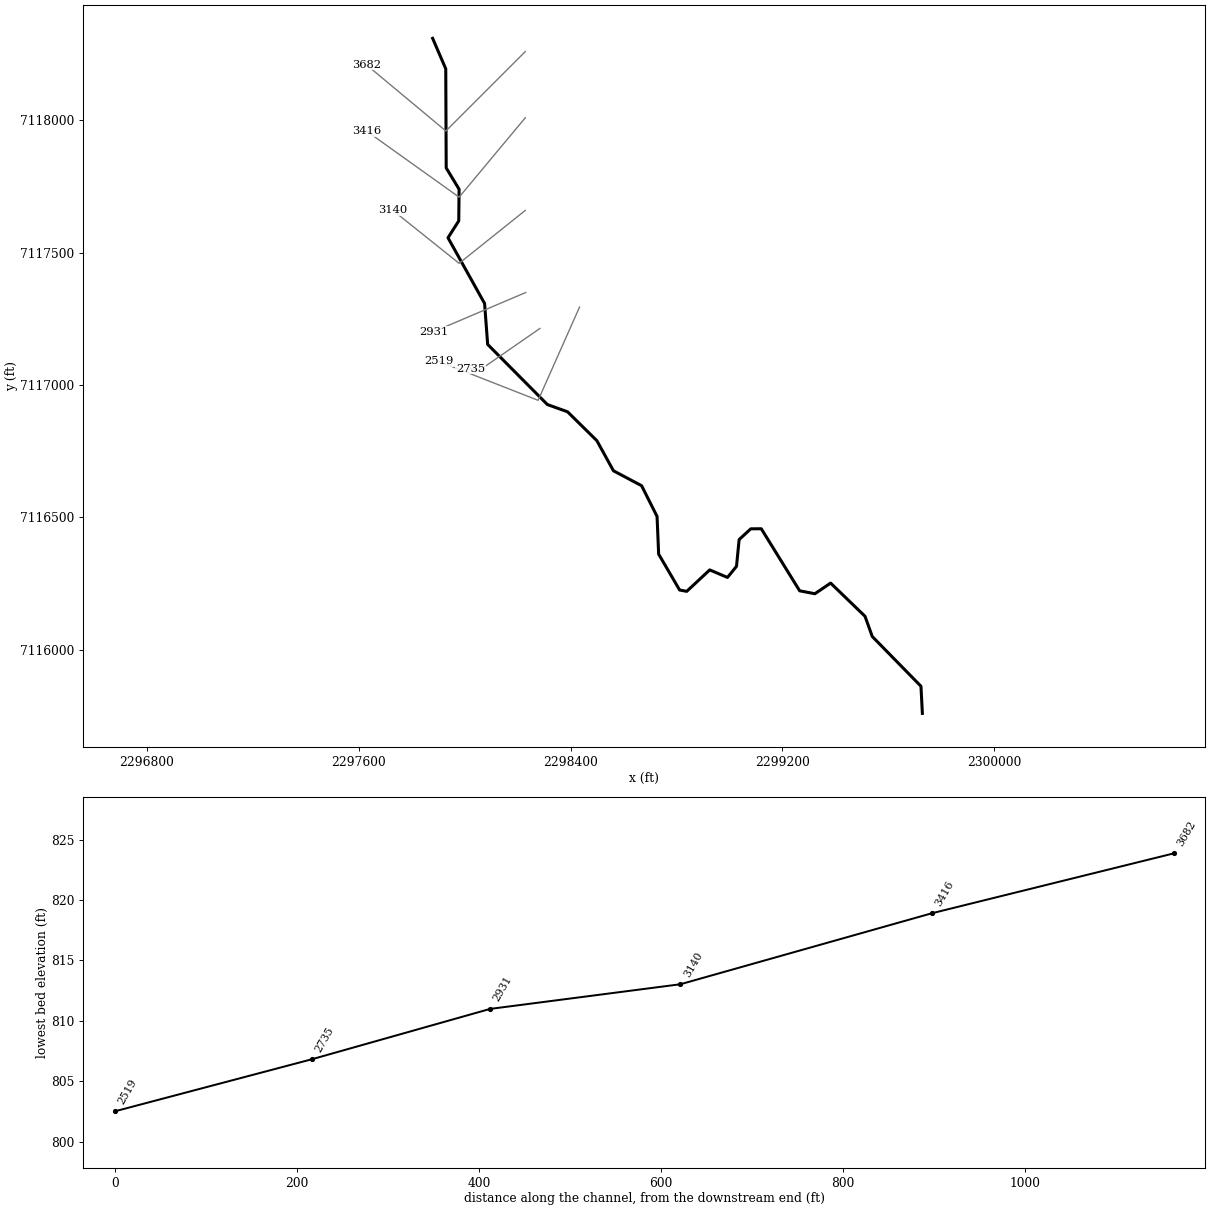
--- MDE S 094.prj (project) ---

Proj Title=MDE S 094 Base Level Engineering
Current Plan=p01
Default Exp/Contr=0.3,0.1
English Units
Geom File=g01
Flow File=f01
Plan File=p01
BEGIN DESCRIPTION:
MDE S 094
END DESCRIPTION:

--- MDE S 094.p01 (plan) ---

Plan Title=Multiple Run
Short Identifier=Multiple
Geom File=g01
Flow File=f01
Subcritical Flow
K Sum by GR= 0
Std Step Tol= 0.01
Critical Tol= 0.01
Num of Std Step Trials= 20
Max Error Tol= 0.3
Flow Tol Ratio= 0.001
Split Flow NTrial= 30
Split Flow Tol= 0.02
Split Flow Ratio= 0.02
Log Output Level= 0
Friction Slope Method= 1
Unsteady Friction Slope Method= 2
Unsteady Bridges Friction Slope Method= 1
Parabolic Critical Depth
Global Vel Dist=  1 , 1 , 1
Global Log Level= 0
CheckData=True
Encroach Param= -1, 0, 0, 0
BEGIN DESCRIPTION:
Multiple Run
END DESCRIPTION:

--- MDE S 094.f01 (steady flow) ---

Flow Title=Multiple
Number of Profiles=7
Profile Names=10-year,25-year,50-year,1pct_min,100-year,1pct_plu,500-year
River Rch & RM= MDE S 094,Reach-1,3682
     310     411     491     293     585    1166     828
Boundary for River Rch & Prof#=MDE S 094,Reach-1,1
Up Type=0
Dn Type=3
Dn Slope=0.005
Boundary for River Rch & Prof#=MDE S 094,Reach-1,2
Up Type=0
Dn Type=3
Dn Slope=0.005
Boundary for River Rch & Prof#=MDE S 094,Reach-1,3
Up Type=0
Dn Type=3
Dn Slope=0.005
Boundary for River Rch & Prof#=MDE S 094,Reach-1,4
Up Type=0
Dn Type=3
Dn Slope=0.005
Boundary for River Rch & Prof#=MDE S 094,Reach-1,5
Up Type=0
Dn Type=3
Dn Slope=0.005
Boundary for River Rch & Prof#=MDE S 094,Reach-1,6
Up Type=0
Dn Type=3
Dn Slope=0.005
Boundary for River Rch & Prof#=MDE S 094,Reach-1,7
Up Type=0
Dn Type=3
Dn Slope=0.005

--- MDE S 094.g01 (geometry) ---

Geom Title=Existing Conditions

River Reach=MDE S 094,Reach-1
Reach XY= 30
      2297879.00      7118310.00      2297928.55      7118194.81
      2297930.22      7117820.50      2297978.95      7117739.96
      2297977.63      7117620.44      2297937.04      7117556.68
      2298075.24      7117308.44      2298086.82      7117153.81
      2298312.33      7116926.65      2298388.68      7116899.22
      2298499.38      7116790.16      2298561.96      7116676.50
      2298668.37      7116620.00      2298726.75      7116504.07
      2298732.76      7116361.55      2298811.96      7116226.04
      2298838.87      7116220.94      2298925.68      7116301.96
      2298992.75      7116273.48      2299026.85      7116315.50
      2299036.79      7116416.57      2299080.77      7116457.15
      2299120.46      7116457.42      2299265.44      7116222.99
      2299322.91      7116211.97      2299382.41      7116252.18
      2299512.35      7116126.68      2299539.78      7116050.32
      2299723.65      7115862.50      2299729.00      7115760.00

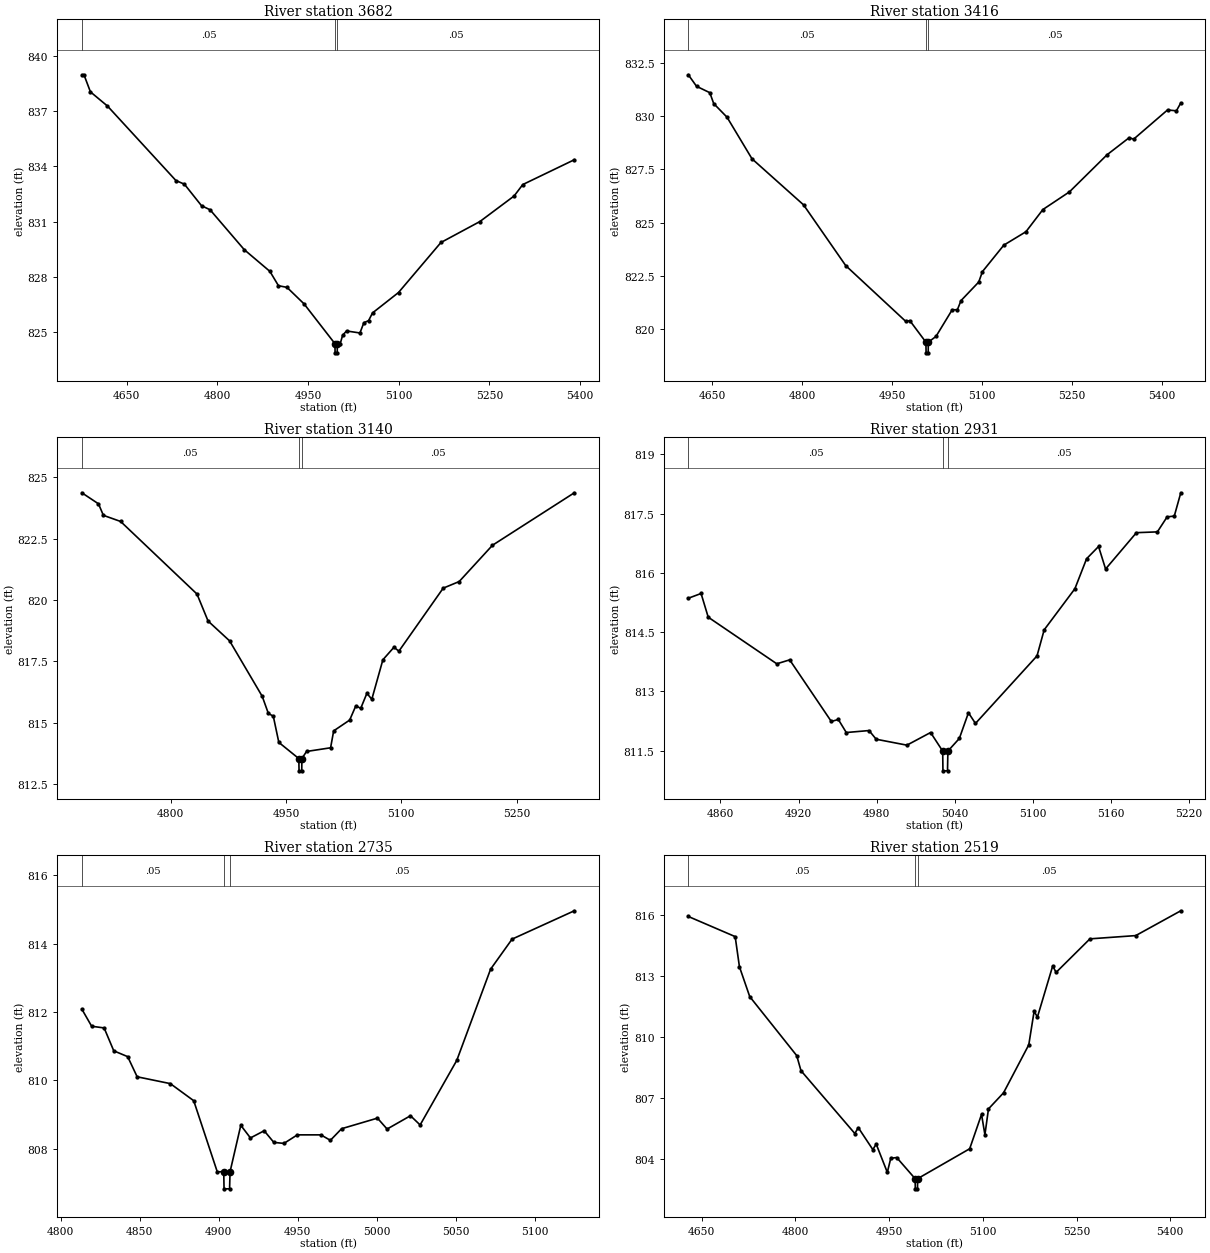
Type RM Length L Ch R = 1,3682,266,266,266
BEGIN DESCRIPTION:
MDE S 094 4.0
END DESCRIPTION:
XS GIS Cut Line= 3
      2298229.01      7118260.01      2297929.00      7117960.00
      2297628.99      7118210.01
#Sta/Elev= 30
  4575.7  838.98  4579.2  838.98  4589.9  838.05  4618.1  837.28  4731.3  833.23
  4745.4  833.03  4773.7  831.86  4787.8  831.64  4844.4  829.47  4886.8  828.29
  4901.0  827.51  4915.1  827.42  4943.4  826.52  4994.4  824.36  4994.7  823.86
  4998.2  823.86  4998.4  824.36  5003.2  824.36  5007.1  824.81  5013.6  825.05
  5035.8  824.94  5042.3  825.50  5050.1  825.61  5056.6  826.03  5099.6  827.14
  5169.8  829.86  5234.3  831.00  5290.9  832.39  5305.2  833.01  5390.5  834.36
#Mann=3,-1,0
  4575.7    0.05       0  4994.4    0.04       0  4998.4    0.05       0
Bank Sta=4994.4,4998.4
Exp/Cntr=0.3,0.1

Type RM Length L Ch R = 1,3416,276,276,276
BEGIN DESCRIPTION:
MDE S 094 3.0
END DESCRIPTION:
XS GIS Cut Line= 3
      2298229.01      7118010.02      2297979.00      7117710.00
      2297629.04      7117959.97
#Sta/Elev= 30
  4610.2  831.94  4623.9  831.40  4646.0  831.10  4652.5  830.59  4674.7  829.95
  4716.3  828.00  4802.2  825.84  4872.5  822.99  4972.7  820.37  4979.3  820.41
  5006.1  819.40  5006.4  818.90  5009.9  818.90  5010.1  819.40  5022.9  819.67
  5049.9  820.92  5058.5  820.92  5064.6  821.35  5094.1  822.22  5100.3  822.71
  5135.9  823.95  5172.8  824.58  5201.0  825.62  5245.3  826.45  5308.0  828.19
  5344.8  828.99  5352.2  828.92  5408.7  830.29  5423.5  830.25  5430.8  830.62
#Mann=3,-1,0
  4610.2    0.05       0  5006.1    0.04       0  5010.1    0.05       0
Bank Sta=5006.1,5010.1
Exp/Cntr=0.3,0.1

Type RM Length L Ch R = 1,3140,209,209,209
BEGIN DESCRIPTION:
MDE S 094 2.0
END DESCRIPTION:
XS GIS Cut Line= 3
      2298229.00      7117660.00      2297979.00      7117460.00
      2297729.01      7117660.00
#Sta/Elev= 30
  4684.6  824.37  4706.2  823.92  4712.6  823.45  4735.0  823.20  4834.3  820.24
  4848.7  819.14  4876.7  818.33  4919.1  816.07  4927.1  815.37  4933.5  815.26
  4940.7  814.19  4966.7  813.53  4967.0  813.03  4970.5  813.03  4970.7  813.53
  4976.7  813.82  5008.0  813.97  5012.0  814.66  5032.8  815.10  5040.8  815.68
  5047.2  815.58  5055.2  816.19  5061.6  815.95  5076.0  817.56  5090.4  818.07
  5096.8  817.91  5154.4  820.48  5175.2  820.75  5218.5  822.23  5324.9  824.37
#Mann=3,-1,0
  4684.6    0.05       0  4966.7   0.033       0  4970.7    0.05       0
Bank Sta=4966.7,4970.7
Exp/Cntr=0.3,0.1

Type RM Length L Ch R = 1,2931,196,196,196
BEGIN DESCRIPTION:
Mapping XS 00568b6c
END DESCRIPTION:
XS GIS Cut Line= 2
      2298230.73      7117349.85      2297882.42      7117201.72
#Sta/Elev= 30
  4835.3  815.36  4845.1  815.48  4850.6  814.88  4903.3  813.70  4913.2  813.80
  4945.2  812.24  4950.6  812.29  4956.7  811.96  4974.2  812.01  4979.7  811.79
  5003.3  811.64  5021.5  811.96  5030.8  811.49  5031.0  810.99  5034.5  810.99
  5034.8  811.49  5043.6  811.81  5050.6  812.46  5056.0  812.19  5103.3  813.90
  5108.8  814.56  5132.4  815.60  5141.4  816.36  5150.6  816.67  5156.0  816.10
  5179.7  817.02  5195.8  817.04  5203.3  817.42  5208.8  817.44  5213.8  818.03
#Mann=3,-1,0
  4835.3    0.05       0  5030.8    0.04       0  5034.8    0.05       0
Bank Sta=5030.8,5034.8
Exp/Cntr=0.3,0.1

Type RM Length L Ch R = 1,2735,216,216,216
BEGIN DESCRIPTION:
Mapping XS 21bcc970
END DESCRIPTION:
XS GIS Cut Line= 3
      2298284.13      7117214.03      2298056.48      7117056.42
      2298022.13      7117062.06
#Sta/Elev= 30
  4813.5  812.08  4819.7  811.58  4827.6  811.53  4833.7  810.86  4842.5  810.69
  4848.5  810.10  4869.5  809.90  4884.3  809.40  4899.2  807.32  4903.3  807.32
  4903.5  806.82  4907.0  806.82  4907.3  807.32  4914.1  808.68  4920.2  808.31
  4928.9  808.52  4935.0  808.18  4941.4  808.15  4949.9  808.40  4964.8  808.40
  4970.8  808.24  4977.9  808.58  5000.6  808.89  5006.7  808.57  5021.5  808.96
  5027.6  808.69  5050.8  810.58  5072.2  813.25  5085.8  814.13  5125.2  814.96
#Mann=3,-1,0
  4813.5    0.05       0  4903.3   0.033       0  4907.3    0.05       0
Bank Sta=4903.3,4907.3
Exp/Cntr=0.3,0.1

Type RM Length L Ch R = 1,2519,0,0,0
BEGIN DESCRIPTION:
MDE S 094 1.0
END DESCRIPTION:
XS GIS Cut Line= 3
      2298433.93      7117294.77      2298277.40      7116942.53
      2297902.47      7117089.60
#Sta/Elev= 30
  4628.7  815.91  4703.7  814.92  4710.5  813.44  4727.0  811.97  4802.2  809.07
  4809.0  808.33  4895.2  805.24  4900.7  805.53  4924.0  804.45  4929.4  804.72
  4947.2  803.33  4952.7  804.02  4962.2  804.06  4991.7  803.02  4992.0  802.52
  4995.5  802.52  4995.7  803.02  5079.0  804.49  5098.0  806.18  5103.4  805.18
  5109.1  806.45  5133.2  807.24  5173.6  809.60  5182.1  811.24  5187.5  810.97
  5211.9  813.48  5217.3  813.16  5271.5  814.81  5344.8  814.97  5416.9  816.19
#Mann=3,-1,0
  4628.7    0.05       0  4991.7   0.033       0  4995.7    0.05       0
Bank Sta=4991.7,4995.7
Exp/Cntr=0.3,0.1

Chan Stop Cuts=-1