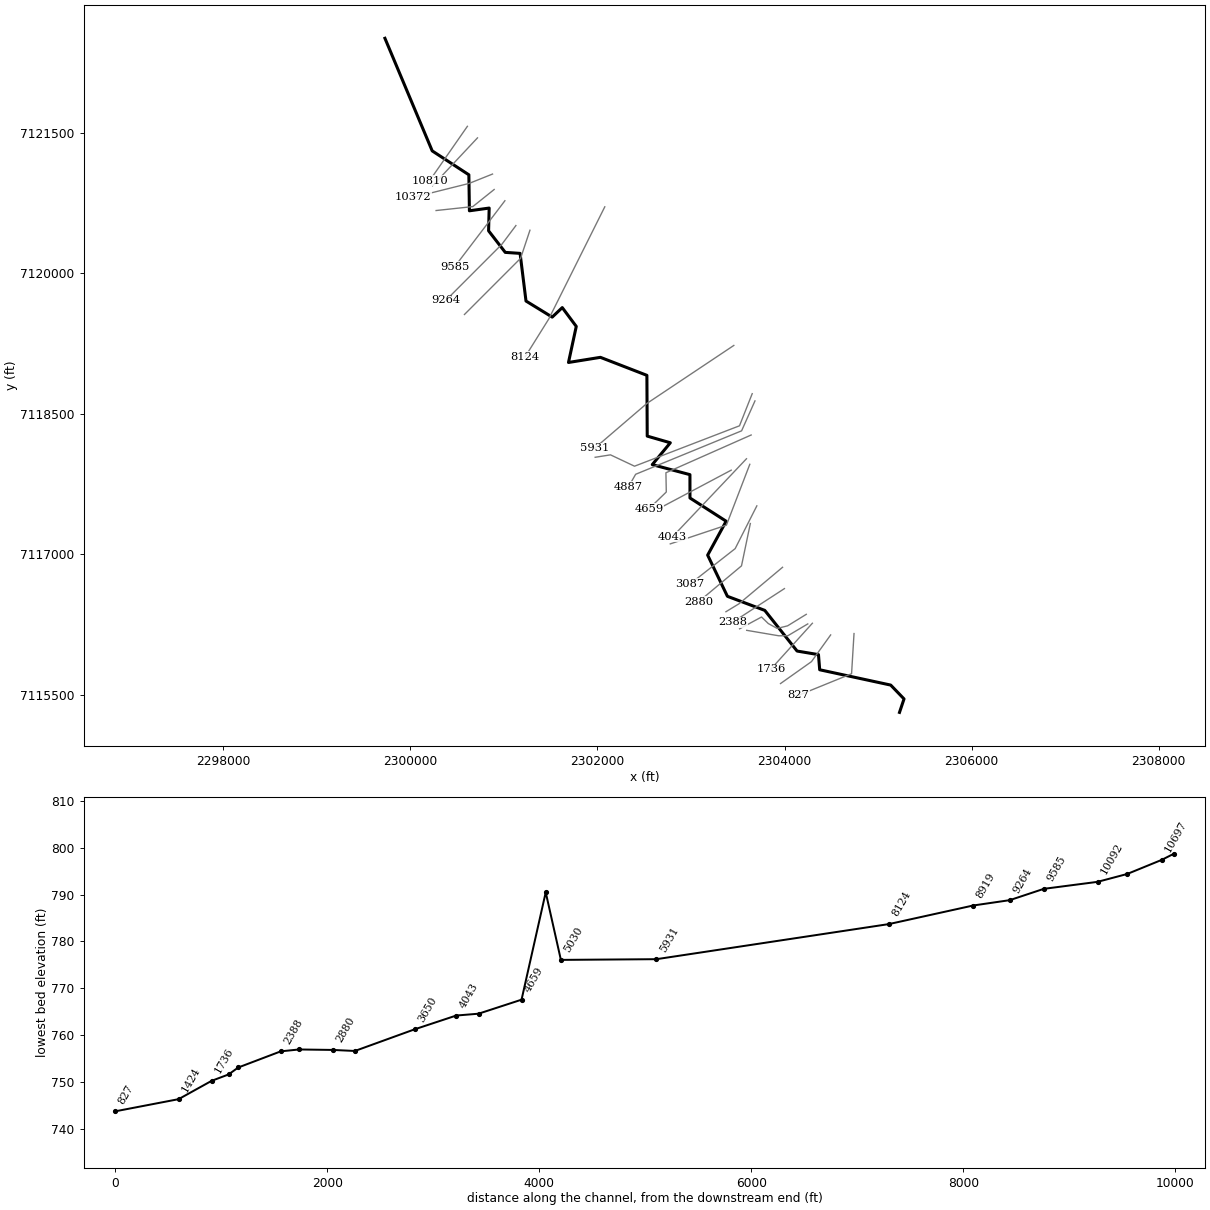
--- MDE S 095.prj (project) ---

Proj Title=MDE S 095 Base Level Engineering
Current Plan=p01
Default Exp/Contr=0.3,0.1
English Units
Geom File=g01
Flow File=f01
Plan File=p01
Y Axis Title=Elevation
X Axis Title(PF)=Main Channel Distance
X Axis Title(XS)=Station
BEGIN DESCRIPTION:
MDE S 095
END DESCRIPTION:
DSS File=dss
DSS Export Rating Curves= 0
DSS Export Rating Curve Sorted= 0
DSS Export Volume Flow Curves= 0
DXF OffsetX= 0
DXF OffsetY= 0
DXF ScaleX= 1
DXF ScaleY= 10

--- MDE S 095.p01 (plan) ---

Plan Title=Multiple Run
Program Version=4.10
Short Identifier=Multiple Run
Geom File=g01
Flow File=f01
Subcritical Flow
K Sum by GR= 0
Std Step Tol= 0.01
Critical Tol= 0.01
Num of Std Step Trials= 20
Max Error Tol= 0.3
Flow Tol Ratio= 0.001
Split Flow NTrial= 30
Split Flow Tol= 0.02
Split Flow Ratio= 0.02
Log Output Level= 0
Friction Slope Method= 1
Unsteady Friction Slope Method= 2
Unsteady Bridges Friction Slope Method= 1
Parabolic Critical Depth
Global Vel Dist= 1 , 1 , 1
Global Log Level= 0
CheckData=True
Encroach Param=-1 ,0,0, 0
BEGIN DESCRIPTION:
Multiple Run
END DESCRIPTION:
Computation Interval=1HOUR
Output Interval=1HOUR
Run HTab= 0
Run UNet= 0
Run PostProcess= 0
Run WQNet= 0
UNET Theta= 1
UNET Theta Warmup= 1
UNET ZTol= 0.02
UNET ZSATol= 0.05
UNET MxIter= 20
UNET MaxInSteps= 0
UNET DtIC= 0
UNET DtMin= 0
UNET MaxCRTS= 20
UNET WFStab= 2
UNET SFStab= 1
UNET WFX= 1
UNET SFX= 1
UNET DSS MLevel= 4
UNET DZMax Abort= 100
UNET Convert EG Bridges= 0
UNET Use Existing IB Tables=-1
UNET Froude Reduction=False
UNET Froude Limit= 1
UNET Froude Power= 10
UNET Time Slicing=0,0, 5
UNET Junction Losses=0
Instantaneous Interval=1HOUR
DSS File=dss
Write IC File= 0
Write IC File at Sim End=0
Echo Input=False
Echo Parameters=False
Echo Output=False
Write Detailed= 0
WQ AD Non Conservative
WQ ULTIMATE=-1
WQ Max Comp Step=1HOUR
WQ Output Interval=15MIN
WQ Output Selected Increments= 0
WQ Output face flow=0
WQ Output face velocity=0
WQ Output face area=0
WQ Output face dispersion=0
WQ Output cell volume=0
WQ Output cell surface area=0
WQ Output cell continuity=0
WQ Output cumulative cell continuity=0
WQ Output face conc=0
WQ Output face dconc_dx=0
WQ Output face courant=0
WQ Output face peclet=0
WQ Output face adv mass=0
WQ Output face disp mass=0
WQ Output cell mass=0
WQ Output cell source sink temp=0
WQ Output cell source sink nsm=0
WQ Output MaxMinRange=-1
WQ Daily Max Min Mean=-1
WQ Daily Range=0
WQ Daily Time=0
WQ Create Restart=0
WQ Fixed Restart=0
WQ System Summary=0
WQ Use Fixed Temperature=0
Sorting and Armoring Iterations= 10
XS Update Threshold= 0.02
Hydraulics Update Threshold= 0.02
Energy Slope Method= 1
Volume Change Method= 0
XS Weighting Method= 0
Number of US Weighted Cross Sections= 1
Number of DS Weighted Cross Sections= 1
Upstream XS Weight=0.25
Main XS Weight=0.5
Downstream XS Weight=0.25
Number of DS XS's Weighted with US Boundary= 1
Upstream Boundary Weight= 1
Weight of XSs Associated with US Boundary= 0
Number of US XS's Weighted with DS Boundary= 1
Downstream Boundary Weight= 0.5
Weight of XSs Associated with DS Boundary= 0.5
Sediment Output Level= 4
Mass or Volume Output= 0
Output Increment Type= 1
Profile and TS Output Increment= 10
XS Output Flag= 0
XS Output Increment= 10
Disregard all LS=0
Disregard all Conn=0
Disregard all Breaches=0
Disregard all Pumps=0

--- MDE S 095.f01 (steady flow) ---

Flow Title=Multiple
Number of Profiles=7
Profile Names=10-year,25-year,50-year,1pct_min,100-year,1pct_plu,500-year
River Rch & RM= MDE S 095,Reach-1,10810
     600     825    1011     616    1228    2451    1817
River Rch & RM= MDE S 095,Reach-1,8124
     751    1045    1291     792    1579    3151    2370
River Rch & RM= MDE S 095,Reach-1,5931
     886    1241    1540     948    1891    3772    2859
River Rch & RM= MDE S 095,Reach-1,2560
    1017    1436    1791    1107    2210    4409    3373
Boundary for River Rch & Prof#=MDE S 095,Reach-1,1
Up Type=0
Dn Type=3
Dn Slope=0.005
Boundary for River Rch & Prof#=MDE S 095,Reach-1,2
Up Type=0
Dn Type=3
Dn Slope=0.005
Boundary for River Rch & Prof#=MDE S 095,Reach-1,3
Up Type=0
Dn Type=3
Dn Slope=0.005
Boundary for River Rch & Prof#=MDE S 095,Reach-1,4
Up Type=0
Dn Type=3
Dn Slope=0.005
Boundary for River Rch & Prof#=MDE S 095,Reach-1,5
Up Type=0
Dn Type=3
Dn Slope=0.005
Boundary for River Rch & Prof#=MDE S 095,Reach-1,6
Up Type=0
Dn Type=3
Dn Slope=0.005
Boundary for River Rch & Prof#=MDE S 095,Reach-1,7
Up Type=0
Dn Type=3
Dn Slope=0.005

--- MDE S 095.g01 (geometry) ---

Geom Title=Existing Conditions

River Reach=MDE S 095,Reach-1
Reach XY= 30
      2299729.00      7122510.00      2300234.36      7121307.30
      2300626.06      7121052.03      2300632.05      7120667.54
      2300843.15      7120696.66      2300836.99      7120453.63
      2301015.20      7120223.37      2301173.64      7120212.78
      2301236.84      7119703.81      2301516.95      7119531.96
      2301624.40      7119633.62      2301774.10      7119432.58
      2301690.93      7119047.50      2302032.34      7119102.37
      2302529.00      7118910.00      2302532.54      7118260.97
      2302779.48      7118189.85      2302586.47      7117956.38
      2302989.12      7117849.37      2302989.43      7117600.21
      2303376.10      7117352.08      2303178.39      7116989.96
      2303389.63      7116550.00      2303789.10      7116399.62
      2304134.45      7115965.21      2304362.96      7115927.14
      2304375.99      7115765.46      2305135.06      7115601.86
      2305277.41      7115453.98      2305229.00      7115310.00

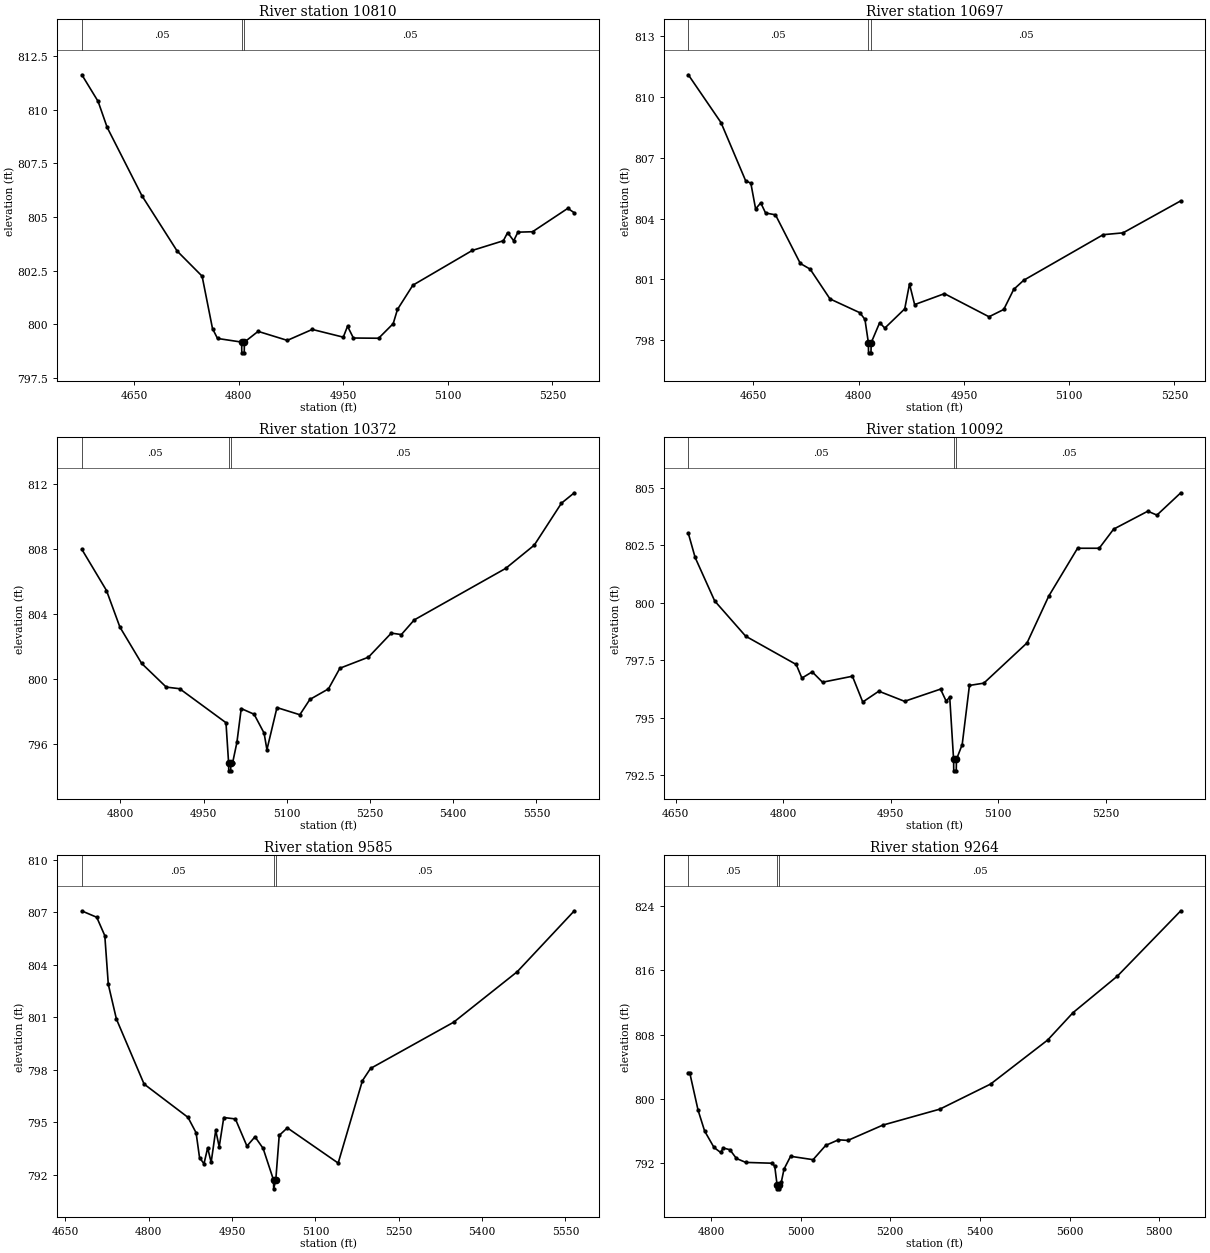
Type RM Length L Ch R = 1,10810,113,113,113
BEGIN DESCRIPTION:
Mapping XS 7a2c4e7e
END DESCRIPTION:
XS GIS Cut Line= 2
      2300610.33      7121569.77      2300206.91      7120989.90
#Sta/Elev= 30
  4575.0  811.62  4598.3  810.38  4611.3  809.17  4661.1  805.99  4711.7  803.41
  4747.5  802.24  4762.4  799.80  4769.6  799.34  4804.2  799.17  4804.4  798.67
  4807.9  798.67  4808.2  799.17  4827.8  799.67  4869.7  799.25  4905.5  799.76
  4950.0  799.40  4956.1  799.91  4964.5  799.36  5000.7  799.35  5021.6  800.03
  5027.7  800.69  5049.8  801.82  5135.1  803.44  5179.6  803.89  5185.7  804.27
  5194.4  803.89  5200.5  804.29  5221.5  804.31  5272.1  805.40  5281.4  805.19
#Mann=3,-1,0
  4575.0    0.05       0  4804.2   0.033       0  4808.2    0.05       0
Bank Sta=4804.2,4808.2
Exp/Cntr=0.3,0.1

Type RM Length L Ch R = 1,10697,325,325,325
BEGIN DESCRIPTION:
Mapping XS d7fa7d06
END DESCRIPTION:
XS GIS Cut Line= 2
      2300718.27      7121446.38      2300238.04      7120934.62
#Sta/Elev= 30
  4557.3  811.10  4603.9  808.74  4639.0  805.87  4646.4  805.75  4653.2  804.48
  4660.5  804.78  4667.4  804.28  4681.5  804.19  4716.9  801.79  4730.9  801.51
  4759.2  800.04  4801.7  799.36  4809.0  799.03  4813.9  797.88  4814.1  797.38
  4817.6  797.38  4817.9  797.88  4830.0  798.87  4837.3  798.60  4865.7  799.55
  4872.5  800.78  4879.8  799.76  4922.3  800.30  4985.8  799.16  5006.8  799.52
  5021.0  800.51  5035.2  800.96  5148.5  803.21  5176.8  803.30  5259.1  804.88
#Mann=3,-1,0
  4557.3    0.05       0  4813.9   0.033       0  4817.9    0.05       0
Bank Sta=4813.9,4817.9
Exp/Cntr=0.3,0.1

Type RM Length L Ch R = 1,10372,280,280,280
BEGIN DESCRIPTION:
MDE S 095 19.0
END DESCRIPTION:
XS GIS Cut Line= 3
      2300878.97      7121059.99      2300629.00      7120960.00
      2300028.99      7120810.00
#Sta/Elev= 30
  4730.5  808.00  4774.9  805.47  4799.1  803.22  4838.2  800.99  4882.6  799.53
  4906.8  799.43  4990.3  797.34  4995.0  794.88  4995.3  794.38  4998.8  794.38
  4999.0  794.88  5002.3  794.88  5010.0  796.13  5017.8  798.21  5041.0  797.86
  5059.0  796.70  5064.1  795.68  5082.2  798.27  5123.4  797.83  5141.5  798.77
  5175.0  799.42  5195.6  800.69  5247.1  801.37  5288.3  802.85  5306.4  802.76
  5329.6  803.66  5494.5  806.83  5546.0  808.26  5595.0  810.84  5618.2  811.48
#Mann=3,-1,0
  4730.5    0.05       0  4995.0   0.033       0  4999.0    0.05       0
Bank Sta=4995,4999
Exp/Cntr=0.3,0.1

Type RM Length L Ch R = 1,10092,507,507,507
BEGIN DESCRIPTION:
Mapping XS 5399c768
END DESCRIPTION:
XS GIS Cut Line= 3
      2300896.53      7120894.90      2300668.45      7120712.49
      2300275.86      7120670.34
#Sta/Elev= 30
  4667.6  803.02  4677.1  801.97  4704.4  800.08  4747.6  798.55  4818.1  797.32
  4826.0  796.73  4840.4  797.00  4854.8  796.55  4896.5  796.81  4910.9  795.69
  4933.3  796.16  4969.2  795.72  5019.4  796.25  5027.2  795.73  5032.2  795.90
  5037.6  793.20  5037.8  792.70  5041.3  792.70  5041.6  793.20  5049.6  793.84
  5059.7  796.41  5079.8  796.51  5140.1  798.26  5170.3  800.29  5210.5  802.37
  5240.7  802.37  5260.8  803.20  5308.5  803.98  5321.2  803.81  5354.5  804.78
#Mann=3,-1,0
  4667.6    0.05       0  5037.6   0.033       0  5041.6    0.05       0
Bank Sta=5037.6,5041.6
Exp/Cntr=0.3,0.1

Type RM Length L Ch R = 1,9585,321,321,321
BEGIN DESCRIPTION:
Mapping XS 72242918
END DESCRIPTION:
XS GIS Cut Line= 2
      2301011.33      7120774.88      2300474.23      7120069.86
#Sta/Elev= 30
  4679.6  807.07  4706.4  806.71  4720.9  805.66  4727.2  802.88  4741.8  800.90
  4791.6  797.19  4870.6  795.29  4885.2  794.41  4891.4  792.99  4899.4  792.64
  4906.0  793.55  4912.3  792.72  4920.5  794.55  4926.8  793.61  4935.0  795.28
  4955.9  795.20  4976.7  793.65  4991.2  794.18  5005.8  793.52  5024.6  791.71
  5024.8  791.21  5028.6  791.71  5034.8  794.26  5049.4  794.69  5140.9  792.68
  5184.5  797.38  5199.1  798.08  5348.7  800.72  5463.1  803.60  5565.9  807.08
#Mann=3,-1,0
  4679.6    0.05       0  5024.6   0.033       0  5028.6    0.05       0
Bank Sta=5024.6,5028.6
Exp/Cntr=0.3,0.1

Type RM Length L Ch R = 1,9264,345,345,345
BEGIN DESCRIPTION:
MDE S 095 16.0
END DESCRIPTION:
XS GIS Cut Line= 3
      2301128.98      7120509.98      2300979.00      7120310.00
      2300379.00      7119710.00
#Sta/Elev= 30
  4749.6  803.26  4752.7  803.26  4771.4  798.58  4786.0  795.99  4806.9  793.95
  4821.4  793.34  4827.7  793.88  4842.3  793.67  4856.9  792.58  4877.7  792.09
  4936.0  791.99  4942.3  791.64  4947.6  789.30  4947.8  788.80  4951.3  788.80
  4951.6  789.30  4956.9  789.61  4963.1  791.26  4977.7  792.85  5027.9  792.43
  5056.1  794.21  5084.4  794.90  5105.6  794.83  5183.4  796.73  5310.7  798.72
  5423.8  801.84  5551.1  807.32  5607.7  810.73  5706.7  815.28  5848.1  823.41
#Mann=3,-1,0
  4749.6    0.05       0  4947.6   0.033       0  4951.6    0.05       0
Bank Sta=4947.6,4951.6
Exp/Cntr=0.3,0.1

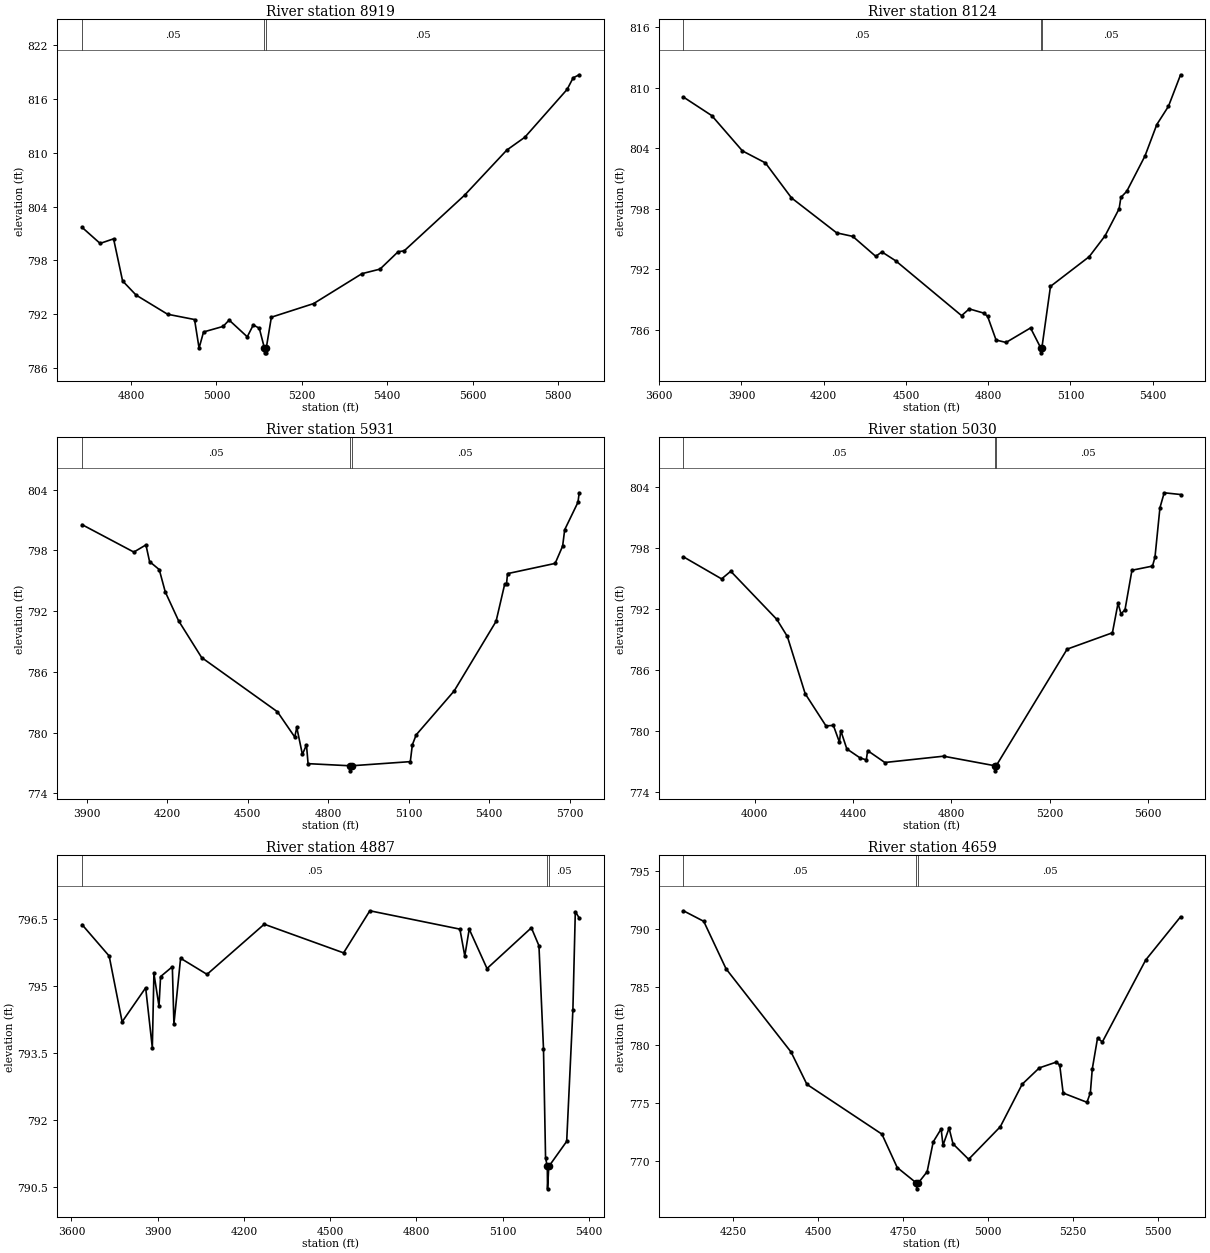
Type RM Length L Ch R = 1,8919,795,795,795
BEGIN DESCRIPTION:
MDE S 095 15.0
END DESCRIPTION:
XS GIS Cut Line= 3
      2301279.01      7120460.02      2301179.00      7120160.00
      2300578.99      7119559.99
#Sta/Elev= 30
  4685.2  801.67  4727.4  799.88  4759.0  800.39  4780.1  795.69  4811.7  794.11
  4885.5  791.97  4948.7  791.38  4959.3  788.19  4969.8  789.99  5015.6  790.61
  5029.7  791.32  5072.2  789.45  5086.3  790.77  5100.4  790.41  5112.6  788.16
  5112.8  787.66  5116.3  787.66  5116.6  788.16  5128.7  791.64  5227.7  793.16
  5340.9  796.50  5383.3  797.01  5425.7  798.95  5439.9  799.05  5581.3  805.26
  5680.3  810.30  5722.7  811.74  5821.7  817.08  5835.8  818.37  5850.0  818.71
#Mann=3,-1,0
  4685.2    0.05       0  5112.6   0.033       0  5116.6    0.05       0
Bank Sta=5112.6,5116.6
Exp/Cntr=0.3,0.1

Type RM Length L Ch R = 1,8124,2193,2193,2193
BEGIN DESCRIPTION:
MDE S 095 13.0
END DESCRIPTION:
XS GIS Cut Line= 3
      2302078.98      7120709.97      2301479.00      7119510.00
      2301229.00      7119110.00
#Sta/Elev= 30
  3688.6  809.07  3792.0  807.23  3903.8  803.73  3987.6  802.54  4082.7  799.07
  4247.6  795.60  4306.3  795.25  4390.1  793.27  4412.5  793.71  4462.8  792.83
  4703.2  787.39  4731.1  788.06  4784.2  787.64  4798.2  787.31  4829.0  784.97
  4865.3  784.73  4954.7  786.17  4991.7  784.20  4992.1  783.70  4996.1  784.20
  5027.4  790.29  5168.8  793.24  5226.6  795.31  5277.8  797.99  5284.3  799.12
  5305.6  799.72  5372.2  803.23  5415.2  806.34  5457.7  808.15  5501.9  811.28
#Mann=3,-1,0
  3688.6    0.05       0  4991.7   0.033       0  4996.1    0.05       0
Bank Sta=4991.7,4996.1
Exp/Cntr=0.3,0.1

Type RM Length L Ch R = 1,5931,901,901,901
BEGIN DESCRIPTION:
MDE S 095 9.0
END DESCRIPTION:
XS GIS Cut Line= 5
      2303458.14      7119229.43      2303279.00      7119110.00
      2302529.00      7118610.00      2302179.00      7118310.00
      2301970.86      7118131.60
#Sta/Elev= 30
  3883.3  800.55  4076.1  797.84  4121.1  798.55  4134.7  796.90  4170.7  796.11
  4193.2  793.90  4242.8  791.05  4328.5  787.42  4610.9  782.06  4675.5  779.56
  4683.0  780.51  4704.0  777.84  4719.1  778.79  4725.1  776.93  4881.8  776.72
  4882.4  776.22  4886.9  776.72  5105.9  777.13  5113.6  778.80  5127.9  779.78
  5269.4  784.12  5425.3  790.99  5457.7  794.69  5464.3  794.69  5468.1  795.71
  5645.4  796.72  5673.3  798.43  5681.0  800.05  5730.4  802.76  5735.1  803.70
#Mann=3,-1,0
  3883.3    0.05       0  4881.8   0.033       0  4886.9    0.05       0
Bank Sta=4881.8,4886.9
Exp/Cntr=0.3,0.1

Type RM Length L Ch R = 1,5030,143,143,143
BEGIN DESCRIPTION:
Mapping XS 241927a7
END DESCRIPTION:
XS GIS Cut Line= 6
      2303654.74      7118714.30      2303548.93      7118447.28
      2303518.79      7118371.21      2302396.82      7117939.65
      2302139.85      7118060.88      2301976.28      7118034.90
#Sta/Elev= 30
  3710.4  797.12  3865.6  794.95  3902.8  795.70  4089.9  790.97  4132.8  789.29
  4205.3  783.66  4289.9  780.49  4319.9  780.54  4344.6  778.89  4349.9  780.03
  4374.6  778.23  4429.2  777.33  4453.9  777.15  4459.2  778.06  4529.2  776.89
  4767.8  777.51  4976.6  776.57  4977.3  776.07  4981.8  776.57  5270.2  788.04
  5454.3  789.65  5477.1  792.55  5489.2  791.51  5505.4  791.91  5533.7  795.80
  5617.2  796.21  5627.3  797.08  5647.5  801.95  5664.8  803.42  5731.3  803.25
#Mann=3,-1,0
  3710.4    0.05       0  4976.6    0.04       0  4981.8    0.05       0
Bank Sta=4976.6,4981.8
Exp/Cntr=0.3,0.1

Type RM Length L Ch R = 1,4887,228,228,228
BEGIN DESCRIPTION:
Mapping XS b0eb5cf4
END DESCRIPTION:
XS GIS Cut Line= 5
      2303684.21      7118637.13      2303603.43      7118456.51
      2303541.19      7118317.34      2302408.64      7117853.19
      2302331.80      7117718.22
#Sta/Elev= 30
  3636.9  796.37  3731.1  795.67  3776.2  794.20  3858.1  794.96  3881.3  793.62
  3886.8  795.28  3904.5  794.55  3910.0  795.21  3950.9  795.43  3956.4  794.15
  3979.6  795.62  4071.6  795.26  4270.6  796.38  4546.7  795.74  4638.0  796.68
  4951.4  796.27  4968.4  795.67  4983.8  796.27  5045.7  795.39  5200.0  796.30
  5226.4  795.90  5242.2  793.60  5249.4  791.16  5255.5  790.97  5256.2  790.47
  5260.7  790.97  5322.9  791.53  5344.5  794.47  5352.9  796.66  5366.5  796.52
#Mann=3,-1,0
  3636.9    0.05       0  5255.5   0.033       0  5260.7    0.05       0
Bank Sta=5255.5,5260.7
Exp/Cntr=0.3,0.1

Type RM Length L Ch R = 1,4659,406,406,406
BEGIN DESCRIPTION:
Mapping XS 50eda35b
END DESCRIPTION:
XS GIS Cut Line= 4
      2303643.54      7118272.95      2302732.40      7117869.55
      2302736.36      7117663.97      2302550.34      7117483.70
#Sta/Elev= 30
  4104.4  791.59  4164.1  790.68  4229.7  786.58  4420.7  779.40  4467.3  776.61
  4687.8  772.31  4732.7  769.43  4789.3  768.09  4790.0  767.59  4794.5  768.09
  4820.7  769.07  4838.5  771.64  4861.8  772.76  4867.3  771.36  4885.1  772.83
  4896.8  771.47  4942.6  770.14  5035.7  772.95  5100.0  776.62  5150.4  778.03
  5200.4  778.53  5210.4  778.26  5220.4  775.86  5290.4  775.06  5300.4  775.88
  5306.0  777.93  5321.5  780.60  5335.7  780.27  5463.0  787.34  5565.5  791.07
#Mann=3,-1,0
  4104.4    0.05       0  4789.3   0.033       0  4794.5    0.05       0
Bank Sta=4789.3,4794.5
Exp/Cntr=0.3,0.1

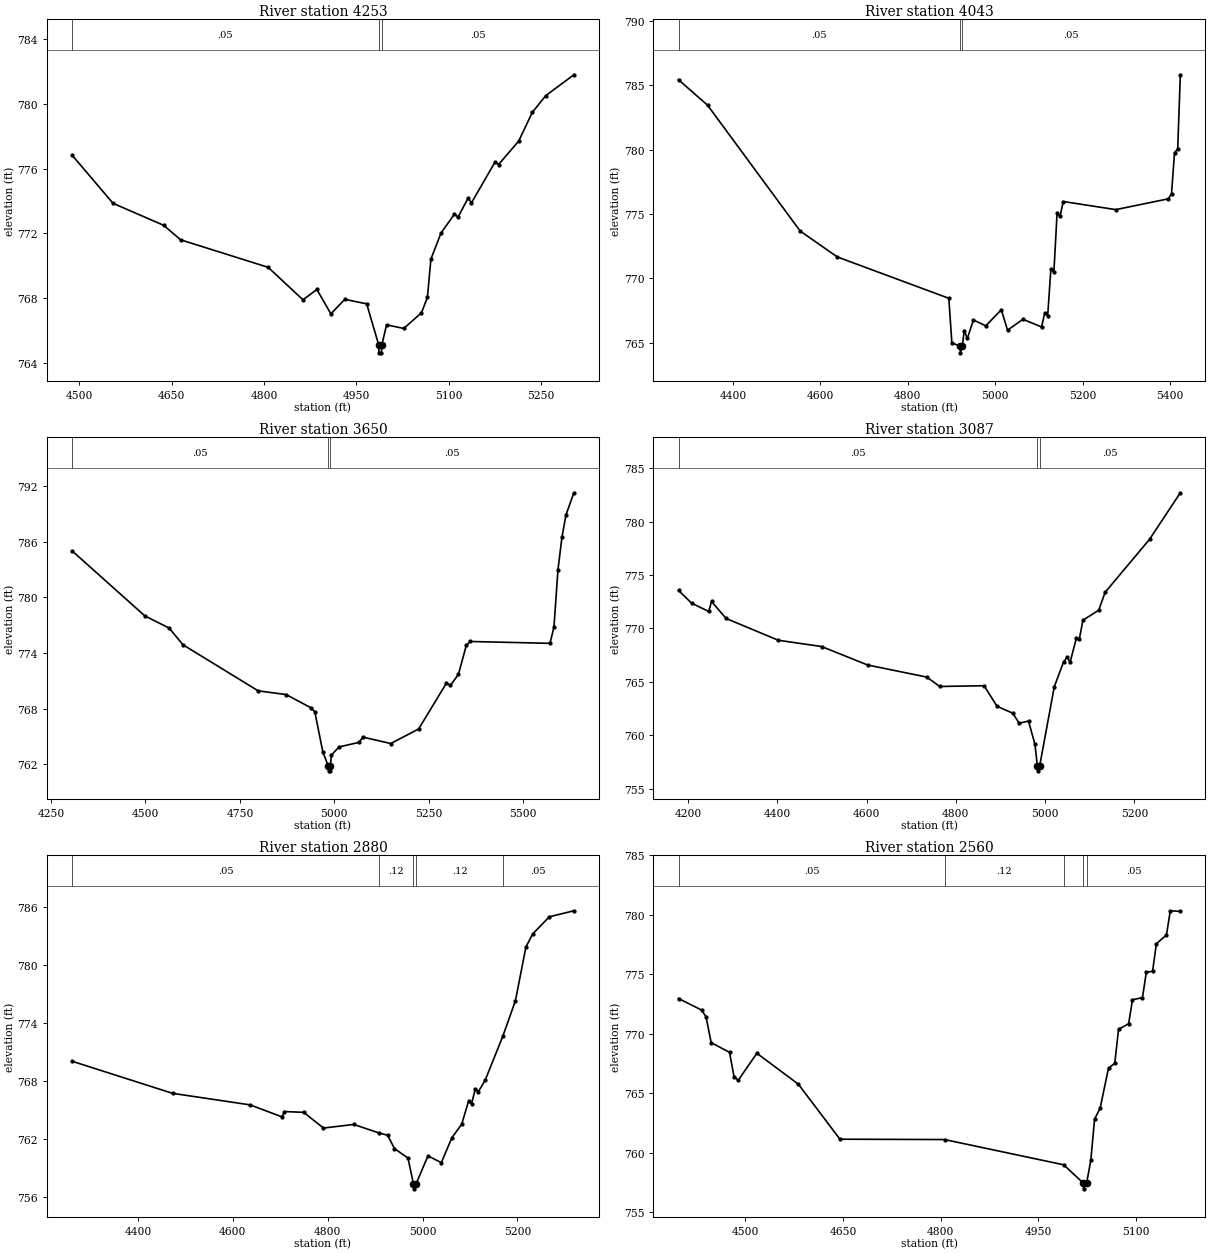
Type RM Length L Ch R = 1,4253,210,210,210
BEGIN DESCRIPTION:
Mapping XS e29e2e84
END DESCRIPTION:
XS GIS Cut Line= 2
      2303430.36      7117897.39      2302710.32      7117515.38
#Sta/Elev= 30
  4488.1  776.83  4554.6  773.85  4636.8  772.49  4664.5  771.59  4806.6  769.89
  4863.2  767.88  4885.8  768.52  4908.5  767.01  4931.1  767.91  4966.7  767.63
  4986.1  765.10  4986.8  764.60  4990.6  764.60  4991.3  765.10  4999.0  766.33
  5027.0  766.11  5055.7  767.08  5065.3  768.03  5071.0  770.40  5087.3  772.00
  5109.3  773.19  5114.9  772.99  5131.3  774.16  5136.9  773.88  5175.3  776.41
  5180.9  776.25  5213.6  777.70  5235.6  779.47  5257.5  780.51  5303.2  781.80
#Mann=3,-1,0
  4488.1    0.05       0  4986.1   0.033       0  4991.3    0.05       0
Bank Sta=4986.1,4991.3
Exp/Cntr=0.3,0.1

Type RM Length L Ch R = 1,4043,393,393,393
BEGIN DESCRIPTION:
Mapping XS c8c34116
END DESCRIPTION:
XS GIS Cut Line= 2
      2303593.41      7118019.17      2302803.58      7117186.74
#Sta/Elev= 30
  4275.7  785.43  4342.0  783.46  4554.0  773.67  4639.0  771.66  4893.8  768.45
  4900.7  765.00  4919.4  764.71  4920.2  764.21  4924.7  764.71  4929.0  765.93
  4936.2  765.33  4950.0  766.76  4978.3  766.31  5013.9  767.56  5028.1  765.97
  5063.3  766.82  5105.8  766.22  5113.0  767.28  5119.9  767.11  5127.2  770.73
  5134.1  770.50  5141.3  775.04  5148.2  774.83  5155.5  775.97  5275.6  775.34
  5395.8  776.18  5403.1  776.58  5409.9  779.77  5417.2  780.06  5423.2  785.82
#Mann=3,-1,0
  4275.7    0.05       0  4919.4   0.033       0  4924.7    0.05       0
Bank Sta=4919.4,4924.7
Exp/Cntr=0.3,0.1

Type RM Length L Ch R = 1,3650,563,563,563
BEGIN DESCRIPTION:
MDE S 095 4.0
END DESCRIPTION:
XS GIS Cut Line= 3
      2303628.99      7117959.97      2303379.00      7117310.00
      2302779.04      7117110.01
#Sta/Elev= 30
  4305.6  785.03  4498.4  778.00  4562.7  776.69  4599.1  774.89  4798.4  769.91
  4872.3  769.51  4937.7  768.09  4948.4  767.65  4969.8  763.28  4984.3  761.77
  4985.1  761.27  4988.9  761.27  4989.6  761.77  4992.3  762.97  5012.5  763.85
  5065.2  764.34  5075.8  764.91  5149.6  764.22  5223.3  765.79  5297.1  770.75
  5307.7  770.51  5328.8  771.69  5349.8  774.86  5360.4  775.24  5571.2  775.04
  5581.7  776.80  5592.3  782.99  5602.8  786.48  5613.4  788.89  5634.4  791.30
#Mann=3,-1,0
  4305.6    0.05       0  4984.3   0.033       0  4989.6    0.05       0
Bank Sta=4984.3,4989.6
Exp/Cntr=0.3,0.1

Type RM Length L Ch R = 1,3087,207,207,207
BEGIN DESCRIPTION:
Mapping XS 7316c9f8
END DESCRIPTION:
XS GIS Cut Line= 3
      2303704.22      7117516.02      2303472.41      7117059.11
      2302990.46      7116681.84
#Sta/Elev= 30
  4178.6  773.56  4207.8  772.36  4246.2  771.59  4252.6  772.52  4285.1  770.93
  4402.1  768.89  4499.3  768.30  4602.4  766.57  4734.9  765.44  4763.8  764.56
  4863.3  764.63  4892.2  762.71  4927.5  762.06  4941.9  761.12  4962.8  761.32
  4977.2  759.15  4982.6  757.16  4983.4  756.66  4988.0  757.16  5020.6  764.54
  5041.4  766.86  5049.5  767.31  5055.9  766.81  5070.3  769.13  5076.7  769.02
  5084.8  770.77  5120.1  771.70  5134.5  773.38  5234.0  778.34  5303.0  782.70
#Mann=3,-1,0
  4178.6    0.05       0  4982.6   0.033       0  4988.0    0.05       0
Bank Sta=4982.6,4988
Exp/Cntr=0.3,0.1

Type RM Length L Ch R = 1,2880,320,320,320
BEGIN DESCRIPTION:
Mapping XS 6f9ab936
END DESCRIPTION:
XS GIS Cut Line= 3
      2303634.70      7117327.43      2303540.24      7116875.25
      2303083.00      7116493.01
#Sta/Elev= 30
  4261.1  770.04  4473.0  766.73  4636.5  765.54  4703.8  764.30  4708.9  764.85
  4749.4  764.77  4791.1  763.15  4855.0  763.52  4908.5  762.64  4926.4  762.41
  4940.7  761.04  4969.3  760.05  4980.9  757.38  4981.7  756.88  4986.3  757.38
  5011.4  760.28  5039.6  759.58  5061.7  762.14  5082.6  763.55  5096.9  765.91
  5103.4  765.66  5111.2  767.17  5117.7  766.90  5132.0  768.08  5169.3  772.63
  5195.8  776.28  5217.9  781.82  5232.2  783.17  5267.3  784.94  5319.0  785.56
#Mann=5,-1,0
  4261.1    0.05       0  4908.5    0.12       0  4980.9    0.07       0
  4986.3    0.12       0  5169.3    0.05       0
Bank Sta=4980.9,4986.3
Exp/Cntr=0.3,0.1

Type RM Length L Ch R = 1,2560,172,172,172
BEGIN DESCRIPTION:
MDE S 095 2.0
END DESCRIPTION:
XS GIS Cut Line= 3
      2303978.98      7116859.98      2303514.70      7116470.97
      2303373.77      7116385.18
#Sta/Elev= 30
  4397.2  772.97  4432.9  771.99  4439.5  771.42  4447.3  769.26  4475.5  768.45
  4482.4  766.41  4488.9  766.10  4517.5  768.37  4581.3  765.77  4645.1  761.15
  4805.8  761.12  4988.7  759.00  5018.6  757.48  5019.4  756.98  5024.0  757.48
  5030.4  759.37  5036.2  762.84  5044.7  763.75  5057.6  767.13  5067.2  767.52
  5073.0  770.38  5088.5  770.85  5094.4  772.86  5109.8  773.05  5115.7  775.19
  5125.3  775.25  5131.1  777.57  5146.6  778.31  5152.5  780.34  5167.9  780.29
#Mann=5,-1,0
  4397.2    0.05       0  4805.8    0.12       0  4988.7    0.05       0
  5018.6   0.033       0  5024.0    0.05       0
Bank Sta=5018.6,5024
Exp/Cntr=0.3,0.1

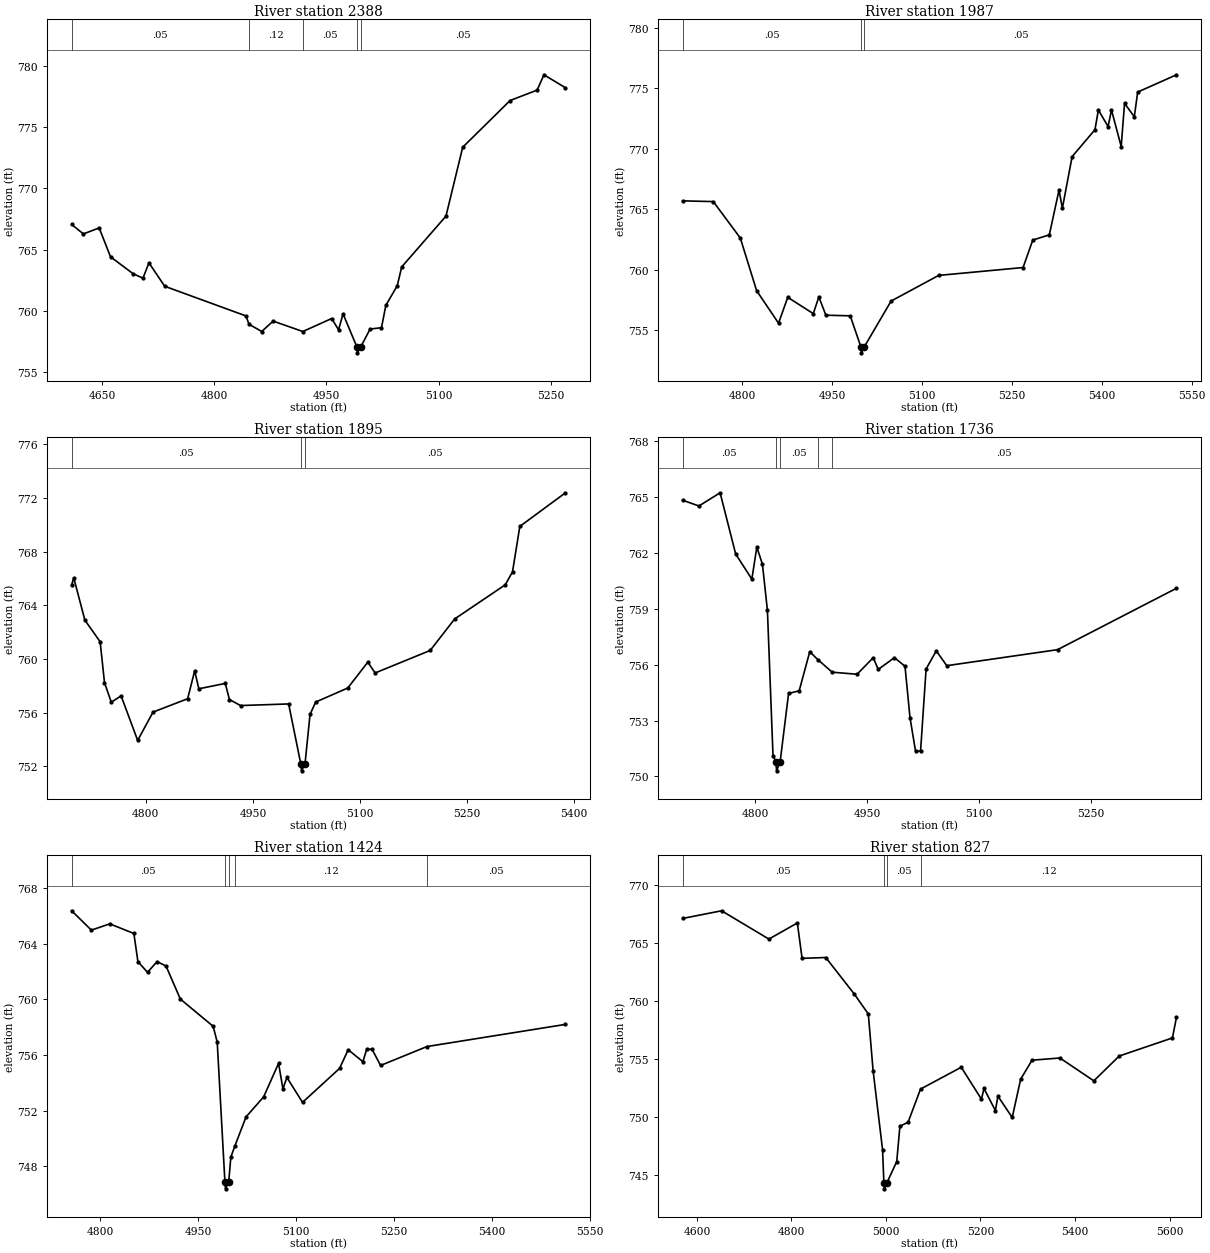
Type RM Length L Ch R = 1,2388,401,401,401
BEGIN DESCRIPTION:
Mapping XS 16c8ee69
END DESCRIPTION:
XS GIS Cut Line= 2
      2303999.06      7116632.35      2303444.85      7116272.66
#Sta/Elev= 30
  4609.1  767.05  4624.8  766.28  4645.9  766.77  4661.1  764.41  4691.4  763.03
  4704.5  762.67  4712.5  763.92  4733.6  762.01  4842.3  759.59  4846.4  758.91
  4863.4  758.32  4878.6  759.17  4918.4  758.32  4957.0  759.38  4966.2  758.46
  4972.2  759.76  4990.6  757.08  4991.4  756.58  4996.0  757.08  5008.4  758.52
  5023.6  758.63  5029.5  760.46  5044.7  762.05  5050.7  763.59  5109.9  767.73
  5132.3  773.35  5195.7  777.16  5231.9  778.01  5241.0  779.26  5269.8  778.20
#Mann=5,-1,0
  4609.1    0.05       0  4846.4    0.12       0  4918.4    0.05       0
  4990.6   0.033       0  4996.0    0.05       0
Bank Sta=4990.6,4996
Exp/Cntr=0.3,0.1

Type RM Length L Ch R = 1,1987,92,92,92
BEGIN DESCRIPTION:
Mapping XS 1da93519
END DESCRIPTION:
XS GIS Cut Line= 6
      2304232.51      7116357.56      2304032.93      7116234.56
      2303921.63      7116206.86      2303826.86      7116258.95
      2303754.22      7116328.97      2303519.97      7116202.67
#Sta/Elev= 30
  4700.4  765.70  4751.5  765.64  4796.6  762.63  4823.8  758.28  4860.4  755.59
  4875.8  757.73  4918.4  756.38  4927.7  757.76  4939.4  756.25  4980.1  756.20
  4997.8  753.64  4998.8  753.14  5003.6  753.64  5048.3  757.42  5127.7  759.54
  5268.6  760.19  5284.8  762.46  5312.4  762.89  5328.6  766.59  5334.2  765.09
  5350.5  769.36  5388.6  771.58  5394.3  773.21  5410.5  771.84  5416.2  773.21
  5432.4  770.19  5438.0  773.76  5454.3  772.65  5459.9  774.69  5524.7  776.12
#Mann=3,-1,0
  4700.4    0.05       0  4997.8   0.033       0  5003.6    0.05       0
Bank Sta=4997.8,5003.6
Exp/Cntr=0.3,0.1

Type RM Length L Ch R = 1,1895,159,159,159
BEGIN DESCRIPTION:
Mapping XS 9c6762d0
END DESCRIPTION:
XS GIS Cut Line= 4
      2304248.60      7116255.18      2304036.66      7116129.41
      2303938.24      7116128.38      2303595.93      7116186.58
#Sta/Elev= 30
  4696.0  765.51  4698.9  766.05  4714.5  762.89  4735.9  761.28  4742.0  758.23
  4751.5  756.77  4765.3  757.24  4788.5  753.92  4810.0  756.03  4858.6  757.03
  4868.4  759.12  4874.2  757.77  4911.3  758.17  4917.1  756.97  4932.7  756.52
  5000.1  756.64  5017.2  752.15  5018.2  751.65  5023.0  752.15  5030.1  755.86
  5038.0  756.78  5083.0  757.83  5111.1  759.76  5121.3  758.95  5198.5  760.63
  5232.8  762.98  5303.8  765.53  5313.9  766.50  5324.1  769.88  5388.1  772.39
#Mann=3,-1,0
  4696.0    0.05       0  5017.2   0.033       0  5023.0    0.05       0
Bank Sta=5017.2,5023
Exp/Cntr=0.3,0.1

Type RM Length L Ch R = 1,1736,312,312,312
BEGIN DESCRIPTION:
Mapping XS 1664f023
END DESCRIPTION:
XS GIS Cut Line= 2
      2304297.73      7116262.19      2303852.91      7115771.09
#Sta/Elev= 30
  4702.4  764.84  4724.2  764.53  4752.6  765.24  4773.5  761.95  4795.2  760.60
  4801.9  762.32  4809.4  761.40  4816.1  758.92  4823.6  751.12  4827.4  750.80
  4828.4  750.30  4833.2  750.80  4844.5  754.46  4858.7  754.60  4872.9  756.70
  4883.6  756.28  4903.0  755.60  4936.4  755.49  4958.1  756.38  4964.8  755.75
  4986.5  756.38  5000.7  755.92  5007.4  753.16  5014.8  751.37  5021.6  751.36
  5029.0  755.77  5042.7  756.75  5056.7  755.95  5205.4  756.81  5365.0  760.11
#Mann=5,-1,0
  4702.4    0.05       0  4827.4   0.033       0  4833.2    0.05       0
  4883.6    0.12       0  4903.0    0.05       0
Bank Sta=4827.4,4833.2
Exp/Cntr=0.3,0.1

Type RM Length L Ch R = 1,1424,597,597,597
BEGIN DESCRIPTION:
Mapping XS d06761ee
END DESCRIPTION:
XS GIS Cut Line= 3
      2304493.16      7116137.45      2304288.35      7115852.41
      2303957.26      7115618.11
#Sta/Elev= 30
  4756.2  766.36  4786.4  764.97  4814.6  765.42  4851.5  764.73  4857.7  762.71
  4872.4  761.94  4887.1  762.71  4900.8  762.39  4922.7  760.02  4973.0  758.06
  4979.2  756.93  4991.0  746.89  4991.9  746.39  4996.8  746.89  5000.1  748.67
  5006.1  749.45  5023.4  751.56  5050.4  753.00  5073.2  755.40  5079.9  753.57
  5086.0  754.39  5109.9  752.60  5166.7  755.04  5179.9  756.38  5202.4  755.52
  5208.5  756.45  5216.6  756.40  5229.5  755.25  5300.6  756.61  5512.8  758.20
#Mann=5,-1,0
  4756.2    0.05       0  4991.0   0.033       0  4996.8    0.05       0
  5006.1    0.12       0  5300.6    0.05       0
Bank Sta=4991,4996.8
Exp/Cntr=0.3,0.1

Type RM Length L Ch R = 1,827,0,0,0
BEGIN DESCRIPTION:
MDE S 095 1.0
END DESCRIPTION:
XS GIS Cut Line= 3
      2304742.87      7116152.11      2304716.78      7115723.25
      2304147.02      7115491.34
#Sta/Elev= 30
  4569.9  767.11  4652.2  767.77  4752.3  765.33  4812.5  766.72  4822.5  763.67
  4872.6  763.74  4932.7  760.61  4962.7  758.87  4972.8  753.97  4992.8  747.17
  4995.6  744.30  4996.6  743.80  5001.7  744.30  5022.8  746.15  5029.5  749.19
  5046.9  749.55  5073.1  752.40  5159.3  754.28  5202.0  751.53  5207.4  752.45
  5231.5  750.55  5236.9  751.79  5267.1  749.95  5285.0  753.25  5309.0  754.89
  5368.0  755.08  5439.8  753.11  5493.6  755.25  5606.1  756.81  5614.7  758.59
#Mann=4,-1,0
  4569.9    0.05       0  4995.6   0.033       0  5001.7    0.05       0
  5073.1    0.12       0
Bank Sta=4995.6,5001.7
Exp/Cntr=0.3,0.1

Chan Stop Cuts=-1