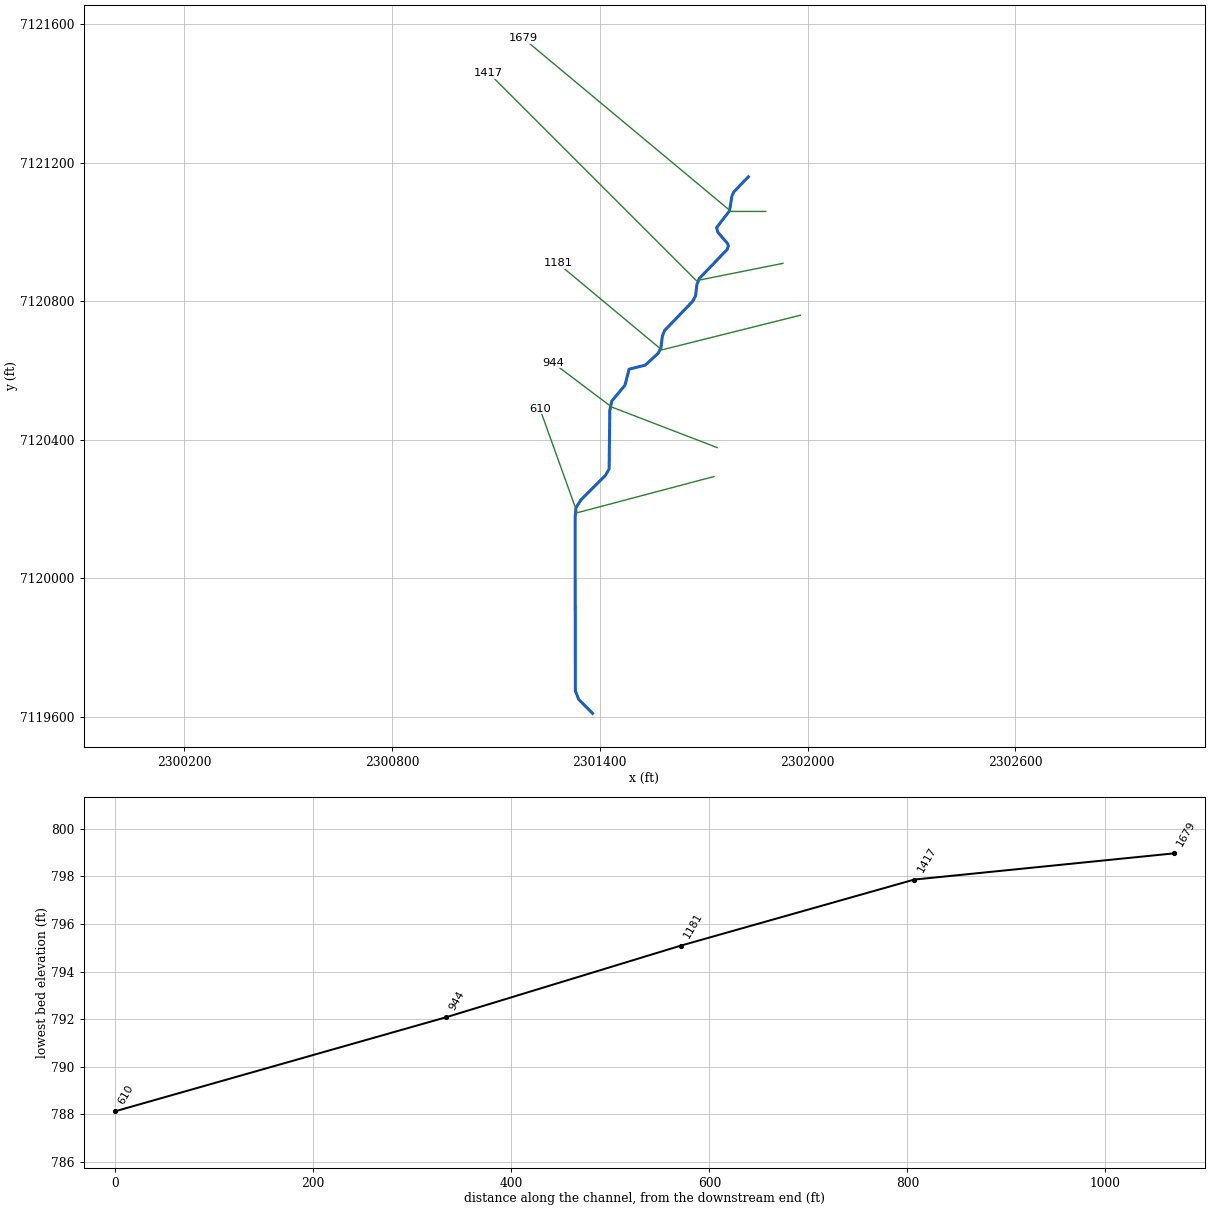
--- MDE S 096.prj (project) ---

Proj Title=MDE S 096 Base Level Engineering
Current Plan=p01
Default Exp/Contr=0.3,0.1
English Units
Geom File=g01
Flow File=f01
Plan File=p01
BEGIN DESCRIPTION:
MDE S 096
END DESCRIPTION:

--- MDE S 096.p01 (plan) ---

Plan Title=Multiple Run
Short Identifier=Multiple
Geom File=g01
Flow File=f01
Subcritical Flow
K Sum by GR= 0
Std Step Tol= 0.01
Critical Tol= 0.01
Num of Std Step Trials= 20
Max Error Tol= 0.3
Flow Tol Ratio= 0.001
Split Flow NTrial= 30
Split Flow Tol= 0.02
Split Flow Ratio= 0.02
Log Output Level= 0
Friction Slope Method= 1
Unsteady Friction Slope Method= 2
Unsteady Bridges Friction Slope Method= 1
Parabolic Critical Depth
Global Vel Dist=  1 , 1 , 1
Global Log Level= 0
CheckData=True
Encroach Param= -1, 0, 0, 0
BEGIN DESCRIPTION:
Multiple Run
END DESCRIPTION:

--- MDE S 096.f01 (steady flow) ---

Flow Title=Multiple
Number of Profiles=7
Profile Names=10-year,25-year,50-year,1pct_min,100-year,1pct_plu,500-year
River Rch & RM= MDE S 096,Reach-1,1679
     247     321     378     222     444     886     610
Boundary for River Rch & Prof#=MDE S 096,Reach-1,1
Up Type=0
Dn Type=3
Dn Slope=0.005
Boundary for River Rch & Prof#=MDE S 096,Reach-1,2
Up Type=0
Dn Type=3
Dn Slope=0.005
Boundary for River Rch & Prof#=MDE S 096,Reach-1,3
Up Type=0
Dn Type=3
Dn Slope=0.005
Boundary for River Rch & Prof#=MDE S 096,Reach-1,4
Up Type=0
Dn Type=3
Dn Slope=0.005
Boundary for River Rch & Prof#=MDE S 096,Reach-1,5
Up Type=0
Dn Type=3
Dn Slope=0.005
Boundary for River Rch & Prof#=MDE S 096,Reach-1,6
Up Type=0
Dn Type=3
Dn Slope=0.005
Boundary for River Rch & Prof#=MDE S 096,Reach-1,7
Up Type=0
Dn Type=3
Dn Slope=0.005

--- MDE S 096.g01 (geometry) ---

Geom Title=Existing Conditions

River Reach=MDE S 096,Reach-1
Reach XY= 30
      2301829.00      7121160.00      2301786.88      7121116.14
      2301781.46      7121103.94      2301774.68      7121061.58
      2301737.23      7121013.23      2301740.83      7120999.95
      2301769.40      7120966.66      2301771.44      7120960.00
      2301767.74      7120950.01      2301687.20      7120866.05
      2301680.56      7120849.36      2301676.46      7120816.05
      2301668.20      7120800.33      2301587.18      7120716.02
      2301580.57      7120699.31      2301576.52      7120665.88
      2301568.30      7120650.03      2301531.20      7120615.89
      2301484.62      7120604.38      2301472.72      7120558.16
      2301434.69      7120512.39      2301428.79      7120485.10
      2301426.93      7120315.86      2301415.60      7120296.69
      2301345.47      7120226.75      2301331.07      7120204.14
      2301328.51      7120175.20      2301329.36      7119675.15
      2301339.05      7119650.02      2301379.00      7119610.00

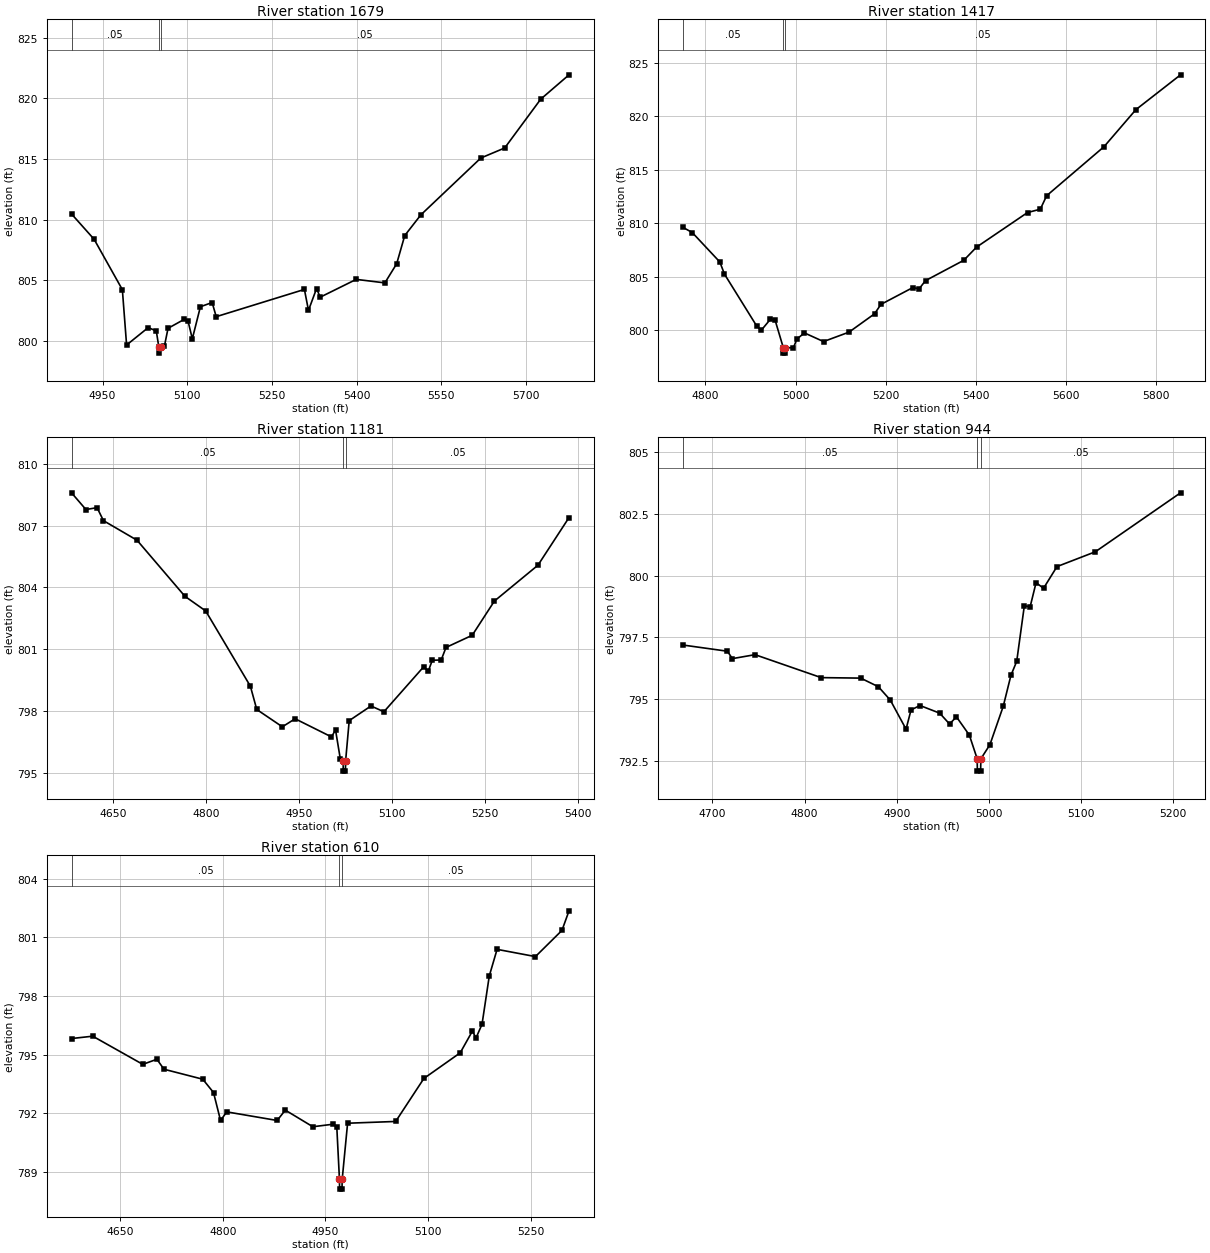
Type RM Length L Ch R = 1,1679,262,262,262
BEGIN DESCRIPTION:
MDE S 096 4.0
END DESCRIPTION:
XS GIS Cut Line= 3
      2301879.00      7121060.00      2301779.00      7121060.00
      2301179.02      7121559.99
#Sta/Elev= 30
  4895.1  810.46  4935.1  808.37  4985.1  804.21  4992.6  799.64  5030.9  801.08
  5045.2  800.80  5049.7  799.47  5050.0  798.97  5053.7  799.47  5059.5  799.53
  5066.0  801.02  5094.7  801.76  5101.2  801.66  5109.0  800.15  5123.3  802.80
  5144.1  803.15  5151.3  801.98  5307.5  804.23  5314.7  802.50  5329.0  804.30
  5335.5  803.59  5399.3  805.06  5450.0  804.77  5470.9  806.35  5485.2  808.68
  5513.8  810.39  5619.9  815.08  5662.2  815.91  5726.0  819.94  5776.1  821.95
#Mann=3,-1,0
  4895.1    0.05       0  5049.7   0.033       0  5053.7    0.05       0
Bank Sta=5049.7,5053.7
Exp/Cntr=0.3,0.1

Type RM Length L Ch R = 1,1417,236,236,236
BEGIN DESCRIPTION:
MDE S 096 3.0
END DESCRIPTION:
XS GIS Cut Line= 3
      2301929.05      7120910.01      2301679.00      7120860.00
      2301079.02      7121459.98
#Sta/Elev= 30
  4750.4  809.61  4770.8  809.13  4832.0  806.38  4842.2  805.25  4913.6  800.41
  4923.8  800.00  4944.2  801.04  4954.4  800.97  4972.8  798.37  4973.1  797.87
  4976.6  797.87  4976.8  798.37  4995.2  798.38  5002.9  799.18  5019.5  799.76
  5062.0  798.95  5118.5  799.83  5175.1  801.54  5189.2  802.42  5260.0  803.99
  5274.1  803.88  5288.2  804.64  5373.1  806.54  5401.4  807.77  5514.5  811.00
  5542.8  811.31  5556.9  812.57  5684.2  817.15  5754.9  820.61  5853.9  823.86
#Mann=3,-1,0
  4750.4    0.05       0  4972.8   0.033       0  4976.8    0.05       0
Bank Sta=4972.8,4976.8
Exp/Cntr=0.3,0.1

Type RM Length L Ch R = 1,1181,237,237,237
BEGIN DESCRIPTION:
MDE S 096 2.0
END DESCRIPTION:
XS GIS Cut Line= 3
      2301979.00      7120760.00      2301579.00      7120660.00
      2301279.01      7120909.99
#Sta/Elev= 30
  4583.2  808.59  4606.4  807.78  4624.4  807.87  4634.7  807.24  4688.9  806.29
  4766.2  803.57  4799.7  802.86  4871.8  799.21  4882.1  798.08  4923.4  797.24
  4944.0  797.63  5002.7  796.75  5009.2  797.09  5017.0  795.67  5021.5  795.59
  5021.7  795.09  5025.2  795.09  5025.5  795.59  5031.3  797.54  5066.4  798.25
  5087.3  797.97  5151.7  800.16  5158.9  799.94  5165.4  800.47  5179.7  800.48
  5187.5  801.09  5229.8  801.68  5265.6  803.34  5335.9  805.08  5386.0  807.39
#Mann=3,-1,0
  4583.2    0.05       0  5021.5   0.033       0  5025.5    0.05       0
Bank Sta=5021.5,5025.5
Exp/Cntr=0.3,0.1

Type RM Length L Ch R = 1,944,334,334,334
BEGIN DESCRIPTION:
Mapping XS eb8f4cd2
END DESCRIPTION:
XS GIS Cut Line= 3
      2301738.96      7120377.76      2301434.33      7120494.90
      2301263.78      7120623.37
#Sta/Elev= 30
  4668.2  797.19  4716.3  796.94  4721.7  796.64  4746.3  796.80  4818.1  795.87
  4861.0  795.85  4880.2  795.50  4893.1  794.96  4910.2  793.78  4915.6  794.56
  4925.3  794.74  4946.7  794.43  4957.4  793.99  4964.9  794.28  4978.9  793.54
  4987.4  792.58  4987.6  792.08  4991.1  792.08  4991.4  792.58  5001.2  793.15
  5015.7  794.71  5024.0  795.96  5030.3  796.53  5038.6  798.79  5044.8  798.73
  5051.3  799.72  5059.4  799.49  5074.0  800.37  5115.6  800.97  5208.1  803.36
#Mann=3,-1,0
  4668.2    0.05       0  4987.4   0.033       0  4991.4    0.05       0
Bank Sta=4987.4,4991.4
Exp/Cntr=0.3,0.1

Type RM Length L Ch R = 1,610,0,0,0
BEGIN DESCRIPTION:
MDE S 096 1.0
END DESCRIPTION:
XS GIS Cut Line= 3
      2301729.69      7120294.08      2301334.77      7120189.55
      2301226.84      7120489.71
#Sta/Elev= 30
  4578.8  795.83  4609.8  795.95  4683.0  794.51  4703.6  794.77  4714.0  794.26
  4770.7  793.75  4786.4  793.07  4796.7  791.64  4805.8  792.08  4879.5  791.64
  4891.4  792.17  4931.7  791.32  4961.5  791.45  4966.7  791.31  4970.6  788.63
  4970.8  788.13  4974.3  788.13  4974.6  788.63  4982.5  791.50  5052.8  791.59
  5094.1  793.79  5147.2  795.10  5165.0  796.21  5170.3  795.86  5179.1  796.56
  5189.7  799.03  5201.1  800.39  5257.2  800.02  5296.0  801.36  5306.3  802.36
#Mann=3,-1,0
  4578.8    0.05       0  4970.6   0.033       0  4974.6    0.05       0
Bank Sta=4970.6,4974.6
Exp/Cntr=0.3,0.1

Chan Stop Cuts=-1