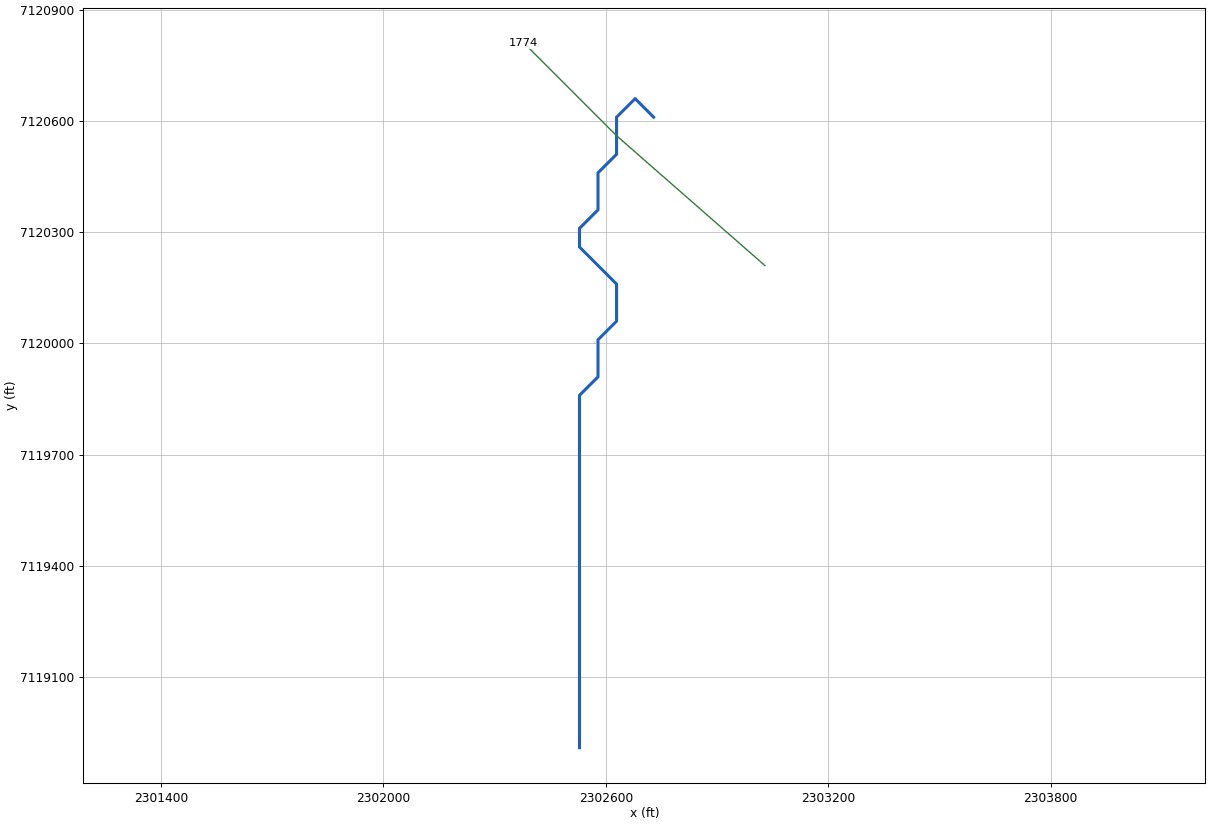
--- MDE S 097.prj (project) ---

Proj Title=MDE S 097 Base Level Engineering
Current Plan=p01
Default Exp/Contr=0.3,0.1
English Units
Geom File=g01
Flow File=f01
Plan File=p01
BEGIN DESCRIPTION:
MDE S 097
END DESCRIPTION:

--- MDE S 097.p01 (plan) ---

Plan Title=Multiple Run
Short Identifier=Multiple
Geom File=g01
Flow File=f01
Subcritical Flow
K Sum by GR= 0
Std Step Tol= 0.01
Critical Tol= 0.01
Num of Std Step Trials= 20
Max Error Tol= 0.3
Flow Tol Ratio= 0.001
Split Flow NTrial= 30
Split Flow Tol= 0.02
Split Flow Ratio= 0.02
Log Output Level= 0
Friction Slope Method= 1
Unsteady Friction Slope Method= 2
Unsteady Bridges Friction Slope Method= 1
Parabolic Critical Depth
Global Vel Dist=  1 , 1 , 1
Global Log Level= 0
CheckData=True
Encroach Param= -1, 0, 0, 0
BEGIN DESCRIPTION:
Multiple Run
END DESCRIPTION:

--- MDE S 097.f01 (steady flow) ---

Flow Title=Multiple
Number of Profiles=7
Profile Names=10-year,25-year,50-year,1pct_min,100-year,1pct_plu,500-year
River Rch & RM= MDE S 097,Reach-1,1774
     172     218     253     146     292     582     389
Boundary for River Rch & Prof#=MDE S 097,Reach-1,1
Up Type=0
Dn Type=3
Dn Slope=0.005
Boundary for River Rch & Prof#=MDE S 097,Reach-1,2
Up Type=0
Dn Type=3
Dn Slope=0.005
Boundary for River Rch & Prof#=MDE S 097,Reach-1,3
Up Type=0
Dn Type=3
Dn Slope=0.005
Boundary for River Rch & Prof#=MDE S 097,Reach-1,4
Up Type=0
Dn Type=3
Dn Slope=0.005
Boundary for River Rch & Prof#=MDE S 097,Reach-1,5
Up Type=0
Dn Type=3
Dn Slope=0.005
Boundary for River Rch & Prof#=MDE S 097,Reach-1,6
Up Type=0
Dn Type=3
Dn Slope=0.005
Boundary for River Rch & Prof#=MDE S 097,Reach-1,7
Up Type=0
Dn Type=3
Dn Slope=0.005

--- MDE S 097.g01 (geometry) ---

Geom Title=Existing Conditions

River Reach=MDE S 097,Reach-1
Reach XY= 14
      2302729.00      7120610.00      2302679.00      7120660.00
      2302629.00      7120610.00      2302629.00      7120510.00
      2302579.00      7120460.00      2302579.00      7120360.00
      2302529.00      7120310.00      2302529.00      7120260.00
      2302629.00      7120160.00      2302629.00      7120060.00
      2302579.00      7120010.00      2302579.00      7119910.00
      2302529.00      7119860.00      2302529.00      7118910.00

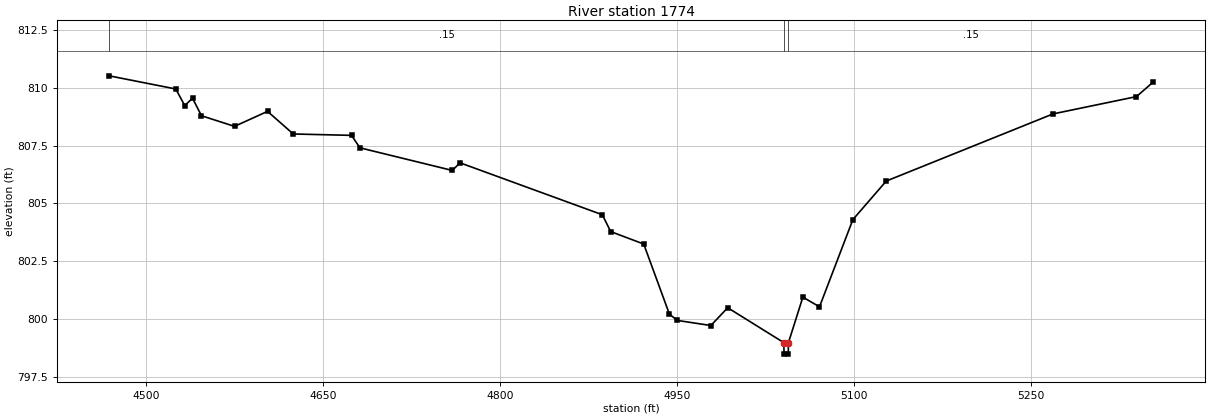
Type RM Length L Ch R = 1,1774,0,0,0
BEGIN DESCRIPTION:
MDE S 097 1.0
END DESCRIPTION:
XS GIS Cut Line= 3
      2303028.99      7120210.00      2302629.00      7120560.00
      2302378.97      7120810.03
#Sta/Elev= 30
  4468.5  810.53  4525.0  809.96  4532.6  809.24  4539.2  809.56  4546.8  808.80
  4574.8  808.34  4602.8  808.99  4624.6  808.01  4674.0  807.95  4681.1  807.41
  4759.4  806.43  4766.0  806.76  4886.6  804.51  4893.7  803.78  4921.7  803.24
  4943.5  800.20  4950.2  799.93  4978.6  799.71  4992.9  800.48  5040.4  798.97
  5040.7  798.47  5044.2  798.47  5044.4  798.97  5056.6  800.94  5070.7  800.52
  5099.0  804.30  5127.3  805.97  5268.7  808.88  5339.4  809.63  5353.6  810.26
#Mann=3,-1,0
  4468.5    0.15       0  5040.4    0.05       0  5044.4    0.15       0
Bank Sta=5040.4,5044.4
Exp/Cntr=0.3,0.1

Chan Stop Cuts=-1