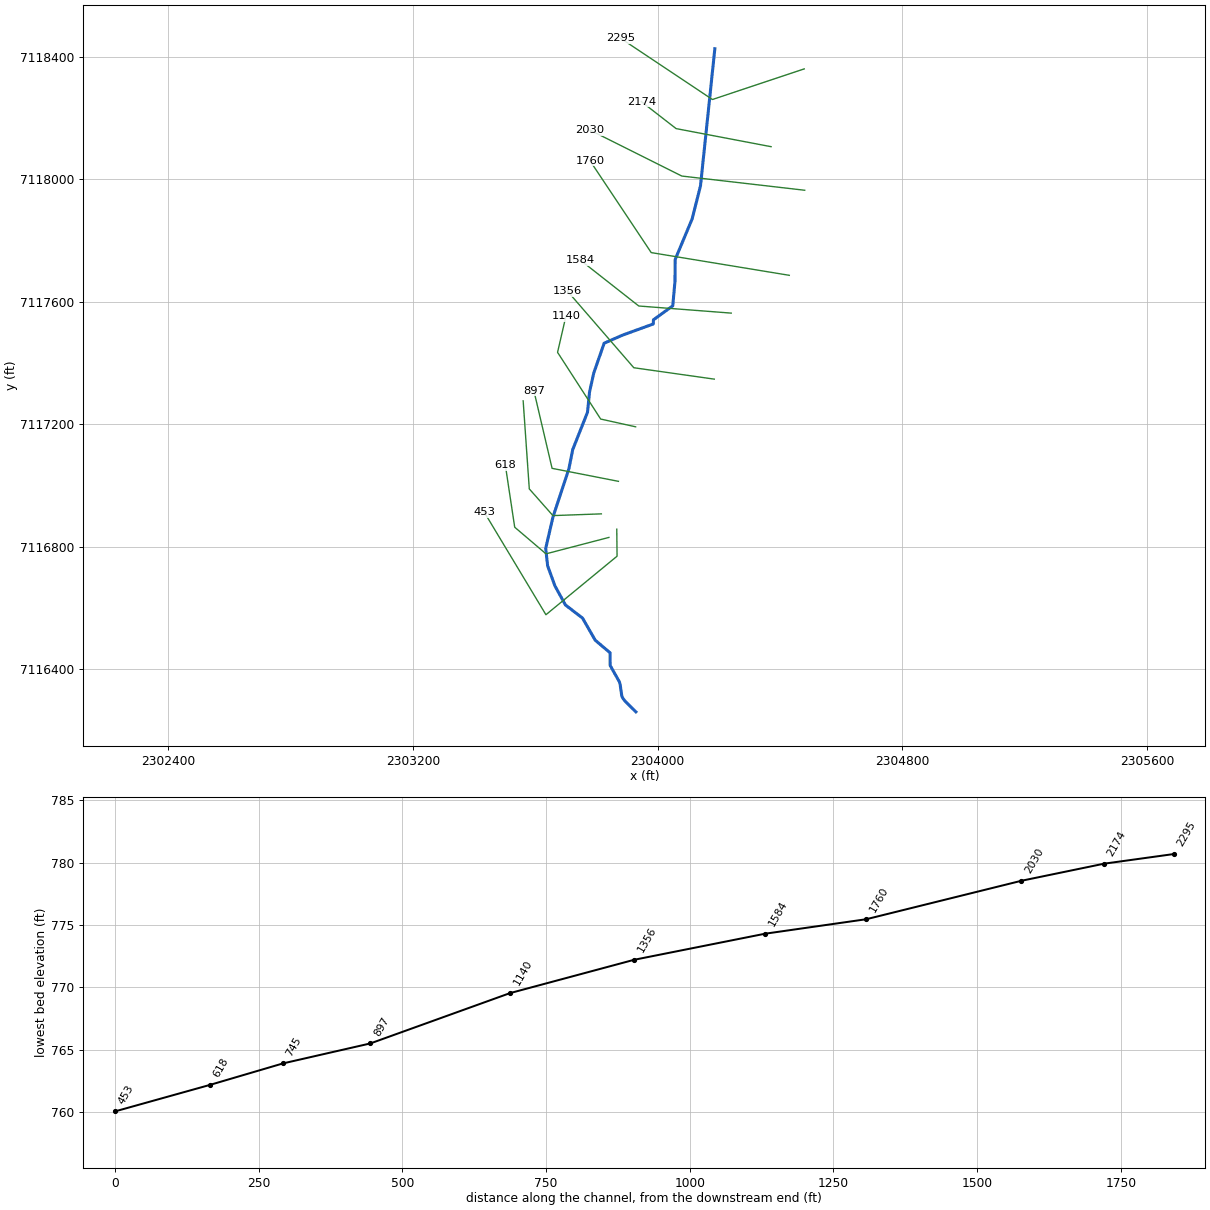
--- MDE S 098.prj (project) ---

Proj Title=MDE S 098 Base Level Engineering
Current Plan=p01
Default Exp/Contr=0.3,0.1
English Units
Geom File=g01
Flow File=f01
Plan File=p01
BEGIN DESCRIPTION:
MDE S 098
END DESCRIPTION:

--- MDE S 098.p01 (plan) ---

Plan Title=Multiple Run
Short Identifier=Multiple
Geom File=g01
Flow File=f01
Subcritical Flow
K Sum by GR= 0
Std Step Tol= 0.01
Critical Tol= 0.01
Num of Std Step Trials= 20
Max Error Tol= 0.3
Flow Tol Ratio= 0.001
Split Flow NTrial= 30
Split Flow Tol= 0.02
Split Flow Ratio= 0.02
Log Output Level= 0
Friction Slope Method= 1
Unsteady Friction Slope Method= 2
Unsteady Bridges Friction Slope Method= 1
Parabolic Critical Depth
Global Vel Dist=  1 , 1 , 1
Global Log Level= 0
CheckData=True
Encroach Param= -1, 0, 0, 0
BEGIN DESCRIPTION:
Multiple Run
END DESCRIPTION:

--- MDE S 098.f01 (steady flow) ---

Flow Title=Multiple
Number of Profiles=7
Profile Names=10-year,25-year,50-year,1pct_min,100-year,1pct_plu,500-year
River Rch & RM= MDE S 098,Reach-1,2295
     194     248     291     170     339     675     459
Boundary for River Rch & Prof#=MDE S 098,Reach-1,1
Up Type=0
Dn Type=3
Dn Slope=0.005
Boundary for River Rch & Prof#=MDE S 098,Reach-1,2
Up Type=0
Dn Type=3
Dn Slope=0.005
Boundary for River Rch & Prof#=MDE S 098,Reach-1,3
Up Type=0
Dn Type=3
Dn Slope=0.005
Boundary for River Rch & Prof#=MDE S 098,Reach-1,4
Up Type=0
Dn Type=3
Dn Slope=0.005
Boundary for River Rch & Prof#=MDE S 098,Reach-1,5
Up Type=0
Dn Type=3
Dn Slope=0.005
Boundary for River Rch & Prof#=MDE S 098,Reach-1,6
Up Type=0
Dn Type=3
Dn Slope=0.005
Boundary for River Rch & Prof#=MDE S 098,Reach-1,7
Up Type=0
Dn Type=3
Dn Slope=0.005

--- MDE S 098.g01 (geometry) ---

Geom Title=Existing Conditions

River Reach=MDE S 098,Reach-1
Reach XY= 30
      2304186.95      7118425.82      2304140.06      7117978.24
      2304112.78      7117870.13      2304057.33      7117737.59
      2304056.72      7117666.77      2304049.44      7117586.23
      2303986.32      7117540.51      2303985.62      7117526.81
      2303886.06      7117490.72      2303825.20      7117464.11
      2303791.27      7117366.79      2303777.36      7117304.32
      2303770.77      7117238.45      2303722.54      7117116.74
      2303710.09      7117054.28      2303657.87      7116896.16
      2303634.19      7116793.76      2303640.61      7116736.69
      2303664.58      7116671.14      2303698.72      7116609.16
      2303754.49      7116566.45      2303796.01      7116494.16
      2303844.48      7116453.11      2303844.91      7116411.56
      2303874.96      7116358.33      2303877.51      7116349.38
      2303882.87      7116311.60      2303886.91      7116303.85
      2303895.41      7116293.07      2303929.00      7116260.00

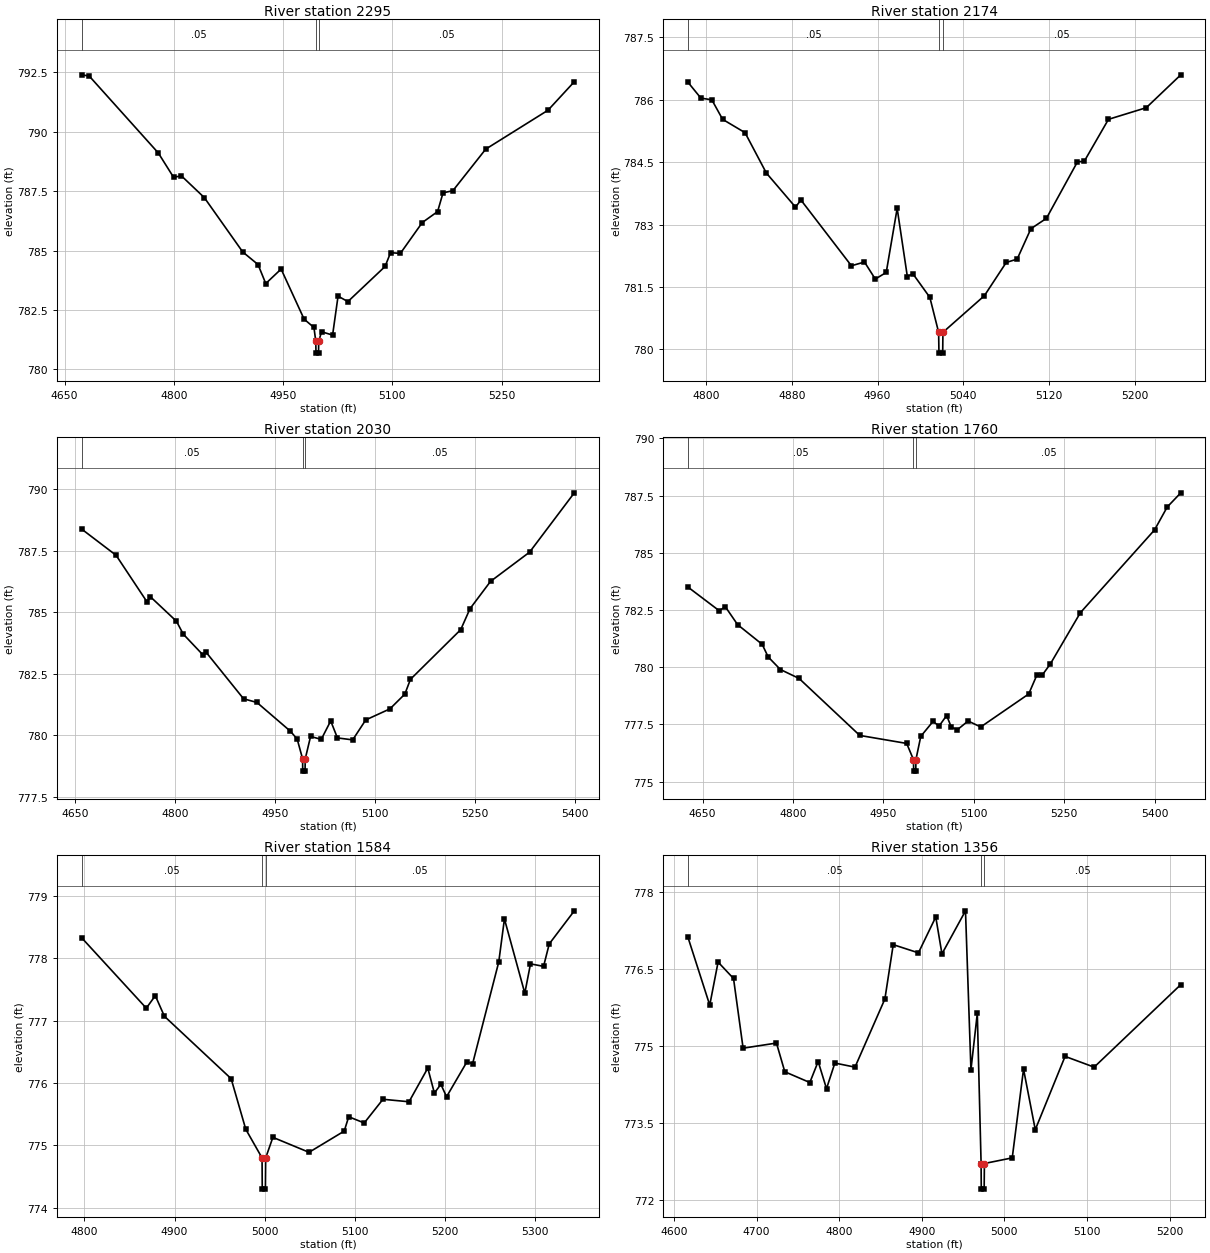
Type RM Length L Ch R = 1,2295,121,121,121
BEGIN DESCRIPTION:
MDE S 098 4.0
END DESCRIPTION:
XS GIS Cut Line= 3
      2304478.99      7118360.00      2304179.00      7118260.00
      2303878.98      7118460.01
#Sta/Elev= 30
  4673.2  792.40  4683.7  792.35  4778.6  789.11  4799.7  788.08  4810.2  788.15
  4841.8  787.23  4894.6  784.94  4915.6  784.41  4926.2  783.61  4947.3  784.22
  4978.9  782.11  4992.4  781.76  4994.9  781.18  4995.2  780.68  4998.7  780.68
  4998.9  781.18  5002.9  781.58  5018.0  781.44  5025.5  783.08  5039.0  782.85
  5090.1  784.33  5097.6  784.91  5111.1  784.88  5141.2  786.18  5162.2  786.64
  5169.7  787.43  5183.2  787.52  5228.3  789.27  5313.9  790.91  5350.0  792.11
#Mann=3,-1,0
  4673.2    0.05       0  4994.9   0.035       0  4998.9    0.05       0
Bank Sta=4994.9,4998.9
Exp/Cntr=0.3,0.1

Type RM Length L Ch R = 1,2174,144,144,144
BEGIN DESCRIPTION:
Mapping XS 656efc78
END DESCRIPTION:
XS GIS Cut Line= 3
      2304370.76      7118105.91      2304060.33      7118164.98
      2303946.65      7118253.20
#Sta/Elev= 30
  4783.1  786.42  4795.1  786.04  4805.3  786.00  4815.4  785.53  4836.3  785.21
  4856.2  784.24  4883.4  783.42  4888.5  783.59  4935.6  782.01  4947.8  782.10
  4957.9  781.69  4968.1  781.85  4978.3  783.39  4987.8  781.75  4992.9  781.82
  5008.8  781.25  5017.0  780.41  5017.3  779.91  5020.8  779.91  5021.0  780.41
  5059.7  781.29  5080.1  782.09  5090.3  782.17  5103.1  782.90  5117.6  783.15
  5146.6  784.51  5152.9  784.52  5175.5  785.53  5210.8  785.81  5243.0  786.60
#Mann=3,-1,0
  4783.1    0.05       0  5017.0   0.035       0  5021.0    0.05       0
Bank Sta=5017,5021
Exp/Cntr=0.3,0.1

Type RM Length L Ch R = 1,2030,270,270,270
BEGIN DESCRIPTION:
MDE S 098 3.0
END DESCRIPTION:
XS GIS Cut Line= 3
      2304480.57      7117963.63      2304079.00      7118010.00
      2303778.96      7118160.02
#Sta/Elev= 30
  4659.8  788.38  4711.7  787.31  4758.0  785.42  4763.0  785.63  4802.3  784.63
  4812.4  784.11  4841.8  783.27  4846.8  783.37  4903.0  781.48  4923.1  781.33
  4973.4  780.16  4983.5  779.84  4991.6  779.04  4991.8  778.54  4995.3  778.54
  4995.6  779.04  5003.6  779.95  5019.6  779.83  5033.8  780.58  5043.9  779.89
  5066.8  779.81  5086.4  780.62  5122.7  781.07  5145.1  781.67  5153.5  782.27
  5229.0  784.29  5242.9  785.14  5273.7  786.25  5332.4  787.44  5399.5  789.85
#Mann=3,-1,0
  4659.8    0.05       0  4991.6   0.033       0  4995.6    0.05       0
Bank Sta=4991.6,4995.6
Exp/Cntr=0.3,0.1

Type RM Length L Ch R = 1,1760,176,176,176
BEGIN DESCRIPTION:
MDE S 098 2.0
END DESCRIPTION:
XS GIS Cut Line= 3
      2304430.22      7117685.82      2303979.00      7117760.00
      2303779.02      7118059.97
#Sta/Elev= 30
  4625.8  783.50  4677.5  782.47  4687.8  782.64  4708.1  781.86  4748.9  781.00
  4758.8  780.45  4779.1  779.90  4810.1  779.51  4910.8  777.02  4988.7  776.67
  5000.0  775.96  5000.3  775.46  5003.8  775.46  5004.0  775.96  5012.1  776.98
  5032.4  777.63  5042.5  777.43  5055.0  777.89  5062.8  777.38  5072.9  777.27
  5090.6  777.65  5111.6  777.39  5191.2  778.83  5204.8  779.66  5213.8  779.66
  5227.3  780.15  5276.9  782.38  5400.1  786.00  5421.1  787.00  5443.6  787.62
#Mann=3,-1,0
  4625.8    0.05       0  5000.0   0.033       0  5004.0    0.05       0
Bank Sta=5000,5004
Exp/Cntr=0.3,0.1

Type RM Length L Ch R = 1,1584,228,228,228
BEGIN DESCRIPTION:
Mapping XS ee6ce3ff
END DESCRIPTION:
XS GIS Cut Line= 3
      2304240.58      7117562.37      2303938.32      7117585.62
      2303746.92      7117735.89
#Sta/Elev= 30
  4796.9  778.33  4868.7  777.20  4878.7  777.40  4888.8  777.07  4962.8  776.07
  4979.0  775.26  4997.1  774.80  4997.3  774.30  5000.8  774.30  5001.1  774.80
  5009.1  775.13  5049.2  774.89  5088.2  775.23  5093.2  775.46  5110.4  775.36
  5131.2  775.74  5160.1  775.70  5180.9  776.24  5188.2  775.84  5195.4  775.98
  5201.7  775.78  5224.3  776.34  5230.6  776.31  5259.6  777.94  5265.9  778.63
  5288.5  777.44  5294.8  777.91  5309.3  777.87  5315.6  778.23  5343.4  778.76
#Mann=3,-1,0
  4796.9    0.05       0  4997.1   0.035       0  5001.1    0.05       0
Bank Sta=4997.1,5001.1
Exp/Cntr=0.3,0.1

Type RM Length L Ch R = 1,1356,216,216,216
BEGIN DESCRIPTION:
Mapping XS 8c548ed8
END DESCRIPTION:
XS GIS Cut Line= 3
      2304185.04      7117346.78      2303922.12      7117384.00
      2303705.20      7117634.22
#Sta/Elev= 30
  4616.9  777.12  4643.2  775.80  4653.3  776.64  4672.0  776.32  4683.6  774.96
  4724.0  775.06  4734.1  774.50  4764.4  774.29  4774.5  774.70  4784.6  774.17
  4794.7  774.67  4819.1  774.59  4855.3  775.92  4865.4  776.98  4895.9  776.82
  4916.9  777.52  4924.4  776.80  4952.9  777.64  4959.5  774.54  4967.2  775.64
  4971.8  772.71  4972.0  772.21  4975.5  772.21  4975.8  772.71  5009.5  772.82
  5023.2  774.55  5037.4  773.37  5073.5  774.80  5108.7  774.59  5213.6  776.20
#Mann=3,-1,0
  4616.9    0.05       0  4971.8   0.033       0  4975.8    0.05       0
Bank Sta=4971.8,4975.8
Exp/Cntr=0.3,0.1

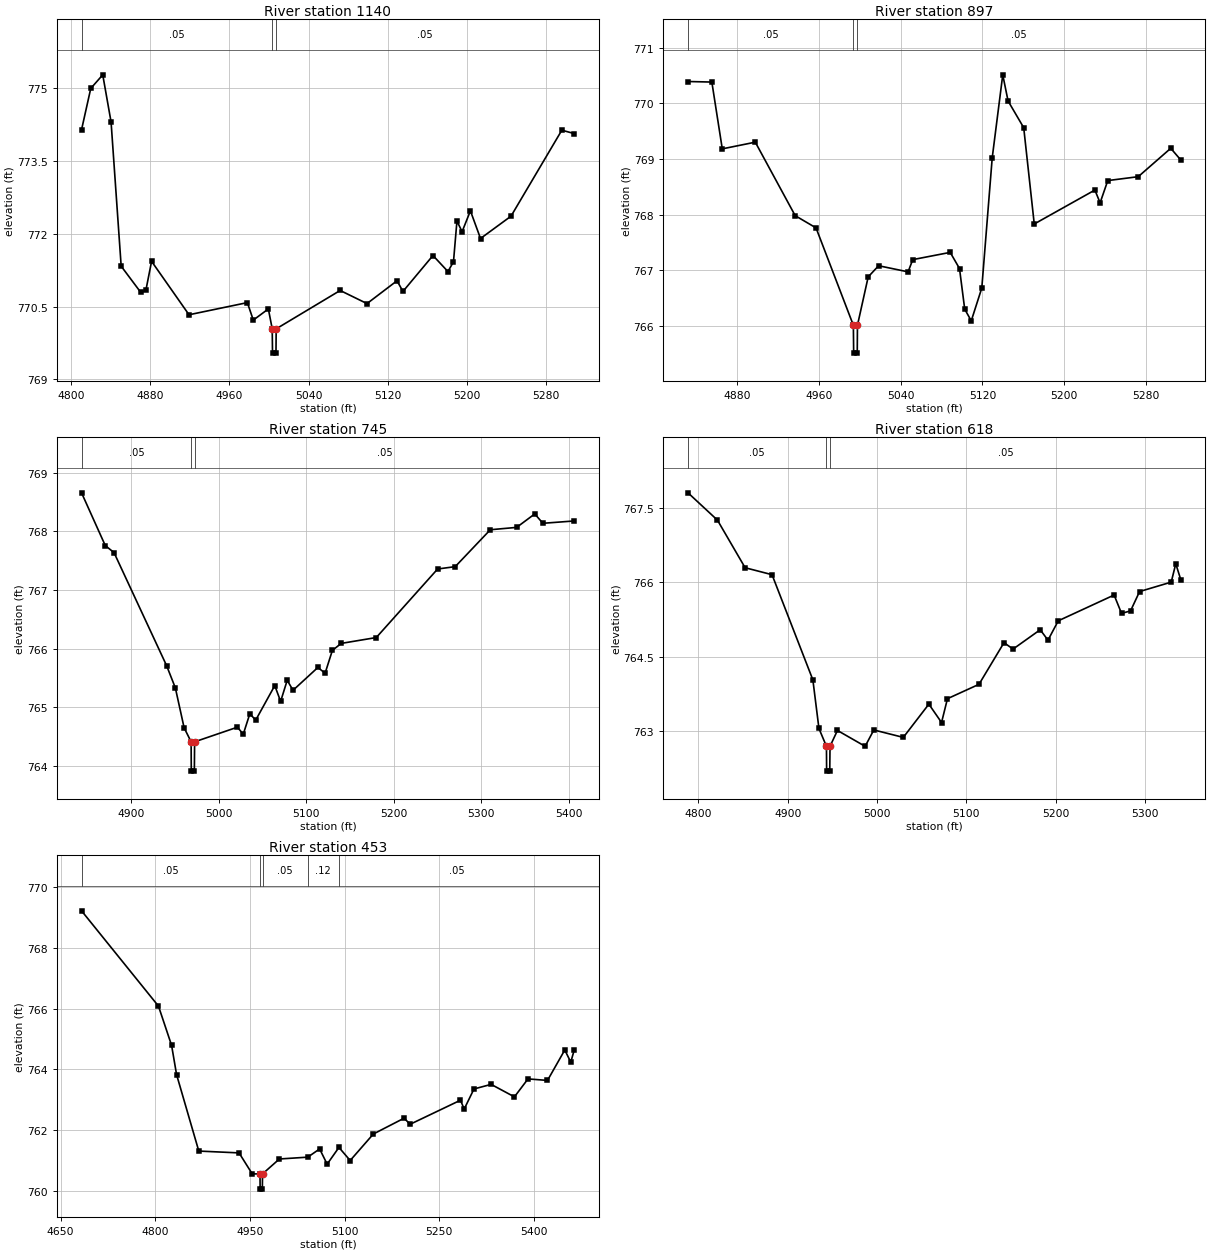
Type RM Length L Ch R = 1,1140,243,243,243
BEGIN DESCRIPTION:
Mapping XS 0bd9b275
END DESCRIPTION:
XS GIS Cut Line= 4
      2303928.05      7117191.08      2303813.87      7117216.40
      2303672.98      7117434.26      2303700.21      7117552.26
#Sta/Elev= 30
  4810.8  774.14  4820.1  774.99  4832.2  775.27  4840.6  774.30  4850.8  771.33
  4870.6  770.79  4875.7  770.83  4881.5  771.43  4919.3  770.33  4978.2  770.58
  4984.2  770.22  4999.4  770.45  5003.3  770.04  5003.6  769.54  5007.1  769.54
  5007.3  770.04  5071.9  770.83  5099.0  770.56  5129.3  771.03  5135.3  770.81
  5165.6  771.55  5180.7  771.22  5186.3  771.42  5189.8  772.26  5195.0  772.04
  5203.4  772.47  5213.6  771.90  5244.4  772.36  5295.7  774.13  5308.3  774.06
#Mann=3,-1,0
  4810.8    0.05       0  5003.3   0.033       0  5007.3    0.05       0
Bank Sta=5003.3,5007.3
Exp/Cntr=0.3,0.1

Type RM Length L Ch R = 1,897,152,152,152
BEGIN DESCRIPTION:
Mapping XS 7470b95e
END DESCRIPTION:
XS GIS Cut Line= 3
      2303871.88      7117013.00      2303655.06      7117055.44
      2303595.46      7117309.50
#Sta/Elev= 30
  4832.1  770.39  4855.4  770.38  4865.6  769.18  4897.9  769.30  4936.9  767.98
  4957.3  767.76  4993.8  766.01  4994.1  765.51  4997.6  765.51  4997.8  766.01
  5008.3  766.88  5018.5  767.08  5047.3  766.97  5051.9  767.19  5088.5  767.32
  5097.6  767.03  5102.7  766.30  5109.1  766.09  5119.4  766.68  5129.6  769.02
  5139.9  770.51  5145.1  770.04  5160.4  769.56  5170.7  767.83  5230.0  768.44
  5235.1  768.21  5242.6  768.61  5272.4  768.68  5304.2  769.19  5314.0  768.98
#Mann=3,-1,0
  4832.1    0.05       0  4993.8   0.033       0  4997.8    0.05       0
Bank Sta=4993.8,4997.8
Exp/Cntr=0.3,0.1

Type RM Length L Ch R = 1,745,127,127,127
BEGIN DESCRIPTION:
Mapping XS 442e239b
END DESCRIPTION:
XS GIS Cut Line= 4
      2303816.10      7116906.76      2303657.81      7116901.05
      2303580.59      7116988.29      2303560.56      7117275.79
#Sta/Elev= 30
  4843.3  768.66  4870.4  767.76  4880.4  767.64  4940.5  765.71  4950.5  765.33
  4960.5  764.65  4968.5  764.41  4968.7  763.91  4972.2  763.91  4972.5  764.41
  5021.4  764.66  5028.1  764.54  5035.6  764.89  5042.3  764.78  5064.1  765.37
  5070.8  765.10  5078.3  765.46  5085.0  765.29  5113.4  765.68  5121.6  765.58
  5129.9  765.97  5140.0  766.09  5180.1  766.19  5250.2  767.36  5270.3  767.40
  5310.4  768.03  5340.5  768.07  5361.2  768.30  5370.5  768.14  5406.4  768.18
#Mann=3,-1,0
  4843.3    0.05       0  4968.5   0.033       0  4972.5    0.05       0
Bank Sta=4968.5,4972.5
Exp/Cntr=0.3,0.1

Type RM Length L Ch R = 1,618,165,165,165
BEGIN DESCRIPTION:
Mapping XS 4088e098
END DESCRIPTION:
XS GIS Cut Line= 4
      2303840.79      7116829.81      2303635.19      7116776.19
      2303532.92      7116863.17      2303502.40      7117065.55
#Sta/Elev= 30
  4788.5  767.80  4821.4  767.25  4852.4  766.29  4882.5  766.15  4928.2  764.03
  4935.0  763.05  4943.4  762.69  4943.6  762.19  4947.1  762.19  4947.4  762.69
  4955.7  763.01  4986.7  762.69  4996.4  763.02  5029.4  762.87  5058.0  763.54
  5072.2  763.17  5078.8  763.65  5114.1  763.94  5142.1  764.78  5152.2  764.65
  5182.6  765.04  5191.3  764.83  5202.8  765.22  5265.3  765.74  5273.6  765.37
  5283.7  765.42  5293.8  765.81  5329.2  766.00  5334.3  766.37  5339.9  766.05
#Mann=3,-1,0
  4788.5    0.05       0  4943.4   0.033       0  4947.4    0.05       0
Bank Sta=4943.4,4947.4
Exp/Cntr=0.3,0.1

Type RM Length L Ch R = 1,453,0,0,0
BEGIN DESCRIPTION:
MDE S 098 1.0
END DESCRIPTION:
XS GIS Cut Line= 4
      2303866.47      7116856.77      2303867.40      7116768.49
      2303634.99      7116577.33      2303433.01      7116912.92
#Sta/Elev= 30
  4683.2  769.21  4805.1  766.08  4825.9  764.79  4833.8  763.83  4869.0  761.32
  4932.8  761.26  4953.7  760.57  4966.0  760.57  4966.2  760.07  4969.7  760.07
  4970.0  760.57  4996.7  761.06  5041.7  761.12  5060.5  761.39  5072.4  760.89
  5091.1  761.44  5108.9  761.01  5145.6  761.88  5194.4  762.40  5203.9  762.20
  5283.7  762.99  5289.6  762.70  5305.1  763.36  5332.3  763.51  5369.2  763.10
  5390.7  763.69  5421.6  763.64  5449.0  764.64  5458.5  764.24  5464.1  764.65
#Mann=5,-1,0
  4683.2    0.05       0  4966.0   0.033       0  4970.0    0.05       0
  5041.7    0.12       0  5091.1    0.05       0
Bank Sta=4966,4970
Exp/Cntr=0.3,0.1

Chan Stop Cuts=-1