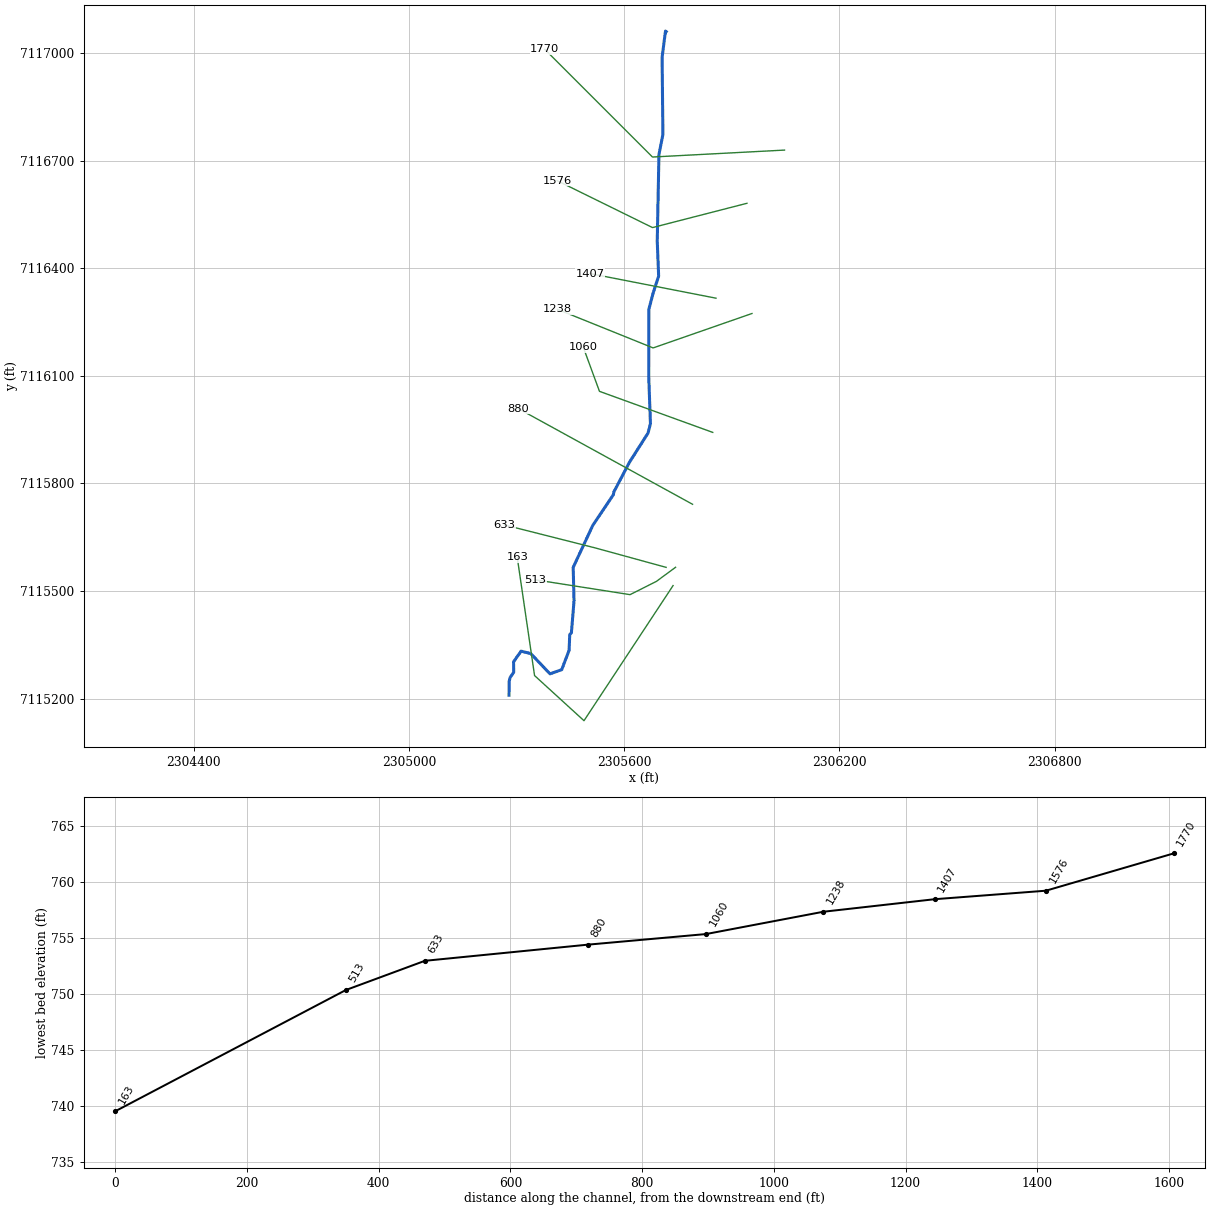
--- MDE S 099.prj (project) ---

Proj Title=MDE S 099 Base Level Engineering
Current Plan=p01
Default Exp/Contr=0.3,0.1
English Units
Geom File=g01
Flow File=f01
Plan File=p01
BEGIN DESCRIPTION:
MDE S 099
END DESCRIPTION:

--- MDE S 099.p01 (plan) ---

Plan Title=Multiple Run
Short Identifier=Multiple
Geom File=g01
Flow File=f01
Subcritical Flow
K Sum by GR= 0
Std Step Tol= 0.01
Critical Tol= 0.01
Num of Std Step Trials= 20
Max Error Tol= 0.3
Flow Tol Ratio= 0.001
Split Flow NTrial= 30
Split Flow Tol= 0.02
Split Flow Ratio= 0.02
Log Output Level= 0
Friction Slope Method= 1
Unsteady Friction Slope Method= 2
Unsteady Bridges Friction Slope Method= 1
Parabolic Critical Depth
Global Vel Dist=  1 , 1 , 1
Global Log Level= 0
CheckData=True
Encroach Param= -1, 0, 0, 0
BEGIN DESCRIPTION:
Multiple Run
END DESCRIPTION:

--- MDE S 099.f01 (steady flow) ---

Flow Title=Multiple
Number of Profiles=7
Profile Names=10-year,25-year,50-year,1pct_min,100-year,1pct_plu,500-year
River Rch & RM= MDE S 099,Reach-1,1770
     253     330     392     232     463     923     645
Boundary for River Rch & Prof#=MDE S 099,Reach-1,1
Up Type=0
Dn Type=3
Dn Slope=0.005
Boundary for River Rch & Prof#=MDE S 099,Reach-1,2
Up Type=0
Dn Type=3
Dn Slope=0.005
Boundary for River Rch & Prof#=MDE S 099,Reach-1,3
Up Type=0
Dn Type=3
Dn Slope=0.005
Boundary for River Rch & Prof#=MDE S 099,Reach-1,4
Up Type=0
Dn Type=3
Dn Slope=0.005
Boundary for River Rch & Prof#=MDE S 099,Reach-1,5
Up Type=0
Dn Type=3
Dn Slope=0.005
Boundary for River Rch & Prof#=MDE S 099,Reach-1,6
Up Type=0
Dn Type=3
Dn Slope=0.005
Boundary for River Rch & Prof#=MDE S 099,Reach-1,7
Up Type=0
Dn Type=3
Dn Slope=0.005

--- MDE S 099.g01 (geometry) ---

Geom Title=Existing Conditions

River Reach=MDE S 099,Reach-1
Reach XY= 30
      2305717.38      7117059.48      2305715.25      7117061.29
      2305705.83      7116987.61      2305708.08      7116772.92
      2305697.03      7116716.53      2305692.28      7116474.94
      2305696.21      7116378.01      2305680.70      7116330.24
      2305668.79      7116285.09      2305668.57      7116098.09
      2305673.32      7115966.80      2305666.59      7115940.50
      2305615.02      7115859.44      2305571.48      7115776.74
      2305569.89      7115768.57      2305512.77      7115683.49
      2305457.94      7115566.04      2305460.37      7115473.43
      2305452.97      7115383.38      2305448.39      7115378.73
      2305446.54      7115334.76      2305425.99      7115280.87
      2305393.35      7115269.27      2305339.62      7115325.85
      2305312.61      7115332.49      2305291.81      7115302.84
      2305292.12      7115273.60      2305282.14      7115258.97
      2305279.50      7115248.38      2305279.00      7115210.00

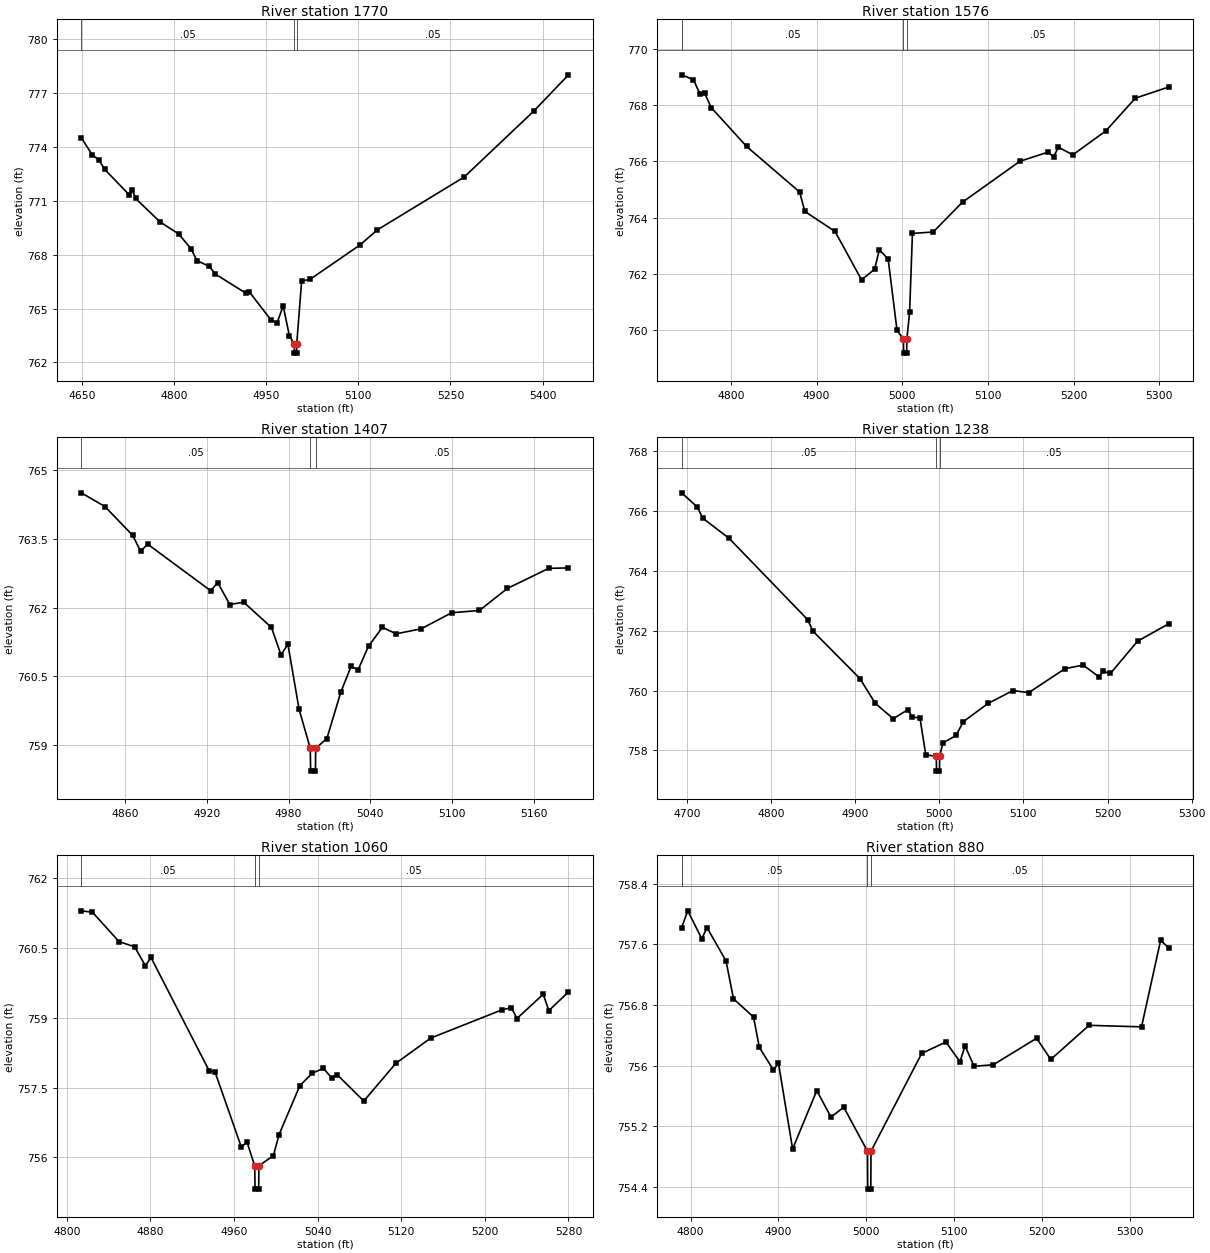
Type RM Length L Ch R = 1,1770,194,194,194
BEGIN DESCRIPTION:
MDE S 099 4.0
END DESCRIPTION:
XS GIS Cut Line= 3
      2306047.13      7116729.35      2305679.00      7116710.00
      2305379.00      7117010.00
#Sta/Elev= 30
  4649.3  774.50  4667.5  773.52  4677.5  773.28  4687.5  772.73  4727.3  771.32
  4732.4  771.60  4737.6  771.12  4777.6  769.81  4807.7  769.15  4827.7  768.33
  4837.7  767.66  4857.7  767.34  4867.7  766.91  4917.7  765.84  4922.7  765.93
  4957.9  764.37  4967.9  764.20  4977.9  765.15  4987.9  763.49  4995.9  763.02
  4996.2  762.52  4999.7  762.52  4999.9  763.02  5007.9  766.53  5021.5  766.62
  5102.8  768.53  5131.1  769.37  5272.5  772.31  5385.6  775.97  5442.2  777.99
#Mann=3,-1,0
  4649.3    0.05       0  4995.9   0.033       0  4999.9    0.05       0
Bank Sta=4995.9,4999.9
Exp/Cntr=0.3,0.1

Type RM Length L Ch R = 1,1576,169,169,169
BEGIN DESCRIPTION:
MDE S 099 3.0
END DESCRIPTION:
XS GIS Cut Line= 3
      2305942.29      7116581.01      2305679.14      7116513.33
      2305413.02      7116644.24
#Sta/Elev= 30
  4742.7  769.07  4756.4  768.90  4764.2  768.38  4769.4  768.43  4777.1  767.91
  4818.4  766.53  4880.3  764.91  4886.4  764.22  4921.6  763.51  4952.6  761.79
  4967.8  762.17  4973.3  762.86  4983.6  762.53  4993.9  760.00  5001.4  759.69
  5001.6  759.19  5005.1  759.19  5005.4  759.69  5008.6  760.64  5011.9  763.44
  5036.1  763.49  5070.3  764.55  5137.2  766.00  5170.6  766.33  5176.5  766.15
  5182.1  766.50  5199.0  766.23  5237.5  767.08  5271.9  768.24  5311.0  768.64
#Mann=3,-1,0
  4742.7    0.05       0  5001.4   0.035       0  5005.4    0.05       0
Bank Sta=5001.4,5005.4
Exp/Cntr=0.3,0.1

Type RM Length L Ch R = 1,1407,169,169,169
BEGIN DESCRIPTION:
Mapping XS 56c4c8c6
END DESCRIPTION:
XS GIS Cut Line= 2
      2305856.07      7116316.50      2305504.82      7116385.16
#Sta/Elev= 30
  4827.7  764.51  4845.1  764.21  4865.5  763.58  4871.3  763.23  4876.4  763.39
  4922.8  762.37  4927.9  762.55  4936.8  762.07  4947.0  762.12  4967.4  761.57
  4974.4  760.97  4979.5  761.20  4987.7  759.78  4995.9  758.93  4996.2  758.43
  4999.7  758.43  4999.9  758.93  5008.1  759.14  5018.3  760.15  5025.9  760.72
  5031.0  760.64  5038.7  761.16  5048.9  761.57  5059.1  761.43  5077.4  761.54
  5099.8  761.89  5120.2  761.94  5140.6  762.42  5171.1  762.86  5185.6  762.87
#Mann=3,-1,0
  4827.7    0.05       0  4995.9   0.035       0  4999.9    0.05       0
Bank Sta=4995.9,4999.9
Exp/Cntr=0.3,0.1

Type RM Length L Ch R = 1,1238,178,178,178
BEGIN DESCRIPTION:
MDE S 099 2.0
END DESCRIPTION:
XS GIS Cut Line= 3
      2305956.42      7116273.81      2305680.84      7116177.86
      2305414.58      7116285.22
#Sta/Elev= 30
  4694.0  766.60  4712.5  766.13  4719.3  765.75  4750.4  765.08  4843.6  762.37
  4850.1  761.98  4905.8  760.40  4924.2  759.57  4945.4  759.06  4962.7  759.36
  4968.0  759.12  4977.2  759.08  4984.1  757.85  4996.6  757.81  4996.8  757.31
  5000.3  757.31  5000.6  757.81  5004.4  758.25  5020.1  758.50  5028.6  758.96
  5058.1  759.57  5087.7  760.00  5106.4  759.93  5149.5  760.73  5171.1  760.85
  5189.7  760.46  5195.1  760.64  5203.4  760.57  5235.8  761.65  5272.9  762.23
#Mann=3,-1,0
  4694.0    0.05       0  4996.6   0.035       0  5000.6    0.05       0
Bank Sta=4996.6,5000.6
Exp/Cntr=0.3,0.1

Type RM Length L Ch R = 1,1060,180,180,180
BEGIN DESCRIPTION:
Mapping XS 785dae36
END DESCRIPTION:
XS GIS Cut Line= 3
      2305846.96      7115942.38      2305531.24      7116056.82
      2305486.27      7116179.30
#Sta/Elev= 30
  4813.8  761.29  4824.5  761.26  4849.9  760.63  4864.8  760.52  4875.2  760.11
  4880.5  760.29  4936.4  757.85  4941.7  757.84  4967.0  756.22  4972.4  756.33
  4979.8  755.82  4980.1  755.32  4983.6  755.32  4983.8  755.82  4997.7  756.04
  5003.1  756.49  5023.0  757.54  5035.0  757.81  5045.6  757.91  5053.6  757.70
  5058.9  757.77  5084.2  757.21  5114.9  758.02  5148.2  758.56  5216.9  759.17
  5225.5  759.21  5230.8  758.98  5255.9  759.50  5261.3  759.15  5280.1  759.55
#Mann=3,-1,0
  4813.8    0.05       0  4979.8   0.035       0  4983.8    0.05       0
Bank Sta=4979.8,4983.8
Exp/Cntr=0.3,0.1

Type RM Length L Ch R = 1,880,247,247,247
BEGIN DESCRIPTION:
Mapping XS 9a74d242
END DESCRIPTION:
XS GIS Cut Line= 2
      2305790.70      7115741.98      2305304.65      7116008.87
#Sta/Elev= 30
  4789.8  757.82  4796.8  758.04  4812.8  757.67  4818.6  757.82  4840.3  757.38
  4848.8  756.88  4871.6  756.64  4878.2  756.24  4894.3  755.94  4900.0  756.03
  4916.1  754.90  4943.6  755.67  4959.7  755.32  4974.3  755.45  5001.3  754.87
  5001.6  754.37  5005.1  754.37  5005.3  754.87  5063.0  756.16  5090.5  756.31
  5106.6  756.05  5112.3  756.26  5122.6  755.99  5144.5  756.01  5193.8  756.36
  5209.9  756.08  5253.5  756.53  5313.2  756.51  5334.9  757.65  5344.3  757.55
#Mann=3,-1,0
  4789.8    0.05       0  5001.3   0.035       0  5005.3    0.05       0
Bank Sta=5001.3,5005.3
Exp/Cntr=0.3,0.1

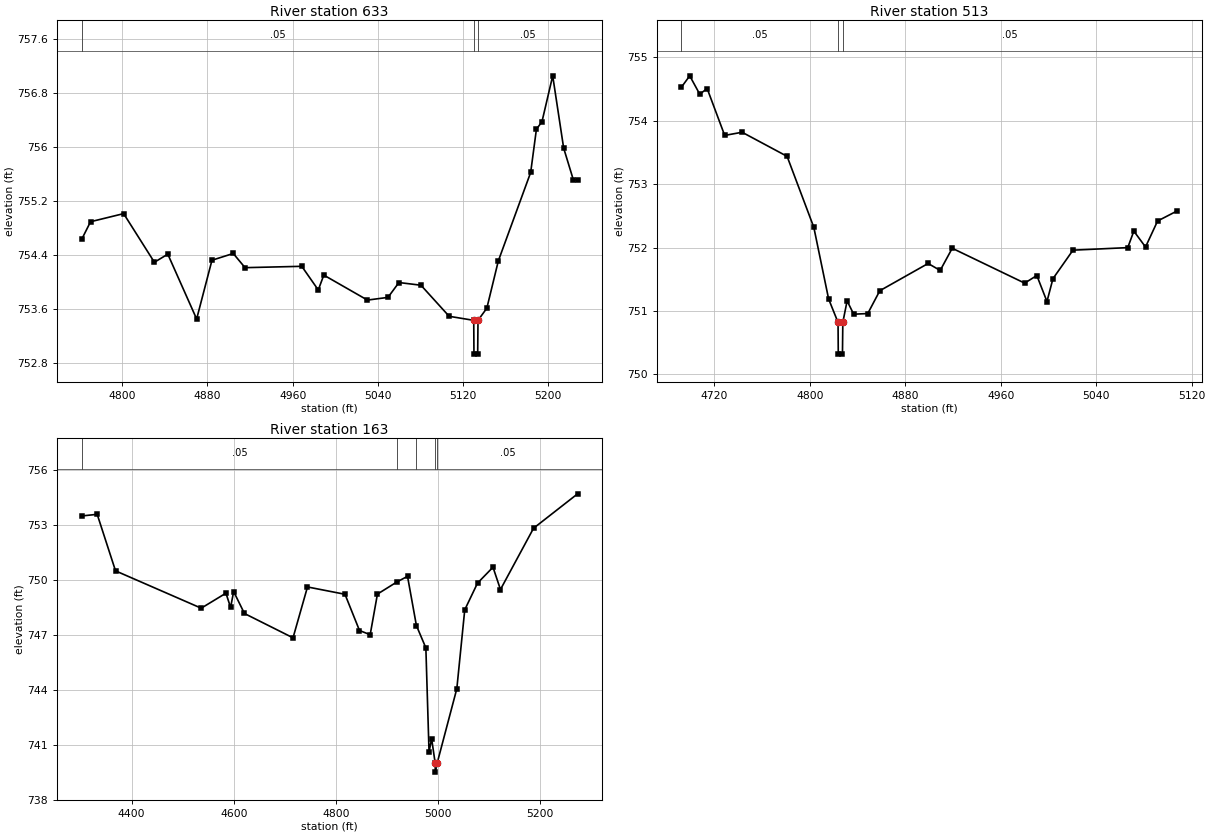
Type RM Length L Ch R = 1,633,120,120,120
BEGIN DESCRIPTION:
Mapping XS 61777f58
END DESCRIPTION:
XS GIS Cut Line= 3
      2305717.00      7115566.16      2305517.52      7115620.84
      2305266.28      7115684.42
#Sta/Elev= 30
  4761.8  754.63  4770.1  754.89  4801.2  755.01  4830.1  754.29  4842.7  754.41
  4869.8  753.45  4884.2  754.32  4904.2  754.42  4915.3  754.21  4968.6  754.23
  4984.1  753.88  4989.3  754.10  5030.3  753.73  5049.6  753.77  5059.9  753.99
  5080.6  753.95  5107.1  753.49  5130.2  753.43  5130.4  752.93  5133.9  752.93
  5134.2  753.43  5142.5  753.61  5153.3  754.31  5183.7  755.62  5189.1  756.26
  5194.3  756.37  5204.4  757.05  5214.7  755.98  5223.8  755.51  5227.8  755.51
#Mann=3,-1,0
  4761.8    0.05       0  5130.2   0.033       0  5134.2    0.05       0
Bank Sta=5130.2,5134.2
Exp/Cntr=0.3,0.1

Type RM Length L Ch R = 1,513,350,350,350
BEGIN DESCRIPTION:
Mapping XS 9d9ce439
END DESCRIPTION:
XS GIS Cut Line= 4
      2305743.39      7115566.34      2305689.69      7115526.87
      2305616.49      7115490.06      2305352.69      7115531.37
#Sta/Elev= 30
  4692.3  754.53  4699.3  754.71  4707.7  754.42  4713.9  754.51  4728.6  753.77
  4743.2  753.82  4780.9  753.44  4803.3  752.32  4815.7  751.19  4823.6  750.82
  4823.8  750.32  4827.3  750.32  4827.6  750.82  4831.2  751.16  4836.7  750.95
  4848.5  750.96  4858.6  751.32  4899.1  751.75  4909.2  751.64  4919.3  751.99
  4980.0  751.44  4990.2  751.56  4998.7  751.15  5003.7  751.51  5020.5  751.96
  5066.4  752.00  5071.5  752.26  5081.3  752.01  5091.4  752.42  5107.9  752.58
#Mann=3,-1,0
  4692.3    0.05       0  4823.6   0.033       0  4827.6    0.05       0
Bank Sta=4823.6,4827.6
Exp/Cntr=0.3,0.1

Type RM Length L Ch R = 1,163,0,0,0
BEGIN DESCRIPTION:
MDE S 099 1.0
END DESCRIPTION:
XS GIS Cut Line= 4
      2305736.38      7115515.28      2305488.09      7115138.67
      2305350.27      7115264.49      2305302.04      7115593.87
#Sta/Elev= 30
  4302.5  753.50  4332.8  753.59  4368.7  750.50  4536.4  748.46  4584.8  749.28
  4593.9  748.50  4599.9  749.37  4621.0  748.17  4716.1  746.84  4744.4  749.62
  4817.8  749.22  4846.2  747.24  4867.1  747.01  4881.3  749.23  4919.8  749.90
  4940.2  750.20  4957.6  747.51  4976.1  746.29  4982.3  740.61  4987.4  741.32
  4994.3  740.00  4994.6  739.50  4998.3  740.00  5036.7  744.06  5052.2  748.37
  5077.2  749.83  5107.5  750.70  5122.1  749.48  5186.9  752.83  5273.1  754.71
#Mann=5,-1,0
  4302.5    0.05       0  4919.8    0.12       0  4957.6    0.05       0
  4994.3   0.033       0  4998.3    0.05       0
Bank Sta=4994.3,4998.3
Exp/Cntr=0.3,0.1

Chan Stop Cuts=-1