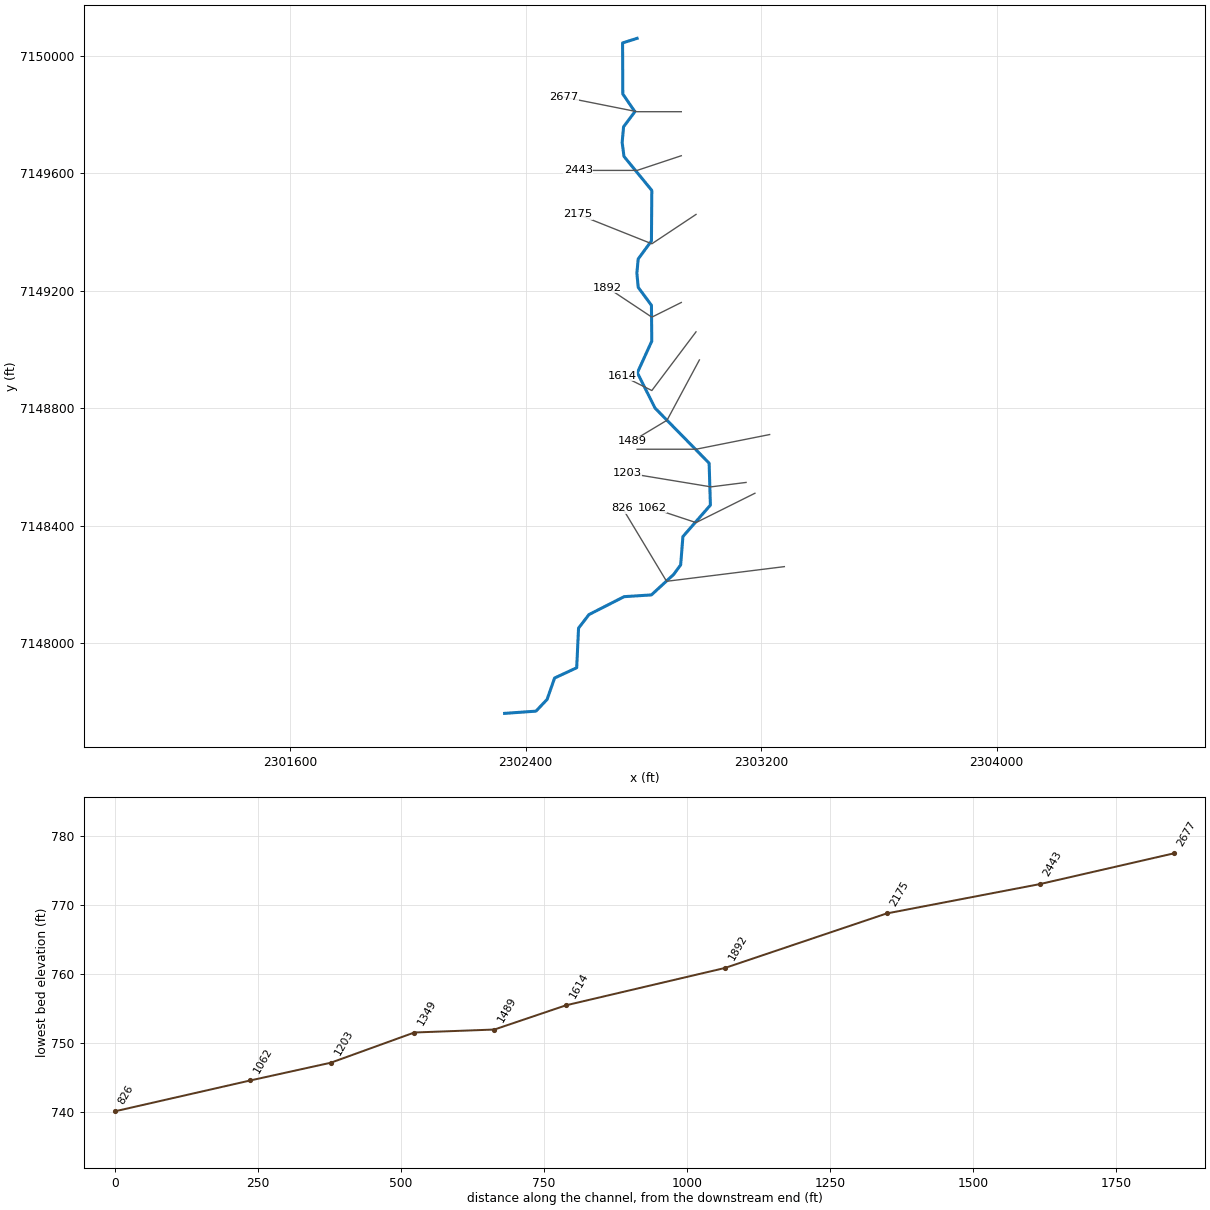
--- MDE S 103.prj (project) ---

Proj Title=MDE S 103 Base Level Engineering
Current Plan=p01
Default Exp/Contr=0.3,0.1
English Units
Geom File=g01
Flow File=f01
Plan File=p01
BEGIN DESCRIPTION:
MDE S 103
END DESCRIPTION:

--- MDE S 103.p01 (plan) ---

Plan Title=Multiple Run
Short Identifier=Multiple
Geom File=g01
Flow File=f01
Subcritical Flow
K Sum by GR= 0
Std Step Tol= 0.01
Critical Tol= 0.01
Num of Std Step Trials= 20
Max Error Tol= 0.3
Flow Tol Ratio= 0.001
Split Flow NTrial= 30
Split Flow Tol= 0.02
Split Flow Ratio= 0.02
Log Output Level= 0
Friction Slope Method= 1
Unsteady Friction Slope Method= 2
Unsteady Bridges Friction Slope Method= 1
Parabolic Critical Depth
Global Vel Dist=  1 , 1 , 1
Global Log Level= 0
CheckData=True
Encroach Param= -1, 0, 0, 0
BEGIN DESCRIPTION:
Multiple Run
END DESCRIPTION:

--- MDE S 103.f01 (steady flow) ---

Flow Title=Multiple
Number of Profiles=7
Profile Names=10-year,25-year,50-year,1pct_min,100-year,1pct_plu,500-year
River Rch & RM= MDE S 103,Reach-1,2677
     212     273     321     188     376     750     515
Boundary for River Rch & Prof#=MDE S 103,Reach-1,1
Up Type=0
Dn Type=3
Dn Slope=0.005
Boundary for River Rch & Prof#=MDE S 103,Reach-1,2
Up Type=0
Dn Type=3
Dn Slope=0.005
Boundary for River Rch & Prof#=MDE S 103,Reach-1,3
Up Type=0
Dn Type=3
Dn Slope=0.005
Boundary for River Rch & Prof#=MDE S 103,Reach-1,4
Up Type=0
Dn Type=3
Dn Slope=0.005
Boundary for River Rch & Prof#=MDE S 103,Reach-1,5
Up Type=0
Dn Type=3
Dn Slope=0.005
Boundary for River Rch & Prof#=MDE S 103,Reach-1,6
Up Type=0
Dn Type=3
Dn Slope=0.005
Boundary for River Rch & Prof#=MDE S 103,Reach-1,7
Up Type=0
Dn Type=3
Dn Slope=0.005

--- MDE S 103.g01 (geometry) ---

Geom Title=Existing Conditions

River Reach=MDE S 103,Reach-1
Reach XY= 30
      2302779.00      7150060.00      2302729.61      7150044.39
      2302730.38      7149870.44      2302771.44      7149810.00
      2302732.94      7149758.50      2302728.18      7149704.96
      2302734.42      7149657.58      2302828.91      7149541.78
      2302827.62      7149369.66      2302782.70      7149308.40
      2302778.18      7149260.00      2302782.71      7149211.60
      2302827.63      7149150.33      2302828.79      7149028.27
      2302779.75      7148920.68      2302839.76      7148800.32
      2303023.55      7148612.45      2303027.80      7148469.60
      2302934.54      7148362.42      2302926.85      7148265.88
      2302902.85      7148233.06      2302827.52      7148163.61
      2302734.97      7148157.67      2302615.36      7148096.56
      2302580.15      7148050.55      2302573.78      7147915.46
      2302498.74      7147880.42      2302473.26      7147807.46
      2302435.55      7147767.60      2302329.00      7147760.00

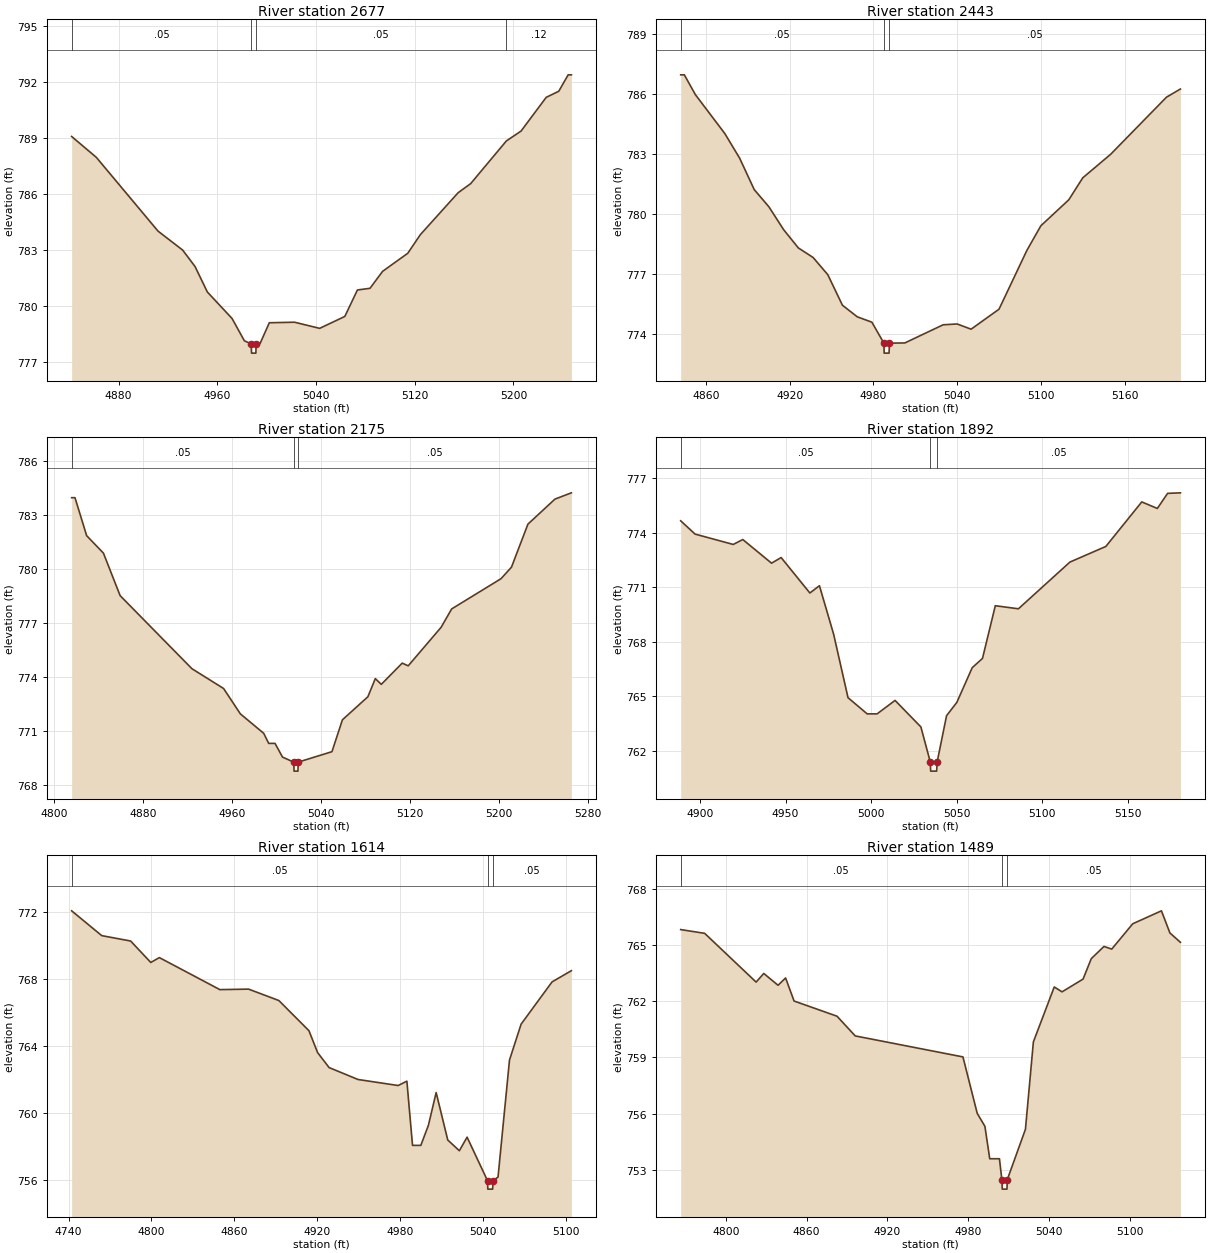
Type RM Length L Ch R = 1,2677,234,234,234
BEGIN DESCRIPTION:
MDE S 103 9.0
END DESCRIPTION:
XS GIS Cut Line= 3
      2302929.04      7149810.00      2302779.00      7149810.00
      2302528.99      7149860.00
#Sta/Elev= 30
  4842.0  789.09  4862.0  787.97  4912.0  784.01  4932.0  782.99  4942.0  782.11
  4952.0  780.74  4972.0  779.32  4982.0  778.12  4987.5  777.96  4987.8  777.46
  4991.3  777.46  4991.5  777.96  4994.6  777.96  5002.2  779.09  5022.6  779.12
  5043.0  778.79  5063.4  779.43  5073.6  780.85  5083.8  780.94  5094.0  781.85
  5114.4  782.82  5124.6  783.82  5155.2  786.07  5165.4  786.56  5194.3  788.85
  5206.2  789.38  5226.6  791.19  5236.8  791.52  5244.4  792.40  5247.0  792.40
#Mann=4,-1,0
  4842.0    0.05       0  4987.5   0.033       0  4991.5    0.05       0
  5194.3    0.12       0
Bank Sta=4987.5,4991.5
Exp/Cntr=0.3,0.1

Type RM Length L Ch R = 1,2443,268,268,268
BEGIN DESCRIPTION:
MDE S 103 8.0
END DESCRIPTION:
XS GIS Cut Line= 3
      2302928.99      7149660.00      2302779.00      7149610.00
      2302579.01      7149610.00
#Sta/Elev= 30
  4841.9  786.96  4844.5  786.96  4852.4  785.97  4873.5  784.02  4884.1  782.79
  4894.6  781.21  4905.1  780.35  4915.7  779.20  4926.2  778.29  4936.8  777.81
  4947.3  776.95  4957.8  775.42  4968.4  774.84  4978.9  774.57  4987.5  773.52
  4987.7  773.02  4991.2  773.02  4991.5  773.52  5002.5  773.53  5030.0  774.44
  5040.0  774.48  5050.0  774.22  5070.0  775.22  5090.0  778.17  5100.0  779.40
  5120.0  780.70  5130.0  781.80  5150.0  782.98  5190.0  785.84  5200.0  786.25
#Mann=3,-1,0
  4841.9    0.05       0  4987.5   0.033       0  4991.5    0.05       0
Bank Sta=4987.5,4991.5
Exp/Cntr=0.3,0.1

Type RM Length L Ch R = 1,2175,283,283,283
BEGIN DESCRIPTION:
MDE S 103 7.0
END DESCRIPTION:
XS GIS Cut Line= 3
      2302979.02      7149460.01      2302829.00      7149360.00
      2302578.96      7149460.01
#Sta/Elev= 30
  4815.6  783.96  4818.6  783.96  4829.1  781.85  4844.2  780.88  4859.2  778.52
  4923.8  774.46  4952.3  773.36  4967.4  771.95  4988.4  770.87  4992.9  770.31
  4998.6  770.31  5005.3  769.55  5015.4  769.27  5015.7  768.77  5019.2  768.77
  5019.4  769.27  5049.8  769.85  5059.2  771.62  5082.1  772.90  5088.8  773.91
  5094.2  773.59  5113.0  774.77  5118.4  774.62  5148.0  776.76  5157.5  777.78
  5201.9  779.46  5211.3  780.10  5226.1  782.49  5250.4  783.88  5265.2  784.23
#Mann=3,-1,0
  4815.6    0.05       0  5015.4   0.033       0  5019.4    0.05       0
Bank Sta=5015.4,5019.4
Exp/Cntr=0.3,0.1

Type RM Length L Ch R = 1,1892,278,278,278
BEGIN DESCRIPTION:
MDE S 103 6.0
END DESCRIPTION:
XS GIS Cut Line= 3
      2302929.00      7149160.00      2302829.00      7149110.00
      2302678.99      7149210.01
#Sta/Elev= 30
  4888.7  774.65  4897.1  773.92  4919.4  773.35  4925.0  773.62  4941.8  772.32
  4947.4  772.63  4964.2  770.68  4969.8  771.08  4978.1  768.41  4986.5  764.92
  4997.7  764.03  5003.5  764.03  5014.0  764.77  5029.1  763.31  5034.6  761.38
  5034.8  760.88  5038.3  760.88  5038.6  761.38  5044.1  763.93  5050.1  764.66
  5059.1  766.57  5065.1  767.08  5072.6  769.98  5086.1  769.81  5116.2  772.38
  5137.2  773.24  5158.2  775.69  5167.3  775.33  5173.3  776.16  5180.8  776.19
#Mann=3,-1,0
  4888.7    0.05       0  5034.6   0.033       0  5038.6    0.05       0
Bank Sta=5034.6,5038.6
Exp/Cntr=0.3,0.1

Type RM Length L Ch R = 1,1614,125,125,125
BEGIN DESCRIPTION:
MDE S 103 5.0
END DESCRIPTION:
XS GIS Cut Line= 3
      2302978.98      7149059.97      2302829.00      7148860.00
      2302728.97      7148910.02
#Sta/Elev= 30
  4742.2  772.08  4764.0  770.60  4784.9  770.28  4799.5  769.00  4805.7  769.29
  4849.5  767.38  4870.3  767.41  4892.2  766.73  4914.0  764.93  4920.3  763.62
  4928.6  762.73  4949.5  762.02  4978.6  761.66  4984.9  761.92  4989.0  758.09
  4995.0  758.09  5000.5  759.29  5006.1  761.24  5014.5  758.41  5022.9  757.77
  5028.5  758.58  5043.3  755.98  5043.5  755.48  5047.0  755.48  5047.3  755.98
  5050.9  756.20  5059.2  763.18  5067.6  765.32  5090.0  767.84  5104.0  768.51
#Mann=3,-1,0
  4742.2    0.05       0  5043.3   0.033       0  5047.3    0.05       0
Bank Sta=5043.3,5047.3
Exp/Cntr=0.3,0.1

Type RM Length L Ch R = 1,1489,140,140,140
BEGIN DESCRIPTION:
Mapping XS 3a5e14dd
END DESCRIPTION:
XS GIS Cut Line= 3
      2302990.46      7148964.25      2302880.60      7148758.79
      2302762.29      7148687.54
#Sta/Elev= 30
  4766.5  765.82  4784.3  765.62  4822.5  763.02  4828.2  763.48  4838.8  762.85
  4844.4  763.24  4850.7  762.01  4882.6  761.20  4896.1  760.15  4976.1  759.03
  4986.7  756.02  4992.4  755.33  4996.0  753.60  5003.2  753.60  5005.0  752.48
  5005.3  751.98  5008.8  751.98  5009.0  752.48  5022.5  755.17  5028.4  759.83
  5043.9  762.76  5049.7  762.50  5065.3  763.18  5071.4  764.27  5080.8  764.92
  5086.6  764.78  5102.2  766.13  5123.5  766.82  5129.8  765.64  5137.6  765.14
#Mann=3,-1,0
  4766.5    0.05       0  5005.0   0.033       0  5009.0    0.05       0
Bank Sta=5005,5009
Exp/Cntr=0.3,0.1

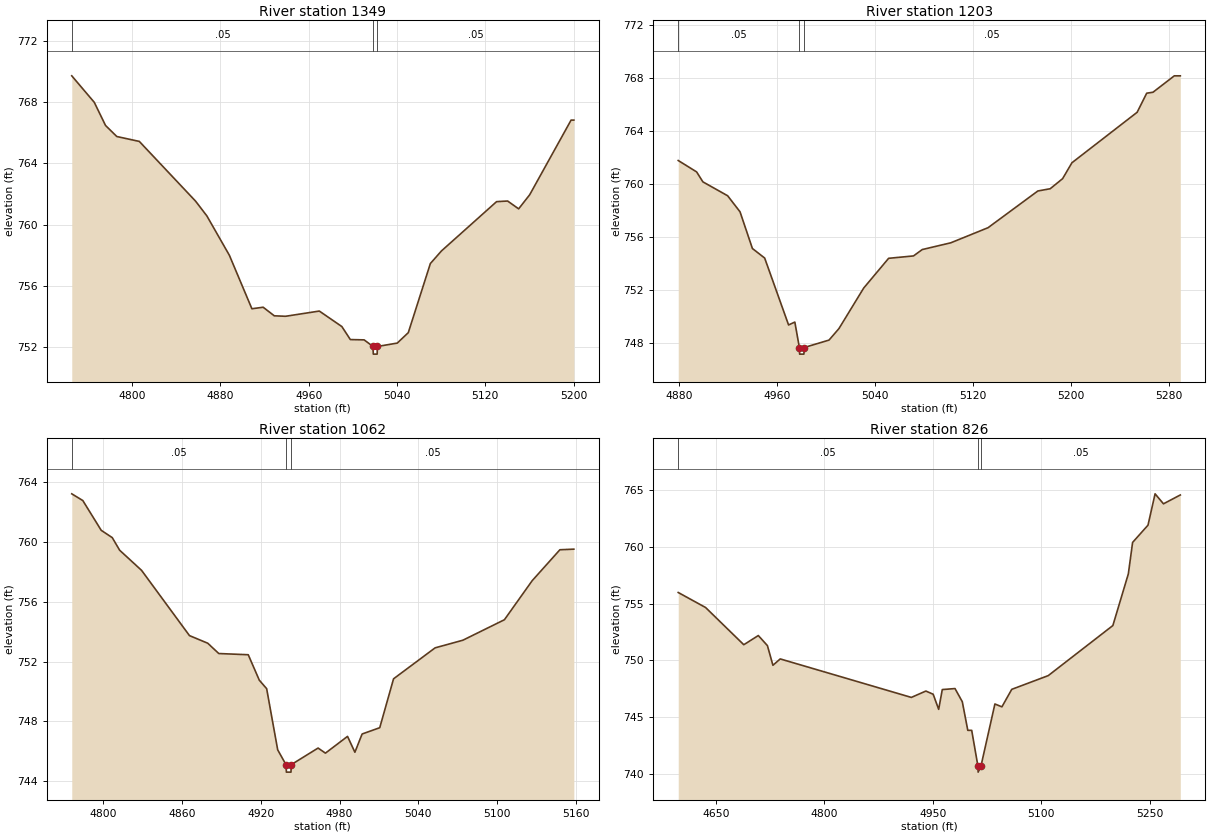
Type RM Length L Ch R = 1,1349,146,146,146
BEGIN DESCRIPTION:
MDE S 103 4.0
END DESCRIPTION:
XS GIS Cut Line= 3
      2303228.98      7148710.00      2302979.00      7148660.00
      2302779.03      7148660.00
#Sta/Elev= 30
  4745.4  769.71  4765.8  767.98  4776.0  766.47  4786.2  765.75  4806.6  765.43
  4857.6  761.53  4867.8  760.57  4888.2  758.00  4908.6  754.51  4918.8  754.61
  4928.9  754.05  4939.1  754.02  4969.7  754.36  4990.1  753.35  4997.8  752.50
  5010.3  752.48  5018.3  752.05  5018.6  751.55  5022.1  751.55  5022.3  752.05
  5040.3  752.27  5050.3  752.95  5070.3  757.46  5080.3  758.28  5130.3  761.50
  5140.3  761.54  5150.3  761.03  5160.3  761.95  5197.8  766.82  5200.3  766.82
#Mann=3,-1,0
  4745.4    0.05       0  5018.3   0.033       0  5022.3    0.05       0
Bank Sta=5018.3,5022.3
Exp/Cntr=0.3,0.1

Type RM Length L Ch R = 1,1203,141,141,141
BEGIN DESCRIPTION:
Mapping XS 470aa7d9
END DESCRIPTION:
XS GIS Cut Line= 3
      2303148.98      7148546.87      2303029.87      7148531.78
      2302744.31      7148579.02
#Sta/Elev= 30
  4879.5  761.79  4894.5  760.93  4899.6  760.18  4919.8  759.13  4929.9  757.92
  4940.0  755.15  4950.0  754.43  4969.5  749.38  4974.6  749.60  4978.3  747.68
  4978.5  747.18  4982.0  747.18  4982.3  747.68  5002.5  748.24  5010.6  749.11
  5030.8  752.17  5051.1  754.41  5071.4  754.59  5078.5  755.07  5101.8  755.58
  5132.2  756.72  5172.8  759.49  5182.9  759.66  5193.0  760.42  5200.6  761.62
  5253.8  765.43  5261.6  766.87  5266.7  766.94  5284.1  768.18  5289.0  768.18
#Mann=3,-1,0
  4879.5    0.05       0  4978.3   0.033       0  4982.3    0.05       0
Bank Sta=4978.3,4982.3
Exp/Cntr=0.3,0.1

Type RM Length L Ch R = 1,1062,236,236,236
BEGIN DESCRIPTION:
MDE S 103 3.0
END DESCRIPTION:
XS GIS Cut Line= 3
      2303179.03      7148510.01      2302979.00      7148410.00
      2302828.95      7148460.02
#Sta/Elev= 30
  4776.4  763.22  4784.8  762.77  4798.8  760.78  4807.2  760.29  4812.8  759.45
  4829.5  758.10  4865.9  753.74  4879.8  753.23  4888.2  752.54  4910.6  752.46
  4919.0  750.76  4924.6  750.19  4933.0  746.10  4939.3  745.11  4939.6  744.61
  4943.1  744.61  4943.3  745.11  4963.7  746.22  4969.3  745.88  4986.1  747.00
  4991.7  745.94  4997.2  747.16  5010.6  747.58  5021.1  750.85  5052.7  752.92
  5073.8  753.43  5105.4  754.80  5126.5  757.41  5147.6  759.48  5158.2  759.52
#Mann=3,-1,0
  4776.4    0.05       0  4939.3   0.033       0  4943.3    0.05       0
Bank Sta=4939.3,4943.3
Exp/Cntr=0.3,0.1

Type RM Length L Ch R = 1,826,0,0,0
BEGIN DESCRIPTION:
MDE S 103 2.0
END DESCRIPTION:
XS GIS Cut Line= 3
      2303278.98      7148260.00      2302879.00      7148210.00
      2302729.02      7148459.97
#Sta/Elev= 30
  4597.7  755.98  4635.5  754.66  4688.4  751.38  4708.5  752.19  4721.1  751.30
  4728.7  749.57  4738.8  750.13  4920.2  746.74  4940.3  747.30  4950.4  747.02
  4958.0  745.69  4963.0  747.43  4980.6  747.52  4990.7  746.36  4998.3  743.84
  5003.7  743.84  5012.4  740.66  5012.6  740.16  5016.4  740.66  5035.8  746.16
  5045.5  745.91  5059.1  747.45  5109.6  748.66  5199.0  753.07  5220.4  757.62
  5226.3  760.39  5247.6  761.91  5257.4  764.67  5269.0  763.79  5292.3  764.57
#Mann=3,-1,0
  4597.7    0.05       0  5012.4   0.033       0  5016.4    0.05       0
Bank Sta=5012.4,5016.4
Exp/Cntr=0.3,0.1

Chan Stop Cuts=-1