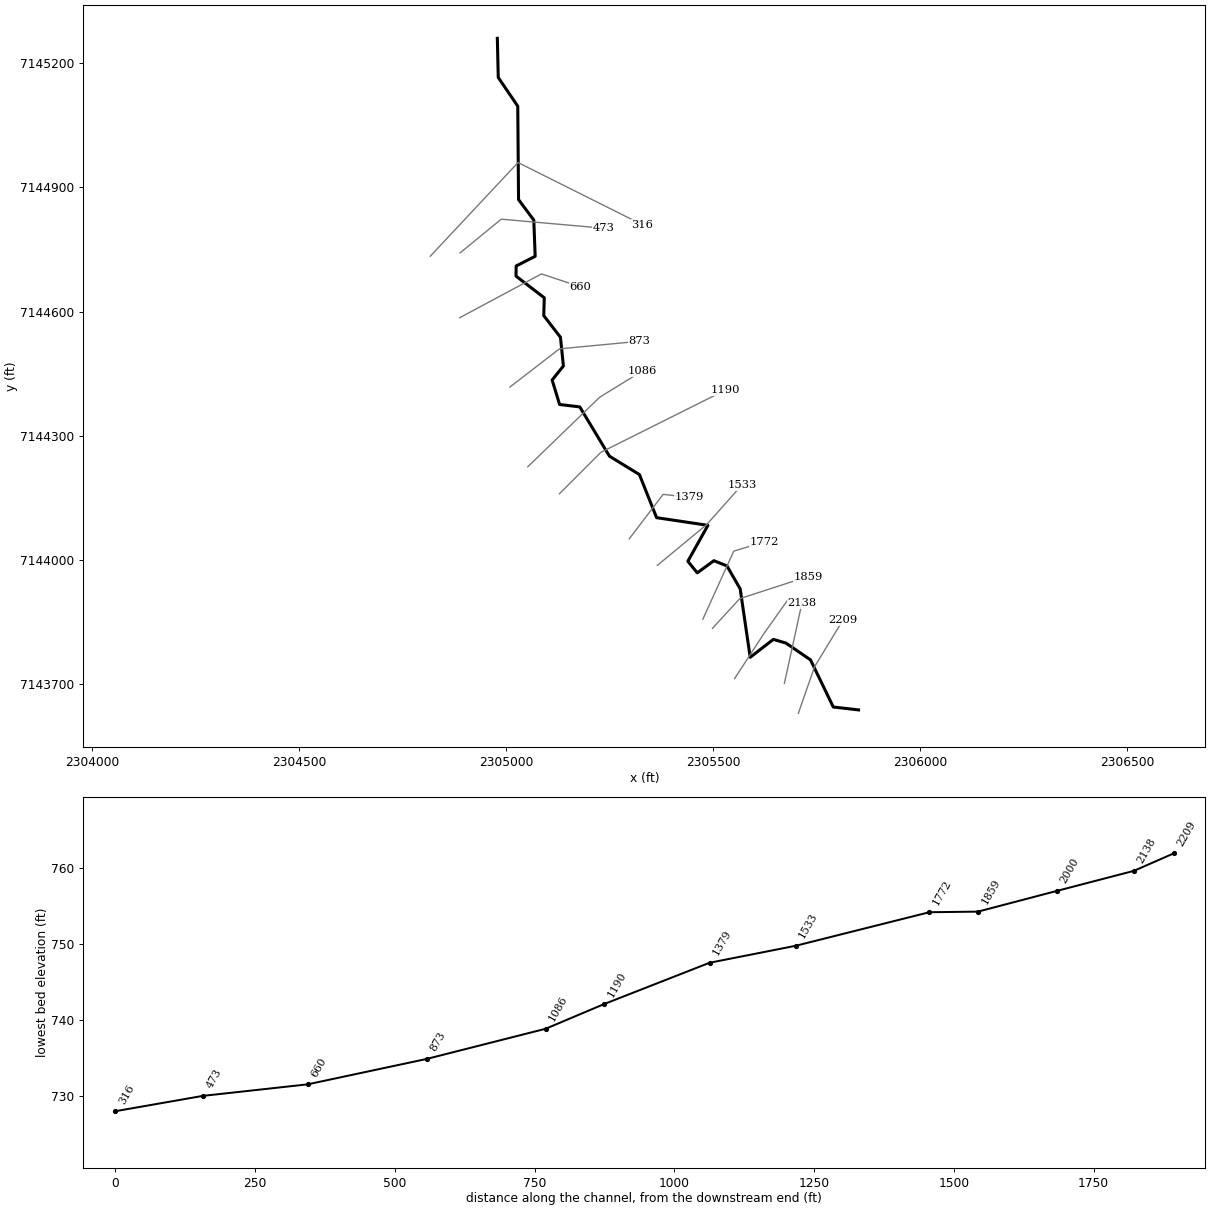
--- MDE S 104.prj (project) ---

Proj Title=MDE S 104 Base Level Engineering
Current Plan=p01
Default Exp/Contr=0.3,0.1
English Units
Geom File=g01
Flow File=f01
Plan File=p01
BEGIN DESCRIPTION:
MDE S 104
END DESCRIPTION:

--- MDE S 104.p01 (plan) ---

Plan Title=Multiple Run
Short Identifier=Multiple
Geom File=g01
Flow File=f01
Subcritical Flow
K Sum by GR= 0
Std Step Tol= 0.01
Critical Tol= 0.01
Num of Std Step Trials= 20
Max Error Tol= 0.3
Flow Tol Ratio= 0.001
Split Flow NTrial= 30
Split Flow Tol= 0.02
Split Flow Ratio= 0.02
Log Output Level= 0
Friction Slope Method= 1
Unsteady Friction Slope Method= 2
Unsteady Bridges Friction Slope Method= 1
Parabolic Critical Depth
Global Vel Dist=  1 , 1 , 1
Global Log Level= 0
CheckData=True
Encroach Param= -1, 0, 0, 0
BEGIN DESCRIPTION:
Multiple Run
END DESCRIPTION:

--- MDE S 104.f01 (steady flow) ---

Flow Title=Multiple
Number of Profiles=7
Profile Names=10-year,25-year,50-year,1pct_min,100-year,1pct_plu,500-year
River Rch & RM= MDE S 104,Reach-1,2209
     235     305     361     213     426     849     590
Boundary for River Rch & Prof#=MDE S 104,Reach-1,1
Up Type=0
Dn Type=3
Dn Slope=0.005
Boundary for River Rch & Prof#=MDE S 104,Reach-1,2
Up Type=0
Dn Type=3
Dn Slope=0.005
Boundary for River Rch & Prof#=MDE S 104,Reach-1,3
Up Type=0
Dn Type=3
Dn Slope=0.005
Boundary for River Rch & Prof#=MDE S 104,Reach-1,4
Up Type=0
Dn Type=3
Dn Slope=0.005
Boundary for River Rch & Prof#=MDE S 104,Reach-1,5
Up Type=0
Dn Type=3
Dn Slope=0.005
Boundary for River Rch & Prof#=MDE S 104,Reach-1,6
Up Type=0
Dn Type=3
Dn Slope=0.005
Boundary for River Rch & Prof#=MDE S 104,Reach-1,7
Up Type=0
Dn Type=3
Dn Slope=0.005

--- MDE S 104.g01 (geometry) ---

Geom Title=Existing Conditions

River Reach=MDE S 104,Reach-1
Reach XY= 30
      2305851.46      7143637.88      2305790.46      7143644.87
      2305735.40      7143758.80      2305675.97      7143799.40
      2305645.73      7143808.24      2305589.75      7143764.91
      2305565.57      7143930.30      2305533.56      7143985.69
      2305502.01      7143998.34      2305461.91      7143968.91
      2305439.17      7143996.92      2305487.64      7144083.69
      2305363.68      7144102.23      2305322.18      7144206.38
      2305249.89      7144250.66      2305178.10      7144369.76
      2305129.35      7144375.66      2305111.36      7144434.71
      2305138.58      7144468.58      2305131.44      7144537.97
      2305091.13      7144590.22      2305092.38      7144633.32
      2305024.08      7144685.70      2305024.46      7144710.14
      2305070.39      7144733.52      2305067.02      7144821.01
      2305030.22      7144870.50      2305028.33      7145096.09
      2304981.22      7145165.47      2304979.00      7145260.00

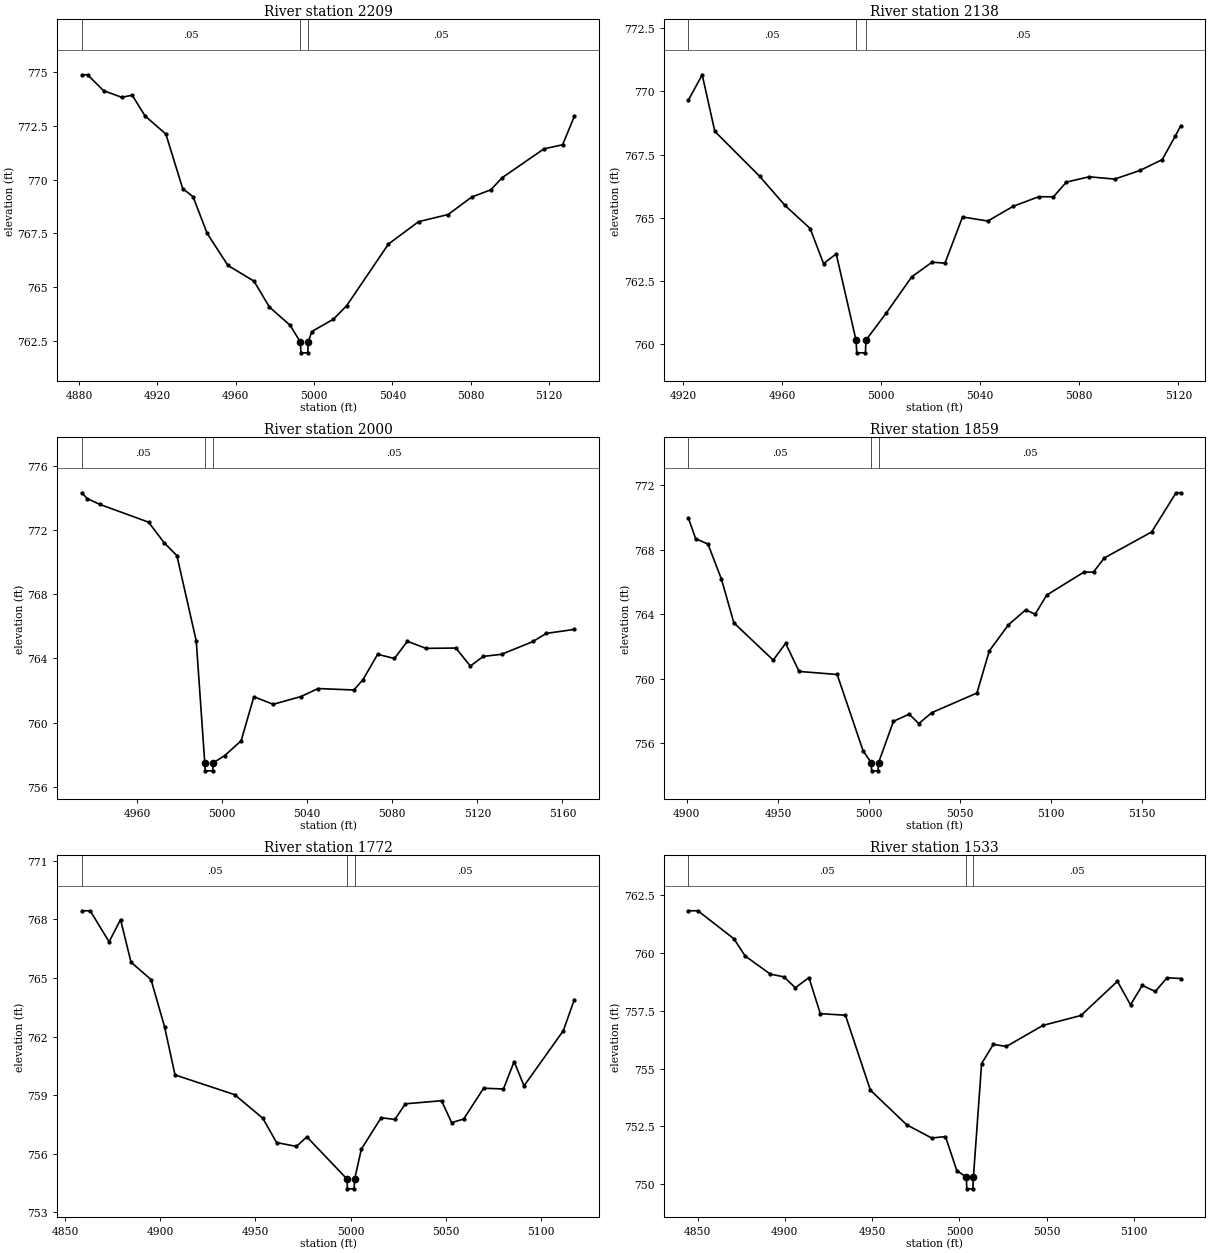
Type RM Length L Ch R = 1,2209,71,71,71
BEGIN DESCRIPTION:
MDE S 104 7.0
END DESCRIPTION:
XS GIS Cut Line= 3
      2305705.98      7143629.52      2305745.19      7143742.11
      2305813.96      7143855.11
#Sta/Elev= 30
  4881.4  774.89  4884.3  774.89  4892.5  774.15  4901.8  773.84  4907.1  773.94
  4913.7  772.97  4924.3  772.13  4932.9  769.59  4938.2  769.21  4945.4  767.50
  4956.0  766.01  4969.3  765.28  4977.2  764.07  4987.8  763.22  4993.0  762.44
  4993.3  761.94  4996.8  761.94  4997.0  762.44  4998.8  762.93  5009.9  763.51
  5016.6  764.13  5038.0  767.01  5053.4  768.05  5068.4  768.38  5080.6  769.20
  5090.2  769.53  5096.1  770.10  5117.4  771.44  5126.9  771.63  5132.9  772.95
#Mann=3,-1,0
  4881.4    0.05       0  4993.0   0.033       0  4997.0    0.05       0
Bank Sta=4993,4997
Exp/Cntr=0.3,0.1

Type RM Length L Ch R = 1,2138,138,138,138
BEGIN DESCRIPTION:
Mapping XS 16ff93cc
END DESCRIPTION:
XS GIS Cut Line= 2
      2305672.31      7143701.89      2305714.76      7143896.10
#Sta/Elev= 28
  4922.2  769.65  4927.8  770.66  4932.9  768.42  4951.0  766.64  4961.2  765.49
  4971.4  764.57  4976.8  763.18  4981.9  763.57  4989.9  760.15  4990.2  759.65
  4993.7  759.65  4993.9  760.15  5002.2  761.24  5012.4  762.66  5020.6  763.24
  5025.8  763.20  5032.9  765.03  5043.1  764.87  5053.3  765.45  5063.6  765.83
  5069.6  765.83  5074.8  766.41  5084.0  766.62  5094.3  766.53  5104.5  766.87
  5113.5  767.30  5118.7  768.22  5121.0  768.64
#Mann=3,-1,0
  4922.2    0.05       0  4989.9   0.033       0  4993.9    0.05       0
Bank Sta=4989.9,4993.9
Exp/Cntr=0.3,0.1

Type RM Length L Ch R = 1,2000,141,141,141
BEGIN DESCRIPTION:
Mapping XS 4fb16338
END DESCRIPTION:
XS GIS Cut Line= 3
      2305552.19      7143713.66      2305621.97      7143820.85
      2305681.88      7143905.49
#Sta/Elev= 30
  4934.0  774.31  4936.5  773.95  4942.4  773.59  4965.4  772.48  4972.7  771.20
  4978.7  770.40  4987.8  765.09  4991.8  757.51  4992.0  757.01  4995.5  757.01
  4995.8  757.51  5001.2  757.96  5008.9  758.88  5014.9  761.62  5024.0  761.15
  5037.0  761.63  5045.1  762.13  5061.9  762.04  5066.2  762.68  5073.1  764.26
  5081.0  764.00  5087.1  765.07  5095.8  764.63  5109.9  764.65  5116.7  763.53
  5122.8  764.13  5131.4  764.26  5146.2  765.06  5152.4  765.56  5165.6  765.81
#Mann=3,-1,0
  4934.0    0.05       0  4991.8   0.033       0  4995.8    0.05       0
Bank Sta=4991.8,4995.8
Exp/Cntr=0.3,0.1

Type RM Length L Ch R = 1,1859,87,87,87
BEGIN DESCRIPTION:
MDE S 104 6.0
END DESCRIPTION:
XS GIS Cut Line= 3
      2305498.58      7143834.93      2305564.54      7143906.63
      2305728.98      7143959.99
#Sta/Elev= 30
  4900.8  769.97  4904.8  768.68  4911.6  768.34  4919.0  766.16  4925.8  763.46
  4947.4  761.15  4954.2  762.19  4961.6  760.45  4982.5  760.26  4996.7  755.54
  5001.2  754.79  5001.4  754.29  5004.9  754.29  5005.2  754.79  5013.4  757.36
  5022.0  757.80  5027.3  757.22  5034.5  757.90  5059.2  759.11  5066.0  761.72
  5076.5  763.34  5085.9  764.26  5091.2  764.00  5097.5  765.18  5117.9  766.60
  5123.2  766.61  5129.1  767.48  5155.1  769.09  5168.5  771.52  5171.1  771.52
#Mann=3,-1,0
  4900.8    0.05       0  5001.2   0.033       0  5005.2    0.05       0
Bank Sta=5001.2,5005.2
Exp/Cntr=0.3,0.1

Type RM Length L Ch R = 1,1772,239,239,239
BEGIN DESCRIPTION:
Mapping XS 20052216
END DESCRIPTION:
XS GIS Cut Line= 3
      2305475.39      7143856.97      2305550.04      7144021.39
      2305624.58      7144044.10
#Sta/Elev= 30
  4858.9  768.44  4863.3  768.44  4873.2  766.85  4879.2  767.99  4884.7  765.81
  4895.2  764.92  4902.3  762.51  4907.8  760.04  4939.1  759.03  4953.9  757.82
  4961.1  756.58  4971.5  756.38  4977.0  756.87  4998.1  754.71  4998.3  754.21
  5001.8  754.21  5002.1  754.71  5005.6  756.24  5016.0  757.85  5023.2  757.76
  5028.7  758.56  5047.7  758.72  5053.0  757.60  5059.3  757.78  5069.8  759.36
  5080.2  759.32  5085.8  760.72  5091.0  759.48  5111.6  762.30  5117.4  763.89
#Mann=3,-1,0
  4858.9    0.05       0  4998.1   0.033       0  5002.1    0.05       0
Bank Sta=4998.1,5002.1
Exp/Cntr=0.3,0.1

Type RM Length L Ch R = 1,1533,154,154,154
BEGIN DESCRIPTION:
MDE S 104 5.0
END DESCRIPTION:
XS GIS Cut Line= 3
      2305365.51      7143986.97      2305485.05      7144085.95
      2305569.39      7144180.76
#Sta/Elev= 30
  4844.7  761.83  4850.2  761.83  4870.8  760.62  4877.3  759.87  4891.7  759.09
  4899.5  758.97  4906.0  758.50  4913.8  758.94  4920.3  757.38  4934.7  757.31
  4949.0  754.07  4969.8  752.57  4984.1  752.00  4992.0  752.06  4998.5  750.59
  5004.0  750.30  5004.2  749.80  5007.7  749.80  5008.0  750.30  5012.7  755.22
  5019.4  756.05  5026.9  755.96  5047.8  756.87  5069.6  757.30  5090.5  758.78
  5098.0  757.76  5104.7  758.60  5112.2  758.34  5118.9  758.93  5126.8  758.90
#Mann=3,-1,0
  4844.7    0.05       0  5004.0   0.033       0  5008.0    0.05       0
Bank Sta=5004,5008
Exp/Cntr=0.3,0.1

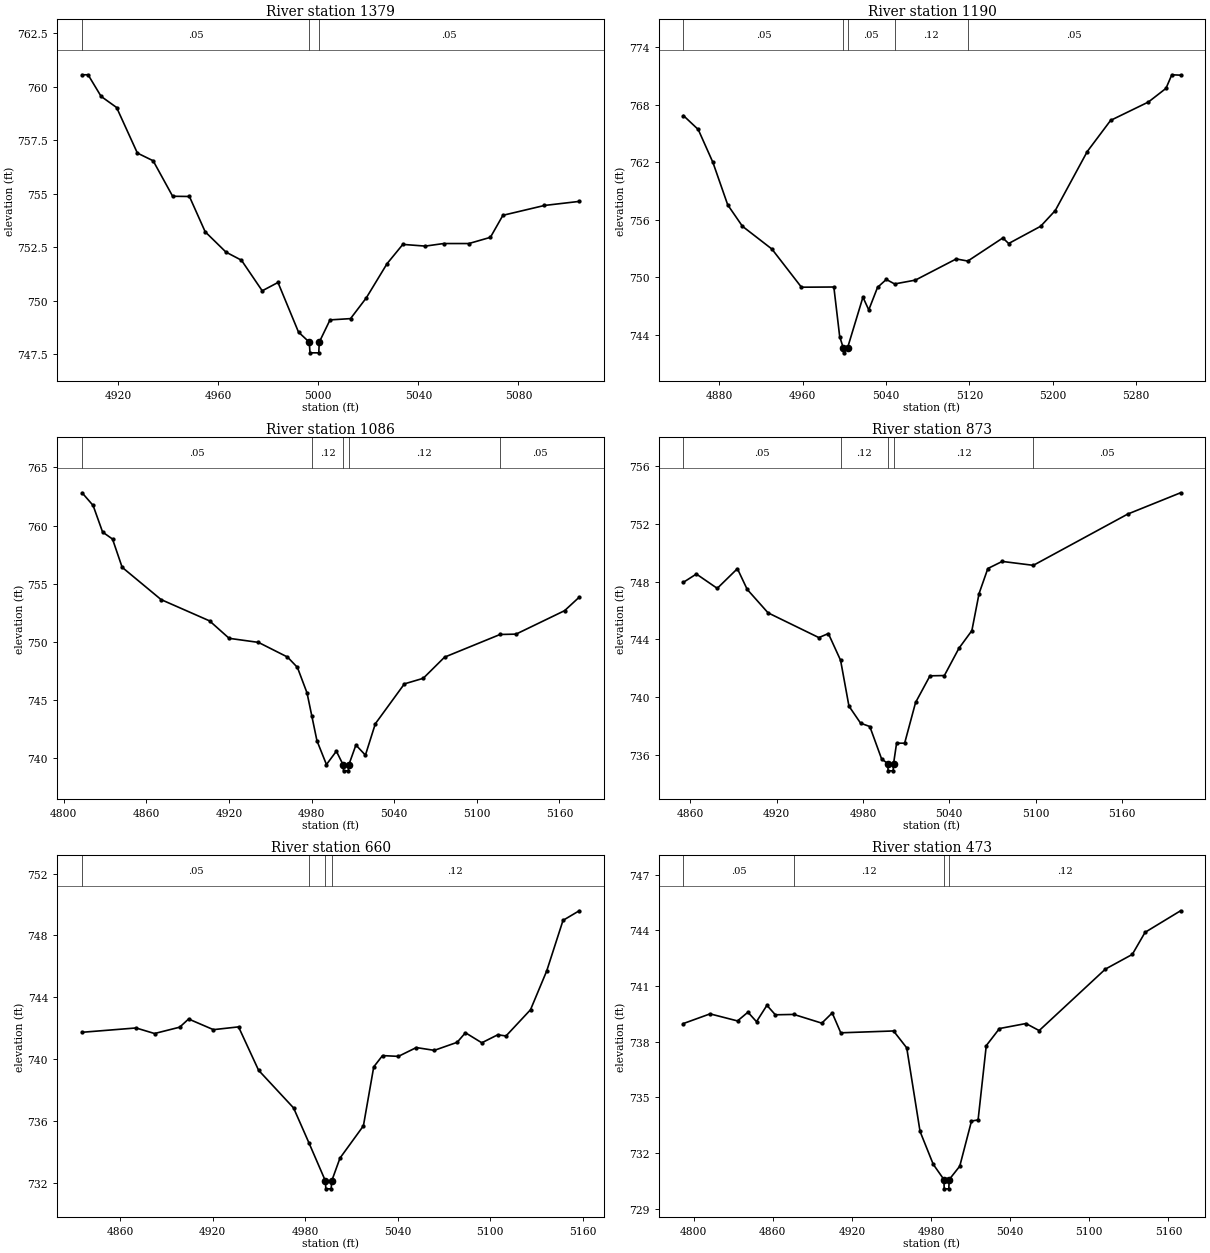
Type RM Length L Ch R = 1,1379,189,189,189
BEGIN DESCRIPTION:
Mapping XS 2eca9a68
END DESCRIPTION:
XS GIS Cut Line= 3
      2305297.71      7144051.23      2305379.49      7144158.56
      2305442.86      7144151.43
#Sta/Elev= 30
  4905.6  760.57  4908.0  760.57  4913.2  759.56  4919.4  759.04  4927.7  756.91
  4934.0  756.55  4941.8  754.89  4948.5  754.88  4954.8  753.23  4963.1  752.28
  4969.3  751.90  4977.6  750.47  4983.9  750.86  4992.1  748.54  4996.4  748.07
  4996.7  747.57  5000.2  747.57  5000.4  748.07  5004.7  749.11  5012.9  749.17
  5019.2  750.14  5027.5  751.74  5033.8  752.64  5042.8  752.56  5050.1  752.68
  5060.2  752.68  5068.8  752.97  5073.8  754.00  5090.4  754.46  5104.3  754.65
#Mann=3,-1,0
  4905.6    0.05       0  4996.4   0.033       0  5000.4    0.05       0
Bank Sta=4996.4,5000.4
Exp/Cntr=0.3,0.1

Type RM Length L Ch R = 1,1190,104,104,104
BEGIN DESCRIPTION:
MDE S 104 4.0
END DESCRIPTION:
XS GIS Cut Line= 3
      2305128.97      7144159.97      2305229.00      7144260.00
      2305529.02      7144410.01
#Sta/Elev= 30
  4845.6  766.89  4859.8  765.44  4873.9  762.00  4888.1  757.57  4902.2  755.34
  4930.5  752.96  4958.8  748.98  4989.9  749.00  4995.5  743.83  4999.0  742.63
  4999.3  742.13  5003.0  742.63  5017.8  747.94  5023.4  746.61  5031.8  748.96
  5040.2  749.79  5048.2  749.32  5068.1  749.72  5107.3  751.93  5118.4  751.71
  5152.0  754.12  5157.6  753.54  5188.3  755.34  5202.3  756.98  5233.0  763.14
  5255.4  766.39  5291.7  768.31  5308.5  769.73  5314.1  771.15  5322.5  771.11
#Mann=5,-1,0
  4845.6    0.05       0  4999.0   0.033       0  5003.0    0.05       0
  5048.2    0.12       0  5118.4    0.05       0
Bank Sta=4999,5003
Exp/Cntr=0.3,0.1

Type RM Length L Ch R = 1,1086,213,213,213
BEGIN DESCRIPTION:
Mapping XS b869589e
END DESCRIPTION:
XS GIS Cut Line= 3
      2305052.59      7144225.26      2305226.47      7144393.31
      2305328.04      7144455.86
#Sta/Elev= 30
  4813.3  762.82  4821.3  761.73  4828.2  759.44  4835.4  758.84  4842.4  756.41
  4870.7  753.63  4905.9  751.80  4920.1  750.30  4941.4  749.95  4962.5  748.69
  4969.7  747.80  4976.7  745.60  4980.2  743.60  4983.9  741.49  4990.8  739.44
  4998.0  740.59  5003.0  739.40  5003.2  738.90  5006.7  738.90  5007.0  739.40
  5012.2  741.12  5019.1  740.25  5026.3  742.95  5047.4  746.38  5061.1  746.86
  5076.6  748.68  5116.9  750.63  5128.5  750.66  5163.8  752.68  5174.4  753.84
#Mann=5,-1,0
  4813.3    0.05       0  4980.2    0.12       0  5003.0    0.07       0
  5007.0    0.12       0  5116.9    0.05       0
Bank Sta=5003,5007
Exp/Cntr=0.3,0.1

Type RM Length L Ch R = 1,873,213,213,213
BEGIN DESCRIPTION:
MDE S 104 3.0
END DESCRIPTION:
XS GIS Cut Line= 3
      2305009.27      7144417.64      2305129.00      7144510.00
      2305322.32      7144528.29
#Sta/Elev= 30
  4855.3  747.95  4864.3  748.52  4878.8  747.53  4892.8  748.89  4899.6  747.46
  4914.1  745.84  4949.4  744.13  4956.0  744.41  4964.5  742.56  4970.3  739.40
  4978.4  738.22  4984.8  737.99  4993.0  735.75  4997.3  735.43  4997.5  734.93
  5001.0  734.93  5001.3  735.43  5003.4  736.84  5009.0  736.84  5016.6  739.65
  5026.6  741.49  5036.6  741.51  5046.7  743.39  5055.7  744.61  5060.7  747.17
  5066.8  748.90  5076.8  749.39  5098.4  749.12  5164.0  752.66  5200.7  754.13
#Mann=5,-1,0
  4855.3    0.05       0  4964.5    0.12       0  4997.3    0.07       0
  5001.3    0.12       0  5098.4    0.05       0
Bank Sta=4997.3,5001.3
Exp/Cntr=0.3,0.1

Type RM Length L Ch R = 1,660,187,187,187
BEGIN DESCRIPTION:
MDE S 104 2.0
END DESCRIPTION:
XS GIS Cut Line= 3
      2304888.12      7144585.14      2305085.62      7144691.03
      2305179.00      7144660.00
#Sta/Elev= 30
  4835.2  741.73  4870.2  742.01  4882.2  741.65  4898.5  742.06  4904.3  742.59
  4920.4  741.90  4936.7  742.08  4949.7  739.27  4972.4  736.83  4982.4  734.56
  4993.1  732.09  4993.3  731.59  4996.8  731.59  4997.1  732.09  5002.5  733.58
  5017.7  735.67  5024.4  739.49  5030.1  740.22  5040.4  740.17  5052.0  740.74
  5063.7  740.56  5078.5  741.08  5083.9  741.70  5094.5  741.05  5104.9  741.57
  5110.2  741.49  5126.1  743.19  5136.6  745.70  5147.2  748.98  5157.7  749.60
#Mann=4,-1,0
  4835.2    0.05       0  4982.4    0.12       0  4993.1    0.07       0
  4997.1    0.12       0
Bank Sta=4993.1,4997.1
Exp/Cntr=0.3,0.1

Type RM Length L Ch R = 1,473,157,157,157
BEGIN DESCRIPTION:
Mapping XS 9618d610
END DESCRIPTION:
XS GIS Cut Line= 3
      2304888.97      7144741.70      2304988.49      7144823.26
      2305235.75      7144801.35
#Sta/Elev= 30
  4792.3  738.98  4812.5  739.50  4833.3  739.12  4841.2  739.59  4847.7  739.08
  4855.6  739.96  4862.0  739.45  4876.0  739.47  4897.2  739.00  4905.1  739.55
  4911.6  738.48  4951.6  738.58  4961.6  737.67  4971.7  733.17  4981.7  731.40
  4989.8  730.58  4990.0  730.08  4993.5  730.08  4993.8  730.58  5001.8  731.30
  5010.7  733.73  5015.7  733.79  5021.9  737.79  5031.9  738.71  5052.0  738.98
  5062.0  738.60  5112.2  741.91  5132.6  742.70  5142.3  743.89  5169.2  745.05
#Mann=4,-1,0
  4792.3    0.05       0  4876.0    0.12       0  4989.8    0.07       0
  4993.8    0.12       0
Bank Sta=4989.8,4993.8
Exp/Cntr=0.3,0.1

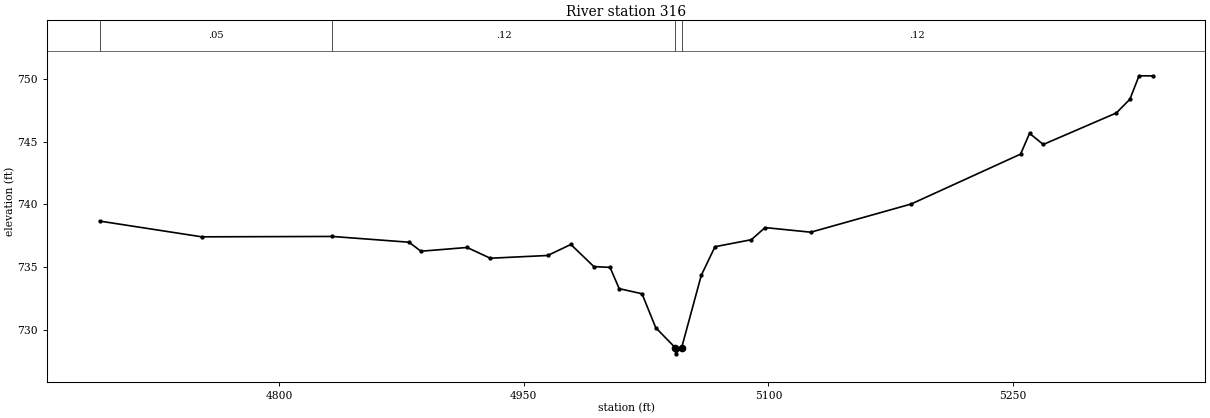
Type RM Length L Ch R = 1,316,0,0,0
BEGIN DESCRIPTION:
MDE S 104 1.0
END DESCRIPTION:
XS GIS Cut Line= 3
      2304817.03      7144733.78      2305029.00      7144960.00
      2305328.99      7144810.01
#Sta/Elev= 30
  4690.1  738.67  4752.7  737.41  4832.7  737.44  4879.7  736.98  4887.0  736.26
  4915.3  736.56  4929.5  735.70  4964.7  735.92  4978.9  736.80  4993.0  735.03
  5002.9  734.97  5008.5  733.27  5022.5  732.86  5030.9  730.15  5042.8  728.56
  5043.1  728.06  5046.8  728.56  5058.8  734.33  5067.2  736.62  5089.5  737.18
  5097.9  738.15  5125.9  737.78  5187.4  740.03  5254.5  744.02  5260.0  745.68
  5268.4  744.79  5313.2  747.31  5321.5  748.41  5327.1  750.28  5335.5  750.27
#Mann=4,-1,0
  4690.1    0.05       0  4832.7    0.12       0  5042.8    0.07       0
  5046.8    0.12       0
Bank Sta=5042.8,5046.8
Exp/Cntr=0.3,0.1

Chan Stop Cuts=-1