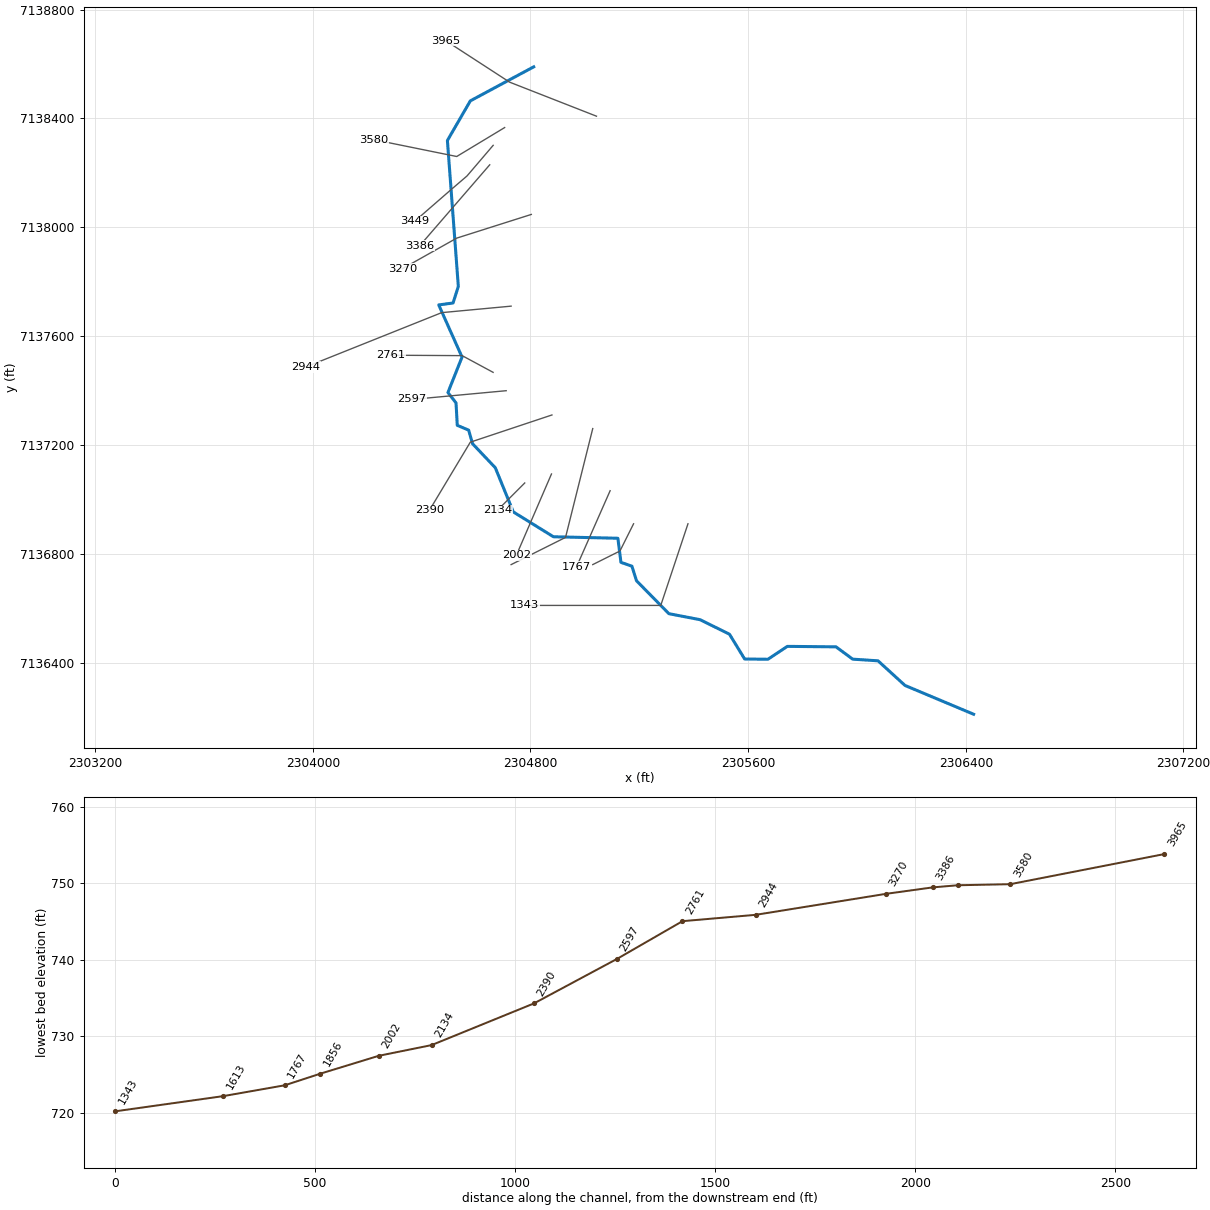
--- MDE S 105.prj (project) ---

Proj Title=MDE S 105 Base Level Engineering
Current Plan=p01
Default Exp/Contr=0.3,0.1
English Units
Geom File=g01
Flow File=f01
Plan File=p01
BEGIN DESCRIPTION:
MDE S 105
END DESCRIPTION:

--- MDE S 105.p01 (plan) ---

Plan Title=Multiple Run
Short Identifier=Multiple
Geom File=g01
Flow File=f01
Subcritical Flow
K Sum by GR= 0
Std Step Tol= 0.01
Critical Tol= 0.01
Num of Std Step Trials= 20
Max Error Tol= 0.3
Flow Tol Ratio= 0.001
Split Flow NTrial= 30
Split Flow Tol= 0.02
Split Flow Ratio= 0.02
Log Output Level= 0
Friction Slope Method= 1
Unsteady Friction Slope Method= 2
Unsteady Bridges Friction Slope Method= 1
Parabolic Critical Depth
Global Vel Dist=  1 , 1 , 1
Global Log Level= 0
CheckData=True
Encroach Param= -1, 0, 0, 0
BEGIN DESCRIPTION:
Multiple Run
END DESCRIPTION:

--- MDE S 105.f01 (steady flow) ---

Flow Title=Multiple
Number of Profiles=7
Profile Names=10-year,25-year,50-year,1pct_min,100-year,1pct_plu,500-year
River Rch & RM= MDE S 105,Reach-1,3965
     125     153     174      99     197     392     252
Boundary for River Rch & Prof#=MDE S 105,Reach-1,1
Up Type=0
Dn Type=3
Dn Slope=0.005
Boundary for River Rch & Prof#=MDE S 105,Reach-1,2
Up Type=0
Dn Type=3
Dn Slope=0.005
Boundary for River Rch & Prof#=MDE S 105,Reach-1,3
Up Type=0
Dn Type=3
Dn Slope=0.005
Boundary for River Rch & Prof#=MDE S 105,Reach-1,4
Up Type=0
Dn Type=3
Dn Slope=0.005
Boundary for River Rch & Prof#=MDE S 105,Reach-1,5
Up Type=0
Dn Type=3
Dn Slope=0.005
Boundary for River Rch & Prof#=MDE S 105,Reach-1,6
Up Type=0
Dn Type=3
Dn Slope=0.005
Boundary for River Rch & Prof#=MDE S 105,Reach-1,7
Up Type=0
Dn Type=3
Dn Slope=0.005

--- MDE S 105.g01 (geometry) ---

Geom Title=Existing Conditions

River Reach=MDE S 105,Reach-1
Reach XY= 30
      2304812.11      7138589.62      2304579.07      7138464.51
      2304494.79      7138318.72      2304534.95      7137782.36
      2304515.58      7137721.56      2304462.92      7137714.51
      2304548.58      7137522.78      2304496.78      7137392.46
      2304526.50      7137354.35      2304531.03      7137271.99
      2304572.95      7137254.20      2304587.25      7137204.23
      2304670.84      7137116.05      2304737.02      7136953.66
      2304884.52      7136862.35      2305121.30      7136856.85
      2305132.70      7136768.28      2305172.95      7136754.21
      2305189.85      7136700.57      2305308.84      7136579.63
      2305423.44      7136557.55      2305531.53      7136504.23
      2305587.35      7136413.00      2305672.94      7136412.13
      2305744.21      7136459.48      2305923.06      7136457.74
      2305984.57      7136412.47      2306077.50      7136406.38
      2306176.71      7136315.85      2306429.00      7136210.00

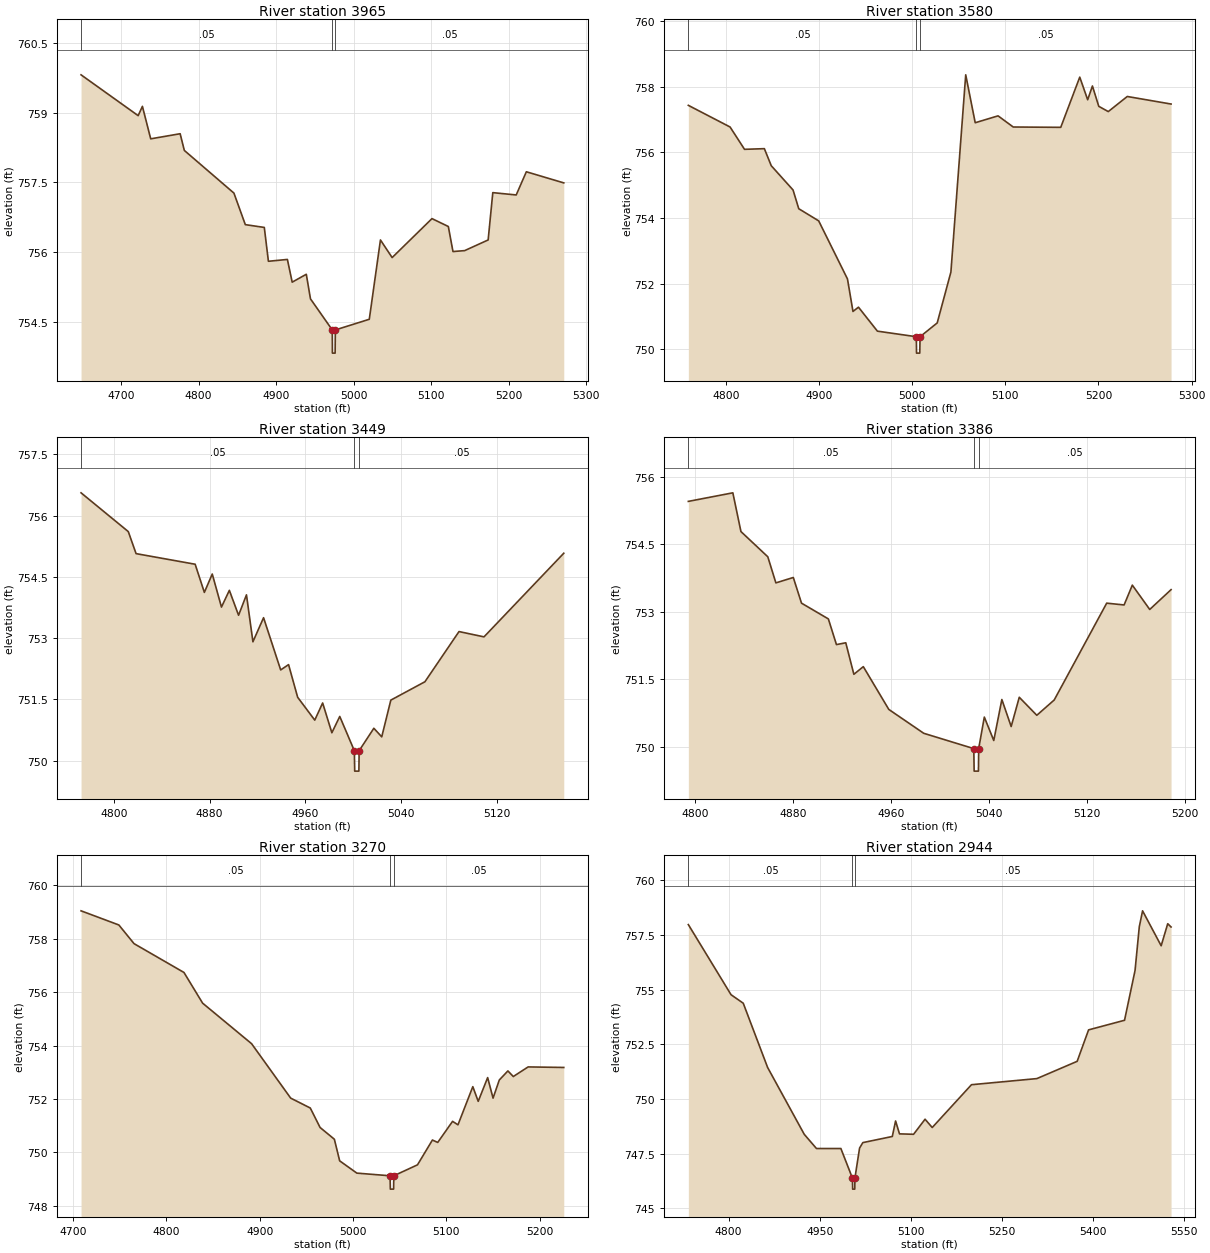
Type RM Length L Ch R = 1,3965,385,385,385
BEGIN DESCRIPTION:
MDE S 105 14.0
END DESCRIPTION:
XS GIS Cut Line= 3
      2305042.71      7138408.16      2304723.51      7138533.22
      2304488.52      7138685.80
#Sta/Elev= 30
  4648.3  759.82  4722.0  758.94  4727.5  759.14  4738.2  758.44  4776.2  758.55
  4781.6  758.19  4845.6  757.27  4860.3  756.59  4884.8  756.53  4890.1  755.80
  4914.6  755.84  4920.8  755.35  4939.0  755.52  4944.4  754.99  4972.5  754.32
  4972.7  753.82  4976.2  753.82  4976.5  754.32  5020.3  754.55  5034.7  756.26
  5049.8  755.88  5101.2  756.72  5122.3  756.55  5128.3  756.01  5143.4  756.03
  5173.7  756.26  5179.7  757.28  5209.9  757.23  5223.0  757.73  5271.3  757.49
#Mann=3,-1,0
  4648.3    0.05       0  4972.5   0.033       0  4976.5    0.05       0
Bank Sta=4972.5,4976.5
Exp/Cntr=0.3,0.1

Type RM Length L Ch R = 1,3580,131,131,131
BEGIN DESCRIPTION:
MDE S 105 13.0
END DESCRIPTION:
XS GIS Cut Line= 3
      2304705.23      7138366.36      2304529.00      7138260.00
      2304222.99      7138322.15
#Sta/Elev= 30
  4759.8  757.43  4804.6  756.77  4820.1  756.09  4841.4  756.11  4848.8  755.59
  4872.2  754.85  4878.3  754.28  4899.7  753.91  4930.6  752.14  4936.5  751.15
  4942.4  751.28  4962.7  750.55  5004.5  750.38  5004.7  749.88  5008.2  749.88
  5008.5  750.38  5026.9  750.80  5041.6  752.35  5057.5  758.36  5067.7  756.90
  5092.2  757.11  5108.5  756.77  5159.5  756.76  5179.9  758.29  5188.4  757.60
  5193.5  758.02  5200.3  757.40  5210.5  757.24  5230.9  757.70  5277.9  757.47
#Mann=3,-1,0
  4759.8    0.05       0  5004.5   0.033       0  5008.5    0.05       0
Bank Sta=5004.5,5008.5
Exp/Cntr=0.3,0.1

Type RM Length L Ch R = 1,3449,63,63,63
BEGIN DESCRIPTION:
Mapping XS 678e28ea
END DESCRIPTION:
XS GIS Cut Line= 4
      2304663.02      7138301.04      2304566.98      7138188.59
      2304506.86      7138137.00      2304373.66      7138021.20
#Sta/Elev= 30
  4772.5  756.56  4812.0  755.61  4818.5  755.07  4867.9  754.81  4875.6  754.12
  4882.2  754.57  4889.9  753.76  4896.5  754.17  4904.2  753.56  4910.8  754.06
  4916.2  752.91  4925.1  753.50  4939.4  752.22  4946.0  752.35  4953.6  751.55
  4967.9  750.99  4974.5  751.41  4982.2  750.68  4988.8  751.08  5001.0  750.24
  5001.3  749.74  5004.8  749.74  5005.0  750.24  5017.3  750.79  5023.9  750.58
  5031.5  751.48  5060.0  751.93  5088.5  753.16  5109.4  753.03  5176.1  755.08
#Mann=3,-1,0
  4772.5    0.05       0  5001.0   0.033       0  5005.0    0.05       0
Bank Sta=5001,5005
Exp/Cntr=0.3,0.1

Type RM Length L Ch R = 1,3386,116,116,116
BEGIN DESCRIPTION:
Mapping XS 27fd366c
END DESCRIPTION:
XS GIS Cut Line= 2
      2304650.31      7138229.45      2304392.80      7137931.65
#Sta/Elev= 30
  4794.8  755.45  4831.1  755.64  4837.7  754.78  4859.6  754.22  4866.2  753.64
  4880.4  753.76  4887.1  753.19  4909.0  752.84  4915.6  752.27  4923.2  752.31
  4929.8  751.61  4937.5  751.78  4958.3  750.83  4986.8  750.30  5027.6  749.96
  5027.9  749.46  5031.4  749.46  5031.6  749.96  5036.2  750.66  5043.9  750.14
  5050.5  751.05  5058.1  750.45  5064.7  751.10  5079.0  750.70  5093.2  751.04
  5136.0  753.19  5150.2  753.15  5156.9  753.59  5171.1  753.05  5188.5  753.49
#Mann=3,-1,0
  4794.8    0.05       0  5027.6   0.033       0  5031.6    0.05       0
Bank Sta=5027.6,5031.6
Exp/Cntr=0.3,0.1

Type RM Length L Ch R = 1,3270,326,326,326
BEGIN DESCRIPTION:
MDE S 105 12.0
END DESCRIPTION:
XS GIS Cut Line= 3
      2304803.18      7138047.07      2304529.00      7137960.00
      2304328.80      7137847.33
#Sta/Elev= 30
  4708.5  759.05  4749.0  758.52  4765.3  757.82  4818.8  756.74  4838.8  755.59
  4891.3  754.07  4933.2  752.03  4954.2  751.66  4964.7  750.93  4980.0  750.49
  4985.7  749.68  5004.1  749.22  5039.7  749.12  5040.0  748.62  5043.5  748.62
  5043.7  749.12  5069.1  749.53  5085.1  750.46  5090.8  750.37  5106.7  751.16
  5112.5  751.03  5128.4  752.46  5134.2  751.91  5144.3  752.80  5150.1  752.03
  5156.8  752.71  5166.0  753.05  5171.8  752.84  5187.7  753.20  5225.9  753.18
#Mann=3,-1,0
  4708.5    0.05       0  5039.7   0.033       0  5043.7    0.05       0
Bank Sta=5039.7,5043.7
Exp/Cntr=0.3,0.1

Type RM Length L Ch R = 1,2944,183,183,183
BEGIN DESCRIPTION:
MDE S 105 11.0
END DESCRIPTION:
XS GIS Cut Line= 3
      2304728.98      7137710.00      2304473.79      7137686.14
      2303973.90      7137486.18
#Sta/Elev= 30
  4733.8  757.98  4804.1  754.77  4824.2  754.38  4864.3  751.44  4924.6  748.38
  4944.7  747.73  4984.9  747.73  5004.0  746.37  5004.3  745.87  5007.8  745.87
  5008.0  746.37  5015.7  747.75  5021.1  748.00  5069.6  748.28  5075.0  748.99
  5081.4  748.40  5104.6  748.38  5123.5  749.07  5135.3  748.69  5199.9  750.65
  5307.6  750.93  5373.9  751.72  5392.7  753.16  5451.9  753.60  5469.2  755.88
  5476.2  757.88  5481.6  758.61  5512.2  757.01  5523.0  758.02  5528.5  757.87
#Mann=3,-1,0
  4733.8    0.05       0  5004.0   0.033       0  5008.0    0.05       0
Bank Sta=5004,5008
Exp/Cntr=0.3,0.1

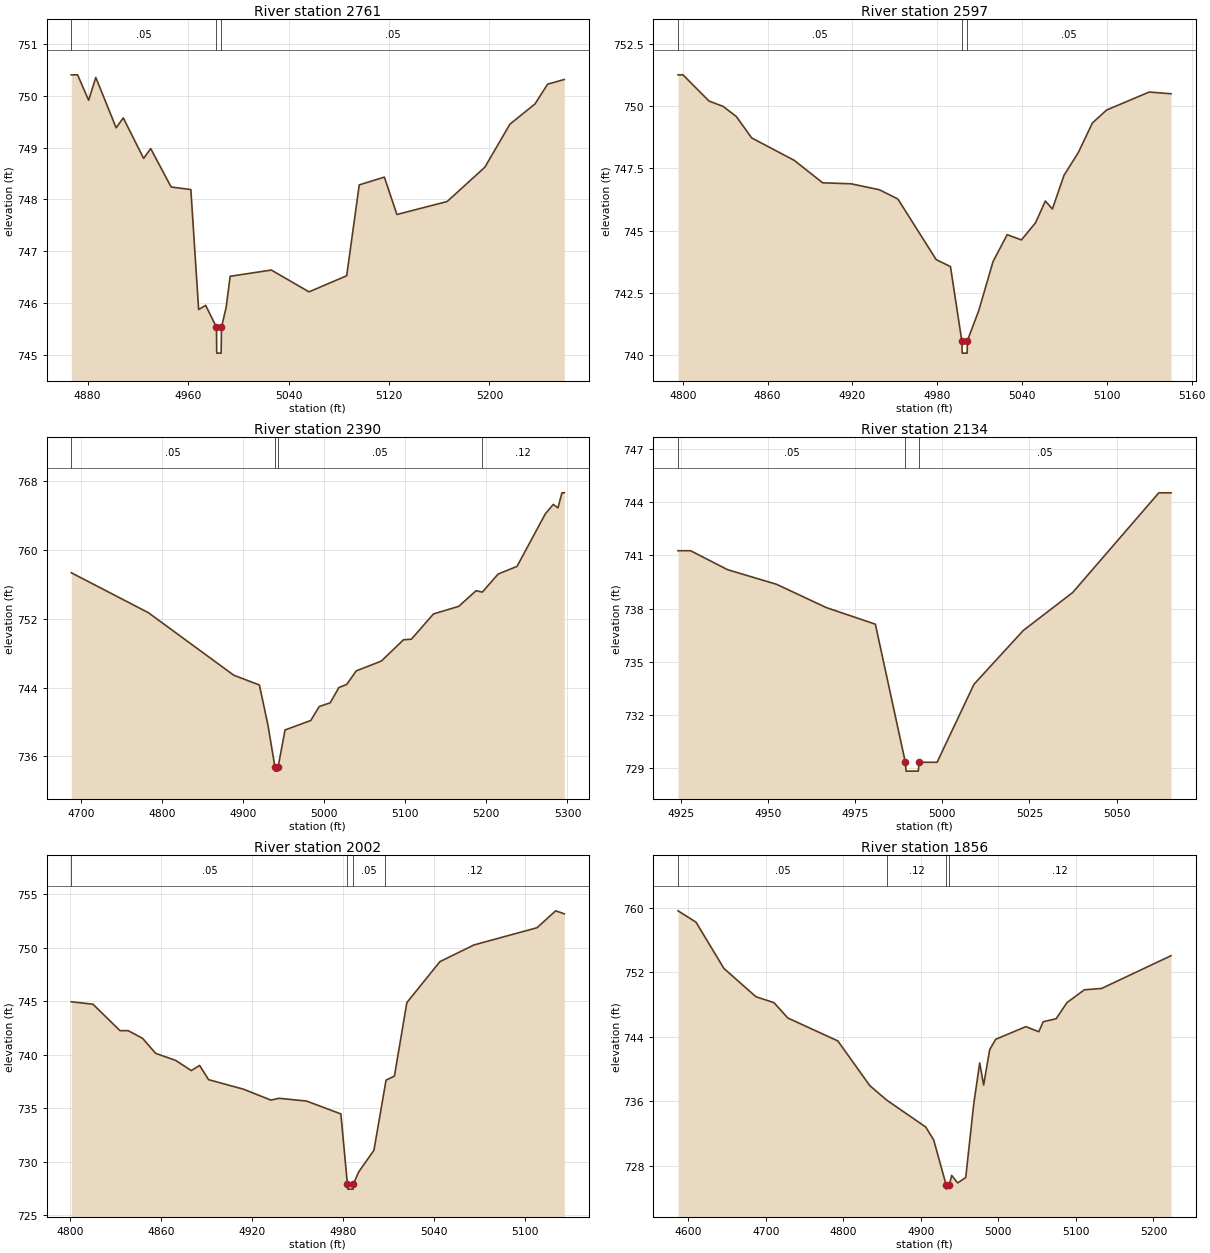
Type RM Length L Ch R = 1,2761,164,164,164
BEGIN DESCRIPTION:
Mapping XS f4eaa413
END DESCRIPTION:
XS GIS Cut Line= 3
      2304662.80      7137466.67      2304548.91      7137528.09
      2304285.71      7137529.58
#Sta/Elev= 30
  4867.0  750.40  4872.0  750.40  4880.8  749.91  4886.5  750.35  4902.7  749.38
  4908.4  749.57  4924.6  748.79  4930.2  748.98  4946.5  748.24  4962.2  748.19
  4968.4  745.88  4974.0  745.96  4982.6  745.54  4982.8  745.04  4986.3  745.04
  4986.6  745.54  4990.3  745.92  4993.5  746.52  5026.3  746.64  5056.3  746.22
  5086.3  746.53  5096.3  748.28  5116.3  748.43  5126.3  747.71  5166.3  747.96
  5196.3  748.62  5216.3  749.45  5236.3  749.84  5246.3  750.22  5259.6  750.31
#Mann=3,-1,0
  4867.0    0.05       0  4982.6   0.033       0  4986.6    0.05       0
Bank Sta=4982.6,4986.6
Exp/Cntr=0.3,0.1

Type RM Length L Ch R = 1,2597,207,207,207
BEGIN DESCRIPTION:
Mapping XS 49001130
END DESCRIPTION:
XS GIS Cut Line= 2
      2304710.85      7137399.21      2304363.65      7137366.94
#Sta/Elev= 30
  4796.7  751.25  4800.2  751.25  4818.6  750.20  4828.7  749.98  4837.9  749.58
  4848.8  748.72  4878.9  747.82  4899.0  746.92  4919.1  746.88  4939.2  746.64
  4952.2  746.27  4979.3  743.84  4989.4  743.56  4997.4  740.59  4997.7  740.09
  5001.2  740.09  5001.4  740.59  5009.5  741.81  5019.5  743.76  5029.5  744.84
  5039.6  744.63  5049.6  745.32  5056.5  746.19  5061.5  745.87  5069.7  747.22
  5079.8  748.13  5089.8  749.32  5099.9  749.84  5130.0  750.56  5145.4  750.49
#Mann=3,-1,0
  4796.7    0.05       0  4997.4   0.033       0  5001.4    0.05       0
Bank Sta=4997.4,5001.4
Exp/Cntr=0.3,0.1

Type RM Length L Ch R = 1,2390,256,256,256
BEGIN DESCRIPTION:
MDE S 105 9.0
END DESCRIPTION:
XS GIS Cut Line= 3
      2304879.02      7137310.01      2304579.00      7137210.00
      2304429.00      7136960.00
#Sta/Elev= 30
  4688.3  757.36  4783.2  752.72  4888.6  745.44  4920.2  744.30  4930.8  739.61
  4939.3  734.78  4939.6  734.28  4943.1  734.28  4943.3  734.78  4951.8  739.07
  4983.5  740.17  4994.0  741.80  5007.5  742.23  5018.2  744.01  5027.9  744.37
  5039.5  745.94  5070.6  747.09  5097.8  749.56  5107.6  749.63  5134.8  752.57
  5165.9  753.45  5187.3  755.27  5195.1  755.11  5214.5  757.21  5237.8  758.10
  5272.8  764.23  5282.5  765.31  5288.3  764.91  5293.2  766.66  5296.1  766.66
#Mann=4,-1,0
  4688.3    0.05       0  4939.3   0.033       0  4943.3    0.05       0
  5195.1    0.12       0
Bank Sta=4939.3,4943.3
Exp/Cntr=0.3,0.1

Type RM Length L Ch R = 1,2134,132,132,132
BEGIN DESCRIPTION:
MDE S 105 8.0
END DESCRIPTION:
XS GIS Cut Line= 3
      2304779.02      7137060.02      2304729.00      7137010.00
      2304679.03      7136960.03
#Sta/Elev= 16
  4924.2  741.27  4927.8  741.27  4938.4  740.20  4952.5  739.37  4966.7  738.06
  4980.8  737.12  4989.4  729.32  4989.6  728.82  4993.1  728.82  4993.4  729.32
  4998.5  729.32  5009.1  733.73  5023.2  736.76  5037.4  738.91  5062.1  744.54
  5065.6  744.54
#Mann=3,-1,0
  4924.2    0.05       0  4989.4   0.033       0  4993.4    0.05       0
Bank Sta=4989.4,4993.4
Exp/Cntr=0.3,0.1

Type RM Length L Ch R = 1,2002,146,146,146
BEGIN DESCRIPTION:
Mapping XS 2e8f1a50
END DESCRIPTION:
XS GIS Cut Line= 2
      2304877.30      7137093.13      2304748.49      7136794.75
#Sta/Elev= 30
  4800.9  744.93  4815.2  744.70  4833.0  742.23  4838.4  742.23  4847.9  741.51
  4856.5  740.11  4869.7  739.45  4880.0  738.50  4885.5  738.98  4891.4  737.65
  4914.4  736.76  4932.5  735.74  4937.9  735.91  4956.0  735.65  4978.6  734.45
  4982.9  727.92  4983.2  727.42  4986.7  727.42  4986.9  727.92  4990.4  729.04
  5000.4  731.05  5007.8  737.12  5008.4  737.61  5013.9  737.98  5022.1  744.85
  5043.9  748.68  5066.3  750.24  5107.9  751.85  5120.2  753.43  5125.9  753.15
#Mann=4,-1,0
  4800.9    0.05       0  4982.9   0.033       0  4986.9    0.05       0
  5007.8    0.12       0
Bank Sta=4982.9,4986.9
Exp/Cntr=0.3,0.1

Type RM Length L Ch R = 1,1856,89,89,89
BEGIN DESCRIPTION:
MDE S 105 7.0
END DESCRIPTION:
XS GIS Cut Line= 3
      2305028.99      7137259.97      2304929.00      7136860.00
      2304728.99      7136759.99
#Sta/Elev= 30
  4586.8  759.61  4610.0  758.20  4646.0  752.46  4687.3  748.95  4710.5  748.22
  4728.5  746.31  4792.9  743.47  4834.2  737.92  4855.9  736.13  4906.3  732.79
  4916.6  731.17  4932.7  725.58  4932.9  725.08  4936.7  725.58  4939.8  726.78
  4947.5  725.85  4957.9  726.52  4968.2  735.62  4975.9  740.74  4981.0  738.00
  4988.8  742.38  4996.5  743.67  5035.4  745.24  5052.2  744.61  5057.8  745.85
  5074.5  746.22  5088.5  748.22  5110.9  749.81  5133.2  749.98  5222.7  754.04
#Mann=4,-1,0
  4586.8    0.05       0  4855.9    0.12       0  4932.7    0.07       0
  4936.7    0.12       0
Bank Sta=4932.7,4936.7
Exp/Cntr=0.3,0.1

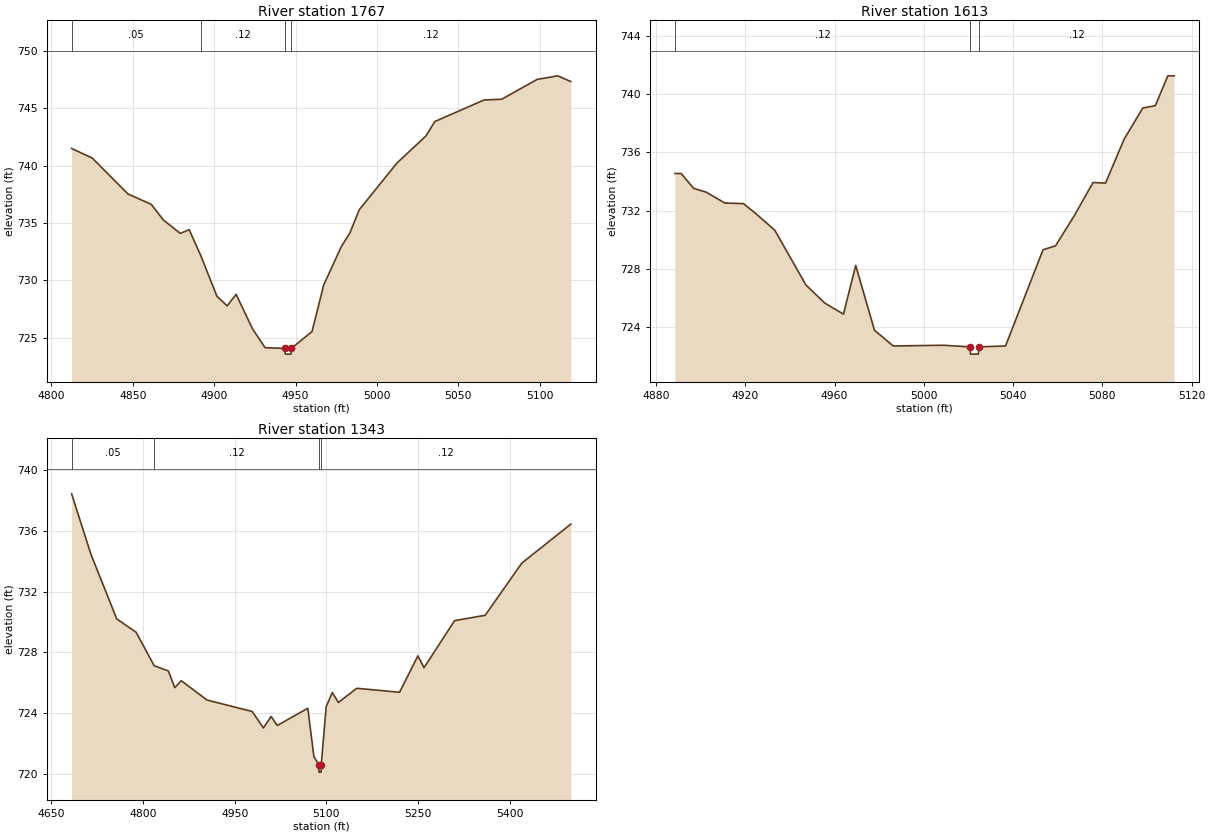
Type RM Length L Ch R = 1,1767,154,154,154
BEGIN DESCRIPTION:
Mapping XS f5cc69ff
END DESCRIPTION:
XS GIS Cut Line= 2
      2305092.89      7137031.62      2304969.19      7136751.19
#Sta/Elev= 30
  4812.5  741.51  4825.2  740.67  4847.1  737.54  4861.4  736.63  4868.9  735.26
  4879.2  734.10  4884.7  734.42  4891.8  732.16  4901.7  728.62  4908.0  727.77
  4913.5  728.78  4923.6  725.76  4931.3  724.12  4943.4  724.06  4943.7  723.56
  4947.2  723.56  4947.4  724.06  4960.1  725.53  4967.3  729.60  4978.0  732.92
  4983.4  734.15  4989.1  736.16  5012.2  740.23  5030.1  742.61  5035.5  743.86
  5065.7  745.74  5076.6  745.81  5098.4  747.54  5111.0  747.85  5119.0  747.35
#Mann=4,-1,0
  4812.5    0.05       0  4891.8    0.12       0  4943.4    0.07       0
  4947.4    0.12       0
Bank Sta=4943.4,4947.4
Exp/Cntr=0.3,0.1

Type RM Length L Ch R = 1,1613,270,270,270
BEGIN DESCRIPTION:
MDE S 105 6.0
END DESCRIPTION:
XS GIS Cut Line= 3
      2305179.00      7136909.99      2305129.00      7136810.00
      2305029.00      7136760.00
#Sta/Elev= 30
  4888.5  734.55  4891.3  734.55  4896.9  733.53  4902.5  733.27  4910.9  732.52
  4919.2  732.48  4924.8  731.79  4933.2  730.66  4947.2  726.89  4955.6  725.65
  4964.0  724.89  4969.5  728.23  4977.9  723.78  4986.3  722.70  5008.7  722.75
  5020.7  722.64  5020.9  722.14  5024.4  722.14  5024.7  722.64  5036.6  722.70
  5053.4  729.31  5059.0  729.58  5067.4  731.65  5075.8  733.93  5081.4  733.89
  5089.7  736.90  5098.1  739.05  5103.7  739.21  5109.3  741.26  5112.1  741.26
#Mann=3,-1,0
  4888.5    0.12       0  5020.7    0.07       0  5024.7    0.12       0
Bank Sta=5020.7,5024.7
Exp/Cntr=0.3,0.1

Type RM Length L Ch R = 1,1343,0,0,0
BEGIN DESCRIPTION:
MDE S 105 5.0
END DESCRIPTION:
XS GIS Cut Line= 3
      2305379.00      7136910.00      2305279.00      7136610.00
      2304779.03      7136610.00
#Sta/Elev= 30
  4683.4  738.41  4715.0  734.44  4757.2  730.20  4788.8  729.33  4818.4  727.13
  4841.5  726.79  4852.1  725.69  4862.6  726.15  4904.8  724.88  4978.6  724.13
  4997.0  723.05  5009.6  723.80  5019.6  723.21  5069.6  724.34  5079.6  721.15
  5087.6  720.65  5087.9  720.15  5091.4  720.15  5091.6  720.65  5099.6  724.44
  5109.6  725.37  5119.6  724.72  5149.6  725.65  5219.6  725.39  5249.6  727.78
  5259.6  727.00  5309.6  730.09  5359.6  730.44  5419.6  733.87  5499.6  736.42
#Mann=4,-1,0
  4683.4    0.05       0  4818.4    0.12       0  5087.6    0.07       0
  5091.6    0.12       0
Bank Sta=5087.6,5091.6
Exp/Cntr=0.3,0.1

Chan Stop Cuts=-1