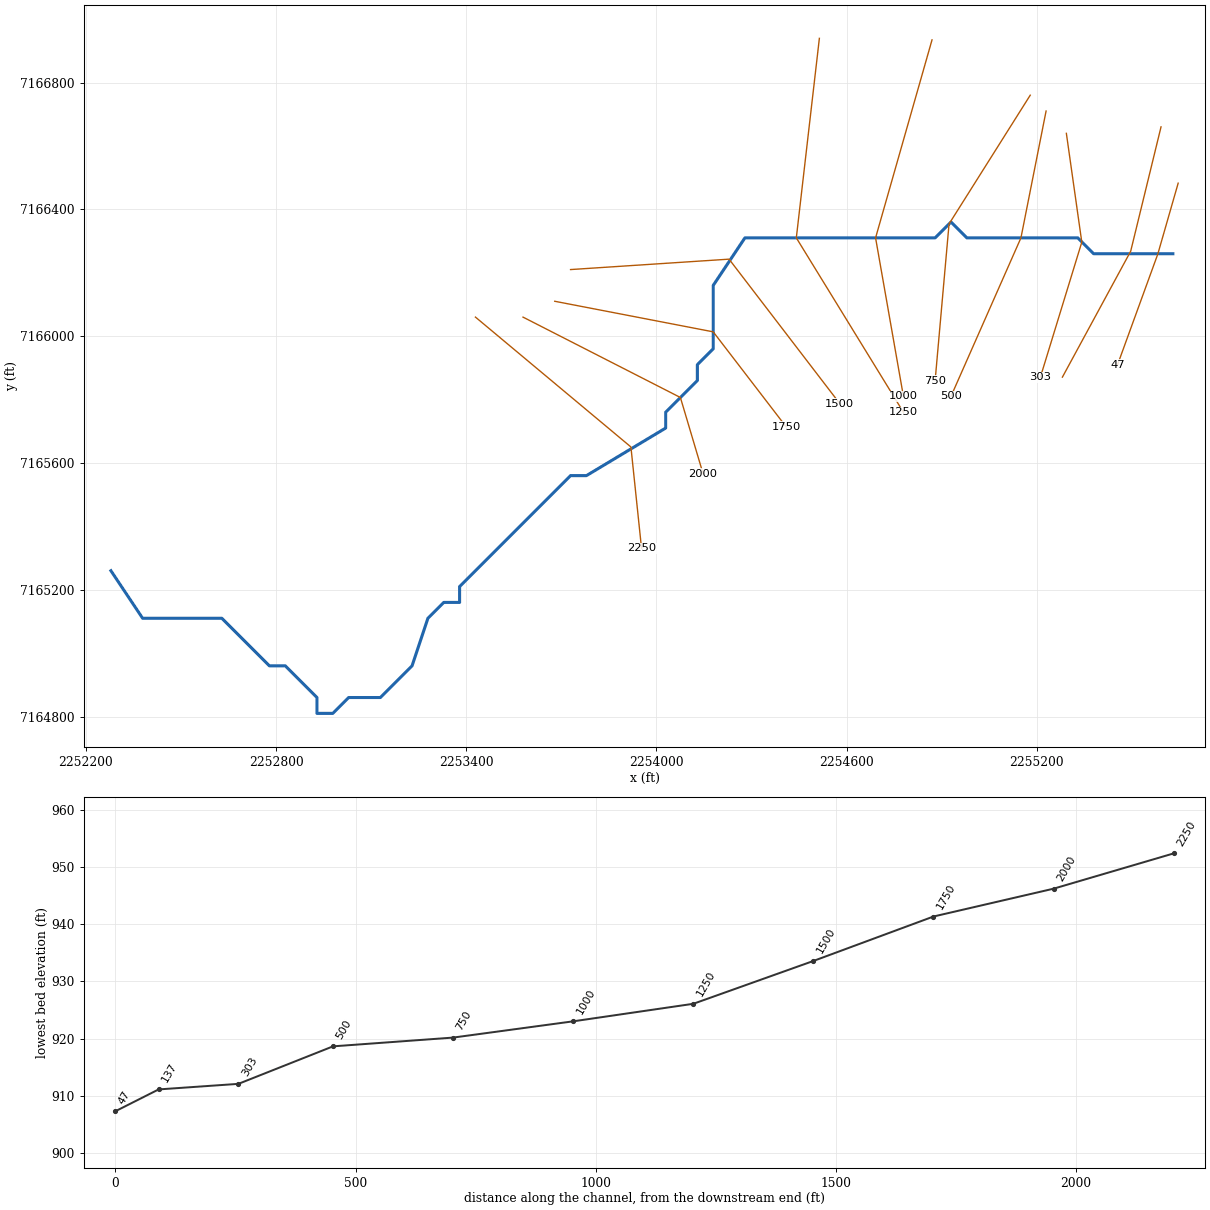
--- MDE S 11.prj (project) ---

Proj Title=MDE S 11 Base Level Engineering
Current Plan=p01
Default Exp/Contr=0.3,0.1
English Units
Geom File=g01
Flow File=f01
Plan File=p01
BEGIN DESCRIPTION:
MDE S 11
END DESCRIPTION:

--- MDE S 11.p01 (plan) ---

Plan Title=Multiple Run
Short Identifier=Multiple
Geom File=g01
Flow File=f01
Subcritical Flow
K Sum by GR= 0
Std Step Tol= 0.01
Critical Tol= 0.01
Num of Std Step Trials= 20
Max Error Tol= 0.3
Flow Tol Ratio= 0.001
Split Flow NTrial= 30
Split Flow Tol= 0.02
Split Flow Ratio= 0.02
Log Output Level= 0
Friction Slope Method= 1
Unsteady Friction Slope Method= 2
Unsteady Bridges Friction Slope Method= 1
Parabolic Critical Depth
Global Vel Dist=  1 , 1 , 1
Global Log Level= 0
CheckData=True
Encroach Param= -1, 0, 0, 0
BEGIN DESCRIPTION:
Multiple Run
END DESCRIPTION:

--- MDE S 11.f01 (steady flow) ---

Flow Title=Multiple
Number of Profiles=7
Profile Names=10-year,25-year,50-year,1pct_min,100-year,1pct_plu,500-year
River Rch & RM= MDE S 11,Reach-1,2250
     207     268     315     186     371     740     512
River Rch & RM= MDE S 11,Reach-1,1500
     225     292     345     204     407     812     564
River Rch & RM= MDE S 11,Reach-1,500
     418     568     692     421     840    1675    1234
River Rch & RM= MDE S 11,Reach-1,47
     529     730     897     549    1096    2187    1638
Boundary for River Rch & Prof#=MDE S 11,Reach-1,1
Up Type=0
Dn Type=3
Dn Slope=0.007
Boundary for River Rch & Prof#=MDE S 11,Reach-1,2
Up Type=0
Dn Type=3
Dn Slope=0.007
Boundary for River Rch & Prof#=MDE S 11,Reach-1,3
Up Type=0
Dn Type=3
Dn Slope=0.007
Boundary for River Rch & Prof#=MDE S 11,Reach-1,4
Up Type=0
Dn Type=3
Dn Slope=0.007
Boundary for River Rch & Prof#=MDE S 11,Reach-1,5
Up Type=0
Dn Type=3
Dn Slope=0.007
Boundary for River Rch & Prof#=MDE S 11,Reach-1,6
Up Type=0
Dn Type=3
Dn Slope=0.007
Boundary for River Rch & Prof#=MDE S 11,Reach-1,7
Up Type=0
Dn Type=3
Dn Slope=0.007

--- MDE S 11.g01 (geometry) ---

Geom Title=Existing Conditions

River Reach=MDE S 11,Reach-1
Reach XY= 30
      2252279.00      7165260.00      2252379.00      7165110.00
      2252629.00      7165110.00      2252779.00      7164960.00
      2252829.00      7164960.00      2252929.00      7164860.00
      2252929.00      7164810.00      2252979.00      7164810.00
      2253029.00      7164860.00      2253129.00      7164860.00
      2253229.00      7164960.00      2253279.00      7165110.00
      2253329.00      7165160.00      2253379.00      7165160.00
      2253379.00      7165210.00      2253729.00      7165560.00
      2253779.00      7165560.00      2254029.00      7165710.00
      2254029.00      7165760.00      2254129.00      7165860.00
      2254129.00      7165910.00      2254179.00      7165960.00
      2254179.00      7166160.00      2254279.00      7166310.00
      2254879.00      7166310.00      2254929.00      7166360.00
      2254979.00      7166310.00      2255329.00      7166310.00
      2255379.00      7166260.00      2255629.00      7166260.00

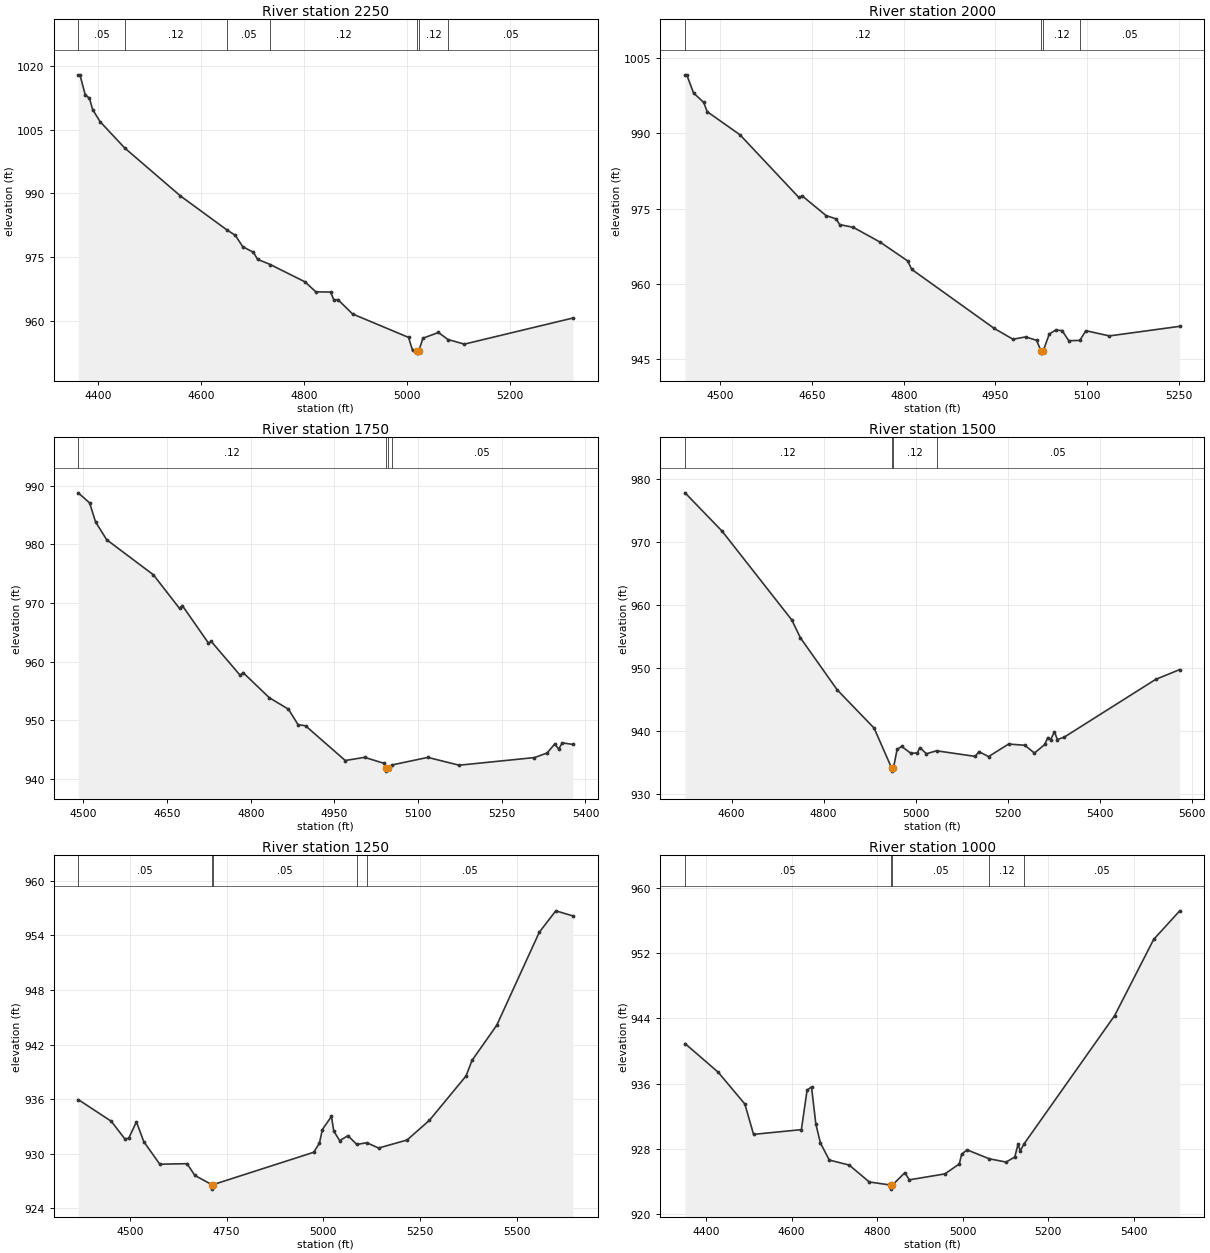
Type RM Length L Ch R = 1,2250,250,250,250
BEGIN DESCRIPTION:
MDE S 11 9.0
END DESCRIPTION:
XS GIS Cut Line= 3
      2253428.96      7166060.03      2253919.38      7165650.38
      2253952.90      7165330.13
#Sta/Elev= 30
  4361.0 1017.92  4364.3 1017.92  4374.7 1013.12  4382.5 1012.46  4389.0 1009.72
  4403.3 1006.90  4451.1 1000.70  4559.5  989.39  4649.1  981.44  4666.2  980.10
  4680.5  977.43  4701.4  976.10  4709.2  974.47  4734.0  973.23  4801.6  969.14
  4822.4  966.80  4851.0  966.75  4857.5  964.91  4865.3  964.97  4894.0  961.58
  5002.7  956.06  5010.4  952.99  5018.5  952.86  5018.7  952.36  5022.5  952.86
  5030.5  955.87  5060.7  957.22  5079.2  955.57  5111.0  954.48  5322.0  960.63
#Mann=7,-1,0
  4361.0    0.05       0  4451.1    0.12       0  4649.1    0.05       0
  4734.0    0.12       0  5018.5    0.07       0  5022.5    0.12       0
  5079.2    0.05       0
Bank Sta=5018.5,5022.5
Exp/Cntr=0.3,0.1

Type RM Length L Ch R = 1,2000,250,250,250
BEGIN DESCRIPTION:
MDE S 11 8.0
END DESCRIPTION:
XS GIS Cut Line= 3
      2253579.04      7166059.98      2254075.45      7165806.45
      2254147.08      7165565.68
#Sta/Elev= 30
  4442.6 1001.65  4445.4 1001.65  4456.5  998.03  4473.1  996.15  4478.7  994.32
  4532.4  989.70  4628.6  977.22  4634.2  977.52  4673.1  973.61  4689.6  972.94
  4695.3  971.81  4717.5  971.27  4762.0  968.28  4806.4  964.58  4813.1  962.89
  4947.8  951.14  4978.6  948.97  4999.2  949.43  5017.2  948.76  5024.2  946.70
  5024.4  946.20  5028.2  946.70  5038.0  950.01  5048.5  950.80  5058.9  950.69
  5069.8  948.68  5087.8  948.73  5097.8  950.67  5136.2  949.63  5251.2  951.54
#Mann=4,-1,0
  4442.6    0.12       0  5024.2    0.07       0  5028.2    0.12       0
  5087.8    0.05       0
Bank Sta=5024.2,5028.2
Exp/Cntr=0.3,0.1

Type RM Length L Ch R = 1,1750,250,250,250
BEGIN DESCRIPTION:
MDE S 11 7.0
END DESCRIPTION:
XS GIS Cut Line= 3
      2253679.02      7166110.00      2254179.00      7166013.55
      2254408.98      7165714.07
#Sta/Elev= 30
  4490.8  988.77  4511.2  987.04  4521.8  983.81  4541.7  980.78  4625.5  974.80
  4672.3  969.07  4677.4  969.55  4724.2  963.16  4729.2  963.44  4781.1  957.66
  4786.2  958.14  4833.0  953.87  4867.6  951.89  4884.8  949.26  4898.2  949.07
  4969.4  943.15  5004.1  943.69  5038.5  942.68  5042.8  941.84  5043.1  941.34
  5046.8  941.84  5052.5  942.38  5117.4  943.68  5173.5  942.35  5308.6  943.65
  5331.3  944.43  5344.9  945.96  5352.1  945.10  5358.4  946.16  5377.6  945.89
#Mann=4,-1,0
  4490.8    0.12       0  5042.8    0.07       0  5046.8    0.12       0
  5052.5    0.05       0
Bank Sta=5042.8,5046.8
Exp/Cntr=0.3,0.1

Type RM Length L Ch R = 1,1500,250,250,250
BEGIN DESCRIPTION:
MDE S 11 6.0
END DESCRIPTION:
XS GIS Cut Line= 3
      2253728.98      7166210.00      2254229.00      7166242.84
      2254578.31      7165787.11
#Sta/Elev= 30
  4498.9  977.78  4579.7  971.67  4731.1  957.57  4749.5  954.77  4829.6  946.49
  4909.8  940.42  4947.9  934.08  4948.1  933.58  4951.9  934.08  4959.9  937.05
  4969.9  937.50  4990.0  936.40  5004.1  936.48  5009.1  937.32  5023.6  936.34
  5045.5  936.81  5129.6  935.92  5137.8  936.68  5158.6  935.89  5202.2  937.88
  5237.5  937.69  5258.3  936.45  5280.8  937.81  5287.4  938.91  5293.7  938.60
  5301.9  939.83  5308.2  938.60  5322.7  938.96  5522.1  948.16  5574.2  949.71
#Mann=4,-1,0
  4498.9    0.12       0  4947.9    0.07       0  4951.9    0.12       0
  5045.5    0.05       0
Bank Sta=4947.9,4951.9
Exp/Cntr=0.3,0.1

Type RM Length L Ch R = 1,1250,250,250,250
BEGIN DESCRIPTION:
MDE S 11 5.0
END DESCRIPTION:
XS GIS Cut Line= 3
      2254513.86      7166939.41      2254441.13      7166310.00
      2254779.01      7165759.99
#Sta/Elev= 30
  4366.4  935.95  4451.8  933.56  4486.6  931.64  4496.7  931.69  4516.8  933.50
  4535.7  931.33  4577.2  928.84  4647.7  928.90  4667.8  927.61  4711.4  926.60
  4711.6  926.10  4715.4  926.60  4974.9  930.15  4989.9  931.14  4997.5  932.65
  5021.1  934.10  5027.0  932.49  5042.4  931.43  5063.7  931.98  5086.5  931.02
  5112.6  931.20  5143.0  930.62  5216.4  931.50  5274.4  933.67  5369.1  938.55
  5384.5  940.26  5448.4  944.12  5558.5  954.36  5601.1  956.71  5645.5  956.15
#Mann=5,-1,0
  4366.4    0.05       0  4711.4    0.04       0  4715.4    0.05       0
  5086.5    0.12       0  5112.6    0.05       0
Bank Sta=4711.4,4715.4
Exp/Cntr=0.3,0.1

Type RM Length L Ch R = 1,1000,250,250,250
BEGIN DESCRIPTION:
MDE S 11 4.0
END DESCRIPTION:
XS GIS Cut Line= 3
      2254869.21      7166934.51      2254691.13      7166310.00
      2254779.01      7165809.96
#Sta/Elev= 30
  4350.6  940.90  4428.1  937.39  4490.5  933.48  4510.8  929.76  4622.7  930.34
  4636.0  935.18  4646.4  935.59  4656.5  931.05  4667.2  928.70  4688.0  926.61
  4734.6  925.99  4781.6  923.92  4831.6  923.54  4831.9  923.04  4835.6  923.54
  4864.8  925.06  4875.1  924.18  4958.4  924.91  4992.2  926.14  4997.4  927.31
  5010.2  927.86  5061.8  926.77  5101.5  926.36  5121.8  926.98  5129.5  928.55
  5134.6  927.74  5143.4  928.58  5355.4  944.33  5446.7  953.68  5507.7  957.19
#Mann=5,-1,0
  4350.6    0.05       0  4831.6    0.04       0  4835.6    0.05       0
  5061.8    0.12       0  5143.4    0.05       0
Bank Sta=4831.6,4835.6
Exp/Cntr=0.3,0.1

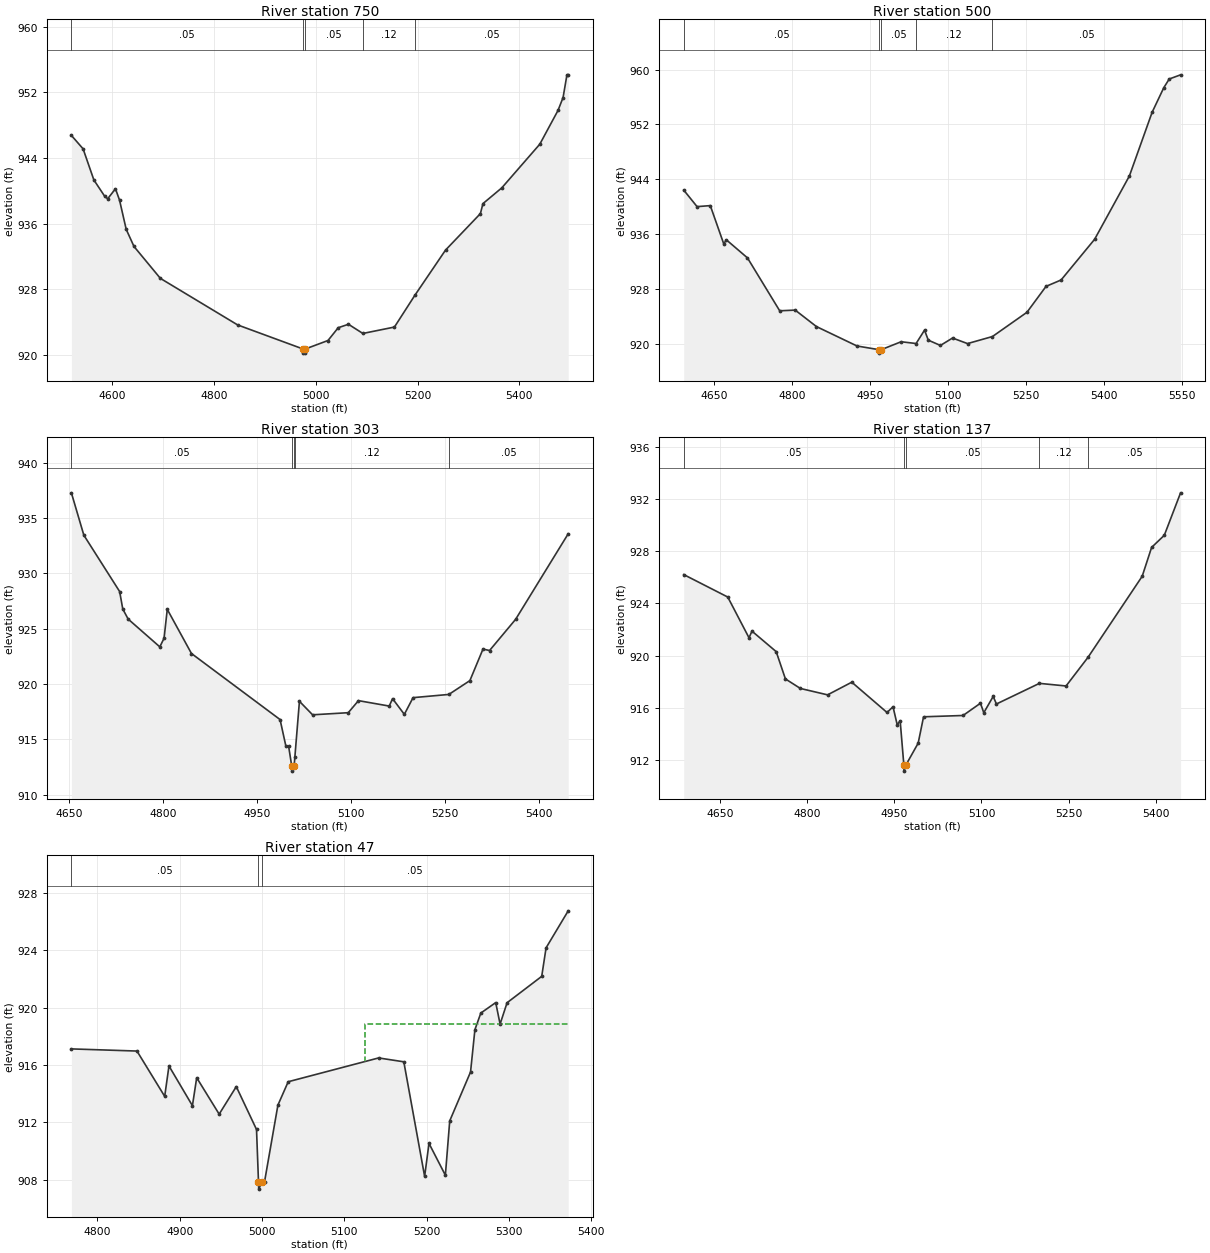
Type RM Length L Ch R = 1,750,250,250,250
BEGIN DESCRIPTION:
MDE S 11 3.0
END DESCRIPTION:
XS GIS Cut Line= 3
      2255179.02      7166760.03      2254922.93      7166353.93
      2254879.00      7165859.98
#Sta/Elev= 30
  4519.9  946.76  4542.9  945.12  4564.1  941.32  4585.3  939.34  4591.2  939.03
  4606.5  940.25  4614.5  938.86  4627.6  935.30  4642.9  933.21  4694.7  929.32
  4846.5  923.64  4975.2  920.70  4975.4  920.20  4978.9  920.20  4979.2  920.70
  5024.0  921.74  5044.1  923.30  5064.2  923.72  5092.5  922.60  5154.5  923.38
  5194.6  927.25  5254.9  932.77  5323.4  937.22  5328.4  938.44  5365.4  940.36
  5440.1  945.69  5475.8  949.80  5485.8  951.38  5493.4  954.15  5495.9  954.15
#Mann=5,-1,0
  4519.9    0.05       0  4975.2    0.04       0  4979.2    0.05       0
  5092.5    0.12       0  5194.6    0.05       0
Bank Sta=4975.2,4979.2
Exp/Cntr=0.3,0.1

Type RM Length L Ch R = 1,500,197,197,197
BEGIN DESCRIPTION:
MDE S 11 2.0
END DESCRIPTION:
XS GIS Cut Line= 3
      2255229.00      7166710.02      2255149.71      7166310.00
      2254929.02      7165810.04
#Sta/Elev= 30
  4592.2  942.43  4617.8  940.02  4643.2  940.17  4669.0  934.60  4674.1  935.18
  4714.6  932.55  4776.5  924.84  4806.3  924.94  4847.1  922.54  4925.0  919.71
  4967.4  919.17  4967.7  918.67  4971.4  919.17  5009.8  920.33  5038.5  920.07
  5054.7  922.02  5061.9  920.56  5085.2  919.79  5108.5  920.87  5137.3  920.06
  5185.2  921.09  5251.4  924.62  5288.1  928.40  5317.0  929.33  5381.4  935.26
  5448.2  944.49  5491.9  953.78  5514.3  957.36  5524.7  958.62  5546.5  959.23
#Mann=5,-1,0
  4592.2    0.05       0  4967.4    0.04       0  4971.4    0.05       0
  5038.5    0.12       0  5185.2    0.05       0
Bank Sta=4967.4,4971.4
Exp/Cntr=0.3,0.1

Type RM Length L Ch R = 1,303,166,166,166
BEGIN DESCRIPTION:
Mapping XS 8fde6479
END DESCRIPTION:
XS GIS Cut Line= 3
      2255292.98      7166639.74      2255341.68      7166296.45
      2255210.89      7165869.98
#Sta/Elev= 30
  4654.3  937.27  4674.2  933.44  4731.3  928.35  4736.3  926.77  4744.9  925.86
  4795.4  923.35  4802.2  924.13  4807.3  926.74  4845.9  922.75  4987.3  916.78
  4996.7  914.35  5001.0  914.35  5005.8  912.62  5006.0  912.12  5009.8  912.62
  5010.9  913.38  5018.2  918.43  5039.2  917.21  5096.1  917.40  5112.4  918.49
  5161.5  918.00  5166.8  918.67  5185.6  917.25  5199.5  918.76  5256.6  919.05
  5290.2  920.30  5311.1  923.15  5321.6  923.02  5363.2  925.84  5447.1  933.57
#Mann=5,-1,0
  4654.3    0.05       0  5005.8    0.04       0  5009.8    0.05       0
  5010.9    0.12       0  5256.6    0.05       0
Bank Sta=5005.8,5009.8
Exp/Cntr=0.3,0.1

Type RM Length L Ch R = 1,137,90,90,90
BEGIN DESCRIPTION:
Mapping XS 0e0760c5
END DESCRIPTION:
XS GIS Cut Line= 3
      2255591.64      7166660.09      2255495.92      7166267.93
      2255280.49      7165870.66
#Sta/Elev= 30
  4587.3  926.20  4663.1  924.48  4699.7  921.36  4704.8  921.87  4746.5  920.30
  4762.4  918.21  4788.2  917.48  4835.0  916.99  4876.7  917.96  4937.4  915.64
  4947.7  916.08  4954.9  914.70  4960.0  915.01  4966.3  911.65  4966.5  911.15
  4970.3  911.65  4991.0  913.29  5000.3  915.31  5068.3  915.41  5098.3  916.35
  5104.0  915.62  5120.2  916.87  5125.8  916.29  5199.8  917.87  5245.7  917.67
  5283.6  919.87  5376.8  926.07  5393.0  928.28  5414.9  929.21  5442.9  932.46
#Mann=5,-1,0
  4587.3    0.05       0  4966.3    0.04       0  4970.3    0.05       0
  5199.8    0.12       0  5283.6    0.05       0
Bank Sta=4966.3,4970.3
Exp/Cntr=0.3,0.1

Type RM Length L Ch R = 1,47,0,0,0
BEGIN DESCRIPTION:
MDE S 11 1.0
END DESCRIPTION:
XS GIS Cut Line= 3
      2255645.70      7166482.60      2255581.54      7166259.19
      2255454.62      7165910.20
#Sta/Elev= 30
  4768.4  917.12  4848.1  916.97  4881.8  913.81  4887.0  915.93  4915.5  913.16
  4920.7  915.11  4948.0  912.57  4968.8  914.49  4993.4  911.50  4995.8  907.84
  4996.1  907.34  4999.8  907.84  5003.1  907.84  5019.4  913.20  5031.9  914.83
  5141.8  916.49  5172.4  916.22  5197.7  908.23  5203.0  910.53  5222.9  908.31
  5228.2  912.10  5253.5  915.51  5258.8  918.46  5266.0  919.62  5284.1  920.35
  5289.4  918.85  5297.9  920.34  5340.0  922.18  5345.3  924.17  5372.2  926.75
#Mann=3,-1,0
  4768.4    0.05       0  4995.8    0.04       0  4999.8    0.05       0
#XS Ineff=2,0
       0                 5124.80    0.00  918.86
Permanent Ineff=
       F       F
Bank Sta=4995.8,4999.8
Exp/Cntr=0.3,0.1

Chan Stop Cuts=-1