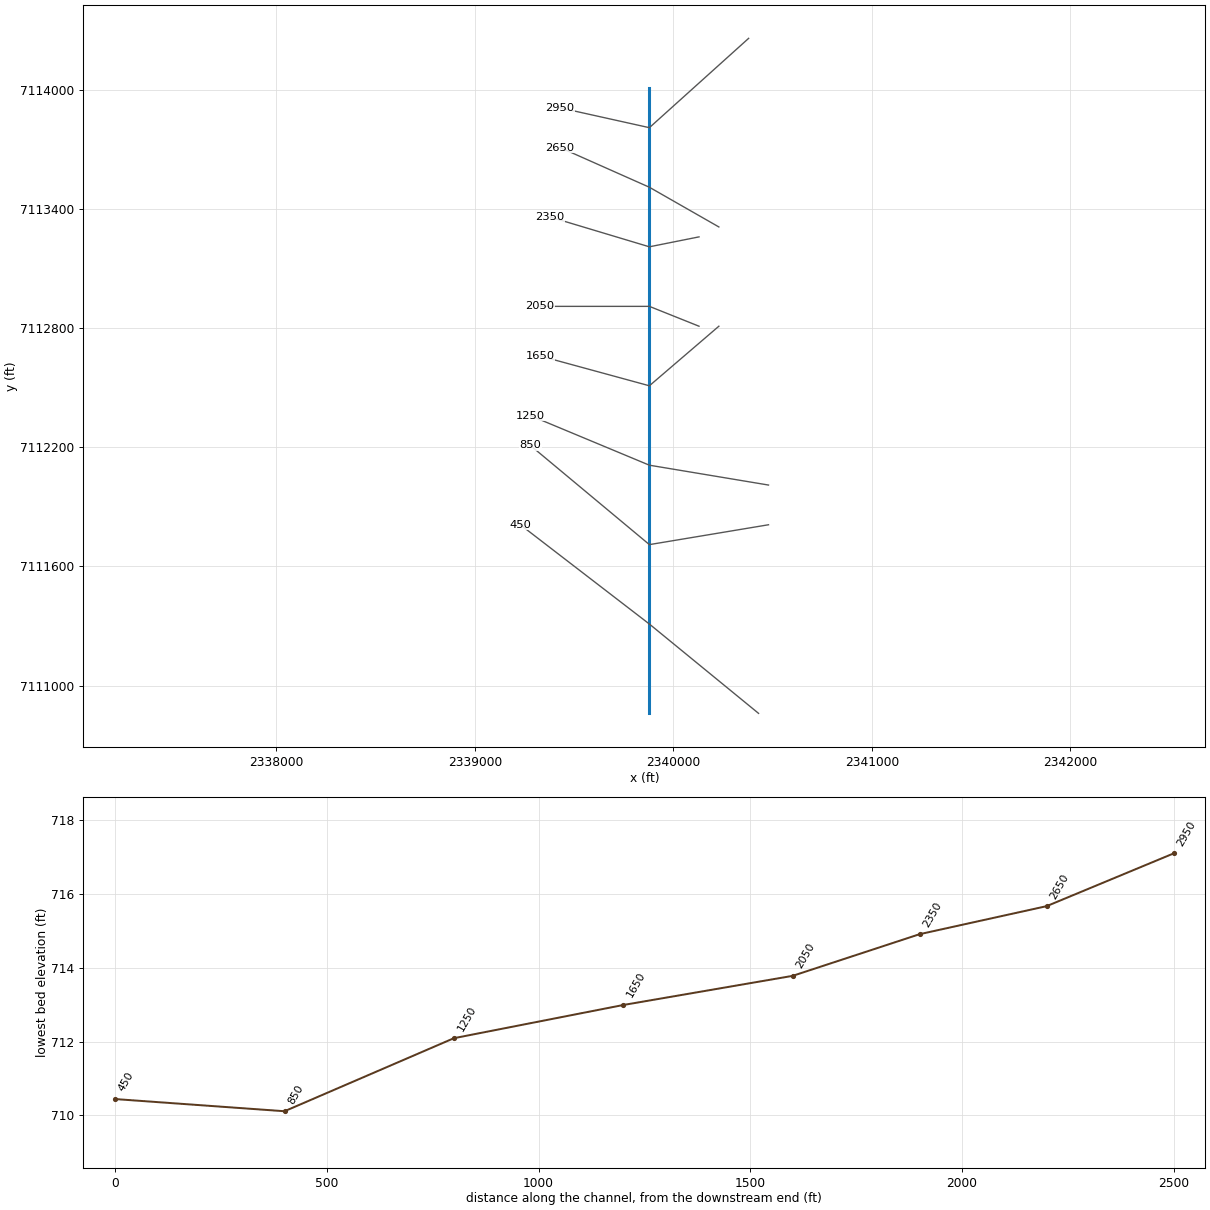
--- MDE S 115.prj (project) ---

Proj Title=MDE S 115 Base Level Engineering
Current Plan=p01
Default Exp/Contr=0.3,0.1
English Units
Geom File=g01
Flow File=f01
Plan File=p01
BEGIN DESCRIPTION:
MDE S 115
END DESCRIPTION:

--- MDE S 115.p01 (plan) ---

Plan Title=Multiple Run
Short Identifier=Multiple
Geom File=g01
Flow File=f01
Subcritical Flow
K Sum by GR= 0
Std Step Tol= 0.01
Critical Tol= 0.01
Num of Std Step Trials= 20
Max Error Tol= 0.3
Flow Tol Ratio= 0.001
Split Flow NTrial= 30
Split Flow Tol= 0.02
Split Flow Ratio= 0.02
Log Output Level= 0
Friction Slope Method= 1
Unsteady Friction Slope Method= 2
Unsteady Bridges Friction Slope Method= 1
Parabolic Critical Depth
Global Vel Dist=  1 , 1 , 1
Global Log Level= 0
CheckData=True
Encroach Param= -1, 0, 0, 0
BEGIN DESCRIPTION:
Multiple Run
END DESCRIPTION:

--- MDE S 115.f01 (steady flow) ---

Flow Title=Multiple
Number of Profiles=7
Profile Names=10-year,25-year,50-year,1pct_min,100-year,1pct_plu,500-year
River Rch & RM= MDE S 115,Reach-1,2950
     334     438     519     306     610    1217     844
Boundary for River Rch & Prof#=MDE S 115,Reach-1,1
Up Type=0
Dn Type=3
Dn Slope=0.005
Boundary for River Rch & Prof#=MDE S 115,Reach-1,2
Up Type=0
Dn Type=3
Dn Slope=0.005
Boundary for River Rch & Prof#=MDE S 115,Reach-1,3
Up Type=0
Dn Type=3
Dn Slope=0.005
Boundary for River Rch & Prof#=MDE S 115,Reach-1,4
Up Type=0
Dn Type=3
Dn Slope=0.005
Boundary for River Rch & Prof#=MDE S 115,Reach-1,5
Up Type=0
Dn Type=3
Dn Slope=0.005
Boundary for River Rch & Prof#=MDE S 115,Reach-1,6
Up Type=0
Dn Type=3
Dn Slope=0.005
Boundary for River Rch & Prof#=MDE S 115,Reach-1,7
Up Type=0
Dn Type=3
Dn Slope=0.005

--- MDE S 115.g01 (geometry) ---

Geom Title=Existing Conditions

River Reach=MDE S 115,Reach-1
Reach XY= 2
      2339879.00      7114010.00      2339879.00      7110860.00

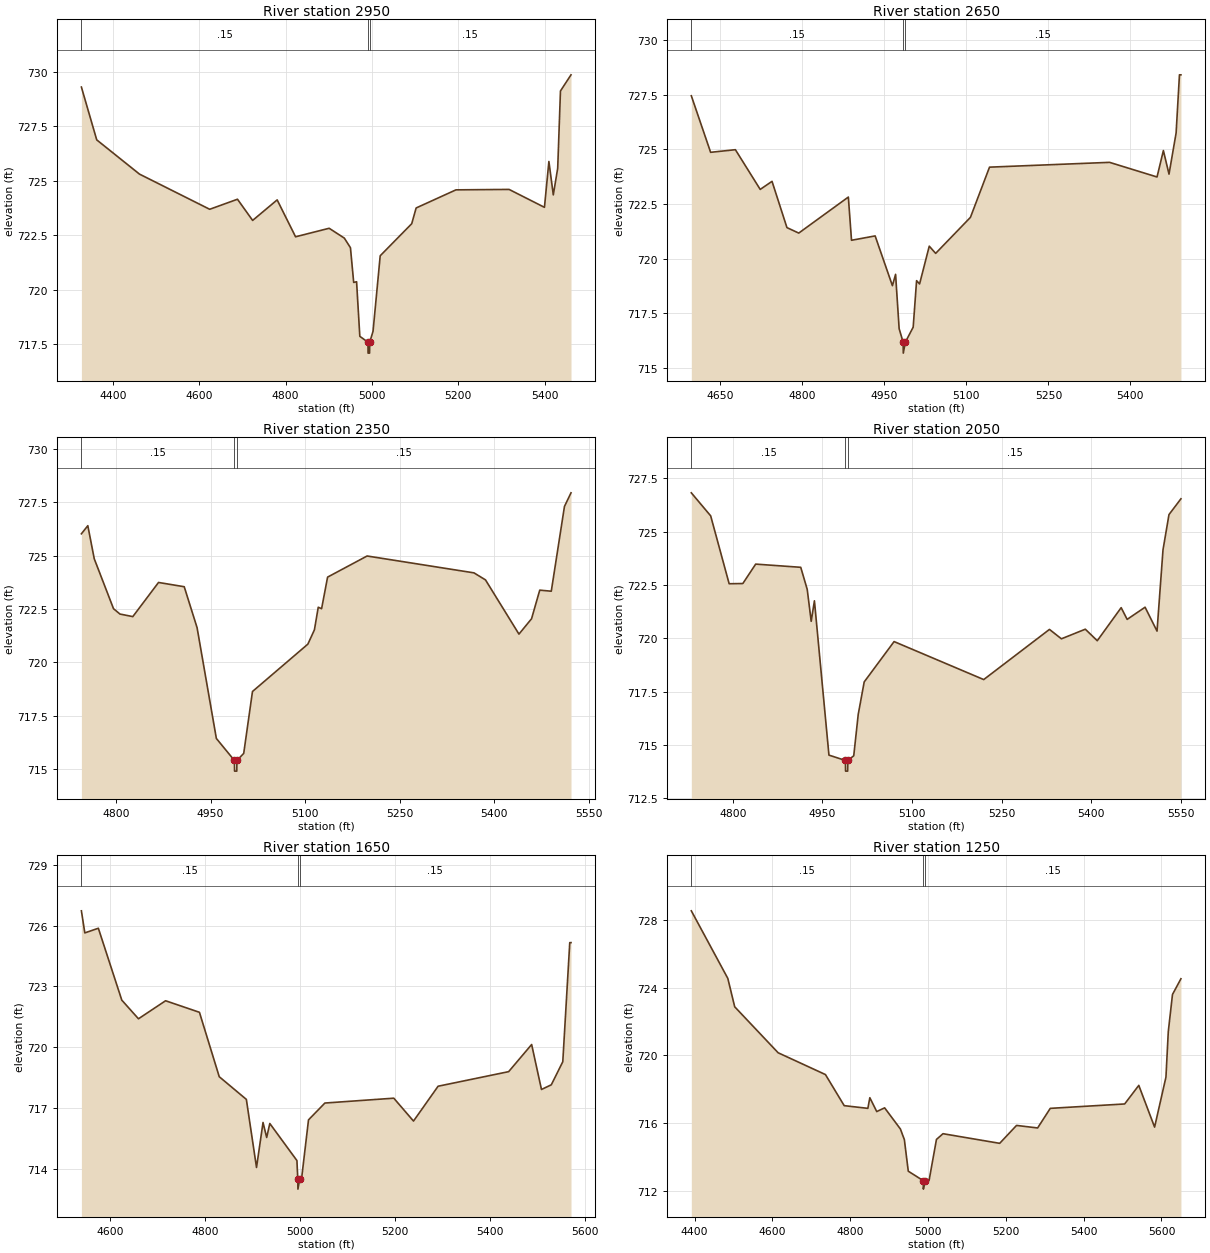
Type RM Length L Ch R = 1,2950,300,300,300
BEGIN DESCRIPTION:
MDE S 115 8.0
END DESCRIPTION:
XS GIS Cut Line= 3
      2340379.01      7114260.01      2339879.00      7113810.00
      2339428.98      7113910.00
#Sta/Elev= 30
  4327.3  729.29  4362.8  726.87  4461.9  725.30  4624.4  723.69  4688.7  724.15
  4723.8  723.18  4780.6  724.12  4823.2  722.43  4901.0  722.82  4936.1  722.37
  4950.3  721.93  4957.8  720.34  4964.5  720.37  4972.0  717.87  4990.9  717.60
  4991.1  717.10  4994.6  717.10  4994.9  717.60  5002.6  718.10  5019.2  721.56
  5092.2  723.03  5102.4  723.75  5194.6  724.58  5317.6  724.60  5399.5  723.78
  5409.8  725.88  5420.0  724.35  5430.2  725.57  5436.6  729.11  5461.0  729.85
#Mann=3,-1,0
  4327.3    0.15       0  4990.9    0.05       0  4994.9    0.15       0
Bank Sta=4990.9,4994.9
Exp/Cntr=0.3,0.1

Type RM Length L Ch R = 1,2650,300,300,300
BEGIN DESCRIPTION:
MDE S 115 7.0
END DESCRIPTION:
XS GIS Cut Line= 3
      2340228.99      7113310.01      2339879.00      7113510.00
      2339429.04      7113709.98
#Sta/Elev= 30
  4596.9  727.46  4632.2  724.87  4677.5  724.99  4722.9  723.17  4744.5  723.54
  4771.8  721.42  4793.4  721.17  4884.1  722.82  4889.9  720.84  4933.1  721.04
  4964.7  718.76  4970.5  719.28  4977.0  716.79  4984.3  716.17  4984.6  715.67
  4988.3  716.17  5002.7  716.86  5008.9  718.99  5014.4  718.84  5032.1  720.57
  5043.8  720.24  5107.4  721.89  5142.3  724.19  5361.8  724.41  5448.7  723.74
  5460.3  724.95  5470.6  723.87  5483.6  725.76  5489.7  728.42  5492.4  728.42
#Mann=3,-1,0
  4596.9    0.15       0  4984.3    0.05       0  4988.3    0.15       0
Bank Sta=4984.3,4988.3
Exp/Cntr=0.3,0.1

Type RM Length L Ch R = 1,2350,300,300,300
BEGIN DESCRIPTION:
MDE S 115 6.0
END DESCRIPTION:
XS GIS Cut Line= 3
      2340129.05      7113260.01      2339879.00      7113210.00
      2339379.01      7113360.00
#Sta/Elev= 30
  4745.0  726.03  4755.2  726.41  4765.4  724.86  4796.0  722.52  4806.2  722.27
  4826.6  722.15  4867.4  723.75  4908.2  723.55  4928.6  721.63  4959.2  716.44
  4987.8  715.41  4988.1  714.91  4991.6  714.91  4991.8  715.41  5002.6  715.74
  5016.5  718.64  5104.4  720.86  5114.8  721.53  5120.9  722.59  5126.2  722.52
  5135.7  724.00  5198.4  724.99  5368.0  724.20  5386.3  723.87  5439.4  721.33
  5459.4  722.05  5472.4  723.39  5490.7  723.34  5511.6  727.31  5522.0  727.95
#Mann=3,-1,0
  4745.0    0.15       0  4987.8    0.05       0  4991.8    0.15       0
Bank Sta=4987.8,4991.8
Exp/Cntr=0.3,0.1

Type RM Length L Ch R = 1,2050,400,400,400
BEGIN DESCRIPTION:
MDE S 115 5.0
END DESCRIPTION:
XS GIS Cut Line= 3
      2340129.04      7112809.98      2339879.00      7112910.00
      2339329.00      7112910.00
#Sta/Elev= 30
  4730.7  726.82  4763.1  725.74  4794.0  722.56  4816.9  722.57  4838.4  723.48
  4913.8  723.33  4924.6  722.30  4931.3  720.80  4936.7  721.76  4961.0  714.53
  4988.6  714.28  4988.8  713.78  4992.3  713.78  4992.6  714.28  5002.5  714.50
  5010.0  716.44  5020.0  717.96  5070.0  719.85  5220.0  718.07  5330.0  720.42
  5350.0  719.98  5390.0  720.43  5410.0  719.89  5450.0  721.44  5460.0  720.89
  5490.0  721.46  5510.0  720.34  5520.0  724.15  5530.0  725.80  5550.0  726.54
#Mann=3,-1,0
  4730.7    0.15       0  4988.6    0.05       0  4992.6    0.15       0
Bank Sta=4988.6,4992.6
Exp/Cntr=0.3,0.1

Type RM Length L Ch R = 1,1650,400,400,400
BEGIN DESCRIPTION:
MDE S 115 4.0
END DESCRIPTION:
XS GIS Cut Line= 3
      2340229.02      7112810.01      2339879.00      7112510.00
      2339328.99      7112660.00
#Sta/Elev= 30
  4539.0  726.73  4546.2  725.64  4574.7  725.87  4624.1  722.32  4659.2  721.40
  4716.3  722.29  4787.6  721.72  4829.3  718.54  4886.4  717.42  4907.8  714.06
  4921.5  716.28  4929.2  715.54  4935.8  716.23  4992.9  714.40  4994.7  713.49
  4995.0  712.99  4998.7  713.49  5002.6  713.49  5017.3  716.41  5051.8  717.24
  5196.9  717.48  5238.4  716.35  5290.2  718.07  5438.8  718.79  5487.2  720.13
  5507.9  717.91  5528.6  718.14  5552.8  719.28  5567.5  725.16  5570.1  725.16
#Mann=3,-1,0
  4539.0    0.15       0  4994.7    0.05       0  4998.7    0.15       0
Bank Sta=4994.7,4998.7
Exp/Cntr=0.3,0.1

Type RM Length L Ch R = 1,1250,400,400,400
BEGIN DESCRIPTION:
MDE S 115 3.0
END DESCRIPTION:
XS GIS Cut Line= 3
      2340479.02      7112010.00      2339879.00      7112110.00
      2339279.00      7112360.00
#Sta/Elev= 30
  4391.7  728.56  4485.5  724.56  4503.2  722.88  4614.8  720.16  4736.4  718.87
  4784.6  717.03  4845.4  716.87  4850.5  717.50  4868.2  716.68  4888.5  716.90
  4929.0  715.65  4939.2  715.02  4949.3  713.15  4987.9  712.59  4988.1  712.09
  4991.9  712.59  5002.7  712.60  5021.7  715.03  5038.5  715.37  5184.2  714.80
  5227.5  715.86  5281.7  715.71  5314.2  716.87  5505.4  717.13  5541.7  718.23
  5582.3  715.76  5611.5  718.72  5617.5  721.41  5628.3  723.61  5650.0  724.54
#Mann=3,-1,0
  4391.7    0.15       0  4987.9    0.05       0  4991.9    0.15       0
Bank Sta=4987.9,4991.9
Exp/Cntr=0.3,0.1

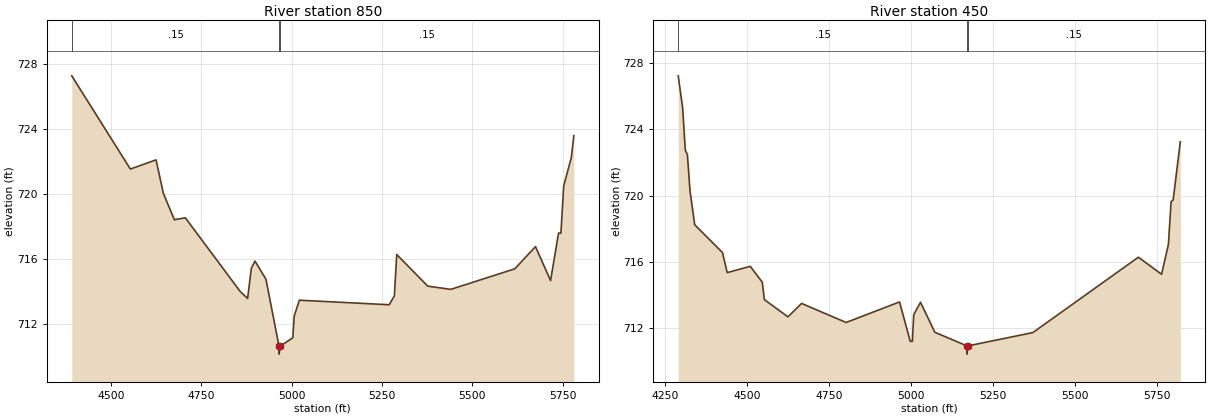
Type RM Length L Ch R = 1,850,400,400,400
BEGIN DESCRIPTION:
MDE S 115 2.0
END DESCRIPTION:
XS GIS Cut Line= 3
      2340479.02      7111810.00      2339879.00      7111710.00
      2339279.02      7112209.98
#Sta/Elev= 30
  4391.7  727.30  4553.9  721.54  4624.9  722.11  4645.2  720.04  4675.6  718.41
  4706.0  718.53  4858.1  713.97  4878.3  713.55  4888.5  715.40  4898.6  715.86
  4929.0  714.74  4965.1  710.61  4965.3  710.11  4969.1  710.61  5003.3  711.12
  5007.2  712.46  5021.5  713.44  5270.1  713.16  5284.4  713.71  5290.9  716.26
  5376.8  714.31  5440.6  714.11  5617.7  715.38  5674.9  716.75  5716.6  714.65
  5738.7  717.59  5745.2  717.58  5753.0  720.51  5773.9  722.24  5781.0  723.60
#Mann=3,-1,0
  4391.7    0.15       0  4965.1    0.05       0  4969.1    0.15       0
Bank Sta=4965.1,4969.1
Exp/Cntr=0.3,0.1

Type RM Length L Ch R = 1,450,0,0,0
BEGIN DESCRIPTION:
MDE S 115 1.0
END DESCRIPTION:
XS GIS Cut Line= 3
      2340428.97      7110860.02      2339879.00      7111310.00
      2339228.97      7111810.02
#Sta/Elev= 30
  4289.4  727.24  4303.0  725.28  4310.9  722.76  4317.4  722.48  4325.3  720.30
  4339.6  718.25  4424.3  716.57  4438.7  715.36  4509.0  715.74  4545.6  714.78
  4552.1  713.73  4623.9  712.69  4665.5  713.50  4801.2  712.35  4964.1  713.59
  4996.8  711.21  5003.2  711.21  5007.3  712.82  5028.1  713.57  5071.6  711.76
  5169.3  710.94  5169.5  710.44  5173.3  710.94  5370.6  711.74  5692.3  716.29
  5763.0  715.26  5783.8  717.06  5792.0  719.64  5798.3  719.75  5820.1  723.26
#Mann=3,-1,0
  4289.4    0.15       0  5169.3    0.05       0  5173.3    0.15       0
Bank Sta=5169.3,5173.3
Exp/Cntr=0.3,0.1

Chan Stop Cuts=-1