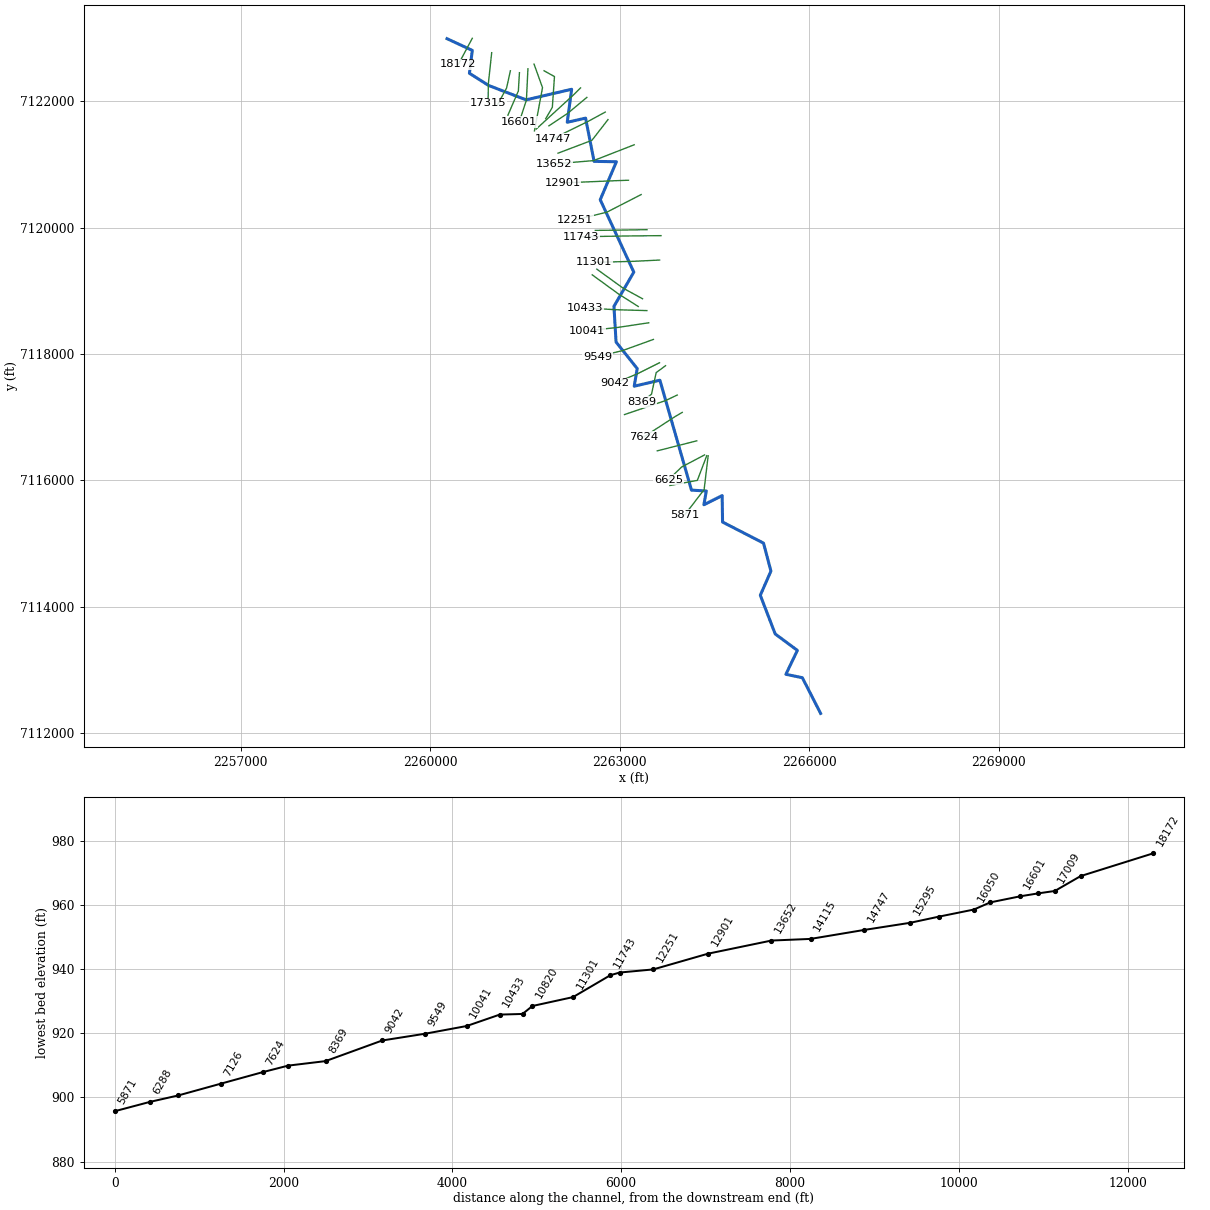
--- MDW T 002.prj (project) ---

Proj Title=MDW T 002 Base Level Engineering
Current Plan=p01
Default Exp/Contr=0.3,0.1
English Units
Geom File=g01
Flow File=f01
Plan File=p01
BEGIN DESCRIPTION:
MDW T 002
END DESCRIPTION:

--- MDW T 002.p01 (plan) ---

Plan Title=Multiple Run
Short Identifier=Multiple
Geom File=g01
Flow File=f01
Subcritical Flow
K Sum by GR= 0
Std Step Tol= 0.01
Critical Tol= 0.01
Num of Std Step Trials= 20
Max Error Tol= 0.3
Flow Tol Ratio= 0.001
Split Flow NTrial= 30
Split Flow Tol= 0.02
Split Flow Ratio= 0.02
Log Output Level= 0
Friction Slope Method= 1
Unsteady Friction Slope Method= 2
Unsteady Bridges Friction Slope Method= 1
Parabolic Critical Depth
Global Vel Dist=  1 , 1 , 1
Global Log Level= 0
CheckData=True
Encroach Param= -1, 0, 0, 0
BEGIN DESCRIPTION:
Multiple Run
END DESCRIPTION:

--- MDW T 002.f01 (steady flow) ---

Flow Title=Multiple
Number of Profiles=7
Profile Names=10-year,25-year,50-year,1pct_min,100-year,1pct_plu,500-year
River Rch & RM= MDW T 002,Reach-1,18172
     341     451     538     320     639    1275     900
River Rch & RM= MDW T 002,Reach-1,15632
     685     947    1165     712    1420    2834    2114
River Rch & RM= MDW T 002,Reach-1,11301
     843    1178    1459     897    1789    3570    2697
River Rch & RM= MDW T 002,Reach-1,5310
    1056    1492    1863    1153    2300    4589    3517
River Rch & RM= MDW T 002,Reach-1,2008
    1073    1517    1894    1172    2339    4666    3576
Boundary for River Rch & Prof#=MDW T 002,Reach-1,1
Up Type=0
Dn Type=3
Dn Slope=0.005
Boundary for River Rch & Prof#=MDW T 002,Reach-1,2
Up Type=0
Dn Type=3
Dn Slope=0.005
Boundary for River Rch & Prof#=MDW T 002,Reach-1,3
Up Type=0
Dn Type=3
Dn Slope=0.005
Boundary for River Rch & Prof#=MDW T 002,Reach-1,4
Up Type=0
Dn Type=3
Dn Slope=0.005
Boundary for River Rch & Prof#=MDW T 002,Reach-1,5
Up Type=0
Dn Type=3
Dn Slope=0.005
Boundary for River Rch & Prof#=MDW T 002,Reach-1,6
Up Type=0
Dn Type=3
Dn Slope=0.005
Boundary for River Rch & Prof#=MDW T 002,Reach-1,7
Up Type=0
Dn Type=3
Dn Slope=0.005

--- MDW T 002.g01 (geometry) ---

Geom Title=Existing Conditions

River Reach=MDW T 002,Reach-1
Reach XY= 30
      2260265.92      7122989.16      2260665.76      7122803.61
      2260620.13      7122441.69      2260924.27      7122248.76
      2261517.71      7122021.10      2262238.07      7122188.68
      2262168.40      7121666.12      2262458.82      7121731.84
      2262593.67      7121047.46      2262946.78      7121041.30
      2262690.59      7120440.55      2263222.24      7119294.24
      2262907.97      7118751.99      2262941.35      7118187.44
      2263275.73      7117767.86      2263228.65      7117488.36
      2263635.03      7117583.32      2264134.99      7115843.70
      2264369.78      7115829.76      2264331.17      7115612.05
      2264620.78      7115757.00      2264627.02      7115338.38
      2265275.42      7115004.91      2265392.33      7114561.89
      2265224.38      7114179.29      2265460.19      7113566.97
      2265811.22      7113307.24      2265629.69      7112928.54
      2265889.69      7112874.59      2266179.00      7112310.00

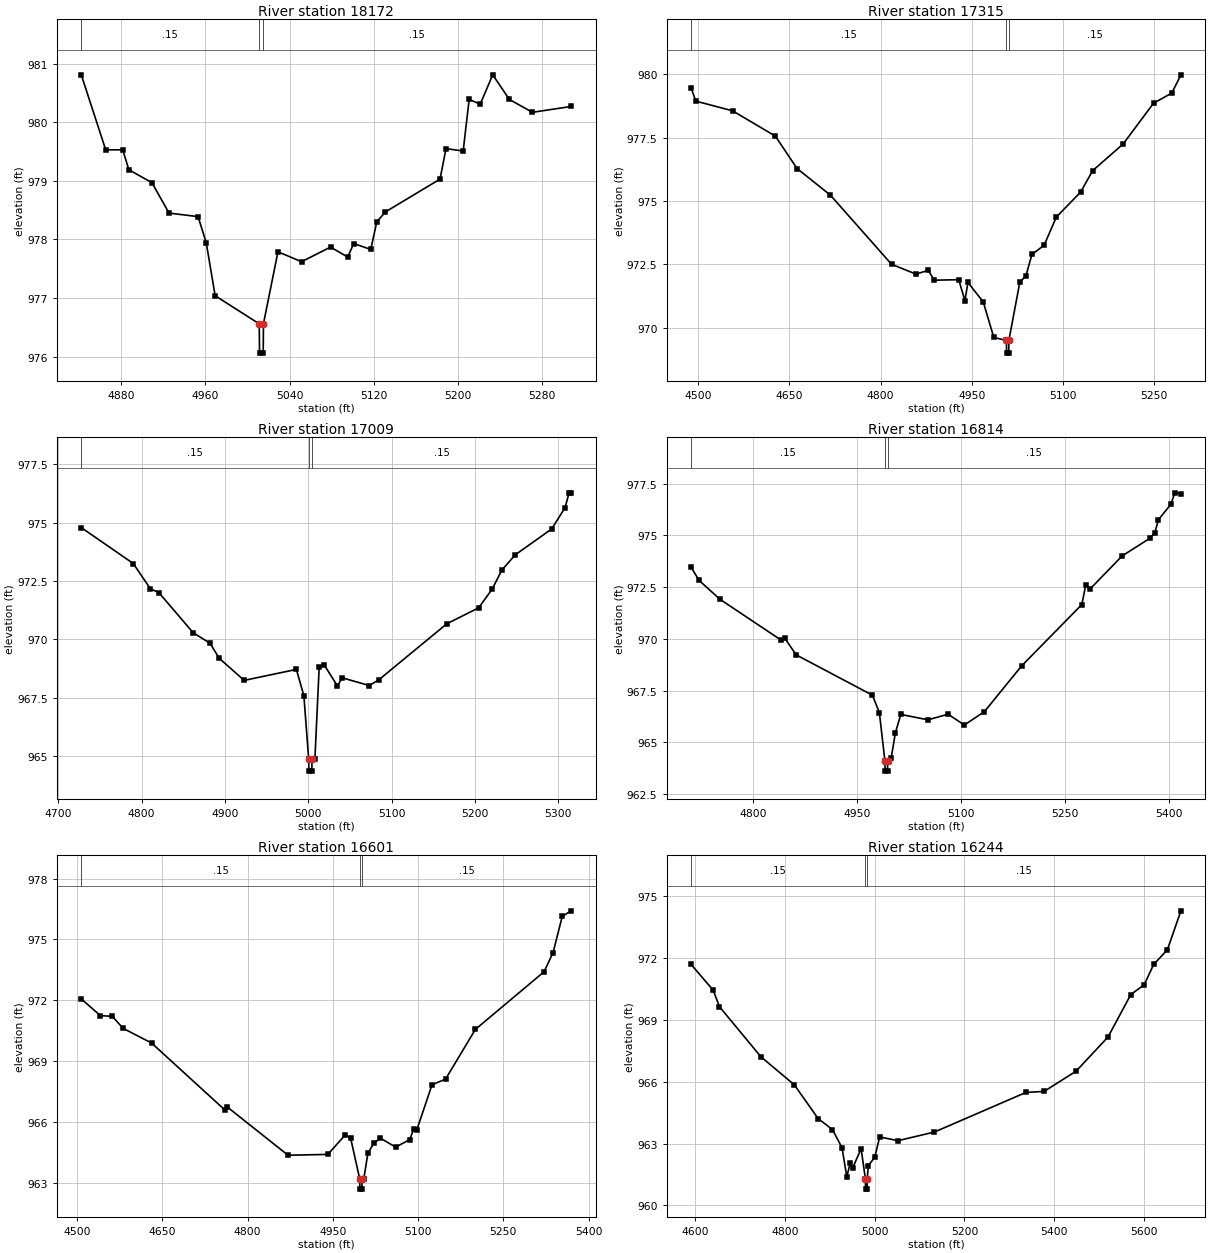
Type RM Length L Ch R = 1,18172,857,857,857
BEGIN DESCRIPTION:
MDW T 002 35.5
END DESCRIPTION:
XS GIS Cut Line= 2
      2260665.36      7122994.75      2260445.65      7122584.36
#Sta/Elev= 30
  4842.1  980.81  4865.3  979.53  4881.5  979.53  4887.3  979.19  4909.2  978.97
  4925.5  978.45  4953.1  978.39  4960.9  977.94  4969.3  977.04  5011.2  976.56
  5011.5  976.06  5015.0  976.06  5015.2  976.56  5029.0  977.79  5051.4  977.62
  5079.0  977.87  5095.3  977.70  5101.0  977.93  5117.2  977.83  5122.9  978.30
  5131.1  978.47  5183.0  979.03  5188.7  979.55  5205.0  979.51  5210.7  980.39
  5221.2  980.31  5233.1  980.81  5248.9  980.39  5270.8  980.17  5307.6  980.27
#Mann=3,-1,0
  4842.1    0.15       0  5011.2    0.05       0  5015.2    0.15       0
Bank Sta=5011.2,5015.2
Exp/Cntr=0.3,0.1

Type RM Length L Ch R = 1,17315,306,306,306
BEGIN DESCRIPTION:
MDW T 002 35.0
END DESCRIPTION:
XS GIS Cut Line= 3
      2260972.69      7122767.81      2260919.21      7122270.50
      2260916.27      7121964.99
#Sta/Elev= 30
  4488.2  979.46  4496.1  978.94  4556.4  978.56  4626.8  977.56  4662.5  976.28
  4717.3  975.23  4817.9  972.50  4858.1  972.11  4878.2  972.26  4888.3  971.87
  4928.5  971.89  4938.6  971.06  4943.6  971.78  4968.8  971.01  4986.1  969.61
  5006.9  969.49  5007.1  968.99  5010.6  968.99  5010.9  969.49  5028.9  971.79
  5038.9  972.04  5048.9  972.89  5068.9  973.25  5088.9  974.36  5128.9  975.35
  5148.9  976.20  5198.9  977.25  5248.9  978.86  5278.9  979.26  5293.9  979.98
#Mann=3,-1,0
  4488.2    0.15       0  5006.9    0.05       0  5010.9    0.15       0
Bank Sta=5006.9,5010.9
Exp/Cntr=0.3,0.1

Type RM Length L Ch R = 1,17009,195,195,195
BEGIN DESCRIPTION:
MDW T 002 34.0
END DESCRIPTION:
XS GIS Cut Line= 3
      2261268.61      7122480.98      2261208.97      7122209.86
      2261061.65      7121936.65
#Sta/Elev= 30
  4727.5  974.79  4789.9  973.25  4810.4  972.17  4820.7  972.00  4861.6  970.29
  4882.1  969.83  4893.0  969.19  4923.0  968.24  4985.7  968.71  4994.7  967.58
  5000.5  964.85  5000.7  964.35  5004.2  964.35  5004.5  964.85  5007.9  964.85
  5013.1  968.83  5018.8  968.92  5035.0  968.00  5040.7  968.35  5073.1  968.02
  5084.5  968.26  5166.4  970.67  5204.5  971.35  5220.7  972.15  5232.2  972.96
  5248.3  973.62  5292.1  974.73  5308.3  975.65  5313.0  976.28  5315.5  976.28
#Mann=3,-1,0
  4727.5    0.15       0  5000.5    0.05       0  5004.5    0.15       0
Bank Sta=5000.5,5004.5
Exp/Cntr=0.3,0.1

Type RM Length L Ch R = 1,16814,213,213,213
BEGIN DESCRIPTION:
MDW T 002 33.0
END DESCRIPTION:
XS GIS Cut Line= 3
      2261411.93      7122451.43      2261394.77      7122161.16
      2261229.64      7121778.66
#Sta/Elev= 30
  4710.3  973.47  4721.8  972.83  4751.8  971.92  4840.8  969.93  4845.8  970.03
  4862.0  969.23  4972.2  967.28  4982.2  966.44  4990.2  964.11  4990.5  963.61
  4994.0  963.61  4994.2  964.11  4999.2  964.23  5005.4  965.47  5013.2  966.35
  5052.4  966.09  5081.4  966.36  5104.9  965.84  5133.8  966.48  5187.5  968.69
  5274.6  971.66  5280.3  972.61  5285.8  972.39  5332.8  974.01  5372.7  974.86
  5379.8  975.11  5385.2  975.76  5403.3  976.51  5408.8  977.06  5417.7  977.02
#Mann=3,-1,0
  4710.3    0.15       0  4990.2    0.05       0  4994.2    0.15       0
Bank Sta=4990.2,4994.2
Exp/Cntr=0.3,0.1

Type RM Length L Ch R = 1,16601,357,357,357
BEGIN DESCRIPTION:
MDW T 002 32.0
END DESCRIPTION:
XS GIS Cut Line= 3
      2261546.48      7122513.50      2261522.32      7122018.95
      2261409.33      7121669.71
#Sta/Elev= 30
  4507.2  972.07  4540.7  971.25  4561.9  971.21  4580.8  970.62  4630.8  969.90
  4759.5  966.61  4764.5  966.74  4871.1  964.37  4941.2  964.41  4972.1  965.38
  4981.3  965.21  4997.3  963.20  4997.6  962.70  5001.1  962.70  5001.3  963.20
  5004.4  963.20  5011.7  964.47  5022.3  964.97  5033.7  965.21  5060.5  964.77
  5085.3  965.14  5092.5  965.68  5097.7  965.61  5124.5  967.84  5148.4  968.12
  5200.9  970.57  5321.8  973.41  5337.6  974.35  5353.8  976.14  5369.4  976.41
#Mann=3,-1,0
  4507.2    0.15       0  4997.3    0.05       0  5001.3    0.15       0
Bank Sta=4997.3,5001.3
Exp/Cntr=0.3,0.1

Type RM Length L Ch R = 1,16244,194,194,194
BEGIN DESCRIPTION:
MDW T 002 31.0
END DESCRIPTION:
XS GIS Cut Line= 3
      2261643.27      7122586.37      2261777.26      7122214.19
      2261649.77      7121530.34
#Sta/Elev= 30
  4591.1  971.69  4640.4  970.44  4654.3  969.64  4746.7  967.21  4821.1  965.85
  4874.2  964.21  4906.1  963.68  4927.3  962.80  4938.0  961.39  4945.4  962.04
  4950.7  961.80  4969.9  962.75  4979.4  961.29  4979.7  960.79  4983.2  960.79
  4983.4  961.29  4986.2  961.93  5000.2  962.34  5011.3  963.32  5052.0  963.14
  5133.3  963.56  5336.9  965.48  5377.5  965.53  5448.7  966.51  5519.9  968.17
  5570.7  970.23  5600.4  970.70  5621.6  971.69  5652.1  972.40  5682.3  974.29
#Mann=3,-1,0
  4591.1    0.15       0  4979.4    0.05       0  4983.4    0.15       0
Bank Sta=4979.4,4983.4
Exp/Cntr=0.3,0.1

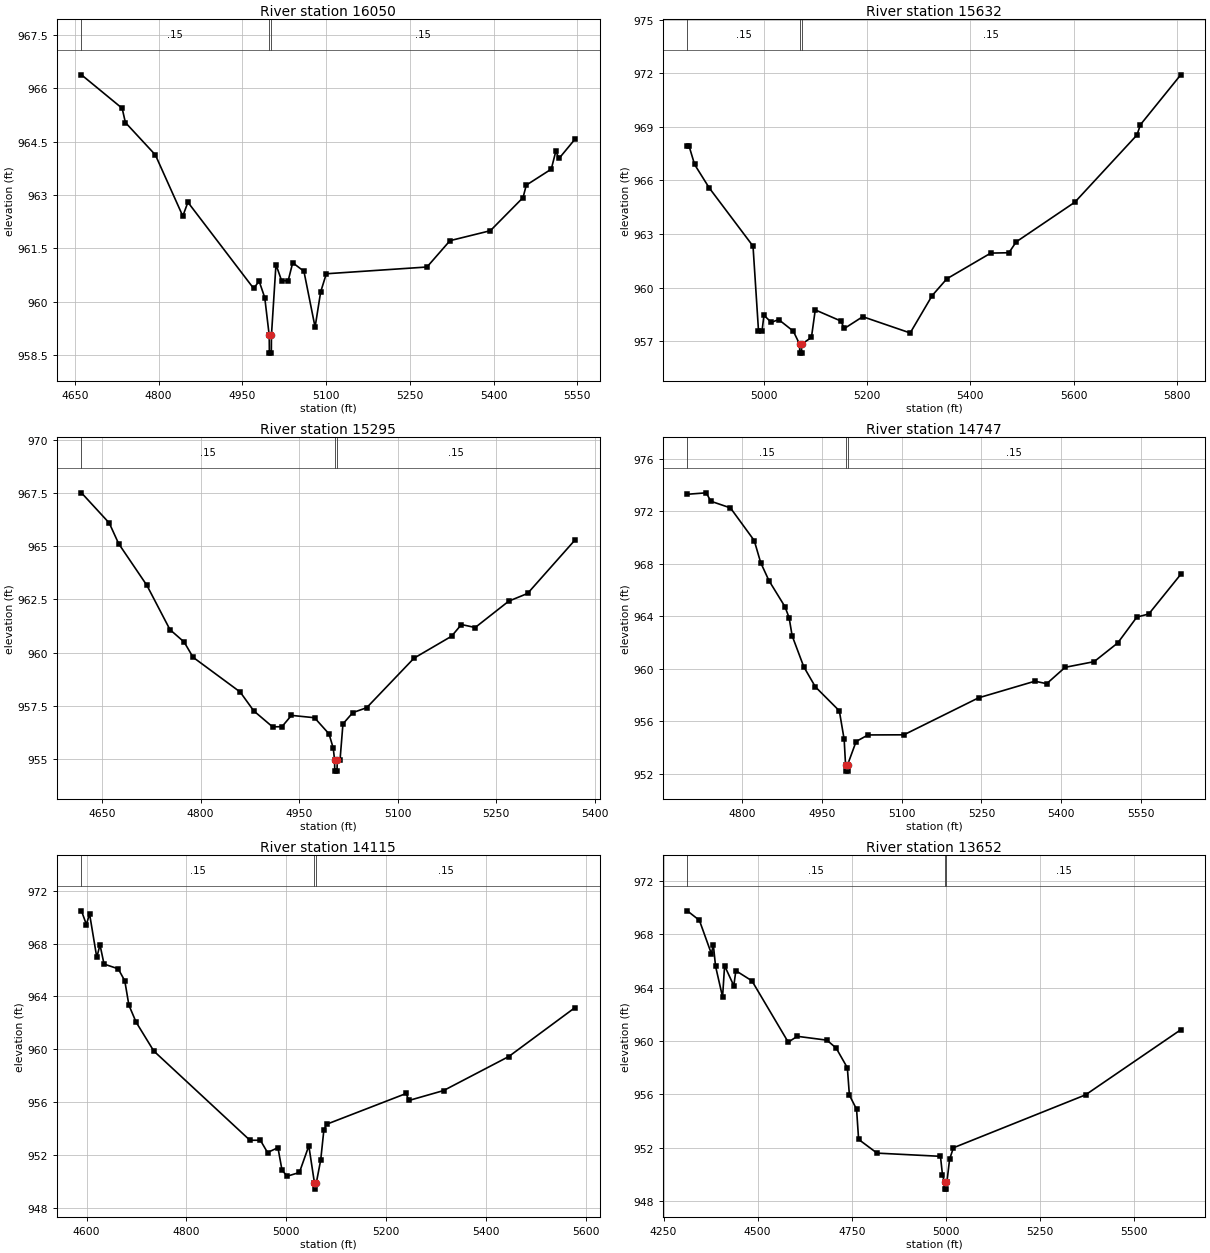
Type RM Length L Ch R = 1,16050,418,418,418
BEGIN DESCRIPTION:
Mapping XS fdde7f66
END DESCRIPTION:
XS GIS Cut Line= 4
      2261801.80      7122481.31      2261966.35      7122389.77
      2261932.60      7121902.48      2261827.81      7121723.45
#Sta/Elev= 30
  4661.7  966.38  4734.6  965.44  4740.4  965.04  4794.1  964.13  4843.3  962.41
  4852.4  962.80  4970.1  960.38  4980.1  960.58  4990.1  960.12  4998.1  959.06
  4998.4  958.56  5001.9  958.56  5002.1  959.06  5010.2  961.05  5020.2  960.60
  5032.0  960.59  5040.2  961.10  5060.3  960.86  5080.3  959.29  5090.3  960.28
  5100.4  960.79  5280.8  960.98  5322.0  961.72  5394.3  962.00  5452.9  962.93
  5458.7  963.28  5503.5  963.73  5511.6  964.23  5517.4  964.03  5545.9  964.57
#Mann=3,-1,0
  4661.7    0.15       0  4998.1    0.05       0  5002.1    0.15       0
Bank Sta=4998.1,5002.1
Exp/Cntr=0.3,0.1

Type RM Length L Ch R = 1,15632,337,337,337
BEGIN DESCRIPTION:
MDW T 002 30.0
END DESCRIPTION:
XS GIS Cut Line= 3
      2262379.02      7122210.02      2262279.00      7122110.00
      2261679.00      7121560.00
#Sta/Elev= 30
  4851.9  967.91  4855.5  967.91  4866.1  966.89  4894.4  965.58  4979.2  962.32
  4989.8  957.59  4996.7  957.59  5000.4  958.45  5014.6  958.05  5028.8  958.21
  5057.2  957.56  5069.4  956.83  5069.6  956.33  5073.1  956.33  5073.4  956.83
  5092.3  957.21  5099.7  958.75  5149.1  958.13  5156.1  957.71  5191.6  958.37
  5283.5  957.46  5326.0  959.55  5354.4  960.49  5439.5  961.93  5474.6  961.95
  5488.8  962.56  5602.3  964.78  5722.5  968.54  5729.3  969.12  5807.3  971.91
#Mann=3,-1,0
  4851.9    0.15       0  5069.4    0.05       0  5073.4    0.15       0
Bank Sta=5069.4,5073.4
Exp/Cntr=0.3,0.1

Type RM Length L Ch R = 1,15295,548,548,548
BEGIN DESCRIPTION:
MDW T 002 29.0
END DESCRIPTION:
XS GIS Cut Line= 3
      2262479.00      7122060.00      2262179.00      7121810.00
      2261878.97      7121609.98
#Sta/Elev= 30
  4618.7  967.51  4661.0  966.09  4675.3  965.12  4718.3  963.16  4753.4  961.08
  4774.9  960.50  4788.6  959.78  4860.2  958.15  4881.0  957.26  4909.6  956.51
  4923.9  956.52  4938.3  957.05  4973.4  956.94  4995.5  956.18  5002.0  955.50
  5004.0  954.93  5004.2  954.43  5007.7  954.43  5008.0  954.93  5012.2  954.93
  5016.7  956.65  5031.7  957.18  5052.8  957.41  5124.9  959.74  5182.0  960.77
  5197.0  961.32  5218.0  961.18  5269.1  962.42  5297.7  962.78  5369.8  965.29
#Mann=3,-1,0
  4618.7    0.15       0  5004.0    0.05       0  5008.0    0.15       0
Bank Sta=5004,5008
Exp/Cntr=0.3,0.1

Type RM Length L Ch R = 1,14747,632,632,632
BEGIN DESCRIPTION:
MDW T 002 28.0
END DESCRIPTION:
XS GIS Cut Line= 3
      2262770.37      7121827.57      2262505.95      7121683.86
      2261942.67      7121407.20
#Sta/Elev= 30
  4696.5  973.31  4732.2  973.42  4740.8  972.78  4777.7  972.27  4822.5  969.78
  4834.6  968.10  4850.1  966.73  4880.2  964.74  4888.1  963.90  4893.8  962.52
  4915.6  960.16  4937.5  958.62  4982.6  956.79  4991.7  954.61  4994.3  952.69
  4994.5  952.19  4998.0  952.19  4998.3  952.69  5014.2  954.45  5036.6  954.95
  5104.1  954.96  5244.5  957.78  5350.6  959.05  5372.8  958.86  5407.5  960.11
  5462.0  960.54  5506.5  961.97  5542.4  963.94  5564.9  964.18  5625.0  967.20
#Mann=3,-1,0
  4696.5    0.15       0  4994.3    0.05       0  4998.3    0.15       0
Bank Sta=4994.3,4998.3
Exp/Cntr=0.3,0.1

Type RM Length L Ch R = 1,14115,463,463,463
BEGIN DESCRIPTION:
MDW T 002 27.0
END DESCRIPTION:
XS GIS Cut Line= 3
      2262813.71      7121708.16      2262559.05      7121380.34
      2262022.84      7121176.97
#Sta/Elev= 30
  4589.9  970.48  4599.8  969.44  4606.1  970.26  4620.6  966.95  4627.0  967.91
  4635.1  966.45  4663.5  966.09  4676.7  965.18  4684.9  963.34  4699.4  962.05
  4734.7  959.87  4927.4  953.11  4948.3  953.11  4962.7  952.18  4983.5  952.55
  4991.7  950.84  5002.1  950.39  5026.5  950.67  5045.4  952.69  5056.5  949.91
  5056.8  949.41  5060.5  949.91  5069.2  951.62  5075.5  953.88  5080.9  954.32
  5240.3  956.65  5245.7  956.12  5315.2  956.87  5446.0  959.45  5578.5  963.15
#Mann=3,-1,0
  4589.9    0.15       0  5056.5    0.05       0  5060.5    0.15       0
Bank Sta=5056.5,5060.5
Exp/Cntr=0.3,0.1

Type RM Length L Ch R = 1,13652,751,751,751
BEGIN DESCRIPTION:
MDW T 002 26.0
END DESCRIPTION:
XS GIS Cut Line= 3
      2263229.03      7121310.01      2262586.31      7121059.54
      2261967.00      7121007.37
#Sta/Elev= 30
  4312.9  969.77  4345.1  969.06  4376.9  966.56  4382.2  967.21  4388.1  965.61
  4406.7  963.31  4412.1  965.65  4436.6  964.15  4442.0  965.28  4484.7  964.52
  4581.2  959.92  4605.1  960.36  4684.0  960.07  4708.5  959.48  4738.3  958.00
  4743.7  955.95  4762.8  954.89  4768.2  952.63  4817.2  951.60  4985.7  951.36
  4991.1  949.96  4996.6  949.40  4996.8  948.90  5000.3  948.90  5000.6  949.40
  5002.7  949.40  5010.0  951.14  5020.1  952.00  5371.3  955.97  5624.2  960.85
#Mann=3,-1,0
  4312.9    0.15       0  4996.6    0.05       0  5000.6    0.15       0
Bank Sta=4996.6,5000.6
Exp/Cntr=0.3,0.1

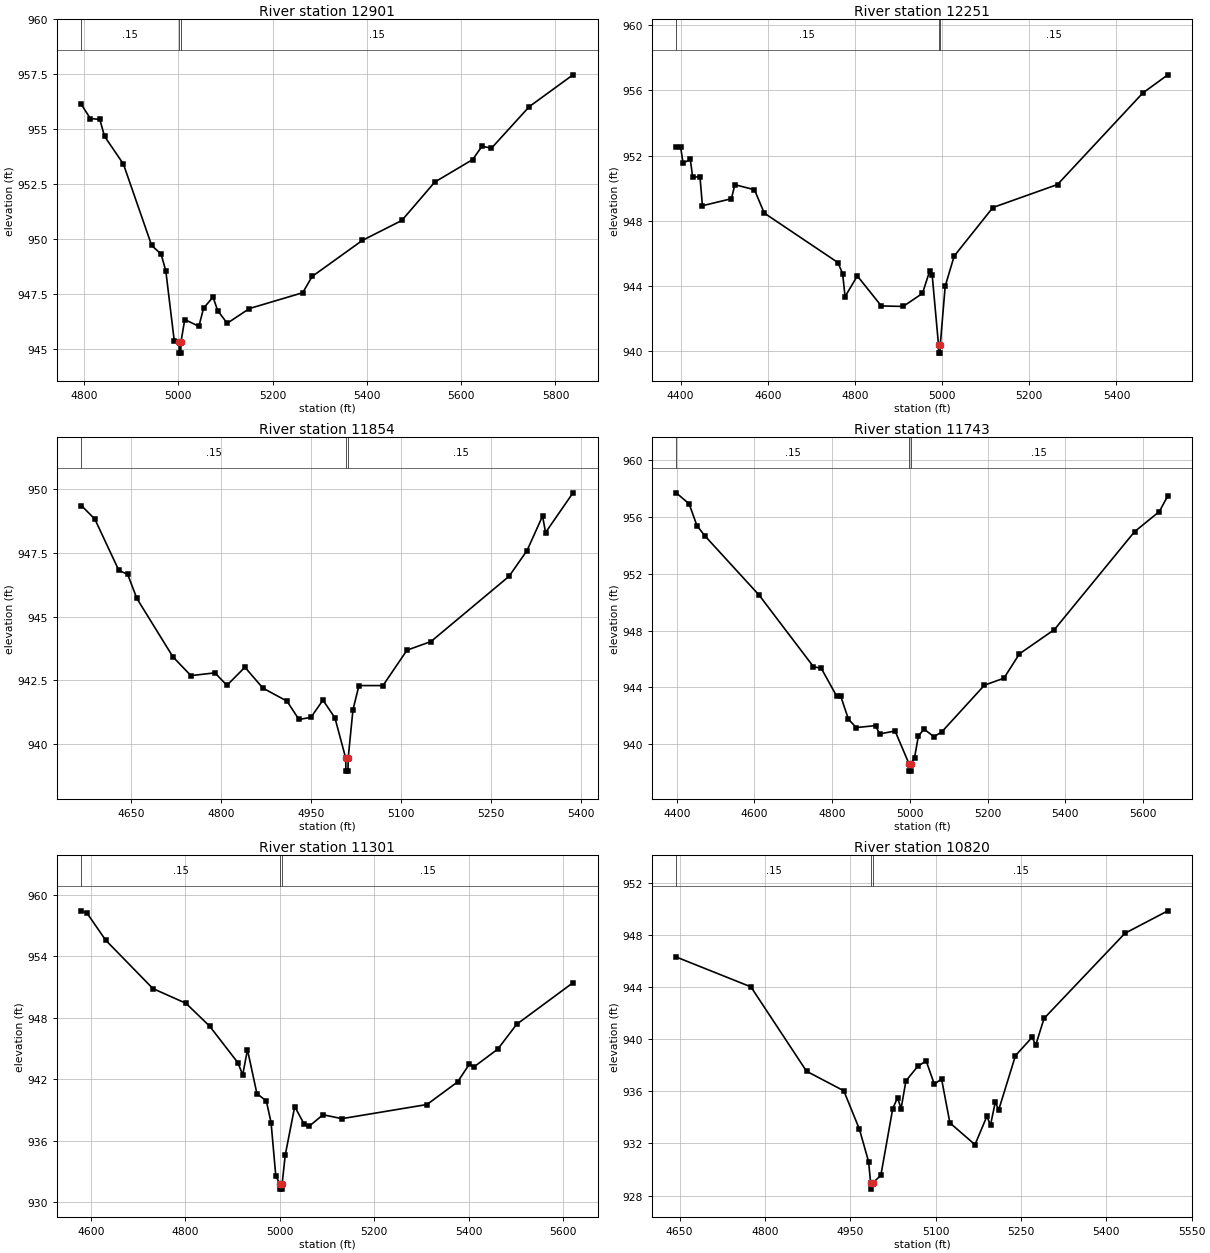
Type RM Length L Ch R = 1,12901,650,650,650
BEGIN DESCRIPTION:
MDW T 002 25.0
END DESCRIPTION:
XS GIS Cut Line= 3
      2263138.03      7120748.63      2262938.46      7120741.66
      2262096.30      7120706.31
#Sta/Elev= 30
  4794.6  956.13  4813.6  955.49  4833.7  955.45  4843.7  954.68  4883.7  953.42
  4943.7  949.71  4963.7  949.32  4973.7  948.55  4991.5  945.38  5001.8  945.31
  5002.0  944.81  5005.5  944.81  5005.8  945.31  5013.8  946.34  5043.8  946.03
  5053.8  946.86  5073.8  947.36  5083.8  946.74  5103.9  946.17  5151.0  946.84
  5264.0  947.56  5284.0  948.30  5390.3  949.94  5474.2  950.85  5544.2  952.60
  5624.3  953.62  5644.3  954.23  5664.3  954.14  5744.4  956.03  5837.2  957.48
#Mann=3,-1,0
  4794.6    0.15       0  5001.8    0.05       0  5005.8    0.15       0
Bank Sta=5001.8,5005.8
Exp/Cntr=0.3,0.1

Type RM Length L Ch R = 1,12251,397,397,397
BEGIN DESCRIPTION:
MDW T 002 24.0
END DESCRIPTION:
XS GIS Cut Line= 3
      2263338.69      7120521.83      2262795.83      7120243.40
      2262293.36      7120118.36
#Sta/Elev= 30
  4389.9  952.53  4400.0  952.53  4405.6  951.54  4422.2  951.77  4427.8  950.66
  4444.4  950.72  4450.0  948.93  4516.6  949.36  4524.4  950.22  4569.4  949.91
  4591.9  948.48  4760.8  945.45  4771.7  944.77  4777.3  943.36  4805.4  944.63
  4860.5  942.79  4910.5  942.76  4954.9  943.56  4971.5  944.94  4977.1  944.70
  4991.7  940.40  4991.9  939.90  4995.4  939.90  4995.7  940.40  5007.0  944.00
  5027.7  945.85  5116.4  948.82  5264.7  950.23  5460.5  955.84  5517.8  956.95
#Mann=3,-1,0
  4389.9    0.15       0  4991.7    0.05       0  4995.7    0.15       0
Bank Sta=4991.7,4995.7
Exp/Cntr=0.3,0.1

Type RM Length L Ch R = 1,11854,111,111,111
BEGIN DESCRIPTION:
Mapping XS d5cd425d
END DESCRIPTION:
XS GIS Cut Line= 2
      2263431.45      7119966.11      2262612.43      7119954.28
#Sta/Elev= 30
  4567.2  949.36  4589.6  948.83  4629.7  946.81  4644.3  946.66  4659.7  945.71
  4719.7  943.42  4749.7  942.68  4789.7  942.79  4809.7  942.30  4839.7  943.01
  4869.7  942.19  4909.7  941.68  4929.7  940.96  4949.7  941.04  4969.7  941.72
  4989.7  941.02  5007.7  939.43  5007.9  938.93  5011.4  938.93  5011.7  939.43
  5019.7  941.34  5029.7  942.29  5069.7  942.29  5109.7  943.68  5149.7  944.02
  5279.7  946.58  5309.7  947.59  5335.6  948.95  5340.6  948.30  5386.3  949.86
#Mann=3,-1,0
  4567.2    0.15       0  5007.7    0.05       0  5011.7    0.15       0
Bank Sta=5007.7,5011.7
Exp/Cntr=0.3,0.1

Type RM Length L Ch R = 1,11743,442,442,442
BEGIN DESCRIPTION:
MDW T 002 23.0
END DESCRIPTION:
XS GIS Cut Line= 3
      2263652.30      7119871.89      2263047.84      7119865.60
      2262387.14      7119853.45
#Sta/Elev= 30
  4398.6  957.71  4431.9  956.93  4451.9  955.40  4471.9  954.69  4611.9  950.50
  4751.9  945.45  4771.9  945.34  4811.9  943.36  4821.9  943.38  4841.9  941.75
  4861.9  941.16  4911.9  941.30  4921.9  940.71  4961.9  940.92  4998.0  938.59
  4998.3  938.09  5001.8  938.09  5002.0  938.59  5011.9  939.02  5021.9  940.57
  5036.4  941.05  5061.9  940.52  5081.9  940.85  5192.0  944.15  5242.0  944.64
  5282.0  946.36  5372.0  948.07  5578.3  954.97  5642.0  956.39  5663.9  957.50
#Mann=3,-1,0
  4398.6    0.15       0  4998.0    0.05       0  5002.0    0.15       0
Bank Sta=4998,5002
Exp/Cntr=0.3,0.1

Type RM Length L Ch R = 1,11301,481,481,481
BEGIN DESCRIPTION:
MDW T 002 22.0
END DESCRIPTION:
XS GIS Cut Line= 3
      2263630.34      7119485.43      2263211.63      7119464.96
      2262589.76      7119448.53
#Sta/Elev= 30
  4579.7  958.44  4592.2  958.18  4631.1  955.58  4731.2  950.85  4801.3  949.41
  4851.4  947.18  4911.4  943.60  4921.4  942.42  4931.5  944.88  4951.5  940.60
  4971.5  939.87  4981.5  937.77  4991.5  932.56  5000.5  931.77  5000.9  931.27
  5004.5  931.27  5004.9  931.77  5011.5  934.59  5031.6  939.33  5051.6  937.61
  5061.6  937.39  5091.6  938.53  5131.6  938.15  5311.7  939.53  5376.4  941.73
  5401.7  943.48  5411.7  943.22  5461.7  944.94  5501.7  947.36  5621.0  951.42
#Mann=3,-1,0
  4579.7    0.15       0  5000.5    0.05       0  5004.9    0.15       0
Bank Sta=5000.5,5004.9
Exp/Cntr=0.3,0.1

Type RM Length L Ch R = 1,10820,117,117,117
BEGIN DESCRIPTION:
MDW T 002 21.0
END DESCRIPTION:
XS GIS Cut Line= 3
      2263360.46      7118872.83      2263052.07      7119040.94
      2262636.46      7119341.61
#Sta/Elev= 30
  4643.9  946.30  4775.2  944.01  4873.0  937.54  4938.5  936.04  4966.0  933.09
  4982.1  930.60  4985.6  929.00  4986.0  928.50  4990.0  929.00  5003.6  929.55
  5024.5  934.67  5033.0  935.51  5039.2  934.67  5047.7  936.80  5068.6  937.92
  5083.3  938.33  5097.7  936.54  5110.3  936.96  5125.0  933.58  5169.1  931.91
  5190.0  934.08  5196.4  933.41  5204.7  935.16  5210.9  934.59  5240.3  938.74
  5269.7  940.15  5275.8  939.53  5290.5  941.59  5432.8  948.12  5508.1  949.84
#Mann=3,-1,0
  4643.9    0.15       0  4985.6    0.05       0  4990.0    0.15       0
Bank Sta=4985.6,4990
Exp/Cntr=0.3,0.1

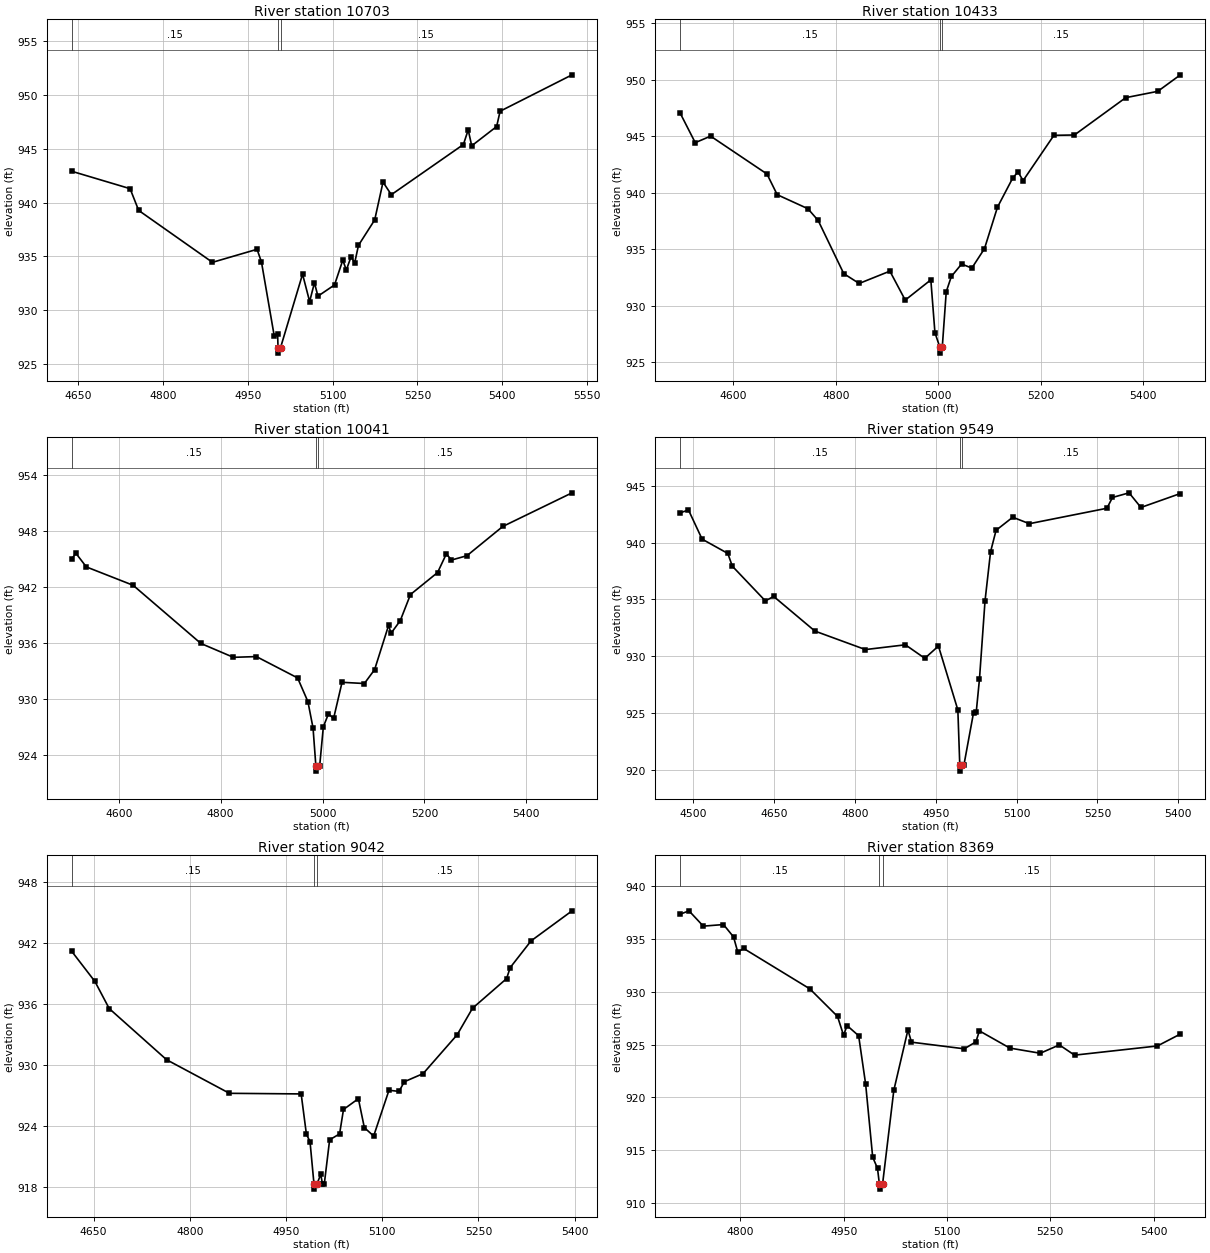
Type RM Length L Ch R = 1,10703,270,270,270
BEGIN DESCRIPTION:
MDW T 002 20.5
END DESCRIPTION:
XS GIS Cut Line= 3
      2263292.72      7118750.45      2262980.66      7118948.16
      2262563.45      7119251.58
#Sta/Elev= 30
  4638.2  942.91  4741.7  941.29  4756.9  939.27  4887.4  934.45  4966.3  935.66
  4974.1  934.48  4996.8  927.58  5002.7  927.75  5003.4  926.52  5003.8  926.02
  5007.8  926.52  5046.8  933.35  5059.3  930.81  5067.8  932.55  5074.0  931.31
  5103.3  932.35  5118.0  934.66  5124.2  933.73  5132.7  934.99  5138.9  934.38
  5145.7  936.03  5174.4  938.39  5189.1  941.90  5203.8  940.73  5331.3  945.39
  5339.8  946.75  5346.0  945.27  5390.1  947.06  5396.2  948.48  5523.5  951.86
#Mann=3,-1,0
  4638.2    0.15       0  5003.4    0.05       0  5007.8    0.15       0
Bank Sta=5003.4,5007.8
Exp/Cntr=0.3,0.1

Type RM Length L Ch R = 1,10433,392,392,392
BEGIN DESCRIPTION:
MDW T 002 20.0
END DESCRIPTION:
XS GIS Cut Line= 3
      2263429.02      7118685.34      2262927.99      7118699.44
      2262452.36      7118727.78
#Sta/Elev= 30
  4495.3  947.09  4525.3  944.43  4555.3  945.01  4665.4  941.66  4685.4  939.83
  4745.4  938.59  4765.4  937.55  4815.4  932.85  4845.5  931.98  4905.5  933.07
  4935.5  930.51  4985.5  932.30  4993.5  927.63  5003.3  926.32  5003.7  925.82
  5007.8  926.32  5015.6  931.25  5025.6  932.60  5045.6  933.70  5065.6  933.34
  5090.3  935.06  5115.7  938.73  5145.8  941.33  5155.8  941.84  5165.8  941.08
  5225.9  945.08  5266.0  945.11  5366.2  948.41  5428.8  948.97  5473.0  950.43
#Mann=3,-1,0
  4495.3    0.15       0  5003.3    0.05       0  5007.8    0.15       0
Bank Sta=5003.3,5007.8
Exp/Cntr=0.3,0.1

Type RM Length L Ch R = 1,10041,492,492,492
BEGIN DESCRIPTION:
MDW T 002 19.0
END DESCRIPTION:
XS GIS Cut Line= 3
      2263457.64      7118492.37      2262978.46      7118420.19
      2262483.80      7118366.08
#Sta/Elev= 30
  4507.5  945.03  4516.2  945.62  4536.5  944.17  4628.3  942.20  4761.2  935.96
  4825.1  934.47  4870.2  934.55  4951.1  932.26  4971.3  929.72  4981.4  926.89
  4987.0  922.76  4987.5  922.26  4991.6  922.76  4994.3  922.76  5001.6  927.02
  5011.7  928.41  5021.7  927.91  5038.3  931.79  5082.1  931.66  5102.2  933.15
  5129.6  937.89  5134.6  937.06  5152.5  938.40  5172.6  941.21  5225.8  943.57
  5243.0  945.57  5253.1  944.91  5283.3  945.37  5353.7  948.51  5489.7  952.12
#Mann=3,-1,0
  4507.5    0.15       0  4987.0    0.05       0  4991.6    0.15       0
Bank Sta=4987,4991.6
Exp/Cntr=0.3,0.1

Type RM Length L Ch R = 1,9549,507,507,507
BEGIN DESCRIPTION:
MDW T 002 18.0
END DESCRIPTION:
XS GIS Cut Line= 3
      2263532.58      7118229.08      2263040.36      7118050.94
      2262646.42      7117957.21
#Sta/Elev= 30
  4475.5  942.61  4491.4  942.87  4516.7  940.30  4564.4  939.04  4572.7  937.92
  4634.0  934.86  4649.5  935.25  4725.9  932.20  4819.6  930.57  4893.8  930.99
  4929.8  929.80  4955.1  930.88  4991.1  925.25  4994.7  920.36  4995.2  919.86
  4999.3  920.36  5002.2  920.36  5020.2  925.01  5025.3  925.11  5031.2  927.97
  5041.5  934.86  5051.8  939.19  5062.0  941.08  5092.9  942.23  5123.7  941.66
  5267.6  943.02  5277.9  943.97  5308.7  944.38  5330.7  943.09  5403.9  944.32
#Mann=3,-1,0
  4475.5    0.15       0  4994.7    0.05       0  4999.3    0.15       0
Bank Sta=4994.7,4999.3
Exp/Cntr=0.3,0.1

Type RM Length L Ch R = 1,9042,673,673,673
BEGIN DESCRIPTION:
MDW T 002 17.0
END DESCRIPTION:
XS GIS Cut Line= 3
      2263629.04      7117860.02      2263279.23      7117684.93
      2262919.95      7117535.76
#Sta/Elev= 30
  4615.7  941.21  4652.1  938.22  4674.4  935.55  4763.8  930.51  4861.8  927.20
  4973.6  927.14  4981.8  923.16  4987.4  922.45  4993.6  918.26  4994.1  917.76
  4998.3  918.26  5004.1  919.22  5006.8  918.29  5009.7  918.29  5018.0  922.62
  5033.5  923.20  5039.6  925.61  5062.8  926.67  5072.1  923.82  5086.6  922.99
  5110.5  927.50  5126.2  927.39  5134.4  928.34  5163.7  929.14  5216.8  932.97
  5240.7  935.58  5293.8  938.50  5299.5  939.59  5332.0  942.22  5395.9  945.18
#Mann=3,-1,0
  4615.7    0.15       0  4993.6    0.05       0  4998.3    0.15       0
Bank Sta=4993.6,4998.3
Exp/Cntr=0.3,0.1

Type RM Length L Ch R = 1,8369,442,442,442
BEGIN DESCRIPTION:
Mapping XS 21700586
END DESCRIPTION:
XS GIS Cut Line= 4
      2263724.23      7117813.11      2263575.99      7117703.51
      2263502.69      7117363.04      2263353.36      7117238.77
#Sta/Elev= 30
  4712.0  937.35  4725.2  937.68  4746.0  936.23  4775.3  936.38  4789.9  935.21
  4796.1  933.76  4804.5  934.12  4900.7  930.29  4940.9  927.68  4949.7  925.89
  4954.8  926.81  4971.6  925.85  4981.8  921.25  4992.0  914.35  4999.0  913.29
  5001.7  911.82  5002.2  911.32  5006.4  911.82  5022.7  920.68  5043.2  926.40
  5048.3  925.24  5125.0  924.61  5141.9  925.27  5147.0  926.31  5191.2  924.68
  5235.4  924.19  5263.1  924.98  5285.2  924.01  5405.5  924.88  5438.9  926.01
#Mann=3,-1,0
  4712.0    0.15       0  5001.7    0.05       0  5006.4    0.15       0
Bank Sta=5001.7,5006.4
Exp/Cntr=0.3,0.1

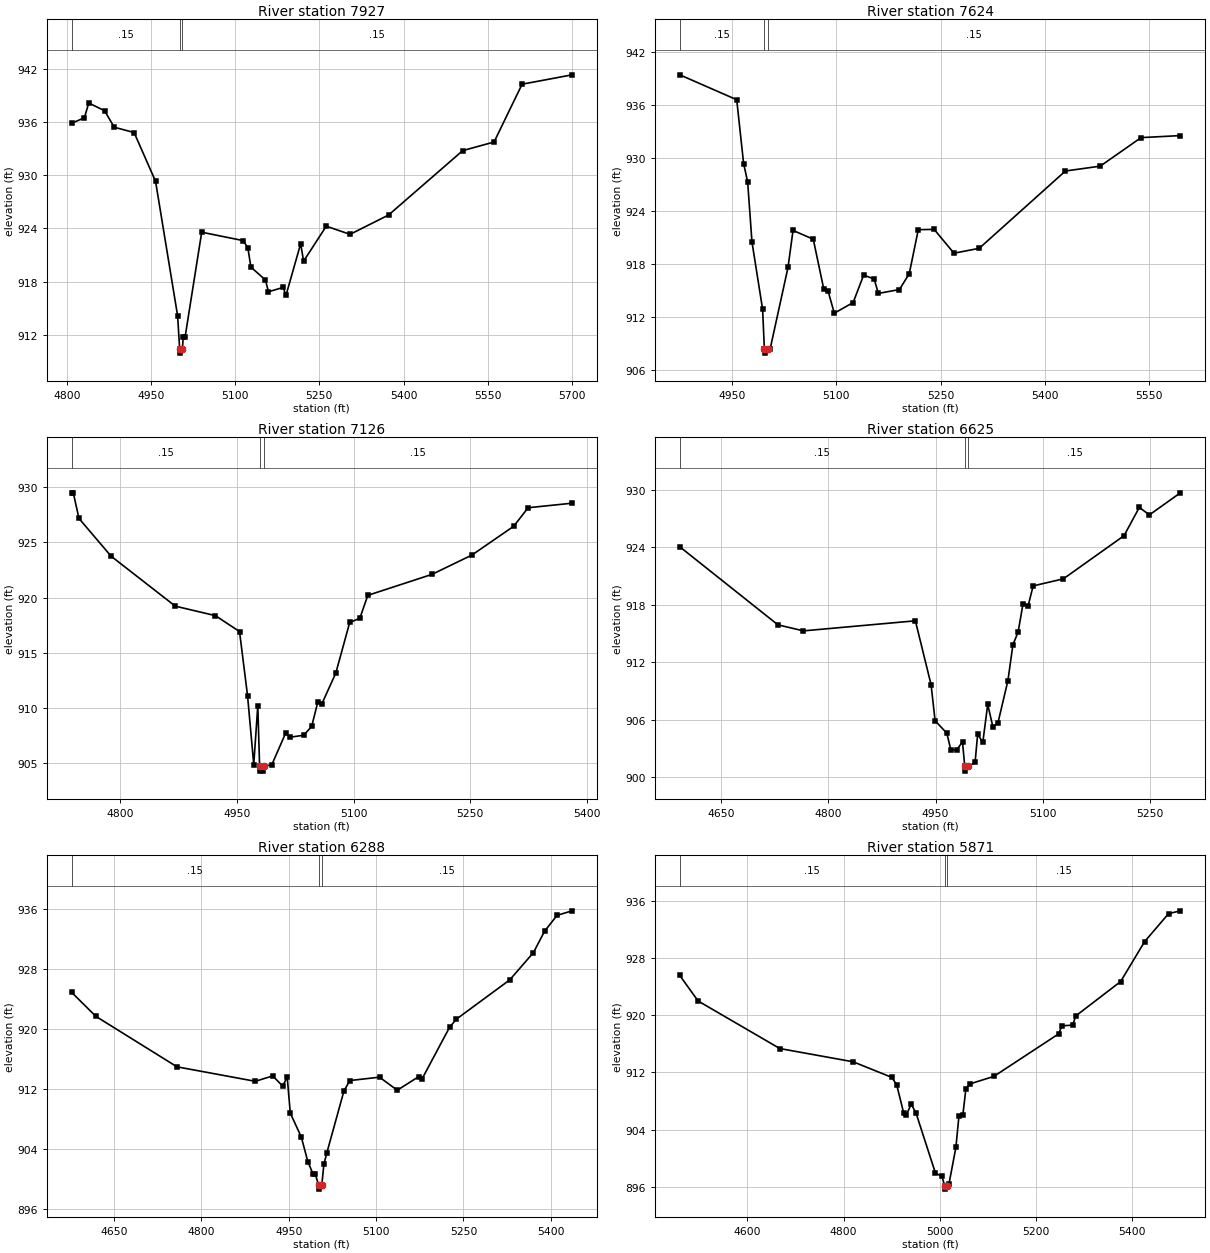
Type RM Length L Ch R = 1,7927,303,303,303
BEGIN DESCRIPTION:
MDW T 002 16.0
END DESCRIPTION:
XS GIS Cut Line= 3
      2263909.56      7117349.14      2263727.16      7117262.19
      2263074.55      7117039.27
#Sta/Elev= 30
  4808.6  935.89  4831.4  936.50  4839.2  938.18  4867.4  937.30  4884.6  935.44
  4920.0  934.84  4958.2  929.33  4997.5  914.13  5001.1  910.42  5001.8  909.92
  5006.1  910.42  5007.4  911.70  5010.7  911.70  5040.4  923.58  5114.4  922.63
  5122.7  921.80  5128.0  919.64  5154.0  918.18  5159.3  916.85  5185.3  917.34
  5190.6  916.46  5216.7  922.28  5221.9  920.31  5262.3  924.26  5304.6  923.34
  5373.2  925.52  5505.4  932.80  5561.2  933.77  5611.1  940.30  5700.3  941.36
#Mann=3,-1,0
  4808.6    0.15       0  5001.1    0.05       0  5006.1    0.15       0
Bank Sta=5001.1,5006.1
Exp/Cntr=0.3,0.1

Type RM Length L Ch R = 1,7624,498,498,498
BEGIN DESCRIPTION:
MDW T 002 15.0
END DESCRIPTION:
XS GIS Cut Line= 3
      2263988.57      7117073.98      2263879.00      7117010.00
      2263382.42      7116686.93
#Sta/Elev= 30
  4875.3  939.39  4957.1  936.57  4967.0  929.35  4972.8  927.27  4979.0  920.47
  4994.3  912.84  4996.8  908.38  4997.4  907.88  5001.8  908.38  5005.2  908.38
  5030.8  917.59  5038.0  921.77  5067.1  920.78  5082.2  915.12  5088.2  914.96
  5097.3  912.40  5124.4  913.61  5139.5  916.72  5154.7  916.26  5160.6  914.64
  5190.9  915.08  5205.0  916.87  5218.0  921.86  5240.8  921.89  5269.3  919.19
  5305.6  919.75  5429.4  928.50  5479.4  929.05  5538.1  932.28  5594.6  932.51
#Mann=3,-1,0
  4875.3    0.15       0  4996.8    0.05       0  5001.8    0.15       0
Bank Sta=4996.8,5001.8
Exp/Cntr=0.3,0.1

Type RM Length L Ch R = 1,7126,501,501,501
BEGIN DESCRIPTION:
MDW T 002 14.0
END DESCRIPTION:
XS GIS Cut Line= 3
      2264218.24      7116623.89      2263979.03      7116562.58
      2263594.13      7116465.91
#Sta/Elev= 30
  4737.2  929.49  4739.4  929.49  4746.7  927.17  4788.0  923.75  4870.6  919.22
  4922.2  918.36  4953.2  916.92  4963.5  911.12  4971.5  904.87  4976.7  910.19
  4979.0  904.77  4979.7  904.27  4983.5  904.27  4984.1  904.77  4994.5  904.81
  5012.6  907.73  5017.8  907.34  5035.7  907.52  5046.0  908.32  5053.8  910.51
  5058.9  910.34  5077.0  913.15  5094.9  917.74  5107.9  918.12  5118.2  920.20
  5200.7  922.10  5252.3  923.86  5305.8  926.46  5324.4  928.14  5381.0  928.55
#Mann=3,-1,0
  4737.2    0.15       0  4979.0    0.05       0  4984.1    0.15       0
Bank Sta=4979,4984.1
Exp/Cntr=0.3,0.1

Type RM Length L Ch R = 1,6625,337,337,337
BEGIN DESCRIPTION:
MDW T 002 13.0
END DESCRIPTION:
XS GIS Cut Line= 3
      2264342.07      7116400.91      2263979.10      7116209.34
      2263770.14      7116007.42
#Sta/Elev= 30
  4591.9  924.03  4729.3  915.89  4765.0  915.26  4921.8  916.31  4943.8  909.64
  4949.4  905.89  4965.8  904.59  4971.5  902.85  4979.8  902.85  4987.8  903.70
  4990.9  901.13  4991.6  900.63  4996.0  901.13  5005.4  901.53  5009.0  904.49
  5016.2  903.62  5023.1  907.59  5030.3  905.26  5037.3  905.62  5051.4  910.08
  5058.4  913.82  5065.6  915.12  5072.5  918.06  5079.7  917.88  5086.7  919.95
  5129.1  920.69  5214.0  925.19  5235.4  928.14  5249.5  927.36  5292.9  929.66
#Mann=3,-1,0
  4591.9    0.15       0  4990.9    0.05       0  4996.0    0.15       0
Bank Sta=4990.9,4996
Exp/Cntr=0.3,0.1

Type RM Length L Ch R = 1,6288,417,417,417
BEGIN DESCRIPTION:
MDW T 002 12.5
END DESCRIPTION:
XS GIS Cut Line= 3
      2264376.79      7116388.94      2264227.78      7115997.97
      2263793.56      7115917.07
#Sta/Elev= 30
  4576.8  924.88  4618.5  921.67  4758.0  914.93  4892.4  913.00  4922.5  913.72
  4939.5  912.36  4947.3  913.56  4952.6  908.76  4971.6  905.54  4982.7  902.29
  4991.4  900.68  4995.2  900.68  5001.5  899.11  5002.2  898.61  5006.7  899.11
  5010.3  901.91  5015.4  903.45  5044.8  911.72  5055.0  913.10  5105.9  913.55
  5136.4  911.81  5173.6  913.64  5178.7  913.28  5226.3  920.21  5238.1  921.30
  5329.6  926.53  5370.3  930.17  5389.6  933.04  5411.0  935.15  5436.9  935.75
#Mann=3,-1,0
  4576.8    0.15       0  5001.5    0.05       0  5006.7    0.15       0
Bank Sta=5001.5,5006.7
Exp/Cntr=0.3,0.1

Type RM Length L Ch R = 1,5871,561,561,561
BEGIN DESCRIPTION:
MDW T 002 12.0
END DESCRIPTION:
XS GIS Cut Line= 3
      2264399.10      7116387.89      2264335.06      7115851.87
      2264030.09      7115454.30
#Sta/Elev= 30
  4459.3  925.53  4497.4  921.97  4667.3  915.33  4819.7  913.48  4900.3  911.30
  4910.4  910.24  4924.6  906.39  4930.5  906.08  4940.6  907.58  4950.7  906.28
  4990.9  897.93  5004.3  897.49  5010.0  896.20  5010.7  895.70  5015.2  896.20
  5018.9  896.39  5033.4  901.52  5039.7  905.88  5047.9  906.07  5054.2  909.70
  5062.4  910.39  5112.3  911.44  5247.3  917.39  5253.6  918.50  5276.3  918.60
  5282.6  919.88  5376.0  924.69  5425.9  930.27  5475.7  934.17  5500.2  934.56
#Mann=3,-1,0
  4459.3    0.15       0  5010.0    0.05       0  5015.2    0.15       0
Bank Sta=5010,5015.2
Exp/Cntr=0.3,0.1