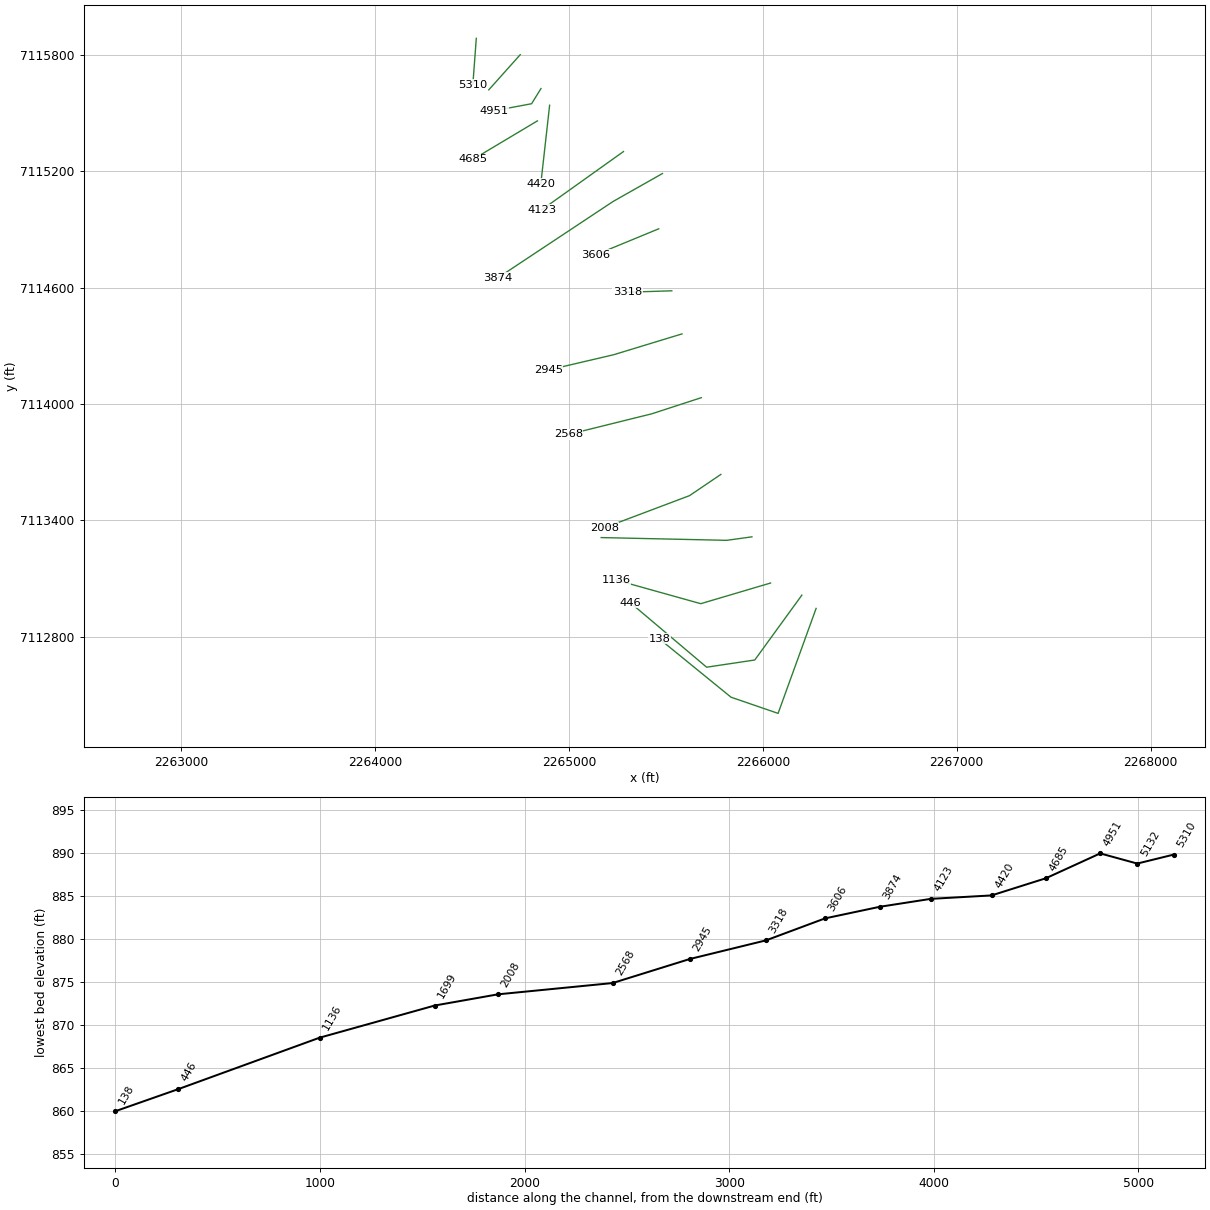
HEC-RAS study MDW T 002.prj: MDW T 002 Base Level Engineering

--- MDW T 002.g01 (geometry) --- (continued)

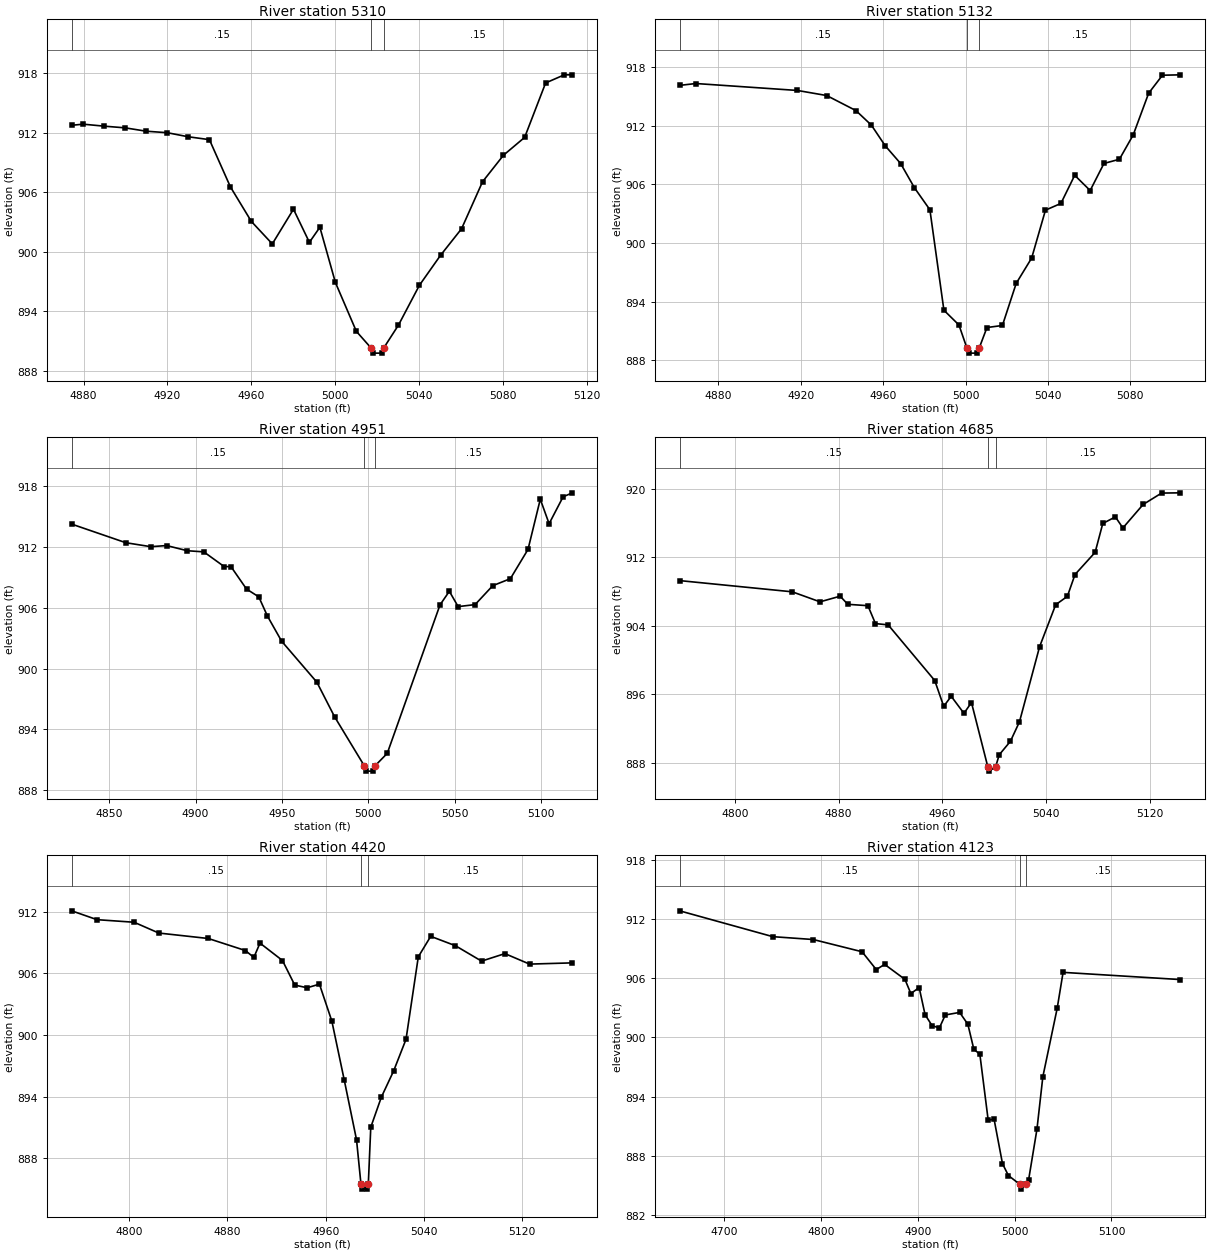
Type RM Length L Ch R = 1,5310,178,178,178
BEGIN DESCRIPTION:
Mapping XS c61d865e
END DESCRIPTION:
XS GIS Cut Line= 2
      2264522.65      7115885.47      2264504.83      7115647.24
#Sta/Elev= 30
  4874.3  912.75  4879.8  912.86  4889.8  912.66  4899.8  912.49  4909.9  912.15
  4919.9  912.00  4929.9  911.59  4940.0  911.30  4950.0  906.54  4960.0  903.05
  4970.0  900.78  4980.1  904.28  4987.7  900.94  4992.7  902.46  5000.1  896.89
  5010.1  891.96  5017.2  890.26  5018.2  889.76  5022.2  889.76  5023.1  890.26
  5030.2  892.59  5040.2  896.61  5050.3  899.64  5060.3  902.31  5070.3  907.05
  5080.3  909.73  5090.4  911.53  5100.4  917.02  5109.3  917.84  5113.2  917.84
#Mann=3,-1,0
  4874.3    0.15       0  5017.2    0.05       0  5023.1    0.15       0
Bank Sta=5017.2,5023.1
Exp/Cntr=0.3,0.1

Type RM Length L Ch R = 1,5132,181,181,181
BEGIN DESCRIPTION:
Mapping XS a7fe72a5
END DESCRIPTION:
XS GIS Cut Line= 2
      2264749.12      7115801.04      2264586.99      7115619.89
#Sta/Elev= 30
  4861.2  916.12  4869.1  916.31  4918.4  915.60  4932.6  915.08  4946.8  913.54
  4954.3  912.05  4961.0  909.94  4968.5  908.12  4975.2  905.64  4982.7  903.39
  4989.5  893.11  4996.8  891.60  5000.7  889.22  5001.7  888.72  5005.7  888.72
  5006.6  889.22  5010.4  891.34  5017.9  891.55  5024.6  895.86  5032.1  898.45
  5038.8  903.35  5046.3  904.04  5053.0  906.92  5060.5  905.36  5067.2  908.13
  5074.7  908.56  5081.4  911.05  5088.9  915.32  5095.6  917.16  5104.3  917.20
#Mann=3,-1,0
  4861.2    0.15       0  5000.7    0.05       0  5006.6    0.15       0
Bank Sta=5000.7,5006.6
Exp/Cntr=0.3,0.1

Type RM Length L Ch R = 1,4951,266,266,266
BEGIN DESCRIPTION:
Mapping XS 9c0b4790
END DESCRIPTION:
XS GIS Cut Line= 3
      2264856.25      7115626.67      2264807.84      7115548.33
      2264613.71      7115511.95
#Sta/Elev= 30
  4828.4  914.21  4859.7  912.38  4874.1  911.99  4883.3  912.10  4895.3  911.59
  4904.8  911.48  4916.6  910.03  4920.5  910.03  4929.5  907.82  4936.6  907.05
  4941.6  905.16  4949.8  902.69  4970.2  898.65  4980.4  895.26  4997.7  890.40
  4998.7  889.90  5002.7  889.90  5003.7  890.40  5010.9  891.65  5041.4  906.26
  5046.8  907.60  5051.9  906.09  5061.7  906.29  5071.9  908.15  5082.1  908.84
  5092.3  911.72  5099.4  916.66  5104.5  914.25  5112.6  916.90  5118.0  917.29
#Mann=3,-1,0
  4828.4    0.15       0  4997.7    0.05       0  5003.7    0.15       0
Bank Sta=4997.7,5003.7
Exp/Cntr=0.3,0.1

Type RM Length L Ch R = 1,4685,265,265,265
BEGIN DESCRIPTION:
Mapping XS a8b6f346
END DESCRIPTION:
XS GIS Cut Line= 2
      2264837.81      7115459.88      2264506.52      7115262.00
#Sta/Elev= 30
  4757.5  909.26  4844.3  907.95  4865.7  906.78  4881.2  907.44  4887.1  906.49
  4902.6  906.33  4908.4  904.24  4918.2  904.09  4954.1  897.59  4961.0  894.58
  4966.8  895.75  4976.6  893.76  4982.4  895.02  4995.0  887.51  4996.0  887.01
  5001.0  887.51  5003.8  888.92  5012.4  890.49  5019.4  892.77  5034.9  901.54
  5047.3  906.44  5056.3  907.42  5062.2  909.97  5077.7  912.56  5083.6  915.93
  5093.3  916.70  5099.1  915.41  5114.7  918.15  5128.9  919.48  5143.4  919.51
#Mann=3,-1,0
  4757.5    0.15       0  4995.0    0.05       0  5001.0    0.15       0
Bank Sta=4995,5001
Exp/Cntr=0.3,0.1

Type RM Length L Ch R = 1,4420,297,297,297
BEGIN DESCRIPTION:
Mapping XS 422a5e69
END DESCRIPTION:
XS GIS Cut Line= 2
      2264900.73      7115540.49      2264855.32      7115135.33
#Sta/Elev= 30
  4753.2  912.08  4773.8  911.22  4804.0  910.97  4824.1  909.92  4864.4  909.39
  4894.6  908.22  4901.5  907.55  4906.5  908.94  4924.8  907.25  4934.8  904.86
  4944.9  904.60  4954.9  904.95  4965.0  901.36  4975.1  895.63  4985.1  889.82
  4988.7  885.52  4989.7  885.02  4993.7  885.02  4994.7  885.52  4996.7  891.04
  5005.3  893.96  5015.3  896.51  5025.4  899.59  5035.4  907.61  5045.5  909.60
  5065.6  908.69  5086.9  907.19  5105.9  907.92  5126.0  906.90  5160.9  907.02
#Mann=3,-1,0
  4753.2    0.15       0  4988.7    0.05       0  4994.7    0.15       0
Bank Sta=4988.7,4994.7
Exp/Cntr=0.3,0.1

Type RM Length L Ch R = 1,4123,249,249,249
BEGIN DESCRIPTION:
Mapping XS f6ee3e08
END DESCRIPTION:
XS GIS Cut Line= 2
      2265281.44      7115301.61      2264860.18      7115001.21
#Sta/Elev= 30
  4653.8  912.84  4750.1  910.22  4791.9  909.93  4842.3  908.69  4857.0  906.88
  4865.6  907.41  4886.6  905.89  4892.7  904.45  4901.3  905.06  4907.4  902.31
  4914.7  901.19  4922.2  900.97  4928.3  902.28  4943.1  902.54  4951.6  901.34
  4957.8  898.80  4964.0  898.30  4972.6  891.62  4978.7  891.71  4987.4  887.20
  4993.5  886.00  5005.1  885.12  5006.2  884.62  5011.3  885.12  5014.4  885.57
  5023.0  890.69  5029.1  896.02  5043.9  902.95  5050.0  906.60  5171.2  905.87
#Mann=3,-1,0
  4653.8    0.15       0  5005.1    0.05       0  5011.3    0.15       0
Bank Sta=5005.1,5011.3
Exp/Cntr=0.3,0.1

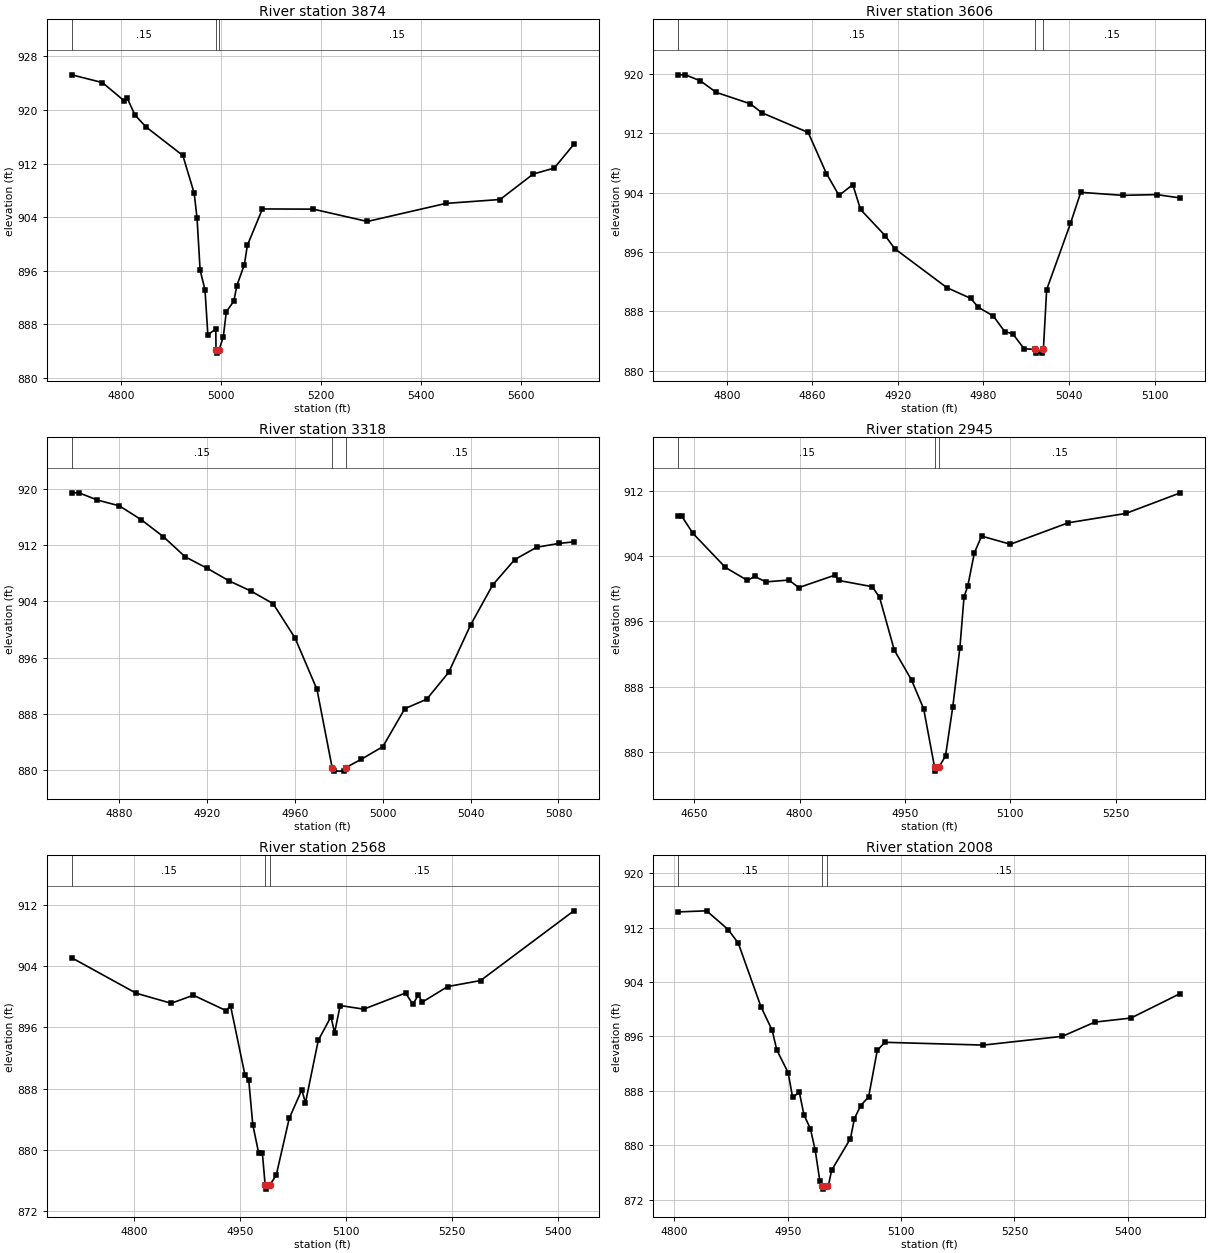
Type RM Length L Ch R = 1,3874,268,268,268
BEGIN DESCRIPTION:
MDW T 002 8.0
END DESCRIPTION:
XS GIS Cut Line= 3
      2265482.31      7115188.23      2265228.03      7115044.28
      2264634.80      7114651.08
#Sta/Elev= 30
  4701.0  925.24  4762.3  924.08  4805.8  921.36  4811.5  921.82  4827.4  919.24
  4849.0  917.49  4923.1  913.20  4945.8  907.56  4951.5  903.84  4957.6  896.11
  4967.4  893.14  4973.1  886.45  4989.0  887.27  4989.4  884.20  4990.4  883.70
  4995.6  884.20  5004.0  886.14  5010.0  889.87  5025.1  891.47  5031.1  893.77
  5046.1  896.92  5052.1  899.79  5082.2  905.22  5184.0  905.19  5292.0  903.35
  5449.2  906.05  5557.4  906.63  5623.6  910.43  5665.7  911.32  5704.9  914.87
#Mann=3,-1,0
  4701.0    0.15       0  4989.4    0.05       0  4995.6    0.15       0
Bank Sta=4989.4,4995.6
Exp/Cntr=0.3,0.1

Type RM Length L Ch R = 1,3606,288,288,288
BEGIN DESCRIPTION:
Mapping XS fa3e2bd3
END DESCRIPTION:
XS GIS Cut Line= 2
      2265463.20      7114903.32      2265137.78      7114769.12
#Sta/Elev= 30
  4766.0  919.87  4771.0  919.87  4781.4  919.07  4792.7  917.50  4816.6  915.96
  4824.6  914.76  4857.1  912.10  4869.9  906.56  4878.7  903.62  4888.4  905.06
  4893.8  901.72  4911.2  898.16  4917.8  896.43  4954.4  891.17  4971.0  889.74
  4976.5  888.51  4986.9  887.36  4995.0  885.22  5000.4  884.99  5008.5  882.94
  5015.8  882.85  5016.8  882.35  5021.0  882.35  5022.0  882.85  5024.3  890.91
  5041.0  899.84  5048.2  904.03  5077.6  903.62  5101.5  903.72  5118.0  903.27
#Mann=3,-1,0
  4766.0    0.15       0  5015.8    0.05       0  5022.0    0.15       0
Bank Sta=5015.8,5022
Exp/Cntr=0.3,0.1

Type RM Length L Ch R = 1,3318,373,373,373
BEGIN DESCRIPTION:
Mapping XS a9bccfe8
END DESCRIPTION:
XS GIS Cut Line= 2
      2265530.65      7114583.62      2265302.07      7114576.44
#Sta/Elev= 28
  4858.3  919.48  4861.6  919.48  4870.0  918.45  4880.0  917.62  4890.0  915.64
  4900.0  913.23  4910.0  910.35  4920.0  908.72  4930.0  906.92  4940.0  905.46
  4950.0  903.68  4960.0  898.79  4970.0  891.44  4976.9  880.30  4977.9  879.80
  4982.1  879.80  4983.1  880.30  4990.0  881.46  5000.0  883.29  5010.0  888.70
  5020.0  890.06  5030.0  893.89  5040.0  900.66  5050.0  906.33  5060.1  909.97
  5070.1  911.72  5080.1  912.26  5087.0  912.49
#Mann=3,-1,0
  4858.3    0.15       0  4976.9    0.05       0  4983.1    0.15       0
Bank Sta=4976.9,4983.1
Exp/Cntr=0.3,0.1

Type RM Length L Ch R = 1,2945,377,377,377
BEGIN DESCRIPTION:
MDW T 002 6.0
END DESCRIPTION:
XS GIS Cut Line= 3
      2265583.18      7114361.38      2265231.14      7114254.03
      2264893.49      7114175.10
#Sta/Elev= 30
  4627.1  908.94  4631.9  908.94  4648.1  906.80  4694.2  902.63  4725.6  901.03
  4736.0  901.52  4751.8  900.85  4784.6  901.08  4798.7  900.15  4850.2  901.68
  4855.5  901.03  4903.3  900.26  4913.7  898.96  4934.7  892.48  4959.2  888.82
  4976.5  885.28  4992.0  878.13  4993.0  877.63  4998.3  878.13  5007.6  879.48
  5017.9  885.47  5028.1  892.78  5034.0  899.03  5039.2  900.29  5048.7  904.42
  5059.0  906.47  5100.0  905.47  5182.2  908.10  5264.3  909.25  5341.9  911.78
#Mann=3,-1,0
  4627.1    0.15       0  4992.0    0.05       0  4998.3    0.15       0
Bank Sta=4992,4998.3
Exp/Cntr=0.3,0.1

Type RM Length L Ch R = 1,2568,560,560,560
BEGIN DESCRIPTION:
MDW T 002 5.0
END DESCRIPTION:
XS GIS Cut Line= 3
      2265683.05      7114032.62      2265428.06      7113949.52
      2264997.29      7113842.73
#Sta/Elev= 30
  4711.1  905.12  4802.5  900.48  4852.1  899.17  4883.6  900.22  4930.1  898.20
  4936.2  898.87  4956.8  889.73  4962.1  889.07  4967.8  883.29  4976.2  879.53
  4981.4  879.53  4985.4  875.34  4986.5  874.84  4991.8  875.34  5001.1  876.69
  5019.5  884.11  5037.3  887.83  5042.5  886.13  5060.7  894.33  5078.7  897.41
  5083.8  895.30  5091.7  898.87  5125.2  898.40  5184.4  900.51  5194.7  899.06
  5202.8  900.25  5208.0  899.31  5244.2  901.36  5290.8  902.14  5423.1  911.27
#Mann=3,-1,0
  4711.1    0.15       0  4985.4    0.05       0  4991.8    0.15       0
Bank Sta=4985.4,4991.8
Exp/Cntr=0.3,0.1

Type RM Length L Ch R = 1,2008,309,309,309
BEGIN DESCRIPTION:
MDW T 002 4.0
END DESCRIPTION:
XS GIS Cut Line= 3
      2265783.82      7113636.89      2265622.15      7113527.44
      2265183.07      7113361.84
#Sta/Elev= 30
  4805.0  914.33  4842.5  914.49  4871.2  911.72  4884.5  909.72  4914.4  900.40
  4929.4  896.88  4935.4  894.02  4950.4  890.69  4956.4  887.03  4965.3  887.78
  4971.4  884.45  4979.9  882.42  4986.3  879.26  4992.4  874.74  4995.9  874.03
  4996.9  873.53  5002.4  874.03  5003.7  874.03  5008.0  876.30  5032.9  880.97
  5038.2  883.91  5046.3  885.79  5057.0  887.12  5068.4  893.94  5078.4  895.14
  5208.8  894.73  5313.5  896.02  5356.3  898.11  5404.1  898.71  5469.5  902.32
#Mann=3,-1,0
  4805.0    0.15       0  4995.9    0.05       0  5002.4    0.15       0
Bank Sta=4995.9,5002.4
Exp/Cntr=0.3,0.1

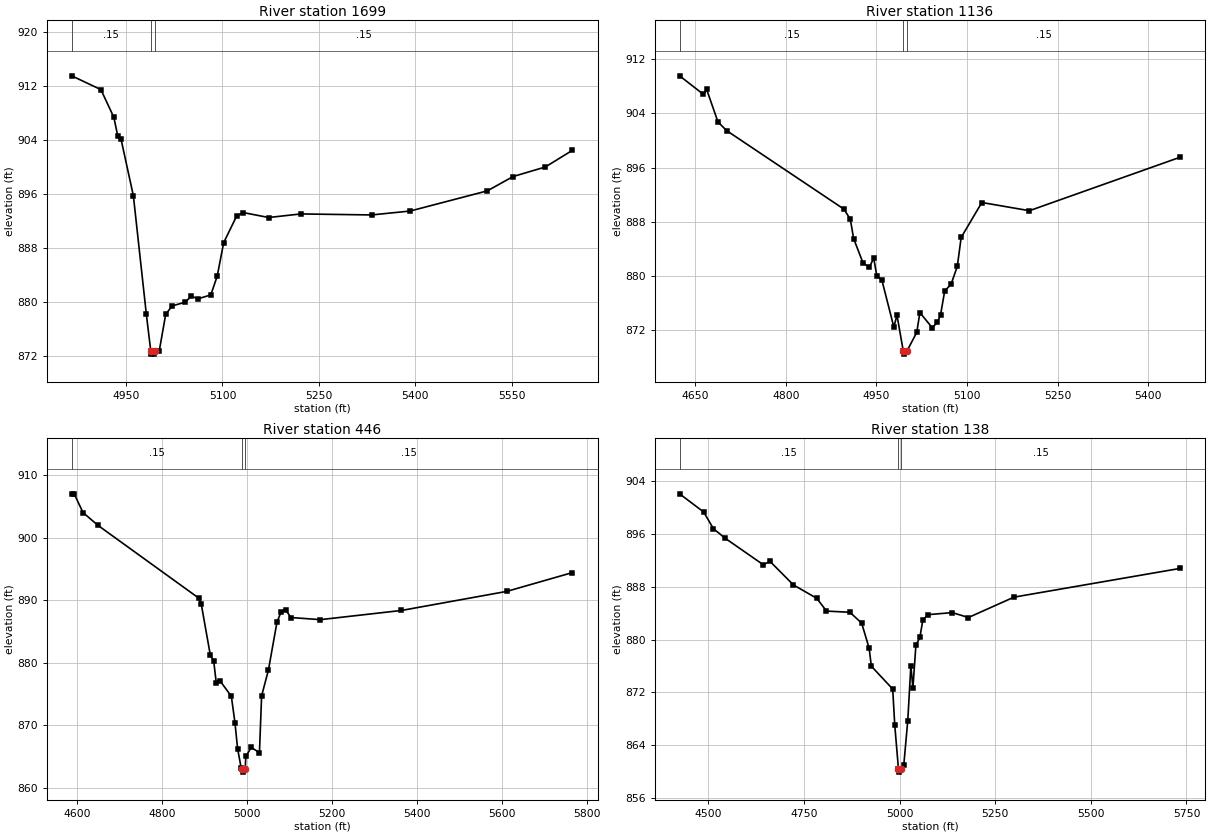
Type RM Length L Ch R = 1,1699,563,563,563
BEGIN DESCRIPTION:
MDW T 002 3.0
END DESCRIPTION:
XS GIS Cut Line= 3
      2265943.99      7113314.98      2265813.98      7113296.98
      2265166.59      7113311.17
#Sta/Elev= 30
  4865.5  913.46  4910.9  911.42  4931.1  907.30  4937.2  904.50  4942.3  904.04
  4961.4  895.69  4981.6  878.11  4988.4  872.73  4989.5  872.23  4993.9  872.23
  4994.9  872.73  5001.7  872.73  5011.7  878.14  5021.7  879.37  5041.7  879.92
  5051.7  880.82  5061.7  880.42  5081.8  881.00  5091.8  883.79  5101.8  888.73
  5121.8  892.65  5131.8  893.21  5171.8  892.47  5221.8  893.00  5331.8  892.85
  5391.8  893.43  5511.9  896.42  5551.9  898.54  5601.9  899.95  5644.3  902.43
#Mann=3,-1,0
  4865.5    0.15       0  4988.4    0.05       0  4994.9    0.15       0
Bank Sta=4988.4,4994.9
Exp/Cntr=0.3,0.1

Type RM Length L Ch R = 1,1136,690,690,690
BEGIN DESCRIPTION:
MDW T 002 2.0
END DESCRIPTION:
XS GIS Cut Line= 3
      2266039.91      7113076.81      2265679.99      7112970.27
      2265243.48      7113092.28
#Sta/Elev= 30
  4624.3  909.53  4663.8  906.79  4669.0  907.54  4687.8  902.73  4702.3  901.44
  4896.4  889.86  4906.8  888.37  4912.3  885.52  4927.7  881.97  4938.1  881.27
  4945.5  882.64  4950.8  879.97  4959.0  879.41  4978.8  872.48  4984.0  874.24
  4994.3  868.99  4995.4  868.49  5000.8  868.99  5016.7  871.70  5021.9  874.61
  5042.2  872.40  5050.9  873.16  5056.1  874.29  5063.0  877.82  5073.4  878.77
  5083.8  881.43  5090.2  885.70  5124.4  890.85  5203.1  889.64  5452.9  897.54
#Mann=3,-1,0
  4624.3    0.15       0  4994.3    0.05       0  5000.8    0.15       0
Bank Sta=4994.3,5000.8
Exp/Cntr=0.3,0.1

Type RM Length L Ch R = 1,446,308,308,308
BEGIN DESCRIPTION:
MDW T 002 1.0
END DESCRIPTION:
XS GIS Cut Line= 4
      2266201.34      7113014.31      2265958.62      7112679.93
      2265710.26      7112642.79      2265316.56      7112975.55
#Sta/Elev= 30
  4587.0  907.02  4592.8  907.02  4613.7  904.02  4649.2  901.96  4885.8  890.37
  4892.0  889.47  4913.6  881.21  4921.4  880.35  4927.5  876.83  4936.0  877.16
  4963.1  874.64  4971.6  870.43  4977.8  866.28  4986.3  863.18  4989.2  863.02
  4990.3  862.52  4995.8  863.02  4997.1  865.02  5009.9  866.47  5029.3  865.64
  5034.4  874.71  5050.4  878.83  5070.6  886.51  5080.7  888.20  5090.8  888.47
  5103.6  887.24  5172.7  886.90  5363.7  888.37  5612.0  891.42  5766.8  894.43
#Mann=3,-1,0
  4587.0    0.15       0  4989.2    0.05       0  4995.8    0.15       0
Bank Sta=4989.2,4995.8
Exp/Cntr=0.3,0.1

Type RM Length L Ch R = 1,138,0,0,0
BEGIN DESCRIPTION:
MDW T 002 0.5
END DESCRIPTION:
XS GIS Cut Line= 4
      2266274.84      7112945.96      2266078.80      7112404.67
      2265836.04      7112488.08      2265466.27      7112789.28
#Sta/Elev= 30
  4424.7  902.03  4487.7  899.28  4513.0  896.77  4543.7  895.32  4643.7  891.30
  4660.9  891.83  4722.2  888.26  4783.4  886.23  4808.8  884.30  4870.0  884.12
  4900.7  882.48  4920.3  878.69  4926.0  875.97  4981.9  872.51  4987.3  867.01
  4996.9  860.45  4998.0  859.95  5003.5  860.45  5010.8  860.99  5021.3  867.75
  5029.4  876.07  5034.7  872.65  5042.5  879.11  5053.0  880.34  5060.7  882.96
  5074.2  883.76  5137.6  884.07  5179.9  883.33  5299.1  886.41  5734.0  890.76
#Mann=3,-1,0
  4424.7    0.15       0  4996.9    0.05       0  5003.5    0.15       0
Bank Sta=4996.9,5003.5
Exp/Cntr=0.3,0.1

Chan Stop Cuts=-1