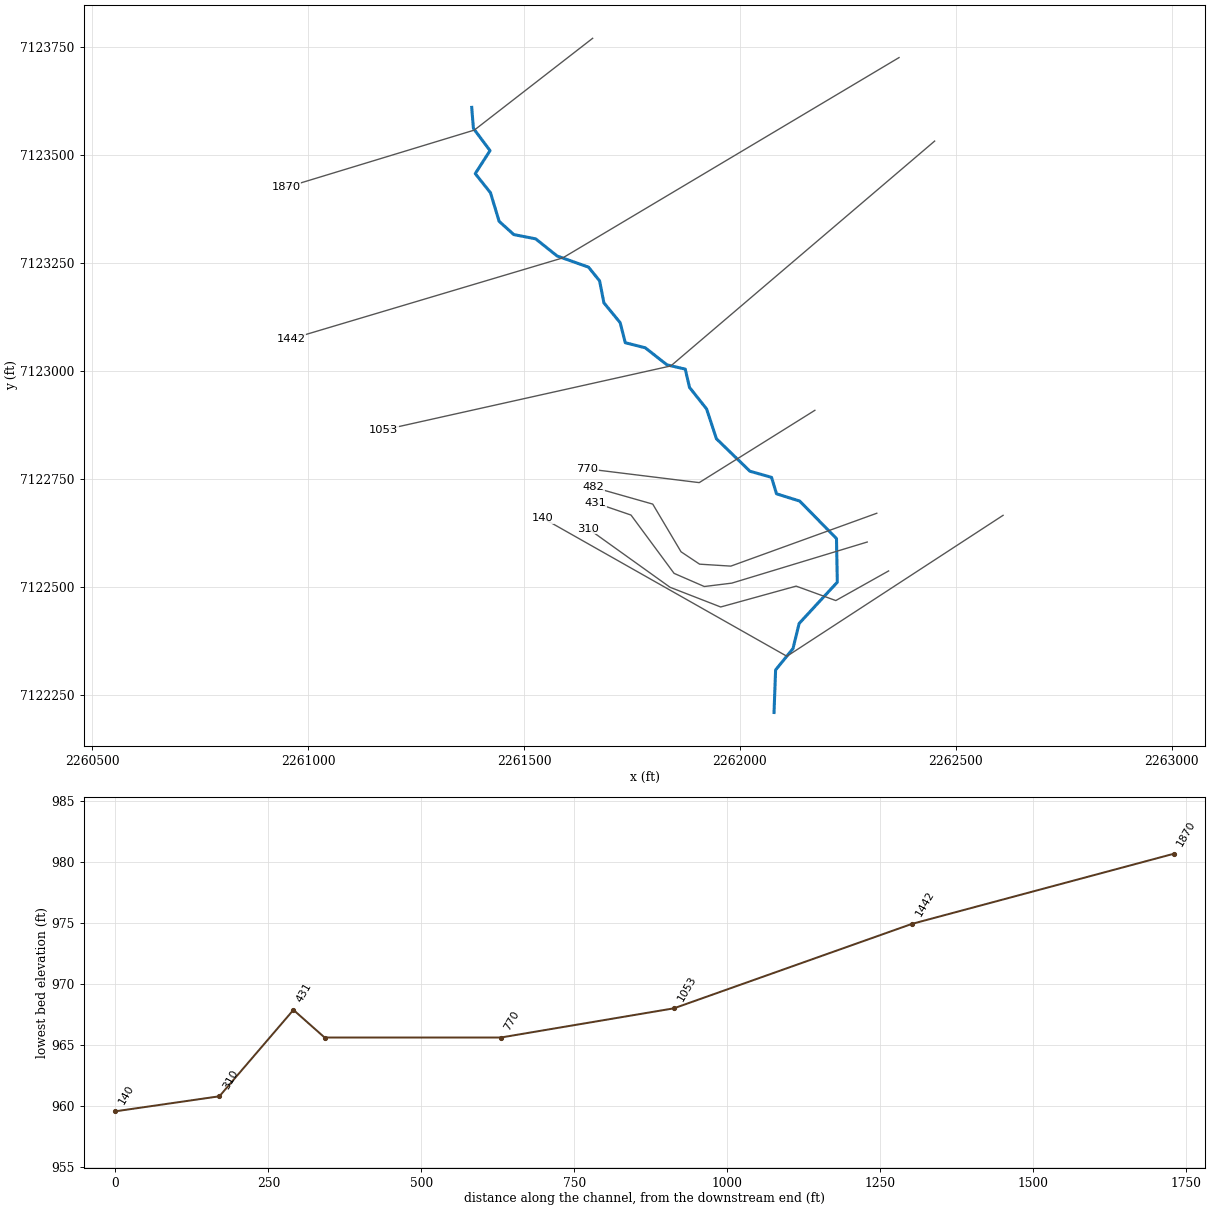
--- MDW T 003.prj (project) ---

Proj Title=MDW T 003 Base Level Engineering
Current Plan=p01
Default Exp/Contr=0.3,0.1
English Units
Geom File=g01
Flow File=f01
Plan File=p01
BEGIN DESCRIPTION:
MDW T 003
END DESCRIPTION:

--- MDW T 003.p01 (plan) ---

Plan Title=Multiple Run
Short Identifier=Multiple
Geom File=g01
Flow File=f01
Subcritical Flow
K Sum by GR= 0
Std Step Tol= 0.01
Critical Tol= 0.01
Num of Std Step Trials= 20
Max Error Tol= 0.3
Flow Tol Ratio= 0.001
Split Flow NTrial= 30
Split Flow Tol= 0.02
Split Flow Ratio= 0.02
Log Output Level= 0
Friction Slope Method= 1
Unsteady Friction Slope Method= 2
Unsteady Bridges Friction Slope Method= 1
Parabolic Critical Depth
Global Vel Dist=  1 , 1 , 1
Global Log Level= 0
CheckData=True
Encroach Param= -1, 0, 0, 0
BEGIN DESCRIPTION:
Multiple Run
END DESCRIPTION:

--- MDW T 003.f01 (steady flow) ---

Flow Title=Multiple
Number of Profiles=7
Profile Names=10-year,25-year,50-year,1pct_min,100-year,1pct_plu,500-year
River Rch & RM= MDW T 003,Reach-1,1870
     205     261     305     177     354     706     475
Boundary for River Rch & Prof#=MDW T 003,Reach-1,1
Up Type=0
Dn Type=3
Dn Slope=0.005
Boundary for River Rch & Prof#=MDW T 003,Reach-1,2
Up Type=0
Dn Type=3
Dn Slope=0.005
Boundary for River Rch & Prof#=MDW T 003,Reach-1,3
Up Type=0
Dn Type=3
Dn Slope=0.005
Boundary for River Rch & Prof#=MDW T 003,Reach-1,4
Up Type=0
Dn Type=3
Dn Slope=0.005
Boundary for River Rch & Prof#=MDW T 003,Reach-1,5
Up Type=0
Dn Type=3
Dn Slope=0.005
Boundary for River Rch & Prof#=MDW T 003,Reach-1,6
Up Type=0
Dn Type=3
Dn Slope=0.005
Boundary for River Rch & Prof#=MDW T 003,Reach-1,7
Up Type=0
Dn Type=3
Dn Slope=0.005

--- MDW T 003.g01 (geometry) ---

Geom Title=Existing Conditions

River Reach=MDW T 003,Reach-1
Reach XY= 30
      2261379.00      7123610.00      2261382.98      7123561.36
      2261421.43      7123509.94      2261387.22      7123456.77
      2261422.59      7123412.27      2261442.46      7123346.44
      2261476.45      7123315.73      2261527.24      7123305.80
      2261576.84      7123266.11      2261649.48      7123240.38
      2261675.14      7123208.58      2261685.10      7123157.80
      2261722.76      7123111.85      2261734.58      7123065.58
      2261780.89      7123053.77      2261831.07      7123014.33
      2261873.42      7123004.42      2261883.34      7122962.10
      2261922.91      7122912.22      2261945.63      7122843.29
      2262023.21      7122768.23      2262073.23      7122754.02
      2262084.77      7122715.98      2262138.46      7122699.16
      2262223.61      7122612.44      2262225.53      7122511.50
      2262137.16      7122416.05      2262122.89      7122357.82
      2262082.63      7122308.50      2262079.00      7122210.00

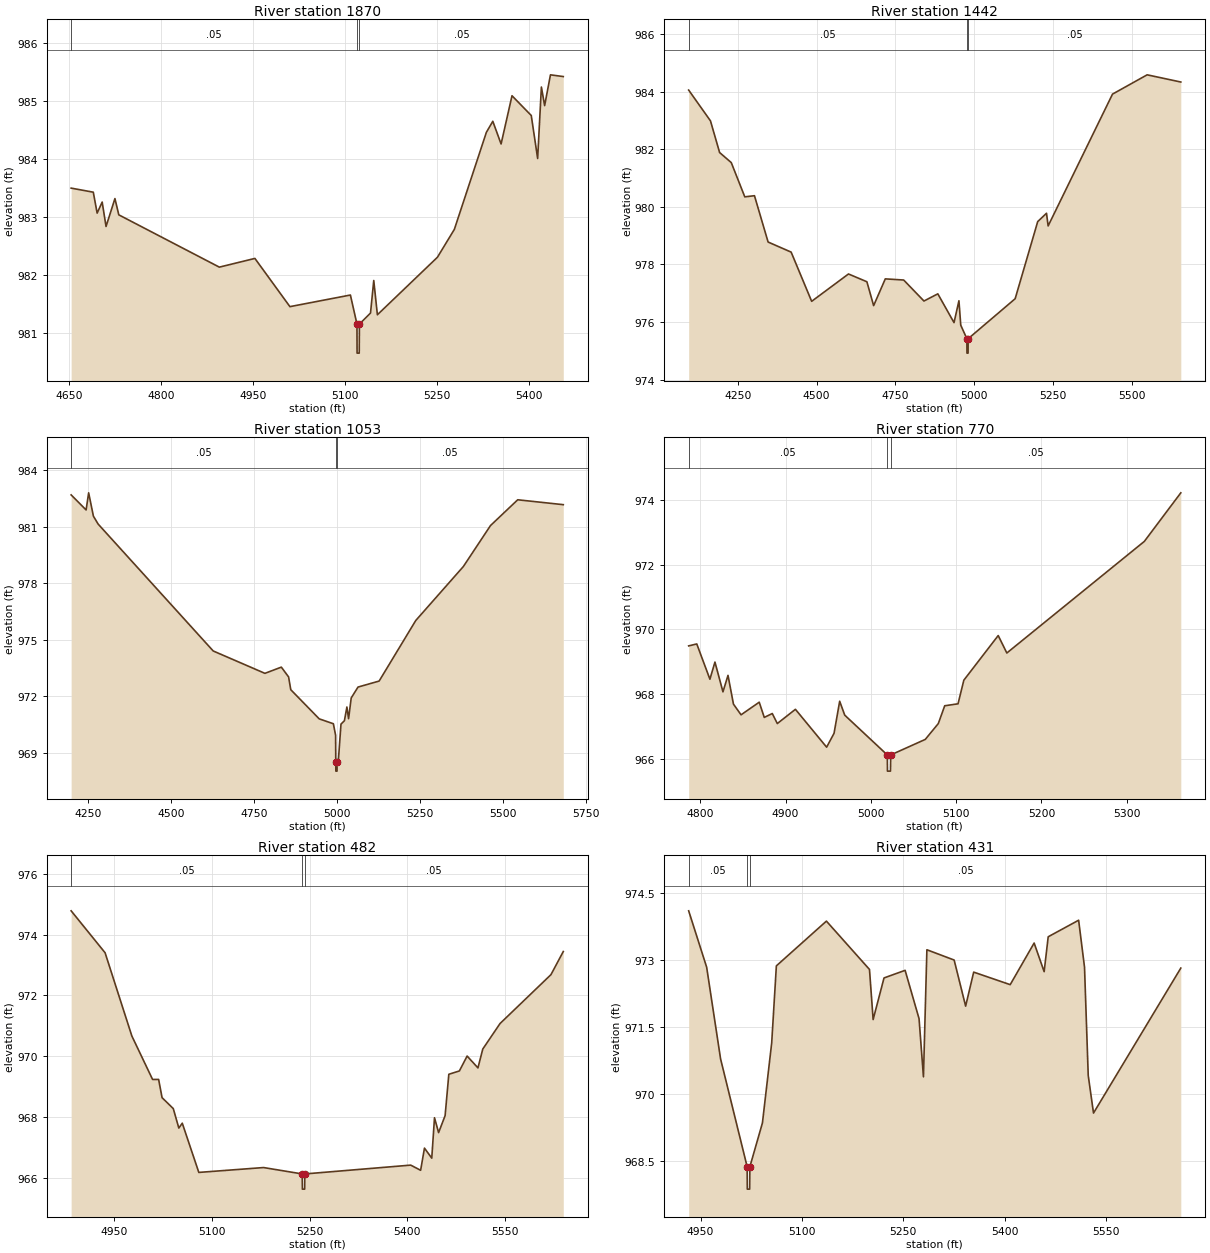
Type RM Length L Ch R = 1,1870,428,428,428
BEGIN DESCRIPTION:
MDW T 003 4.0
END DESCRIPTION:
XS GIS Cut Line= 3
      2261659.05      7123769.84      2261385.12      7123557.48
      2260949.04      7123424.87
#Sta/Elev= 30
  4653.4  983.50  4689.5  983.43  4695.8  983.07  4704.0  983.26  4710.3  982.84
  4724.8  983.32  4731.1  983.04  4895.0  982.14  4953.0  982.29  5010.1  981.46
  5108.7  981.66  5119.4  981.16  5119.6  980.66  5123.1  980.66  5123.4  981.16
  5141.5  981.35  5146.8  981.91  5152.7  981.32  5250.6  982.31  5278.2  982.79
  5330.4  984.46  5340.9  984.65  5354.4  984.26  5372.2  985.09  5403.6  984.75
  5414.0  984.01  5420.1  985.24  5425.4  984.92  5434.9  985.45  5455.8  985.42
#Mann=3,-1,0
  4653.4    0.05       0  5119.4    0.04       0  5123.4    0.05       0
Bank Sta=5119.4,5123.4
Exp/Cntr=0.3,0.1

Type RM Length L Ch R = 1,1442,389,389,389
BEGIN DESCRIPTION:
MDW T 003 3.0
END DESCRIPTION:
XS GIS Cut Line= 3
      2262368.45      7123725.21      2261589.75      7123261.72
      2260961.43      7123074.58
#Sta/Elev= 30
  4093.8  984.06  4163.0  982.99  4192.0  981.89  4229.0  981.54  4271.9  980.35
  4302.6  980.39  4345.9  978.78  4419.0  978.43  4484.1  976.72  4601.0  977.67
  4659.4  977.40  4680.8  976.57  4717.8  977.50  4776.2  977.46  4840.5  976.73
  4884.5  976.98  4935.9  975.98  4951.5  976.74  4957.3  975.89  4976.7  975.42
  4977.0  974.92  4980.5  974.92  4980.7  975.42  5129.9  976.81  5201.5  979.49
  5229.4  979.78  5234.6  979.34  5438.9  983.92  5548.8  984.59  5655.6  984.34
#Mann=3,-1,0
  4093.8    0.05       0  4976.7    0.04       0  4980.7    0.05       0
Bank Sta=4976.7,4980.7
Exp/Cntr=0.3,0.1

Type RM Length L Ch R = 1,1053,283,283,283
BEGIN DESCRIPTION:
MDW T 003 2.0
END DESCRIPTION:
XS GIS Cut Line= 3
      2262450.88      7123532.04      2261840.07      7123011.85
      2261174.88      7122863.66
#Sta/Elev= 30
  4197.7  982.70  4242.8  981.90  4250.5  982.81  4264.8  981.57  4279.0  981.15
  4626.0  974.40  4781.9  973.21  4831.4  973.54  4853.3  973.02  4859.9  972.34
  4945.6  970.79  4988.3  970.53  4995.0  969.92  4995.6  968.51  4995.8  968.01
  4999.3  968.01  4999.6  968.51  5003.1  968.51  5011.3  970.51  5021.6  970.69
  5029.1  971.42  5034.2  970.80  5042.1  971.90  5062.6  972.48  5126.3  972.80
  5236.7  976.02  5380.2  978.89  5462.1  981.07  5544.1  982.44  5681.5  982.18
#Mann=3,-1,0
  4197.7    0.05       0  4995.6    0.04       0  4999.6    0.05       0
Bank Sta=4995.6,4999.6
Exp/Cntr=0.3,0.1

Type RM Length L Ch R = 1,770,288,288,288
BEGIN DESCRIPTION:
MDW T 003 1.8
END DESCRIPTION:
XS GIS Cut Line= 3
      2262173.54      7122909.14      2261905.77      7122741.86
      2261646.65      7122773.71
#Sta/Elev= 30
  4786.5  969.49  4796.0  969.55  4811.4  968.46  4817.3  968.99  4826.7  968.07
  4832.6  968.58  4839.0  967.69  4847.9  967.36  4869.2  967.75  4875.1  967.28
  4884.5  967.40  4890.4  967.09  4911.6  967.53  4948.2  966.36  4956.9  966.79
  4963.5  967.78  4969.4  967.35  5019.3  966.12  5019.5  965.62  5023.0  965.62
  5023.3  966.12  5063.8  966.60  5079.1  967.09  5086.6  967.64  5102.2  967.70
  5109.0  968.43  5149.3  969.81  5159.4  969.27  5320.6  972.72  5363.3  974.22
#Mann=3,-1,0
  4786.5    0.05       0  5019.3    0.04       0  5023.3    0.05       0
Bank Sta=5019.3,5023.3
Exp/Cntr=0.3,0.1

Type RM Length L Ch R = 1,482,51,51,51
BEGIN DESCRIPTION:
MDW T 003 1.6
END DESCRIPTION:
XS GIS Cut Line= 6
      2262316.92      7122671.00      2261978.99      7122548.68
      2261906.62      7122553.20      2261863.66      7122581.84
      2261798.16      7122692.16      2261660.07      7122731.34
#Sta/Elev= 30
  4883.8  974.78  4935.9  973.40  4977.0  970.66  5008.8  969.23  5018.1  969.23
  5023.4  968.63  5040.6  968.27  5049.1  967.63  5054.4  967.79  5079.8  966.17
  5179.2  966.33  5238.5  966.12  5238.8  965.62  5242.3  965.62  5242.5  966.12
  5405.1  966.41  5420.3  966.24  5426.2  966.97  5437.4  966.64  5441.6  967.97
  5447.9  967.48  5457.9  968.04  5463.6  969.40  5479.8  969.51  5491.7  970.00
  5508.3  969.61  5515.7  970.23  5542.2  971.07  5620.4  972.68  5639.3  973.44
#Mann=3,-1,0
  4883.8    0.05       0  5238.5   0.033       0  5242.5    0.05       0
Bank Sta=5238.5,5242.5
Exp/Cntr=0.3,0.1

Type RM Length L Ch R = 1,431,121,121,121
BEGIN DESCRIPTION:
MDW T 003 1.4
END DESCRIPTION:
XS GIS Cut Line= 6
      2262294.81      7122604.43      2261981.10      7122509.31
      2261917.55      7122501.47      2261847.55      7122531.93
      2261747.85      7122666.82      2261664.70      7122695.24
#Sta/Elev= 30
  4932.5  974.10  4959.1  972.84  4979.7  970.79  5019.0  968.38  5019.2  967.88
  5022.7  967.88  5023.0  968.38  5041.6  969.36  5055.3  971.15  5062.2  972.87
  5136.2  973.87  5199.9  972.79  5205.3  971.67  5221.4  972.60  5252.6  972.77
  5273.2  971.69  5279.7  970.39  5284.8  973.23  5325.1  973.00  5342.1  971.97
  5354.0  972.73  5408.0  972.45  5443.4  973.38  5458.2  972.74  5464.2  973.52
  5509.2  973.89  5517.9  972.84  5523.4  970.42  5531.2  969.58  5660.3  972.82
#Mann=3,-1,0
  4932.5    0.05       0  5019.0   0.033       0  5023.0    0.05       0
Bank Sta=5019,5023
Exp/Cntr=0.3,0.1

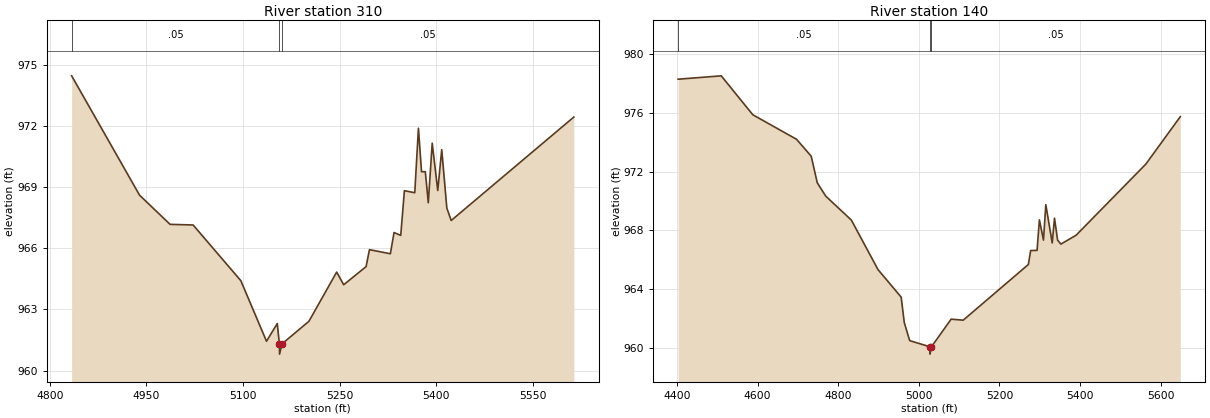
Type RM Length L Ch R = 1,310,170,170,170
BEGIN DESCRIPTION:
MDW T 003 1.2
END DESCRIPTION:
XS GIS Cut Line= 6
      2262344.27      7122537.52      2262221.99      7122469.01
      2262130.18      7122502.38      2261955.46      7122454.13
      2261838.26      7122499.71      2261648.52      7122635.41
#Sta/Elev= 30
  4833.9  974.45  4939.4  968.60  4986.8  967.17  5022.6  967.14  5096.7  964.41
  5136.6  961.44  5153.3  962.31  5156.6  961.31  5156.9  960.81  5160.6  961.31
  5202.5  962.42  5245.6  964.83  5256.5  964.21  5291.3  965.10  5296.5  965.93
  5329.0  965.73  5334.7  966.77  5345.1  966.63  5350.8  968.82  5366.9  968.72
  5372.6  971.88  5377.4  969.75  5383.3  969.75  5387.9  968.23  5394.0  971.15
  5402.6  968.83  5408.8  970.83  5416.7  967.97  5423.5  967.36  5614.0  972.43
#Mann=3,-1,0
  4833.9    0.05       0  5156.6    0.04       0  5160.6    0.05       0
Bank Sta=5156.6,5160.6
Exp/Cntr=0.3,0.1

Type RM Length L Ch R = 1,140,0,0,0
BEGIN DESCRIPTION:
MDW T 003 1.0
END DESCRIPTION:
XS GIS Cut Line= 3
      2262609.33      7122666.18      2262108.77      7122340.09
      2261543.87      7122659.60
#Sta/Elev= 30
  4402.6  978.29  4509.6  978.52  4588.0  975.87  4696.6  974.20  4732.9  973.05
  4748.0  971.24  4769.1  970.33  4832.6  968.70  4898.8  965.33  4956.2  963.46
  4963.9  961.73  4977.3  960.50  5027.4  960.08  5027.6  959.58  5031.4  960.08
  5080.2  961.96  5110.2  961.89  5271.9  965.68  5277.6  966.63  5293.5  966.64
  5299.3  968.72  5309.4  967.34  5315.2  969.75  5331.1  967.15  5336.8  968.83
  5344.4  967.34  5352.7  967.07  5390.3  967.67  5563.4  972.51  5649.0  975.74
#Mann=3,-1,0
  4402.6    0.05       0  5027.4    0.04       0  5031.4    0.05       0
Bank Sta=5027.4,5031.4
Exp/Cntr=0.3,0.1

Chan Stop Cuts=-1