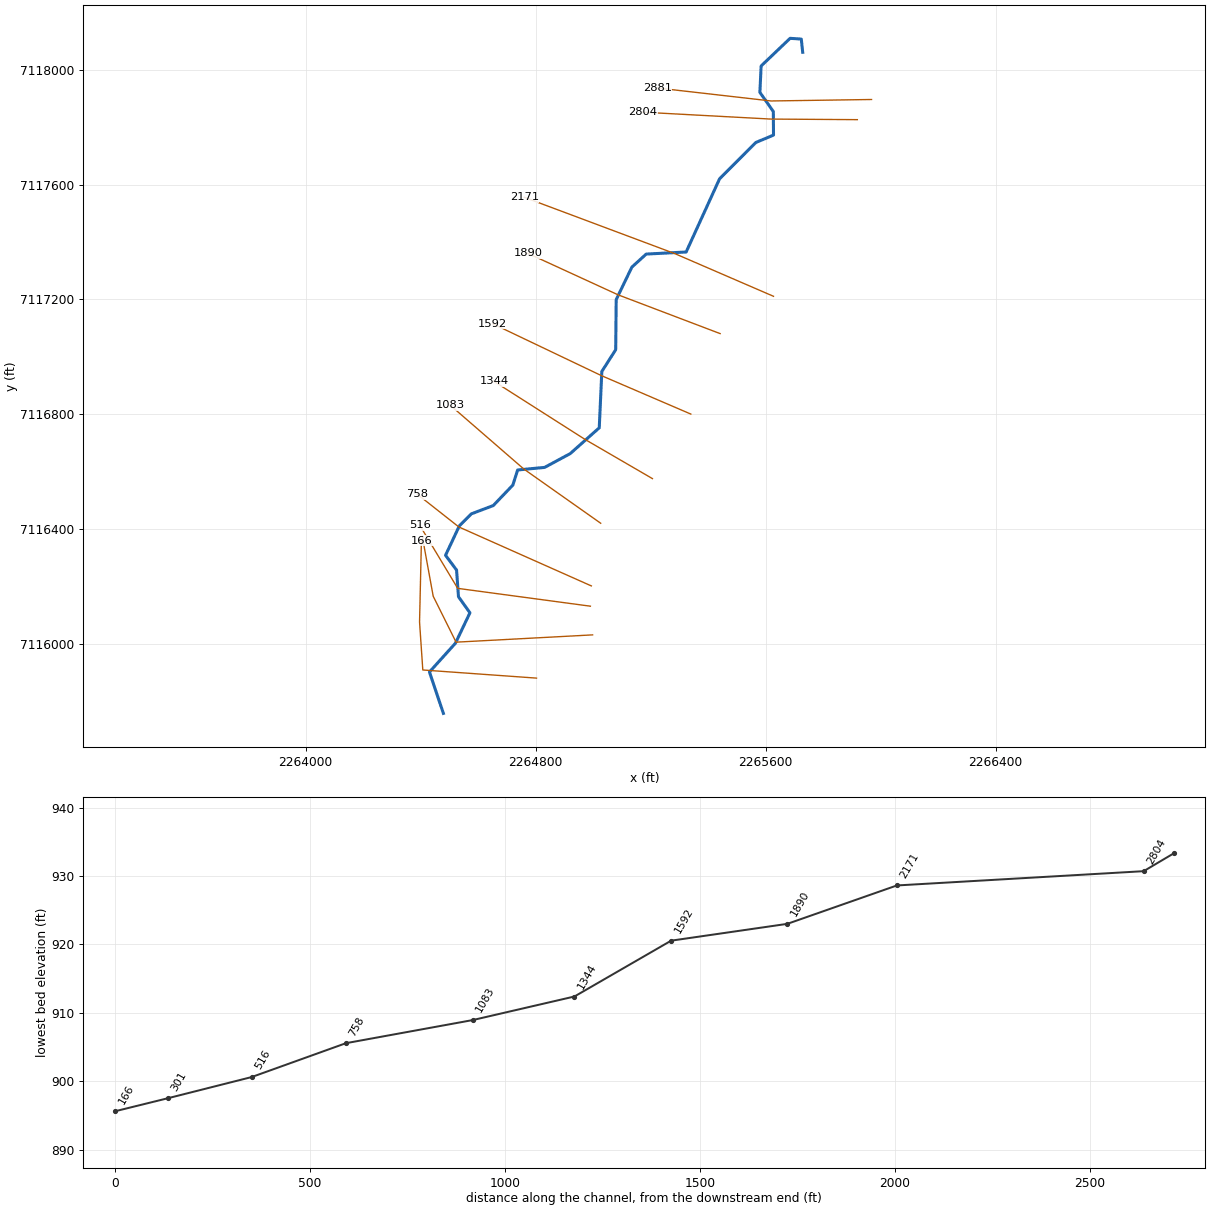
--- MDW T 004.prj (project) ---

Proj Title=MDW T 004 Base Level Engineering
Current Plan=p01
Default Exp/Contr=0.3,0.1
English Units
Geom File=g01
Flow File=f01
Plan File=p01
BEGIN DESCRIPTION:
MDW T 004
END DESCRIPTION:

--- MDW T 004.p01 (plan) ---

Plan Title=Multiple Run
Short Identifier=Multiple
Geom File=g01
Flow File=f01
Subcritical Flow
K Sum by GR= 0
Std Step Tol= 0.01
Critical Tol= 0.01
Num of Std Step Trials= 20
Max Error Tol= 0.3
Flow Tol Ratio= 0.001
Split Flow NTrial= 30
Split Flow Tol= 0.02
Split Flow Ratio= 0.02
Log Output Level= 0
Friction Slope Method= 1
Unsteady Friction Slope Method= 2
Unsteady Bridges Friction Slope Method= 1
Parabolic Critical Depth
Global Vel Dist=  1 , 1 , 1
Global Log Level= 0
CheckData=True
Encroach Param= -1, 0, 0, 0
BEGIN DESCRIPTION:
Multiple Run
END DESCRIPTION:

--- MDW T 004.f01 (steady flow) ---

Flow Title=Multiple
Number of Profiles=7
Profile Names=10-year,25-year,50-year,1pct_min,100-year,1pct_plu,500-year
River Rch & RM= MDW T 004,Reach-1,2881
     317     420     503     300     598    1193     846
Boundary for River Rch & Prof#=MDW T 004,Reach-1,1
Up Type=0
Dn Type=3
Dn Slope=0.005
Boundary for River Rch & Prof#=MDW T 004,Reach-1,2
Up Type=0
Dn Type=3
Dn Slope=0.005
Boundary for River Rch & Prof#=MDW T 004,Reach-1,3
Up Type=0
Dn Type=3
Dn Slope=0.005
Boundary for River Rch & Prof#=MDW T 004,Reach-1,4
Up Type=0
Dn Type=3
Dn Slope=0.005
Boundary for River Rch & Prof#=MDW T 004,Reach-1,5
Up Type=0
Dn Type=3
Dn Slope=0.005
Boundary for River Rch & Prof#=MDW T 004,Reach-1,6
Up Type=0
Dn Type=3
Dn Slope=0.005
Boundary for River Rch & Prof#=MDW T 004,Reach-1,7
Up Type=0
Dn Type=3
Dn Slope=0.005

--- MDW T 004.g01 (geometry) ---

Geom Title=Existing Conditions

River Reach=MDW T 004,Reach-1
Reach XY= 30
      2265729.00      7118060.00      2265724.08      7118106.07
      2265685.20      7118108.58      2265584.39      7118012.44
      2265580.10      7117920.55      2265626.87      7117853.94
      2265627.49      7117771.87      2265566.05      7117746.26
      2265439.76      7117619.68      2265323.59      7117365.18
      2265184.68      7117358.00      2265134.71      7117312.59
      2265080.20      7117199.50      2265078.48      7117025.22
      2265030.22      7116949.49      2265021.26      7116753.54
      2264920.38      7116663.84      2264831.30      7116615.78
      2264737.34      7116606.83      2264720.70      7116554.28
      2264652.51      7116483.00      2264576.46      7116454.25
      2264534.70      7116412.54      2264486.53      7116310.01
      2264524.91      7116258.50      2264531.55      7116165.90
      2264571.47      7116109.99      2264520.86      7116003.96
      2264430.60      7115903.97      2264479.00      7115760.00

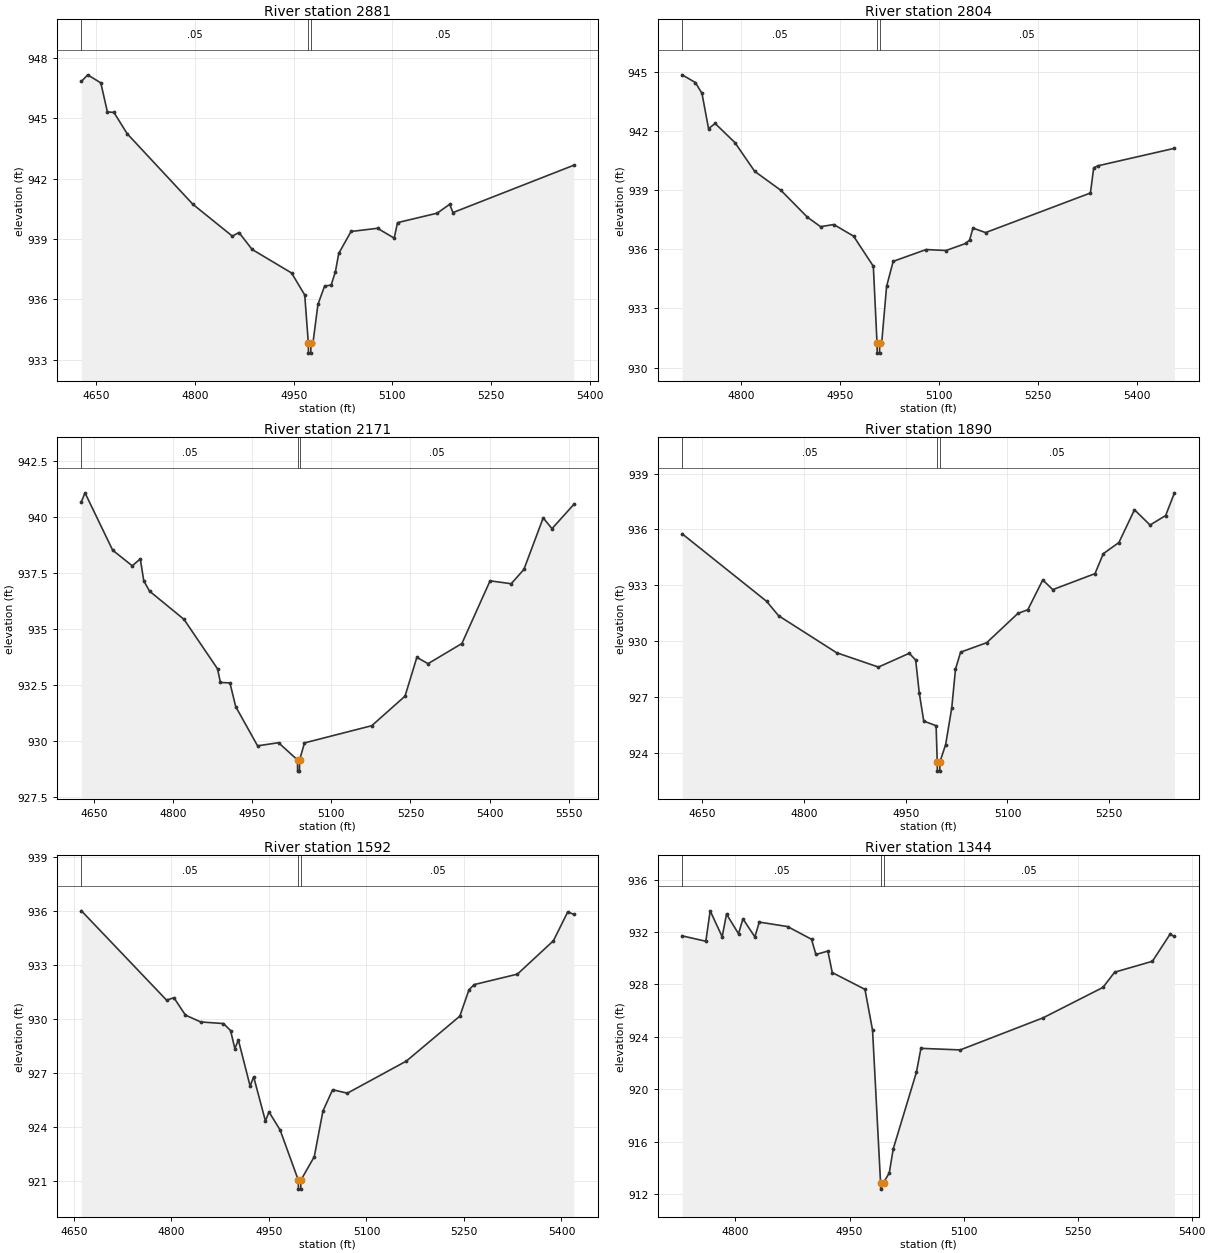
Type RM Length L Ch R = 1,2881,77,77,77
BEGIN DESCRIPTION:
MDW T 004 10.0
END DESCRIPTION:
XS GIS Cut Line= 3
      2265968.49      7117895.80      2265619.13      7117890.68
      2265222.61      7117935.93
#Sta/Elev= 30
  4627.3  946.82  4636.8  947.15  4656.8  946.75  4666.8  945.31  4676.8  945.28
  4696.8  944.23  4796.8  940.72  4856.8  939.14  4866.8  939.32  4886.8  938.48
  4946.8  937.31  4966.8  936.22  4972.3  933.83  4972.5  933.33  4976.0  933.33
  4976.3  933.83  4979.3  933.83  4986.9  935.75  4997.0  936.66  5007.0  936.71
  5013.5  937.38  5018.5  938.28  5037.2  939.37  5077.5  939.53  5102.8  939.04
  5107.9  939.81  5168.1  940.28  5187.2  940.72  5192.2  940.31  5375.8  942.66
#Mann=3,-1,0
  4627.3    0.05       0  4972.3   0.033       0  4976.3    0.05       0
Bank Sta=4972.3,4976.3
Exp/Cntr=0.3,0.1

Type RM Length L Ch R = 1,2804,633,633,633
BEGIN DESCRIPTION:
MDW T 004 9.0
END DESCRIPTION:
XS GIS Cut Line= 3
      2265919.13      7117825.67      2265618.87      7117827.65
      2265172.88      7117851.65
#Sta/Elev= 30
  4710.6  944.86  4730.7  944.47  4740.7  943.92  4750.7  942.13  4760.7  942.39
  4790.7  941.42  4820.7  939.96  4860.7  938.99  4900.7  937.63  4920.7  937.15
  4940.7  937.26  4970.7  936.67  5000.7  935.14  5006.3  931.23  5006.6  930.73
  5010.1  930.73  5010.3  931.23  5013.3  931.23  5020.8  934.12  5030.8  935.39
  5080.8  935.99  5110.9  935.94  5140.9  936.30  5146.8  936.48  5151.8  937.08
  5171.0  936.85  5330.0  938.86  5335.0  940.14  5341.2  940.24  5457.5  941.13
#Mann=3,-1,0
  4710.6    0.05       0  5006.3    0.04       0  5010.3    0.05       0
Bank Sta=5006.3,5010.3
Exp/Cntr=0.3,0.1

Type RM Length L Ch R = 1,2171,281,281,281
BEGIN DESCRIPTION:
MDW T 004 8.0
END DESCRIPTION:
XS GIS Cut Line= 3
      2265627.45      7117211.09      2265284.55      7117359.43
      2264760.46      7117555.58
#Sta/Elev= 30
  4626.4  940.67  4633.2  941.07  4685.6  938.51  4722.8  937.81  4738.0  938.12
  4744.6  937.14  4755.5  936.68  4820.8  935.42  4884.4  933.21  4889.9  932.60
  4907.9  932.58  4918.9  931.52  4960.3  929.77  5000.0  929.91  5036.0  929.14
  5036.2  928.64  5039.7  928.64  5040.0  929.14  5049.2  929.90  5176.8  930.67
  5239.8  931.99  5262.2  933.72  5283.5  933.44  5347.6  934.34  5401.0  937.14
  5441.1  937.01  5465.1  937.65  5501.7  939.95  5518.4  939.47  5559.6  940.55
#Mann=3,-1,0
  4626.4    0.05       0  5036.0    0.04       0  5040.0    0.05       0
Bank Sta=5036,5040
Exp/Cntr=0.3,0.1

Type RM Length L Ch R = 1,1890,298,298,298
BEGIN DESCRIPTION:
MDW T 004 7.0
END DESCRIPTION:
XS GIS Cut Line= 3
      2265441.84      7117081.27      2265087.09      7117216.08
      2264772.61      7117360.60
#Sta/Elev= 30
  4620.5  935.77  4745.1  932.14  4762.6  931.37  4848.2  929.38  4909.8  928.61
  4955.2  929.35  4964.7  928.99  4970.0  927.22  4976.6  925.71  4994.8  925.46
  4996.5  923.52  4996.7  923.02  5000.2  923.02  5000.5  923.52  5008.9  924.45
  5017.9  926.42  5023.4  928.50  5030.9  929.41  5069.4  929.92  5115.3  931.49
  5130.0  931.69  5152.0  933.29  5166.8  932.77  5229.0  933.63  5241.2  934.70
  5264.2  935.30  5287.2  937.06  5310.1  936.24  5333.1  936.75  5346.1  937.97
#Mann=3,-1,0
  4620.5    0.05       0  4996.5    0.04       0  5000.5    0.05       0
Bank Sta=4996.5,5000.5
Exp/Cntr=0.3,0.1

Type RM Length L Ch R = 1,1592,248,248,248
BEGIN DESCRIPTION:
MDW T 004 6.0
END DESCRIPTION:
XS GIS Cut Line= 3
      2265339.86      7116801.32      2265028.80      7116935.08
      2264650.75      7117115.51
#Sta/Elev= 30
  4661.4  935.99  4792.4  931.04  4803.8  931.17  4821.4  930.21  4844.9  929.83
  4880.0  929.74  4890.9  929.35  4897.5  928.35  4902.9  928.83  4921.0  926.27
  4926.4  926.79  4944.5  924.34  4950.0  924.84  4967.1  923.84  4995.1  921.06
  4995.3  920.56  4998.8  920.56  4999.1  921.06  5019.7  922.36  5033.0  924.89
  5047.9  926.07  5070.6  925.88  5161.4  927.66  5243.6  930.15  5257.7  931.61
  5265.7  931.90  5332.2  932.48  5387.6  934.33  5409.8  935.94  5418.9  935.79
#Mann=3,-1,0
  4661.4    0.05       0  4995.1    0.04       0  4999.1    0.05       0
Bank Sta=4995.1,4999.1
Exp/Cntr=0.3,0.1

Type RM Length L Ch R = 1,1344,261,261,261
BEGIN DESCRIPTION:
MDW T 004 5.0
END DESCRIPTION:
XS GIS Cut Line= 3
      2265206.40      7116576.71      2264972.81      7116712.52
      2264654.55      7116915.35
#Sta/Elev= 30
  4729.8  931.71  4761.0  931.30  4766.7  933.62  4782.5  931.64  4788.2  933.37
  4804.0  931.87  4809.8  933.01  4825.5  931.63  4831.3  932.76  4868.5  932.42
  4900.0  931.45  4905.8  930.29  4921.5  930.55  4927.3  928.91  4970.3  927.63
  4980.3  924.51  4990.8  912.89  4991.1  912.39  4994.8  912.89  5002.3  913.63
  5007.5  915.46  5038.0  921.31  5043.9  923.13  5095.6  923.01  5204.7  925.46
  5283.4  927.78  5298.7  928.94  5348.4  929.77  5371.5  931.83  5377.4  931.67
#Mann=3,-1,0
  4729.8    0.05       0  4990.8    0.04       0  4994.8    0.05       0
Bank Sta=4990.8,4994.8
Exp/Cntr=0.3,0.1

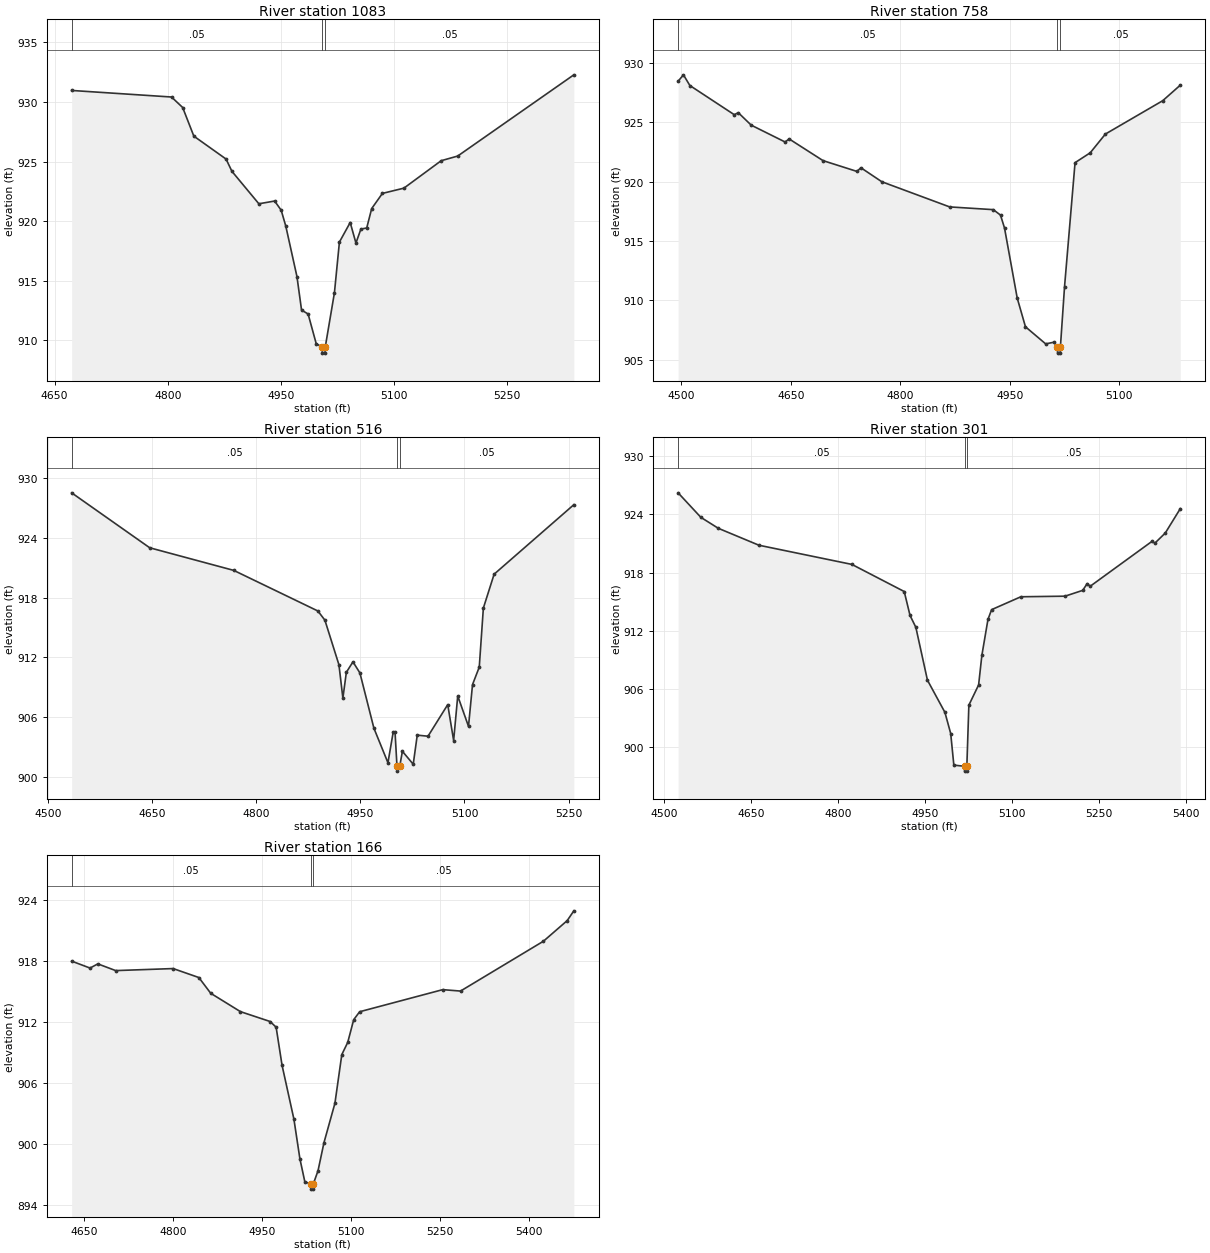
Type RM Length L Ch R = 1,1083,325,325,325
BEGIN DESCRIPTION:
MDW T 004 4.0
END DESCRIPTION:
XS GIS Cut Line= 3
      2265026.29      7116421.53      2264758.66      7116610.30
      2264503.12      7116831.98
#Sta/Elev= 30
  4672.5  930.96  4804.9  930.41  4819.7  929.53  4834.5  927.13  4877.2  925.21
  4885.0  924.18  4920.7  921.46  4941.6  921.69  4950.3  920.92  4956.4  919.59
  4971.2  915.36  4977.3  912.55  4986.0  912.22  4996.7  909.74  5004.7  909.44
  5004.9  908.94  5008.4  908.94  5008.7  909.44  5020.9  914.00  5027.5  918.25
  5041.8  919.89  5049.4  918.17  5056.0  919.34  5063.7  919.43  5070.3  921.06
  5084.5  922.33  5113.0  922.77  5162.4  925.07  5184.3  925.46  5338.3  932.27
#Mann=3,-1,0
  4672.5    0.05       0  5004.7   0.033       0  5008.7    0.05       0
Bank Sta=5004.7,5008.7
Exp/Cntr=0.3,0.1

Type RM Length L Ch R = 1,758,242,242,242
BEGIN DESCRIPTION:
MDW T 004 3.0
END DESCRIPTION:
XS GIS Cut Line= 3
      2264993.74      7116203.44      2264532.82      7116408.57
      2264388.29      7116522.43
#Sta/Elev= 30
  4495.5  928.47  4502.8  929.01  4511.6  928.11  4572.5  925.65  4578.0  925.82
  4595.7  924.77  4642.2  923.35  4647.7  923.61  4694.2  921.78  4740.7  920.87
  4746.1  921.18  4774.8  920.00  4867.8  917.88  4927.6  917.65  4937.5  917.19
  4943.0  916.10  4960.4  910.20  4971.7  907.78  4999.4  906.34  5010.8  906.48
  5015.6  906.06  5015.8  905.56  5019.3  905.56  5019.6  906.06  5025.3  911.17
  5039.7  921.61  5060.5  922.44  5081.3  924.02  5159.9  926.83  5184.0  928.14
#Mann=3,-1,0
  4495.5    0.05       0  5015.6    0.04       0  5019.6    0.05       0
Bank Sta=5015.6,5019.6
Exp/Cntr=0.3,0.1

Type RM Length L Ch R = 1,516,215,215,215
BEGIN DESCRIPTION:
MDW T 004 2.0
END DESCRIPTION:
XS GIS Cut Line= 3
      2264990.45      7116132.92      2264528.89      7116194.92
      2264396.17      7116415.58
#Sta/Elev= 30
  4534.3  928.51  4646.7  923.00  4767.8  920.73  4888.9  916.66  4899.0  915.74
  4919.2  911.27  4924.9  907.92  4929.9  910.51  4939.4  911.56  4949.4  910.45
  4969.6  904.90  4989.8  901.44  4997.4  904.53  5000.0  904.53  5002.8  901.10
  5003.0  900.60  5006.8  901.10  5010.6  902.59  5026.2  901.29  5032.0  904.21
  5047.5  904.10  5075.9  907.27  5084.4  903.67  5090.3  908.14  5105.8  905.09
  5111.6  909.28  5121.3  911.03  5127.2  916.95  5142.7  920.35  5257.5  927.32
#Mann=3,-1,0
  4534.3    0.05       0  5002.8   0.033       0  5006.8    0.05       0
Bank Sta=5002.8,5006.8
Exp/Cntr=0.3,0.1

Type RM Length L Ch R = 1,301,135,135,135
BEGIN DESCRIPTION:
MDW T 004 1.0
END DESCRIPTION:
XS GIS Cut Line= 4
      2264998.10      7116033.09      2264523.18      7116007.72
      2264443.59      7116167.64      2264405.70      7116375.48
#Sta/Elev= 30
  4524.4  926.23  4563.6  923.70  4593.6  922.57  4663.7  920.82  4823.9  918.84
  4914.1  916.04  4924.1  913.57  4934.1  912.35  4954.1  906.89  4984.2  903.57
  4994.2  901.38  4999.6  898.12  5018.0  898.00  5018.2  897.50  5021.7  897.50
  5022.0  898.00  5025.5  904.31  5042.3  906.40  5047.9  909.45  5058.4  913.16
  5064.7  914.17  5115.1  915.50  5191.2  915.56  5221.7  916.16  5229.4  916.86
  5234.5  916.58  5341.1  921.22  5346.2  921.04  5364.0  922.08  5389.9  924.60
#Mann=3,-1,0
  4524.4    0.05       0  5018.0   0.033       0  5022.0    0.05       0
Bank Sta=5018,5022
Exp/Cntr=0.3,0.1

Type RM Length L Ch R = 1,166,0,0,0
BEGIN DESCRIPTION:
MDW T 004 0.5
END DESCRIPTION:
XS GIS Cut Line= 4
      2264803.07      7115882.65      2264407.45      7115910.97
      2264396.12      7116077.97      2264402.63      7116361.17
#Sta/Elev= 30
  4628.5  917.99  4659.5  917.31  4672.7  917.72  4702.8  917.06  4799.7  917.26
  4843.1  916.38  4863.2  914.83  4913.3  913.03  4963.4  912.06  4973.5  911.50
  4983.5  907.76  5003.5  902.47  5013.6  898.58  5021.9  896.33  5032.2  896.10
  5032.4  895.60  5035.9  895.60  5036.2  896.10  5044.2  897.41  5054.2  900.16
  5072.7  904.03  5084.3  908.81  5094.3  910.01  5104.4  912.24  5114.4  913.02
  5254.6  915.19  5284.6  915.05  5424.6  919.95  5464.6  921.97  5475.8  922.93
#Mann=3,-1,0
  4628.5    0.05       0  5032.2   0.033       0  5036.2    0.05       0
Bank Sta=5032.2,5036.2
Exp/Cntr=0.3,0.1

Chan Stop Cuts=-1