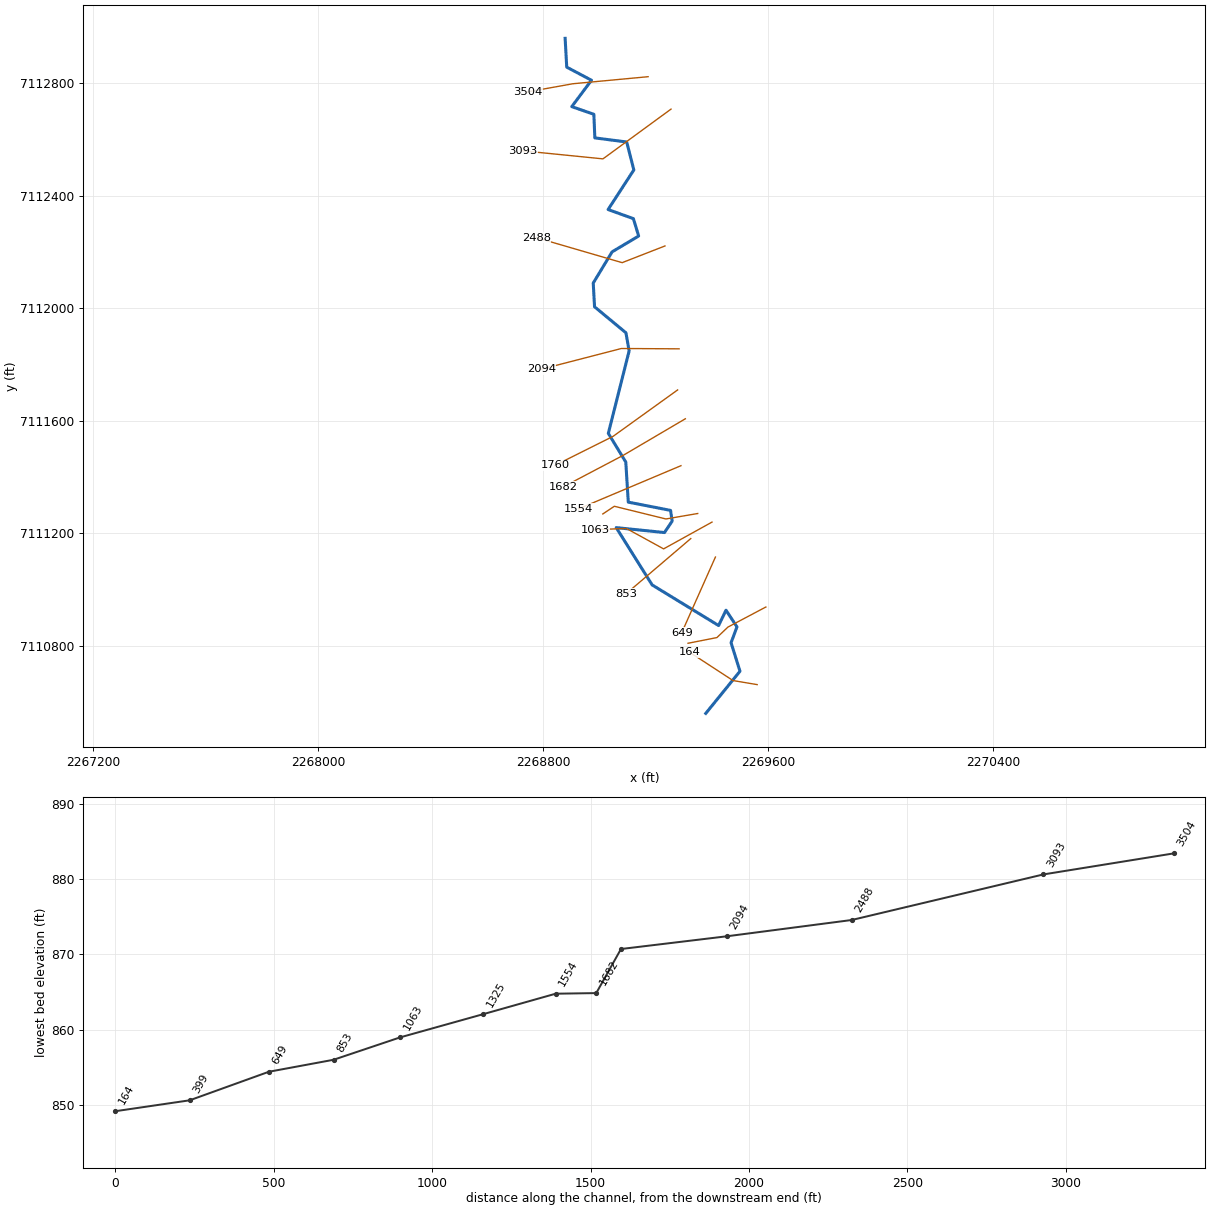
--- MDW T 005.prj (project) ---

Proj Title=MDW T 005 Base Level Engineering
Current Plan=p01
Default Exp/Contr=0.3,0.1
English Units
Geom File=g01
Flow File=f01
Plan File=p01
BEGIN DESCRIPTION:
MDW T 005
END DESCRIPTION:

--- MDW T 005.p01 (plan) ---

Plan Title=Multiple Run
Short Identifier=Multiple
Geom File=g01
Flow File=f01
Subcritical Flow
K Sum by GR= 0
Std Step Tol= 0.01
Critical Tol= 0.01
Num of Std Step Trials= 20
Max Error Tol= 0.3
Flow Tol Ratio= 0.001
Split Flow NTrial= 30
Split Flow Tol= 0.02
Split Flow Ratio= 0.02
Log Output Level= 0
Friction Slope Method= 1
Unsteady Friction Slope Method= 2
Unsteady Bridges Friction Slope Method= 1
Parabolic Critical Depth
Global Vel Dist=  1 , 1 , 1
Global Log Level= 0
CheckData=True
Encroach Param= -1, 0, 0, 0
BEGIN DESCRIPTION:
Multiple Run
END DESCRIPTION:

--- MDW T 005.f01 (steady flow) ---

Flow Title=Multiple
Number of Profiles=7
Profile Names=10-year,25-year,50-year,1pct_min,100-year,1pct_plu,500-year
River Rch & RM= MDW T 005,Reach-1,3504
     460     623     757     457     912    1819    1326
Boundary for River Rch & Prof#=MDW T 005,Reach-1,1
Up Type=0
Dn Type=3
Dn Slope=0.005
Boundary for River Rch & Prof#=MDW T 005,Reach-1,2
Up Type=0
Dn Type=3
Dn Slope=0.005
Boundary for River Rch & Prof#=MDW T 005,Reach-1,3
Up Type=0
Dn Type=3
Dn Slope=0.005
Boundary for River Rch & Prof#=MDW T 005,Reach-1,4
Up Type=0
Dn Type=3
Dn Slope=0.005
Boundary for River Rch & Prof#=MDW T 005,Reach-1,5
Up Type=0
Dn Type=3
Dn Slope=0.005
Boundary for River Rch & Prof#=MDW T 005,Reach-1,6
Up Type=0
Dn Type=3
Dn Slope=0.005
Boundary for River Rch & Prof#=MDW T 005,Reach-1,7
Up Type=0
Dn Type=3
Dn Slope=0.005

--- MDW T 005.g01 (geometry) ---

Geom Title=Existing Conditions

River Reach=MDW T 005,Reach-1
Reach XY= 30
      2268879.00      7112960.00      2268884.63      7112857.62
      2268972.73      7112810.96      2268902.55      7112717.20
      2268981.10      7112689.95      2268984.60      7112606.02
      2269097.88      7112591.48      2269123.25      7112492.15
      2269031.79      7112351.37      2269121.70      7112318.84
      2269140.38      7112257.13      2269045.87      7112200.81
      2268978.88      7112089.90      2268983.57      7112005.51
      2269095.17      7111913.10      2269106.49      7111848.43
      2269032.49      7111555.50      2269094.63      7111453.49
      2269103.48      7111311.06      2269253.79      7111281.67
      2269259.50      7111243.50      2269232.20      7111202.89
      2269060.57      7111220.40      2269188.39      7111016.64
      2269424.62      7110872.30      2269450.90      7110926.71
      2269489.86      7110867.60      2269468.95      7110811.13
      2269500.59      7110709.79      2269379.00      7110560.00

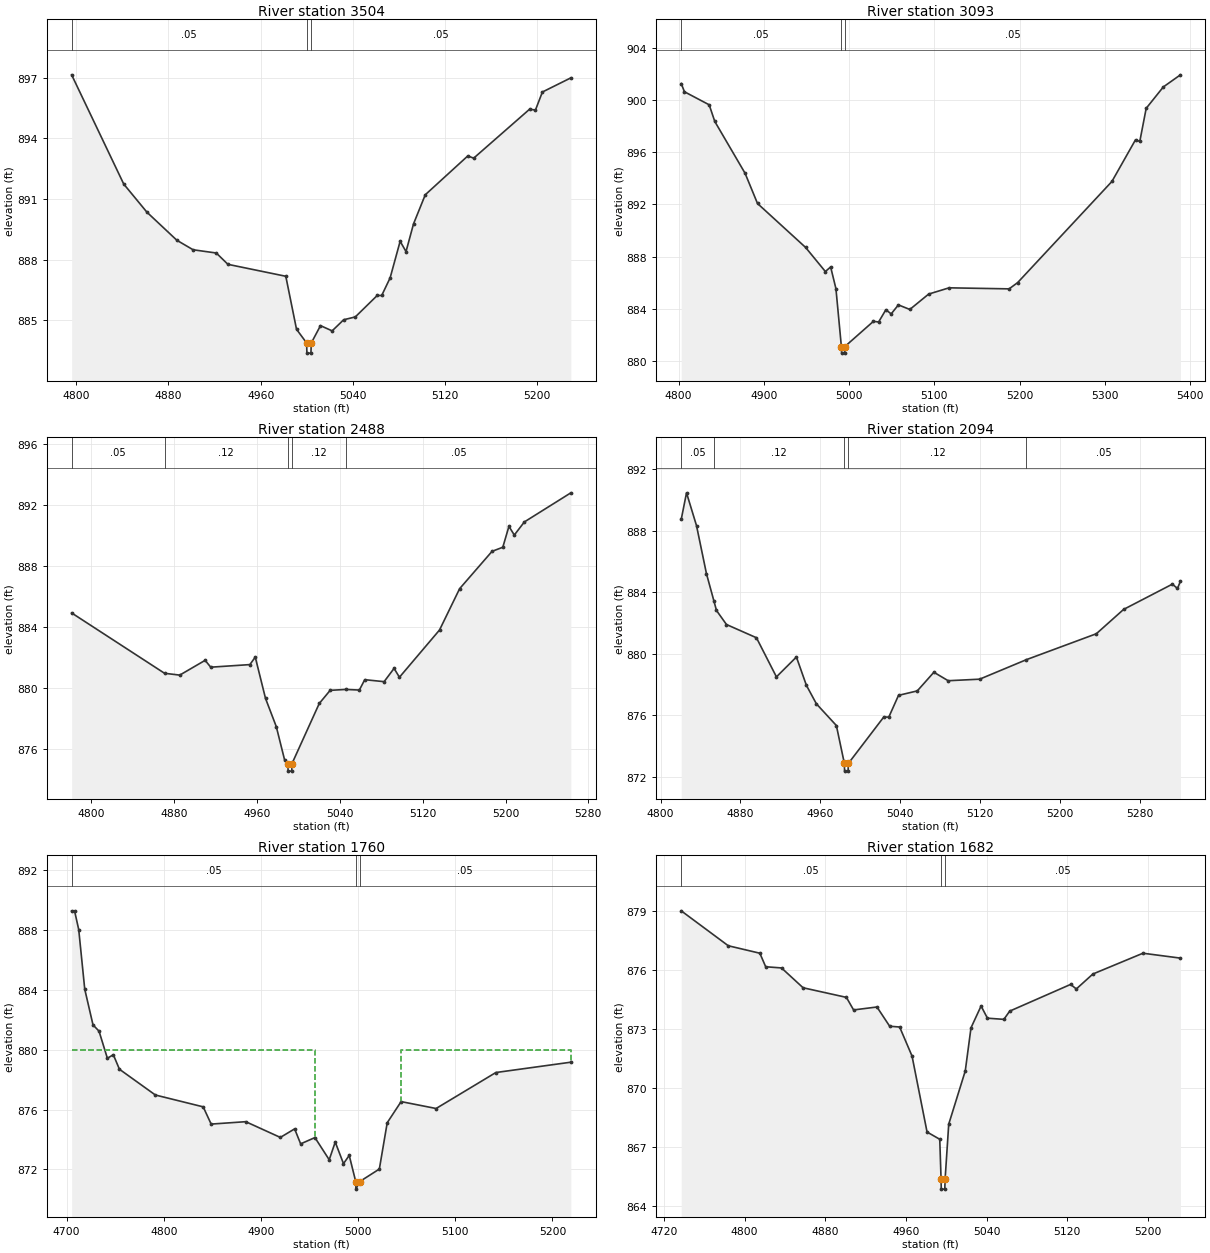
Type RM Length L Ch R = 1,3504,411,411,411
BEGIN DESCRIPTION:
MDW T 005 8.0
END DESCRIPTION:
XS GIS Cut Line= 3
      2269173.99      7112823.60      2268906.18      7112798.50
      2268744.66      7112769.39
#Sta/Elev= 30
  4796.0  897.14  4841.2  891.74  4861.3  890.35  4887.3  888.96  4901.4  888.49
  4921.5  888.33  4931.6  887.77  4981.8  887.18  4991.1  884.56  4999.9  883.88
  5000.1  883.38  5003.6  883.38  5003.9  883.88  5011.9  884.74  5022.0  884.48
  5032.0  885.03  5042.1  885.17  5061.1  886.23  5065.0  886.23  5072.3  887.10
  5081.0  888.91  5086.1  888.40  5092.6  889.77  5102.8  891.21  5139.7  893.13
  5144.8  893.02  5193.3  895.44  5198.4  895.40  5204.4  896.29  5229.1  896.99
#Mann=3,-1,0
  4796.0    0.05       0  4999.9   0.033       0  5003.9    0.05       0
Bank Sta=4999.9,5003.9
Exp/Cntr=0.3,0.1

Type RM Length L Ch R = 1,3093,605,605,605
BEGIN DESCRIPTION:
MDW T 005 7.0
END DESCRIPTION:
XS GIS Cut Line= 3
      2269255.50      7112708.42      2269013.48      7112531.49
      2268729.00      7112560.00
#Sta/Elev= 30
  4803.0  901.27  4806.8  900.64  4835.8  899.64  4842.4  898.36  4877.9  894.39
  4892.5  892.07  4948.9  888.70  4972.1  886.85  4978.3  887.20  4984.5  885.54
  4990.9  881.09  4991.2  880.59  4994.7  880.59  4994.9  881.09  5028.5  883.03
  5034.6  882.98  5043.1  883.92  5049.3  883.60  5057.8  884.29  5071.2  883.94
  5093.3  885.12  5117.3  885.60  5187.7  885.52  5197.7  886.00  5308.3  893.76
  5336.0  896.96  5341.0  896.83  5348.5  899.37  5368.6  901.01  5388.7  901.94
#Mann=3,-1,0
  4803.0    0.05       0  4990.9   0.033       0  4994.9    0.05       0
Bank Sta=4990.9,4994.9
Exp/Cntr=0.3,0.1

Type RM Length L Ch R = 1,2488,394,394,394
BEGIN DESCRIPTION:
MDW T 005 6.0
END DESCRIPTION:
XS GIS Cut Line= 3
      2269234.03      7112221.88      2269081.72      7112162.46
      2268775.92      7112251.52
#Sta/Elev= 30
  4781.1  884.92  4870.8  880.96  4885.5  880.84  4910.0  881.81  4915.4  881.36
  4953.2  881.53  4958.4  882.02  4968.3  879.31  4978.7  877.46  4986.7  875.28
  4989.9  875.04  4990.1  874.54  4993.6  874.54  4993.9  875.04  5020.2  878.98
  5030.7  879.84  5045.8  879.90  5058.9  879.86  5064.1  880.54  5082.8  880.41
  5092.4  881.28  5097.6  880.70  5136.3  883.80  5155.7  886.51  5187.0  888.96
  5197.4  889.23  5203.3  890.60  5208.5  890.03  5218.2  890.89  5263.1  892.80
#Mann=5,-1,0
  4781.1    0.05       0  4870.8    0.12       0  4989.9    0.07       0
  4993.9    0.12       0  5045.8    0.05       0
Bank Sta=4989.9,4993.9
Exp/Cntr=0.3,0.1

Type RM Length L Ch R = 1,2094,334,334,334
BEGIN DESCRIPTION:
MDW T 005 5.0
END DESCRIPTION:
XS GIS Cut Line= 3
      2269284.27      7111856.08      2269079.05      7111857.25
      2268793.95      7111783.52
#Sta/Elev= 30
  4820.7  888.72  4826.0  890.45  4836.0  888.32  4846.0  885.19  4853.5  883.41
  4856.0  882.81  4866.0  881.90  4896.0  881.04  4916.0  878.50  4936.0  879.79
  4946.0  877.95  4956.0  876.75  4976.0  875.34  4984.0  872.88  4984.2  872.38
  4987.7  872.38  4988.0  872.88  5023.4  875.89  5028.5  875.89  5038.2  877.30
  5057.0  877.59  5073.6  878.80  5087.9  878.25  5119.4  878.35  5166.3  879.62
  5236.2  881.30  5263.5  882.88  5312.3  884.52  5317.4  884.24  5320.4  884.71
#Mann=5,-1,0
  4820.7    0.05       0  4853.5    0.12       0  4984.0    0.07       0
  4988.0    0.12       0  5166.3    0.05       0
Bank Sta=4984,4988
Exp/Cntr=0.3,0.1

Type RM Length L Ch R = 1,1760,78,78,78
BEGIN DESCRIPTION:
MDW T 005 4.0
END DESCRIPTION:
XS GIS Cut Line= 3
      2269278.97      7111709.98      2269049.49      7111544.95
      2268842.71      7111441.65
#Sta/Elev= 30
  4705.1  889.26  4708.1  889.26  4712.4  888.01  4718.6  884.03  4727.1  881.65
  4733.3  881.23  4741.9  879.42  4748.0  879.66  4754.3  878.69  4791.3  876.97
  4840.5  876.18  4848.7  875.03  4884.3  875.19  4919.9  874.14  4934.6  874.71
  4940.8  873.71  4955.5  874.13  4970.2  872.65  4976.4  873.83  4984.9  872.39
  4990.8  872.94  4997.5  871.19  4997.7  870.69  5001.5  871.19  5021.8  872.03
  5029.9  875.12  5044.2  876.53  5080.2  876.07  5141.7  878.47  5218.9  879.16
#Mann=3,-1,0
  4705.1    0.05       0  4997.5   0.033       0  5001.5    0.05       0
#XS Ineff=2,0
    0.00 4955.90  879.98 5044.10    0.00  879.98
Permanent Ineff=
       F       F
Bank Sta=4997.5,5001.5
Exp/Cntr=0.3,0.1

Type RM Length L Ch R = 1,1682,128,128,128
BEGIN DESCRIPTION:
MDW T 005 3.5
END DESCRIPTION:
XS GIS Cut Line= 3
      2269306.39      7111607.41      2269085.29      7111477.34
      2268873.99      7111366.14
#Sta/Elev= 30
  4737.1  879.02  4783.8  877.24  4815.1  876.86  4820.9  876.17  4836.6  876.11
  4858.0  875.10  4901.0  874.61  4908.1  873.97  4931.3  874.12  4943.9  873.14
  4953.8  873.10  4966.1  871.62  4981.0  867.75  4993.6  867.38  4994.9  865.34
  4995.1  864.84  4998.6  864.84  4998.9  865.34  5002.5  868.15  5018.9  870.86
  5024.6  873.06  5034.6  874.17  5040.9  873.55  5057.2  873.49  5063.0  873.91
  5123.4  875.27  5129.1  875.04  5145.5  875.80  5195.2  876.86  5232.4  876.61
#Mann=3,-1,0
  4737.1    0.05       0  4994.9   0.033       0  4998.9    0.05       0
Bank Sta=4994.9,4998.9
Exp/Cntr=0.3,0.1

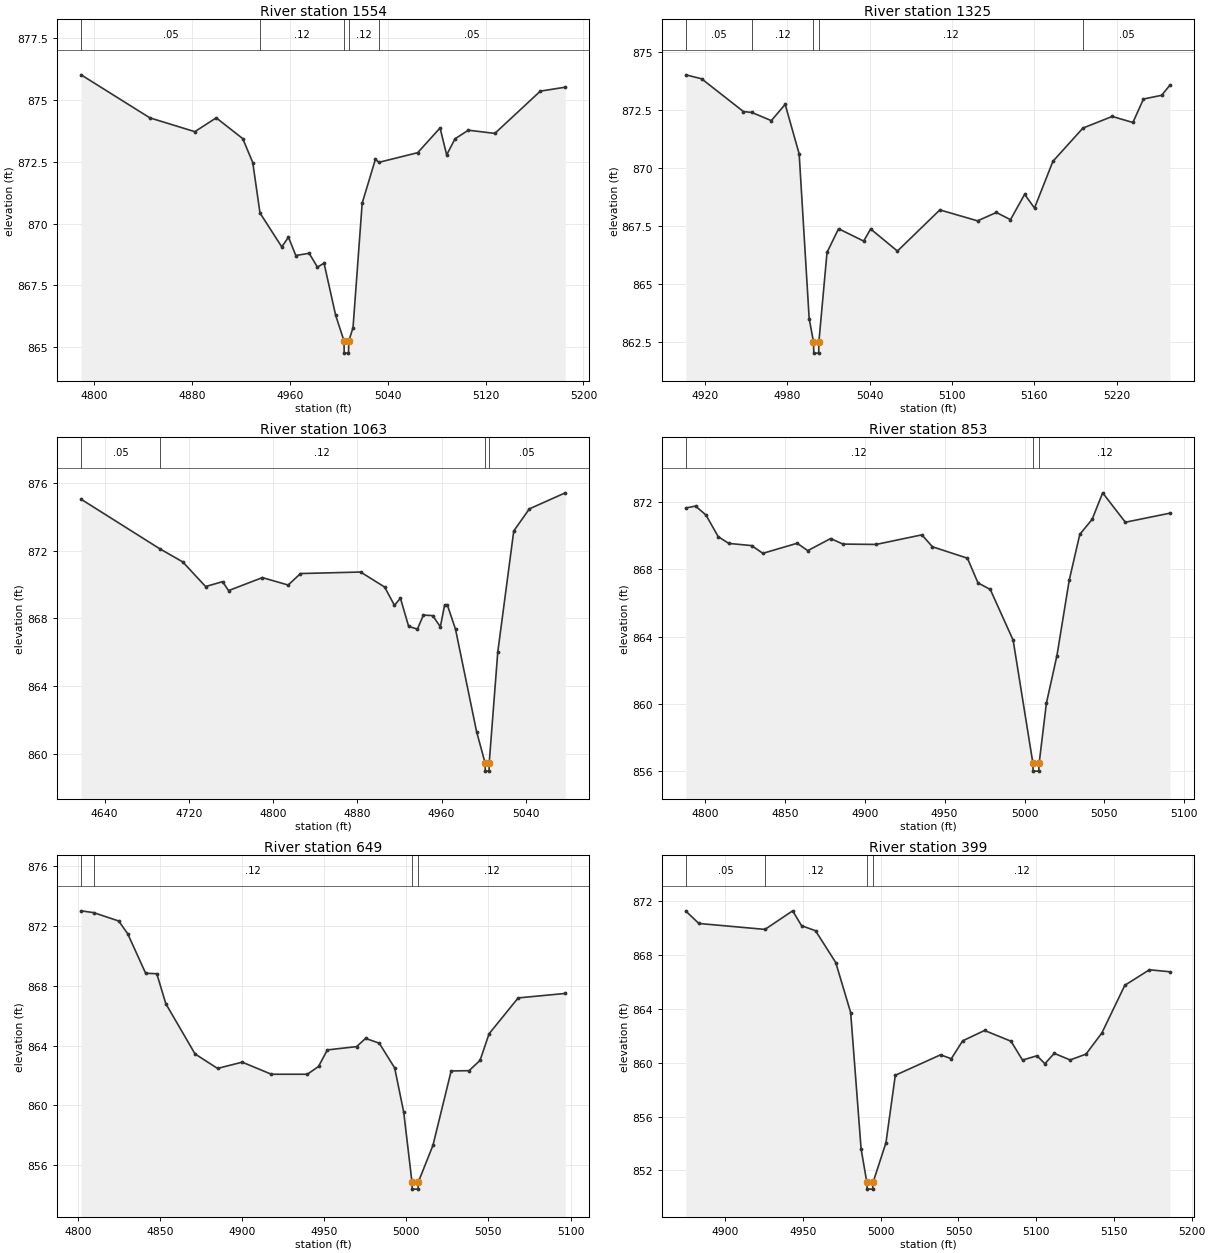
Type RM Length L Ch R = 1,1554,229,229,229
BEGIN DESCRIPTION:
Mapping XS 92d04cd3
END DESCRIPTION:
XS GIS Cut Line= 2
      2269290.81      7111440.64      2268925.93      7111286.76
#Sta/Elev= 30
  4789.1  876.02  4845.3  874.28  4882.1  873.72  4899.6  874.28  4921.3  873.44
  4929.5  872.47  4935.4  870.43  4953.2  869.06  4958.7  869.45  4964.7  868.71
  4975.6  868.80  4982.4  868.24  4987.8  868.40  4997.3  866.29  5004.1  865.26
  5004.3  864.76  5007.8  864.76  5008.1  865.26  5011.5  865.79  5019.0  870.83
  5029.8  872.60  5032.7  872.48  5064.4  872.87  5082.7  873.87  5088.1  872.78
  5094.9  873.43  5105.8  873.78  5127.5  873.65  5164.7  875.36  5185.1  875.52
#Mann=5,-1,0
  4789.1    0.05       0  4935.4    0.12       0  5004.1    0.07       0
  5008.1    0.12       0  5032.7    0.05       0
Bank Sta=5004.1,5008.1
Exp/Cntr=0.3,0.1

Type RM Length L Ch R = 1,1325,262,262,262
BEGIN DESCRIPTION:
Mapping XS 0675bac0
END DESCRIPTION:
XS GIS Cut Line= 4
      2269350.36      7111270.64      2269237.28      7111251.18
      2269053.91      7111296.32      2269012.98      7111269.00
#Sta/Elev= 30
  4906.1  874.01  4917.6  873.84  4948.1  872.43  4954.3  872.39  4968.4  872.04
  4978.5  872.74  4988.7  870.61  4996.0  863.52  4999.1  862.54  4999.4  862.04
  5002.9  862.04  5003.1  862.54  5009.0  866.37  5017.4  867.39  5035.7  866.86
  5040.8  867.38  5060.3  866.43  5091.2  868.20  5118.7  867.73  5132.4  868.09
  5142.7  867.78  5153.0  868.87  5160.2  868.28  5173.6  870.29  5195.5  871.72
  5216.8  872.22  5231.9  871.96  5239.6  872.97  5252.9  873.13  5258.9  873.57
#Mann=5,-1,0
  4906.1    0.05       0  4954.3    0.12       0  4999.1    0.07       0
  5003.1    0.12       0  5195.5    0.05       0
Bank Sta=4999.1,5003.1
Exp/Cntr=0.3,0.1

Type RM Length L Ch R = 1,1063,210,210,210
BEGIN DESCRIPTION:
Mapping XS ab24efdd
END DESCRIPTION:
XS GIS Cut Line= 4
      2269401.29      7111240.14      2269229.13      7111144.84
      2269096.84      7111217.43      2268984.90      7111213.13
#Sta/Elev= 30
  4617.8  875.06  4692.4  872.13  4714.3  871.35  4736.0  869.89  4752.1  870.18
  4757.8  869.65  4789.9  870.42  4814.4  869.98  4826.1  870.66  4883.2  870.75
  4906.0  869.86  4915.3  868.78  4921.0  869.20  4928.8  867.53  4937.1  867.37
  4942.8  868.20  4951.6  868.17  4958.9  867.51  4963.0  868.81  4965.5  868.81
  4973.3  867.36  4993.3  861.30  5001.3  859.46  5001.6  858.96  5005.1  858.96
  5005.3  859.46  5013.4  866.00  5028.6  873.18  5043.4  874.49  5077.5  875.44
#Mann=4,-1,0
  4617.8    0.05       0  4692.4    0.12       0  5001.3    0.07       0
  5005.3    0.05       0
Bank Sta=5001.3,5005.3
Exp/Cntr=0.3,0.1

Type RM Length L Ch R = 1,853,204,204,204
BEGIN DESCRIPTION:
Mapping XS 65d3840f
END DESCRIPTION:
XS GIS Cut Line= 2
      2269325.66      7111181.45      2269095.22      7110984.87
#Sta/Elev= 30
  4788.1  871.65  4794.2  871.76  4800.7  871.23  4808.4  869.94  4815.0  869.54
  4829.3  869.41  4836.3  868.95  4857.8  869.55  4864.4  869.11  4878.7  869.83
  4886.4  869.50  4907.2  869.48  4935.8  870.05  4942.4  869.34  4964.3  868.66
  4970.9  867.19  4978.6  866.80  4992.9  863.78  5005.2  856.49  5005.4  855.99
  5008.9  855.99  5009.2  856.49  5013.7  860.03  5020.3  862.87  5028.0  867.36
  5034.6  870.08  5042.3  870.97  5048.9  872.55  5063.1  870.80  5091.0  871.34
#Mann=3,-1,0
  4788.1    0.12       0  5005.2    0.07       0  5009.2    0.12       0
Bank Sta=5005.2,5009.2
Exp/Cntr=0.3,0.1

Type RM Length L Ch R = 1,649,250,250,250
BEGIN DESCRIPTION:
Mapping XS 9d173382
END DESCRIPTION:
XS GIS Cut Line= 2
      2269413.33      7111115.88      2269293.38      7110846.48
#Sta/Elev= 30
  4801.9  873.03  4809.5  872.91  4824.8  872.35  4830.3  871.49  4841.2  868.85
  4848.0  868.82  4853.5  866.81  4871.3  863.45  4885.0  862.48  4900.0  862.90
  4917.8  862.09  4939.7  862.09  4946.5  862.61  4951.9  863.72  4969.7  863.94
  4975.2  864.49  4983.5  864.17  4992.9  862.51  4998.4  859.55  5003.4  854.90
  5003.6  854.40  5007.1  854.40  5007.4  854.90  5016.2  857.33  5027.3  862.31
  5038.2  862.33  5044.9  863.02  5050.4  864.80  5068.1  867.20  5096.8  867.50
#Mann=4,-1,0
  4801.9    0.05       0  4809.5    0.12       0  5003.4    0.07       0
  5007.4    0.12       0
Bank Sta=5003.4,5007.4
Exp/Cntr=0.3,0.1

Type RM Length L Ch R = 1,399,235,235,235
BEGIN DESCRIPTION:
Mapping XS f4e50290
END DESCRIPTION:
XS GIS Cut Line= 4
      2269592.70      7110938.21      2269457.60      7110866.68
      2269418.55      7110829.50      2269316.01      7110809.30
#Sta/Elev= 30
  4874.7  871.27  4883.1  870.35  4925.6  869.91  4943.4  871.29  4949.1  870.19
  4958.1  869.81  4971.1  867.45  4980.7  863.73  4987.4  853.61  4991.1  851.11
  4991.3  850.61  4994.8  850.61  4995.1  851.11  5003.4  854.06  5009.4  859.07
  5038.5  860.59  5045.4  860.30  5052.7  861.63  5066.8  862.40  5083.8  861.60
  5091.2  860.20  5100.5  860.52  5105.6  859.93  5111.6  860.70  5121.8  860.21
  5132.0  860.64  5142.2  862.21  5157.0  865.76  5172.8  866.91  5186.0  866.76
#Mann=4,-1,0
  4874.7    0.05       0  4925.6    0.12       0  4991.1    0.07       0
  4995.1    0.12       0
Bank Sta=4991.1,4995.1
Exp/Cntr=0.3,0.1

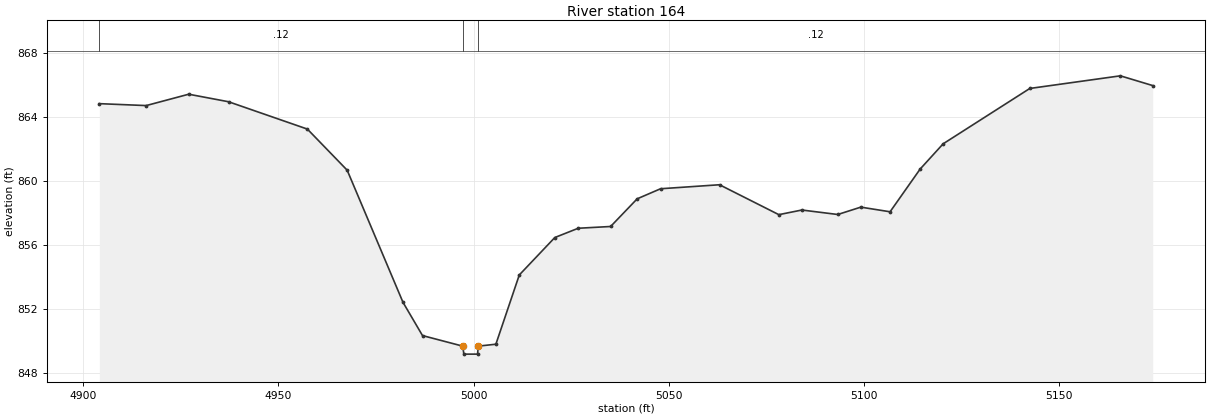
Type RM Length L Ch R = 1,164,0,0,0
BEGIN DESCRIPTION:
MDW T 005 2.0
END DESCRIPTION:
XS GIS Cut Line= 3
      2269561.60      7110662.30      2269475.95      7110676.64
      2269322.62      7110776.64
#Sta/Elev= 30
  4904.1  864.82  4916.1  864.70  4927.0  865.41  4937.2  864.94  4957.4  863.23
  4967.6  860.66  4981.9  852.40  4986.9  850.32  4997.2  849.66  4997.5  849.16
  5001.0  849.16  5001.2  849.66  5005.7  849.78  5011.7  854.11  5020.8  856.45
  5026.8  857.03  5035.1  857.14  5041.9  858.87  5047.9  859.50  5063.0  859.75
  5078.2  857.88  5084.1  858.17  5093.3  857.89  5099.2  858.35  5106.7  858.06
  5114.4  860.73  5120.3  862.31  5142.5  865.77  5165.7  866.56  5174.0  865.95
#Mann=3,-1,0
  4904.1    0.12       0  4997.2    0.07       0  5001.2    0.12       0
Bank Sta=4997.2,5001.2
Exp/Cntr=0.3,0.1

Chan Stop Cuts=-1