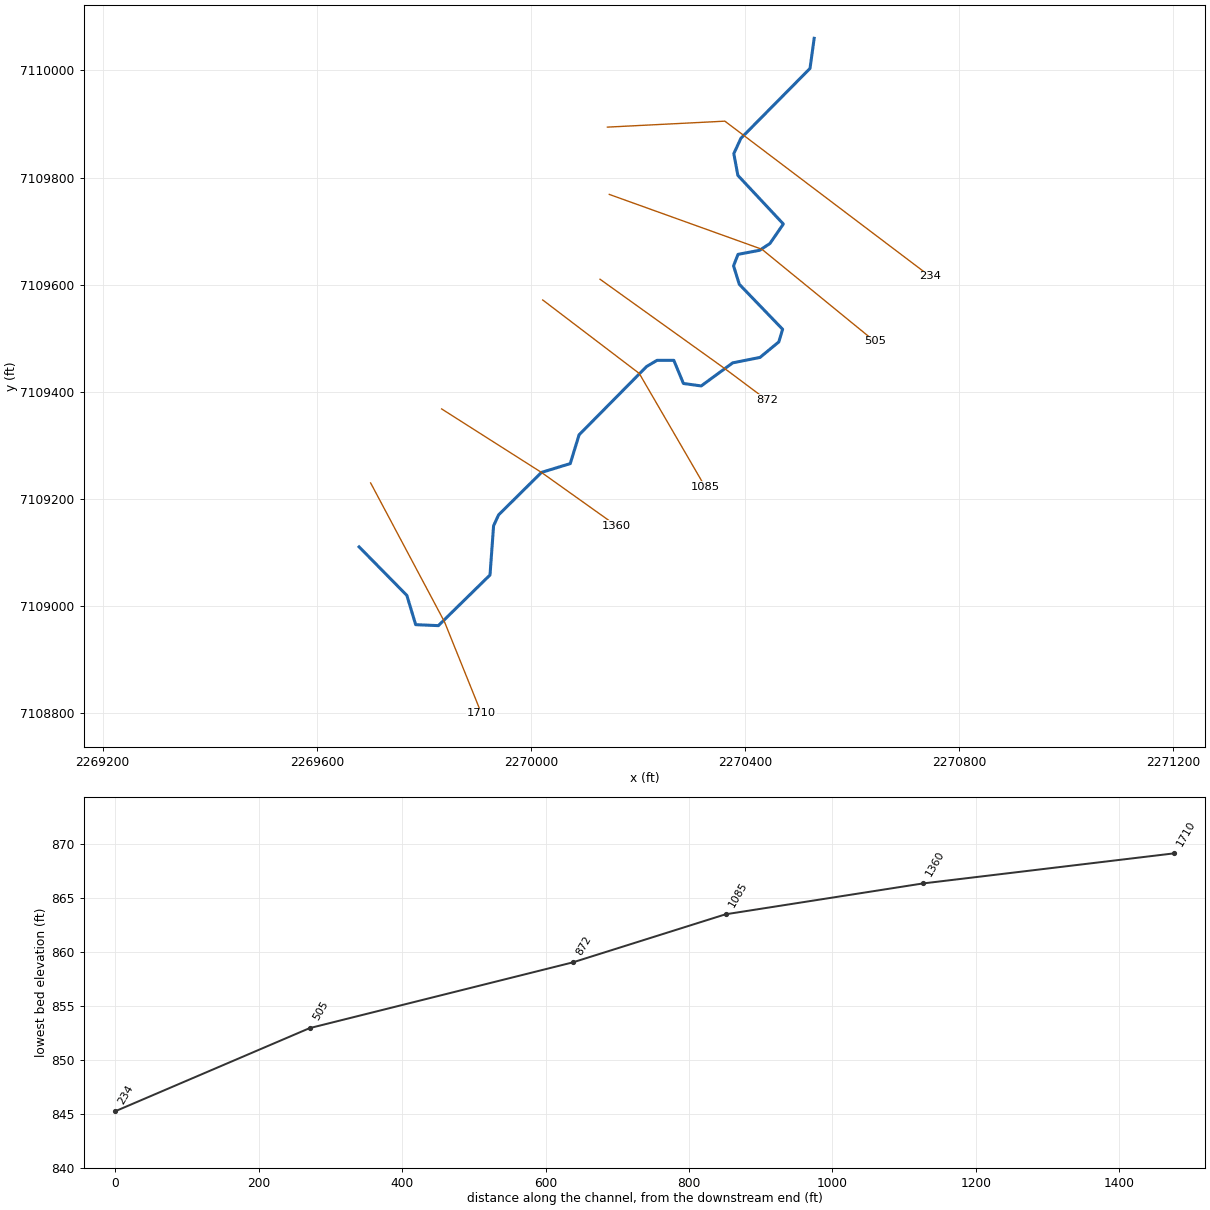
--- MDW T 006.prj (project) ---

Proj Title=MDW T 006 Base Level Engineering
Current Plan=p01
Default Exp/Contr=0.3,0.1
English Units
Geom File=g01
Flow File=f01
Plan File=p01
BEGIN DESCRIPTION:
MDW T 006
END DESCRIPTION:

--- MDW T 006.p01 (plan) ---

Plan Title=Multiple Run
Short Identifier=Multiple
Geom File=g01
Flow File=f01
Subcritical Flow
K Sum by GR= 0
Std Step Tol= 0.01
Critical Tol= 0.01
Num of Std Step Trials= 20
Max Error Tol= 0.3
Flow Tol Ratio= 0.001
Split Flow NTrial= 30
Split Flow Tol= 0.02
Split Flow Ratio= 0.02
Log Output Level= 0
Friction Slope Method= 1
Unsteady Friction Slope Method= 2
Unsteady Bridges Friction Slope Method= 1
Parabolic Critical Depth
Global Vel Dist=  1 , 1 , 1
Global Log Level= 0
CheckData=True
Encroach Param= -1, 0, 0, 0
BEGIN DESCRIPTION:
Multiple Run
END DESCRIPTION:

--- MDW T 006.f01 (steady flow) ---

Flow Title=Multiple
Number of Profiles=7
Profile Names=10-year,25-year,50-year,1pct_min,100-year,1pct_plu,500-year
River Rch & RM= MDW T 006,Reach-1,1710
     247     320     378     222     443     884     610
Boundary for River Rch & Prof#=MDW T 006,Reach-1,1
Up Type=0
Dn Type=3
Dn Slope=0.005
Boundary for River Rch & Prof#=MDW T 006,Reach-1,2
Up Type=0
Dn Type=3
Dn Slope=0.005
Boundary for River Rch & Prof#=MDW T 006,Reach-1,3
Up Type=0
Dn Type=3
Dn Slope=0.005
Boundary for River Rch & Prof#=MDW T 006,Reach-1,4
Up Type=0
Dn Type=3
Dn Slope=0.005
Boundary for River Rch & Prof#=MDW T 006,Reach-1,5
Up Type=0
Dn Type=3
Dn Slope=0.005
Boundary for River Rch & Prof#=MDW T 006,Reach-1,6
Up Type=0
Dn Type=3
Dn Slope=0.005
Boundary for River Rch & Prof#=MDW T 006,Reach-1,7
Up Type=0
Dn Type=3
Dn Slope=0.005

--- MDW T 006.g01 (geometry) ---

Geom Title=Existing Conditions

River Reach=MDW T 006,Reach-1
Reach XY= 30
      2269679.00      7109110.00      2269768.17      7109019.33
      2269784.61      7108964.72      2269827.00      7108962.94
      2269923.48      7109057.56      2269930.16      7109149.52
      2269939.51      7109169.81      2270019.56      7109249.12
      2270073.38      7109265.62      2270089.89      7109319.42
      2270216.00      7109446.95      2270235.40      7109458.47
      2270266.85      7109458.48      2270284.76      7109415.29
      2270317.96      7109410.67      2270376.83      7109453.81
      2270427.85      7109463.94      2270462.96      7109492.95
      2270470.09      7109516.51      2270389.11      7109600.58
      2270378.40      7109635.08      2270386.79      7109656.45
      2270427.32      7109664.13      2270446.35      7109676.73
      2270471.44      7109713.15      2270386.50      7109803.95
      2270378.89      7109844.64      2270392.11      7109873.21
      2270521.24      7110003.79      2270529.00      7110060.00

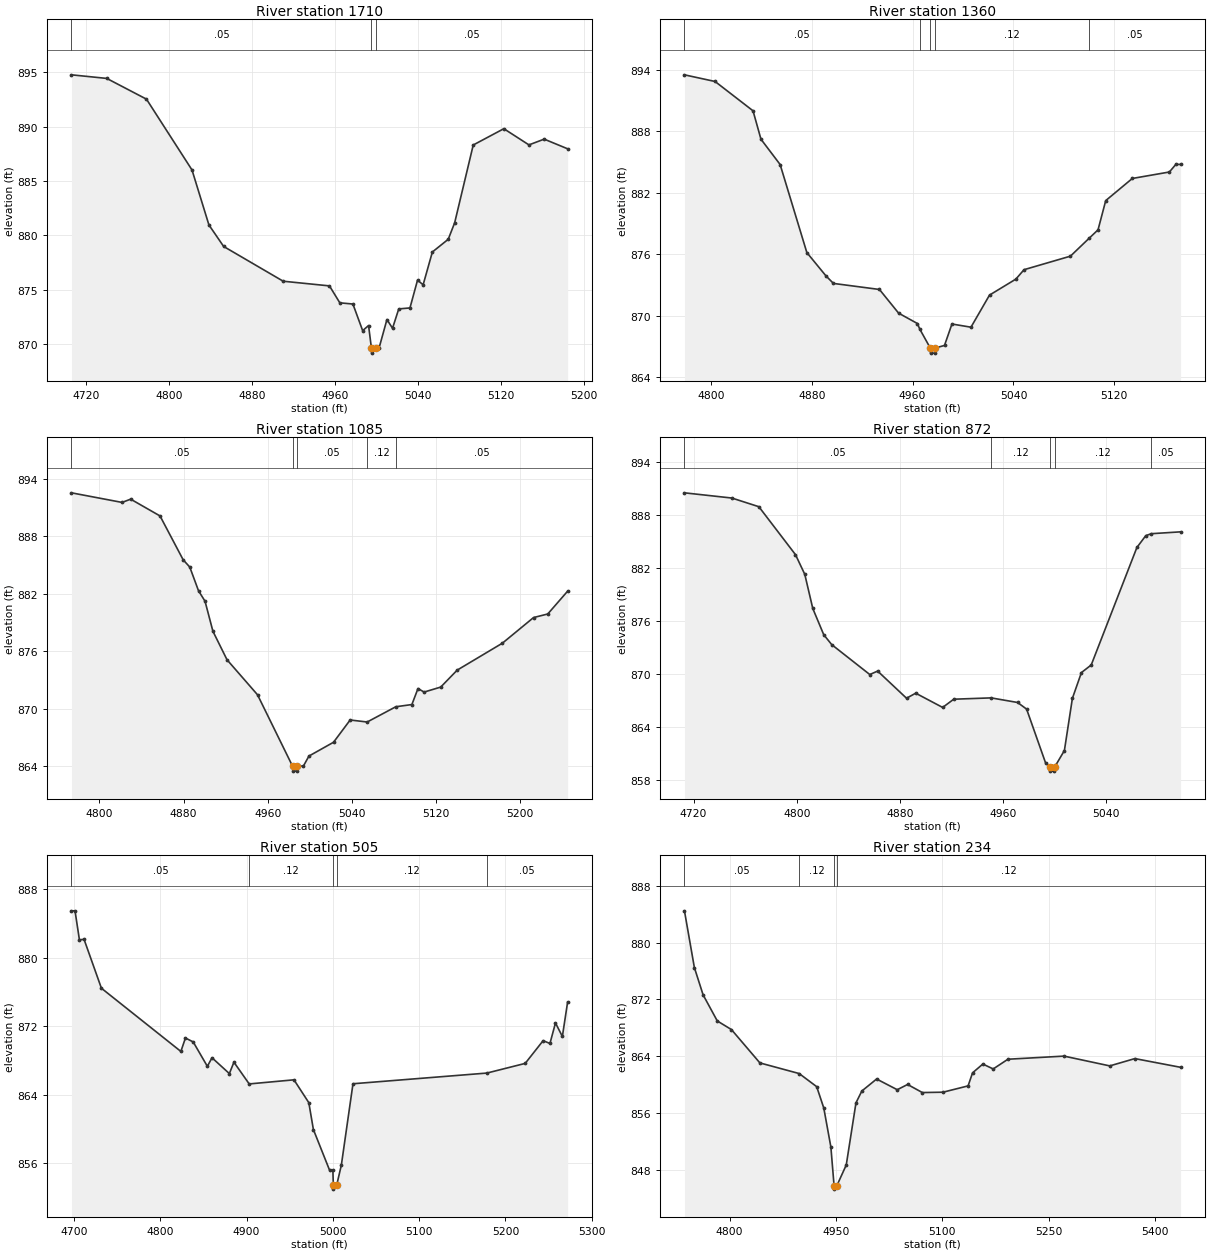
Type RM Length L Ch R = 1,1710,350,350,350
BEGIN DESCRIPTION:
MDW T 006 6.0
END DESCRIPTION:
XS GIS Cut Line= 3
      2269700.46      7109229.55      2269838.44      7108970.05
      2269907.39      7108799.03
#Sta/Elev= 30
  4706.1  894.78  4740.1  894.45  4778.4  892.54  4822.3  886.02  4838.6  880.96
  4852.8  878.98  4910.2  875.78  4954.8  875.35  4964.8  873.79  4977.4  873.68
  4986.8  871.23  4992.5  871.70  4995.2  869.66  4995.4  869.16  4999.2  869.66
  5002.7  869.66  5010.2  872.25  5015.6  871.45  5021.6  873.23  5032.4  873.32
  5039.7  875.88  5045.1  875.45  5054.0  878.47  5069.3  879.64  5075.5  881.16
  5093.4  888.32  5122.9  889.82  5147.1  888.33  5161.8  888.86  5184.4  887.97
#Mann=3,-1,0
  4706.1    0.05       0  4995.2   0.033       0  4999.2    0.05       0
Bank Sta=4995.2,4999.2
Exp/Cntr=0.3,0.1

Type RM Length L Ch R = 1,1360,275,275,275
BEGIN DESCRIPTION:
MDW T 006 5.0
END DESCRIPTION:
XS GIS Cut Line= 3
      2269833.10      7109367.76      2270019.56      7109249.12
      2270160.17      7109149.02
#Sta/Elev= 30
  4779.0  893.52  4803.3  892.87  4833.4  890.01  4839.7  887.24  4854.9  884.77
  4876.1  876.18  4891.3  873.90  4897.2  873.17  4933.7  872.58  4948.9  870.27
  4963.8  869.26  4965.7  868.71  4974.0  866.87  4974.2  866.37  4977.7  866.37
  4978.0  866.87  4985.3  867.12  4991.2  869.21  5006.3  868.90  5021.0  872.03
  5041.9  873.59  5048.4  874.51  5085.2  875.83  5099.9  877.56  5107.1  878.40
  5113.2  881.25  5134.3  883.41  5163.7  884.04  5168.8  884.78  5172.6  884.78
#Mann=5,-1,0
  4779.0    0.05       0  4965.7    0.12       0  4974.0    0.07       0
  4978.0    0.12       0  5099.9    0.05       0
Bank Sta=4974,4978
Exp/Cntr=0.3,0.1

Type RM Length L Ch R = 1,1085,213,213,213
BEGIN DESCRIPTION:
MDW T 006 4.0
END DESCRIPTION:
XS GIS Cut Line= 3
      2270021.98      7109571.24      2270202.29      7109434.00
      2270325.43      7109221.96
#Sta/Elev= 30
  4773.4  892.52  4821.5  891.52  4829.7  891.86  4857.6  890.11  4879.6  885.54
  4885.9  884.78  4894.2  882.31  4900.4  881.22  4907.9  878.09  4921.3  875.12
  4950.3  871.47  4983.7  864.01  4984.0  863.51  4987.5  863.51  4987.7  864.01
  4994.0  864.05  4999.2  865.08  5022.6  866.52  5038.4  868.84  5054.6  868.63
  5081.8  870.22  5097.1  870.45  5102.9  872.12  5108.7  871.75  5124.5  872.27
  5140.2  874.04  5183.2  876.85  5212.8  879.52  5226.3  879.89  5245.2  882.27
#Mann=5,-1,0
  4773.4    0.05       0  4983.7   0.033       0  4987.7    0.05       0
  5054.6    0.12       0  5081.8    0.05       0
Bank Sta=4983.7,4987.7
Exp/Cntr=0.3,0.1

Type RM Length L Ch R = 1,872,367,367,367
BEGIN DESCRIPTION:
MDW T 006 3.0
END DESCRIPTION:
XS GIS Cut Line= 3
      2270129.04      7109609.97      2270362.43      7109442.77
      2270440.61      7109384.35
#Sta/Elev= 30
  4712.9  890.51  4749.7  889.92  4770.6  888.94  4799.0  883.52  4806.2  881.30
  4812.4  877.44  4820.9  874.47  4827.1  873.35  4856.6  869.97  4862.7  870.36
  4885.1  867.29  4892.2  867.86  4913.1  866.25  4921.7  867.18  4950.7  867.33
  4971.2  866.81  4978.2  866.06  4992.9  859.98  4996.1  859.55  4996.3  859.05
  4999.8  859.05  5000.1  859.55  5007.5  861.38  5013.7  867.28  5020.7  870.19
  5028.3  871.05  5063.7  884.33  5070.6  885.67  5074.9  885.89  5097.6  886.10
#Mann=5,-1,0
  4712.9    0.05       0  4950.7    0.12       0  4996.1    0.07       0
  5000.1    0.12       0  5074.9    0.05       0
Bank Sta=4996.1,5000.1
Exp/Cntr=0.3,0.1

Type RM Length L Ch R = 1,505,271,271,271
BEGIN DESCRIPTION:
MDW T 006 2.0
END DESCRIPTION:
XS GIS Cut Line= 3
      2270146.26      7109768.47      2270431.40      7109665.99
      2270642.15      7109493.88
#Sta/Elev= 30
  4697.0  885.49  4701.1  885.49  4706.2  882.11  4711.6  882.15  4731.7  876.44
  4823.8  869.05  4829.1  870.62  4838.1  870.16  4854.5  867.31  4859.9  868.31
  4880.0  866.46  4885.3  867.79  4903.0  865.25  4954.9  865.73  4972.1  863.06
  4977.4  859.92  4996.1  855.18  5000.0  855.18  5000.5  853.45  5000.7  852.95
  5004.5  853.45  5009.8  855.75  5023.3  865.27  5178.5  866.52  5222.9  867.65
  5243.7  870.31  5251.6  869.98  5258.0  872.38  5266.0  870.80  5272.1  874.84
#Mann=5,-1,0
  4697.0    0.05       0  4903.0    0.12       0  5000.5    0.07       0
  5004.5    0.12       0  5178.5    0.05       0
Bank Sta=5000.5,5004.5
Exp/Cntr=0.3,0.1

Type RM Length L Ch R = 1,234,0,0,0
BEGIN DESCRIPTION:
MDW T 006 1.0
END DESCRIPTION:
XS GIS Cut Line= 3
      2270142.78      7109894.15      2270362.26      7109905.27
      2270745.05      7109615.76
#Sta/Elev= 30
  4736.4  884.49  4750.4  876.49  4762.7  872.64  4782.7  868.96  4802.7  867.74
  4842.8  863.04  4898.2  861.54  4922.9  859.69  4932.9  856.68  4942.9  851.18
  4947.4  845.74  4947.6  845.24  4951.4  845.74  4964.6  848.65  4978.3  857.41
  4986.6  859.08  5007.4  860.77  5036.5  859.26  5051.1  860.00  5071.9  858.86
  5101.0  858.91  5136.4  859.80  5142.7  861.64  5157.2  862.88  5171.8  862.19
  5192.6  863.56  5271.7  864.00  5336.2  862.62  5371.6  863.65  5436.1  862.42
#Mann=4,-1,0
  4736.4    0.05       0  4898.2    0.12       0  4947.4    0.07       0
  4951.4    0.12       0
Bank Sta=4947.4,4951.4
Exp/Cntr=0.3,0.1

Chan Stop Cuts=-1