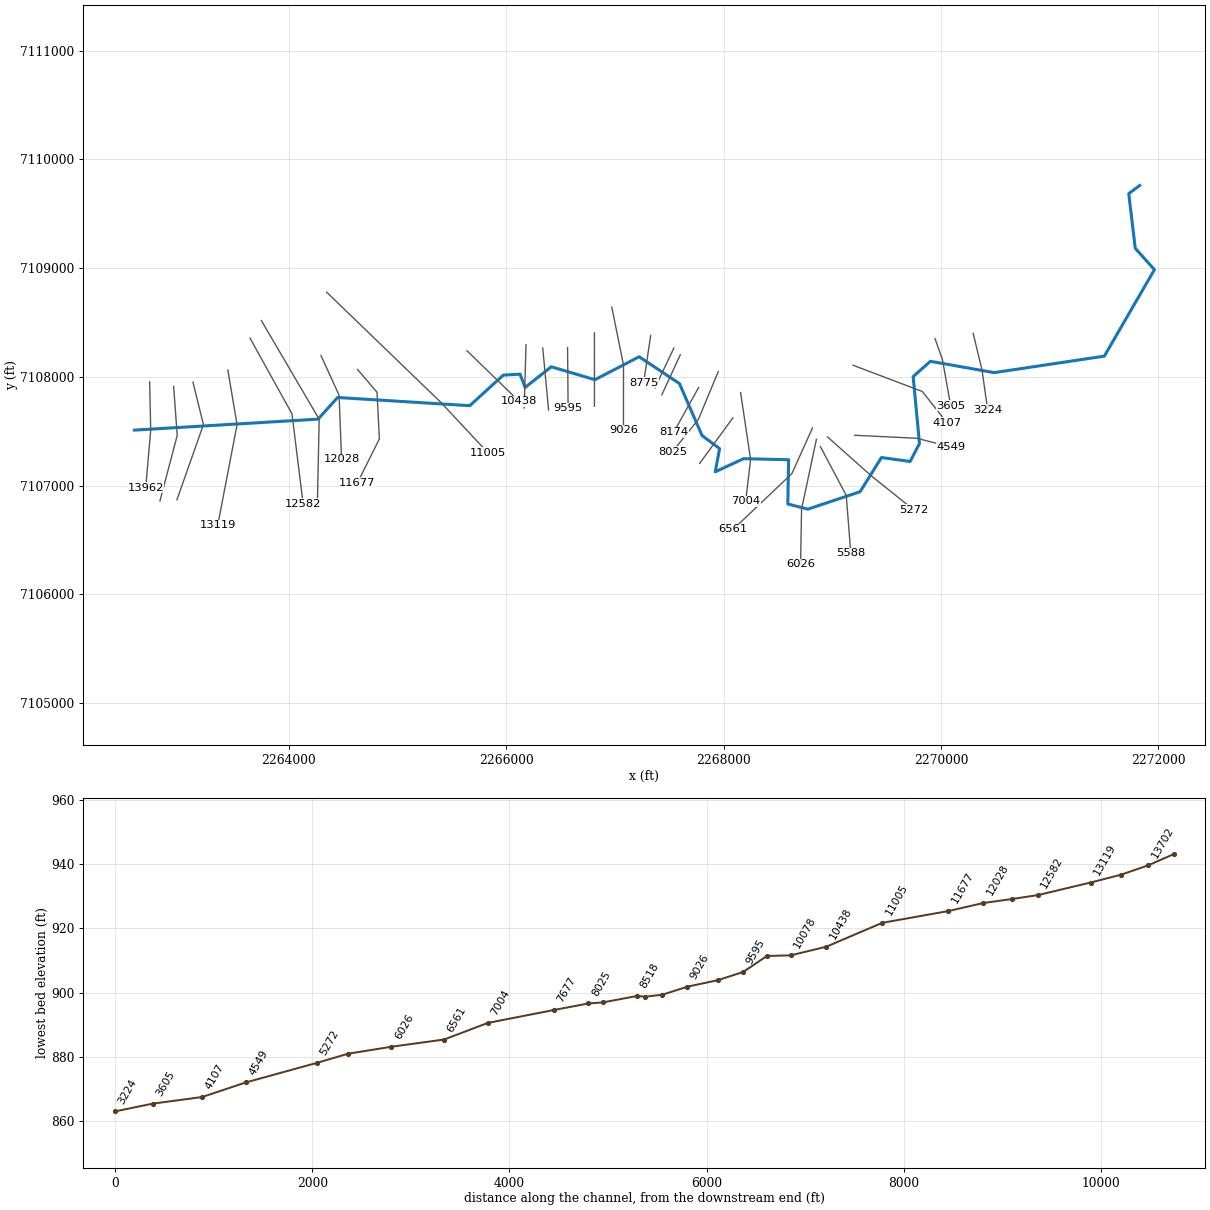
--- MDW T 007.prj (project) ---

Proj Title=MDW T 007 Base Level Engineering
Current Plan=p01
Default Exp/Contr=0.3,0.1
English Units
Geom File=g01
Flow File=f01
Plan File=p01
BEGIN DESCRIPTION:
MDW T 007
END DESCRIPTION:

--- MDW T 007.p01 (plan) ---

Plan Title=Multiple Run
Short Identifier=Multiple
Geom File=g01
Flow File=f01
Subcritical Flow
K Sum by GR= 0
Std Step Tol= 0.01
Critical Tol= 0.01
Num of Std Step Trials= 20
Max Error Tol= 0.3
Flow Tol Ratio= 0.001
Split Flow NTrial= 30
Split Flow Tol= 0.02
Split Flow Ratio= 0.02
Log Output Level= 0
Friction Slope Method= 1
Unsteady Friction Slope Method= 2
Unsteady Bridges Friction Slope Method= 1
Parabolic Critical Depth
Global Vel Dist=  1 , 1 , 1
Global Log Level= 0
CheckData=True
Encroach Param= -1, 0, 0, 0
BEGIN DESCRIPTION:
Multiple Run
END DESCRIPTION:

--- MDW T 007.f01 (steady flow) ---

Flow Title=Multiple
Number of Profiles=7
Profile Names=10-year,25-year,50-year,1pct_min,100-year,1pct_plu,500-year
River Rch & RM= MDW T 007,Reach-1,13962
     386     515     618     369     737    1470    1048
River Rch & RM= MDW T 007,Reach-1,10078
     620     852    1042     634    1264    2522    1864
River Rch & RM= MDW T 007,Reach-1,7004
     649     892    1093     665    1327    2647    1959
River Rch & RM= MDW T 007,Reach-1,5272
     739    1024    1261     771    1538    3069    2294
River Rch & RM= MDW T 007,Reach-1,2317
     882    1234    1530     940    1877    3744    2832
Boundary for River Rch & Prof#=MDW T 007,Reach-1,1
Up Type=0
Dn Type=3
Dn Slope=0.005
Boundary for River Rch & Prof#=MDW T 007,Reach-1,2
Up Type=0
Dn Type=3
Dn Slope=0.005
Boundary for River Rch & Prof#=MDW T 007,Reach-1,3
Up Type=0
Dn Type=3
Dn Slope=0.005
Boundary for River Rch & Prof#=MDW T 007,Reach-1,4
Up Type=0
Dn Type=3
Dn Slope=0.005
Boundary for River Rch & Prof#=MDW T 007,Reach-1,5
Up Type=0
Dn Type=3
Dn Slope=0.005
Boundary for River Rch & Prof#=MDW T 007,Reach-1,6
Up Type=0
Dn Type=3
Dn Slope=0.005
Boundary for River Rch & Prof#=MDW T 007,Reach-1,7
Up Type=0
Dn Type=3
Dn Slope=0.005

--- MDW T 007.g01 (geometry) ---

Geom Title=Existing Conditions

River Reach=MDW T 007,Reach-1
Reach XY= 30
      2262579.00      7107510.00      2264268.53      7107610.93
      2264448.88      7107810.09      2265664.88      7107734.77
      2265973.63      7108016.01      2266127.98      7108024.84
      2266173.95      7107902.37      2266415.04      7108092.66
      2266815.92      7107973.47      2267223.70      7108184.57
      2267594.64      7107937.77      2267802.09      7107459.93
      2267963.87      7107340.01      2267923.51      7107126.41
      2268183.93      7107247.29      2268598.75      7107237.84
      2268591.34      7106830.56      2268776.11      7106783.42
      2269256.60      7106943.39      2269452.93      7107257.67
      2269717.30      7107221.64      2269802.94      7107386.81
      2269744.86      7108002.27      2269902.95      7108142.94
      2270490.52      7108038.88      2271504.10      7108190.57
      2271964.86      7108985.65      2271788.66      7109182.41
      2271728.62      7109685.21      2271829.00      7109760.00

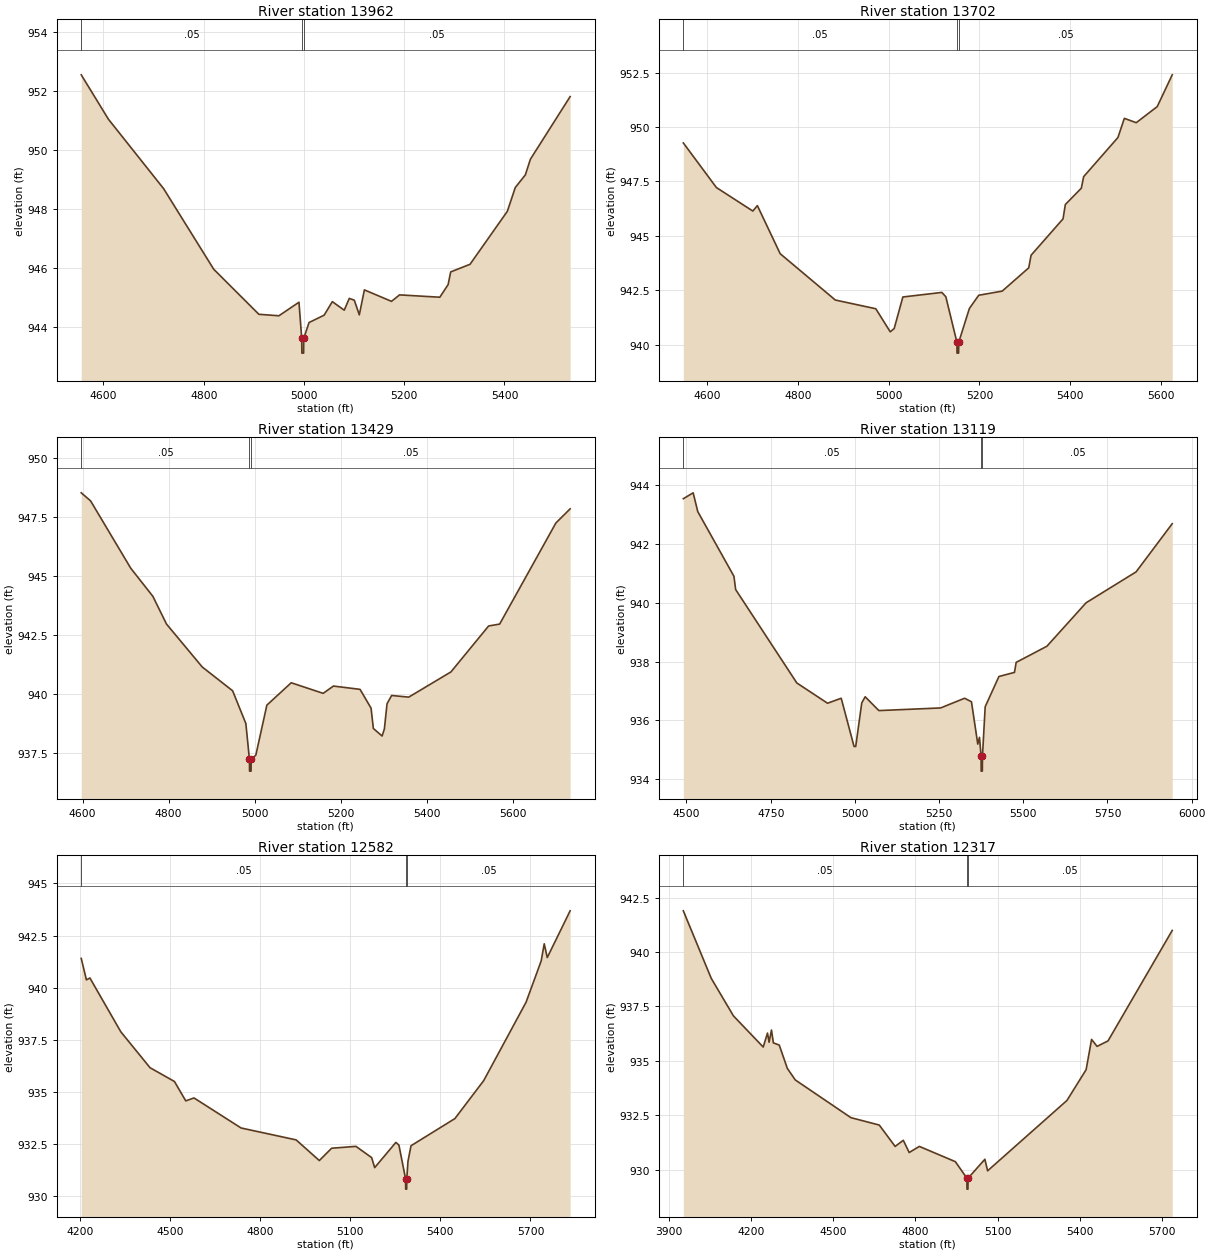
Type RM Length L Ch R = 1,13962,260,260,260
BEGIN DESCRIPTION:
MDW T 007 35.0
END DESCRIPTION:
XS GIS Cut Line= 3
      2262718.90      7107954.32      2262729.00      7107510.00
      2262683.09      7106981.02
#Sta/Elev= 30
  4555.6  952.56  4609.9  951.05  4720.0  948.69  4820.0  945.95  4910.0  944.42
  4950.0  944.37  4990.0  944.83  4995.5  943.60  4995.8  943.10  4999.3  943.10
  4999.5  943.60  5010.1  944.14  5040.2  944.39  5056.6  944.85  5080.3  944.56
  5090.4  944.96  5100.4  944.90  5110.4  944.40  5120.5  945.25  5174.6  944.86
  5190.7  945.08  5271.0  945.00  5287.6  945.43  5292.7  945.86  5331.3  946.12
  5405.7  947.92  5421.6  948.73  5441.7  949.16  5451.7  949.69  5531.0  951.82
#Mann=3,-1,0
  4555.6    0.05       0  4995.5   0.033       0  4999.5    0.05       0
Bank Sta=4995.5,4999.5
Exp/Cntr=0.3,0.1

Type RM Length L Ch R = 1,13702,273,273,273
BEGIN DESCRIPTION:
MDW T 007 34.0
END DESCRIPTION:
XS GIS Cut Line= 3
      2262939.76      7107912.58      2262972.89      7107461.80
      2262813.94      7106858.07
#Sta/Elev= 30
  4548.0  949.27  4620.8  947.22  4701.0  946.14  4711.0  946.39  4761.2  944.18
  4882.6  942.05  4971.7  941.65  5003.5  940.59  5012.2  940.74  5031.3  942.19
  5117.1  942.40  5125.9  942.20  5150.3  940.11  5150.5  939.61  5154.0  939.61
  5154.3  940.11  5177.7  941.66  5198.3  942.27  5250.0  942.46  5308.4  943.53
  5313.6  944.11  5383.9  945.78  5389.0  946.44  5424.2  947.19  5429.3  947.72
  5504.8  949.52  5518.9  950.40  5545.1  950.20  5591.3  950.94  5624.3  952.40
#Mann=3,-1,0
  4548.0    0.05       0  5150.3   0.033       0  5154.3    0.05       0
Bank Sta=5150.3,5154.3
Exp/Cntr=0.3,0.1

Type RM Length L Ch R = 1,13429,310,310,310
BEGIN DESCRIPTION:
MDW T 007 33.0
END DESCRIPTION:
XS GIS Cut Line= 3
      2263117.72      7107951.59      2263213.94      7107560.14
      2262970.15      7106868.76
#Sta/Elev= 30
  4596.9  948.53  4618.6  948.19  4712.0  945.33  4763.3  944.14  4795.1  942.96
  4878.1  941.14  4948.7  940.13  4979.5  938.74  4987.8  937.22  4988.1  936.72
  4991.6  936.72  4991.8  937.22  5002.7  937.40  5028.3  939.52  5084.9  940.47
  5159.2  940.02  5183.0  940.33  5244.9  940.19  5270.5  939.39  5275.8  938.53
  5296.1  938.21  5301.4  938.51  5307.6  939.58  5318.3  939.93  5358.0  939.86
  5456.1  940.93  5543.7  942.88  5569.3  942.96  5700.0  947.25  5733.1  947.85
#Mann=3,-1,0
  4596.9    0.05       0  4987.8   0.033       0  4991.8    0.05       0
Bank Sta=4987.8,4991.8
Exp/Cntr=0.3,0.1

Type RM Length L Ch R = 1,13119,537,537,537
BEGIN DESCRIPTION:
MDW T 007 32.0
END DESCRIPTION:
XS GIS Cut Line= 3
      2263438.89      7108062.31      2263523.53      7107559.99
      2263345.63      7106634.63
#Sta/Elev= 30
  4490.6  943.54  4519.8  943.74  4533.5  943.10  4640.9  940.90  4645.9  940.45
  4827.6  937.27  4918.9  936.58  4959.4  936.75  4997.5  935.11  5002.5  935.11
  5020.4  936.59  5030.5  936.80  5071.3  936.33  5254.6  936.42  5325.8  936.75
  5346.2  936.63  5364.9  935.19  5370.0  935.42  5374.8  934.77  5375.0  934.27
  5378.5  934.27  5378.8  934.77  5386.9  936.46  5427.7  937.49  5473.9  937.63
  5478.9  937.97  5570.2  938.52  5686.7  940.00  5835.0  941.05  5942.3  942.69
#Mann=3,-1,0
  4490.6    0.05       0  5374.8   0.033       0  5378.8    0.05       0
Bank Sta=5374.8,5378.8
Exp/Cntr=0.3,0.1

Type RM Length L Ch R = 1,12582,265,265,265
BEGIN DESCRIPTION:
MDW T 007 30.0
END DESCRIPTION:
XS GIS Cut Line= 3
      2263642.89      7108355.26      2264029.00      7107660.00
      2264131.11      7106834.46
#Sta/Elev= 30
  4204.9  941.41  4222.2  940.38  4233.8  940.47  4336.7  937.89  4433.9  936.17
  4515.1  935.51  4552.8  934.58  4580.3  934.72  4737.0  933.28  4920.1  932.71
  4997.3  931.72  5038.2  932.31  5119.2  932.40  5171.5  931.86  5181.5  931.38
  5252.1  932.59  5262.2  932.46  5284.3  930.85  5284.6  930.35  5288.1  930.35
  5288.3  930.85  5292.4  931.69  5302.5  932.43  5448.4  933.73  5544.3  935.55
  5685.4  939.31  5735.7  941.29  5745.8  942.11  5755.9  941.45  5832.0  943.69
#Mann=3,-1,0
  4204.9    0.05       0  5284.3   0.033       0  5288.3    0.05       0
Bank Sta=5284.3,5288.3
Exp/Cntr=0.3,0.1

Type RM Length L Ch R = 1,12317,289,289,289
BEGIN DESCRIPTION:
MDW T 007 29.0
END DESCRIPTION:
XS GIS Cut Line= 3
      2263747.03      7108518.08      2264279.00      7107610.00
      2264263.54      7106875.29
#Sta/Elev= 30
  3951.4  941.89  4053.5  938.79  4134.6  937.07  4243.4  935.64  4259.1  936.28
  4264.9  935.86  4273.7  936.42  4280.6  935.83  4302.1  935.73  4331.6  934.66
  4360.7  934.13  4564.0  932.40  4667.7  932.06  4725.7  931.08  4755.6  931.36
  4777.1  930.80  4814.2  931.08  4945.9  930.38  4988.2  929.62  4988.4  929.12
  4991.9  929.12  4992.2  929.62  5053.8  930.49  5063.8  929.96  5353.9  933.19
  5423.9  934.60  5443.9  935.99  5463.9  935.67  5503.9  935.92  5738.7  940.99
#Mann=3,-1,0
  3951.4    0.05       0  4988.2   0.033       0  4992.2    0.05       0
Bank Sta=4988.2,4992.2
Exp/Cntr=0.3,0.1

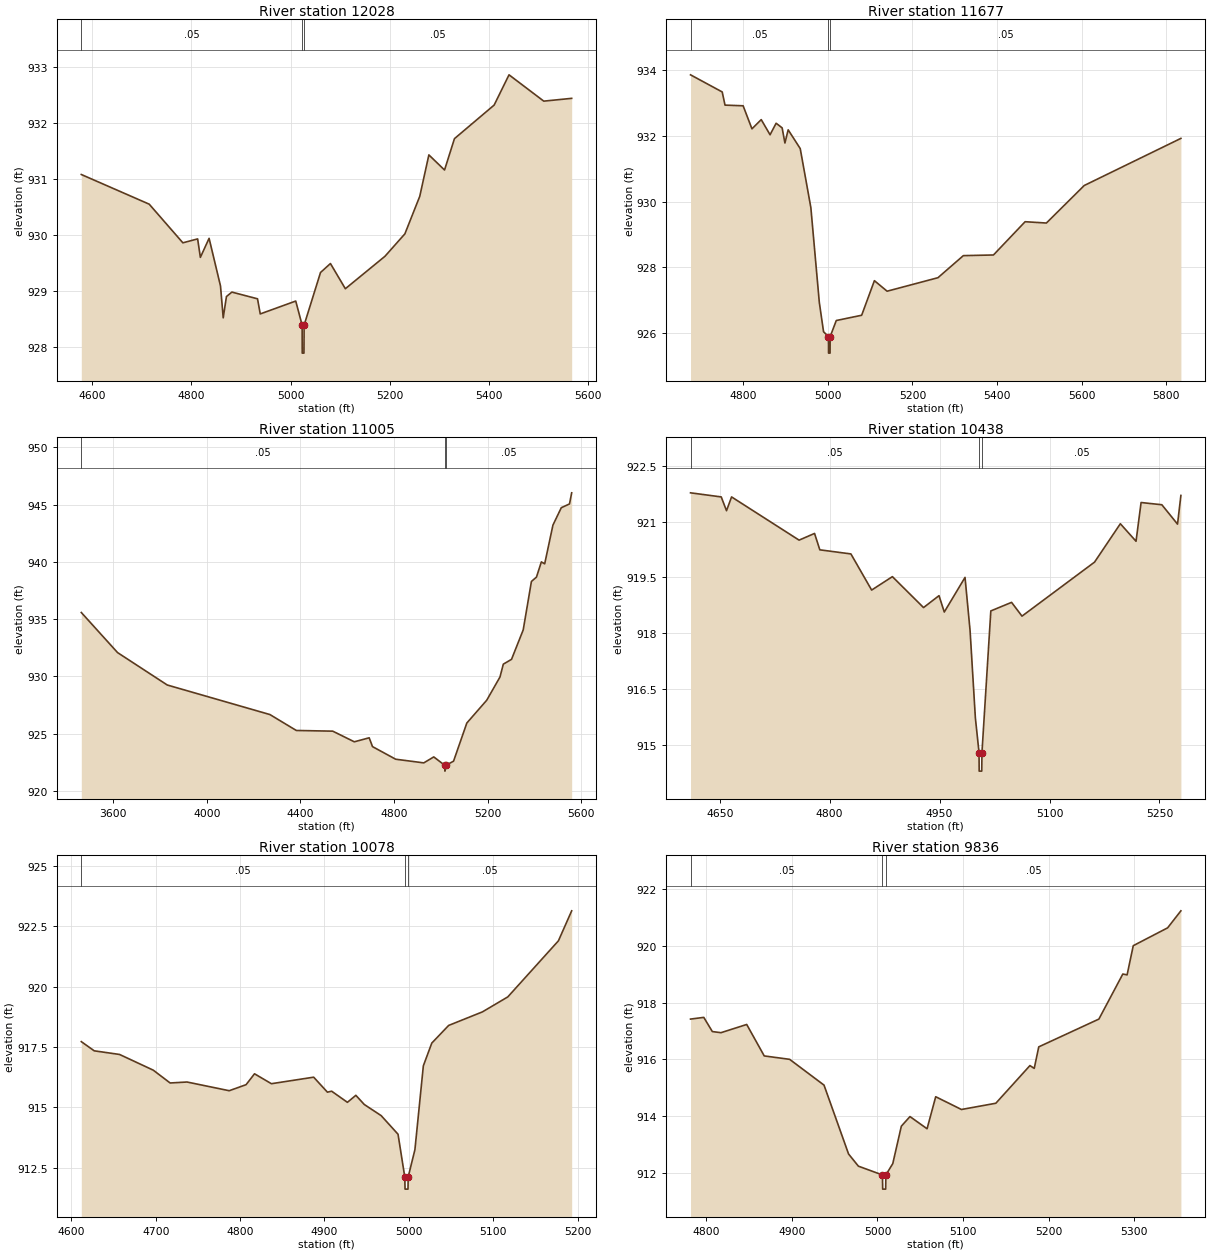
Type RM Length L Ch R = 1,12028,351,351,351
BEGIN DESCRIPTION:
Mapping XS dff9fead
END DESCRIPTION:
XS GIS Cut Line= 3
      2264295.75      7108196.45      2264462.22      7107830.90
      2264485.07      7107243.71
#Sta/Elev= 30
  4577.9  931.08  4714.9  930.55  4782.8  929.86  4812.6  929.93  4818.1  929.60
  4835.7  929.94  4858.7  929.09  4864.2  928.52  4870.7  928.90  4881.7  928.98
  4933.4  928.86  4938.9  928.59  5010.5  928.82  5023.4  928.39  5023.6  927.89
  5027.1  927.89  5027.4  928.39  5060.5  929.33  5080.5  929.49  5110.6  929.04
  5190.6  929.62  5230.7  930.02  5260.7  930.69  5279.1  931.43  5310.7  931.16
  5330.7  931.72  5410.8  932.32  5440.8  932.86  5510.9  932.39  5567.2  932.44
#Mann=3,-1,0
  4577.9    0.05       0  5023.4   0.033       0  5027.4    0.05       0
Bank Sta=5023.4,5027.4
Exp/Cntr=0.3,0.1

Type RM Length L Ch R = 1,11677,672,672,672
BEGIN DESCRIPTION:
Mapping XS 4e10c519
END DESCRIPTION:
XS GIS Cut Line= 4
      2264631.87      7108067.96      2264811.48      7107858.35
      2264832.91      7107429.14      2264630.60      7107023.58
#Sta/Elev= 30
  4675.6  933.85  4750.5  933.33  4757.1  932.93  4799.9  932.91  4820.8  932.21
  4842.7  932.49  4863.6  932.03  4877.9  932.38  4892.1  932.24  4898.7  931.78
  4906.4  932.18  4934.9  931.61  4960.0  929.82  4980.0  926.94  4990.0  926.05
  5001.6  925.90  5001.9  925.40  5005.4  925.40  5005.6  925.90  5020.1  926.39
  5080.1  926.55  5110.2  927.60  5140.2  927.28  5260.4  927.69  5320.4  928.36
  5391.6  928.38  5466.4  929.39  5516.7  929.35  5606.2  930.49  5834.6  931.92
#Mann=3,-1,0
  4675.6    0.05       0  5001.6   0.033       0  5005.6    0.05       0
Bank Sta=5001.6,5005.6
Exp/Cntr=0.3,0.1

Type RM Length L Ch R = 1,11005,567,567,567
BEGIN DESCRIPTION:
MDW T 007 25.0
END DESCRIPTION:
XS GIS Cut Line= 3
      2264348.20      7108778.44      2265404.01      7107760.02
      2265832.55      7107300.60
#Sta/Elev= 30
  3463.7  935.58  3618.6  932.08  3830.9  929.25  4269.5  926.67  4382.4  925.28
  4538.1  925.22  4630.2  924.29  4693.7  924.64  4707.9  923.87  4806.9  922.77
  4927.0  922.45  4969.7  922.97  5017.1  922.23  5017.3  921.73  5021.1  922.23
  5054.2  922.60  5110.9  925.93  5195.9  927.92  5252.6  929.95  5266.8  931.07
  5301.9  931.49  5351.8  934.06  5386.9  938.29  5408.4  938.67  5429.4  940.00
  5443.6  939.83  5478.8  943.21  5514.5  944.73  5549.6  945.06  5558.9  946.03
#Mann=3,-1,0
  3463.7    0.05       0  5017.1   0.033       0  5021.1    0.05       0
Bank Sta=5017.1,5021.1
Exp/Cntr=0.3,0.1

Type RM Length L Ch R = 1,10438,360,360,360
BEGIN DESCRIPTION:
Mapping XS bc81632b
END DESCRIPTION:
XS GIS Cut Line= 2
      2265639.39      7108239.76      2266119.75      7107774.12
#Sta/Elev= 30
  4610.2  921.77  4652.1  921.66  4659.3  921.29  4666.2  921.66  4758.3  920.50
  4779.4  920.68  4786.6  920.24  4829.0  920.13  4857.3  919.16  4885.6  919.52
  4928.1  918.69  4949.2  919.01  4956.4  918.57  4984.7  919.50  4991.6  918.07
  4998.8  915.73  5003.8  914.80  5004.0  914.30  5007.5  914.30  5007.8  914.80
  5019.9  918.60  5048.2  918.83  5062.4  918.46  5161.4  919.91  5196.6  920.94
  5218.0  920.47  5224.9  921.51  5253.2  921.45  5274.6  920.93  5279.2  921.70
#Mann=3,-1,0
  4610.2    0.05       0  5003.8   0.033       0  5007.8    0.05       0
Bank Sta=5003.8,5007.8
Exp/Cntr=0.3,0.1

Type RM Length L Ch R = 1,10078,242,242,242
BEGIN DESCRIPTION:
Mapping XS 75071e92
END DESCRIPTION:
XS GIS Cut Line= 2
      2266182.48      7108295.25      2266165.66      7107714.29
#Sta/Elev= 30
  4611.8  917.72  4627.1  917.34  4657.1  917.19  4697.1  916.54  4717.1  916.01
  4737.1  916.05  4787.1  915.69  4807.1  915.94  4817.1  916.39  4837.1  915.98
  4887.2  916.25  4903.5  915.63  4908.5  915.67  4927.2  915.21  4937.2  915.50
  4947.2  915.12  4967.2  914.66  4987.2  913.89  4995.2  912.12  4995.5  911.62
  4999.0  911.62  4999.2  912.12  5007.2  913.25  5017.2  916.72  5027.2  917.66
  5047.2  918.39  5087.2  918.95  5117.3  919.57  5177.3  921.89  5193.0  923.13
#Mann=3,-1,0
  4611.8    0.05       0  4995.2   0.033       0  4999.2    0.05       0
Bank Sta=4995.2,4999.2
Exp/Cntr=0.3,0.1

Type RM Length L Ch R = 1,9836,241,241,241
BEGIN DESCRIPTION:
Mapping XS 319b402a
END DESCRIPTION:
XS GIS Cut Line= 2
      2266336.35      7108265.43      2266390.10      7107694.55
#Sta/Elev= 30
  4781.4  917.42  4796.9  917.48  4806.9  916.98  4817.0  916.94  4847.1  917.23
  4867.6  916.12  4897.3  916.00  4937.5  915.09  4966.2  912.66  4977.7  912.23
  5005.8  911.92  5006.1  911.42  5009.6  911.42  5009.8  911.92  5017.9  912.32
  5027.9  913.64  5038.0  913.98  5058.0  913.55  5068.1  914.68  5098.2  914.23
  5138.4  914.45  5178.3  915.78  5183.3  915.68  5188.6  916.44  5258.9  917.42
  5286.9  919.01  5291.9  918.98  5299.1  920.01  5339.3  920.64  5354.8  921.24
#Mann=3,-1,0
  4781.4    0.05       0  5005.8   0.033       0  5009.8    0.05       0
Bank Sta=5005.8,5009.8
Exp/Cntr=0.3,0.1

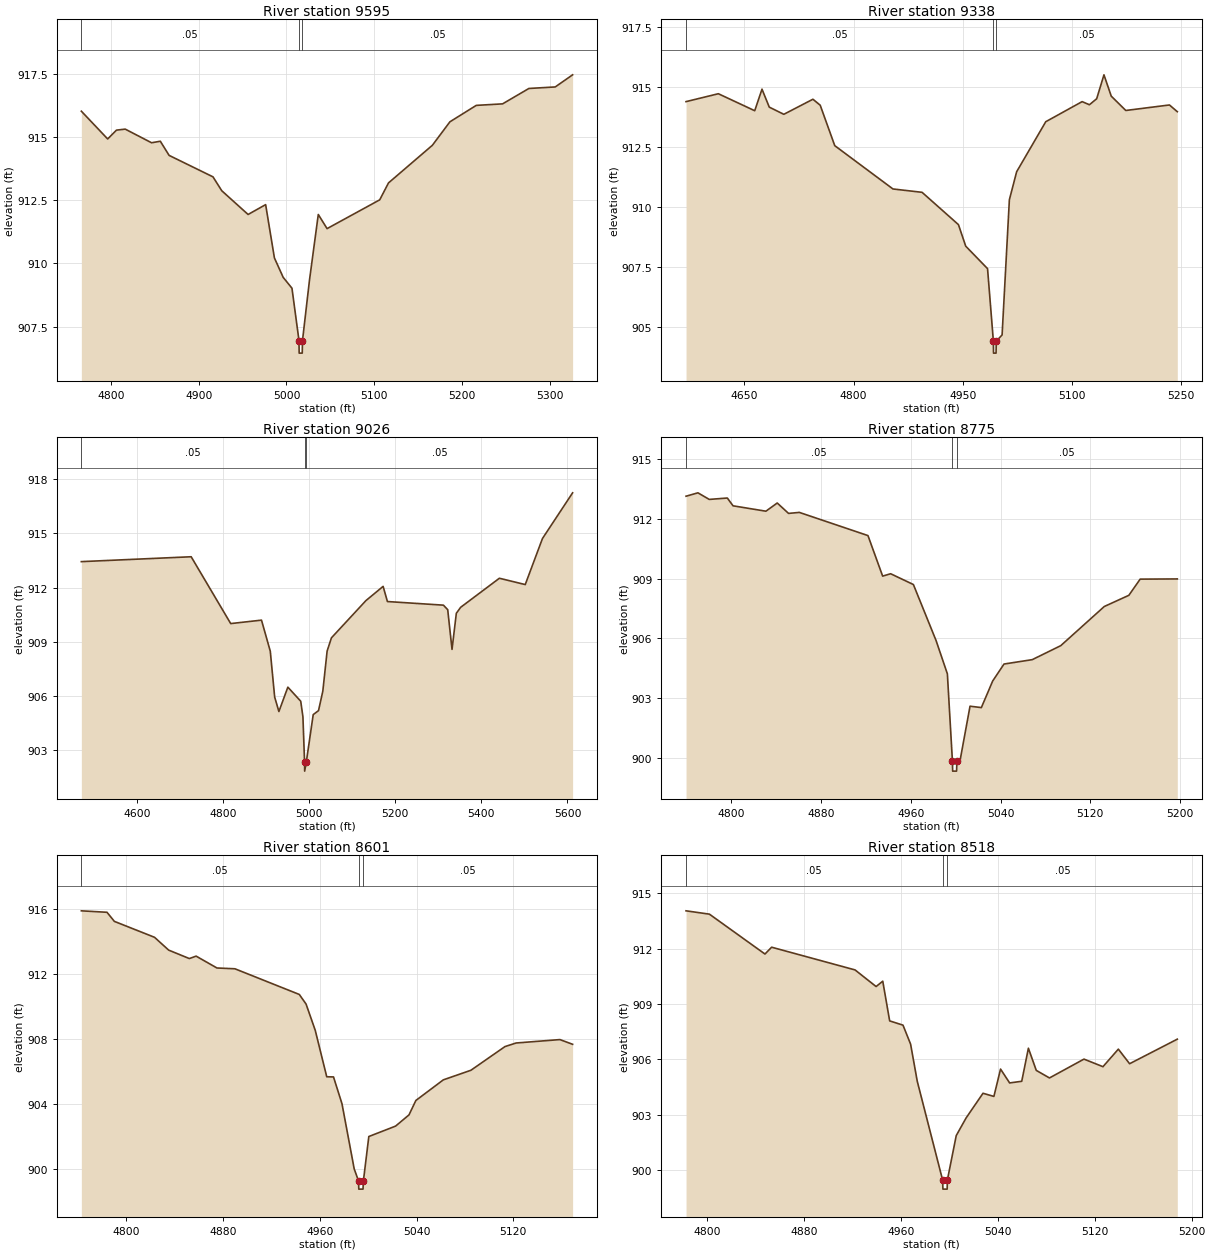
Type RM Length L Ch R = 1,9595,257,257,257
BEGIN DESCRIPTION:
Mapping XS 1ab93bcf
END DESCRIPTION:
XS GIS Cut Line= 2
      2266564.67      7108269.96      2266569.86      7107710.19
#Sta/Elev= 30
  4766.3  916.03  4796.3  914.93  4806.3  915.28  4816.3  915.32  4846.3  914.78
  4856.3  914.84  4866.3  914.28  4916.3  913.43  4926.3  912.88  4956.3  911.94
  4976.3  912.33  4986.3  910.22  4996.3  909.45  5006.3  909.02  5014.3  906.95
  5014.5  906.45  5018.0  906.45  5018.3  906.95  5026.3  909.35  5036.3  911.94
  5046.3  911.38  5106.3  912.52  5116.3  913.19  5166.3  914.68  5186.3  915.61
  5216.3  916.26  5246.3  916.32  5276.3  916.93  5306.3  916.99  5326.1  917.47
#Mann=3,-1,0
  4766.3    0.05       0  5014.3   0.033       0  5018.3    0.05       0
Bank Sta=5014.3,5018.3
Exp/Cntr=0.3,0.1

Type RM Length L Ch R = 1,9338,312,312,312
BEGIN DESCRIPTION:
Mapping XS 06f17f90
END DESCRIPTION:
XS GIS Cut Line= 2
      2266812.00      7108404.38      2266812.20      7107729.18
#Sta/Elev= 30
  4569.7  914.40  4614.1  914.73  4664.1  914.02  4674.1  914.92  4684.1  914.17
  4704.1  913.87  4744.1  914.50  4754.1  914.25  4774.1  912.56  4854.1  910.75
  4894.1  910.61  4944.1  909.26  4954.1  908.36  4984.1  907.42  4992.1  904.39
  4992.3  903.89  4995.8  903.89  4996.1  904.39  5004.1  904.65  5014.1  910.30
  5024.1  911.47  5064.1  913.56  5114.1  914.40  5124.1  914.27  5134.1  914.52
  5144.1  915.52  5154.1  914.63  5174.1  914.03  5234.1  914.26  5244.9  913.98
#Mann=3,-1,0
  4569.7    0.05       0  4992.1   0.033       0  4996.1    0.05       0
Bank Sta=4992.1,4996.1
Exp/Cntr=0.3,0.1

Type RM Length L Ch R = 1,9026,251,251,251
BEGIN DESCRIPTION:
MDW T 007 19.0
END DESCRIPTION:
XS GIS Cut Line= 3
      2266971.98      7108639.94      2267079.41      7108109.59
      2267079.00      7107510.01
#Sta/Elev= 30
  4471.2  913.44  4726.2  913.71  4818.0  910.01  4889.5  910.20  4909.9  908.48
  4920.1  905.94  4929.9  905.14  4950.7  906.49  4980.6  905.71  4985.7  904.85
  4989.5  902.34  4989.7  901.84  4993.5  902.34  5009.6  904.97  5021.9  905.19
  5031.9  906.27  5041.9  908.49  5051.9  909.22  5131.9  911.28  5171.9  912.07
  5181.9  911.23  5311.9  911.03  5321.9  910.78  5331.9  908.58  5341.9  910.58
  5351.9  910.91  5441.9  912.52  5501.9  912.17  5541.9  914.72  5611.9  917.25
#Mann=3,-1,0
  4471.2    0.05       0  4989.5    0.04       0  4993.5    0.05       0
Bank Sta=4989.5,4993.5
Exp/Cntr=0.3,0.1

Type RM Length L Ch R = 1,8775,174,174,174
BEGIN DESCRIPTION:
Mapping XS 5e03c114
END DESCRIPTION:
XS GIS Cut Line= 2
      2267329.58      7108380.44      2267264.88      7107947.24
#Sta/Elev= 30
  4759.6  913.12  4770.2  913.29  4780.3  912.96  4796.4  913.03  4801.5  912.64
  4830.8  912.37  4840.9  912.78  4851.0  912.26  4860.6  912.31  4921.8  911.15
  4934.9  909.12  4942.0  909.24  4962.3  908.70  4982.5  905.90  4992.6  904.23
  4997.1  899.86  4997.3  899.36  5000.8  899.36  5001.1  899.86  5004.1  899.95
  5012.8  902.61  5022.9  902.54  5033.0  903.87  5043.1  904.72  5068.3  904.94
  5093.7  905.64  5132.5  907.60  5154.4  908.16  5164.5  908.97  5197.6  908.98
#Mann=3,-1,0
  4759.6    0.05       0  4997.1    0.04       0  5001.1    0.05       0
Bank Sta=4997.1,5001.1
Exp/Cntr=0.3,0.1

Type RM Length L Ch R = 1,8601,83,83,83
BEGIN DESCRIPTION:
Mapping XS 88d573b1
END DESCRIPTION:
XS GIS Cut Line= 2
      2267542.86      7108264.66      2267368.43      7107897.82
#Sta/Elev= 30
  4762.8  915.89  4784.0  915.80  4790.1  915.24  4823.3  914.26  4835.0  913.47
  4852.1  912.95  4857.7  913.10  4874.9  912.37  4889.8  912.32  4943.0  910.74
  4948.6  910.15  4956.2  908.53  4965.7  905.67  4971.3  905.66  4978.3  904.01
  4988.4  900.00  4992.0  899.25  4992.2  898.75  4995.7  898.75  4996.0  899.25
  5000.5  901.99  5022.6  902.63  5033.7  903.32  5039.4  904.21  5062.1  905.48
  5084.9  906.07  5113.1  907.53  5122.3  907.75  5158.5  907.96  5169.0  907.67
#Mann=3,-1,0
  4762.8    0.05       0  4992.0   0.033       0  4996.0    0.05       0
Bank Sta=4992,4996
Exp/Cntr=0.3,0.1

Type RM Length L Ch R = 1,8518,344,344,344
BEGIN DESCRIPTION:
Mapping XS 59a38dec
END DESCRIPTION:
XS GIS Cut Line= 2
      2267602.03      7108202.71      2267432.01      7107834.24
#Sta/Elev= 30
  4782.3  914.04  4801.6  913.86  4847.5  911.70  4853.0  912.07  4921.9  910.84
  4939.3  909.94  4944.8  910.23  4950.5  908.08  4961.5  907.85  4967.8  906.82
  4973.3  904.81  4994.2  899.47  4994.5  898.97  4998.0  898.97  4998.2  899.47
  5005.5  901.87  5013.7  902.83  5027.6  904.16  5036.6  903.99  5042.1  905.47
  5049.6  904.72  5059.6  904.81  5065.1  906.60  5071.6  905.40  5082.5  904.99
  5111.0  906.01  5126.7  905.60  5139.4  906.55  5148.7  905.76  5188.1  907.09
#Mann=3,-1,0
  4782.3    0.05       0  4994.2   0.033       0  4998.2    0.05       0
Bank Sta=4994.2,4998.2
Exp/Cntr=0.3,0.1

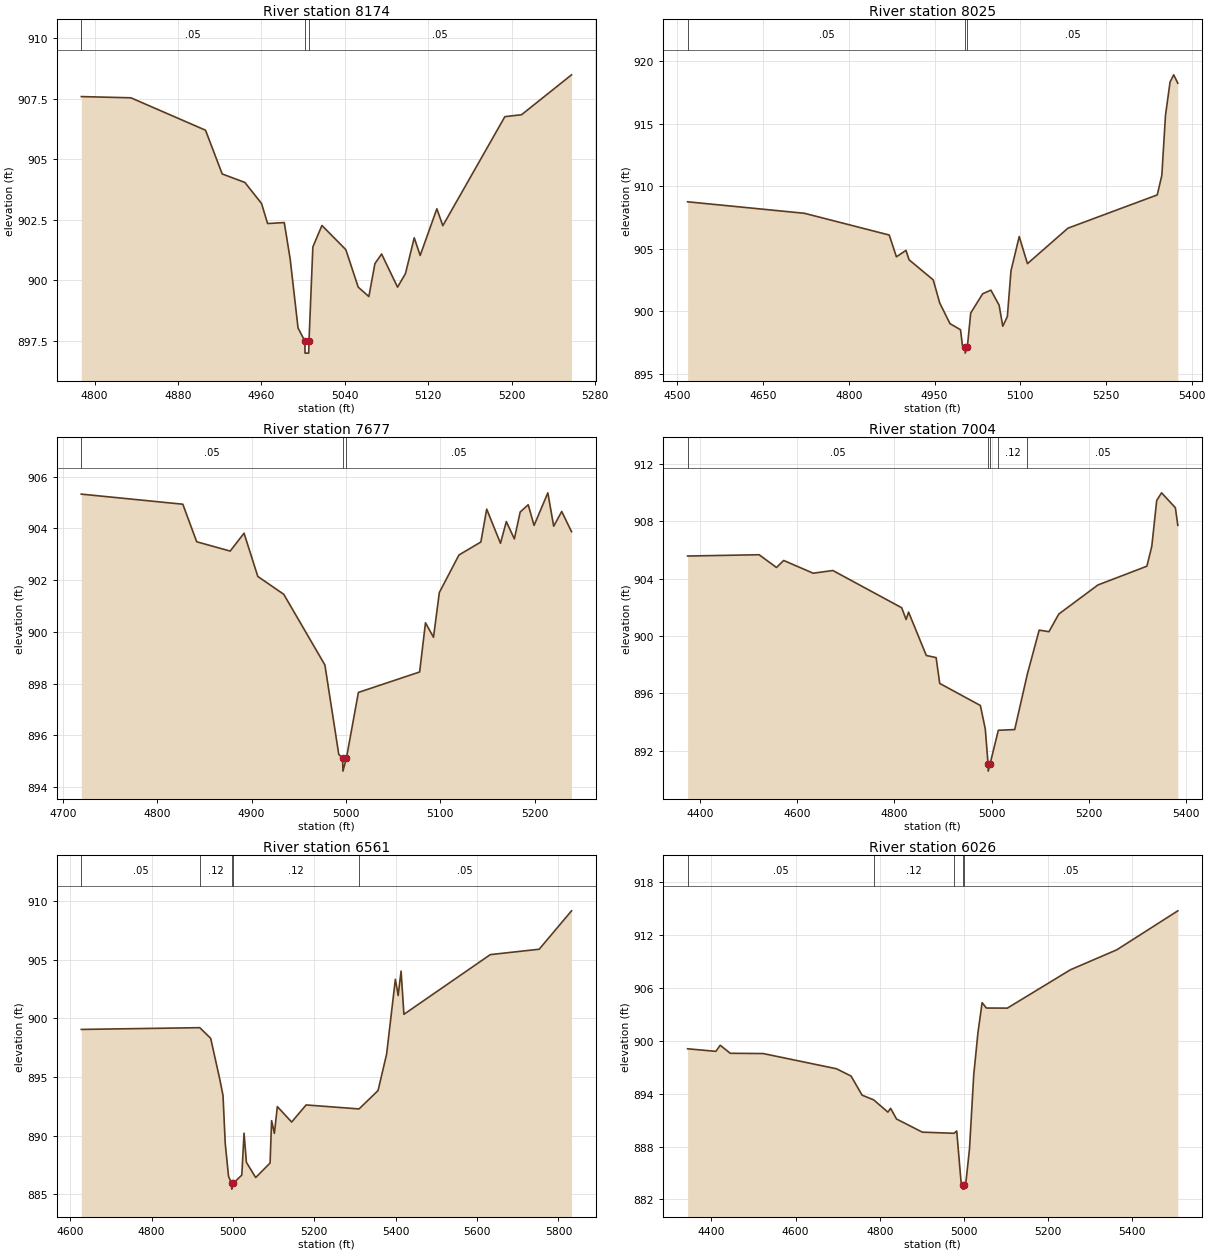
Type RM Length L Ch R = 1,8174,149,149,149
BEGIN DESCRIPTION:
Mapping XS af9f3a4e
END DESCRIPTION:
XS GIS Cut Line= 2
      2267770.56      7107901.54      2267541.95      7107490.88
#Sta/Elev= 30
  4787.3  907.59  4834.8  907.54  4906.4  906.20  4922.4  904.39  4944.1  904.04
  4960.1  903.17  4965.9  902.34  4981.9  902.38  4987.6  900.86  4995.1  898.02
  5001.6  897.48  5001.8  896.98  5005.3  896.98  5005.6  897.48  5009.3  901.37
  5018.0  902.26  5040.9  901.26  5052.8  899.71  5063.0  899.32  5068.8  900.68
  5075.2  901.08  5090.5  899.71  5098.1  900.27  5106.5  901.75  5112.2  901.02
  5128.2  902.95  5133.9  902.25  5193.4  906.76  5209.4  906.84  5257.3  908.49
#Mann=3,-1,0
  4787.3    0.05       0  5001.6   0.033       0  5005.6    0.05       0
Bank Sta=5001.6,5005.6
Exp/Cntr=0.3,0.1

Type RM Length L Ch R = 1,8025,348,348,348
BEGIN DESCRIPTION:
MDW T 007 16.0
END DESCRIPTION:
XS GIS Cut Line= 3
      2267950.93      7108047.52      2267768.48      7107608.50
      2267529.01      7107310.01
#Sta/Elev= 30
  4517.7  908.75  4722.2  907.83  4870.7  906.09  4883.2  904.35  4900.0  904.86
  4905.4  904.11  4947.7  902.50  4959.0  900.66  4977.0  899.00  4995.4  898.51
  4998.9  897.23  5003.4  897.14  5003.6  896.64  5007.4  897.14  5013.3  899.85
  5034.2  901.39  5048.6  901.68  5063.0  900.48  5069.4  898.79  5077.4  899.56
  5083.8  903.23  5098.2  905.97  5112.6  903.80  5183.5  906.64  5339.8  909.30
  5347.8  910.86  5354.2  915.66  5362.2  918.33  5368.6  918.91  5375.8  918.24
#Mann=3,-1,0
  4517.7    0.05       0  5003.4   0.033       0  5007.4    0.05       0
Bank Sta=5003.4,5007.4
Exp/Cntr=0.3,0.1

Type RM Length L Ch R = 1,7677,673,673,673
BEGIN DESCRIPTION:
Mapping XS aedb131f
END DESCRIPTION:
XS GIS Cut Line= 2
      2268086.39      7107623.32      2267780.02      7107203.65
#Sta/Elev= 30
  4719.5  905.32  4827.1  904.93  4841.8  903.48  4877.3  903.12  4892.0  903.81
  4906.6  902.14  4934.1  901.45  4977.7  898.72  4992.4  895.27  4996.5  895.12
  4996.8  894.62  5000.5  895.12  5013.2  897.66  5078.1  898.45  5084.3  900.35
  5092.8  899.79  5099.0  901.52  5119.8  902.97  5143.0  903.47  5149.2  904.74
  5163.8  903.42  5170.0  904.26  5178.5  903.59  5184.7  904.63  5193.2  904.91
  5199.4  904.11  5214.0  905.37  5220.2  904.08  5228.7  904.65  5239.1  903.87
#Mann=3,-1,0
  4719.5    0.05       0  4996.5   0.033       0  5000.5    0.05       0
Bank Sta=4996.5,5000.5
Exp/Cntr=0.3,0.1

Type RM Length L Ch R = 1,7004,443,443,443
BEGIN DESCRIPTION:
MDW T 007 15.0
END DESCRIPTION:
XS GIS Cut Line= 3
      2268156.87      7107855.44      2268249.07      7107239.63
      2268203.78      7106856.88
#Sta/Elev= 30
  4374.9  905.59  4522.0  905.68  4557.7  904.79  4572.5  905.28  4633.2  904.39
  4673.6  904.58  4815.2  901.98  4824.3  901.16  4829.3  901.68  4865.8  898.65
  4886.0  898.50  4893.4  896.70  4977.0  895.16  4987.1  893.52  4992.8  891.08
  4993.1  890.58  4996.9  891.08  5013.9  893.43  5047.6  893.48  5073.5  897.34
  5097.9  900.42  5118.0  900.31  5138.2  901.54  5218.7  903.57  5319.4  904.88
  5329.5  906.27  5339.6  909.47  5349.6  910.00  5378.0  908.96  5383.0  907.73
#Mann=5,-1,0
  4374.9    0.05       0  4992.8   0.033       0  4996.9    0.05       0
  5013.9    0.12       0  5073.5    0.05       0
Bank Sta=4992.8,4996.9
Exp/Cntr=0.3,0.1

Type RM Length L Ch R = 1,6561,535,535,535
BEGIN DESCRIPTION:
MDW T 007 14.0
END DESCRIPTION:
XS GIS Cut Line= 3
      2268818.32      7107529.90      2268629.00      7107110.00
      2268089.14      7106597.62
#Sta/Elev= 30
  4627.2  899.06  4918.4  899.21  4945.2  898.30  4967.1  894.88  4975.5  893.42
  4981.0  889.31  4989.1  886.51  4996.5  885.92  4996.9  885.42  5000.7  885.92
  5021.7  886.62  5027.2  890.20  5033.0  887.71  5055.8  886.41  5091.2  887.65
  5094.9  891.27  5101.8  890.18  5109.0  892.47  5144.2  891.15  5179.8  892.61
  5309.9  892.27  5356.6  893.84  5377.6  896.95  5399.1  903.34  5406.0  901.96
  5413.2  904.04  5420.1  900.35  5632.5  905.45  5752.6  905.91  5832.1  909.19
#Mann=5,-1,0
  4627.2    0.05       0  4918.4    0.12       0  4996.5    0.07       0
  5000.7    0.12       0  5309.9    0.05       0
Bank Sta=4996.5,5000.7
Exp/Cntr=0.3,0.1

Type RM Length L Ch R = 1,6026,438,438,438
BEGIN DESCRIPTION:
MDW T 007 13.0
END DESCRIPTION:
XS GIS Cut Line= 3
      2268854.80      7107425.80      2268717.98      7106783.40
      2268708.96      7106274.89
#Sta/Elev= 30
  4343.2  899.08  4410.5  898.79  4420.7  899.48  4444.7  898.57  4522.9  898.54
  4696.8  896.82  4731.8  895.99  4758.1  893.82  4785.6  893.29  4819.4  891.90
  4825.8  892.33  4839.9  891.12  4901.2  889.63  4976.6  889.50  4983.0  889.76
  4993.3  883.99  4997.0  883.67  4997.4  883.17  5001.0  883.17  5001.3  883.67
  5004.2  883.67  5013.4  887.74  5023.4  896.08  5033.4  900.88  5043.4  904.31
  5053.4  903.70  5103.4  903.69  5253.4  908.04  5363.5  910.30  5508.6  914.72
#Mann=5,-1,0
  4343.2    0.05       0  4785.6    0.12       0  4976.6    0.05       0
  4997.0   0.033       0  5001.3    0.05       0
Bank Sta=4997,5001.3
Exp/Cntr=0.3,0.1

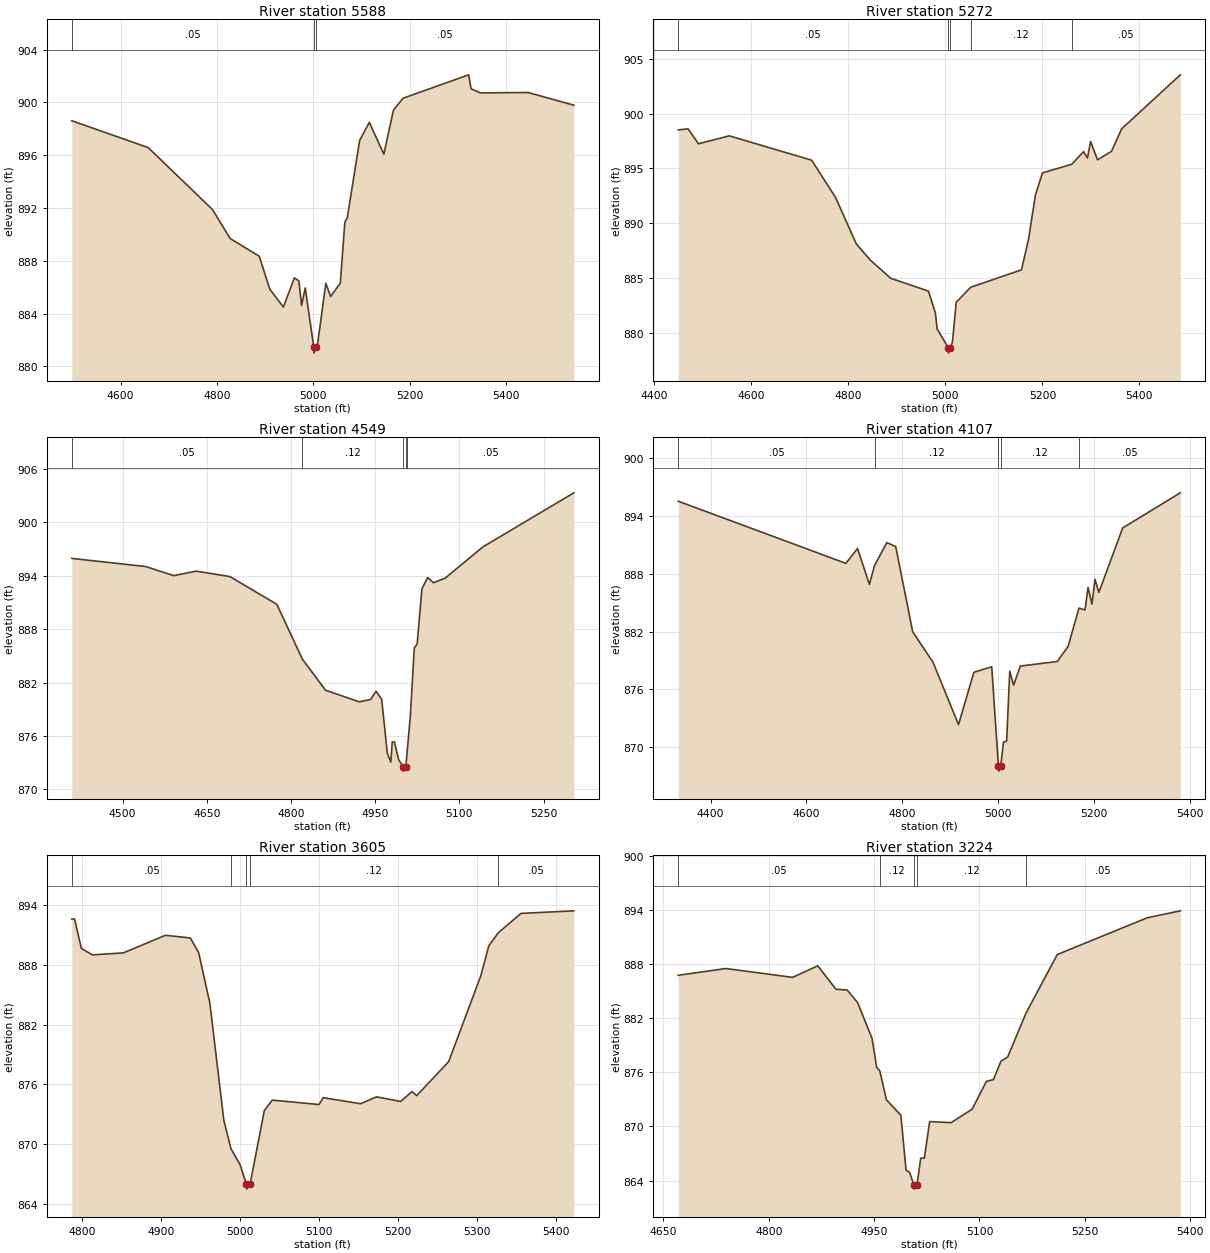
Type RM Length L Ch R = 1,5588,316,316,316
BEGIN DESCRIPTION:
MDW T 007 12.0
END DESCRIPTION:
XS GIS Cut Line= 3
      2268891.25      7107358.05      2269128.93      7106910.30
      2269171.19      7106376.79
#Sta/Elev= 30
  4498.5  898.61  4657.1  896.58  4790.7  891.88  4827.3  889.69  4887.6  888.35
  4909.6  885.85  4937.8  884.50  4960.5  886.71  4969.9  886.48  4975.5  884.62
  4983.1  885.95  5000.6  881.51  5001.0  881.01  5004.9  881.51  5008.1  881.51
  5025.8  886.30  5035.8  885.30  5055.9  886.31  5065.3  890.93  5070.3  891.25
  5096.0  897.12  5116.1  898.49  5146.2  896.08  5166.2  899.42  5186.3  900.32
  5322.3  902.09  5327.3  901.03  5346.8  900.72  5445.8  900.75  5540.6  899.79
#Mann=3,-1,0
  4498.5    0.05       0  5000.6   0.033       0  5004.9    0.05       0
Bank Sta=5000.6,5004.9
Exp/Cntr=0.3,0.1

Type RM Length L Ch R = 1,5272,723,723,723
BEGIN DESCRIPTION:
MDW T 007 11.0
END DESCRIPTION:
XS GIS Cut Line= 3
      2268957.56      7107447.04      2269358.65      7107090.07
      2269747.47      7106778.65
#Sta/Elev= 30
  4449.2  898.51  4469.3  898.61  4491.0  897.25  4554.5  897.97  4724.3  895.75
  4773.6  892.35  4816.3  888.13  4844.7  886.67  4887.3  884.99  4965.1  883.82
  4979.3  881.84  4983.0  880.37  5005.8  878.67  5006.2  878.17  5010.3  878.67
  5014.4  879.15  5022.4  882.81  5052.0  884.17  5156.9  885.76  5171.3  888.52
  5185.7  892.60  5200.1  894.59  5260.4  895.38  5284.9  896.53  5292.9  895.95
  5299.3  897.45  5313.7  895.79  5342.5  896.56  5363.4  898.61  5484.3  903.53
#Mann=5,-1,0
  4449.2    0.05       0  5005.8   0.033       0  5010.3    0.05       0
  5052.0    0.12       0  5260.4    0.05       0
Bank Sta=5005.8,5010.3
Exp/Cntr=0.3,0.1

Type RM Length L Ch R = 1,4549,442,442,442
BEGIN DESCRIPTION:
MDW T 007 10.0
END DESCRIPTION:
XS GIS Cut Line= 3
      2269207.53      7107462.66      2269779.01      7107434.88
      2270091.20      7107355.03
#Sta/Elev= 30
  4409.6  895.93  4541.2  895.02  4591.3  894.00  4631.3  894.50  4691.4  893.89
  4774.9  890.78  4820.3  884.64  4861.6  881.14  4921.7  879.84  4941.7  880.09
  4951.7  881.02  4961.7  880.11  4971.7  874.08  4978.0  873.07  4980.5  875.34
  4984.3  875.34  4992.1  873.31  5000.1  872.56  5000.6  872.06  5004.7  872.56
  5007.1  874.26  5012.7  878.22  5019.8  885.87  5024.9  886.33  5033.4  892.54
  5043.7  893.78  5054.0  893.20  5074.6  893.71  5142.2  897.23  5304.0  903.29
#Mann=5,-1,0
  4409.6    0.05       0  4820.3    0.12       0  5000.1    0.07       0
  5004.7    0.12       0  5007.1    0.05       0
Bank Sta=5000.1,5004.7
Exp/Cntr=0.3,0.1

Type RM Length L Ch R = 1,4107,502,502,502
BEGIN DESCRIPTION:
MDW T 007 9.0
END DESCRIPTION:
XS GIS Cut Line= 3
      2269191.92      7108106.76      2269829.44      7107865.18
      2270056.61      7107578.04
#Sta/Elev= 30
  4332.5  895.51  4682.3  889.07  4706.7  890.61  4731.5  886.89  4742.2  888.84
  4767.8  891.22  4786.4  890.81  4821.9  881.97  4864.1  878.83  4917.5  872.35
  4949.6  877.78  4986.8  878.35  5000.8  868.03  5001.3  867.53  5005.4  868.03
  5011.3  870.52  5018.0  870.66  5024.4  877.89  5032.5  876.44  5046.4  878.42
  5123.8  878.90  5146.3  880.47  5168.8  884.42  5181.5  884.24  5187.9  886.57
  5196.0  884.85  5202.3  887.42  5210.4  886.05  5260.1  892.74  5380.4  896.38
#Mann=5,-1,0
  4332.5    0.05       0  4742.2    0.12       0  5000.8    0.07       0
  5005.4    0.12       0  5168.8    0.05       0
Bank Sta=5000.8,5005.4
Exp/Cntr=0.3,0.1

Type RM Length L Ch R = 1,3605,381,381,381
BEGIN DESCRIPTION:
MDW T 007 8.0
END DESCRIPTION:
XS GIS Cut Line= 3
      2269945.93      7108351.49      2270013.98      7108160.03
      2270090.29      7107734.00
#Sta/Elev= 30
  4787.2  892.64  4790.7  892.64  4799.4  889.68  4813.3  889.03  4852.5  889.23
  4905.9  891.00  4937.4  890.73  4948.0  889.24  4962.2  884.14  4979.8  872.41
  4988.8  869.55  5000.6  867.89  5008.4  865.97  5008.9  865.47  5013.1  865.97
  5031.1  873.37  5041.2  874.42  5100.5  873.98  5105.6  874.67  5153.0  874.06
  5173.3  874.75  5203.8  874.29  5218.2  875.28  5224.1  874.87  5264.7  878.30
  5305.4  886.94  5315.5  889.95  5327.5  891.25  5356.2  893.20  5423.2  893.46
#Mann=5,-1,0
  4787.2    0.05       0  4988.8    0.12       0  5008.4    0.07       0
  5013.1    0.12       0  5327.5    0.05       0
Bank Sta=5008.4,5013.1
Exp/Cntr=0.3,0.1

Type RM Length L Ch R = 1,3224,230,230,230
BEGIN DESCRIPTION:
MDW T 007 7.0
END DESCRIPTION:
XS GIS Cut Line= 3
      2270297.50      7108398.33      2270379.00      7108060.00
      2270430.31      7107696.51
#Sta/Elev= 30
  4671.0  886.74  4738.8  887.49  4833.9  886.51  4869.7  887.79  4895.6  885.20
  4911.6  885.11  4926.4  883.73  4947.0  879.76  4953.6  876.56  4958.1  876.15
  4967.6  872.94  4988.1  871.24  4995.5  865.15  5000.6  864.91  5006.4  863.56
  5006.9  863.06  5011.1  863.56  5016.4  866.49  5021.5  866.49  5029.1  870.54
  5059.6  870.42  5089.7  871.92  5109.9  875.00  5120.0  875.19  5130.7  877.24
  5140.2  877.69  5166.4  882.56  5210.9  889.04  5339.0  893.11  5386.1  893.88
#Mann=5,-1,0
  4671.0    0.05       0  4958.1    0.12       0  5006.4    0.07       0
  5011.1    0.12       0  5166.4    0.05       0
Bank Sta=5006.4,5011.1
Exp/Cntr=0.3,0.1