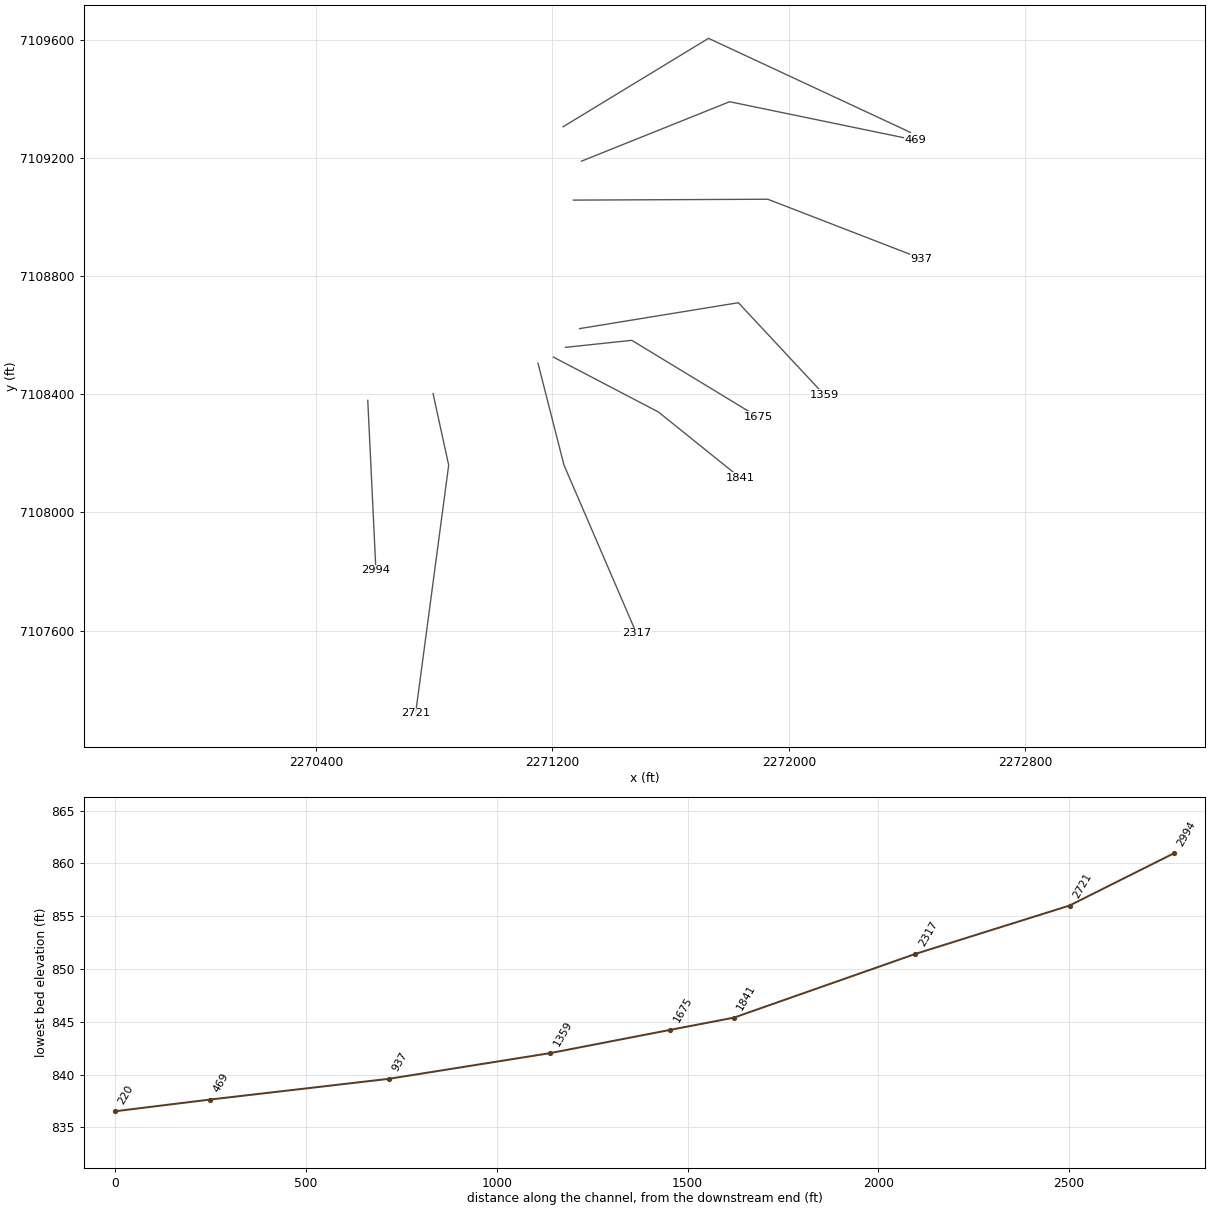
HEC-RAS study MDW T 007.prj: MDW T 007 Base Level Engineering

--- MDW T 007.g01 (geometry) --- (continued)

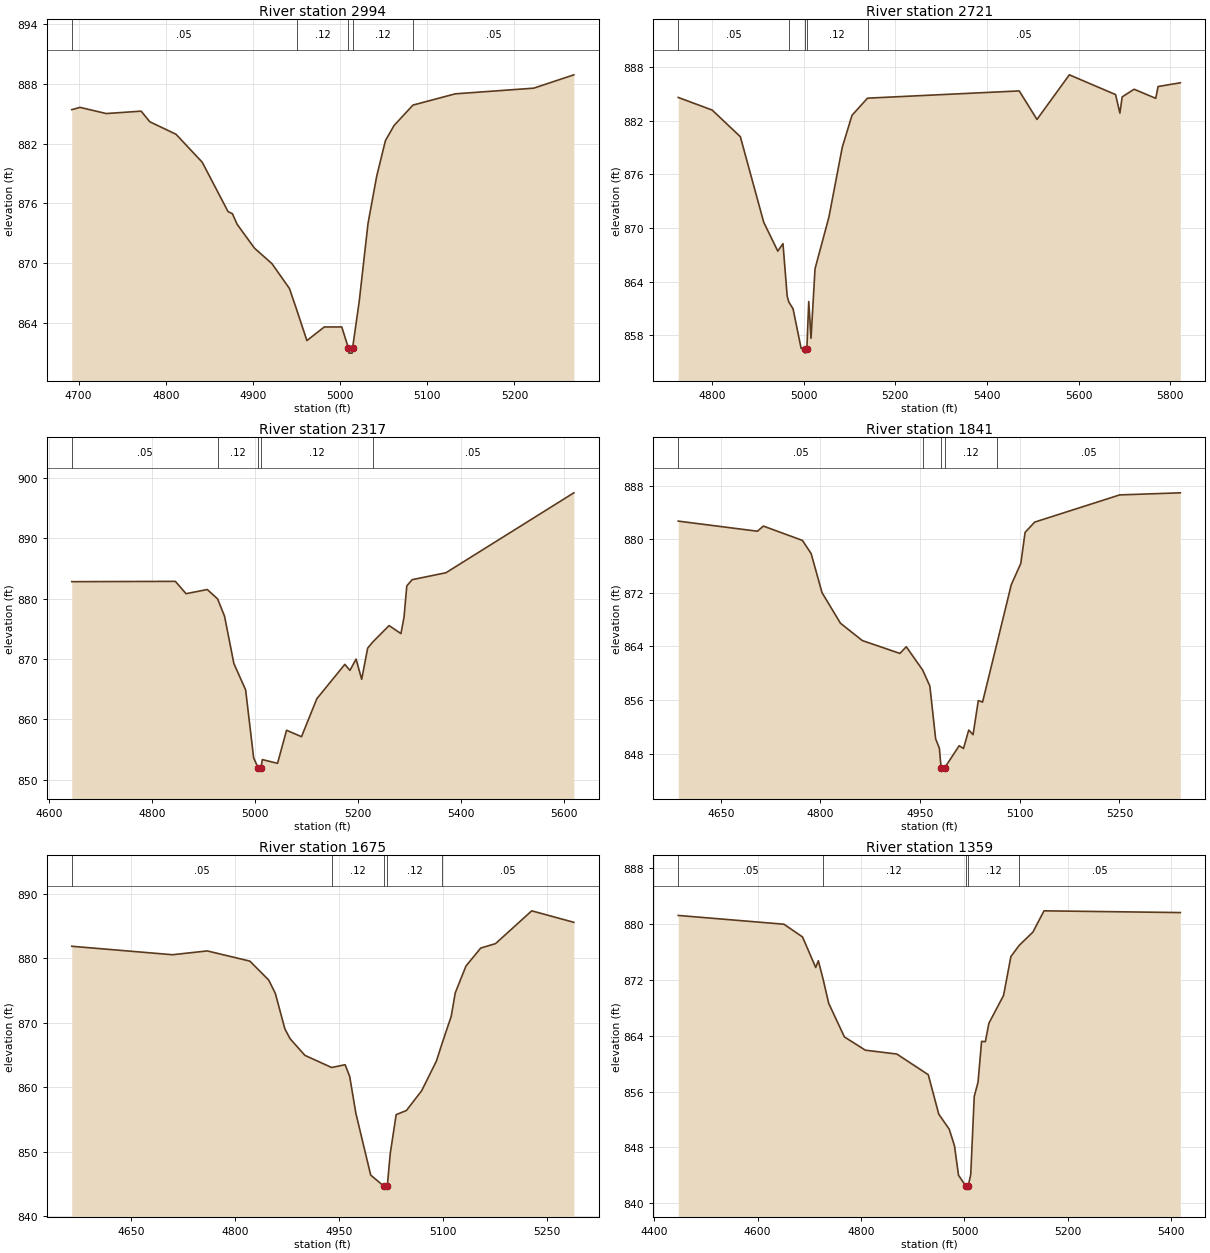
Type RM Length L Ch R = 1,2994,273,273,273
BEGIN DESCRIPTION:
Mapping XS cbcdf928
END DESCRIPTION:
XS GIS Cut Line= 2
      2270575.19      7108379.49      2270602.79      7107804.05
#Sta/Elev= 30
  4692.1  885.41  4701.6  885.64  4731.6  885.02  4771.7  885.26  4781.7  884.19
  4811.7  882.94  4841.8  880.13  4871.4  875.17  4876.4  874.96  4881.8  873.90
  4901.8  871.49  4921.8  869.94  4941.9  867.44  4950.0  865.36  4961.9  862.21
  4981.9  863.58  5001.9  863.58  5009.6  861.45  5010.1  860.95  5013.8  860.95
  5014.3  861.45  5022.0  866.19  5032.0  873.96  5042.0  878.73  5052.0  882.30
  5062.0  883.83  5083.6  885.87  5132.1  887.00  5222.2  887.57  5268.2  888.91
#Mann=5,-1,0
  4692.1    0.05       0  4950.0    0.12       0  5009.6    0.07       0
  5014.3    0.12       0  5083.6    0.05       0
Bank Sta=5009.6,5014.3
Exp/Cntr=0.3,0.1

Type RM Length L Ch R = 1,2721,404,404,404
BEGIN DESCRIPTION:
MDW T 007 6.0
END DESCRIPTION:
XS GIS Cut Line= 3
      2270796.20      7108402.26      2270849.03      7108159.93
      2270737.17      7107320.07
#Sta/Elev= 30
  4726.5  884.61  4800.5  883.20  4862.0  880.22  4913.0  870.65  4943.7  867.42
  4955.0  868.26  4964.2  862.37  4967.8  861.72  4977.0  860.97  4994.6  856.54
  5002.4  856.51  5002.9  856.01  5007.1  856.51  5011.2  861.78  5016.2  857.67
  5024.9  865.44  5055.2  871.22  5084.4  879.05  5105.6  882.61  5139.4  884.53
  5470.4  885.34  5509.1  882.15  5579.7  887.14  5680.6  884.93  5690.0  882.86
  5695.0  884.67  5721.0  885.53  5768.2  884.51  5773.3  885.83  5821.8  886.25
#Mann=5,-1,0
  4726.5    0.05       0  4967.8    0.12       0  5002.4    0.07       0
  5007.1    0.12       0  5139.4    0.05       0
Bank Sta=5002.4,5007.1
Exp/Cntr=0.3,0.1

Type RM Length L Ch R = 1,2317,476,476,476
BEGIN DESCRIPTION:
MDW T 007 5.0
END DESCRIPTION:
XS GIS Cut Line= 3
      2271151.23      7108504.99      2271239.19      7108160.45
      2271484.27      7107591.60
#Sta/Elev= 30
  4644.4  882.80  4845.6  882.85  4866.3  880.81  4907.6  881.50  4927.6  879.95
  4941.1  877.08  4959.2  869.25  4982.0  864.89  4997.6  853.64  5006.4  851.93
  5007.1  851.43  5011.7  851.93  5014.5  853.34  5044.0  852.72  5061.5  858.20
  5090.5  857.13  5120.3  863.42  5174.7  869.11  5184.6  868.11  5196.5  869.98
  5207.4  866.63  5219.0  871.79  5228.7  872.79  5260.6  875.53  5283.6  874.20
  5289.6  876.91  5295.0  882.10  5305.4  883.13  5371.1  884.28  5619.4  897.51
#Mann=5,-1,0
  4644.4    0.05       0  4927.6    0.12       0  5006.4    0.07       0
  5011.7    0.12       0  5228.7    0.05       0
Bank Sta=5006.4,5011.7
Exp/Cntr=0.3,0.1

Type RM Length L Ch R = 1,1841,166,166,166
BEGIN DESCRIPTION:
MDW T 007 4.0
END DESCRIPTION:
XS GIS Cut Line= 3
      2271203.32      7108525.81      2271558.62      7108340.16
      2271835.03      7108117.84
#Sta/Elev= 30
  4586.0  882.69  4705.2  881.18  4714.1  881.95  4772.9  879.81  4786.0  877.85
  4802.4  872.02  4830.1  867.46  4863.0  864.87  4919.6  862.95  4929.2  863.95
  4953.9  860.46  4964.7  858.08  4973.4  850.20  4979.0  848.81  4981.6  845.89
  4982.4  845.39  4987.0  845.89  5008.8  849.18  5015.3  848.77  5023.2  851.52
  5029.7  850.83  5037.6  855.91  5044.0  855.69  5066.2  864.67  5087.2  873.20
  5101.6  876.39  5108.0  881.01  5122.4  882.54  5250.4  886.60  5341.6  886.91
#Mann=5,-1,0
  4586.0    0.05       0  4953.9    0.12       0  4981.6    0.07       0
  4987.0    0.12       0  5066.2    0.05       0
Bank Sta=4981.6,4987
Exp/Cntr=0.3,0.1

Type RM Length L Ch R = 1,1675,316,316,316
BEGIN DESCRIPTION:
Mapping XS 7e302faa
END DESCRIPTION:
XS GIS Cut Line= 3
      2271244.40      7108558.80      2271468.54      7108582.54
      2271895.73      7108323.29
#Sta/Elev= 30
  4564.2  881.86  4709.6  880.55  4759.9  881.14  4821.4  879.56  4848.6  876.63
  4858.2  874.56  4872.0  869.05  4879.5  867.54  4900.9  864.96  4939.5  863.08
  4959.0  863.51  4965.6  861.69  4974.5  855.99  4995.9  846.42  5014.5  844.74
  5015.3  844.24  5019.9  844.74  5024.1  849.73  5032.7  855.78  5047.5  856.42
  5069.5  859.48  5090.8  864.07  5098.9  866.78  5112.2  871.01  5118.0  874.63
  5133.5  878.80  5154.8  881.58  5176.2  882.27  5228.5  887.35  5289.3  885.57
#Mann=5,-1,0
  4564.2    0.05       0  4939.5    0.12       0  5014.5    0.07       0
  5019.9    0.12       0  5098.9    0.05       0
Bank Sta=5014.5,5019.9
Exp/Cntr=0.3,0.1

Type RM Length L Ch R = 1,1359,422,422,422
BEGIN DESCRIPTION:
MDW T 007 3.0
END DESCRIPTION:
XS GIS Cut Line= 3
      2271291.88      7108622.17      2271829.40      7108709.83
      2272119.97      7108398.22
#Sta/Elev= 30
  4446.6  881.25  4651.0  879.99  4686.9  878.17  4712.4  873.79  4717.5  874.76
  4726.5  872.17  4737.5  868.66  4767.9  863.84  4808.4  861.94  4869.2  861.39
  4930.0  858.43  4950.3  852.78  4970.6  850.61  4980.7  848.23  4988.5  844.02
  5002.0  842.53  5002.8  842.03  5007.4  842.53  5012.1  844.11  5018.9  855.31
  5026.2  857.34  5033.1  863.20  5040.4  863.17  5047.2  865.80  5075.6  869.79
  5089.7  875.35  5105.7  876.95  5132.3  878.86  5153.8  881.91  5417.3  881.66
#Mann=5,-1,0
  4446.6    0.05       0  4726.5    0.12       0  5002.0    0.07       0
  5007.4    0.12       0  5105.7    0.05       0
Bank Sta=5002,5007.4
Exp/Cntr=0.3,0.1

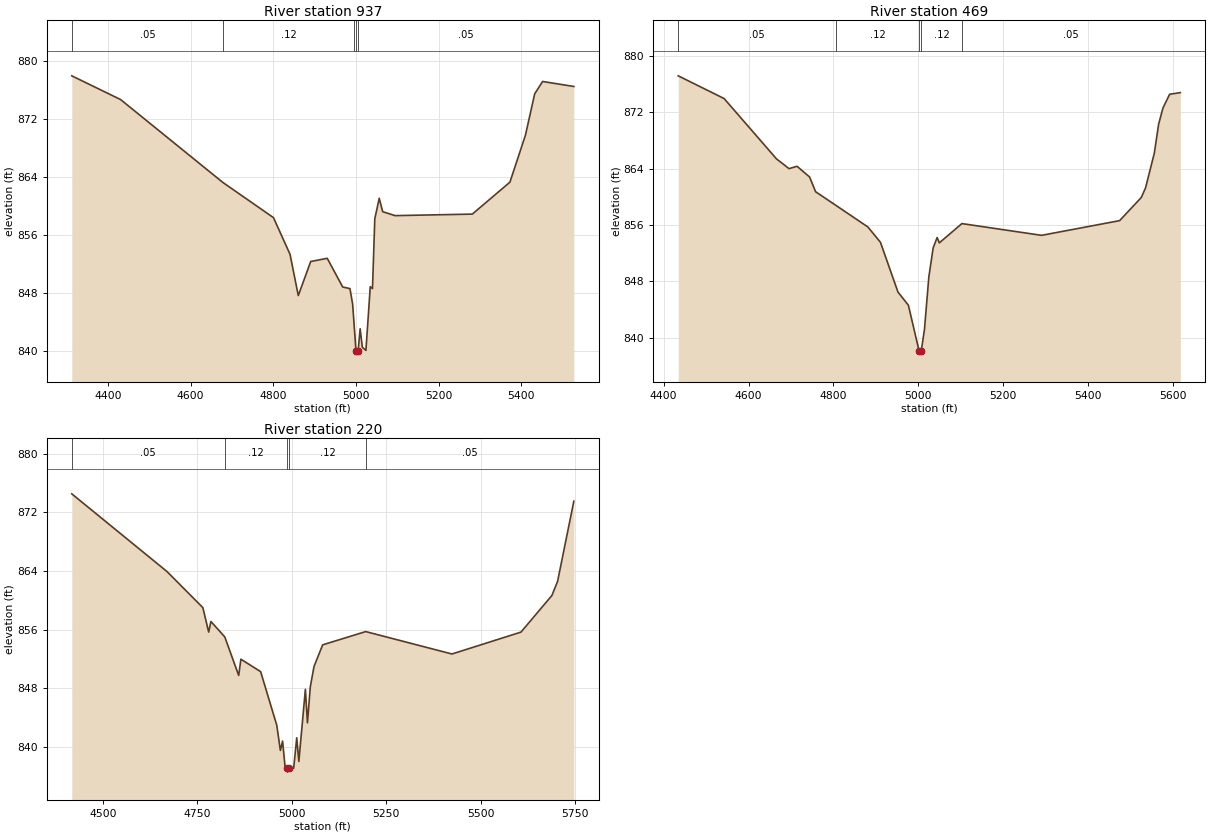
Type RM Length L Ch R = 1,937,468,468,468
BEGIN DESCRIPTION:
MDW T 007 2.0
END DESCRIPTION:
XS GIS Cut Line= 3
      2271270.98      7109057.06      2271929.00      7109060.00
      2272448.08      7108859.16
#Sta/Elev= 30
  4312.7  878.00  4430.7  874.73  4678.2  863.29  4800.7  858.43  4840.7  853.38
  4860.7  847.68  4890.7  852.38  4930.7  852.82  4968.2  848.86  4985.7  848.64
  4992.2  846.48  4995.7  843.69  5000.2  840.10  5000.9  839.60  5005.6  840.10
  5010.3  843.10  5015.6  840.55  5024.3  840.11  5034.8  848.90  5040.2  848.65
  5045.8  858.28  5056.5  861.10  5064.8  859.26  5094.7  858.71  5281.7  858.92
  5372.7  863.33  5410.3  869.83  5432.6  875.52  5451.8  877.22  5527.3  876.53
#Mann=5,-1,0
  4312.7    0.05       0  4678.2    0.12       0  4995.7    0.05       0
  5000.2   0.033       0  5005.6    0.05       0
Bank Sta=5000.2,5005.6
Exp/Cntr=0.3,0.1

Type RM Length L Ch R = 1,469,249,249,249
BEGIN DESCRIPTION:
MDW T 007 1.0
END DESCRIPTION:
XS GIS Cut Line= 3
      2271298.79      7109189.00      2271799.78      7109390.02
      2272428.97      7109260.01
#Sta/Elev= 30
  4434.5  877.21  4542.5  873.98  4665.9  865.40  4695.5  864.01  4714.3  864.35
  4743.9  862.82  4758.0  860.73  4806.5  858.76  4881.1  855.72  4910.7  853.54
  4951.9  846.47  4976.5  844.59  5001.5  838.14  5002.2  837.64  5006.9  838.14
  5014.4  841.19  5024.6  848.60  5034.8  852.74  5044.2  854.22  5049.3  853.46
  5102.5  856.20  5290.1  854.53  5473.9  856.62  5524.9  859.91  5535.1  861.30
  5555.6  866.22  5565.8  870.35  5576.0  872.64  5591.7  874.59  5616.8  874.82
#Mann=5,-1,0
  4434.5    0.05       0  4806.5    0.12       0  5001.5    0.07       0
  5006.9    0.12       0  5102.5    0.05       0
Bank Sta=5001.5,5006.9
Exp/Cntr=0.3,0.1

Type RM Length L Ch R = 1,220,0,0,0
BEGIN DESCRIPTION:
MDW T 007 0.5
END DESCRIPTION:
XS GIS Cut Line= 3
      2271236.27      7109305.31      2271728.38      7109604.54
      2272411.63      7109286.23
#Sta/Elev= 30
  4417.5  874.53  4669.7  863.92  4764.7  858.99  4780.1  855.65  4786.0  857.10
  4822.8  854.99  4859.6  849.73  4865.4  851.95  4917.7  850.25  4960.4  842.94
  4970.0  839.49  4975.8  840.77  4982.5  837.23  4988.1  837.03  4988.9  836.53
  4993.6  837.03  5005.2  837.06  5013.3  841.22  5018.9  837.99  5036.2  847.83
  5041.7  843.26  5049.3  848.19  5059.1  850.96  5082.0  853.91  5196.0  855.72
  5424.4  852.66  5607.2  855.65  5689.1  860.65  5704.2  862.58  5747.2  873.53
#Mann=5,-1,0
  4417.5    0.05       0  4822.8    0.12       0  4988.1    0.07       0
  4993.6    0.12       0  5196.0    0.05       0
Bank Sta=4988.1,4993.6
Exp/Cntr=0.3,0.1

Chan Stop Cuts=-1