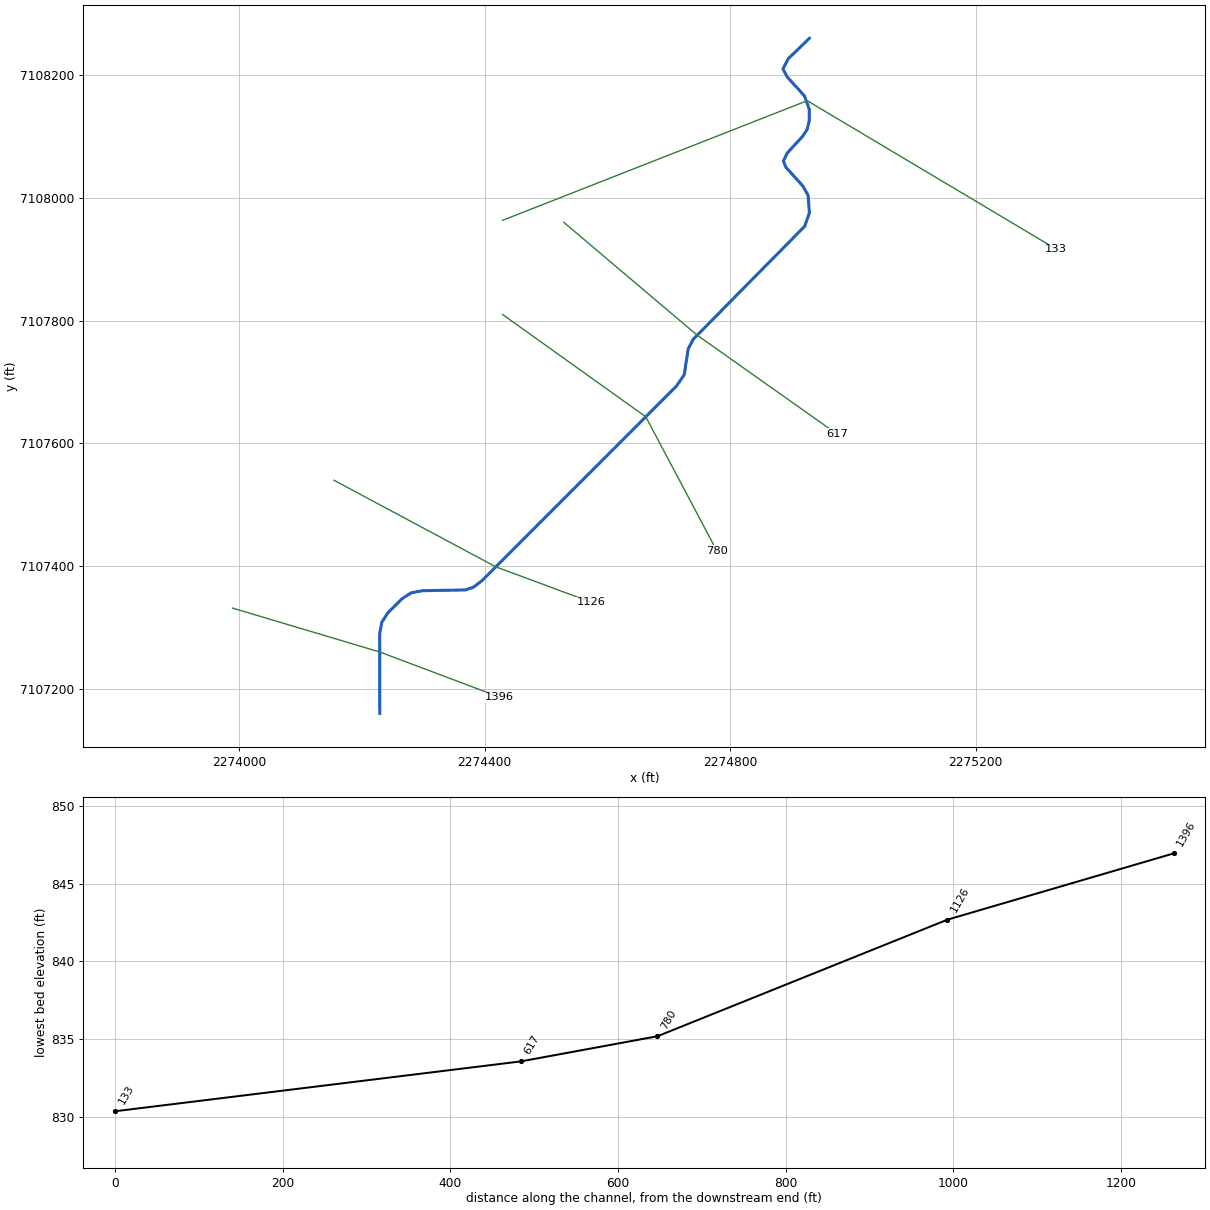
--- MDW T 008.prj (project) ---

Proj Title=MDW T 008 Base Level Engineering
Current Plan=p01
Default Exp/Contr=0.3,0.1
English Units
Geom File=g01
Flow File=f01
Plan File=p01
BEGIN DESCRIPTION:
MDW T 008
END DESCRIPTION:

--- MDW T 008.p01 (plan) ---

Plan Title=Multiple Run
Short Identifier=Multiple
Geom File=g01
Flow File=f01
Subcritical Flow
K Sum by GR= 0
Std Step Tol= 0.01
Critical Tol= 0.01
Num of Std Step Trials= 20
Max Error Tol= 0.3
Flow Tol Ratio= 0.001
Split Flow NTrial= 30
Split Flow Tol= 0.02
Split Flow Ratio= 0.02
Log Output Level= 0
Friction Slope Method= 1
Unsteady Friction Slope Method= 2
Unsteady Bridges Friction Slope Method= 1
Parabolic Critical Depth
Global Vel Dist=  1 , 1 , 1
Global Log Level= 0
CheckData=True
Encroach Param= -1, 0, 0, 0
BEGIN DESCRIPTION:
Multiple Run
END DESCRIPTION:

--- MDW T 008.f01 (steady flow) ---

Flow Title=Multiple
Number of Profiles=7
Profile Names=10-year,25-year,50-year,1pct_min,100-year,1pct_plu,500-year
River Rch & RM= MDW T 008,Reach-1,1396
     366     491     593     356     711    1419    1023
Boundary for River Rch & Prof#=MDW T 008,Reach-1,1
Up Type=0
Dn Type=3
Dn Slope=0.005
Boundary for River Rch & Prof#=MDW T 008,Reach-1,2
Up Type=0
Dn Type=3
Dn Slope=0.005
Boundary for River Rch & Prof#=MDW T 008,Reach-1,3
Up Type=0
Dn Type=3
Dn Slope=0.005
Boundary for River Rch & Prof#=MDW T 008,Reach-1,4
Up Type=0
Dn Type=3
Dn Slope=0.005
Boundary for River Rch & Prof#=MDW T 008,Reach-1,5
Up Type=0
Dn Type=3
Dn Slope=0.005
Boundary for River Rch & Prof#=MDW T 008,Reach-1,6
Up Type=0
Dn Type=3
Dn Slope=0.005
Boundary for River Rch & Prof#=MDW T 008,Reach-1,7
Up Type=0
Dn Type=3
Dn Slope=0.005

--- MDW T 008.g01 (geometry) ---

Geom Title=Existing Conditions

River Reach=MDW T 008,Reach-1
Reach XY= 30
      2274229.00      7107160.00      2274228.83      7107290.17
      2274232.39      7107308.80      2274242.19      7107323.75
      2274265.27      7107346.77      2274280.25      7107356.49
      2274298.94      7107359.91      2274368.51      7107361.17
      2274381.42      7107365.53      2274395.75      7107376.46
      2274712.35      7107693.33      2274725.02      7107711.65
      2274731.53      7107753.95      2274739.78      7107769.68
      2274921.50      7107953.95      2274928.99      7107975.36
      2274927.02      7108003.95      2274918.10      7108019.67
      2274890.55      7108050.08      2274886.62      7108060.00
      2274893.03      7108073.23      2274918.07      7108100.33
      2274925.37      7108111.65      2274928.74      7108125.36
      2274928.79      7108144.64      2274921.04      7108166.07
      2274893.05      7108196.85      2274885.95      7108210.12
      2274894.56      7108226.83      2274929.00      7108260.00

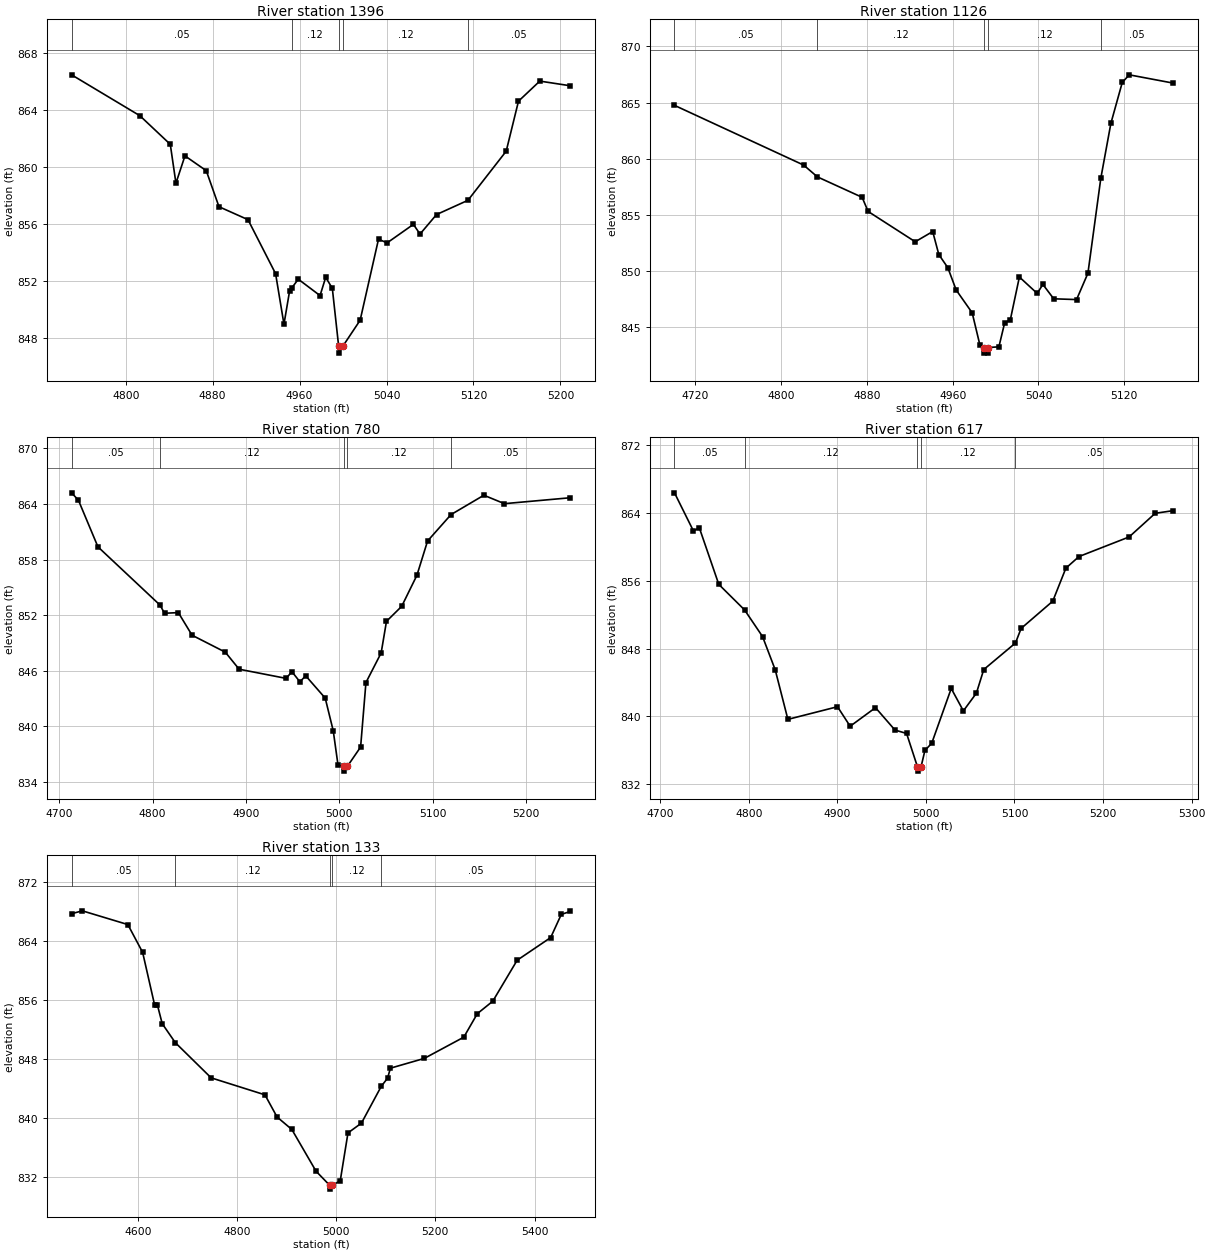
Type RM Length L Ch R = 1,1396,270,270,270
BEGIN DESCRIPTION:
MDW T 008 5.0
END DESCRIPTION:
XS GIS Cut Line= 3
      2273989.10      7107331.56      2274229.00      7107260.00
      2274424.28      7107186.51
#Sta/Elev= 30
  4750.2  866.49  4813.0  863.62  4841.0  861.61  4846.2  858.88  4854.5  860.80
  4874.1  859.76  4885.8  857.23  4912.5  856.32  4937.9  852.53  4945.6  848.98
  4950.8  851.32  4952.9  851.54  4958.8  852.14  4978.8  850.99  4984.0  852.27
  4990.1  851.50  4995.9  847.45  4996.2  846.95  4999.9  847.45  5015.7  849.26
  5032.6  854.95  5040.5  854.69  5064.7  855.99  5070.8  855.31  5086.0  856.68
  5114.9  857.68  5150.1  861.13  5161.4  864.64  5181.0  866.05  5209.2  865.72
#Mann=5,-1,0
  4750.2    0.05       0  4952.9    0.12       0  4995.9    0.07       0
  4999.9    0.12       0  5114.9    0.05       0
Bank Sta=4995.9,4999.9
Exp/Cntr=0.3,0.1

Type RM Length L Ch R = 1,1126,346,346,346
BEGIN DESCRIPTION:
MDW T 008 4.0
END DESCRIPTION:
XS GIS Cut Line= 3
      2274154.31      7107539.89      2274418.23      7107398.72
      2274573.59      7107341.10
#Sta/Elev= 30
  4700.7  864.75  4821.1  859.43  4833.9  858.38  4875.6  856.56  4881.2  855.30
  4925.1  852.60  4941.4  853.51  4947.1  851.46  4955.5  850.29  4963.3  848.30
  4978.2  846.27  4985.3  843.44  4988.9  843.18  4989.2  842.68  4992.7  842.68
  4992.9  843.18  5003.1  843.24  5008.4  845.35  5013.8  845.67  5022.2  849.46
  5038.8  848.00  5044.1  848.80  5054.2  847.52  5075.5  847.45  5086.1  849.80
  5098.1  858.25  5107.5  863.15  5118.1  866.79  5124.6  867.47  5165.7  866.73
#Mann=5,-1,0
  4700.7    0.05       0  4833.9    0.12       0  4988.9    0.07       0
  4992.9    0.12       0  5098.1    0.05       0
Bank Sta=4988.9,4992.9
Exp/Cntr=0.3,0.1

Type RM Length L Ch R = 1,780,163,163,163
BEGIN DESCRIPTION:
MDW T 008 3.0
END DESCRIPTION:
XS GIS Cut Line= 3
      2274429.03      7107809.98      2274662.42      7107643.30
      2274778.29      7107424.70
#Sta/Elev= 30
  4713.2  865.21  4720.5  864.41  4741.4  859.38  4807.9  853.09  4812.7  852.21
  4827.5  852.28  4842.2  849.84  4877.8  848.01  4892.6  846.17  4943.0  845.18
  4949.1  845.91  4957.7  844.81  4963.9  845.46  4984.8  843.05  4993.4  839.52
  4998.5  835.82  5004.4  835.67  5004.6  835.17  5008.4  835.67  5022.7  837.77
  5028.4  844.73  5044.7  847.93  5050.4  851.34  5066.7  852.96  5083.0  856.31
  5094.4  860.01  5119.5  862.86  5154.7  864.95  5176.7  864.04  5247.4  864.68
#Mann=5,-1,0
  4713.2    0.05       0  4807.9    0.12       0  5004.4    0.07       0
  5008.4    0.12       0  5119.5    0.05       0
Bank Sta=5004.4,5008.4
Exp/Cntr=0.3,0.1

Type RM Length L Ch R = 1,617,484,484,484
BEGIN DESCRIPTION:
MDW T 008 2.0
END DESCRIPTION:
XS GIS Cut Line= 3
      2274529.01      7107960.00      2274745.65      7107776.67
      2274973.71      7107615.44
#Sta/Elev= 30
  4716.2  866.35  4737.6  861.85  4744.2  862.24  4766.2  855.56  4795.3  852.55
  4815.6  849.41  4829.9  845.49  4844.2  839.65  4900.2  841.14  4914.5  838.84
  4943.1  841.03  4965.1  838.39  4978.2  837.99  4990.5  834.05  4990.7  833.55
  4994.5  834.05  4998.9  835.99  5006.6  836.84  5028.6  843.29  5042.3  840.65
  5057.0  842.74  5065.3  845.52  5101.1  848.65  5107.5  850.37  5143.2  853.58
  5158.0  857.47  5172.8  858.84  5229.4  861.15  5258.9  863.94  5279.3  864.25
#Mann=5,-1,0
  4716.2    0.05       0  4795.3    0.12       0  4990.5    0.07       0
  4994.5    0.12       0  5101.1    0.05       0
Bank Sta=4990.5,4994.5
Exp/Cntr=0.3,0.1

Type RM Length L Ch R = 1,133,0,0,0
BEGIN DESCRIPTION:
MDW T 008 1.0
END DESCRIPTION:
XS GIS Cut Line= 3
      2274428.92      7107963.36      2274925.50      7108158.37
      2275331.27      7107916.47
#Sta/Elev= 30
  4466.5  867.64  4488.1  868.03  4579.9  866.17  4609.7  862.41  4634.1  855.21
  4639.5  855.28  4649.2  852.75  4675.6  850.18  4747.9  845.41  4856.4  843.11
  4880.8  840.11  4910.6  838.42  4959.4  832.77  4987.2  830.84  4987.5  830.34
  4991.2  830.84  5008.2  831.46  5023.8  837.95  5051.0  839.28  5091.0  844.27
  5103.6  845.36  5109.4  846.72  5177.6  848.04  5257.4  850.92  5284.6  854.10
  5315.8  855.79  5365.0  861.34  5432.6  864.41  5454.0  867.55  5472.4  867.95
#Mann=5,-1,0
  4466.5    0.05       0  4675.6    0.12       0  4987.2    0.07       0
  4991.2    0.12       0  5091.0    0.05       0
Bank Sta=4987.2,4991.2
Exp/Cntr=0.3,0.1

Chan Stop Cuts=-1