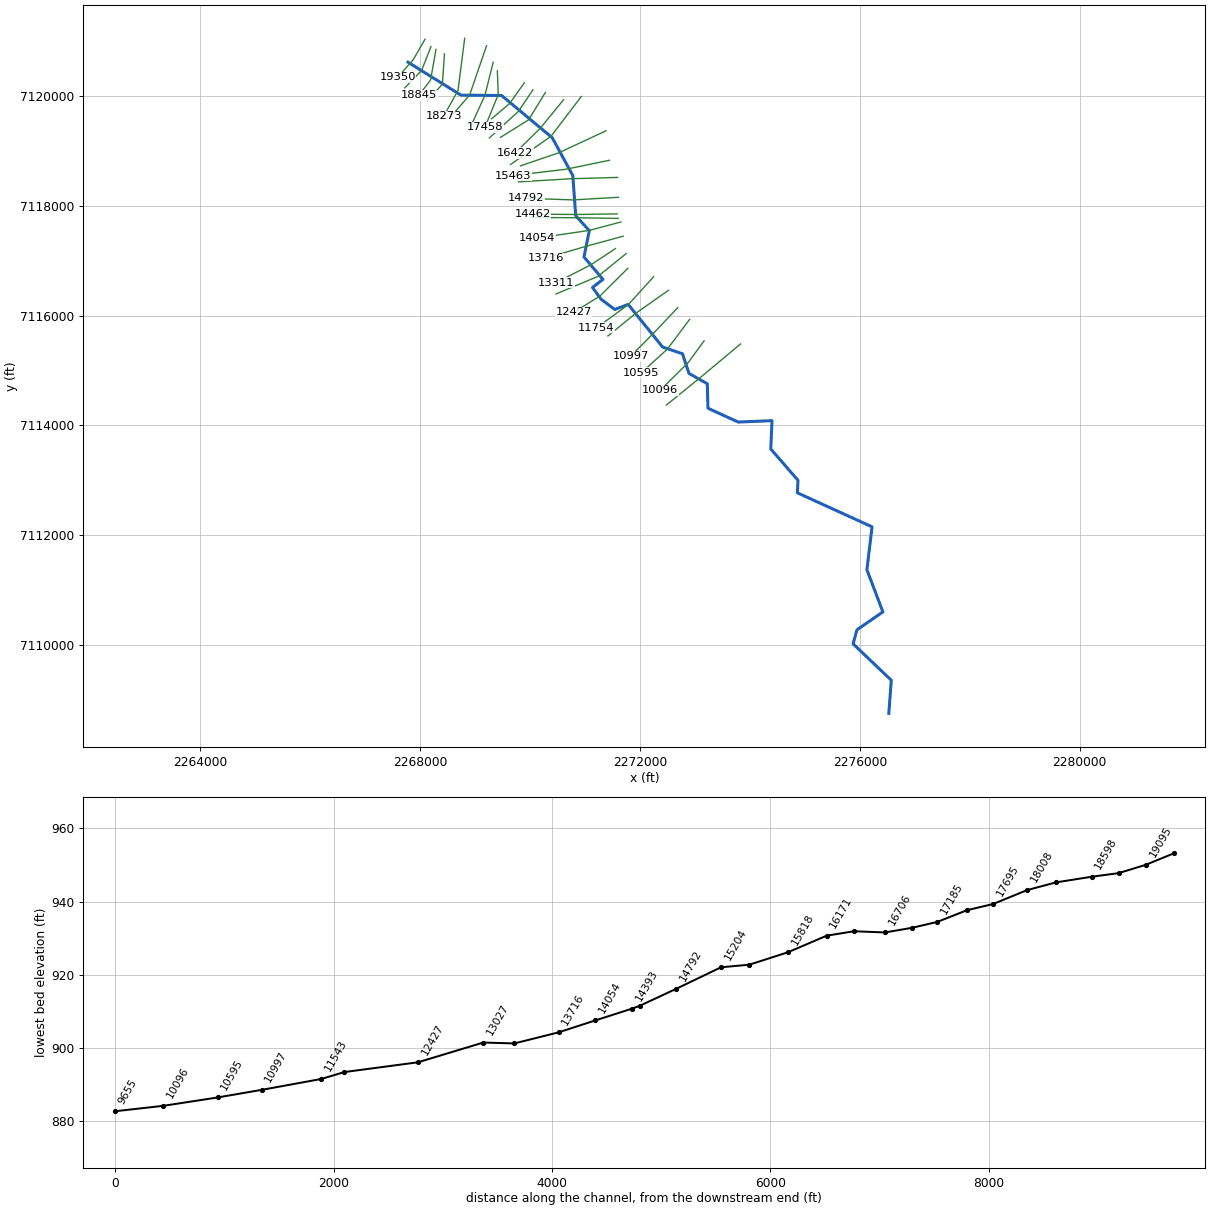
--- MDW T 009.prj (project) ---

Proj Title=MDW T 009 Base Level Engineering
Current Plan=p01
Default Exp/Contr=0.3,0.1
English Units
Geom File=g01
Flow File=f01
Plan File=p01
BEGIN DESCRIPTION:
MDW T 009
END DESCRIPTION:

--- MDW T 009.p01 (plan) ---

Plan Title=Multiple Run
Short Identifier=Multiple
Geom File=g01
Flow File=f01
Subcritical Flow
K Sum by GR= 0
Std Step Tol= 0.01
Critical Tol= 0.01
Num of Std Step Trials= 20
Max Error Tol= 0.3
Flow Tol Ratio= 0.001
Split Flow NTrial= 30
Split Flow Tol= 0.02
Split Flow Ratio= 0.02
Log Output Level= 0
Friction Slope Method= 1
Unsteady Friction Slope Method= 2
Unsteady Bridges Friction Slope Method= 1
Parabolic Critical Depth
Global Vel Dist=  1 , 1 , 1
Global Log Level= 0
CheckData=True
Encroach Param= -1, 0, 0, 0
BEGIN DESCRIPTION:
Multiple Run
END DESCRIPTION:

--- MDW T 009.f01 (steady flow) ---

Flow Title=Multiple
Number of Profiles=7
Profile Names=10-year,25-year,50-year,1pct_min,100-year,1pct_plu,500-year
River Rch & RM= MDW T 009,Reach-1,19350
     287     378     450     267     533    1063     747
River Rch & RM= MDW T 009,Reach-1,17695
     428     577     699     421     839    1674    1212
River Rch & RM= MDW T 009,Reach-1,14792
     495     673     820     496     991    1977    1449
River Rch & RM= MDW T 009,Reach-1,13311
     646     892    1097     670    1337    2668    1991
River Rch & RM= MDW T 009,Reach-1,10997
     675     934    1149     702    1401    2795    2086
River Rch & RM= MDW T 009,Reach-1,9476
     736    1023    1264     774    1545    3083    2316
River Rch & RM= MDW T 009,Reach-1,7668
     841    1177    1459     898    1791    3574    2706
River Rch & RM= MDW T 009,Reach-1,4890
     924    1298    1613     994    1984    3959    3010
River Rch & RM= MDW T 009,Reach-1,1872
     963    1354    1684    1039    2072    4134    3146
Boundary for River Rch & Prof#=MDW T 009,Reach-1,1
Up Type=0
Dn Type=3
Dn Slope=0.005
Boundary for River Rch & Prof#=MDW T 009,Reach-1,2
Up Type=0
Dn Type=3
Dn Slope=0.005
Boundary for River Rch & Prof#=MDW T 009,Reach-1,3
Up Type=0
Dn Type=3
Dn Slope=0.005
Boundary for River Rch & Prof#=MDW T 009,Reach-1,4
Up Type=0
Dn Type=3
Dn Slope=0.005
Boundary for River Rch & Prof#=MDW T 009,Reach-1,5
Up Type=0
Dn Type=3
Dn Slope=0.005
Boundary for River Rch & Prof#=MDW T 009,Reach-1,6
Up Type=0
Dn Type=3
Dn Slope=0.005
Boundary for River Rch & Prof#=MDW T 009,Reach-1,7
Up Type=0
Dn Type=3
Dn Slope=0.005

--- MDW T 009.g01 (geometry) ---

Geom Title=Existing Conditions

River Reach=MDW T 009,Reach-1
Reach XY= 30
      2267779.00      7120610.00      2268740.83      7120011.65
      2269481.45      7120004.54      2270402.83      7119236.88
      2270777.53      7118547.87      2270830.80      7117816.11
      2271078.62      7117544.85      2270980.66      7117066.05
      2271326.01      7116658.54      2271135.97      7116510.24
      2271292.49      7116296.44      2271539.64      7116110.55
      2271785.17      7116202.24      2272412.29      7115426.63
      2272773.39      7115304.41      2272892.20      7114946.26
      2273225.39      7114758.50      2273236.91      7114312.92
      2273789.50      7114061.20      2274403.15      7114087.30
      2274380.51      7113571.87      2274875.51      7113001.49
      2274864.84      7112773.37      2276223.83      7112154.59
      2276129.52      7111375.22      2276420.93      7110606.69
      2275948.40      7110280.66      2275878.96      7110025.34
      2276573.53      7109362.44      2276529.00      7108760.00

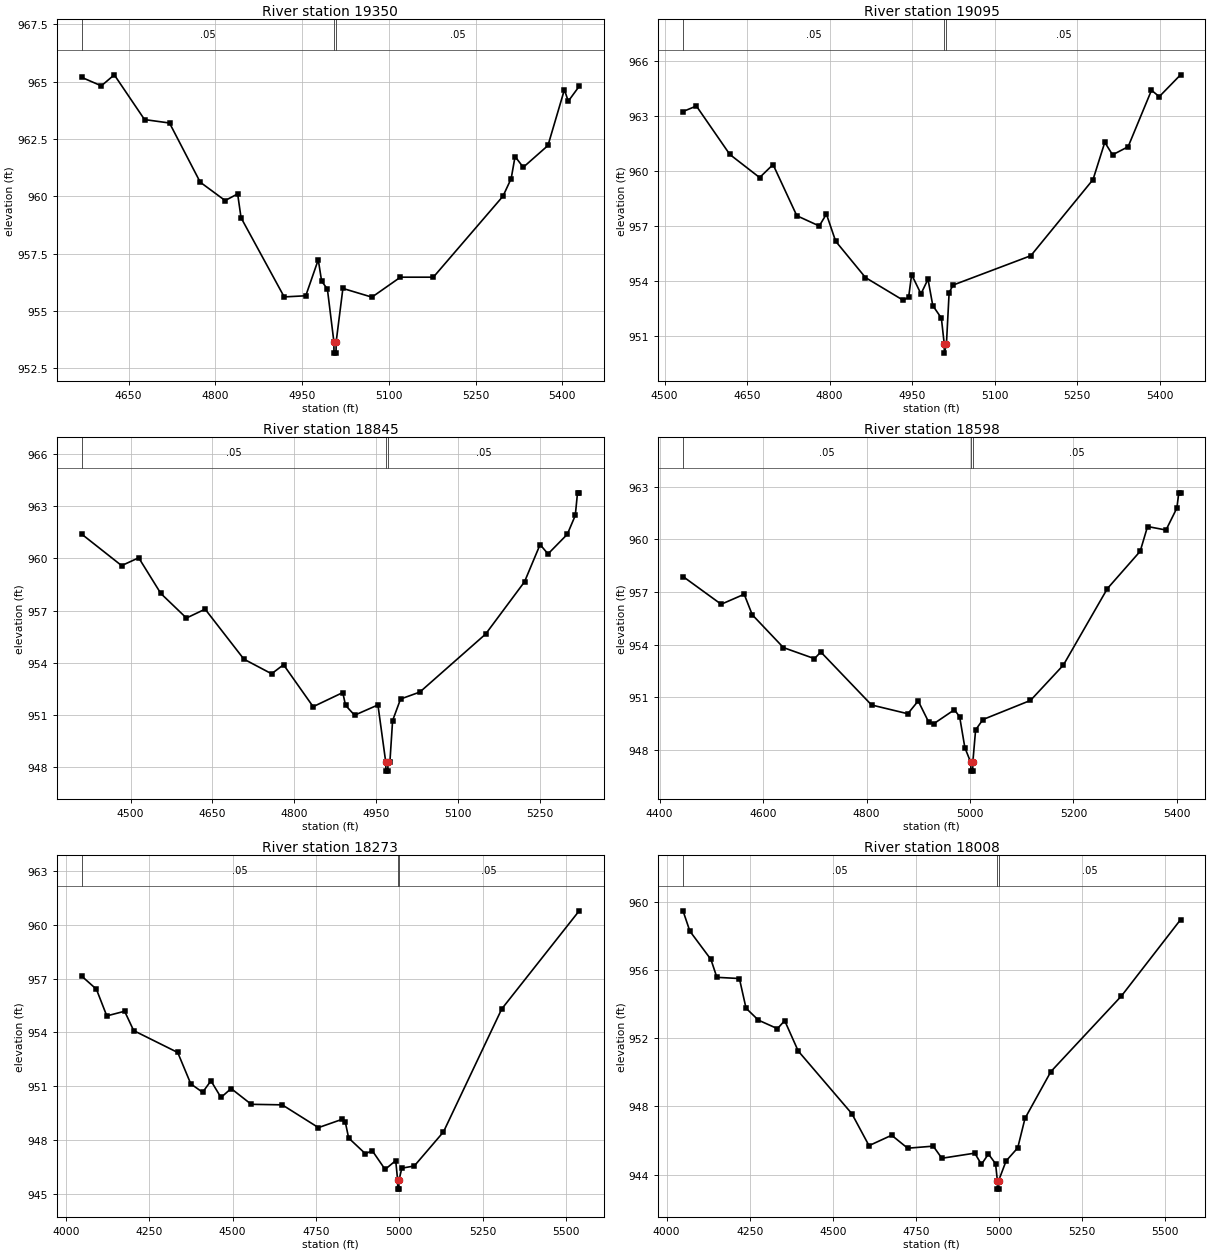
Type RM Length L Ch R = 1,19350,255,255,255
BEGIN DESCRIPTION:
MDW T 009 48.0
END DESCRIPTION:
XS GIS Cut Line= 3
      2268088.42      7121028.88      2267873.49      7120655.30
      2267588.20      7120334.51
#Sta/Elev= 30
  4569.0  965.19  4603.0  964.82  4625.4  965.30  4677.7  963.35  4720.9  963.20
  4774.0  960.62  4817.1  959.82  4838.7  960.11  4844.6  959.07  4919.2  955.62
  4956.5  955.67  4978.1  957.24  4983.9  956.31  4993.9  955.96  5005.1  953.67
  5005.3  953.17  5008.8  953.17  5009.1  953.67  5020.7  955.99  5070.9  955.61
  5120.2  956.48  5177.1  956.48  5297.5  960.01  5311.7  960.78  5318.4  961.74
  5332.6  961.27  5375.3  962.22  5403.7  964.65  5410.4  964.15  5429.3  964.80
#Mann=3,-1,0
  4569.0    0.05       0  5005.1   0.033       0  5009.1    0.05       0
Bank Sta=5005.1,5009.1
Exp/Cntr=0.3,0.1

Type RM Length L Ch R = 1,19095,250,250,250
BEGIN DESCRIPTION:
MDW T 009 47.0
END DESCRIPTION:
XS GIS Cut Line= 3
      2268195.82      7120892.57      2268025.02      7120458.35
      2267720.40      7120143.77
#Sta/Elev= 30
  4533.4  963.23  4557.7  963.53  4618.5  960.89  4672.7  959.63  4697.1  960.34
  4740.3  957.55  4781.1  956.99  4794.1  957.64  4810.9  956.16  4865.1  954.18
  4933.8  952.94  4943.6  953.11  4949.0  954.34  4966.0  953.29  4978.8  954.09
  4987.5  952.65  5003.1  951.97  5008.3  950.56  5008.5  950.06  5012.3  950.56
  5017.2  953.36  5024.4  953.77  5165.7  955.37  5278.8  959.52  5300.2  961.55
  5314.3  960.87  5342.6  961.31  5385.1  964.39  5399.2  964.04  5437.9  965.23
#Mann=3,-1,0
  4533.4    0.05       0  5008.3   0.033       0  5012.3    0.05       0
Bank Sta=5008.3,5012.3
Exp/Cntr=0.3,0.1

Type RM Length L Ch R = 1,18845,247,247,247
BEGIN DESCRIPTION:
MDW T 009 46.0
END DESCRIPTION:
XS GIS Cut Line= 3
      2268287.40      7120843.01      2268190.08      7120288.45
      2267979.03      7120010.04
#Sta/Elev= 30
  4410.2  961.39  4483.5  959.58  4514.8  960.03  4555.4  957.98  4602.3  956.57
  4636.6  957.08  4707.7  954.21  4758.5  953.37  4780.4  953.89  4834.7  951.48
  4889.0  952.29  4894.1  951.56  4910.7  950.99  4953.5  951.58  4967.9  948.28
  4968.2  947.78  4971.7  947.78  4971.9  948.28  4975.4  948.28  4980.4  950.68
  4995.0  951.92  5030.4  952.32  5151.0  955.65  5222.3  958.65  5250.9  960.79
  5265.4  960.25  5300.8  961.38  5315.4  962.46  5319.5  963.76  5322.6  963.76
#Mann=3,-1,0
  4410.2    0.05       0  4967.9   0.033       0  4971.9    0.05       0
Bank Sta=4967.9,4971.9
Exp/Cntr=0.3,0.1

Type RM Length L Ch R = 1,18598,325,325,325
BEGIN DESCRIPTION:
MDW T 009 45.0
END DESCRIPTION:
XS GIS Cut Line= 3
      2268442.08      7120763.60      2268404.00      7120210.01
      2268128.99      7119909.99
#Sta/Elev= 30
  4445.1  957.88  4518.9  956.30  4563.4  956.87  4579.0  955.70  4639.2  953.83
  4699.3  953.20  4711.5  953.58  4809.6  950.56  4879.7  950.06  4899.8  950.79
  4919.8  949.60  4929.8  949.49  4969.9  950.29  4980.0  949.88  4990.0  948.13
  5001.4  947.29  5001.7  946.79  5005.2  946.79  5005.4  947.29  5010.8  949.14
  5025.0  949.73  5116.9  950.82  5180.4  952.83  5265.5  957.19  5329.0  959.32
  5343.2  960.73  5378.9  960.53  5399.9  961.78  5403.6  962.65  5407.0  962.65
#Mann=3,-1,0
  4445.1    0.05       0  5001.4    0.04       0  5005.4    0.05       0
Bank Sta=5001.4,5005.4
Exp/Cntr=0.3,0.1

Type RM Length L Ch R = 1,18273,265,265,265
BEGIN DESCRIPTION:
MDW T 009 44.0
END DESCRIPTION:
XS GIS Cut Line= 3
      2268810.13      7121044.83      2268689.08      7120099.55
      2268428.21      7119626.52
#Sta/Elev= 30
  4047.0  957.14  4091.2  956.41  4122.4  954.92  4175.9  955.18  4203.1  954.10
  4335.3  952.88  4374.5  951.13  4410.0  950.66  4435.0  951.30  4465.2  950.37
  4495.5  950.87  4556.0  949.99  4649.0  949.96  4757.6  948.69  4828.2  949.15
  4838.2  949.00  4848.3  948.11  4898.7  947.23  4918.9  947.41  4957.7  946.36
  4989.5  946.85  4995.3  945.76  4995.5  945.26  4999.0  945.26  4999.3  945.76
  5007.9  946.43  5045.2  946.55  5132.8  948.45  5307.8  955.31  5540.2  960.78
#Mann=3,-1,0
  4047.0    0.05       0  4995.3   0.033       0  4999.3    0.05       0
Bank Sta=4995.3,4999.3
Exp/Cntr=0.3,0.1

Type RM Length L Ch R = 1,18008,313,313,313
BEGIN DESCRIPTION:
MDW T 009 43.0
END DESCRIPTION:
XS GIS Cut Line= 3
      2269207.71      7120909.47      2268899.15      7120010.34
      2268539.27      7119598.66
#Sta/Elev= 30
  4049.4  959.47  4070.0  958.28  4133.4  956.62  4151.3  955.57  4219.1  955.50
  4239.1  953.76  4276.3  953.06  4333.6  952.56  4355.4  953.03  4396.1  951.25
  4557.7  947.57  4609.2  945.70  4677.4  946.31  4725.5  945.55  4802.5  945.67
  4828.5  944.96  4927.5  945.26  4947.5  944.60  4968.6  945.21  4990.1  944.64
  4995.5  943.65  4995.8  943.15  4999.3  943.15  4999.5  943.65  5021.7  944.80
  5056.8  945.57  5078.7  947.30  5156.5  950.04  5369.1  954.48  5546.8  958.95
#Mann=3,-1,0
  4049.4    0.05       0  4995.5   0.033       0  4999.5    0.05       0
Bank Sta=4995.5,4999.5
Exp/Cntr=0.3,0.1

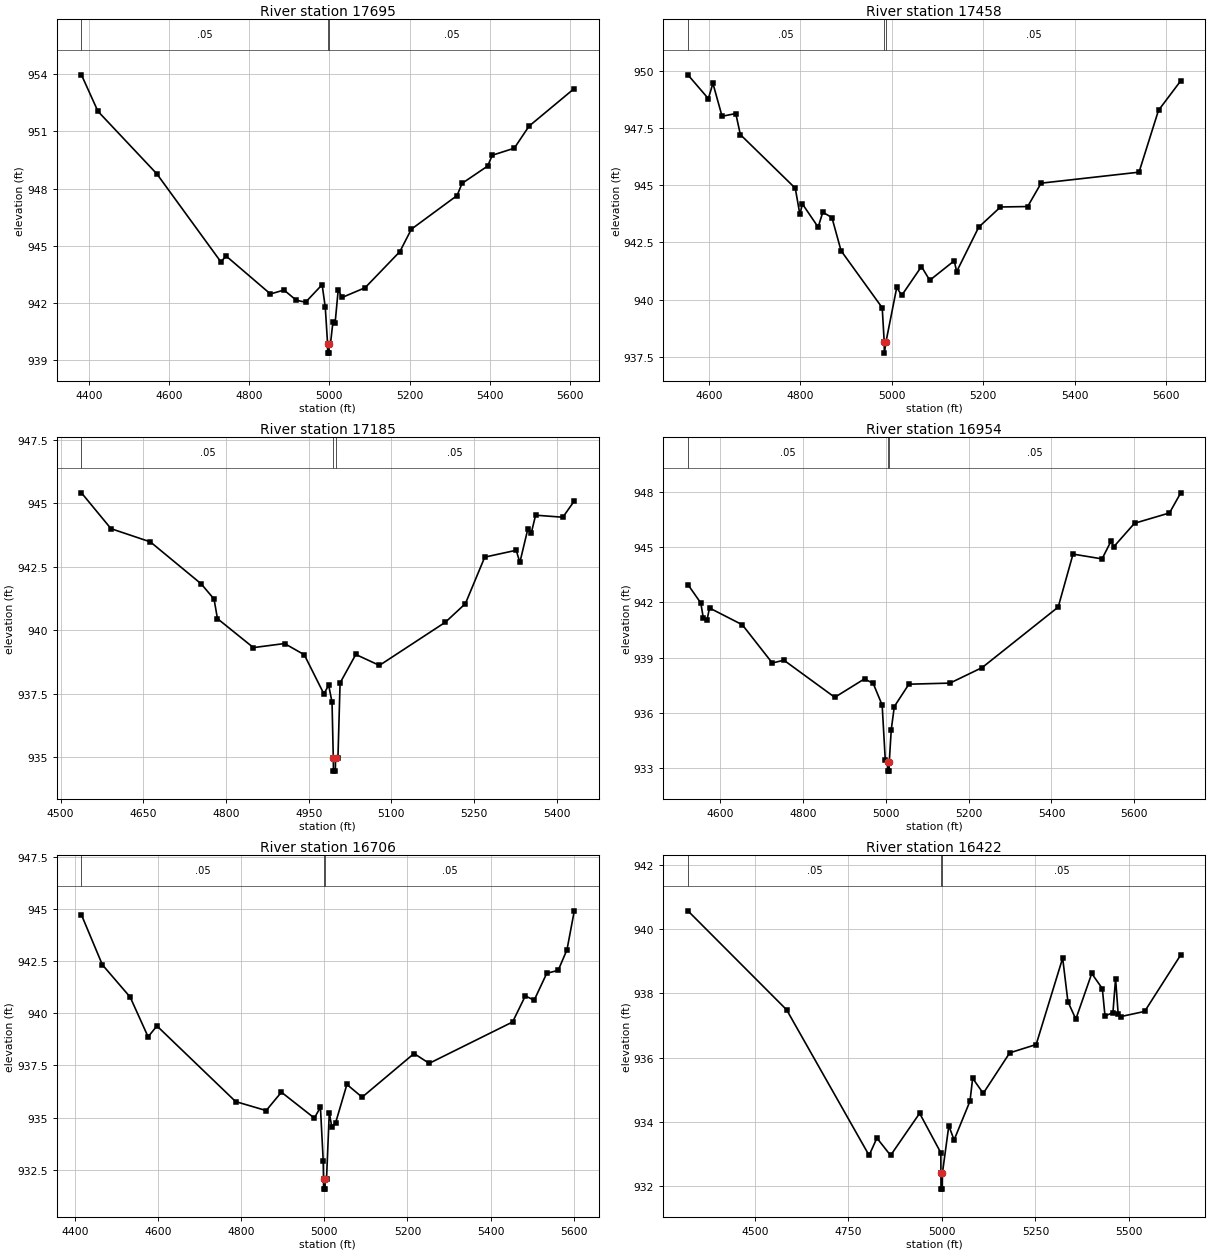
Type RM Length L Ch R = 1,17695,237,237,237
BEGIN DESCRIPTION:
MDW T 009 42.0
END DESCRIPTION:
XS GIS Cut Line= 3
      2269329.00      7120610.00      2269178.97      7120010.08
      2268926.73      7119453.68
#Sta/Elev= 30
  4381.6  953.98  4422.8  952.06  4569.7  948.77  4729.4  944.14  4742.4  944.45
  4853.1  942.45  4886.7  942.66  4917.6  942.12  4940.7  942.02  4981.9  942.94
  4989.8  941.75  4995.5  939.84  4995.7  939.34  4999.2  939.34  4999.5  939.84
  5002.8  939.84  5008.8  940.97  5014.3  940.92  5022.0  942.66  5031.9  942.27
  5089.1  942.78  5175.8  944.68  5204.5  945.86  5318.5  947.63  5330.9  948.27
  5394.7  949.18  5406.3  949.75  5461.2  950.12  5498.0  951.28  5610.9  953.26
#Mann=3,-1,0
  4381.6    0.05       0  4995.5   0.033       0  4999.5    0.05       0
Bank Sta=4995.5,4999.5
Exp/Cntr=0.3,0.1

Type RM Length L Ch R = 1,17458,273,273,273
BEGIN DESCRIPTION:
MDW T 009 41.0
END DESCRIPTION:
XS GIS Cut Line= 3
      2269404.24      7120454.63      2269421.04      7120022.48
      2269177.77      7119424.87
#Sta/Elev= 30
  4554.4  949.82  4599.1  948.78  4609.1  949.45  4629.1  948.01  4659.1  948.13
  4669.1  947.21  4789.2  944.87  4799.2  943.73  4804.9  944.18  4839.2  943.17
  4849.3  943.82  4869.3  943.59  4889.3  942.14  4979.3  939.65  4983.6  938.17
  4983.9  937.67  4987.6  938.17  5011.1  940.54  5021.9  940.19  5065.1  941.45
  5083.2  940.85  5136.7  941.70  5142.1  941.23  5190.3  943.17  5237.9  944.05
  5297.3  944.07  5326.7  945.09  5540.8  945.57  5583.4  948.27  5632.1  949.56
#Mann=3,-1,0
  4554.4    0.05       0  4983.6    0.04       0  4987.6    0.05       0
Bank Sta=4983.6,4987.6
Exp/Cntr=0.3,0.1

Type RM Length L Ch R = 1,17185,231,231,231
BEGIN DESCRIPTION:
MDW T 009 40.0
END DESCRIPTION:
XS GIS Cut Line= 3
      2269896.18      7120237.04      2269629.00      7119860.00
      2269299.33      7119580.52
#Sta/Elev= 30
  4537.7  945.41  4591.3  944.00  4662.7  943.48  4754.9  941.83  4778.3  941.23
  4784.5  940.46  4849.7  939.32  4906.3  939.48  4942.0  939.04  4977.6  937.50
  4986.3  937.84  4992.4  937.17  4994.7  934.96  4995.0  934.46  4998.5  934.46
  4998.7  934.96  5003.1  934.96  5007.0  937.93  5035.5  939.05  5078.4  938.62
  5198.1  940.32  5234.4  941.05  5269.5  942.88  5326.6  943.15  5333.2  942.67
  5347.5  943.97  5354.0  943.84  5361.8  944.53  5411.2  944.45  5432.0  945.09
#Mann=3,-1,0
  4537.7    0.05       0  4994.7   0.033       0  4998.7    0.05       0
Bank Sta=4994.7,4998.7
Exp/Cntr=0.3,0.1

Type RM Length L Ch R = 1,16954,248,248,248
BEGIN DESCRIPTION:
MDW T 009 39.0
END DESCRIPTION:
XS GIS Cut Line= 3
      2270052.75      7120108.97      2269784.88      7119712.48
      2269258.52      7119232.28
#Sta/Elev= 30
  4521.5  942.96  4552.7  941.96  4558.8  941.14  4567.7  941.04  4573.7  941.69
  4653.0  940.78  4725.4  938.71  4753.5  938.86  4876.4  936.85  4948.3  937.85
  4969.3  937.60  4990.9  936.43  4998.5  933.43  5004.1  933.35  5004.4  932.85
  5007.9  932.85  5008.1  933.35  5012.9  935.10  5020.3  936.35  5055.5  937.56
  5154.8  937.62  5232.5  938.46  5416.3  941.74  5452.1  944.61  5522.3  944.35
  5543.9  945.31  5550.7  945.01  5600.7  946.28  5685.2  946.84  5712.5  947.93
#Mann=3,-1,0
  4521.5    0.05       0  5004.1   0.033       0  5008.1    0.05       0
Bank Sta=5004.1,5008.1
Exp/Cntr=0.3,0.1

Type RM Length L Ch R = 1,16706,284,284,284
BEGIN DESCRIPTION:
MDW T 009 38.0
END DESCRIPTION:
XS GIS Cut Line= 3
      2270278.98      7120059.97      2269973.01      7119561.96
      2269462.79      7119243.40
#Sta/Elev= 30
  4415.5  944.71  4465.8  942.32  4532.8  940.77  4575.9  938.87  4597.2  939.39
  4786.6  935.77  4860.0  935.34  4896.7  936.22  4976.0  934.98  4990.6  935.50
  4997.3  932.94  4998.0  932.08  4998.2  931.58  5001.7  931.58  5002.0  932.08
  5005.3  932.08  5011.9  935.24  5017.8  934.57  5027.2  934.76  5054.3  936.59
  5090.9  935.98  5215.9  938.07  5252.3  937.60  5453.0  939.58  5483.7  940.83
  5504.9  940.62  5535.2  941.91  5562.7  942.05  5583.9  943.04  5601.5  944.90
#Mann=3,-1,0
  4415.5    0.05       0  4998.0   0.033       0  5002.0    0.05       0
Bank Sta=4998,5002
Exp/Cntr=0.3,0.1

Type RM Length L Ch R = 1,16422,251,251,251
BEGIN DESCRIPTION:
MDW T 009 37.0
END DESCRIPTION:
XS GIS Cut Line= 3
      2270610.94      7119929.33      2270181.19      7119403.90
      2269725.50      7118957.07
#Sta/Elev= 30
  4321.2  940.57  4585.0  937.49  4805.4  932.96  4826.2  933.50  4862.8  932.96
  4940.4  934.27  4997.1  933.04  4997.3  932.41  4997.5  931.91  5001.0  931.91
  5001.3  932.41  5018.4  933.88  5032.5  933.44  5075.0  934.65  5082.1  935.36
  5110.4  934.89  5181.1  936.15  5251.8  936.41  5322.6  939.10  5336.7  937.74
  5357.8  937.20  5400.3  938.62  5428.6  938.15  5435.7  937.30  5456.9  937.40
  5464.0  938.46  5471.0  937.35  5478.1  937.28  5541.7  937.44  5638.2  939.20
#Mann=3,-1,0
  4321.2    0.05       0  4997.3   0.033       0  5001.3    0.05       0
Bank Sta=4997.3,5001.3
Exp/Cntr=0.3,0.1

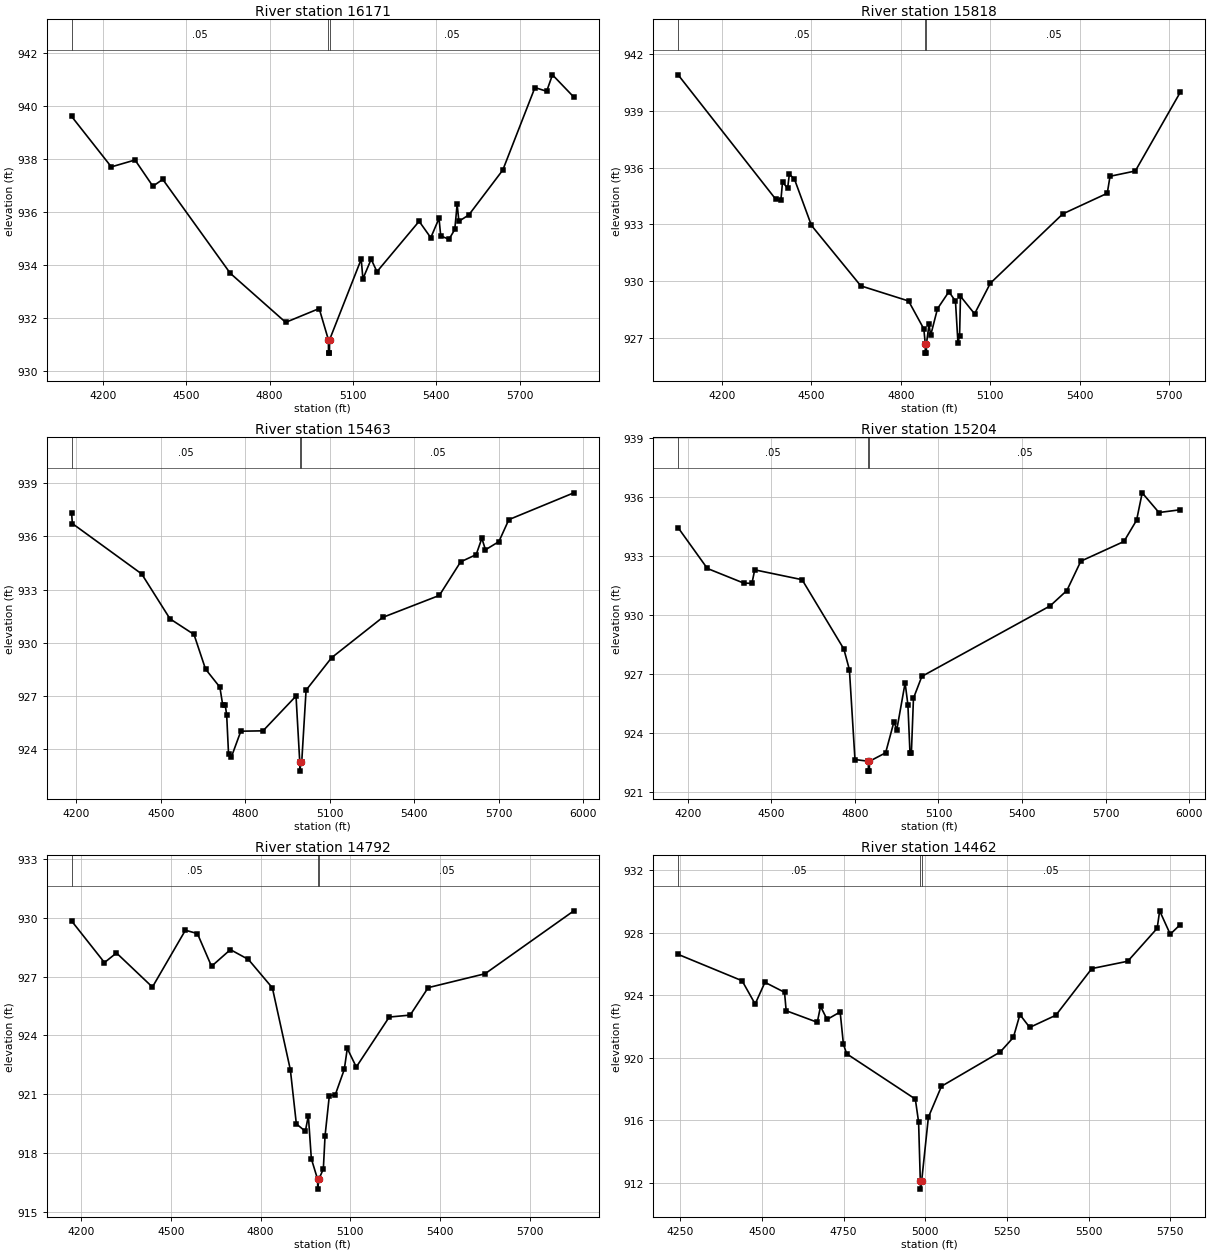
Type RM Length L Ch R = 1,16171,353,353,353
BEGIN DESCRIPTION:
MDW T 009 36.0
END DESCRIPTION:
XS GIS Cut Line= 3
      2270932.13      7119986.62      2270379.00      7119260.00
      2269643.99      7118748.80
#Sta/Elev= 30
  4087.1  939.61  4230.0  937.71  4315.3  937.97  4379.7  936.98  4415.1  937.24
  4658.3  933.70  4857.9  931.85  4978.5  932.37  5011.8  931.19  5012.1  930.69
  5015.6  930.69  5015.8  931.19  5129.9  934.23  5136.0  933.49  5165.7  934.23
  5186.6  933.76  5338.5  935.66  5380.4  935.04  5410.1  935.77  5416.2  935.11
  5445.9  934.98  5466.8  935.35  5475.3  936.30  5481.7  935.66  5517.5  935.90
  5639.7  937.59  5755.5  940.70  5797.7  940.56  5818.6  941.18  5895.6  940.34
#Mann=3,-1,0
  4087.1    0.05       0  5011.8   0.033       0  5015.8    0.05       0
Bank Sta=5011.8,5015.8
Exp/Cntr=0.3,0.1

Type RM Length L Ch R = 1,15818,355,355,355
BEGIN DESCRIPTION:
MDW T 009 35.0
END DESCRIPTION:
XS GIS Cut Line= 3
      2271382.27      7119362.37      2270523.52      7118962.45
      2269825.93      7118724.67
#Sta/Elev= 30
  4052.7  940.91  4379.9  934.33  4397.3  934.26  4402.8  935.22  4420.1  934.92
  4425.7  935.64  4442.4  935.41  4499.8  932.94  4665.4  929.74  4825.6  928.94
  4876.8  927.46  4881.6  926.68  4881.9  926.18  4885.4  926.18  4885.6  926.68
  4894.2  927.70  4899.7  927.12  4922.6  928.53  4960.9  929.43  4982.9  928.93
  4991.2  926.74  4996.7  927.08  4999.7  929.19  5047.0  928.26  5099.9  929.88
  5342.9  933.55  5492.0  934.64  5501.3  935.54  5586.1  935.82  5737.0  939.99
#Mann=3,-1,0
  4052.7    0.05       0  4881.6   0.033       0  4885.6    0.05       0
Bank Sta=4881.6,4885.6
Exp/Cntr=0.3,0.1

Type RM Length L Ch R = 1,15463,259,259,259
BEGIN DESCRIPTION:
MDW T 009 34.0
END DESCRIPTION:
XS GIS Cut Line= 3
      2271444.58      7118825.85      2270644.41      7118660.89
      2269684.62      7118548.08
#Sta/Elev= 30
  4183.0  937.31  4185.4  936.72  4431.7  933.88  4532.3  931.35  4617.5  930.47
  4658.4  928.52  4709.4  927.50  4719.6  926.48  4728.4  926.49  4733.5  925.94
  4740.1  923.76  4750.3  923.57  4783.8  925.02  4862.6  925.04  4979.8  927.00
  4993.1  923.27  4993.4  922.77  4997.1  923.27  5000.0  923.27  5015.5  927.33
  5106.1  929.16  5287.4  931.43  5488.8  932.67  5564.3  934.56  5619.6  934.97
  5639.8  935.89  5652.5  935.24  5700.2  935.70  5735.6  936.94  5966.4  938.45
#Mann=3,-1,0
  4183.0    0.05       0  4993.1   0.033       0  4997.1    0.05       0
Bank Sta=4993.1,4997.1
Exp/Cntr=0.3,0.1

Type RM Length L Ch R = 1,15204,412,412,412
BEGIN DESCRIPTION:
MDW T 009 33.0
END DESCRIPTION:
XS GIS Cut Line= 3
      2271594.00      7118513.64      2270759.13      7118490.27
      2269792.32      7118433.01
#Sta/Elev= 30
  4164.8  934.43  4269.8  932.36  4399.9  931.62  4429.9  931.60  4439.9  932.29
  4610.0  931.79  4760.0  928.27  4780.0  927.22  4800.0  922.66  4848.1  922.57
  4848.3  922.07  4851.8  922.07  4852.1  922.57  4910.1  923.00  4940.1  924.58
  4950.1  924.16  4980.1  926.55  4990.1  925.44  4997.6  922.98  5002.6  922.98
  5010.1  925.77  5040.2  926.88  5501.0  930.46  5561.1  931.24  5611.2  932.73
  5766.1  933.73  5811.5  934.81  5831.6  936.20  5891.7  935.20  5968.5  935.34
#Mann=3,-1,0
  4164.8    0.05       0  4848.1   0.033       0  4852.1    0.05       0
Bank Sta=4848.1,4852.1
Exp/Cntr=0.3,0.1

Type RM Length L Ch R = 1,14792,330,330,330
BEGIN DESCRIPTION:
MDW T 009 32.0
END DESCRIPTION:
XS GIS Cut Line= 3
      2271608.41      7118151.66      2270778.45      7118104.46
      2269932.65      7118133.38
#Sta/Elev= 30
  4168.7  929.84  4278.3  927.72  4318.4  928.21  4438.5  926.47  4548.7  929.37
  4588.8  929.20  4636.0  927.53  4699.0  928.38  4759.1  927.88  4839.2  926.43
  4899.3  922.25  4919.3  919.49  4949.4  919.11  4959.4  919.91  4969.4  917.71
  4990.4  916.66  4990.7  916.16  4994.4  916.66  5009.5  917.19  5015.2  918.88
  5029.5  920.93  5049.5  920.98  5079.5  922.27  5089.5  923.34  5119.5  922.39
  5229.6  924.94  5299.6  925.04  5359.7  926.44  5549.8  927.15  5846.3  930.36
#Mann=3,-1,0
  4168.7    0.05       0  4990.4   0.033       0  4994.4    0.05       0
Bank Sta=4990.4,4994.4
Exp/Cntr=0.3,0.1

Type RM Length L Ch R = 1,14462,69,69,69
BEGIN DESCRIPTION:
MDW T 009 31.0
END DESCRIPTION:
XS GIS Cut Line= 3
      2271584.72      7117849.85      2270839.38      7117838.91
      2270048.23      7117845.51
#Sta/Elev= 30
  4243.9  926.62  4439.6  924.93  4479.6  923.44  4509.6  924.83  4569.5  924.19
  4574.5  923.01  4669.7  922.27  4679.7  923.29  4699.7  922.45  4739.7  922.93
  4749.7  920.86  4759.7  920.25  4969.7  917.35  4979.7  915.88  4985.0  912.08
  4985.3  911.58  4989.0  912.08  5009.7  916.19  5049.7  918.17  5229.7  920.37
  5269.7  921.30  5289.7  922.76  5319.7  921.94  5399.7  922.72  5509.7  925.71
  5619.7  926.18  5709.7  928.29  5717.3  929.41  5749.7  927.91  5780.5  928.53
#Mann=3,-1,0
  4243.9    0.05       0  4985.0   0.033       0  4989.0    0.05       0
Bank Sta=4985,4989
Exp/Cntr=0.3,0.1

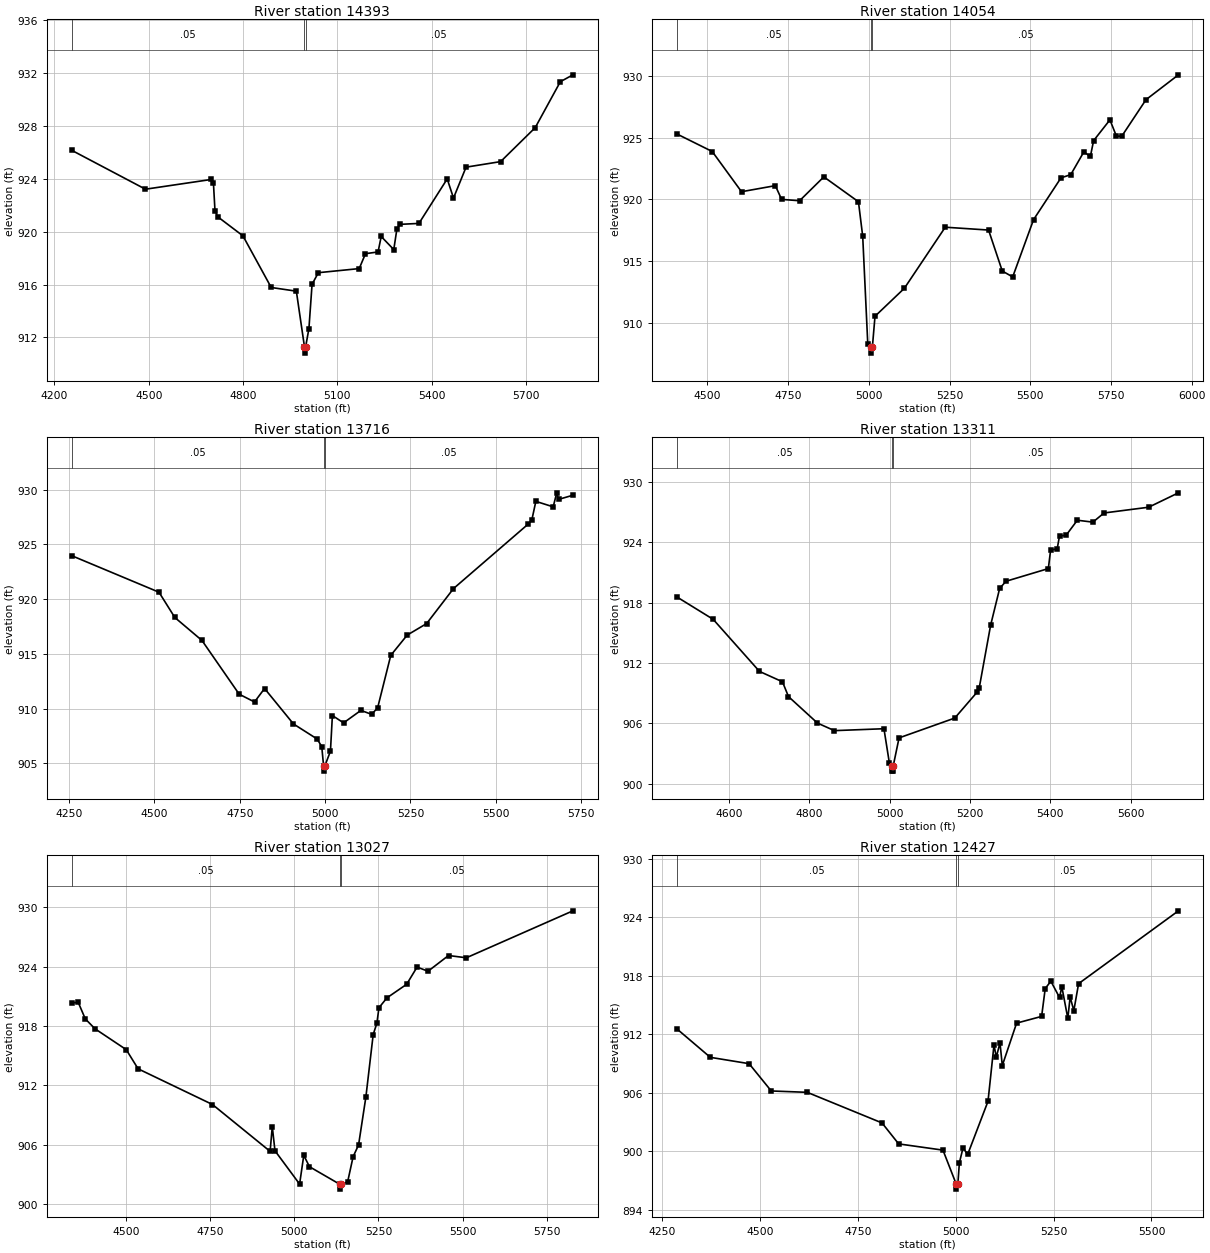
Type RM Length L Ch R = 1,14393,339,339,339
BEGIN DESCRIPTION:
MDW T 009 30.5
END DESCRIPTION:
XS GIS Cut Line= 3
      2271604.00      7117767.41      2270858.61      7117779.92
      2270009.02      7117784.77
#Sta/Elev= 30
  4254.5  926.17  4489.5  923.22  4699.6  923.96  4705.7  923.72  4710.7  921.59
  4719.6  921.13  4799.6  919.69  4889.6  915.78  4969.6  915.50  4995.3  911.31
  4995.6  910.81  4999.3  911.31  5009.6  912.67  5019.6  916.02  5039.6  916.90
  5169.6  917.21  5189.6  918.34  5229.6  918.47  5239.6  919.64  5279.6  918.65
  5289.6  920.22  5299.6  920.56  5359.6  920.63  5449.6  924.00  5469.6  922.55
  5509.6  924.89  5619.6  925.31  5729.6  927.88  5809.6  931.36  5849.6  931.88
#Mann=3,-1,0
  4254.5    0.05       0  4995.3   0.033       0  4999.3    0.05       0
Bank Sta=4995.3,4999.3
Exp/Cntr=0.3,0.1

Type RM Length L Ch R = 1,14054,338,338,338
BEGIN DESCRIPTION:
MDW T 009 30.0
END DESCRIPTION:
XS GIS Cut Line= 3
      2271651.78      7117702.31      2271077.96      7117549.57
      2270129.11      7117409.69
#Sta/Elev= 30
  4406.2  925.28  4515.0  923.87  4605.7  920.62  4710.5  921.11  4729.9  920.00
  4785.6  919.89  4860.7  921.82  4967.9  919.81  4981.1  917.02  4996.9  908.27
  5007.1  908.07  5007.3  907.57  5011.1  908.07  5019.2  910.55  5110.1  912.81
  5236.8  917.75  5371.0  917.52  5413.4  914.21  5445.7  913.73  5510.3  918.36
  5595.3  921.74  5625.6  922.00  5666.1  923.84  5686.3  923.47  5696.4  924.75
  5746.9  926.43  5767.2  925.10  5783.9  925.12  5858.6  928.06  5959.1  930.07
#Mann=3,-1,0
  4406.2    0.05       0  5007.1    0.04       0  5011.1    0.05       0
Bank Sta=5007.1,5011.1
Exp/Cntr=0.3,0.1

Type RM Length L Ch R = 1,13716,405,405,405
BEGIN DESCRIPTION:
MDW T 009 29.0
END DESCRIPTION:
XS GIS Cut Line= 3
      2271695.87      7117444.39      2270979.65      7117249.36
      2270283.58      7117043.05
#Sta/Elev= 30
  4257.7  923.98  4513.6  920.64  4560.0  918.33  4639.5  916.23  4748.5  911.32
  4793.4  910.61  4822.8  911.84  4907.5  908.60  4976.6  907.23  4990.3  906.54
  4995.7  904.79  4996.0  904.29  4999.7  904.79  5015.8  906.11  5021.5  909.37
  5054.3  908.70  5105.0  909.84  5136.3  909.48  5154.0  910.07  5192.5  914.87
  5240.6  916.72  5297.4  917.77  5376.2  920.97  5595.2  926.87  5605.6  927.23
  5617.4  928.94  5668.2  928.44  5678.6  929.72  5683.9  929.12  5726.0  929.50
#Mann=3,-1,0
  4257.7    0.05       0  4995.7    0.04       0  4999.7    0.05       0
Bank Sta=4995.7,4999.7
Exp/Cntr=0.3,0.1

Type RM Length L Ch R = 1,13311,284,284,284
BEGIN DESCRIPTION:
MDW T 009 28.0
END DESCRIPTION:
XS GIS Cut Line= 3
      2271553.86      7117219.03      2271112.57      7116926.76
      2270472.95      7116598.56
#Sta/Elev= 30
  4470.7  918.55  4560.5  916.34  4675.8  911.17  4733.0  910.14  4748.0  908.67
  4820.2  906.04  4862.3  905.29  4985.7  905.48  4999.1  902.10  5004.7  901.77
  5005.0  901.27  5008.5  901.27  5008.7  901.77  5023.3  904.57  5162.1  906.54
  5217.4  909.10  5223.0  909.55  5251.3  915.76  5273.8  919.41  5289.6  920.12
  5395.0  921.38  5400.6  923.20  5417.1  923.36  5422.8  924.61  5439.3  924.69
  5467.2  926.18  5505.9  925.99  5533.7  926.90  5644.7  927.47  5718.9  928.90
#Mann=3,-1,0
  4470.7    0.05       0  5004.7    0.04       0  5008.7    0.05       0
Bank Sta=5004.7,5008.7
Exp/Cntr=0.3,0.1

Type RM Length L Ch R = 1,13027,600,600,600
BEGIN DESCRIPTION:
MDW T 009 27.0
END DESCRIPTION:
XS GIS Cut Line= 3
      2271749.26      7117127.54      2271235.14      7116712.72
      2270472.55      7116392.50
#Sta/Elev= 30
  4339.4  920.36  4359.2  920.39  4380.0  918.73  4408.8  917.73  4501.5  915.62
  4536.7  913.68  4757.4  910.07  4928.5  905.33  4934.9  907.83  4942.9  905.39
  5016.0  902.02  5028.4  904.93  5045.2  903.78  5134.8  902.01  5135.1  901.51
  5138.8  902.01  5158.5  902.24  5174.8  904.79  5191.0  905.98  5212.7  910.83
  5234.4  917.15  5245.3  918.29  5251.5  919.86  5275.3  920.86  5333.7  922.23
  5364.6  923.97  5397.1  923.55  5457.9  925.14  5510.8  924.91  5827.1  929.66
#Mann=3,-1,0
  4339.4    0.05       0  5134.8    0.04       0  5138.8    0.05       0
Bank Sta=5134.8,5138.8
Exp/Cntr=0.3,0.1

Type RM Length L Ch R = 1,12427,673,673,673
BEGIN DESCRIPTION:
MDW T 009 26.0
END DESCRIPTION:
XS GIS Cut Line= 3
      2271778.99      7116859.99      2271275.01      7116358.32
      2270793.09      7116056.00
#Sta/Elev= 30
  4288.9  912.53  4373.7  909.63  4472.7  908.98  4529.3  906.18  4621.2  906.04
  4812.1  902.90  4854.6  900.75  4967.7  900.11  5001.7  896.61  5002.0  896.11
  5005.7  896.61  5009.6  898.81  5018.9  900.34  5030.8  899.67  5082.7  905.12
  5098.0  910.90  5103.9  909.65  5113.3  911.12  5119.2  908.79  5155.7  913.14
  5219.6  913.83  5228.8  916.69  5243.2  917.44  5265.3  915.77  5271.2  916.87
  5286.5  913.63  5292.4  915.82  5301.8  914.42  5314.0  917.19  5568.9  924.66
#Mann=3,-1,0
  4288.9    0.05       0  5001.7    0.04       0  5005.7    0.05       0
Bank Sta=5001.7,5005.7
Exp/Cntr=0.3,0.1

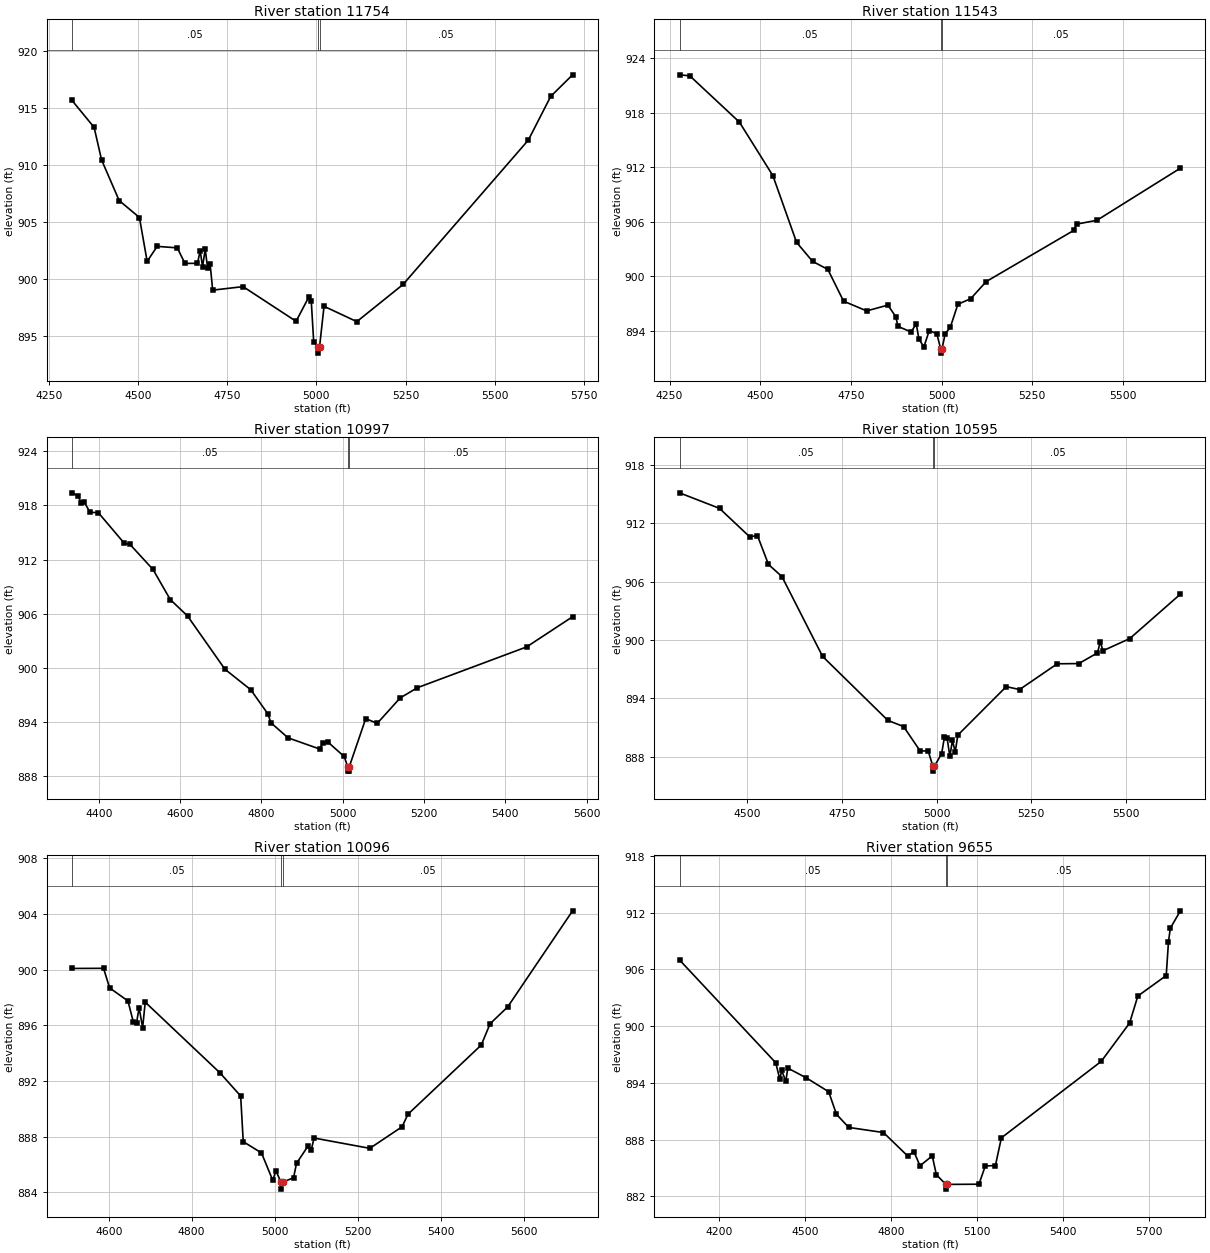
Type RM Length L Ch R = 1,11754,211,211,211
BEGIN DESCRIPTION:
MDW T 009 25.0
END DESCRIPTION:
XS GIS Cut Line= 3
      2272250.04      7116707.35      2271788.79      7116199.57
      2271208.89      7115775.51
#Sta/Elev= 30
  4314.0  915.71  4376.8  913.31  4397.8  910.44  4447.1  906.87  4503.9  905.38
  4525.5  901.52  4553.6  902.84  4610.0  902.71  4631.6  901.34  4666.7  901.35
  4674.2  902.45  4680.9  901.06  4688.4  902.59  4695.1  900.90  4702.2  901.25
  4709.3  898.99  4794.5  899.30  4943.1  896.25  4978.3  898.35  4985.7  898.04
  4992.5  894.45  5004.8  893.95  5005.1  893.45  5008.8  893.95  5021.5  897.57
  5113.4  896.22  5243.1  899.49  5594.4  912.19  5657.0  916.03  5718.4  917.93
#Mann=3,-1,0
  4314.0    0.05       0  5004.8   0.033       0  5008.8    0.05       0
Bank Sta=5004.8,5008.8
Exp/Cntr=0.3,0.1

Type RM Length L Ch R = 1,11543,546,546,546
BEGIN DESCRIPTION:
MDW T 009 24.0
END DESCRIPTION:
XS GIS Cut Line= 3
      2272519.16      7116459.98      2271927.98      7116044.29
      2271417.21      7115628.36
#Sta/Elev= 30
  4277.3  922.15  4305.7  922.04  4442.5  916.95  4534.8  911.07  4600.2  903.73
  4644.2  901.65  4686.4  900.76  4729.8  897.27  4793.6  896.20  4852.1  896.84
  4873.7  895.57  4879.8  894.50  4915.6  893.89  4930.4  894.75  4937.6  893.11
  4951.3  892.24  4966.1  894.04  4987.0  893.69  4997.4  892.06  4997.6  891.56
  5001.4  892.06  5009.9  893.66  5024.3  894.42  5045.1  896.93  5080.3  897.54
  5123.4  899.43  5364.7  905.05  5372.6  905.74  5428.6  906.16  5658.7  911.89
#Mann=3,-1,0
  4277.3    0.05       0  4997.4   0.033       0  5001.4    0.05       0
Bank Sta=4997.4,5001.4
Exp/Cntr=0.3,0.1

Type RM Length L Ch R = 1,10997,402,402,402
BEGIN DESCRIPTION:
MDW T 009 23.0
END DESCRIPTION:
XS GIS Cut Line= 3
      2272688.07      7116144.01      2272229.00      7115660.00
      2271828.98      7115259.98
#Sta/Elev= 30
  4332.9  919.38  4349.3  919.03  4356.2  918.20  4363.5  918.39  4377.6  917.24
  4398.7  917.17  4462.5  913.79  4476.4  913.67  4533.0  910.90  4575.5  907.57
  4617.9  905.76  4710.1  899.86  4773.7  897.59  4816.1  894.90  4823.0  893.95
  4865.5  892.27  4943.6  891.03  4950.4  891.70  4964.6  891.76  5003.5  890.21
  5012.1  889.09  5012.4  888.59  5015.9  888.59  5016.2  889.09  5056.6  894.40
  5084.8  893.87  5141.4  896.69  5183.8  897.82  5452.5  902.33  5565.7  905.67
#Mann=3,-1,0
  4332.9    0.05       0  5012.1   0.033       0  5016.2    0.05       0
Bank Sta=5012.1,5016.2
Exp/Cntr=0.3,0.1

Type RM Length L Ch R = 1,10595,499,499,499
BEGIN DESCRIPTION:
MDW T 009 22.0
END DESCRIPTION:
XS GIS Cut Line= 3
      2272905.50      7115931.75      2272498.88      7115389.72
      2272023.33      7114957.08
#Sta/Elev= 30
  4322.4  915.14  4427.9  913.54  4507.0  910.63  4527.9  910.74  4557.0  907.77
  4592.4  906.53  4699.6  898.32  4871.6  891.74  4913.3  891.10  4957.0  888.58
  4977.9  888.61  4990.4  887.02  4990.7  886.52  4994.5  887.02  5013.6  888.33
  5021.0  890.06  5027.8  889.94  5035.2  888.03  5041.9  889.67  5049.4  888.51
  5056.1  890.22  5183.8  895.21  5219.0  894.91  5318.3  897.56  5375.1  897.58
  5424.4  898.68  5431.8  899.85  5438.6  898.90  5509.5  900.15  5642.9  904.72
#Mann=3,-1,0
  4322.4    0.05       0  4990.4   0.033       0  4994.5    0.05       0
Bank Sta=4990.4,4994.5
Exp/Cntr=0.3,0.1

Type RM Length L Ch R = 1,10096,441,441,441
BEGIN DESCRIPTION:
MDW T 009 21.0
END DESCRIPTION:
XS GIS Cut Line= 3
      2273167.23      7115539.83      2272878.61      7115144.84
      2272367.72      7114640.06
#Sta/Elev= 30
  4510.8  900.08  4587.6  900.09  4602.2  898.68  4646.3  897.75  4659.2  896.26
  4667.1  896.18  4673.3  897.26  4681.8  895.83  4688.0  897.66  4867.9  892.59
  4918.1  890.92  4924.3  887.64  4968.3  886.83  4995.3  884.87  5003.2  885.54
  5015.2  884.73  5015.5  884.23  5019.4  884.73  5045.6  885.05  5052.7  886.08
  5081.0  887.35  5088.0  887.02  5095.1  887.90  5229.4  887.16  5307.2  888.71
  5321.4  889.61  5498.1  894.58  5519.4  896.11  5561.8  897.32  5718.2  904.22
#Mann=3,-1,0
  4510.8    0.05       0  5015.2   0.033       0  5019.4    0.05       0
Bank Sta=5015.2,5019.4
Exp/Cntr=0.3,0.1

Type RM Length L Ch R = 1,9655,179,179,179
BEGIN DESCRIPTION:
MDW T 009 20.0
END DESCRIPTION:
XS GIS Cut Line= 3
      2273828.94      7115482.79      2273109.21      7114880.49
      2272479.73      7114370.57
#Sta/Elev= 30
  4061.5  907.01  4397.4  896.13  4411.7  894.38  4418.2  895.32  4432.5  894.16
  4439.6  895.56  4504.1  894.53  4582.2  893.06  4609.5  890.67  4652.4  889.28
  4773.5  888.74  4858.0  886.26  4880.1  886.71  4901.0  885.22  4943.9  886.27
  4958.2  884.28  4991.3  883.25  4991.6  882.75  4995.5  883.25  5106.9  883.27
  5129.0  885.20  5164.4  885.25  5185.2  888.18  5533.7  896.27  5632.8  900.33
  5661.6  903.19  5760.7  905.36  5768.6  908.96  5775.1  910.37  5810.1  912.21
#Mann=3,-1,0
  4061.5    0.05       0  4991.3   0.033       0  4995.5    0.05       0
Bank Sta=4991.3,4995.5
Exp/Cntr=0.3,0.1