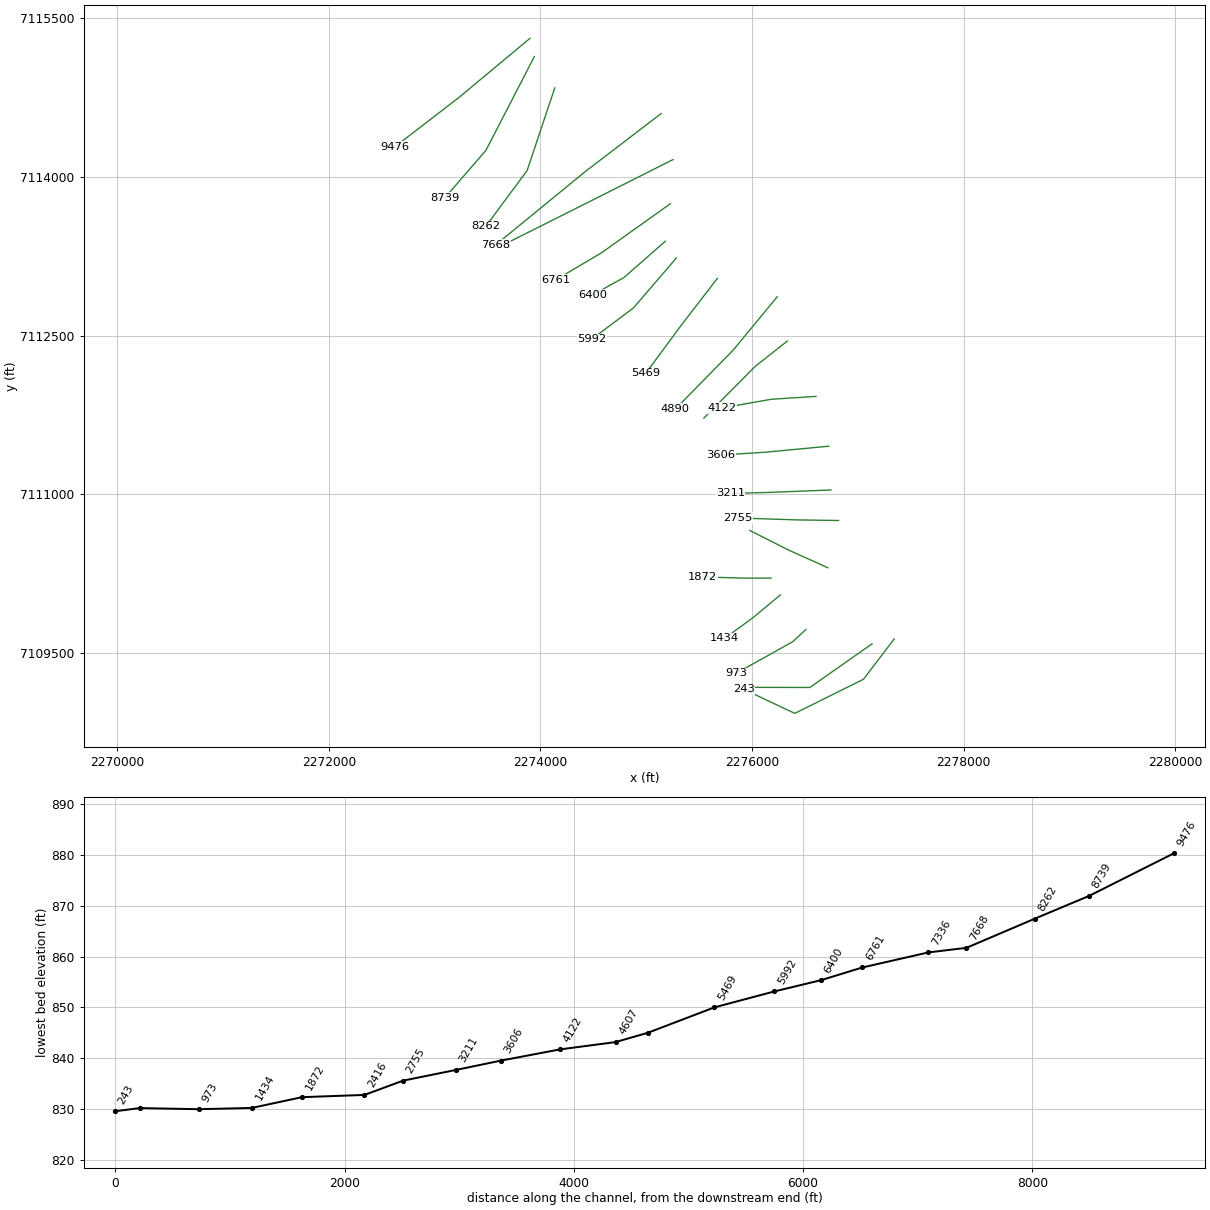
HEC-RAS study MDW T 009.prj: MDW T 009 Base Level Engineering

--- MDW T 009.g01 (geometry) --- (continued)

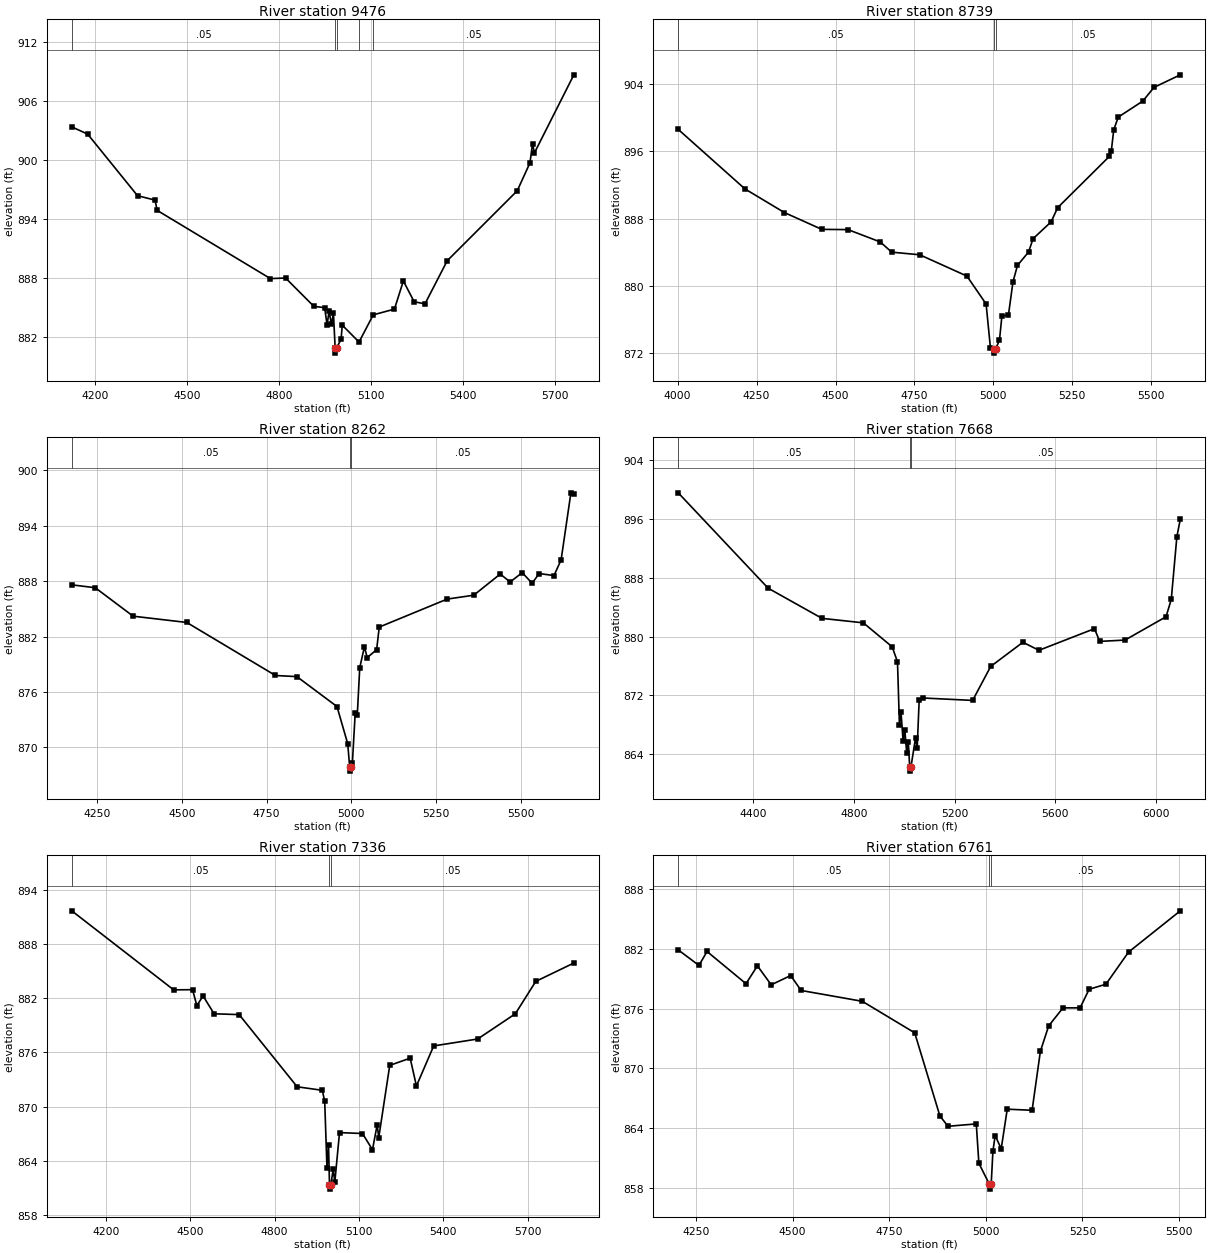
Type RM Length L Ch R = 1,9476,737,737,737
BEGIN DESCRIPTION:
MDW T 009 19.5
END DESCRIPTION:
XS GIS Cut Line= 3
      2273901.42      7115310.20      2273227.84      7114749.52
      2272624.01      7114285.06
#Sta/Elev= 30
  4123.6  903.35  4175.5  902.61  4338.2  896.34  4395.5  895.89  4402.0  894.85
  4771.7  887.90  4821.2  887.96  4913.6  885.07  4948.7  884.94  4956.6  883.18
  4963.1  884.57  4970.9  883.24  4977.4  884.39  4983.0  880.81  4983.4  880.31
  4987.4  880.81  5002.4  881.73  5006.1  883.16  5060.9  881.44  5107.3  884.21
  5176.4  884.79  5205.5  887.66  5240.8  885.54  5276.1  885.33  5348.7  889.72
  5577.0  896.84  5618.7  899.69  5626.9  901.63  5633.2  900.70  5761.8  908.65
#Mann=5,-1,0
  4123.6    0.05       0  4983.0   0.033       0  4987.4    0.05       0
  5060.9    0.12       0  5107.3    0.05       0
Bank Sta=4983,4987.4
Exp/Cntr=0.3,0.1

Type RM Length L Ch R = 1,8739,477,477,477
BEGIN DESCRIPTION:
MDW T 009 19.0
END DESCRIPTION:
XS GIS Cut Line= 3
      2273942.94      7115138.46      2273484.93      7114251.54
      2273097.67      7113803.77
#Sta/Elev= 30
  4001.8  898.63  4212.9  891.54  4337.7  888.72  4456.5  886.71  4539.5  886.68
  4641.6  885.21  4678.0  883.99  4766.6  883.68  4916.1  881.14  4976.9  877.81
  4990.5  872.62  5002.8  872.45  5003.2  871.95  5007.2  872.45  5019.3  873.52
  5026.9  876.36  5047.8  876.53  5062.0  880.45  5076.3  882.42  5111.4  884.01
  5125.7  885.60  5182.7  887.60  5203.6  889.30  5367.0  895.40  5373.6  896.11
  5381.2  898.59  5395.5  900.10  5473.3  902.01  5508.5  903.64  5592.0  905.14
#Mann=3,-1,0
  4001.8    0.05       0  5002.8   0.033       0  5007.2    0.05       0
Bank Sta=5002.8,5007.2
Exp/Cntr=0.3,0.1

Type RM Length L Ch R = 1,8262,594,594,594
BEGIN DESCRIPTION:
MDW T 009 18.0
END DESCRIPTION:
XS GIS Cut Line= 3
      2274135.64      7114841.57      2273873.96      7114059.91
      2273482.99      7113533.02
#Sta/Elev= 30
  4175.7  887.60  4244.9  887.29  4356.6  884.21  4514.8  883.53  4776.3  877.79
  4839.4  877.67  4957.7  874.43  4989.4  870.40  4995.0  867.94  4995.5  867.44
  4999.5  867.94  5003.1  868.34  5011.4  873.70  5017.6  873.54  5024.8  878.63
  5038.5  880.88  5046.9  879.73  5074.6  880.58  5082.3  883.03  5282.6  886.06
  5361.0  886.48  5439.1  888.77  5468.3  887.91  5503.8  888.92  5533.0  887.78
  5553.9  888.82  5597.6  888.61  5618.6  890.31  5647.4  897.56  5656.1  897.43
#Mann=3,-1,0
  4175.7    0.05       0  4995.0   0.033       0  4999.5    0.05       0
Bank Sta=4995,4999.5
Exp/Cntr=0.3,0.1

Type RM Length L Ch R = 1,7668,332,332,332
BEGIN DESCRIPTION:
MDW T 009 17.0
END DESCRIPTION:
XS GIS Cut Line= 3
      2275140.84      7114599.39      2274427.43      7114054.16
      2273579.01      7113360.01
#Sta/Elev= 30
  4102.1  899.54  4459.1  886.58  4673.2  882.48  4837.3  881.87  4951.6  878.62
  4972.9  876.58  4980.6  868.02  4986.9  869.70  4995.2  865.85  5002.2  867.27
  5009.4  864.20  5015.9  865.68  5021.5  862.22  5022.0  861.72  5026.1  862.22
  5044.6  866.24  5051.1  864.83  5059.0  871.32  5073.3  871.66  5271.4  871.33
  5343.2  875.95  5471.0  879.23  5534.9  878.14  5755.3  881.08  5776.1  879.35
  5876.6  879.53  6039.5  882.70  6060.3  885.06  6082.6  893.60  6096.2  895.96
#Mann=3,-1,0
  4102.1    0.05       0  5021.5   0.033       0  5026.1    0.05       0
Bank Sta=5021.5,5026.1
Exp/Cntr=0.3,0.1

Type RM Length L Ch R = 1,7336,575,575,575
BEGIN DESCRIPTION:
MDW T 009 16.0
END DESCRIPTION:
XS GIS Cut Line= 3
      2275252.82      7114164.50      2274429.45      7113749.81
      2273656.50      7113362.43
#Sta/Elev= 30
  4078.1  891.74  4440.7  882.96  4507.9  882.98  4523.1  881.22  4545.4  882.28
  4584.5  880.30  4673.7  880.21  4880.1  872.19  4969.4  871.80  4978.1  870.59
  4986.1  863.21  4991.7  865.77  4995.1  861.32  4995.6  860.82  4999.8  861.32
  5008.4  863.01  5014.0  861.58  5030.8  867.10  5112.4  867.00  5148.1  865.20
  5164.8  867.97  5170.4  866.54  5209.5  874.57  5282.2  875.37  5304.5  872.28
  5365.9  876.73  5522.4  877.50  5656.4  880.30  5729.1  883.90  5864.6  885.94
#Mann=3,-1,0
  4078.1    0.05       0  4995.1   0.033       0  4999.8    0.05       0
Bank Sta=4995.1,4999.8
Exp/Cntr=0.3,0.1

Type RM Length L Ch R = 1,6761,361,361,361
BEGIN DESCRIPTION:
MDW T 009 15.0
END DESCRIPTION:
XS GIS Cut Line= 3
      2275226.79      7113746.75      2274578.87      7113284.87
      2274146.04      7113028.42
#Sta/Elev= 30
  4204.3  881.92  4257.9  880.36  4278.8  881.76  4379.6  878.52  4409.1  880.32
  4444.8  878.41  4495.2  879.34  4522.2  877.84  4680.5  876.75  4816.0  873.58
  4881.2  865.22  4902.1  864.18  4975.3  864.42  4982.0  860.46  5009.1  858.36
  5009.6  857.86  5013.9  858.36  5018.3  861.67  5024.1  863.25  5039.8  861.92
  5055.4  865.90  5119.7  865.79  5141.1  871.72  5162.6  874.28  5199.6  876.09
  5243.9  876.09  5267.2  877.96  5310.7  878.47  5369.2  881.70  5503.1  885.85
#Mann=3,-1,0
  4204.3    0.05       0  5009.1   0.033       0  5013.9    0.05       0
Bank Sta=5009.1,5013.9
Exp/Cntr=0.3,0.1

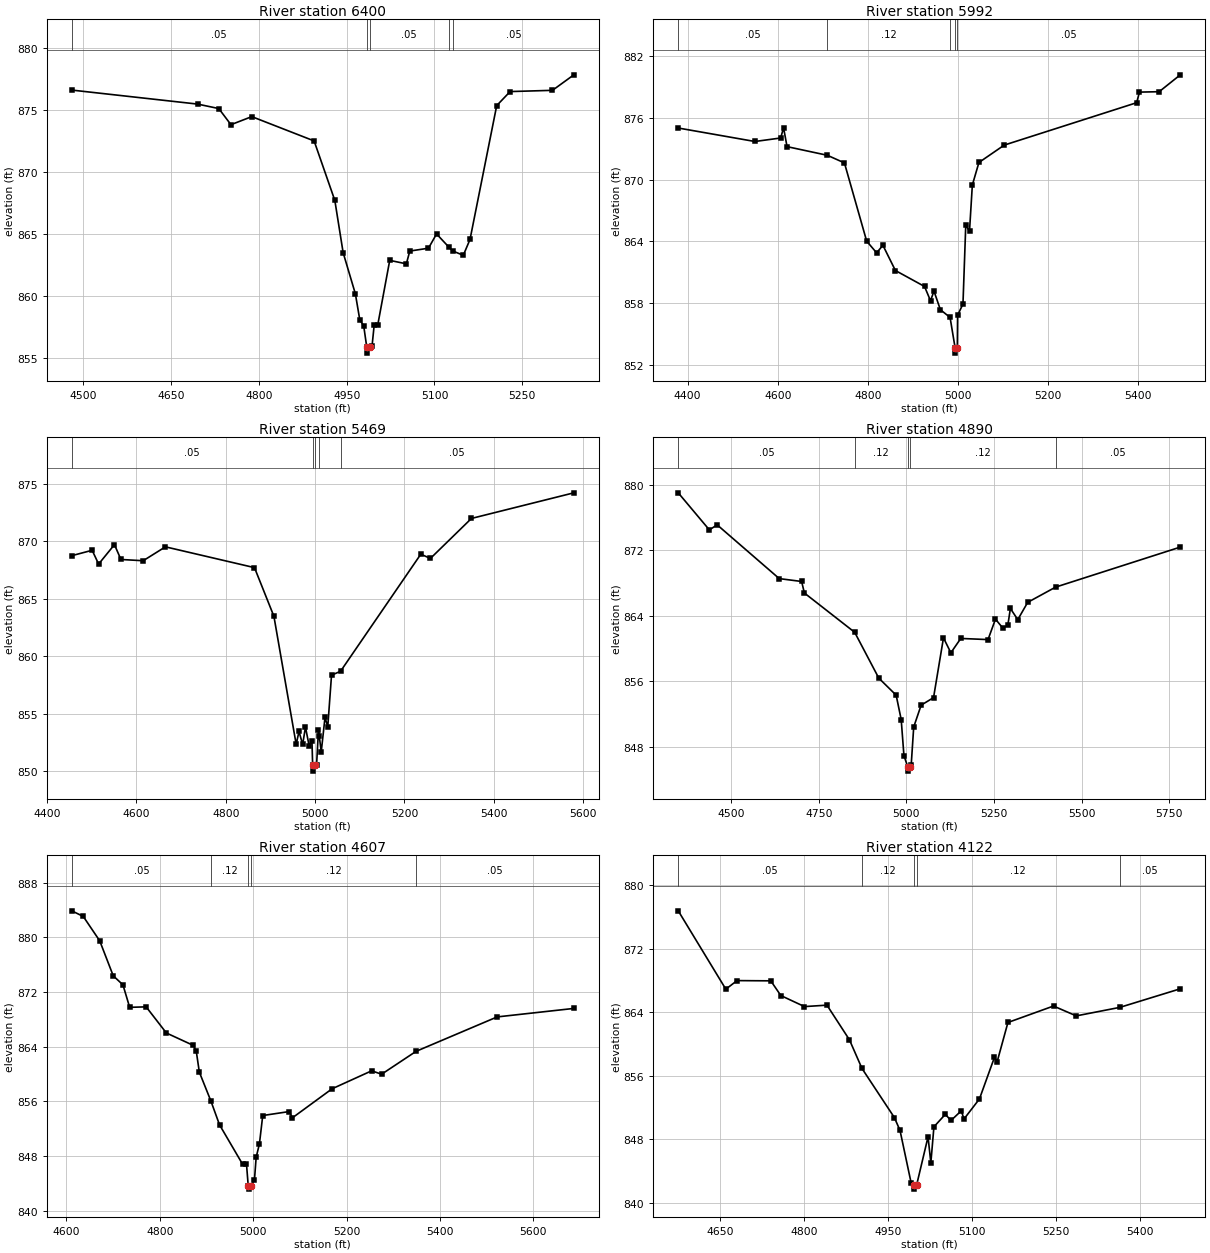
Type RM Length L Ch R = 1,6400,408,408,408
BEGIN DESCRIPTION:
MDW T 009 14.0
END DESCRIPTION:
XS GIS Cut Line= 3
      2275180.13      7113393.01      2274789.69      7113050.02
      2274493.65      7112886.49
#Sta/Elev= 30
  4480.3  876.57  4695.4  875.44  4731.5  875.08  4752.3  873.78  4787.9  874.43
  4894.4  872.47  4929.8  867.67  4944.0  863.46  4964.9  860.14  4972.5  858.03
  4979.1  857.57  4984.3  855.86  4984.9  855.36  4989.1  855.86  4993.4  855.94
  4997.1  857.65  5003.2  857.65  5023.6  862.84  5052.0  862.56  5057.9  863.59
  5089.8  863.82  5103.6  864.97  5125.0  863.89  5131.5  863.59  5149.3  863.25
  5160.8  864.53  5206.4  875.32  5229.3  876.45  5301.7  876.55  5338.2  877.80
#Mann=5,-1,0
  4480.3    0.05       0  4984.3   0.033       0  4989.1    0.05       0
  5125.0    0.12       0  5131.5    0.05       0
Bank Sta=4984.3,4989.1
Exp/Cntr=0.3,0.1

Type RM Length L Ch R = 1,5992,523,523,523
BEGIN DESCRIPTION:
MDW T 009 13.0
END DESCRIPTION:
XS GIS Cut Line= 3
      2275284.31      7113234.61      2274879.98      7112763.54
      2274485.68      7112467.44
#Sta/Elev= 30
  4379.2  875.02  4549.3  873.71  4606.4  874.05  4612.9  875.04  4620.6  873.21
  4710.0  872.37  4747.9  871.63  4797.3  864.02  4819.3  862.89  4833.3  863.62
  4861.0  861.17  4925.6  859.62  4938.9  858.23  4946.6  859.17  4960.8  857.36
  4982.3  856.61  4993.5  853.64  4994.1  853.14  4998.4  853.64  4999.0  856.82
  5010.9  857.91  5017.1  865.59  5025.4  864.99  5031.7  869.48  5046.3  871.67
  5102.5  873.36  5396.2  877.48  5402.5  878.51  5446.2  878.55  5493.1  880.19
#Mann=5,-1,0
  4379.2    0.05       0  4710.0    0.12       0  4982.3    0.05       0
  4993.5   0.033       0  4998.4    0.05       0
Bank Sta=4993.5,4998.4
Exp/Cntr=0.3,0.1

Type RM Length L Ch R = 1,5469,579,579,579
BEGIN DESCRIPTION:
MDW T 009 12.0
END DESCRIPTION:
XS GIS Cut Line= 3
      2275671.65      7113041.43      2275339.07      7112610.17
      2274994.92      7112144.55
#Sta/Elev= 30
  4455.4  868.75  4501.0  869.22  4515.5  868.02  4550.9  869.71  4565.4  868.42
  4615.2  868.31  4665.0  869.52  4864.3  867.71  4907.8  863.47  4957.6  852.33
  4963.9  853.45  4972.1  852.32  4978.4  853.83  4986.6  852.21  4992.9  852.62
  4994.5  850.50  4995.1  850.00  4999.5  850.50  5003.2  850.50  5007.5  853.58
  5009.3  853.03  5013.7  851.68  5022.1  854.67  5028.3  853.87  5036.7  858.35
  5056.9  858.69  5236.5  868.88  5258.0  868.51  5349.8  871.99  5579.0  874.22
#Mann=5,-1,0
  4455.4    0.05       0  4994.5   0.033       0  4999.5    0.05       0
  5009.3    0.12       0  5056.9    0.05       0
Bank Sta=4994.5,4999.5
Exp/Cntr=0.3,0.1

Type RM Length L Ch R = 1,4890,283,283,283
BEGIN DESCRIPTION:
MDW T 009 11.0
END DESCRIPTION:
XS GIS Cut Line= 3
      2276236.97      7112867.82      2275822.93      7112365.84
      2275275.61      7111807.72
#Sta/Elev= 30
  4349.3  879.01  4438.1  874.48  4460.3  875.10  4637.5  868.53  4701.3  868.18
  4709.2  866.77  4852.7  861.97  4921.5  856.37  4971.0  854.29  4985.4  851.31
  4993.2  846.91  5004.3  845.51  5005.1  845.01  5009.6  845.51  5014.0  845.80
  5021.1  850.40  5042.3  853.07  5077.7  853.99  5106.0  861.29  5127.1  859.47
  5155.4  861.22  5233.1  861.08  5254.4  863.58  5275.6  862.47  5289.7  862.86
  5296.9  864.88  5318.0  863.52  5346.3  865.63  5425.9  867.49  5781.7  872.38
#Mann=5,-1,0
  4349.3    0.05       0  4852.7    0.12       0  5004.3    0.07       0
  5009.6    0.12       0  5425.9    0.05       0
Bank Sta=5004.3,5009.6
Exp/Cntr=0.3,0.1

Type RM Length L Ch R = 1,4607,485,485,485
BEGIN DESCRIPTION:
MDW T 009 10.0
END DESCRIPTION:
XS GIS Cut Line= 3
      2276333.55      7112450.09      2276029.00      7112210.00
      2275544.73      7111722.02
#Sta/Elev= 30
  4611.5  883.86  4636.1  883.04  4671.4  879.47  4700.3  874.36  4721.1  873.04
  4735.5  869.75  4770.8  869.82  4814.1  866.00  4871.9  864.18  4878.2  863.31
  4884.7  860.28  4909.6  856.03  4927.9  852.58  4977.6  846.78  4985.7  846.84
  4989.4  843.67  4990.2  843.17  4994.7  843.67  5002.8  844.55  5006.4  847.82
  5013.4  849.79  5020.5  853.93  5077.1  854.51  5084.1  853.60  5169.0  857.84
  5253.8  860.47  5275.1  859.97  5349.0  863.32  5522.6  868.35  5686.8  869.59
#Mann=5,-1,0
  4611.5    0.05       0  4909.6    0.12       0  4989.4    0.07       0
  4994.7    0.12       0  5349.0    0.05       0
Bank Sta=4989.4,4994.7
Exp/Cntr=0.3,0.1

Type RM Length L Ch R = 1,4122,516,516,516
BEGIN DESCRIPTION:
MDW T 009 9.0
END DESCRIPTION:
XS GIS Cut Line= 3
      2276603.72      7111927.09      2276180.22      7111899.50
      2275716.21      7111817.51
#Sta/Elev= 30
  4575.6  876.75  4660.5  866.89  4680.5  867.97  4740.7  867.94  4758.6  866.09
  4800.8  864.70  4840.9  864.88  4881.0  860.52  4903.4  856.91  4961.1  850.74
  4971.2  849.12  4991.2  842.46  4995.5  842.23  4996.2  841.73  5000.8  842.23
  5021.2  848.31  5026.2  845.04  5031.7  849.57  5052.0  851.14  5062.2  850.37
  5080.4  851.58  5085.4  850.56  5112.9  853.08  5139.6  858.30  5144.6  857.79
  5163.7  862.70  5245.0  864.77  5285.6  863.53  5363.3  864.60  5471.2  866.94
#Mann=5,-1,0
  4575.6    0.05       0  4903.4    0.12       0  4995.5    0.07       0
  5000.8    0.12       0  5363.3    0.05       0
Bank Sta=4995.5,5000.8
Exp/Cntr=0.3,0.1

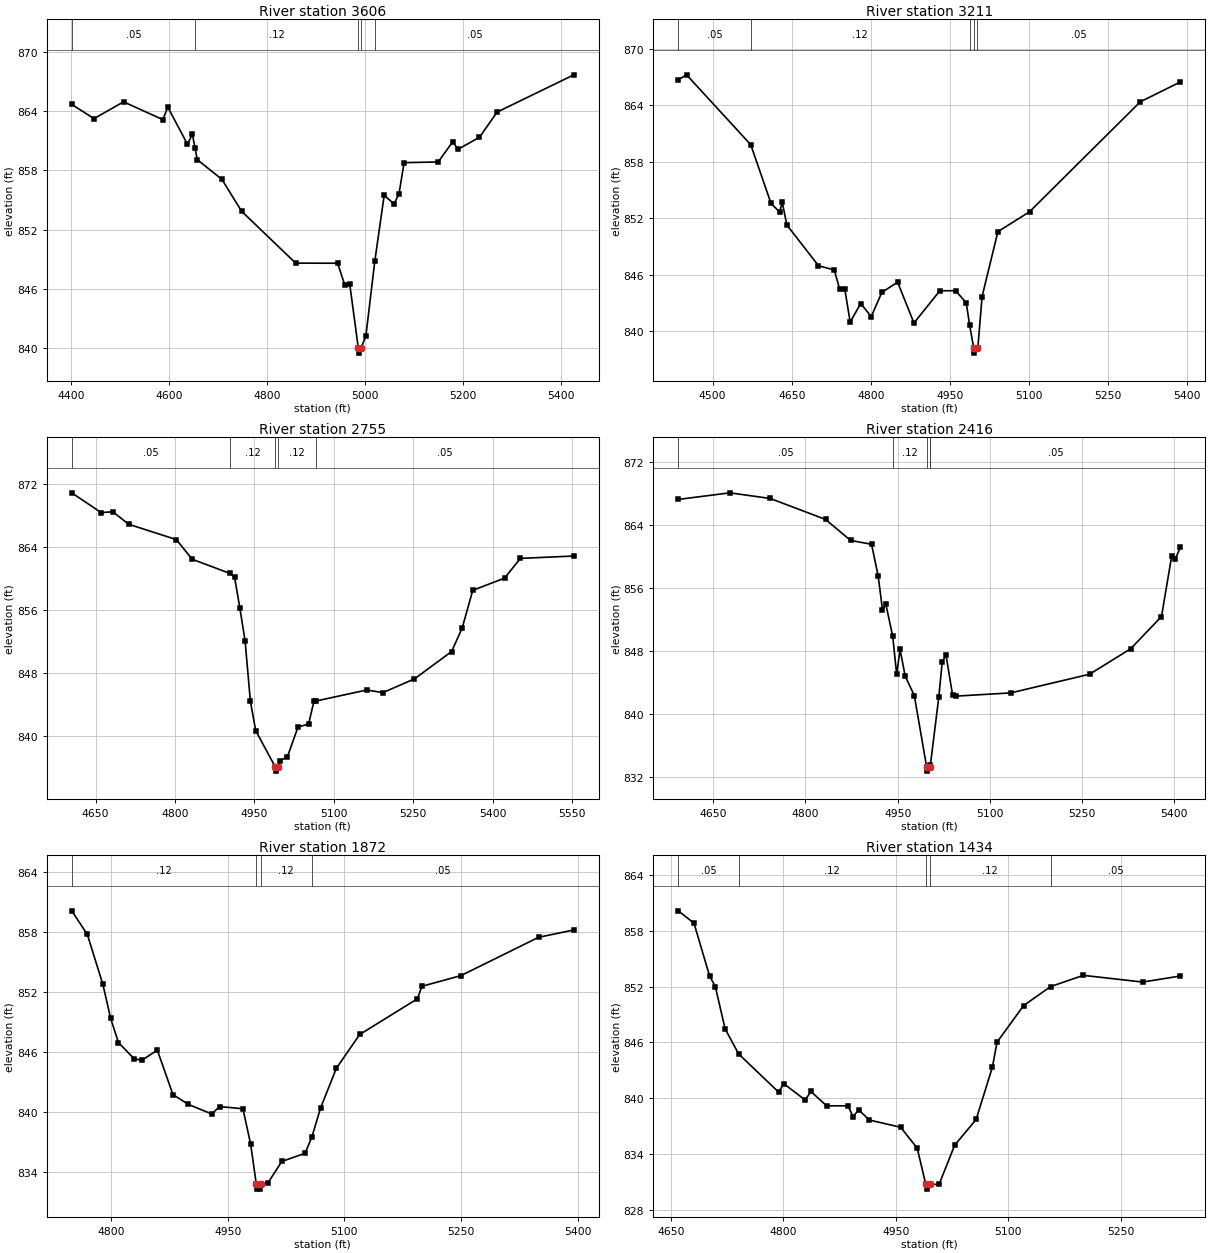
Type RM Length L Ch R = 1,3606,395,395,395
BEGIN DESCRIPTION:
MDW T 009 8.0
END DESCRIPTION:
XS GIS Cut Line= 3
      2276724.19      7111456.17      2276128.55      7111399.81
      2275702.51      7111372.72
#Sta/Elev= 30
  4401.7  864.67  4447.1  863.23  4507.4  864.93  4587.7  863.13  4597.8  864.39
  4637.9  860.65  4648.0  861.64  4653.3  860.28  4658.0  859.08  4708.3  857.09
  4748.4  853.87  4858.9  848.62  4944.6  848.61  4959.4  846.37  4969.4  846.46
  4986.8  840.02  4987.6  839.52  4992.2  840.02  5002.3  841.27  5020.6  848.87
  5039.6  855.47  5059.7  854.62  5069.7  855.58  5080.3  858.78  5149.9  858.85
  5179.9  860.91  5189.9  860.12  5234.2  861.34  5270.1  863.89  5426.9  867.66
#Mann=5,-1,0
  4401.7    0.05       0  4653.3    0.12       0  4986.8    0.07       0
  4992.2    0.12       0  5020.6    0.05       0
Bank Sta=4986.8,4992.2
Exp/Cntr=0.3,0.1

Type RM Length L Ch R = 1,3211,456,456,456
BEGIN DESCRIPTION:
MDW T 009 7.0
END DESCRIPTION:
XS GIS Cut Line= 3
      2276744.79      7111042.76      2276180.05      7111020.11
      2275793.07      7111010.24
#Sta/Elev= 30
  4434.8  866.72  4450.6  867.24  4572.3  859.82  4610.7  853.59  4627.1  852.66
  4632.1  853.70  4640.8  851.29  4700.8  846.96  4730.8  846.50  4740.8  844.50
  4750.8  844.45  4760.9  840.97  4780.9  842.94  4800.9  841.55  4820.9  844.12
  4850.9  845.21  4881.9  840.87  4931.0  844.30  4961.0  844.30  4981.0  843.02
  4987.4  840.69  4995.3  838.17  4996.1  837.67  5000.7  838.17  5003.0  838.17
  5011.1  843.68  5041.1  850.58  5101.1  852.69  5311.1  864.37  5387.1  866.48
#Mann=5,-1,0
  4434.8    0.05       0  4572.3    0.12       0  4987.4    0.05       0
  4995.3   0.033       0  5000.7    0.05       0
Bank Sta=4995.3,5000.7
Exp/Cntr=0.3,0.1

Type RM Length L Ch R = 1,2755,339,339,339
BEGIN DESCRIPTION:
MDW T 009 6.0
END DESCRIPTION:
XS GIS Cut Line= 3
      2276816.47      7110754.13      2276421.41      7110759.99
      2275868.10      7110778.01
#Sta/Elev= 30
  4604.9  870.91  4660.4  868.40  4682.4  868.51  4712.4  866.92  4802.4  864.98
  4832.4  862.48  4903.9  860.68  4912.4  860.23  4922.4  856.35  4932.4  852.11
  4942.4  844.46  4952.4  840.74  4989.7  836.09  4990.5  835.59  4995.2  836.09
  4998.7  836.92  5012.4  837.42  5032.4  841.19  5052.4  841.56  5062.4  844.43
  5065.8  844.48  5162.5  845.89  5192.5  845.55  5252.5  847.30  5322.6  850.77
  5342.6  853.75  5362.6  858.54  5422.6  860.08  5452.6  862.59  5553.6  862.89
#Mann=5,-1,0
  4604.9    0.05       0  4903.9    0.12       0  4989.7    0.07       0
  4995.2    0.12       0  5065.8    0.05       0
Bank Sta=4989.7,4995.2
Exp/Cntr=0.3,0.1

Type RM Length L Ch R = 1,2416,544,544,544
BEGIN DESCRIPTION:
MDW T 009 5.0
END DESCRIPTION:
XS GIS Cut Line= 3
      2276715.52      7110308.17      2276344.52      7110475.05
      2275979.04      7110659.98
#Sta/Elev= 30
  4593.2  867.29  4677.1  868.13  4742.9  867.41  4832.7  864.75  4873.5  862.08
  4907.6  861.59  4918.3  857.55  4925.3  853.30  4930.8  853.97  4941.9  849.92
  4948.4  845.06  4953.9  848.23  4962.2  844.85  4977.1  842.36  4997.2  833.27
  4998.0  832.77  5002.7  833.27  5003.2  833.53  5016.9  842.18  5022.5  846.68
  5028.6  847.52  5039.2  842.48  5044.8  842.30  5133.9  842.71  5262.0  845.08
  5328.9  848.32  5379.0  852.41  5395.7  860.15  5401.3  859.66  5409.6  861.22
#Mann=5,-1,0
  4593.2    0.05       0  4941.9    0.12       0  4997.2    0.07       0
  5002.7    0.12       0  5003.2    0.05       0
Bank Sta=4997.2,5002.7
Exp/Cntr=0.3,0.1

Type RM Length L Ch R = 1,1872,438,438,438
BEGIN DESCRIPTION:
MDW T 009 4.0
END DESCRIPTION:
XS GIS Cut Line= 3
      2276179.02      7110210.00      2275929.00      7110210.00
      2275533.76      7110220.22
#Sta/Elev= 30
  4749.6  860.10  4769.6  857.74  4789.6  852.76  4799.6  849.36  4809.6  846.96
  4829.6  845.35  4839.6  845.18  4859.6  846.20  4879.6  841.77  4899.6  840.78
  4929.6  839.83  4939.6  840.57  4969.6  840.35  4979.6  836.80  4986.8  832.83
  4987.7  832.33  4991.6  832.33  4992.4  832.83  5002.1  832.99  5019.6  835.09
  5049.6  835.91  5058.3  837.55  5069.6  840.47  5089.7  844.38  5119.7  847.76
  5193.9  851.32  5199.7  852.57  5249.7  853.63  5349.7  857.46  5395.0  858.19
#Mann=4,-1,0
  4749.6    0.12       0  4986.8    0.07       0  4992.4    0.12       0
  5058.3    0.05       0
Bank Sta=4986.8,4992.4
Exp/Cntr=0.3,0.1

Type RM Length L Ch R = 1,1434,461,461,461
BEGIN DESCRIPTION:
MDW T 009 3.0
END DESCRIPTION:
XS GIS Cut Line= 3
      2276267.02      7110050.98      2276005.29      7109833.18
      2275738.35      7109639.50
#Sta/Elev= 30
  4659.5  860.14  4680.5  858.82  4701.3  853.15  4709.0  851.99  4722.1  847.44
  4740.2  844.74  4793.7  840.63  4800.2  841.56  4828.9  839.80  4836.7  840.71
  4857.5  839.17  4886.2  839.17  4892.7  838.01  4900.5  838.72  4914.8  837.64
  4956.5  836.86  4978.6  834.61  4990.0  830.71  4991.0  830.21  4995.8  830.71
  5007.8  830.73  5028.6  834.94  5057.2  837.70  5078.9  843.32  5085.1  846.01
  5120.6  849.95  5156.6  851.99  5200.3  853.20  5279.6  852.48  5329.8  853.13
#Mann=5,-1,0
  4659.5    0.05       0  4740.2    0.12       0  4990.0    0.07       0
  4995.8    0.12       0  5156.6    0.05       0
Bank Sta=4990,4995.8
Exp/Cntr=0.3,0.1

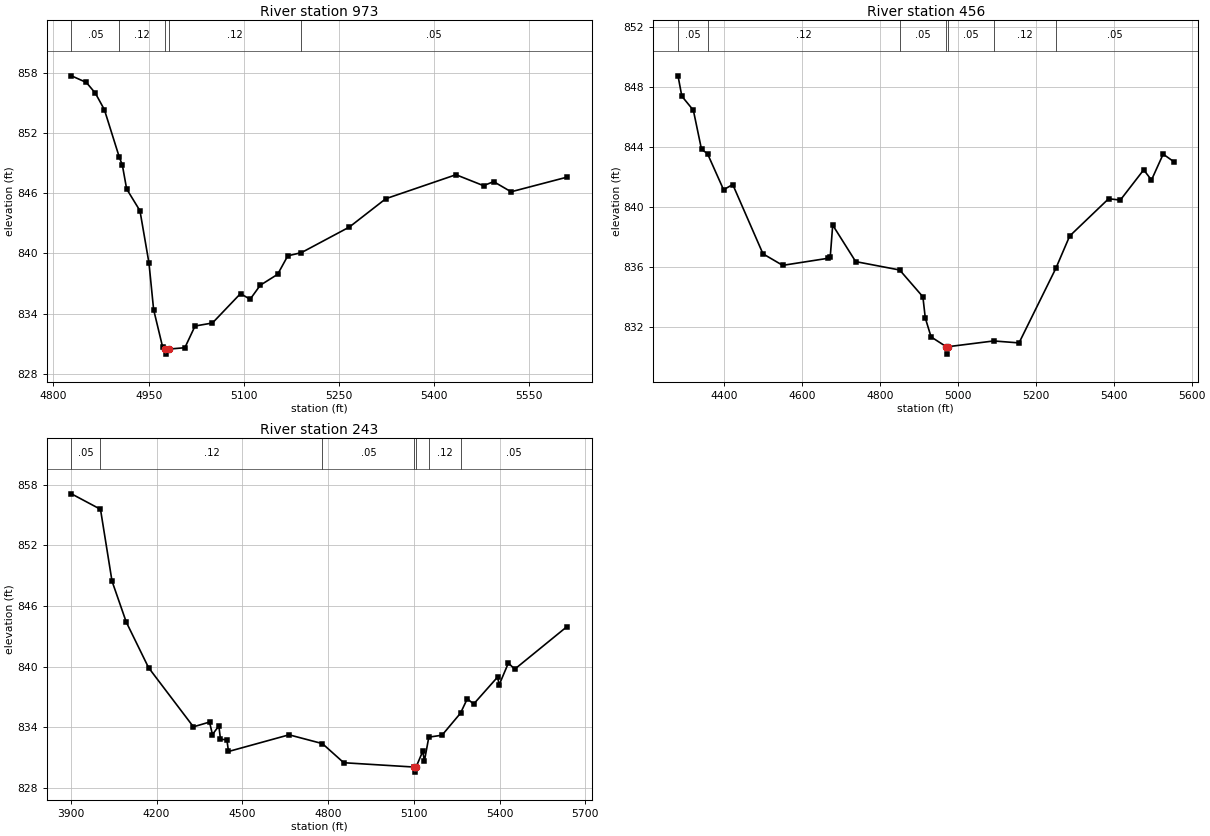
Type RM Length L Ch R = 1,973,517,517,517
BEGIN DESCRIPTION:
MDW T 009 2.0
END DESCRIPTION:
XS GIS Cut Line= 3
      2276508.28      7109723.67      2276381.77      7109607.57
      2275849.46      7109310.50
#Sta/Elev= 30
  4828.3  857.68  4851.8  857.02  4866.0  855.95  4880.2  854.31  4903.8  849.56
  4908.5  848.80  4915.3  846.41  4936.3  844.24  4950.5  839.03  4957.8  834.40
  4972.0  830.67  4975.9  830.46  4976.9  829.96  4981.7  830.46  5007.1  830.60
  5023.1  832.76  5050.5  833.06  5094.8  835.99  5109.9  835.42  5125.9  836.82
  5153.3  837.91  5169.3  839.75  5190.8  840.07  5266.4  842.62  5323.8  845.44
  5434.4  847.83  5477.8  846.74  5493.8  847.14  5521.3  846.13  5609.6  847.59
#Mann=5,-1,0
  4828.3    0.05       0  4903.8    0.12       0  4975.9    0.07       0
  4981.7    0.12       0  5190.8    0.05       0
Bank Sta=4975.9,4981.7
Exp/Cntr=0.3,0.1

Type RM Length L Ch R = 1,456,213,213,213
BEGIN DESCRIPTION:
MDW T 009 1.0
END DESCRIPTION:
XS GIS Cut Line= 3
      2277134.15      7109589.13      2276545.90      7109176.57
      2275992.00      7109177.68
#Sta/Elev= 30
  4281.5  848.77  4291.3  847.41  4320.9  846.47  4341.8  843.86  4357.2  843.57
  4398.5  841.16  4422.0  841.51  4499.6  836.88  4550.2  836.11  4666.1  836.58
  4672.2  836.65  4678.6  838.80  4737.6  836.36  4850.5  835.80  4910.1  834.01
  4916.2  832.60  4931.1  831.33  4969.9  830.68  4970.9  830.18  4975.8  830.68
  5091.8  831.06  5156.9  830.93  5251.4  835.91  5286.9  838.07  5386.9  840.56
  5416.9  840.47  5476.9  842.49  5496.9  841.81  5526.9  843.54  5553.9  843.04
#Mann=7,-1,0
  4281.5    0.05       0  4357.2    0.12       0  4850.5    0.05       0
  4969.9   0.033       0  4975.8    0.05       0  5091.8    0.12       0
  5251.4    0.05       0
Bank Sta=4969.9,4975.8
Exp/Cntr=0.3,0.1

Type RM Length L Ch R = 1,243,0,0,0
BEGIN DESCRIPTION:
MDW T 009 0.5
END DESCRIPTION:
XS GIS Cut Line= 4
      2277342.52      7109634.52      2277052.58      7109254.29
      2276403.54      7108931.78      2275923.14      7109158.44
#Sta/Elev= 30
  3902.4  857.08  4004.0  855.55  4044.3  848.45  4094.1  844.40  4172.2  839.89
  4329.1  834.04  4385.4  834.51  4395.7  833.28  4418.1  834.13  4423.8  832.81
  4446.2  832.76  4451.8  831.60  4663.7  833.25  4780.3  832.38  4855.0  830.49
  5102.1  830.06  5103.1  829.56  5108.0  830.06  5131.6  831.63  5137.1  830.64
  5152.6  833.02  5198.8  833.21  5263.5  835.39  5287.3  836.82  5309.4  836.29
  5393.2  838.96  5398.7  838.19  5431.0  840.35  5453.1  839.74  5636.5  843.96
#Mann=7,-1,0
  3902.4    0.05       0  4004.0    0.12       0  4780.3    0.05       0
  5102.1   0.033       0  5108.0    0.05       0  5152.6    0.12       0
  5263.5    0.05       0
Bank Sta=5102.1,5108
Exp/Cntr=0.3,0.1

Chan Stop Cuts=-1