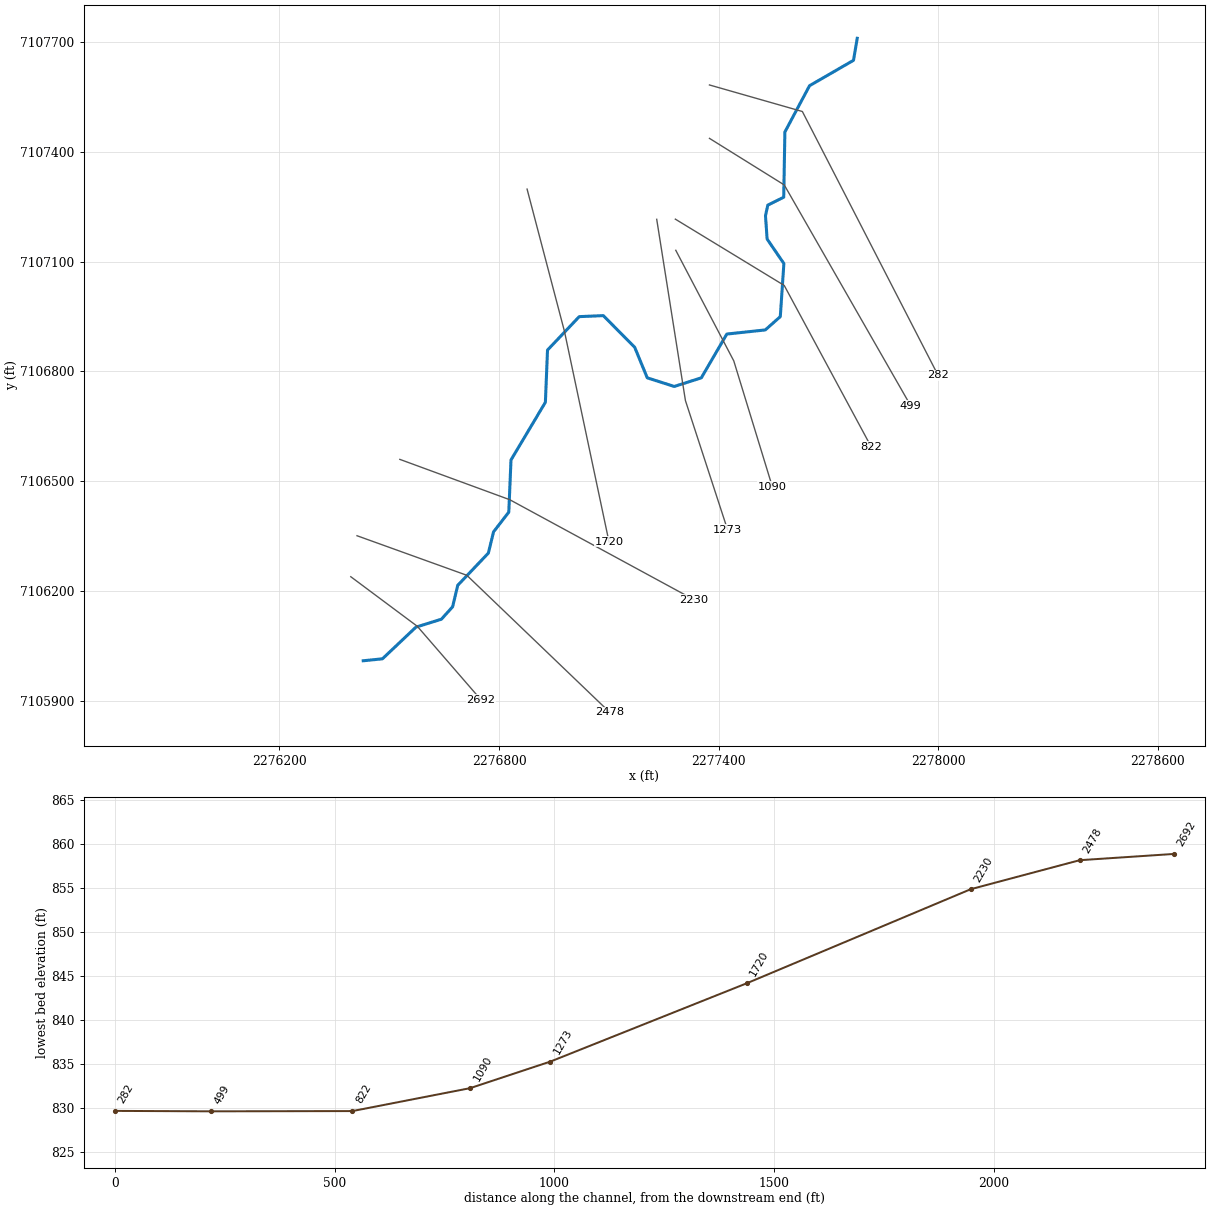
--- MDW T 010.prj (project) ---

Proj Title=MDW T 010 Base Level Engineering
Current Plan=p01
Default Exp/Contr=0.3,0.1
English Units
Geom File=g01
Flow File=f01
Plan File=p01
BEGIN DESCRIPTION:
MDW T 010
END DESCRIPTION:

--- MDW T 010.p01 (plan) ---

Plan Title=Multiple Run
Short Identifier=Multiple
Geom File=g01
Flow File=f01
Subcritical Flow
K Sum by GR= 0
Std Step Tol= 0.01
Critical Tol= 0.01
Num of Std Step Trials= 20
Max Error Tol= 0.3
Flow Tol Ratio= 0.001
Split Flow NTrial= 30
Split Flow Tol= 0.02
Split Flow Ratio= 0.02
Log Output Level= 0
Friction Slope Method= 1
Unsteady Friction Slope Method= 2
Unsteady Bridges Friction Slope Method= 1
Parabolic Critical Depth
Global Vel Dist=  1 , 1 , 1
Global Log Level= 0
CheckData=True
Encroach Param= -1, 0, 0, 0
BEGIN DESCRIPTION:
Multiple Run
END DESCRIPTION:

--- MDW T 010.f01 (steady flow) ---

Flow Title=Multiple
Number of Profiles=7
Profile Names=10-year,25-year,50-year,1pct_min,100-year,1pct_plu,500-year
River Rch & RM= MDW T 010,Reach-1,2692
     262     344     408     242     482     963     674
Boundary for River Rch & Prof#=MDW T 010,Reach-1,1
Up Type=0
Dn Type=3
Dn Slope=0.005
Boundary for River Rch & Prof#=MDW T 010,Reach-1,2
Up Type=0
Dn Type=3
Dn Slope=0.005
Boundary for River Rch & Prof#=MDW T 010,Reach-1,3
Up Type=0
Dn Type=3
Dn Slope=0.005
Boundary for River Rch & Prof#=MDW T 010,Reach-1,4
Up Type=0
Dn Type=3
Dn Slope=0.005
Boundary for River Rch & Prof#=MDW T 010,Reach-1,5
Up Type=0
Dn Type=3
Dn Slope=0.005
Boundary for River Rch & Prof#=MDW T 010,Reach-1,6
Up Type=0
Dn Type=3
Dn Slope=0.005
Boundary for River Rch & Prof#=MDW T 010,Reach-1,7
Up Type=0
Dn Type=3
Dn Slope=0.005

--- MDW T 010.g01 (geometry) ---

Geom Title=Existing Conditions

River Reach=MDW T 010,Reach-1
Reach XY= 30
      2276429.00      7106010.00      2276481.51      7106015.33
      2276572.97      7106101.83      2276642.56      7106123.49
      2276673.25      7106157.46      2276687.18      7106216.02
      2276770.84      7106303.95      2276785.14      7106362.17
      2276826.75      7106415.93      2276832.76      7106558.44
      2276926.75      7106715.93      2276932.54      7106858.55
      2277019.30      7106949.84      2277085.06      7106952.55
      2277170.84      7106866.05      2277205.11      7106782.69
      2277279.00      7106759.10      2277352.89      7106782.69
      2277422.55      7106902.25      2277527.75      7106913.51
      2277568.68      7106949.83      2277578.49      7107094.78
      2277532.68      7107161.67      2277528.23      7107225.37
      2277534.55      7107254.35      2277578.04      7107275.96
      2277581.24      7107454.07      2277648.62      7107580.48
      2277768.67      7107649.75      2277779.00      7107710.00

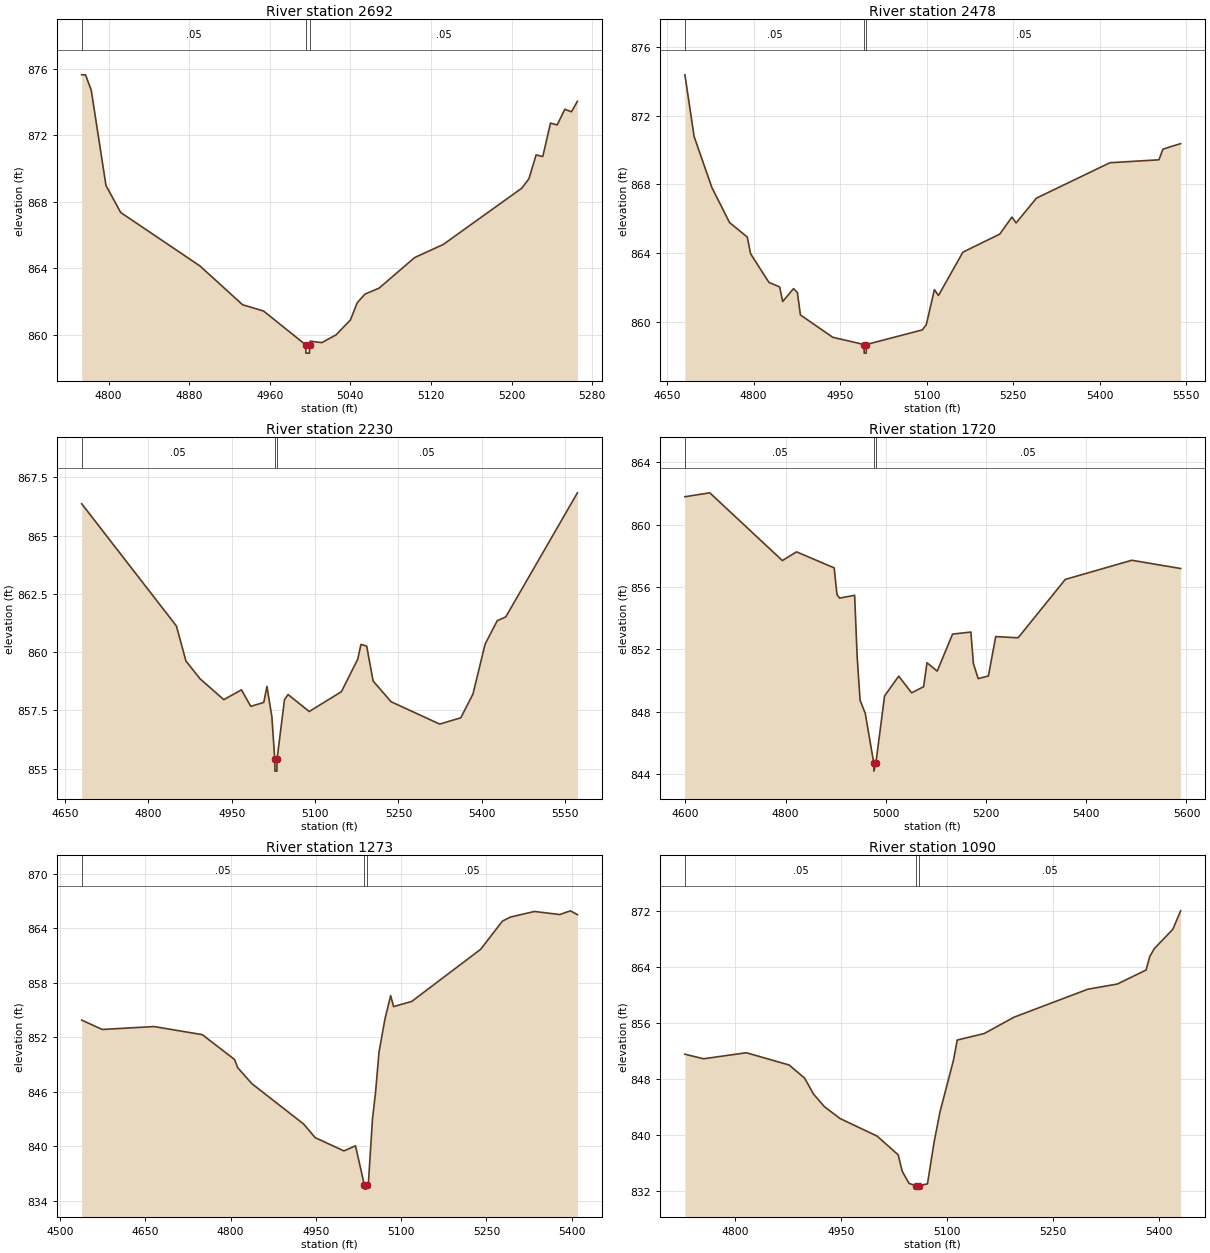
Type RM Length L Ch R = 1,2692,214,214,214
BEGIN DESCRIPTION:
MDW T 010 9.0
END DESCRIPTION:
XS GIS Cut Line= 3
      2276394.93      7106239.55      2276576.74      7106104.13
      2276750.52      7105903.67
#Sta/Elev= 30
  4773.3  875.62  4777.1  875.62  4782.8  874.69  4797.4  868.97  4812.0  867.35
  4890.6  864.14  4932.9  861.81  4953.8  861.43  4995.6  859.40  4995.8  858.90
  4999.3  858.90  4999.6  859.40  5000.0  859.62  5011.6  859.53  5025.8  860.00
  5040.1  860.90  5046.7  861.92  5054.3  862.44  5068.6  862.81  5103.7  864.64
  5132.2  865.43  5210.1  868.81  5217.2  869.38  5224.3  870.81  5230.9  870.71
  5238.6  872.72  5245.2  872.61  5252.8  873.55  5259.4  873.40  5265.3  874.03
#Mann=3,-1,0
  4773.3    0.05       0  4995.6   0.033       0  4999.6    0.05       0
Bank Sta=4995.6,4999.6
Exp/Cntr=0.3,0.1

Type RM Length L Ch R = 1,2478,248,248,248
BEGIN DESCRIPTION:
MDW T 010 8.0
END DESCRIPTION:
XS GIS Cut Line= 3
      2276411.91      7106351.50      2276712.05      7106243.45
      2277101.98      7105869.74
#Sta/Elev= 30
  4681.0  874.37  4697.0  870.78  4727.7  867.82  4758.4  865.78  4789.1  864.94
  4794.8  863.97  4826.7  862.30  4845.2  862.04  4850.5  861.19  4869.2  861.94
  4875.9  861.72  4881.2  860.41  4937.3  859.11  4991.4  858.69  4991.7  858.19
  4995.2  858.19  4995.4  858.69  5092.4  859.54  5099.3  859.84  5113.4  861.88
  5120.4  861.54  5162.8  864.06  5226.7  865.11  5247.7  866.10  5255.0  865.76
  5290.2  867.20  5417.6  869.26  5502.5  869.43  5509.4  870.05  5540.1  870.37
#Mann=3,-1,0
  4681.0    0.05       0  4991.4   0.033       0  4995.4    0.05       0
Bank Sta=4991.4,4995.4
Exp/Cntr=0.3,0.1

Type RM Length L Ch R = 1,2230,510,510,510
BEGIN DESCRIPTION:
MDW T 010 7.0
END DESCRIPTION:
XS GIS Cut Line= 3
      2276528.97      7106560.01      2276829.41      7106449.83
      2277332.40      7106177.06
#Sta/Elev= 30
  4680.0  866.37  4850.5  861.12  4867.6  859.62  4892.8  858.86  4935.7  857.96
  4967.6  858.38  4984.3  857.67  5007.7  857.84  5013.4  858.53  5022.3  857.22
  5027.5  855.39  5027.8  854.89  5031.3  854.89  5031.5  855.39  5045.0  857.96
  5051.4  858.18  5089.5  857.45  5147.4  858.30  5176.9  859.70  5182.6  860.33
  5192.9  860.26  5204.5  858.76  5236.8  857.87  5324.3  856.91  5362.3  857.18
  5384.2  858.20  5406.0  860.34  5427.9  861.35  5443.2  861.51  5572.2  866.84
#Mann=3,-1,0
  4680.0    0.05       0  5027.5   0.033       0  5031.5    0.05       0
Bank Sta=5027.5,5031.5
Exp/Cntr=0.3,0.1

Type RM Length L Ch R = 1,1720,447,447,447
BEGIN DESCRIPTION:
MDW T 010 6.0
END DESCRIPTION:
XS GIS Cut Line= 3
      2276876.72      7107298.10      2276978.67      7106910.38
      2277100.64      7106334.76
#Sta/Elev= 30
  4599.1  861.80  4648.8  862.05  4793.6  857.70  4821.9  858.26  4897.0  857.23
  4902.6  855.52  4907.8  855.29  4937.8  855.47  4942.9  851.51  4948.7  848.73
  4959.0  847.89  4976.1  844.68  4976.3  844.18  4980.1  844.68  4997.6  849.01
  5025.8  850.28  5051.5  849.21  5075.5  849.60  5082.2  851.14  5102.6  850.60
  5133.3  852.98  5169.8  853.11  5174.9  851.08  5184.4  850.12  5204.8  850.29
  5219.4  852.82  5264.0  852.74  5358.2  856.49  5491.0  857.72  5588.4  857.19
#Mann=3,-1,0
  4599.1    0.05       0  4976.1   0.033       0  4980.1    0.05       0
Bank Sta=4976.1,4980.1
Exp/Cntr=0.3,0.1

Type RM Length L Ch R = 1,1273,183,183,183
BEGIN DESCRIPTION:
MDW T 010 5.0
END DESCRIPTION:
XS GIS Cut Line= 3
      2277230.98      7107215.63      2277309.44      7106720.61
      2277424.49      7106368.22
#Sta/Elev= 30
  4538.1  853.89  4574.2  852.86  4665.3  853.18  4750.2  852.29  4807.0  849.55
  4812.5  848.65  4837.4  846.89  4928.5  842.44  4948.8  840.94  4999.4  839.48
  5019.7  840.04  5035.1  835.77  5035.3  835.27  5038.8  835.27  5039.1  835.77
  5042.2  835.77  5049.6  843.04  5054.9  845.90  5061.0  850.35  5071.5  854.02
  5081.5  856.59  5086.7  855.38  5118.6  855.95  5239.8  861.69  5278.1  864.80
  5292.4  865.25  5334.5  865.86  5379.0  865.52  5397.6  865.93  5410.0  865.51
#Mann=3,-1,0
  4538.1    0.05       0  5035.1   0.033       0  5039.1    0.05       0
Bank Sta=5035.1,5039.1
Exp/Cntr=0.3,0.1

Type RM Length L Ch R = 1,1090,268,268,268
BEGIN DESCRIPTION:
MDW T 010 4.0
END DESCRIPTION:
XS GIS Cut Line= 3
      2277283.07      7107130.99      2277441.56      7106828.95
      2277547.20      7106484.48
#Sta/Elev= 30
  4729.0  851.50  4755.4  850.85  4815.9  851.71  4876.5  849.96  4898.5  848.07
  4910.8  845.83  4926.2  844.03  4948.3  842.33  5001.1  839.80  5030.8  837.13
  5036.5  834.78  5046.3  833.04  5056.5  832.74  5056.8  832.24  5060.3  832.24
  5060.5  832.74  5072.2  832.99  5081.6  838.95  5089.9  843.25  5109.1  850.69
  5114.3  853.52  5152.7  854.46  5194.5  856.78  5299.1  860.78  5340.9  861.52
  5381.5  863.52  5386.7  865.44  5393.2  866.58  5419.4  869.34  5430.4  871.97
#Mann=3,-1,0
  4729.0    0.05       0  5056.5   0.033       0  5060.5    0.05       0
Bank Sta=5056.5,5060.5
Exp/Cntr=0.3,0.1

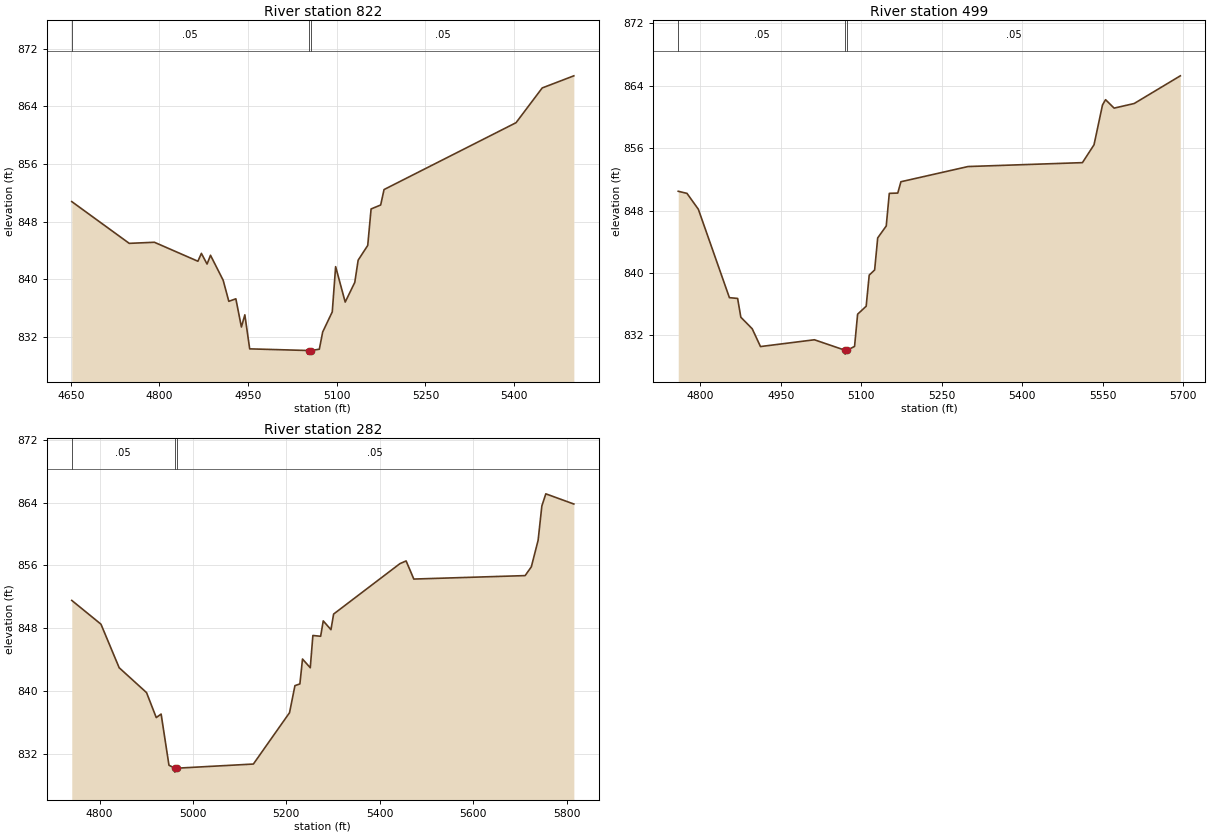
Type RM Length L Ch R = 1,822,323,323,323
BEGIN DESCRIPTION:
MDW T 010 3.0
END DESCRIPTION:
XS GIS Cut Line= 3
      2277281.88      7107216.05      2277579.42      7107034.99
      2277817.28      7106593.94
#Sta/Elev= 30
  4651.7  850.78  4748.9  844.99  4791.5  845.14  4865.1  842.51  4871.0  843.60
  4880.6  842.12  4886.4  843.34  4907.8  839.88  4917.4  836.95  4929.3  837.30
  4938.7  833.39  4944.5  835.08  4952.7  830.36  5052.3  830.13  5052.5  829.63
  5056.3  830.13  5070.5  830.31  5076.2  832.70  5092.4  835.49  5098.1  841.76
  5114.3  836.85  5130.5  839.58  5136.2  842.66  5152.4  844.70  5158.1  849.76
  5174.3  850.31  5180.0  852.45  5403.3  861.72  5447.6  866.54  5501.1  868.22
#Mann=3,-1,0
  4651.7    0.05       0  5052.3   0.033       0  5056.3    0.05       0
Bank Sta=5052.3,5056.3
Exp/Cntr=0.3,0.1

Type RM Length L Ch R = 1,499,217,217,217
BEGIN DESCRIPTION:
MDW T 010 2.0
END DESCRIPTION:
XS GIS Cut Line= 3
      2277375.14      7107436.66      2277579.50      7107309.49
      2277924.76      7106707.01
#Sta/Elev= 30
  4759.3  850.48  4775.6  850.21  4796.8  848.17  4854.6  836.84  4869.9  836.74
  4875.9  834.33  4897.1  832.85  4912.5  830.57  5012.9  831.44  5069.9  830.10
  5070.1  829.60  5073.9  830.10  5087.7  830.59  5093.4  834.72  5109.3  835.74
  5115.0  839.73  5125.1  840.39  5130.8  844.50  5146.7  846.03  5152.4  850.21
  5168.2  850.25  5174.0  851.70  5299.1  853.65  5512.1  854.15  5533.7  856.44
  5549.5  861.55  5555.2  862.22  5571.1  861.14  5608.5  861.73  5694.4  865.28
#Mann=3,-1,0
  4759.3    0.05       0  5069.9   0.033       0  5073.9    0.05       0
Bank Sta=5069.9,5073.9
Exp/Cntr=0.3,0.1

Type RM Length L Ch R = 1,282,0,0,0
BEGIN DESCRIPTION:
MDW T 010 1.0
END DESCRIPTION:
XS GIS Cut Line= 3
      2277375.09      7107582.51      2277629.00      7107510.00
      2278000.14      7106789.08
#Sta/Elev= 30
  4740.6  851.53  4803.1  848.50  4842.1  842.95  4900.7  839.78  4921.5  836.60
  4931.9  837.05  4948.7  830.53  4961.1  830.15  4961.3  829.65  4965.1  830.15
  5129.4  830.68  5206.8  837.22  5218.4  840.67  5229.0  840.89  5234.6  844.06
  5251.2  842.95  5256.8  847.06  5273.4  846.96  5279.0  848.92  5295.5  847.80
  5301.2  849.79  5443.3  856.22  5456.4  856.56  5472.9  854.25  5711.2  854.69
  5724.5  855.81  5739.0  859.19  5747.0  863.56  5755.5  865.11  5815.5  863.81
#Mann=3,-1,0
  4740.6    0.05       0  4961.1   0.033       0  4965.1    0.05       0
Bank Sta=4961.1,4965.1
Exp/Cntr=0.3,0.1

Chan Stop Cuts=-1