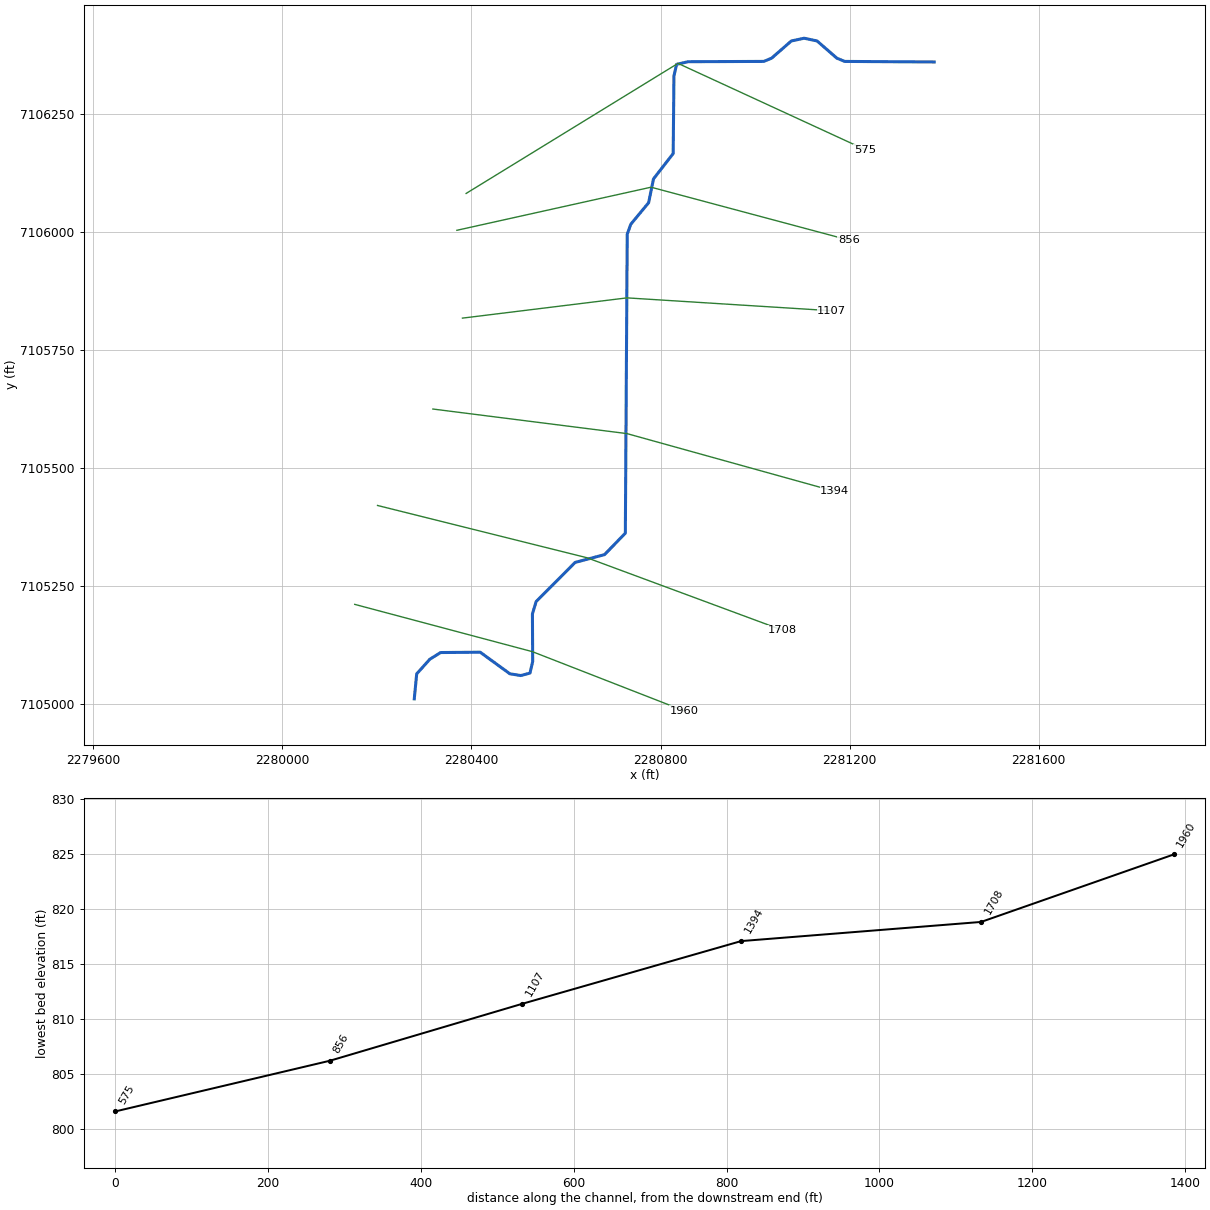
--- MDW T 011.prj (project) ---

Proj Title=MDW T 011 Base Level Engineering
Current Plan=p01
Default Exp/Contr=0.3,0.1
English Units
Geom File=g01
Flow File=f01
Plan File=p01
BEGIN DESCRIPTION:
MDW T 011
END DESCRIPTION:

--- MDW T 011.p01 (plan) ---

Plan Title=Multiple Run
Short Identifier=Multiple
Geom File=g01
Flow File=f01
Subcritical Flow
K Sum by GR= 0
Std Step Tol= 0.01
Critical Tol= 0.01
Num of Std Step Trials= 20
Max Error Tol= 0.3
Flow Tol Ratio= 0.001
Split Flow NTrial= 30
Split Flow Tol= 0.02
Split Flow Ratio= 0.02
Log Output Level= 0
Friction Slope Method= 1
Unsteady Friction Slope Method= 2
Unsteady Bridges Friction Slope Method= 1
Parabolic Critical Depth
Global Vel Dist=  1 , 1 , 1
Global Log Level= 0
CheckData=True
Encroach Param= -1, 0, 0, 0
BEGIN DESCRIPTION:
Multiple Run
END DESCRIPTION:

--- MDW T 011.f01 (steady flow) ---

Flow Title=Multiple
Number of Profiles=7
Profile Names=10-year,25-year,50-year,1pct_min,100-year,1pct_plu,500-year
River Rch & RM= MDW T 011,Reach-1,1960
     261     343     408     242     484     965     679
Boundary for River Rch & Prof#=MDW T 011,Reach-1,1
Up Type=0
Dn Type=3
Dn Slope=0.005
Boundary for River Rch & Prof#=MDW T 011,Reach-1,2
Up Type=0
Dn Type=3
Dn Slope=0.005
Boundary for River Rch & Prof#=MDW T 011,Reach-1,3
Up Type=0
Dn Type=3
Dn Slope=0.005
Boundary for River Rch & Prof#=MDW T 011,Reach-1,4
Up Type=0
Dn Type=3
Dn Slope=0.005
Boundary for River Rch & Prof#=MDW T 011,Reach-1,5
Up Type=0
Dn Type=3
Dn Slope=0.005
Boundary for River Rch & Prof#=MDW T 011,Reach-1,6
Up Type=0
Dn Type=3
Dn Slope=0.005
Boundary for River Rch & Prof#=MDW T 011,Reach-1,7
Up Type=0
Dn Type=3
Dn Slope=0.005

--- MDW T 011.g01 (geometry) ---

Geom Title=Existing Conditions

River Reach=MDW T 011,Reach-1
Reach XY= 30
      2280279.00      7105010.00      2280284.13      7105062.95
      2280311.87      7105093.91      2280334.73      7105108.17
      2280418.47      7105108.87      2280481.19      7105063.16
      2280504.33      7105059.38      2280523.82      7105064.60
      2280529.51      7105089.23      2280528.98      7105189.99
      2280536.81      7105216.20      2280619.32      7105299.22
      2280681.57      7105315.74      2280725.55      7105361.25
      2280729.51      7105994.79      2280737.09      7106016.08
      2280774.81      7106061.74      2280785.12      7106112.18
      2280826.76      7106165.93      2280828.39      7106330.61
      2280834.00      7106355.00      2280858.39      7106360.61
      2281018.50      7106361.24      2281035.07      7106368.19
      2281076.82      7106404.62      2281104.00      7106410.40
      2281131.18      7106404.62      2281172.92      7106368.19
      2281189.49      7106361.23      2281379.00      7106360.00

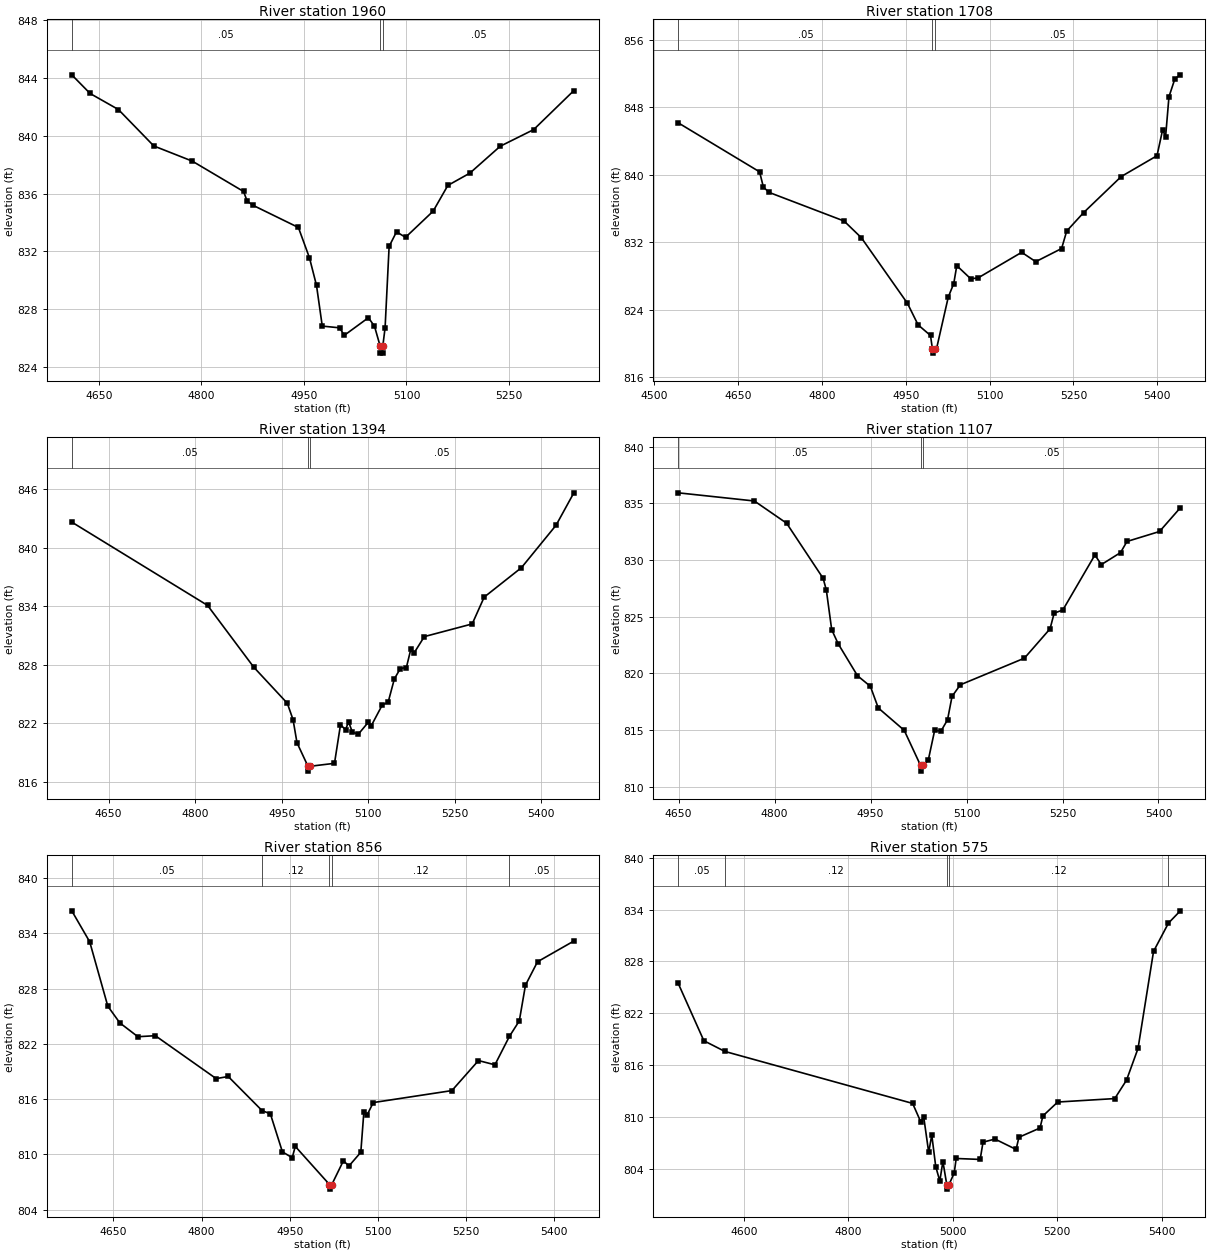
Type RM Length L Ch R = 1,1960,252,252,252
BEGIN DESCRIPTION:
MDW T 011 6.0
END DESCRIPTION:
XS GIS Cut Line= 3
      2280153.07      7105210.29      2280529.00      7105110.00
      2280850.66      7104984.37
#Sta/Elev= 30
  4610.4  844.22  4637.2  842.93  4678.6  841.82  4730.4  839.30  4786.7  838.25
  4861.7  836.15  4866.9  835.49  4875.3  835.20  4941.9  833.66  4958.1  831.56
  4968.4  829.65  4976.8  826.84  5002.2  826.72  5009.0  826.20  5044.3  827.42
  5053.2  826.83  5061.4  825.47  5061.6  824.97  5065.1  824.97  5065.4  825.47
  5068.7  826.72  5074.6  832.35  5085.4  833.36  5098.6  832.98  5139.0  834.79
  5160.5  836.57  5192.7  837.42  5237.1  839.28  5286.0  840.43  5344.8  843.13
#Mann=3,-1,0
  4610.4    0.05       0  5061.4   0.033       0  5065.4    0.05       0
Bank Sta=5061.4,5065.4
Exp/Cntr=0.3,0.1

Type RM Length L Ch R = 1,1708,314,314,314
BEGIN DESCRIPTION:
MDW T 011 5.0
END DESCRIPTION:
XS GIS Cut Line= 3
      2280201.26      7105419.93      2280644.42      7105309.10
      2281058.05      7105155.59
#Sta/Elev= 30
  4543.2  846.14  4688.7  840.33  4695.5  838.52  4705.8  837.89  4839.8  834.50
  4870.7  832.52  4953.2  824.74  4972.2  822.19  4994.4  820.93  4997.8  819.34
  4998.0  818.84  5001.8  819.34  5005.1  819.34  5026.2  825.49  5036.0  827.09
  5041.4  829.21  5066.4  827.65  5079.6  827.76  5157.5  830.79  5182.6  829.68
  5228.9  831.24  5238.0  833.31  5268.3  835.50  5335.5  839.77  5399.5  842.24
  5409.5  845.29  5414.9  844.51  5420.9  849.23  5431.5  851.36  5441.2  851.83
#Mann=3,-1,0
  4543.2    0.05       0  4997.8   0.033       0  5001.8    0.05       0
Bank Sta=4997.8,5001.8
Exp/Cntr=0.3,0.1

Type RM Length L Ch R = 1,1394,287,287,287
BEGIN DESCRIPTION:
MDW T 011 4.0
END DESCRIPTION:
XS GIS Cut Line= 3
      2280318.42      7105624.36      2280729.03      7105572.27
      2281168.71      7105449.87
#Sta/Elev= 30
  4586.1  842.63  4821.5  834.09  4901.5  827.76  4959.7  824.06  4969.7  822.37
  4976.5  820.01  4995.5  817.60  4995.7  817.10  4999.5  817.60  5041.5  817.90
  5051.9  821.85  5060.7  821.35  5065.9  822.16  5072.6  821.08  5083.0  820.90
  5100.1  822.11  5105.3  821.76  5124.5  823.90  5134.4  824.14  5145.3  826.56
  5155.7  827.62  5166.1  827.72  5173.8  829.59  5178.9  829.16  5197.2  830.89
  5280.2  832.19  5301.0  834.94  5365.6  837.96  5425.6  842.31  5456.4  845.63
#Mann=3,-1,0
  4586.1    0.05       0  4995.5   0.033       0  4999.5    0.05       0
Bank Sta=4995.5,4999.5
Exp/Cntr=0.3,0.1

Type RM Length L Ch R = 1,1107,251,251,251
BEGIN DESCRIPTION:
MDW T 011 3.0
END DESCRIPTION:
XS GIS Cut Line= 3
      2280380.92      7105817.06      2280729.00      7105860.00
      2281162.22      7105832.69
#Sta/Elev= 30
  4649.3  835.93  4768.3  835.21  4818.7  833.25  4875.8  828.39  4880.8  827.35
  4889.2  823.86  4899.3  822.62  4929.5  819.80  4949.6  818.87  4962.0  816.96
  5002.5  814.99  5028.1  811.89  5028.3  811.39  5032.1  811.89  5040.1  812.35
  5050.1  814.98  5060.1  814.93  5070.2  815.91  5077.3  817.98  5090.2  819.00
  5190.4  821.35  5230.5  823.94  5236.9  825.32  5250.5  825.60  5300.6  830.45
  5310.6  829.60  5340.7  830.66  5350.7  831.64  5401.6  832.52  5434.1  834.61
#Mann=3,-1,0
  4649.3    0.05       0  5028.1   0.033       0  5032.1    0.05       0
Bank Sta=5028.1,5032.1
Exp/Cntr=0.3,0.1

Type RM Length L Ch R = 1,856,281,281,281
BEGIN DESCRIPTION:
MDW T 011 2.0
END DESCRIPTION:
XS GIS Cut Line= 3
      2280369.19      7106003.25      2280779.95      7106094.61
      2281198.68      7105982.42
#Sta/Elev= 30
  4579.2  836.45  4609.7  833.09  4640.5  826.10  4661.0  824.28  4691.7  822.78
  4721.4  822.89  4824.9  818.23  4845.4  818.46  4903.1  814.75  4917.1  814.41
  4937.6  810.28  4954.3  809.64  4959.5  810.87  5017.7  806.73  5018.0  806.23
  5021.7  806.73  5041.4  809.31  5050.8  808.74  5071.0  810.23  5076.2  814.61
  5081.8  814.29  5092.2  815.63  5226.0  816.93  5271.2  820.19  5299.2  819.73
  5323.9  822.82  5340.7  824.50  5351.2  828.38  5371.7  830.92  5433.5  833.17
#Mann=5,-1,0
  4579.2    0.05       0  4903.1    0.12       0  5017.7    0.07       0
  5021.7    0.12       0  5323.9    0.05       0
Bank Sta=5017.7,5021.7
Exp/Cntr=0.3,0.1

Type RM Length L Ch R = 1,575,0,0,0
BEGIN DESCRIPTION:
MDW T 011 1.0
END DESCRIPTION:
XS GIS Cut Line= 3
      2280388.73      7106081.37      2280836.91      7106357.09
      2281232.57      7106174.40
#Sta/Elev= 30
  4473.8  825.45  4522.9  818.81  4563.2  817.57  4922.9  811.55  4938.3  809.44
  4944.2  809.96  4953.7  805.88  4959.6  807.89  4967.2  804.22  4975.0  802.56
  4980.9  804.82  4988.4  802.12  4988.7  801.62  4992.4  802.12  5002.5  803.48
  5006.4  805.17  5052.3  805.06  5057.8  807.06  5080.7  807.42  5121.1  806.22
  5126.6  807.63  5167.0  808.70  5172.5  810.10  5200.9  811.71  5310.2  812.11
  5332.7  814.24  5354.8  817.92  5384.5  829.16  5413.1  832.44  5435.8  833.86
#Mann=5,-1,0
  4473.8    0.05       0  4563.2    0.12       0  4988.4    0.07       0
  4992.4    0.12       0  5413.1    0.05       0
Bank Sta=4988.4,4992.4
Exp/Cntr=0.3,0.1

Chan Stop Cuts=-1