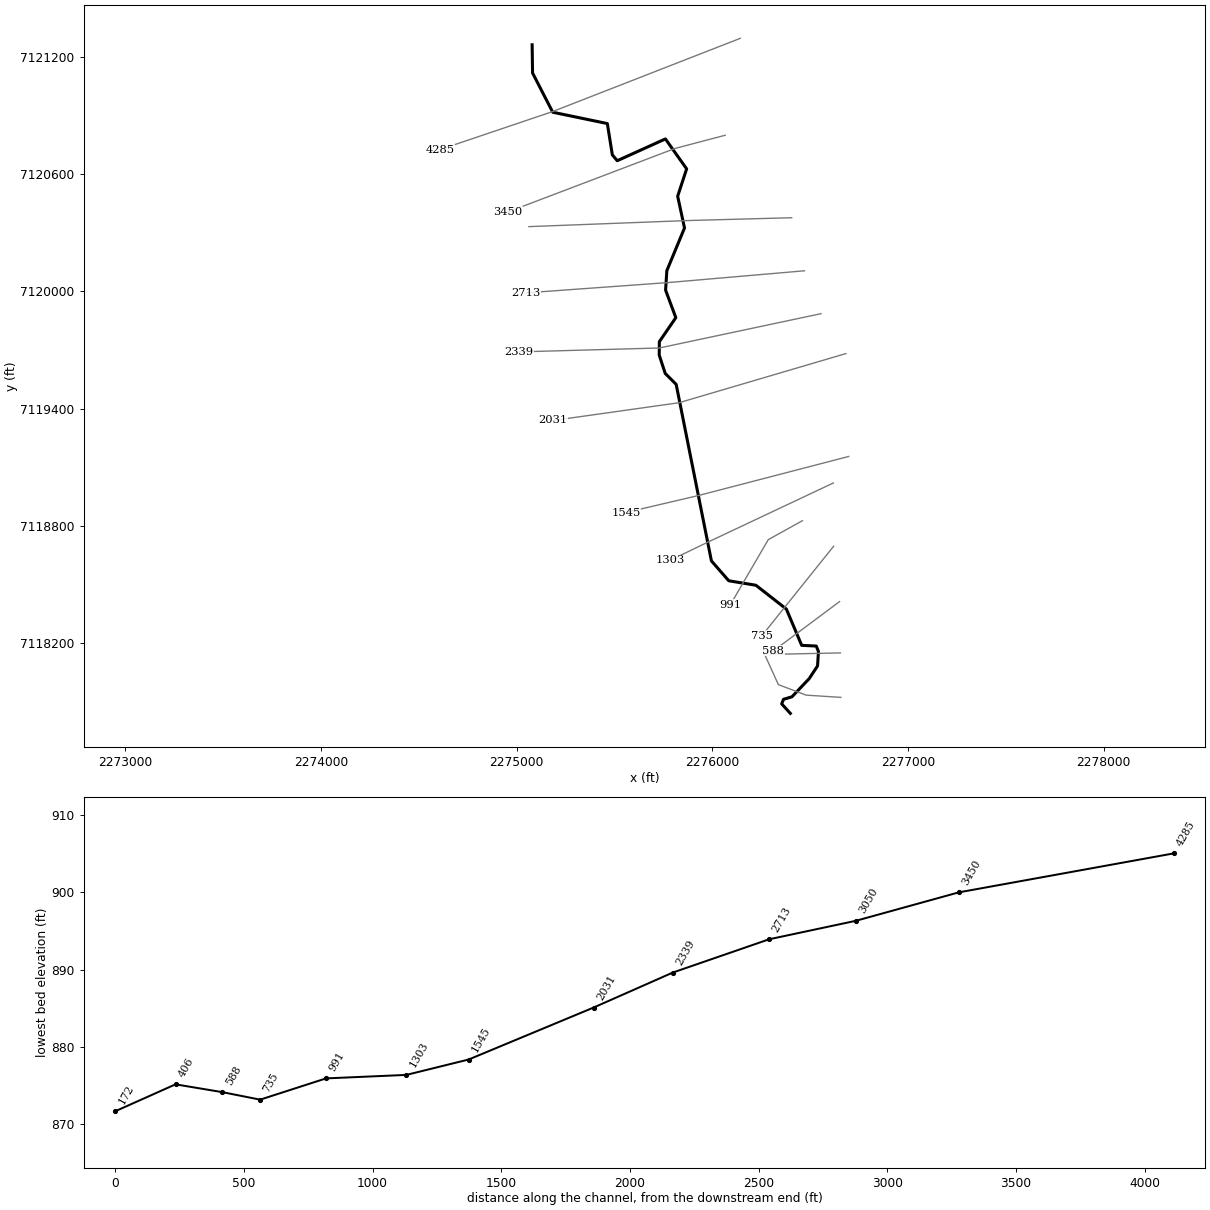
--- MDW T 013.prj (project) ---

Proj Title=MDW T 013 Base Level Engineering
Current Plan=p01
Default Exp/Contr=0.3,0.1
English Units
Geom File=g01
Flow File=f01
Plan File=p01
BEGIN DESCRIPTION:
MDW T 013
END DESCRIPTION:

--- MDW T 013.p01 (plan) ---

Plan Title=Multiple Run
Short Identifier=Multiple
Geom File=g01
Flow File=f01
Subcritical Flow
K Sum by GR= 0
Std Step Tol= 0.01
Critical Tol= 0.01
Num of Std Step Trials= 20
Max Error Tol= 0.3
Flow Tol Ratio= 0.001
Split Flow NTrial= 30
Split Flow Tol= 0.02
Split Flow Ratio= 0.02
Log Output Level= 0
Friction Slope Method= 1
Unsteady Friction Slope Method= 2
Unsteady Bridges Friction Slope Method= 1
Parabolic Critical Depth
Global Vel Dist=  1 , 1 , 1
Global Log Level= 0
CheckData=True
Encroach Param= -1, 0, 0, 0
BEGIN DESCRIPTION:
Multiple Run
END DESCRIPTION:

--- MDW T 013.f01 (steady flow) ---

Flow Title=Multiple
Number of Profiles=7
Profile Names=10-year,25-year,50-year,1pct_min,100-year,1pct_plu,500-year
River Rch & RM= MDW T 013,Reach-1,4285
     614     844    1035     630    1257    2508    1860
Boundary for River Rch & Prof#=MDW T 013,Reach-1,1
Up Type=0
Dn Type=3
Dn Slope=0.005
Boundary for River Rch & Prof#=MDW T 013,Reach-1,2
Up Type=0
Dn Type=3
Dn Slope=0.005
Boundary for River Rch & Prof#=MDW T 013,Reach-1,3
Up Type=0
Dn Type=3
Dn Slope=0.005
Boundary for River Rch & Prof#=MDW T 013,Reach-1,4
Up Type=0
Dn Type=3
Dn Slope=0.005
Boundary for River Rch & Prof#=MDW T 013,Reach-1,5
Up Type=0
Dn Type=3
Dn Slope=0.005
Boundary for River Rch & Prof#=MDW T 013,Reach-1,6
Up Type=0
Dn Type=3
Dn Slope=0.005
Boundary for River Rch & Prof#=MDW T 013,Reach-1,7
Up Type=0
Dn Type=3
Dn Slope=0.005

--- MDW T 013.g01 (geometry) ---

Geom Title=Existing Conditions

River Reach=MDW T 013,Reach-1
Reach XY= 30
      2275079.00      7121260.00      2275081.20      7121115.91
      2275184.44      7120915.25      2275463.45      7120857.36
      2275489.00      7120697.44      2275514.03      7120667.38
      2275760.37      7120778.82      2275868.90      7120625.75
      2275822.92      7120485.93      2275857.96      7120323.50
      2275767.61      7120105.33      2275761.28      7120005.71
      2275813.58      7119865.09      2275729.25      7119742.22
      2275728.71      7119673.58      2275759.53      7119579.75
      2275815.38      7119524.01      2275995.52      7118621.59
      2276084.27      7118520.02      2276222.88      7118497.23
      2276378.72      7118375.36      2276456.93      7118189.97
      2276531.57      7118186.36      2276542.76      7118158.33
      2276538.01      7118084.69      2276494.96      7118019.35
      2276407.20      7117926.95      2276364.08      7117914.09
      2276354.75      7117890.73      2276398.92      7117842.20

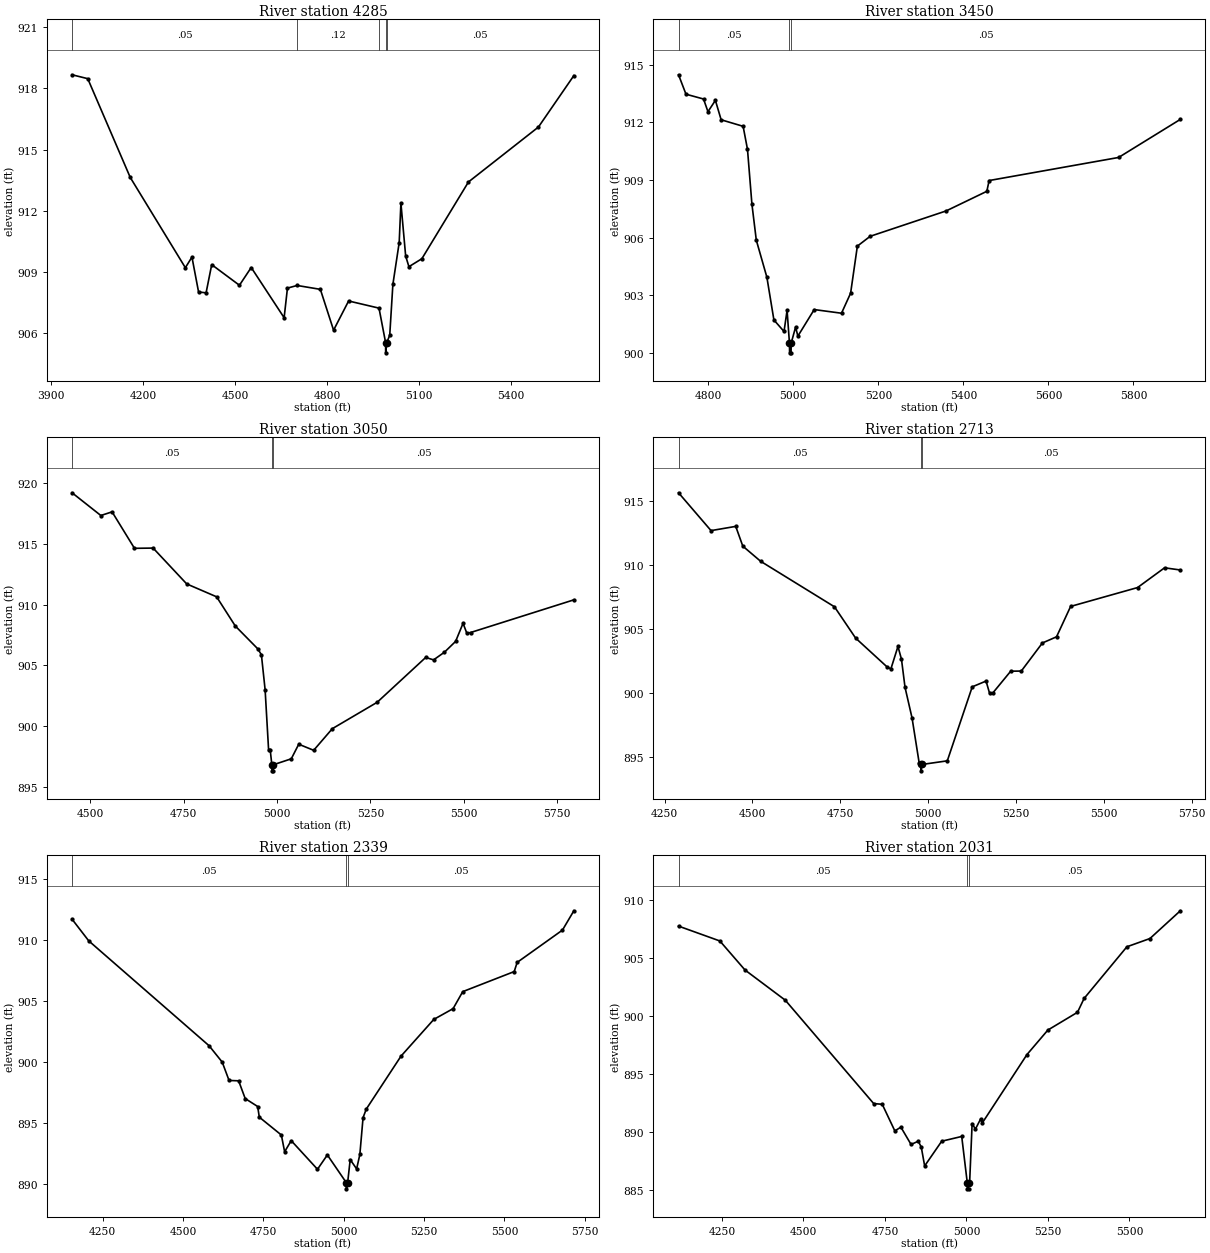
Type RM Length L Ch R = 1,4285,835,835,835
BEGIN DESCRIPTION:
MDW T 013 9.0
END DESCRIPTION:
XS GIS Cut Line= 3
      2276143.02      7121293.04      2275182.38      7120918.15
      2274609.55      7120724.74
#Sta/Elev= 30
  3968.8  918.67  4019.9  918.48  4158.5  913.64  4338.1  909.22  4359.6  909.74
  4381.2  908.03  4405.7  907.99  4424.0  909.37  4514.4  908.36  4552.8  909.23
  4660.1  906.77  4670.9  908.22  4702.4  908.35  4778.2  908.16  4821.3  906.16
  4870.3  907.59  4969.4  907.24  4990.9  905.55  4991.1  905.05  4994.9  905.55
  5004.4  905.92  5014.6  908.40  5035.2  910.45  5040.8  912.38  5056.3  909.79
  5066.9  909.27  5109.1  909.66  5261.0  913.42  5489.1  916.11  5604.6  918.63
#Mann=5,-1,0
  3968.8    0.05       0  4702.4    0.12       0  4969.4    0.05       0
  4990.9   0.033       0  4994.9    0.05       0
Bank Sta=4990.9,4994.9
Exp/Cntr=0.3,0.1

Type RM Length L Ch R = 1,3450,400,400,400
BEGIN DESCRIPTION:
MDW T 013 8.0
END DESCRIPTION:
XS GIS Cut Line= 3
      2276065.88      7120797.57      2275809.22      7120730.09
      2274954.13      7120404.98
#Sta/Elev= 30
  4730.1  914.47  4747.6  913.46  4788.9  913.21  4799.3  912.55  4816.8  913.14
  4830.3  912.13  4882.0  911.79  4892.3  910.59  4902.7  907.74  4913.0  905.87
  4937.9  903.94  4954.4  901.72  4978.2  901.12  4985.4  902.22  4991.0  900.51
  4991.3  900.01  4994.8  900.01  4995.0  900.51  5005.4  901.35  5010.8  900.88
  5049.2  902.26  5113.4  902.07  5134.8  903.11  5150.7  905.56  5180.8  906.07
  5359.5  907.39  5455.2  908.41  5460.6  908.97  5765.1  910.17  5910.3  912.15
#Mann=3,-1,0
  4730.1    0.05       0  4991.0   0.033       0  4995.0    0.05       0
Bank Sta=4991,4995
Exp/Cntr=0.3,0.1

Type RM Length L Ch R = 1,3050,337,337,337
BEGIN DESCRIPTION:
MDW T 013 7.0
END DESCRIPTION:
XS GIS Cut Line= 3
      2276406.12      7120375.99      2275875.22      7120361.57
      2275062.31      7120330.48
#Sta/Elev= 30
  4450.7  919.21  4527.8  917.34  4557.9  917.64  4617.9  914.64  4667.9  914.66
  4757.9  911.71  4838.0  910.65  4888.0  908.25  4948.0  906.38  4958.0  905.89
  4968.0  903.00  4977.4  898.01  4981.8  898.01  4986.0  896.83  4986.3  896.33
  4989.8  896.33  4990.0  896.83  5038.1  897.32  5058.1  898.52  5098.1  898.02
  5148.1  899.80  5268.2  901.97  5398.3  905.66  5419.4  905.46  5448.4  906.09
  5478.4  906.98  5498.4  908.47  5508.4  907.66  5518.4  907.71  5795.3  910.40
#Mann=3,-1,0
  4450.7    0.05       0  4986.0   0.033       0  4990.0    0.05       0
Bank Sta=4986,4990
Exp/Cntr=0.3,0.1

Type RM Length L Ch R = 1,2713,374,374,374
BEGIN DESCRIPTION:
MDW T 013 6.0
END DESCRIPTION:
XS GIS Cut Line= 3
      2276471.18      7120104.72      2275779.21      7120044.91
      2275047.58      7119991.88
#Sta/Elev= 30
  4289.9  915.62  4382.4  912.67  4452.7  913.00  4472.8  911.46  4523.5  910.28
  4733.7  906.73  4793.9  904.29  4884.3  902.02  4894.3  901.89  4914.4  903.64
  4924.4  902.64  4934.5  900.45  4954.5  898.06  4974.6  894.58  4979.5  894.44
  4979.8  893.94  4983.5  894.44  5054.8  894.72  5125.8  900.49  5165.1  900.94
  5175.2  899.98  5185.2  900.04  5235.3  901.71  5265.4  901.72  5325.5  903.91
  5365.7  904.39  5405.8  906.76  5596.3  908.23  5673.1  909.77  5718.0  909.60
#Mann=3,-1,0
  4289.9    0.05       0  4979.5   0.033       0  4983.5    0.05       0
Bank Sta=4979.5,4983.5
Exp/Cntr=0.3,0.1

Type RM Length L Ch R = 1,2339,308,308,308
BEGIN DESCRIPTION:
MDW T 013 5.0
END DESCRIPTION:
XS GIS Cut Line= 3
      2276555.87      7119885.55      2275729.00      7119710.00
      2275013.47      7119690.25
#Sta/Elev= 30
  4154.7  911.68  4206.6  909.91  4580.9  901.34  4621.8  900.00  4643.1  898.50
  4672.9  898.47  4693.3  897.02  4732.1  896.37  4737.2  895.50  4805.8  894.04
  4816.0  892.67  4836.5  893.58  4918.2  891.24  4948.9  892.41  5008.0  890.14
  5008.3  889.64  5012.0  890.14  5020.0  892.03  5040.0  891.27  5050.0  892.45
  5060.0  895.46  5070.0  896.16  5178.1  900.49  5280.1  903.49  5340.1  904.37
  5370.1  905.76  5530.2  907.40  5539.4  908.15  5680.3  910.79  5715.8  912.37
#Mann=3,-1,0
  4154.7    0.05       0  5008.0   0.033       0  5012.0    0.05       0
Bank Sta=5008,5012
Exp/Cntr=0.3,0.1

Type RM Length L Ch R = 1,2031,486,486,486
BEGIN DESCRIPTION:
MDW T 013 4.0
END DESCRIPTION:
XS GIS Cut Line= 3
      2276683.19      7119681.55      2275829.33      7119430.14
      2275186.69      7119339.54
#Sta/Elev= 30
  4117.0  907.73  4243.8  906.45  4320.9  903.95  4444.5  901.35  4715.6  892.45
  4741.8  892.39  4780.4  890.10  4799.0  890.42  4830.2  888.93  4852.3  889.21
  4861.5  888.71  4871.9  887.08  4924.2  889.21  4985.6  889.62  5002.7  885.61
  5002.9  885.11  5006.4  885.11  5006.7  885.61  5009.8  885.61  5017.5  890.73
  5027.6  890.25  5043.3  891.11  5048.4  890.77  5185.7  896.67  5249.8  898.78
  5340.7  900.31  5360.9  901.50  5492.2  905.95  5562.9  906.66  5656.1  909.05
#Mann=3,-1,0
  4117.0    0.05       0  5002.7   0.033       0  5006.7    0.05       0
Bank Sta=5002.7,5006.7
Exp/Cntr=0.3,0.1

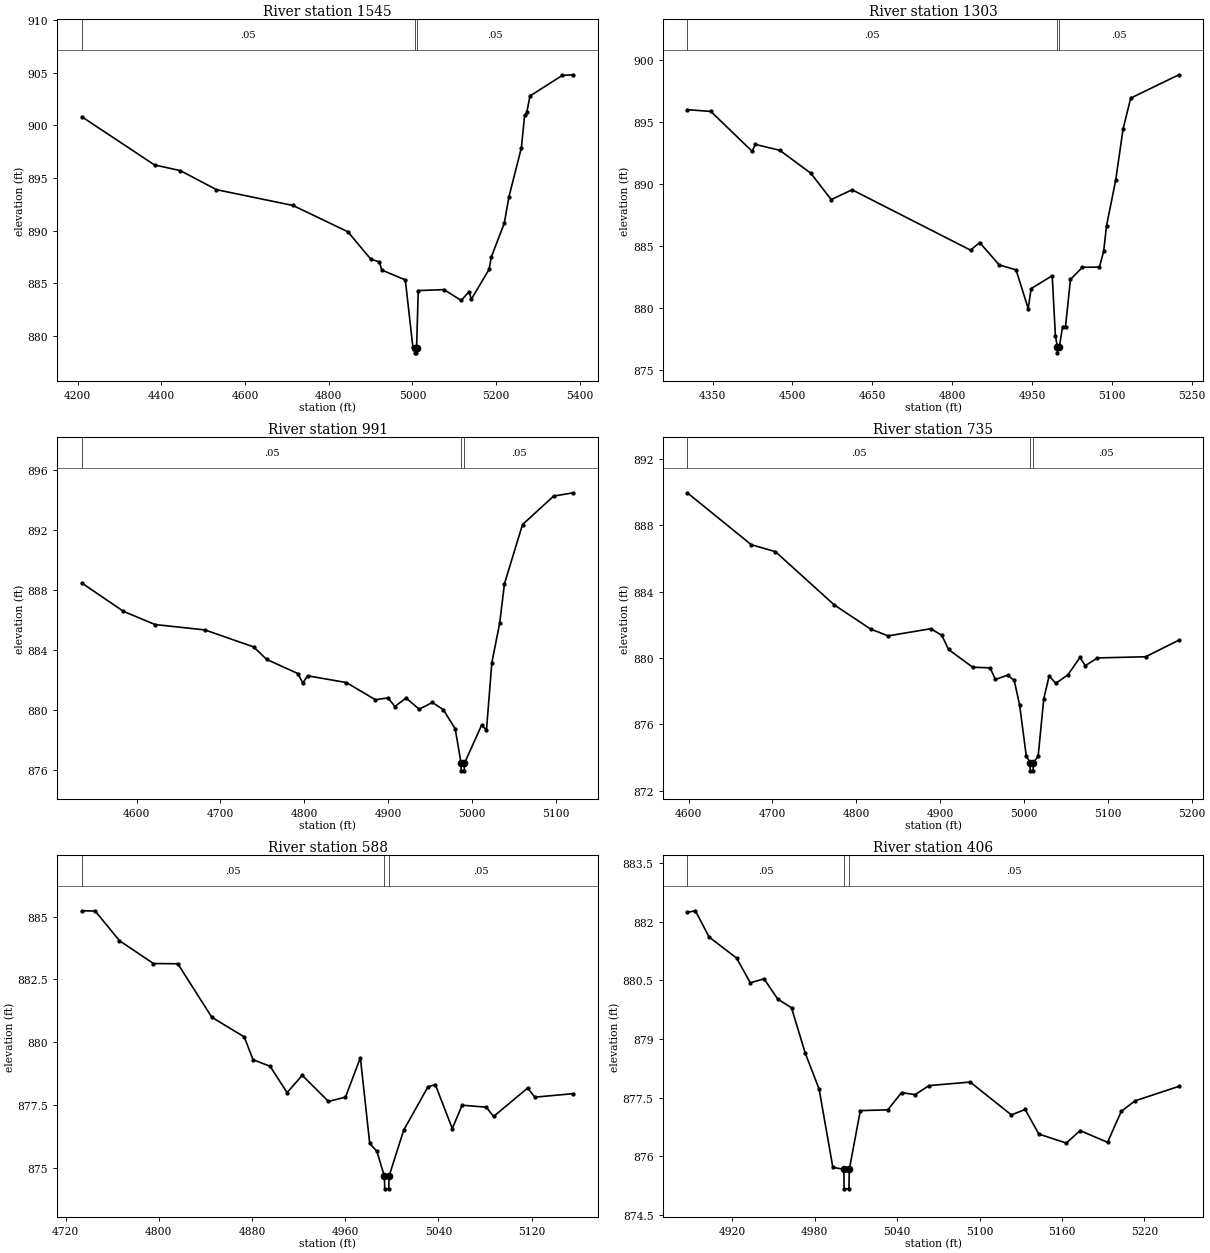
Type RM Length L Ch R = 1,1545,242,242,242
BEGIN DESCRIPTION:
MDW T 013 3.0
END DESCRIPTION:
XS GIS Cut Line= 3
      2276697.12      7119155.52      2275928.98      7118955.78
      2275558.17      7118869.04
#Sta/Elev= 30
  4210.1  900.82  4383.8  896.24  4445.6  895.70  4531.8  893.89  4714.4  892.39
  4845.8  889.89  4900.4  887.29  4921.1  887.02  4926.8  886.25  4983.1  885.31
  5001.2  878.91  5006.0  878.88  5006.3  878.38  5009.8  878.38  5010.0  878.88
  5014.0  884.30  5075.6  884.39  5116.7  883.36  5135.5  884.20  5140.7  883.47
  5183.2  886.31  5188.6  887.50  5219.4  890.68  5230.8  893.23  5260.5  897.89
  5268.1  900.95  5273.3  901.23  5281.0  902.80  5358.3  904.75  5384.6  904.81
#Mann=3,-1,0
  4210.1    0.05       0  5006.0   0.033       0  5010.0    0.05       0
Bank Sta=5006,5010
Exp/Cntr=0.3,0.1

Type RM Length L Ch R = 1,1303,312,312,312
BEGIN DESCRIPTION:
MDW T 013 2.0
END DESCRIPTION:
XS GIS Cut Line= 3
      2276618.95      7119020.09      2275978.79      7118718.21
      2275784.73      7118624.66
#Sta/Elev= 30
  4302.6  895.97  4346.8  895.83  4424.2  892.63  4430.7  893.17  4476.3  892.70
  4534.7  890.85  4572.9  888.73  4612.1  889.52  4834.6  884.66  4851.8  885.27
  4888.5  883.47  4920.1  883.07  4942.9  879.96  4948.4  881.56  4988.0  882.60
  4994.0  877.77  4997.5  876.89  4997.8  876.39  5001.5  876.89  5007.5  878.50
  5013.0  878.50  5022.3  882.30  5044.9  883.28  5076.7  883.29  5084.6  884.56
  5090.1  886.64  5107.2  890.28  5121.1  894.41  5135.4  896.90  5225.8  898.78
#Mann=3,-1,0
  4302.6    0.05       0  4997.5   0.033       0  5001.5    0.05       0
Bank Sta=4997.5,5001.5
Exp/Cntr=0.3,0.1

Type RM Length L Ch R = 1,991,256,256,256
BEGIN DESCRIPTION:
Mapping XS 9d929e77
END DESCRIPTION:
XS GIS Cut Line= 3
      2276460.85      7118827.18      2276286.33      7118730.47
      2276091.47      7118395.91
#Sta/Elev= 30
  4534.6  888.47  4584.3  886.58  4622.0  885.70  4681.6  885.34  4739.6  884.21
  4755.3  883.37  4792.5  882.43  4798.3  881.80  4804.1  882.28  4850.4  881.83
  4885.1  880.68  4900.1  880.81  4908.3  880.23  4921.6  880.80  4937.3  880.05
  4953.0  880.50  4966.1  880.02  4980.3  878.74  4987.3  876.44  4987.5  875.94
  4991.0  875.94  4991.3  876.44  5011.8  878.99  5017.6  878.66  5024.0  883.16
  5033.3  885.77  5039.1  888.43  5060.6  892.37  5097.8  894.27  5121.3  894.49
#Mann=3,-1,0
  4534.6    0.05       0  4987.3   0.033       0  4991.3    0.05       0
Bank Sta=4987.3,4991.3
Exp/Cntr=0.3,0.1

Type RM Length L Ch R = 1,735,147,147,147
BEGIN DESCRIPTION:
Mapping XS 31db37b7
END DESCRIPTION:
XS GIS Cut Line= 2
      2276620.20      7118696.47      2276253.39      7118239.08
#Sta/Elev= 30
  4598.5  889.96  4674.8  886.83  4703.6  886.41  4774.0  883.19  4817.2  881.74
  4838.1  881.33  4888.8  881.76  4902.1  881.37  4910.1  880.51  4938.9  879.44
  4959.7  879.40  4966.1  878.70  4980.5  878.96  4988.5  878.64  4994.9  877.16
  5002.9  874.07  5007.3  873.69  5007.5  873.19  5011.0  873.19  5011.3  873.69
  5017.0  874.06  5023.7  877.53  5030.1  878.91  5038.1  878.47  5052.5  878.98
  5066.9  880.03  5073.3  879.53  5087.7  880.00  5145.2  880.07  5184.8  881.07
#Mann=3,-1,0
  4598.5    0.05       0  5007.3    0.04       0  5011.3    0.05       0
Bank Sta=5007.3,5011.3
Exp/Cntr=0.3,0.1

Type RM Length L Ch R = 1,588,182,182,182
BEGIN DESCRIPTION:
Mapping XS db8d1b54
END DESCRIPTION:
XS GIS Cut Line= 2
      2276650.73      7118413.71      2276312.46      7118161.58
#Sta/Elev= 30
  4733.9  885.23  4745.4  885.22  4766.2  884.04  4795.4  883.13  4816.3  883.12
  4845.5  880.99  4873.3  880.21  4880.9  879.30  4895.5  879.04  4910.1  877.99
  4923.1  878.68  4945.6  877.64  4960.2  877.81  4973.0  879.38  4981.0  875.97
  4987.2  875.65  4993.6  874.66  4993.9  874.16  4997.4  874.16  4997.6  874.66
  5010.2  876.50  5031.0  878.22  5037.3  878.31  5051.9  876.56  5060.3  877.49
  5081.1  877.41  5087.3  877.04  5116.5  878.17  5122.8  877.81  5155.8  877.95
#Mann=3,-1,0
  4733.9    0.05       0  4993.6   0.033       0  4997.6    0.05       0
Bank Sta=4993.6,4997.6
Exp/Cntr=0.3,0.1

Type RM Length L Ch R = 1,406,234,234,234
BEGIN DESCRIPTION:
Mapping XS c5192f50
END DESCRIPTION:
XS GIS Cut Line= 2
      2276654.93      7118151.32      2276297.11      7118143.75
#Sta/Elev= 30
  4887.2  882.24  4893.1  882.28  4903.1  881.61  4923.1  881.07  4933.1  880.44
  4943.1  880.54  4953.1  880.02  4963.1  879.80  4973.1  878.64  4983.2  877.72
  4993.2  875.72  5001.2  875.67  5001.4  875.17  5004.9  875.17  5005.2  875.67
  5013.2  877.17  5033.2  877.19  5043.2  877.63  5053.2  877.58  5063.2  877.81
  5093.2  877.90  5123.2  877.06  5133.2  877.20  5143.2  876.57  5163.2  876.34
  5173.2  876.66  5193.2  876.36  5203.2  877.15  5213.2  877.42  5245.1  877.79
#Mann=3,-1,0
  4887.2    0.05       0  5001.2   0.033       0  5005.2    0.05       0
Bank Sta=5001.2,5005.2
Exp/Cntr=0.3,0.1

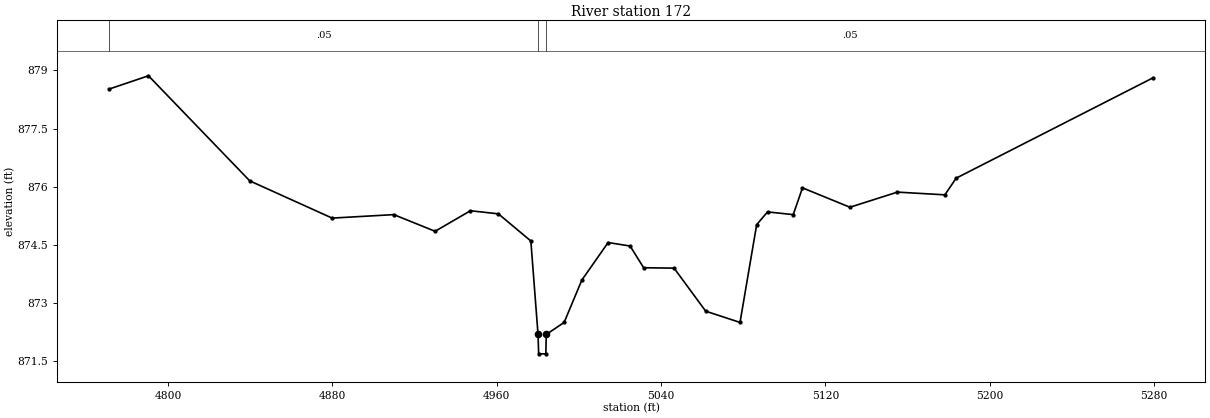
Type RM Length L Ch R = 1,172,0,0,0
BEGIN DESCRIPTION:
MDW T 013 0.5
END DESCRIPTION:
XS GIS Cut Line= 4
      2276657.15      7117924.05      2276479.67      7117935.43
      2276337.77      7117989.21      2276264.08      7118151.69
#Sta/Elev= 30
  4771.5  878.52  4790.5  878.86  4839.8  876.15  4879.9  875.19  4909.9  875.28
  4930.0  874.85  4947.2  875.38  4960.8  875.30  4976.6  874.60  4980.1  872.19
  4980.4  871.69  4983.9  871.69  4984.1  872.19  4992.8  872.50  5001.4  873.59
  5014.2  874.56  5024.9  874.47  5031.5  873.91  5046.3  873.90  5061.7  872.79
  5078.4  872.50  5086.5  875.02  5091.8  875.35  5104.3  875.28  5108.8  875.97
  5131.9  875.47  5155.0  875.86  5178.1  875.79  5183.6  876.22  5279.5  878.81
#Mann=3,-1,0
  4771.5    0.05       0  4980.1   0.033       0  4984.1    0.05       0
Bank Sta=4980.1,4984.1
Exp/Cntr=0.3,0.1

Chan Stop Cuts=-1