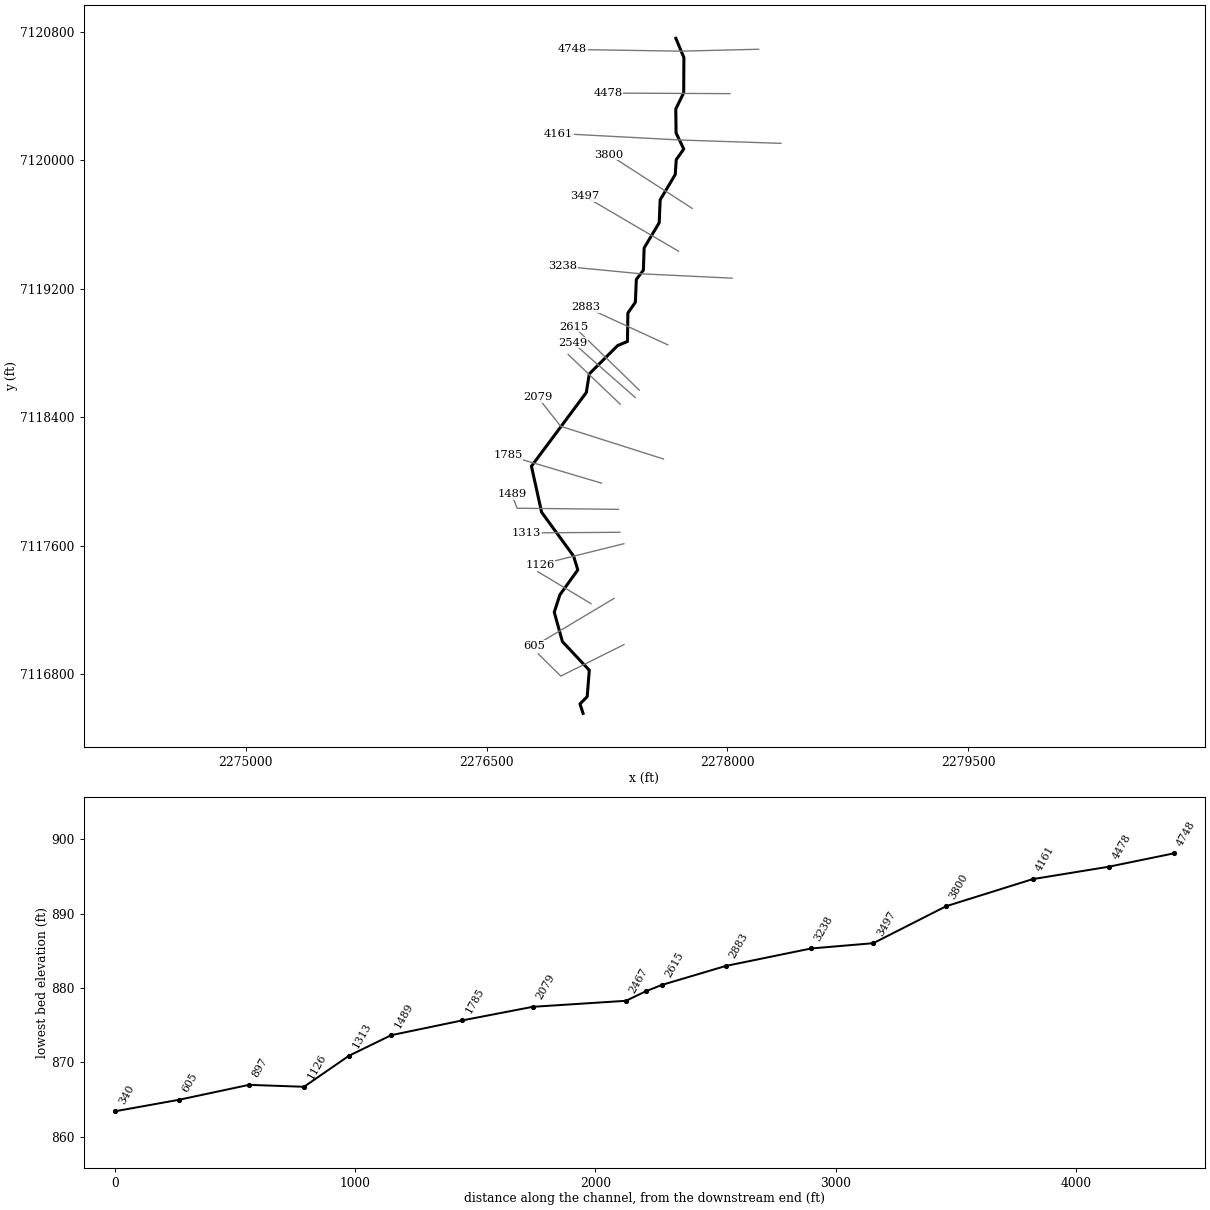
--- MDW T 014.prj (project) ---

Proj Title=MDW T 014 Base Level Engineering
Current Plan=p01
Default Exp/Contr=0.3,0.1
English Units
Geom File=g01
Flow File=f01
Plan File=p01
BEGIN DESCRIPTION:
MDW T 014
END DESCRIPTION:

--- MDW T 014.p01 (plan) ---

Plan Title=Multiple Run
Short Identifier=Multiple
Geom File=g01
Flow File=f01
Subcritical Flow
K Sum by GR= 0
Std Step Tol= 0.01
Critical Tol= 0.01
Num of Std Step Trials= 20
Max Error Tol= 0.3
Flow Tol Ratio= 0.001
Split Flow NTrial= 30
Split Flow Tol= 0.02
Split Flow Ratio= 0.02
Log Output Level= 0
Friction Slope Method= 1
Unsteady Friction Slope Method= 2
Unsteady Bridges Friction Slope Method= 1
Parabolic Critical Depth
Global Vel Dist=  1 , 1 , 1
Global Log Level= 0
CheckData=True
Encroach Param= -1, 0, 0, 0
BEGIN DESCRIPTION:
Multiple Run
END DESCRIPTION:

--- MDW T 014.f01 (steady flow) ---

Flow Title=Multiple
Number of Profiles=7
Profile Names=10-year,25-year,50-year,1pct_min,100-year,1pct_plu,500-year
River Rch & RM= MDW T 014,Reach-1,4748
     561     768     940     572    1141    2276    1682
River Rch & RM= MDW T 014,Reach-1,1489
     548     747     911     552    1101    2196    1610
Boundary for River Rch & Prof#=MDW T 014,Reach-1,1
Up Type=0
Dn Type=3
Dn Slope=0.005
Boundary for River Rch & Prof#=MDW T 014,Reach-1,2
Up Type=0
Dn Type=3
Dn Slope=0.005
Boundary for River Rch & Prof#=MDW T 014,Reach-1,3
Up Type=0
Dn Type=3
Dn Slope=0.005
Boundary for River Rch & Prof#=MDW T 014,Reach-1,4
Up Type=0
Dn Type=3
Dn Slope=0.005
Boundary for River Rch & Prof#=MDW T 014,Reach-1,5
Up Type=0
Dn Type=3
Dn Slope=0.005
Boundary for River Rch & Prof#=MDW T 014,Reach-1,6
Up Type=0
Dn Type=3
Dn Slope=0.005
Boundary for River Rch & Prof#=MDW T 014,Reach-1,7
Up Type=0
Dn Type=3
Dn Slope=0.005

--- MDW T 014.g01 (geometry) ---

Geom Title=Existing Conditions

River Reach=MDW T 014,Reach-1
Reach XY= 30
      2277679.00      7120760.00      2277728.98      7120639.99
      2277727.78      7120420.50      2277678.54      7120320.18
      2277680.24      7120170.50      2277728.23      7120070.69
      2277681.38      7120004.03      2277675.17      7119911.58
      2277581.25      7119754.07      2277575.24      7119611.56
      2277481.25      7119454.07      2277476.73      7119315.94
      2277432.79      7119258.43      2277426.73      7119115.94
      2277380.22      7119049.49      2277377.37      7118871.83
      2277316.05      7118846.26      2277139.52      7118669.79
      2277121.12      7118553.84      2276779.38      7118094.84
      2276842.74      7117808.41      2277041.90      7117535.45
      2277068.21      7117449.13      2276956.86      7117294.39
      2276921.51      7117185.83      2276972.41      7117002.35
      2277139.72      7116824.31      2277126.74      7116659.69
      2277081.78      7116614.58      2277100.95      7116555.51

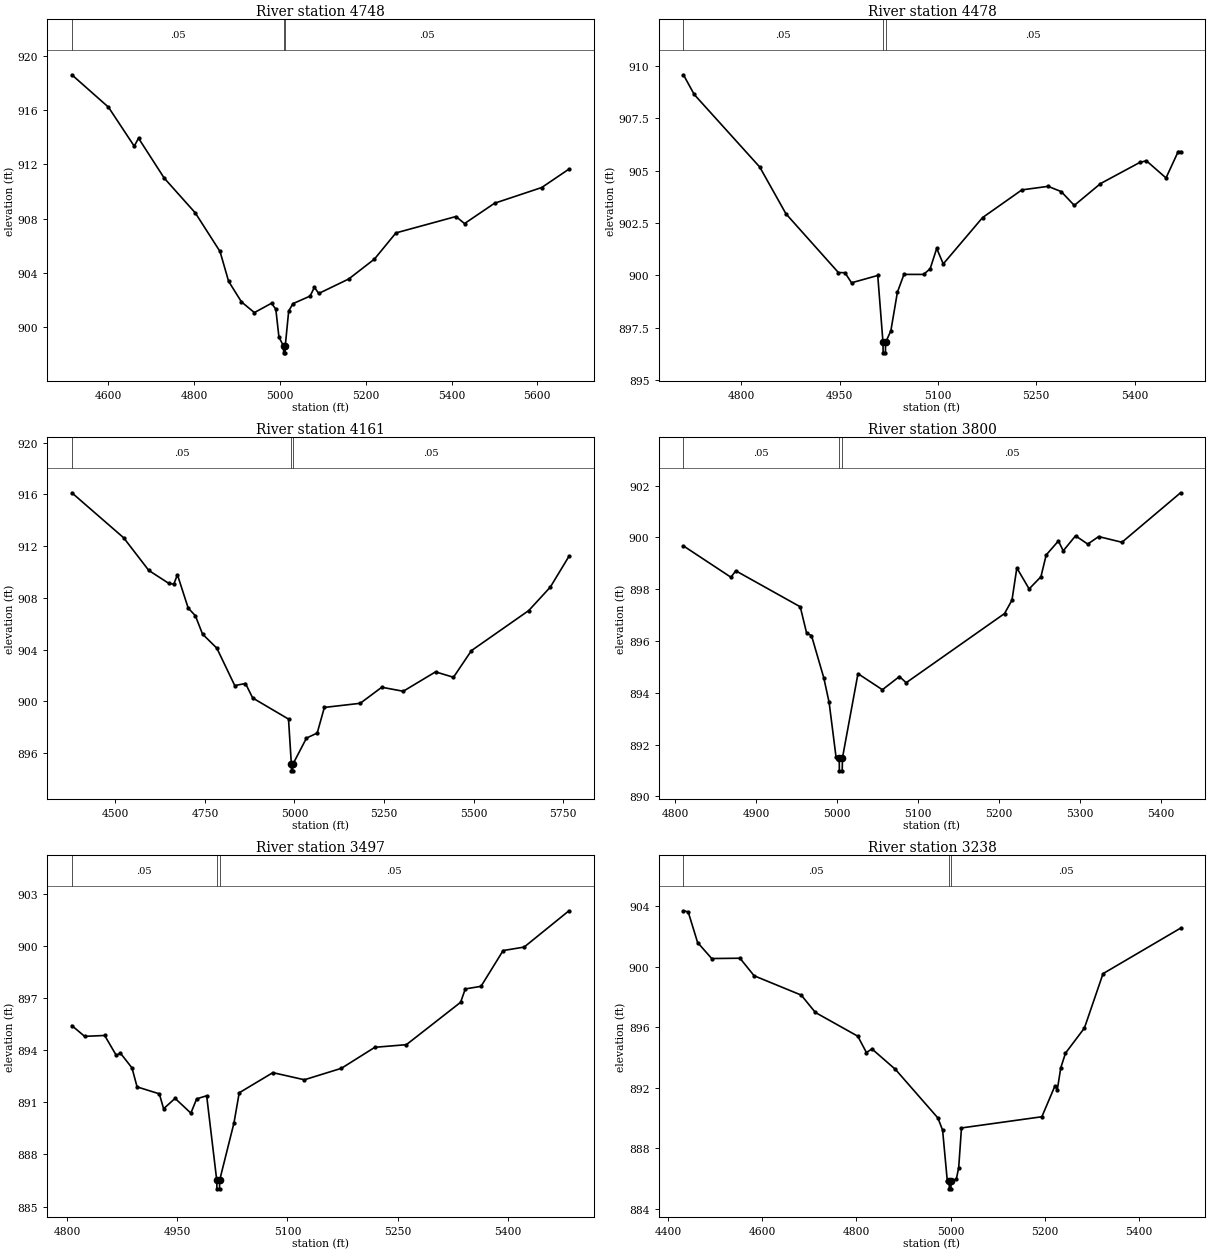
Type RM Length L Ch R = 1,4748,270,270,270
BEGIN DESCRIPTION:
MDW T 014 8.0
END DESCRIPTION:
XS GIS Cut Line= 3
      2278194.42      7120691.97      2277709.27      7120680.11
      2277035.55      7120690.66
#Sta/Elev= 30
  4514.7  918.62  4600.1  916.23  4660.2  913.35  4670.2  913.94  4730.2  910.99
  4802.5  908.43  4860.2  905.58  4880.2  903.38  4910.2  901.86  4940.3  901.07
  4980.3  901.76  4990.3  901.32  4997.6  899.26  5008.3  898.60  5008.5  898.10
  5012.0  898.10  5012.3  898.60  5020.3  901.19  5030.3  901.73  5070.3  902.29
  5080.3  902.94  5090.3  902.48  5160.3  903.55  5220.3  905.02  5270.3  906.95
  5410.3  908.16  5430.3  907.64  5500.3  909.14  5610.3  910.30  5673.8  911.66
#Mann=3,-1,0
  4514.7    0.05       0  5008.3   0.033       0  5012.3    0.05       0
Bank Sta=5008.3,5012.3
Exp/Cntr=0.3,0.1

Type RM Length L Ch R = 1,4478,317,317,317
BEGIN DESCRIPTION:
Mapping XS e0cd353c
END DESCRIPTION:
XS GIS Cut Line= 2
      2278015.55      7120415.53      2277256.76      7120419.05
#Sta/Elev= 30
  4711.4  909.57  4727.9  908.63  4827.9  905.17  4867.9  902.94  4947.9  900.14
  4958.0  900.13  4968.0  899.65  5008.0  900.00  5016.0  896.81  5016.2  896.31
  5019.7  896.31  5020.0  896.81  5028.0  897.36  5038.0  899.20  5048.0  900.05
  5078.0  900.05  5088.0  900.32  5098.0  901.29  5108.0  900.55  5168.0  902.76
  5228.0  904.08  5268.0  904.25  5288.0  904.00  5308.0  903.34  5348.0  904.38
  5408.0  905.39  5418.0  905.47  5448.0  904.65  5466.6  905.91  5470.2  905.91
#Mann=3,-1,0
  4711.4    0.05       0  5016.0   0.033       0  5020.0    0.05       0
Bank Sta=5016,5020
Exp/Cntr=0.3,0.1

Type RM Length L Ch R = 1,4161,361,361,361
BEGIN DESCRIPTION:
MDW T 014 7.0
END DESCRIPTION:
XS GIS Cut Line= 3
      2278333.68      7120106.03      2277712.32      7120126.49
      2276947.00      7120167.22
#Sta/Elev= 30
  4378.3  916.13  4523.1  912.65  4593.1  910.13  4649.5  909.12  4663.1  909.07
  4673.1  909.80  4703.2  907.22  4723.2  906.63  4743.2  905.21  4783.2  904.12
  4833.2  901.23  4863.2  901.39  4883.3  900.27  4983.3  898.64  4991.3  895.14
  4991.6  894.64  4995.1  894.64  4995.3  895.14  5033.4  897.17  5063.4  897.56
  5083.4  899.54  5183.6  899.86  5243.7  901.10  5303.7  900.79  5393.9  902.29
  5443.9  901.87  5494.0  903.93  5654.2  907.03  5714.3  908.84  5766.4  911.22
#Mann=3,-1,0
  4378.3    0.05       0  4991.3    0.04       0  4995.3    0.05       0
Bank Sta=4991.3,4995.3
Exp/Cntr=0.3,0.1

Type RM Length L Ch R = 1,3800,303,303,303
BEGIN DESCRIPTION:
Mapping XS e228051b
END DESCRIPTION:
XS GIS Cut Line= 2
      2277780.38      7119701.20      2277263.91      7120034.91
#Sta/Elev= 30
  4809.9  899.67  4868.7  898.46  4874.6  898.71  4954.4  897.32  4962.3  896.30
  4968.3  896.21  4983.5  894.58  4990.1  893.63  4998.6  891.54  5002.6  891.49
  5002.8  890.99  5006.3  890.99  5006.6  891.49  5025.8  894.74  5056.0  894.12
  5077.1  894.63  5085.4  894.39  5207.1  897.06  5216.3  897.58  5222.3  898.82
  5237.5  898.01  5252.1  898.48  5258.6  899.32  5273.7  899.86  5279.7  899.48
  5294.9  900.06  5310.0  899.74  5323.5  900.03  5352.3  899.81  5424.8  901.72
#Mann=3,-1,0
  4809.9    0.05       0  5002.6    0.04       0  5006.6    0.05       0
Bank Sta=5002.6,5006.6
Exp/Cntr=0.3,0.1

Type RM Length L Ch R = 1,3497,259,259,259
BEGIN DESCRIPTION:
Mapping XS a2b9c713
END DESCRIPTION:
XS GIS Cut Line= 2
      2277695.59      7119434.17      2277111.70      7119776.01
#Sta/Elev= 30
  4806.6  895.42  4824.0  894.80  4851.3  894.85  4867.0  893.71  4872.8  893.83
  4888.5  892.98  4895.4  891.89  4925.7  891.49  4931.5  890.63  4947.1  891.23
  4968.6  890.38  4976.5  891.20  4990.1  891.38  5003.8  886.52  5004.1  886.02
  5007.6  886.02  5007.8  886.52  5027.3  889.82  5034.4  891.55  5080.2  892.71
  5123.1  892.30  5173.5  892.96  5219.0  894.17  5261.9  894.32  5335.7  896.76
  5342.1  897.53  5363.5  897.68  5393.6  899.74  5422.2  899.94  5483.2  902.03
#Mann=3,-1,0
  4806.6    0.05       0  5003.8    0.04       0  5007.8    0.05       0
Bank Sta=5003.8,5007.8
Exp/Cntr=0.3,0.1

Type RM Length L Ch R = 1,3238,355,355,355
BEGIN DESCRIPTION:
MDW T 014 4.0
END DESCRIPTION:
XS GIS Cut Line= 3
      2278029.05      7119266.18      2277462.11      7119293.43
      2276975.67      7119340.40
#Sta/Elev= 30
  4432.4  903.71  4442.5  903.64  4462.5  901.61  4492.5  900.55  4552.6  900.57
  4582.6  899.41  4682.7  898.13  4712.8  896.98  4802.9  895.41  4821.2  894.33
  4832.9  894.57  4883.0  893.21  4973.1  890.00  4983.1  889.19  4993.1  885.82
  4997.1  885.81  4997.3  885.31  5000.8  885.31  5001.1  885.81  5012.2  885.94
  5017.3  886.72  5023.2  889.34  5194.0  890.08  5221.8  892.12  5226.8  891.87
  5234.2  893.32  5244.2  894.29  5284.4  895.95  5324.0  899.55  5488.7  902.56
#Mann=3,-1,0
  4432.4    0.05       0  4997.1   0.033       0  5001.1    0.05       0
Bank Sta=4997.1,5001.1
Exp/Cntr=0.3,0.1

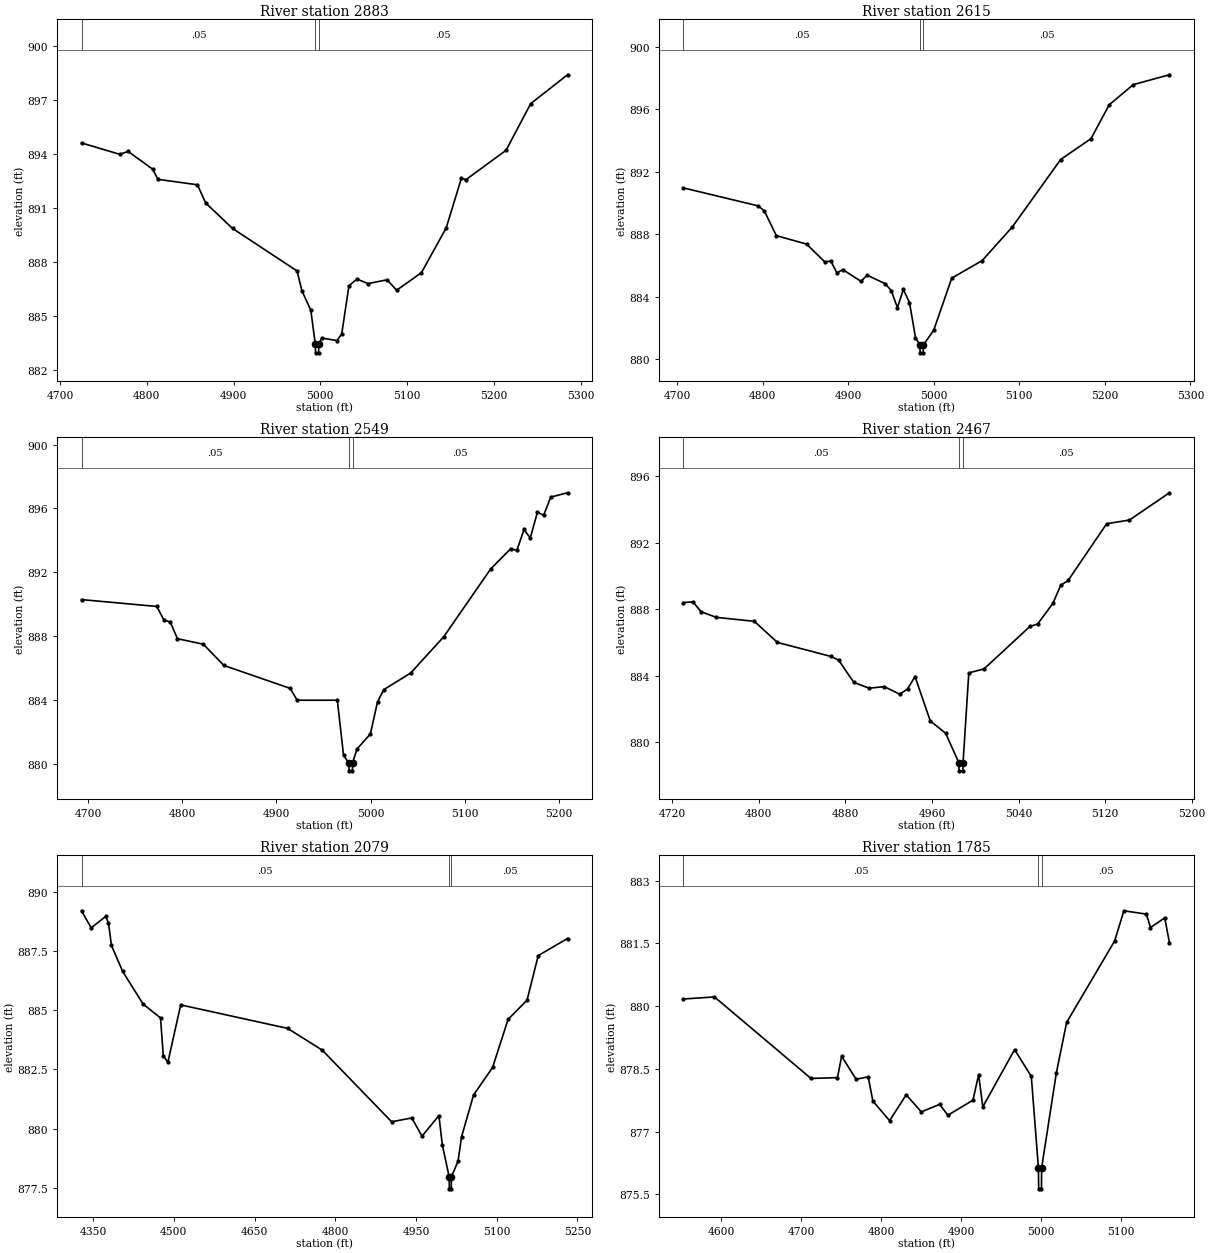
Type RM Length L Ch R = 1,2883,268,268,268
BEGIN DESCRIPTION:
Mapping XS 7b4d5237
END DESCRIPTION:
XS GIS Cut Line= 2
      2277629.01      7118850.86      2277120.16      7119084.91
#Sta/Elev= 30
  4724.8  894.60  4768.8  893.97  4778.5  894.13  4806.9  893.14  4812.9  892.58
  4858.4  892.28  4867.9  891.27  4898.8  889.86  4973.2  887.50  4978.8  886.40
  4989.0  885.33  4994.2  883.46  4994.5  882.96  4998.0  882.96  4998.2  883.46
  5001.7  883.78  5019.2  883.64  5024.7  884.01  5033.0  886.68  5042.2  887.05
  5055.0  886.80  5077.0  887.01  5088.0  886.43  5116.6  887.41  5145.1  889.89
  5162.5  892.63  5168.0  892.57  5214.0  894.19  5242.5  896.78  5284.9  898.38
#Mann=3,-1,0
  4724.8    0.05       0  4994.2   0.033       0  4998.2    0.05       0
Bank Sta=4994.2,4998.2
Exp/Cntr=0.3,0.1

Type RM Length L Ch R = 1,2615,66,66,66
BEGIN DESCRIPTION:
Mapping XS 6f5f5f25
END DESCRIPTION:
XS GIS Cut Line= 2
      2277451.20      7118568.65      2277044.10      7118964.75
#Sta/Elev= 30
  4707.5  890.96  4794.8  889.81  4802.0  889.49  4816.1  887.90  4851.4  887.36
  4872.7  886.22  4879.7  886.27  4886.8  885.52  4893.8  885.72  4915.1  884.97
  4922.1  885.37  4943.4  884.82  4950.4  884.38  4957.6  883.28  4964.5  884.45
  4971.7  883.61  4978.7  881.37  4983.9  880.89  4984.1  880.39  4987.6  880.39
  4987.9  880.89  5000.0  881.84  5021.1  885.18  5056.6  886.30  5091.9  888.46
  5148.4  892.78  5183.9  894.12  5205.0  896.28  5233.3  897.58  5275.5  898.21
#Mann=3,-1,0
  4707.5    0.05       0  4983.9    0.04       0  4987.9    0.05       0
Bank Sta=4983.9,4987.9
Exp/Cntr=0.3,0.1

Type RM Length L Ch R = 1,2549,82,82,82
BEGIN DESCRIPTION:
Mapping XS d89d1d9e
END DESCRIPTION:
XS GIS Cut Line= 2
      2277425.46      7118523.35      2277037.81      7118864.23
#Sta/Elev= 30
  4693.0  890.28  4773.0  889.85  4780.6  888.99  4787.3  888.88  4794.8  887.83
  4822.4  887.48  4844.2  886.15  4914.7  884.71  4922.0  883.97  4964.7  883.97
  4971.3  880.51  4976.9  880.04  4977.2  879.54  4980.7  879.54  4980.9  880.04
  4985.6  880.91  4999.8  881.85  5007.4  883.87  5014.0  884.63  5042.5  885.67
  5077.6  887.94  5127.7  892.21  5148.7  893.46  5155.4  893.37  5163.0  894.68
  5169.6  894.14  5177.2  895.75  5183.9  895.58  5191.4  896.71  5209.2  896.98
#Mann=3,-1,0
  4693.0    0.05       0  4976.9    0.04       0  4980.9    0.05       0
Bank Sta=4976.9,4980.9
Exp/Cntr=0.3,0.1

Type RM Length L Ch R = 1,2467,388,388,388
BEGIN DESCRIPTION:
Mapping XS 86e119b0
END DESCRIPTION:
XS GIS Cut Line= 2
      2277332.66      7118480.94      2277007.96      7118791.20
#Sta/Elev= 30
  4730.3  888.39  4739.2  888.43  4746.5  887.84  4760.6  887.50  4795.8  887.26
  4817.2  885.99  4866.6  885.15  4873.7  884.93  4887.7  883.59  4901.8  883.24
  4916.0  883.33  4930.1  882.88  4937.4  883.19  4944.3  883.94  4958.4  881.27
  4972.6  880.53  4984.7  878.77  4985.0  878.27  4988.5  878.27  4988.7  878.77
  4994.0  884.16  5008.1  884.40  5050.6  886.96  5057.5  887.09  5071.7  888.34
  5078.9  889.42  5085.8  889.72  5121.4  893.13  5142.4  893.35  5179.4  894.99
#Mann=3,-1,0
  4730.3    0.05       0  4984.7    0.04       0  4988.7    0.05       0
Bank Sta=4984.7,4988.7
Exp/Cntr=0.3,0.1

Type RM Length L Ch R = 1,2079,294,294,294
BEGIN DESCRIPTION:
MDW T 014 1.0
END DESCRIPTION:
XS GIS Cut Line= 3
      2277601.95      7118139.88      2276962.05      7118343.45
      2276818.23      7118525.11
#Sta/Elev= 30
  4328.5  889.19  4346.4  888.47  4373.4  888.95  4378.6  888.68  4384.1  887.73
  4405.0  886.63  4443.1  885.25  4475.3  884.67  4480.5  883.07  4489.0  882.80
  4512.8  885.22  4711.4  884.23  4775.9  883.31  4904.8  880.29  4942.3  880.45
  4961.2  879.68  4992.7  880.55  4999.0  879.32  5011.8  877.96  5012.1  877.46
  5015.6  877.46  5015.8  877.96  5028.3  878.63  5034.7  879.65  5057.1  881.42
  5092.4  882.58  5121.3  884.61  5156.5  885.42  5177.3  887.30  5231.7  888.02
#Mann=3,-1,0
  4328.5    0.05       0  5011.8    0.04       0  5015.8    0.05       0
Bank Sta=5011.8,5015.8
Exp/Cntr=0.3,0.1

Type RM Length L Ch R = 1,1785,296,296,296
BEGIN DESCRIPTION:
Mapping XS 8ee6bba4
END DESCRIPTION:
XS GIS Cut Line= 2
      2277216.22      7117989.46      2276633.33      7118162.37
#Sta/Elev= 30
  4552.5  880.17  4591.3  880.22  4712.0  878.27  4745.2  878.29  4750.4  878.80
  4768.6  878.25  4783.6  878.31  4789.5  877.73  4810.4  877.26  4831.2  877.88
  4850.1  877.47  4873.0  877.65  4883.3  877.39  4914.7  877.75  4921.8  878.36
  4927.0  877.59  4966.8  878.96  4987.7  878.32  4996.6  876.13  4996.9  875.63
  5000.4  875.63  5000.6  876.13  5019.0  878.40  5031.9  879.61  5092.0  881.56
  5103.5  882.28  5131.6  882.20  5136.8  881.88  5154.6  882.11  5160.5  881.52
#Mann=3,-1,0
  4552.5    0.05       0  4996.6    0.04       0  5000.6    0.05       0
Bank Sta=4996.6,5000.6
Exp/Cntr=0.3,0.1

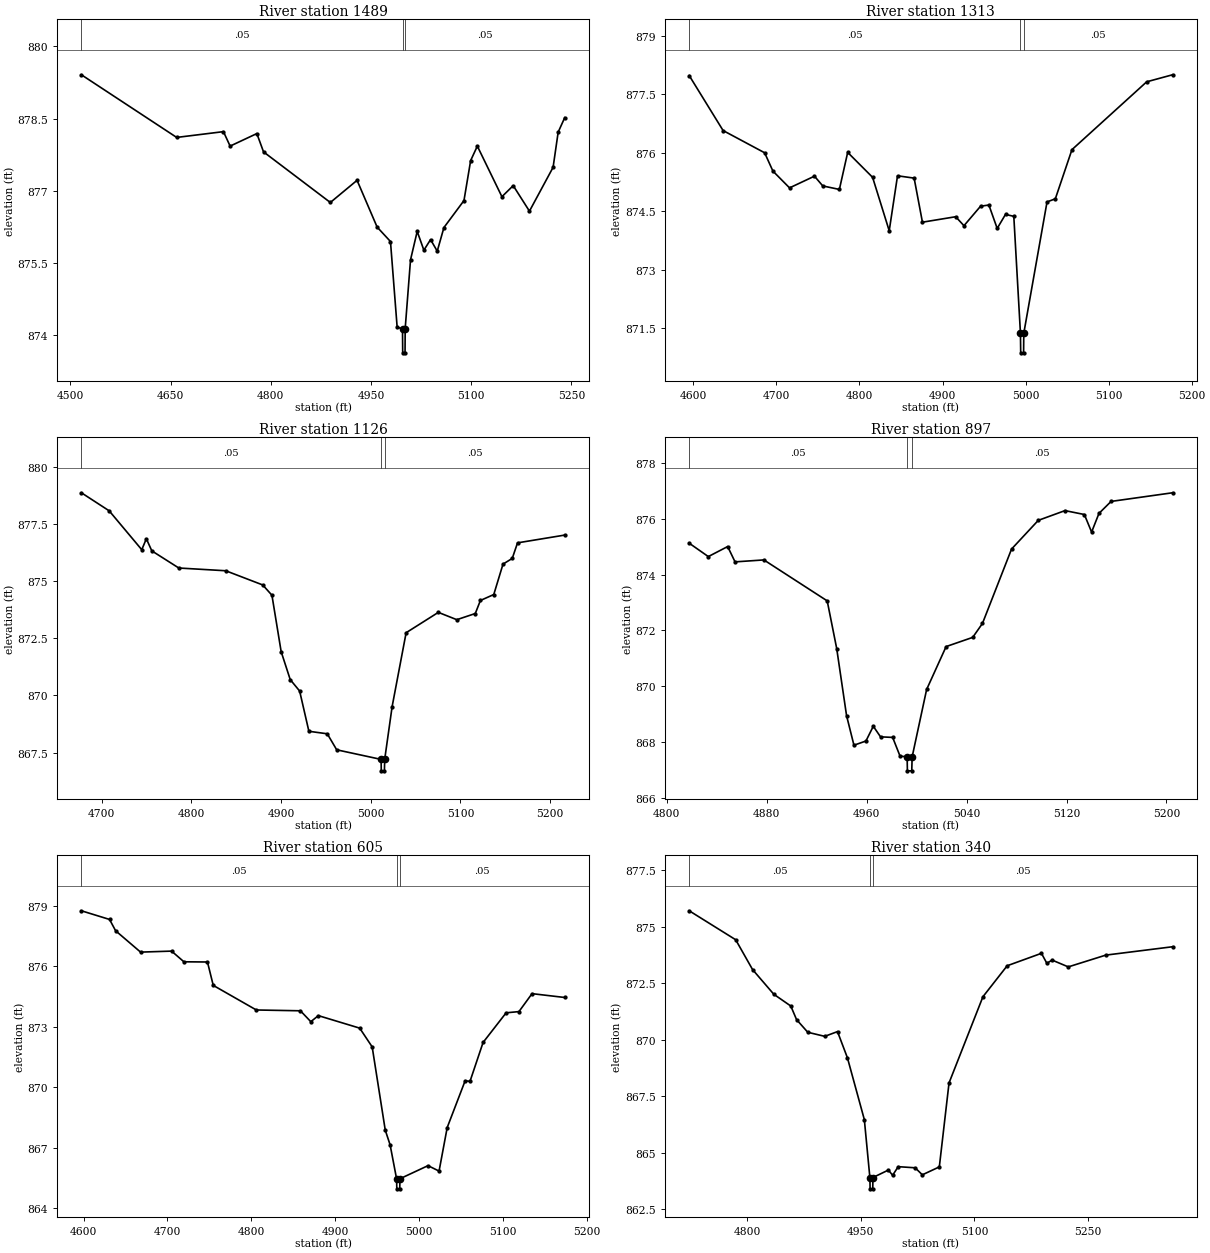
Type RM Length L Ch R = 1,1489,176,176,176
BEGIN DESCRIPTION:
Mapping XS ffd09b9f
END DESCRIPTION:
XS GIS Cut Line= 3
      2277321.61      7117826.35      2276690.43      7117833.29
      2276656.80      7117919.12
#Sta/Elev= 30
  4516.5  879.41  4659.1  878.11  4729.1  878.23  4739.1  877.93  4779.1  878.19
  4789.1  877.81  4889.1  876.76  4929.1  877.22  4959.1  876.25  4979.1  875.95
  4989.1  874.17  4997.1  874.14  4997.4  873.64  5000.9  873.64  5001.1  874.14
  5009.1  875.57  5019.1  876.16  5029.1  875.77  5039.1  875.99  5049.1  875.75
  5059.1  876.24  5089.1  876.80  5099.1  877.63  5109.1  877.93  5145.9  876.88
  5162.8  877.11  5187.1  876.58  5222.5  877.49  5230.1  878.22  5239.9  878.52
#Mann=3,-1,0
  4516.5    0.05       0  4997.1    0.04       0  5001.1    0.05       0
Bank Sta=4997.1,5001.1
Exp/Cntr=0.3,0.1

Type RM Length L Ch R = 1,1313,187,187,187
BEGIN DESCRIPTION:
Mapping XS 8a895cb6
END DESCRIPTION:
XS GIS Cut Line= 2
      2277329.84      7117683.44      2276747.95      7117679.48
#Sta/Elev= 30
  4595.0  877.98  4635.8  876.57  4685.8  876.00  4695.8  875.53  4715.8  875.10
  4745.8  875.40  4755.8  875.15  4775.8  875.06  4785.8  876.01  4815.8  875.37
  4835.8  874.00  4845.8  875.41  4865.8  875.35  4875.8  874.22  4915.8  874.36
  4925.8  874.13  4945.8  874.63  4955.8  874.66  4965.8  874.06  4975.8  874.42
  4985.8  874.37  4993.8  871.37  4994.1  870.87  4997.6  870.87  4997.8  871.37
  5025.8  874.74  5035.8  874.82  5055.8  876.08  5145.8  877.82  5176.9  878.00
#Mann=3,-1,0
  4595.0    0.05       0  4993.8   0.033       0  4997.8    0.05       0
Bank Sta=4993.8,4997.8
Exp/Cntr=0.3,0.1

Type RM Length L Ch R = 1,1126,229,229,229
BEGIN DESCRIPTION:
Mapping XS 1193c411
END DESCRIPTION:
XS GIS Cut Line= 2
      2277355.18      7117612.21      2276832.23      7117482.50
#Sta/Elev= 30
  4677.5  878.86  4708.5  878.07  4744.8  876.37  4749.9  876.85  4756.0  876.32
  4786.1  875.57  4838.4  875.45  4879.6  874.83  4889.9  874.38  4900.2  871.91
  4910.3  870.69  4920.8  870.19  4931.1  868.43  4951.6  868.32  4962.1  867.62
  5011.6  867.20  5011.8  866.70  5015.3  866.70  5015.6  867.20  5023.9  869.51
  5039.5  872.74  5075.4  873.63  5096.0  873.31  5116.6  873.58  5122.3  874.15
  5137.2  874.41  5147.5  875.74  5157.8  875.99  5163.7  876.67  5216.3  877.01
#Mann=3,-1,0
  4677.5    0.05       0  5011.6   0.033       0  5015.6    0.05       0
Bank Sta=5011.6,5015.6
Exp/Cntr=0.3,0.1

Type RM Length L Ch R = 1,897,292,292,292
BEGIN DESCRIPTION:
Mapping XS 31b78699
END DESCRIPTION:
XS GIS Cut Line= 2
      2277150.23      7117239.00      2276818.56      7117438.41
#Sta/Elev= 30
  4817.9  875.13  4833.2  874.65  4848.7  875.01  4854.6  874.46  4877.7  874.53
  4928.4  873.06  4936.0  871.35  4943.9  868.94  4949.8  867.88  4959.4  868.03
  4965.3  868.56  4971.1  868.18  4980.8  868.16  4986.7  867.49  4992.4  867.46
  4992.6  866.96  4996.1  866.96  4996.4  867.46  5008.0  869.88  5023.6  871.42
  5044.9  871.75  5052.7  872.25  5076.0  874.92  5097.4  875.95  5118.8  876.30
  5134.3  876.16  5140.1  875.53  5146.0  876.20  5155.7  876.63  5204.9  876.94
#Mann=3,-1,0
  4817.9    0.05       0  4992.4   0.033       0  4996.4    0.05       0
Bank Sta=4992.4,4996.4
Exp/Cntr=0.3,0.1

Type RM Length L Ch R = 1,605,265,265,265
BEGIN DESCRIPTION:
Mapping XS d33edefc
END DESCRIPTION:
XS GIS Cut Line= 2
      2277294.02      7117271.53      2276798.98      7116975.90
#Sta/Elev= 30
  4597.3  878.74  4630.9  878.31  4638.1  877.75  4667.9  876.69  4704.9  876.74
  4719.6  876.21  4747.7  876.20  4754.6  875.04  4806.0  873.82  4858.6  873.78
  4871.0  873.24  4880.0  873.54  4929.3  872.92  4944.2  871.99  4959.8  867.86
  4965.6  867.13  4973.3  865.45  4973.6  864.95  4977.1  864.95  4977.3  865.45
  5010.8  866.10  5024.0  865.83  5033.7  867.99  5055.1  870.31  5060.9  870.28
  5076.5  872.21  5104.0  873.68  5119.3  873.74  5134.9  874.63  5173.9  874.44
#Mann=3,-1,0
  4597.3    0.05       0  4973.3    0.04       0  4977.3    0.05       0
Bank Sta=4973.3,4977.3
Exp/Cntr=0.3,0.1

Type RM Length L Ch R = 1,340,0,0,0
BEGIN DESCRIPTION:
MDW T 014 0.5
END DESCRIPTION:
XS GIS Cut Line= 3
      2277355.76      7116983.84      2276962.39      7116787.87
      2276821.27      7116926.79
#Sta/Elev= 30
  4723.8  875.70  4785.1  874.42  4807.4  873.10  4835.4  872.01  4857.8  871.49
  4865.4  870.89  4880.2  870.33  4902.6  870.15  4919.4  870.36  4932.5  869.20
  4954.8  866.47  4962.1  863.91  4962.4  863.41  4965.9  863.41  4966.1  863.91
  4986.5  864.24  4992.1  864.01  4999.5  864.39  5021.8  864.34  5031.3  864.03
  5053.7  864.38  5066.5  868.09  5111.2  871.90  5143.2  873.27  5188.4  873.82
  5195.5  873.38  5202.5  873.52  5223.8  873.22  5273.2  873.74  5361.3  874.11
#Mann=3,-1,0
  4723.8    0.05       0  4962.1   0.033       0  4966.1    0.05       0
Bank Sta=4962.1,4966.1
Exp/Cntr=0.3,0.1

Chan Stop Cuts=-1