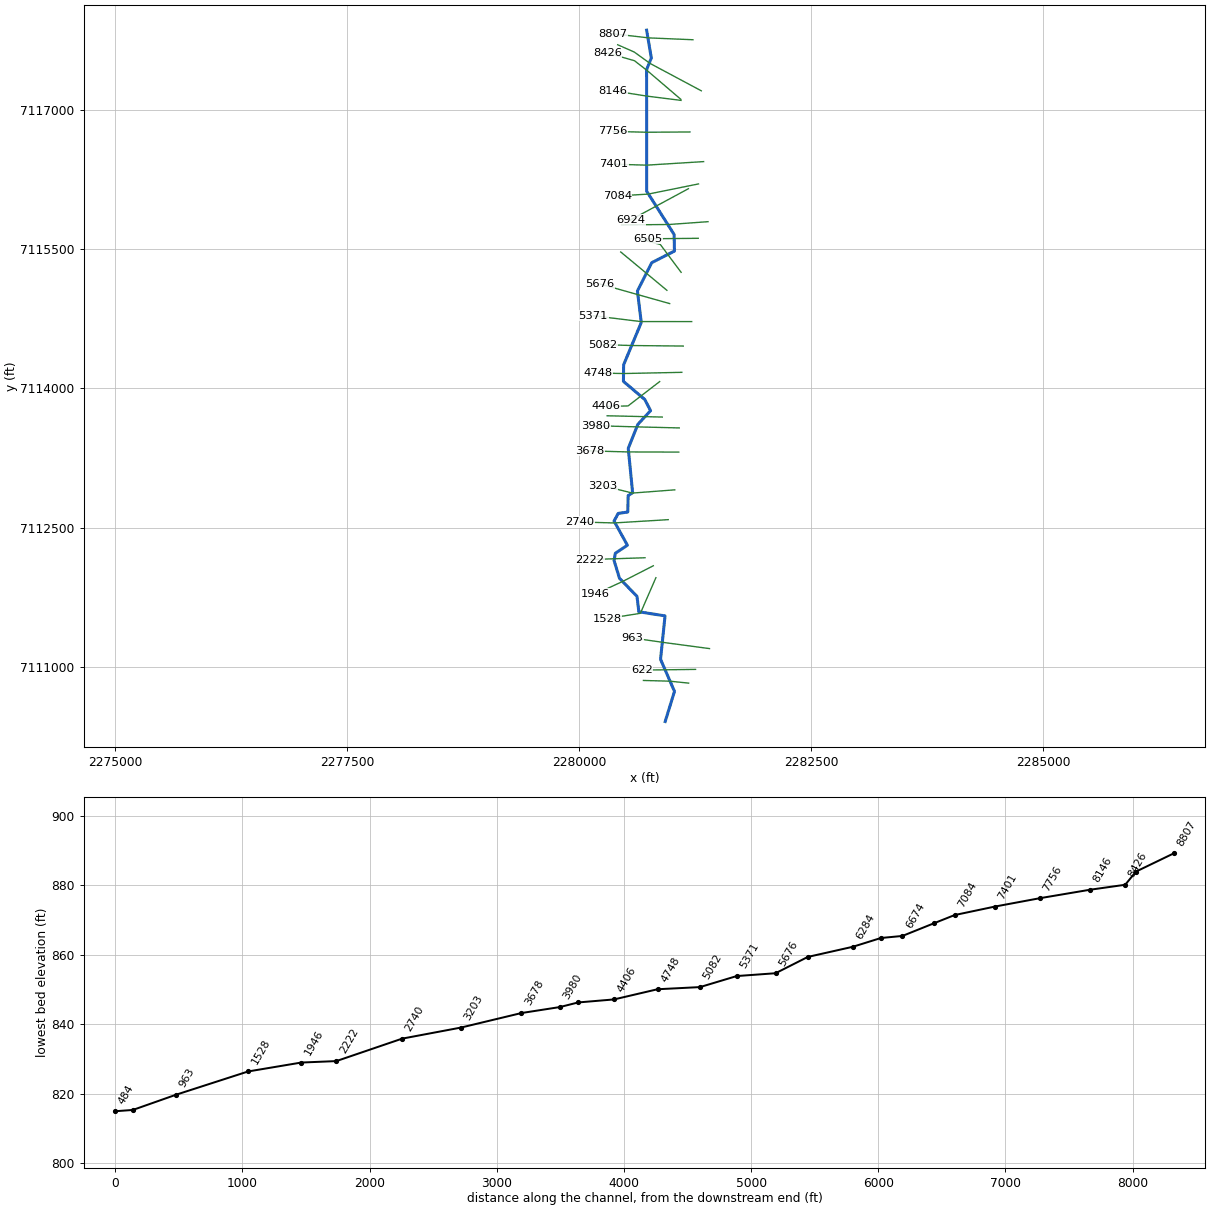
--- MDW T 015.prj (project) ---

Proj Title=MDW T 015 Base Level Engineering
Current Plan=p01
Default Exp/Contr=0.3,0.1
English Units
Geom File=g01
Flow File=f01
Plan File=p01
BEGIN DESCRIPTION:
MDW T 015
END DESCRIPTION:

--- MDW T 015.p01 (plan) ---

Plan Title=Multiple Run
Short Identifier=Multiple
Geom File=g01
Flow File=f01
Subcritical Flow
K Sum by GR= 0
Std Step Tol= 0.01
Critical Tol= 0.01
Num of Std Step Trials= 20
Max Error Tol= 0.3
Flow Tol Ratio= 0.001
Split Flow NTrial= 30
Split Flow Tol= 0.02
Split Flow Ratio= 0.02
Log Output Level= 0
Friction Slope Method= 1
Unsteady Friction Slope Method= 2
Unsteady Bridges Friction Slope Method= 1
Parabolic Critical Depth
Global Vel Dist=  1 , 1 , 1
Global Log Level= 0
CheckData=True
Encroach Param= -1, 0, 0, 0
BEGIN DESCRIPTION:
Multiple Run
END DESCRIPTION:

--- MDW T 015.f01 (steady flow) ---

Flow Title=Multiple
Number of Profiles=7
Profile Names=10-year,25-year,50-year,1pct_min,100-year,1pct_plu,500-year
River Rch & RM= MDW T 015,Reach-1,8807
     656     908    1118     684    1364    2722    2036
River Rch & RM= MDW T 015,Reach-1,3203
     666     922    1135     694    1385    2763    2066
River Rch & RM= MDW T 015,Reach-1,963
     778    1087    1346     828    1652    3297    2494
Boundary for River Rch & Prof#=MDW T 015,Reach-1,1
Up Type=0
Dn Type=3
Dn Slope=0.005
Boundary for River Rch & Prof#=MDW T 015,Reach-1,2
Up Type=0
Dn Type=3
Dn Slope=0.005
Boundary for River Rch & Prof#=MDW T 015,Reach-1,3
Up Type=0
Dn Type=3
Dn Slope=0.005
Boundary for River Rch & Prof#=MDW T 015,Reach-1,4
Up Type=0
Dn Type=3
Dn Slope=0.005
Boundary for River Rch & Prof#=MDW T 015,Reach-1,5
Up Type=0
Dn Type=3
Dn Slope=0.005
Boundary for River Rch & Prof#=MDW T 015,Reach-1,6
Up Type=0
Dn Type=3
Dn Slope=0.005
Boundary for River Rch & Prof#=MDW T 015,Reach-1,7
Up Type=0
Dn Type=3
Dn Slope=0.005

--- MDW T 015.g01 (geometry) ---

Geom Title=Existing Conditions

River Reach=MDW T 015,Reach-1
Reach XY= 30
      2280729.00      7117860.00      2280779.82      7117560.00
      2280728.80      7117435.08      2280729.51      7116125.21
      2281025.25      7115658.45      2281029.09      7115479.87
      2280784.25      7115354.56      2280630.05      7115049.56
      2280671.44      7114710.00      2280481.26      7114254.06
      2280479.38      7114075.15      2280709.24      7113880.13
      2280771.72      7113759.91      2280634.52      7113612.43
      2280531.24      7113354.07      2280578.04      7112875.96
      2280529.96      7112844.04      2280526.06      7112667.97
      2280422.55      7112652.25      2280378.15      7112570.12
      2280522.01      7112309.78      2280392.20      7112223.65
      2280378.27      7112144.96      2280436.86      7111953.83
      2280625.46      7111758.53      2280645.24      7111592.77
      2280927.57      7111548.57      2280879.12      7111080.36
      2281029.40      7110735.00      2280929.00      7110410.00

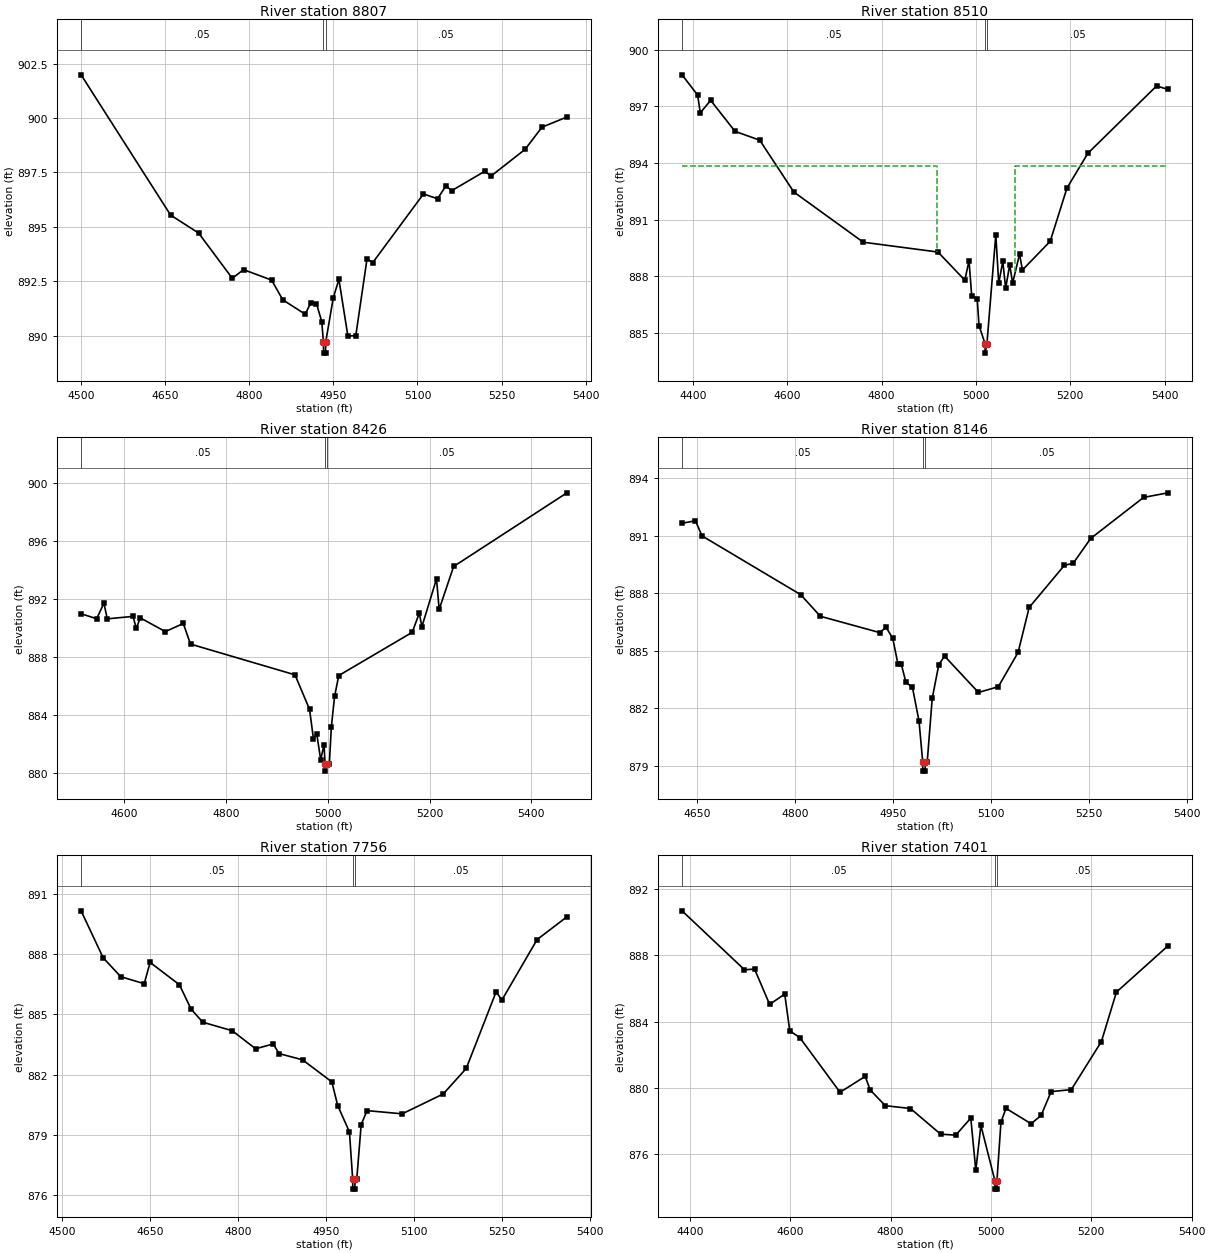
Type RM Length L Ch R = 1,8807,297,297,297
BEGIN DESCRIPTION:
MDW T 015 21.0
END DESCRIPTION:
XS GIS Cut Line= 3
      2281228.57      7117756.84      2280752.03      7117776.80
      2280364.75      7117821.41
#Sta/Elev= 30
  4499.8  901.99  4659.5  895.54  4709.6  894.71  4769.6  892.63  4789.6  893.03
  4839.7  892.55  4859.7  891.64  4899.7  890.98  4909.7  891.51  4919.7  891.47
  4929.2  890.64  4932.2  889.69  4932.5  889.19  4936.0  889.19  4936.2  889.69
  4949.8  891.74  4959.8  892.58  4975.8  889.98  4989.9  889.99  5010.0  893.53
  5020.1  893.35  5110.7  896.51  5135.8  896.29  5150.9  896.89  5161.0  896.66
  5219.8  897.55  5231.5  897.34  5291.9  898.56  5322.1  899.58  5366.6  900.05
#Mann=3,-1,0
  4499.8    0.05       0  4932.2   0.033       0  4936.2    0.05       0
Bank Sta=4932.2,4936.2
Exp/Cntr=0.3,0.1

Type RM Length L Ch R = 1,8510,84,84,84
BEGIN DESCRIPTION:
MDW T 015 20.0
END DESCRIPTION:
XS GIS Cut Line= 4
      2281318.10      7117206.72      2280768.19      7117500.37
      2280595.95      7117624.20      2280417.45      7117702.62
#Sta/Elev= 30
  4376.6  898.67  4409.6  897.60  4415.3  896.66  4437.3  897.32  4488.9  895.68
  4541.4  895.21  4613.6  892.47  4761.0  889.81  4919.5  889.29  4976.4  887.80
  4985.3  888.83  4991.0  886.97  5002.6  886.83  5006.5  885.40  5019.3  884.44
  5019.5  883.94  5023.3  884.44  5042.1  890.21  5048.3  887.63  5056.9  888.80
  5063.0  887.38  5071.6  888.61  5077.8  887.65  5092.5  889.18  5098.6  888.34
  5157.5  889.86  5193.1  892.68  5237.5  894.52  5383.1  898.08  5407.1  897.90
#Mann=3,-1,0
  4376.6    0.05       0  5019.3   0.033       0  5023.3    0.05       0
#XS Ineff=2,0
    0.00 4916.50  893.84 5083.50    0.00  893.84
Permanent Ineff=
       F       F
Bank Sta=5019.3,5023.3
Exp/Cntr=0.3,0.1

Type RM Length L Ch R = 1,8426,280,280,280
BEGIN DESCRIPTION:
MDW T 015 19.5
END DESCRIPTION:
XS GIS Cut Line= 4
      2281097.32      7117115.18      2280728.64      7117430.15
      2280597.34      7117531.14      2280304.94      7117614.49
#Sta/Elev= 30
  4515.1  891.01  4545.7  890.67  4560.0  891.74  4566.5  890.66  4617.1  890.83
  4623.6  890.00  4631.3  890.73  4680.7  889.78  4715.9  890.34  4730.1  888.92
  4935.4  886.80  4964.0  884.42  4971.7  882.39  4978.2  882.72  4985.9  880.95
  4992.5  881.99  4994.5  880.66  4994.7  880.16  4998.5  880.66  5002.9  880.66
  5006.9  883.23  5013.2  885.31  5021.4  886.75  5165.7  889.73  5179.6  891.05
  5184.8  890.12  5213.5  893.42  5218.7  891.31  5247.1  894.27  5469.7  899.35
#Mann=3,-1,0
  4515.1    0.05       0  4994.5   0.033       0  4998.5    0.05       0
Bank Sta=4994.5,4998.5
Exp/Cntr=0.3,0.1

Type RM Length L Ch R = 1,8146,390,390,390
BEGIN DESCRIPTION:
MDW T 015 19.0
END DESCRIPTION:
XS GIS Cut Line= 3
      2281099.38      7117103.37      2280728.99      7117149.89
      2280362.26      7117207.95
#Sta/Elev= 30
  4626.7  891.66  4647.2  891.79  4657.3  891.00  4808.5  887.93  4838.7  886.80
  4929.4  885.95  4939.5  886.22  4949.6  885.65  4957.7  884.29  4962.7  884.30
  4969.8  883.35  4979.8  883.09  4989.9  881.32  4995.5  879.21  4995.7  878.71
  4999.2  878.71  4999.5  879.21  5002.5  879.21  5010.1  882.51  5020.2  884.27
  5029.0  884.72  5081.0  882.82  5111.4  883.12  5141.7  884.91  5158.7  887.26
  5212.6  889.46  5226.2  889.57  5253.1  890.87  5334.1  893.01  5371.3  893.25
#Mann=3,-1,0
  4626.7    0.05       0  4995.5   0.033       0  4999.5    0.05       0
Bank Sta=4995.5,4999.5
Exp/Cntr=0.3,0.1

Type RM Length L Ch R = 1,7756,355,355,355
BEGIN DESCRIPTION:
MDW T 015 18.0
END DESCRIPTION:
XS GIS Cut Line= 3
      2281196.68      7116763.09      2280729.00      7116760.00
      2280368.22      7116769.34
#Sta/Elev= 30
  4532.3  890.16  4570.0  887.82  4600.0  886.88  4640.0  886.53  4650.0  887.59
  4700.0  886.48  4720.0  885.26  4740.0  884.61  4790.0  884.19  4830.0  883.29
  4860.0  883.53  4870.0  883.05  4910.0  882.74  4960.0  881.64  4970.0  880.46
  4990.0  879.15  4995.5  876.80  4995.7  876.30  4999.2  876.30  4999.5  876.80
  5002.5  876.80  5010.0  879.51  5020.0  880.21  5080.0  880.05  5150.0  881.04
  5189.2  882.31  5240.1  886.12  5250.1  885.72  5310.1  888.73  5360.9  889.86
#Mann=3,-1,0
  4532.3    0.05       0  4995.5   0.033       0  4999.5    0.05       0
Bank Sta=4995.5,4999.5
Exp/Cntr=0.3,0.1

Type RM Length L Ch R = 1,7401,317,317,317
BEGIN DESCRIPTION:
MDW T 015 17.0
END DESCRIPTION:
XS GIS Cut Line= 3
      2281343.21      7116443.64      2280729.00      7116405.45
      2280376.55      7116415.86
#Sta/Elev= 30
  4384.6  890.69  4509.0  887.13  4529.1  887.17  4559.1  885.04  4589.2  885.66
  4599.2  883.44  4619.3  883.03  4699.4  879.73  4749.5  880.69  4759.5  879.87
  4789.6  878.92  4839.7  878.75  4899.8  877.20  4929.9  877.14  4959.9  878.17
  4969.9  875.01  4980.0  877.73  5008.0  874.38  5008.3  873.88  5011.8  873.88
  5012.0  874.38  5020.0  877.92  5030.0  878.76  5080.0  877.83  5100.0  878.33
  5120.0  879.77  5160.1  879.89  5220.1  882.79  5250.1  885.78  5352.6  888.57
#Mann=3,-1,0
  4384.6    0.05       0  5008.0   0.033       0  5012.0    0.05       0
Bank Sta=5008,5012
Exp/Cntr=0.3,0.1

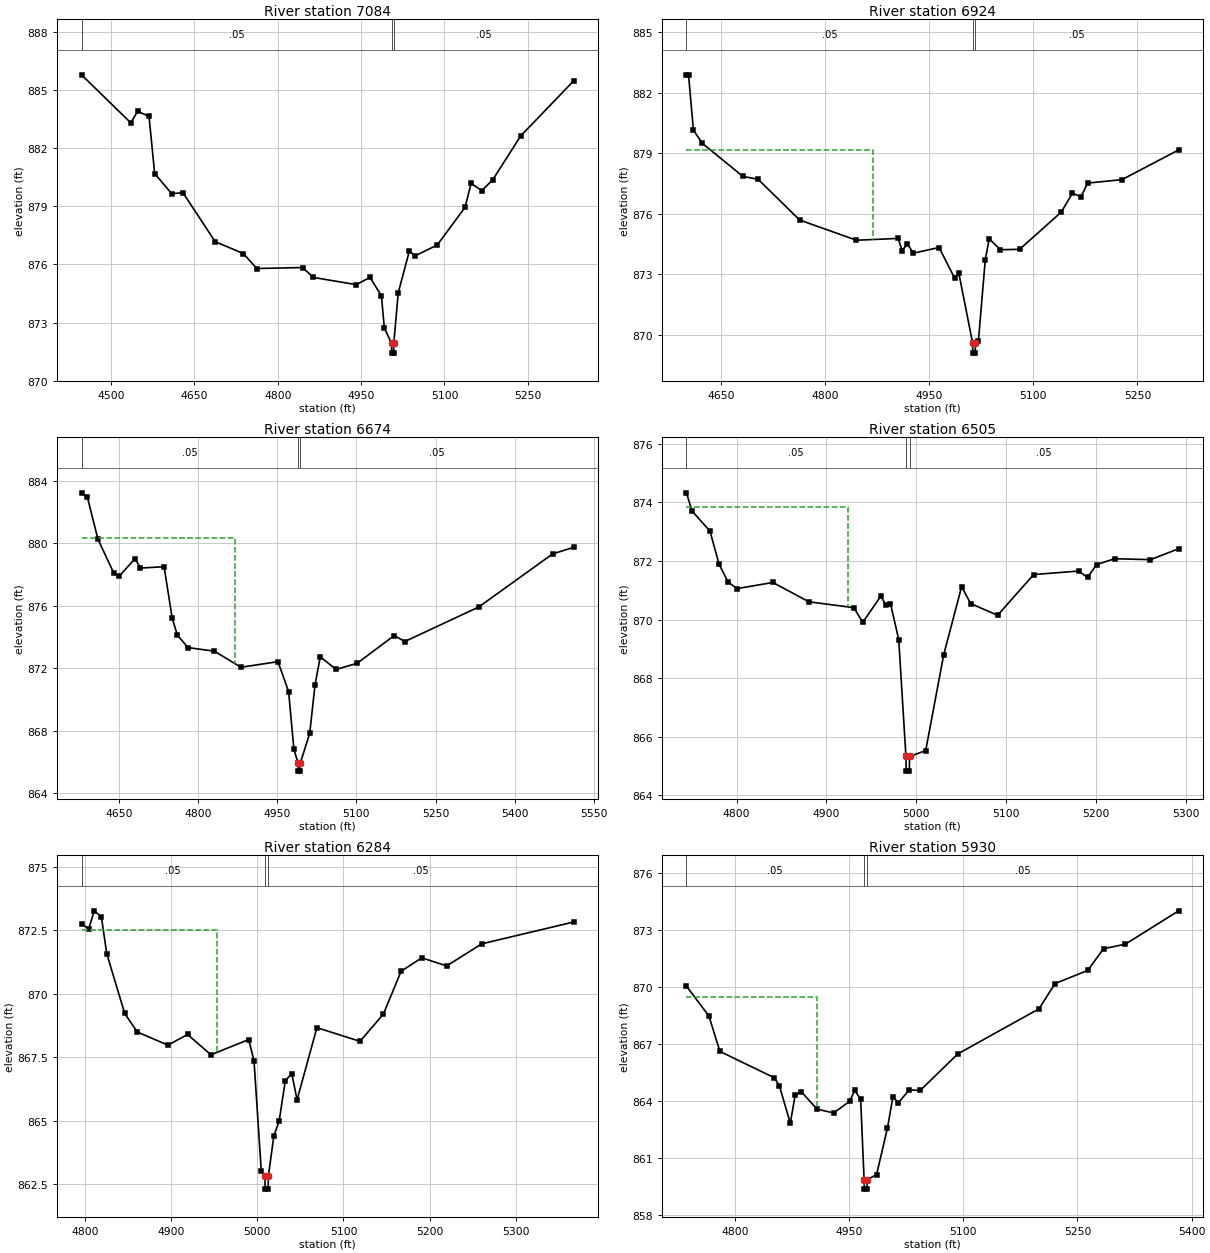
Type RM Length L Ch R = 1,7084,160,160,160
BEGIN DESCRIPTION:
MDW T 015 16.0
END DESCRIPTION:
XS GIS Cut Line= 3
      2281288.12      7116203.10      2280745.80      7116093.39
      2280413.77      7116073.99
#Sta/Elev= 30
  4446.7  885.77  4535.3  883.30  4547.8  883.89  4568.2  883.63  4578.4  880.68
  4609.0  879.65  4629.4  879.69  4687.4  877.17  4738.1  876.56  4762.1  875.79
  4844.7  875.84  4864.1  875.33  4941.0  874.96  4966.1  875.33  4986.5  874.38
  4991.8  872.72  5004.8  871.93  5005.1  871.43  5008.6  871.43  5008.8  871.93
  5016.8  874.54  5036.9  876.70  5046.9  876.44  5087.0  877.00  5137.0  878.94
  5148.0  880.18  5167.1  879.80  5187.1  880.37  5237.2  882.62  5332.6  885.46
#Mann=3,-1,0
  4446.7    0.05       0  5004.8   0.033       0  5008.8    0.05       0
Bank Sta=5004.8,5008.8
Exp/Cntr=0.3,0.1

Type RM Length L Ch R = 1,6924,250,250,250
BEGIN DESCRIPTION:
Mapping XS db75b4c0
END DESCRIPTION:
XS GIS Cut Line= 2
      2281179.36      7116151.62      2280555.16      7115814.55
#Sta/Elev= 30
  4600.0  882.88  4603.0  882.88  4610.0  880.14  4623.1  879.48  4681.4  877.85
  4703.2  877.71  4763.2  875.69  4845.1  874.69  4905.1  874.78  4910.8  874.18
  4918.6  874.51  4927.0  874.05  4964.1  874.33  4986.8  872.80  4992.6  873.06
  5012.5  869.60  5012.8  869.10  5016.3  869.10  5016.5  869.60  5020.9  869.72
  5030.7  873.72  5036.4  874.76  5052.6  874.22  5080.2  874.24  5140.2  876.08
  5156.4  877.02  5168.7  876.84  5178.3  877.52  5227.7  877.69  5309.4  879.16
#Mann=3,-1,0
  4600.0    0.05       0  5012.5   0.033       0  5016.5    0.05       0
#XS Ineff=2,0
    0.00 4868.70  879.14               0
Permanent Ineff=
       F       F
Bank Sta=5012.5,5016.5
Exp/Cntr=0.3,0.1

Type RM Length L Ch R = 1,6674,169,169,169
BEGIN DESCRIPTION:
MDW T 015 15.0
END DESCRIPTION:
XS GIS Cut Line= 3
      2281390.16      7115796.21      2280970.84      7115766.05
      2280459.16      7115761.48
#Sta/Elev= 30
  4579.6  883.24  4590.8  882.95  4610.8  880.26  4640.9  878.09  4650.9  877.90
  4681.0  879.03  4691.0  878.42  4736.0  878.51  4751.2  875.23  4761.2  874.12
  4781.3  873.33  4831.4  873.10  4881.5  872.07  4951.7  872.43  4971.8  870.51
  4981.8  866.82  4989.8  865.92  4990.1  865.42  4993.6  865.42  4993.8  865.92
  5011.8  867.84  5021.8  870.94  5031.8  872.74  5061.8  871.93  5101.8  872.33
  5171.8  874.10  5191.9  873.72  5331.9  875.93  5471.9  879.33  5511.7  879.75
#Mann=3,-1,0
  4579.6    0.05       0  4989.8   0.033       0  4993.8    0.05       0
#XS Ineff=2,0
    0.00 4870.50  880.33               0
Permanent Ineff=
       F       F
Bank Sta=4989.8,4993.8
Exp/Cntr=0.3,0.1

Type RM Length L Ch R = 1,6505,221,221,221
BEGIN DESCRIPTION:
Mapping XS af8807c3
END DESCRIPTION:
XS GIS Cut Line= 2
      2281285.23      7115617.17      2280737.66      7115611.84
#Sta/Elev= 30
  4744.2  874.33  4750.4  873.71  4770.4  873.02  4780.4  871.90  4790.4  871.29
  4800.4  871.06  4840.4  871.27  4880.4  870.61  4930.4  870.41  4940.4  869.91
  4960.4  870.80  4966.2  870.50  4971.2  870.55  4980.4  869.32  4988.4  865.33
  4988.7  864.83  4992.2  864.83  4992.4  865.33  5010.4  865.53  5030.4  868.80
  5050.4  871.13  5060.4  870.55  5090.4  870.15  5130.5  871.54  5180.5  871.66
  5190.5  871.44  5200.5  871.88  5220.5  872.08  5260.5  872.05  5291.8  872.42
#Mann=3,-1,0
  4744.2    0.05       0  4988.4   0.033       0  4992.4    0.05       0
#XS Ineff=2,0
    0.00 4923.50  873.85               0
Permanent Ineff=
       F       F
Bank Sta=4988.4,4992.4
Exp/Cntr=0.3,0.1

Type RM Length L Ch R = 1,6284,354,354,354
BEGIN DESCRIPTION:
Mapping XS 77df6535
END DESCRIPTION:
XS GIS Cut Line= 3
      2281100.75      7115250.51      2280876.81      7115550.42
      2280686.66      7115601.53
#Sta/Elev= 30
  4796.0  872.75  4804.4  872.55  4810.7  873.26  4819.0  873.03  4825.3  871.57
  4846.1  869.22  4860.7  868.49  4896.2  867.97  4919.1  868.39  4946.2  867.59
  4990.0  868.19  4996.2  867.35  5004.6  863.03  5008.8  862.80  5009.1  862.30
  5012.6  862.30  5012.8  862.80  5019.2  864.39  5025.4  864.99  5032.5  866.57
  5040.0  866.85  5046.2  865.82  5069.2  868.66  5119.2  868.12  5146.3  869.19
  5166.9  870.88  5190.9  871.41  5219.8  871.09  5260.5  871.96  5367.2  872.82
#Mann=3,-1,0
  4796.0    0.05       0  5008.8   0.033       0  5012.8    0.05       0
#XS Ineff=2,0
    0.00 4952.80  872.50               0
Permanent Ineff=
       F       F
Bank Sta=5008.8,5012.8
Exp/Cntr=0.3,0.1

Type RM Length L Ch R = 1,5930,254,254,254
BEGIN DESCRIPTION:
Mapping XS 61cf0096
END DESCRIPTION:
XS GIS Cut Line= 2
      2280947.60      7115056.78      2280450.37      7115469.80
#Sta/Elev= 30
  4736.5  870.04  4766.1  868.46  4780.4  866.61  4851.7  865.23  4858.5  864.81
  4872.9  862.84  4879.4  864.34  4887.2  864.50  4908.0  863.58  4929.7  863.38
  4951.0  863.99  4957.5  864.57  4965.3  864.09  4969.8  859.88  4970.1  859.38
  4973.6  859.38  4973.8  859.88  4986.2  860.14  5000.5  862.59  5007.7  864.23
  5014.8  863.91  5029.1  864.59  5043.5  864.56  5092.9  866.48  5199.7  868.85
  5220.5  870.17  5263.5  870.86  5284.3  872.00  5313.0  872.24  5382.9  873.99
#Mann=3,-1,0
  4736.5    0.05       0  4969.8   0.033       0  4973.8    0.05       0
#XS Ineff=2,0
    0.00 4908.40  869.49               0
Permanent Ineff=
       F       F
Bank Sta=4969.8,4973.8
Exp/Cntr=0.3,0.1

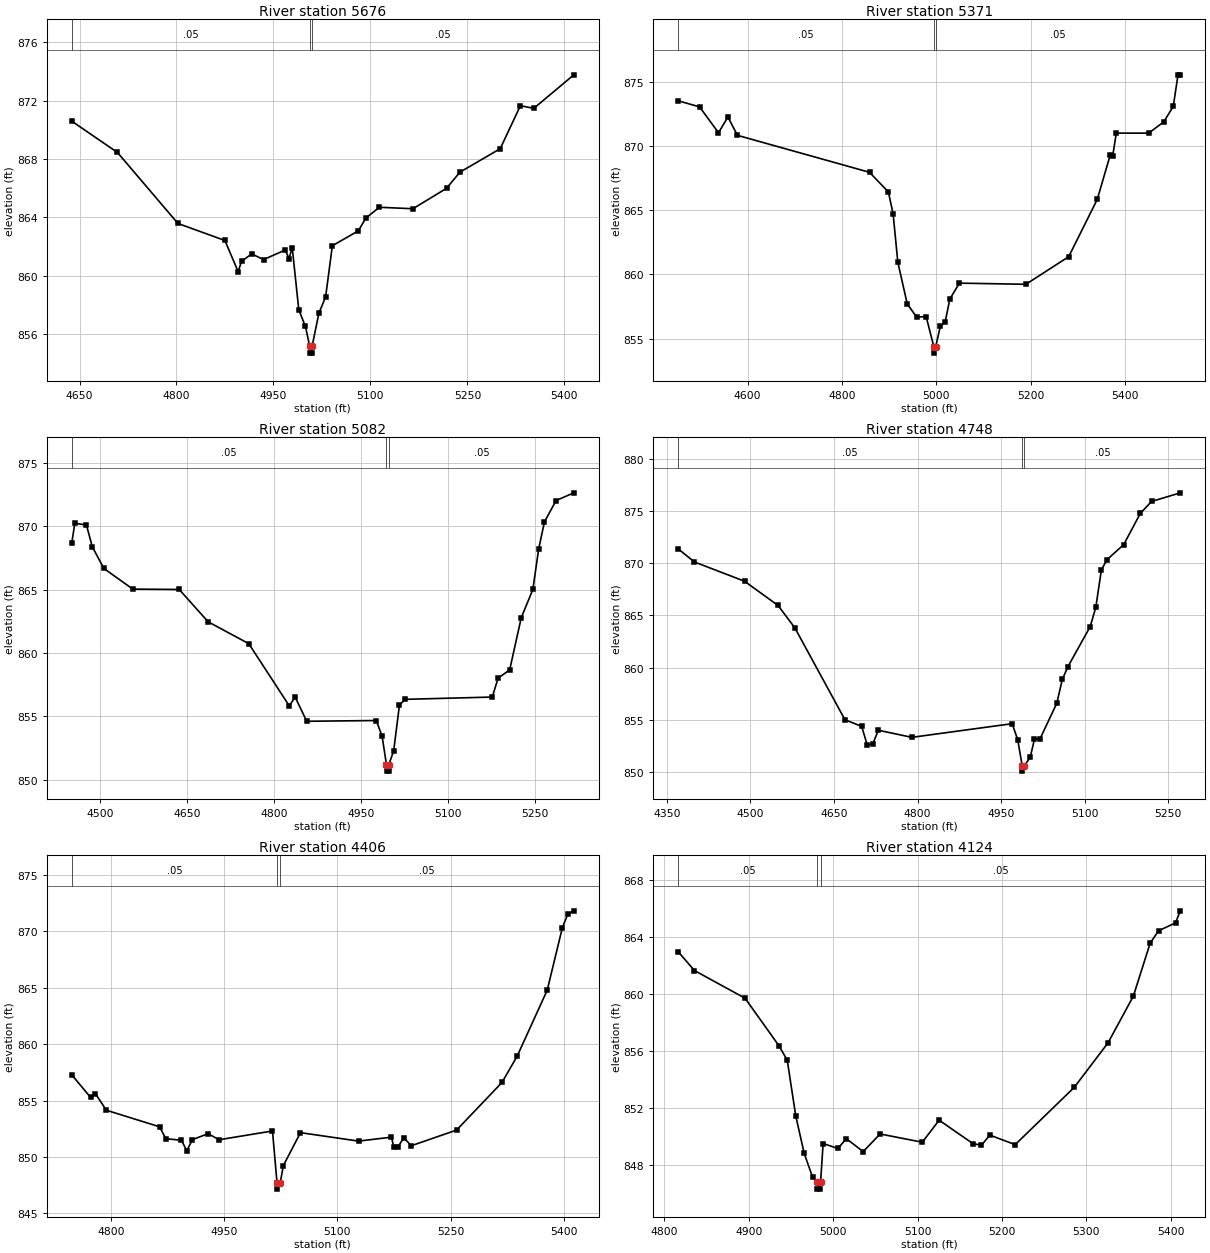
Type RM Length L Ch R = 1,5676,305,305,305
BEGIN DESCRIPTION:
Mapping XS aee242a0
END DESCRIPTION:
XS GIS Cut Line= 2
      2280977.02      7114913.89      2280229.38      7115124.38
#Sta/Elev= 30
  4638.0  870.60  4708.7  868.45  4802.2  863.58  4874.9  862.41  4895.4  860.27
  4900.6  860.98  4916.4  861.49  4934.7  861.10  4968.4  861.76  4973.9  861.17
  4979.1  861.90  4989.2  857.65  4999.5  856.51  5005.9  855.18  5006.2  854.68
  5009.7  854.68  5009.9  855.18  5020.3  857.42  5030.7  858.54  5041.1  862.05
  5081.2  863.07  5093.0  863.95  5113.8  864.69  5165.8  864.59  5217.7  865.99
  5238.5  867.10  5300.8  868.71  5332.0  871.66  5352.8  871.48  5414.7  873.78
#Mann=3,-1,0
  4638.0    0.05       0  5005.9   0.033       0  5009.9    0.05       0
Bank Sta=5005.9,5009.9
Exp/Cntr=0.3,0.1

Type RM Length L Ch R = 1,5371,289,289,289
BEGIN DESCRIPTION:
MDW T 015 12.0
END DESCRIPTION:
XS GIS Cut Line= 3
      2281214.33      7114719.81      2280667.53      7114719.90
      2280154.26      7114782.75
#Sta/Elev= 30
  4453.2  873.52  4498.5  873.04  4538.5  871.03  4558.5  872.26  4578.5  870.83
  4858.5  867.95  4898.5  866.42  4908.5  864.72  4918.5  860.95  4938.5  857.70
  4958.5  856.67  4978.5  856.72  4994.8  854.37  4995.0  853.87  4998.8  854.37
  5008.6  855.97  5018.7  856.28  5028.7  858.07  5048.9  859.32  5189.9  859.23
  5280.6  861.38  5341.1  865.84  5368.7  869.31  5373.7  869.19  5381.4  871.00
  5450.1  871.00  5482.1  871.88  5502.2  873.08  5512.2  875.54  5517.1  875.54
#Mann=3,-1,0
  4453.2    0.05       0  4994.8   0.033       0  4998.8    0.05       0
Bank Sta=4994.8,4998.8
Exp/Cntr=0.3,0.1

Type RM Length L Ch R = 1,5082,334,334,334
BEGIN DESCRIPTION:
MDW T 015 11.0
END DESCRIPTION:
XS GIS Cut Line= 3
      2281124.29      7114456.14      2280574.81      7114461.73
      2280258.36      7114471.33
#Sta/Elev= 30
  4450.5  868.69  4455.8  870.22  4475.8  870.10  4485.8  868.39  4505.8  866.67
  4555.8  865.04  4635.8  865.01  4685.8  862.46  4755.8  860.74  4825.8  855.83
  4835.8  856.53  4855.8  854.62  4975.8  854.68  4985.8  853.45  4993.4  851.19
  4993.7  850.69  4997.2  850.69  4997.4  851.19  5005.8  852.29  5015.8  855.91
  5025.8  856.35  5175.9  856.53  5185.9  858.02  5205.9  858.67  5225.9  862.79
  5245.9  865.01  5255.9  868.20  5265.9  870.34  5285.9  872.02  5316.6  872.63
#Mann=3,-1,0
  4450.5    0.05       0  4993.4   0.033       0  4997.4    0.05       0
Bank Sta=4993.4,4997.4
Exp/Cntr=0.3,0.1

Type RM Length L Ch R = 1,4748,342,342,342
BEGIN DESCRIPTION:
MDW T 015 10.0
END DESCRIPTION:
XS GIS Cut Line= 3
      2281108.01      7114172.94      2280478.85      7114160.00
      2280207.40      7114165.34
#Sta/Elev= 30
  4370.7  871.38  4399.7  870.13  4489.7  868.28  4549.7  865.96  4579.8  863.82
  4669.8  855.00  4699.8  854.36  4709.8  852.57  4719.8  852.70  4729.8  853.99
  4789.8  853.31  4969.8  854.62  4979.8  853.08  4987.8  850.57  4988.1  850.07
  4991.8  850.57  5002.4  851.43  5009.8  853.14  5019.8  853.17  5049.9  856.58
  5059.9  858.88  5069.9  860.09  5109.9  863.94  5119.9  865.79  5129.9  869.37
  5139.9  870.35  5169.9  871.79  5199.9  874.80  5219.9  875.93  5271.5  876.76
#Mann=3,-1,0
  4370.7    0.05       0  4987.8   0.033       0  4991.8    0.05       0
Bank Sta=4987.8,4991.8
Exp/Cntr=0.3,0.1

Type RM Length L Ch R = 1,4406,282,282,282
BEGIN DESCRIPTION:
Mapping XS 447a1710
END DESCRIPTION:
XS GIS Cut Line= 3
      2280869.75      7114073.32      2280529.18      7113811.06
      2280293.70      7113804.86
#Sta/Elev= 30
  4748.0  857.28  4772.9  855.28  4779.3  855.62  4793.8  854.14  4864.4  852.67
  4872.6  851.62  4893.4  851.47  4900.4  850.54  4907.9  851.53  4928.7  852.06
  4943.2  851.52  5014.0  852.30  5020.1  847.64  5020.3  847.14  5024.1  847.64
  5028.4  849.23  5051.1  852.15  5128.1  851.40  5171.6  851.75  5174.8  850.89
  5180.4  850.89  5188.0  851.70  5198.0  850.99  5258.0  852.38  5318.1  856.60
  5338.1  858.91  5378.1  864.79  5398.1  870.31  5405.6  871.58  5413.4  871.83
#Mann=3,-1,0
  4748.0    0.05       0  5020.1   0.033       0  5024.1    0.05       0
Bank Sta=5020.1,5024.1
Exp/Cntr=0.3,0.1

Type RM Length L Ch R = 1,4124,144,144,144
BEGIN DESCRIPTION:
Mapping XS afcef8d5
END DESCRIPTION:
XS GIS Cut Line= 2
      2280898.16      7113691.07      2280303.33      7113704.89
#Sta/Elev= 30
  4816.3  862.97  4835.5  861.65  4895.5  859.70  4935.5  856.37  4945.5  855.34
  4955.5  851.44  4965.5  848.80  4975.5  847.11  4981.0  846.77  4981.3  846.27
  4984.8  846.27  4985.0  846.77  4988.0  849.48  5005.5  849.13  5015.5  849.82
  5035.5  848.91  5055.5  850.15  5105.5  849.57  5125.5  851.12  5165.6  849.47
  5175.6  849.36  5185.6  850.07  5215.6  849.40  5285.6  853.43  5325.6  856.56
  5355.6  859.84  5375.6  863.58  5385.6  864.45  5405.6  865.00  5411.3  865.85
#Mann=3,-1,0
  4816.3    0.05       0  4981.0   0.033       0  4985.0    0.05       0
Bank Sta=4981,4985
Exp/Cntr=0.3,0.1

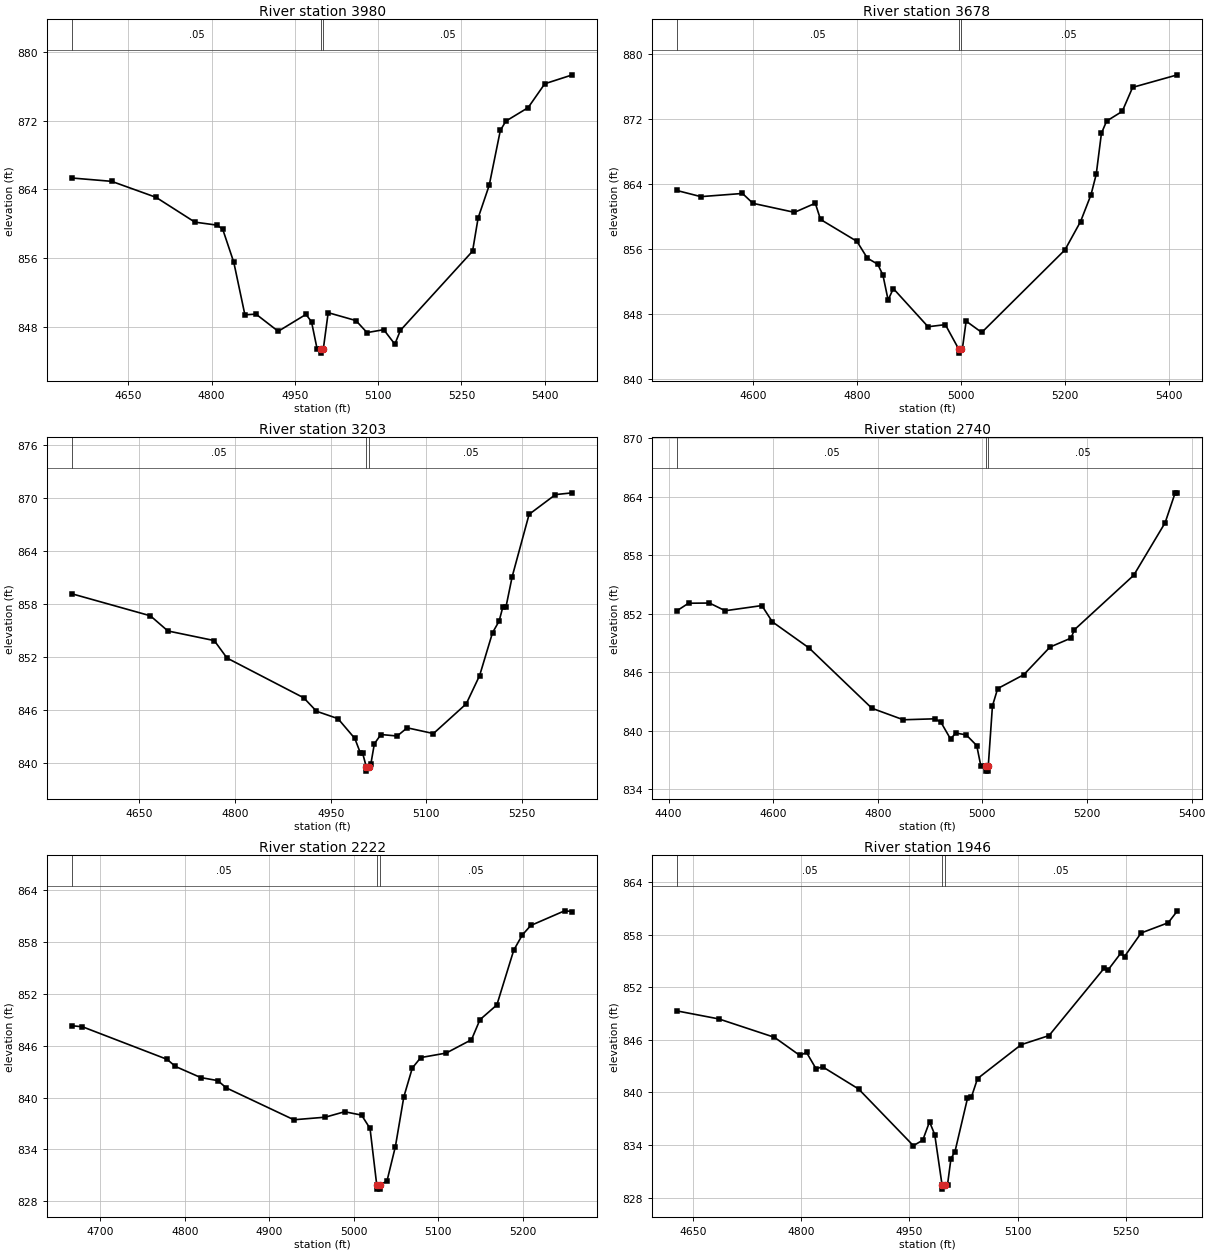
Type RM Length L Ch R = 1,3980,302,302,302
BEGIN DESCRIPTION:
MDW T 015 9.0
END DESCRIPTION:
XS GIS Cut Line= 3
      2281080.87      7113573.98      2280628.91      7113585.04
      2280179.19      7113597.85
#Sta/Elev= 30
  4547.9  865.33  4619.8  864.94  4699.8  863.08  4769.8  860.19  4809.8  859.84
  4819.9  859.37  4839.9  855.51  4859.9  849.40  4879.9  849.48  4919.9  847.48
  4969.9  849.45  4979.9  848.59  4989.9  845.45  4997.2  845.44  4997.5  844.94
  5001.2  845.44  5009.9  849.65  5059.9  848.73  5079.9  847.33  5110.0  847.67
  5130.0  845.98  5140.0  847.59  5270.0  856.81  5280.0  860.67  5300.0  864.48
  5320.0  870.86  5330.0  871.95  5370.1  873.52  5400.1  876.30  5449.9  877.34
#Mann=3,-1,0
  4547.9    0.05       0  4997.2   0.033       0  5001.2    0.05       0
Bank Sta=4997.2,5001.2
Exp/Cntr=0.3,0.1

Type RM Length L Ch R = 1,3678,475,475,475
BEGIN DESCRIPTION:
MDW T 015 8.0
END DESCRIPTION:
XS GIS Cut Line= 3
      2281075.45      7113313.56      2280528.56      7113315.18
      2280112.91      7113326.56
#Sta/Elev= 30
  4453.1  863.20  4499.6  862.44  4579.6  862.83  4599.6  861.62  4679.6  860.51
  4719.6  861.63  4729.6  859.64  4799.6  856.95  4819.6  854.89  4839.6  854.14
  4849.6  852.81  4859.6  849.74  4869.6  851.15  4936.4  846.46  4969.6  846.72
  4995.3  843.72  4995.5  843.22  4999.3  843.72  5002.3  843.72  5009.6  847.15
  5039.6  845.76  5199.6  855.90  5229.6  859.38  5249.7  862.68  5259.7  865.18
  5269.7  870.22  5279.7  871.72  5309.7  872.91  5329.7  875.86  5415.8  877.40
#Mann=3,-1,0
  4453.1    0.05       0  4995.3   0.033       0  4999.3    0.05       0
Bank Sta=4995.3,4999.3
Exp/Cntr=0.3,0.1

Type RM Length L Ch R = 1,3203,463,463,463
BEGIN DESCRIPTION:
MDW T 015 7.0
END DESCRIPTION:
XS GIS Cut Line= 3
      2281032.01      7112906.66      2280577.03      7112871.97
      2280257.29      7112951.16
#Sta/Elev= 30
  4543.7  859.15  4667.1  856.65  4694.6  854.93  4767.4  853.84  4787.4  851.86
  4907.8  847.35  4927.8  845.83  4961.5  844.99  4988.0  842.74  4996.5  841.12
  5000.0  841.12  5005.9  839.54  5006.1  839.04  5009.9  839.54  5013.0  839.80
  5018.6  842.14  5028.9  843.19  5054.4  843.02  5070.1  843.95  5111.3  843.30
  5162.8  846.67  5183.8  849.88  5204.0  854.73  5214.3  856.04  5220.0  857.59
  5225.2  857.68  5234.9  861.10  5261.4  868.15  5302.8  870.39  5329.4  870.59
#Mann=3,-1,0
  4543.7    0.05       0  5005.9   0.033       0  5009.9    0.05       0
Bank Sta=5005.9,5009.9
Exp/Cntr=0.3,0.1

Type RM Length L Ch R = 1,2740,518,518,518
BEGIN DESCRIPTION:
MDW T 015 6.0
END DESCRIPTION:
XS GIS Cut Line= 3
      2280961.51      7112585.48      2280378.19      7112549.97
      2280005.54      7112560.53
#Sta/Elev= 30
  4415.6  852.29  4438.2  853.08  4478.2  853.10  4508.3  852.31  4578.4  852.84
  4598.5  851.17  4668.6  848.49  4788.8  842.30  4848.9  841.12  4909.0  841.22
  4920.7  840.87  4939.1  839.15  4949.1  839.76  4969.1  839.57  4989.2  838.47
  4997.1  836.36  5007.2  836.35  5007.4  835.85  5010.9  835.85  5011.2  836.35
  5019.2  842.54  5029.2  844.32  5079.2  845.75  5129.2  848.58  5169.3  849.50
  5175.9  850.36  5289.3  855.95  5349.3  861.34  5368.5  864.41  5372.8  864.41
#Mann=3,-1,0
  4415.6    0.05       0  5007.2   0.033       0  5011.2    0.05       0
Bank Sta=5007.2,5011.2
Exp/Cntr=0.3,0.1

Type RM Length L Ch R = 1,2222,276,276,276
BEGIN DESCRIPTION:
Mapping XS 3619e133
END DESCRIPTION:
XS GIS Cut Line= 2
      2280711.67      7112174.94      2280119.69      7112155.46
#Sta/Elev= 30
  4666.3  848.32  4679.0  848.20  4779.0  844.43  4789.0  843.60  4819.0  842.31
  4839.1  841.96  4849.1  841.12  4929.1  837.42  4966.3  837.72  4989.1  838.35
  5009.2  837.96  5019.2  836.41  5027.1  829.88  5027.4  829.38  5030.9  829.38
  5031.2  829.88  5039.2  830.31  5049.2  834.32  5059.2  840.09  5069.2  843.42
  5079.2  844.63  5109.2  845.15  5139.2  846.70  5149.2  849.02  5169.2  850.73
  5189.2  857.08  5199.3  858.84  5209.3  859.94  5249.3  861.64  5258.6  861.56
#Mann=3,-1,0
  4666.3    0.05       0  5027.1   0.033       0  5031.2    0.05       0
Bank Sta=5027.1,5031.2
Exp/Cntr=0.3,0.1

Type RM Length L Ch R = 1,1946,418,418,418
BEGIN DESCRIPTION:
MDW T 015 4.0
END DESCRIPTION:
XS GIS Cut Line= 3
      2280800.98      7112088.54      2280469.54      7111918.97
      2280177.48      7111784.33
#Sta/Elev= 30
  4627.7  849.31  4686.1  848.39  4763.2  846.29  4798.4  844.22  4807.6  844.57
  4820.9  842.69  4829.8  842.93  4879.8  840.39  4955.7  833.92  4968.7  834.55
  4978.1  836.65  4985.3  835.18  4995.4  829.46  4995.7  828.96  4999.5  829.46
  5003.0  829.46  5007.8  832.45  5013.3  833.23  5030.7  839.33  5036.2  839.49
  5044.6  841.58  5105.1  845.45  5143.7  846.49  5219.9  854.16  5225.4  853.97
  5242.8  855.86  5248.3  855.51  5271.3  858.20  5308.9  859.37  5321.6  860.73
#Mann=3,-1,0
  4627.7    0.05       0  4995.4   0.033       0  4999.5    0.05       0
Bank Sta=4995.4,4999.5
Exp/Cntr=0.3,0.1

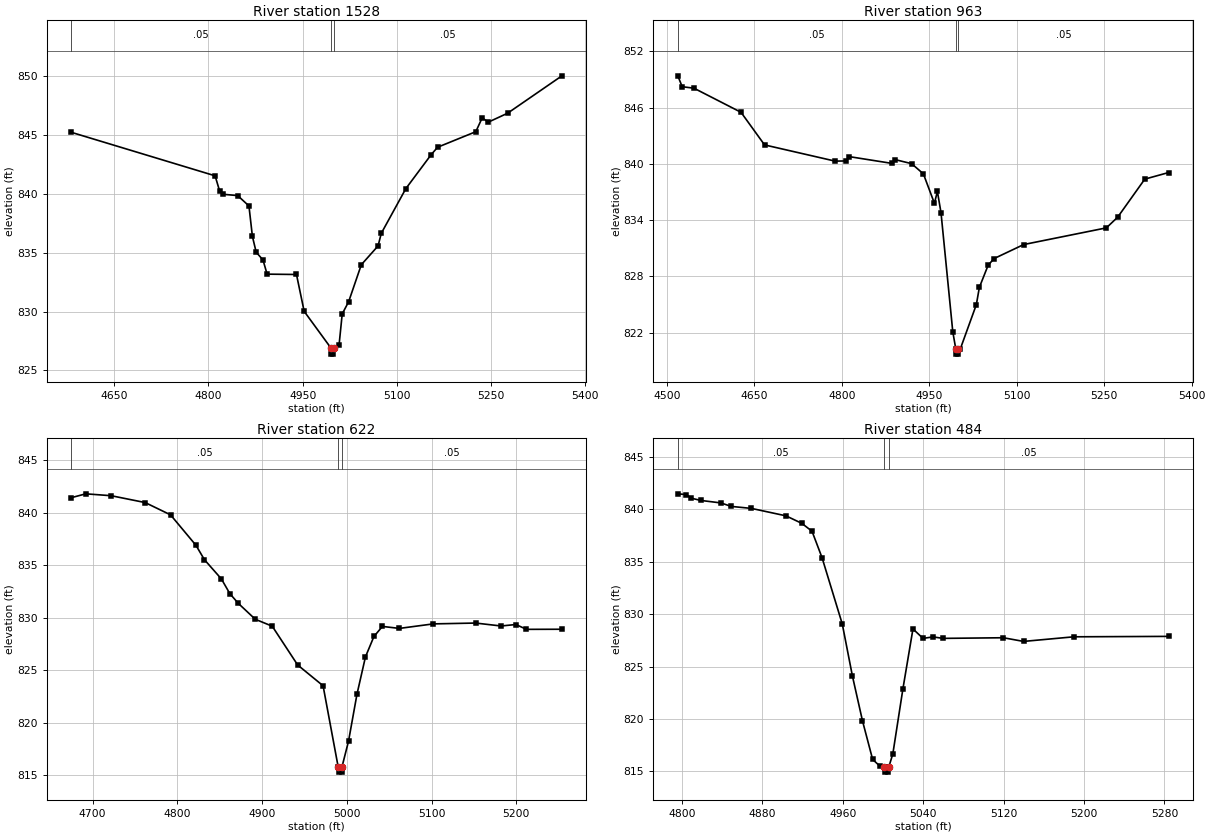
Type RM Length L Ch R = 1,1528,565,565,565
BEGIN DESCRIPTION:
MDW T 015 3.0
END DESCRIPTION:
XS GIS Cut Line= 3
      2280828.99      7111959.98      2280661.77      7111576.24
      2280303.59      7111519.15
#Sta/Elev= 30
  4581.4  845.25  4810.5  841.55  4817.6  840.28  4823.0  839.98  4846.4  839.87
  4864.4  838.99  4869.9  836.40  4875.9  835.06  4886.8  834.39  4893.3  833.19
  4940.1  833.16  4952.3  830.03  4995.2  826.89  4995.5  826.39  4999.0  826.39
  4999.3  826.89  5007.9  827.17  5012.9  829.81  5023.1  830.84  5043.3  833.99
  5070.0  835.59  5075.1  836.66  5114.2  840.46  5154.7  843.36  5164.8  843.98
  5225.6  845.30  5235.7  846.47  5245.8  846.12  5276.2  846.87  5362.7  850.05
#Mann=3,-1,0
  4581.4    0.05       0  4995.2   0.033       0  4999.3    0.05       0
Bank Sta=4995.2,4999.3
Exp/Cntr=0.3,0.1

Type RM Length L Ch R = 1,963,341,341,341
BEGIN DESCRIPTION:
MDW T 015 2.0
END DESCRIPTION:
XS GIS Cut Line= 3
      2281406.44      7111196.16      2280929.00      7111260.00
      2280572.66      7111310.56
#Sta/Elev= 30
  4518.7  849.40  4526.2  848.24  4546.4  848.08  4627.1  845.51  4667.5  842.03
  4788.5  840.30  4807.7  840.32  4812.7  840.78  4885.8  840.06  4890.8  840.47
  4919.7  840.03  4939.9  838.94  4958.8  835.80  4963.9  837.07  4970.1  834.80
  4990.3  822.10  4995.6  820.21  4996.1  819.71  4999.7  819.71  5000.1  820.21
  5002.9  820.21  5030.7  824.99  5035.9  826.83  5050.9  829.19  5061.0  829.90
  5111.9  831.40  5253.7  833.18  5273.1  834.32  5319.6  838.38  5360.3  839.08
#Mann=3,-1,0
  4518.7    0.05       0  4995.6   0.033       0  5000.1    0.05       0
Bank Sta=4995.6,5000.1
Exp/Cntr=0.3,0.1

Type RM Length L Ch R = 1,622,138,138,138
BEGIN DESCRIPTION:
Mapping XS fefd50f8
END DESCRIPTION:
XS GIS Cut Line= 2
      2281256.20      7110971.91      2280677.25      7110964.32
#Sta/Elev= 30
  4674.8  841.43  4692.0  841.80  4722.0  841.62  4762.0  840.97  4792.0  839.80
  4822.0  836.90  4832.0  835.53  4852.0  833.70  4862.0  832.30  4872.0  831.37
  4892.0  829.86  4912.0  829.20  4942.0  825.51  4972.0  823.53  4989.8  815.81
  4990.2  815.31  4993.8  815.31  4994.3  815.81  5002.0  818.25  5012.0  822.73
  5022.0  826.28  5032.0  828.22  5042.0  829.18  5062.0  828.99  5102.0  829.42
  5152.0  829.50  5182.0  829.22  5199.5  829.36  5212.0  828.90  5253.8  828.91
#Mann=3,-1,0
  4674.8    0.05       0  4989.8   0.033       0  4994.3    0.05       0
Bank Sta=4989.8,4994.3
Exp/Cntr=0.3,0.1

Type RM Length L Ch R = 1,484,0,0,0
BEGIN DESCRIPTION:
MDW T 015 1.0
END DESCRIPTION:
XS GIS Cut Line= 3
      2281181.79      7110824.06      2280978.86      7110844.94
      2280694.86      7110852.68
#Sta/Elev= 30
  4796.0  841.49  4804.5  841.42  4809.5  841.07  4818.9  840.86  4839.0  840.62
  4849.1  840.29  4869.2  840.10  4903.6  839.39  4919.4  838.67  4929.5  837.92
  4939.5  835.39  4959.6  829.07  4969.7  824.10  4979.7  819.83  4989.8  816.15
  4997.4  815.48  5001.4  815.44  5001.8  814.94  5005.4  814.94  5005.9  815.44
  5009.9  816.69  5019.9  822.88  5029.9  828.60  5039.9  827.70  5049.9  827.84
  5059.9  827.70  5119.9  827.76  5139.9  827.41  5189.9  827.85  5284.1  827.89
#Mann=3,-1,0
  4796.0    0.05       0  5001.4   0.033       0  5005.9    0.05       0
Bank Sta=5001.4,5005.9
Exp/Cntr=0.3,0.1

Chan Stop Cuts=-1