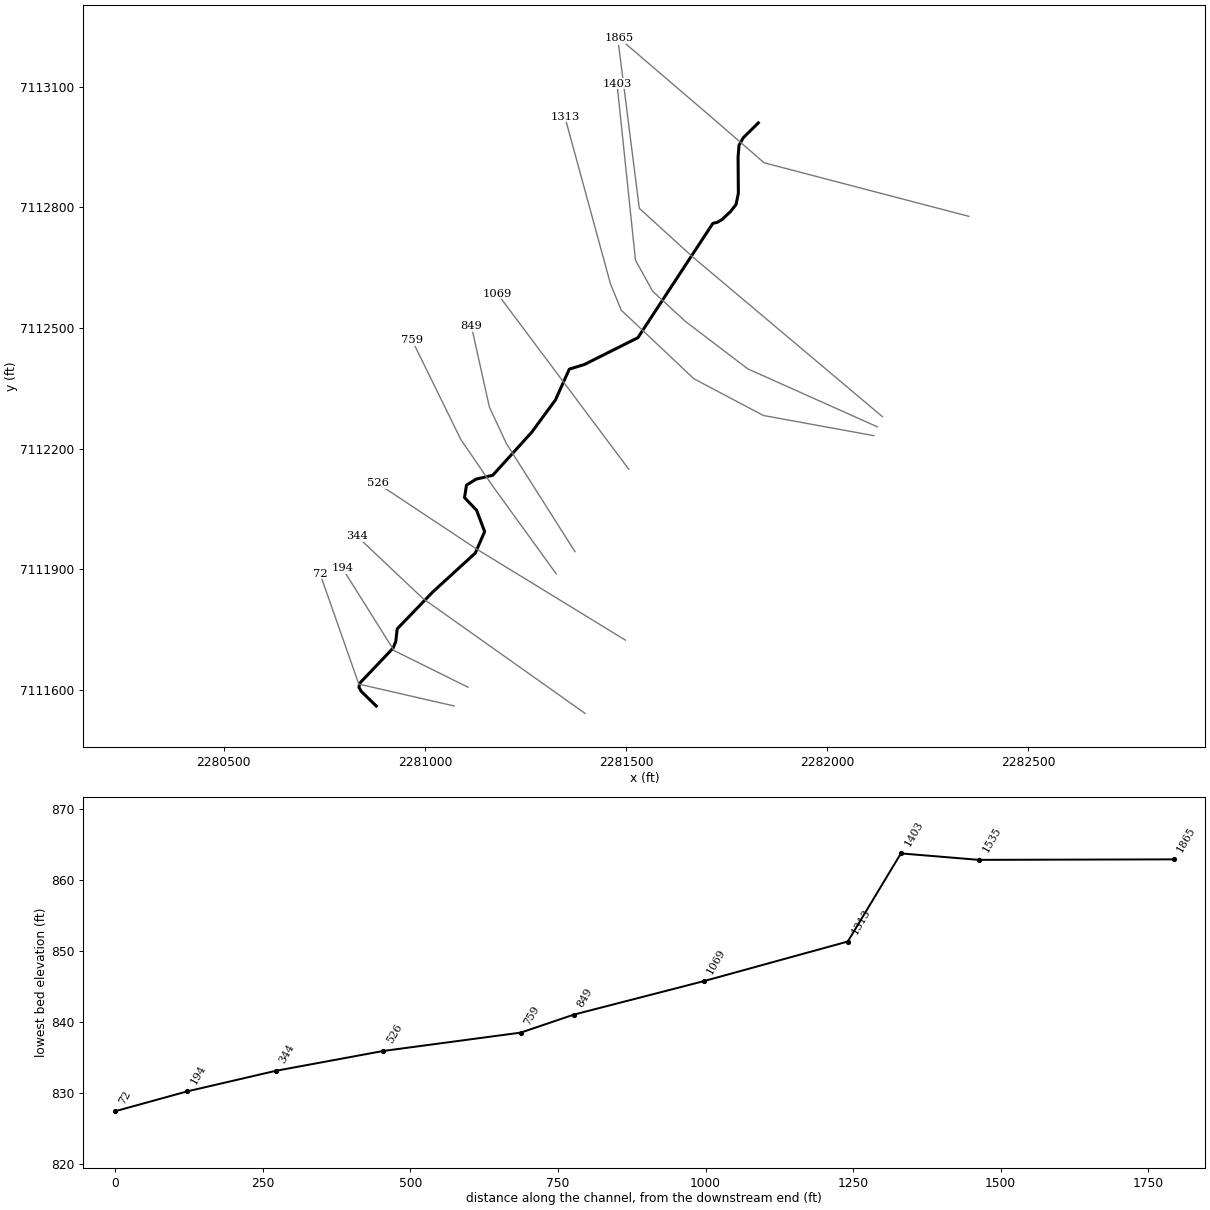
--- MDW T 016.prj (project) ---

Proj Title=MDW T 016 Base Level Engineering
Current Plan=p01
Default Exp/Contr=0.3,0.1
English Units
Geom File=g01
Flow File=f01
Plan File=p01
BEGIN DESCRIPTION:
MDW T 016
END DESCRIPTION:

--- MDW T 016.p01 (plan) ---

Plan Title=Multiple Run
Short Identifier=Multiple
Geom File=g01
Flow File=f01
Subcritical Flow
K Sum by GR= 0
Std Step Tol= 0.01
Critical Tol= 0.01
Num of Std Step Trials= 20
Max Error Tol= 0.3
Flow Tol Ratio= 0.001
Split Flow NTrial= 30
Split Flow Tol= 0.02
Split Flow Ratio= 0.02
Log Output Level= 0
Friction Slope Method= 1
Unsteady Friction Slope Method= 2
Unsteady Bridges Friction Slope Method= 1
Parabolic Critical Depth
Global Vel Dist=  1 , 1 , 1
Global Log Level= 0
CheckData=True
Encroach Param= -1, 0, 0, 0
BEGIN DESCRIPTION:
Multiple Run
END DESCRIPTION:

--- MDW T 016.f01 (steady flow) ---

Flow Title=Multiple
Number of Profiles=7
Profile Names=10-year,25-year,50-year,1pct_min,100-year,1pct_plu,500-year
River Rch & RM= MDW T 016,Reach-1,1865
     198     254     297     174     347     693     472
Boundary for River Rch & Prof#=MDW T 016,Reach-1,1
Up Type=0
Dn Type=3
Dn Slope=0.005
Boundary for River Rch & Prof#=MDW T 016,Reach-1,2
Up Type=0
Dn Type=3
Dn Slope=0.005
Boundary for River Rch & Prof#=MDW T 016,Reach-1,3
Up Type=0
Dn Type=3
Dn Slope=0.005
Boundary for River Rch & Prof#=MDW T 016,Reach-1,4
Up Type=0
Dn Type=3
Dn Slope=0.005
Boundary for River Rch & Prof#=MDW T 016,Reach-1,5
Up Type=0
Dn Type=3
Dn Slope=0.005
Boundary for River Rch & Prof#=MDW T 016,Reach-1,6
Up Type=0
Dn Type=3
Dn Slope=0.005
Boundary for River Rch & Prof#=MDW T 016,Reach-1,7
Up Type=0
Dn Type=3
Dn Slope=0.005

--- MDW T 016.g01 (geometry) ---

Geom Title=Existing Conditions

River Reach=MDW T 016,Reach-1
Reach XY= 30
      2281829.00      7113010.00      2281791.92      7112973.50
      2281780.91      7112954.21      2281778.64      7112925.15
      2281779.32      7112834.78      2281773.64      7112807.22
      2281759.56      7112789.24      2281739.06      7112770.03
      2281727.61      7112763.02      2281715.92      7112760.17
      2281529.43      7112475.83      2281396.46      7112409.27
      2281359.02      7112397.74      2281324.38      7112320.96
      2281265.21      7112240.51      2281168.75      7112133.94
      2281126.95      7112124.08      2281103.26      7112109.25
      2281098.51      7112078.29      2281128.42      7112046.80
      2281148.44      7111993.74      2281125.13      7111940.27
      2281020.61      7111844.78      2280931.10      7111751.99
      2280927.44      7111720.64      2280920.81      7111703.95
      2280837.79      7111616.66      2280835.96      7111606.66
      2280841.51      7111596.66      2280879.00      7111560.00

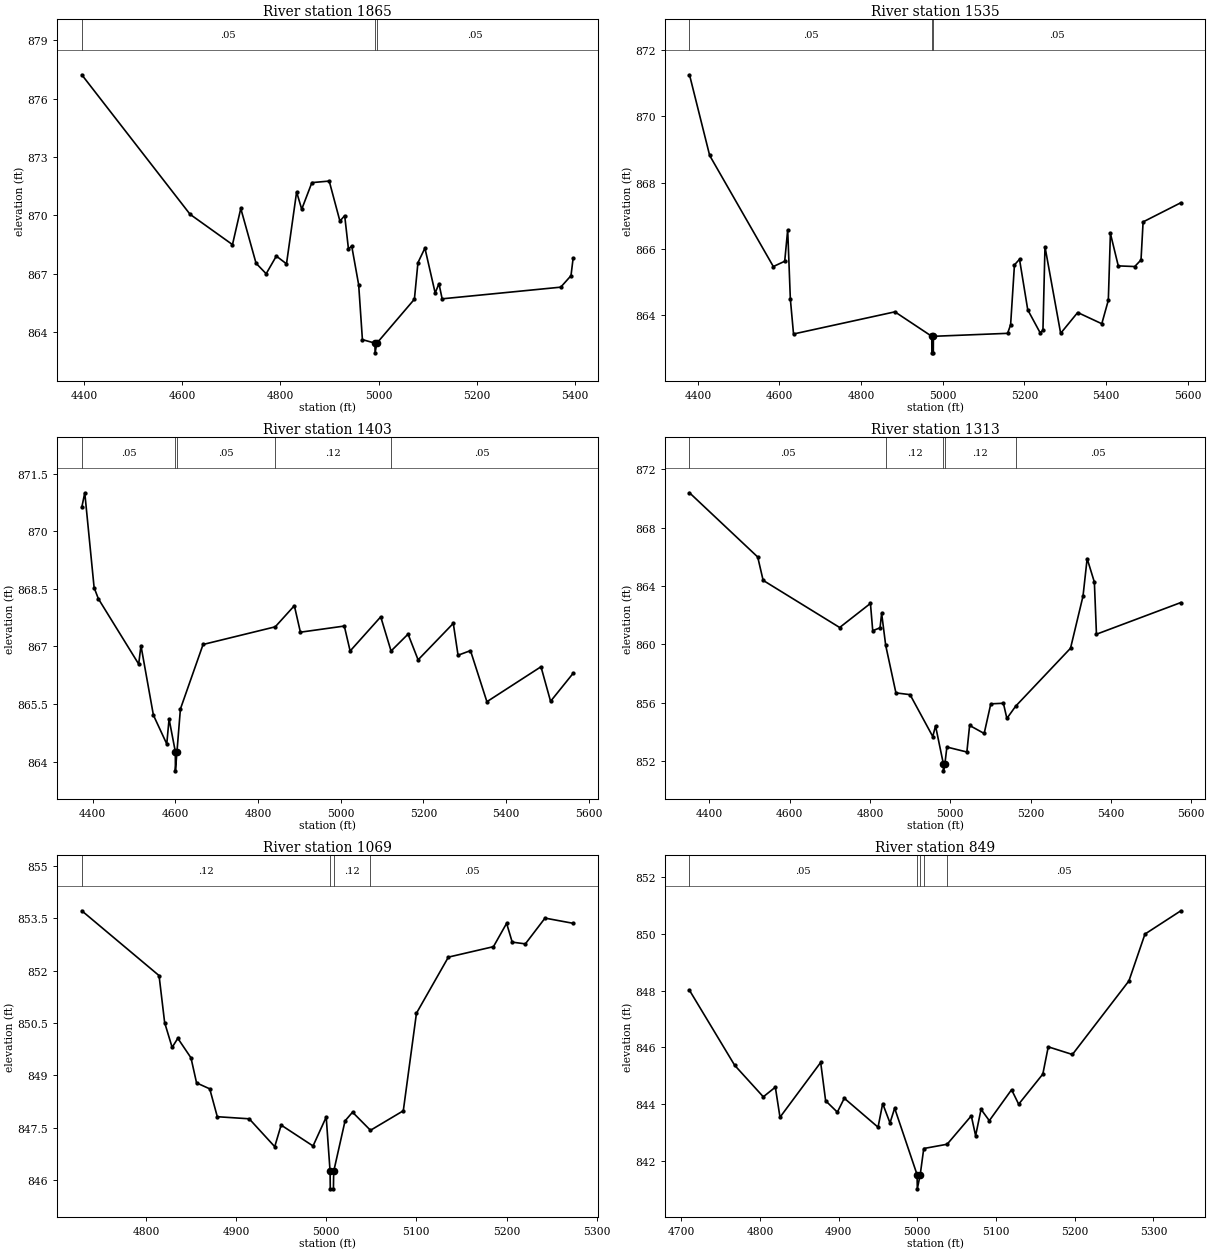
Type RM Length L Ch R = 1,1865,330,330,330
BEGIN DESCRIPTION:
MDW T 016 5.0
END DESCRIPTION:
XS GIS Cut Line= 4
      2282352.30      7112777.69      2281843.43      7112910.82
      2281710.53      7113025.89      2281483.45      7113220.27
#Sta/Elev= 30
  4395.4  877.23  4615.9  870.05  4702.3  868.49  4719.2  870.35  4750.3  867.53
  4770.9  866.99  4791.6  867.90  4812.3  867.50  4832.9  871.20  4843.3  870.31
  4864.0  871.68  4899.3  871.76  4921.1  869.70  4930.8  869.98  4938.5  868.26
  4945.1  868.42  4959.3  866.42  4966.9  863.60  4992.4  863.42  4992.7  862.92
  4996.4  863.42  5072.8  865.68  5080.0  867.56  5094.2  868.31  5115.1  866.00
  5122.8  866.48  5129.3  865.70  5370.8  866.30  5391.7  866.89  5396.1  867.80
#Mann=3,-1,0
  4395.4    0.05       0  4992.4   0.035       0  4996.4    0.05       0
Bank Sta=4992.4,4996.4
Exp/Cntr=0.3,0.1

Type RM Length L Ch R = 1,1535,132,132,132
BEGIN DESCRIPTION:
MDW T 016 4.0
END DESCRIPTION:
XS GIS Cut Line= 4
      2282137.47      7112279.59      2281666.50      7112676.09
      2281533.00      7112797.66      2281481.79      7113202.12
#Sta/Elev= 30
  4379.5  871.26  4428.9  868.82  4584.9  865.46  4612.8  865.62  4620.1  866.57
  4626.6  864.48  4634.4  863.42  4882.8  864.09  4973.1  863.35  4973.4  862.85
  4976.9  862.85  4977.1  863.35  5158.9  863.44  5166.3  863.70  5175.7  865.51
  5188.1  865.68  5208.3  864.15  5238.5  863.46  5245.5  863.53  5250.5  866.06
  5288.9  863.44  5330.6  864.07  5389.7  863.73  5405.7  864.44  5410.8  866.46
  5430.1  865.48  5470.4  865.46  5485.8  865.66  5490.9  866.81  5583.4  867.39
#Mann=3,-1,0
  4379.5    0.05       0  4973.1   0.033       0  4977.1    0.05       0
Bank Sta=4973.1,4977.1
Exp/Cntr=0.3,0.1

Type RM Length L Ch R = 1,1403,90,90,90
BEGIN DESCRIPTION:
MDW T 016 3.7
END DESCRIPTION:
XS GIS Cut Line= 6
      2282125.16      7112254.16      2281802.76      7112398.42
      2281647.65      7112516.38      2281566.02      7112591.61
      2281523.52      7112668.77      2281477.63      7113106.96
#Sta/Elev= 30
  4374.0  870.62  4381.2  871.00  4403.8  868.53  4414.1  868.24  4511.6  866.54
  4517.1  867.02  4547.2  865.21  4579.5  864.46  4585.1  865.11  4600.2  864.26
  4600.4  863.76  4604.2  864.26  4612.5  865.37  4667.3  867.05  4841.9  867.51
  4888.1  868.06  4902.7  867.37  5008.9  867.53  5023.0  866.88  5097.0  867.77
  5122.0  866.88  5163.1  867.32  5187.4  866.65  5272.5  867.60  5284.0  866.77
  5314.1  866.89  5353.8  865.56  5484.6  866.47  5507.8  865.57  5562.4  866.30
#Mann=5,-1,0
  4374.0    0.05       0  4600.2    0.07       0  4604.2    0.05       0
  4841.9    0.12       0  5122.0    0.05       0
Bank Sta=4600.2,4604.2
Exp/Cntr=0.3,0.1

Type RM Length L Ch R = 1,1313,244,244,244
BEGIN DESCRIPTION:
MDW T 016 3.5
END DESCRIPTION:
XS GIS Cut Line= 6
      2282116.19      7112232.36      2281841.73      7112282.43
      2281668.61      7112373.84      2281488.20      7112544.30
      2281461.47      7112609.21      2281347.89      7113025.22
#Sta/Elev= 30
  4350.2  870.38  4520.2  865.98  4533.7  864.38  4724.4  861.15  4801.1  862.80
  4806.8  860.93  4825.0  861.13  4829.0  862.12  4839.1  859.93  4864.6  856.67
  4899.8  856.55  4956.4  853.68  4963.3  854.41  4982.7  851.83  4983.0  851.33
  4986.7  851.83  4991.6  852.96  5041.4  852.62  5048.2  854.44  5084.5  853.89
  5101.0  855.92  5132.4  855.96  5141.1  854.92  5163.0  855.76  5299.7  859.73
  5330.8  863.30  5341.1  865.87  5359.1  864.26  5364.3  860.69  5574.6  862.86
#Mann=5,-1,0
  4350.2    0.05       0  4839.1    0.12       0  4982.7    0.07       0
  4986.7    0.12       0  5163.0    0.05       0
Bank Sta=4982.7,4986.7
Exp/Cntr=0.3,0.1

Type RM Length L Ch R = 1,1069,220,220,220
BEGIN DESCRIPTION:
Mapping XS 04f10bef
END DESCRIPTION:
XS GIS Cut Line= 2
      2281506.99      7112148.66      2281180.47      7112585.02
#Sta/Elev= 30
  4728.9  853.72  4814.6  851.86  4820.8  850.51  4829.1  849.80  4835.4  850.06
  4850.0  849.50  4856.2  848.78  4870.8  848.61  4879.2  847.81  4914.6  847.75
  4942.9  846.95  4950.0  847.57  4985.4  846.97  5000.0  847.80  5004.3  846.24
  5004.5  845.74  5008.0  845.74  5008.3  846.24  5020.9  847.69  5029.2  847.94
  5049.1  847.42  5085.5  847.98  5100.1  850.78  5135.5  852.39  5185.5  852.69
  5200.1  853.36  5206.3  852.82  5220.9  852.77  5242.7  853.51  5273.9  853.36
#Mann=4,-1,0
  4728.9    0.12       0  5004.3    0.07       0  5008.3    0.12       0
  5049.1    0.05       0
Bank Sta=5004.3,5008.3
Exp/Cntr=0.3,0.1

Type RM Length L Ch R = 1,849,90,90,90
BEGIN DESCRIPTION:
Mapping XS 11ce8884
END DESCRIPTION:
XS GIS Cut Line= 4
      2281373.07      7111943.88      2281202.41      7112212.90
      2281160.29      7112303.30      2281115.57      7112504.47
#Sta/Elev= 30
  4710.5  848.01  4767.9  845.37  4804.3  844.26  4819.6  844.60  4825.5  843.54
  4877.2  845.47  4883.5  844.12  4898.4  843.72  4907.2  844.21  4950.1  843.19
  4956.0  844.02  4965.3  843.34  4971.2  843.86  4999.7  841.52  5000.0  841.02
  5003.7  841.52  5008.2  842.44  5037.9  842.59  5068.6  843.59  5074.1  842.89
  5081.0  843.82  5091.5  843.42  5119.8  844.51  5128.8  844.00  5159.5  845.06
  5166.4  846.02  5197.1  845.75  5268.9  848.34  5289.3  849.99  5334.9  850.81
#Mann=5,-1,0
  4710.5    0.05       0  4999.7   0.033       0  5003.7    0.05       0
  5008.2    0.12       0  5037.9    0.05       0
Bank Sta=4999.7,5003.7
Exp/Cntr=0.3,0.1

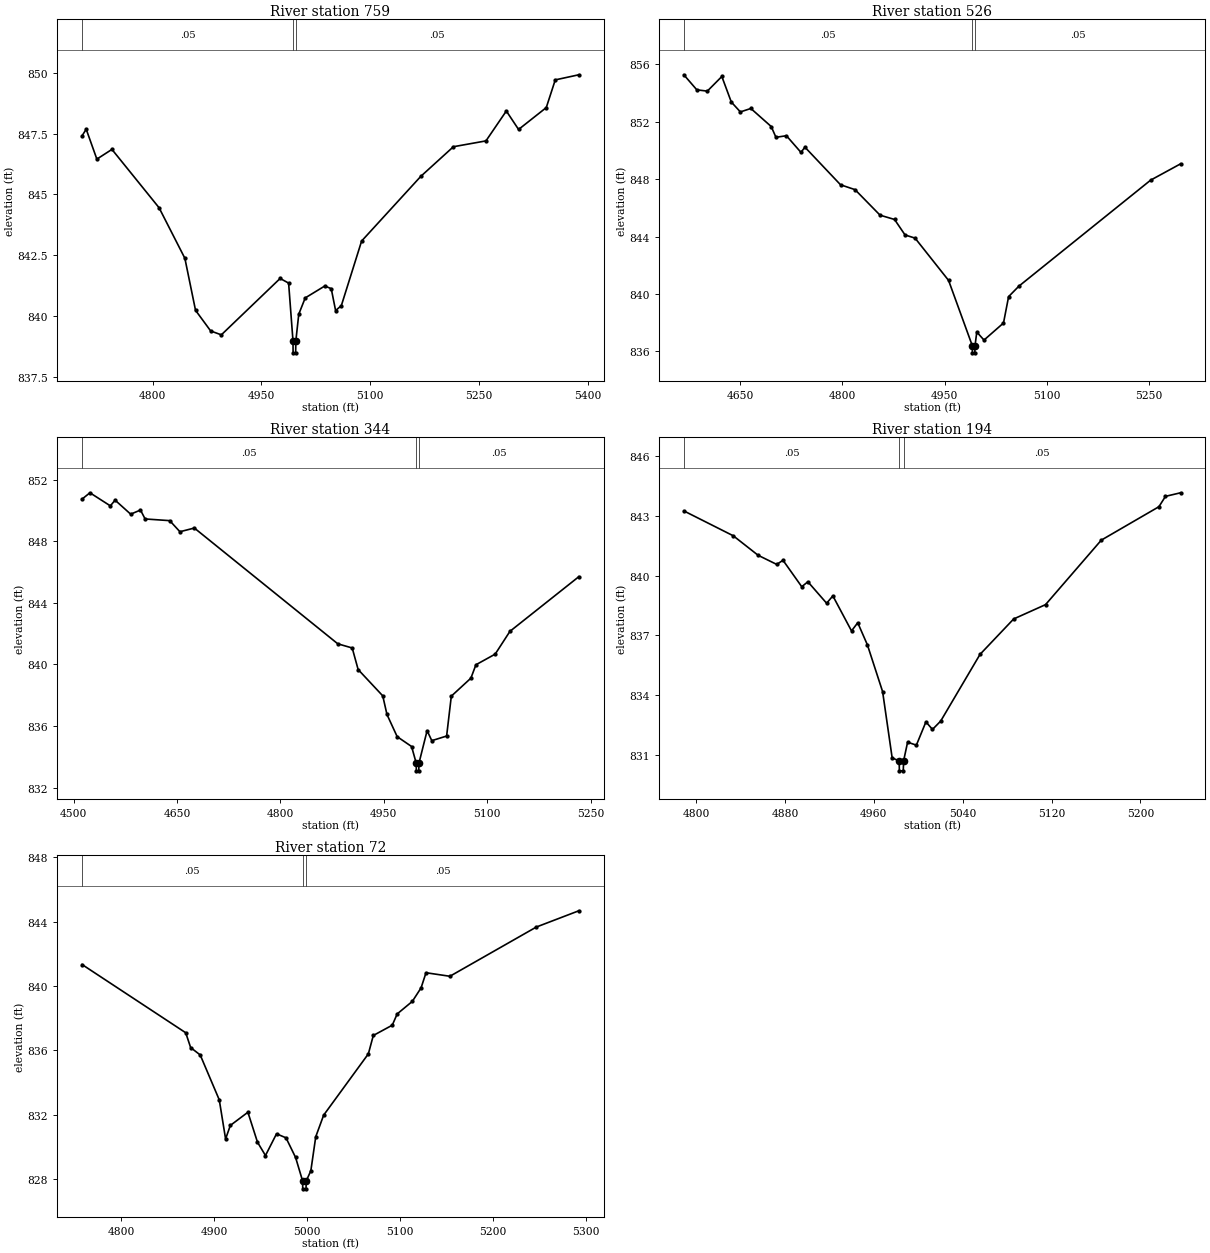
Type RM Length L Ch R = 1,759,233,233,233
BEGIN DESCRIPTION:
Mapping XS 3dec9f1b
END DESCRIPTION:
XS GIS Cut Line= 4
      2281326.26      7111888.94      2281168.31      7112107.22
      2281089.29      7112222.69      2280967.75      7112470.32
#Sta/Elev= 30
  4702.8  847.41  4708.5  847.68  4723.2  846.45  4744.0  846.85  4809.0  844.45
  4844.6  842.37  4859.3  840.23  4880.2  839.38  4894.9  839.22  4976.0  841.54
  4987.7  841.35  4993.7  838.98  4993.9  838.48  4997.4  838.48  4997.7  838.98
  5001.7  840.07  5010.6  840.74  5037.6  841.23  5046.5  841.12  5052.5  840.22
  5060.4  840.42  5088.4  843.08  5170.0  845.74  5215.0  846.96  5259.9  847.20
  5288.0  848.43  5304.9  847.67  5343.1  848.57  5355.5  849.71  5388.0  849.92
#Mann=3,-1,0
  4702.8    0.05       0  4993.7   0.033       0  4997.7    0.05       0
Bank Sta=4993.7,4997.7
Exp/Cntr=0.3,0.1

Type RM Length L Ch R = 1,526,182,182,182
BEGIN DESCRIPTION:
MDW T 016 2.0
END DESCRIPTION:
XS GIS Cut Line= 3
      2281498.46      7111723.94      2281129.47      7111949.77
      2280882.37      7112113.61
#Sta/Elev= 30
  4567.2  855.28  4586.3  854.23  4601.7  854.14  4623.0  855.16  4636.9  853.38
  4650.2  852.69  4665.6  852.93  4695.5  851.67  4702.4  850.92  4717.8  851.03
  4739.1  849.87  4745.0  850.23  4797.2  847.61  4818.5  847.27  4855.2  845.49
  4876.5  845.19  4891.9  844.11  4906.6  843.89  4955.8  840.94  4990.6  836.39
  4990.8  835.89  4994.3  835.89  4994.6  836.39  4997.2  837.34  5007.8  836.78
  5036.4  837.97  5043.9  839.81  5059.0  840.54  5252.3  847.93  5296.3  849.07
#Mann=3,-1,0
  4567.2    0.05       0  4990.6   0.033       0  4994.6    0.05       0
Bank Sta=4990.6,4994.6
Exp/Cntr=0.3,0.1

Type RM Length L Ch R = 1,344,150,150,150
BEGIN DESCRIPTION:
MDW T 016 1.0
END DESCRIPTION:
XS GIS Cut Line= 3
      2281398.10      7111541.78      2280995.43      7111827.08
      2280830.45      7111982.70
#Sta/Elev= 30
  4512.4  850.74  4523.8  851.15  4553.4  850.30  4560.3  850.67  4582.9  849.76
  4597.1  850.03  4603.8  849.45  4639.5  849.34  4654.3  848.62  4675.2  848.86
  4883.2  841.34  4904.1  841.07  4912.7  839.67  4948.4  837.96  4954.5  836.75
  4969.3  835.31  4990.2  834.67  4996.9  833.59  4997.1  833.09  5000.6  833.09
  5000.9  833.59  5012.7  835.70  5019.5  835.05  5041.0  835.35  5047.8  837.94
  5076.2  839.11  5083.5  839.98  5111.4  840.67  5132.8  842.15  5232.7  845.70
#Mann=3,-1,0
  4512.4    0.05       0  4996.9   0.033       0  5000.9    0.05       0
Bank Sta=4996.9,5000.9
Exp/Cntr=0.3,0.1

Type RM Length L Ch R = 1,194,122,122,122
BEGIN DESCRIPTION:
Mapping XS cdb0eba8
END DESCRIPTION:
XS GIS Cut Line= 3
      2281107.10      7111606.88      2280923.19      7111697.93
      2280794.54      7111903.00
#Sta/Elev= 30
  4788.9  843.25  4833.4  842.00  4855.8  841.02  4872.6  840.56  4878.2  840.77
  4895.1  839.44  4900.6  839.69  4917.5  838.61  4923.1  838.98  4939.9  837.22
  4945.5  837.63  4954.2  836.52  4967.9  834.17  4976.5  830.84  4982.8  830.69
  4983.0  830.19  4986.5  830.19  4986.8  830.69  4990.4  831.63  4998.3  831.48
  5006.9  832.65  5012.8  832.27  5020.2  832.69  5055.6  836.04  5085.9  837.82
  5114.6  838.54  5164.8  841.78  5216.7  843.46  5222.6  843.98  5236.2  844.16
#Mann=3,-1,0
  4788.9    0.05       0  4982.8   0.033       0  4986.8    0.05       0
Bank Sta=4982.8,4986.8
Exp/Cntr=0.3,0.1

Type RM Length L Ch R = 1,72,0,0,0
BEGIN DESCRIPTION:
MDW T 016 0.5
END DESCRIPTION:
XS GIS Cut Line= 3
      2281072.88      7111560.13      2280835.53      7111614.56
      2280739.18      7111889.03
#Sta/Elev= 30
  4757.7  841.33  4869.2  837.09  4874.5  836.17  4884.8  835.71  4905.3  832.92
  4912.1  830.49  4917.2  831.33  4936.1  832.15  4946.4  830.29  4955.0  829.46
  4966.9  830.81  4977.1  830.56  4987.4  829.34  4994.9  827.89  4995.1  827.39
  4998.6  827.39  4998.9  827.89  5003.8  828.51  5009.1  830.63  5017.6  831.97
  5065.7  835.78  5071.0  836.92  5091.4  837.56  5096.7  838.26  5113.0  839.04
  5122.4  839.88  5127.7  840.82  5153.4  840.60  5246.4  843.66  5292.1  844.67
#Mann=3,-1,0
  4757.7    0.05       0  4994.9   0.033       0  4998.9    0.05       0
Bank Sta=4994.9,4998.9
Exp/Cntr=0.3,0.1

Chan Stop Cuts=-1