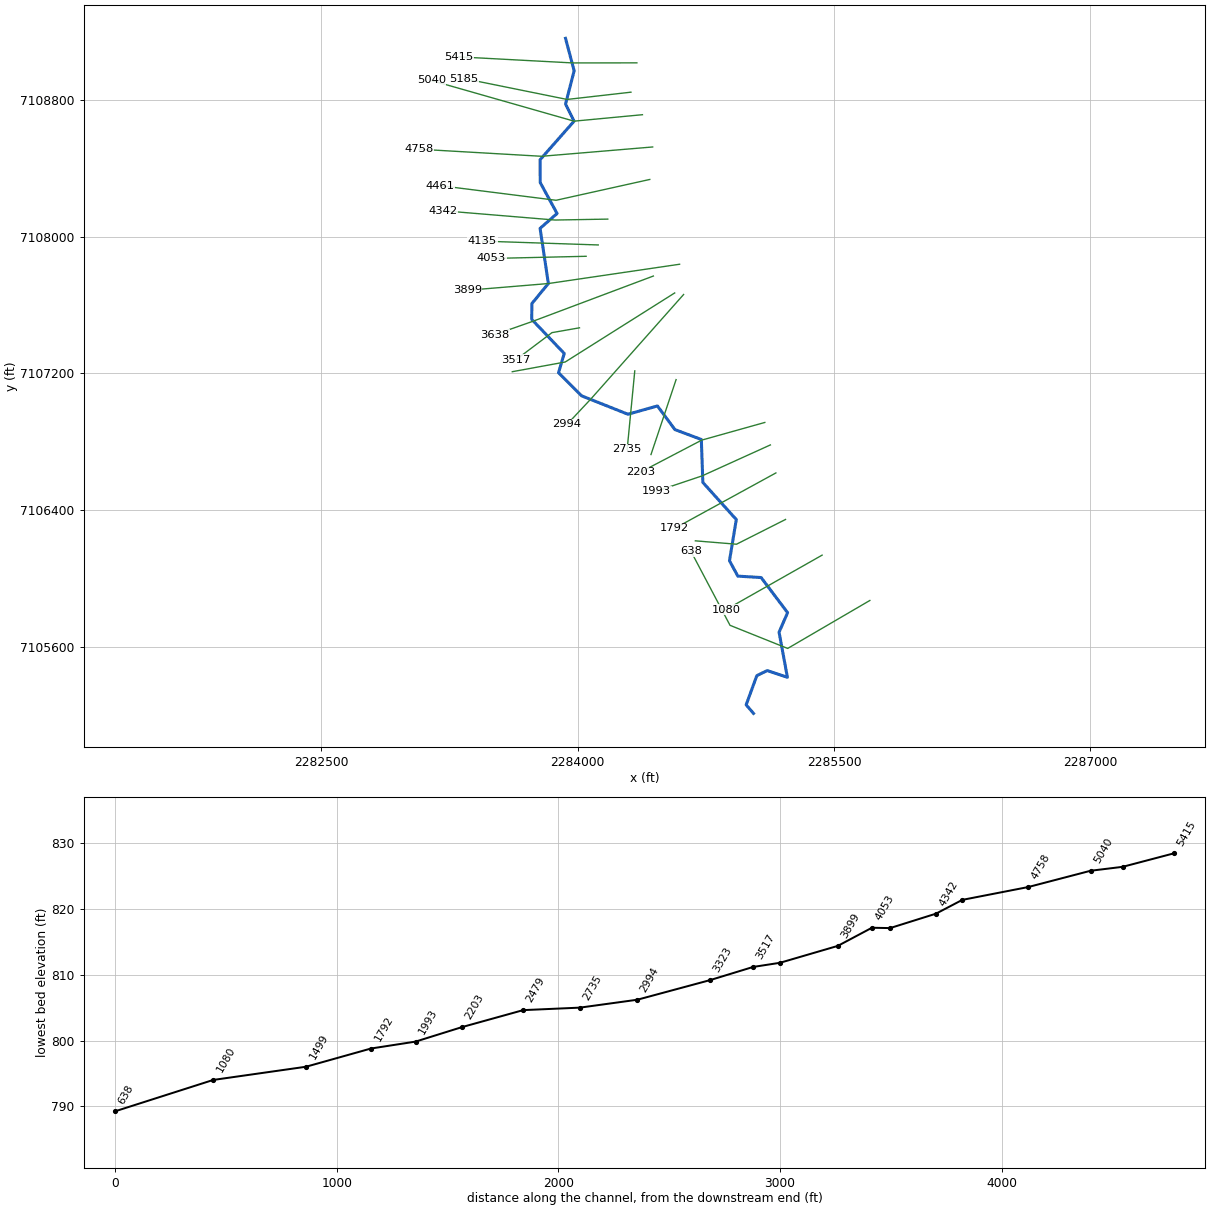
--- MDW T 017.prj (project) ---

Proj Title=MDW T 017 Base Level Engineering
Current Plan=p01
Default Exp/Contr=0.3,0.1
English Units
Geom File=g01
Flow File=f01
Plan File=p01
Y Axis Title=Elevation
X Axis Title(PF)=Main Channel Distance
X Axis Title(XS)=Station
BEGIN DESCRIPTION:
MDW T 017
END DESCRIPTION:
DSS Export Rating Curves= 0
DSS Export Rating Curve Sorted= 0
DSS Export Volume Flow Curves= 0
DXF OffsetX= 0
DXF OffsetY= 0
DXF ScaleX= 1
DXF ScaleY= 10

--- MDW T 017.p01 (plan) ---

Plan Title=Multiple Run
Short Identifier=Multiple
Geom File=g01
Flow File=f01
Subcritical Flow
K Sum by GR= 0
Std Step Tol= 0.01
Critical Tol= 0.01
Num of Std Step Trials= 20
Max Error Tol= 0.3
Flow Tol Ratio= 0.001
Split Flow NTrial= 30
Split Flow Tol= 0.02
Split Flow Ratio= 0.02
Log Output Level= 0
Friction Slope Method= 1
Unsteady Friction Slope Method= 2
Unsteady Bridges Friction Slope Method= 1
Parabolic Critical Depth
Global Vel Dist=  1 , 1 , 1
Global Log Level= 0
CheckData=True
Encroach Param= -1, 0, 0, 0
BEGIN DESCRIPTION:
Multiple Run
END DESCRIPTION:

--- MDW T 017.f01 (steady flow) ---

Flow Title=Multiple
Number of Profiles=7
Profile Names=10-year,25-year,50-year,1pct_min,100-year,1pct_plu,500-year
River Rch & RM= MDW T 017,Reach-1,5415
     410     550     664     399     796    1589    1146
River Rch & RM= MDW T 017,Reach-1,2479
     465     630     764     461     920    1836    1335
Boundary for River Rch & Prof#=MDW T 017,Reach-1,1
Up Type=0
Dn Type=3
Dn Slope=0.005
Boundary for River Rch & Prof#=MDW T 017,Reach-1,2
Up Type=0
Dn Type=3
Dn Slope=0.005
Boundary for River Rch & Prof#=MDW T 017,Reach-1,3
Up Type=0
Dn Type=3
Dn Slope=0.005
Boundary for River Rch & Prof#=MDW T 017,Reach-1,4
Up Type=0
Dn Type=3
Dn Slope=0.005
Boundary for River Rch & Prof#=MDW T 017,Reach-1,5
Up Type=0
Dn Type=3
Dn Slope=0.005
Boundary for River Rch & Prof#=MDW T 017,Reach-1,6
Up Type=0
Dn Type=3
Dn Slope=0.005
Boundary for River Rch & Prof#=MDW T 017,Reach-1,7
Up Type=0
Dn Type=3
Dn Slope=0.005

--- MDW T 017.g01 (geometry) ---

Geom Title=Existing Conditions

River Reach=MDW T 017,Reach-1
Reach XY= 30
      2283929.00      7109160.00      2283979.50      7108970.17
      2283929.11      7108775.39      2283979.04      7108675.34
      2283780.03      7108449.56      2283781.06      7108315.86
      2283879.53      7108134.88      2283780.19      7108047.98
      2283828.61      7107725.16      2283732.47      7107608.50
      2283730.96      7107515.89      2283921.50      7107316.05
      2283888.15      7107203.27      2284022.94      7107068.14
      2284294.27      7106960.38      2284466.99      7107008.83
      2284569.20      7106870.51      2284723.66      7106812.74
      2284732.55      7106561.47      2284928.33      7106344.16
      2284888.39      7106103.33      2284937.26      7106013.08
      2285073.55      7106004.81      2285228.40      7105799.38
      2285178.61      7105685.00      2285227.38      7105421.16
      2285108.73      7105460.37      2285048.46      7105430.75
      2284985.90      7105259.86      2285029.00      7105210.00

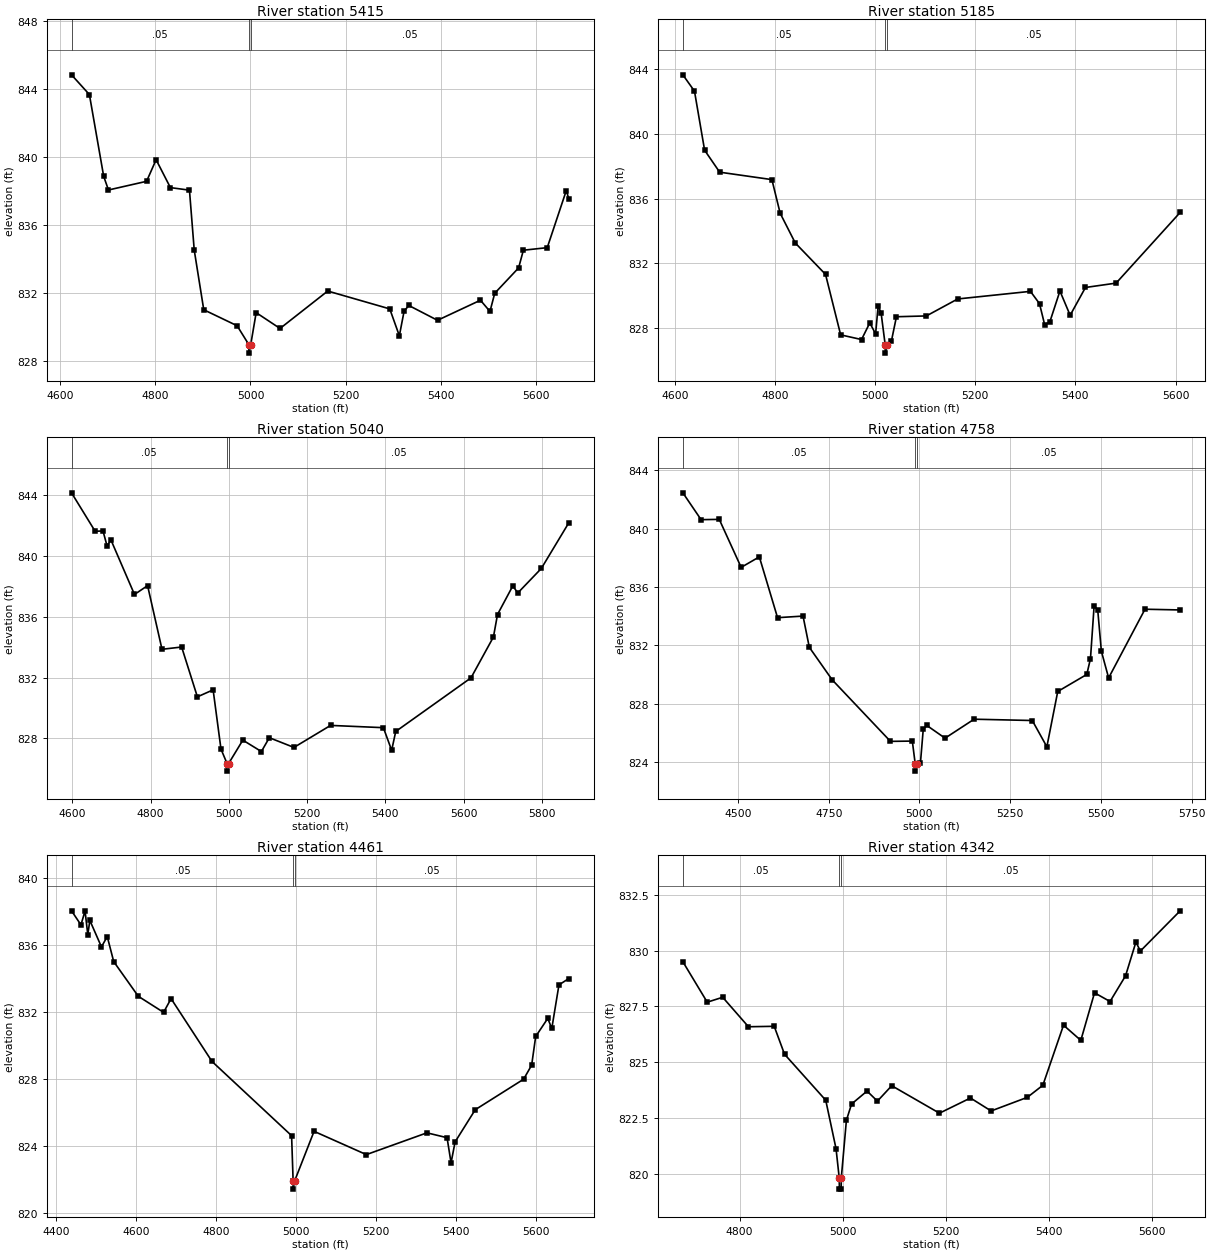
Type RM Length L Ch R = 1,5415,230,230,230
BEGIN DESCRIPTION:
MDW T 017 14.0
END DESCRIPTION:
XS GIS Cut Line= 3
      2284346.51      7109016.50      2283970.91      7109016.07
      2283303.76      7109051.65
#Sta/Elev= 30
  4624.4  844.85  4661.9  843.69  4691.9  838.88  4701.9  838.08  4781.9  838.59
  4801.9  839.86  4831.9  838.22  4871.9  838.07  4881.9  834.55  4901.9  831.04
  4971.9  830.10  4996.5  828.99  4996.7  828.49  5000.5  828.99  5011.9  830.87
  5062.0  829.94  5162.1  832.14  5292.3  831.09  5312.4  829.51  5322.4  830.96
  5332.4  831.29  5392.5  830.42  5482.6  831.60  5502.6  830.94  5512.6  832.01
  5562.7  833.50  5572.7  834.54  5622.8  834.69  5662.8  838.05  5668.1  837.55
#Mann=3,-1,0
  4624.4    0.05       0  4996.5    0.04       0  5000.5    0.05       0
Bank Sta=4996.5,5000.5
Exp/Cntr=0.3,0.1

Type RM Length L Ch R = 1,5185,145,145,145
BEGIN DESCRIPTION:
Mapping XS 378a992e
END DESCRIPTION:
XS GIS Cut Line= 3
      2284312.07      7108844.96      2283938.37      7108802.40
      2283333.68      7108924.95
#Sta/Elev= 30
  4616.2  843.66  4639.4  842.65  4659.6  839.00  4689.7  837.64  4794.0  837.18
  4810.5  835.10  4840.7  833.26  4901.1  831.32  4931.3  827.58  4973.0  827.29
  4989.5  828.32  5001.1  827.64  5006.2  829.38  5012.1  828.93  5020.3  826.95
  5020.5  826.45  5024.3  826.95  5032.5  827.17  5042.7  828.70  5102.5  828.75
  5165.1  829.80  5310.3  830.27  5328.4  829.51  5338.6  828.22  5348.8  828.36
  5369.2  830.29  5389.6  828.79  5420.2  830.51  5481.4  830.78  5609.3  835.15
#Mann=3,-1,0
  4616.2    0.05       0  5020.3    0.04       0  5024.3    0.05       0
Bank Sta=5020.3,5024.3
Exp/Cntr=0.3,0.1

Type RM Length L Ch R = 1,5040,282,282,282
BEGIN DESCRIPTION:
MDW T 017 13.0
END DESCRIPTION:
XS GIS Cut Line= 3
      2284379.06      7108713.12      2283979.04      7108675.34
      2283143.74      7108913.54
#Sta/Elev= 30
  4598.2  844.17  4658.5  841.64  4678.6  841.66  4689.1  840.66  4698.7  841.08
  4759.0  837.48  4792.5  838.06  4829.3  833.87  4879.5  834.02  4919.7  830.74
  4959.9  831.20  4980.0  827.30  4995.5  826.35  4995.8  825.85  4999.5  826.35
  5035.8  827.89  5083.2  827.14  5103.5  828.05  5166.4  827.41  5260.0  828.86
  5394.9  828.71  5416.0  827.22  5426.4  828.46  5618.7  831.99  5676.0  834.68
  5686.4  836.16  5725.4  838.04  5738.3  837.58  5798.3  839.19  5868.6  842.20
#Mann=3,-1,0
  4598.2    0.05       0  4995.5    0.04       0  4999.5    0.05       0
Bank Sta=4995.5,4999.5
Exp/Cntr=0.3,0.1

Type RM Length L Ch R = 1,4758,297,297,297
BEGIN DESCRIPTION:
MDW T 017 12.0
END DESCRIPTION:
XS GIS Cut Line= 3
      2284438.99      7108524.32      2283789.47      7108469.80
      2283072.26      7108511.19
#Sta/Elev= 30
  4348.2  842.45  4398.4  840.61  4448.5  840.63  4508.8  837.34  4558.9  838.06
  4609.1  833.89  4679.3  834.00  4696.6  831.86  4759.6  829.63  4920.2  825.41
  4980.4  825.43  4988.4  823.87  4988.7  823.37  4992.4  823.87  5002.7  823.91
  5010.5  826.23  5020.5  826.50  5070.6  825.63  5150.7  826.93  5311.0  826.84
  5351.1  825.04  5381.1  828.83  5461.2  830.00  5471.3  831.09  5481.3  834.69
  5491.3  834.41  5501.3  831.59  5521.3  829.76  5621.5  834.47  5718.4  834.42
#Mann=3,-1,0
  4348.2    0.05       0  4988.4    0.04       0  4992.4    0.05       0
Bank Sta=4988.4,4992.4
Exp/Cntr=0.3,0.1

Type RM Length L Ch R = 1,4461,119,119,119
BEGIN DESCRIPTION:
MDW T 017 11.0
END DESCRIPTION:
XS GIS Cut Line= 3
      2284422.03      7108334.21      2283873.59      7108212.42
      2283196.75      7108297.75
#Sta/Elev= 30
  4438.2  838.03  4461.8  837.19  4472.0  838.03  4478.9  836.60  4484.0  837.46
  4513.0  835.88  4527.6  836.49  4543.7  835.00  4605.2  832.93  4668.5  831.97
  4687.2  832.79  4789.6  829.04  4988.7  824.61  4992.5  821.92  4992.7  821.42
  4996.5  821.92  5044.9  824.87  5175.7  823.48  5327.2  824.78  5377.6  824.49
  5387.6  822.99  5397.7  824.24  5448.1  826.16  5569.1  827.98  5589.2  828.82
  5599.3  830.53  5629.5  831.61  5639.6  831.01  5657.5  833.61  5682.2  833.99
#Mann=3,-1,0
  4438.2    0.05       0  4992.5    0.04       0  4996.5    0.05       0
Bank Sta=4992.5,4996.5
Exp/Cntr=0.3,0.1

Type RM Length L Ch R = 1,4342,207,207,207
BEGIN DESCRIPTION:
Mapping XS b086ed07
END DESCRIPTION:
XS GIS Cut Line= 3
      2284176.30      7108102.23      2283867.60      7108096.77
      2283213.40      7108151.08
#Sta/Elev= 30
  4689.8  829.50  4737.1  827.69  4767.1  827.91  4817.1  826.59  4867.1  826.61
  4887.1  825.36  4967.1  823.30  4987.1  821.13  4993.3  819.82  4993.6  819.32
  4997.1  819.32  4997.3  819.82  5007.2  822.40  5017.2  823.13  5047.3  823.71
  5067.4  823.26  5095.2  823.95  5187.8  822.72  5248.0  823.40  5288.1  822.82
  5358.4  823.43  5388.5  823.97  5428.6  826.66  5462.2  825.98  5488.8  828.11
  5518.9  827.72  5549.0  828.87  5569.1  830.38  5577.8  829.98  5655.0  831.78
#Mann=3,-1,0
  4689.8    0.05       0  4993.3    0.04       0  4997.3    0.05       0
Bank Sta=4993.3,4997.3
Exp/Cntr=0.3,0.1

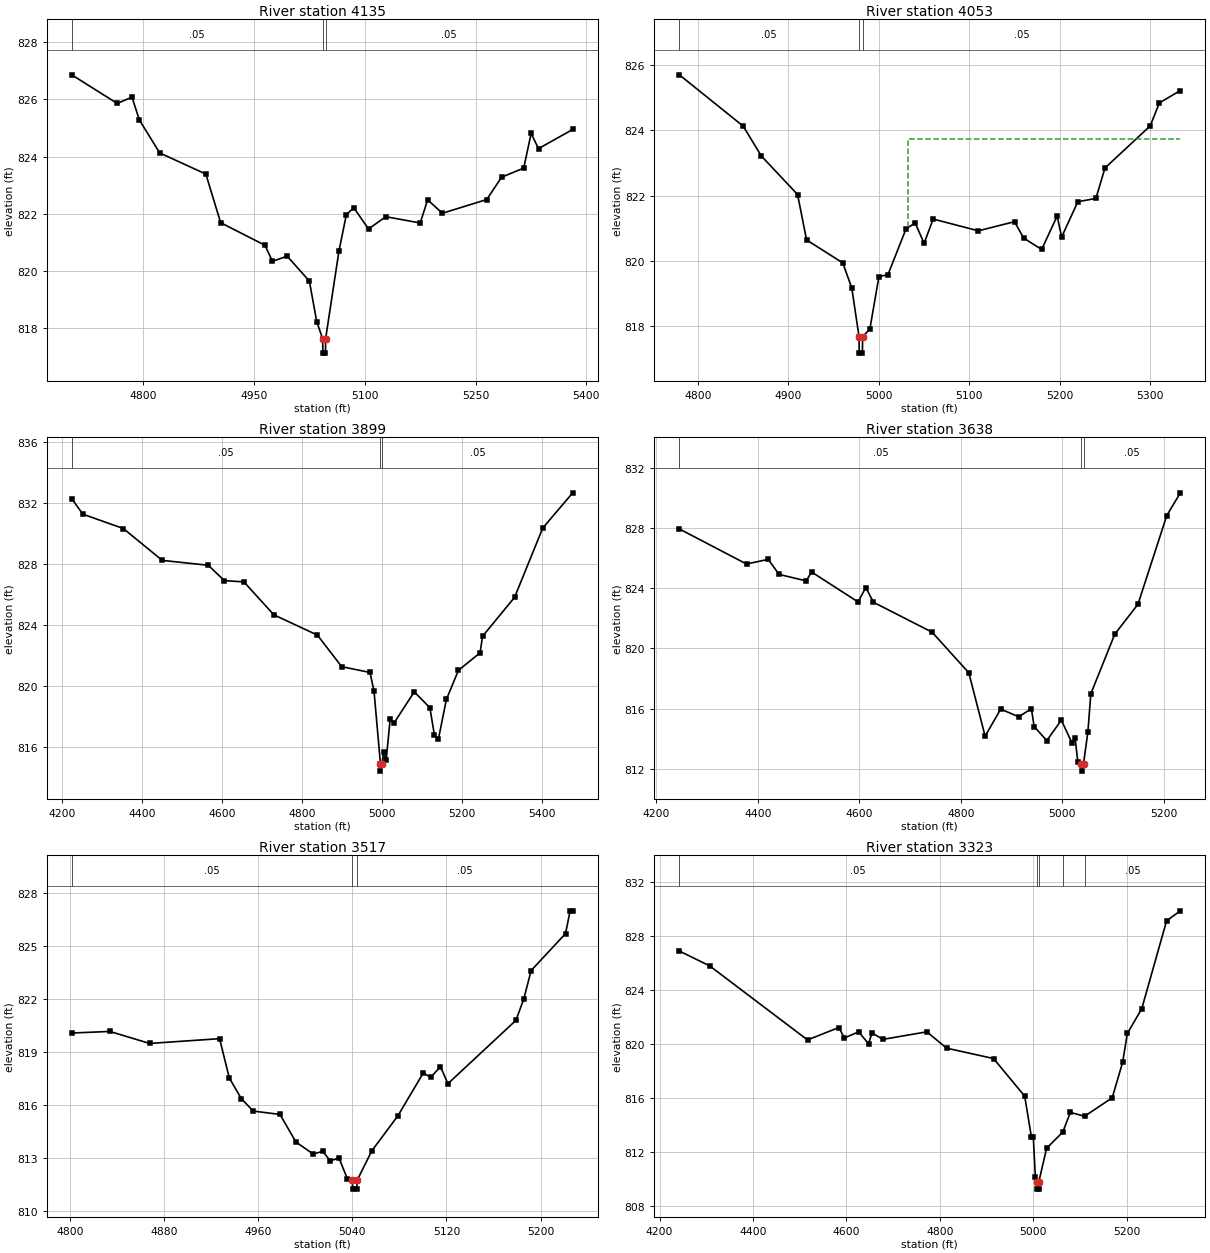
Type RM Length L Ch R = 1,4135,82,82,82
BEGIN DESCRIPTION:
Mapping XS ebab1bef
END DESCRIPTION:
XS GIS Cut Line= 2
      2284120.54      7107950.97      2283442.71      7107973.44
#Sta/Elev= 30
  4703.3  826.86  4764.9  825.86  4784.9  826.08  4794.9  825.28  4822.4  824.13
  4884.9  823.39  4904.9  821.69  4965.0  820.90  4975.0  820.34  4995.0  820.52
  5025.0  819.65  5035.0  818.23  5043.0  817.63  5043.3  817.13  5046.8  817.13
  5047.0  817.63  5065.0  820.69  5075.0  821.96  5085.0  822.22  5105.1  821.47
  5128.4  821.90  5175.1  821.68  5185.1  822.49  5205.1  822.02  5265.1  822.50
  5285.2  823.28  5315.2  823.60  5325.2  824.81  5335.2  824.28  5381.5  824.95
#Mann=3,-1,0
  4703.3    0.05       0  5043.0   0.033       0  5047.0    0.05       0
Bank Sta=5043,5047
Exp/Cntr=0.3,0.1

Type RM Length L Ch R = 1,4053,154,154,154
BEGIN DESCRIPTION:
Mapping XS 7675930e
END DESCRIPTION:
XS GIS Cut Line= 2
      2284049.62      7107884.65      2283495.67      7107871.92
#Sta/Elev= 30
  4779.5  825.69  4850.1  824.12  4870.1  823.21  4910.2  822.03  4920.2  820.64
  4960.2  819.94  4970.2  819.17  4978.2  817.68  4978.4  817.18  4981.9  817.18
  4982.2  817.68  4990.2  817.92  5000.2  819.52  5010.2  819.58  5030.2  820.98
  5040.2  821.16  5050.2  820.54  5060.2  821.28  5110.2  820.92  5150.2  821.20
  5160.2  820.70  5180.2  820.35  5197.3  821.37  5202.3  820.73  5220.2  821.81
  5240.2  821.91  5250.2  822.84  5300.3  824.13  5310.3  824.83  5333.6  825.21
#Mann=3,-1,0
  4779.5    0.05       0  4978.2   0.033       0  4982.2    0.05       0
#XS Ineff=2,0
       0                 5032.90    0.00  823.73
Permanent Ineff=
       F       F
Bank Sta=4978.2,4982.2
Exp/Cntr=0.3,0.1

Type RM Length L Ch R = 1,3899,261,261,261
BEGIN DESCRIPTION:
MDW T 017 9.0
END DESCRIPTION:
XS GIS Cut Line= 3
      2284596.55      7107838.12      2283828.61      7107725.16
      2283354.35      7107685.77
#Sta/Elev= 30
  4223.8  832.29  4251.6  831.27  4352.7  830.33  4450.1  828.24  4565.0  827.92
  4605.4  826.91  4654.2  826.83  4729.0  824.67  4837.9  823.34  4898.5  821.27
  4969.3  820.89  4979.4  819.65  4995.3  814.92  4995.5  814.42  4999.3  814.92
  5003.3  815.67  5009.6  815.12  5019.7  817.84  5029.7  817.59  5079.9  819.62
  5118.9  818.58  5130.1  816.82  5140.1  816.50  5160.2  819.12  5190.3  821.03
  5244.5  822.18  5250.5  823.26  5330.7  825.82  5401.0  830.36  5475.9  832.67
#Mann=3,-1,0
  4223.8    0.05       0  4995.3   0.033       0  4999.3    0.05       0
Bank Sta=4995.3,4999.3
Exp/Cntr=0.3,0.1

Type RM Length L Ch R = 1,3638,121,121,121
BEGIN DESCRIPTION:
MDW T 017 8.0
END DESCRIPTION:
XS GIS Cut Line= 3
      2284442.87      7107769.11      2283736.76      7107503.83
      2283517.12      7107426.67
#Sta/Elev= 30
  4245.7  827.94  4378.0  825.61  4420.8  825.92  4442.1  824.92  4495.5  824.49
  4506.2  825.08  4597.8  823.09  4613.0  824.05  4628.0  823.07  4743.7  821.08
  4816.0  818.38  4848.1  814.17  4878.8  815.97  4914.4  815.46  4939.3  816.00
  4944.7  814.81  4969.6  813.88  4998.3  815.24  5018.8  813.75  5025.4  814.07
  5030.7  812.46  5038.0  812.35  5038.3  811.85  5042.0  812.35  5050.6  814.46
  5056.4  816.99  5103.6  820.95  5149.3  822.94  5206.0  828.83  5232.8  830.34
#Mann=3,-1,0
  4245.7    0.05       0  5038.0   0.033       0  5042.0    0.05       0
Bank Sta=5038,5042
Exp/Cntr=0.3,0.1

Type RM Length L Ch R = 1,3517,194,194,194
BEGIN DESCRIPTION:
Mapping XS 1287b64a
END DESCRIPTION:
XS GIS Cut Line= 3
      2284010.80      7107466.17      2283849.53      7107437.84
      2283640.53      7107280.25
#Sta/Elev= 30
  4801.7  820.06  4834.0  820.15  4867.9  819.47  4927.3  819.74  4935.5  817.52
  4945.7  816.35  4955.8  815.64  4978.6  815.45  4992.1  813.89  5006.7  813.21
  5015.0  813.36  5021.2  812.82  5028.7  812.98  5035.8  811.81  5040.1  811.72
  5040.3  811.22  5043.8  811.22  5044.1  811.72  5056.6  813.39  5078.8  815.38
  5100.3  817.80  5106.6  817.55  5114.9  818.16  5121.2  817.19  5179.0  820.78
  5185.7  822.00  5191.9  823.60  5221.1  825.69  5225.0  826.98  5227.2  826.98
#Mann=3,-1,0
  4801.7    0.05       0  5040.1   0.033       0  5044.1    0.05       0
Bank Sta=5040.1,5044.1
Exp/Cntr=0.3,0.1

Type RM Length L Ch R = 1,3323,329,329,329
BEGIN DESCRIPTION:
MDW T 017 7.0
END DESCRIPTION:
XS GIS Cut Line= 3
      2284567.85      7107670.14      2283927.01      7107266.05
      2283617.38      7107209.22
#Sta/Elev= 30
  4242.4  826.87  4307.2  825.77  4516.7  820.28  4583.7  821.20  4595.7  820.42
  4626.1  820.88  4647.3  820.00  4654.8  820.80  4677.9  820.32  4772.1  820.88
  4814.4  819.67  4914.9  818.90  4981.6  816.11  4995.9  813.09  5000.0  813.09
  5004.4  810.14  5007.5  809.72  5007.8  809.22  5011.3  809.22  5011.5  809.72
  5028.5  812.25  5063.1  813.45  5079.3  814.91  5109.7  814.62  5168.9  815.99
  5191.2  818.62  5201.3  820.76  5232.1  822.59  5285.3  829.11  5314.8  829.85
#Mann=5,-1,0
  4242.4    0.05       0  5007.5   0.033       0  5011.5    0.05       0
  5063.1    0.12       0  5109.7    0.05       0
Bank Sta=5007.5,5011.5
Exp/Cntr=0.3,0.1

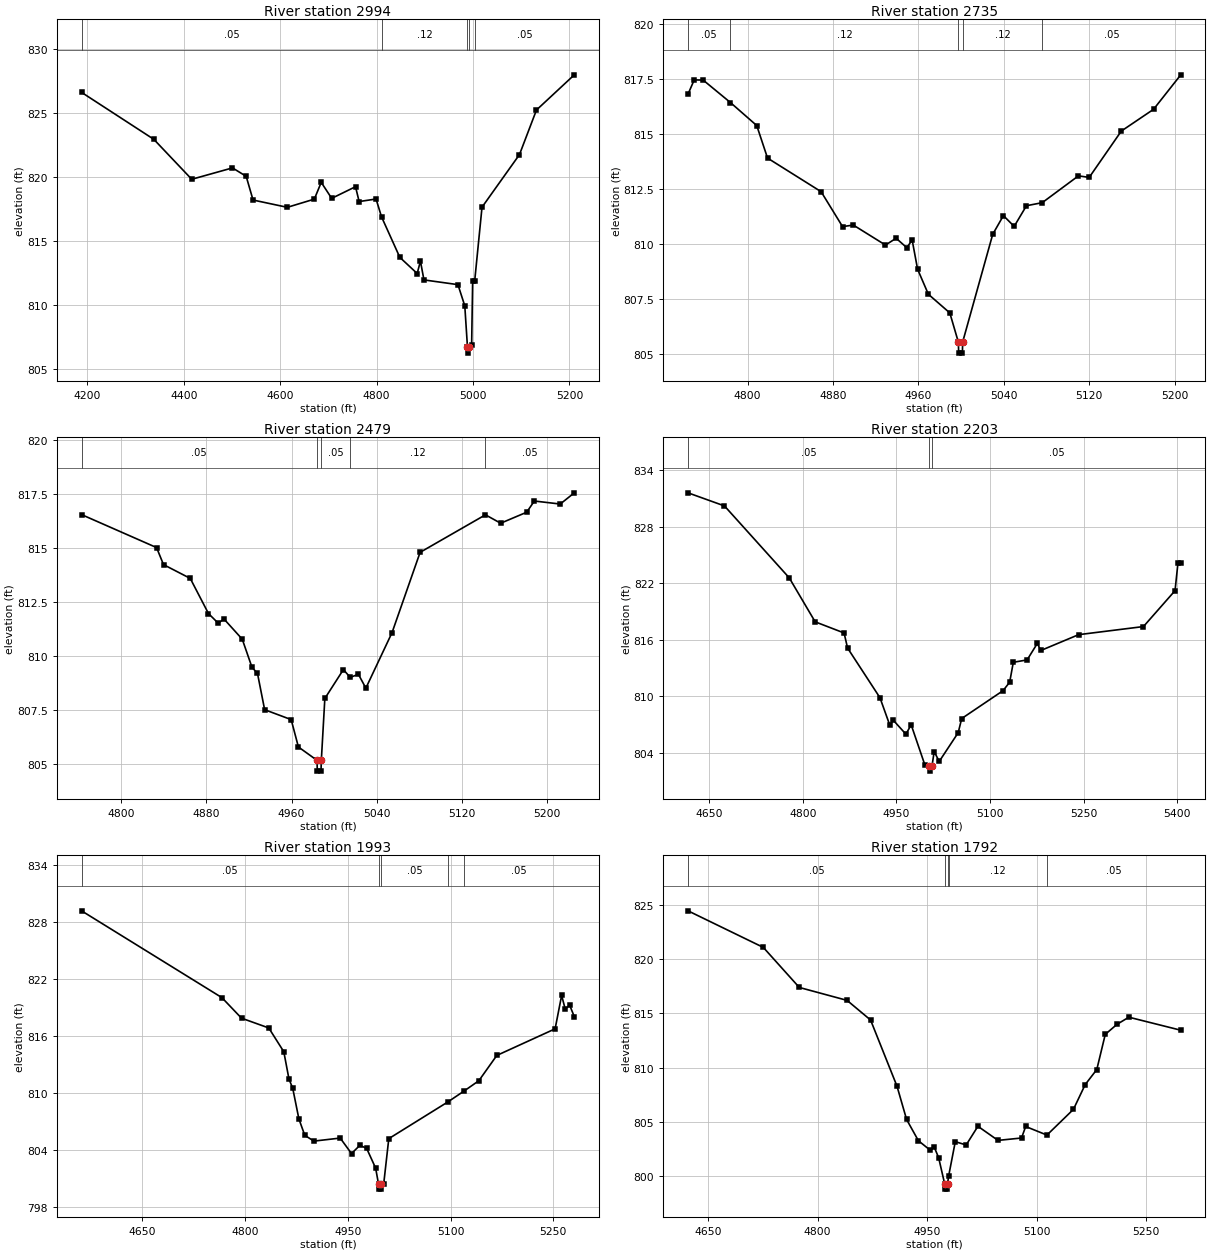
Type RM Length L Ch R = 1,2994,259,259,259
BEGIN DESCRIPTION:
MDW T 017 6.0
END DESCRIPTION:
XS GIS Cut Line= 3
      2284619.98      7107661.07      2284081.17      7107053.86
      2283937.63      7106900.58
#Sta/Elev= 30
  4188.2  826.60  4338.1  822.93  4416.7  819.81  4501.2  820.70  4529.6  820.04
  4543.8  818.19  4614.9  817.62  4670.9  818.26  4685.2  819.57  4706.9  818.32
  4756.3  819.23  4763.8  818.07  4798.9  818.27  4810.2  816.88  4848.2  813.71
  4884.2  812.45  4890.9  813.42  4898.2  811.95  4968.7  811.58  4982.9  809.92
  4988.4  806.73  4988.7  806.23  4992.4  806.73  4997.1  806.86  4999.2  811.86
  5003.4  811.86  5018.6  817.63  5096.3  821.74  5131.5  825.22  5210.0  827.97
#Mann=5,-1,0
  4188.2    0.05       0  4810.2    0.12       0  4988.4    0.07       0
  4992.4    0.12       0  5003.4    0.05       0
Bank Sta=4988.4,4992.4
Exp/Cntr=0.3,0.1

Type RM Length L Ch R = 1,2735,256,256,256
BEGIN DESCRIPTION:
Mapping XS 66b088f3
END DESCRIPTION:
XS GIS Cut Line= 2
      2284334.24      7107214.13      2284289.71      7106754.59
#Sta/Elev= 30
  4744.1  816.82  4749.9  817.47  4758.3  817.46  4783.8  816.44  4808.5  815.39
  4818.6  813.91  4868.8  812.38  4888.9  810.79  4899.0  810.86  4929.1  809.95
  4939.1  810.26  4949.1  809.83  4954.1  810.18  4959.2  808.85  4969.3  807.71
  4989.4  806.86  4997.4  805.53  4997.7  805.03  5001.2  805.03  5001.4  805.53
  5029.6  810.44  5039.6  811.29  5049.7  810.80  5061.2  811.74  5076.0  811.88
  5109.9  813.10  5120.0  813.03  5150.1  815.14  5180.3  816.13  5205.8  817.70
#Mann=5,-1,0
  4744.1    0.05       0  4783.8    0.12       0  4997.4    0.07       0
  5001.4    0.12       0  5076.0    0.05       0
Bank Sta=4997.4,5001.4
Exp/Cntr=0.3,0.1

Type RM Length L Ch R = 1,2479,276,276,276
BEGIN DESCRIPTION:
Mapping XS cb8cc80c
END DESCRIPTION:
XS GIS Cut Line= 2
      2284575.97      7107162.96      2284429.17      7106724.48
#Sta/Elev= 30
  4762.9  816.55  4833.3  815.02  4839.8  814.23  4864.9  813.59  4882.0  811.96
  4891.2  811.51  4896.5  811.71  4913.7  810.77  4922.8  809.47  4928.0  809.18
  4934.7  807.50  4959.6  807.04  4966.4  805.77  4983.9  805.15  4984.1  804.65
  4987.6  804.65  4987.9  805.15  4991.2  808.02  5008.6  809.36  5015.0  809.00
  5022.7  809.14  5029.7  808.50  5054.3  811.08  5080.6  814.80  5141.9  816.54
  5156.2  816.15  5180.6  816.66  5187.8  817.18  5212.1  817.04  5225.3  817.56
#Mann=5,-1,0
  4762.9    0.05       0  4983.9   0.033       0  4987.9    0.05       0
  5015.0    0.12       0  5141.9    0.05       0
Bank Sta=4983.9,4987.9
Exp/Cntr=0.3,0.1

Type RM Length L Ch R = 1,2203,210,210,210
BEGIN DESCRIPTION:
MDW T 017 4.0
END DESCRIPTION:
XS GIS Cut Line= 3
      2285095.23      7106912.34      2284725.56      7106808.78
      2284366.01      7106620.65
#Sta/Elev= 30
  4616.1  831.60  4674.5  830.21  4778.3  822.58  4819.9  817.91  4866.2  816.73
  4871.8  815.13  4923.7  809.86  4939.6  806.92  4944.8  807.49  4965.3  805.99
  4973.7  806.99  4995.6  802.74  5003.0  802.57  5003.2  802.07  5007.0  802.57
  5010.6  804.14  5018.7  803.10  5049.1  806.15  5054.7  807.65  5121.0  810.61
  5131.6  811.51  5137.4  813.62  5159.5  813.87  5175.9  815.62  5181.5  814.87
  5242.1  816.55  5346.0  817.41  5396.6  821.22  5401.3  824.17  5405.8  824.17
#Mann=3,-1,0
  4616.1    0.05       0  5003.0   0.033       0  5007.0    0.05       0
Bank Sta=5003,5007
Exp/Cntr=0.3,0.1

Type RM Length L Ch R = 1,1993,201,201,201
BEGIN DESCRIPTION:
MDW T 017 3.0
END DESCRIPTION:
XS GIS Cut Line= 3
      2285127.78      7106780.83      2284728.50      7106599.79
      2284462.50      7106510.46
#Sta/Elev= 30
  4561.6  829.13  4766.4  820.00  4795.0  817.84  4834.8  816.81  4856.7  814.31
  4864.3  811.42  4869.7  810.48  4878.7  807.25  4887.3  805.52  4900.6  804.91
  4939.0  805.23  4955.5  803.60  4967.6  804.46  4977.5  804.16  4990.7  802.07
  4995.0  800.36  4995.2  799.86  4998.7  799.86  4999.0  800.36  5002.4  800.36
  5009.9  805.17  5096.3  809.04  5119.8  810.18  5141.3  811.26  5167.5  813.92
  5252.6  816.72  5262.1  820.23  5267.4  818.78  5273.7  819.23  5280.6  817.99
#Mann=5,-1,0
  4561.6    0.05       0  4995.0   0.033       0  4999.0    0.05       0
  5096.3    0.12       0  5119.8    0.05       0
Bank Sta=4995,4999
Exp/Cntr=0.3,0.1

Type RM Length L Ch R = 1,1792,293,293,293
BEGIN DESCRIPTION:
Mapping XS 9893190a
END DESCRIPTION:
XS GIS Cut Line= 2
      2285159.97      7106616.96      2284568.19      7106292.69
#Sta/Elev= 30
  4622.5  824.45  4725.6  821.08  4774.9  817.39  4840.3  816.20  4872.5  814.39
  4908.7  808.29  4921.8  805.23  4938.0  803.27  4954.1  802.40  4959.8  802.66
  4965.7  801.71  4973.9  799.31  4974.1  798.81  4977.6  798.81  4977.9  799.31
  4979.5  800.05  4988.5  803.18  5003.4  802.88  5019.5  804.60  5047.0  803.30
  5079.2  803.52  5084.9  804.58  5114.0  803.79  5150.3  806.16  5166.4  808.44
  5182.3  809.83  5193.9  813.07  5210.1  814.00  5226.2  814.65  5297.3  813.45
#Mann=5,-1,0
  4622.5    0.05       0  4973.9    0.07       0  4977.9    0.05       0
  4979.5    0.12       0  5114.0    0.05       0
Bank Sta=4973.9,4977.9
Exp/Cntr=0.3,0.1

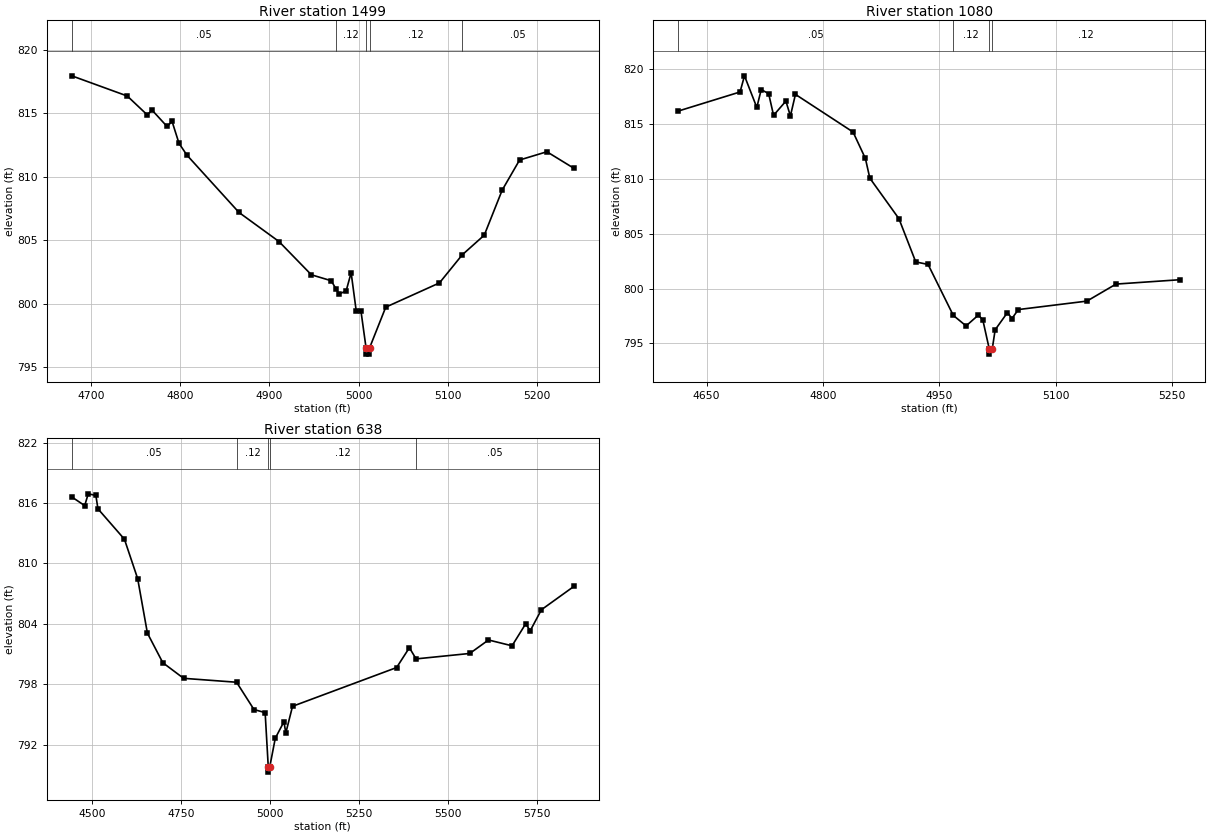
Type RM Length L Ch R = 1,1499,419,419,419
BEGIN DESCRIPTION:
MDW T 017 2.0
END DESCRIPTION:
XS GIS Cut Line= 3
      2285216.32      7106344.64      2284929.41      7106199.80
      2284688.93      7106219.63
#Sta/Elev= 30
  4678.6  817.96  4740.8  816.37  4763.1  814.89  4768.7  815.25  4785.4  813.97
  4791.0  814.37  4798.8  812.64  4807.7  811.71  4866.0  807.20  4910.8  804.91
  4947.1  802.29  4969.4  801.82  4974.8  801.17  4978.1  800.77  4986.1  801.02
  4991.7  802.45  4997.4  799.44  5002.7  799.44  5008.4  796.54  5008.7  796.04
  5012.2  796.04  5012.4  796.54  5030.5  799.74  5090.7  801.65  5116.2  803.86
  5140.9  805.41  5161.0  808.96  5180.5  811.33  5211.1  811.98  5241.3  810.68
#Mann=5,-1,0
  4678.6    0.05       0  4974.8    0.12       0  5008.4    0.07       0
  5012.4    0.12       0  5116.2    0.05       0
Bank Sta=5008.4,5012.4
Exp/Cntr=0.3,0.1

Type RM Length L Ch R = 1,1080,442,442,442
BEGIN DESCRIPTION:
Mapping XS 1a125562
END DESCRIPTION:
XS GIS Cut Line= 2
      2285430.48      7106135.88      2284867.30      7105816.77
#Sta/Elev= 30
  4613.5  816.17  4693.2  817.91  4698.9  819.38  4714.8  816.50  4720.5  818.13
  4730.1  817.75  4736.4  815.78  4752.3  817.08  4758.1  815.72  4764.6  817.69
  4838.9  814.26  4854.8  811.85  4860.5  810.06  4898.0  806.37  4919.7  802.43
  4935.6  802.20  4968.1  797.56  4984.6  796.60  5000.5  797.59  5006.2  797.14
  5014.4  794.53  5014.6  794.03  5018.4  794.53  5022.1  796.25  5038.0  797.82
  5043.7  797.27  5052.0  798.09  5140.4  798.86  5177.9  800.41  5260.8  800.81
#Mann=4,-1,0
  4613.5    0.05       0  4968.1    0.12       0  5014.4    0.07       0
  5018.4    0.12       0
Bank Sta=5014.4,5018.4
Exp/Cntr=0.3,0.1

Type RM Length L Ch R = 1,638,0,0,0
BEGIN DESCRIPTION:
MDW T 017 1.0
END DESCRIPTION:
XS GIS Cut Line= 4
      2285709.79      7105870.66      2285228.92      7105589.97
      2284891.56      7105725.28      2284662.91      7106158.45
#Sta/Elev= 30
  4443.2  816.61  4479.5  815.75  4489.4  816.92  4510.9  816.76  4516.7  815.43
  4591.1  812.41  4628.3  808.49  4655.6  803.08  4698.9  800.14  4757.3  798.59
  4906.1  798.20  4954.9  795.49  4986.3  795.18  4995.1  789.77  4995.3  789.27
  4999.1  789.77  5014.8  792.64  5039.0  794.27  5044.4  793.17  5063.2  795.81
  5355.5  799.66  5391.4  801.63  5410.2  800.52  5561.0  801.06  5613.6  802.40
  5679.7  801.82  5718.1  804.01  5730.7  803.31  5762.1  805.40  5853.3  807.72
#Mann=5,-1,0
  4443.2    0.05       0  4906.1    0.12       0  4995.1    0.07       0
  4999.1    0.12       0  5410.2    0.05       0
Bank Sta=4995.1,4999.1
Exp/Cntr=0.3,0.1

Chan Stop Cuts=-1