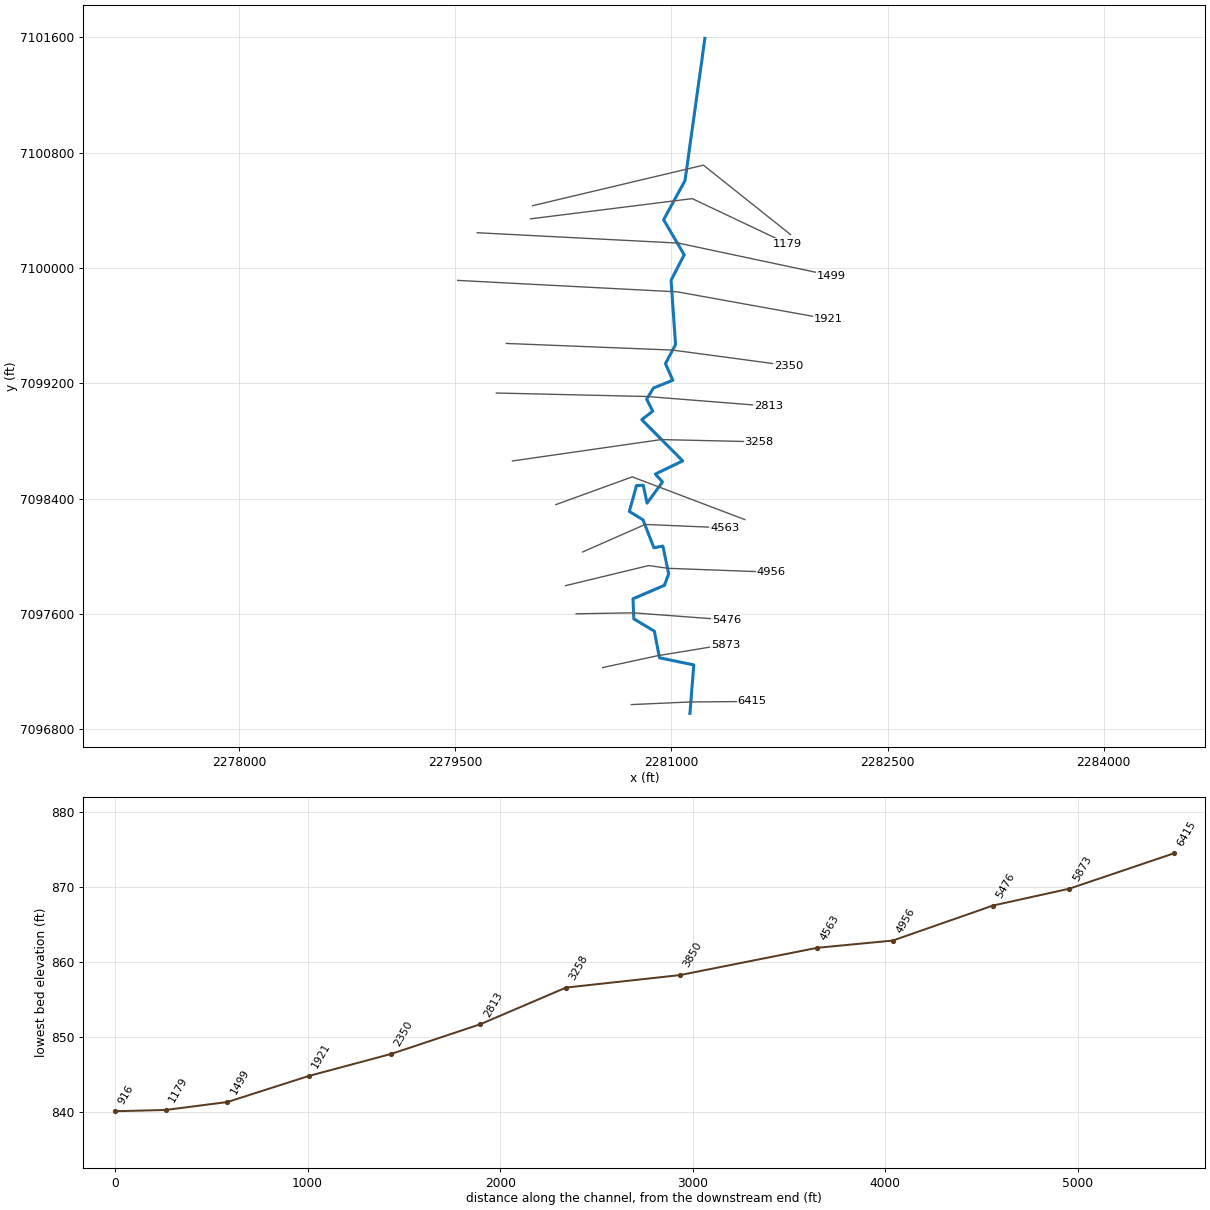
--- MDW T 020.prj (project) ---

Proj Title=MDW T 020 Base Level Engineering
Current Plan=p01
Default Exp/Contr=0.3,0.1
English Units
Geom File=g01
Flow File=f01
Plan File=p01
BEGIN DESCRIPTION:
MDW T 020
END DESCRIPTION:

--- MDW T 020.p01 (plan) ---

Plan Title=Multiple Run
Short Identifier=Multiple
Geom File=g01
Flow File=f01
Subcritical Flow
K Sum by GR= 0
Std Step Tol= 0.01
Critical Tol= 0.01
Num of Std Step Trials= 20
Max Error Tol= 0.3
Flow Tol Ratio= 0.001
Split Flow NTrial= 30
Split Flow Tol= 0.02
Split Flow Ratio= 0.02
Log Output Level= 0
Friction Slope Method= 1
Unsteady Friction Slope Method= 2
Unsteady Bridges Friction Slope Method= 1
Parabolic Critical Depth
Global Vel Dist=  1 , 1 , 1
Global Log Level= 0
CheckData=True
Encroach Param= -1, 0, 0, 0
BEGIN DESCRIPTION:
Multiple Run
END DESCRIPTION:

--- MDW T 020.f01 (steady flow) ---

Flow Title=Multiple
Number of Profiles=7
Profile Names=10-year,25-year,50-year,1pct_min,100-year,1pct_plu,500-year
River Rch & RM= MDW T 020,Reach-1,6415
     493     672     820     498     993    1981    1458
River Rch & RM= MDW T 020,Reach-1,4563
     597     823    1010     617    1231    2455    1828
River Rch & RM= MDW T 020,Reach-1,1921
     659     912    1124     688    1373    2739    2051
Boundary for River Rch & Prof#=MDW T 020,Reach-1,1
Up Type=0
Dn Type=3
Dn Slope=0.005
Boundary for River Rch & Prof#=MDW T 020,Reach-1,2
Up Type=0
Dn Type=3
Dn Slope=0.005
Boundary for River Rch & Prof#=MDW T 020,Reach-1,3
Up Type=0
Dn Type=3
Dn Slope=0.005
Boundary for River Rch & Prof#=MDW T 020,Reach-1,4
Up Type=0
Dn Type=3
Dn Slope=0.005
Boundary for River Rch & Prof#=MDW T 020,Reach-1,5
Up Type=0
Dn Type=3
Dn Slope=0.005
Boundary for River Rch & Prof#=MDW T 020,Reach-1,6
Up Type=0
Dn Type=3
Dn Slope=0.005
Boundary for River Rch & Prof#=MDW T 020,Reach-1,7
Up Type=0
Dn Type=3
Dn Slope=0.005

--- MDW T 020.g01 (geometry) ---

Geom Title=Existing Conditions

River Reach=MDW T 020,Reach-1
Reach XY= 30
      2281129.00      7096910.00      2281155.77      7097246.11
      2280917.69      7097295.63      2280882.08      7097480.38
      2280739.76      7097565.72      2280733.96      7097704.89
      2280951.96      7097798.36      2280981.44      7097877.97
      2280941.30      7098071.14      2280879.13      7098058.90
      2280803.39      7098252.78      2280708.50      7098311.09
      2280758.42      7098490.41      2280805.51      7098492.90
      2280831.63      7098368.34      2280938.77      7098515.35
      2280888.96      7098570.27      2281078.83      7098661.61
      2280794.86      7098947.60      2280870.85      7099006.69
      2280828.78      7099089.80      2280876.57      7099167.40
      2281010.21      7099221.52      2280959.26      7099336.31
      2281029.16      7099469.20      2280998.16      7099914.57
      2281089.10      7100091.48      2280946.53      7100334.67
      2281094.96      7100606.83      2281232.87      7101593.22

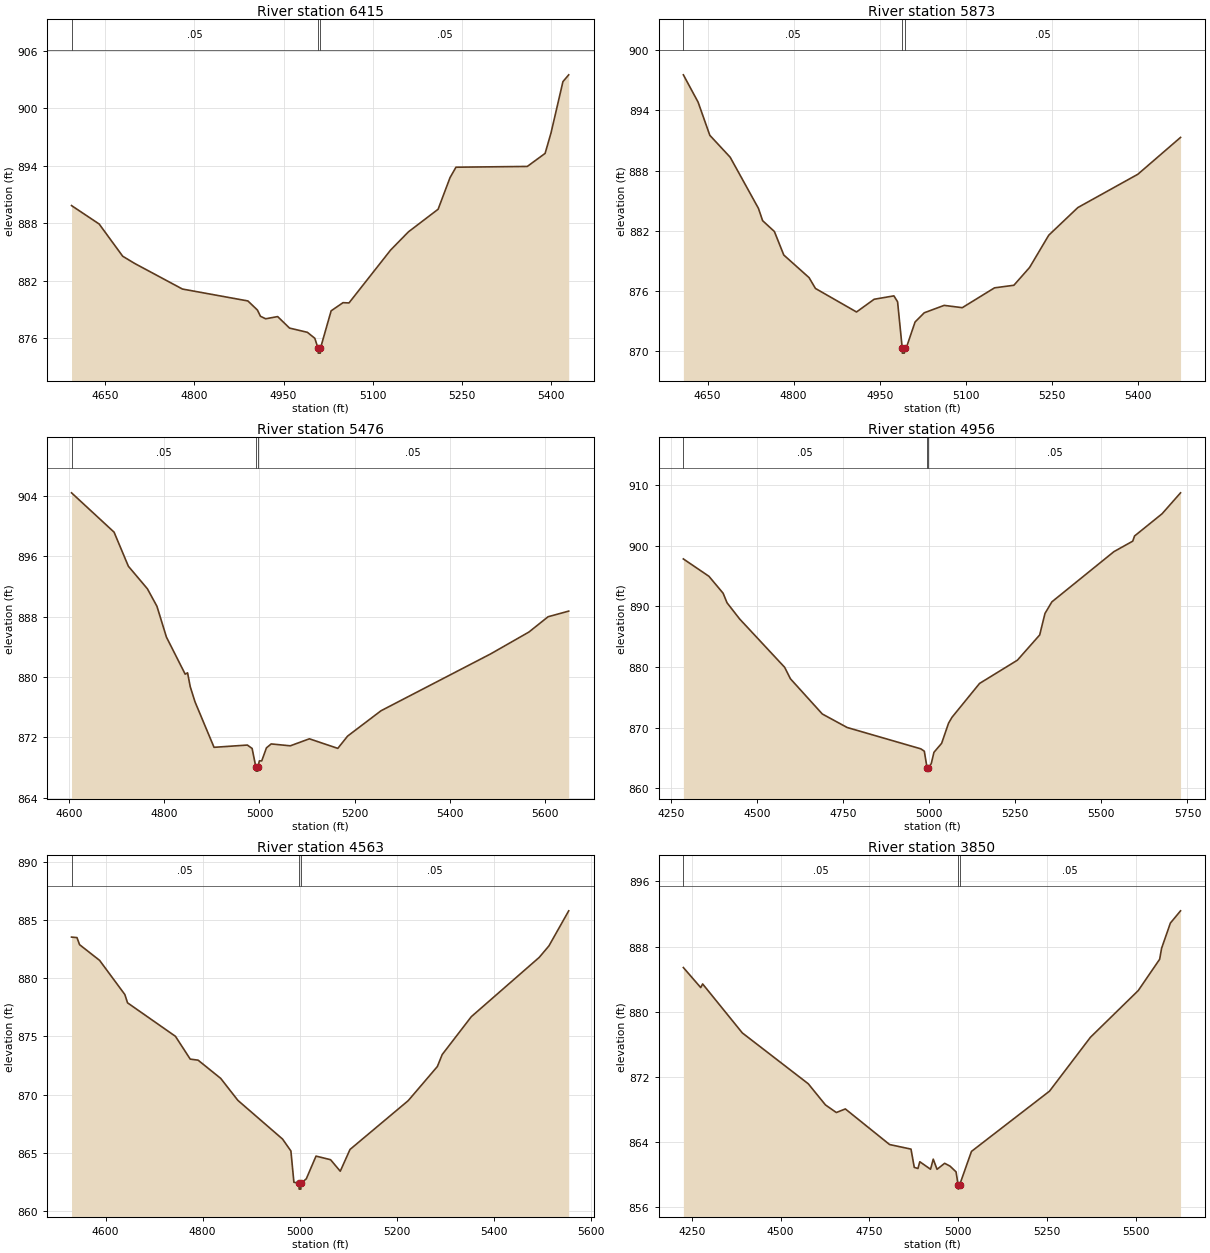
Type RM Length L Ch R = 1,6415,542,542,542
BEGIN DESCRIPTION:
MDW T 020 16.0
END DESCRIPTION:
XS GIS Cut Line= 3
      2280722.58      7096970.93      2281128.97      7096989.16
      2281558.66      7096992.46
#Sta/Elev= 30
  4593.2  889.85  4639.7  887.93  4679.3  884.57  4699.7  883.81  4779.8  881.15
  4889.9  879.91  4906.0  878.96  4911.1  878.31  4919.9  878.05  4940.0  878.28
  4960.0  877.08  4990.0  876.64  5002.5  876.02  5008.0  874.97  5008.3  874.47
  5011.8  874.47  5012.0  874.97  5030.0  878.88  5050.0  879.73  5060.0  879.70
  5130.0  885.21  5160.0  887.11  5210.0  889.47  5230.0  892.76  5240.0  893.85
  5360.0  893.93  5390.0  895.29  5400.0  897.44  5420.0  902.77  5429.7  903.48
#Mann=3,-1,0
  4593.2    0.05       0  5008.0   0.033       0  5012.0    0.05       0
Bank Sta=5008,5012
Exp/Cntr=0.3,0.1

Type RM Length L Ch R = 1,5873,397,397,397
BEGIN DESCRIPTION:
MDW T 020 15.0
END DESCRIPTION:
XS GIS Cut Line= 3
      2280523.90      7097227.87      2280903.67      7097309.78
      2281375.74      7097387.32
#Sta/Elev= 30
  4607.8  897.56  4633.5  894.83  4653.9  891.52  4689.4  889.33  4738.7  884.22
  4746.0  882.99  4766.5  881.91  4782.9  879.56  4827.0  877.30  4838.1  876.22
  4909.7  873.87  4940.4  875.14  4974.9  875.48  4981.3  874.89  4989.4  870.26
  4989.6  869.76  4993.1  869.76  4993.4  870.26  4996.3  870.26  5011.8  872.87
  5027.8  873.79  5062.5  874.53  5094.1  874.30  5150.3  876.28  5184.1  876.54
  5211.5  878.32  5244.9  881.54  5295.6  884.30  5400.3  887.63  5474.7  891.31
#Mann=3,-1,0
  4607.8    0.05       0  4989.4   0.033       0  4993.4    0.05       0
Bank Sta=4989.4,4993.4
Exp/Cntr=0.3,0.1

Type RM Length L Ch R = 1,5476,520,520,520
BEGIN DESCRIPTION:
MDW T 020 14.0
END DESCRIPTION:
XS GIS Cut Line= 3
      2280339.62      7097600.79      2280734.36      7097607.62
      2281382.25      7097559.13
#Sta/Elev= 30
  4605.2  904.45  4694.6  899.23  4724.6  894.71  4764.6  891.71  4784.6  889.40
  4804.6  885.30  4844.0  880.38  4849.0  880.56  4854.6  878.72  4864.6  876.71
  4904.6  870.67  4974.6  870.97  4984.6  870.52  4992.6  868.01  4992.9  867.51
  4996.4  867.51  4996.6  868.01  4999.8  868.87  5004.8  868.87  5014.7  870.60
  5024.7  871.12  5064.8  870.87  5104.9  871.80  5164.6  870.53  5185.2  872.16
  5255.3  875.52  5486.0  883.08  5566.1  885.97  5606.3  888.00  5649.7  888.75
#Mann=3,-1,0
  4605.2    0.05       0  4992.6   0.033       0  4996.6    0.05       0
Bank Sta=4992.6,4996.6
Exp/Cntr=0.3,0.1

Type RM Length L Ch R = 1,4956,393,393,393
BEGIN DESCRIPTION:
MDW T 020 13.0
END DESCRIPTION:
XS GIS Cut Line= 4
      2280266.76      7097796.11      2280842.26      7097935.43
      2280979.40      7097916.24      2281692.51      7097889.86
#Sta/Elev= 30
  4285.8  897.79  4360.1  894.93  4401.3  892.14  4412.6  890.57  4449.3  887.90
  4580.0  879.94  4596.8  878.05  4689.4  872.25  4761.4  870.03  4975.6  866.51
  4985.7  866.12  4993.8  863.34  4994.1  862.84  4997.6  862.84  4997.8  863.34
  5005.9  864.09  5013.7  865.94  5036.0  867.42  5056.0  870.73  5066.0  871.70
  5146.1  877.28  5256.2  881.12  5320.8  885.27  5336.2  888.81  5356.2  890.72
  5536.4  898.99  5591.1  900.72  5596.4  901.57  5676.5  905.24  5730.0  908.68
#Mann=3,-1,0
  4285.8    0.05       0  4993.8   0.033       0  4997.8    0.05       0
Bank Sta=4993.8,4997.8
Exp/Cntr=0.3,0.1

Type RM Length L Ch R = 1,4563,713,713,713
BEGIN DESCRIPTION:
MDW T 020 12.0
END DESCRIPTION:
XS GIS Cut Line= 3
      2280384.94      7098029.98      2280818.46      7098220.71
      2281369.65      7098197.49
#Sta/Elev= 30
  4529.6  883.54  4540.8  883.50  4546.2  882.89  4587.5  881.54  4639.6  878.60
  4645.1  877.89  4743.9  875.01  4774.4  873.05  4790.6  872.96  4837.3  871.39
  4872.7  869.50  4964.9  866.17  4982.0  865.15  4988.2  862.46  4998.8  862.37
  4999.0  861.87  5002.5  861.87  5002.8  862.37  5013.8  862.76  5033.8  864.71
  5063.8  864.40  5083.8  863.41  5103.9  865.28  5224.0  869.48  5284.0  872.41
  5294.0  873.44  5354.1  876.70  5494.2  881.80  5514.2  882.79  5554.9  885.80
#Mann=3,-1,0
  4529.6    0.05       0  4998.8   0.033       0  5002.8    0.05       0
Bank Sta=4998.8,5002.8
Exp/Cntr=0.3,0.1

Type RM Length L Ch R = 1,3850,592,592,592
BEGIN DESCRIPTION:
MDW T 020 11.0
END DESCRIPTION:
XS GIS Cut Line= 3
      2280198.68      7098358.08      2280728.82      7098550.86
      2281509.76      7098254.46
#Sta/Elev= 30
  4226.2  885.42  4275.1  882.96  4280.4  883.41  4392.1  877.40  4577.7  871.16
  4626.2  868.56  4656.8  867.63  4682.1  868.07  4806.7  863.70  4866.9  863.14
  4876.1  860.90  4886.4  860.76  4891.7  861.59  4921.9  860.67  4929.5  861.91
  4940.2  860.66  4961.6  861.40  4976.8  861.05  4993.7  860.35  4999.6  858.73
  4999.8  858.23  5003.6  858.73  5037.1  862.86  5256.7  870.25  5371.9  876.86
  5506.6  882.60  5566.8  886.44  5572.2  887.78  5597.0  890.88  5625.6  892.38
#Mann=3,-1,0
  4226.2    0.05       0  4999.6   0.033       0  5003.6    0.05       0
Bank Sta=4999.6,5003.6
Exp/Cntr=0.3,0.1

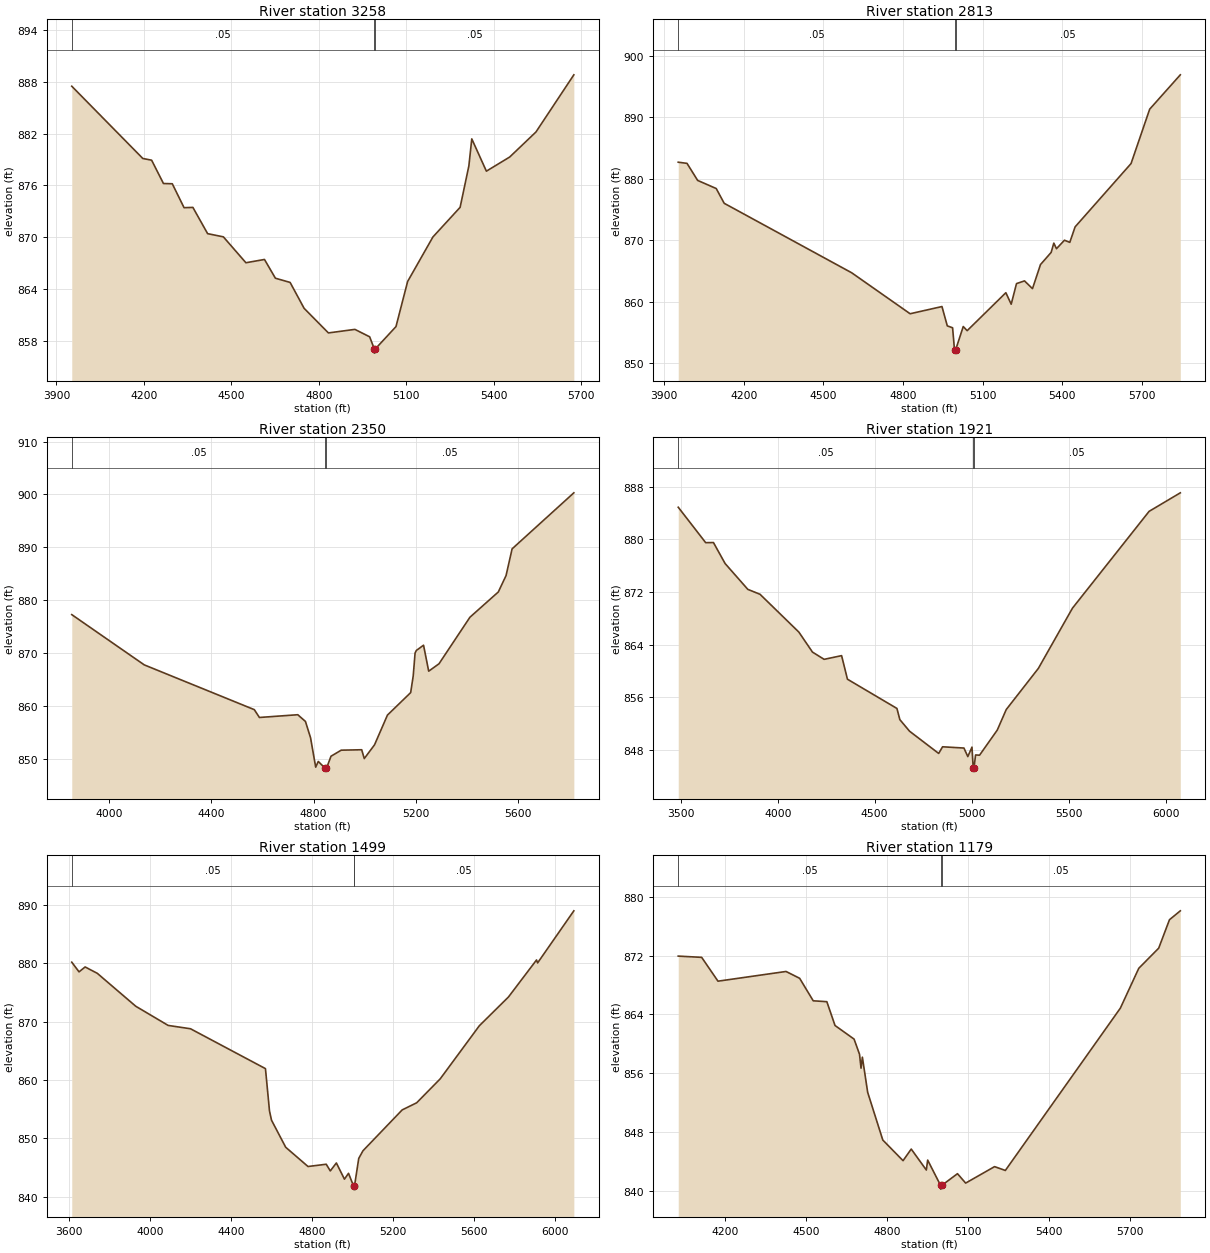
Type RM Length L Ch R = 1,3258,445,445,445
BEGIN DESCRIPTION:
MDW T 020 10.0
END DESCRIPTION:
XS GIS Cut Line= 3
      2279897.84      7098661.21      2280929.21      7098809.52
      2281608.86      7098794.03
#Sta/Elev= 30
  3952.8  887.48  4196.4  879.11  4226.7  878.91  4267.2  876.21  4297.5  876.18
  4337.9  873.41  4368.2  873.44  4418.7  870.40  4472.7  870.03  4550.0  867.03
  4613.7  867.41  4651.1  865.24  4701.6  864.75  4749.6  861.75  4832.9  858.90
  4923.8  859.31  4974.4  858.45  4990.1  857.06  4990.4  856.56  4994.1  857.06
  5064.6  859.63  5104.6  864.86  5191.4  870.02  5284.6  873.45  5314.6  878.25
  5324.6  881.38  5374.7  877.64  5454.7  879.28  5544.7  882.18  5674.6  888.80
#Mann=3,-1,0
  3952.8    0.05       0  4990.1   0.033       0  4994.1    0.05       0
Bank Sta=4990.1,4994.1
Exp/Cntr=0.3,0.1

Type RM Length L Ch R = 1,2813,463,463,463
BEGIN DESCRIPTION:
MDW T 020 9.0
END DESCRIPTION:
XS GIS Cut Line= 3
      2279785.95      7099132.57      2280832.37      7099108.26
      2281673.92      7099041.43
#Sta/Elev= 30
  3953.3  882.70  3986.4  882.51  4026.4  879.74  4096.4  878.42  4126.4  876.02
  4606.5  864.73  4826.6  858.07  4946.6  859.24  4966.6  856.10  4986.6  855.79
  4993.8  852.17  4994.1  851.67  4997.8  852.17  5026.7  855.99  5041.5  855.32
  5187.2  861.49  5207.3  859.62  5227.3  862.97  5257.4  863.41  5287.5  862.15
  5317.6  866.06  5357.8  868.04  5367.8  869.55  5377.8  868.64  5407.9  870.02
  5428.0  869.67  5448.0  872.19  5658.7  882.48  5728.9  891.32  5844.2  896.90
#Mann=3,-1,0
  3953.3    0.05       0  4993.8   0.033       0  4997.8    0.05       0
Bank Sta=4993.8,4997.8
Exp/Cntr=0.3,0.1

Type RM Length L Ch R = 1,2350,429,429,429
BEGIN DESCRIPTION:
MDW T 020 8.0
END DESCRIPTION:
XS GIS Cut Line= 3
      2279855.19      7099476.50      2281008.31      7099430.49
      2281811.98      7099322.67
#Sta/Elev= 30
  3853.7  877.29  4137.4  867.79  4568.1  859.33  4588.1  857.85  4738.2  858.37
  4768.2  857.10  4788.2  854.02  4808.3  848.46  4818.3  849.54  4846.3  848.21
  4846.5  847.71  4850.3  848.21  4868.3  850.53  4908.3  851.67  4988.4  851.75
  4998.4  850.08  5038.7  852.69  5089.1  858.30  5180.0  862.55  5190.0  865.71
  5197.3  870.04  5202.3  870.52  5230.4  871.51  5250.6  866.60  5290.9  868.00
  5412.0  876.80  5523.0  881.57  5553.3  884.67  5577.0  889.72  5818.6  900.31
#Mann=3,-1,0
  3853.7    0.05       0  4846.3   0.033       0  4850.3    0.05       0
Bank Sta=4846.3,4850.3
Exp/Cntr=0.3,0.1

Type RM Length L Ch R = 1,1921,422,422,422
BEGIN DESCRIPTION:
MDW T 020 7.0
END DESCRIPTION:
XS GIS Cut Line= 3
      2279517.64      7099913.83      2281043.47      7099834.14
      2282087.98      7099645.60
#Sta/Elev= 30
  3487.0  884.89  3628.6  879.50  3668.6  879.52  3728.7  876.33  3845.9  872.40
  3908.9  871.65  4109.2  865.90  4179.3  862.86  4239.4  861.76  4329.5  862.32
  4359.6  858.74  4614.9  854.29  4629.9  852.59  4680.0  850.83  4830.2  847.45
  4850.2  848.46  4960.4  848.27  4980.4  846.97  5001.9  848.41  5008.2  845.26
  5008.4  844.76  5012.2  845.26  5020.5  847.22  5040.9  847.18  5132.3  851.00
  5178.5  854.12  5344.2  860.38  5520.1  869.54  5915.3  884.26  6076.3  887.08
#Mann=3,-1,0
  3487.0    0.05       0  5008.2   0.033       0  5012.2    0.05       0
Bank Sta=5008.2,5012.2
Exp/Cntr=0.3,0.1

Type RM Length L Ch R = 1,1499,320,320,320
BEGIN DESCRIPTION:
MDW T 020 6.0
END DESCRIPTION:
XS GIS Cut Line= 3
      2279653.09      7100244.55      2281048.67      7100172.68
      2282108.82      7099947.68
#Sta/Elev= 30
  3613.8  880.22  3649.8  878.56  3679.8  879.40  3739.9  878.31  3930.1  872.66
  4090.3  869.37  4200.5  868.80  4571.0  861.96  4591.0  854.69  4601.0  853.11
  4671.1  848.47  4781.3  845.17  4871.4  845.56  4891.4  844.41  4921.4  845.78
  4961.3  843.00  4981.5  844.00  5006.9  841.79  5007.1  841.29  5010.9  841.79
  5032.0  846.56  5052.9  847.87  5246.7  854.88  5318.3  856.10  5434.7  860.21
  5628.1  869.32  5771.9  874.25  5910.6  880.60  5915.8  880.09  6095.0  889.03
#Mann=3,-1,0
  3613.8    0.05       0  5006.9   0.033       0  5010.9    0.05       0
Bank Sta=5006.9,5010.9
Exp/Cntr=0.3,0.1

Type RM Length L Ch R = 1,1179,263,263,263
BEGIN DESCRIPTION:
MDW T 020 5.0
END DESCRIPTION:
XS GIS Cut Line= 3
      2280022.92      7100340.91      2281145.03      7100481.27
      2281803.14      7100169.22
#Sta/Elev= 30
  4025.6  871.93  4112.4  871.76  4172.8  868.52  4424.8  869.84  4475.2  868.91
  4525.5  865.85  4575.9  865.73  4606.2  862.49  4676.7  860.64  4696.9  858.58
  4702.5  856.68  4707.5  858.18  4727.1  853.40  4783.1  846.91  4858.1  844.10
  4888.4  845.68  4944.3  842.83  4949.3  844.18  4997.2  840.73  4997.5  840.23
  5001.2  840.73  5059.7  842.33  5089.9  841.05  5197.0  843.29  5236.9  842.77
  5662.8  864.85  5731.0  870.27  5804.8  873.01  5844.7  876.88  5884.8  878.09
#Mann=3,-1,0
  4025.6    0.05       0  4997.2   0.033       0  5001.2    0.05       0
Bank Sta=4997.2,5001.2
Exp/Cntr=0.3,0.1

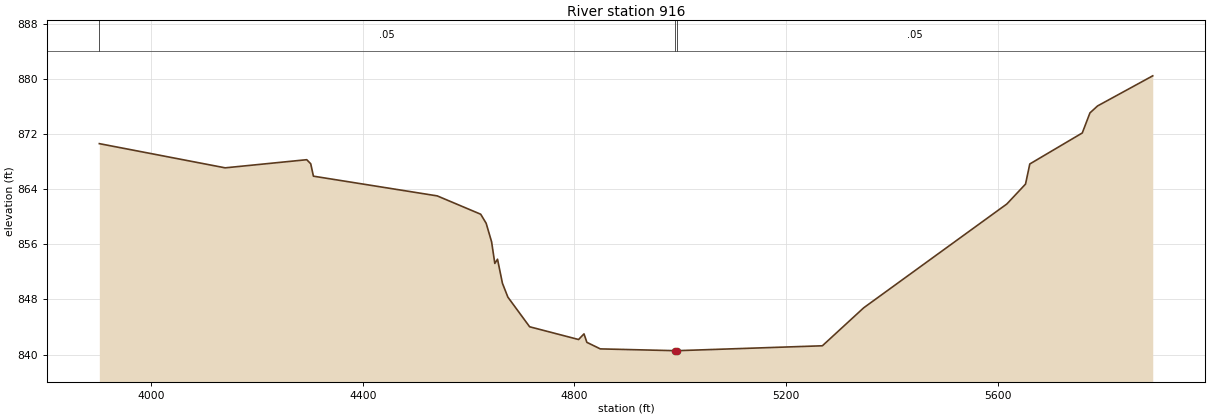
Type RM Length L Ch R = 1,916,0,0,0
BEGIN DESCRIPTION:
MDW T 020 4.0
END DESCRIPTION:
XS GIS Cut Line= 3
      2280037.53      7100432.23      2281222.58      7100713.34
      2281827.54      7100231.56
#Sta/Elev= 30
  3901.9  870.60  4139.8  867.09  4294.0  868.27  4301.5  867.68  4306.6  865.88
  4540.6  863.02  4622.8  860.36  4633.1  859.05  4643.4  856.36  4649.5  853.22
  4654.6  853.83  4663.9  850.34  4674.2  848.33  4715.3  844.03  4807.8  842.18
  4818.1  843.00  4823.5  841.77  4848.9  840.82  4990.4  840.56  4990.6  840.06
  4994.4  840.56  5268.7  841.27  5346.8  846.78  5617.5  861.85  5652.7  864.73
  5660.8  867.65  5760.0  872.15  5774.5  875.06  5788.9  876.07  5893.2  880.44
#Mann=3,-1,0
  3901.9    0.05       0  4990.4   0.033       0  4994.4    0.05       0
Bank Sta=4990.4,4994.4
Exp/Cntr=0.3,0.1

Chan Stop Cuts=-1