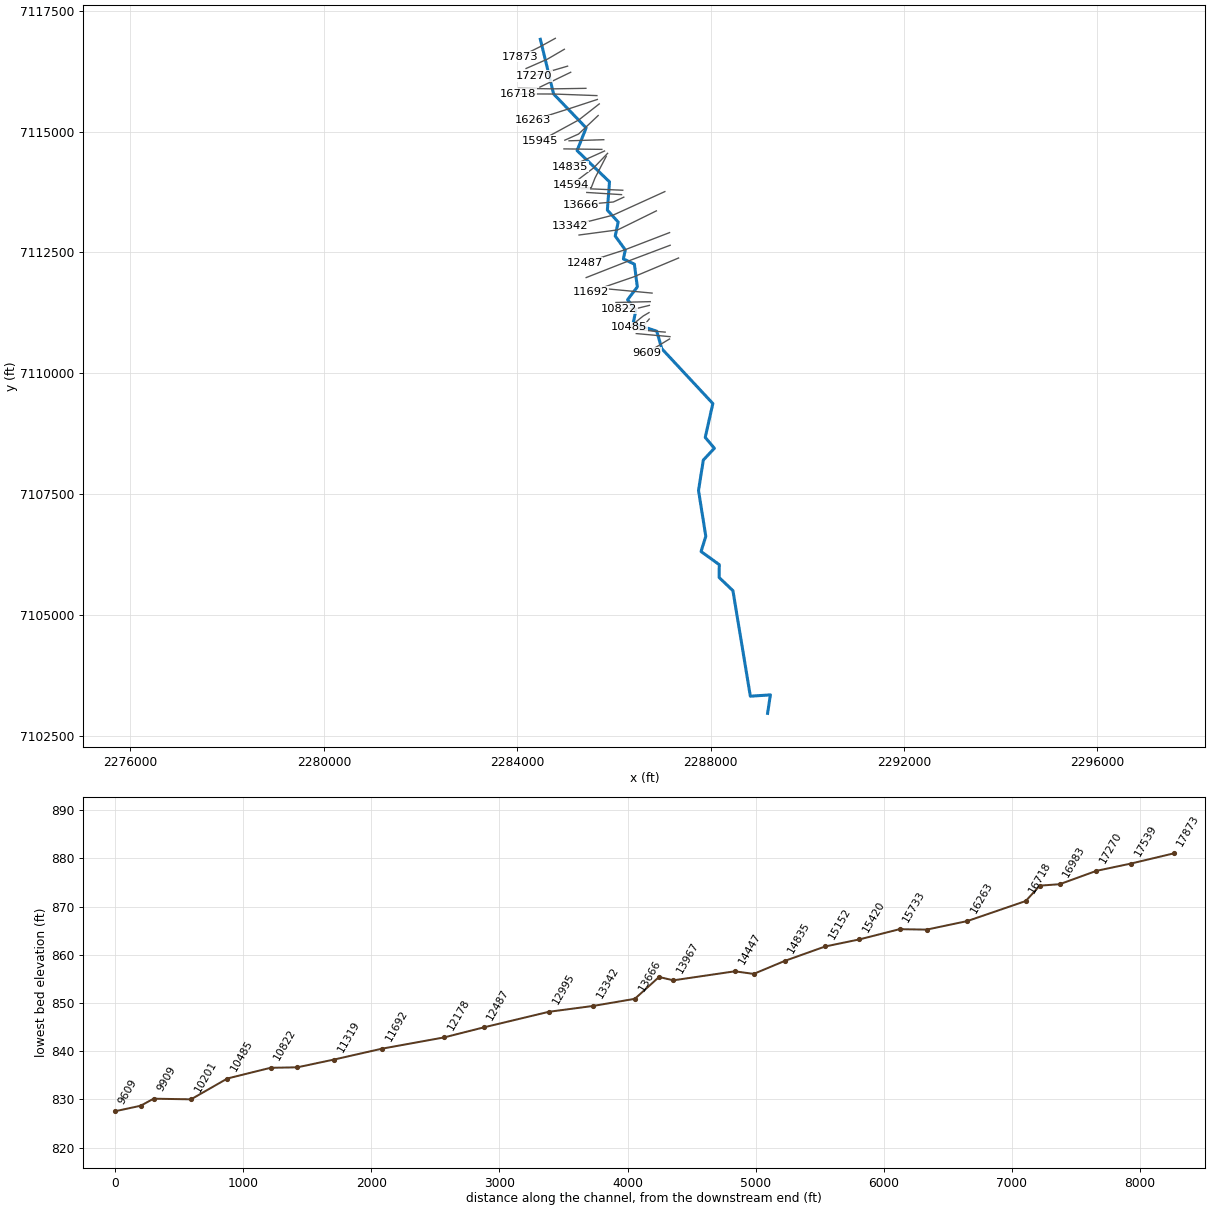
--- MDW T 021.prj (project) ---

Proj Title=MDW T 021 Base Level Engineering
Current Plan=p01
Default Exp/Contr=0.3,0.1
English Units
Geom File=g01
Flow File=f01
Plan File=p01
Y Axis Title=Elevation
X Axis Title(PF)=Main Channel Distance
X Axis Title(XS)=Station
BEGIN DESCRIPTION:
MDW T 021
END DESCRIPTION:
DSS Export Rating Curves= 0
DSS Export Rating Curve Sorted= 0
DSS Export Volume Flow Curves= 0
DXF OffsetX= 0
DXF OffsetY= 0
DXF ScaleX= 1
DXF ScaleY= 10

--- MDW T 021.p01 (plan) ---

Plan Title=Multiple Run
Short Identifier=Multiple
Geom File=g01
Flow File=f01
Subcritical Flow
K Sum by GR= 0
Std Step Tol= 0.01
Critical Tol= 0.01
Num of Std Step Trials= 20
Max Error Tol= 0.3
Flow Tol Ratio= 0.001
Split Flow NTrial= 30
Split Flow Tol= 0.02
Split Flow Ratio= 0.02
Log Output Level= 0
Friction Slope Method= 1
Unsteady Friction Slope Method= 2
Unsteady Bridges Friction Slope Method= 1
Parabolic Critical Depth
Global Vel Dist=  1 , 1 , 1
Global Log Level= 0
CheckData=True
Encroach Param= -1, 0, 0, 0
BEGIN DESCRIPTION:
Multiple Run
END DESCRIPTION:

--- MDW T 021.f01 (steady flow) ---

Flow Title=Multiple
Number of Profiles=7
Profile Names=10-year,25-year,50-year,1pct_min,100-year,1pct_plu,500-year
River Rch & RM= MDW T 021,Reach-1,17873
     581     796     973     591    1179    2353    1735
River Rch & RM= MDW T 021,Reach-1,13342
     791    1103    1365     838    1673    3338    2519
River Rch & RM= MDW T 021,Reach-1,12995
     880    1231    1527     939    1873    3738    2829
River Rch & RM= MDW T 021,Reach-1,8582
    1127    1597    1998    1239    2471    4931    3793
River Rch & RM= MDW T 021,Reach-1,3829
    1166    1656    2073    1286    2566    5119    3943
River Rch & RM= MDW T 021,Reach-1,2757
    1182    1678    2101    1303    2600    5187    3993
Boundary for River Rch & Prof#=MDW T 021,Reach-1,1
Up Type=0
Dn Type=3
Dn Slope=0.005
Boundary for River Rch & Prof#=MDW T 021,Reach-1,2
Up Type=0
Dn Type=3
Dn Slope=0.005
Boundary for River Rch & Prof#=MDW T 021,Reach-1,3
Up Type=0
Dn Type=3
Dn Slope=0.005
Boundary for River Rch & Prof#=MDW T 021,Reach-1,4
Up Type=0
Dn Type=3
Dn Slope=0.005
Boundary for River Rch & Prof#=MDW T 021,Reach-1,5
Up Type=0
Dn Type=3
Dn Slope=0.005
Boundary for River Rch & Prof#=MDW T 021,Reach-1,6
Up Type=0
Dn Type=3
Dn Slope=0.005
Boundary for River Rch & Prof#=MDW T 021,Reach-1,7
Up Type=0
Dn Type=3
Dn Slope=0.005

--- MDW T 021.g01 (geometry) ---

Geom Title=Existing Conditions

River Reach=MDW T 021,Reach-1
Reach XY= 30
      2284479.00      7116910.00      2284753.19      7115779.45
      2285425.52      7115077.93      2285238.81      7114607.38
      2285909.22      7113960.19      2285865.01      7113375.58
      2286088.80      7113128.15      2286027.40      7112838.85
      2286235.87      7112552.22      2286196.31      7112365.02
      2286424.45      7112256.90      2286484.81      7111785.40
      2286283.21      7111520.18      2286455.31      7111302.82
      2286398.00      7111032.24      2286886.62      7110868.95
      2286991.61      7110506.58      2288046.88      7109372.47
      2287889.60      7108671.25      2288078.93      7108447.27
      2287849.98      7108202.16      2287750.54      7107572.84
      2287901.36      7106625.05      2287803.08      7106309.90
      2288180.45      7106037.55      2288176.68      7105772.44
      2288462.57      7105499.56      2288822.61      7103315.57
      2289237.53      7103342.56      2289179.00      7102960.00

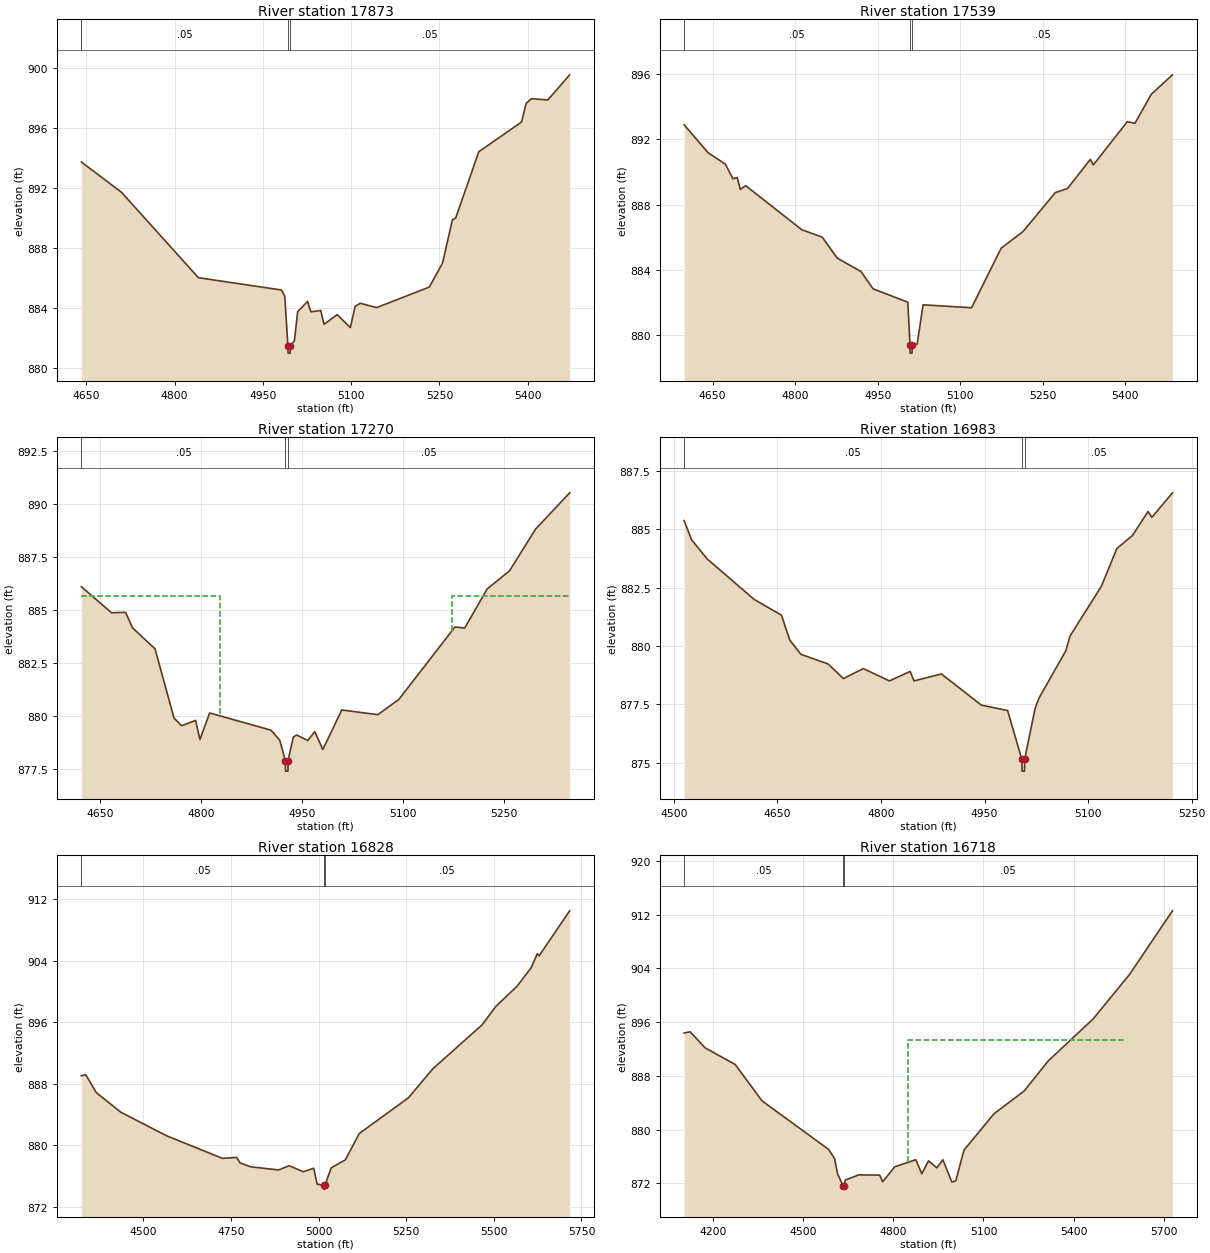
Type RM Length L Ch R = 1,17873,334,334,334
BEGIN DESCRIPTION:
MDW T 021 36.0
END DESCRIPTION:
XS GIS Cut Line= 3
      2284788.64      7116930.63      2284474.59      7116757.93
      2284052.85      7116547.55
#Sta/Elev= 30
  4641.6  893.74  4709.7  891.73  4840.5  886.04  4981.6  885.22  4987.3  884.81
  4992.6  881.52  4992.9  881.02  4996.4  881.02  4996.6  881.52  5003.6  881.83
  5009.2  883.78  5026.0  884.46  5031.6  883.77  5048.4  883.86  5054.0  882.94
  5076.3  883.58  5098.7  882.72  5106.8  884.13  5115.5  884.34  5143.5  884.05
  5233.0  885.42  5255.3  887.01  5272.1  889.89  5277.7  890.01  5316.9  894.42
  5389.6  896.40  5397.4  897.64  5406.4  897.95  5434.3  897.87  5471.3  899.54
#Mann=3,-1,0
  4641.6    0.05       0  4992.6    0.04       0  4996.6    0.05       0
Bank Sta=4992.6,4996.6
Exp/Cntr=0.3,0.1

Type RM Length L Ch R = 1,17539,269,269,269
BEGIN DESCRIPTION:
MDW T 021 35.0
END DESCRIPTION:
XS GIS Cut Line= 3
      2284975.70      7116704.52      2284624.48      7116499.69
      2284183.82      7116306.59
#Sta/Elev= 30
  4598.2  892.90  4641.7  891.19  4673.1  890.49  4687.0  889.59  4694.6  889.67
  4700.4  888.94  4710.1  889.17  4812.1  886.47  4849.1  886.02  4876.6  884.73
  4919.6  883.91  4941.7  882.85  5004.8  882.03  5008.8  879.41  5009.0  878.91
  5012.5  878.91  5012.8  879.41  5021.8  879.46  5032.6  881.87  5120.8  881.69
  5174.5  885.34  5214.3  886.36  5272.8  888.74  5295.3  889.00  5336.6  890.78
  5342.1  890.44  5403.8  893.09  5417.7  892.99  5447.5  894.77  5485.9  895.96
#Mann=3,-1,0
  4598.2    0.05       0  5008.8    0.04       0  5012.8    0.05       0
Bank Sta=5008.8,5012.8
Exp/Cntr=0.3,0.1

Type RM Length L Ch R = 1,17270,287,287,287
BEGIN DESCRIPTION:
Mapping XS 30ca60dc
END DESCRIPTION:
XS GIS Cut Line= 2
      2285042.11      7116354.98      2284345.33      7116150.75
#Sta/Elev= 30
  4621.6  886.09  4666.5  884.86  4687.4  884.88  4697.8  884.15  4731.2  883.16
  4759.4  879.90  4770.7  879.54  4791.6  879.79  4798.0  878.89  4812.4  880.14
  4903.5  879.33  4916.6  878.86  4925.0  877.90  4925.3  877.40  4928.8  877.40
  4929.0  877.90  4936.9  879.01  4942.1  879.10  4958.3  878.84  4968.7  879.26
  4980.7  878.42  5008.9  880.28  5062.5  880.06  5093.8  880.78  5177.1  884.19
  5191.6  884.14  5225.0  885.98  5258.4  886.84  5297.0  888.80  5347.7  890.51
#Mann=3,-1,0
  4621.6    0.05       0  4925.0    0.04       0  4929.0    0.05       0
#XS Ineff=2,0
    0.00 4827.10  885.67 5172.90    0.00  885.67
Permanent Ineff=
       F       F
Bank Sta=4925,4929
Exp/Cntr=0.3,0.1

Type RM Length L Ch R = 1,16983,155,155,155
BEGIN DESCRIPTION:
Mapping XS 03f3f18d
END DESCRIPTION:
XS GIS Cut Line= 2
      2285106.70      7116228.36      2284469.87      7115920.82
#Sta/Elev= 30
  4514.9  885.38  4525.8  884.55  4548.4  883.73  4616.2  882.00  4655.9  881.32
  4667.8  880.26  4684.0  879.64  4723.3  879.23  4745.6  878.60  4774.4  879.03
  4812.2  878.50  4842.3  878.91  4847.8  878.50  4887.5  878.80  4945.4  877.46
  4983.4  877.23  5004.0  875.13  5004.3  874.63  5007.8  874.63  5008.0  875.13
  5023.1  877.31  5028.6  877.75  5067.6  879.79  5073.8  880.43  5119.0  882.55
  5141.6  884.18  5164.2  884.74  5186.8  885.77  5192.4  885.52  5222.1  886.57
#Mann=3,-1,0
  4514.9    0.05       0  5004.0    0.04       0  5008.0    0.05       0
Bank Sta=5004,5008
Exp/Cntr=0.3,0.1

Type RM Length L Ch R = 1,16828,110,110,110
BEGIN DESCRIPTION:
MDW T 021 34.0
END DESCRIPTION:
XS GIS Cut Line= 3
      2285421.78      7115895.88      2284744.15      7115885.11
      2284029.05      7115896.41
#Sta/Elev= 30
  4323.3  889.04  4336.1  889.17  4366.1  886.85  4436.1  884.31  4566.1  881.26
  4726.1  878.32  4766.1  878.45  4776.1  877.74  4806.1  877.23  4886.1  876.82
  4916.2  877.37  4956.2  876.59  4986.2  877.04  4996.1  874.97  5014.2  874.83
  5014.4  874.33  5017.9  874.33  5018.2  874.83  5036.2  877.10  5076.2  878.12
  5116.2  881.55  5256.2  886.18  5326.2  889.96  5466.2  895.64  5506.2  898.07
  5566.2  900.66  5606.2  903.05  5624.0  904.89  5629.0  904.60  5716.2  910.45
#Mann=3,-1,0
  4323.3    0.05       0  5014.2   0.033       0  5018.2    0.05       0
Bank Sta=5014.2,5018.2
Exp/Cntr=0.3,0.1

Type RM Length L Ch R = 1,16718,455,455,455
BEGIN DESCRIPTION:
MDW T 021 33.0
END DESCRIPTION:
XS GIS Cut Line= 3
      2285648.85      7115745.37      2284748.11      7115778.34
      2284025.56      7115780.09
#Sta/Elev= 30
  4104.6  894.37  4124.5  894.55  4174.5  892.16  4274.6  889.68  4363.7  884.27
  4584.8  877.06  4604.8  875.70  4614.8  873.45  4632.8  871.64  4633.1  871.14
  4636.8  871.64  4640.5  872.49  4684.8  873.26  4754.9  873.23  4764.9  872.23
  4804.9  874.46  4875.0  875.52  4895.0  873.43  4917.3  875.34  4945.0  874.31
  4965.0  875.52  4995.0  872.18  5008.0  872.37  5035.1  876.93  5135.1  882.36
  5235.1  885.73  5315.1  890.20  5465.1  896.48  5585.1  903.04  5728.5  912.55
#Mann=3,-1,0
  4104.6    0.05       0  4632.8   0.033       0  4636.8    0.05       0
#XS Ineff=1,-1
 4850.00 5571.00  893.36
Permanent Ineff=
       F
Bank Sta=4632.8,4636.8
Exp/Cntr=0.3,0.1

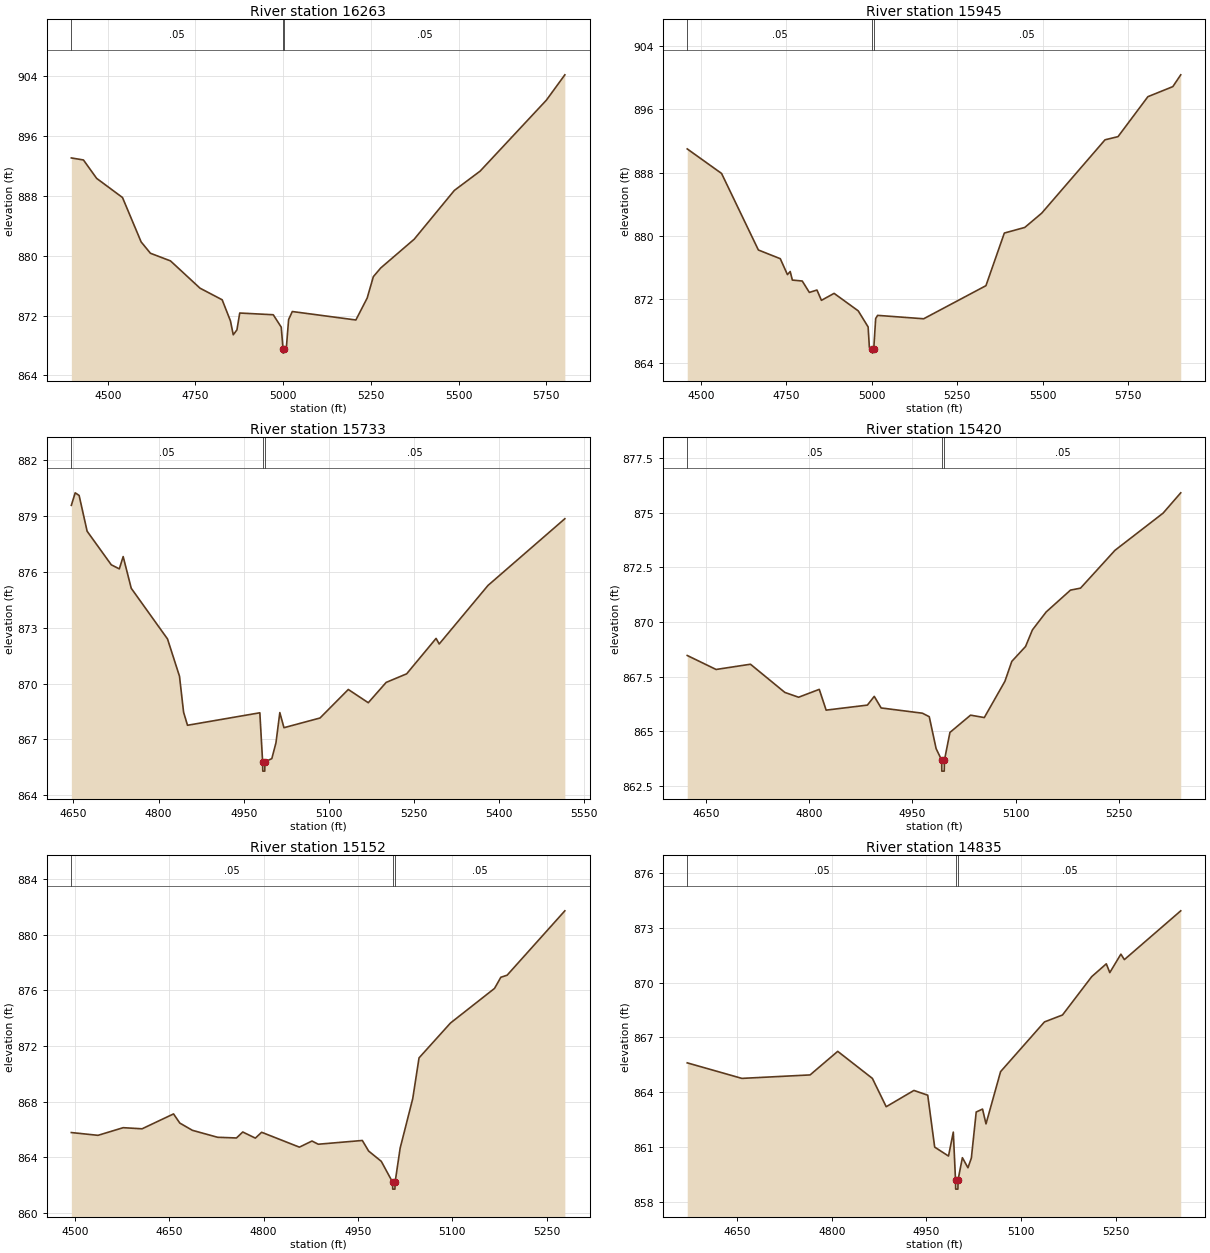
Type RM Length L Ch R = 1,16263,318,318,318
BEGIN DESCRIPTION:
MDW T 021 32.0
END DESCRIPTION:
XS GIS Cut Line= 3
      2285657.51      7115665.50      2285080.41      7115476.14
      2284318.99      7115233.22
#Sta/Elev= 30
  4396.2  893.08  4430.7  892.81  4468.3  890.35  4542.0  887.79  4595.1  881.86
  4621.6  880.34  4678.8  879.32  4763.0  875.67  4826.1  874.12  4849.7  871.30
  4857.7  869.44  4868.2  870.10  4876.2  872.35  4971.7  872.12  4994.5  870.46
  4999.7  867.49  4999.9  866.99  5003.7  867.49  5008.8  867.57  5015.5  871.48
  5026.0  872.55  5207.2  871.42  5239.4  874.35  5257.0  877.21  5278.0  878.37
  5373.5  882.22  5487.9  888.74  5561.4  891.32  5750.3  900.81  5802.8  904.19
#Mann=3,-1,0
  4396.2    0.05       0  4999.7   0.033       0  5003.7    0.05       0
Bank Sta=4999.7,5003.7
Exp/Cntr=0.3,0.1

Type RM Length L Ch R = 1,15945,212,212,212
BEGIN DESCRIPTION:
MDW T 021 31.0
END DESCRIPTION:
XS GIS Cut Line= 3
      2285697.45      7115573.49      2285278.13      7115244.64
      2284478.72      7114809.62
#Sta/Elev= 30
  4460.3  891.01  4560.7  887.91  4668.3  878.24  4732.4  877.14  4753.3  875.13
  4761.4  875.52  4767.7  874.44  4796.6  874.32  4817.4  872.88  4839.6  873.18
  4852.7  871.88  4889.7  872.76  4960.3  870.55  4989.2  868.52  4992.9  865.93
  5001.6  865.71  5001.8  865.21  5005.6  865.71  5011.3  869.58  5017.0  869.98
  5151.6  869.55  5333.7  873.73  5387.5  880.38  5447.3  881.09  5496.7  882.89
  5681.9  892.16  5719.9  892.56  5807.3  897.61  5880.2  898.88  5903.3  900.37
#Mann=3,-1,0
  4460.3    0.05       0  5001.6   0.033       0  5005.6    0.05       0
Bank Sta=5001.6,5005.6
Exp/Cntr=0.3,0.1

Type RM Length L Ch R = 1,15733,313,313,313
BEGIN DESCRIPTION:
Mapping XS ff091364
END DESCRIPTION:
XS GIS Cut Line= 3
      2285675.26      7115333.13      2285270.30      7114950.68
      2284985.46      7114822.89
#Sta/Elev= 30
  4646.4  879.56  4653.2  880.23  4660.1  880.09  4674.2  878.17  4716.7  876.37
  4730.9  876.15  4737.7  876.81  4751.9  875.11  4815.8  872.39  4836.9  870.39
  4844.1  868.46  4851.0  867.76  4978.4  868.43  4983.3  865.80  4983.6  865.30
  4987.1  865.30  4987.3  865.80  4999.5  865.97  5006.8  866.82  5013.6  868.44
  5020.9  867.63  5084.4  868.15  5134.2  869.68  5169.4  868.97  5200.9  870.06
  5237.0  870.52  5288.8  872.42  5294.3  872.12  5380.2  875.26  5515.6  878.84
#Mann=3,-1,0
  4646.4    0.05       0  4983.3   0.033       0  4987.3    0.05       0
Bank Sta=4983.3,4987.3
Exp/Cntr=0.3,0.1

Type RM Length L Ch R = 1,15420,268,268,268
BEGIN DESCRIPTION:
Mapping XS 922134d2
END DESCRIPTION:
XS GIS Cut Line= 2
      2285790.97      7114832.60      2285073.32      7114809.95
#Sta/Elev= 30
  4622.4  868.47  4664.4  867.83  4714.4  868.07  4764.4  866.78  4784.4  866.56
  4814.5  866.92  4824.5  865.97  4884.5  866.20  4894.5  866.60  4904.5  866.07
  4964.5  865.83  4974.5  865.67  4984.5  864.21  4992.6  863.68  4992.8  863.18
  4996.3  863.18  4996.6  863.68  5004.6  864.95  5034.6  865.74  5054.6  865.63
  5084.6  867.29  5094.6  868.20  5114.6  868.88  5124.6  869.64  5144.6  870.46
  5180.0  871.46  5194.6  871.55  5244.7  873.28  5314.7  874.98  5340.4  875.91
#Mann=3,-1,0
  4622.4    0.05       0  4992.6   0.033       0  4996.6    0.05       0
Bank Sta=4992.6,4996.6
Exp/Cntr=0.3,0.1

Type RM Length L Ch R = 1,15152,317,317,317
BEGIN DESCRIPTION:
Mapping XS db193223
END DESCRIPTION:
XS GIS Cut Line= 2
      2285751.41      7114632.22      2284967.28      7114642.67
#Sta/Elev= 30
  4494.5  865.78  4536.9  865.58  4576.9  866.13  4606.9  866.05  4656.9  867.12
  4666.9  866.46  4686.9  865.94  4726.9  865.44  4756.9  865.39  4766.9  865.82
  4786.9  865.38  4796.9  865.80  4856.9  864.73  4876.9  865.17  4886.9  864.94
  4956.9  865.21  4966.9  864.45  4987.0  863.71  5005.0  862.21  5005.2  861.71
  5008.7  861.71  5009.0  862.21  5017.0  864.66  5037.0  868.22  5047.0  871.15
  5097.0  873.66  5167.0  876.15  5177.0  876.95  5187.0  877.10  5278.7  881.73
#Mann=3,-1,0
  4494.5    0.05       0  5005.0   0.033       0  5009.0    0.05       0
Bank Sta=5005,5009
Exp/Cntr=0.3,0.1

Type RM Length L Ch R = 1,14835,241,241,241
BEGIN DESCRIPTION:
Mapping XS 681a3260
END DESCRIPTION:
XS GIS Cut Line= 2
      2285806.39      7114599.01      2285093.59      7114277.88
#Sta/Elev= 30
  4571.0  865.61  4657.6  864.76  4765.6  864.95  4809.4  866.24  4864.3  864.76
  4886.2  863.21  4930.1  864.10  4952.0  863.84  4963.0  861.00  4984.9  860.51
  4992.5  861.82  4996.0  859.20  4996.3  858.70  4999.8  858.70  5000.0  859.20
  5006.9  860.42  5015.7  859.87  5021.1  860.40  5028.8  862.92  5038.8  863.08
  5044.3  862.27  5067.4  865.13  5136.9  867.85  5165.5  868.23  5211.8  870.33
  5234.9  871.03  5240.4  870.55  5258.0  871.56  5263.5  871.26  5352.8  873.93
#Mann=3,-1,0
  4571.0    0.05       0  4996.0   0.033       0  5000.0    0.05       0
Bank Sta=4996,5000
Exp/Cntr=0.3,0.1

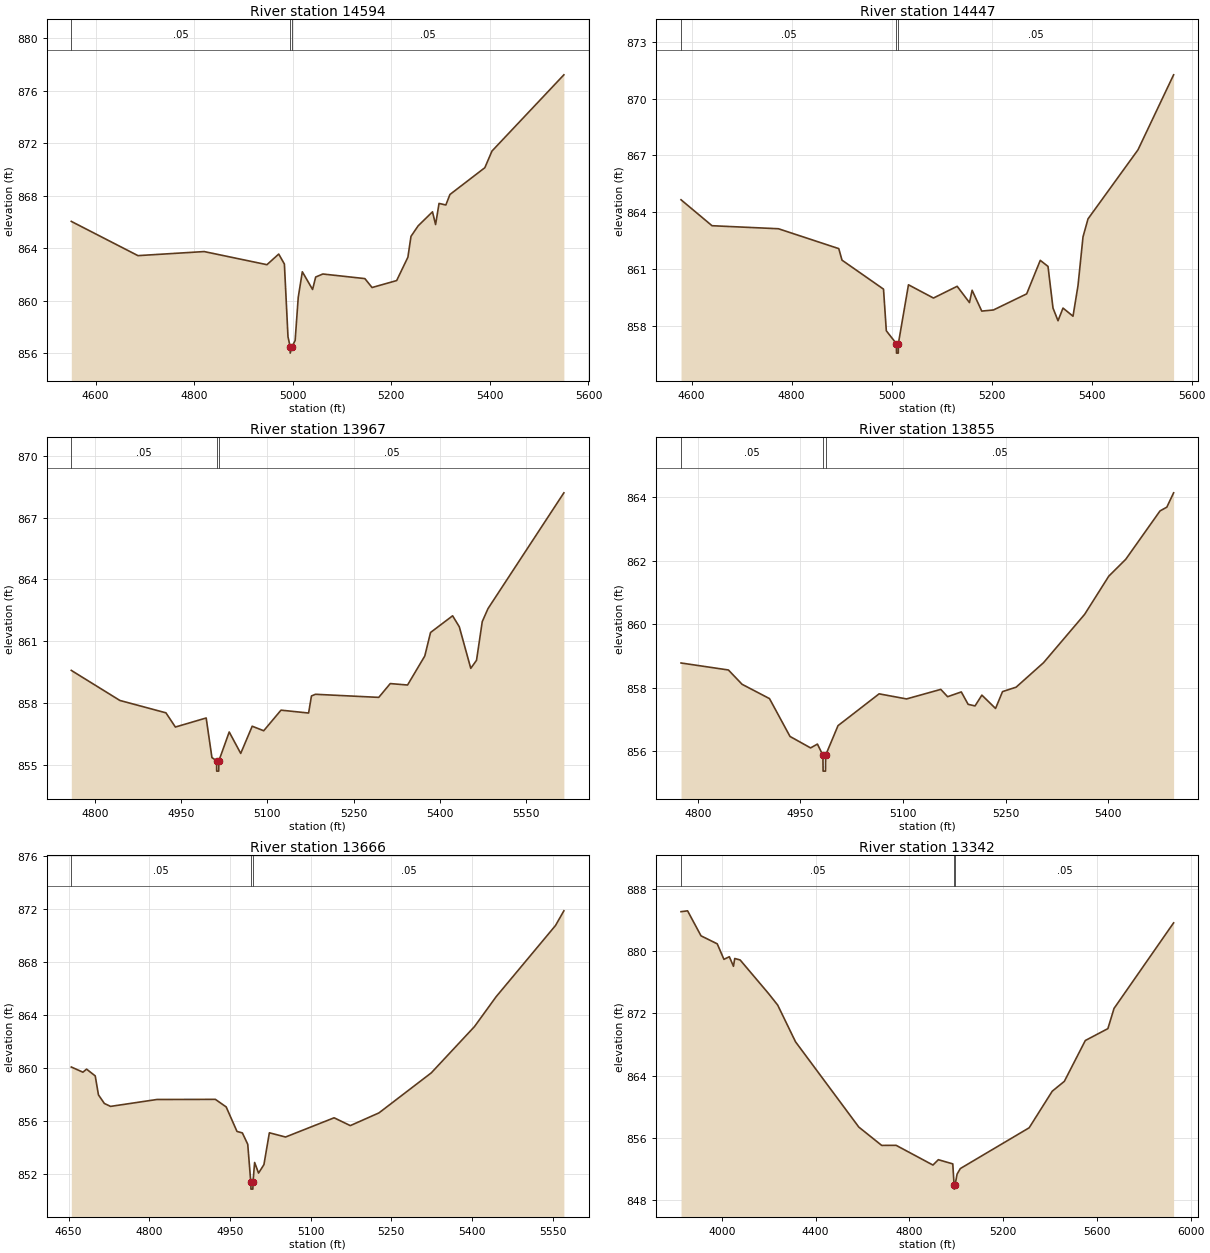
Type RM Length L Ch R = 1,14594,147,147,147
BEGIN DESCRIPTION:
MDW T 021 28.0
END DESCRIPTION:
XS GIS Cut Line= 3
      2285869.80      7114550.40      2285580.83      7114248.97
      2285117.23      7113897.24
#Sta/Elev= 30
  4550.6  866.06  4685.9  863.45  4820.2  863.76  4947.6  862.76  4971.5  863.57
  4983.0  862.81  4990.3  857.27  4994.6  856.52  4994.8  856.02  4998.6  856.52
  5004.8  856.98  5011.1  860.27  5019.4  862.22  5040.2  860.87  5046.5  861.82
  5061.0  862.05  5146.3  861.70  5160.9  861.02  5210.8  861.55  5233.6  863.33
  5239.9  864.92  5254.4  865.72  5283.5  866.79  5289.8  865.82  5296.8  867.43
  5310.6  867.31  5318.9  868.11  5389.7  870.15  5404.2  871.42  5550.1  877.23
#Mann=3,-1,0
  4550.6    0.05       0  4994.6   0.033       0  4998.6    0.05       0
Bank Sta=4994.6,4998.6
Exp/Cntr=0.3,0.1

Type RM Length L Ch R = 1,14447,480,480,480
BEGIN DESCRIPTION:
Mapping XS e8f30b1c
END DESCRIPTION:
XS GIS Cut Line= 4
      2285842.36      7114490.24      2285608.77      7114038.64
      2285532.10      7113840.49      2285267.80      7113840.48
#Sta/Elev= 30
  4578.7  864.66  4640.7  863.29  4773.5  863.13  4894.2  862.08  4900.7  861.47
  4983.7  859.94  4989.3  857.74  5009.4  857.06  5009.7  856.56  5013.2  856.56
  5013.4  857.06  5033.6  860.17  5083.6  859.47  5131.0  860.09  5155.6  859.23
  5160.9  859.88  5180.2  858.78  5203.6  858.84  5270.0  859.69  5297.2  861.46
  5312.7  861.14  5322.7  858.94  5332.7  858.27  5342.7  858.94  5362.7  858.51
  5372.7  860.13  5382.7  862.70  5392.7  863.65  5492.7  867.30  5563.9  871.26
#Mann=3,-1,0
  4578.7    0.05       0  5009.4   0.033       0  5013.4    0.05       0
Bank Sta=5009.4,5013.4
Exp/Cntr=0.3,0.1

Type RM Length L Ch R = 1,13967,112,112,112
BEGIN DESCRIPTION:
Mapping XS 34ef4f79
END DESCRIPTION:
XS GIS Cut Line= 3
      2286183.52      7113787.19      2285543.28      7113814.63
      2285327.03      7113817.69
#Sta/Elev= 30
  4758.8  859.58  4843.4  858.12  4923.5  857.52  4939.9  856.83  4993.5  857.27
  5003.5  855.35  5011.6  855.19  5011.8  854.69  5015.3  854.69  5015.6  855.19
  5033.6  856.59  5053.6  855.55  5073.6  856.87  5093.6  856.65  5123.7  857.65
  5171.7  857.51  5176.7  858.34  5183.7  858.42  5293.8  858.27  5313.8  858.94
  5343.9  858.87  5373.9  860.28  5383.9  861.42  5422.3  862.23  5433.9  861.70
  5453.9  859.68  5463.9  860.07  5473.9  861.95  5483.9  862.58  5615.9  868.20
#Mann=3,-1,0
  4758.8    0.05       0  5011.6   0.033       0  5015.6    0.05       0
Bank Sta=5011.6,5015.6
Exp/Cntr=0.3,0.1

Type RM Length L Ch R = 1,13855,189,189,189
BEGIN DESCRIPTION:
Mapping XS 16a9ebd4
END DESCRIPTION:
XS GIS Cut Line= 2
      2286158.13      7113696.04      2285439.13      7113740.88
#Sta/Elev= 30
  4775.3  858.78  4844.6  858.56  4864.6  858.11  4904.7  857.66  4934.7  856.47
  4964.8  856.11  4974.8  856.23  4982.8  855.88  4983.1  855.38  4986.6  855.38
  4986.8  855.88  5004.9  856.81  5065.0  857.81  5105.1  857.65  5155.2  857.95
  5165.2  857.72  5185.2  857.87  5195.2  857.48  5205.3  857.43  5215.3  857.77
  5235.3  857.35  5245.5  857.88  5265.4  858.02  5305.5  858.79  5365.6  860.31
  5400.9  861.51  5425.7  862.04  5475.8  863.56  5485.8  863.68  5495.7  864.13
#Mann=3,-1,0
  4775.3    0.05       0  4982.8   0.033       0  4986.8    0.05       0
Bank Sta=4982.8,4986.8
Exp/Cntr=0.3,0.1

Type RM Length L Ch R = 1,13666,324,324,324
BEGIN DESCRIPTION:
Mapping XS a87e9c59
END DESCRIPTION:
XS GIS Cut Line= 3
      2286204.80      7113643.53      2285989.31      7113543.73
      2285313.42      7113485.16
#Sta/Elev= 30
  4655.1  860.06  4676.7  859.67  4683.5  859.90  4699.6  859.39  4705.6  857.96
  4716.6  857.31  4728.1  857.09  4814.2  857.61  4923.0  857.62  4943.1  857.05
  4963.2  855.20  4973.2  855.09  4983.2  854.23  4988.9  851.35  4989.2  850.85
  4992.7  850.85  4992.9  851.35  4996.0  852.86  5003.3  852.06  5013.3  852.70
  5023.4  855.10  5053.5  854.78  5143.8  856.23  5173.9  855.64  5227.2  856.60
  5324.5  859.62  5404.8  863.11  5445.0  865.36  5555.4  870.73  5571.0  871.84
#Mann=3,-1,0
  4655.1    0.05       0  4988.9   0.033       0  4992.9    0.05       0
Bank Sta=4988.9,4992.9
Exp/Cntr=0.3,0.1

Type RM Length L Ch R = 1,13342,347,347,347
BEGIN DESCRIPTION:
MDW T 021 25.0
END DESCRIPTION:
XS GIS Cut Line= 3
      2287054.46      7113759.05      2285980.70      7113270.70
      2285087.41      7113042.02
#Sta/Elev= 30
  3825.6  885.11  3853.6  885.22  3910.9  882.00  3980.1  880.97  4008.7  878.97
  4031.7  879.31  4049.3  878.08  4054.8  879.08  4077.9  878.89  4198.7  874.58
  4238.1  873.08  4314.0  868.36  4584.2  857.37  4681.9  855.01  4743.4  855.02
  4900.5  852.48  4923.5  853.17  4985.1  852.63  4990.7  849.88  4991.0  849.38
  4994.7  849.88  5003.4  851.31  5017.3  852.03  5311.0  857.28  5409.5  861.99
  5461.1  863.26  5550.6  868.52  5646.9  870.05  5673.1  872.65  5927.3  883.67
#Mann=3,-1,0
  3825.6    0.05       0  4990.7    0.04       0  4994.7    0.05       0
Bank Sta=4990.7,4994.7
Exp/Cntr=0.3,0.1

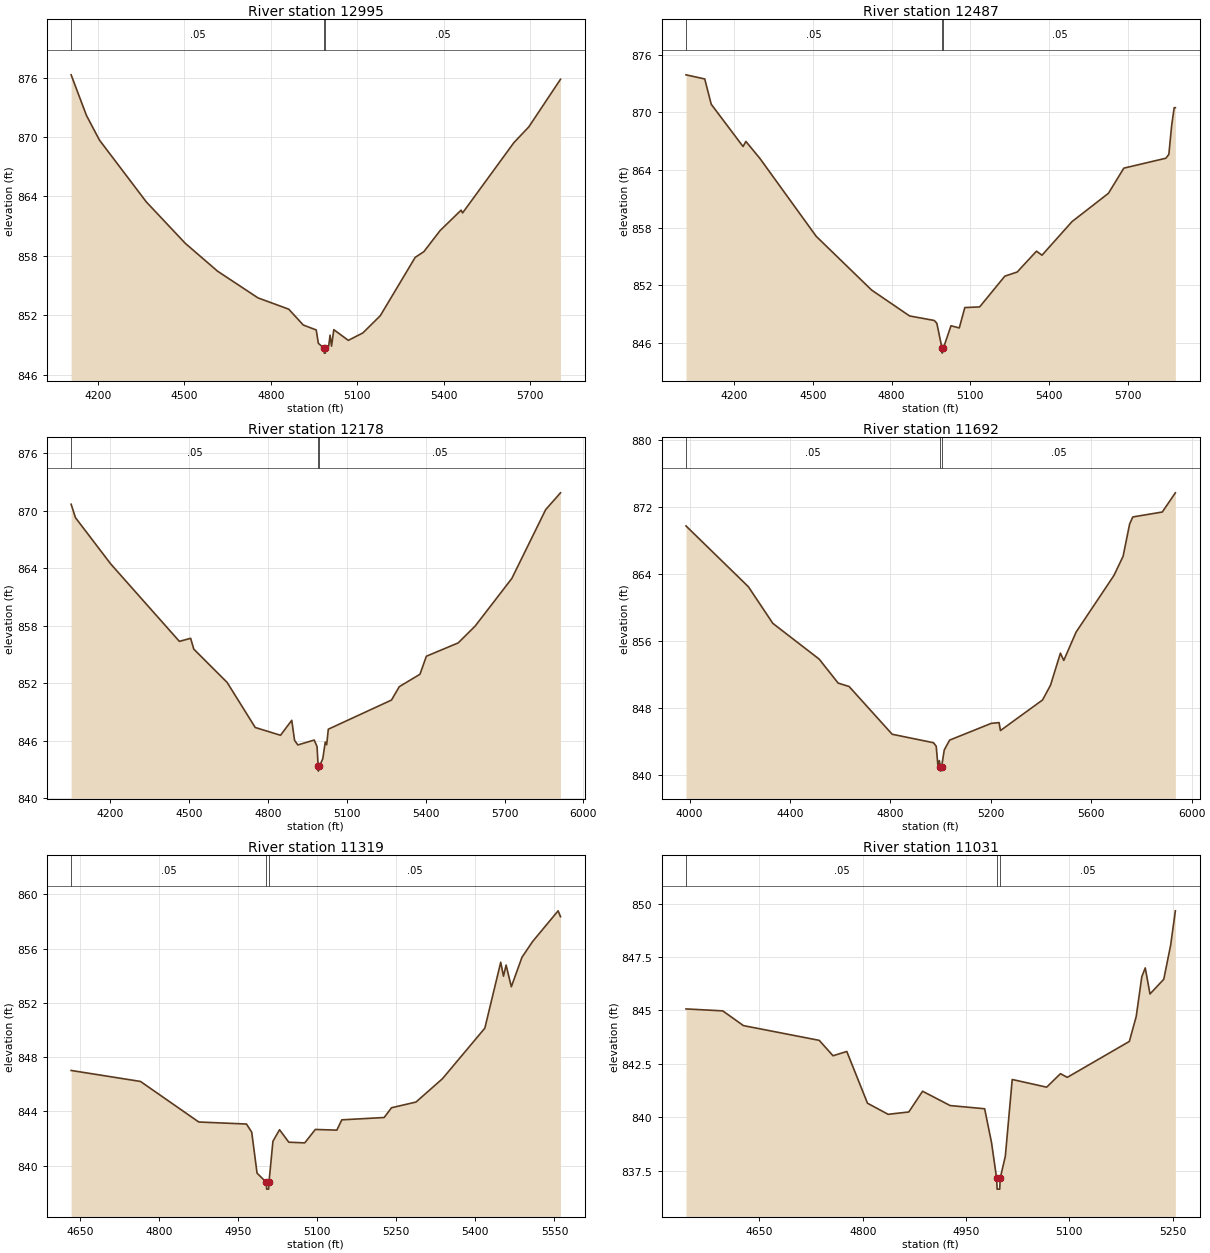
Type RM Length L Ch R = 1,12995,508,508,508
BEGIN DESCRIPTION:
MDW T 021 24.0
END DESCRIPTION:
XS GIS Cut Line= 3
      2286878.96      7113359.98      2286079.44      7112966.32
      2285278.95      7112859.99
#Sta/Elev= 30
  4106.9  876.27  4160.2  872.16  4205.2  869.68  4368.0  863.43  4502.8  859.26
  4615.1  856.44  4755.5  853.74  4862.2  852.60  4912.7  851.00  4957.7  850.50
  4965.1  849.15  4985.0  848.66  4985.6  848.16  4989.3  848.16  4989.8  848.66
  5000.8  848.85  5005.8  849.97  5010.9  848.87  5018.7  850.53  5069.1  849.45
  5119.6  850.20  5180.1  851.94  5301.2  857.83  5331.4  858.41  5387.4  860.53
  5460.6  862.60  5465.7  862.32  5644.1  869.43  5695.6  871.01  5805.6  875.82
#Mann=3,-1,0
  4106.9    0.05       0  4985.0    0.04       0  4989.8    0.05       0
Bank Sta=4985,4989.8
Exp/Cntr=0.3,0.1

Type RM Length L Ch R = 1,12487,309,309,309
BEGIN DESCRIPTION:
MDW T 021 23.0
END DESCRIPTION:
XS GIS Cut Line= 3
      2287151.91      7112910.20      2286227.07      7112554.02
      2285395.39      7112285.19
#Sta/Elev= 30
  4016.1  873.89  4087.5  873.46  4112.2  870.83  4233.5  866.43  4244.3  866.96
  4297.8  865.19  4512.2  857.09  4723.7  851.49  4868.2  848.80  4962.2  848.33
  4972.1  848.04  4991.9  845.43  4992.5  844.93  4996.8  845.43  5026.1  847.78
  5057.7  847.55  5078.7  849.67  5135.3  849.74  5231.3  852.94  5278.4  853.37
  5351.9  855.54  5373.0  855.12  5487.5  858.62  5626.1  861.56  5684.9  864.18
  5845.0  865.21  5856.4  865.61  5866.9  868.57  5876.7  870.47  5881.2  870.47
#Mann=3,-1,0
  4016.1    0.05       0  4991.9    0.04       0  4996.8    0.05       0
Bank Sta=4991.9,4996.8
Exp/Cntr=0.3,0.1

Type RM Length L Ch R = 1,12178,486,486,486
BEGIN DESCRIPTION:
MDW T 021 22.0
END DESCRIPTION:
XS GIS Cut Line= 3
      2287164.46      7112648.46      2286272.97      7112311.89
      2285426.62      7111979.19
#Sta/Elev= 30
  4050.7  870.68  4067.2  869.28  4201.5  864.45  4462.7  856.38  4505.5  856.70
  4517.5  855.57  4644.4  852.10  4751.3  847.40  4847.5  846.59  4890.3  848.15
  4901.0  846.06  4913.4  845.58  4975.8  846.09  4986.5  845.41  4990.9  843.35
  4991.5  842.85  4995.8  843.35  5008.4  844.15  5017.8  845.88  5023.2  845.60
  5029.4  847.22  5269.8  850.26  5299.6  851.66  5378.2  852.95  5402.6  854.83
  5523.6  856.22  5588.1  857.97  5727.8  862.94  5856.7  870.12  5913.0  871.87
#Mann=3,-1,0
  4050.7    0.05       0  4990.9    0.04       0  4995.8    0.05       0
Bank Sta=4990.9,4995.8
Exp/Cntr=0.3,0.1

Type RM Length L Ch R = 1,11692,373,373,373
BEGIN DESCRIPTION:
MDW T 021 21.0
END DESCRIPTION:
XS GIS Cut Line= 3
      2287338.05      7112384.57      2286399.08      7111990.04
      2285518.67      7111686.67
#Sta/Elev= 30
  3985.4  869.77  4233.8  862.52  4331.5  858.14  4515.9  853.88  4591.8  851.01
  4635.2  850.61  4806.8  844.91  4971.4  843.90  4982.3  843.48  4989.4  841.06
  4994.8  841.77  4998.8  841.01  4999.4  840.51  5003.7  841.01  5014.3  843.03
  5035.7  844.21  5201.6  846.21  5232.8  846.30  5238.1  845.35  5405.9  849.00
  5437.6  850.76  5477.2  854.59  5490.5  853.72  5539.6  857.10  5690.4  863.86
  5726.9  866.15  5752.9  870.00  5765.5  870.84  5883.0  871.43  5935.1  873.72
#Mann=3,-1,0
  3985.4    0.05       0  4998.8    0.04       0  5003.7    0.05       0
Bank Sta=4998.8,5003.7
Exp/Cntr=0.3,0.1

Type RM Length L Ch R = 1,11319,288,288,288
BEGIN DESCRIPTION:
Mapping XS 43cb9217
END DESCRIPTION:
XS GIS Cut Line= 2
      2286789.92      7111658.25      2285866.19      7111745.11
#Sta/Elev= 30
  4633.6  847.01  4765.1  846.20  4875.6  843.21  4966.0  843.06  4976.0  842.46
  4986.1  839.44  5003.7  838.76  5004.3  838.26  5008.1  838.26  5008.7  838.76
  5016.2  841.79  5028.7  842.64  5046.3  841.72  5076.5  841.67  5096.6  842.66
  5137.4  842.61  5146.8  843.37  5227.1  843.54  5241.0  844.26  5287.4  844.68
  5337.6  846.40  5418.0  850.13  5448.1  854.99  5453.3  853.96  5458.3  854.78
  5468.2  853.18  5488.3  855.35  5508.4  856.51  5556.9  858.78  5561.4  858.35
#Mann=3,-1,0
  4633.6    0.05       0  5003.7    0.04       0  5008.7    0.05       0
Bank Sta=5003.7,5008.7
Exp/Cntr=0.3,0.1

Type RM Length L Ch R = 1,11031,209,209,209
BEGIN DESCRIPTION:
Mapping XS a028791e
END DESCRIPTION:
XS GIS Cut Line= 2
      2286752.33      7111481.27      2286042.24      7111463.88
#Sta/Elev= 30
  4543.5  845.07  4596.8  844.98  4626.9  844.29  4736.9  843.60  4756.9  842.88
  4776.9  843.08  4806.9  840.66  4836.9  840.14  4866.9  840.25  4886.9  841.22
  4926.9  840.55  4977.0  840.40  4987.0  838.81  4994.4  837.14  4995.1  836.64
  4998.9  836.64  4999.5  837.14  5007.0  838.18  5017.0  841.77  5067.0  841.41
  5087.0  842.04  5097.0  841.87  5187.0  843.55  5197.0  844.72  5205.1  846.58
  5210.1  846.99  5217.0  845.77  5237.0  846.46  5247.0  848.06  5253.8  849.66
#Mann=3,-1,0
  4543.5    0.05       0  4994.4    0.04       0  4999.5    0.05       0
Bank Sta=4994.4,4999.5
Exp/Cntr=0.3,0.1

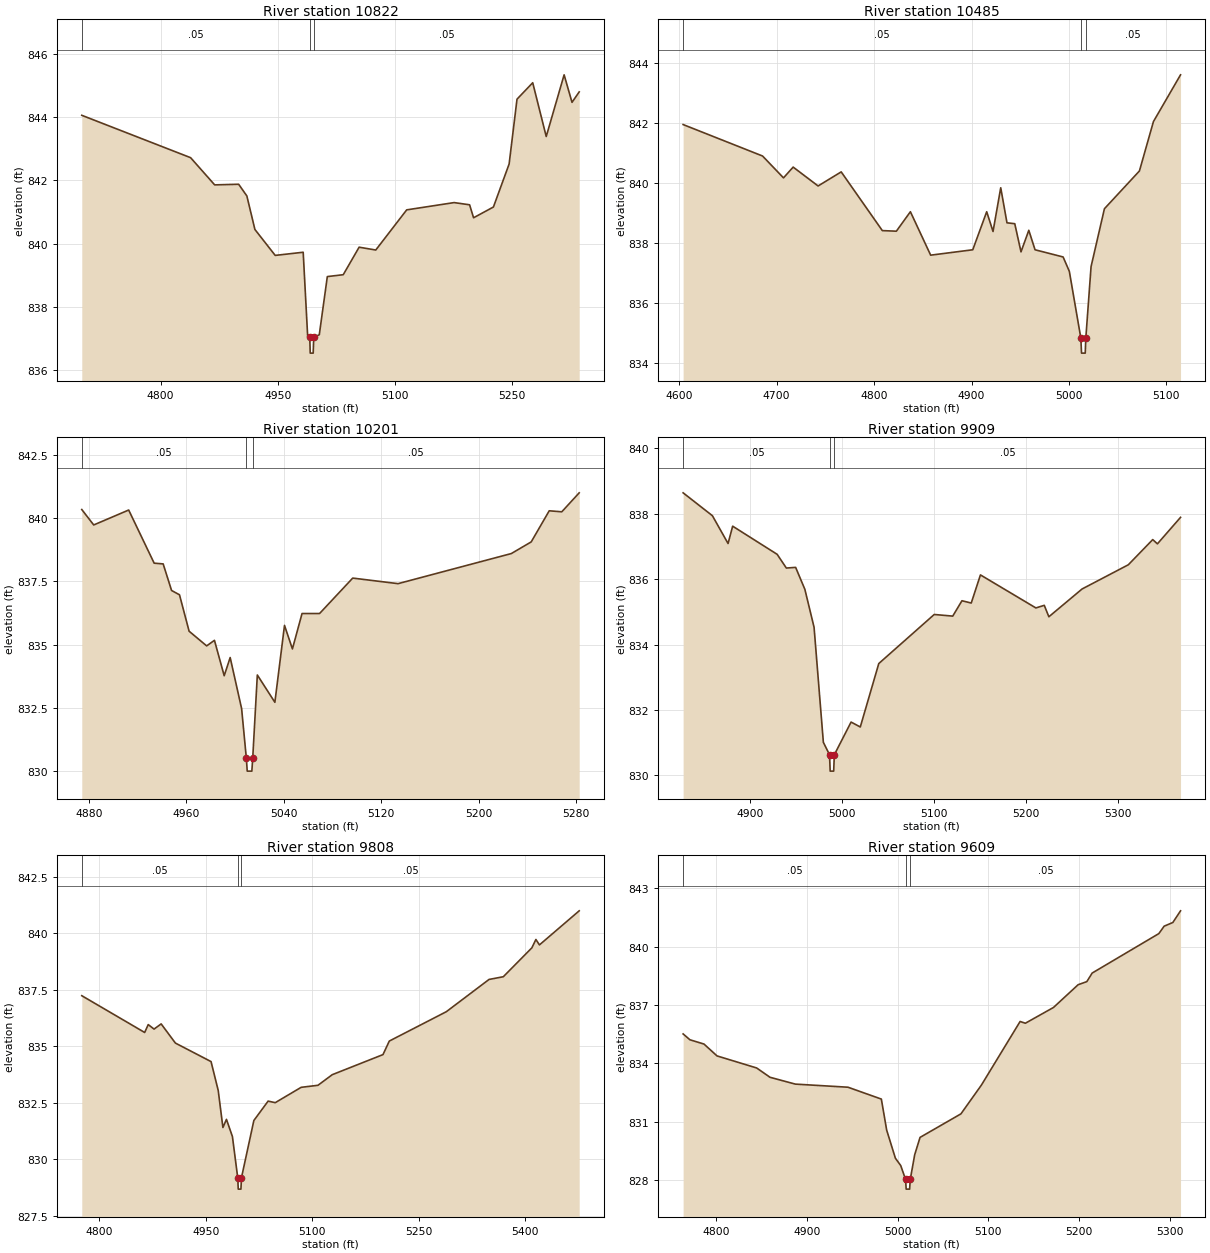
Type RM Length L Ch R = 1,10822,337,337,337
BEGIN DESCRIPTION:
Mapping XS fe252512
END DESCRIPTION:
XS GIS Cut Line= 4
      2286734.27      7111403.90      2286419.28      7111326.82
      2286288.14      7111349.58      2286109.81      7111330.83
#Sta/Elev= 30
  4699.2  844.06  4838.5  842.72  4869.3  841.86  4900.0  841.88  4910.5  841.51
  4920.8  840.45  4946.8  839.63  4982.6  839.73  4988.4  837.04  4991.0  837.04
  4991.6  836.54  4995.4  836.54  4996.1  837.04  5003.2  837.12  5013.5  838.96
  5033.9  839.02  5054.2  839.89  5075.5  839.80  5115.1  841.07  5175.8  841.30
  5195.6  841.23  5200.7  840.82  5226.1  841.16  5246.2  842.52  5256.3  844.57
  5276.4  845.09  5293.7  843.39  5316.6  845.34  5326.7  844.47  5335.9  844.80
#Mann=3,-1,0
  4699.2    0.05       0  4991.0    0.04       0  4996.1    0.05       0
Bank Sta=4991,4996.1
Exp/Cntr=0.3,0.1

Type RM Length L Ch R = 1,10485,284,284,284
BEGIN DESCRIPTION:
Mapping XS 47e06ace
END DESCRIPTION:
XS GIS Cut Line= 3
      2286726.96      7111254.69      2286606.82      7111184.23
      2286318.29      7110950.82
#Sta/Elev= 30
  4604.1  841.95  4685.6  840.90  4707.1  840.17  4717.0  840.53  4742.6  839.90
  4766.3  840.37  4808.5  838.41  4822.9  838.39  4837.3  839.04  4858.1  837.59
  4901.3  837.77  4915.6  839.04  4922.1  838.38  4930.0  839.84  4936.4  838.67
  4944.4  838.64  4950.8  837.70  4958.8  838.42  4965.2  837.77  4994.0  837.53
  5000.4  837.05  5012.2  834.82  5012.9  834.32  5016.7  834.32  5017.3  834.82
  5022.7  837.21  5036.4  839.14  5072.3  840.40  5086.7  842.05  5114.5  843.61
#Mann=3,-1,0
  4604.1    0.05       0  5012.2    0.04       0  5017.3    0.05       0
Bank Sta=5012.2,5017.3
Exp/Cntr=0.3,0.1

Type RM Length L Ch R = 1,10201,292,292,292
BEGIN DESCRIPTION:
Mapping XS a0591341
END DESCRIPTION:
XS GIS Cut Line= 3
      2286730.75      7111121.90      2286582.59      7110939.27
      2286415.18      7110895.15
#Sta/Elev= 30
  4874.2  840.34  4884.0  839.73  4912.7  840.32  4933.6  838.22  4941.0  838.19
  4947.9  837.14  4954.4  836.97  4962.3  835.53  4976.7  834.95  4983.1  835.17
  4991.1  833.77  4996.0  834.49  5005.4  832.47  5009.3  830.50  5010.0  830.00
  5013.8  830.00  5014.5  830.50  5018.3  833.80  5032.7  832.72  5040.6  835.76
  5047.1  834.83  5055.0  836.23  5069.4  836.23  5096.6  837.63  5133.8  837.41
  5226.8  838.60  5243.1  839.06  5257.9  840.29  5268.2  840.25  5282.5  841.00
#Mann=3,-1,0
  4874.2    0.05       0  5009.3    0.04       0  5014.5    0.05       0
Bank Sta=5009.3,5014.5
Exp/Cntr=0.3,0.1

Type RM Length L Ch R = 1,9909,101,101,101
BEGIN DESCRIPTION:
Mapping XS 354fb0fb
END DESCRIPTION:
XS GIS Cut Line= 2
      2287060.70      7110850.60      2286522.54      7110897.49
#Sta/Elev= 30
  4827.5  838.64  4859.3  837.94  4876.3  837.09  4881.3  837.62  4929.6  836.76
  4939.6  836.34  4949.7  836.36  4959.7  835.69  4969.7  834.53  4979.8  831.01
  4986.5  830.63  4987.2  830.13  4991.0  830.13  4991.7  830.63  5009.9  831.63
  5019.9  831.48  5040.0  833.42  5100.2  834.92  5120.3  834.87  5130.3  835.34
  5140.4  835.27  5150.4  836.13  5210.6  835.12  5219.7  835.20  5224.7  834.85
  5260.8  835.70  5311.0  836.44  5337.5  837.21  5342.6  837.08  5367.7  837.89
#Mann=3,-1,0
  4827.5    0.05       0  4986.5    0.04       0  4991.7    0.05       0
Bank Sta=4986.5,4991.7
Exp/Cntr=0.3,0.1

Type RM Length L Ch R = 1,9808,199,199,199
BEGIN DESCRIPTION:
Mapping XS a54acd95
END DESCRIPTION:
XS GIS Cut Line= 2
      2287160.37      7110756.78      2286462.57      7110820.48
#Sta/Elev= 30
  4775.1  837.24  4863.7  835.61  4868.7  835.96  4876.9  835.76  4886.9  835.99
  4907.0  835.14  4957.2  834.32  4967.3  833.04  4973.9  831.40  4978.9  831.76
  4987.3  831.00  4994.8  829.17  4995.5  828.67  4999.3  828.67  5000.0  829.17
  5017.5  831.71  5037.6  832.57  5047.6  832.50  5084.1  833.18  5107.8  833.27
  5127.9  833.74  5199.4  834.63  5208.3  835.23  5288.6  836.53  5348.8  837.96
  5368.9  838.08  5409.1  839.36  5414.8  839.73  5419.8  839.49  5475.8  841.00
#Mann=3,-1,0
  4775.1    0.05       0  4994.8    0.04       0  5000.0    0.05       0
Bank Sta=4994.8,5000
Exp/Cntr=0.3,0.1

Type RM Length L Ch R = 1,9609,262,262,262
BEGIN DESCRIPTION:
Mapping XS 2170054f
END DESCRIPTION:
XS GIS Cut Line= 2
      2287150.91      7110708.63      2286681.99      7110423.51
#Sta/Elev= 30
  4763.3  835.51  4770.8  835.21  4786.3  834.99  4800.7  834.38  4844.4  833.76
  4859.2  833.28  4887.1  832.93  4945.2  832.77  4982.0  832.16  4987.9  830.56
  4997.5  829.12  5003.4  828.74  5008.7  828.03  5009.4  827.53  5013.2  827.53
  5013.9  828.03  5018.8  829.30  5024.7  830.19  5069.8  831.40  5092.4  832.88
  5135.1  836.15  5140.9  836.06  5171.9  836.87  5199.1  838.04  5208.7  838.20
  5214.6  838.64  5288.2  840.67  5294.0  841.05  5303.6  841.24  5312.1  841.84
#Mann=3,-1,0
  4763.3    0.05       0  5008.7    0.04       0  5013.9    0.05       0
Bank Sta=5008.7,5013.9
Exp/Cntr=0.3,0.1