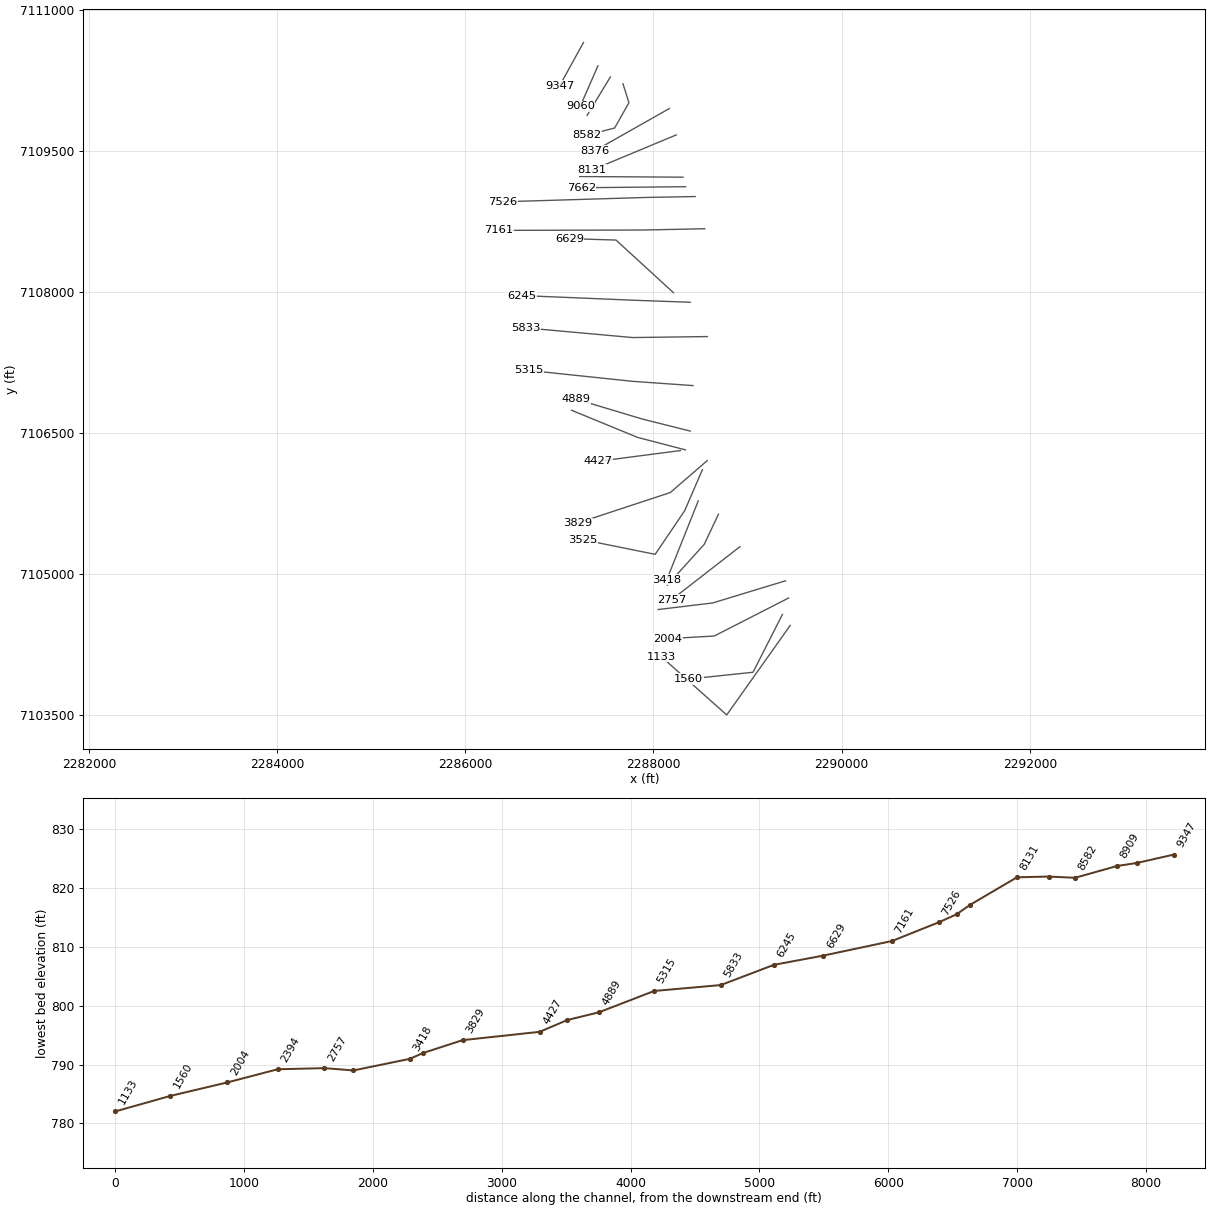
HEC-RAS study MDW T 021.prj: MDW T 021 Base Level Engineering

--- MDW T 021.g01 (geometry) --- (continued)

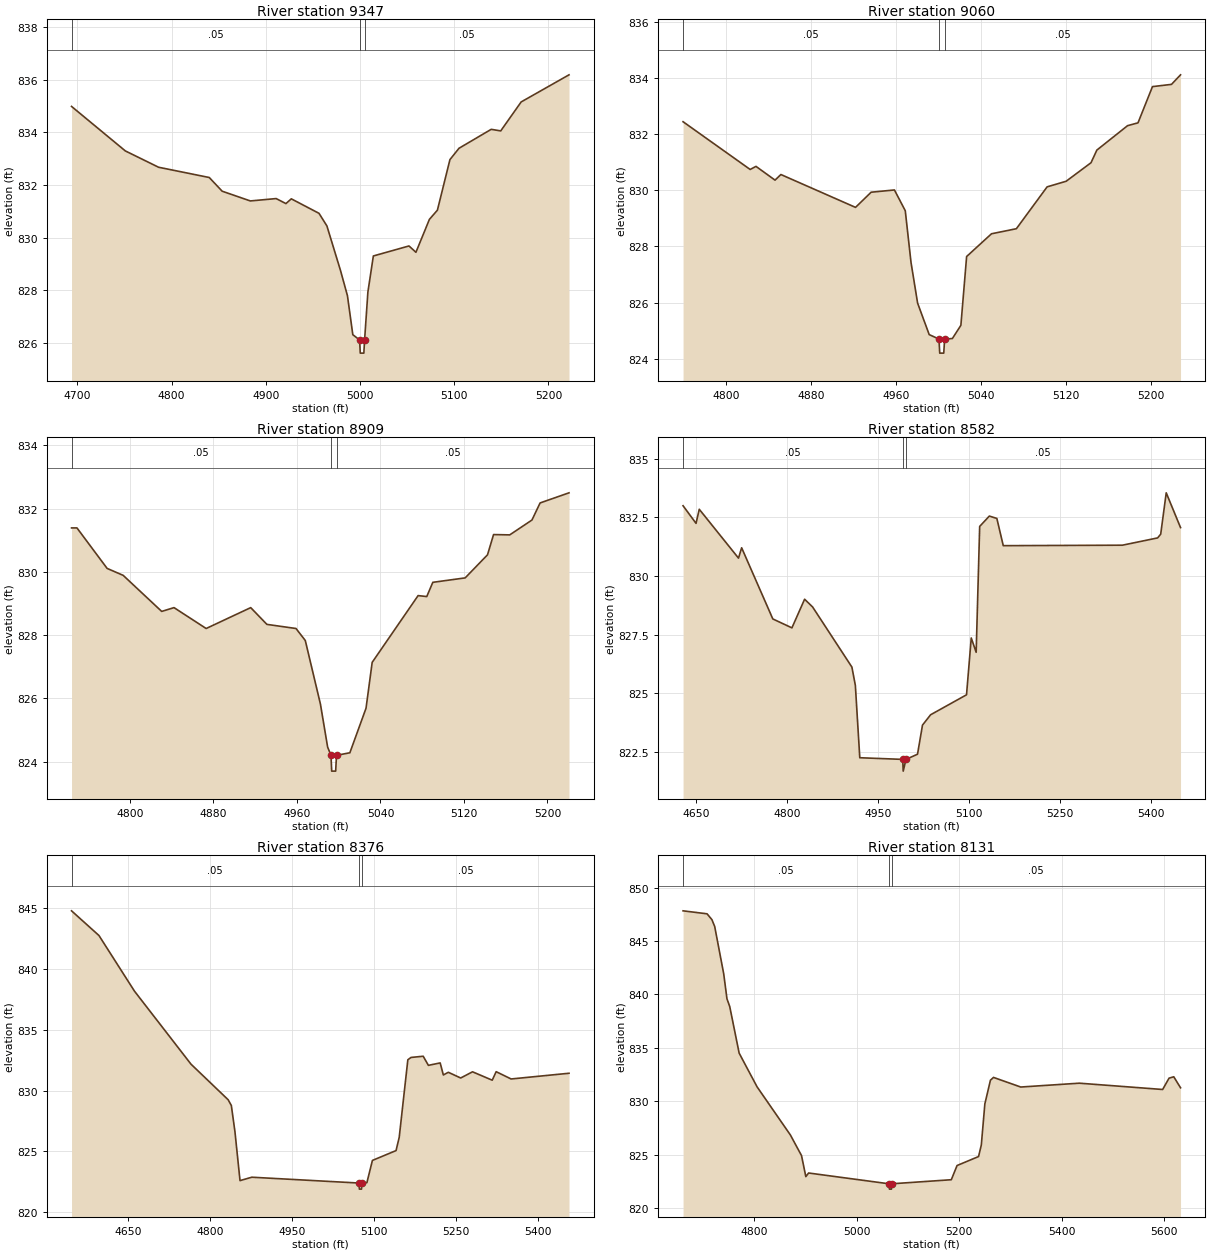
Type RM Length L Ch R = 1,9347,287,287,287
BEGIN DESCRIPTION:
Mapping XS 53b60daa
END DESCRIPTION:
XS GIS Cut Line= 2
      2287256.38      7110649.98      2287001.03      7110187.72
#Sta/Elev= 30
  4693.7  834.99  4750.8  833.30  4786.1  832.68  4839.9  832.29  4853.6  831.77
  4883.5  831.40  4910.9  831.49  4921.3  831.30  4927.0  831.48  4956.4  830.93
  4964.8  830.45  4979.3  828.75  4986.6  827.80  4992.3  826.32  4999.5  826.12
  5000.2  825.62  5004.0  825.62  5004.8  826.12  5008.3  827.94  5014.1  829.31
  5051.9  829.69  5059.3  829.45  5073.6  830.70  5082.1  831.05  5095.4  832.97
  5105.0  833.40  5139.2  834.12  5149.3  834.06  5171.0  835.16  5221.8  836.19
#Mann=3,-1,0
  4693.7    0.05       0  4999.5    0.04       0  5004.8    0.05       0
Bank Sta=4999.5,5004.8
Exp/Cntr=0.3,0.1

Type RM Length L Ch R = 1,9060,151,151,151
BEGIN DESCRIPTION:
Mapping XS f79a7a34
END DESCRIPTION:
XS GIS Cut Line= 2
      2287409.55      7110402.15      2287222.30      7109973.35
#Sta/Elev= 30
  4759.7  832.44  4822.8  830.74  4828.3  830.85  4846.2  830.36  4851.7  830.56
  4921.9  829.39  4936.6  829.93  4958.5  830.01  4968.7  829.27  4974.1  827.43
  4980.3  825.98  4991.2  824.86  5000.4  824.70  5001.1  824.20  5004.9  824.20
  5005.7  824.70  5013.0  824.72  5021.0  825.19  5026.4  827.64  5049.8  828.45
  5073.2  828.63  5102.1  830.12  5120.0  830.32  5143.4  830.98  5148.9  831.43
  5177.8  832.30  5187.6  832.40  5201.2  833.69  5219.1  833.77  5227.6  834.11
#Mann=3,-1,0
  4759.7    0.05       0  5000.4    0.04       0  5005.7    0.05       0
Bank Sta=5000.4,5005.7
Exp/Cntr=0.3,0.1

Type RM Length L Ch R = 1,8909,327,327,327
BEGIN DESCRIPTION:
Mapping XS 1b928eab
END DESCRIPTION:
XS GIS Cut Line= 2
      2287541.76      7110283.95      2287294.60      7109876.32
#Sta/Elev= 30
  4744.0  831.39  4749.2  831.39  4778.1  830.11  4793.5  829.89  4830.4  828.75
  4842.2  828.87  4873.0  828.21  4915.7  828.87  4931.2  828.34  4959.1  828.21
  4968.0  827.83  4982.5  825.82  4989.4  824.46  4992.6  824.20  4993.3  823.70
  4997.1  823.70  4997.9  824.20  5010.7  824.28  5026.2  825.69  5032.1  827.14
  5076.1  829.25  5084.4  829.22  5090.2  829.67  5121.2  829.81  5142.6  830.54
  5148.4  831.18  5163.9  831.17  5185.2  831.64  5193.0  832.18  5220.7  832.50
#Mann=3,-1,0
  4744.0    0.05       0  4992.6    0.04       0  4997.9    0.05       0
Bank Sta=4992.6,4997.9
Exp/Cntr=0.3,0.1

Type RM Length L Ch R = 1,8582,206,206,206
BEGIN DESCRIPTION:
Mapping XS a124624f
END DESCRIPTION:
XS GIS Cut Line= 4
      2287676.21      7110211.16      2287739.51      7110010.44
      2287587.43      7109741.60      2287296.17      7109665.80
#Sta/Elev= 30
  4628.5  832.99  4649.9  832.24  4655.2  832.84  4719.9  830.76  4725.1  831.20
  4776.5  828.17  4808.0  827.79  4828.9  829.01  4842.1  828.68  4906.9  826.12
  4912.6  825.34  4919.9  822.26  4990.7  822.19  4991.5  821.69  4996.1  822.19
  5015.1  822.41  5023.3  823.65  5036.7  824.09  5095.9  824.94  5103.7  827.36
  5111.8  826.75  5117.6  832.11  5133.5  832.55  5145.9  832.45  5156.5  831.29
  5352.9  831.31  5411.0  831.62  5416.1  831.78  5425.2  833.54  5448.8  832.06
#Mann=3,-1,0
  4628.5    0.05       0  4990.7    0.04       0  4996.1    0.05       0
Bank Sta=4990.7,4996.1
Exp/Cntr=0.3,0.1

Type RM Length L Ch R = 1,8376,245,245,245
BEGIN DESCRIPTION:
Mapping XS 16d94aea
END DESCRIPTION:
XS GIS Cut Line= 2
      2288169.34      7109948.75      2287376.67      7109499.95
#Sta/Elev= 30
  4545.9  844.79  4596.1  842.76  4661.2  838.18  4764.6  832.18  4832.7  829.25
  4838.5  828.78  4845.1  826.63  4854.4  822.60  4876.0  822.88  5072.2  822.40
  5073.0  821.90  5076.9  821.90  5077.6  822.40  5086.7  822.43  5096.8  824.26
  5140.1  825.07  5145.9  826.16  5161.7  832.54  5167.5  832.73  5189.8  832.83
  5199.3  832.08  5220.9  832.28  5226.7  831.29  5235.8  831.51  5258.5  831.04
  5280.1  831.55  5316.2  830.86  5323.4  831.56  5350.8  830.96  5456.8  831.43
#Mann=3,-1,0
  4545.9    0.05       0  5072.2    0.04       0  5077.6    0.05       0
Bank Sta=5072.2,5077.6
Exp/Cntr=0.3,0.1

Type RM Length L Ch R = 1,8131,362,362,362
BEGIN DESCRIPTION:
Mapping XS 1ef4ddb8
END DESCRIPTION:
XS GIS Cut Line= 2
      2288242.19      7109668.25      2287346.81      7109294.91
#Sta/Elev= 30
  4661.7  847.83  4708.5  847.55  4718.0  847.00  4723.4  846.36  4741.0  841.92
  4747.3  839.59  4752.7  838.87  4771.1  834.50  4806.0  831.35  4871.0  826.84
  4892.7  824.91  4901.1  822.94  4906.5  823.28  5063.3  822.27  5064.1  821.77
  5068.0  821.77  5068.7  822.27  5184.8  822.65  5196.0  823.98  5237.9  824.82
  5243.3  825.90  5250.2  829.75  5261.1  831.97  5267.1  832.23  5320.2  831.33
  5434.4  831.69  5596.9  831.10  5609.4  832.16  5618.6  832.29  5631.8  831.26
#Mann=3,-1,0
  4661.7    0.05       0  5063.3    0.04       0  5068.7    0.05       0
Bank Sta=5063.3,5068.7
Exp/Cntr=0.3,0.1

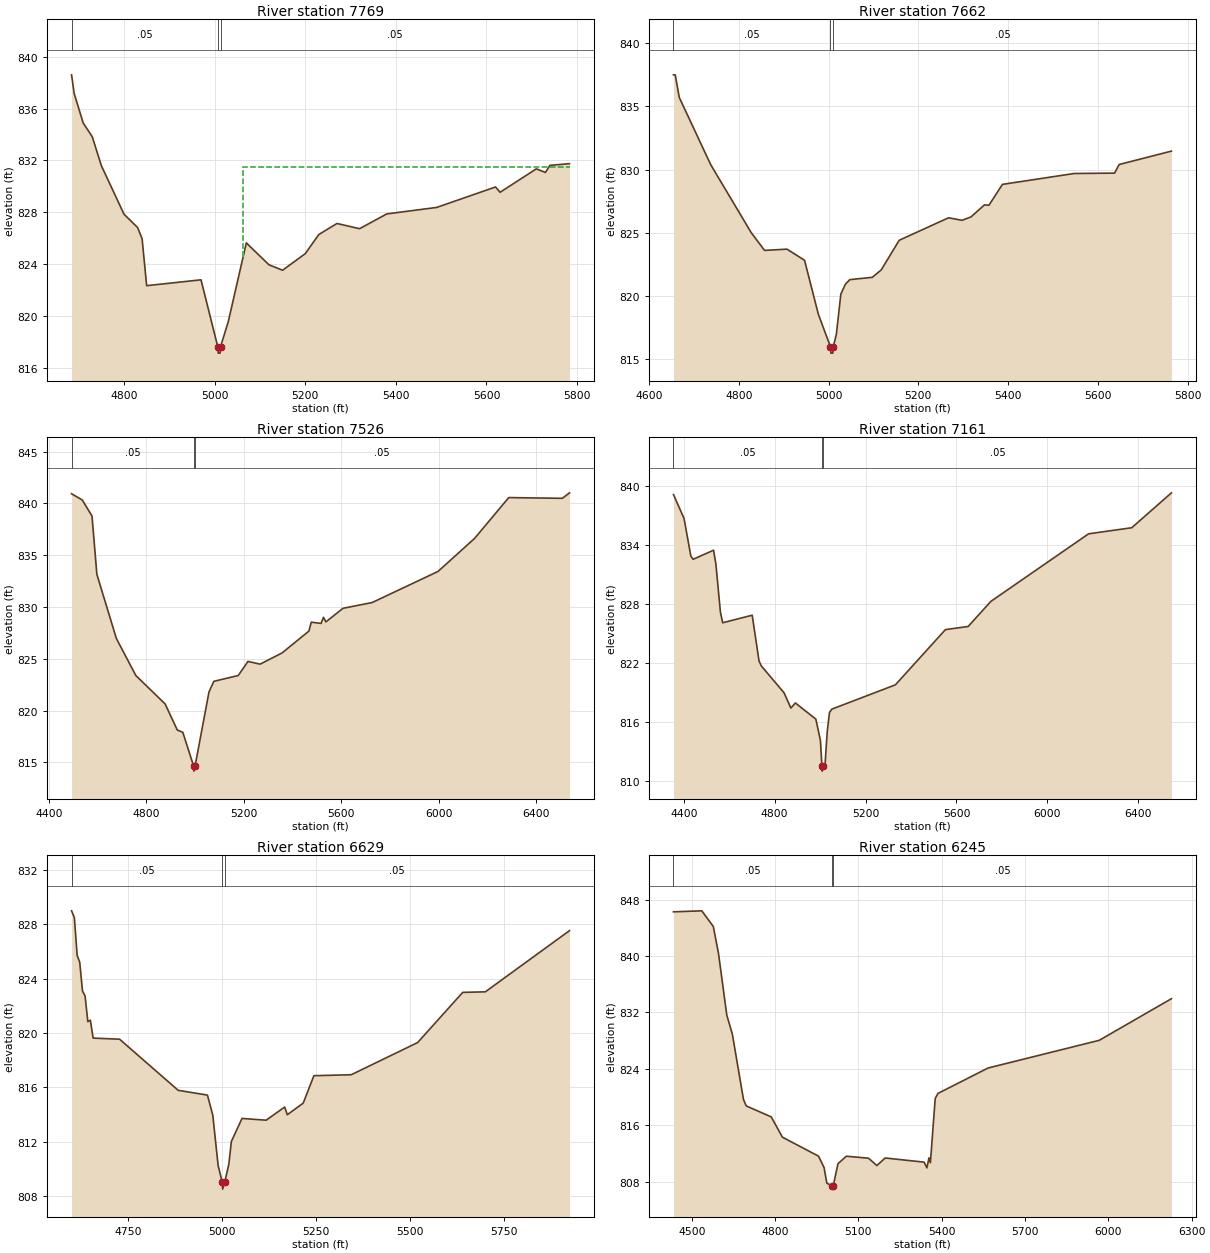
Type RM Length L Ch R = 1,7769,107,107,107
BEGIN DESCRIPTION:
Mapping XS ca30459f
END DESCRIPTION:
XS GIS Cut Line= 2
      2288314.72      7109219.00      2287215.84      7109226.27
#Sta/Elev= 30
  4684.4  838.61  4690.1  837.18  4710.1  834.89  4730.1  833.83  4750.1  831.60
  4800.1  827.85  4830.1  826.82  4840.1  825.95  4850.1  822.33  4970.1  822.78
  5007.0  817.62  5008.1  817.12  5012.2  817.12  5013.2  817.62  5030.1  819.53
  5070.1  825.63  5120.1  823.94  5150.1  823.52  5200.1  824.80  5230.1  826.28
  5270.1  827.13  5320.1  826.73  5380.1  827.87  5490.1  828.37  5620.1  829.95
  5630.1  829.54  5710.1  831.35  5730.1  831.07  5740.1  831.62  5783.3  831.75
#Mann=3,-1,0
  4684.4    0.05       0  5007.0   0.033       0  5013.2    0.05       0
#XS Ineff=2,0
       0                 5063.00    0.00  831.48
Permanent Ineff=
       F       F
Bank Sta=5007,5013.2
Exp/Cntr=0.3,0.1

Type RM Length L Ch R = 1,7662,136,136,136
BEGIN DESCRIPTION:
Mapping XS bdd37fa5
END DESCRIPTION:
XS GIS Cut Line= 2
      2288341.88      7109117.94      2287232.43      7109106.92
#Sta/Elev= 30
  4654.4  837.49  4658.3  837.49  4667.3  835.70  4737.3  830.39  4827.3  825.03
  4857.3  823.61  4907.3  823.71  4946.4  822.83  4977.3  818.55  5004.2  815.99
  5005.2  815.49  5009.3  815.49  5010.4  815.99  5017.3  816.98  5027.3  820.16
  5037.3  820.93  5047.3  821.30  5097.3  821.48  5117.3  822.07  5157.3  824.41
  5267.3  826.19  5297.3  825.99  5317.3  826.26  5347.3  827.21  5357.3  827.18
  5387.3  828.83  5547.3  829.69  5637.3  829.72  5647.3  830.40  5763.9  831.46
#Mann=3,-1,0
  4654.4    0.05       0  5004.2   0.033       0  5010.4    0.05       0
Bank Sta=5004.2,5010.4
Exp/Cntr=0.3,0.1

Type RM Length L Ch R = 1,7526,365,365,365
BEGIN DESCRIPTION:
MDW T 021 12.0
END DESCRIPTION:
XS GIS Cut Line= 3
      2288442.89      7109013.30      2287931.91      7109003.97
      2286399.57      7108957.74
#Sta/Elev= 30
  4493.6  840.93  4537.5  840.33  4577.5  838.78  4597.5  833.15  4677.5  826.96
  4757.5  823.38  4877.6  820.64  4927.6  818.12  4950.3  817.90  4994.5  814.65
  4995.5  814.15  5000.7  814.65  5057.6  821.78  5077.6  822.82  5177.7  823.38
  5217.7  824.74  5267.7  824.48  5357.7  825.56  5467.8  827.67  5477.8  828.53
  5517.8  828.41  5527.8  829.00  5537.8  828.56  5607.9  829.87  5727.9  830.43
  5998.0  833.43  6148.1  836.62  6288.2  840.56  6508.3  840.49  6537.7  841.02
#Mann=3,-1,0
  4493.6    0.05       0  4994.5    0.04       0  5000.7    0.05       0
Bank Sta=4994.5,5000.7
Exp/Cntr=0.3,0.1

Type RM Length L Ch R = 1,7161,532,532,532
BEGIN DESCRIPTION:
MDW T 021 11.0
END DESCRIPTION:
XS GIS Cut Line= 3
      2288545.37      7108671.28      2287884.45      7108657.53
      2286354.41      7108653.92
#Sta/Elev= 30
  4354.8  839.16  4401.2  836.73  4431.2  832.89  4441.2  832.56  4531.2  833.49
  4541.2  832.12  4561.2  827.20  4571.2  826.09  4701.2  826.86  4731.2  822.19
  4741.2  821.69  4841.3  818.95  4871.3  817.39  4891.3  817.91  4981.3  816.26
  5001.3  814.10  5008.0  811.46  5009.0  810.96  5014.2  811.46  5021.3  811.49
  5031.3  814.99  5041.3  816.94  5051.3  817.28  5331.3  819.76  5551.3  825.39
  5651.3  825.71  5751.3  828.27  6181.3  835.16  6371.3  835.78  6545.9  839.34
#Mann=3,-1,0
  4354.8    0.05       0  5008.0    0.04       0  5014.2    0.05       0
Bank Sta=5008,5014.2
Exp/Cntr=0.3,0.1

Type RM Length L Ch R = 1,6629,384,384,384
BEGIN DESCRIPTION:
Mapping XS b0177e8c
END DESCRIPTION:
XS GIS Cut Line= 3
      2288211.93      7107992.13      2287602.17      7108550.92
      2287105.18      7108566.17
#Sta/Elev= 30
  4600.1  829.00  4607.6  828.50  4615.0  825.71  4621.8  825.21  4629.2  823.09
  4636.0  822.73  4643.4  820.83  4650.1  820.94  4657.5  819.62  4727.8  819.54
  4883.8  815.77  4961.5  815.42  4975.7  813.94  4989.9  810.23  5000.9  808.99
  5001.9  808.49  5007.3  808.99  5018.3  810.32  5025.1  812.00  5053.4  813.70
  5117.6  813.57  5166.9  814.54  5173.8  813.97  5216.2  814.83  5244.6  816.85
  5343.9  816.92  5520.4  819.29  5640.4  822.99  5700.5  823.03  5924.4  827.54
#Mann=3,-1,0
  4600.1    0.05       0  5000.9    0.04       0  5007.3    0.05       0
Bank Sta=5000.9,5007.3
Exp/Cntr=0.3,0.1

Type RM Length L Ch R = 1,6245,412,412,412
BEGIN DESCRIPTION:
MDW T 021 9.0
END DESCRIPTION:
XS GIS Cut Line= 3
      2288390.86      7107890.03      2287829.00      7107910.00
      2286599.18      7107961.21
#Sta/Elev= 30
  4434.1  846.28  4536.0  846.42  4577.5  844.20  4596.1  840.39  4626.1  831.61
  4646.1  828.91  4686.1  819.65  4696.1  818.73  4786.2  817.17  4826.2  814.30
  4956.3  811.60  4976.3  809.99  4986.3  807.76  5003.1  807.42  5004.2  806.92
  5009.5  807.42  5026.3  810.52  5056.4  811.59  5136.4  811.31  5166.5  810.27
  5196.5  811.34  5336.6  810.75  5346.6  809.94  5354.2  811.36  5359.2  810.67
  5376.6  819.80  5386.7  820.51  5566.8  824.11  5967.2  828.04  6227.2  833.95
#Mann=3,-1,0
  4434.1    0.05       0  5003.1    0.04       0  5009.5    0.05       0
Bank Sta=5003.1,5009.5
Exp/Cntr=0.3,0.1

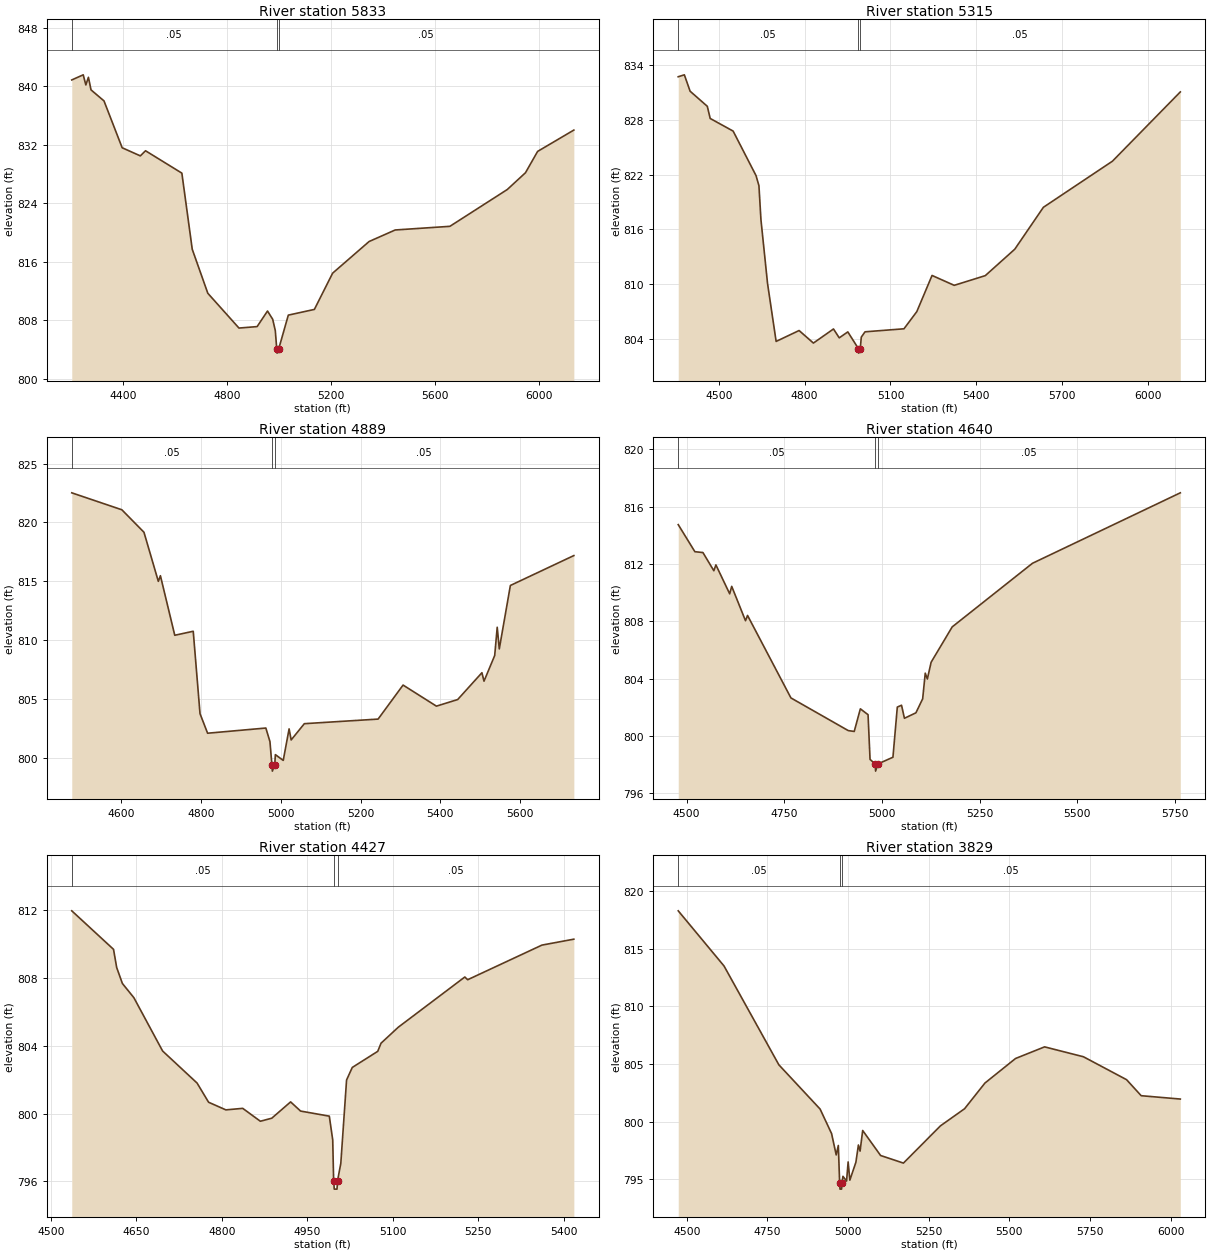
Type RM Length L Ch R = 1,5833,518,518,518
BEGIN DESCRIPTION:
MDW T 021 8.0
END DESCRIPTION:
XS GIS Cut Line= 3
      2288573.16      7107525.45      2287778.94      7107514.97
      2286643.34      7107617.40
#Sta/Elev= 30
  4200.9  840.87  4245.1  841.57  4255.1  840.19  4265.1  841.23  4275.1  839.51
  4325.1  838.00  4395.1  831.59  4465.1  830.48  4485.1  831.18  4625.1  828.12
  4665.1  817.70  4725.1  811.68  4845.1  806.92  4915.1  807.12  4955.1  809.25
  4975.1  808.12  4985.1  806.57  4990.9  803.99  4991.9  803.49  4997.6  803.99
  5035.3  808.69  5135.7  809.47  5206.0  814.43  5346.5  818.76  5447.0  820.34
  5657.8  820.84  5878.7  825.87  5949.0  828.17  5995.8  831.09  6135.4  834.01
#Mann=3,-1,0
  4200.9    0.05       0  4990.9   0.033       0  4997.6    0.05       0
Bank Sta=4990.9,4997.6
Exp/Cntr=0.3,0.1

Type RM Length L Ch R = 1,5315,426,426,426
BEGIN DESCRIPTION:
MDW T 021 7.0
END DESCRIPTION:
XS GIS Cut Line= 3
      2288420.38      7107004.62      2287780.06      7107049.56
      2286673.06      7107165.97
#Sta/Elev= 30
  4358.1  832.69  4379.5  832.90  4399.6  831.11  4459.7  829.46  4469.8  828.13
  4550.0  826.75  4630.1  821.88  4640.2  820.78  4647.2  817.07  4670.2  810.11
  4700.3  803.76  4780.5  804.95  4830.6  803.58  4900.8  805.12  4920.9  804.15
  4950.9  804.80  4987.7  802.98  4988.7  802.48  4994.4  802.98  4998.0  804.23
  5011.1  804.81  5147.2  805.14  5192.1  807.02  5245.3  810.97  5322.8  809.89
  5431.4  810.95  5534.5  813.84  5634.5  818.42  5875.9  823.46  6113.1  831.03
#Mann=3,-1,0
  4358.1    0.05       0  4987.7    0.04       0  4994.4    0.05       0
Bank Sta=4987.7,4994.4
Exp/Cntr=0.3,0.1

Type RM Length L Ch R = 1,4889,249,249,249
BEGIN DESCRIPTION:
MDW T 021 6.0
END DESCRIPTION:
XS GIS Cut Line= 3
      2288390.87      7106521.30      2287879.36      7106649.59
      2287179.03      7106859.99
#Sta/Elev= 30
  4476.1  822.52  4601.7  821.08  4657.1  819.17  4693.1  815.00  4698.3  815.48
  4734.3  810.42  4780.6  810.76  4797.6  803.76  4816.6  802.10  4962.6  802.54
  4972.9  801.39  4977.9  799.38  4979.0  798.88  4984.8  799.38  4986.5  800.28
  5006.2  799.79  5020.9  802.47  5026.1  801.53  5059.1  802.91  5244.0  803.30
  5306.6  806.19  5390.2  804.40  5443.5  804.96  5504.3  807.24  5509.5  806.52
  5536.3  808.70  5542.6  811.10  5547.8  809.26  5575.6  814.65  5734.7  817.19
#Mann=3,-1,0
  4476.1    0.05       0  4977.9    0.04       0  4984.8    0.05       0
Bank Sta=4977.9,4984.8
Exp/Cntr=0.3,0.1

Type RM Length L Ch R = 1,4640,213,213,213
BEGIN DESCRIPTION:
MDW T 021 5.5
END DESCRIPTION:
XS GIS Cut Line= 3
      2288340.18      7106321.46      2287831.26      7106454.06
      2287128.95      7106742.65
#Sta/Elev= 30
  4478.5  814.75  4521.1  812.86  4541.7  812.80  4569.7  811.53  4574.9  811.94
  4610.2  809.92  4615.4  810.44  4650.7  808.04  4655.9  808.41  4767.0  802.65
  4913.7  800.37  4929.0  800.31  4944.7  801.89  4964.4  801.48  4969.5  798.36
  4982.6  798.04  4983.7  797.54  4989.5  798.04  5028.1  798.51  5039.3  802.01
  5050.1  802.14  5057.5  801.23  5086.9  801.61  5104.2  802.59  5110.8  804.38
  5116.2  803.97  5125.8  805.14  5179.8  807.61  5385.2  812.05  5763.7  816.97
#Mann=3,-1,0
  4478.5    0.05       0  4982.6   0.033       0  4989.5    0.05       0
Bank Sta=4982.6,4989.5
Exp/Cntr=0.3,0.1

Type RM Length L Ch R = 1,4427,598,598,598
BEGIN DESCRIPTION:
Mapping XS 9afe4cc8
END DESCRIPTION:
XS GIS Cut Line= 2
      2288287.09      7106314.44      2287413.51      7106200.33
#Sta/Elev= 30
  4536.7  811.95  4610.0  809.68  4615.5  808.61  4625.5  807.67  4645.7  806.83
  4696.1  803.69  4756.6  801.80  4776.8  800.67  4807.1  800.22  4836.7  800.31
  4867.6  799.55  4887.7  799.73  4920.7  800.69  4938.2  800.15  4988.6  799.85
  4994.6  798.45  4996.2  796.05  4997.3  795.55  5002.1  795.55  5003.1  796.05
  5008.8  797.07  5018.9  801.98  5028.9  802.72  5073.6  803.67  5079.4  804.15
  5109.6  805.09  5226.4  808.05  5231.4  807.89  5361.7  809.93  5417.7  810.28
#Mann=3,-1,0
  4536.7    0.05       0  4996.2   0.033       0  5003.1    0.05       0
Bank Sta=4996.2,5003.1
Exp/Cntr=0.3,0.1

Type RM Length L Ch R = 1,3829,304,304,304
BEGIN DESCRIPTION:
MDW T 021 5.0
END DESCRIPTION:
XS GIS Cut Line= 3
      2288571.75      7106207.58      2288179.01      7105868.08
      2287193.83      7105543.55
#Sta/Elev= 30
  4473.5  818.30  4615.5  813.51  4785.5  804.93  4913.3  801.09  4948.9  798.96
  4963.2  797.11  4969.8  797.93  4973.9  794.64  4975.0  794.14  4979.8  794.14
  4980.9  794.64  4984.1  795.25  4995.3  794.84  5000.2  796.50  5005.5  794.92
  5024.2  796.47  5032.0  797.97  5037.2  797.44  5045.3  799.23  5100.8  797.06
  5171.6  796.40  5286.2  799.63  5361.2  801.12  5424.3  803.35  5519.1  805.48
  5609.2  806.49  5729.7  805.63  5863.4  803.64  5908.6  802.25  6029.9  801.96
#Mann=3,-1,0
  4473.5    0.05       0  4973.9    0.04       0  4980.9    0.05       0
Bank Sta=4973.9,4980.9
Exp/Cntr=0.3,0.1

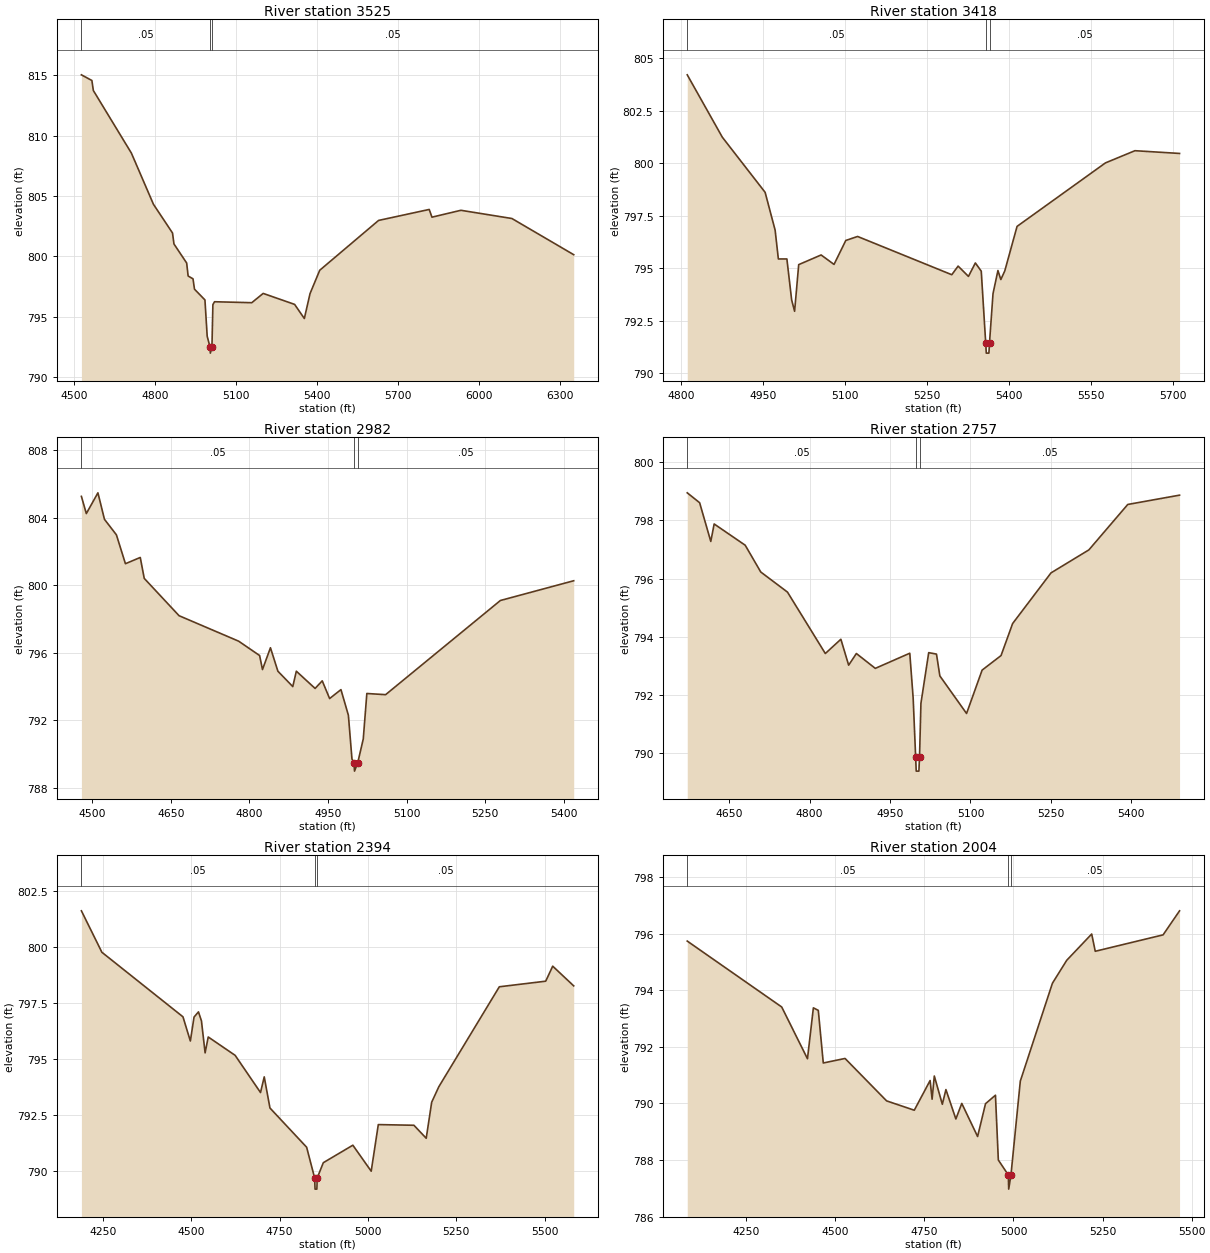
Type RM Length L Ch R = 1,3525,107,107,107
BEGIN DESCRIPTION:
MDW T 021 4.0
END DESCRIPTION:
XS GIS Cut Line= 4
      2288519.67      7106109.95      2288332.20      7105675.52
      2288018.35      7105211.48      2287244.63      7105367.70
#Sta/Elev= 30
  4528.2  815.05  4567.0  814.58  4572.4  813.75  4713.3  808.56  4794.9  804.32
  4865.5  801.94  4870.9  801.03  4917.9  799.45  4923.4  798.37  4941.4  798.14
  4946.9  797.28  4985.6  796.39  4993.9  793.38  5004.5  792.48  5005.6  791.98
  5011.5  792.48  5015.0  796.00  5021.1  796.24  5158.9  796.16  5201.2  796.93
  5317.6  796.02  5353.6  794.85  5374.6  796.91  5410.6  798.85  5628.5  802.98
  5815.9  803.89  5826.1  803.25  5933.2  803.82  6122.0  803.14  6350.9  800.14
#Mann=3,-1,0
  4528.2    0.05       0  5004.5    0.04       0  5011.5    0.05       0
Bank Sta=5004.5,5011.5
Exp/Cntr=0.3,0.1

Type RM Length L Ch R = 1,3418,436,436,436
BEGIN DESCRIPTION:
Mapping XS 109a4e1b
END DESCRIPTION:
XS GIS Cut Line= 2
      2288475.99      7105779.24      2288142.15      7104943.23
#Sta/Elev= 30
  4811.0  804.20  4875.2  801.23  4953.4  798.61  4971.7  796.81  4977.6  795.44
  4993.2  795.44  5001.9  793.49  5007.3  792.95  5014.8  795.17  5055.8  795.63
  5079.4  795.18  5100.9  796.32  5122.5  796.51  5294.7  794.69  5306.3  795.10
  5325.2  794.61  5337.8  795.25  5348.6  794.86  5356.7  791.46  5357.8  790.96
  5362.6  790.96  5363.7  791.46  5370.1  793.79  5379.1  794.89  5384.4  794.46
  5391.6  794.87  5414.1  796.99  5575.7  800.01  5629.6  800.59  5711.2  800.46
#Mann=3,-1,0
  4811.0    0.05       0  5356.7   0.033       0  5363.7    0.05       0
Bank Sta=5356.7,5363.7
Exp/Cntr=0.3,0.1

Type RM Length L Ch R = 1,2982,225,225,225
BEGIN DESCRIPTION:
Mapping XS ffa49520
END DESCRIPTION:
XS GIS Cut Line= 3
      2288691.09      7105638.46      2288539.54      7105317.59
      2288147.54      7104884.11
#Sta/Elev= 30
  4479.6  805.28  4489.0  804.26  4511.1  805.49  4523.6  803.92  4546.4  803.00
  4563.6  801.29  4591.9  801.66  4599.5  800.42  4665.9  798.21  4779.6  796.70
  4819.6  795.85  4825.1  795.02  4840.3  796.31  4854.5  794.92  4882.9  794.01
  4889.7  794.92  4925.5  793.90  4939.1  794.35  4953.2  793.30  4974.8  793.83
  4989.0  792.31  4995.8  789.72  4999.6  789.50  5000.7  789.00  5006.9  789.50
  5017.4  790.91  5024.2  793.60  5060.0  793.53  5279.0  799.11  5418.9  800.28
#Mann=3,-1,0
  4479.6    0.05       0  4999.6    0.04       0  5006.9    0.05       0
Bank Sta=4999.6,5006.9
Exp/Cntr=0.3,0.1

Type RM Length L Ch R = 1,2757,363,363,363
BEGIN DESCRIPTION:
Mapping XS 51e0cc9a
END DESCRIPTION:
XS GIS Cut Line= 2
      2288918.44      7105292.07      2288192.99      7104729.38
#Sta/Elev= 30
  4571.8  798.95  4594.9  798.61  4615.7  797.28  4622.0  797.88  4679.9  797.15
  4708.9  796.23  4758.7  795.54  4829.3  793.43  4858.3  793.92  4872.8  793.03
  4887.2  793.43  4922.5  792.92  4986.8  793.44  4993.1  791.90  4997.7  789.89
  4998.8  789.39  5003.8  789.39  5005.0  789.89  5007.6  791.72  5022.1  793.46
  5036.6  793.41  5042.9  792.66  5092.7  791.37  5121.7  792.86  5157.0  793.36
  5178.6  794.46  5250.2  796.20  5320.8  796.99  5393.3  798.55  5489.9  798.87
#Mann=3,-1,0
  4571.8    0.05       0  4997.7   0.033       0  5005.0    0.05       0
Bank Sta=4997.7,5005
Exp/Cntr=0.3,0.1

Type RM Length L Ch R = 1,2394,390,390,390
BEGIN DESCRIPTION:
MDW T 021 3.0
END DESCRIPTION:
XS GIS Cut Line= 3
      2289403.96      7104930.49      2288629.40      7104694.84
      2288050.02      7104624.96
#Sta/Elev= 30
  4189.4  801.62  4247.4  799.77  4476.8  796.89  4497.7  795.81  4508.2  796.88
  4520.7  797.11  4529.1  796.71  4539.5  795.28  4548.3  795.99  4624.5  795.17
  4696.3  793.51  4706.8  794.21  4723.0  792.82  4826.8  791.07  4849.4  789.70
  4850.6  789.20  4855.7  789.20  4856.8  789.70  4874.0  790.38  4957.6  791.16
  5009.5  790.00  5029.6  792.08  5130.4  792.05  5165.2  791.47  5180.7  793.08
  5200.9  793.77  5372.1  798.23  5503.4  798.48  5523.2  799.15  5582.6  798.27
#Mann=3,-1,0
  4189.4    0.05       0  4849.4   0.033       0  4856.8    0.05       0
Bank Sta=4849.4,4856.8
Exp/Cntr=0.3,0.1

Type RM Length L Ch R = 1,2004,444,444,444
BEGIN DESCRIPTION:
MDW T 021 2.0
END DESCRIPTION:
XS GIS Cut Line= 3
      2289436.45      7104747.52      2288646.13      7104343.52
      2288152.83      7104315.27
#Sta/Elev= 30
  4084.4  795.74  4349.5  793.41  4421.8  791.58  4438.4  793.38  4452.2  793.29
  4466.2  791.43  4527.3  791.59  4643.9  790.09  4721.6  789.76  4766.0  790.81
  4771.6  790.15  4777.8  790.97  4800.3  789.97  4810.4  790.49  4838.3  789.45
  4854.9  790.00  4899.3  788.83  4921.5  789.99  4949.4  790.29  4957.5  788.00
  4985.5  787.47  4986.6  786.97  4992.9  787.47  5019.2  790.79  5109.3  794.25
  5149.4  795.06  5219.5  795.99  5229.5  795.38  5419.9  795.96  5466.1  796.81
#Mann=3,-1,0
  4084.4    0.05       0  4985.5   0.033       0  4992.9    0.05       0
Bank Sta=4985.5,4992.9
Exp/Cntr=0.3,0.1

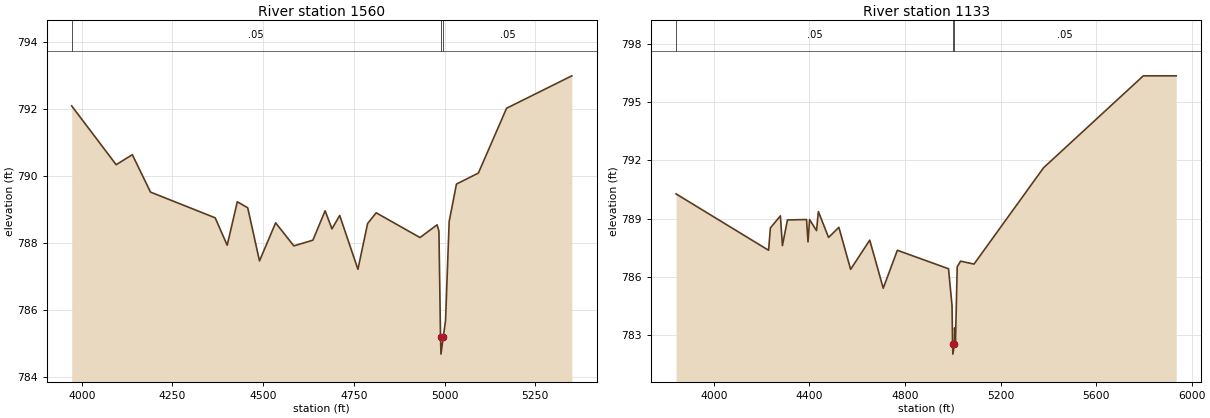
Type RM Length L Ch R = 1,1560,427,427,427
BEGIN DESCRIPTION:
Mapping XS 99a1bc27
END DESCRIPTION:
XS GIS Cut Line= 3
      2289370.47      7104572.47      2289058.29      7103958.35
      2288372.86      7103886.49
#Sta/Elev= 30
  3972.4  792.10  4095.0  790.34  4139.5  790.64  4189.6  789.52  4367.8  788.75
  4400.9  787.93  4428.8  789.23  4457.5  789.05  4489.9  787.46  4534.4  788.60
  4584.5  787.91  4637.0  788.08  4670.7  788.96  4689.6  788.42  4710.9  788.82
  4761.1  787.21  4787.8  788.58  4811.4  788.90  4932.1  788.16  4979.2  788.54
  4984.3  788.35  4988.7  785.17  4989.9  784.67  4996.1  785.17  5002.5  785.67
  5012.5  788.64  5032.6  789.76  5093.0  790.09  5170.7  792.03  5350.5  793.00
#Mann=3,-1,0
  3972.4    0.05       0  4988.7   0.033       0  4996.1    0.05       0
Bank Sta=4988.7,4996.1
Exp/Cntr=0.3,0.1

Type RM Length L Ch R = 1,1133,0,0,0
BEGIN DESCRIPTION:
MDW T 021 1.0
END DESCRIPTION:
XS GIS Cut Line= 3
      2289453.34      7104455.84      2288778.52      7103504.80
      2288086.16      7104121.62
#Sta/Elev= 30
  3842.0  790.28  4229.3  787.38  4236.9  788.53  4278.7  789.15  4287.3  787.62
  4308.2  788.94  4388.2  788.96  4394.3  787.81  4400.9  788.96  4430.0  788.39
  4437.7  789.37  4480.4  788.04  4523.5  788.56  4572.7  786.40  4652.7  787.90
  4709.2  785.43  4768.3  787.38  4982.4  786.43  4997.1  784.54  4999.5  782.54
  5000.7  782.04  5007.0  782.54  5008.0  783.39  5011.3  782.54  5018.8  786.53
  5033.0  786.82  5089.1  786.67  5380.0  791.62  5797.7  796.35  5935.4  796.35
#Mann=3,-1,0
  3842.0    0.05       0  4999.5   0.033       0  5007.0    0.05       0
Bank Sta=4999.5,5007
Exp/Cntr=0.3,0.1