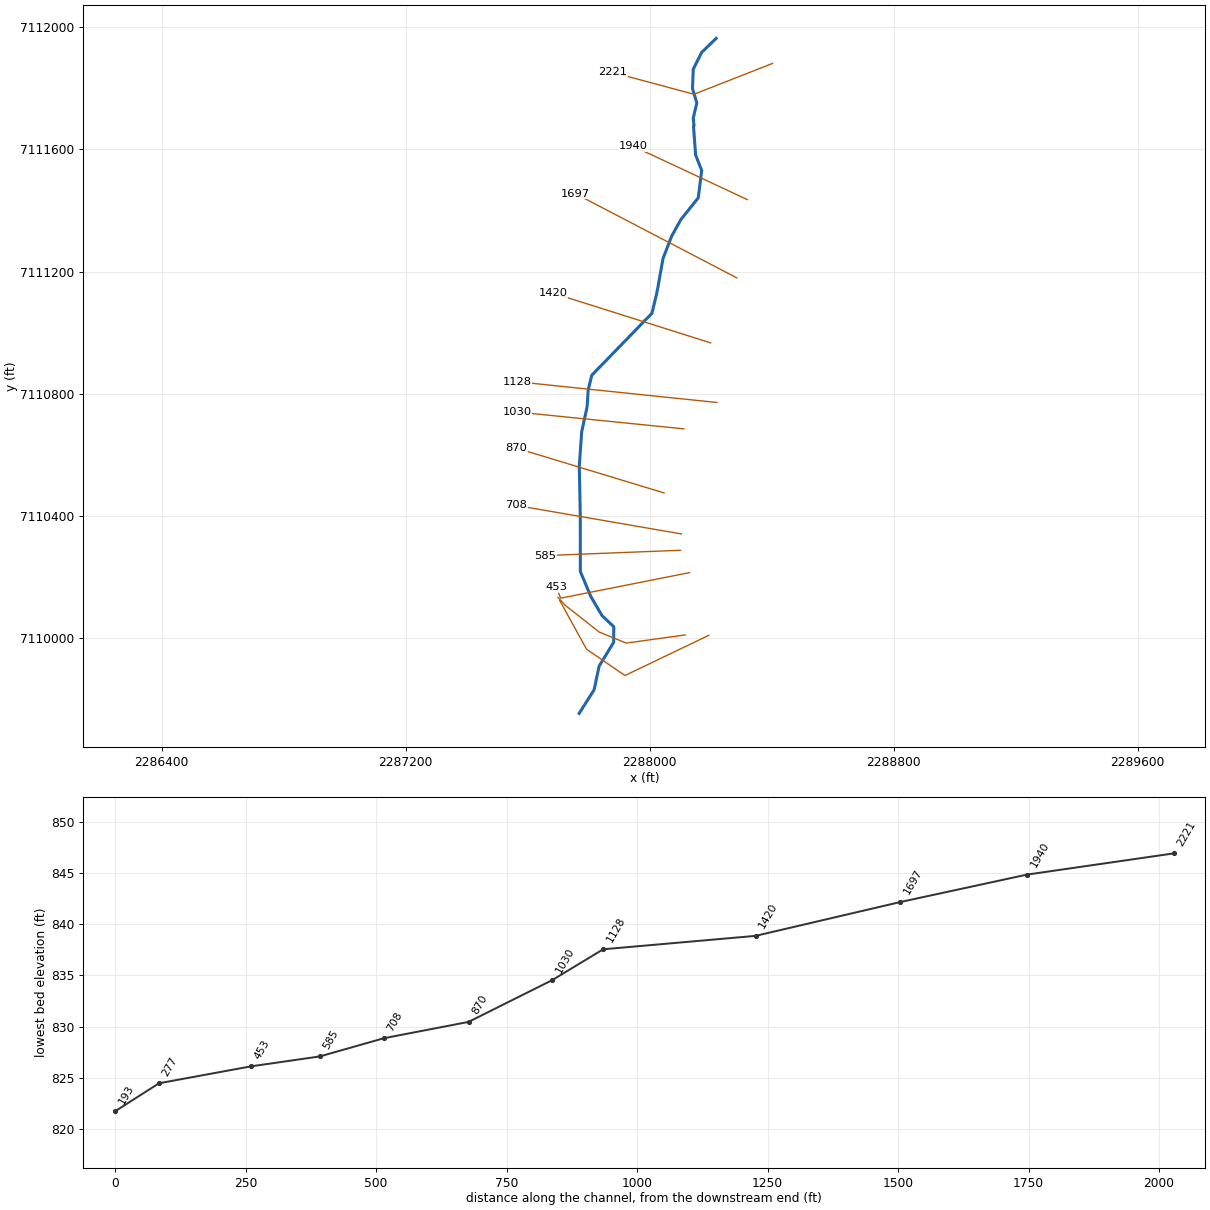
--- MDW T 022.prj (project) ---

Proj Title=MDW T 022 Base Level Engineering
Current Plan=p01
Default Exp/Contr=0.3,0.1
English Units
Geom File=g01
Flow File=f01
Plan File=p01
BEGIN DESCRIPTION:
MDW T 022
END DESCRIPTION:

--- MDW T 022.p01 (plan) ---

Plan Title=Multiple Run
Short Identifier=Multiple
Geom File=g01
Flow File=f01
Subcritical Flow
K Sum by GR= 0
Std Step Tol= 0.01
Critical Tol= 0.01
Num of Std Step Trials= 20
Max Error Tol= 0.3
Flow Tol Ratio= 0.001
Split Flow NTrial= 30
Split Flow Tol= 0.02
Split Flow Ratio= 0.02
Log Output Level= 0
Friction Slope Method= 1
Unsteady Friction Slope Method= 2
Unsteady Bridges Friction Slope Method= 1
Parabolic Critical Depth
Global Vel Dist=  1 , 1 , 1
Global Log Level= 0
CheckData=True
Encroach Param= -1, 0, 0, 0
BEGIN DESCRIPTION:
Multiple Run
END DESCRIPTION:

--- MDW T 022.f01 (steady flow) ---

Flow Title=Multiple
Number of Profiles=7
Profile Names=10-year,25-year,50-year,1pct_min,100-year,1pct_plu,500-year
River Rch & RM= MDW T 022,Reach-1,2221
     299     394     470     279     558    1112     785
Boundary for River Rch & Prof#=MDW T 022,Reach-1,1
Up Type=0
Dn Type=3
Dn Slope=0.005
Boundary for River Rch & Prof#=MDW T 022,Reach-1,2
Up Type=0
Dn Type=3
Dn Slope=0.005
Boundary for River Rch & Prof#=MDW T 022,Reach-1,3
Up Type=0
Dn Type=3
Dn Slope=0.005
Boundary for River Rch & Prof#=MDW T 022,Reach-1,4
Up Type=0
Dn Type=3
Dn Slope=0.005
Boundary for River Rch & Prof#=MDW T 022,Reach-1,5
Up Type=0
Dn Type=3
Dn Slope=0.005
Boundary for River Rch & Prof#=MDW T 022,Reach-1,6
Up Type=0
Dn Type=3
Dn Slope=0.005
Boundary for River Rch & Prof#=MDW T 022,Reach-1,7
Up Type=0
Dn Type=3
Dn Slope=0.005

--- MDW T 022.g01 (geometry) ---

Geom Title=Existing Conditions

River Reach=MDW T 022,Reach-1
Reach XY= 30
      2288218.29      7111964.39      2288170.93      7111918.63
      2288143.12      7111863.42      2288140.51      7111799.79
      2288154.75      7111752.71      2288143.09      7111703.45
      2288145.50      7111677.83      2288143.86      7111675.98
      2288150.78      7111582.10      2288170.73      7111531.22
      2288159.47      7111441.49      2288102.63      7111370.58
      2288072.38      7111316.31      2288043.93      7111242.79
      2288024.75      7111134.66      2288007.63      7111063.18
      2287810.28      7110859.81      2287798.60      7110811.51
      2287795.10      7110756.54      2287777.27      7110674.45
      2287769.47      7110562.59      2287772.72      7110398.80
      2287772.90      7110216.66      2287806.94      7110135.09
      2287844.04      7110071.85      2287882.49      7110035.62
      2287882.19      7109984.54      2287834.34      7109906.00
      2287818.01      7109828.71      2287769.09      7109751.49

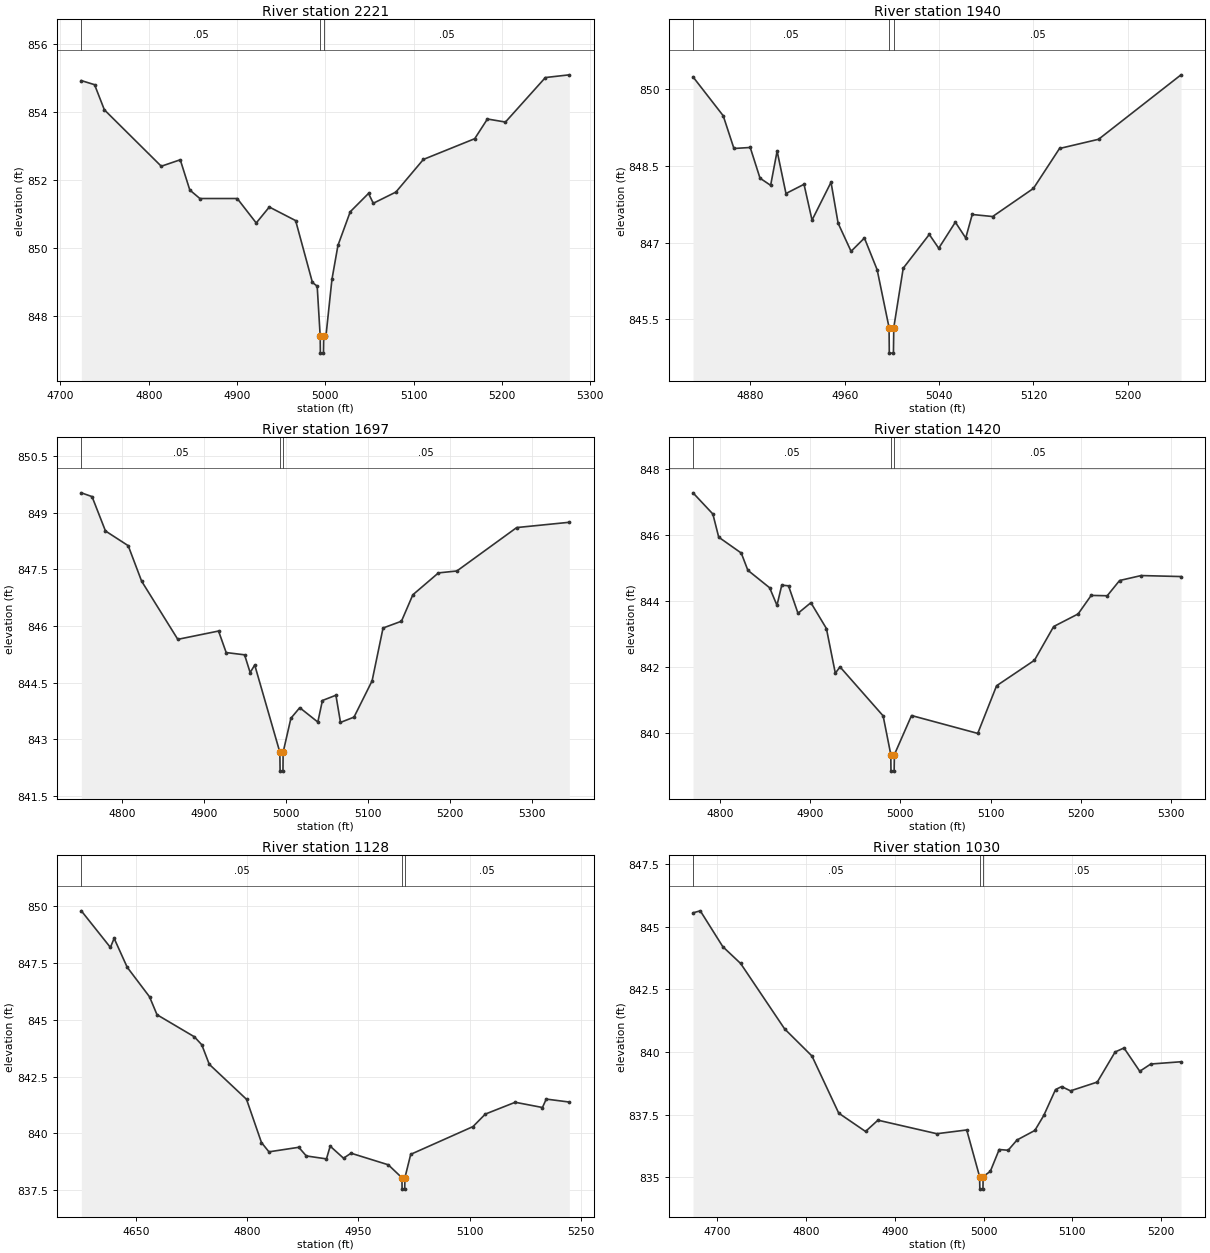
Type RM Length L Ch R = 1,2221,281,281,281
BEGIN DESCRIPTION:
MDW T 022 6.0
END DESCRIPTION:
XS GIS Cut Line= 3
      2288403.27      7111882.32      2288145.50      7111781.08
      2287879.45      7111852.44
#Sta/Elev= 30
  4723.7  854.93  4738.7  854.81  4749.8  854.07  4814.2  852.41  4835.7  852.60
  4846.5  851.71  4857.9  851.46  4900.2  851.46  4921.7  850.74  4936.5  851.21
  4966.3  850.81  4985.3  848.99  4990.7  848.88  4994.1  847.41  4994.3  846.91
  4997.8  846.91  4998.1  847.41  5000.6  847.41  5007.4  849.08  5014.2  850.08
  5028.1  851.07  5048.8  851.61  5054.2  851.32  5079.8  851.65  5110.9  852.61
  5169.0  853.22  5183.4  853.80  5203.8  853.71  5249.0  855.02  5276.1  855.10
#Mann=3,-1,0
  4723.7    0.05       0  4994.1    0.04       0  4998.1    0.05       0
Bank Sta=4994.1,4998.1
Exp/Cntr=0.3,0.1

Type RM Length L Ch R = 1,1940,243,243,243
BEGIN DESCRIPTION:
Mapping XS 301f39cb
END DESCRIPTION:
XS GIS Cut Line= 2
      2288320.41      7111435.64      2287945.70      7111610.97
#Sta/Elev= 30
  4831.4  850.24  4857.0  849.48  4866.1  848.84  4879.9  848.86  4888.2  848.26
  4897.2  848.12  4902.7  848.79  4910.2  847.96  4925.5  848.14  4932.3  847.44
  4948.4  848.18  4954.4  847.38  4965.4  846.83  4976.7  847.09  4987.5  846.47
  4997.6  845.34  4997.8  844.84  5001.3  844.84  5001.6  845.34  5009.6  846.50
  5031.7  847.16  5039.7  846.89  5053.8  847.40  5062.6  847.09  5068.1  847.55
  5085.4  847.51  5120.0  848.06  5142.1  848.84  5175.2  849.02  5245.1  850.28
#Mann=3,-1,0
  4831.4    0.05       0  4997.6    0.04       0  5001.6    0.05       0
Bank Sta=4997.6,5001.6
Exp/Cntr=0.3,0.1

Type RM Length L Ch R = 1,1697,277,277,277
BEGIN DESCRIPTION:
Mapping XS d02a614b
END DESCRIPTION:
XS GIS Cut Line= 2
      2288285.89      7111179.09      2287757.19      7111454.86
#Sta/Elev= 30
  4749.8  849.53  4762.9  849.43  4779.3  848.52  4807.1  848.13  4823.5  847.19
  4867.7  845.65  4917.5  845.87  4926.8  845.30  4949.3  845.24  4956.1  844.77
  4961.7  844.97  4992.4  842.66  4992.7  842.16  4996.2  842.16  4996.4  842.66
  5005.9  843.56  5016.7  843.84  5038.8  843.46  5044.4  844.03  5060.9  844.17
  5066.5  843.45  5083.0  843.59  5105.1  844.55  5118.5  845.95  5141.0  846.13
  5154.9  846.83  5186.2  847.41  5208.7  847.46  5281.8  848.61  5346.1  848.75
#Mann=3,-1,0
  4749.8    0.05       0  4992.4    0.04       0  4996.4    0.05       0
Bank Sta=4992.4,4996.4
Exp/Cntr=0.3,0.1

Type RM Length L Ch R = 1,1420,292,292,292
BEGIN DESCRIPTION:
Mapping XS 68812992
END DESCRIPTION:
XS GIS Cut Line= 2
      2288200.01      7110966.08      2287684.03      7111129.01
#Sta/Elev= 30
  4770.1  847.27  4792.1  846.63  4798.6  845.93  4823.6  845.45  4830.9  844.93
  4855.1  844.40  4863.2  843.87  4868.5  844.48  4876.0  844.46  4886.5  843.63
  4900.8  843.95  4918.0  843.17  4927.9  841.82  4933.1  842.01  4980.9  840.53
  4989.4  839.36  4989.6  838.86  4993.1  838.86  4993.4  839.36  5012.4  840.54
  5085.8  840.00  5106.7  841.44  5148.7  842.21  5170.0  843.23  5197.1  843.61
  5211.6  844.17  5229.4  844.16  5243.1  844.62  5267.0  844.77  5311.2  844.74
#Mann=3,-1,0
  4770.1    0.05       0  4989.4    0.04       0  4993.4    0.05       0
Bank Sta=4989.4,4993.4
Exp/Cntr=0.3,0.1

Type RM Length L Ch R = 1,1128,98,98,98
BEGIN DESCRIPTION:
Mapping XS c9d50ccc
END DESCRIPTION:
XS GIS Cut Line= 2
      2288220.44      7110770.69      2287566.45      7110838.57
#Sta/Elev= 30
  4576.6  849.79  4615.8  848.18  4620.8  848.58  4638.4  847.31  4668.5  846.01
  4678.6  845.22  4728.9  844.25  4738.9  843.90  4749.0  843.04  4799.2  841.50
  4819.3  839.60  4829.4  839.19  4869.6  839.39  4879.7  839.01  4906.9  838.88
  4911.9  839.44  4929.9  838.91  4940.0  839.13  4990.2  838.62  5008.6  838.05
  5008.8  837.55  5012.3  837.55  5012.6  838.05  5020.4  839.08  5104.3  840.30
  5120.9  840.85  5161.2  841.37  5197.9  841.14  5203.0  841.51  5234.1  841.38
#Mann=3,-1,0
  4576.6    0.05       0  5008.6    0.04       0  5012.6    0.05       0
Bank Sta=5008.6,5012.6
Exp/Cntr=0.3,0.1

Type RM Length L Ch R = 1,1030,160,160,160
BEGIN DESCRIPTION:
Mapping XS 1cd5b1af
END DESCRIPTION:
XS GIS Cut Line= 2
      2288112.47      7110684.20      2287565.04      7110739.38
#Sta/Elev= 30
  4672.4  845.55  4680.6  845.63  4706.0  844.20  4726.1  843.53  4775.7  840.92
  4806.5  839.84  4836.7  837.56  4866.9  836.83  4880.9  837.28  4947.3  836.74
  4981.0  836.89  4995.5  835.03  4995.8  834.53  4999.3  834.53  4999.5  835.03
  5007.6  835.24  5017.6  836.11  5027.7  836.08  5037.7  836.49  5057.8  836.87
  5067.9  837.47  5081.1  838.50  5088.0  838.62  5098.0  838.45  5128.2  838.80
  5148.3  840.00  5158.3  840.16  5176.1  839.23  5188.5  839.52  5222.6  839.61
#Mann=3,-1,0
  4672.4    0.05       0  4995.5    0.04       0  4999.5    0.05       0
Bank Sta=4995.5,4999.5
Exp/Cntr=0.3,0.1

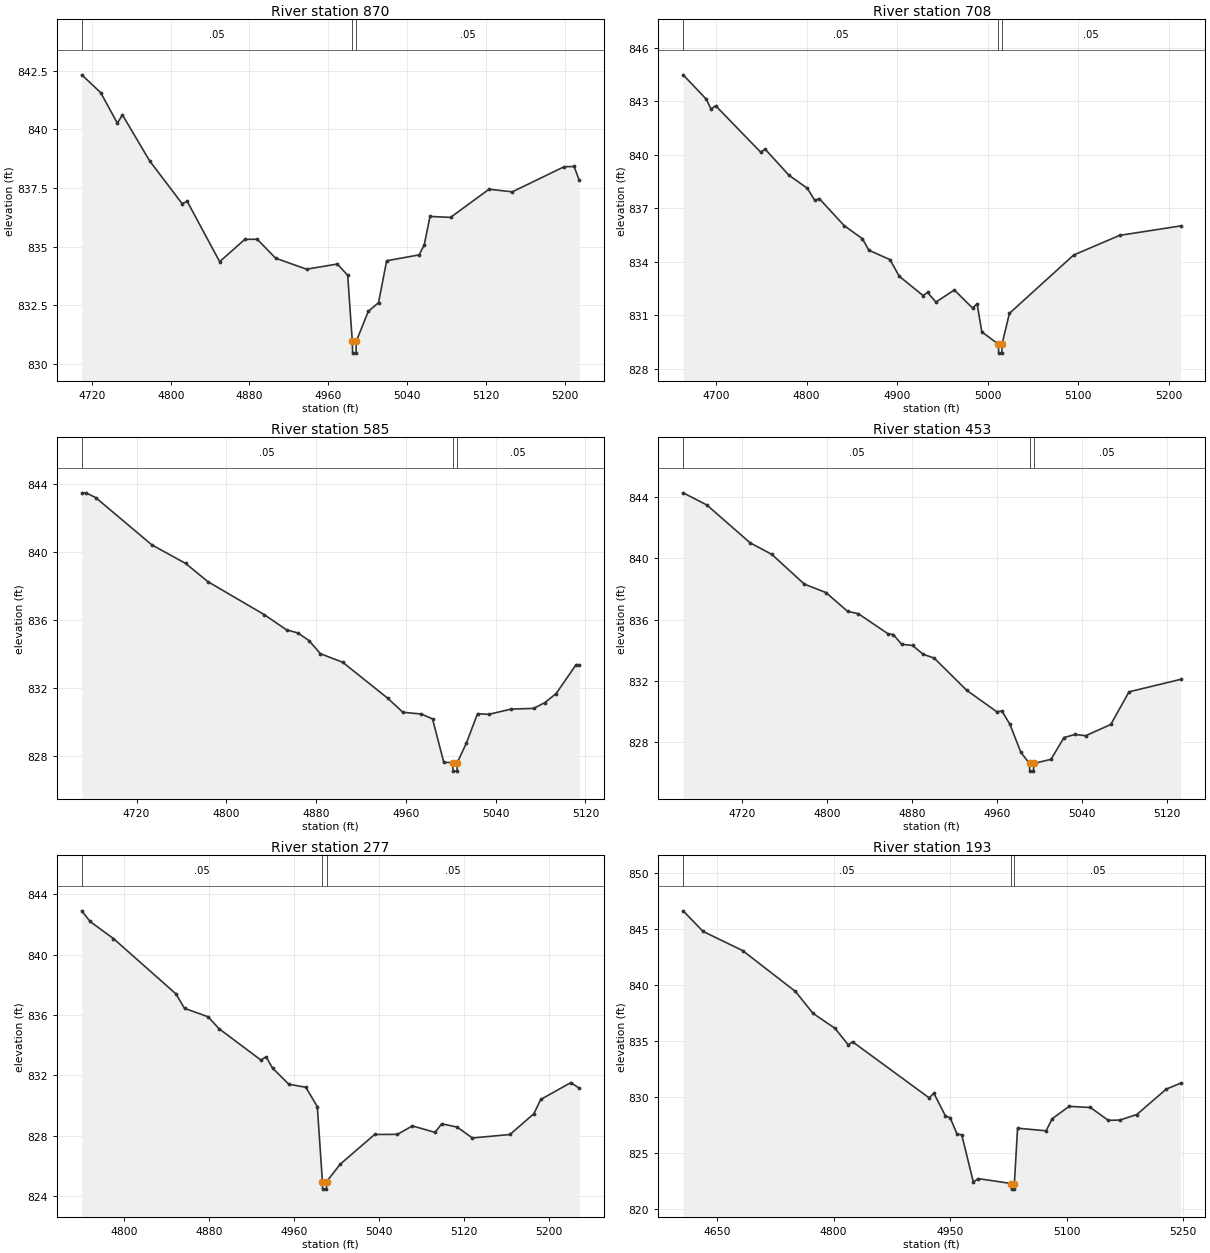
Type RM Length L Ch R = 1,870,162,162,162
BEGIN DESCRIPTION:
Mapping XS d24ca6fa
END DESCRIPTION:
XS GIS Cut Line= 2
      2288047.33      7110474.17      2287564.01      7110620.88
#Sta/Elev= 30
  4709.7  842.33  4728.9  841.57  4745.8  840.27  4751.0  840.62  4778.6  838.66
  4811.5  836.84  4816.8  836.93  4849.7  834.36  4875.2  835.31  4887.8  835.32
  4906.5  834.51  4937.9  834.04  4969.2  834.26  4979.7  833.78  4984.4  830.96
  4984.7  830.46  4988.2  830.46  4988.4  830.96  5000.6  832.24  5011.0  832.61
  5019.3  834.40  5052.2  834.65  5057.4  835.07  5063.3  836.29  5084.2  836.25
  5123.2  837.45  5146.9  837.34  5199.5  838.41  5209.6  838.42  5214.8  837.84
#Mann=3,-1,0
  4709.7    0.05       0  4984.4    0.04       0  4988.4    0.05       0
Bank Sta=4984.4,4988.4
Exp/Cntr=0.3,0.1

Type RM Length L Ch R = 1,708,123,123,123
BEGIN DESCRIPTION:
Mapping XS 7dc0d493
END DESCRIPTION:
XS GIS Cut Line= 2
      2288104.31      7110339.74      2287562.63      7110433.28
#Sta/Elev= 30
  4663.5  844.47  4689.2  843.10  4694.3  842.55  4699.4  842.74  4749.1  840.14
  4754.2  840.30  4780.5  838.84  4800.8  838.11  4808.9  837.44  4814.0  837.53
  4841.4  836.02  4861.7  835.28  4868.7  834.64  4892.1  834.11  4902.3  833.18
  4928.6  832.10  4933.6  832.27  4942.9  831.73  4963.2  832.41  4983.3  831.40
  4988.4  831.63  4993.6  830.06  5011.9  829.37  5012.2  828.87  5015.7  828.87
  5015.9  829.37  5024.1  831.10  5095.1  834.37  5145.8  835.47  5213.2  836.00
#Mann=3,-1,0
  4663.5    0.05       0  5011.9    0.04       0  5015.9    0.05       0
Bank Sta=5011.9,5015.9
Exp/Cntr=0.3,0.1

Type RM Length L Ch R = 1,585,132,132,132
BEGIN DESCRIPTION:
Mapping XS ee857b73
END DESCRIPTION:
XS GIS Cut Line= 2
      2288101.39      7110286.20      2287658.43      7110268.77
#Sta/Elev= 30
  4671.2  843.46  4674.9  843.46  4683.6  843.18  4733.6  840.40  4763.7  839.31
  4783.7  838.23  4833.7  836.30  4853.7  835.40  4863.7  835.22  4873.7  834.77
  4883.8  834.00  4903.8  833.49  4943.8  831.38  4957.4  830.55  4973.8  830.45
  4983.8  830.16  4993.8  827.61  5001.8  827.59  5002.1  827.09  5005.6  827.09
  5005.8  827.59  5013.9  828.73  5023.9  830.47  5033.9  830.43  5053.9  830.74
  5073.9  830.78  5083.9  831.12  5093.9  831.65  5111.7  833.35  5114.5  833.35
#Mann=3,-1,0
  4671.2    0.05       0  5001.8    0.04       0  5005.8    0.05       0
Bank Sta=5001.8,5005.8
Exp/Cntr=0.3,0.1

Type RM Length L Ch R = 1,453,176,176,176
BEGIN DESCRIPTION:
Mapping XS 6cf63e12
END DESCRIPTION:
XS GIS Cut Line= 3
      2288130.89      7110212.92      2287708.31      7110129.16
      2287694.80      7110164.25
#Sta/Elev= 30
  4664.4  844.26  4686.7  843.47  4727.5  841.00  4747.9  840.25  4778.5  838.31
  4798.9  837.76  4819.2  836.54  4829.4  836.38  4857.2  835.08  4862.3  835.02
  4870.2  834.39  4880.4  834.31  4890.6  833.73  4900.8  833.49  4931.4  831.39
  4959.6  830.00  4964.7  830.03  4972.2  829.16  4982.4  827.35  4990.6  826.62
  4990.8  826.12  4994.3  826.12  4994.6  826.62  5010.8  826.89  5023.1  828.31
  5033.3  828.51  5043.5  828.43  5067.1  829.16  5084.3  831.29  5132.8  832.10
#Mann=3,-1,0
  4664.4    0.05       0  4990.6    0.04       0  4994.6    0.05       0
Bank Sta=4990.6,4994.6
Exp/Cntr=0.3,0.1

Type RM Length L Ch R = 1,277,84,84,84
BEGIN DESCRIPTION:
Mapping XS 7c9db6ab
END DESCRIPTION:
XS GIS Cut Line= 5
      2288116.67      7110008.66      2287923.62      7109981.92
      2287835.22      7110017.74      2287722.71      7110106.19
      2287699.78      7110131.85
#Sta/Elev= 30
  4760.5  842.91  4768.2  842.21  4790.3  841.07  4849.0  837.41  4857.1  836.45
  4879.3  835.89  4889.4  835.11  4928.8  833.03  4933.9  833.23  4939.9  832.49
  4955.2  831.42  4971.2  831.22  4982.0  829.94  4986.8  824.97  4987.0  824.47
  4990.5  824.47  4990.8  824.97  5003.5  826.12  5035.9  828.09  5057.4  828.10
  5071.4  828.66  5092.7  828.23  5099.0  828.80  5113.5  828.58  5127.9  827.86
  5163.2  828.09  5185.7  829.47  5192.1  830.41  5220.5  831.53  5228.3  831.16
#Mann=3,-1,0
  4760.5    0.05       0  4986.8    0.04       0  4990.8    0.05       0
Bank Sta=4986.8,4990.8
Exp/Cntr=0.3,0.1

Type RM Length L Ch R = 1,193,0,0,0
BEGIN DESCRIPTION:
MDW T 022 0.5
END DESCRIPTION:
XS GIS Cut Line= 4
      2288194.34      7110007.47      2287919.25      7109875.62
      2287793.34      7109961.75      2287705.29      7110121.48
#Sta/Elev= 30
  4606.5  846.59  4632.2  844.75  4683.1  843.04  4751.0  839.39  4773.7  837.43
  4801.9  836.10  4819.0  834.62  4824.5  834.90  4923.0  829.89  4929.1  830.30
  4944.0  828.28  4950.1  828.11  4958.9  826.66  4965.0  826.59  4979.9  822.37
  4986.0  822.68  5028.7  822.24  5029.0  821.74  5032.5  821.74  5032.7  822.24
  5036.8  827.18  5073.5  826.95  5081.3  828.02  5103.1  829.13  5130.6  829.03
  5153.5  827.88  5168.5  827.91  5190.2  828.40  5228.1  830.67  5246.5  831.20
#Mann=3,-1,0
  4606.5    0.05       0  5028.7    0.04       0  5032.7    0.05       0
Bank Sta=5028.7,5032.7
Exp/Cntr=0.3,0.1

Chan Stop Cuts=-1