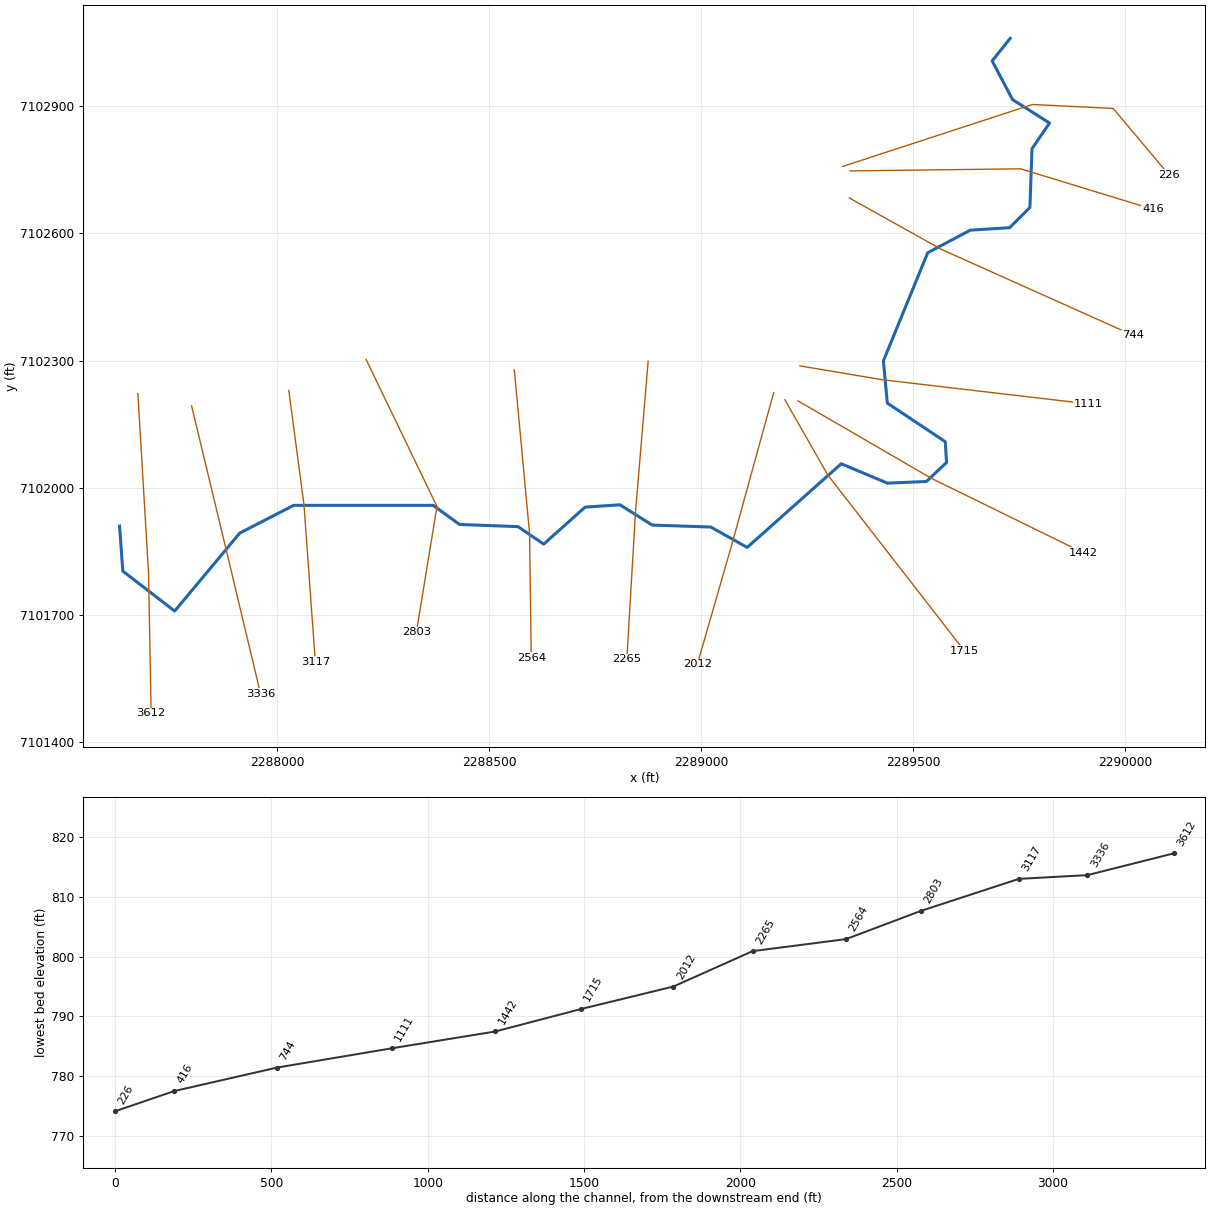
--- MDW T 023.prj (project) ---

Proj Title=MDW T 023 Base Level Engineering
Current Plan=p01
Default Exp/Contr=0.3,0.1
English Units
Geom File=g01
Flow File=f01
Plan File=p01
BEGIN DESCRIPTION:
MDW T 023
END DESCRIPTION:

--- MDW T 023.p01 (plan) ---

Plan Title=Multiple Run
Short Identifier=Multiple
Geom File=g01
Flow File=f01
Subcritical Flow
K Sum by GR= 0
Std Step Tol= 0.01
Critical Tol= 0.01
Num of Std Step Trials= 20
Max Error Tol= 0.3
Flow Tol Ratio= 0.001
Split Flow NTrial= 30
Split Flow Tol= 0.02
Split Flow Ratio= 0.02
Log Output Level= 0
Friction Slope Method= 1
Unsteady Friction Slope Method= 2
Unsteady Bridges Friction Slope Method= 1
Parabolic Critical Depth
Global Vel Dist=  1 , 1 , 1
Global Log Level= 0
CheckData=True
Encroach Param= -1, 0, 0, 0
BEGIN DESCRIPTION:
Multiple Run
END DESCRIPTION:

--- MDW T 023.f01 (steady flow) ---

Flow Title=Multiple
Number of Profiles=7
Profile Names=10-year,25-year,50-year,1pct_min,100-year,1pct_plu,500-year
River Rch & RM= MDW T 023,Reach-1,3612
     393     530     643     388     774    1545    1125
River Rch & RM= MDW T 023,Reach-1,1715
     572     791     974     597    1191    2376    1782
Boundary for River Rch & Prof#=MDW T 023,Reach-1,1
Up Type=0
Dn Type=3
Dn Slope=0.005
Boundary for River Rch & Prof#=MDW T 023,Reach-1,2
Up Type=0
Dn Type=3
Dn Slope=0.005
Boundary for River Rch & Prof#=MDW T 023,Reach-1,3
Up Type=0
Dn Type=3
Dn Slope=0.005
Boundary for River Rch & Prof#=MDW T 023,Reach-1,4
Up Type=0
Dn Type=3
Dn Slope=0.005
Boundary for River Rch & Prof#=MDW T 023,Reach-1,5
Up Type=0
Dn Type=3
Dn Slope=0.005
Boundary for River Rch & Prof#=MDW T 023,Reach-1,6
Up Type=0
Dn Type=3
Dn Slope=0.005
Boundary for River Rch & Prof#=MDW T 023,Reach-1,7
Up Type=0
Dn Type=3
Dn Slope=0.005

--- MDW T 023.g01 (geometry) ---

Geom Title=Existing Conditions

River Reach=MDW T 023,Reach-1
Reach XY= 30
      2287629.00      7101910.00      2287636.73      7101803.75
      2287758.94      7101709.48      2287912.29      7101893.37
      2288039.50      7101958.80      2288368.50      7101958.78
      2288430.57      7101913.79      2288568.56      7101908.60
      2288629.10      7101867.33      2288726.57      7101954.57
      2288808.90      7101960.10      2288884.94      7101912.27
      2289023.07      7101907.70      2289108.87      7101859.60
      2289330.63      7102056.87      2289439.53      7102011.11
      2289531.55      7102015.05      2289579.00      7102060.00
      2289575.86      7102108.97      2289439.30      7102199.90
      2289430.10      7102299.44      2289534.58      7102554.42
      2289634.95      7102607.67      2289727.75      7102613.51
      2289775.56      7102661.23      2289780.41      7102799.57
      2289821.74      7102860.30      2289734.62      7102915.61
      2289686.56      7103006.76      2289729.00      7103060.00

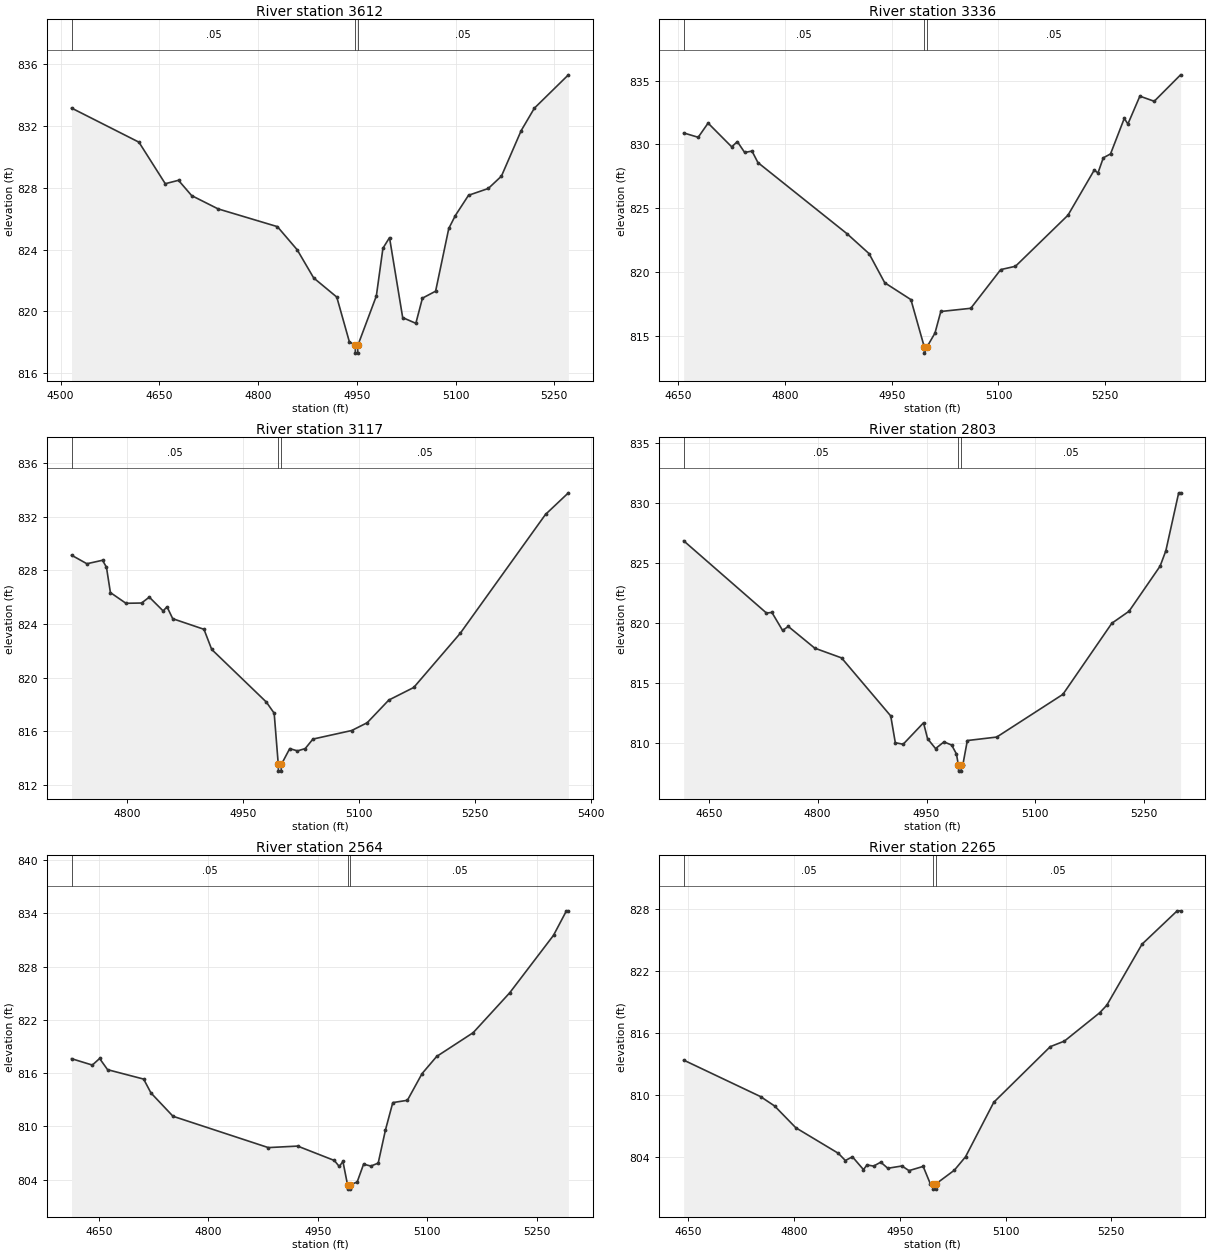
Type RM Length L Ch R = 1,3612,276,276,276
BEGIN DESCRIPTION:
MDW T 023 12.0
END DESCRIPTION:
XS GIS Cut Line= 3
      2287672.18      7102222.20      2287697.45      7101797.17
      2287703.43      7101468.30
#Sta/Elev= 30
  4516.7  833.17  4619.1  830.96  4659.1  828.27  4679.2  828.49  4699.2  827.50
  4739.3  826.64  4829.4  825.49  4859.5  823.99  4884.5  822.17  4919.6  820.93
  4938.6  818.05  4947.6  817.80  4947.9  817.30  4951.4  817.30  4951.6  817.80
  4979.7  821.00  4989.7  824.09  4999.7  824.78  5019.7  819.60  5039.7  819.23
  5049.7  820.86  5069.7  821.31  5089.7  825.37  5099.7  826.21  5119.7  827.52
  5149.7  827.96  5169.7  828.76  5199.7  831.71  5219.7  833.16  5271.4  835.32
#Mann=3,-1,0
  4516.7    0.05       0  4947.6    0.04       0  4951.6    0.05       0
Bank Sta=4947.6,4951.6
Exp/Cntr=0.3,0.1

Type RM Length L Ch R = 1,3336,219,219,219
BEGIN DESCRIPTION:
MDW T 023 11.0
END DESCRIPTION:
XS GIS Cut Line= 3
      2287798.87      7102193.34      2287878.86      7101860.51
      2287961.47      7101514.33
#Sta/Elev= 30
  4657.7  830.90  4678.1  830.56  4692.0  831.67  4725.2  829.81  4733.1  830.22
  4743.4  829.37  4753.7  829.48  4762.0  828.58  4887.4  823.00  4918.2  821.45
  4940.2  819.17  4977.0  817.85  4995.7  814.16  4995.9  813.66  4999.7  814.16
  5010.8  815.23  5019.0  816.92  5061.1  817.17  5103.2  820.20  5123.9  820.46
  5197.7  824.46  5234.7  828.00  5239.8  827.76  5247.3  828.95  5257.5  829.26
  5276.8  832.04  5281.9  831.60  5298.7  833.78  5318.9  833.38  5355.9  835.45
#Mann=3,-1,0
  4657.7    0.05       0  4995.7   0.033       0  4999.7    0.05       0
Bank Sta=4995.7,4999.7
Exp/Cntr=0.3,0.1

Type RM Length L Ch R = 1,3117,314,314,314
BEGIN DESCRIPTION:
MDW T 023 10.0
END DESCRIPTION:
XS GIS Cut Line= 3
      2288028.04      7102229.77      2288063.82      7101960.44
      2288090.53      7101590.50
#Sta/Elev= 30
  4728.3  829.14  4748.2  828.50  4768.4  828.76  4773.5  828.24  4778.6  826.35
  4798.7  825.55  4818.9  825.57  4828.9  826.01  4846.8  824.98  4851.8  825.29
  4859.2  824.40  4899.6  823.61  4909.6  822.11  4980.3  818.18  4990.4  817.35
  4995.7  813.53  4995.9  813.03  4999.4  813.03  4999.7  813.53  5010.5  814.71
  5020.5  814.54  5030.5  814.71  5040.5  815.42  5090.7  816.06  5110.7  816.64
  5138.6  818.33  5170.9  819.27  5231.0  823.31  5341.3  832.18  5370.9  833.79
#Mann=3,-1,0
  4728.3    0.05       0  4995.7   0.033       0  4999.7    0.05       0
Bank Sta=4995.7,4999.7
Exp/Cntr=0.3,0.1

Type RM Length L Ch R = 1,2803,239,239,239
BEGIN DESCRIPTION:
MDW T 023 9.0
END DESCRIPTION:
XS GIS Cut Line= 3
      2288210.33      7102302.73      2288377.43      7101956.22
      2288328.99      7101659.95
#Sta/Elev= 30
  4615.3  826.85  4729.4  820.83  4736.9  820.88  4751.6  819.38  4759.5  819.71
  4796.0  817.90  4832.9  817.09  4900.7  812.25  4907.0  810.02  4917.8  809.89
  4945.9  811.68  4951.5  810.35  4962.5  809.53  4974.1  810.09  4984.7  809.82
  4991.2  809.09  4994.0  808.15  4994.3  807.65  4997.8  807.65  4998.0  808.15
  5000.0  808.15  5006.3  810.20  5046.8  810.49  5138.0  814.05  5205.5  819.98
  5229.2  820.98  5272.0  824.74  5279.9  826.02  5297.6  830.85  5300.2  830.85
#Mann=3,-1,0
  4615.3    0.05       0  4994.0   0.033       0  4998.0    0.05       0
Bank Sta=4994,4998
Exp/Cntr=0.3,0.1

Type RM Length L Ch R = 1,2564,299,299,299
BEGIN DESCRIPTION:
MDW T 023 8.0
END DESCRIPTION:
XS GIS Cut Line= 3
      2288559.81      7102278.37      2288595.76      7101892.64
      2288599.74      7101599.57
#Sta/Elev= 30
  4612.6  817.63  4641.1  816.91  4651.1  817.65  4662.0  816.39  4711.4  815.33
  4721.4  813.77  4751.6  811.14  4882.1  807.61  4922.3  807.78  4972.5  806.16
  4979.3  805.48  4984.3  806.05  4990.6  803.43  4990.9  802.93  4994.4  802.93
  4994.6  803.43  5003.8  803.73  5012.6  805.74  5022.6  805.53  5032.6  805.86
  5042.6  809.61  5052.6  812.68  5072.6  812.94  5092.7  815.95  5112.7  817.88
  5162.7  820.56  5212.7  825.05  5272.7  831.53  5290.4  834.29  5293.1  834.29
#Mann=3,-1,0
  4612.6    0.05       0  4990.6   0.033       0  4994.6    0.05       0
Bank Sta=4990.6,4994.6
Exp/Cntr=0.3,0.1

Type RM Length L Ch R = 1,2265,253,253,253
BEGIN DESCRIPTION:
MDW T 023 7.0
END DESCRIPTION:
XS GIS Cut Line= 3
      2288875.36      7102298.59      2288845.56      7101943.14
      2288825.02      7101595.44
#Sta/Elev= 30
  4643.3  813.40  4752.3  809.87  4772.3  808.96  4802.4  806.85  4862.7  804.38
  4872.7  803.68  4882.7  804.04  4898.4  802.80  4903.4  803.25  4912.8  803.14
  4922.9  803.52  4932.9  802.93  4953.0  803.15  4963.0  802.70  4983.1  803.11
  4993.1  801.45  4997.1  801.41  4997.3  800.91  5000.8  800.91  5001.1  801.41
  5027.3  802.74  5043.2  804.04  5083.3  809.32  5163.4  814.70  5183.5  815.24
  5233.5  817.98  5243.6  818.71  5293.6  824.62  5343.5  827.85  5348.3  827.85
#Mann=3,-1,0
  4643.3    0.05       0  4997.1   0.033       0  5001.1    0.05       0
Bank Sta=4997.1,5001.1
Exp/Cntr=0.3,0.1

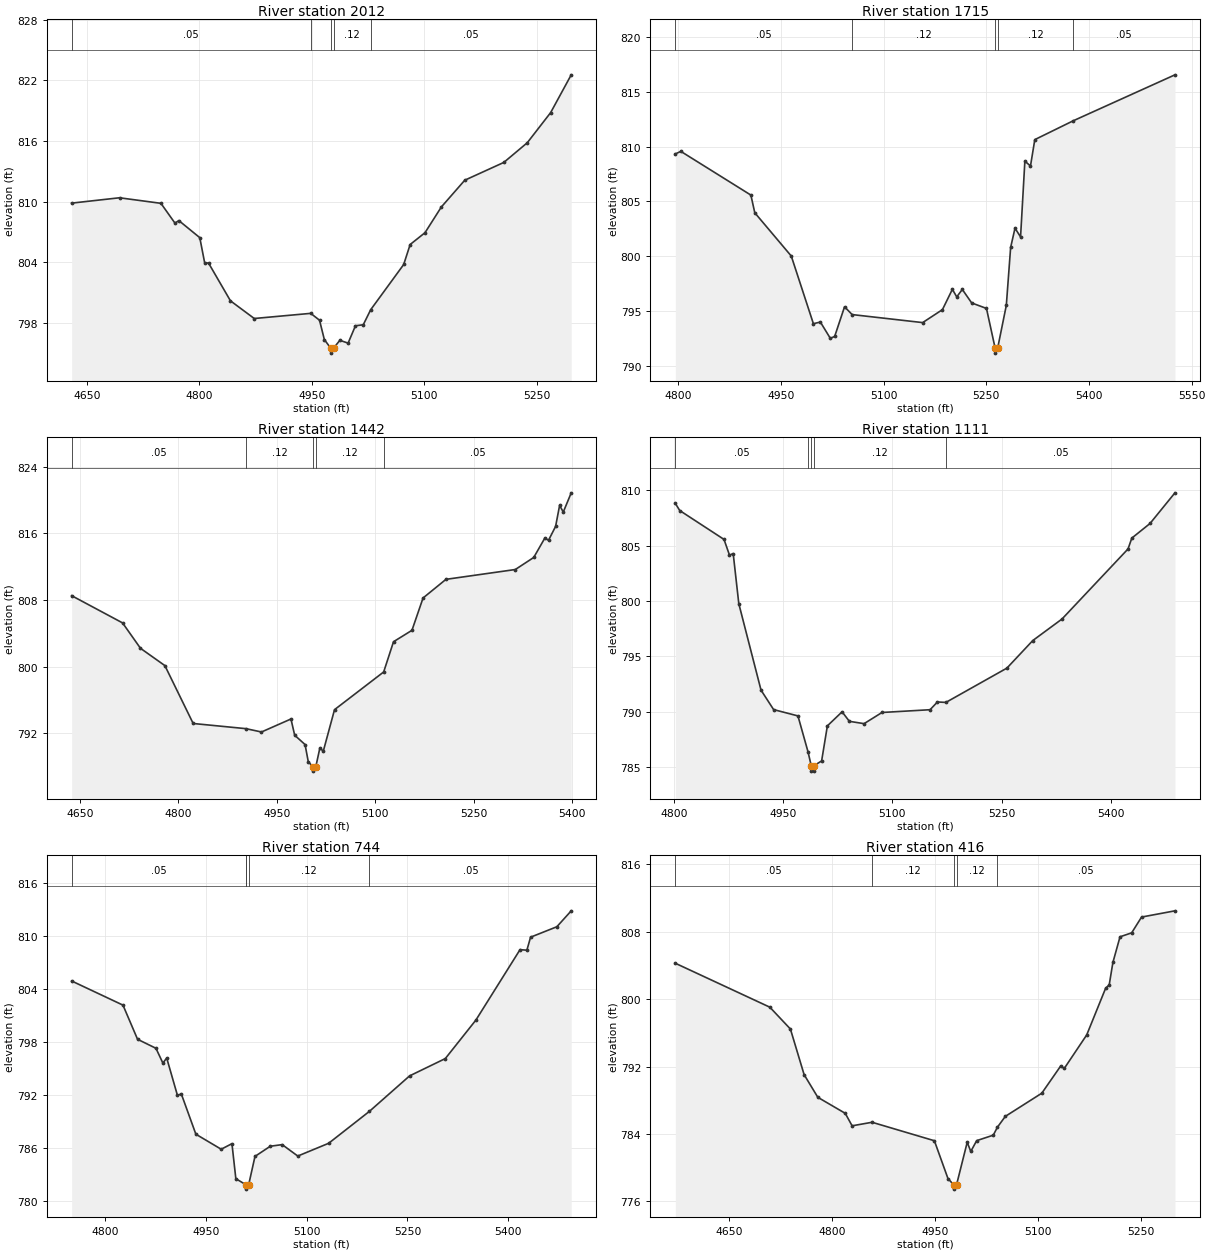
Type RM Length L Ch R = 1,2012,297,297,297
BEGIN DESCRIPTION:
MDW T 023 6.0
END DESCRIPTION:
XS GIS Cut Line= 3
      2289171.42      7102224.69      2289073.09      7101867.79
      2288991.25      7101583.64
#Sta/Elev= 30
  4629.8  809.84  4693.6  810.37  4748.8  809.82  4767.5  807.86  4772.7  808.11
  4800.6  806.42  4807.1  803.93  4812.3  803.90  4841.5  800.16  4873.2  798.41
  4948.5  798.92  4960.2  798.24  4966.6  796.33  4975.0  795.48  4975.2  794.98
  4979.0  795.48  4987.3  796.25  4998.3  795.97  5008.1  797.69  5018.5  797.79
  5028.4  799.28  5072.4  803.76  5081.0  805.74  5100.8  806.91  5122.6  809.46
  5153.8  812.11  5205.8  813.87  5237.1  815.82  5268.3  818.81  5295.7  822.55
#Mann=5,-1,0
  4629.8    0.05       0  4948.5    0.12       0  4975.0    0.07       0
  4979.0    0.12       0  5028.4    0.05       0
Bank Sta=4975,4979
Exp/Cntr=0.3,0.1

Type RM Length L Ch R = 1,1715,273,273,273
BEGIN DESCRIPTION:
MDW T 023 5.0
END DESCRIPTION:
XS GIS Cut Line= 3
      2289197.67      7102207.86      2289298.84      7102030.60
      2289621.27      7101615.52
#Sta/Elev= 30
  4795.9  809.33  4803.9  809.56  4906.2  805.58  4911.9  803.97  4965.2  800.03
  4997.5  793.87  5007.7  794.02  5022.2  792.54  5028.6  792.71  5043.0  795.41
  5054.1  794.70  5157.1  793.97  5186.0  795.15  5200.5  797.00  5206.9  796.31
  5215.0  796.99  5228.7  795.76  5250.3  795.26  5262.8  791.69  5263.0  791.19
  5266.8  791.69  5279.3  795.54  5285.6  800.81  5292.0  802.57  5300.1  801.77
  5306.4  808.67  5314.6  808.23  5320.9  810.63  5377.2  812.35  5525.6  816.53
#Mann=5,-1,0
  4795.9    0.05       0  5054.1    0.12       0  5262.8   0.033       0
  5266.8    0.12       0  5377.2    0.05       0
Bank Sta=5262.8,5266.8
Exp/Cntr=0.3,0.1

Type RM Length L Ch R = 1,1442,331,331,331
BEGIN DESCRIPTION:
MDW T 023 4.0
END DESCRIPTION:
XS GIS Cut Line= 3
      2289228.89      7102205.10      2289542.48      7102022.87
      2289900.41      7101847.46
#Sta/Elev= 30
  4637.3  808.51  4714.9  805.24  4742.2  802.19  4779.4  800.11  4822.5  793.16
  4902.9  792.54  4926.6  792.14  4971.5  793.70  4977.2  791.75  4993.0  790.63
  4997.9  788.57  5005.3  787.94  5005.5  787.44  5009.3  787.94  5015.4  790.16
  5020.9  789.87  5037.9  794.82  5112.8  799.35  5127.8  802.98  5155.9  804.35
  5172.8  808.23  5207.7  810.47  5313.4  811.65  5341.5  813.10  5358.4  815.43
  5364.0  815.16  5374.8  816.83  5380.9  819.35  5386.5  818.55  5398.6  820.86
#Mann=5,-1,0
  4637.3    0.05       0  4902.9    0.12       0  5005.3    0.07       0
  5009.3    0.12       0  5112.8    0.05       0
Bank Sta=5005.3,5009.3
Exp/Cntr=0.3,0.1

Type RM Length L Ch R = 1,1111,367,367,367
BEGIN DESCRIPTION:
MDW T 023 3.0
END DESCRIPTION:
XS GIS Cut Line= 3
      2289233.08      7102287.72      2289428.14      7102254.92
      2289912.92      7102198.14
#Sta/Elev= 30
  4802.2  808.81  4808.2  808.17  4869.0  805.56  4876.5  804.14  4881.6  804.28
  4889.3  799.75  4919.8  791.94  4937.1  790.18  4970.5  789.61  4984.3  786.37
  4988.7  785.12  4989.0  784.62  4992.5  784.62  4992.7  785.12  5003.0  785.54
  5010.9  788.71  5031.1  789.98  5041.1  789.12  5061.3  788.91  5085.9  789.92
  5151.9  790.17  5162.0  790.87  5173.6  790.83  5257.4  793.93  5292.9  796.42
  5333.1  798.37  5423.7  804.70  5428.9  805.68  5453.9  807.00  5488.1  809.77
#Mann=5,-1,0
  4802.2    0.05       0  4984.3    0.12       0  4988.7    0.07       0
  4992.7    0.12       0  5173.6    0.05       0
Bank Sta=4988.7,4992.7
Exp/Cntr=0.3,0.1

Type RM Length L Ch R = 1,744,328,328,328
BEGIN DESCRIPTION:
MDW T 023 2.0
END DESCRIPTION:
XS GIS Cut Line= 3
      2289349.74      7102683.56      2289567.90      7102561.88
      2290018.52      7102359.93
#Sta/Elev= 30
  4750.2  804.92  4826.6  802.19  4848.3  798.33  4875.7  797.31  4886.0  795.64
  4891.7  796.21  4907.7  791.98  4913.4  792.16  4935.1  787.60  4972.8  785.90
  4988.8  786.53  4994.6  782.57  5009.3  781.90  5009.7  781.89  5010.0  781.39
  5013.7  781.89  5023.1  785.09  5045.9  786.24  5063.6  786.42  5086.8  785.13
  5132.7  786.57  5193.4  790.18  5253.2  794.19  5306.4  796.15  5351.9  800.50
  5417.6  808.46  5427.8  808.40  5433.3  809.87  5472.4  811.05  5493.8  812.85
#Mann=5,-1,0
  4750.2    0.05       0  5009.3    0.12       0  5009.7   0.033       0
  5013.7    0.12       0  5193.4    0.05       0
Bank Sta=5009.7,5013.7
Exp/Cntr=0.3,0.1

Type RM Length L Ch R = 1,416,190,190,190
BEGIN DESCRIPTION:
MDW T 023 1.0
END DESCRIPTION:
XS GIS Cut Line= 3
      2289351.18      7102747.44      2289753.52      7102752.36
      2290065.59      7102656.93
#Sta/Elev= 30
  4571.1  804.25  4708.9  799.04  4738.9  796.45  4758.9  791.04  4778.9  788.35
  4818.9  786.45  4828.9  784.97  4858.0  785.39  4948.9  783.20  4968.7  778.72
  4977.2  777.96  4977.4  777.46  4981.2  777.96  4996.8  783.02  5002.0  781.93
  5010.6  783.21  5034.8  783.86  5040.9  784.81  5052.4  786.09  5105.6  788.84
  5133.1  792.06  5138.4  791.78  5171.1  795.75  5198.7  801.29  5203.9  801.68
  5209.3  804.35  5219.7  807.39  5236.7  807.86  5251.1  809.73  5299.8  810.47
#Mann=5,-1,0
  4571.1    0.05       0  4858.0    0.12       0  4977.2    0.07       0
  4981.2    0.12       0  5040.9    0.05       0
Bank Sta=4977.2,4981.2
Exp/Cntr=0.3,0.1

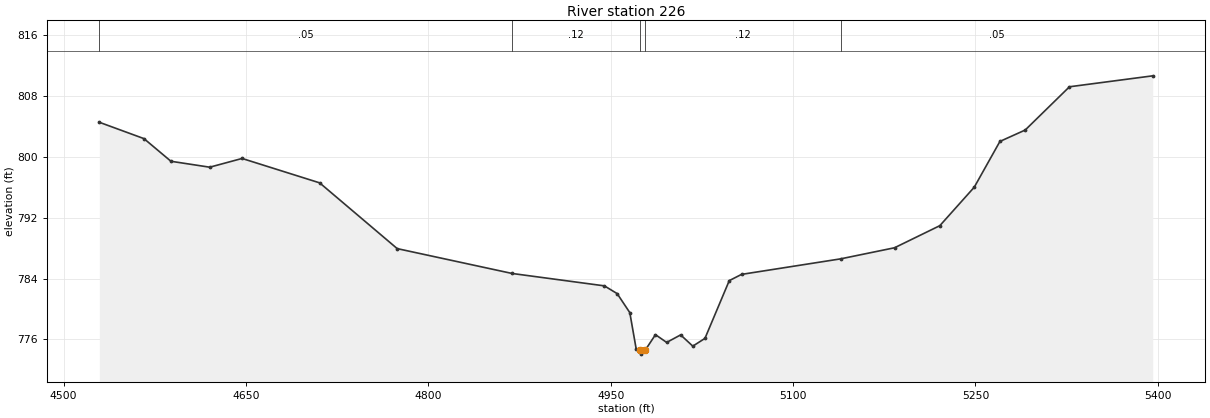
Type RM Length L Ch R = 1,226,0,0,0
BEGIN DESCRIPTION:
MDW T 023 0.5
END DESCRIPTION:
XS GIS Cut Line= 4
      2289334.15      7102757.97      2289781.51      7102904.01
      2289971.95      7102894.68      2290103.87      7102737.59
#Sta/Elev= 30
  4529.4  804.57  4566.1  802.42  4588.3  799.44  4620.2  798.66  4646.8  799.81
  4710.6  796.60  4774.4  787.95  4868.9  784.68  4944.8  783.05  4955.3  782.03
  4965.7  779.53  4971.0  774.70  4974.3  774.57  4974.6  774.07  4978.3  774.57
  4986.8  776.63  4996.0  775.61  5007.5  776.60  5017.5  775.12  5027.5  776.14
  5047.5  783.74  5057.6  784.56  5139.0  786.60  5183.4  788.06  5220.7  790.97
  5249.0  796.03  5270.1  802.05  5290.9  803.55  5327.3  809.24  5395.8  810.68
#Mann=5,-1,0
  4529.4    0.05       0  4868.9    0.12       0  4974.3    0.07       0
  4978.3    0.12       0  5139.0    0.05       0
Bank Sta=4974.3,4978.3
Exp/Cntr=0.3,0.1

Chan Stop Cuts=-1