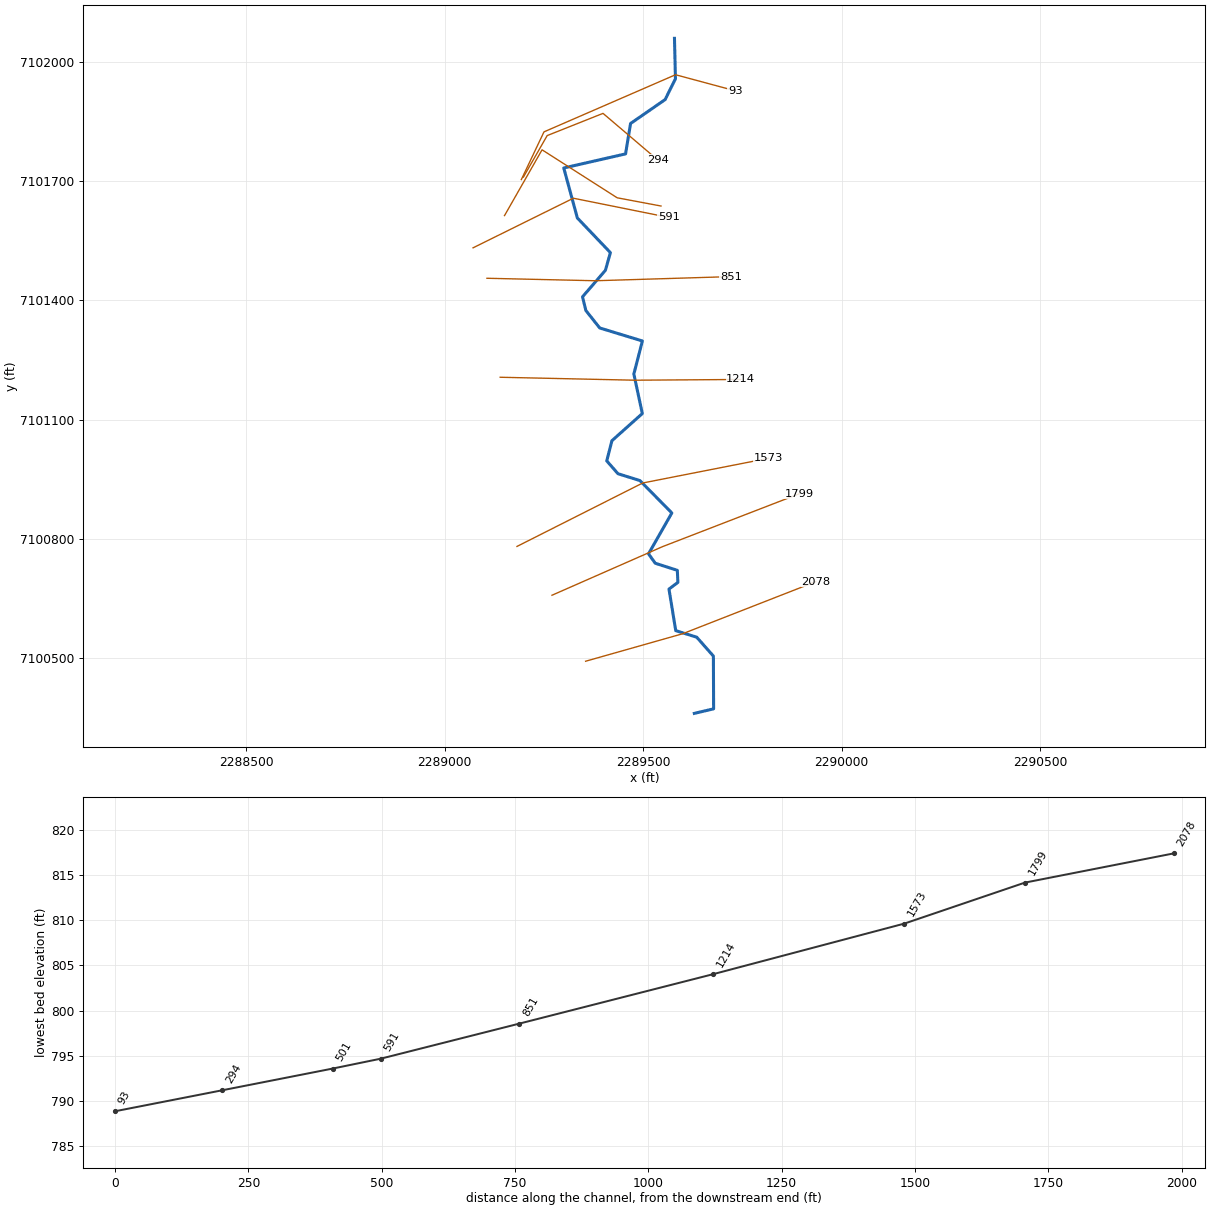
--- MDW T 024.prj (project) ---

Proj Title=MDW T 024 Base Level Engineering
Current Plan=p01
Default Exp/Contr=0.3,0.1
English Units
Geom File=g01
Flow File=f01
Plan File=p01
BEGIN DESCRIPTION:
MDW T 024
END DESCRIPTION:

--- MDW T 024.p01 (plan) ---

Plan Title=Multiple Run
Short Identifier=Multiple
Geom File=g01
Flow File=f01
Subcritical Flow
K Sum by GR= 0
Std Step Tol= 0.01
Critical Tol= 0.01
Num of Std Step Trials= 20
Max Error Tol= 0.3
Flow Tol Ratio= 0.001
Split Flow NTrial= 30
Split Flow Tol= 0.02
Split Flow Ratio= 0.02
Log Output Level= 0
Friction Slope Method= 1
Unsteady Friction Slope Method= 2
Unsteady Bridges Friction Slope Method= 1
Parabolic Critical Depth
Global Vel Dist=  1 , 1 , 1
Global Log Level= 0
CheckData=True
Encroach Param= -1, 0, 0, 0
BEGIN DESCRIPTION:
Multiple Run
END DESCRIPTION:

--- MDW T 024.f01 (steady flow) ---

Flow Title=Multiple
Number of Profiles=7
Profile Names=10-year,25-year,50-year,1pct_min,100-year,1pct_plu,500-year
River Rch & RM= MDW T 024,Reach-1,2078
     266     350     417     248     496     989     698
Boundary for River Rch & Prof#=MDW T 024,Reach-1,1
Up Type=0
Dn Type=3
Dn Slope=0.005
Boundary for River Rch & Prof#=MDW T 024,Reach-1,2
Up Type=0
Dn Type=3
Dn Slope=0.005
Boundary for River Rch & Prof#=MDW T 024,Reach-1,3
Up Type=0
Dn Type=3
Dn Slope=0.005
Boundary for River Rch & Prof#=MDW T 024,Reach-1,4
Up Type=0
Dn Type=3
Dn Slope=0.005
Boundary for River Rch & Prof#=MDW T 024,Reach-1,5
Up Type=0
Dn Type=3
Dn Slope=0.005
Boundary for River Rch & Prof#=MDW T 024,Reach-1,6
Up Type=0
Dn Type=3
Dn Slope=0.005
Boundary for River Rch & Prof#=MDW T 024,Reach-1,7
Up Type=0
Dn Type=3
Dn Slope=0.005

--- MDW T 024.g01 (geometry) ---

Geom Title=Existing Conditions

River Reach=MDW T 024,Reach-1
Reach XY= 30
      2289629.00      7100360.00      2289677.59      7100371.44
      2289677.01      7100504.31      2289635.04      7100551.83
      2289582.19      7100568.35      2289565.18      7100673.01
      2289587.57      7100689.89      2289586.21      7100720.26
      2289530.71      7100738.02      2289513.66      7100761.58
      2289572.35      7100864.77      2289491.95      7100946.29
      2289436.74      7100963.54      2289408.44      7100995.81
      2289421.48      7101046.67      2289498.02      7101115.07
      2289476.70      7101214.70      2289498.22      7101297.85
      2289390.71      7101330.61      2289355.89      7101374.54
      2289347.42      7101409.08      2289405.00      7101475.68
      2289417.67      7101520.33      2289334.42      7101607.58
      2289300.19      7101733.49      2289455.87      7101768.99
      2289468.37      7101845.49      2289555.47      7101905.76
      2289581.46      7101958.15      2289579.00      7102060.00

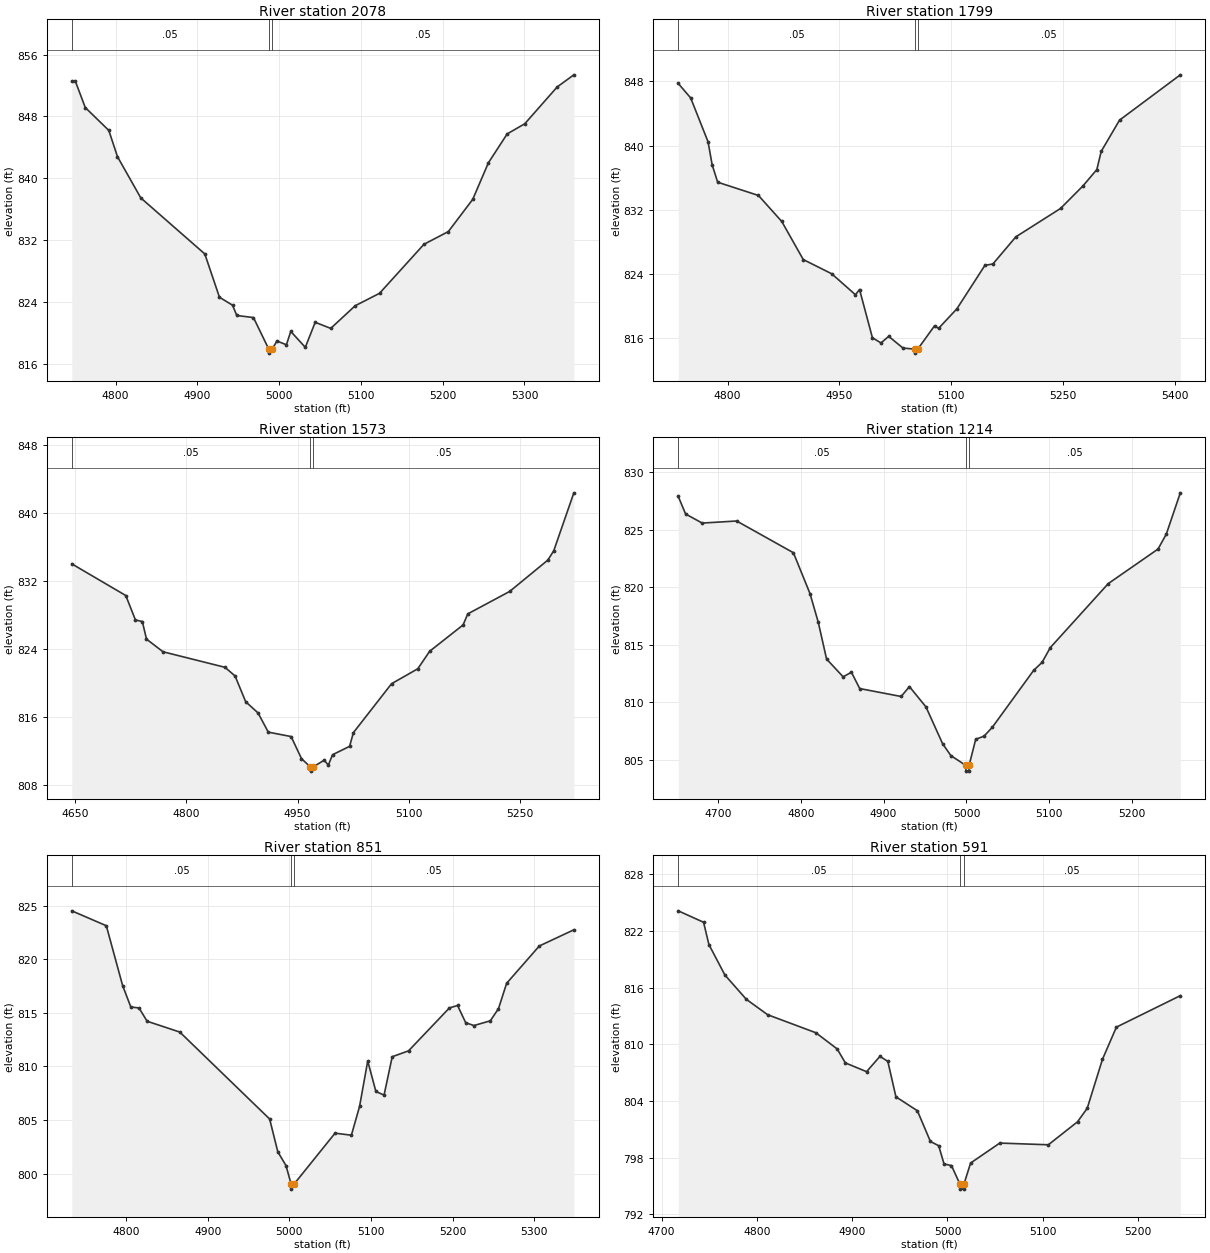
Type RM Length L Ch R = 1,2078,279,279,279
BEGIN DESCRIPTION:
MDW T 024 6.0
END DESCRIPTION:
XS GIS Cut Line= 3
      2289355.22      7100491.31      2289599.23      7100560.42
      2289934.86      7100691.71
#Sta/Elev= 30
  4746.4  852.52  4750.9  852.52  4762.9  849.15  4791.7  846.19  4802.3  842.79
  4830.8  837.46  4909.1  830.21  4927.0  824.61  4943.0  823.58  4948.2  822.25
  4968.6  821.98  4987.4  817.88  4987.6  817.38  4991.4  817.88  4997.3  818.95
  5008.9  818.46  5014.2  820.19  5032.0  818.13  5044.1  821.37  5063.1  820.58
  5093.0  823.51  5122.8  825.12  5177.1  831.46  5206.9  833.10  5236.8  837.28
  5255.9  842.00  5278.9  845.74  5300.4  847.05  5340.0  851.81  5360.4  853.38
#Mann=3,-1,0
  4746.4    0.05       0  4987.4   0.033       0  4991.4    0.05       0
Bank Sta=4987.4,4991.4
Exp/Cntr=0.3,0.1

Type RM Length L Ch R = 1,1799,226,226,226
BEGIN DESCRIPTION:
MDW T 024 5.0
END DESCRIPTION:
XS GIS Cut Line= 3
      2289270.54      7100657.49      2289549.03      7100779.93
      2289893.49      7100913.05
#Sta/Elev= 30
  4733.9  847.73  4750.6  845.92  4773.9  840.46  4779.4  837.60  4786.8  835.43
  4841.5  833.78  4872.8  830.54  4901.6  825.80  4939.8  824.03  4971.6  821.42
  4977.1  822.07  4994.4  816.06  5005.9  815.42  5016.2  816.24  5035.4  814.78
  5051.2  814.65  5051.4  814.15  5055.2  814.65  5077.8  817.56  5083.1  817.23
  5107.7  819.67  5145.3  825.08  5156.0  825.25  5186.8  828.63  5246.7  832.16
  5276.7  834.96  5295.4  837.00  5301.3  839.27  5325.9  843.16  5407.4  848.80
#Mann=3,-1,0
  4733.9    0.05       0  5051.2   0.033       0  5055.2    0.05       0
Bank Sta=5051.2,5055.2
Exp/Cntr=0.3,0.1

Type RM Length L Ch R = 1,1573,359,359,359
BEGIN DESCRIPTION:
MDW T 024 4.0
END DESCRIPTION:
XS GIS Cut Line= 3
      2289182.35      7100780.40      2289498.93      7100940.16
      2289815.58      7101002.34
#Sta/Elev= 30
  4645.4  834.02  4718.3  830.29  4731.3  827.41  4740.6  827.23  4746.2  825.16
  4768.5  823.67  4852.1  821.84  4865.7  820.82  4880.0  817.79  4896.7  816.47
  4910.5  814.21  4941.3  813.69  4955.3  811.09  4967.2  810.12  4967.5  809.62
  4971.2  810.12  4985.9  810.91  4991.5  810.33  4997.2  811.55  5020.2  812.54
  5025.3  814.15  5076.8  819.91  5112.2  821.67  5128.2  823.73  5173.3  826.83
  5179.6  828.13  5236.1  830.77  5287.6  834.46  5295.6  835.56  5322.7  842.38
#Mann=3,-1,0
  4645.4    0.05       0  4967.2   0.033       0  4971.2    0.05       0
Bank Sta=4967.2,4971.2
Exp/Cntr=0.3,0.1

Type RM Length L Ch R = 1,1214,363,363,363
BEGIN DESCRIPTION:
MDW T 024 3.0
END DESCRIPTION:
XS GIS Cut Line= 3
      2289140.06      7101206.47      2289479.36      7101199.04
      2289745.87      7101200.90
#Sta/Elev= 30
  4652.2  827.91  4661.1  826.38  4681.1  825.59  4722.7  825.77  4791.2  823.01
  4811.2  819.46  4821.2  816.96  4831.2  813.77  4851.2  812.22  4861.2  812.62
  4871.2  811.20  4921.2  810.51  4931.2  811.37  4951.2  809.60  4971.2  806.41
  4981.2  805.37  4999.2  804.52  4999.5  804.02  5003.0  804.02  5003.2  804.52
  5011.2  806.79  5021.2  807.06  5031.2  807.83  5081.2  812.79  5091.2  813.47
  5101.2  814.76  5171.2  820.33  5231.2  823.33  5241.2  824.63  5258.1  828.22
#Mann=3,-1,0
  4652.2    0.05       0  4999.2   0.033       0  5003.2    0.05       0
Bank Sta=4999.2,5003.2
Exp/Cntr=0.3,0.1

Type RM Length L Ch R = 1,851,260,260,260
BEGIN DESCRIPTION:
MDW T 024 2.0
END DESCRIPTION:
XS GIS Cut Line= 3
      2289106.72      7101455.77      2289380.27      7101449.52
      2289721.29      7101459.94
#Sta/Elev= 30
  4733.5  824.52  4775.8  823.13  4795.8  817.54  4805.8  815.55  4815.8  815.46
  4825.8  814.22  4865.8  813.21  4975.8  805.10  4985.8  802.04  4995.8  800.76
  5002.0  799.06  5002.2  798.56  5006.0  799.06  5055.9  803.78  5075.9  803.59
  5085.9  806.27  5095.9  810.51  5105.9  807.67  5115.9  807.33  5125.9  810.91
  5145.9  811.46  5195.9  815.46  5205.9  815.69  5215.9  814.08  5226.0  813.82
  5246.0  814.26  5256.0  815.39  5266.0  817.76  5306.0  821.24  5348.3  822.75
#Mann=3,-1,0
  4733.5    0.05       0  5002.0   0.033       0  5006.0    0.05       0
Bank Sta=5002,5006
Exp/Cntr=0.3,0.1

Type RM Length L Ch R = 1,591,90,90,90
BEGIN DESCRIPTION:
Mapping XS aebc1916
END DESCRIPTION:
XS GIS Cut Line= 3
      2289071.76      7101532.41      2289324.41      7101657.36
      2289564.74      7101609.02
#Sta/Elev= 30
  4717.4  824.11  4744.0  822.90  4749.6  820.54  4766.4  817.32  4788.9  814.75
  4811.3  813.12  4861.8  811.22  4884.2  809.51  4892.8  808.03  4915.1  807.10
  4929.1  808.72  4937.4  808.19  4945.9  804.44  4968.4  802.97  4982.1  799.72
  4990.8  799.27  4996.4  797.34  5004.2  797.17  5013.2  795.18  5013.5  794.68
  5017.0  794.68  5017.2  795.18  5024.3  797.44  5054.9  799.55  5105.9  799.37
  5136.5  801.80  5146.7  803.23  5162.7  808.41  5177.3  811.81  5244.4  815.14
#Mann=3,-1,0
  4717.4    0.05       0  5013.2   0.033       0  5017.2    0.05       0
Bank Sta=5013.2,5017.2
Exp/Cntr=0.3,0.1

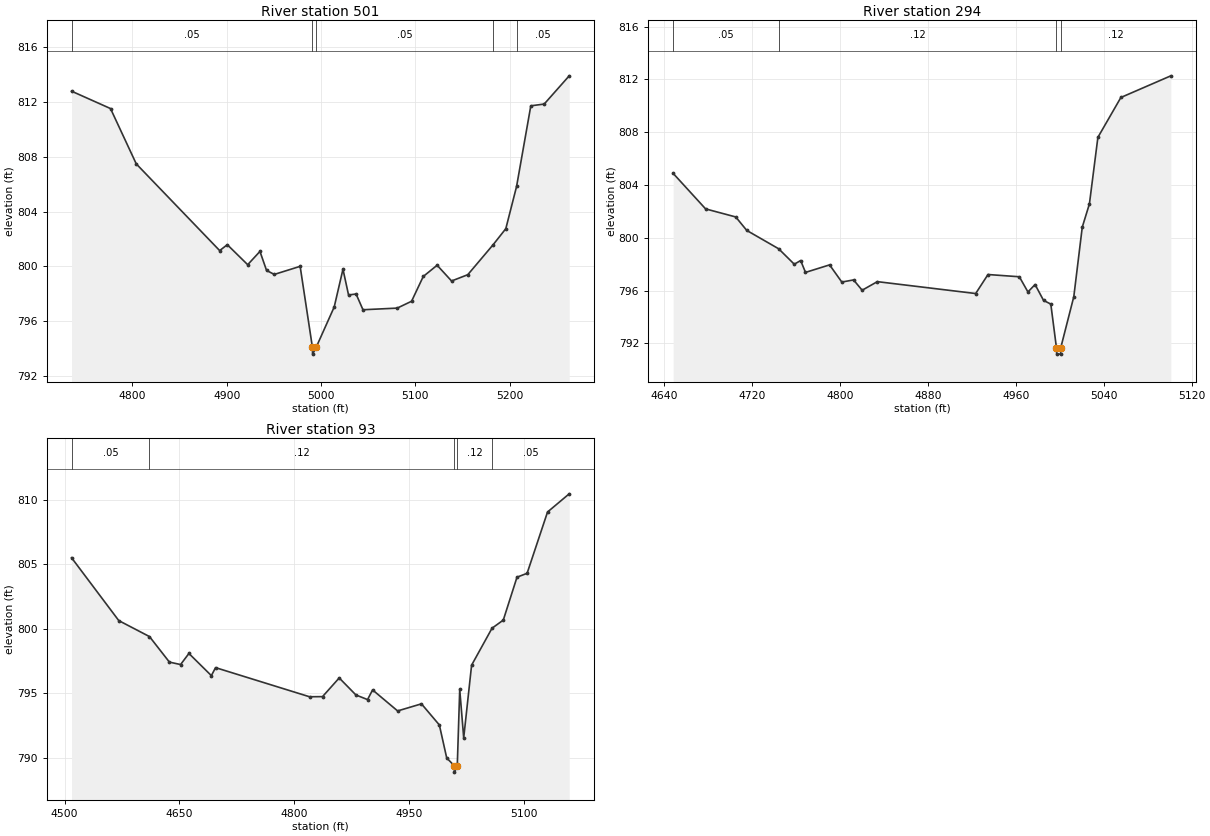
Type RM Length L Ch R = 1,501,207,207,207
BEGIN DESCRIPTION:
Mapping XS 69c0b630
END DESCRIPTION:
XS GIS Cut Line= 4
      2289151.00      7101613.62      2289245.54      7101779.28
      2289434.74      7101658.41      2289545.07      7101637.70
#Sta/Elev= 30
  4735.5  812.79  4776.8  811.52  4804.1  807.48  4892.5  801.15  4900.6  801.58
  4922.2  800.12  4935.2  801.09  4942.2  799.70  4950.4  799.41  4977.8  800.00
  4990.8  794.09  4991.0  793.59  4994.8  794.09  5013.9  797.03  5023.2  799.79
  5029.1  797.91  5037.1  797.98  5044.4  796.83  5080.7  796.95  5095.9  797.45
  5108.3  799.26  5123.0  800.08  5138.3  798.93  5155.5  799.39  5182.5  801.59
  5195.8  802.75  5207.2  805.83  5222.3  811.72  5236.5  811.85  5263.0  813.91
#Mann=5,-1,0
  4735.5    0.05       0  4990.8   0.033       0  4994.8    0.05       0
  5182.5    0.12       0  5207.2    0.05       0
Bank Sta=4990.8,4994.8
Exp/Cntr=0.3,0.1

Type RM Length L Ch R = 1,294,201,201,201
BEGIN DESCRIPTION:
Mapping XS b6b14838
END DESCRIPTION:
XS GIS Cut Line= 4
      2289198.59      7101710.65      2289258.42      7101815.08
      2289399.08      7101871.03      2289536.64      7101753.92
#Sta/Elev= 30
  4648.6  804.88  4678.1  802.19  4705.5  801.58  4715.5  800.56  4744.5  799.17
  4758.7  798.00  4764.5  798.28  4768.9  797.38  4790.8  797.95  4801.9  796.65
  4812.6  796.81  4820.4  796.03  4834.2  796.68  4923.6  795.78  4934.8  797.22
  4963.3  797.05  4971.1  795.90  4977.6  796.46  4985.3  795.26  4991.9  794.98
  4997.0  791.69  4997.3  791.19  5000.8  791.19  5001.0  791.69  5012.8  795.54
  5020.5  800.81  5027.0  802.57  5034.7  807.61  5055.6  810.63  5101.0  812.27
#Mann=4,-1,0
  4648.6    0.05       0  4744.5    0.12       0  4997.0    0.07       0
  5001.0    0.12       0
Bank Sta=4997,5001
Exp/Cntr=0.3,0.1

Type RM Length L Ch R = 1,93,0,0,0
BEGIN DESCRIPTION:
MDW T 024 1.0
END DESCRIPTION:
XS GIS Cut Line= 4
      2289193.33      7101704.26      2289250.39      7101824.44
      2289581.68      7101968.33      2289732.11      7101927.87
#Sta/Elev= 30
  4509.1  805.51  4570.8  800.63  4610.9  799.39  4636.9  797.41  4651.5  797.22
  4662.4  798.08  4691.7  796.36  4697.2  796.98  4819.9  794.72  4836.9  794.73
  4858.7  796.18  4880.5  794.86  4895.7  794.50  4902.3  795.25  4935.0  793.62
  4966.1  794.17  4989.5  792.53  4999.1  789.97  5008.9  789.37  5009.2  788.87
  5012.9  789.37  5016.1  795.29  5021.3  791.53  5031.6  797.17  5058.3  800.04
  5073.0  800.67  5090.9  804.00  5104.1  804.30  5130.8  809.06  5159.1  810.47
#Mann=5,-1,0
  4509.1    0.05       0  4610.9    0.12       0  5008.9    0.07       0
  5012.9    0.12       0  5058.3    0.05       0
Bank Sta=5008.9,5012.9
Exp/Cntr=0.3,0.1

Chan Stop Cuts=-1