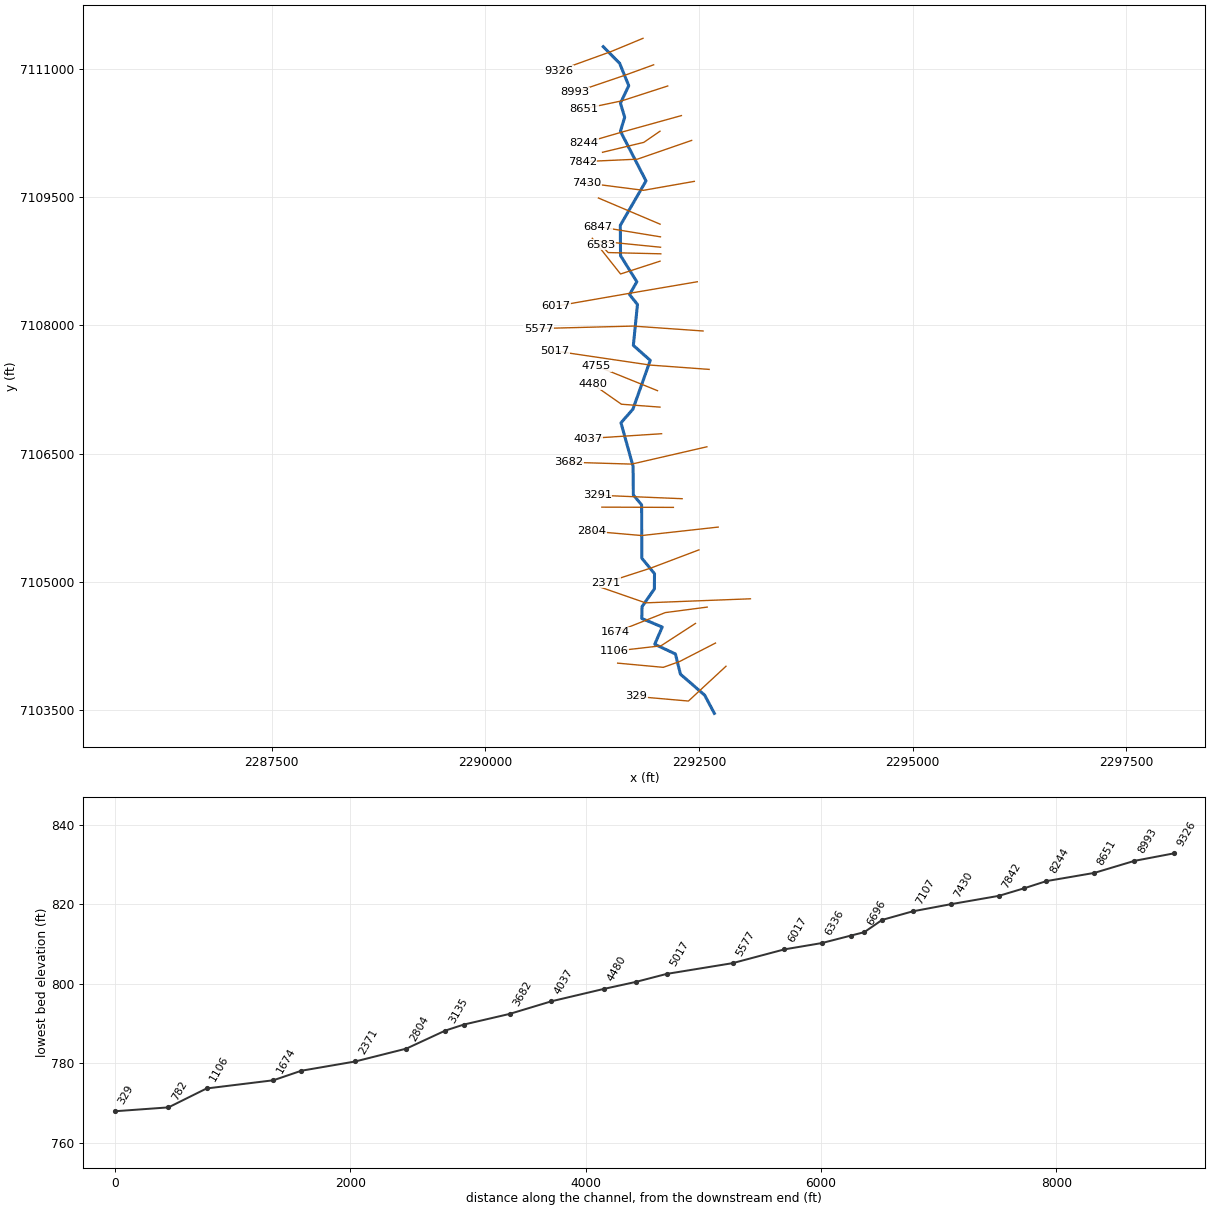
--- MDW T 025.prj (project) ---

Proj Title=MDW T 025 Base Level Engineering
Current Plan=p01
Default Exp/Contr=0.3,0.1
English Units
Geom File=g01
Flow File=f01
Plan File=p01
BEGIN DESCRIPTION:
MDW T 025
END DESCRIPTION:

--- MDW T 025.p01 (plan) ---

Plan Title=Multiple Run
Short Identifier=Multiple
Geom File=g01
Flow File=f01
Subcritical Flow
K Sum by GR= 0
Std Step Tol= 0.01
Critical Tol= 0.01
Num of Std Step Trials= 20
Max Error Tol= 0.3
Flow Tol Ratio= 0.001
Split Flow NTrial= 30
Split Flow Tol= 0.02
Split Flow Ratio= 0.02
Log Output Level= 0
Friction Slope Method= 1
Unsteady Friction Slope Method= 2
Unsteady Bridges Friction Slope Method= 1
Parabolic Critical Depth
Global Vel Dist=  1 , 1 , 1
Global Log Level= 0
CheckData=True
Encroach Param= -1, 0, 0, 0
BEGIN DESCRIPTION:
Multiple Run
END DESCRIPTION:

--- MDW T 025.f01 (steady flow) ---

Flow Title=Multiple
Number of Profiles=7
Profile Names=10-year,25-year,50-year,1pct_min,100-year,1pct_plu,500-year
River Rch & RM= MDW T 025,Reach-1,9326
     531     726     886     538    1074    2142    1578
River Rch & RM= MDW T 025,Reach-1,7842
     568     779     954     580    1157    2309    1708
River Rch & RM= MDW T 025,Reach-1,6336
     775    1081    1339     822    1641    3274    2473
River Rch & RM= MDW T 025,Reach-1,2804
     872    1224    1521     937    1870    3732    2837
Boundary for River Rch & Prof#=MDW T 025,Reach-1,1
Up Type=0
Dn Type=3
Dn Slope=0.005
Boundary for River Rch & Prof#=MDW T 025,Reach-1,2
Up Type=0
Dn Type=3
Dn Slope=0.005
Boundary for River Rch & Prof#=MDW T 025,Reach-1,3
Up Type=0
Dn Type=3
Dn Slope=0.005
Boundary for River Rch & Prof#=MDW T 025,Reach-1,4
Up Type=0
Dn Type=3
Dn Slope=0.005
Boundary for River Rch & Prof#=MDW T 025,Reach-1,5
Up Type=0
Dn Type=3
Dn Slope=0.005
Boundary for River Rch & Prof#=MDW T 025,Reach-1,6
Up Type=0
Dn Type=3
Dn Slope=0.005
Boundary for River Rch & Prof#=MDW T 025,Reach-1,7
Up Type=0
Dn Type=3
Dn Slope=0.005

--- MDW T 025.g01 (geometry) ---

Geom Title=Existing Conditions

River Reach=MDW T 025,Reach-1
Reach XY= 30
      2291379.00      7111260.00      2291570.84      7111066.05
      2291677.18      7110803.88      2291580.09      7110599.46
      2291629.40      7110435.00      2291580.09      7110270.54
      2291879.21      7109689.94      2291578.54      7109170.19
      2291581.24      7108815.93      2291771.81      7108510.09
      2291686.30      7108359.92      2291779.04      7108244.66
      2291730.98      7107765.67      2291929.07      7107590.01
      2291725.51      7107018.48      2291586.33      7106860.10
      2291727.78      7106349.50      2291731.07      7106015.86
      2291827.94      7105899.56      2291829.92      7105275.94
      2291978.62      7105094.84      2291976.94      7104915.86
      2291832.74      7104708.44      2291829.96      7104570.27
      2292068.74      7104470.12      2291981.58      7104268.53
      2292223.56      7104154.75      2292282.08      7103918.31
      2292565.38      7103673.22      2292679.00      7103460.00

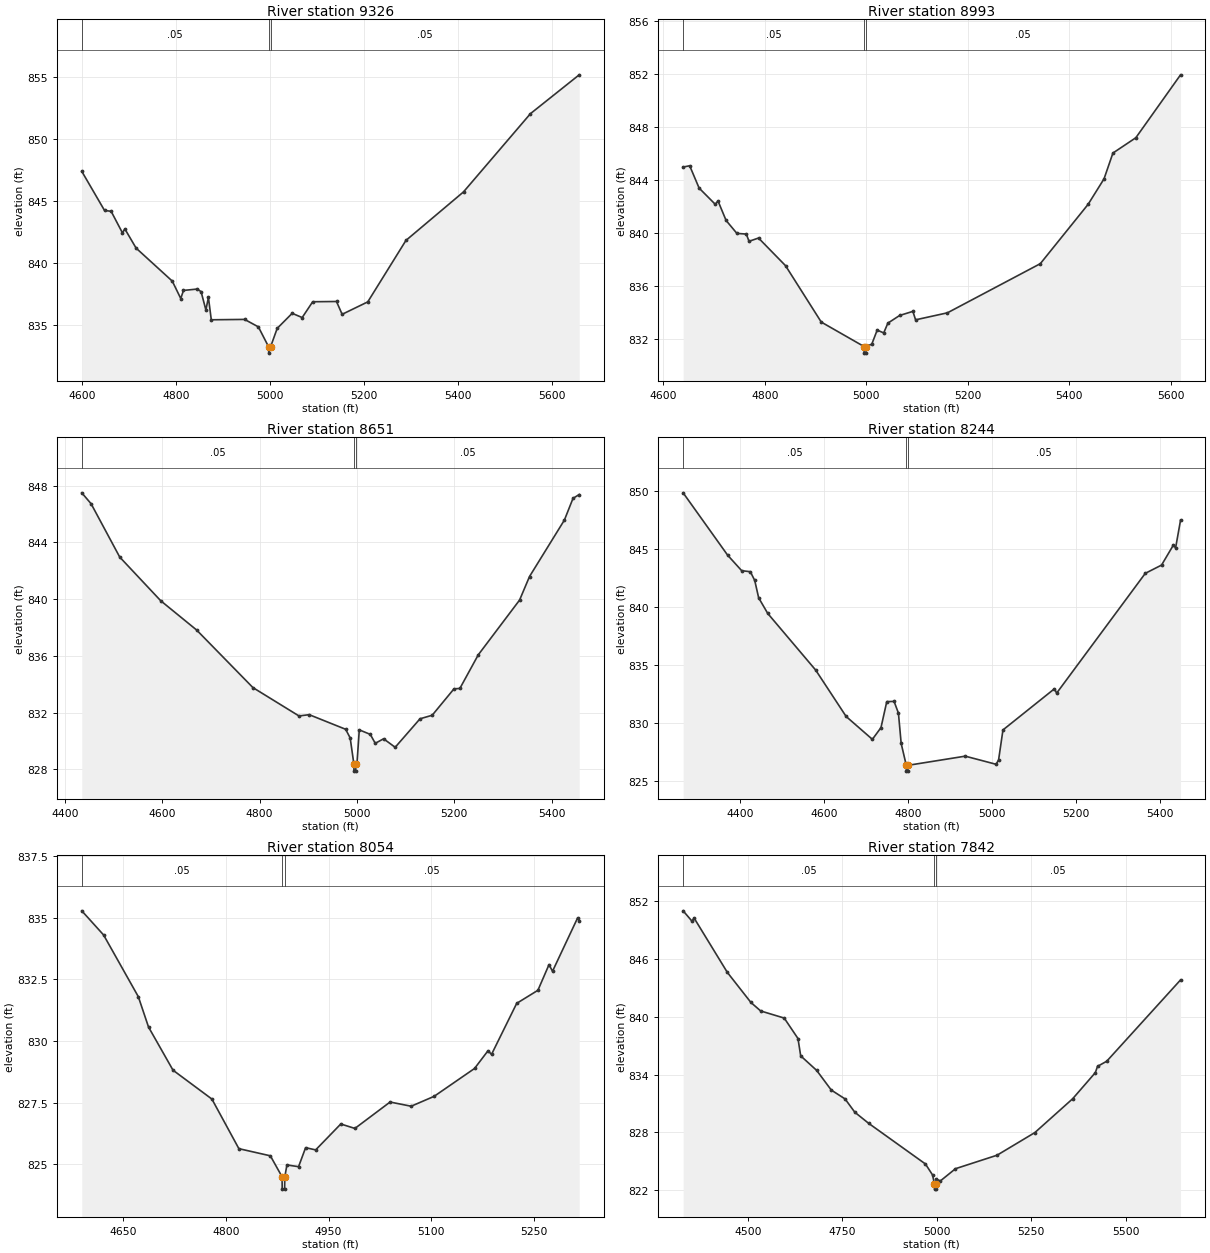
Type RM Length L Ch R = 1,9326,333,333,333
BEGIN DESCRIPTION:
MDW T 025 20.0
END DESCRIPTION:
XS GIS Cut Line= 3
      2291843.72      7111358.11      2291473.49      7111204.56
      2290854.17      7110980.52
#Sta/Elev= 30
  4599.2  847.38  4647.6  844.24  4661.7  844.17  4685.6  842.45  4691.0  842.75
  4714.9  841.21  4791.9  838.56  4810.0  837.16  4815.8  837.81  4845.1  837.92
  4853.3  837.71  4863.5  836.24  4868.9  837.25  4875.0  835.45  4946.0  835.48
  4975.3  834.88  4997.2  833.27  4997.4  832.77  5001.2  833.27  5015.4  834.76
  5047.3  835.97  5068.6  835.63  5091.0  836.90  5141.7  836.92  5153.7  835.89
  5208.3  836.89  5289.6  841.83  5412.2  845.73  5554.8  852.02  5658.6  855.14
#Mann=3,-1,0
  4599.2    0.05       0  4997.2   0.035       0  5001.2    0.05       0
Bank Sta=4997.2,5001.2
Exp/Cntr=0.3,0.1

Type RM Length L Ch R = 1,8993,342,342,342
BEGIN DESCRIPTION:
MDW T 025 19.0
END DESCRIPTION:
XS GIS Cut Line= 3
      2291968.62      7111048.49      2291629.16      7110925.06
      2291042.73      7110725.98
#Sta/Elev= 30
  4638.8  844.98  4651.7  845.08  4670.3  843.39  4702.2  842.16  4707.5  842.42
  4723.5  840.94  4744.8  839.96  4763.4  839.91  4768.7  839.36  4787.4  839.61
  4840.6  837.52  4911.1  833.25  4995.4  831.40  4995.7  830.90  4999.2  830.90
  4999.4  831.40  5010.7  831.58  5021.3  832.64  5034.2  832.43  5042.4  833.17
  5065.6  833.75  5091.7  834.06  5097.0  833.42  5159.8  833.95  5342.9  837.67
  5437.1  842.16  5468.5  844.09  5486.0  846.04  5531.2  847.20  5619.3  851.96
#Mann=3,-1,0
  4638.8    0.05       0  4995.4    0.04       0  4999.4    0.05       0
Bank Sta=4995.4,4999.4
Exp/Cntr=0.3,0.1

Type RM Length L Ch R = 1,8651,407,407,407
BEGIN DESCRIPTION:
MDW T 025 18.0
END DESCRIPTION:
XS GIS Cut Line= 3
      2292133.23      7110800.55      2291595.78      7110626.60
      2291149.21      7110532.87
#Sta/Elev= 30
  4435.1  847.49  4454.2  846.72  4513.0  842.96  4597.2  839.88  4670.8  837.82
  4786.4  833.76  4881.0  831.76  4902.0  831.85  4976.8  830.82  4986.1  830.21
  4993.7  828.37  4993.9  827.87  4997.4  827.87  4997.7  828.37  5000.0  828.37
  5004.8  830.78  5027.4  830.46  5037.6  829.83  5054.7  830.15  5078.5  829.55
  5129.5  831.56  5154.5  831.81  5199.2  833.67  5211.3  833.70  5249.1  836.07
  5333.9  839.93  5354.3  841.59  5425.9  845.57  5443.6  847.10  5456.3  847.37
#Mann=3,-1,0
  4435.1    0.05       0  4993.7   0.033       0  4997.7    0.05       0
Bank Sta=4993.7,4997.7
Exp/Cntr=0.3,0.1

Type RM Length L Ch R = 1,8244,190,190,190
BEGIN DESCRIPTION:
MDW T 025 17.0
END DESCRIPTION:
XS GIS Cut Line= 3
      2292293.40      7110454.20      2291584.65      7110257.68
      2291152.76      7110131.66
#Sta/Elev= 30
  4264.5  849.80  4370.7  844.42  4404.0  843.09  4424.7  843.00  4435.1  842.25
  4444.5  840.75  4466.2  839.40  4580.4  834.52  4653.0  830.52  4715.5  828.55
  4736.0  829.56  4749.8  831.80  4767.2  831.82  4777.6  830.81  4784.1  828.20
  4796.3  826.31  4796.6  825.81  4800.1  825.81  4800.3  826.31  4936.8  827.10
  5010.3  826.40  5016.3  826.78  5026.7  829.36  5149.4  832.91  5154.6  832.53
  5365.9  842.86  5404.6  843.57  5432.9  845.30  5438.1  845.05  5449.9  847.44
#Mann=3,-1,0
  4264.5    0.05       0  4796.3    0.04       0  4800.3    0.05       0
Bank Sta=4796.3,4800.3
Exp/Cntr=0.3,0.1

Type RM Length L Ch R = 1,8054,212,212,212
BEGIN DESCRIPTION:
Mapping XS 09f16c95
END DESCRIPTION:
XS GIS Cut Line= 3
      2292042.66      7110271.43      2291853.51      7110140.99
      2291370.33      7110024.86
#Sta/Elev= 30
  4589.5  835.28  4621.4  834.30  4672.1  831.80  4687.0  830.57  4722.8  828.82
  4779.6  827.65  4819.0  825.64  4865.0  825.35  4882.1  824.50  4882.3  824.00
  4885.8  824.00  4886.1  824.50  4889.2  824.98  4906.2  824.91  4916.5  825.68
  4931.2  825.59  4967.9  826.64  4988.5  826.46  5039.9  827.53  5070.7  827.36
  5104.2  827.76  5163.3  828.89  5183.0  829.61  5188.1  829.46  5224.9  831.53
  5255.9  832.06  5272.1  833.10  5277.2  832.83  5314.0  835.00  5316.2  834.87
#Mann=3,-1,0
  4589.5    0.05       0  4882.1   0.033       0  4886.1    0.05       0
Bank Sta=4882.1,4886.1
Exp/Cntr=0.3,0.1

Type RM Length L Ch R = 1,7842,412,412,412
BEGIN DESCRIPTION:
MDW T 025 16.0
END DESCRIPTION:
XS GIS Cut Line= 3
      2292413.17      7110163.83      2291778.31      7109944.15
      2291133.66      7109915.15
#Sta/Elev= 30
  4328.2  851.00  4351.8  849.92  4357.1  850.26  4445.3  844.61  4507.7  841.49
  4533.5  840.61  4595.9  839.87  4632.3  837.75  4639.5  835.95  4681.8  834.44
  4720.5  832.40  4757.0  831.48  4782.8  830.10  4819.4  828.95  4969.8  824.73
  4988.7  823.59  4993.7  822.62  4993.9  822.12  4997.4  822.12  4997.7  822.62
  4998.7  823.16  5009.3  822.97  5049.4  824.24  5159.5  825.64  5259.6  827.99
  5359.7  831.50  5419.7  834.21  5425.5  834.86  5449.8  835.39  5645.3  843.83
#Mann=3,-1,0
  4328.2    0.05       0  4993.7   0.033       0  4997.7    0.05       0
Bank Sta=4993.7,4997.7
Exp/Cntr=0.3,0.1

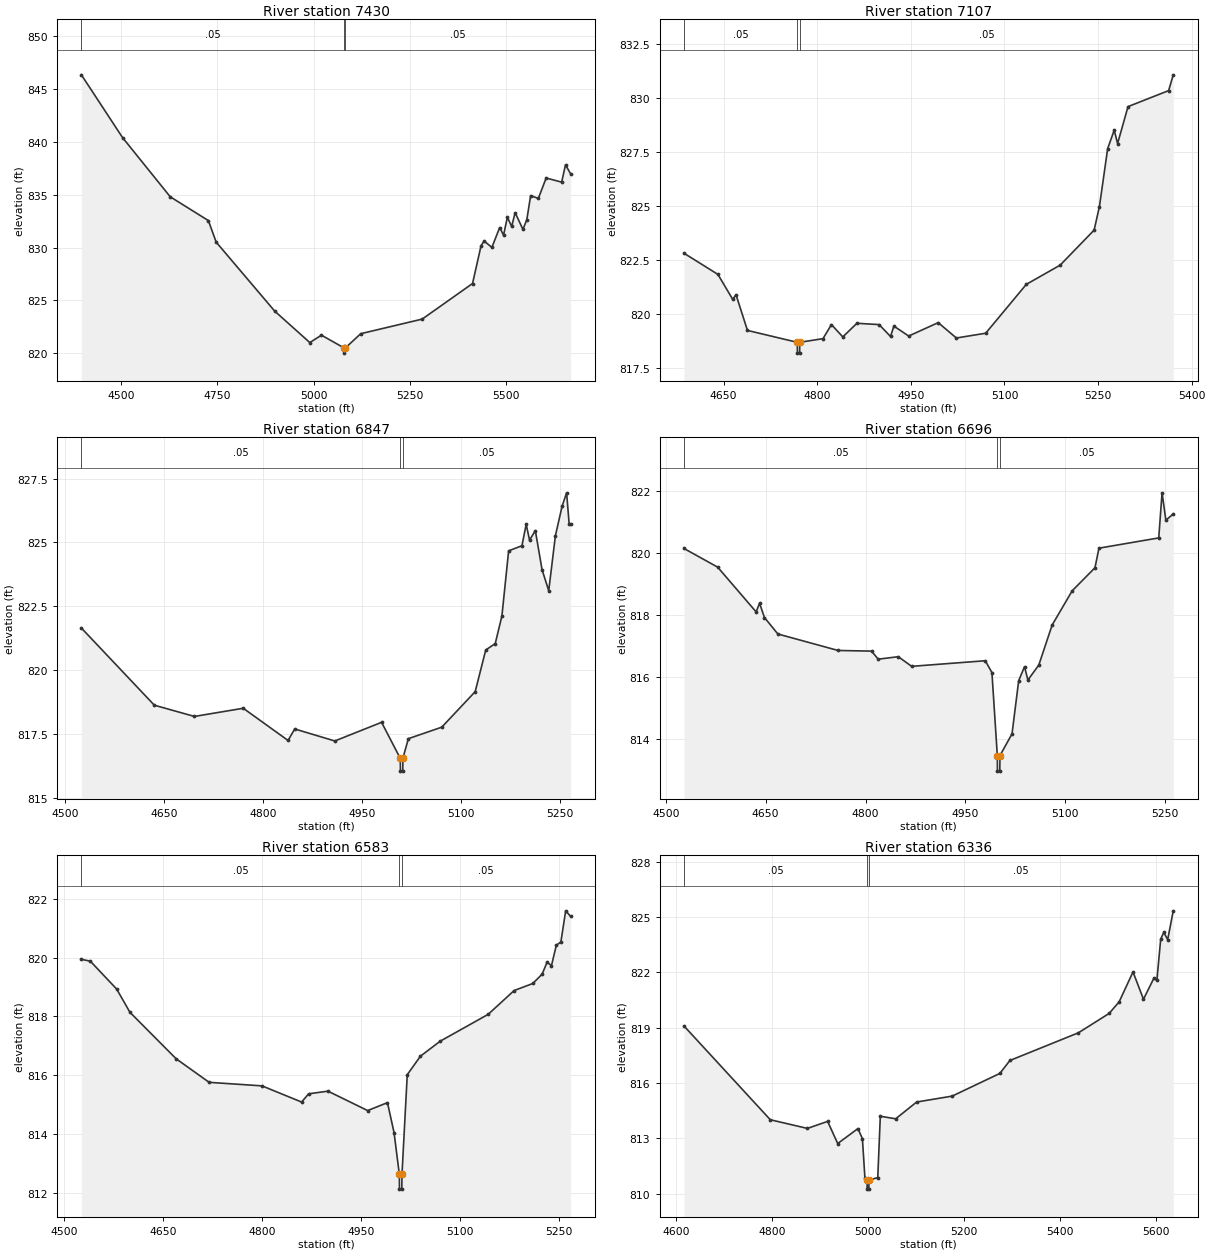
Type RM Length L Ch R = 1,7430,323,323,323
BEGIN DESCRIPTION:
MDW T 025 15.0
END DESCRIPTION:
XS GIS Cut Line= 3
      2292444.47      7109684.67      2291849.43      7109579.83
      2291185.78      7109665.07
#Sta/Elev= 30
  4395.8  846.35  4502.9  840.41  4627.1  834.80  4726.3  832.55  4746.6  830.51
  4898.9  823.98  4990.3  821.00  5020.6  821.70  5079.1  820.50  5079.3  820.00
  5083.1  820.50  5122.8  821.84  5282.7  823.22  5413.8  826.59  5436.0  830.17
  5444.0  830.61  5464.2  830.01  5484.4  831.89  5494.5  831.17  5504.5  832.87
  5515.6  831.99  5524.7  833.30  5544.9  831.72  5555.0  832.62  5565.0  834.91
  5585.1  834.65  5605.4  836.58  5645.7  836.19  5655.8  837.83  5669.1  836.97
#Mann=3,-1,0
  4395.8    0.05       0  5079.1    0.04       0  5083.1    0.05       0
Bank Sta=5079.1,5083.1
Exp/Cntr=0.3,0.1

Type RM Length L Ch R = 1,7107,260,260,260
BEGIN DESCRIPTION:
Mapping XS cf14a1ce
END DESCRIPTION:
XS GIS Cut Line= 2
      2292044.06      7109183.79      2291322.22      7109489.99
#Sta/Elev= 30
  4586.4  822.83  4640.8  821.85  4664.4  820.70  4669.8  820.91  4688.1  819.26
  4767.9  818.71  4768.2  818.21  4771.7  818.21  4771.9  818.71  4809.2  818.88
  4822.7  819.53  4840.9  818.96  4863.5  819.59  4899.1  819.53  4917.4  818.98
  4922.8  819.46  4946.5  819.00  4993.8  819.62  5022.9  818.91  5069.9  819.13
  5135.0  821.39  5189.3  822.28  5243.7  823.90  5252.2  824.99  5265.4  827.67
  5275.9  828.52  5281.3  827.90  5298.0  829.61  5363.1  830.35  5370.5  831.08
#Mann=3,-1,0
  4586.4    0.05       0  4767.9    0.04       0  4771.9    0.05       0
Bank Sta=4767.9,4771.9
Exp/Cntr=0.3,0.1

Type RM Length L Ch R = 1,6847,151,151,151
BEGIN DESCRIPTION:
Mapping XS f012eacc
END DESCRIPTION:
XS GIS Cut Line= 2
      2292048.13      7109035.56      2291316.22      7109155.71
#Sta/Elev= 30
  4524.5  821.65  4635.1  818.63  4695.9  818.19  4769.9  818.51  4837.8  817.25
  4847.9  817.70  4908.7  817.23  4979.6  817.96  5007.9  816.55  5008.2  816.05
  5011.7  816.05  5011.9  816.55  5020.2  817.32  5070.8  817.77  5121.5  819.16
  5137.5  820.79  5151.9  821.04  5162.0  822.12  5172.2  824.67  5192.4  824.87
  5198.8  825.71  5203.9  825.09  5212.7  825.46  5222.9  823.93  5233.0  823.11
  5243.1  825.26  5253.3  826.42  5260.1  826.94  5264.0  825.71  5266.2  825.71
#Mann=3,-1,0
  4524.5    0.05       0  5007.9    0.04       0  5011.9    0.05       0
Bank Sta=5007.9,5011.9
Exp/Cntr=0.3,0.1

Type RM Length L Ch R = 1,6696,113,113,113
BEGIN DESCRIPTION:
Mapping XS ccff403e
END DESCRIPTION:
XS GIS Cut Line= 2
      2292049.35      7108914.02      2291317.95      7108986.72
#Sta/Elev= 30
  4527.3  820.14  4577.9  819.54  4635.7  818.10  4640.8  818.38  4648.2  817.92
  4668.3  817.39  4758.8  816.86  4809.0  816.84  4819.1  816.58  4849.2  816.66
  4869.3  816.35  4979.9  816.53  4989.9  816.15  4998.0  813.48  4998.2  812.98
  5001.7  812.98  5002.0  813.48  5020.1  814.18  5030.1  815.89  5038.9  816.34
  5043.9  815.91  5060.3  816.39  5080.4  817.68  5110.5  818.78  5144.7  819.52
  5150.7  820.15  5240.5  820.48  5245.5  821.93  5251.2  821.05  5262.3  821.25
#Mann=3,-1,0
  4527.3    0.05       0  4998.0    0.04       0  5002.0    0.05       0
Bank Sta=4998,5002
Exp/Cntr=0.3,0.1

Type RM Length L Ch R = 1,6583,247,247,247
BEGIN DESCRIPTION:
Mapping XS 8c327dcd
END DESCRIPTION:
XS GIS Cut Line= 3
      2292052.53      7108836.97      2291436.52      7108851.53
      2291350.84      7108942.56
#Sta/Elev= 30
  4525.9  819.94  4539.4  819.88  4579.4  818.93  4599.5  818.14  4669.5  816.56
  4719.5  815.76  4799.5  815.64  4859.5  815.09  4870.2  815.37  4899.5  815.46
  4959.6  814.80  4989.6  815.07  4999.6  814.05  5007.6  812.63  5007.8  812.13
  5011.3  812.13  5011.6  812.63  5019.6  816.02  5039.6  816.65  5069.6  817.16
  5142.1  818.07  5181.5  818.88  5209.8  819.12  5224.0  819.44  5231.3  819.84
  5238.1  819.73  5245.4  820.42  5252.3  820.53  5259.6  821.59  5267.1  821.40
#Mann=3,-1,0
  4525.9    0.05       0  5007.6    0.04       0  5011.6    0.05       0
Bank Sta=5007.6,5011.6
Exp/Cntr=0.3,0.1

Type RM Length L Ch R = 1,6336,319,319,319
BEGIN DESCRIPTION:
Mapping XS 611ad294
END DESCRIPTION:
XS GIS Cut Line= 3
      2292043.47      7108750.90      2291581.17      7108600.97
      2291250.35      7109018.62
#Sta/Elev= 30
  4617.2  819.09  4796.9  814.01  4874.2  813.54  4916.3  813.92  4937.3  812.72
  4979.3  813.53  4988.7  812.99  4994.0  810.84  4998.4  810.75  4998.6  810.25
  5002.1  810.25  5002.4  810.75  5020.7  810.87  5026.0  814.20  5057.9  814.06
  5101.7  814.97  5175.6  815.29  5275.0  816.52  5295.8  817.22  5438.4  818.72
  5502.5  819.77  5523.4  820.40  5552.2  822.02  5574.0  820.54  5595.5  821.67
  5601.9  821.57  5609.9  823.80  5616.3  824.16  5624.4  823.77  5636.0  825.33
#Mann=3,-1,0
  4617.2    0.05       0  4998.4    0.04       0  5002.4    0.05       0
Bank Sta=4998.4,5002.4
Exp/Cntr=0.3,0.1

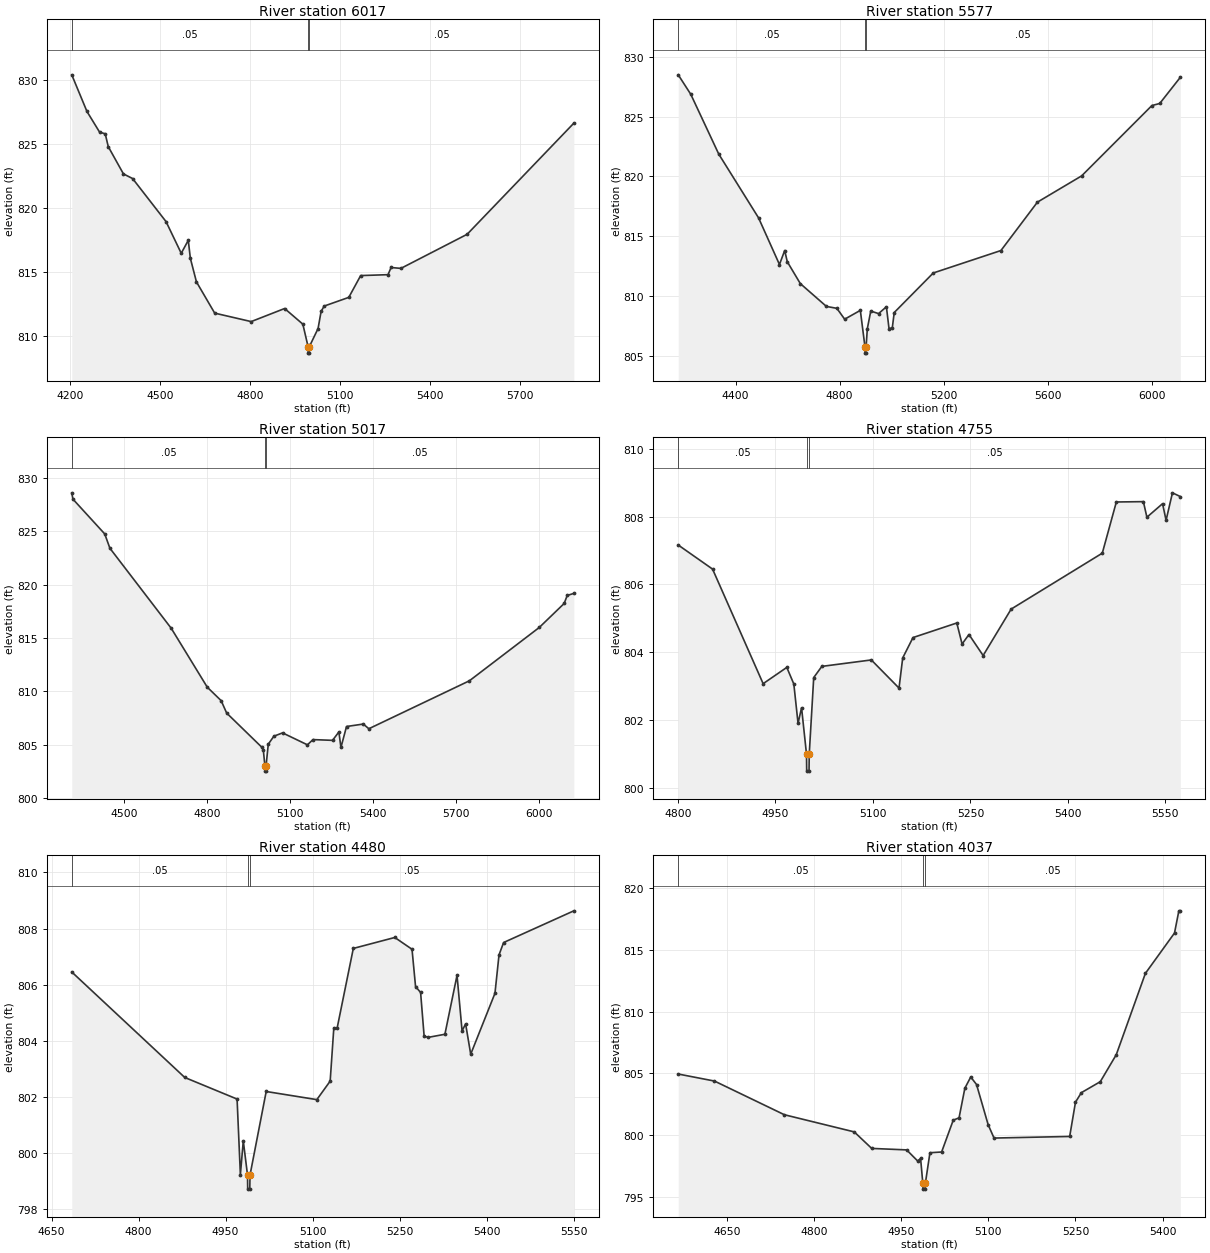
Type RM Length L Ch R = 1,6017,440,440,440
BEGIN DESCRIPTION:
MDW T 025 12.0
END DESCRIPTION:
XS GIS Cut Line= 3
      2292478.99      7108510.00      2291695.58      7108376.51
      2290828.31      7108225.57
#Sta/Elev= 30
  4205.3  830.37  4256.0  827.51  4298.1  825.90  4316.9  825.77  4327.0  824.77
  4377.7  822.64  4408.2  822.28  4519.8  818.92  4570.5  816.45  4594.0  817.46
  4600.9  816.06  4621.2  814.22  4682.1  811.78  4803.8  811.12  4915.4  812.14
  4976.2  810.92  4993.7  809.16  4994.0  808.66  4997.5  808.66  4997.8  809.16
  5027.0  810.58  5037.1  811.91  5047.3  812.33  5129.5  813.01  5169.1  814.71
  5260.4  814.78  5270.6  815.34  5303.3  815.27  5524.3  817.93  5880.3  826.60
#Mann=3,-1,0
  4205.3    0.05       0  4993.7    0.04       0  4997.8    0.05       0
Bank Sta=4993.7,4997.8
Exp/Cntr=0.3,0.1

Type RM Length L Ch R = 1,5577,560,560,560
BEGIN DESCRIPTION:
MDW T 025 11.0
END DESCRIPTION:
XS GIS Cut Line= 3
      2292547.05      7107933.91      2291728.97      7107991.41
      2290619.95      7107962.55
#Sta/Elev= 30
  4179.9  828.50  4228.1  826.87  4335.7  821.86  4488.7  816.52  4568.9  812.62
  4589.0  813.79  4599.0  812.85  4649.1  811.02  4749.4  809.11  4789.5  808.95
  4819.5  808.04  4879.7  808.78  4897.7  805.70  4898.0  805.20  4901.5  805.20
  4901.8  805.70  4906.6  807.25  4919.8  808.72  4949.8  808.51  4979.9  809.08
  4989.9  807.26  5002.5  807.31  5010.0  808.60  5160.0  811.91  5420.1  813.79
  5560.2  817.84  5730.2  820.04  6000.3  825.93  6030.3  826.10  6109.4  828.29
#Mann=3,-1,0
  4179.9    0.05       0  4897.7    0.04       0  4901.8    0.05       0
Bank Sta=4897.7,4901.8
Exp/Cntr=0.3,0.1

Type RM Length L Ch R = 1,5017,262,262,262
BEGIN DESCRIPTION:
MDW T 025 10.0
END DESCRIPTION:
XS GIS Cut Line= 3
      2292617.99      7107484.69      2291929.42      7107535.00
      2290815.31      7107699.53
#Sta/Elev= 30
  4309.6  828.63  4313.7  828.04  4428.9  824.77  4447.5  823.43  4669.5  815.91
  4799.9  810.38  4850.0  809.12  4870.1  807.95  4997.7  804.73  5002.7  804.48
  5008.4  803.00  5008.7  802.50  5012.3  802.50  5012.6  803.00  5020.6  805.03
  5040.9  805.78  5072.3  806.09  5162.2  804.97  5182.4  805.46  5253.1  805.39
  5276.1  806.18  5283.5  804.72  5303.7  806.69  5364.3  806.92  5384.5  806.48
  5748.2  810.98  6001.2  815.99  6091.1  818.24  6102.2  818.99  6126.2  819.19
#Mann=3,-1,0
  4309.6    0.05       0  5008.4   0.033       0  5012.6    0.05       0
Bank Sta=5008.4,5012.6
Exp/Cntr=0.3,0.1

Type RM Length L Ch R = 1,4755,275,275,275
BEGIN DESCRIPTION:
Mapping XS 344a14e2
END DESCRIPTION:
XS GIS Cut Line= 2
      2292013.85      7107235.55      2291297.77      7107524.83
#Sta/Elev= 30
  4800.6  807.16  4853.4  806.45  4931.2  803.07  4967.6  803.55  4978.4  803.06
  4984.9  801.90  4990.3  802.36  4997.9  800.99  4998.2  800.49  5001.8  800.49
  5002.1  800.99  5009.0  803.25  5021.5  803.58  5097.6  803.77  5140.2  802.94
  5145.9  803.83  5161.7  804.43  5229.1  804.86  5237.2  804.24  5247.8  804.52
  5269.6  803.90  5312.7  805.27  5452.9  806.92  5474.5  808.43  5516.1  808.44
  5521.5  807.98  5545.6  808.38  5551.0  807.89  5560.8  808.70  5572.9  808.59
#Mann=3,-1,0
  4800.6    0.05       0  4997.9   0.033       0  5002.1    0.05       0
Bank Sta=4997.9,5002.1
Exp/Cntr=0.3,0.1

Type RM Length L Ch R = 1,4480,443,443,443
BEGIN DESCRIPTION:
Mapping XS 7d22206e
END DESCRIPTION:
XS GIS Cut Line= 3
      2292043.24      7107043.13      2291591.50      7107077.14
      2291253.23      7107313.35
#Sta/Elev= 30
  4684.9  806.45  4879.7  802.69  4969.9  801.92  4975.6  799.23  4980.6  800.43
  4987.9  799.21  4988.2  798.71  4991.8  798.71  4992.2  799.21  5020.1  802.19
  5107.4  801.90  5130.4  802.56  5136.7  804.46  5142.5  804.46  5170.3  807.29
  5241.8  807.68  5271.5  807.26  5277.6  805.93  5286.3  805.72  5292.4  804.16
  5299.5  804.12  5328.2  804.23  5349.1  806.33  5357.8  804.35  5363.9  804.60
  5372.7  803.52  5414.5  805.69  5421.5  807.06  5429.4  807.50  5550.5  808.63
#Mann=3,-1,0
  4684.9    0.05       0  4987.9    0.04       0  4992.2    0.05       0
Bank Sta=4987.9,4992.2
Exp/Cntr=0.3,0.1

Type RM Length L Ch R = 1,4037,355,355,355
BEGIN DESCRIPTION:
Mapping XS cfe40192
END DESCRIPTION:
XS GIS Cut Line= 2
      2292061.30      7106732.01      2291199.03      7106675.90
#Sta/Elev= 30
  4566.4  804.95  4628.8  804.38  4749.1  801.65  4869.3  800.26  4899.4  798.92
  4959.5  798.80  4978.5  797.90  4983.5  798.11  4987.3  796.12  4987.8  795.62
  4991.4  795.62  4991.8  796.12  4999.6  798.57  5019.7  798.63  5039.7  801.21
  5049.7  801.40  5059.7  803.80  5069.8  804.71  5079.8  804.10  5099.8  800.84
  5109.9  799.76  5240.1  799.89  5250.1  802.67  5260.2  803.44  5292.8  804.33
  5320.3  806.52  5370.4  813.11  5420.5  816.38  5428.0  818.18  5430.5  818.18
#Mann=3,-1,0
  4566.4    0.05       0  4987.3   0.033       0  4991.8    0.05       0
Bank Sta=4987.3,4991.8
Exp/Cntr=0.3,0.1

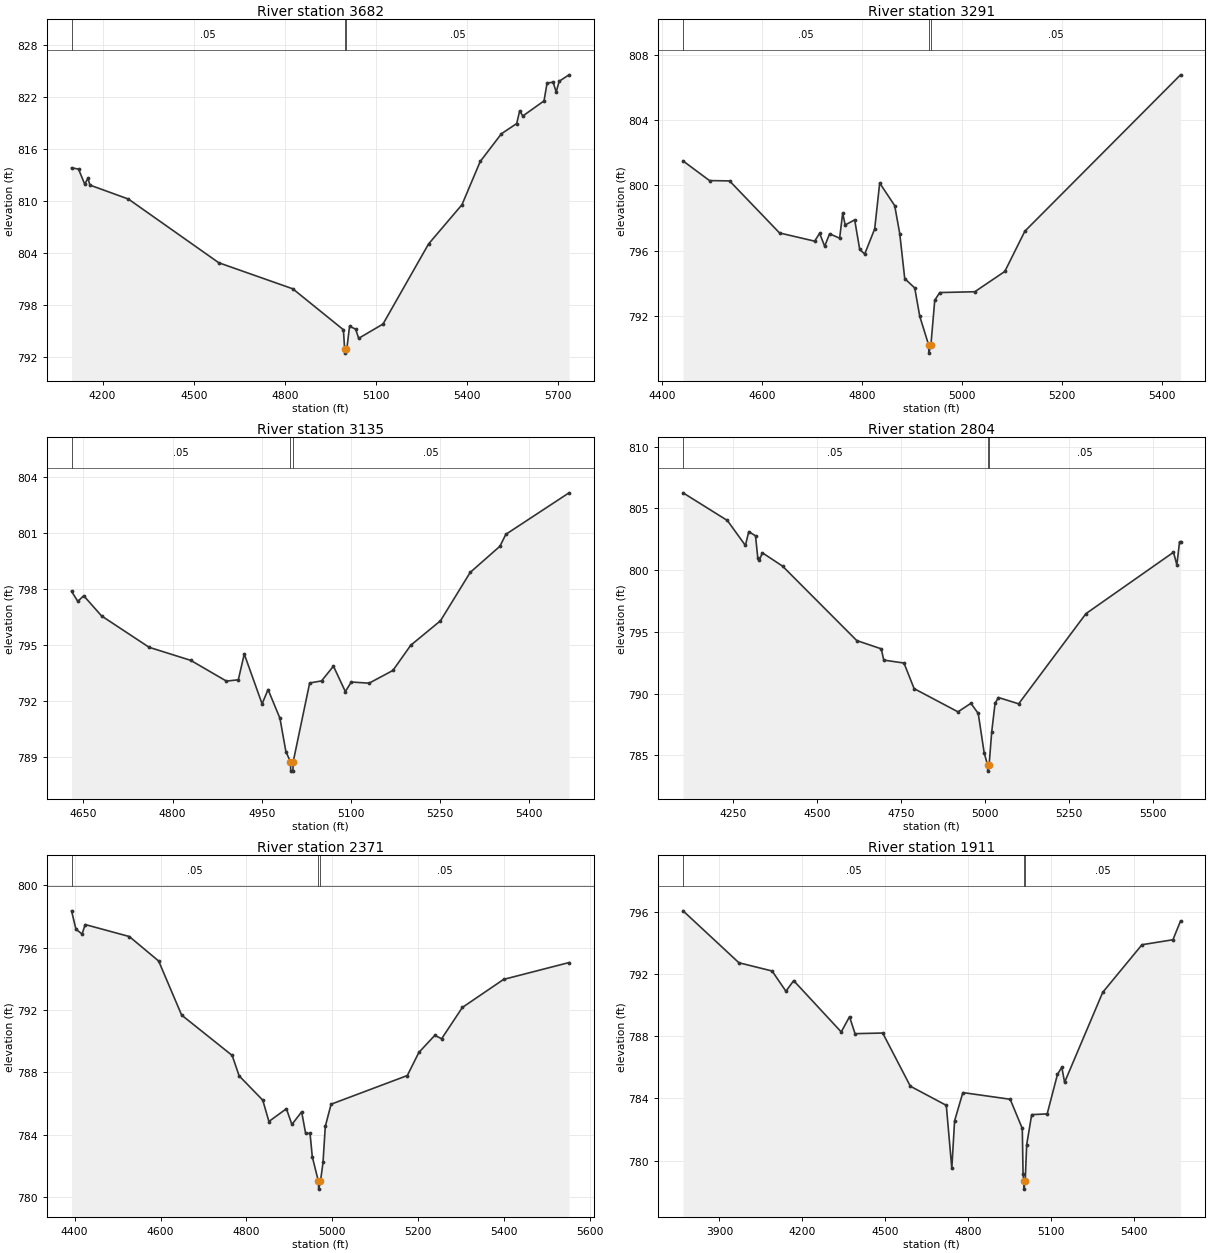
Type RM Length L Ch R = 1,3682,391,391,391
BEGIN DESCRIPTION:
MDW T 025 7.0
END DESCRIPTION:
XS GIS Cut Line= 3
      2292591.40      7106579.03      2291712.11      7106376.57
      2290976.73      7106398.46
#Sta/Elev= 30
  4097.7  813.86  4120.7  813.71  4141.2  811.96  4151.5  812.66  4158.4  811.86
  4284.9  810.25  4582.5  802.89  4826.2  799.88  4992.9  795.15  4996.8  792.95
  4997.2  792.45  5001.3  792.95  5004.1  792.95  5013.1  795.56  5033.1  795.22
  5043.1  794.16  5123.2  795.81  5273.2  805.06  5383.3  809.60  5443.3  814.59
  5513.3  817.80  5563.4  818.97  5573.4  820.46  5583.4  819.84  5653.4  821.59
  5663.4  823.65  5683.4  823.75  5693.4  822.62  5703.4  823.86  5735.7  824.60
#Mann=3,-1,0
  4097.7    0.05       0  4996.8   0.033       0  5001.3    0.05       0
Bank Sta=4996.8,5001.3
Exp/Cntr=0.3,0.1

Type RM Length L Ch R = 1,3291,156,156,156
BEGIN DESCRIPTION:
Mapping XS 923df5d4
END DESCRIPTION:
XS GIS Cut Line= 2
      2292301.88      7105971.78      2291307.93      7106012.86
#Sta/Elev= 30
  4441.7  801.50  4494.6  800.30  4534.7  800.28  4634.7  797.10  4704.8  796.60
  4714.8  797.08  4724.8  796.29  4734.8  797.05  4754.8  796.78  4760.9  798.31
  4765.9  797.59  4784.9  797.90  4794.9  796.10  4804.9  795.81  4824.9  797.35
  4834.9  800.15  4864.9  798.77  4875.0  797.06  4885.0  794.31  4905.0  793.74
  4915.0  792.01  4932.8  790.26  4933.2  789.76  4937.3  790.26  4945.0  792.99
  4955.0  793.46  5025.1  793.51  5085.1  794.75  5125.2  797.21  5436.5  806.76
#Mann=3,-1,0
  4441.7    0.05       0  4932.8    0.05       0  4937.3    0.05       0
Bank Sta=4932.8,4937.3
Exp/Cntr=0.3,0.1

Type RM Length L Ch R = 1,3135,331,331,331
BEGIN DESCRIPTION:
Mapping XS b6189951
END DESCRIPTION:
XS GIS Cut Line= 2
      2292199.48      7105870.18      2291362.79      7105872.92
#Sta/Elev= 30
  4630.0  797.89  4640.5  797.35  4650.5  797.65  4680.5  796.57  4760.5  794.89
  4830.5  794.19  4890.5  793.08  4910.5  793.15  4920.5  794.53  4950.5  791.86
  4960.5  792.63  4980.5  791.09  4990.5  789.31  4998.2  788.76  4998.7  788.26
  5002.3  788.26  5002.8  788.76  5030.5  792.98  5050.5  793.09  5070.5  793.88
  5090.5  792.52  5100.5  793.03  5130.5  792.97  5170.5  793.65  5200.5  795.00
  5250.5  796.31  5300.5  798.90  5350.5  800.30  5360.5  800.94  5466.7  803.16
#Mann=3,-1,0
  4630.0    0.05       0  4998.2   0.033       0  5002.8    0.05       0
Bank Sta=4998.2,5002.8
Exp/Cntr=0.3,0.1

Type RM Length L Ch R = 1,2804,433,433,433
BEGIN DESCRIPTION:
MDW T 025 5.0
END DESCRIPTION:
XS GIS Cut Line= 3
      2292723.73      7105639.70      2291828.98      7105540.75
      2291248.06      7105591.09
#Sta/Elev= 30
  4099.8  806.26  4231.9  804.02  4285.7  802.00  4295.7  803.12  4315.8  802.78
  4322.7  800.97  4327.7  800.81  4336.0  801.41  4396.3  800.33  4617.7  794.30
  4690.8  793.63  4698.2  792.72  4758.5  792.48  4788.7  790.41  4919.5  788.53
  4958.0  789.22  4979.9  788.40  4997.5  785.23  5007.7  784.23  5008.2  783.73
  5012.3  784.23  5020.1  786.91  5030.1  789.22  5040.1  789.69  5100.4  789.18
  5301.1  796.48  5562.1  801.45  5572.1  800.43  5580.1  802.29  5583.1  802.29
#Mann=3,-1,0
  4099.8    0.05       0  5007.7   0.033       0  5012.3    0.05       0
Bank Sta=5007.7,5012.3
Exp/Cntr=0.3,0.1

Type RM Length L Ch R = 1,2371,460,460,460
BEGIN DESCRIPTION:
MDW T 025 4.0
END DESCRIPTION:
XS GIS Cut Line= 3
      2292498.61      7105373.04      2291933.35      7105159.23
      2291406.87      7104988.88
#Sta/Elev= 30
  4392.9  798.37  4403.2  797.19  4417.4  796.88  4424.6  797.49  4527.4  796.72
  4595.6  795.15  4649.1  791.68  4766.7  789.09  4782.9  787.78  4837.9  786.22
  4852.2  784.85  4892.9  785.67  4905.7  784.66  4928.4  785.47  4937.7  784.08
  4947.9  784.09  4953.2  782.58  4967.4  781.01  4968.0  780.51  4972.2  781.01
  4978.1  782.22  4983.4  784.53  4996.9  785.96  5174.3  787.80  5201.1  789.28
  5238.3  790.38  5254.1  790.16  5302.4  792.17  5398.4  793.97  5550.6  795.05
#Mann=3,-1,0
  4392.9    0.05       0  4967.4   0.033       0  4972.2    0.05       0
Bank Sta=4967.4,4972.2
Exp/Cntr=0.3,0.1

Type RM Length L Ch R = 1,1911,237,237,237
BEGIN DESCRIPTION:
MDW T 025 3.0
END DESCRIPTION:
XS GIS Cut Line= 3
      2293101.05      7104800.58      2291874.05      7104753.16
      2291332.98      7104941.10
#Sta/Elev= 30
  3768.5  796.07  3970.7  792.73  4090.8  792.20  4140.8  790.90  4168.9  791.58
  4341.0  788.28  4371.0  789.26  4391.0  788.17  4491.1  788.21  4591.2  784.79
  4721.3  783.56  4741.3  779.50  4751.3  782.56  4781.3  784.38  4952.6  783.95
  4996.4  782.07  4999.2  779.13  5002.1  778.67  5002.7  778.17  5006.9  778.67
  5012.3  781.03  5030.4  782.96  5086.5  783.01  5123.7  785.55  5139.4  786.01
  5149.5  785.04  5287.6  790.83  5429.6  793.89  5541.7  794.21  5569.2  795.42
#Mann=3,-1,0
  3768.5    0.05       0  5002.1    0.04       0  5006.9    0.05       0
Bank Sta=5002.1,5006.9
Exp/Cntr=0.3,0.1

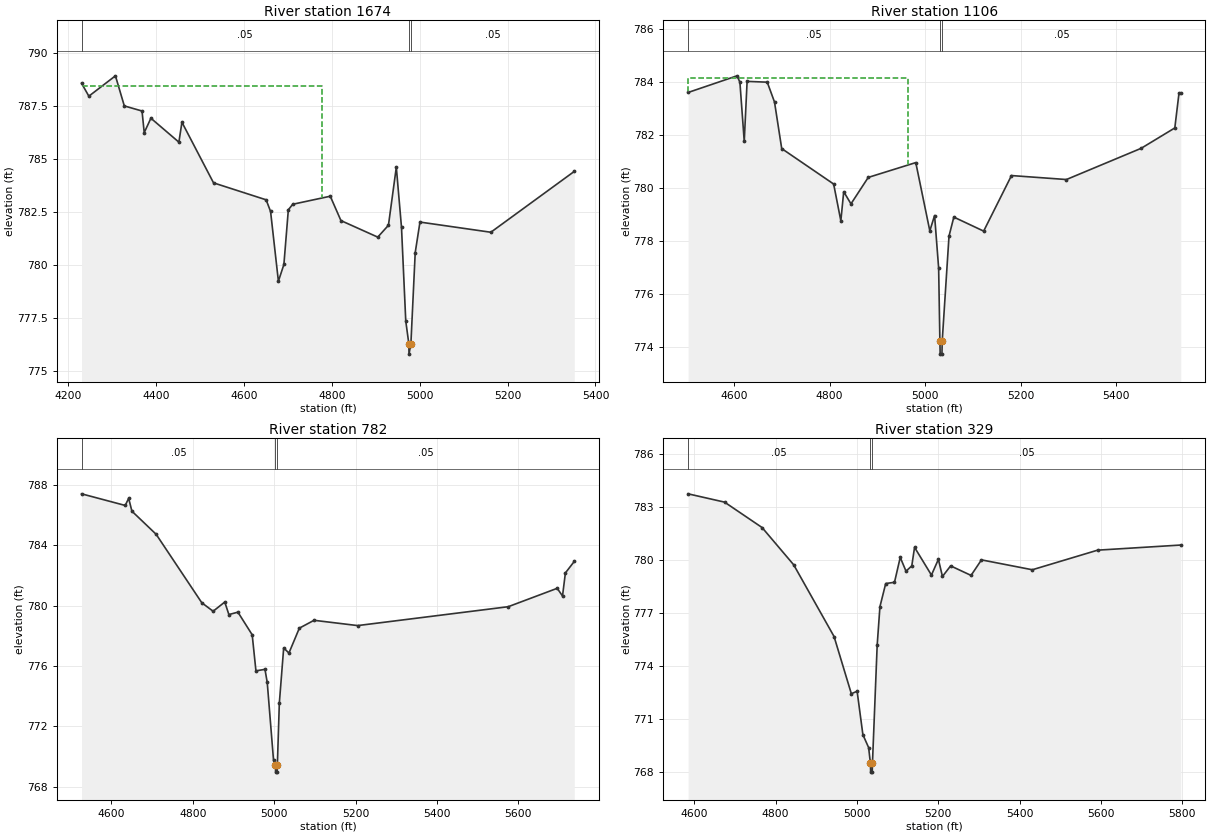
Type RM Length L Ch R = 1,1674,568,568,568
BEGIN DESCRIPTION:
Mapping XS 6049f9b3
END DESCRIPTION:
XS GIS Cut Line= 3
      2292595.48      7104703.50      2292104.80      7104639.26
      2291522.57      7104408.66
#Sta/Elev= 30
  4230.6  788.56  4247.2  787.95  4307.7  788.91  4327.9  787.49  4368.2  787.25
  4373.2  786.23  4388.4  786.91  4452.1  785.78  4459.0  786.72  4530.9  783.86
  4650.6  783.06  4660.7  782.51  4678.5  779.22  4691.0  780.01  4701.1  782.59
  4711.1  782.85  4796.5  783.23  4820.8  782.08  4904.6  781.30  4928.9  781.86
  4946.8  784.60  4958.6  781.76  4968.3  777.34  4975.2  776.28  4975.7  775.78
  4980.0  776.28  4989.8  780.57  5000.6  782.01  5161.9  781.53  5351.7  784.40
#Mann=3,-1,0
  4230.6    0.05       0  4975.2   0.033       0  4980.0    0.05       0
#XS Ineff=2,0
    0.00 4777.60  788.44               0
Permanent Ineff=
       F       F
Bank Sta=4975.2,4980
Exp/Cntr=0.3,0.1

Type RM Length L Ch R = 1,1106,324,324,324
BEGIN DESCRIPTION:
Mapping XS f0d13394
END DESCRIPTION:
XS GIS Cut Line= 3
      2292457.74      7104512.37      2292053.85      7104250.35
      2291506.57      7104187.67
#Sta/Elev= 30
  4503.5  783.61  4606.1  784.24  4612.1  784.00  4621.2  781.76  4627.2  784.03
  4669.4  784.00  4684.6  783.25  4699.7  781.49  4808.5  780.15  4823.6  778.76
  4829.6  779.86  4844.8  779.40  4881.0  780.40  4980.6  780.96  5010.0  778.38
  5020.0  778.96  5028.5  776.97  5031.1  774.22  5031.7  773.72  5035.4  773.72
  5036.0  774.22  5050.2  778.18  5060.3  778.90  5122.8  778.37  5181.1  780.47
  5296.2  780.32  5452.8  781.50  5523.3  782.27  5532.1  783.59  5535.8  783.59
#Mann=3,-1,0
  4503.5    0.05       0  5031.1   0.033       0  5036.0    0.05       0
#XS Ineff=2,0
    0.00 4965.00  784.14               0
Permanent Ineff=
       F       F
Bank Sta=5031.1,5036
Exp/Cntr=0.3,0.1

Type RM Length L Ch R = 1,782,453,453,453
BEGIN DESCRIPTION:
MDW T 025 2.0
END DESCRIPTION:
XS GIS Cut Line= 4
      2292691.96      7104282.74      2292270.92      7104066.12
      2292080.88      7103998.66      2291547.30      7104047.84
#Sta/Elev= 30
  4526.5  787.41  4633.8  786.64  4642.3  787.11  4650.3  786.26  4709.8  784.73
  4822.1  780.19  4849.9  779.63  4878.5  780.24  4888.6  779.41  4910.8  779.57
  4945.9  778.07  4955.1  775.68  4977.3  775.78  4982.9  774.91  4998.3  769.77
  5002.8  769.47  5003.5  768.97  5007.2  768.97  5007.8  769.47  5012.6  773.54
  5023.3  777.20  5036.2  776.86  5061.8  778.51  5097.9  779.03  5205.1  778.68
  5575.1  779.93  5695.6  781.15  5708.6  780.64  5715.7  782.17  5737.5  782.93
#Mann=3,-1,0
  4526.5    0.05       0  5002.8   0.033       0  5007.8    0.05       0
Bank Sta=5002.8,5007.8
Exp/Cntr=0.3,0.1

Type RM Length L Ch R = 1,329,0,0,0
BEGIN DESCRIPTION:
MDW T 025 1.0
END DESCRIPTION:
XS GIS Cut Line= 3
      2292814.79      7104011.22      2292375.42      7103604.25
      2291765.36      7103657.84
#Sta/Elev= 30
  4584.7  783.76  4674.4  783.29  4766.7  781.85  4844.4  779.74  4943.6  775.68
  4986.1  772.44  5000.3  772.58  5014.5  770.12  5028.6  769.39  5033.0  768.50
  5033.6  768.00  5037.4  768.00  5038.0  768.50  5049.6  775.18  5056.4  777.37
  5070.6  778.68  5092.2  778.75  5106.3  780.16  5120.5  779.38  5134.7  779.68
  5141.5  780.73  5183.0  779.16  5200.1  780.05  5210.1  779.08  5230.2  779.68
  5280.4  779.14  5306.0  780.02  5431.0  779.46  5591.6  780.57  5796.0  780.86
#Mann=3,-1,0
  4584.7    0.05       0  5033.0   0.033       0  5038.0    0.05       0
Bank Sta=5033,5038
Exp/Cntr=0.3,0.1

Chan Stop Cuts=-1