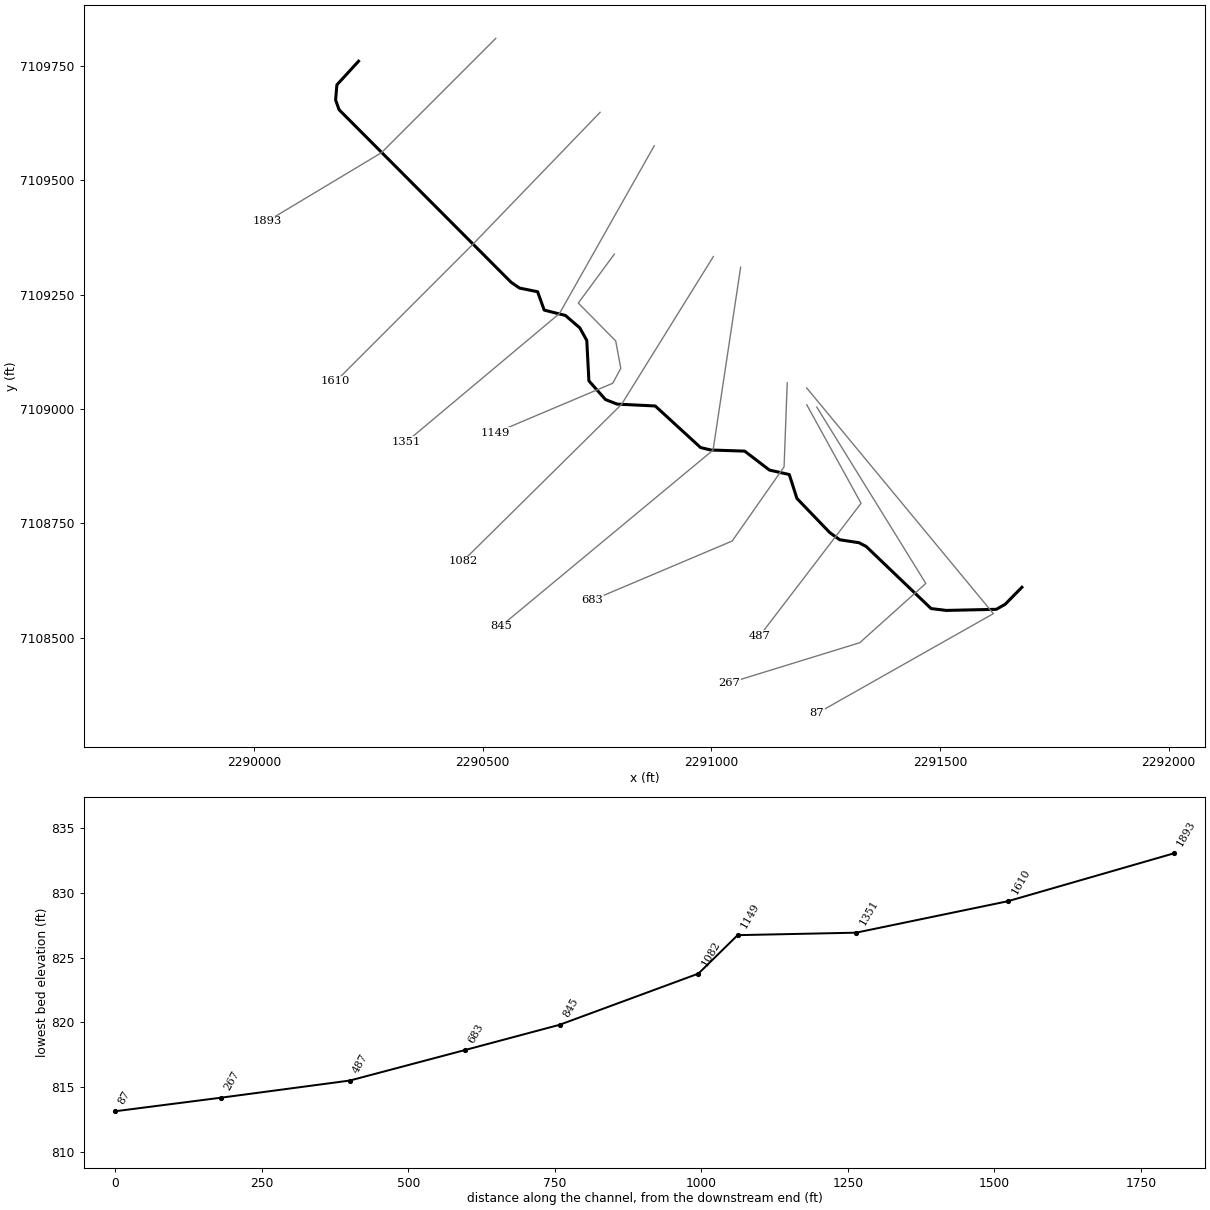
--- MDW T 026.prj (project) ---

Proj Title=MDW T 026 Base Level Engineering
Current Plan=p01
Default Exp/Contr=0.3,0.1
English Units
Geom File=g01
Flow File=f01
Plan File=p01
BEGIN DESCRIPTION:
MDW T 026
END DESCRIPTION:

--- MDW T 026.p01 (plan) ---

Plan Title=Multiple Run
Short Identifier=Multiple
Geom File=g01
Flow File=f01
Subcritical Flow
K Sum by GR= 0
Std Step Tol= 0.01
Critical Tol= 0.01
Num of Std Step Trials= 20
Max Error Tol= 0.3
Flow Tol Ratio= 0.001
Split Flow NTrial= 30
Split Flow Tol= 0.02
Split Flow Ratio= 0.02
Log Output Level= 0
Friction Slope Method= 1
Unsteady Friction Slope Method= 2
Unsteady Bridges Friction Slope Method= 1
Parabolic Critical Depth
Global Vel Dist=  1 , 1 , 1
Global Log Level= 0
CheckData=True
Encroach Param= -1, 0, 0, 0
BEGIN DESCRIPTION:
Multiple Run
END DESCRIPTION:

--- MDW T 026.f01 (steady flow) ---

Flow Title=Multiple
Number of Profiles=7
Profile Names=10-year,25-year,50-year,1pct_min,100-year,1pct_plu,500-year
River Rch & RM= MDW T 026,Reach-1,1893
     187     238     278     162     323     645     436
Boundary for River Rch & Prof#=MDW T 026,Reach-1,1
Up Type=0
Dn Type=3
Dn Slope=0.005
Boundary for River Rch & Prof#=MDW T 026,Reach-1,2
Up Type=0
Dn Type=3
Dn Slope=0.005
Boundary for River Rch & Prof#=MDW T 026,Reach-1,3
Up Type=0
Dn Type=3
Dn Slope=0.005
Boundary for River Rch & Prof#=MDW T 026,Reach-1,4
Up Type=0
Dn Type=3
Dn Slope=0.005
Boundary for River Rch & Prof#=MDW T 026,Reach-1,5
Up Type=0
Dn Type=3
Dn Slope=0.005
Boundary for River Rch & Prof#=MDW T 026,Reach-1,6
Up Type=0
Dn Type=3
Dn Slope=0.005
Boundary for River Rch & Prof#=MDW T 026,Reach-1,7
Up Type=0
Dn Type=3
Dn Slope=0.005

--- MDW T 026.g01 (geometry) ---

Geom Title=Existing Conditions

River Reach=MDW T 026,Reach-1
Reach XY= 30
      2290229.00      7109760.00      2290181.67      7109708.38
      2290178.81      7109675.26      2290186.47      7109653.91
      2290562.51      7109276.71      2290580.98      7109264.05
      2290620.37      7109256.12      2290634.80      7109216.00
      2290681.26      7109204.18      2290712.62      7109177.10
      2290727.88      7109149.66      2290732.51      7109061.26
      2290768.84      7109020.36      2290794.08      7109010.47
      2290877.49      7109006.37      2290976.58      7108915.54
      2290999.05      7108910.13      2291073.06      7108907.68
      2291127.16      7108866.28      2291170.52      7108856.49
      2291187.28      7108804.23      2291258.87      7108729.78
      2291280.64      7108713.97      2291322.95      7108707.46
      2291338.68      7108699.22      2291480.47      7108563.53
      2291513.81      7108559.47      2291623.21      7108561.88
      2291642.50      7108572.91      2291679.00      7108610.00

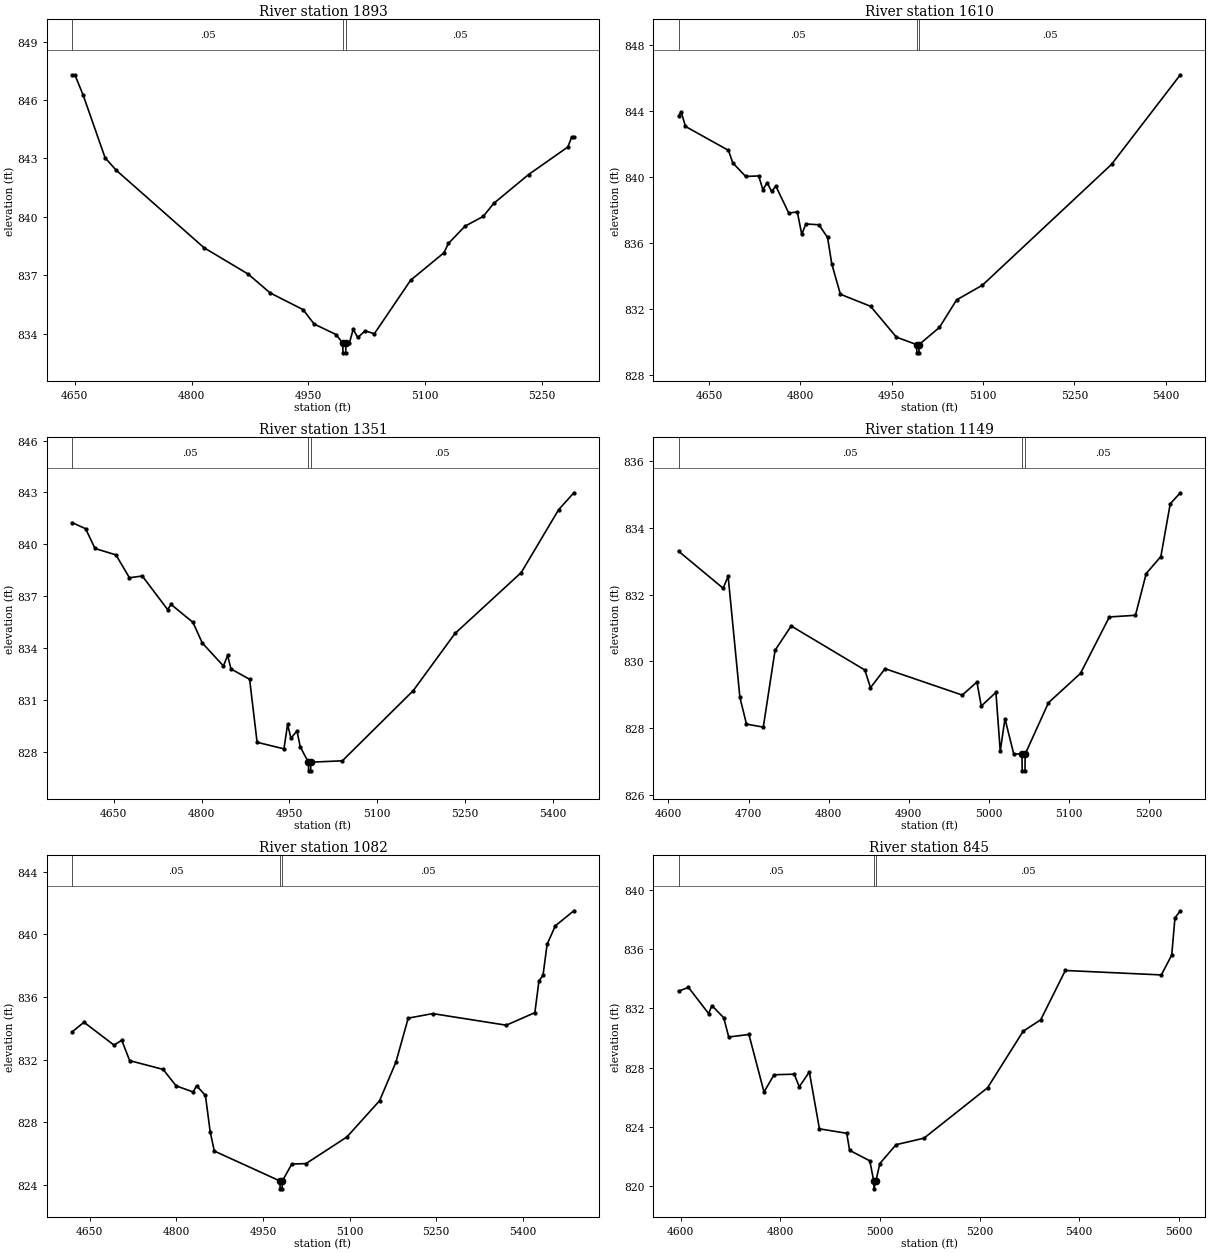
Type RM Length L Ch R = 1,1893,283,283,283
BEGIN DESCRIPTION:
MDW T 026 5.0
END DESCRIPTION:
XS GIS Cut Line= 3
      2290529.02      7109810.02      2290279.00      7109560.00
      2290029.02      7109410.01
#Sta/Elev= 30
  4646.4  847.30  4650.0  847.30  4660.6  846.26  4688.9  843.03  4703.0  842.40
  4816.1  838.41  4872.7  837.06  4901.0  836.09  4943.4  835.23  4957.6  834.49
  4985.8  833.95  4994.4  833.51  4994.7  833.01  4998.2  833.01  4998.4  833.51
  5002.9  833.51  5007.8  834.22  5013.6  833.80  5023.3  834.14  5035.0  833.99
  5081.6  836.74  5124.4  838.15  5130.2  838.63  5151.6  839.52  5174.9  840.02
  5188.5  840.69  5233.2  842.17  5283.8  843.59  5288.6  844.09  5291.5  844.09
#Mann=3,-1,0
  4646.4    0.05       0  4994.4    0.04       0  4998.4    0.05       0
Bank Sta=4994.4,4998.4
Exp/Cntr=0.3,0.1

Type RM Length L Ch R = 1,1610,259,259,259
BEGIN DESCRIPTION:
MDW T 026 4.0
END DESCRIPTION:
XS GIS Cut Line= 3
      2290756.93      7109648.21      2290479.00      7109360.00
      2290179.03      7109060.03
#Sta/Elev= 30
  4599.6  843.68  4603.9  843.94  4611.0  843.05  4681.6  841.60  4688.8  840.84
  4709.9  840.02  4731.3  840.05  4738.2  839.22  4745.4  839.64  4752.4  839.11
  4759.6  839.43  4780.7  837.80  4794.8  837.87  4802.0  836.52  4809.0  837.14
  4830.3  837.09  4844.5  836.32  4851.4  834.72  4865.6  832.88  4915.2  832.15
  4957.7  830.28  4990.9  829.83  4991.2  829.33  4994.7  829.33  4994.9  829.83
  5028.3  830.87  5056.6  832.54  5099.0  833.43  5311.1  840.75  5424.2  846.18
#Mann=3,-1,0
  4599.6    0.05       0  4990.9    0.04       0  4994.9    0.05       0
Bank Sta=4990.9,4994.9
Exp/Cntr=0.3,0.1

Type RM Length L Ch R = 1,1351,202,202,202
BEGIN DESCRIPTION:
MDW T 026 3.0
END DESCRIPTION:
XS GIS Cut Line= 3
      2290875.41      7109575.29      2290668.19      7109208.47
      2290333.89      7108928.27
#Sta/Elev= 30
  4578.7  841.26  4601.9  840.90  4617.9  839.76  4653.7  839.39  4676.7  838.07
  4698.7  838.17  4742.0  836.23  4747.8  836.53  4785.3  835.49  4801.2  834.30
  4837.4  832.97  4844.5  833.58  4850.3  832.80  4882.1  832.20  4894.9  828.56
  4940.8  828.18  4947.0  829.60  4952.8  828.79  4963.0  829.22  4968.7  828.29
  4982.6  827.41  4982.9  826.91  4986.4  826.91  4986.6  827.41  5040.6  827.49
  5161.6  831.54  5233.1  834.85  5346.3  838.37  5410.1  842.00  5436.2  842.98
#Mann=3,-1,0
  4578.7    0.05       0  4982.6    0.04       0  4986.6    0.05       0
Bank Sta=4982.6,4986.6
Exp/Cntr=0.3,0.1

Type RM Length L Ch R = 1,1149,67,67,67
BEGIN DESCRIPTION:
Mapping XS 233bc0ed
END DESCRIPTION:
XS GIS Cut Line= 6
      2290788.16      7109338.31      2290709.39      7109231.35
      2290791.09      7109148.51      2290802.19      7109088.68
      2290784.66      7109056.04      2290527.38      7108947.31
#Sta/Elev= 30
  4612.6  833.30  4668.3  832.19  4674.5  832.55  4689.2  828.92  4697.4  828.12
  4718.4  828.03  4733.1  830.33  4753.2  831.06  4845.2  829.74  4852.2  829.21
  4870.4  829.78  4966.8  828.99  4985.1  829.38  4990.5  828.66  5008.8  829.07
  5014.2  827.31  5020.1  828.28  5031.0  827.23  5041.3  827.22  5041.6  826.72
  5045.1  826.72  5045.3  827.22  5074.4  828.76  5114.4  829.64  5150.4  831.33
  5183.0  831.38  5196.4  832.63  5214.7  833.14  5226.4  834.72  5239.0  835.05
#Mann=3,-1,0
  4612.6    0.05       0  5041.3    0.04       0  5045.3    0.05       0
Bank Sta=5041.3,5045.3
Exp/Cntr=0.3,0.1

Type RM Length L Ch R = 1,1082,237,237,237
BEGIN DESCRIPTION:
MDW T 026 2.0
END DESCRIPTION:
XS GIS Cut Line= 3
      2291004.59      7109333.01      2290803.87      7109009.88
      2290456.66      7108666.82
#Sta/Elev= 30
  4619.6  833.77  4640.2  834.39  4692.2  832.93  4705.6  833.24  4719.3  831.94
  4777.2  831.38  4799.7  830.33  4829.2  829.94  4835.1  830.34  4850.4  829.72
  4858.6  827.41  4865.8  826.17  4979.5  824.26  4979.7  823.76  4983.2  823.76
  4983.5  824.26  4999.9  825.34  5024.5  825.37  5095.3  827.07  5151.8  829.38
  5180.1  831.84  5201.4  834.65  5243.8  834.94  5371.1  834.20  5420.6  835.00
  5427.7  837.03  5434.7  837.38  5441.8  839.36  5456.0  840.54  5488.1  841.50
#Mann=3,-1,0
  4619.6    0.05       0  4979.5    0.04       0  4983.5    0.05       0
Bank Sta=4979.5,4983.5
Exp/Cntr=0.3,0.1

Type RM Length L Ch R = 1,845,162,162,162
BEGIN DESCRIPTION:
MDW T 026 1.0
END DESCRIPTION:
XS GIS Cut Line= 3
      2291064.22      7109309.69      2291003.96      7108909.91
      2290539.75      7108524.74
#Sta/Elev= 30
  4595.7  833.16  4615.6  833.42  4656.1  831.65  4662.7  832.19  4686.4  831.37
  4696.5  830.07  4737.0  830.24  4767.3  826.36  4787.5  827.52  4828.0  827.56
  4838.1  826.71  4858.3  827.71  4878.6  823.87  4933.4  823.57  4939.2  822.42
  4979.7  821.71  4987.8  820.32  4988.0  819.82  4991.8  820.32  4999.9  821.53
  5032.4  822.80  5088.5  823.24  5216.1  826.64  5287.7  830.46  5322.9  831.23
  5372.3  834.56  5565.1  834.26  5585.9  835.60  5592.4  838.11  5603.2  838.59
#Mann=3,-1,0
  4595.7    0.05       0  4987.8    0.04       0  4991.8    0.05       0
Bank Sta=4987.8,4991.8
Exp/Cntr=0.3,0.1

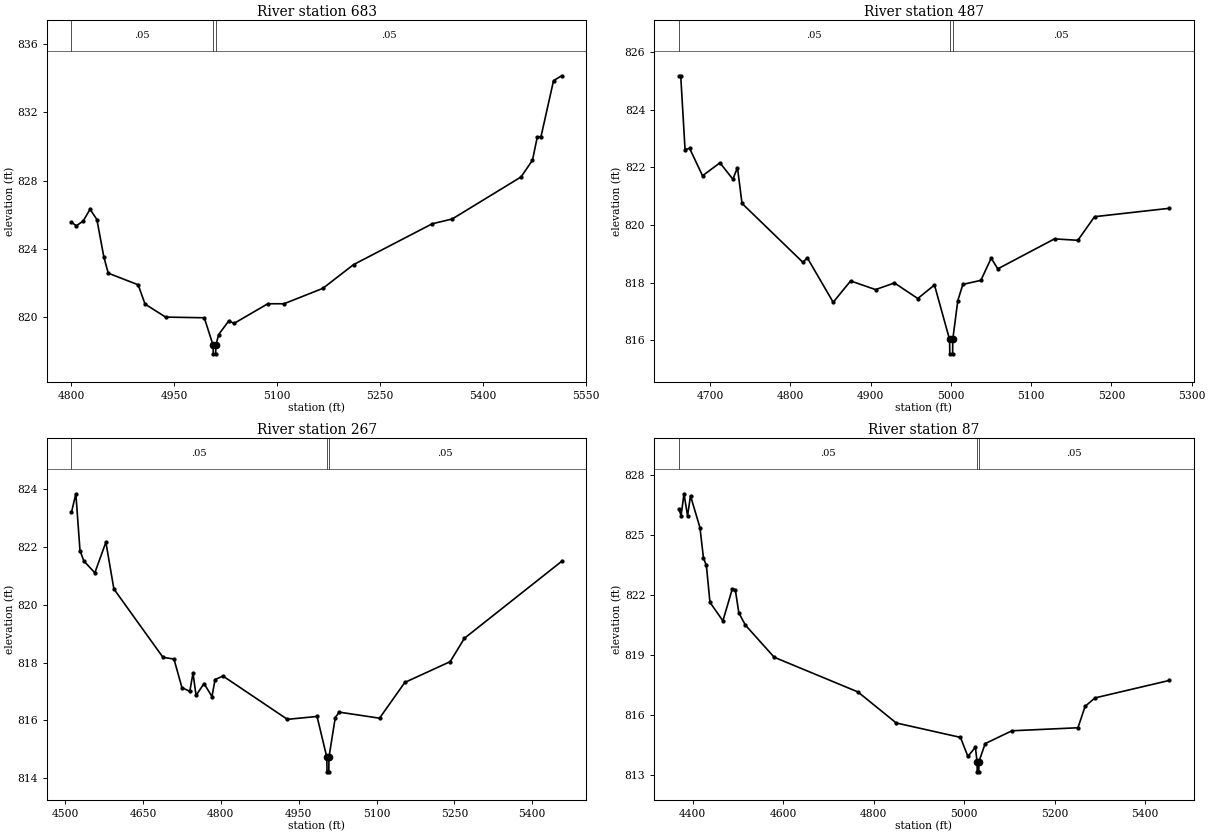
Type RM Length L Ch R = 1,683,196,196,196
BEGIN DESCRIPTION:
Mapping XS ea2668a1
END DESCRIPTION:
XS GIS Cut Line= 4
      2291166.06      7109056.99      2291159.16      7108873.36
      2291045.75      7108711.19      2290739.77      7108581.72
#Sta/Elev= 30
  4800.6  825.57  4807.6  825.36  4817.6  825.64  4827.6  826.33  4837.6  825.73
  4847.6  823.56  4854.1  822.59  4897.7  821.91  4907.7  820.78  4937.7  820.02
  4994.0  819.98  5006.8  818.37  5007.0  817.87  5010.5  817.87  5010.8  818.37
  5014.9  819.00  5029.7  819.80  5037.3  819.65  5086.4  820.80  5110.0  820.80
  5166.6  821.70  5211.3  823.09  5325.9  825.48  5355.0  825.76  5455.2  828.22
  5471.9  829.20  5478.9  830.56  5484.3  830.58  5502.6  833.86  5514.5  834.14
#Mann=3,-1,0
  4800.6    0.05       0  5006.8    0.04       0  5010.8    0.05       0
Bank Sta=5006.8,5010.8
Exp/Cntr=0.3,0.1

Type RM Length L Ch R = 1,487,220,220,220
BEGIN DESCRIPTION:
Mapping XS d9f18388
END DESCRIPTION:
XS GIS Cut Line= 3
      2291208.75      7109008.96      2291327.43      7108793.67
      2291105.70      7108503.66
#Sta/Elev= 30
  4661.0  825.18  4663.3  825.18  4668.7  822.62  4674.4  822.66  4690.5  821.71
  4712.2  822.16  4728.3  821.59  4734.0  821.99  4739.7  820.75  4815.4  818.71
  4821.1  818.86  4853.3  817.32  4875.0  818.06  4906.1  817.76  4929.6  817.99
  4958.7  817.45  4979.5  817.92  4998.3  816.03  4998.6  815.53  5002.1  815.53
  5002.3  816.03  5008.6  817.38  5014.9  817.94  5037.3  818.08  5050.2  818.85
  5058.4  818.48  5129.1  819.52  5158.2  819.47  5179.0  820.29  5271.9  820.58
#Mann=3,-1,0
  4661.0    0.05       0  4998.3    0.04       0  5002.3    0.05       0
Bank Sta=4998.3,5002.3
Exp/Cntr=0.3,0.1

Type RM Length L Ch R = 1,267,180,180,180
BEGIN DESCRIPTION:
Mapping XS 7020bd35
END DESCRIPTION:
XS GIS Cut Line= 4
      2291230.69      7109003.91      2291468.99      7108618.48
      2291324.67      7108488.90      2291040.09      7108401.19
#Sta/Elev= 30
  4512.1  823.21  4520.5  823.85  4528.5  821.88  4535.9  821.52  4557.1  821.11
  4578.4  822.17  4593.8  820.55  4688.4  818.18  4709.6  818.12  4725.0  817.13
  4740.1  817.00  4746.3  817.63  4752.2  816.86  4767.5  817.27  4782.9  816.82
  4788.8  817.41  4804.2  817.53  4928.2  816.03  4985.4  816.13  5004.3  814.71
  5004.6  814.21  5008.1  814.21  5008.3  814.71  5020.5  816.09  5028.0  816.28
  5105.8  816.07  5154.6  817.31  5242.0  818.03  5269.4  818.84  5457.0  821.51
#Mann=3,-1,0
  4512.1    0.05       0  5004.3    0.04       0  5008.3    0.05       0
Bank Sta=5004.3,5008.3
Exp/Cntr=0.3,0.1

Type RM Length L Ch R = 1,87,0,0,0
BEGIN DESCRIPTION:
MDW T 026 0.3
END DESCRIPTION:
XS GIS Cut Line= 3
      2291208.53      7109045.88      2291616.74      7108552.44
      2291231.11      7108334.41
#Sta/Elev= 30
  4369.5  826.29  4374.4  825.96  4380.8  827.05  4388.7  825.95  4395.2  826.95
  4416.1  825.36  4423.8  823.85  4430.3  823.47  4438.2  821.63  4466.8  820.71
  4487.7  822.31  4494.2  822.26  4502.0  821.11  4516.3  820.50  4580.2  818.89
  4765.1  817.16  4849.8  815.61  4991.8  814.89  5008.2  813.94  5024.8  814.40
  5028.5  813.67  5028.8  813.17  5032.3  813.17  5032.5  813.67  5046.4  814.58
  5105.6  815.22  5251.4  815.37  5267.3  816.44  5289.0  816.86  5452.9  817.73
#Mann=3,-1,0
  4369.5    0.05       0  5028.5    0.04       0  5032.5    0.05       0
Bank Sta=5028.5,5032.5
Exp/Cntr=0.3,0.1

Chan Stop Cuts=-1