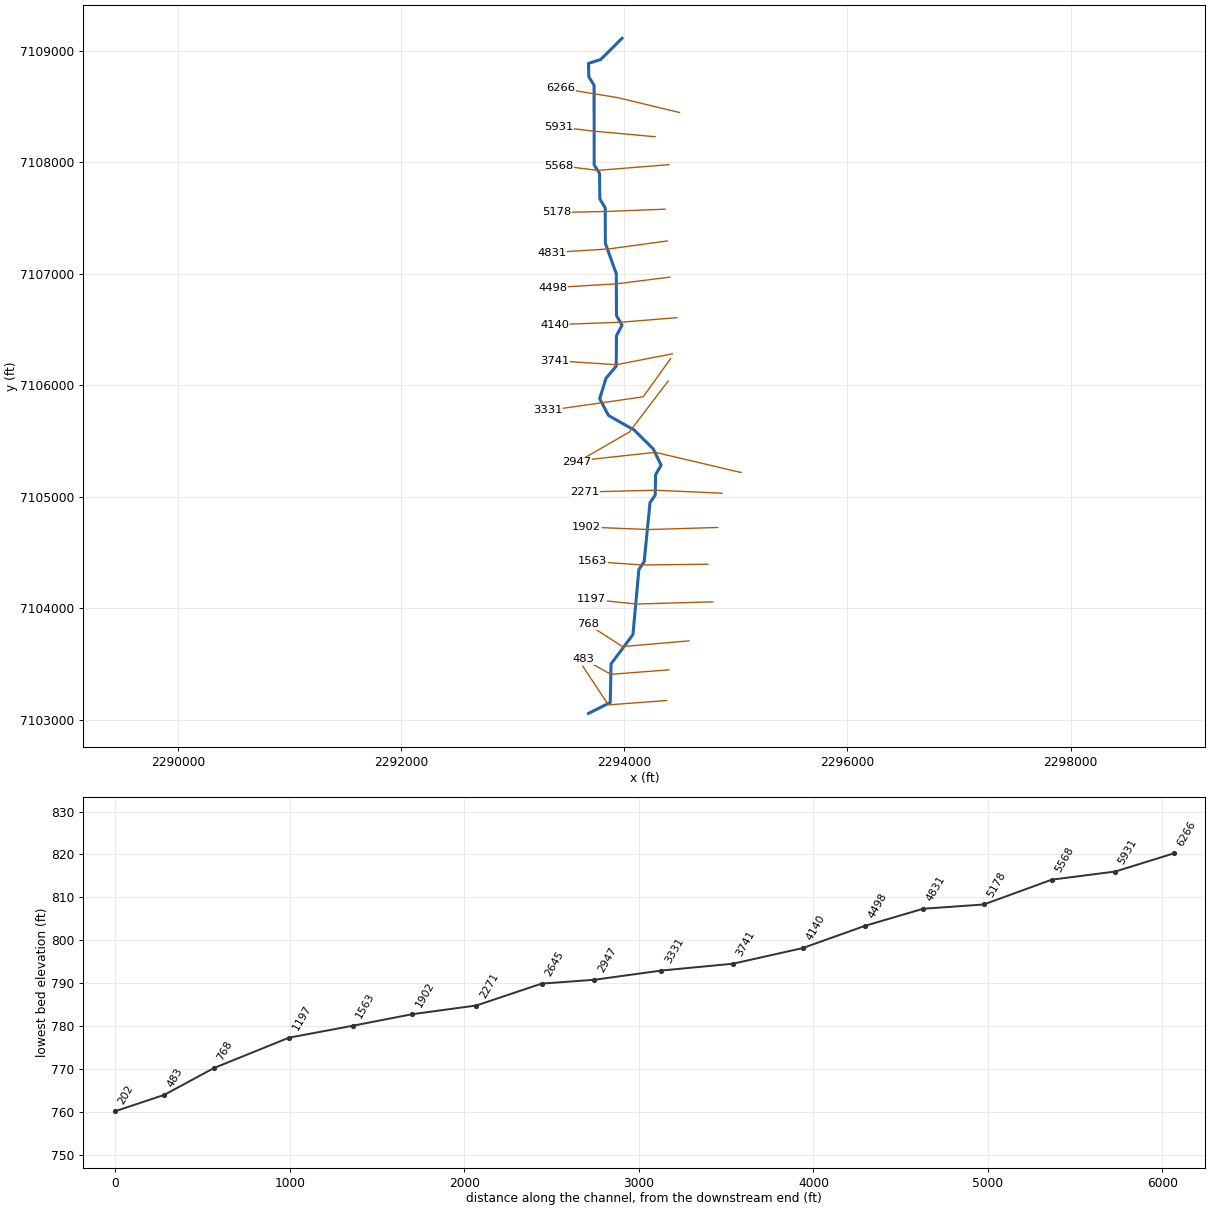
--- MDW T 027.prj (project) ---

Proj Title=MDW T 027 Base Level Engineering
Current Plan=p01
Default Exp/Contr=0.3,0.1
English Units
Geom File=g01
Flow File=f01
Plan File=p01
BEGIN DESCRIPTION:
MDW T 027
END DESCRIPTION:

--- MDW T 027.p01 (plan) ---

Plan Title=Multiple Run
Short Identifier=Multiple
Geom File=g01
Flow File=f01
Subcritical Flow
K Sum by GR= 0
Std Step Tol= 0.01
Critical Tol= 0.01
Num of Std Step Trials= 20
Max Error Tol= 0.3
Flow Tol Ratio= 0.001
Split Flow NTrial= 30
Split Flow Tol= 0.02
Split Flow Ratio= 0.02
Log Output Level= 0
Friction Slope Method= 1
Unsteady Friction Slope Method= 2
Unsteady Bridges Friction Slope Method= 1
Parabolic Critical Depth
Global Vel Dist=  1 , 1 , 1
Global Log Level= 0
CheckData=True
Encroach Param= -1, 0, 0, 0
BEGIN DESCRIPTION:
Multiple Run
END DESCRIPTION:

--- MDW T 027.f01 (steady flow) ---

Flow Title=Multiple
Number of Profiles=7
Profile Names=10-year,25-year,50-year,1pct_min,100-year,1pct_plu,500-year
River Rch & RM= MDW T 027,Reach-1,6266
     434     587     712     430     858    1713    1248
River Rch & RM= MDW T 027,Reach-1,4831
     473     643     782     473     944    1883    1377
River Rch & RM= MDW T 027,Reach-1,2271
     677     940    1160     711    1420    2832    2130
Boundary for River Rch & Prof#=MDW T 027,Reach-1,1
Up Type=0
Dn Type=3
Dn Slope=0.005
Boundary for River Rch & Prof#=MDW T 027,Reach-1,2
Up Type=0
Dn Type=3
Dn Slope=0.005
Boundary for River Rch & Prof#=MDW T 027,Reach-1,3
Up Type=0
Dn Type=3
Dn Slope=0.005
Boundary for River Rch & Prof#=MDW T 027,Reach-1,4
Up Type=0
Dn Type=3
Dn Slope=0.005
Boundary for River Rch & Prof#=MDW T 027,Reach-1,5
Up Type=0
Dn Type=3
Dn Slope=0.005
Boundary for River Rch & Prof#=MDW T 027,Reach-1,6
Up Type=0
Dn Type=3
Dn Slope=0.005
Boundary for River Rch & Prof#=MDW T 027,Reach-1,7
Up Type=0
Dn Type=3
Dn Slope=0.005

--- MDW T 027.g01 (geometry) ---

Geom Title=Existing Conditions

River Reach=MDW T 027,Reach-1
Reach XY= 30
      2293979.00      7109110.00      2293788.74      7108920.54
      2293678.57      7108885.38      2293681.25      7108765.95
      2293728.93      7108689.97      2293729.52      7107975.22
      2293777.78      7107899.50      2293780.22      7107670.50
      2293828.93      7107589.97      2293829.52      7107275.22
      2293927.78      7106999.50      2293929.54      7106625.21
      2293979.28      7106539.82      2293929.54      7106444.79
      2293927.08      7106171.95      2293835.07      7106062.23
      2293778.89      7105880.09      2293858.52      7105729.63
      2294088.68      7105599.22      2294259.24      7105430.10
      2294329.27      7105284.69      2294280.12      7105199.54
      2294276.74      7105015.94      2294230.22      7104949.50
      2294177.78      7104420.50      2294130.22      7104349.50
      2294076.94      7103765.86      2293881.06      7103504.14
      2293873.64      7103157.30      2293679.00      7103060.00

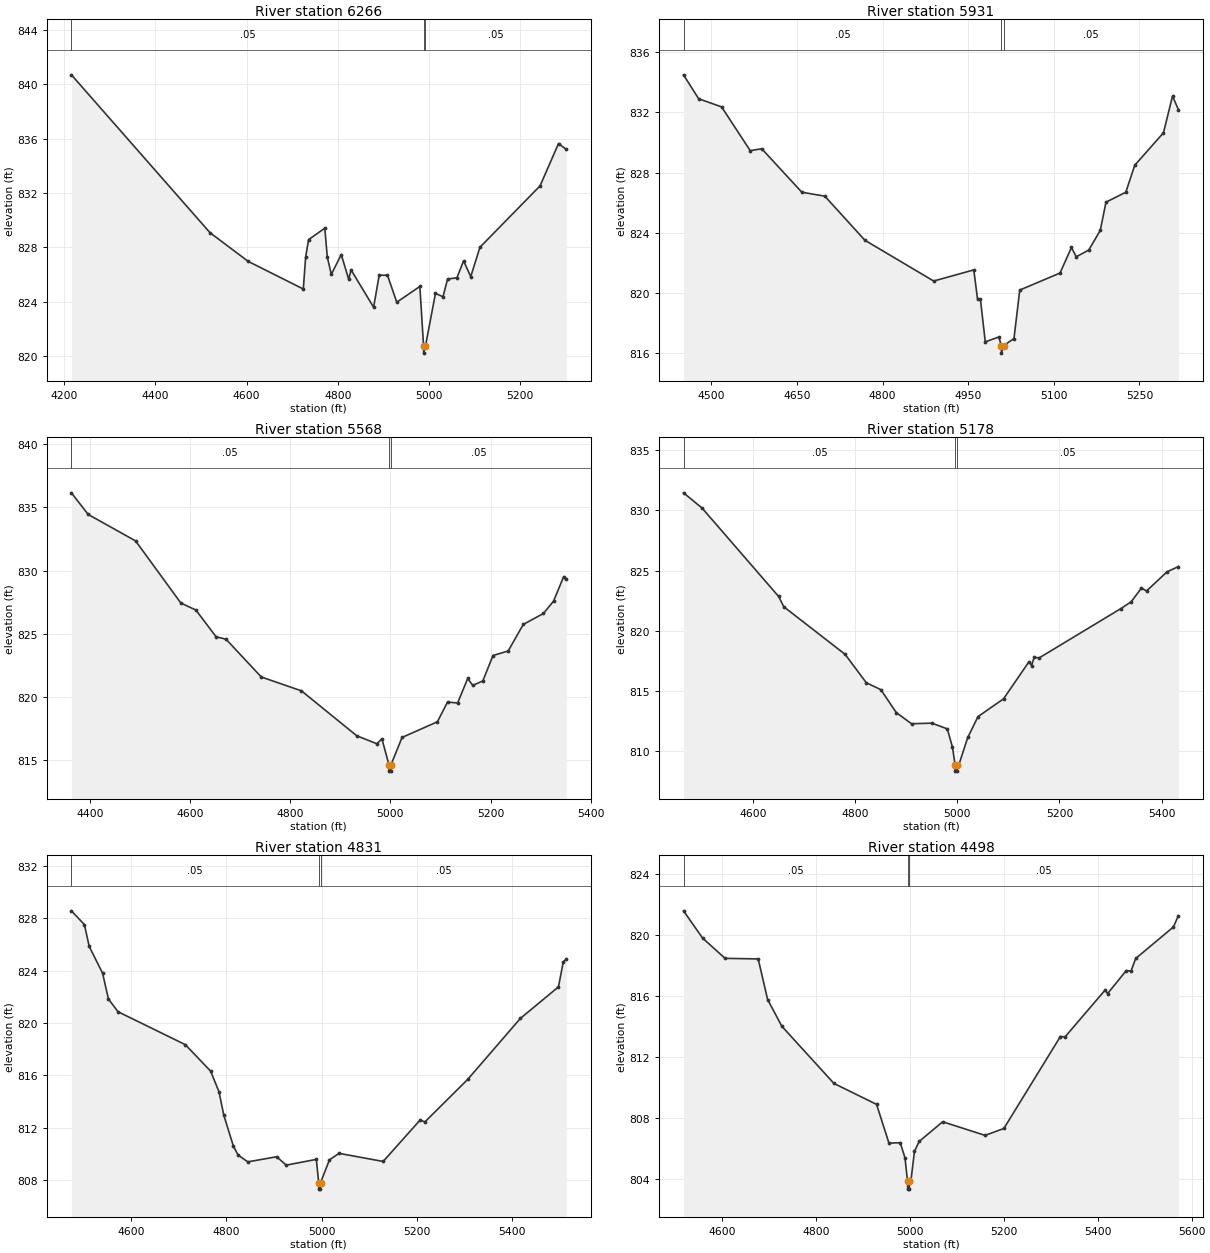
Type RM Length L Ch R = 1,6266,335,335,335
BEGIN DESCRIPTION:
MDW T 027 17.0
END DESCRIPTION:
XS GIS Cut Line= 3
      2294494.28      7108445.18      2293937.01      7108579.29
      2293432.27      7108661.04
#Sta/Elev= 30
  4216.2  840.68  4519.9  829.08  4603.7  826.97  4724.4  824.94  4729.5  827.27
  4735.9  828.57  4771.5  829.41  4777.0  827.28  4785.8  826.02  4807.6  827.47
  4823.9  825.65  4829.0  826.35  4878.5  823.60  4890.7  825.96  4908.9  825.95
  4929.2  823.97  4979.8  825.13  4988.0  820.73  4988.2  820.23  4992.0  820.73
  5014.0  824.62  5030.5  824.37  5040.6  825.68  5060.9  825.76  5075.7  827.01
  5091.3  825.85  5111.5  828.01  5243.2  832.52  5283.7  835.63  5300.7  835.20
#Mann=3,-1,0
  4216.2    0.05       0  4988.0   0.033       0  4992.0    0.05       0
Bank Sta=4988,4992
Exp/Cntr=0.3,0.1

Type RM Length L Ch R = 1,5931,363,363,363
BEGIN DESCRIPTION:
MDW T 027 16.0
END DESCRIPTION:
XS GIS Cut Line= 3
      2294275.44      7108228.23      2293725.41      7108278.23
      2293413.10      7108316.17
#Sta/Elev= 30
  4451.3  834.49  4477.8  832.90  4518.0  832.36  4568.2  829.45  4588.3  829.58
  4658.6  826.69  4698.8  826.43  4769.0  823.50  4889.5  820.79  4959.8  821.53
  4966.4  819.58  4971.4  819.59  4979.9  816.75  5003.6  817.07  5008.1  816.50
  5008.3  816.00  5012.1  816.50  5030.2  816.97  5040.3  820.19  5110.8  821.32
  5130.9  823.02  5139.3  822.40  5161.2  822.85  5181.3  824.15  5191.4  826.03
  5226.1  826.69  5241.7  828.48  5292.1  830.64  5307.9  833.08  5318.2  832.18
#Mann=3,-1,0
  4451.3    0.05       0  5008.1    0.04       0  5012.1    0.05       0
Bank Sta=5008.1,5012.1
Exp/Cntr=0.3,0.1

Type RM Length L Ch R = 1,5568,390,390,390
BEGIN DESCRIPTION:
MDW T 027 15.0
END DESCRIPTION:
XS GIS Cut Line= 3
      2294396.65      7107977.73      2293762.11      7107926.57
      2293413.79      7107969.89
#Sta/Elev= 30
  4363.4  836.16  4396.8  834.45  4491.5  832.35  4581.8  827.43  4611.9  826.87
  4652.0  824.76  4672.0  824.56  4742.3  821.57  4822.5  820.47  4932.9  816.91
  4973.0  816.28  4983.1  816.67  4997.1  814.61  4997.3  814.11  5000.8  814.11
  5001.1  814.61  5023.3  816.78  5093.8  818.02  5114.0  819.58  5134.1  819.51
  5154.3  821.45  5164.4  820.90  5184.5  821.26  5204.7  823.27  5235.1  823.63
  5265.1  825.73  5305.4  826.60  5325.6  827.58  5345.8  829.52  5351.0  829.31
#Mann=3,-1,0
  4363.4    0.05       0  4997.1    0.04       0  5001.1    0.05       0
Bank Sta=4997.1,5001.1
Exp/Cntr=0.3,0.1

Type RM Length L Ch R = 1,5178,347,347,347
BEGIN DESCRIPTION:
MDW T 027 14.0
END DESCRIPTION:
XS GIS Cut Line= 3
      2294365.16      7107578.91      2293829.38      7107557.86
      2293396.66      7107549.34
#Sta/Elev= 30
  4463.8  831.46  4500.0  830.20  4650.1  822.84  4660.1  821.99  4780.2  818.03
  4821.7  815.67  4850.3  815.09  4880.3  813.19  4910.3  812.26  4950.3  812.31
  4980.4  811.83  4990.4  810.31  4995.7  808.82  4995.9  808.32  4999.4  808.32
  4999.7  808.82  5002.7  808.82  5020.4  811.12  5040.4  812.85  5090.4  814.33
  5140.3  817.42  5145.3  817.10  5150.4  817.77  5160.4  817.74  5320.4  821.84
  5340.4  822.40  5360.4  823.54  5370.4  823.30  5410.5  824.89  5432.8  825.33
#Mann=3,-1,0
  4463.8    0.05       0  4995.7    0.04       0  4999.7    0.05       0
Bank Sta=4995.7,4999.7
Exp/Cntr=0.3,0.1

Type RM Length L Ch R = 1,4831,333,333,333
BEGIN DESCRIPTION:
MDW T 027 13.0
END DESCRIPTION:
XS GIS Cut Line= 3
      2294386.08      7107294.20      2293865.20      7107223.14
      2293352.67      7107190.11
#Sta/Elev= 30
  4474.3  828.56  4501.6  827.51  4511.7  825.84  4539.7  823.81  4552.1  821.83
  4572.3  820.86  4713.6  818.35  4766.7  816.33  4784.2  814.76  4794.3  812.97
  4814.5  810.61  4824.6  809.92  4844.8  809.41  4905.3  809.80  4925.5  809.16
  4988.7  809.60  4993.6  807.83  4993.8  807.33  4997.3  807.33  4997.6  807.83
  5016.2  809.56  5036.3  810.06  5129.0  809.44  5206.6  812.60  5216.7  812.46
  5306.8  815.71  5417.1  820.35  5497.2  822.76  5507.3  824.67  5513.6  824.86
#Mann=3,-1,0
  4474.3    0.05       0  4993.6    0.04       0  4997.6    0.05       0
Bank Sta=4993.6,4997.6
Exp/Cntr=0.3,0.1

Type RM Length L Ch R = 1,4498,358,358,358
BEGIN DESCRIPTION:
MDW T 027 12.0
END DESCRIPTION:
XS GIS Cut Line= 3
      2294406.62      7106969.76      2293929.09      7106909.65
      2293358.29      7106875.79
#Sta/Elev= 30
  4518.7  821.57  4559.2  819.79  4607.0  818.46  4677.6  818.42  4697.7  815.76
  4728.0  814.01  4838.8  810.27  4929.5  808.90  4955.9  806.36  4979.9  806.39
  4990.0  805.40  4995.5  803.85  4995.8  803.35  4999.3  803.35  4999.5  803.85
  5002.5  803.85  5010.1  805.82  5020.1  806.47  5070.2  807.76  5160.4  806.87
  5200.4  807.32  5320.7  813.34  5330.7  813.32  5416.1  816.39  5421.1  816.15
  5460.9  817.66  5470.9  817.62  5480.9  818.45  5561.1  820.51  5571.8  821.25
#Mann=3,-1,0
  4518.7    0.05       0  4995.5    0.04       0  4999.5    0.05       0
Bank Sta=4995.5,4999.5
Exp/Cntr=0.3,0.1

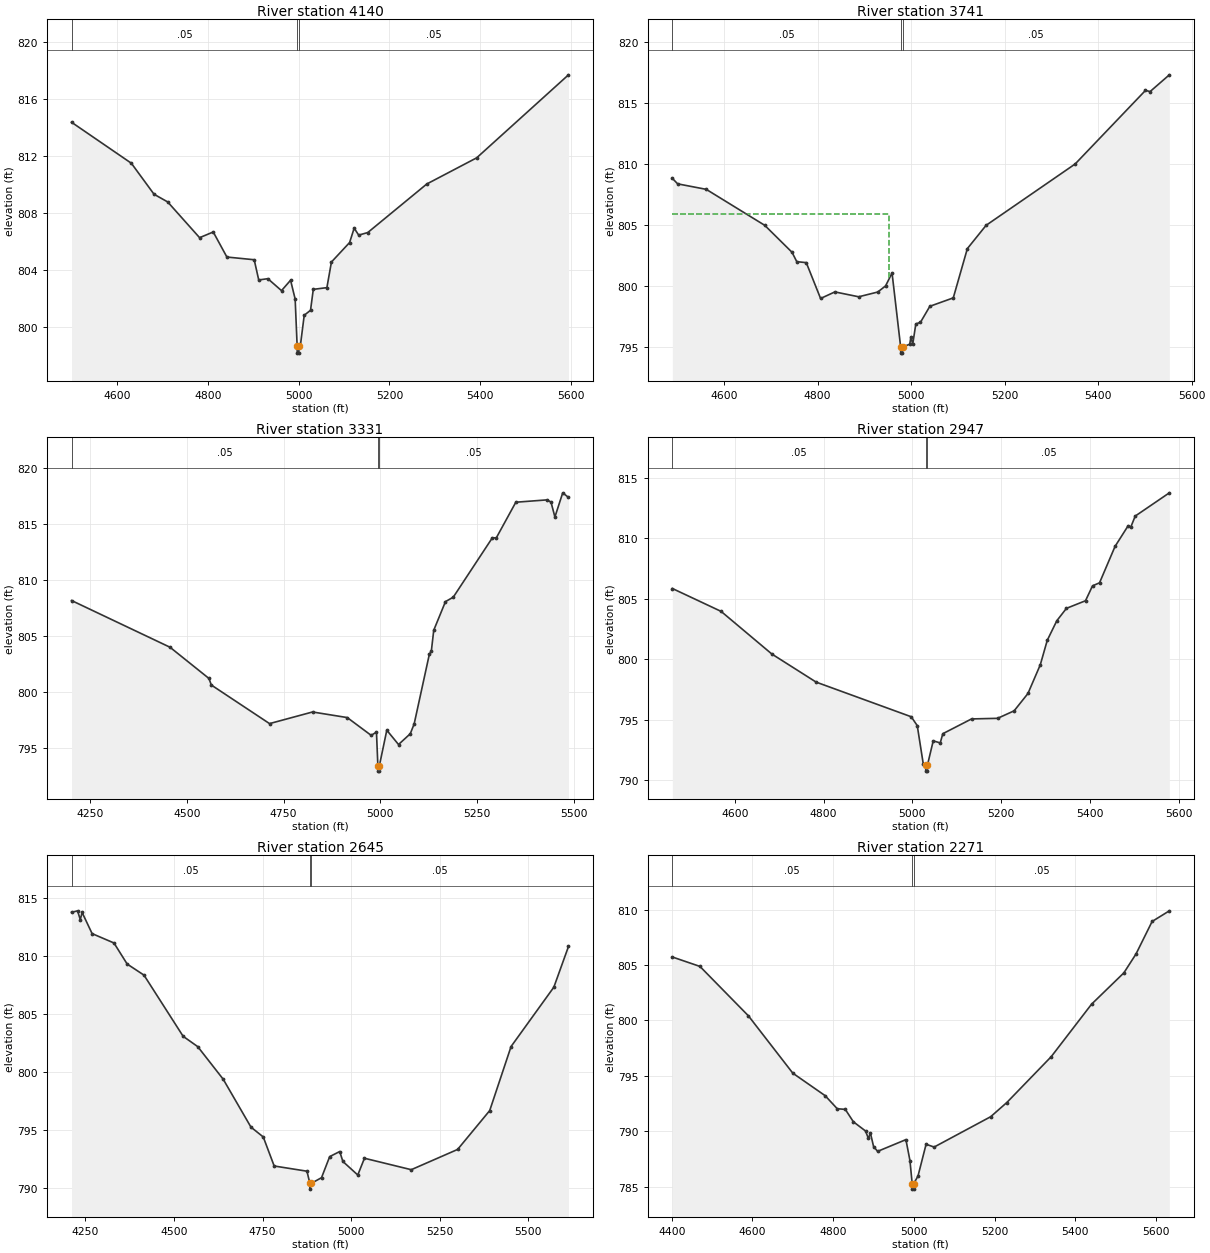
Type RM Length L Ch R = 1,4140,399,399,399
BEGIN DESCRIPTION:
MDW T 027 11.0
END DESCRIPTION:
XS GIS Cut Line= 3
      2294470.44      7106606.48      2293971.19      7106565.92
      2293376.69      7106543.98
#Sta/Elev= 30
  4499.1  814.37  4631.0  811.49  4681.1  809.31  4711.2  808.77  4781.5  806.26
  4811.6  806.66  4841.7  804.90  4901.9  804.71  4911.9  803.29  4932.0  803.38
  4962.1  802.54  4982.1  803.27  4992.2  801.95  4996.6  798.65  4996.8  798.15
  5000.3  798.15  5000.6  798.65  5003.6  798.65  5012.2  800.81  5026.1  801.16
  5032.2  802.63  5062.2  802.75  5072.2  804.55  5112.3  805.92  5122.3  806.93
  5132.3  806.44  5152.3  806.62  5282.4  810.03  5392.5  811.87  5594.9  817.70
#Mann=3,-1,0
  4499.1    0.05       0  4996.6   0.033       0  5000.6    0.05       0
Bank Sta=4996.6,5000.6
Exp/Cntr=0.3,0.1

Type RM Length L Ch R = 1,3741,410,410,410
BEGIN DESCRIPTION:
MDW T 027 10.0
END DESCRIPTION:
XS GIS Cut Line= 3
      2294430.07      7106282.26      2293929.15      7106184.87
      2293378.03      7106221.06
#Sta/Elev= 30
  4489.7  808.84  4501.0  808.39  4562.1  807.94  4687.2  804.99  4745.5  802.78
  4755.7  802.01  4776.0  801.93  4806.6  798.99  4837.1  799.53  4888.1  799.13
  4928.8  799.52  4945.5  800.02  4959.4  801.08  4977.8  795.01  4978.0  794.51
  4981.5  794.51  4981.8  795.01  4997.2  795.24  4999.7  795.83  5003.6  795.24
  5010.2  796.90  5020.2  797.04  5040.2  798.35  5090.3  799.04  5120.4  803.08
  5160.5  804.99  5350.9  810.02  5501.2  816.05  5511.2  815.96  5552.3  817.33
#Mann=3,-1,0
  4489.7    0.05       0  4977.8    0.04       0  4981.8    0.05       0
#XS Ineff=2,0
    0.00 4953.80  805.92               0
Permanent Ineff=
       F       F
Bank Sta=4977.8,4981.8
Exp/Cntr=0.3,0.1

Type RM Length L Ch R = 1,3331,384,384,384
BEGIN DESCRIPTION:
MDW T 027 9.0
END DESCRIPTION:
XS GIS Cut Line= 4
      2294414.66      7106238.78      2294168.65      7105897.03
      2293795.78      7105843.40      2293314.21      7105774.97
#Sta/Elev= 30
  4202.2  808.18  4456.7  804.00  4557.3  801.21  4563.5  800.62  4713.9  797.17
  4825.0  798.21  4914.7  797.71  4976.5  796.12  4990.2  796.41  4993.8  793.42
  4994.1  792.92  4997.6  792.92  4997.8  793.42  5016.9  796.58  5047.2  795.30
  5077.5  796.26  5087.6  797.14  5126.9  803.38  5131.9  803.63  5138.2  805.52
  5168.5  808.08  5188.7  808.48  5289.7  813.79  5299.8  813.78  5350.3  816.97
  5431.1  817.18  5441.2  816.98  5451.3  815.65  5471.5  817.81  5486.4  817.40
#Mann=3,-1,0
  4202.2    0.05       0  4993.8    0.04       0  4997.8    0.05       0
Bank Sta=4993.8,4997.8
Exp/Cntr=0.3,0.1

Type RM Length L Ch R = 1,2947,302,302,302
BEGIN DESCRIPTION:
MDW T 027 8.0
END DESCRIPTION:
XS GIS Cut Line= 3
      2294392.97      7106039.06      2294044.87      7105581.58
      2293573.13      7105308.97
#Sta/Elev= 30
  4459.4  805.85  4569.2  803.96  4683.5  800.44  4783.3  798.12  4997.5  795.26
  5011.1  794.53  5024.6  791.38  5030.1  791.27  5030.4  790.77  5033.9  790.77
  5034.1  791.27  5047.1  793.27  5062.9  793.10  5068.7  793.86  5133.4  795.08
  5192.1  795.13  5229.4  795.75  5260.5  797.18  5288.3  799.55  5304.1  801.58
  5325.6  803.19  5347.2  804.21  5390.2  804.84  5406.0  806.07  5421.8  806.32
  5456.8  809.33  5486.4  811.04  5492.2  810.92  5502.2  811.83  5579.1  813.75
#Mann=3,-1,0
  4459.4    0.05       0  5030.1    0.04       0  5034.1    0.05       0
Bank Sta=5030.1,5034.1
Exp/Cntr=0.3,0.1

Type RM Length L Ch R = 1,2645,374,374,374
BEGIN DESCRIPTION:
MDW T 027 7.0
END DESCRIPTION:
XS GIS Cut Line= 3
      2295045.60      7105218.76      2294277.68      7105399.45
      2293667.95      7105333.35
#Sta/Elev= 30
  4211.1  813.80  4228.2  813.93  4235.8  813.17  4241.0  813.79  4269.2  811.96
  4330.9  811.15  4368.1  809.33  4415.6  808.37  4526.1  803.08  4567.2  802.19
  4639.1  799.37  4717.4  795.23  4752.1  794.38  4782.9  791.87  4875.4  791.42
  4883.6  790.37  4883.9  789.87  4887.6  790.37  4916.5  790.86  4939.5  792.68
  4967.8  793.12  4976.8  792.26  5018.8  791.09  5037.6  792.54  5169.7  791.55
  5300.4  793.30  5391.0  796.66  5451.3  802.20  5572.0  807.33  5613.3  810.85
#Mann=3,-1,0
  4211.1    0.05       0  4883.6    0.04       0  4887.6    0.05       0
Bank Sta=4883.6,4887.6
Exp/Cntr=0.3,0.1

Type RM Length L Ch R = 1,2271,369,369,369
BEGIN DESCRIPTION:
MDW T 027 6.0
END DESCRIPTION:
XS GIS Cut Line= 3
      2294877.18      7105033.00      2294279.00      7105060.00
      2293646.29      7105044.29
#Sta/Elev= 30
  4401.6  805.73  4469.9  804.88  4590.0  800.42  4700.1  795.24  4780.2  793.21
  4810.2  792.03  4830.2  791.97  4850.2  790.85  4880.3  790.02  4887.4  789.35
  4892.4  789.84  4900.3  788.61  4910.3  788.18  4980.4  789.24  4990.4  787.35
  4995.9  785.27  4996.1  784.77  4999.6  784.77  4999.9  785.27  5010.4  785.96
  5030.4  788.82  5050.4  788.57  5190.5  791.31  5230.5  792.59  5340.5  796.73
  5440.5  801.47  5520.6  804.30  5550.6  806.00  5590.6  808.94  5633.3  809.90
#Mann=3,-1,0
  4401.6    0.05       0  4995.9    0.04       0  4999.9    0.05       0
Bank Sta=4995.9,4999.9
Exp/Cntr=0.3,0.1

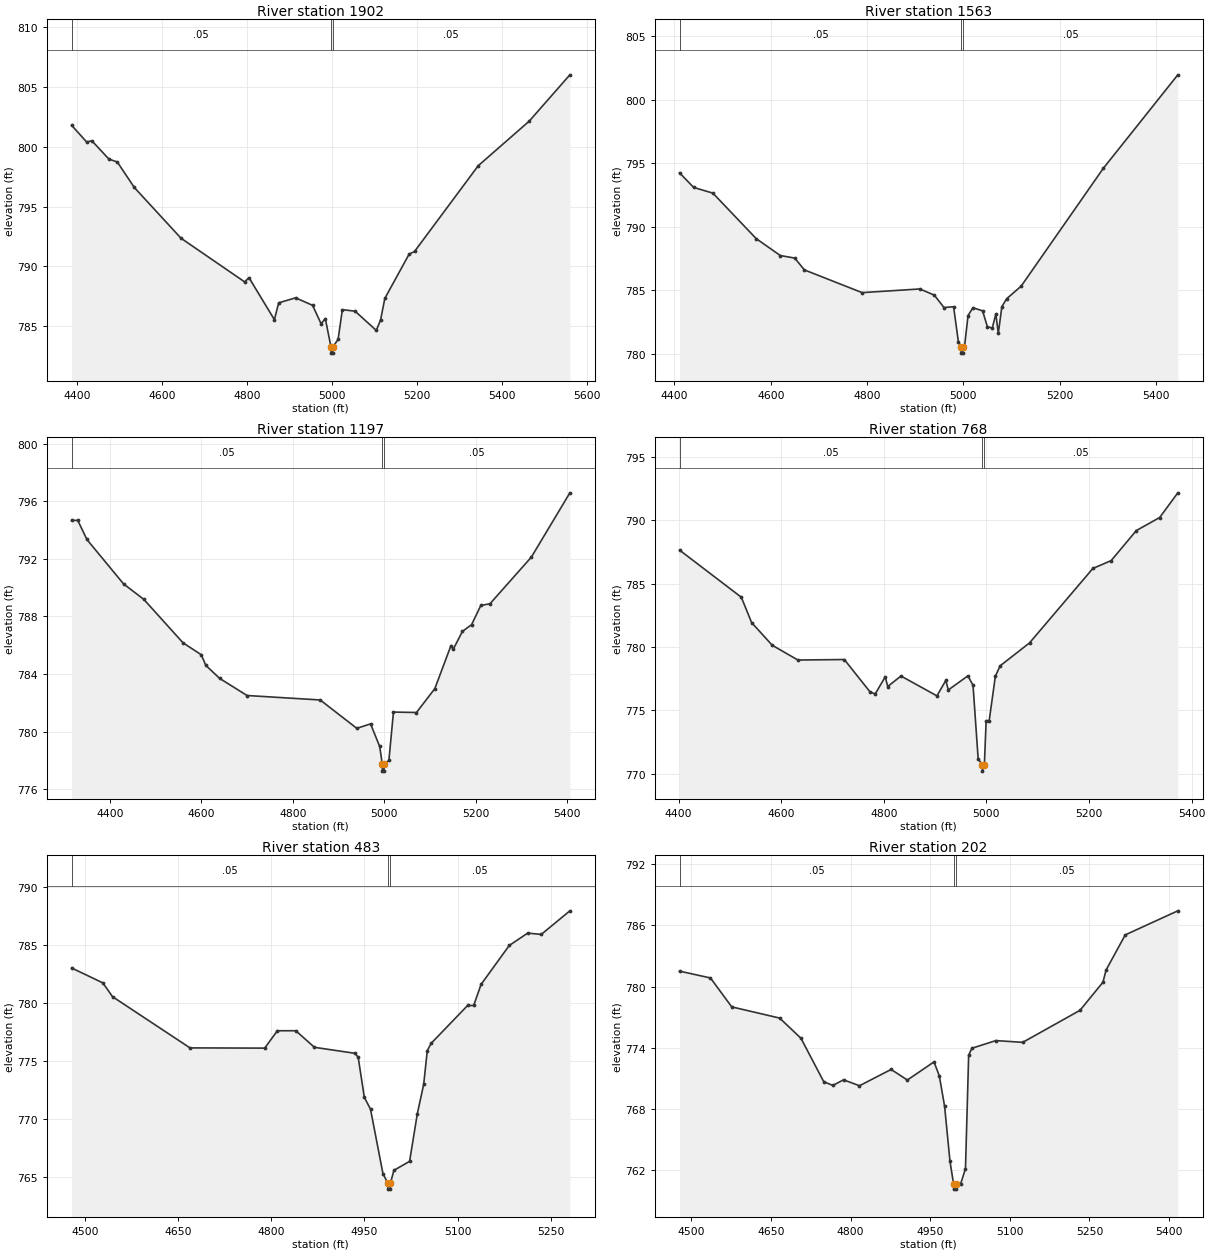
Type RM Length L Ch R = 1,1902,339,339,339
BEGIN DESCRIPTION:
MDW T 027 5.0
END DESCRIPTION:
XS GIS Cut Line= 3
      2294836.78      7104726.15      2294223.25      7104707.67
      2293663.20      7104730.02
#Sta/Elev= 30
  4386.2  801.81  4421.6  800.41  4434.0  800.51  4474.0  798.98  4494.0  798.73
  4534.0  796.60  4644.1  792.35  4794.2  788.69  4804.2  789.05  4864.2  785.53
  4874.2  786.94  4914.2  787.36  4954.2  786.73  4974.2  785.19  4984.2  785.62
  4997.6  783.23  4997.9  782.73  5001.4  782.73  5001.6  783.23  5014.3  783.88
  5024.3  786.37  5054.3  786.24  5104.3  784.63  5114.3  785.50  5124.4  787.31
  5181.7  791.02  5194.4  791.24  5344.5  798.42  5464.6  802.15  5560.5  806.03
#Mann=3,-1,0
  4386.2    0.05       0  4997.6    0.04       0  5001.6    0.05       0
Bank Sta=4997.6,5001.6
Exp/Cntr=0.3,0.1

Type RM Length L Ch R = 1,1563,366,366,366
BEGIN DESCRIPTION:
MDW T 027 4.0
END DESCRIPTION:
XS GIS Cut Line= 3
      2294748.27      7104396.72      2294158.90      7104390.04
      2293714.41      7104421.46
#Sta/Elev= 30
  4410.6  794.24  4439.9  793.09  4479.9  792.64  4569.9  789.06  4619.9  787.73
  4649.9  787.53  4669.9  786.60  4789.9  784.81  4909.9  785.10  4939.9  784.61
  4959.9  783.64  4979.9  783.70  4989.9  780.92  4995.5  780.55  4995.7  780.05
  4999.2  780.05  4999.5  780.55  5002.5  780.55  5009.9  783.01  5020.0  783.62
  5040.0  783.38  5050.0  782.14  5060.1  782.02  5067.7  783.13  5072.7  781.60
  5080.1  783.70  5090.1  784.33  5120.2  785.32  5290.6  794.58  5445.6  801.95
#Mann=3,-1,0
  4410.6    0.05       0  4995.5    0.04       0  4999.5    0.05       0
Bank Sta=4995.5,4999.5
Exp/Cntr=0.3,0.1

Type RM Length L Ch R = 1,1197,429,429,429
BEGIN DESCRIPTION:
MDW T 027 3.0
END DESCRIPTION:
XS GIS Cut Line= 3
      2294792.53      7104059.48      2294108.90      7104040.04
      2293705.24      7104081.62
#Sta/Elev= 30
  4316.1  794.66  4329.6  794.67  4349.6  793.34  4429.7  790.26  4474.2  789.18
  4559.7  786.17  4599.7  785.34  4609.7  784.60  4639.8  783.70  4699.8  782.51
  4859.8  782.20  4939.9  780.23  4969.9  780.54  4989.9  778.97  4995.5  777.76
  4995.7  777.26  4999.2  777.26  4999.5  777.76  5010.0  778.00  5020.0  781.36
  5070.3  781.33  5110.5  782.99  5145.8  785.98  5150.9  785.73  5170.8  786.96
  5190.9  787.43  5211.0  788.76  5231.1  788.88  5321.6  792.12  5405.8  796.58
#Mann=3,-1,0
  4316.1    0.05       0  4995.5    0.04       0  4999.5    0.05       0
Bank Sta=4995.5,4999.5
Exp/Cntr=0.3,0.1

Type RM Length L Ch R = 1,768,285,285,285
BEGIN DESCRIPTION:
MDW T 027 2.0
END DESCRIPTION:
XS GIS Cut Line= 3
      2294578.95      7103710.00      2293982.99      7103658.35
      2293670.10      7103861.58
#Sta/Elev= 30
  4401.8  787.64  4522.2  783.92  4542.3  781.92  4582.4  780.13  4632.6  778.96
  4723.0  779.00  4773.1  776.45  4783.2  776.28  4802.7  777.63  4807.7  776.87
  4833.4  777.70  4903.6  776.13  4920.8  777.35  4925.8  776.60  4963.9  777.71
  4973.9  776.97  4983.9  771.17  4992.0  770.69  4992.2  770.19  4996.0  770.69
  4999.5  774.17  5005.4  774.17  5017.4  777.67  5026.6  778.50  5084.0  780.31
  5207.5  786.19  5243.2  786.81  5292.2  789.18  5337.7  790.21  5373.1  792.16
#Mann=3,-1,0
  4401.8    0.05       0  4992.0   0.033       0  4996.0    0.05       0
Bank Sta=4992,4996
Exp/Cntr=0.3,0.1

Type RM Length L Ch R = 1,483,281,281,281
BEGIN DESCRIPTION:
MDW T 027 1.0
END DESCRIPTION:
XS GIS Cut Line= 3
      2294399.28      7103450.10      2293878.92      7103410.03
      2293633.83      7103547.67
#Sta/Elev= 30
  4478.1  783.02  4528.5  781.73  4544.1  780.54  4668.9  776.12  4789.3  776.10
  4809.7  777.60  4839.4  777.60  4869.5  776.17  4935.0  775.65  4940.0  775.30
  4949.8  771.86  4959.8  770.83  4979.9  765.26  4987.9  764.43  4988.1  763.93
  4991.6  763.93  4991.9  764.43  4997.5  765.55  5022.8  766.33  5035.3  770.45
  5045.5  772.97  5051.3  775.87  5057.3  776.50  5116.3  779.78  5126.1  779.78
  5138.0  781.60  5183.4  784.96  5213.2  786.03  5234.9  785.91  5281.1  787.95
#Mann=3,-1,0
  4478.1    0.05       0  4987.9   0.033       0  4991.9    0.05       0
Bank Sta=4987.9,4991.9
Exp/Cntr=0.3,0.1

Type RM Length L Ch R = 1,202,0,0,0
BEGIN DESCRIPTION:
MDW T 027 0.5
END DESCRIPTION:
XS GIS Cut Line= 3
      2294377.14      7103175.15      2293856.30      7103136.09
      2293627.13      7103484.00
#Sta/Elev= 30
  4477.7  781.52  4536.0  780.85  4576.1  778.01  4666.4  776.91  4706.5  774.93
  4749.4  770.67  4766.6  770.30  4786.7  770.85  4816.8  770.27  4876.4  771.87
  4907.0  770.83  4957.2  772.61  4967.2  771.24  4977.2  768.24  4987.3  762.85
  4994.1  760.62  4994.4  760.12  4997.9  760.12  4998.1  760.62  5007.4  760.64
  5016.5  762.13  5022.5  773.27  5028.6  773.95  5073.7  774.70  5124.4  774.53
  5232.2  777.67  5275.5  780.43  5281.5  781.64  5317.6  785.08  5416.6  787.44
#Mann=3,-1,0
  4477.7    0.05       0  4994.1   0.033       0  4998.1    0.05       0
Bank Sta=4994.1,4998.1
Exp/Cntr=0.3,0.1

Chan Stop Cuts=-1