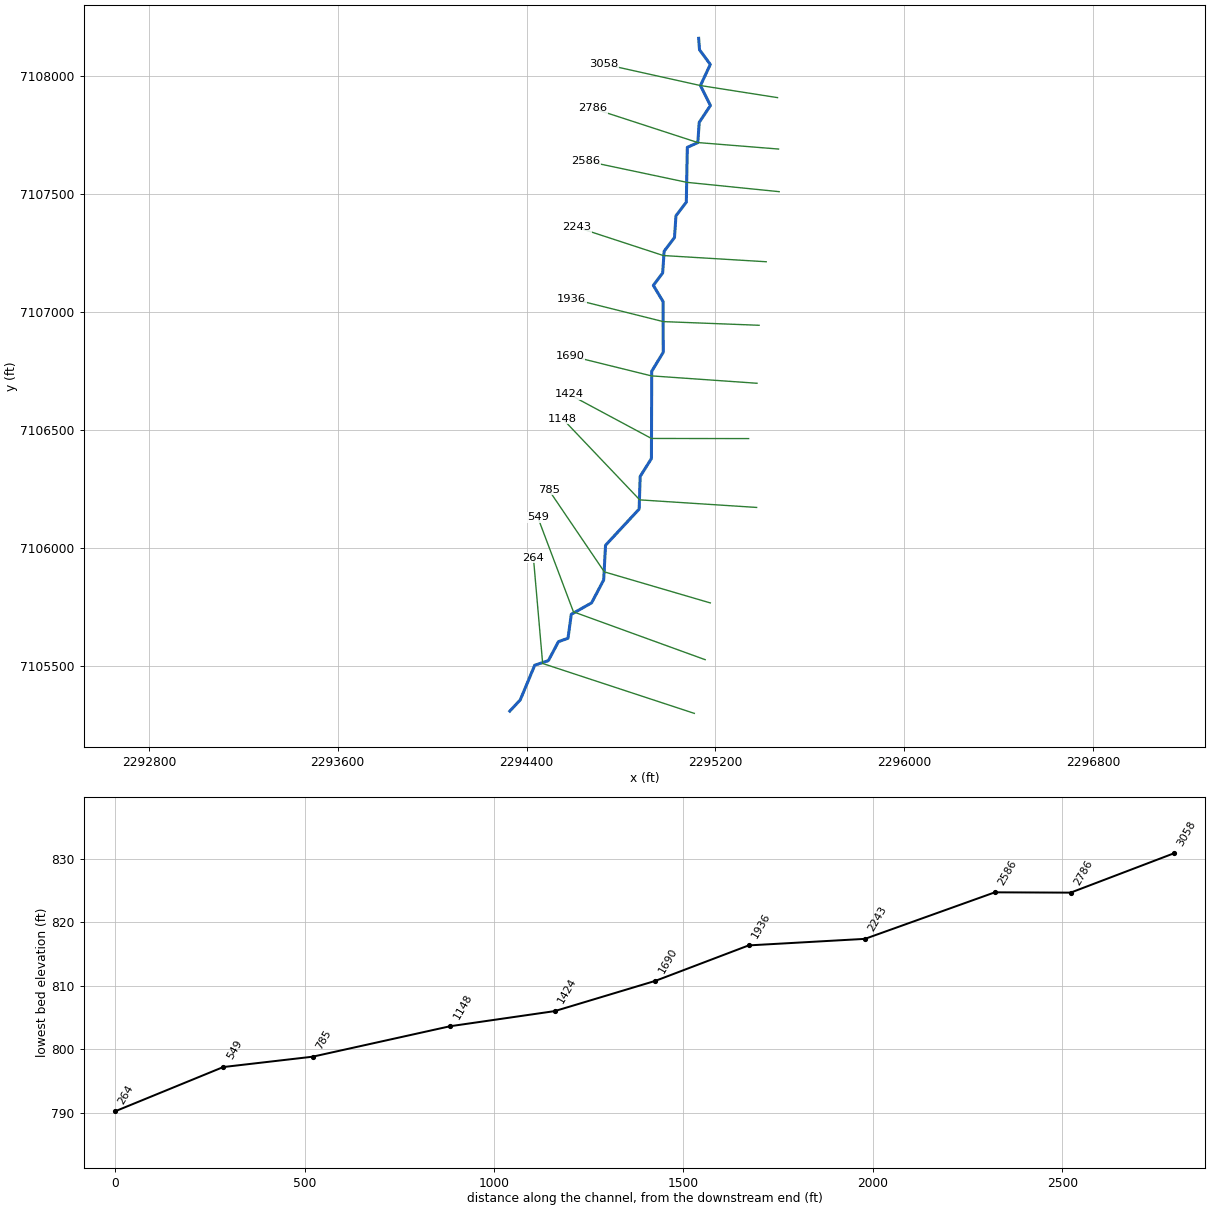
--- MDW T 028.prj (project) ---

Proj Title=MDW T 028 Base Level Engineering
Current Plan=p01
Default Exp/Contr=0.3,0.1
English Units
Geom File=g01
Flow File=f01
Plan File=p01
BEGIN DESCRIPTION:
MDW T 028
END DESCRIPTION:

--- MDW T 028.p01 (plan) ---

Plan Title=Multiple Run
Short Identifier=Multiple
Geom File=g01
Flow File=f01
Subcritical Flow
K Sum by GR= 0
Std Step Tol= 0.01
Critical Tol= 0.01
Num of Std Step Trials= 20
Max Error Tol= 0.3
Flow Tol Ratio= 0.001
Split Flow NTrial= 30
Split Flow Tol= 0.02
Split Flow Ratio= 0.02
Log Output Level= 0
Friction Slope Method= 1
Unsteady Friction Slope Method= 2
Unsteady Bridges Friction Slope Method= 1
Parabolic Critical Depth
Global Vel Dist=  1 , 1 , 1
Global Log Level= 0
CheckData=True
Encroach Param= -1, 0, 0, 0
BEGIN DESCRIPTION:
Multiple Run
END DESCRIPTION:

--- MDW T 028.f01 (steady flow) ---

Flow Title=Multiple
Number of Profiles=7
Profile Names=10-year,25-year,50-year,1pct_min,100-year,1pct_plu,500-year
River Rch & RM= MDW T 028,Reach-1,3058
     243     316     374     220     439     876     607
Boundary for River Rch & Prof#=MDW T 028,Reach-1,1
Up Type=0
Dn Type=3
Dn Slope=0.005
Boundary for River Rch & Prof#=MDW T 028,Reach-1,2
Up Type=0
Dn Type=3
Dn Slope=0.005
Boundary for River Rch & Prof#=MDW T 028,Reach-1,3
Up Type=0
Dn Type=3
Dn Slope=0.005
Boundary for River Rch & Prof#=MDW T 028,Reach-1,4
Up Type=0
Dn Type=3
Dn Slope=0.005
Boundary for River Rch & Prof#=MDW T 028,Reach-1,5
Up Type=0
Dn Type=3
Dn Slope=0.005
Boundary for River Rch & Prof#=MDW T 028,Reach-1,6
Up Type=0
Dn Type=3
Dn Slope=0.005
Boundary for River Rch & Prof#=MDW T 028,Reach-1,7
Up Type=0
Dn Type=3
Dn Slope=0.005

--- MDW T 028.g01 (geometry) ---

Geom Title=Existing Conditions

River Reach=MDW T 028,Reach-1
Reach XY= 30
      2295129.00      7108160.00      2295132.69      7108111.49
      2295178.33      7108049.31      2295136.62      7107960.00
      2295178.85      7107875.42      2295131.41      7107803.95
      2295125.44      7107718.50      2295080.96      7107698.03
      2295076.74      7107465.94      2295032.86      7107408.40
      2295026.65      7107315.97      2294982.85      7107258.40
      2294976.45      7107165.89      2294937.08      7107113.30
      2294978.34      7107044.84      2294978.93      7106830.03
      2294930.22      7106749.50      2294928.93      7106380.03
      2294881.27      7106304.06      2294876.93      7106165.86
      2294734.47      7106012.45      2294726.76      7105865.91
      2294675.47      7105768.49      2294589.45      7105720.04
      2294575.50      7105618.48      2294535.06      7105604.17
      2294492.31      7105523.64      2294434.62      7105504.38
      2294373.32      7105357.64      2294329.00      7105310.00

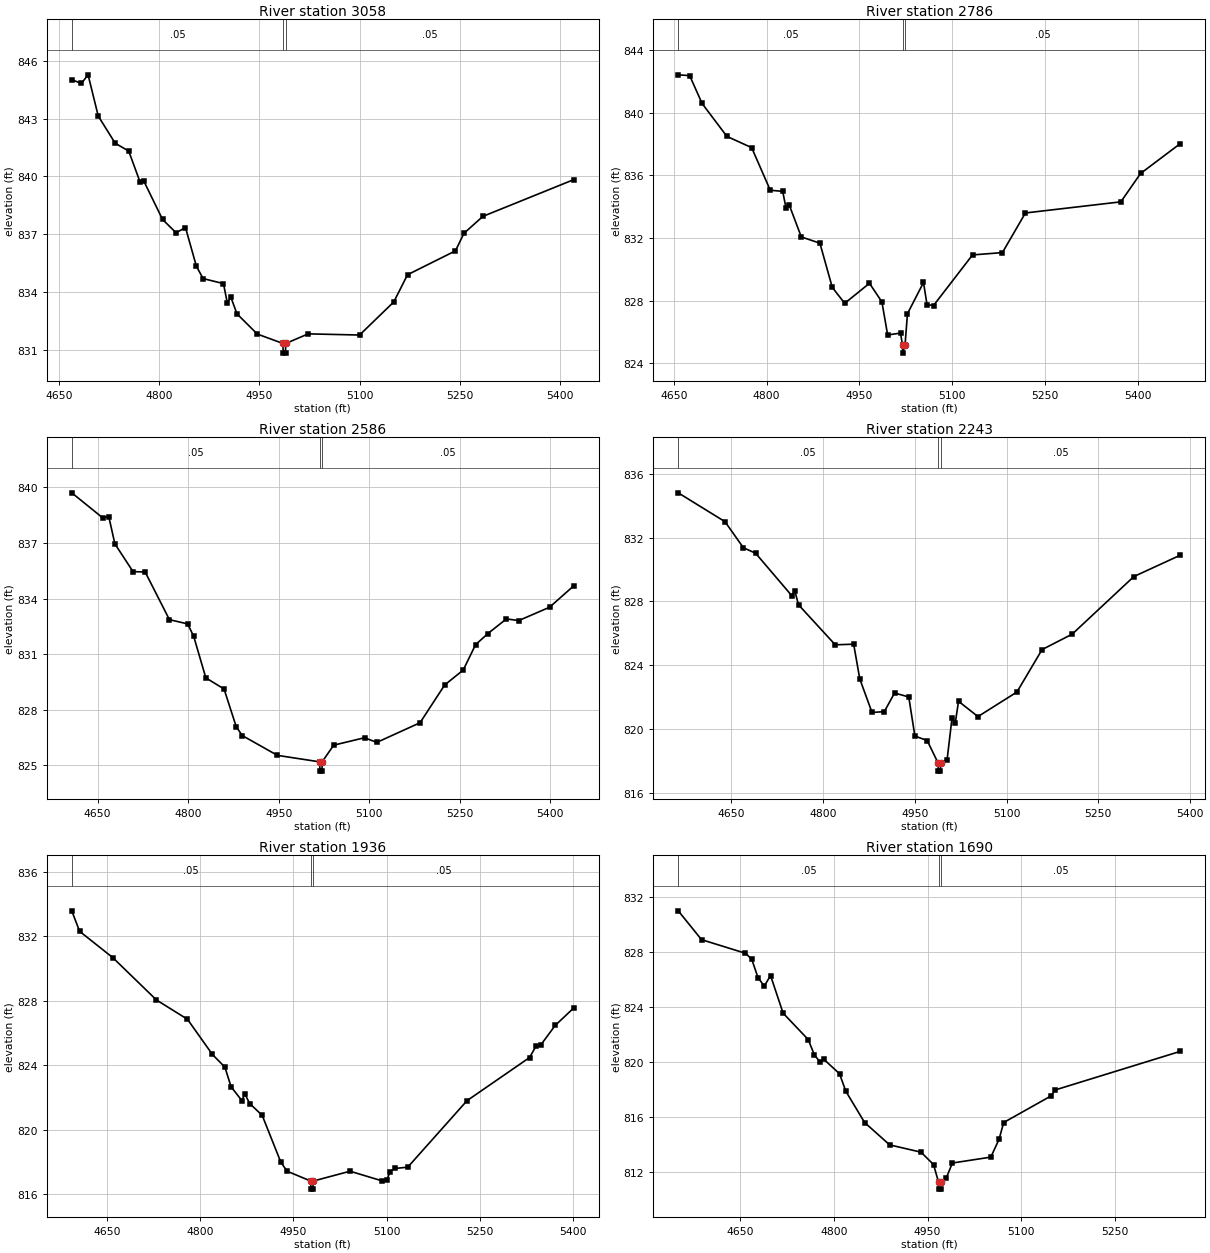
Type RM Length L Ch R = 1,3058,272,272,272
BEGIN DESCRIPTION:
MDW T 028 11.0
END DESCRIPTION:
XS GIS Cut Line= 3
      2295463.14      7107908.87      2295136.62      7107960.00
      2294726.14      7108051.23
#Sta/Elev= 30
  4669.5  845.02  4683.8  844.82  4693.9  845.27  4709.1  843.13  4734.4  841.72
  4754.7  841.31  4771.8  839.69  4776.9  839.78  4805.3  837.76  4825.5  837.07
  4839.6  837.34  4855.9  835.33  4866.0  834.69  4896.4  834.43  4902.2  833.42
  4907.3  833.74  4916.6  832.86  4947.0  831.81  4985.5  831.32  4985.7  830.82
  4989.2  830.82  4989.5  831.32  5023.1  831.82  5100.0  831.76  5151.2  833.48
  5171.7  834.89  5243.4  836.13  5256.1  837.04  5284.4  837.92  5420.5  839.83
#Mann=3,-1,0
  4669.5    0.05       0  4985.5    0.04       0  4989.5    0.05       0
Bank Sta=4985.5,4989.5
Exp/Cntr=0.3,0.1

Type RM Length L Ch R = 1,2786,200,200,200
BEGIN DESCRIPTION:
MDW T 028 10.0
END DESCRIPTION:
XS GIS Cut Line= 3
      2295467.44      7107690.99      2295125.44      7107718.50
      2294679.28      7107863.72
#Sta/Elev= 30
  4656.9  842.41  4675.4  842.36  4695.5  840.58  4735.6  838.48  4775.7  837.76
  4805.8  835.04  4825.9  834.97  4831.3  833.90  4836.3  834.12  4856.0  832.06
  4886.1  831.66  4906.1  828.84  4926.2  827.82  4966.3  829.10  4986.4  827.91
  4995.7  825.80  5016.5  825.92  5019.8  825.14  5020.0  824.64  5023.8  825.14
  5027.8  827.16  5053.7  829.15  5059.4  827.74  5069.9  827.68  5133.0  830.91
  5181.4  831.06  5218.6  833.59  5373.0  834.30  5404.9  836.11  5469.2  838.02
#Mann=3,-1,0
  4656.9    0.05       0  5019.8    0.04       0  5023.8    0.05       0
Bank Sta=5019.8,5023.8
Exp/Cntr=0.3,0.1

Type RM Length L Ch R = 1,2586,343,343,343
BEGIN DESCRIPTION:
MDW T 028 9.0
END DESCRIPTION:
XS GIS Cut Line= 3
      2295470.02      7107510.44      2295079.11      7107549.96
      2294649.68      7107640.65
#Sta/Elev= 30
  4607.1  839.70  4658.4  838.35  4668.4  838.42  4678.5  836.95  4708.6  835.45
  4728.7  835.43  4768.9  832.86  4799.1  832.63  4809.1  831.96  4829.2  829.72
  4859.4  829.12  4879.5  827.09  4889.5  826.61  4947.8  825.54  5017.9  825.19
  5018.2  824.69  5021.7  824.69  5021.9  825.19  5041.0  826.09  5092.1  826.49
  5112.5  826.24  5184.1  827.30  5225.0  829.34  5255.6  830.14  5276.1  831.51
  5296.5  832.11  5327.2  832.90  5347.6  832.81  5398.7  833.53  5438.9  834.69
#Mann=3,-1,0
  4607.1    0.05       0  5017.9    0.04       0  5021.9    0.05       0
Bank Sta=5017.9,5021.9
Exp/Cntr=0.3,0.1

Type RM Length L Ch R = 1,2243,307,307,307
BEGIN DESCRIPTION:
MDW T 028 8.0
END DESCRIPTION:
XS GIS Cut Line= 3
      2295415.34      7107213.56      2294979.23      7107239.90
      2294614.09      7107359.41
#Sta/Elev= 30
  4563.1  834.81  4639.6  833.00  4669.6  831.37  4689.7  831.02  4748.8  828.36
  4753.8  828.65  4759.8  827.79  4819.9  825.28  4850.0  825.32  4860.0  823.14
  4880.0  821.04  4900.1  821.09  4916.9  822.26  4940.1  822.01  4950.1  819.56
  4970.2  819.28  4988.2  817.86  4988.5  817.36  4992.0  817.36  4992.2  817.86
  5002.8  818.07  5010.8  820.68  5016.2  820.39  5021.5  821.74  5053.3  820.78
  5117.0  822.32  5158.1  824.98  5207.4  825.95  5308.2  829.56  5384.2  830.90
#Mann=3,-1,0
  4563.1    0.05       0  4988.2    0.04       0  4992.2    0.05       0
Bank Sta=4988.2,4992.2
Exp/Cntr=0.3,0.1

Type RM Length L Ch R = 1,1936,246,246,246
BEGIN DESCRIPTION:
MDW T 028 7.0
END DESCRIPTION:
XS GIS Cut Line= 3
      2295385.00      7106944.46      2294979.00      7106960.00
      2294589.88      7107057.30
#Sta/Elev= 30
  4593.8  833.57  4606.4  832.30  4659.8  830.67  4729.9  828.05  4779.9  826.85
  4820.0  824.67  4840.0  823.89  4850.0  822.67  4867.2  821.82  4872.2  822.22
  4880.0  821.63  4900.0  820.90  4930.0  818.00  4940.1  817.44  4978.1  816.83
  4978.3  816.33  4981.8  816.33  4982.1  816.83  5041.3  817.44  5092.9  816.84
  5100.6  816.90  5105.7  817.42  5113.5  817.61  5134.1  817.69  5229.4  821.81
  5329.9  824.48  5340.3  825.18  5348.0  825.26  5371.2  826.47  5401.2  827.56
#Mann=3,-1,0
  4593.8    0.05       0  4978.1    0.04       0  4982.1    0.05       0
Bank Sta=4978.1,4982.1
Exp/Cntr=0.3,0.1

Type RM Length L Ch R = 1,1690,266,266,266
BEGIN DESCRIPTION:
MDW T 028 6.0
END DESCRIPTION:
XS GIS Cut Line= 3
      2295376.25      7106698.81      2294928.64      7106730.15
      2294584.88      7106815.06
#Sta/Elev= 30
  4551.3  831.01  4588.6  828.91  4658.8  827.92  4668.8  827.49  4678.9  826.14
  4688.9  825.53  4698.9  826.30  4719.0  823.56  4759.1  821.64  4769.1  820.51
  4778.6  819.98  4783.6  820.22  4809.2  819.15  4819.2  817.88  4849.3  815.60
  4889.4  813.97  4939.5  813.44  4959.5  812.54  4967.6  811.25  4967.8  810.75
  4971.3  810.75  4971.6  811.25  4979.6  811.53  4989.6  812.65  5051.1  813.08
  5064.3  814.38  5071.7  815.60  5147.2  817.53  5154.1  817.97  5354.1  820.78
#Mann=3,-1,0
  4551.3    0.05       0  4967.6    0.04       0  4971.6    0.05       0
Bank Sta=4967.6,4971.6
Exp/Cntr=0.3,0.1

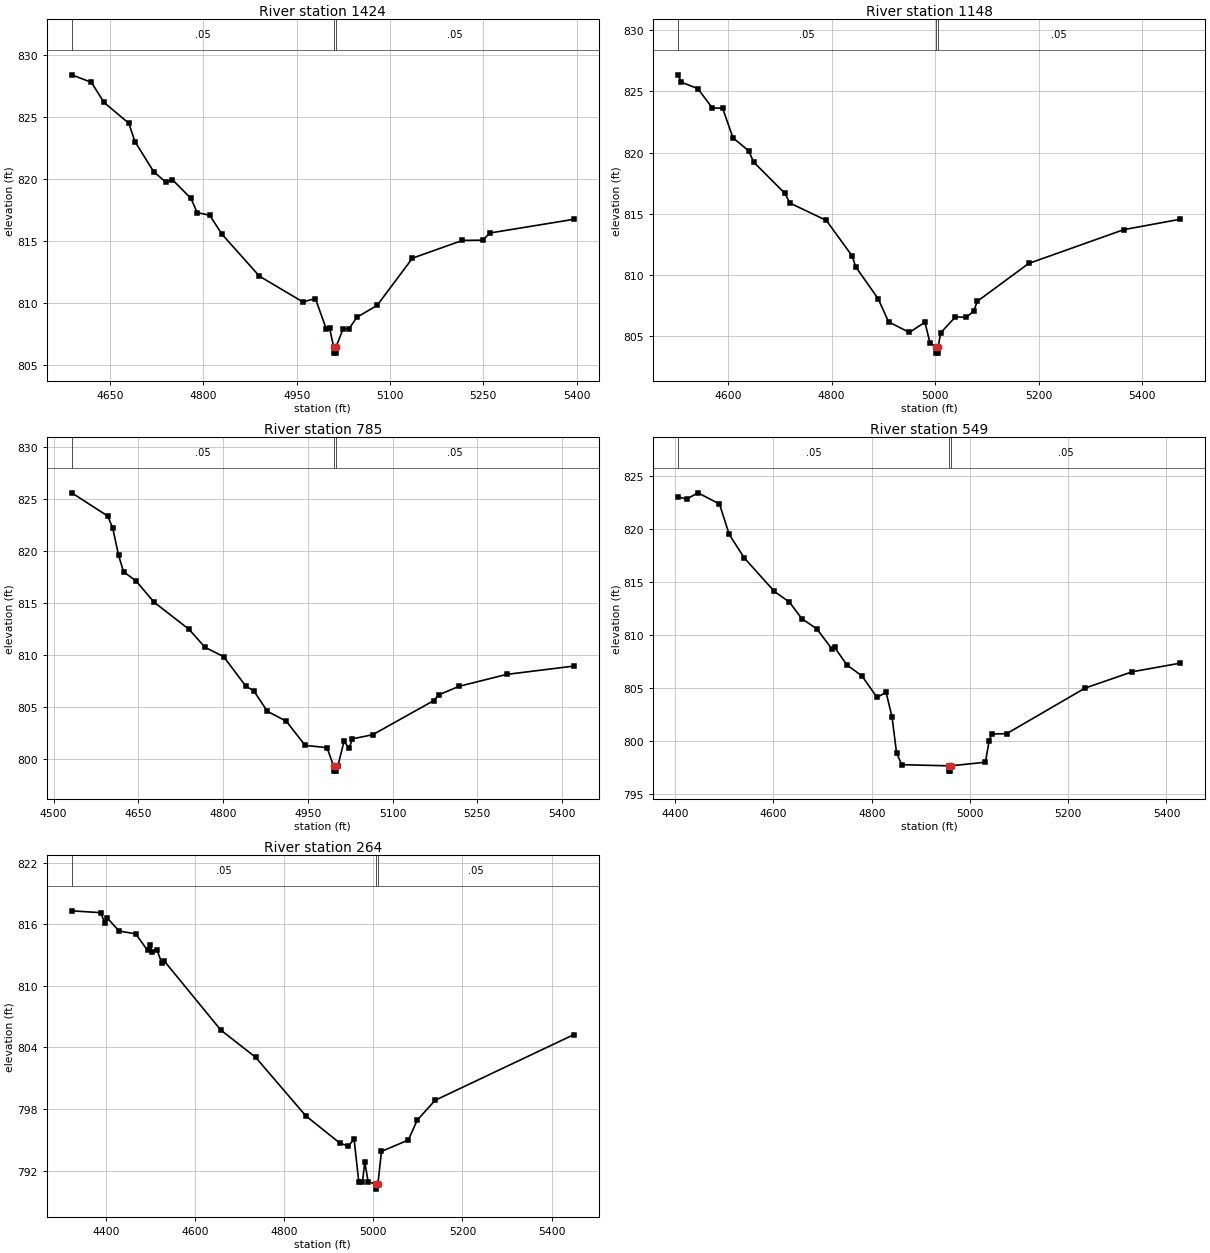
Type RM Length L Ch R = 1,1424,276,276,276
BEGIN DESCRIPTION:
MDW T 028 5.0
END DESCRIPTION:
XS GIS Cut Line= 3
      2295340.66      7106464.43      2294929.06      7106464.97
      2294580.30      7106651.92
#Sta/Elev= 30
  4588.4  828.40  4620.1  827.79  4640.1  826.18  4680.1  824.50  4690.1  823.01
  4720.1  820.60  4740.1  819.73  4750.1  819.96  4780.1  818.44  4790.1  817.30
  4810.1  817.09  4830.1  815.55  4890.1  812.18  4960.1  810.10  4980.1  810.38
  4997.5  807.94  5002.9  808.02  5009.4  806.48  5009.7  805.98  5013.2  805.98
  5013.4  806.48  5024.8  807.96  5034.1  807.93  5046.8  808.87  5079.3  809.82
  5136.2  813.63  5216.5  815.06  5249.0  815.08  5261.0  815.66  5395.7  816.76
#Mann=3,-1,0
  4588.4    0.05       0  5009.4    0.04       0  5013.4    0.05       0
Bank Sta=5009.4,5013.4
Exp/Cntr=0.3,0.1

Type RM Length L Ch R = 1,1148,363,363,363
BEGIN DESCRIPTION:
MDW T 028 4.0
END DESCRIPTION:
XS GIS Cut Line= 3
      2295374.58      7106172.76      2294879.42      7106204.83
      2294552.84      7106548.23
#Sta/Elev= 30
  4503.8  826.36  4509.4  825.76  4541.5  825.24  4569.5  823.66  4589.6  823.62
  4609.6  821.21  4639.7  820.15  4649.7  819.22  4709.8  816.67  4719.8  815.87
  4790.0  814.45  4840.1  811.53  4846.5  810.67  4890.2  808.04  4910.2  806.16
  4950.3  805.29  4980.4  806.13  4990.4  804.41  5002.0  804.10  5002.3  803.60
  5005.8  803.60  5006.0  804.10  5010.9  805.26  5039.3  806.56  5060.7  806.53
  5074.8  807.05  5081.7  807.84  5180.8  810.93  5364.8  813.70  5473.9  814.55
#Mann=3,-1,0
  4503.8    0.05       0  5002.0   0.033       0  5006.0    0.05       0
Bank Sta=5002,5006
Exp/Cntr=0.3,0.1

Type RM Length L Ch R = 1,785,236,236,236
BEGIN DESCRIPTION:
MDW T 028 3.0
END DESCRIPTION:
XS GIS Cut Line= 3
      2295178.42      7105768.23      2294729.41      7105899.83
      2294493.29      7106248.14
#Sta/Elev= 30
  4532.1  825.61  4595.5  823.38  4604.4  822.26  4614.9  819.60  4623.7  818.01
  4646.1  817.11  4677.4  815.09  4739.9  812.45  4767.7  810.74  4801.1  809.82
  4839.8  807.01  4854.5  806.51  4878.4  804.56  4911.8  803.61  4945.2  801.28
  4983.8  801.06  4995.6  799.30  4995.9  798.80  4999.4  798.80  4999.6  799.30
  5003.1  799.30  5014.0  801.67  5022.9  801.01  5028.9  801.91  5064.9  802.31
  5172.7  805.59  5181.4  806.14  5217.6  806.97  5302.2  808.12  5420.8  808.92
#Mann=3,-1,0
  4532.1    0.05       0  4995.6    0.04       0  4999.6    0.05       0
Bank Sta=4995.6,4999.6
Exp/Cntr=0.3,0.1

Type RM Length L Ch R = 1,549,285,285,285
BEGIN DESCRIPTION:
MDW T 028 2.0
END DESCRIPTION:
XS GIS Cut Line= 3
      2295156.70      7105527.78      2294598.57      7105730.48
      2294447.46      7106131.13
#Sta/Elev= 30
  4406.2  823.04  4423.5  822.84  4446.3  823.43  4490.1  822.38  4510.0  819.50
  4540.6  817.29  4601.8  814.13  4632.5  813.12  4657.7  811.56  4688.3  810.59
  4718.9  808.71  4724.3  808.86  4749.6  807.19  4780.2  806.15  4810.8  804.13
  4829.3  804.60  4841.4  802.28  4850.6  798.89  4861.2  797.78  4956.5  797.67
  4956.7  797.17  4960.2  797.17  4960.5  797.67  5031.5  798.01  5039.1  800.04
  5044.4  800.68  5074.6  800.70  5234.5  805.01  5330.8  806.55  5428.2  807.36
#Mann=3,-1,0
  4406.2    0.05       0  4956.5    0.04       0  4960.5    0.05       0
Bank Sta=4956.5,4960.5
Exp/Cntr=0.3,0.1

Type RM Length L Ch R = 1,264,0,0,0
BEGIN DESCRIPTION:
MDW T 028 1.0
END DESCRIPTION:
XS GIS Cut Line= 3
      2295110.67      7105300.36      2294468.12      7105511.66
      2294429.00      7105959.96
#Sta/Elev= 30
  4323.6  817.30  4388.5  817.12  4398.1  816.08  4403.4  816.59  4429.9  815.33
  4467.0  815.06  4493.5  813.46  4498.8  814.02  4504.3  813.26  4514.8  813.49
  4525.3  812.24  4530.6  812.44  4657.8  805.70  4735.9  803.05  4848.5  797.35
  4925.4  794.68  4943.9  794.40  4957.0  795.07  4967.5  790.92  4975.7  790.89
  4981.0  792.84  4988.5  790.92  5006.4  790.71  5006.6  790.21  5010.4  790.71
  5018.4  793.88  5078.6  794.99  5098.7  796.93  5138.9  798.86  5450.0  805.25
#Mann=3,-1,0
  4323.6    0.05       0  5006.4    0.04       0  5010.4    0.05       0
Bank Sta=5006.4,5010.4
Exp/Cntr=0.3,0.1

Chan Stop Cuts=-1