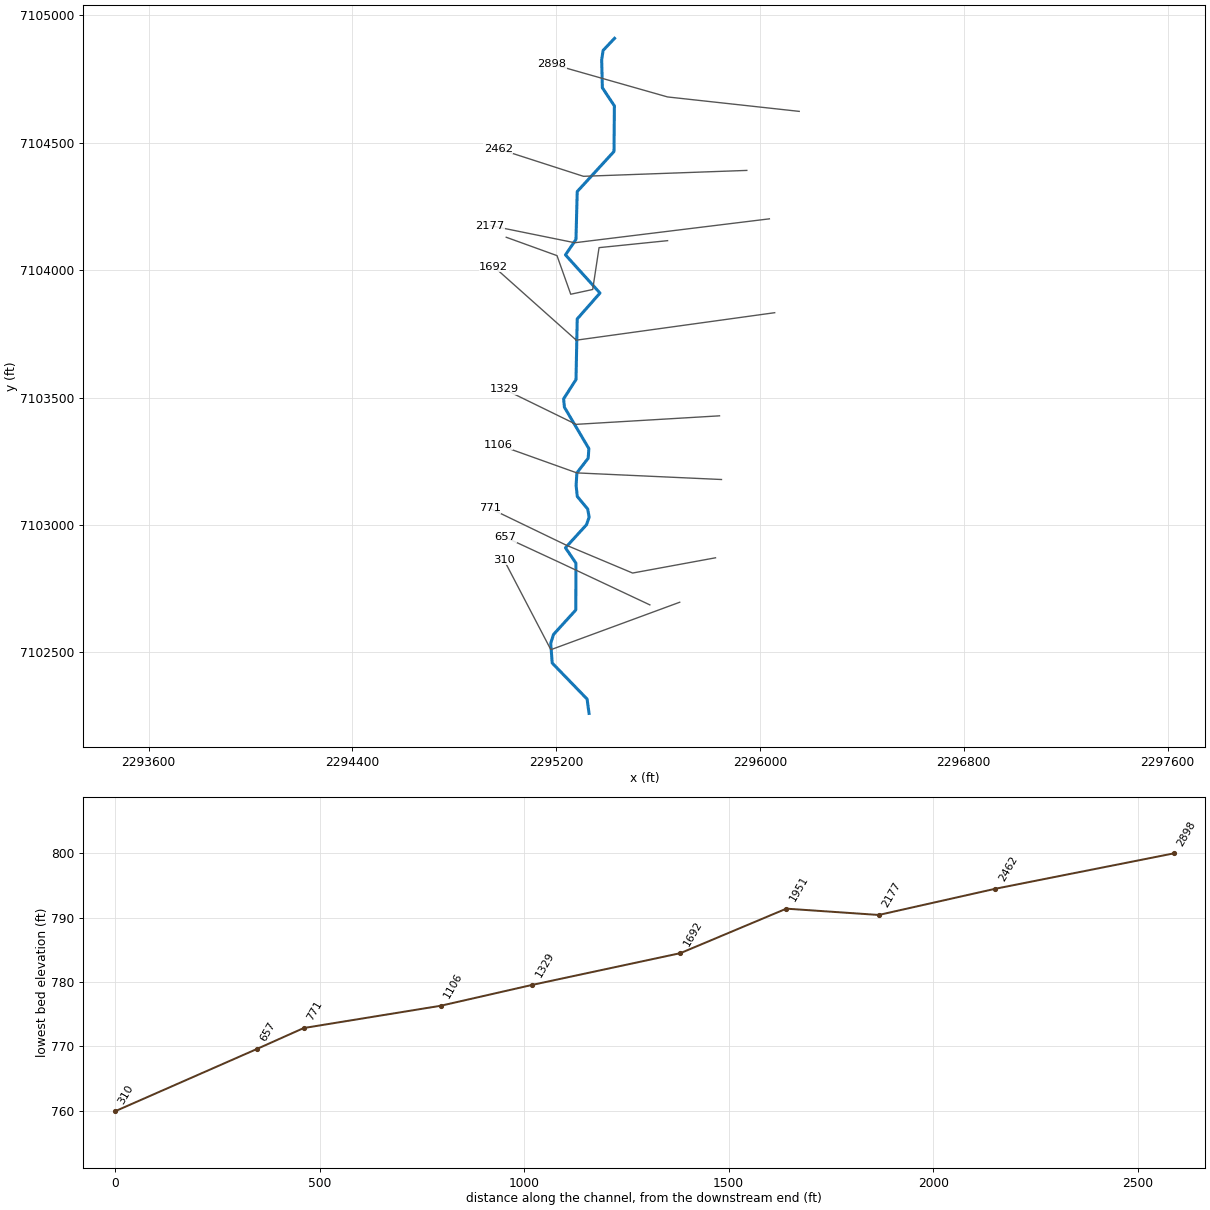
--- MDW T 029.prj (project) ---

Proj Title=MDW T 029 Base Level Engineering
Current Plan=p01
Default Exp/Contr=0.3,0.1
English Units
Geom File=g01
Flow File=f01
Plan File=p01
BEGIN DESCRIPTION:
MDW T 029
END DESCRIPTION:

--- MDW T 029.p01 (plan) ---

Plan Title=Multiple Run
Short Identifier=Multiple
Geom File=g01
Flow File=f01
Subcritical Flow
K Sum by GR= 0
Std Step Tol= 0.01
Critical Tol= 0.01
Num of Std Step Trials= 20
Max Error Tol= 0.3
Flow Tol Ratio= 0.001
Split Flow NTrial= 30
Split Flow Tol= 0.02
Split Flow Ratio= 0.02
Log Output Level= 0
Friction Slope Method= 1
Unsteady Friction Slope Method= 2
Unsteady Bridges Friction Slope Method= 1
Parabolic Critical Depth
Global Vel Dist=  1 , 1 , 1
Global Log Level= 0
CheckData=True
Encroach Param= -1, 0, 0, 0
BEGIN DESCRIPTION:
Multiple Run
END DESCRIPTION:

--- MDW T 029.f01 (steady flow) ---

Flow Title=Multiple
Number of Profiles=7
Profile Names=10-year,25-year,50-year,1pct_min,100-year,1pct_plu,500-year
River Rch & RM= MDW T 029,Reach-1,2898
     197     252     295     172     343     685     466
Boundary for River Rch & Prof#=MDW T 029,Reach-1,1
Up Type=0
Dn Type=3
Dn Slope=0.005
Boundary for River Rch & Prof#=MDW T 029,Reach-1,2
Up Type=0
Dn Type=3
Dn Slope=0.005
Boundary for River Rch & Prof#=MDW T 029,Reach-1,3
Up Type=0
Dn Type=3
Dn Slope=0.005
Boundary for River Rch & Prof#=MDW T 029,Reach-1,4
Up Type=0
Dn Type=3
Dn Slope=0.005
Boundary for River Rch & Prof#=MDW T 029,Reach-1,5
Up Type=0
Dn Type=3
Dn Slope=0.005
Boundary for River Rch & Prof#=MDW T 029,Reach-1,6
Up Type=0
Dn Type=3
Dn Slope=0.005
Boundary for River Rch & Prof#=MDW T 029,Reach-1,7
Up Type=0
Dn Type=3
Dn Slope=0.005

--- MDW T 029.g01 (geometry) ---

Geom Title=Existing Conditions

River Reach=MDW T 029,Reach-1
Reach XY= 30
      2295429.00      7104910.00      2295384.13      7104862.58
      2295378.55      7104825.15      2295381.25      7104715.94
      2295428.48      7104644.78      2295426.94      7104465.85
      2295282.54      7104308.54      2295277.61      7104120.43
      2295236.32      7104059.90      2295371.92      7103910.01
      2295282.56      7103808.54      2295277.76      7103570.50
      2295229.09      7103494.60      2295232.34      7103461.72
      2295328.25      7103299.32      2295325.63      7103261.74
      2295281.19      7103204.03      2295278.20      7103154.97
      2295282.74      7103111.58      2295323.64      7103062.17
      2295329.39      7103030.13      2295318.77      7103000.32
      2295236.33      7102910.10      2295277.61      7102849.57
      2295276.94      7102665.86      2295189.46      7102569.78
      2295178.50      7102535.03      2295184.40      7102457.57
      2295321.24      7102316.21      2295329.00      7102260.00

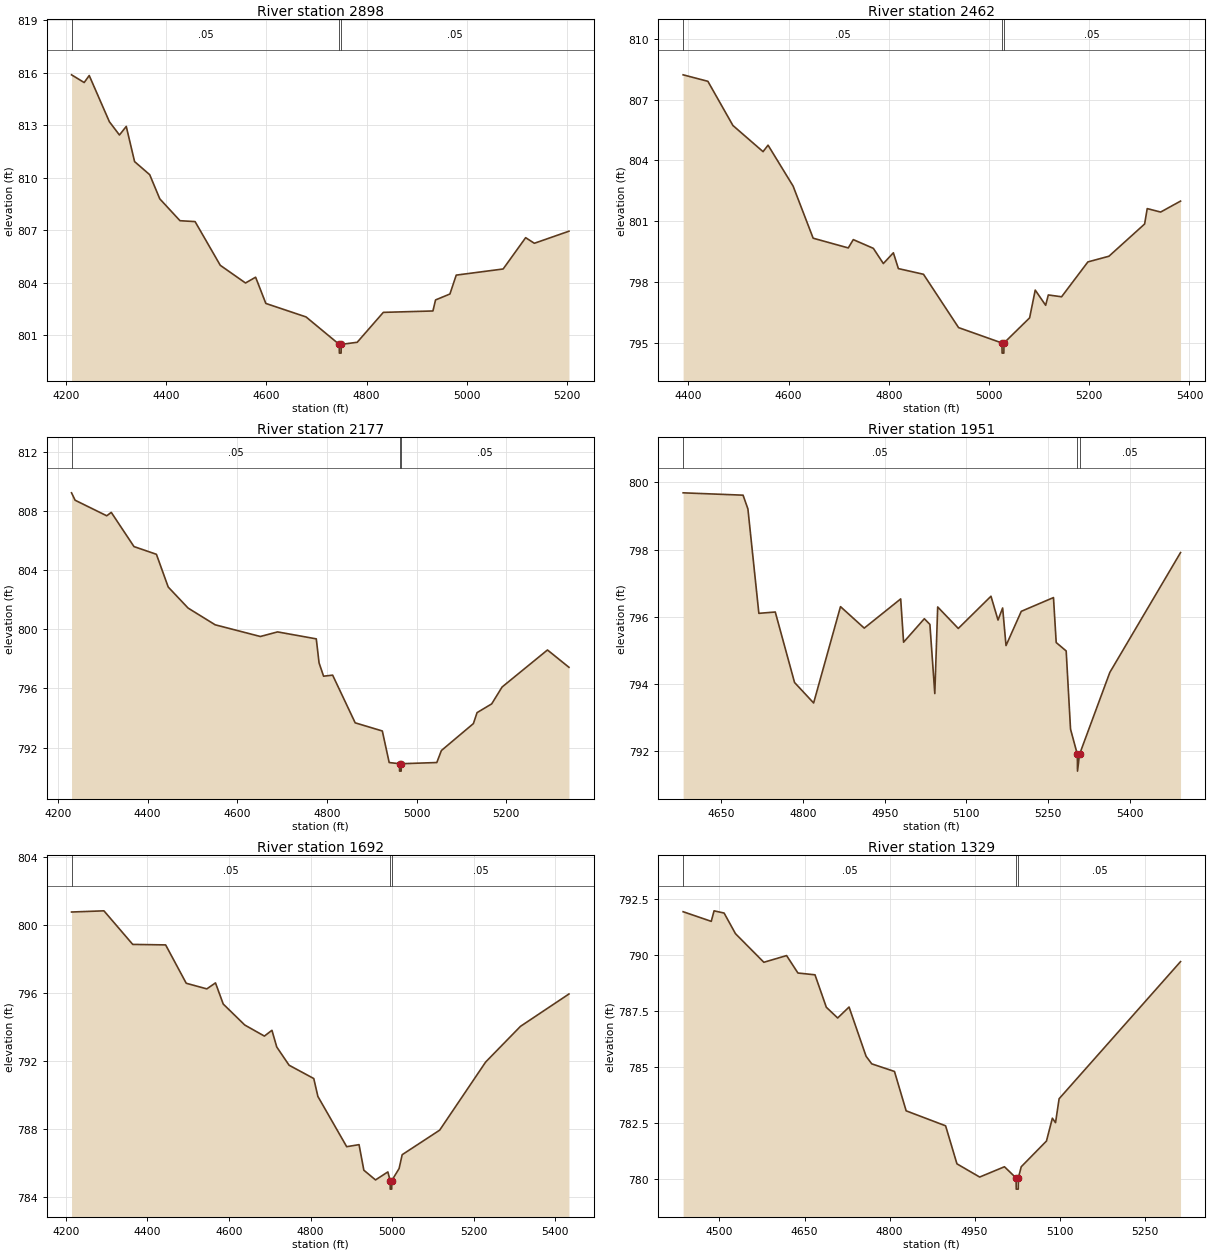
Type RM Length L Ch R = 1,2898,436,436,436
BEGIN DESCRIPTION:
MDW T 029 9.0
END DESCRIPTION:
XS GIS Cut Line= 3
      2296154.07      7104623.28      2295637.26      7104679.91
      2295182.67      7104809.12
#Sta/Elev= 30
  4211.1  815.89  4236.3  815.45  4246.4  815.85  4286.6  813.21  4306.7  812.45
  4320.3  812.94  4336.9  810.93  4367.1  810.18  4387.2  808.80  4427.5  807.55
  4457.6  807.50  4507.9  805.00  4558.2  803.99  4578.4  804.32  4598.8  802.82
  4679.0  802.05  4745.2  800.48  4745.5  799.98  4749.0  799.98  4749.2  800.48
  4781.1  800.60  4833.2  802.31  4932.2  802.39  4937.4  803.02  4966.1  803.36
  4978.7  804.44  5072.3  804.79  5117.2  806.58  5134.6  806.26  5203.6  806.95
#Mann=3,-1,0
  4211.1    0.05       0  4745.2   0.033       0  4749.2    0.05       0
Bank Sta=4745.2,4749.2
Exp/Cntr=0.3,0.1

Type RM Length L Ch R = 1,2462,285,285,285
BEGIN DESCRIPTION:
MDW T 029 8.0
END DESCRIPTION:
XS GIS Cut Line= 3
      2295948.36      7104391.51      2295306.95      7104368.37
      2294973.05      7104476.16
#Sta/Elev= 30
  4389.5  808.22  4438.9  807.90  4488.9  805.72  4549.0  804.43  4559.0  804.75
  4609.0  802.73  4649.0  800.16  4719.1  799.68  4729.1  800.09  4769.1  799.66
  4789.1  798.91  4809.1  799.44  4819.1  798.66  4869.2  798.38  4939.2  795.75
  5025.8  794.99  5026.1  794.49  5029.6  794.49  5029.8  794.99  5081.0  796.23
  5092.2  797.60  5113.0  796.85  5118.3  797.36  5144.8  797.27  5197.3  798.99
  5239.3  799.27  5310.5  800.86  5315.7  801.62  5342.5  801.45  5382.2  801.99
#Mann=3,-1,0
  4389.5    0.05       0  5025.8    0.04       0  5029.8    0.05       0
Bank Sta=5025.8,5029.8
Exp/Cntr=0.3,0.1

Type RM Length L Ch R = 1,2177,226,226,226
BEGIN DESCRIPTION:
MDW T 029 7.0
END DESCRIPTION:
XS GIS Cut Line= 3
      2296036.92      7104201.41      2295272.97      7104107.55
      2294940.17      7104175.17
#Sta/Elev= 30
  4230.3  809.21  4238.3  808.71  4308.8  807.66  4318.9  807.89  4369.6  805.58
  4419.6  805.06  4445.9  802.85  4490.2  801.43  4550.6  800.30  4651.4  799.51
  4689.8  799.82  4776.1  799.35  4782.3  797.73  4792.4  796.83  4812.6  796.90
  4862.9  793.68  4923.4  793.13  4938.7  791.00  4961.7  790.92  4961.9  790.42
  4965.4  790.42  4965.7  790.92  5044.9  791.00  5055.1  791.81  5126.5  793.63
  5134.7  794.37  5167.3  794.96  5190.5  796.10  5291.7  798.60  5339.6  797.43
#Mann=3,-1,0
  4230.3    0.05       0  4961.7   0.033       0  4965.7    0.05       0
Bank Sta=4961.7,4965.7
Exp/Cntr=0.3,0.1

Type RM Length L Ch R = 1,1951,259,259,259
BEGIN DESCRIPTION:
MDW T 029 6.5
END DESCRIPTION:
XS GIS Cut Line= 6
      2295637.28      7104115.76      2295368.24      7104088.32
      2295343.31      7103924.04      2295257.06      7103905.38
      2295203.16      7104057.00      2295003.86      7104129.07
#Sta/Elev= 30
  4580.1  799.69  4690.1  799.62  4699.0  799.21  4719.1  796.10  4749.2  796.14
  4784.6  794.04  4819.6  793.43  4868.9  796.30  4912.5  795.66  4979.4  796.53
  4984.7  795.24  5022.8  795.94  5033.0  795.77  5042.0  793.71  5047.3  796.29
  5085.1  795.65  5145.1  796.61  5158.0  795.90  5166.5  796.26  5172.7  795.14
  5200.7  796.16  5259.8  796.57  5264.8  795.23  5283.1  794.98  5291.1  792.65
  5303.6  791.90  5303.9  791.40  5307.6  791.90  5363.2  794.34  5493.0  797.91
#Mann=3,-1,0
  4580.1    0.05       0  5303.6   0.033       0  5307.6    0.05       0
Bank Sta=5303.6,5307.6
Exp/Cntr=0.3,0.1

Type RM Length L Ch R = 1,1692,363,363,363
BEGIN DESCRIPTION:
MDW T 029 6.0
END DESCRIPTION:
XS GIS Cut Line= 3
      2296057.73      7103832.92      2295278.86      7103725.06
      2294954.83      7104013.93
#Sta/Elev= 30
  4213.7  800.75  4293.2  800.82  4363.8  798.85  4444.6  798.82  4495.1  796.57
  4545.6  796.24  4566.9  796.59  4585.9  795.35  4638.7  794.12  4686.9  793.47
  4705.4  793.81  4717.2  792.83  4747.5  791.76  4808.0  790.98  4818.1  789.93
  4888.8  786.98  4919.1  787.10  4930.9  785.60  4959.5  785.03  4989.8  785.50
  4995.4  784.99  4995.7  784.49  4999.2  784.49  4999.4  784.99  5017.4  785.70
  5024.9  786.51  5116.9  787.95  5229.8  791.95  5315.1  794.04  5434.1  795.94
#Mann=3,-1,0
  4213.7    0.05       0  4995.4    0.04       0  4999.4    0.05       0
Bank Sta=4995.4,4999.4
Exp/Cntr=0.3,0.1

Type RM Length L Ch R = 1,1329,223,223,223
BEGIN DESCRIPTION:
MDW T 029 5.0
END DESCRIPTION:
XS GIS Cut Line= 3
      2295841.15      7103428.08      2295278.04      7103394.61
      2294996.53      7103532.13
#Sta/Elev= 30
  4435.9  791.95  4485.5  791.52  4490.5  791.99  4508.2  791.89  4528.2  790.97
  4578.3  789.69  4618.4  789.99  4638.4  789.21  4668.5  789.13  4688.5  787.68
  4708.5  787.20  4728.6  787.69  4758.6  785.49  4768.6  785.15  4808.7  784.81
  4829.3  783.05  4898.9  782.38  4918.9  780.68  4959.0  780.09  5002.7  780.55
  5023.2  780.05  5023.5  779.55  5027.0  779.55  5027.2  780.05  5032.3  780.55
  5076.8  781.70  5087.2  782.72  5092.8  782.52  5099.1  783.59  5313.3  789.72
#Mann=3,-1,0
  4435.9    0.05       0  5023.2    0.04       0  5027.2    0.05       0
Bank Sta=5023.2,5027.2
Exp/Cntr=0.3,0.1

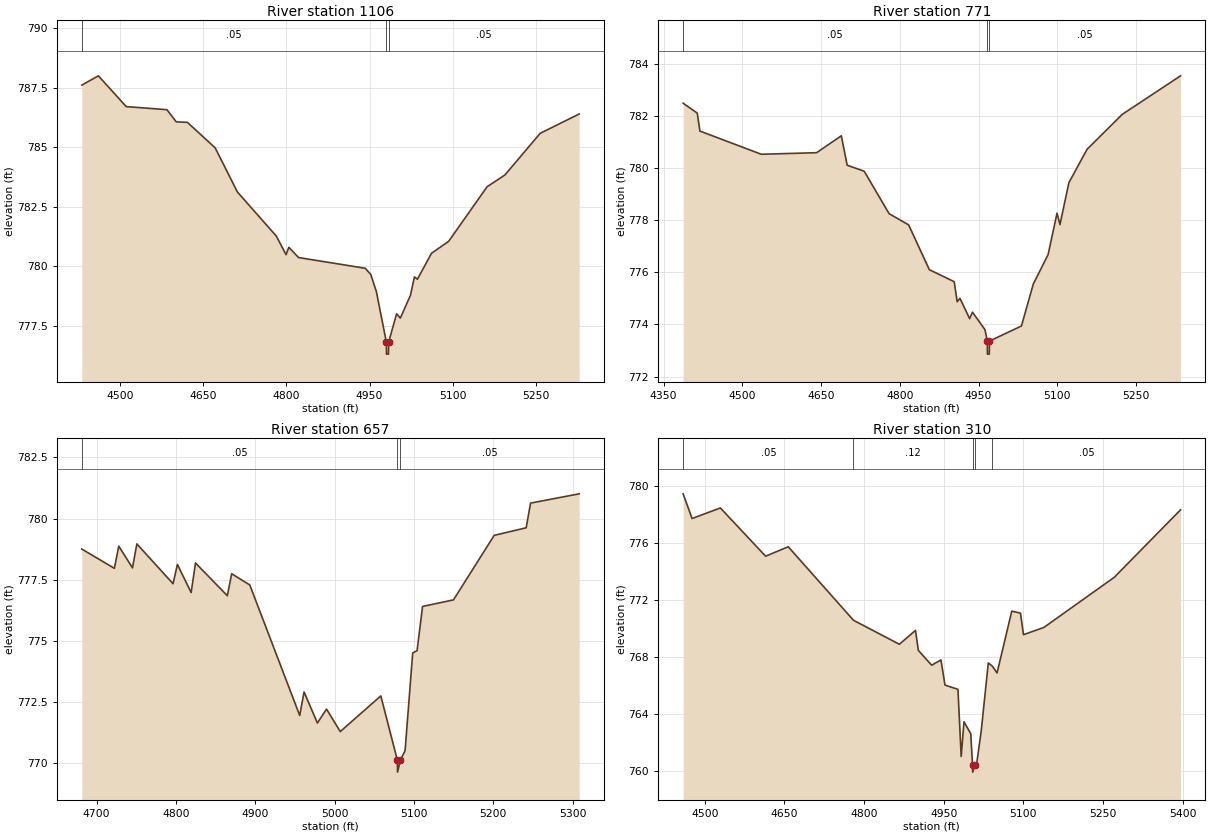
Type RM Length L Ch R = 1,1106,335,335,335
BEGIN DESCRIPTION:
MDW T 029 4.0
END DESCRIPTION:
XS GIS Cut Line= 3
      2295848.90      7103178.08      2295281.19      7103204.03
      2294972.91      7103314.28
#Sta/Elev= 30
  4431.7  787.60  4461.6  787.99  4511.7  786.70  4585.0  786.57  4601.8  786.06
  4621.8  786.04  4671.9  784.97  4711.9  783.12  4782.0  781.27  4799.6  780.49
  4804.6  780.80  4822.0  780.37  4942.1  779.92  4952.1  779.66  4962.2  778.94
  4980.2  776.82  4980.4  776.32  4983.9  776.32  4984.2  776.82  4998.6  778.01
  5005.3  777.83  5023.6  778.79  5030.7  779.56  5036.0  779.46  5061.5  780.55
  5092.3  781.05  5161.6  783.34  5193.5  783.83  5257.2  785.58  5327.4  786.39
#Mann=3,-1,0
  4431.7    0.05       0  4980.2    0.04       0  4984.2    0.05       0
Bank Sta=4980.2,4984.2
Exp/Cntr=0.3,0.1

Type RM Length L Ch R = 1,771,114,114,114
BEGIN DESCRIPTION:
MDW T 029 3.0
END DESCRIPTION:
XS GIS Cut Line= 4
      2295825.46      7102870.78      2295499.99      7102810.89
      2295240.12      7102920.05      2294938.60      7103065.56
#Sta/Elev= 30
  4387.2  782.49  4414.1  782.11  4419.2  781.42  4536.1  780.53  4641.5  780.59
  4688.6  781.24  4699.7  780.11  4732.1  779.88  4779.6  778.25  4816.8  777.82
  4856.3  776.10  4903.6  775.64  4909.3  774.87  4914.7  775.00  4933.0  774.22
  4938.4  774.47  4962.2  773.80  4966.7  773.36  4966.9  772.86  4970.4  772.86
  4970.7  773.36  5031.7  773.94  5054.3  775.55  5082.5  776.68  5099.5  778.27
  5105.1  777.83  5122.1  779.44  5156.7  780.72  5223.7  782.06  5334.8  783.54
#Mann=3,-1,0
  4387.2    0.05       0  4966.7    0.05       0  4970.7    0.05       0
Bank Sta=4966.7,4970.7
Exp/Cntr=0.3,0.1

Type RM Length L Ch R = 1,657,347,347,347
BEGIN DESCRIPTION:
MDW T 029 2.0
END DESCRIPTION:
XS GIS Cut Line= 3
      2295567.69      7102685.89      2295209.62      7102854.29
      2294999.96      7102951.53
#Sta/Elev= 30
  4681.4  778.75  4722.5  777.96  4728.0  778.87  4745.3  777.98  4750.8  778.96
  4796.4  777.33  4801.9  778.12  4819.2  776.97  4824.7  778.18  4864.8  776.84
  4870.3  777.74  4893.1  777.28  4956.0  771.94  4961.5  772.90  4978.3  771.63
  4989.8  772.20  5007.1  771.28  5058.2  772.74  5079.0  770.12  5079.3  769.62
  5083.0  770.12  5088.8  770.50  5098.4  774.50  5103.9  774.59  5110.8  776.40
  5149.8  776.67  5201.1  779.31  5241.4  779.62  5246.9  780.63  5308.2  781.01
#Mann=3,-1,0
  4681.4    0.05       0  5079.0    0.05       0  5083.0    0.05       0
Bank Sta=5079,5083
Exp/Cntr=0.3,0.1

Type RM Length L Ch R = 1,310,0,0,0
BEGIN DESCRIPTION:
MDW T 029 1.0
END DESCRIPTION:
XS GIS Cut Line= 3
      2295684.86      7102696.30      2295179.00      7102510.00
      2294994.80      7102862.94
#Sta/Elev= 30
  4459.1  779.44  4476.0  777.71  4529.3  778.45  4614.5  775.07  4657.2  775.73
  4780.1  770.58  4866.5  768.90  4896.9  769.87  4902.3  768.47  4927.4  767.43
  4944.9  767.80  4952.5  766.04  4976.9  765.74  4983.0  761.04  4988.3  763.47
  5001.0  762.63  5004.4  760.44  5004.7  759.94  5008.4  760.44  5012.0  760.48
  5020.7  762.81  5034.1  767.59  5041.8  767.36  5050.6  766.89  5078.3  771.22
  5094.7  771.08  5100.4  769.57  5138.9  770.08  5271.4  773.59  5396.3  778.32
#Mann=5,-1,0
  4459.1    0.05       0  4780.1    0.12       0  5004.4    0.07       0
  5008.4    0.12       0  5041.8    0.05       0
Bank Sta=5004.4,5008.4
Exp/Cntr=0.3,0.1

Chan Stop Cuts=-1