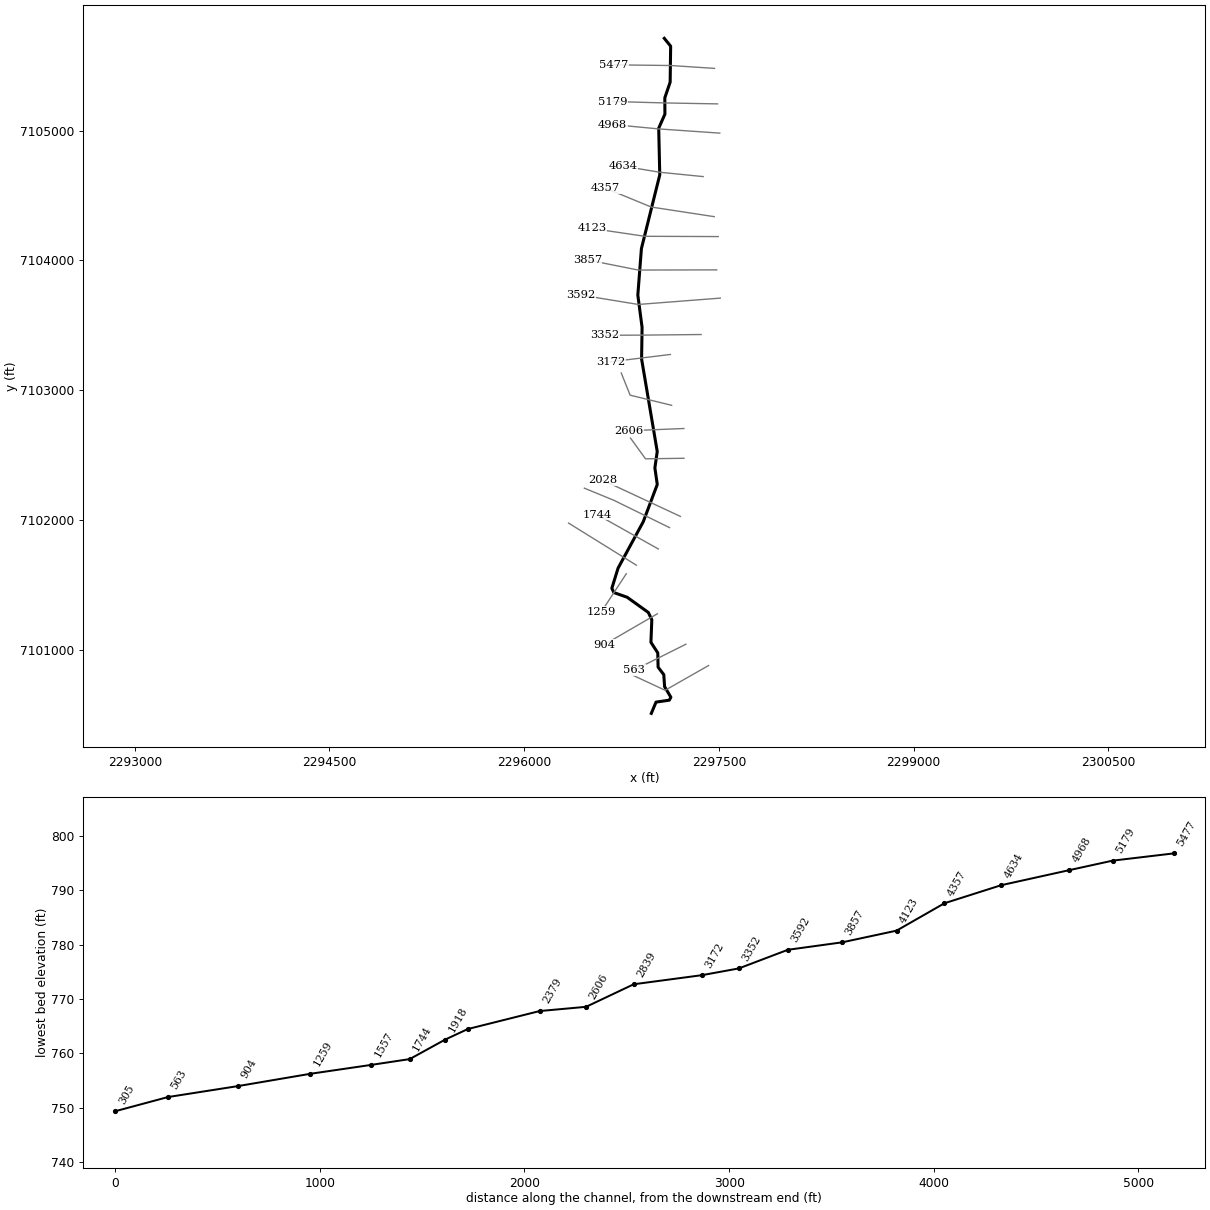
--- MDW T 030.prj (project) ---

Proj Title=MDW T 030 Base Level Engineering
Current Plan=p01
Default Exp/Contr=0.3,0.1
English Units
Geom File=g01
Flow File=f01
Plan File=p01
BEGIN DESCRIPTION:
MDW T 030
END DESCRIPTION:

--- MDW T 030.p01 (plan) ---

Plan Title=Multiple Run
Short Identifier=Multiple
Geom File=g01
Flow File=f01
Subcritical Flow
K Sum by GR= 0
Std Step Tol= 0.01
Critical Tol= 0.01
Num of Std Step Trials= 20
Max Error Tol= 0.3
Flow Tol Ratio= 0.001
Split Flow NTrial= 30
Split Flow Tol= 0.02
Split Flow Ratio= 0.02
Log Output Level= 0
Friction Slope Method= 1
Unsteady Friction Slope Method= 2
Unsteady Bridges Friction Slope Method= 1
Parabolic Critical Depth
Global Vel Dist=  1 , 1 , 1
Global Log Level= 0
CheckData=True
Encroach Param= -1, 0, 0, 0
BEGIN DESCRIPTION:
Multiple Run
END DESCRIPTION:

--- MDW T 030.f01 (steady flow) ---

Flow Title=Multiple
Number of Profiles=7
Profile Names=10-year,25-year,50-year,1pct_min,100-year,1pct_plu,500-year
River Rch & RM= MDW T 030,Reach-1,5477
     451     610     740     446     891    1777    1292
Boundary for River Rch & Prof#=MDW T 030,Reach-1,1
Up Type=0
Dn Type=3
Dn Slope=0.005
Boundary for River Rch & Prof#=MDW T 030,Reach-1,2
Up Type=0
Dn Type=3
Dn Slope=0.005
Boundary for River Rch & Prof#=MDW T 030,Reach-1,3
Up Type=0
Dn Type=3
Dn Slope=0.005
Boundary for River Rch & Prof#=MDW T 030,Reach-1,4
Up Type=0
Dn Type=3
Dn Slope=0.005
Boundary for River Rch & Prof#=MDW T 030,Reach-1,5
Up Type=0
Dn Type=3
Dn Slope=0.005
Boundary for River Rch & Prof#=MDW T 030,Reach-1,6
Up Type=0
Dn Type=3
Dn Slope=0.005
Boundary for River Rch & Prof#=MDW T 030,Reach-1,7
Up Type=0
Dn Type=3
Dn Slope=0.005

--- MDW T 030.g01 (geometry) ---

Geom Title=Existing Conditions

River Reach=MDW T 030,Reach-1
Reach XY= 30
      2297079.00      7105710.00      2297128.04      7105649.60
      2297124.19      7105372.15      2297083.18      7105252.26
      2297083.74      7105125.87      2297036.05      7105018.03
      2297044.10      7104657.96      2296902.80      7104090.32
      2296875.16      7103732.01      2296907.92      7103483.57
      2296904.21      7103239.37      2297024.65      7102527.45
      2297006.56      7102401.03      2297024.92      7102273.15
      2296917.01      7101986.42      2296723.02      7101628.78
      2296674.99      7101473.50      2296690.83      7101440.49
      2296792.74      7101404.67      2296955.93      7101287.48
      2296982.86      7101231.55      2296976.11      7101057.34
      2297028.88      7100975.88      2297031.27      7100865.94
      2297075.14      7100808.40      2297081.39      7100715.94
      2297129.61      7100634.69      2297117.80      7100611.73
      2297015.39      7100596.86      2296979.00      7100510.00

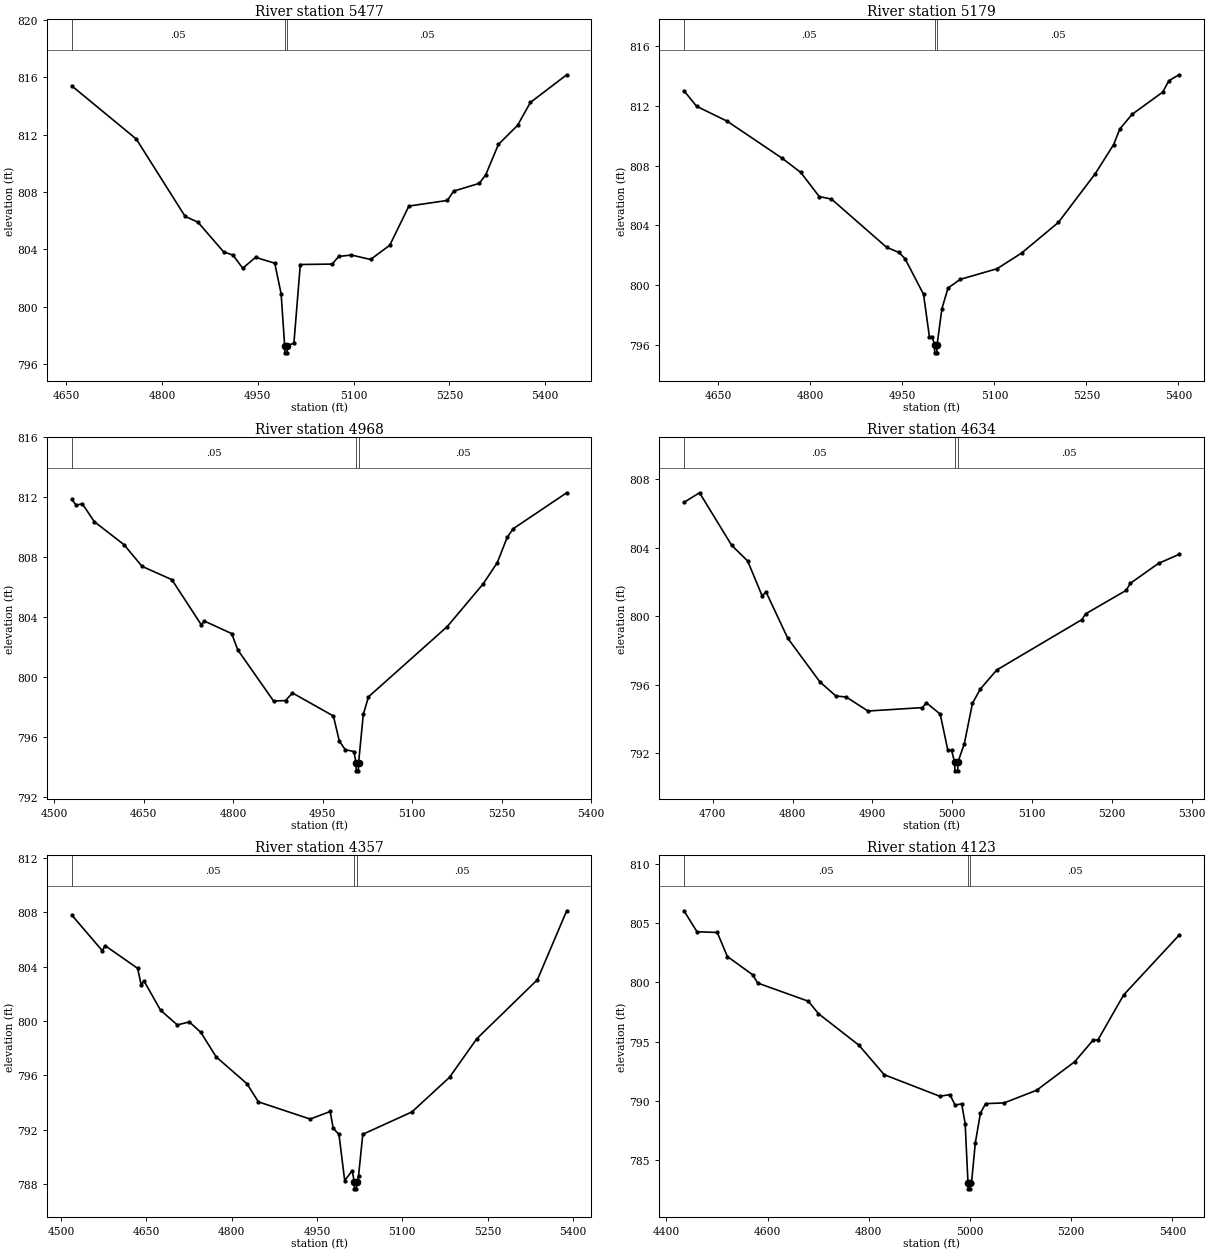
Type RM Length L Ch R = 1,5477,298,298,298
BEGIN DESCRIPTION:
MDW T 030 15.0
END DESCRIPTION:
XS GIS Cut Line= 3
      2297466.11      7105478.47      2297129.03      7105500.61
      2296692.06      7105505.79
#Sta/Elev= 30
  4658.7  815.39  4759.7  811.69  4836.2  806.30  4856.2  805.90  4896.3  803.84
  4911.2  803.60  4926.4  802.69  4946.4  803.45  4976.5  803.04  4986.5  800.91
  4992.0  797.30  4992.3  796.80  4995.8  796.80  4996.0  797.30  5006.5  797.47
  5016.5  802.95  5066.5  802.98  5076.5  803.51  5096.5  803.61  5126.5  803.30
  5156.5  804.29  5186.5  807.02  5246.6  807.41  5256.6  808.06  5296.6  808.60
  5306.6  809.18  5326.6  811.31  5356.6  812.64  5376.6  814.23  5433.5  816.16
#Mann=3,-1,0
  4658.7    0.05       0  4992.0   0.033       0  4996.0    0.05       0
Bank Sta=4992,4996
Exp/Cntr=0.3,0.1

Type RM Length L Ch R = 1,5179,211,211,211
BEGIN DESCRIPTION:
MDW T 030 14.0
END DESCRIPTION:
XS GIS Cut Line= 3
      2297489.59      7105205.03      2297084.75      7105212.33
      2296682.50      7105223.22
#Sta/Elev= 30
  4593.7  813.01  4614.3  811.97  4664.3  810.97  4754.3  808.48  4784.3  807.54
  4814.3  805.93  4834.3  805.76  4924.3  802.53  4944.3  802.19  4954.3  801.77
  4984.4  799.39  4994.0  796.55  4998.6  796.55  5002.4  795.97  5002.6  795.47
  5006.1  795.47  5006.4  795.97  5014.4  798.43  5024.4  799.81  5044.4  800.39
  5104.4  801.10  5144.4  802.15  5204.4  804.20  5264.5  807.46  5294.5  809.41
  5304.5  810.45  5324.5  811.43  5374.5  812.92  5384.5  813.68  5401.0  814.08
#Mann=3,-1,0
  4593.7    0.05       0  5002.4   0.033       0  5006.4    0.05       0
Bank Sta=5002.4,5006.4
Exp/Cntr=0.3,0.1

Type RM Length L Ch R = 1,4968,334,334,334
BEGIN DESCRIPTION:
MDW T 030 13.0
END DESCRIPTION:
XS GIS Cut Line= 3
      2297506.54      7104979.77      2297034.75      7105012.33
      2296679.67      7105046.18
#Sta/Elev= 30
  4529.6  811.85  4537.2  811.45  4547.2  811.57  4567.2  810.37  4617.4  808.82
  4647.4  807.38  4697.5  806.49  4746.7  803.48  4751.7  803.73  4797.8  802.89
  4807.8  801.81  4867.9  798.39  4888.0  798.42  4899.5  798.93  4968.2  797.39
  4978.2  795.70  4988.2  795.14  5002.5  795.02  5006.3  794.23  5006.5  793.73
  5010.0  793.73  5010.3  794.23  5018.3  797.50  5027.0  798.67  5159.0  803.36
  5219.2  806.21  5242.9  807.63  5259.4  809.31  5269.5  809.89  5359.2  812.29
#Mann=3,-1,0
  4529.6    0.05       0  5006.3   0.033       0  5010.3    0.05       0
Bank Sta=5006.3,5010.3
Exp/Cntr=0.3,0.1

Type RM Length L Ch R = 1,4634,277,277,277
BEGIN DESCRIPTION:
MDW T 030 12.0
END DESCRIPTION:
XS GIS Cut Line= 3
      2297378.37      7104644.96      2297044.83      7104678.35
      2296763.77      7104724.97
#Sta/Elev= 30
  4664.0  806.66  4683.5  807.22  4723.7  804.15  4743.8  803.23  4761.8  801.20
  4766.9  801.41  4794.0  798.71  4834.2  796.16  4854.3  795.33  4867.3  795.27
  4894.5  794.45  4962.7  794.65  4967.7  794.93  4985.0  794.27  4994.6  792.15
  4999.2  792.15  5003.1  791.45  5003.4  790.95  5006.9  790.95  5007.1  791.45
  5015.2  792.53  5025.4  794.90  5035.2  795.73  5055.8  796.85  5162.2  799.79
  5167.3  800.14  5218.0  801.51  5223.1  801.92  5258.5  803.09  5284.1  803.61
#Mann=3,-1,0
  4664.0    0.05       0  5003.1   0.033       0  5007.1    0.05       0
Bank Sta=5003.1,5007.1
Exp/Cntr=0.3,0.1

Type RM Length L Ch R = 1,4357,234,234,234
BEGIN DESCRIPTION:
MDW T 030 11.0
END DESCRIPTION:
XS GIS Cut Line= 3
      2297463.42      7104336.33      2296978.50      7104410.51
      2296627.44      7104555.01
#Sta/Elev= 30
  4519.0  807.81  4572.7  805.18  4577.7  805.55  4634.8  803.88  4641.1  802.67
  4646.2  802.94  4675.2  800.79  4704.6  799.71  4725.8  799.93  4746.0  799.16
  4773.0  797.35  4827.0  795.38  4847.2  794.04  4938.2  792.77  4973.4  793.33
  4978.7  792.09  4988.8  791.65  4998.9  788.24  5012.0  788.97  5015.9  788.13
  5016.1  787.63  5019.6  787.63  5019.9  788.13  5023.3  788.60  5030.7  791.65
  5117.2  793.30  5183.2  795.85  5231.1  798.69  5337.7  803.04  5389.2  808.12
#Mann=3,-1,0
  4519.0    0.05       0  5015.9   0.033       0  5019.9    0.05       0
Bank Sta=5015.9,5019.9
Exp/Cntr=0.3,0.1

Type RM Length L Ch R = 1,4123,266,266,266
BEGIN DESCRIPTION:
MDW T 030 10.0
END DESCRIPTION:
XS GIS Cut Line= 3
      2297494.83      7104182.90      2296928.82      7104185.07
      2296520.84      7104245.20
#Sta/Elev= 30
  4434.6  806.05  4460.4  804.28  4500.4  804.22  4520.4  802.19  4570.4  800.65
  4580.4  799.95  4680.4  798.42  4700.4  797.37  4780.4  794.71  4830.4  792.22
  4940.4  790.40  4960.4  790.54  4970.4  789.66  4983.5  789.76  4990.4  788.10
  4996.0  783.09  4996.3  782.59  4999.8  782.59  5000.0  783.09  5003.0  783.09
  5010.5  786.47  5020.6  788.97  5030.8  789.78  5067.4  789.84  5131.8  790.91
  5206.8  793.31  5243.0  795.12  5253.1  795.17  5303.7  798.95  5413.0  803.98
#Mann=3,-1,0
  4434.6    0.05       0  4996.0   0.033       0  5000.0    0.05       0
Bank Sta=4996,5000
Exp/Cntr=0.3,0.1

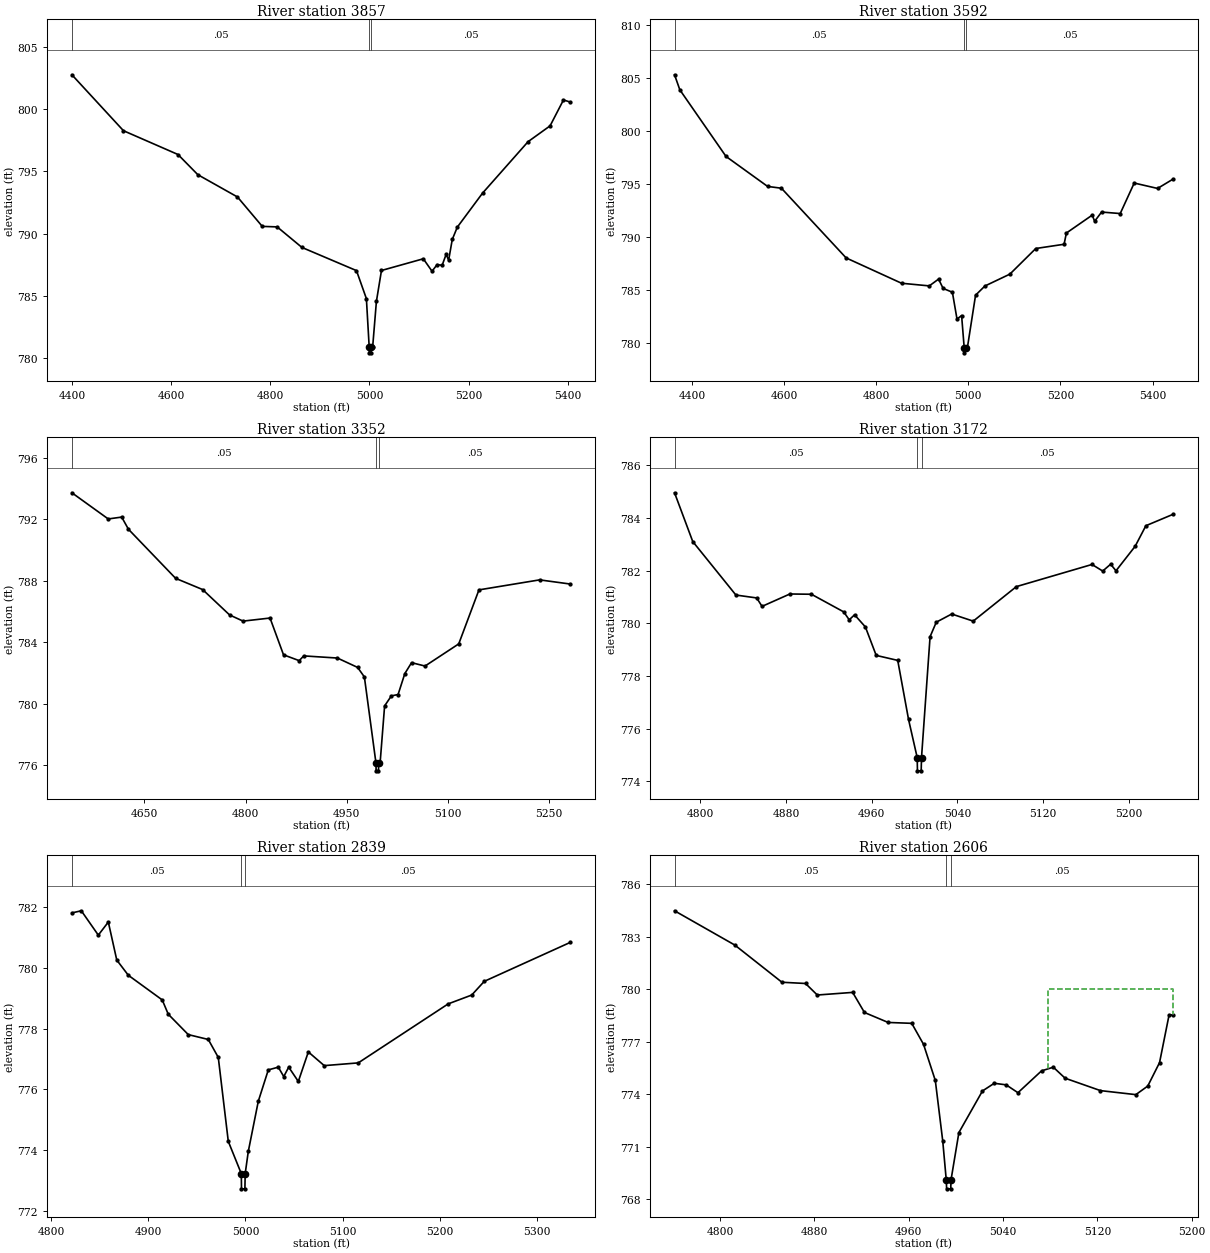
Type RM Length L Ch R = 1,3857,265,265,265
BEGIN DESCRIPTION:
MDW T 030 9.0
END DESCRIPTION:
XS GIS Cut Line= 3
      2297483.04      7103926.39      2296878.86      7103925.06
      2296485.63      7104003.22
#Sta/Elev= 30
  4399.8  802.76  4503.8  798.27  4613.8  796.36  4653.8  794.74  4733.8  792.95
  4783.8  790.59  4813.8  790.55  4863.8  788.90  4973.8  787.04  4993.8  784.79
  4999.4  780.94  4999.7  780.44  5003.2  780.44  5003.4  780.94  5006.5  780.94
  5014.0  784.57  5024.2  787.05  5108.6  787.99  5126.2  786.99  5136.4  787.52
  5146.6  787.47  5154.6  788.34  5159.7  787.88  5167.0  789.54  5177.2  790.53
  5228.1  793.26  5319.9  797.39  5364.3  798.66  5391.3  800.74  5404.9  800.57
#Mann=3,-1,0
  4399.8    0.05       0  4999.4   0.033       0  5003.4    0.05       0
Bank Sta=4999.4,5003.4
Exp/Cntr=0.3,0.1

Type RM Length L Ch R = 1,3592,240,240,240
BEGIN DESCRIPTION:
MDW T 030 8.0
END DESCRIPTION:
XS GIS Cut Line= 3
      2297510.45      7103708.94      2296878.92      7103659.97
      2296436.23      7103732.37
#Sta/Elev= 30
  4362.1  805.32  4373.6  803.90  4473.9  797.61  4564.2  794.78  4594.2  794.61
  4734.7  788.03  4855.0  785.64  4915.2  785.39  4935.4  786.03  4945.3  785.15
  4965.4  784.79  4975.4  782.26  4985.4  782.59  4991.0  779.57  4991.2  779.07
  4995.0  779.57  4998.0  779.57  5015.7  784.51  5036.0  785.38  5090.2  786.50
  5146.5  788.92  5207.9  789.32  5212.9  790.38  5269.0  792.07  5274.3  791.49
  5289.3  792.36  5329.8  792.22  5360.2  795.10  5410.9  794.59  5444.1  795.46
#Mann=3,-1,0
  4362.1    0.05       0  4991.0   0.033       0  4995.0    0.05       0
Bank Sta=4991,4995
Exp/Cntr=0.3,0.1

Type RM Length L Ch R = 1,3352,180,180,180
BEGIN DESCRIPTION:
MDW T 030 7.0
END DESCRIPTION:
XS GIS Cut Line= 3
      2297362.94      7103428.43      2296905.63      7103423.76
      2296623.57      7103422.60
#Sta/Elev= 30
  4542.3  793.71  4596.2  792.01  4616.2  792.13  4626.2  791.34  4696.2  788.15
  4736.3  787.42  4776.3  785.77  4796.3  785.37  4836.3  785.57  4856.3  783.18
  4879.6  782.80  4886.3  783.11  4936.3  782.97  4966.3  782.36  4976.3  781.74
  4993.5  776.14  4993.7  775.64  4997.2  775.64  4997.5  776.14  4999.6  776.14
  5006.3  779.86  5016.3  780.51  5026.3  780.60  5036.3  781.96  5046.3  782.67
  5066.3  782.45  5116.3  783.89  5146.3  787.40  5236.3  788.05  5281.7  787.78
#Mann=3,-1,0
  4542.3    0.05       0  4993.5   0.033       0  4997.5    0.05       0
Bank Sta=4993.5,4997.5
Exp/Cntr=0.3,0.1

Type RM Length L Ch R = 1,3172,333,333,333
BEGIN DESCRIPTION:
Mapping XS 5aa44b20
END DESCRIPTION:
XS GIS Cut Line= 2
      2297125.87      7103274.86      2296664.04      7103218.20
#Sta/Elev= 30
  4775.9  784.95  4792.9  783.10  4833.2  781.07  4852.6  780.96  4857.6  780.64
  4883.6  781.11  4903.7  781.10  4933.9  780.43  4939.0  780.13  4944.0  780.32
  4954.1  779.86  4964.2  778.78  4984.3  778.59  4994.4  776.35  5002.5  774.90
  5002.7  774.40  5006.2  774.40  5006.5  774.90  5014.5  779.49  5020.3  780.04
  5034.7  780.35  5054.8  780.08  5095.1  781.39  5165.7  782.23  5175.7  781.98
  5183.1  782.24  5188.1  781.99  5206.0  782.92  5216.0  783.70  5241.2  784.13
#Mann=3,-1,0
  4775.9    0.05       0  5002.5   0.033       0  5006.5    0.05       0
Bank Sta=5002.5,5006.5
Exp/Cntr=0.3,0.1

Type RM Length L Ch R = 1,2839,233,233,233
BEGIN DESCRIPTION:
Mapping XS 602ae454
END DESCRIPTION:
XS GIS Cut Line= 3
      2297135.41      7102883.20      2296816.07      7102961.12
      2296747.46      7103132.16
#Sta/Elev= 30
  4821.3  781.80  4831.0  781.87  4848.5  781.07  4858.8  781.50  4867.5  780.25
  4879.4  779.75  4914.3  778.94  4920.5  778.47  4941.1  777.80  4961.7  777.64
  4972.0  777.05  4982.3  774.29  4995.7  773.23  4995.9  772.73  4999.4  772.73
  4999.7  773.23  5002.9  773.96  5013.2  775.61  5023.5  776.64  5033.8  776.73
  5039.4  776.42  5044.5  776.73  5054.4  776.26  5064.7  777.23  5081.1  776.78
  5116.1  776.87  5208.7  778.81  5232.9  779.10  5245.8  779.55  5334.3  780.83
#Mann=3,-1,0
  4821.3    0.05       0  4995.7   0.033       0  4999.7    0.05       0
Bank Sta=4995.7,4999.7
Exp/Cntr=0.3,0.1

Type RM Length L Ch R = 1,2606,227,227,227
BEGIN DESCRIPTION:
Mapping XS daf0fb56
END DESCRIPTION:
XS GIS Cut Line= 2
      2297230.01      7102704.53      2296807.68      7102686.92
#Sta/Elev= 30
  4761.3  784.49  4812.4  782.53  4852.4  780.40  4872.4  780.33  4882.4  779.67
  4912.4  779.82  4922.4  778.67  4942.5  778.10  4962.5  778.05  4972.5  776.85
  4982.5  774.78  4988.8  771.32  4991.8  769.08  4992.1  768.58  4995.6  768.58
  4995.8  769.08  5002.5  771.80  5022.5  774.18  5032.5  774.62  5042.6  774.53
  5052.6  774.08  5072.6  775.33  5082.6  775.54  5092.6  774.91  5122.6  774.20
  5152.6  773.97  5162.7  774.46  5172.7  775.80  5180.8  778.53  5184.0  778.53
#Mann=3,-1,0
  4761.3    0.05       0  4991.8   0.033       0  4995.8    0.05       0
#XS Ineff=2,0
       0                 5077.80    0.00  779.99
Permanent Ineff=
       F       F
Bank Sta=4991.8,4995.8
Exp/Cntr=0.3,0.1

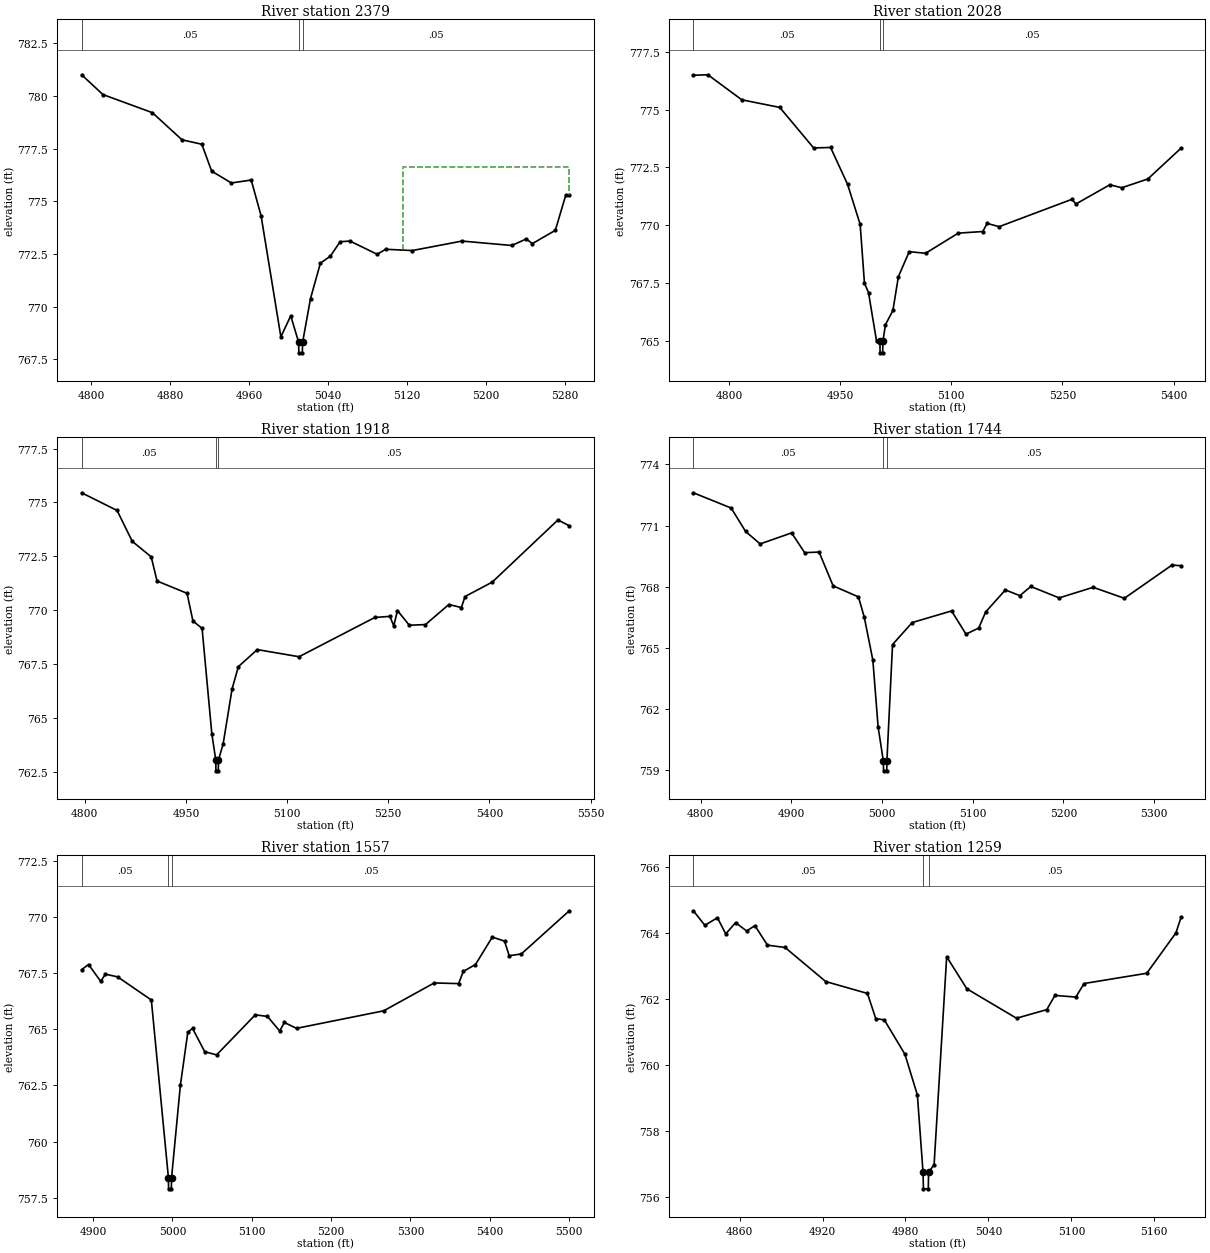
Type RM Length L Ch R = 1,2379,351,351,351
BEGIN DESCRIPTION:
Mapping XS a7e360b8
END DESCRIPTION:
XS GIS Cut Line= 3
      2297230.55      7102475.12      2296934.24      7102470.92
      2296818.80      7102630.63
#Sta/Elev= 30
  4790.6  781.01  4812.2  780.07  4862.2  779.21  4892.2  777.92  4912.2  777.71
  4922.2  776.43  4942.2  775.87  4962.2  776.01  4972.2  774.31  4992.2  768.56
  5002.2  769.56  5010.2  768.30  5010.4  767.80  5013.9  767.80  5014.2  768.30
  5022.2  770.38  5032.2  772.06  5042.2  772.39  5052.2  773.08  5062.2  773.11
  5089.7  772.48  5098.1  772.72  5125.2  772.66  5175.5  773.11  5225.8  772.90
  5240.5  773.21  5246.7  772.99  5269.9  773.62  5280.5  775.30  5284.0  775.30
#Mann=3,-1,0
  4790.6    0.05       0  5010.2   0.033       0  5014.2    0.05       0
#XS Ineff=2,0
       0                 5115.90    0.00  776.63
Permanent Ineff=
       F       F
Bank Sta=5010.2,5014.2
Exp/Cntr=0.3,0.1

Type RM Length L Ch R = 1,2028,110,110,110
BEGIN DESCRIPTION:
Mapping XS aa0e7546
END DESCRIPTION:
XS GIS Cut Line= 2
      2297203.04      7102027.32      2296606.47      7102305.40
#Sta/Elev= 30
  4751.9  776.48  4771.5  776.50  4817.2  775.42  4868.5  775.09  4914.2  773.34
  4937.1  773.36  4960.0  771.77  4977.0  770.04  4982.8  767.50  4988.3  767.09
  4999.1  765.00  5003.7  764.99  5003.9  764.49  5007.4  764.49  5007.7  764.99
  5011.2  765.71  5021.2  766.32  5028.6  767.78  5043.2  768.86  5065.3  768.79
  5109.4  769.66  5142.5  769.73  5148.4  770.08  5164.6  769.94  5262.7  771.12
  5268.3  770.92  5314.0  771.75  5330.1  771.62  5365.3  772.00  5410.1  773.33
#Mann=3,-1,0
  4751.9    0.05       0  5003.7    0.04       0  5007.7    0.05       0
Bank Sta=5003.7,5007.7
Exp/Cntr=0.3,0.1

Type RM Length L Ch R = 1,1918,174,174,174
BEGIN DESCRIPTION:
Mapping XS 11f5675a
END DESCRIPTION:
XS GIS Cut Line= 3
      2297119.41      7101940.90      2296690.56      7102151.39
      2296463.42      7102244.76
#Sta/Elev= 30
  4795.2  775.45  4847.8  774.63  4870.3  773.20  4898.4  772.48  4907.1  771.36
  4951.6  770.79  4960.3  769.51  4973.9  769.16  4988.3  764.29  4994.2  763.06
  4994.4  762.56  4997.9  762.56  4998.2  763.06  5005.2  763.82  5018.4  766.36
  5027.7  767.39  5055.8  768.18  5117.7  767.85  5230.1  769.67  5252.4  769.72
  5258.2  769.28  5263.7  769.99  5281.2  769.31  5305.2  769.34  5339.9  770.27
  5358.5  770.13  5363.9  770.64  5404.3  771.31  5501.7  774.19  5518.5  773.92
#Mann=3,-1,0
  4795.2    0.05       0  4994.2    0.05       0  4998.2    0.05       0
Bank Sta=4994.2,4998.2
Exp/Cntr=0.3,0.1

Type RM Length L Ch R = 1,1744,187,187,187
BEGIN DESCRIPTION:
Mapping XS ae09e87b
END DESCRIPTION:
XS GIS Cut Line= 2
      2297033.42      7101776.35      2296564.46      7102039.40
#Sta/Elev= 30
  4791.9  772.61  4833.6  771.86  4849.5  770.71  4865.5  770.10  4900.2  770.64
  4914.6  769.67  4930.5  769.70  4946.0  768.04  4973.9  767.50  4980.4  766.49
  4989.8  764.39  4995.6  761.11  5001.3  759.46  5001.6  758.96  5005.1  758.96
  5005.3  759.46  5011.5  765.16  5033.2  766.24  5076.6  766.81  5092.5  765.67
  5106.5  765.97  5114.2  766.76  5135.9  767.84  5151.9  767.56  5163.9  768.01
  5195.2  767.45  5232.7  767.97  5267.1  767.43  5319.6  769.06  5329.6  769.03
#Mann=3,-1,0
  4791.9    0.05       0  5001.3    0.04       0  5005.3    0.05       0
Bank Sta=5001.3,5005.3
Exp/Cntr=0.3,0.1

Type RM Length L Ch R = 1,1557,298,298,298
BEGIN DESCRIPTION:
Mapping XS 8c1b4f29
END DESCRIPTION:
XS GIS Cut Line= 2
      2296863.61      7101651.74      2296341.41      7101976.03
#Sta/Elev= 30
  4885.5  767.65  4894.2  767.88  4909.6  767.13  4915.5  767.45  4930.9  767.33
  4973.4  766.30  4994.9  758.40  4995.1  757.90  4998.6  757.90  4998.9  758.40
  5010.0  762.51  5019.4  764.87  5025.3  765.04  5040.7  764.00  5055.7  763.86
  5104.4  765.64  5119.8  765.57  5135.2  764.92  5141.1  765.30  5156.4  765.04
  5266.3  765.82  5330.0  767.06  5360.7  767.03  5366.6  767.57  5382.0  767.88
  5403.2  769.10  5418.6  768.92  5424.5  768.27  5439.8  768.35  5500.2  770.27
#Mann=3,-1,0
  4885.5    0.05       0  4994.9    0.04       0  4998.9    0.05       0
Bank Sta=4994.9,4998.9
Exp/Cntr=0.3,0.1

Type RM Length L Ch R = 1,1259,355,355,355
BEGIN DESCRIPTION:
Mapping XS 9733b0a7
END DESCRIPTION:
XS GIS Cut Line= 2
      2296786.21      7101585.49      2296592.92      7101290.47
#Sta/Elev= 30
  4826.6  764.67  4834.9  764.23  4844.0  764.46  4850.0  763.97  4857.1  764.31
  4865.1  764.06  4871.1  764.22  4880.2  763.63  4892.9  763.56  4922.3  762.53
  4952.5  762.17  4958.5  761.41  4964.7  761.37  4979.6  760.33  4988.6  759.10
  4992.7  756.76  4993.0  756.26  4996.5  756.26  4996.7  756.76  5000.7  756.99
  5009.8  763.28  5024.4  762.31  5060.3  761.42  5082.2  761.68  5088.1  762.11
  5103.2  762.06  5109.2  762.47  5154.5  762.78  5175.6  764.00  5179.3  764.47
#Mann=3,-1,0
  4826.6    0.05       0  4992.7   0.033       0  4996.7    0.05       0
Bank Sta=4992.7,4996.7
Exp/Cntr=0.3,0.1

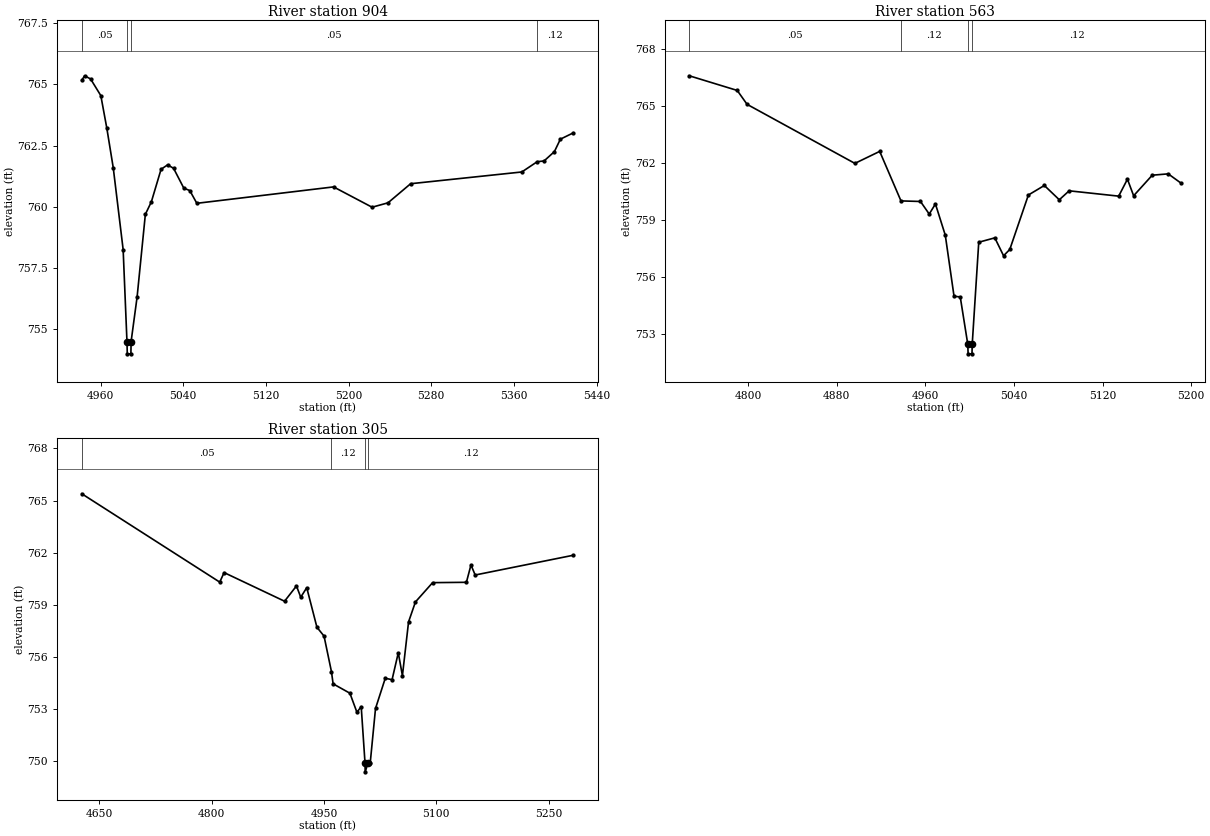
Type RM Length L Ch R = 1,904,341,341,341
BEGIN DESCRIPTION:
Mapping XS 2cb6fd8a
END DESCRIPTION:
XS GIS Cut Line= 2
      2297025.30      7101276.94      2296613.85      7101038.20
#Sta/Elev= 30
  4941.9  765.17  4944.6  765.35  4950.4  765.22  4960.3  764.54  4966.1  763.21
  4972.3  761.60  4981.9  758.25  4985.6  754.49  4985.9  753.99  4989.4  753.99
  4989.6  754.49  4995.4  756.31  5003.4  759.69  5009.2  760.20  5018.6  761.53
  5024.9  761.71  5030.7  761.57  5040.6  760.76  5046.4  760.66  5053.2  760.14
  5185.5  760.81  5222.8  759.98  5238.2  760.16  5260.1  760.94  5367.7  761.42
  5382.6  761.84  5389.2  761.87  5399.2  762.25  5405.0  762.76  5417.6  763.02
#Mann=4,-1,0
  4941.9    0.05       0  4985.6    0.04       0  4989.6    0.05       0
  5382.6    0.12       0
Bank Sta=4985.6,4989.6
Exp/Cntr=0.3,0.1

Type RM Length L Ch R = 1,563,258,258,258
BEGIN DESCRIPTION:
Mapping XS 9cedaf73
END DESCRIPTION:
XS GIS Cut Line= 2
      2297245.69      7101042.89      2296848.81      7100844.50
#Sta/Elev= 30
  4746.9  766.58  4790.2  765.81  4799.1  765.08  4896.4  761.98  4918.8  762.61
  4938.0  760.01  4955.6  759.98  4963.5  759.32  4969.1  759.85  4978.0  758.21
  4985.9  755.00  4991.5  754.97  4998.3  752.48  4998.6  751.98  5002.1  751.98
  5002.3  752.48  5008.2  757.84  5022.7  758.07  5030.6  757.13  5036.2  757.46
  5053.0  760.32  5067.4  760.82  5080.9  760.07  5089.8  760.54  5134.5  760.26
  5142.4  761.15  5148.0  760.28  5164.8  761.36  5179.2  761.43  5190.6  760.95
#Mann=4,-1,0
  4746.9    0.05       0  4938.0    0.12       0  4998.3    0.07       0
  5002.3    0.12       0
Bank Sta=4998.3,5002.3
Exp/Cntr=0.3,0.1

Type RM Length L Ch R = 1,305,0,0,0
BEGIN DESCRIPTION:
MDW T 030 2.0
END DESCRIPTION:
XS GIS Cut Line= 3
      2297419.94      7100878.43      2297085.41      7100688.01
      2296839.53      7100802.38
#Sta/Elev= 30
  4626.8  765.39  4810.9  760.30  4816.7  760.85  4897.4  759.20  4913.3  760.08
  4919.0  759.43  4927.0  759.98  4940.6  757.70  4950.1  757.19  4960.0  755.14
  4962.2  754.44  4984.6  753.90  4994.0  752.80  4999.7  753.13  5004.8  749.87
  5005.0  749.37  5008.8  749.87  5011.7  749.87  5018.8  753.02  5031.8  754.76
  5040.9  754.68  5049.2  756.23  5054.7  754.91  5062.9  758.01  5072.1  759.16
  5095.0  760.27  5140.1  760.29  5146.2  761.29  5151.8  760.71  5282.9  761.85
#Mann=4,-1,0
  4626.8    0.05       0  4960.0    0.12       0  5004.8    0.07       0
  5008.8    0.12       0
Bank Sta=5004.8,5008.8
Exp/Cntr=0.3,0.1

Chan Stop Cuts=-1