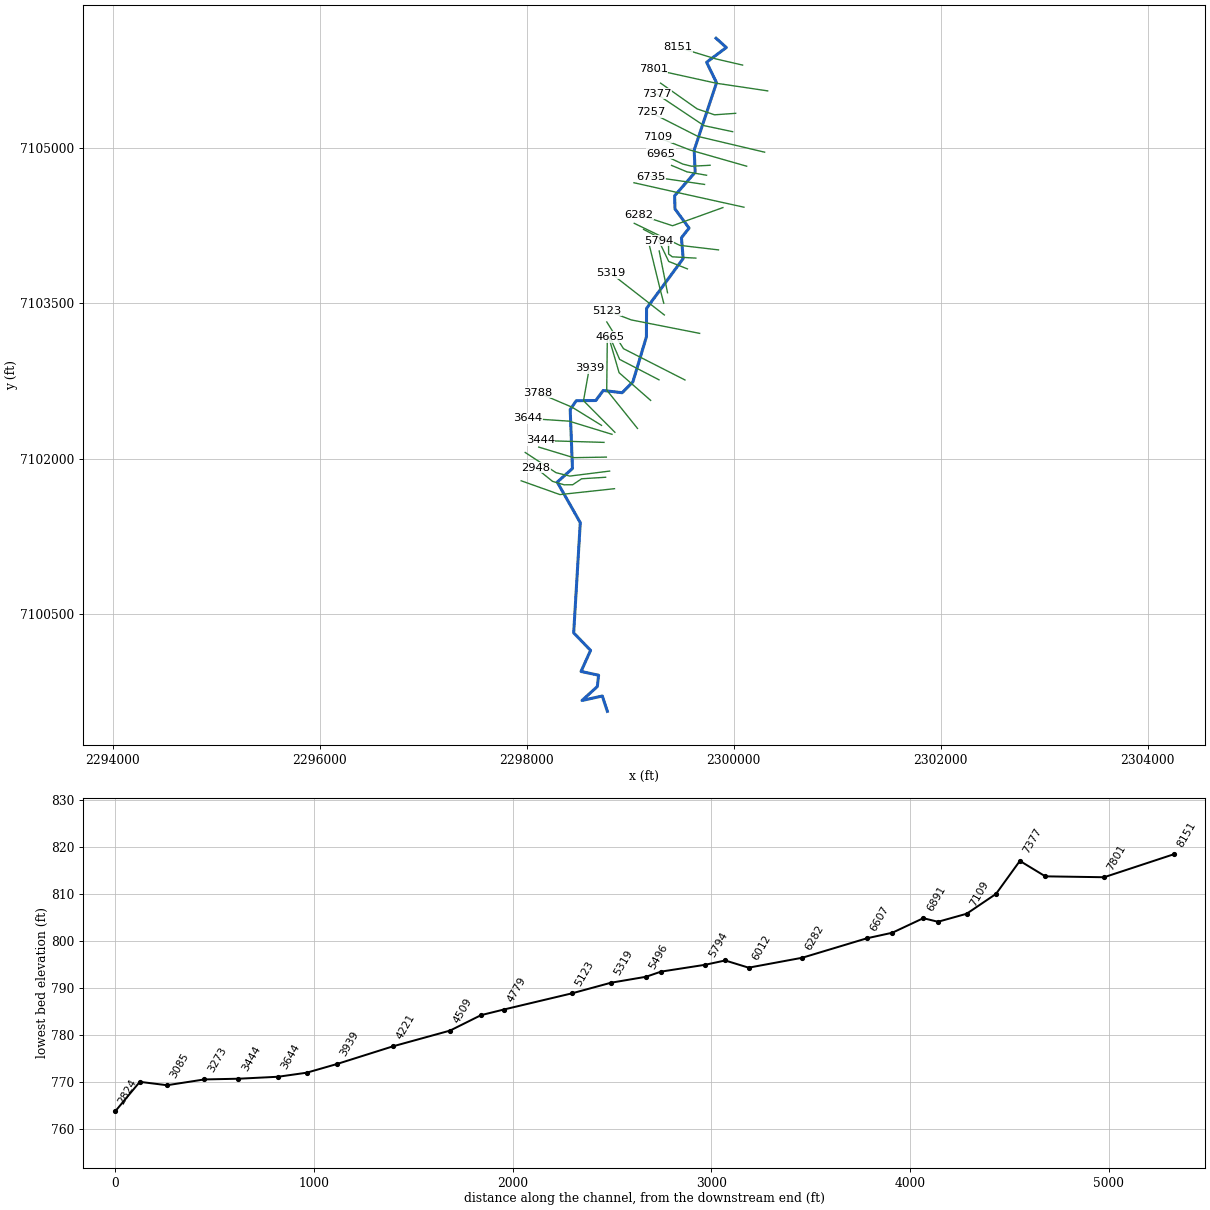
--- MDW T 031.prj (project) ---

Proj Title=MDW T 031 Base Level Engineering
Current Plan=p01
Default Exp/Contr=0.3,0.1
English Units
Geom File=g01
Flow File=f01
Plan File=p01
BEGIN DESCRIPTION:
MDW T 031
END DESCRIPTION:

--- MDW T 031.p01 (plan) ---

Plan Title=Multiple Run
Short Identifier=Multiple
Geom File=g01
Flow File=f01
Subcritical Flow
K Sum by GR= 0
Std Step Tol= 0.01
Critical Tol= 0.01
Num of Std Step Trials= 20
Max Error Tol= 0.3
Flow Tol Ratio= 0.001
Split Flow NTrial= 30
Split Flow Tol= 0.02
Split Flow Ratio= 0.02
Log Output Level= 0
Friction Slope Method= 1
Unsteady Friction Slope Method= 2
Unsteady Bridges Friction Slope Method= 1
Parabolic Critical Depth
Global Vel Dist=  1 , 1 , 1
Global Log Level= 0
CheckData=True
Encroach Param= -1, 0, 0, 0
BEGIN DESCRIPTION:
Multiple Run
END DESCRIPTION:

--- MDW T 031.f01 (steady flow) ---

Flow Title=Multiple
Number of Profiles=7
Profile Names=10-year,25-year,50-year,1pct_min,100-year,1pct_plu,500-year
River Rch & RM= MDW T 031,Reach-1,8151
     176     223     260     151     301     601     404
River Rch & RM= MDW T 031,Reach-1,7377
     272     356     423     250     499     996     696
River Rch & RM= MDW T 031,Reach-1,3788
     465     631     766     463     924    1843    1345
Boundary for River Rch & Prof#=MDW T 031,Reach-1,1
Up Type=0
Dn Type=3
Dn Slope=0.005
Boundary for River Rch & Prof#=MDW T 031,Reach-1,2
Up Type=0
Dn Type=3
Dn Slope=0.005
Boundary for River Rch & Prof#=MDW T 031,Reach-1,3
Up Type=0
Dn Type=3
Dn Slope=0.005
Boundary for River Rch & Prof#=MDW T 031,Reach-1,4
Up Type=0
Dn Type=3
Dn Slope=0.005
Boundary for River Rch & Prof#=MDW T 031,Reach-1,5
Up Type=0
Dn Type=3
Dn Slope=0.005
Boundary for River Rch & Prof#=MDW T 031,Reach-1,6
Up Type=0
Dn Type=3
Dn Slope=0.005
Boundary for River Rch & Prof#=MDW T 031,Reach-1,7
Up Type=0
Dn Type=3
Dn Slope=0.005

--- MDW T 031.g01 (geometry) ---

Geom Title=Existing Conditions

River Reach=MDW T 031,Reach-1
Reach XY= 30
      2299829.00      7106060.00      2299928.49      7105970.66
      2299737.82      7105827.77      2299833.85      7105630.48
      2299617.69      7104979.36      2299627.46      7104765.83
      2299428.99      7104538.86      2299432.54      7104411.47
      2299568.37      7104226.40      2299494.84      7104133.58
      2299511.65      7103932.97      2299157.74      7103451.55
      2299156.54      7103176.70      2299025.38      7102740.97
      2298922.31      7102636.88      2298739.50      7102658.49
      2298667.18      7102561.63      2298479.00      7102560.00
      2298420.00      7102475.02      2298441.96      7101905.16
      2298294.92      7101773.79      2298517.43      7101382.15
      2298453.70      7100317.72      2298616.89      7100149.08
      2298524.90      7099945.10      2298694.61      7099908.96
      2298682.07      7099799.53      2298534.15      7099664.91
      2298730.35      7099708.04      2298779.00      7099560.00

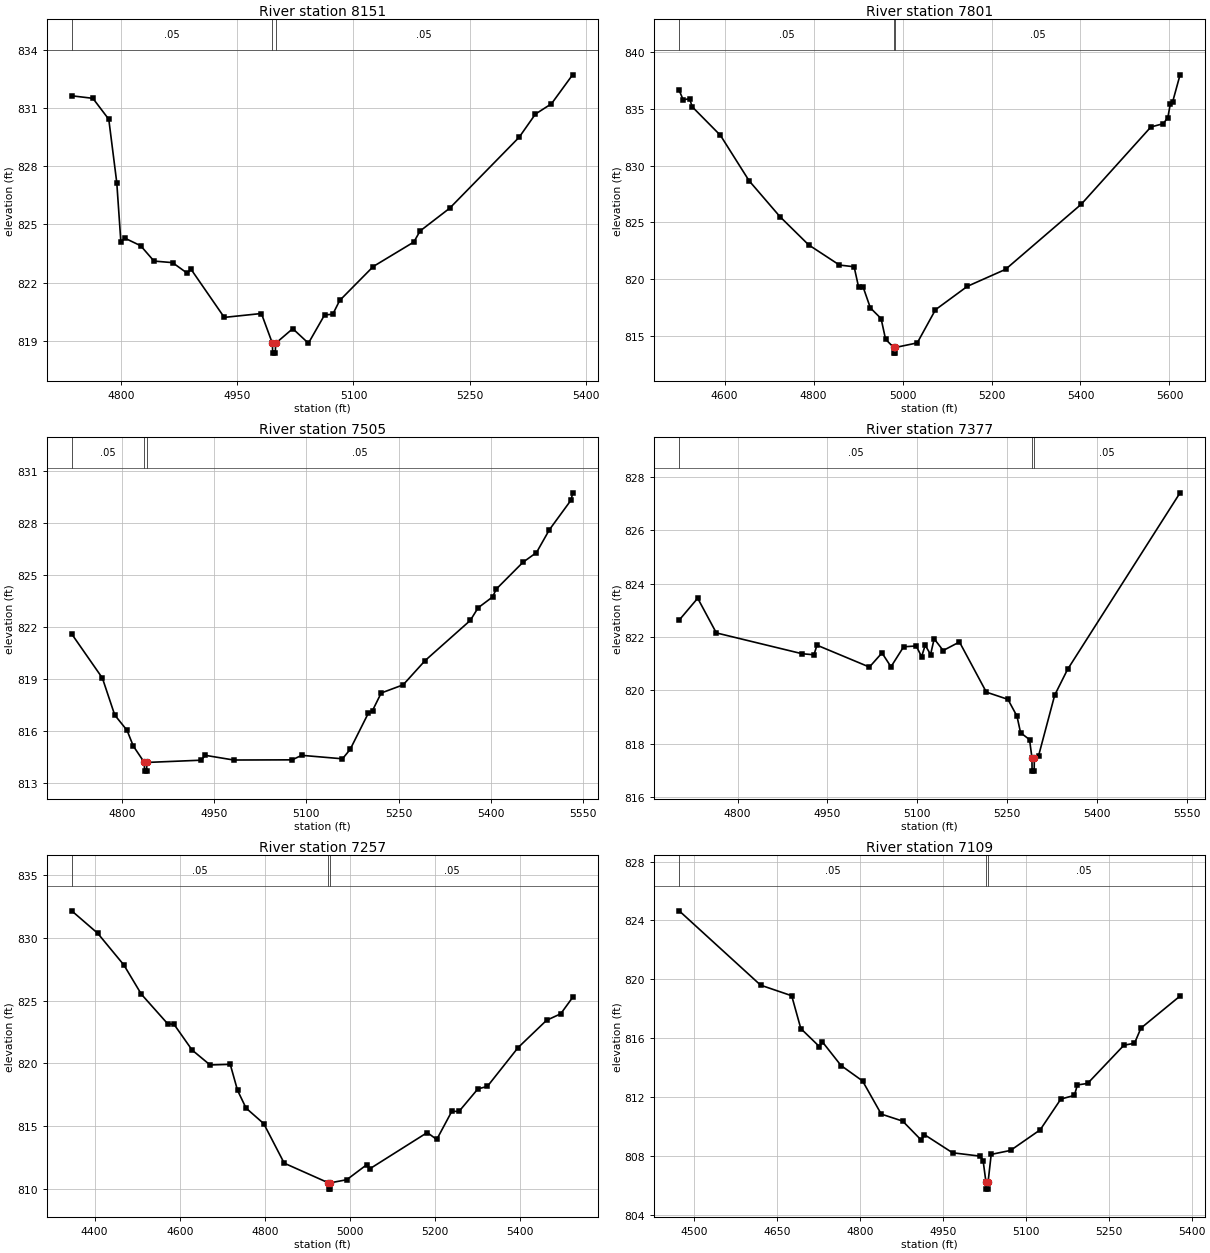
Type RM Length L Ch R = 1,8151,350,350,350
BEGIN DESCRIPTION:
MDW T 031 24.0
END DESCRIPTION:
XS GIS Cut Line= 3
      2300085.61      7105800.70      2299829.00      7105860.00
      2299463.18      7105971.45
#Sta/Elev= 30
  4736.7  831.62  4764.0  831.49  4784.5  830.41  4794.8  827.15  4800.1  824.09
  4805.2  824.29  4825.6  823.90  4842.8  823.11  4866.7  823.03  4885.5  822.49
  4890.7  822.68  4933.4  820.21  4981.3  820.41  4995.5  818.87  4995.8  818.37
  4999.3  818.37  4999.5  818.87  5021.7  819.63  5041.9  818.88  5062.8  820.34
  5073.3  820.37  5082.2  821.08  5125.5  822.83  5177.8  824.09  5185.9  824.66
  5224.0  825.83  5313.7  829.49  5334.6  830.68  5355.3  831.21  5382.5  832.70
#Mann=3,-1,0
  4736.7    0.05       0  4995.5   0.033       0  4999.5    0.05       0
Bank Sta=4995.5,4999.5
Exp/Cntr=0.3,0.1

Type RM Length L Ch R = 1,7801,296,296,296
BEGIN DESCRIPTION:
MDW T 031 23.0
END DESCRIPTION:
XS GIS Cut Line= 3
      2300327.89      7105551.67      2299832.67      7105625.27
      2299222.13      7105759.59
#Sta/Elev= 30
  4498.0  836.62  4507.0  835.79  4521.4  835.89  4527.2  835.18  4590.8  832.66
  4655.1  828.67  4724.5  825.51  4788.9  823.03  4858.3  821.25  4891.2  821.10
  4901.3  819.30  4911.4  819.32  4927.7  817.48  4951.8  816.54  4961.9  814.72
  4980.1  814.00  4980.4  813.50  4983.9  813.50  4984.1  814.00  5033.1  814.40
  5074.1  817.32  5145.8  819.38  5231.5  820.87  5401.7  826.60  5558.2  833.40
  5586.0  833.69  5596.3  834.23  5601.9  835.42  5607.0  835.59  5623.8  837.99
#Mann=3,-1,0
  4498.0    0.05       0  4980.1   0.033       0  4984.1    0.05       0
Bank Sta=4980.1,4984.1
Exp/Cntr=0.3,0.1

Type RM Length L Ch R = 1,7505,128,128,128
BEGIN DESCRIPTION:
Mapping XS a9a5268d
END DESCRIPTION:
XS GIS Cut Line= 4
      2300018.83      7105334.99      2299814.26      7105320.59
      2299646.13      7105377.87      2299293.01      7105626.75
#Sta/Elev= 30
  4718.3  821.59  4768.2  819.05  4788.3  816.92  4808.3  816.04  4818.4  815.14
  4836.4  814.19  4836.7  813.69  4840.2  813.69  4840.4  814.19  4928.9  814.32
  4935.6  814.60  4981.8  814.33  5076.8  814.34  5092.4  814.60  5158.7  814.40
  5171.2  814.94  5200.8  817.03  5207.6  817.18  5221.7  818.19  5257.4  818.66
  5293.2  820.06  5366.6  822.37  5379.4  823.10  5402.8  823.72  5409.0  824.18
  5452.3  825.72  5474.3  826.28  5495.2  827.59  5530.9  829.32  5533.0  829.72
#Mann=3,-1,0
  4718.3    0.05       0  4836.4   0.033       0  4840.4    0.05       0
Bank Sta=4836.4,4840.4
Exp/Cntr=0.3,0.1

Type RM Length L Ch R = 1,7377,120,120,120
BEGIN DESCRIPTION:
Mapping XS f806e571
END DESCRIPTION:
XS GIS Cut Line= 3
      2299989.64      7105157.65      2299711.91      7105216.26
      2299252.82      7105523.03
#Sta/Elev= 30
  4702.5  822.63  4733.4  823.45  4764.5  822.15  4907.6  821.37  4927.4  821.33
  4932.5  821.69  5020.0  820.87  5041.0  821.40  5056.0  820.88  5077.1  821.63
  5098.1  821.66  5107.1  821.26  5113.1  821.69  5122.1  821.34  5128.1  821.93
  5143.1  821.49  5170.3  821.81  5215.2  819.93  5251.2  819.66  5266.3  819.03
  5272.3  818.41  5287.3  818.15  5291.3  817.47  5291.5  816.97  5295.0  816.97
  5295.3  817.47  5302.3  817.54  5329.3  819.82  5350.7  820.78  5538.5  827.40
#Mann=3,-1,0
  4702.5    0.05       0  5291.3   0.033       0  5295.3    0.05       0
Bank Sta=5291.3,5295.3
Exp/Cntr=0.3,0.1

Type RM Length L Ch R = 1,7257,148,148,148
BEGIN DESCRIPTION:
MDW T 031 21.0
END DESCRIPTION:
XS GIS Cut Line= 3
      2300298.46      7104959.64      2299653.63      7105112.03
      2299194.15      7105345.09
#Sta/Elev= 30
  4346.0  832.15  4407.1  830.36  4468.7  827.83  4509.8  825.50  4571.5  823.15
  4586.8  823.09  4629.1  821.05  4671.4  819.86  4718.8  819.91  4735.9  817.84
  4756.0  816.42  4797.6  815.18  4845.7  812.03  4949.7  810.46  4949.9  809.96
  4953.4  809.96  4953.7  810.46  4992.8  810.71  5039.5  811.90  5047.4  811.59
  5182.0  814.47  5204.4  813.92  5239.9  816.17  5256.6  816.15  5301.1  817.95
  5323.4  818.15  5395.8  821.25  5462.6  823.42  5495.9  823.94  5523.8  825.24
#Mann=3,-1,0
  4346.0    0.05       0  4949.7   0.033       0  4953.7    0.05       0
Bank Sta=4949.7,4953.7
Exp/Cntr=0.3,0.1

Type RM Length L Ch R = 1,7109,144,144,144
BEGIN DESCRIPTION:
MDW T 031 20.0
END DESCRIPTION:
XS GIS Cut Line= 3
      2300124.84      7104824.22      2299579.40      7104980.16
      2299263.02      7105103.33
#Sta/Elev= 30
  4472.3  824.65  4619.7  819.60  4676.0  818.88  4692.5  816.65  4726.3  815.42
  4731.5  815.75  4765.3  814.14  4804.3  813.09  4838.1  810.84  4877.0  810.36
  4910.8  809.06  4916.0  809.45  4967.2  808.21  5017.4  807.98  5022.6  807.66
  5027.6  806.24  5027.9  805.74  5031.4  805.74  5031.6  806.24  5037.2  808.10
  5072.2  808.37  5125.9  809.77  5163.3  811.86  5187.8  812.11  5193.2  812.82
  5211.7  812.92  5277.5  815.52  5296.6  815.65  5308.3  816.68  5379.1  818.86
#Mann=3,-1,0
  4472.3    0.05       0  5027.6   0.033       0  5031.6    0.05       0
Bank Sta=5027.6,5031.6
Exp/Cntr=0.3,0.1

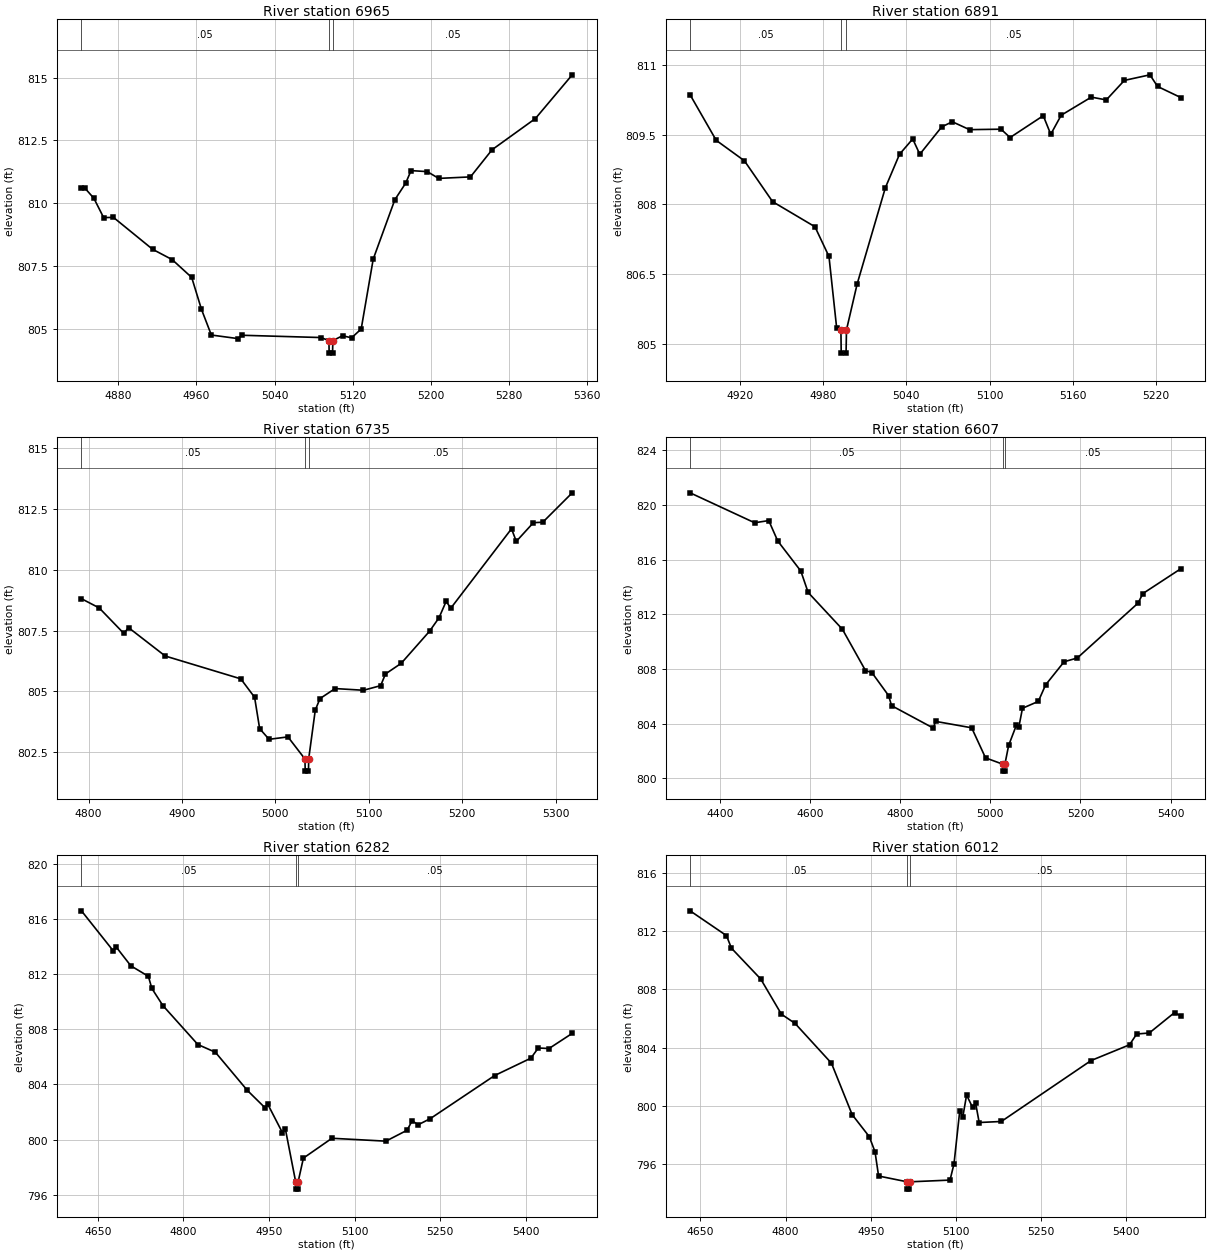
Type RM Length L Ch R = 1,6965,74,74,74
BEGIN DESCRIPTION:
Mapping XS e25ee6c2
END DESCRIPTION:
XS GIS Cut Line= 4
      2299771.69      7104833.28      2299591.85      7104824.05
      2299506.83      7104845.30      2299294.87      7104945.37
#Sta/Elev= 30
  4842.4  810.59  4846.2  810.59  4855.1  810.20  4865.1  809.43  4875.1  809.44
  4915.2  808.17  4935.2  807.76  4955.2  807.05  4965.2  805.78  4975.3  804.76
  5002.1  804.62  5007.1  804.75  5087.3  804.66  5095.6  804.54  5095.8  804.04
  5099.3  804.04  5099.6  804.54  5109.5  804.73  5118.8  804.65  5128.6  805.00
  5140.9  807.78  5163.0  810.14  5174.1  810.80  5179.6  811.30  5196.2  811.26
  5207.9  810.99  5240.4  811.05  5262.5  812.13  5306.8  813.37  5344.5  815.11
#Mann=3,-1,0
  4842.4    0.05       0  5095.6   0.033       0  5099.6    0.05       0
Bank Sta=5095.6,5099.6
Exp/Cntr=0.3,0.1

Type RM Length L Ch R = 1,6891,156,156,156
BEGIN DESCRIPTION:
Mapping XS e604d3b2
END DESCRIPTION:
XS GIS Cut Line= 3
      2299737.57      7104737.02      2299548.98      7104769.51
      2299399.44      7104831.89
#Sta/Elev= 30
  4884.3  810.36  4903.1  809.38  4923.4  808.94  4943.7  808.06  4974.2  807.52
  4984.3  806.88  4989.8  805.35  4992.9  805.30  4993.1  804.80  4996.6  804.80
  4996.9  805.30  5004.6  806.29  5024.9  808.36  5035.1  809.08  5044.6  809.41
  5049.7  809.08  5065.5  809.67  5073.1  809.78  5085.5  809.61  5108.2  809.62
  5114.7  809.44  5138.6  809.91  5144.0  809.51  5151.5  809.92  5173.2  810.31
  5184.0  810.25  5197.0  810.67  5215.4  810.79  5220.9  810.54  5237.7  810.30
#Mann=3,-1,0
  4884.3    0.05       0  4992.9   0.033       0  4996.9    0.05       0
Bank Sta=4992.9,4996.9
Exp/Cntr=0.3,0.1

Type RM Length L Ch R = 1,6735,128,128,128
BEGIN DESCRIPTION:
Mapping XS 3a65a67c
END DESCRIPTION:
XS GIS Cut Line= 2
      2299717.79      7104648.30      2299197.79      7104724.10
#Sta/Elev= 30
  4792.3  808.81  4811.3  808.43  4837.7  807.38  4842.7  807.62  4882.0  806.45
  4962.9  805.51  4977.7  804.75  4983.1  803.46  4993.2  803.02  5013.4  803.12
  5031.6  802.21  5031.9  801.71  5035.4  801.71  5035.6  802.21  5042.7  804.23
  5047.8  804.70  5063.9  805.11  5094.3  805.04  5112.7  805.23  5117.8  805.71
  5134.7  806.15  5165.0  807.47  5175.1  808.02  5182.8  808.70  5187.8  808.42
  5252.8  811.69  5257.9  811.17  5276.2  811.94  5286.3  811.96  5317.8  813.17
#Mann=3,-1,0
  4792.3    0.05       0  5031.6   0.033       0  5035.6    0.05       0
Bank Sta=5031.6,5035.6
Exp/Cntr=0.3,0.1

Type RM Length L Ch R = 1,6607,325,325,325
BEGIN DESCRIPTION:
MDW T 031 18.0
END DESCRIPTION:
XS GIS Cut Line= 3
      2300098.76      7104428.40      2299442.78      7104573.15
      2299036.28      7104664.50
#Sta/Elev= 30
  4334.3  820.89  4477.4  818.70  4508.7  818.86  4528.6  817.37  4579.8  815.17
  4596.1  813.60  4672.0  810.91  4723.2  807.89  4737.4  807.74  4774.4  806.06
  4781.1  805.32  4873.6  803.68  4878.7  804.17  4958.7  803.70  4989.5  801.50
  5028.4  801.03  5028.7  800.53  5032.2  800.53  5032.4  801.03  5040.7  802.41
  5058.1  803.91  5063.2  803.73  5071.4  805.13  5106.5  805.63  5122.7  806.84
  5163.7  808.53  5193.1  808.81  5327.7  812.82  5338.4  813.52  5422.7  815.34
#Mann=3,-1,0
  4334.3    0.05       0  5028.4    0.04       0  5032.4    0.05       0
Bank Sta=5028.4,5032.4
Exp/Cntr=0.3,0.1

Type RM Length L Ch R = 1,6282,270,270,270
BEGIN DESCRIPTION:
MDW T 031 17.0
END DESCRIPTION:
XS GIS Cut Line= 3
      2299895.07      7104424.50      2299408.58      7104249.36
      2299082.48      7104356.79
#Sta/Elev= 30
  4621.2  816.59  4677.1  813.68  4682.4  813.95  4707.8  812.60  4738.5  811.84
  4744.6  810.96  4763.9  809.72  4825.3  806.89  4856.0  806.33  4912.1  803.56
  4942.8  802.31  4948.1  802.54  4973.5  800.50  4978.8  800.74  4996.9  796.90
  4997.2  796.40  5000.7  796.40  5000.9  796.90  5010.3  798.65  5060.3  800.09
  5154.9  799.88  5192.0  800.67  5201.0  801.36  5211.5  801.07  5232.6  801.51
  5345.6  804.64  5409.1  805.90  5422.1  806.64  5440.9  806.60  5481.6  807.70
#Mann=3,-1,0
  4621.2    0.05       0  4996.9   0.033       0  5000.9    0.05       0
Bank Sta=4996.9,5000.9
Exp/Cntr=0.3,0.1

Type RM Length L Ch R = 1,6012,118,118,118
BEGIN DESCRIPTION:
MDW T 031 16.0
END DESCRIPTION:
XS GIS Cut Line= 3
      2299852.65      7104016.07      2299479.00      7104060.00
      2299038.87      7104272.58
#Sta/Elev= 30
  4631.8  813.38  4695.9  811.68  4704.6  810.82  4756.3  808.70  4792.7  806.29
  4816.7  805.66  4880.9  802.93  4917.4  799.40  4947.6  797.89  4957.7  796.85
  4964.0  795.19  5014.5  794.79  5014.8  794.29  5018.3  794.29  5018.5  794.79
  5089.9  794.91  5096.9  796.02  5107.0  799.64  5112.5  799.26  5119.1  800.74
  5129.6  799.90  5135.1  800.17  5141.3  798.86  5180.3  798.93  5338.5  803.11
  5406.3  804.19  5418.9  804.93  5441.1  805.00  5485.6  806.40  5496.8  806.16
#Mann=3,-1,0
  4631.8    0.05       0  5014.5   0.033       0  5018.5    0.05       0
Bank Sta=5014.5,5018.5
Exp/Cntr=0.3,0.1

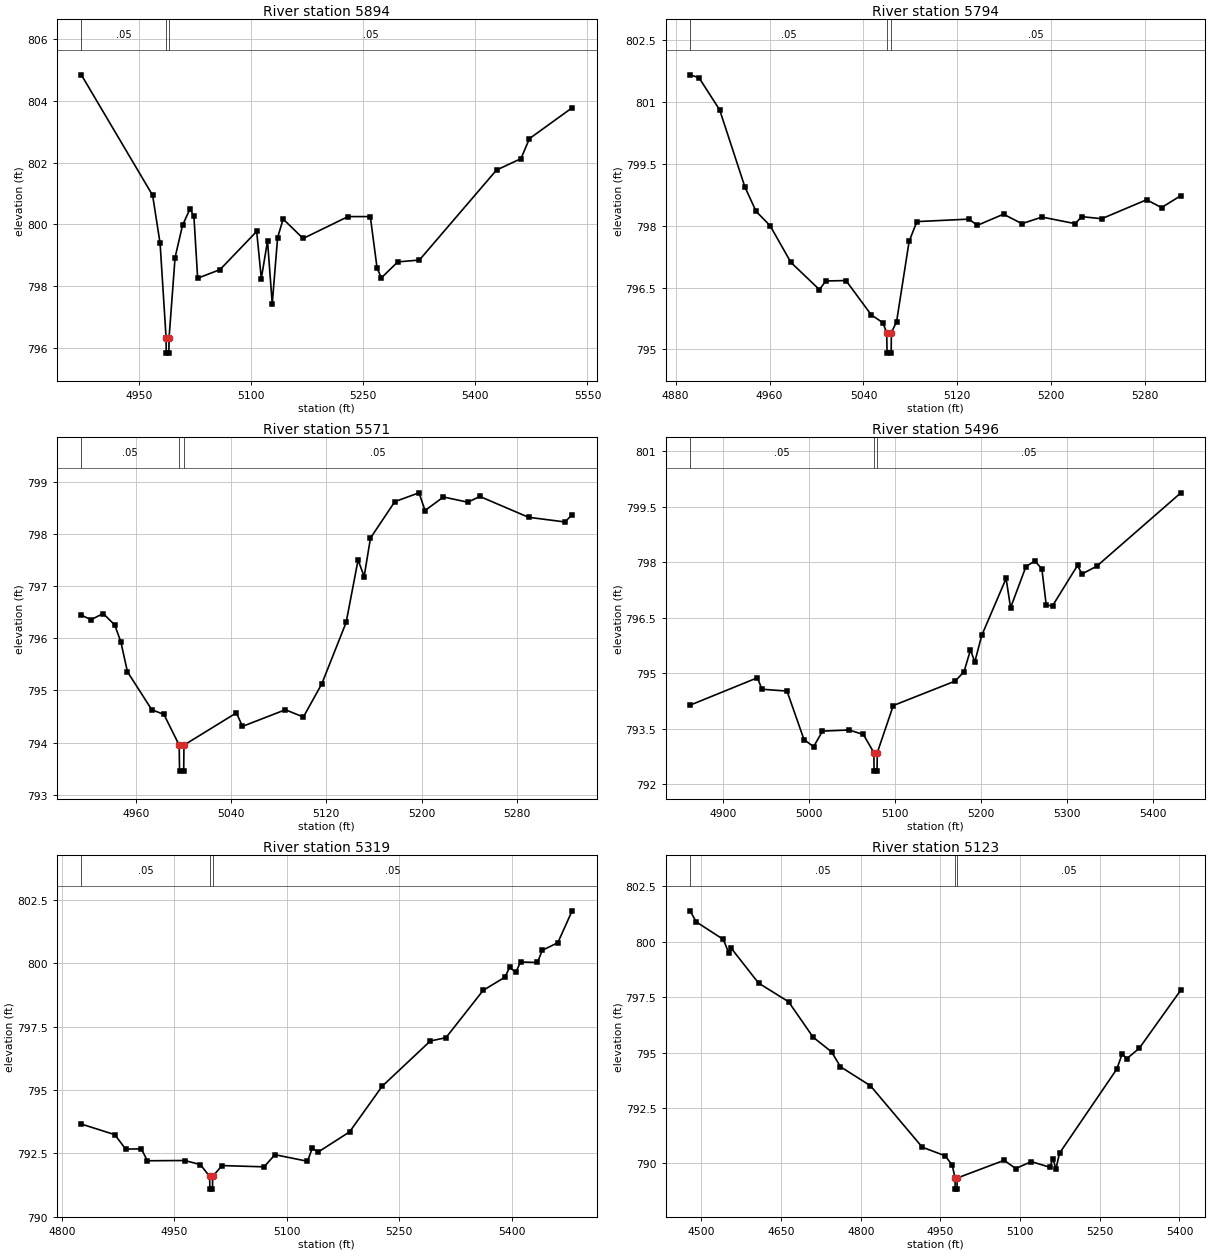
Type RM Length L Ch R = 1,5894,100,100,100
BEGIN DESCRIPTION:
Mapping XS 528dbe2d
END DESCRIPTION:
XS GIS Cut Line= 5
      2299634.12      7103936.80      2299406.44      7103949.21
      2299371.00      7103975.90      2299369.86      7104086.54
      2299128.58      7104214.40
#Sta/Elev= 30
  4873.4  804.85  4968.7  800.94  4978.7  799.38  4986.7  796.32  4986.9  795.82
  4990.4  795.82  4990.7  796.32  4998.7  798.92  5008.7  799.97  5018.7  800.50
  5023.9  800.26  5028.9  798.25  5058.8  798.53  5107.8  799.77  5114.0  798.24
  5122.3  799.46  5128.6  797.42  5135.8  799.57  5143.2  800.17  5169.9  799.54
  5229.9  800.25  5259.7  800.25  5268.7  798.59  5274.4  798.26  5296.4  798.78
  5325.3  798.84  5428.4  801.76  5461.1  802.13  5472.4  802.78  5529.5  803.78
#Mann=3,-1,0
  4873.4    0.05       0  4986.7   0.033       0  4990.7    0.05       0
Bank Sta=4986.7,4990.7
Exp/Cntr=0.3,0.1

Type RM Length L Ch R = 1,5794,223,223,223
BEGIN DESCRIPTION:
Mapping XS a4d2aee8
END DESCRIPTION:
XS GIS Cut Line= 3
      2299552.41      7103832.69      2299371.73      7103904.59
      2299275.16      7104106.31
#Sta/Elev= 30
  4892.3  801.66  4899.9  801.59  4917.5  800.81  4939.0  798.94  4948.5  798.35
  4960.5  798.00  4978.2  797.11  5002.5  796.45  5007.9  796.66  5025.1  796.67
  5046.6  795.84  5056.4  795.65  5059.8  795.41  5060.1  794.91  5063.6  794.91
  5063.8  795.41  5068.2  795.67  5078.9  797.62  5085.5  798.10  5129.7  798.16
  5137.1  798.01  5159.3  798.28  5175.0  798.05  5192.1  798.21  5220.4  798.05
  5225.9  798.22  5243.0  798.17  5281.2  798.63  5293.9  798.44  5310.4  798.73
#Mann=3,-1,0
  4892.3    0.05       0  5059.8   0.033       0  5063.8    0.05       0
Bank Sta=5059.8,5063.8
Exp/Cntr=0.3,0.1

Type RM Length L Ch R = 1,5571,75,75,75
BEGIN DESCRIPTION:
Mapping XS f29003e0
END DESCRIPTION:
XS GIS Cut Line= 2
      2299360.36      7103602.07      2299279.87      7104005.92
#Sta/Elev= 30
  4914.4  796.45  4922.5  796.36  4932.7  796.48  4942.4  796.26  4947.5  795.94
  4953.1  795.36  4973.5  794.63  4983.7  794.54  4996.5  793.95  4996.8  793.45
  5000.3  793.45  5000.5  793.95  5044.5  794.57  5049.6  794.31  5085.6  794.63
  5100.7  794.49  5116.2  795.13  5136.6  796.31  5146.6  797.51  5151.7  797.19
  5157.0  797.93  5177.4  798.63  5197.7  798.80  5202.8  798.46  5218.2  798.72
  5238.6  798.62  5248.8  798.73  5289.6  798.33  5320.2  798.24  5326.2  798.38
#Mann=3,-1,0
  4914.4    0.05       0  4996.5    0.04       0  5000.5    0.05       0
Bank Sta=4996.5,5000.5
Exp/Cntr=0.3,0.1

Type RM Length L Ch R = 1,5496,177,177,177
BEGIN DESCRIPTION:
Mapping XS a9083797
END DESCRIPTION:
XS GIS Cut Line= 3
      2299324.18      7103500.82      2299289.72      7103633.27
      2299186.11      7104055.08
#Sta/Elev= 30
  4861.2  794.14  4939.6  794.88  4944.8  794.57  4974.0  794.52  4993.8  793.21
  5005.0  793.02  5015.3  793.44  5046.2  793.47  5062.8  793.35  5075.1  792.86
  5075.3  792.36  5078.8  792.36  5079.1  792.86  5097.7  794.13  5169.7  794.79
  5180.0  795.04  5187.5  795.63  5192.6  795.31  5200.6  796.02  5229.0  797.56
  5234.2  796.77  5252.1  797.88  5262.4  798.03  5270.6  797.82  5275.7  796.84
  5283.0  796.82  5312.1  797.91  5317.3  797.68  5334.5  797.89  5432.4  799.87
#Mann=3,-1,0
  4861.2    0.05       0  5075.1    0.04       0  5079.1    0.05       0
Bank Sta=5075.1,5079.1
Exp/Cntr=0.3,0.1

Type RM Length L Ch R = 1,5319,196,196,196
BEGIN DESCRIPTION:
Mapping XS 21641360
END DESCRIPTION:
XS GIS Cut Line= 2
      2299329.50      7103387.76      2298813.20      7103790.00
#Sta/Elev= 30
  4826.0  793.66  4870.7  793.24  4885.1  792.67  4906.0  792.68  4914.1  792.21
  4963.8  792.22  4984.7  792.06  4997.1  791.59  4997.4  791.09  5000.9  791.09
  5001.1  791.59  5013.6  792.02  5069.7  791.97  5084.2  792.45  5127.6  792.19
  5133.9  792.70  5142.1  792.56  5183.7  793.35  5227.1  795.15  5291.4  796.94
  5312.2  797.07  5361.9  798.94  5390.9  799.46  5397.2  799.85  5405.4  799.65
  5411.7  800.06  5434.3  800.04  5440.6  800.52  5461.4  800.82  5480.5  802.08
#Mann=3,-1,0
  4826.0    0.05       0  4997.1    0.04       0  5001.1    0.05       0
Bank Sta=4997.1,5001.1
Exp/Cntr=0.3,0.1

Type RM Length L Ch R = 1,5123,344,344,344
BEGIN DESCRIPTION:
MDW T 031 13.0
END DESCRIPTION:
XS GIS Cut Line= 3
      2299670.42      7103210.07      2299009.13      7103340.20
      2298775.83      7103430.14
#Sta/Elev= 30
  4478.6  801.39  4490.2  800.89  4541.2  800.10  4551.1  799.51  4556.2  799.70
  4607.6  798.13  4664.0  797.29  4710.3  795.69  4745.0  795.03  4761.7  794.36
  4818.2  793.50  4915.8  790.73  4959.1  790.34  4972.3  789.91  4977.4  789.34
  4977.7  788.84  4981.2  788.84  4981.4  789.34  5069.9  790.14  5091.5  789.77
  5121.3  790.08  5155.3  789.83  5162.0  790.21  5167.3  789.74  5174.1  790.46
  5281.9  794.25  5292.0  794.93  5301.1  794.73  5324.2  795.19  5402.6  797.82
#Mann=3,-1,0
  4478.6    0.05       0  4977.4    0.04       0  4981.4    0.05       0
Bank Sta=4977.4,4981.4
Exp/Cntr=0.3,0.1

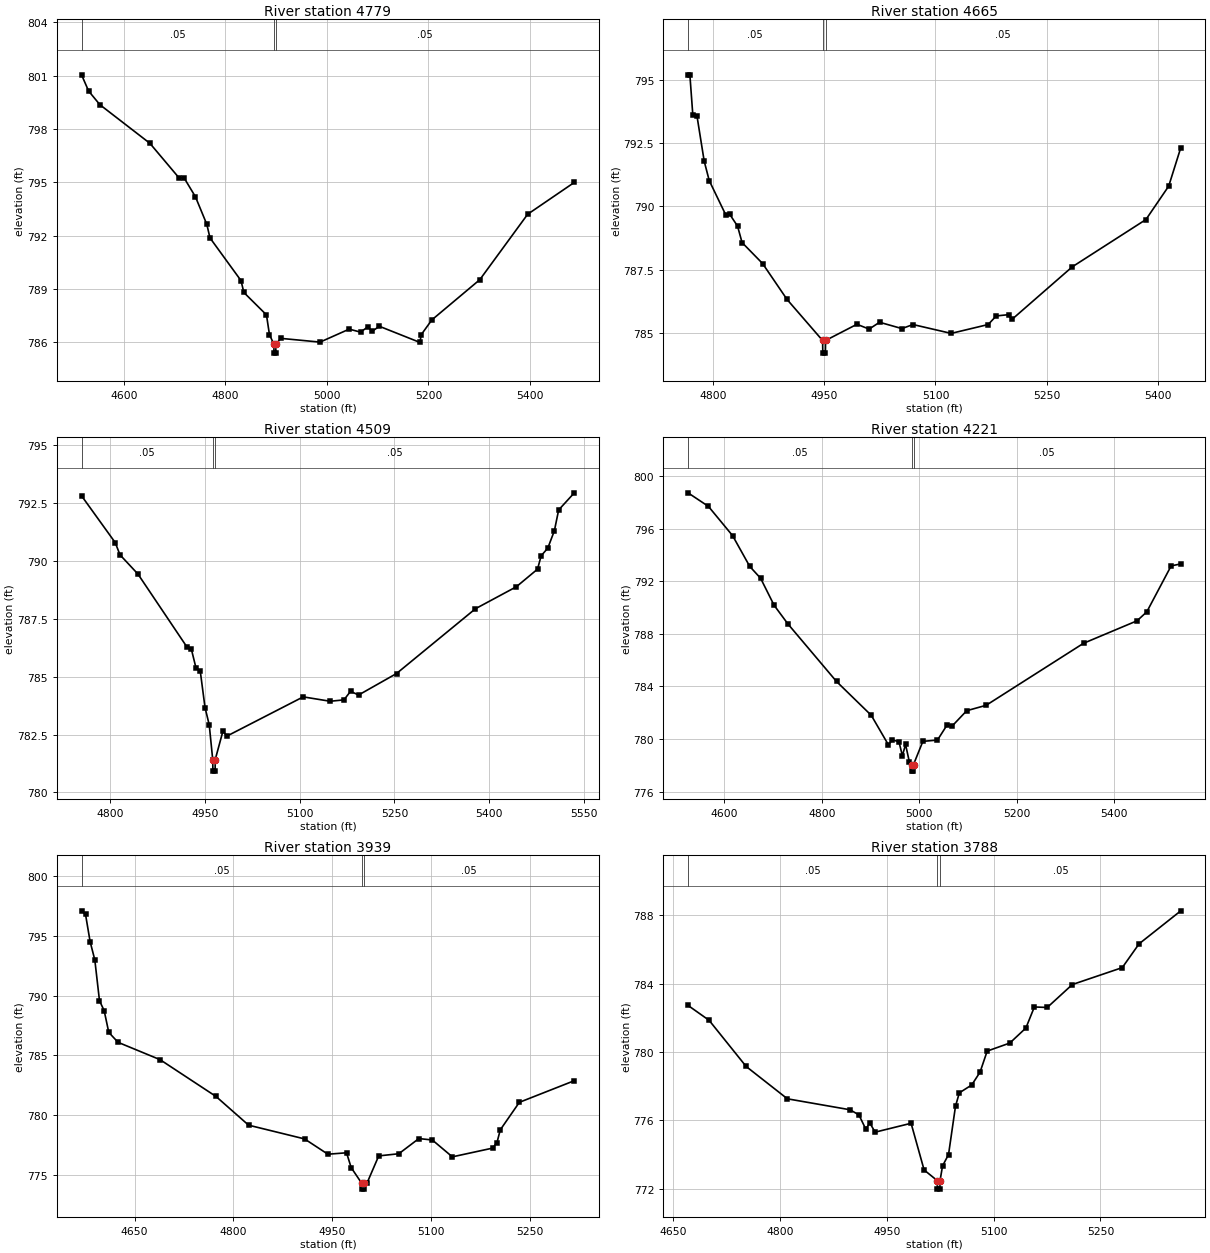
Type RM Length L Ch R = 1,4779,114,114,114
BEGIN DESCRIPTION:
MDW T 031 12.0
END DESCRIPTION:
XS GIS Cut Line= 3
      2299528.97      7102760.01      2298934.69      7103062.31
      2298773.61      7103320.18
#Sta/Elev= 30
  4516.7  801.04  4530.6  800.13  4552.8  799.36  4651.3  797.19  4708.6  795.25
  4718.6  795.25  4741.1  794.18  4763.5  792.63  4769.7  791.87  4830.8  789.47
  4836.5  788.80  4881.0  787.54  4886.9  786.43  4895.6  785.89  4895.8  785.39
  4899.3  785.39  4899.6  785.89  4909.3  786.22  4986.6  786.01  5044.0  786.74
  5066.4  786.57  5081.2  786.88  5088.9  786.61  5103.4  786.90  5183.5  785.99
  5185.7  786.42  5206.9  787.26  5301.3  789.52  5395.6  793.20  5487.5  794.99
#Mann=3,-1,0
  4516.7    0.05       0  4895.6    0.04       0  4899.6    0.05       0
Bank Sta=4895.6,4899.6
Exp/Cntr=0.3,0.1

Type RM Length L Ch R = 1,4665,156,156,156
BEGIN DESCRIPTION:
Mapping XS 4908d4ba
END DESCRIPTION:
XS GIS Cut Line= 3
      2299278.34      7102761.26      2298897.57      7102958.65
      2298803.96      7103174.98
#Sta/Elev= 30
  4766.3  795.20  4768.8  795.20  4772.8  793.60  4778.4  793.57  4788.1  791.79
  4794.9  791.02  4817.1  789.67  4822.7  789.68  4833.1  789.22  4839.2  788.57
  4866.9  787.74  4899.9  786.32  4947.8  784.70  4948.1  784.20  4951.6  784.20
  4951.8  784.70  4994.1  785.34  5010.6  785.15  5024.6  785.42  5054.8  785.17
  5069.7  785.33  5121.2  784.98  5171.1  785.33  5182.0  785.67  5198.6  785.72
  5203.1  785.53  5284.5  787.61  5383.9  789.48  5414.6  790.80  5430.9  792.32
#Mann=3,-1,0
  4766.3    0.05       0  4947.8    0.04       0  4951.8    0.05       0
Bank Sta=4947.8,4951.8
Exp/Cntr=0.3,0.1

Type RM Length L Ch R = 1,4509,288,288,288
BEGIN DESCRIPTION:
Mapping XS ccf2f883
END DESCRIPTION:
XS GIS Cut Line= 3
      2299197.28      7102562.70      2298892.56      7102830.02
      2298787.52      7103190.37
#Sta/Elev= 30
  4754.3  792.82  4807.6  790.80  4815.2  790.27  4843.6  789.44  4921.4  786.28
  4928.1  786.21  4935.7  785.37  4942.3  785.26  4949.9  783.67  4956.6  782.92
  4962.1  781.42  4962.4  780.92  4965.9  780.92  4966.1  781.42  4978.2  782.64
  4985.0  782.44  5105.5  784.13  5148.2  783.94  5170.0  784.00  5180.5  784.37
  5193.2  784.21  5253.4  785.14  5378.4  787.94  5443.2  788.89  5476.7  789.65
  5482.5  790.23  5493.0  790.56  5503.4  791.31  5510.2  792.21  5535.0  792.95
#Mann=3,-1,0
  4754.3    0.05       0  4962.1    0.04       0  4966.1    0.05       0
Bank Sta=4962.1,4966.1
Exp/Cntr=0.3,0.1

Type RM Length L Ch R = 1,4221,282,282,282
BEGIN DESCRIPTION:
MDW T 031 11.0
END DESCRIPTION:
XS GIS Cut Line= 3
      2299070.11      7102292.13      2298772.92      7102662.54
      2298779.16      7103199.81
#Sta/Elev= 30
  4525.1  798.71  4567.0  797.68  4616.6  795.46  4651.9  793.12  4674.2  792.22
  4701.9  790.17  4730.3  788.75  4830.1  784.38  4901.5  781.81  4936.7  779.57
  4944.7  779.94  4958.3  779.81  4965.5  778.74  4971.9  779.60  4979.9  778.25
  4984.3  778.07  4984.6  777.57  4988.1  777.57  4988.3  778.07  5007.5  779.83
  5037.5  779.93  5057.5  781.09  5067.5  780.99  5097.6  782.16  5137.5  782.57
  5337.5  787.28  5447.5  788.99  5467.5  789.67  5517.5  793.16  5537.3  793.31
#Mann=3,-1,0
  4525.1    0.05       0  4984.3    0.04       0  4988.3    0.05       0
Bank Sta=4984.3,4988.3
Exp/Cntr=0.3,0.1

Type RM Length L Ch R = 1,3939,151,151,151
BEGIN DESCRIPTION:
MDW T 031 10.0
END DESCRIPTION:
XS GIS Cut Line= 3
      2298852.09      7102254.67      2298548.67      7102559.92
      2298604.30      7102872.11
#Sta/Elev= 30
  4569.6  797.09  4575.6  796.80  4582.6  794.51  4589.7  792.99  4596.8  789.57
  4603.9  788.74  4610.9  786.92  4625.0  786.09  4688.7  784.64  4773.6  781.56
  4823.0  779.16  4907.9  778.01  4943.3  776.73  4971.6  776.85  4978.6  775.61
  4994.5  774.31  4994.8  773.81  4998.3  773.81  4998.5  774.31  5002.6  774.31
  5020.4  776.59  5050.9  776.77  5081.3  778.04  5101.7  777.92  5132.1  776.51
  5193.1  777.24  5199.8  777.71  5204.8  778.77  5233.7  781.07  5317.1  782.88
#Mann=3,-1,0
  4569.6    0.05       0  4994.5    0.04       0  4998.5    0.05       0
Bank Sta=4994.5,4998.5
Exp/Cntr=0.3,0.1

Type RM Length L Ch R = 1,3788,144,144,144
BEGIN DESCRIPTION:
Mapping XS d43c93bb
END DESCRIPTION:
XS GIS Cut Line= 3
      2298722.72      7102321.65      2298439.08      7102496.65
      2298108.81      7102637.41
#Sta/Elev= 30
  4670.5  782.72  4700.1  781.85  4752.2  779.15  4810.1  777.26  4898.1  776.62
  4910.6  776.32  4920.1  775.50  4926.0  775.84  4933.4  775.31  4983.9  775.83
  5002.2  773.10  5020.6  772.48  5020.9  771.98  5024.4  771.98  5024.6  772.48
  5028.1  773.34  5036.5  774.00  5046.3  776.83  5051.7  777.61  5069.1  778.07
  5080.8  778.82  5090.8  780.05  5122.6  780.52  5145.2  781.40  5157.1  782.63
  5175.2  782.60  5210.4  783.94  5280.6  784.93  5304.2  786.32  5362.8  788.25
#Mann=3,-1,0
  4670.5    0.05       0  5020.6    0.04       0  5024.6    0.05       0
Bank Sta=5020.6,5024.6
Exp/Cntr=0.3,0.1

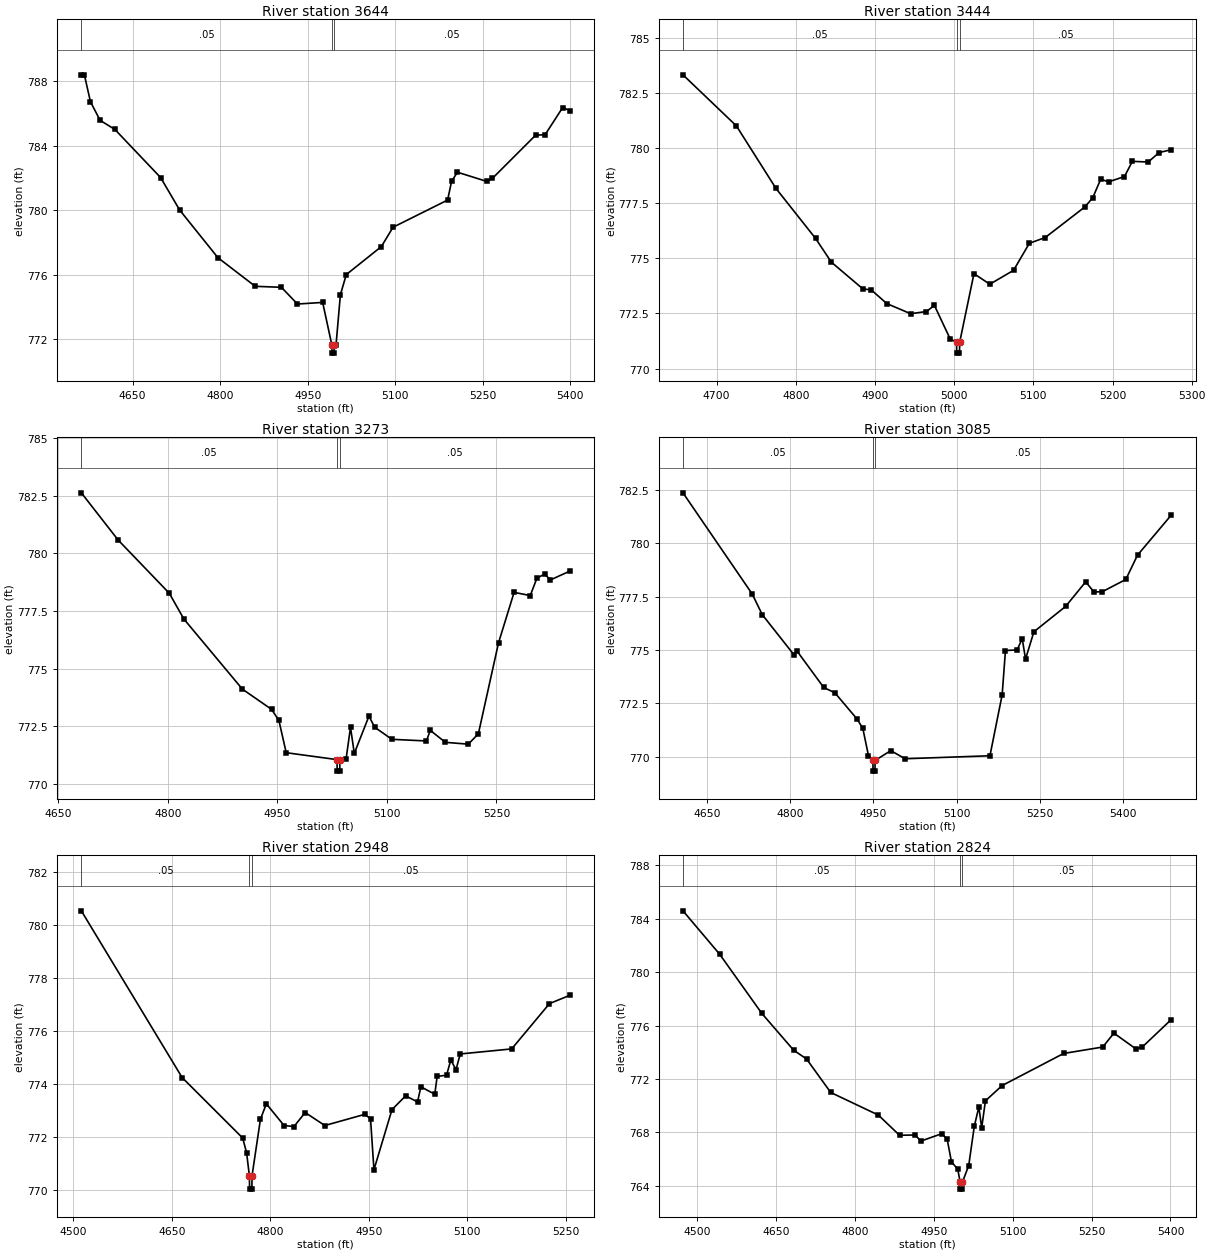
Type RM Length L Ch R = 1,3644,200,200,200
BEGIN DESCRIPTION:
MDW T 031 9.0
END DESCRIPTION:
XS GIS Cut Line= 3
      2298823.91      7102235.28      2298409.11      7102362.31
      2298007.01      7102388.94
#Sta/Elev= 30
  4562.2  788.41  4567.4  788.41  4577.8  786.74  4594.4  785.58  4619.6  785.02
  4698.0  782.03  4730.7  780.01  4796.2  777.05  4860.2  775.27  4905.0  775.21
  4932.5  774.17  4975.7  774.27  4991.5  771.62  4991.7  771.12  4995.2  771.12
  4995.5  771.62  4998.6  771.62  5006.1  774.75  5016.2  776.00  5076.3  777.74
  5096.3  778.94  5189.8  780.63  5196.6  781.79  5206.6  782.36  5256.7  781.79
  5266.7  781.98  5340.6  784.66  5356.9  784.69  5387.0  786.38  5399.0  786.19
#Mann=3,-1,0
  4562.2    0.05       0  4991.5    0.04       0  4995.5    0.05       0
Bank Sta=4991.5,4995.5
Exp/Cntr=0.3,0.1

Type RM Length L Ch R = 1,3444,171,171,171
BEGIN DESCRIPTION:
Mapping XS 41a6e6ce
END DESCRIPTION:
XS GIS Cut Line= 2
      2298746.45      7102157.23      2298129.82      7102175.49
#Sta/Elev= 30
  4657.4  783.34  4724.9  781.02  4774.9  778.18  4824.9  775.91  4844.9  774.83
  4884.9  773.61  4895.0  773.58  4914.9  772.95  4945.0  772.49  4965.0  772.59
  4975.0  772.87  4995.0  771.34  5003.0  771.20  5003.2  770.70  5006.7  770.70
  5007.0  771.20  5025.0  774.31  5045.0  773.83  5075.0  774.46  5095.0  775.69
  5115.0  775.95  5165.1  777.34  5175.1  777.76  5185.1  778.60  5195.1  778.48
  5215.1  778.72  5225.1  779.41  5245.1  779.38  5258.9  779.81  5274.3  779.94
#Mann=3,-1,0
  4657.4    0.05       0  5003.0    0.04       0  5007.0    0.05       0
Bank Sta=5003,5007
Exp/Cntr=0.3,0.1

Type RM Length L Ch R = 1,3273,188,188,188
BEGIN DESCRIPTION:
Mapping XS 5f4f2698
END DESCRIPTION:
XS GIS Cut Line= 3
      2298769.36      7102015.03      2298453.07      7102009.67
      2298116.16      7102111.84
#Sta/Elev= 30
  4681.8  782.63  4732.2  780.58  4802.2  778.27  4822.2  777.15  4902.2  774.11
  4942.2  773.23  4952.2  772.75  4962.2  771.35  5031.7  771.05  5032.0  770.55
  5035.5  770.55  5035.7  771.05  5044.2  771.09  5050.2  772.45  5055.4  771.32
  5075.5  772.94  5083.1  772.46  5106.9  771.93  5154.1  771.86  5159.4  772.32
  5180.0  771.80  5211.4  771.72  5225.2  772.17  5252.8  776.12  5274.1  778.31
  5296.2  778.17  5305.4  778.93  5315.9  779.10  5323.9  778.85  5350.2  779.23
#Mann=3,-1,0
  4681.8    0.05       0  5031.7    0.04       0  5035.7    0.05       0
Bank Sta=5031.7,5035.7
Exp/Cntr=0.3,0.1

Type RM Length L Ch R = 1,3085,137,137,137
BEGIN DESCRIPTION:
MDW T 031 8.0
END DESCRIPTION:
XS GIS Cut Line= 4
      2298800.95      7101880.17      2298415.80      7101831.85
      2298283.97      7101864.29      2297985.29      7102059.97
#Sta/Elev= 30
  4606.5  782.36  4731.4  777.62  4749.6  776.65  4806.8  774.77  4811.9  774.96
  4860.4  773.24  4880.6  772.99  4920.9  771.75  4931.0  771.32  4941.1  770.05
  4949.1  769.82  4949.4  769.32  4952.9  769.32  4953.1  769.82  4981.4  770.28
  5007.3  769.90  5160.3  770.04  5182.3  772.89  5188.3  774.97  5209.4  775.00
  5218.5  775.53  5224.5  774.57  5239.6  775.85  5296.9  777.04  5333.0  778.19
  5348.1  777.71  5363.2  777.73  5405.4  778.30  5426.5  779.44  5487.5  781.32
#Mann=3,-1,0
  4606.5    0.05       0  4949.1   0.033       0  4953.1    0.05       0
Bank Sta=4949.1,4953.1
Exp/Cntr=0.3,0.1

Type RM Length L Ch R = 1,2948,124,124,124
BEGIN DESCRIPTION:
Mapping XS df23e778
END DESCRIPTION:
XS GIS Cut Line= 6
      2298762.27      7101820.52      2298530.75      7101805.85
      2298444.46      7101748.41      2298361.73      7101747.56
      2298249.69      7101780.83      2298087.00      7101911.94
#Sta/Elev= 30
  4512.0  780.54  4665.6  774.25  4757.8  771.97  4763.8  771.42  4768.1  770.54
  4768.4  770.04  4771.9  770.04  4772.1  770.54  4784.9  772.67  4793.9  773.26
  4820.9  772.44  4836.0  772.40  4853.1  772.93  4883.1  772.44  4943.7  772.86
  4952.7  772.70  4957.9  770.77  4985.4  773.04  5006.2  773.56  5024.3  773.33
  5029.5  773.90  5050.6  773.62  5054.2  774.29  5068.6  774.34  5075.0  774.91
  5083.0  774.55  5089.4  775.14  5167.8  775.33  5225.4  777.04  5256.2  777.35
#Mann=3,-1,0
  4512.0    0.05       0  4768.1   0.033       0  4772.1    0.05       0
Bank Sta=4768.1,4772.1
Exp/Cntr=0.3,0.1

Type RM Length L Ch R = 1,2824,154,154,154
BEGIN DESCRIPTION:
MDW T 031 7.0
END DESCRIPTION:
XS GIS Cut Line= 3
      2298848.17      7101710.12      2298320.78      7101653.17
      2297946.26      7101786.51
#Sta/Elev= 30
  4473.6  784.58  4543.2  781.34  4623.6  776.90  4684.0  774.15  4708.4  773.50
  4754.4  770.99  4844.9  769.30  4885.1  767.79  4915.3  767.81  4925.4  767.35
  4965.6  767.91  4975.7  767.49  4983.8  765.80  4995.8  765.25  5000.4  764.26
  5000.7  763.76  5004.2  763.76  5004.4  764.26  5016.6  765.52  5027.2  768.46
  5035.9  769.91  5041.2  768.34  5048.4  770.37  5080.2  771.51  5197.0  773.91
  5271.3  774.39  5292.5  775.43  5333.6  774.27  5345.6  774.36  5401.6  776.45
#Mann=3,-1,0
  4473.6    0.05       0  5000.4    0.04       0  5004.4    0.05       0
Bank Sta=5000.4,5004.4
Exp/Cntr=0.3,0.1