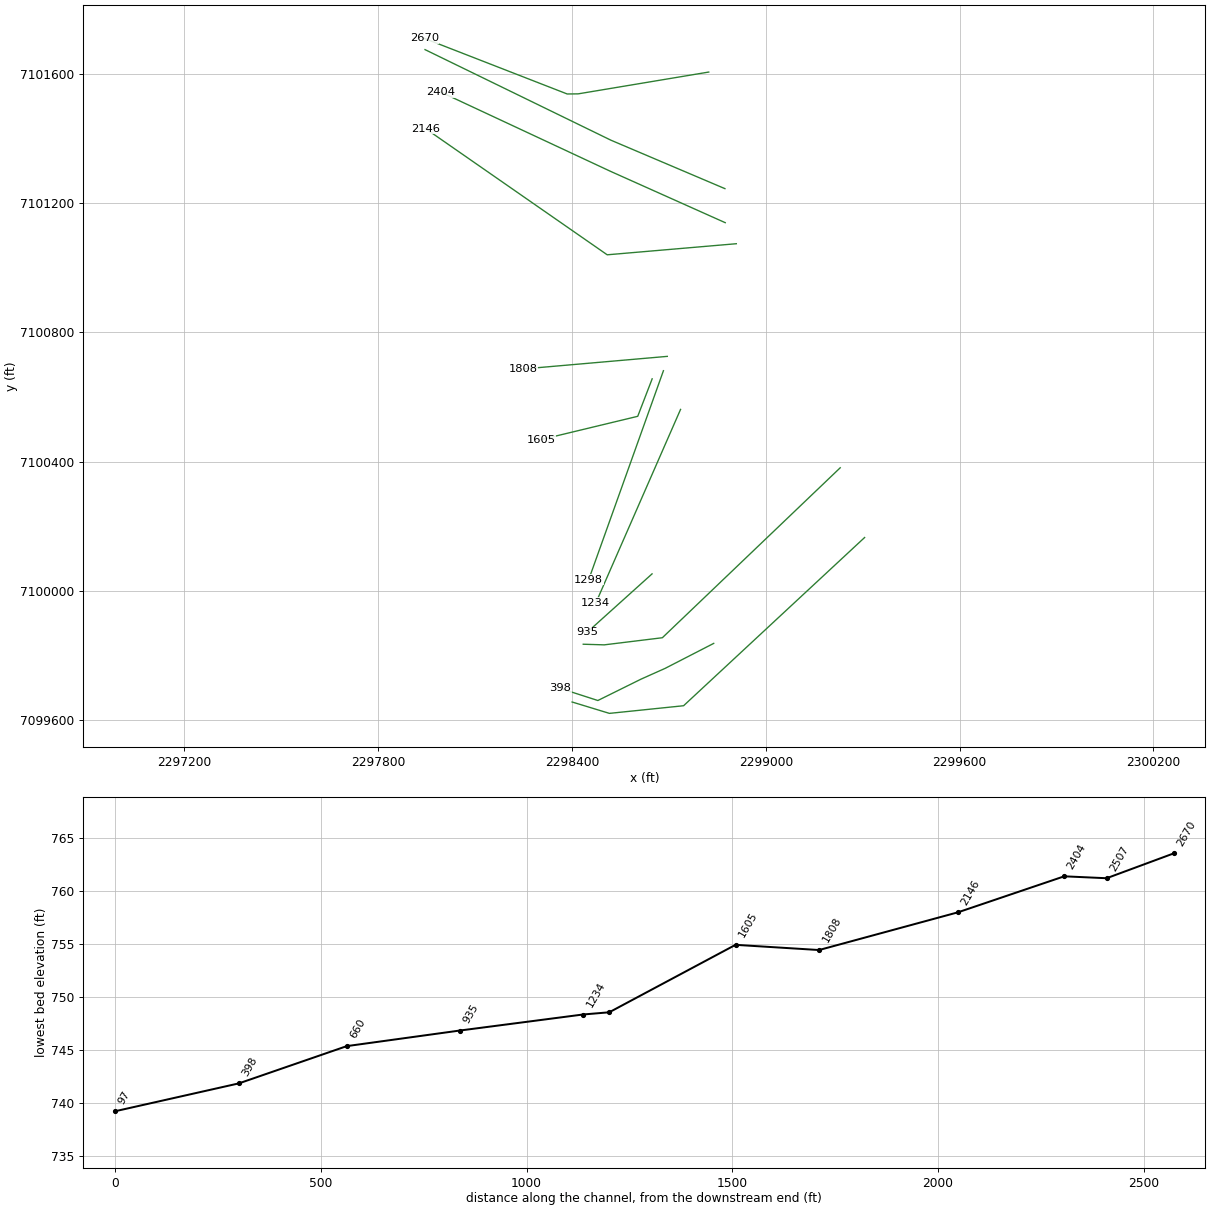
HEC-RAS study MDW T 031.prj: MDW T 031 Base Level Engineering

--- MDW T 031.g01 (geometry) --- (continued)

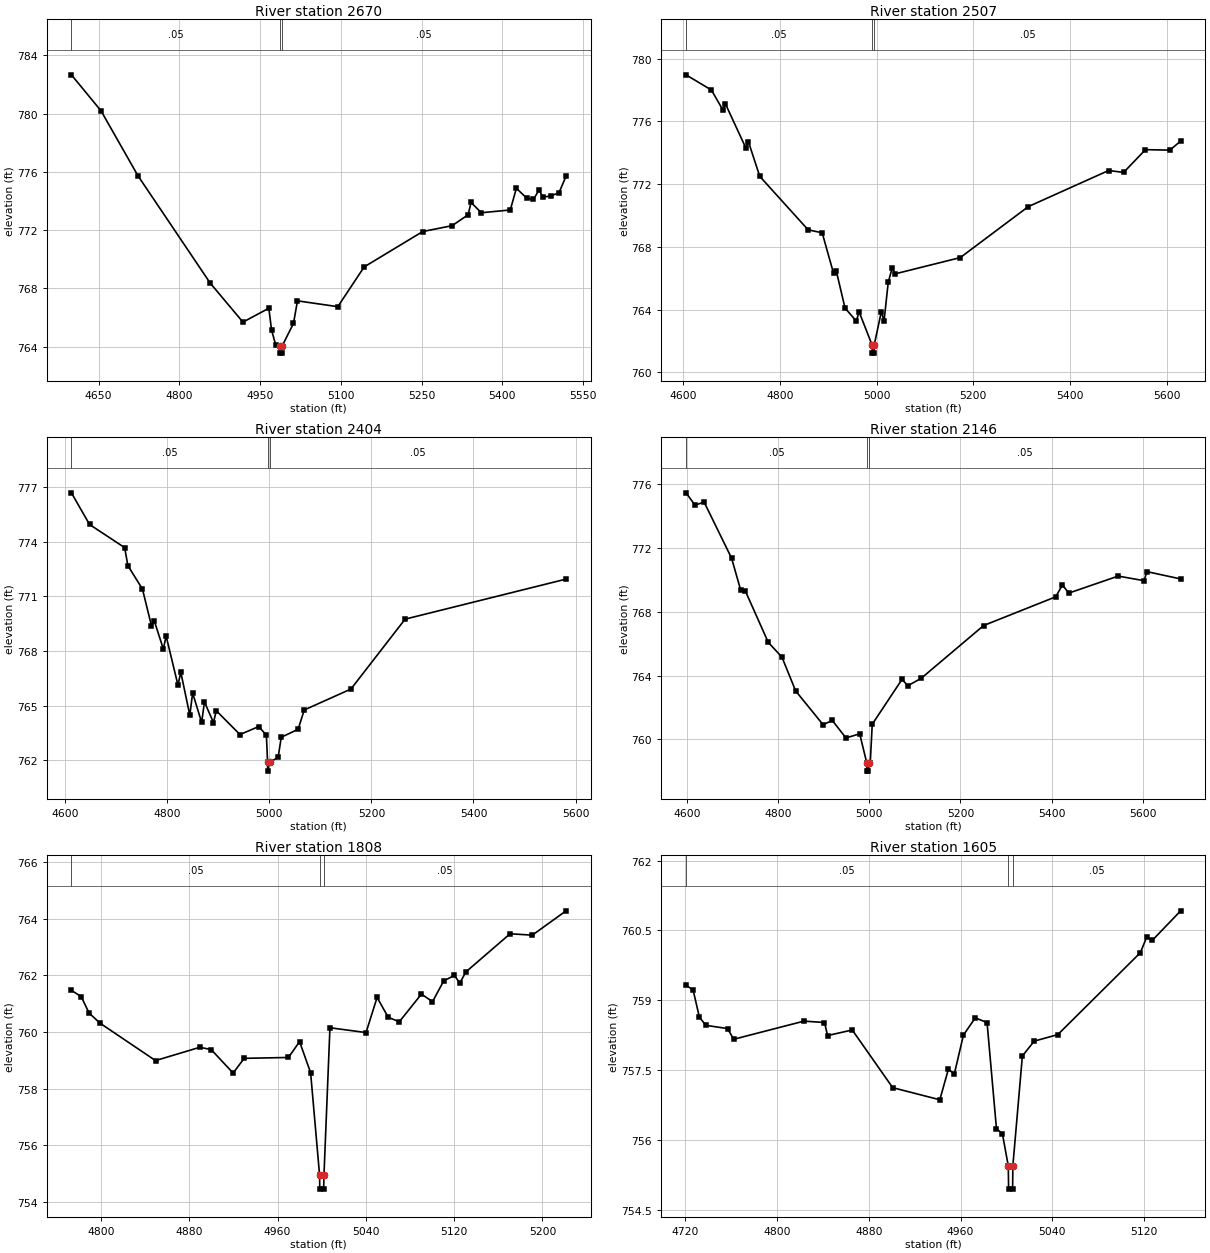
Type RM Length L Ch R = 1,2670,163,163,163
BEGIN DESCRIPTION:
Mapping XS c7fc835b
END DESCRIPTION:
XS GIS Cut Line= 4
      2298823.29      7101605.79      2298418.81      7101538.26
      2298385.06      7101537.91      2297942.43      7101710.17
#Sta/Elev= 30
  4599.6  782.67  4654.6  780.20  4723.2  775.74  4857.4  768.37  4918.2  765.69
  4966.3  766.64  4971.4  765.14  4979.1  764.12  4987.2  764.06  4987.5  763.56
  4991.0  763.56  4991.2  764.06  5012.1  765.60  5019.5  767.15  5094.4  766.75
  5143.4  769.48  5252.2  771.91  5306.6  772.31  5336.5  773.06  5341.9  773.91
  5361.0  773.20  5414.8  773.39  5426.1  774.88  5445.3  774.20  5457.7  774.11
  5468.4  774.77  5475.2  774.26  5489.9  774.36  5505.1  774.56  5518.4  775.71
#Mann=3,-1,0
  4599.6    0.05       0  4987.2    0.04       0  4991.2    0.05       0
Bank Sta=4987.2,4991.2
Exp/Cntr=0.3,0.1

Type RM Length L Ch R = 1,2507,103,103,103
BEGIN DESCRIPTION:
MDW T 031 6.0
END DESCRIPTION:
XS GIS Cut Line= 3
      2298873.38      7101244.83      2298520.21      7101394.92
      2297944.90      7101675.22
#Sta/Elev= 30
  4605.5  778.96  4658.1  777.99  4681.8  776.72  4687.2  777.10  4729.1  774.31
  4734.5  774.71  4758.1  772.49  4858.2  769.08  4887.3  768.89  4910.9  766.30
  4916.3  766.48  4934.6  764.09  4958.0  763.26  4963.6  763.86  4990.8  761.72
  4991.0  761.22  4994.5  761.22  4994.8  761.72  5009.8  763.87  5015.3  763.26
  5024.0  765.74  5032.3  766.66  5037.9  766.27  5173.1  767.31  5313.9  770.56
  5480.0  772.86  5511.2  772.74  5556.3  774.19  5606.9  774.16  5629.2  774.74
#Mann=3,-1,0
  4605.5    0.05       0  4990.8    0.05       0  4994.8    0.05       0
Bank Sta=4990.8,4994.8
Exp/Cntr=0.3,0.1

Type RM Length L Ch R = 1,2404,258,258,258
BEGIN DESCRIPTION:
MDW T 031 5.5
END DESCRIPTION:
XS GIS Cut Line= 3
      2298874.28      7101139.47      2298519.01      7101298.48
      2297993.15      7101544.04
#Sta/Elev= 30
  4611.9  776.69  4647.5  774.95  4716.3  773.68  4722.6  772.69  4751.2  771.40
  4768.9  769.38  4774.4  769.65  4792.1  768.11  4797.6  768.82  4820.8  766.12
  4826.3  766.84  4844.0  764.47  4849.5  765.69  4867.2  764.08  4872.7  765.20
  4890.4  764.07  4895.9  764.72  4942.3  763.41  4979.2  763.85  4994.1  763.37
  4996.4  761.90  4996.6  761.40  5000.4  761.90  5017.1  762.15  5023.2  763.26
  5056.3  763.70  5068.3  764.76  5159.8  765.91  5266.0  769.75  5581.5  771.95
#Mann=3,-1,0
  4611.9    0.05       0  4996.4    0.05       0  5000.4    0.05       0
Bank Sta=4996.4,5000.4
Exp/Cntr=0.3,0.1

Type RM Length L Ch R = 1,2146,338,338,338
BEGIN DESCRIPTION:
MDW T 031 5.0
END DESCRIPTION:
XS GIS Cut Line= 3
      2298908.59      7101074.33      2298508.90      7101040.04
      2297947.19      7101430.25
#Sta/Elev= 30
  4598.1  775.46  4617.8  774.69  4637.8  774.88  4698.1  771.36  4718.1  769.35
  4728.2  769.31  4778.4  766.09  4808.5  765.16  4838.6  763.04  4898.8  760.92
  4918.9  761.19  4949.0  760.09  4979.1  760.35  4994.7  758.51  4994.9  758.01
  4998.4  758.01  4998.7  758.51  5002.2  758.51  5006.6  760.95  5072.1  763.77
  5084.4  763.36  5114.0  763.83  5251.0  767.14  5409.1  768.94  5423.9  769.69
  5437.5  769.17  5546.1  770.24  5602.9  769.95  5609.0  770.52  5683.2  770.06
#Mann=3,-1,0
  4598.1    0.05       0  4994.7   0.033       0  4998.7    0.05       0
Bank Sta=4994.7,4998.7
Exp/Cntr=0.3,0.1

Type RM Length L Ch R = 1,1808,203,203,203
BEGIN DESCRIPTION:
Mapping XS abe44724
END DESCRIPTION:
XS GIS Cut Line= 2
      2298694.89      7100725.60      2298248.50      7100686.59
#Sta/Elev= 30
  4773.3  761.47  4782.2  761.25  4789.3  760.67  4799.3  760.31  4849.5  758.99
  4889.6  759.46  4899.9  759.38  4919.8  758.55  4929.8  759.07  4969.9  759.10
  4980.0  759.66  4990.0  758.56  4998.1  754.95  4998.3  754.45  5001.8  754.45
  5002.1  754.95  5007.5  760.15  5040.2  759.98  5050.2  761.22  5060.3  760.52
  5070.3  760.36  5090.4  761.34  5100.4  761.07  5110.5  761.80  5120.1  762.00
  5125.2  761.73  5130.6  762.12  5170.7  763.47  5190.8  763.42  5221.4  764.28
#Mann=3,-1,0
  4773.3    0.05       0  4998.1   0.033       0  5002.1    0.05       0
Bank Sta=4998.1,5002.1
Exp/Cntr=0.3,0.1

Type RM Length L Ch R = 1,1605,307,307,307
BEGIN DESCRIPTION:
Mapping XS 893257c2
END DESCRIPTION:
XS GIS Cut Line= 3
      2298648.06      7100656.05      2298603.37      7100540.02
      2298304.74      7100468.12
#Sta/Elev= 30
  4720.5  759.32  4726.7  759.22  4732.1  758.64  4737.7  758.46  4756.7  758.39
  4762.1  758.16  4823.4  758.55  4841.3  758.52  4844.0  758.24  4865.5  758.36
  4900.8  757.12  4941.9  756.86  4949.4  757.52  4954.5  757.41  4962.5  758.25
  4972.8  758.62  4983.1  758.52  4991.3  756.24  4996.5  756.13  5001.6  755.44
  5001.9  754.94  5005.4  754.94  5005.6  755.44  5013.9  757.80  5024.2  758.12
  5044.8  758.26  5116.8  760.02  5122.3  760.35  5127.4  760.29  5152.0  760.92
#Mann=3,-1,0
  4720.5    0.05       0  5001.6    0.04       0  5005.6    0.05       0
Bank Sta=5001.6,5005.6
Exp/Cntr=0.3,0.1

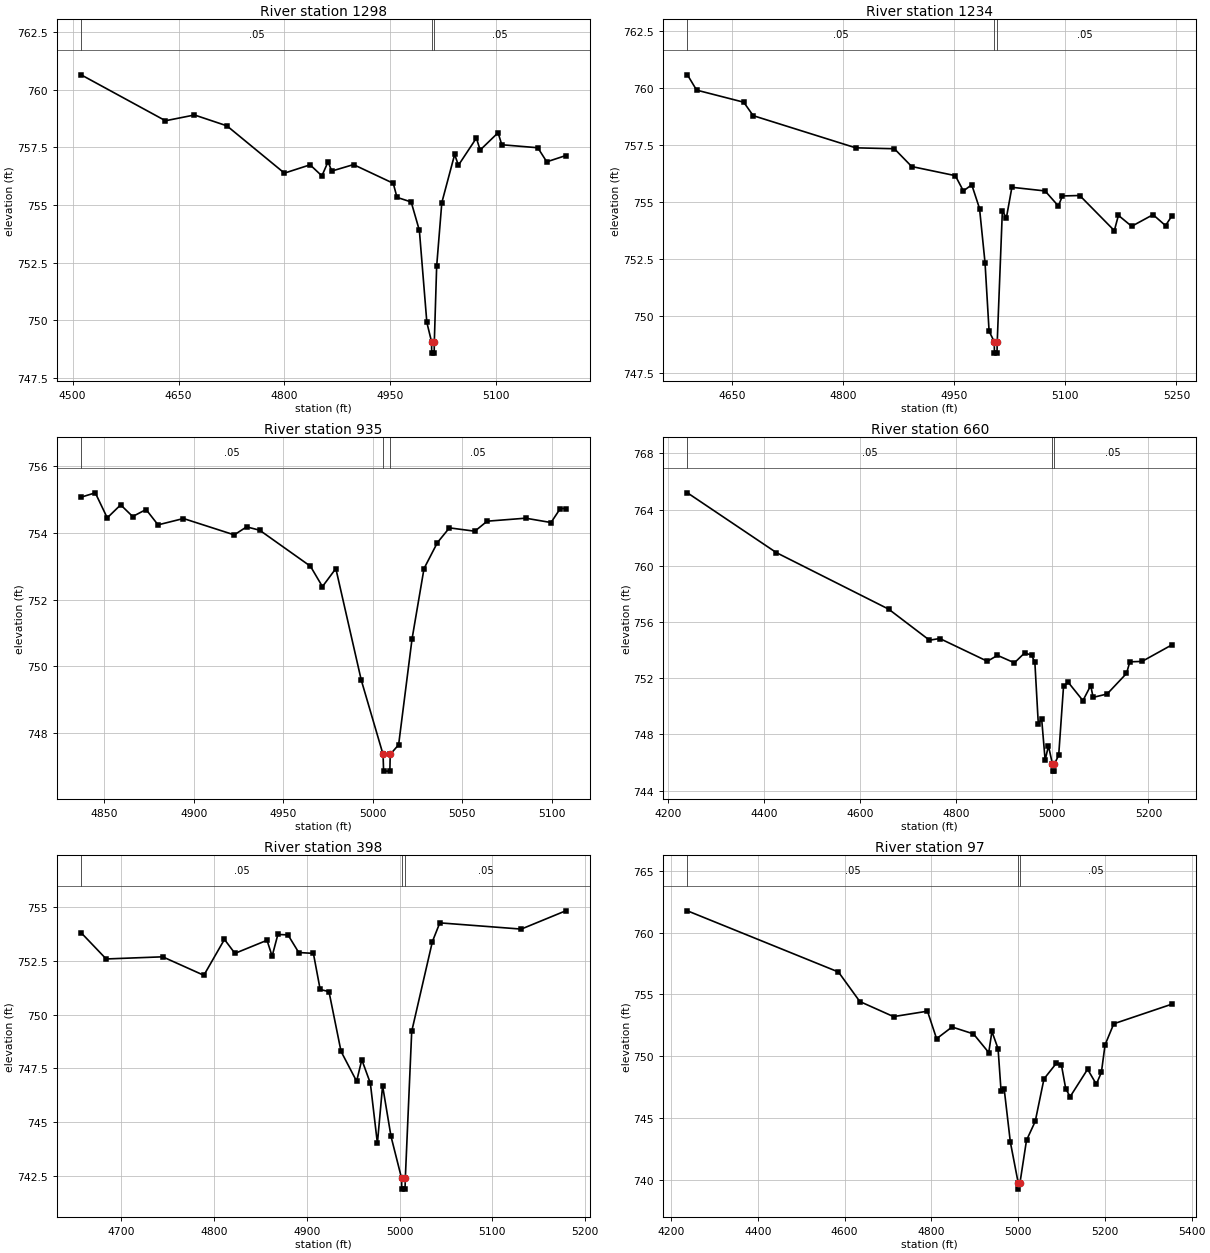
Type RM Length L Ch R = 1,1298,64,64,64
BEGIN DESCRIPTION:
Mapping XS c56d1e10
END DESCRIPTION:
XS GIS Cut Line= 2
      2298682.95      7100681.18      2298451.77      7100034.77
#Sta/Elev= 30
  4512.0  760.64  4631.5  758.65  4672.6  758.90  4718.5  758.43  4800.0  756.38
  4836.4  756.74  4853.1  756.26  4861.8  756.87  4867.1  756.47  4897.9  756.75
  4954.2  755.94  4959.5  755.33  4979.6  755.13  4991.2  753.90  5001.8  749.91
  5008.4  749.08  5008.7  748.58  5012.2  748.58  5012.4  749.08  5015.7  752.34
  5023.0  755.10  5041.2  757.19  5046.5  756.72  5072.0  757.90  5077.3  757.38
  5102.7  758.13  5108.0  757.61  5159.0  757.48  5171.7  756.87  5198.5  757.14
#Mann=3,-1,0
  4512.0    0.05       0  5008.4   0.033       0  5012.4    0.05       0
Bank Sta=5008.4,5012.4
Exp/Cntr=0.3,0.1

Type RM Length L Ch R = 1,1234,299,299,299
BEGIN DESCRIPTION:
Mapping XS 44556dbf
END DESCRIPTION:
XS GIS Cut Line= 3
      2298735.93      7100561.31      2298519.64      7100067.26
      2298473.58      7099962.02
#Sta/Elev= 30
  4589.7  760.57  4602.1  759.90  4665.7  759.37  4678.5  758.78  4816.9  757.37
  4869.1  757.33  4892.5  756.55  4951.4  756.15  4962.3  755.48  4973.6  755.75
  4984.1  754.71  4991.5  752.34  4997.0  749.33  5004.0  748.87  5004.2  748.37
  5007.7  748.37  5008.0  748.87  5014.9  754.59  5020.4  754.31  5027.8  755.64
  5072.6  755.48  5090.5  754.82  5096.0  755.26  5119.4  755.28  5166.1  753.74
  5171.6  754.41  5189.5  753.93  5218.4  754.44  5235.2  753.96  5243.9  754.39
#Mann=3,-1,0
  4589.7    0.05       0  5004.0   0.033       0  5008.0    0.05       0
Bank Sta=5004,5008
Exp/Cntr=0.3,0.1

Type RM Length L Ch R = 1,935,275,275,275
BEGIN DESCRIPTION:
Mapping XS c736cb3b
END DESCRIPTION:
XS GIS Cut Line= 2
      2298647.71      7100052.20      2298446.39      7099870.94
#Sta/Elev= 30
  4837.0  755.07  4844.9  755.20  4851.6  754.45  4859.1  754.84  4865.8  754.49
  4873.3  754.70  4880.0  754.24  4894.2  754.43  4922.6  753.94  4929.5  754.18
  4936.8  754.08  4965.2  753.00  4971.9  752.39  4979.4  752.93  4993.6  749.59
  5005.8  747.36  5006.1  746.86  5009.6  746.86  5009.8  747.36  5014.5  747.65
  5022.0  750.82  5028.7  752.93  5036.2  753.71  5042.9  754.15  5057.1  754.05
  5064.0  754.35  5085.5  754.44  5099.7  754.31  5104.9  754.73  5107.9  754.73
#Mann=3,-1,0
  4837.0    0.05       0  5005.8   0.033       0  5009.8    0.05       0
Bank Sta=5005.8,5009.8
Exp/Cntr=0.3,0.1

Type RM Length L Ch R = 1,660,262,262,262
BEGIN DESCRIPTION:
MDW T 031 1.0
END DESCRIPTION:
XS GIS Cut Line= 4
      2299230.24      7100380.70      2298679.62      7099854.55
      2298499.73      7099832.49      2298434.68      7099834.44
#Sta/Elev= 30
  4241.0  765.20  4426.2  760.94  4659.6  756.92  4744.5  754.71  4765.9  754.83
  4864.9  753.21  4886.0  753.63  4921.2  753.10  4942.6  753.81  4956.8  753.64
  4963.7  753.15  4970.9  748.74  4977.8  749.13  4985.1  746.17  4992.0  747.19
  5000.3  745.89  5000.5  745.39  5004.0  745.39  5004.3  745.89  5013.3  746.52
  5023.4  751.44  5033.4  751.70  5063.7  750.41  5079.9  751.48  5084.9  750.64
  5114.0  750.88  5154.3  752.34  5161.3  753.17  5186.7  753.20  5248.9  754.38
#Mann=3,-1,0
  4241.0    0.05       0  5000.3   0.033       0  5004.3    0.05       0
Bank Sta=5000.3,5004.3
Exp/Cntr=0.3,0.1

Type RM Length L Ch R = 1,398,301,301,301
BEGIN DESCRIPTION:
Mapping XS 5ba048ad
END DESCRIPTION:
XS GIS Cut Line= 5
      2298838.62      7099837.04      2298688.28      7099759.74
      2298613.96      7099726.51      2298479.90      7099660.20
      2298363.45      7099697.81
#Sta/Elev= 30
  4656.7  753.81  4683.7  752.59  4744.6  752.69  4789.0  751.83  4811.2  753.50
  4822.5  752.85  4857.1  753.46  4862.6  752.72  4868.8  753.73  4879.7  753.71
  4891.3  752.89  4907.1  752.85  4914.4  751.17  4923.9  751.07  4936.9  748.29
  4953.7  746.90  4959.3  747.90  4968.5  746.81  4976.1  744.01  4981.7  746.69
  4990.8  744.33  5002.2  742.38  5002.4  741.88  5005.9  741.88  5006.2  742.38
  5013.1  749.22  5035.4  753.40  5043.4  754.27  5131.2  753.98  5179.1  754.83
#Mann=3,-1,0
  4656.7    0.05       0  5002.2    0.04       0  5006.2    0.05       0
Bank Sta=5002.2,5006.2
Exp/Cntr=0.3,0.1

Type RM Length L Ch R = 1,97,0,0,0
BEGIN DESCRIPTION:
MDW T 031 0.5
END DESCRIPTION:
XS GIS Cut Line= 4
      2299305.74      7100164.79      2298745.35      7099644.02
      2298515.70      7099620.37      2298400.22      7099655.57
#Sta/Elev= 30
  4238.0  761.77  4586.0  756.82  4635.3  754.43  4713.0  753.21  4791.2  753.65
  4812.2  751.42  4847.8  752.37  4897.2  751.81  4932.4  750.30  4939.7  752.01
  4953.9  750.61  4960.7  747.21  4968.0  747.35  4982.2  743.05  5000.3  739.75
  5000.5  739.25  5004.3  739.75  5019.4  743.20  5039.5  744.73  5059.7  748.17
  5087.9  749.42  5099.9  749.29  5109.9  747.36  5120.0  746.73  5160.2  748.95
  5180.3  747.74  5192.0  748.70  5200.4  750.92  5220.5  752.63  5354.6  754.22
#Mann=3,-1,0
  4238.0    0.05       0  5000.3   0.033       0  5004.3    0.05       0
Bank Sta=5000.3,5004.3
Exp/Cntr=0.3,0.1

Chan Stop Cuts=-1