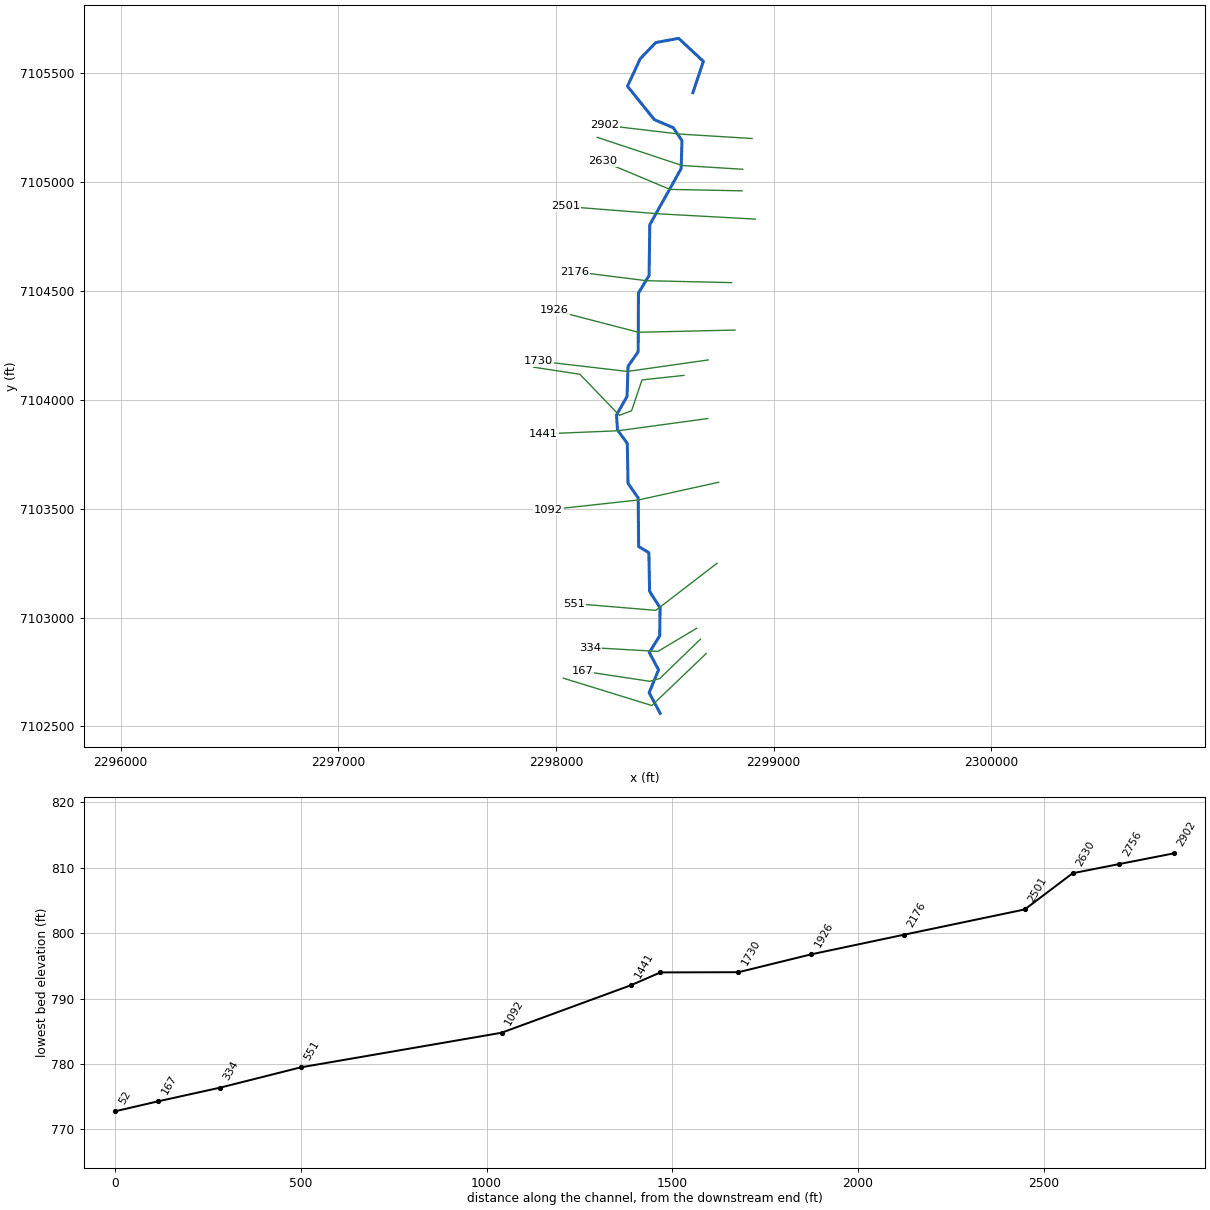
--- MDW T 032.prj (project) ---

Proj Title=MDW T 032 Base Level Engineering
Current Plan=p01
Default Exp/Contr=0.3,0.1
English Units
Geom File=g01
Flow File=f01
Plan File=p01
BEGIN DESCRIPTION:
MDW T 032
END DESCRIPTION:

--- MDW T 032.p01 (plan) ---

Plan Title=Multiple Run
Short Identifier=Multiple
Geom File=g01
Flow File=f01
Subcritical Flow
K Sum by GR= 0
Std Step Tol= 0.01
Critical Tol= 0.01
Num of Std Step Trials= 20
Max Error Tol= 0.3
Flow Tol Ratio= 0.001
Split Flow NTrial= 30
Split Flow Tol= 0.02
Split Flow Ratio= 0.02
Log Output Level= 0
Friction Slope Method= 1
Unsteady Friction Slope Method= 2
Unsteady Bridges Friction Slope Method= 1
Parabolic Critical Depth
Global Vel Dist=  1 , 1 , 1
Global Log Level= 0
CheckData=True
Encroach Param= -1, 0, 0, 0
BEGIN DESCRIPTION:
Multiple Run
END DESCRIPTION:

--- MDW T 032.f01 (steady flow) ---

Flow Title=Multiple
Number of Profiles=7
Profile Names=10-year,25-year,50-year,1pct_min,100-year,1pct_plu,500-year
River Rch & RM= MDW T 032,Reach-1,2902
     196     251     294     172     342     683     464
Boundary for River Rch & Prof#=MDW T 032,Reach-1,1
Up Type=0
Dn Type=3
Dn Slope=0.013
Boundary for River Rch & Prof#=MDW T 032,Reach-1,2
Up Type=0
Dn Type=3
Dn Slope=0.013
Boundary for River Rch & Prof#=MDW T 032,Reach-1,3
Up Type=0
Dn Type=3
Dn Slope=0.013
Boundary for River Rch & Prof#=MDW T 032,Reach-1,4
Up Type=0
Dn Type=3
Dn Slope=0.013
Boundary for River Rch & Prof#=MDW T 032,Reach-1,5
Up Type=0
Dn Type=3
Dn Slope=0.013
Boundary for River Rch & Prof#=MDW T 032,Reach-1,6
Up Type=0
Dn Type=3
Dn Slope=0.013
Boundary for River Rch & Prof#=MDW T 032,Reach-1,7
Up Type=0
Dn Type=3
Dn Slope=0.013

--- MDW T 032.g01 (geometry) ---

Geom Title=Existing Conditions

River Reach=MDW T 032,Reach-1
Reach XY= 30
      2298629.00      7105410.00      2298677.41      7105553.99
      2298563.79      7105659.77      2298458.80      7105640.44
      2298387.13      7105566.08      2298328.63      7105439.80
      2298452.18      7105286.30      2298539.06      7105249.38
      2298579.11      7105190.11      2298575.26      7105061.56
      2298431.24      7104804.07      2298427.78      7104570.50
      2298379.07      7104489.97      2298377.78      7104220.50
      2298331.27      7104154.06      2298326.73      7104015.94
      2298278.41      7103930.05      2298282.70      7103861.60
      2298327.78      7103799.50      2298331.26      7103615.94
      2298377.78      7103549.50      2298379.96      7103325.96
      2298427.03      7103298.03      2298430.22      7103120.51
      2298478.49      7103044.78      2298476.72      7102915.93
      2298428.79      7102839.79      2298471.41      7102760.01
      2298428.22      7102655.02      2298479.00      7102560.00

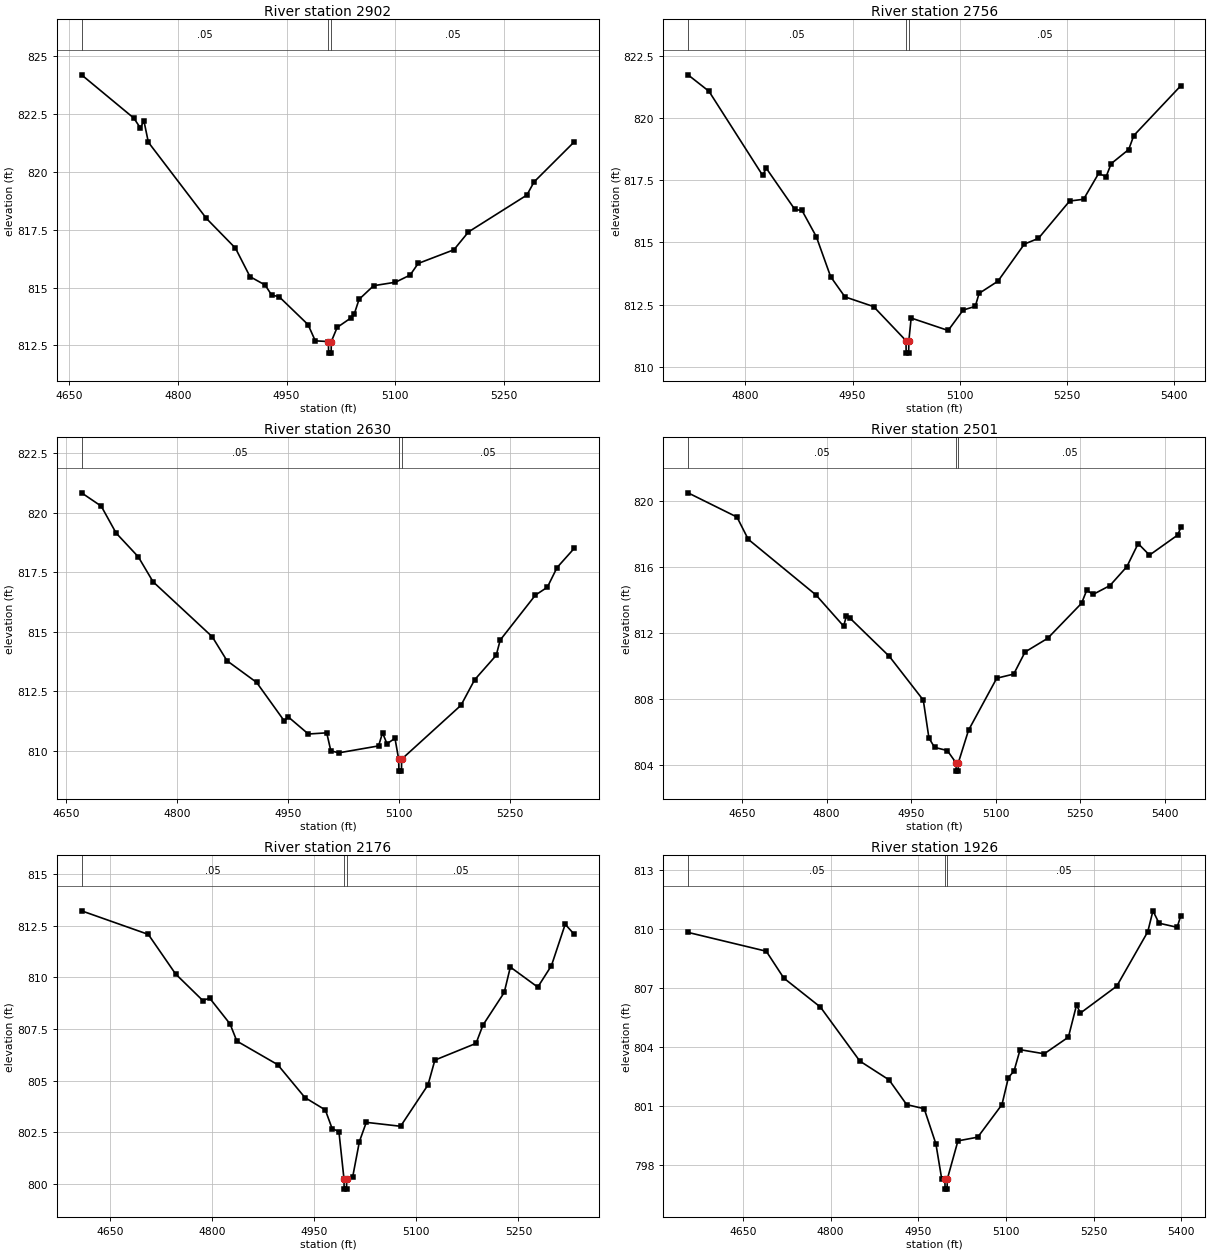
Type RM Length L Ch R = 1,2902,146,146,146
BEGIN DESCRIPTION:
MDW T 032 7.0
END DESCRIPTION:
XS GIS Cut Line= 3
      2298901.04      7105199.82      2298568.66      7105220.12
      2298223.93      7105260.59
#Sta/Elev= 30
  4667.0  824.18  4739.2  822.31  4748.1  821.89  4753.1  822.19  4759.2  821.27
  4839.4  817.98  4879.4  816.70  4899.5  815.47  4920.3  815.11  4929.5  814.67
  4939.5  814.61  4979.6  813.40  4989.6  812.70  5007.7  812.67  5008.0  812.17
  5011.5  812.17  5011.7  812.67  5019.8  813.28  5038.4  813.68  5043.4  813.86
  5050.0  814.49  5070.1  815.08  5100.3  815.23  5120.5  815.54  5131.6  816.04
  5180.9  816.63  5201.0  817.40  5281.6  818.99  5291.6  819.56  5347.1  821.29
#Mann=3,-1,0
  4667.0    0.05       0  5007.7   0.033       0  5011.7    0.05       0
Bank Sta=5007.7,5011.7
Exp/Cntr=0.3,0.1

Type RM Length L Ch R = 1,2756,126,126,126
BEGIN DESCRIPTION:
Mapping XS a41e36ab
END DESCRIPTION:
XS GIS Cut Line= 3
      2298858.29      7105058.56      2298580.15      7105075.73
      2298189.81      7105205.13
#Sta/Elev= 30
  4719.7  821.73  4749.0  821.07  4824.2  817.69  4829.2  817.98  4869.3  816.32
  4879.3  816.28  4899.3  815.23  4919.4  813.62  4939.4  812.81  4979.5  812.42
  5024.9  811.05  5025.1  810.55  5028.6  810.55  5028.9  811.05  5032.1  811.96
  5083.9  811.46  5104.9  812.28  5121.9  812.43  5127.2  812.95  5153.6  813.44
  5190.6  814.93  5210.3  815.16  5254.0  816.66  5273.5  816.73  5294.6  817.77
  5305.1  817.64  5312.1  818.16  5336.7  818.73  5343.8  819.29  5409.6  821.29
#Mann=3,-1,0
  4719.7    0.05       0  5024.9   0.033       0  5028.9    0.05       0
Bank Sta=5024.9,5028.9
Exp/Cntr=0.3,0.1

Type RM Length L Ch R = 1,2630,129,129,129
BEGIN DESCRIPTION:
Mapping XS 5dac8d09
END DESCRIPTION:
XS GIS Cut Line= 3
      2298855.64      7104959.49      2298524.18      7104966.10
      2298215.29      7105095.18
#Sta/Elev= 30
  4670.6  820.84  4697.2  820.28  4717.3  819.15  4747.3  818.15  4767.3  817.10
  4847.3  814.79  4867.3  813.78  4907.3  812.87  4944.7  811.25  4949.7  811.43
  4977.3  810.70  5002.1  810.75  5007.7  809.99  5018.6  809.91  5072.2  810.20
  5077.6  810.75  5083.6  810.29  5094.4  810.52  5099.4  809.64  5099.7  809.14
  5103.2  809.14  5103.4  809.64  5183.7  811.91  5202.1  812.98  5231.3  814.01
  5236.7  814.65  5284.3  816.54  5300.4  816.87  5313.6  817.70  5336.9  818.51
#Mann=3,-1,0
  4670.6    0.05       0  5099.4   0.033       0  5103.4    0.05       0
Bank Sta=5099.4,5103.4
Exp/Cntr=0.3,0.1

Type RM Length L Ch R = 1,2501,325,325,325
BEGIN DESCRIPTION:
MDW T 032 6.0
END DESCRIPTION:
XS GIS Cut Line= 3
      2298915.66      7104829.68      2298470.53      7104854.08
      2298043.66      7104887.81
#Sta/Elev= 30
  4554.2  820.50  4641.0  819.03  4661.0  817.68  4781.2  814.30  4830.2  812.41
  4835.2  813.03  4841.3  812.90  4911.4  810.57  4971.5  807.92  4981.5  805.62
  4991.5  805.05  5014.1  804.86  5029.6  804.11  5029.9  803.61  5033.4  803.61
  5033.6  804.11  5051.7  806.09  5101.8  809.25  5131.9  809.50  5152.0  810.84
  5192.1  811.67  5252.3  813.80  5261.5  814.60  5272.4  814.33  5302.5  814.87
  5332.6  816.02  5352.6  817.42  5372.7  816.72  5422.8  817.94  5428.2  818.40
#Mann=3,-1,0
  4554.2    0.05       0  5029.6   0.033       0  5033.6    0.05       0
Bank Sta=5029.6,5033.6
Exp/Cntr=0.3,0.1

Type RM Length L Ch R = 1,2176,250,250,250
BEGIN DESCRIPTION:
MDW T 032 5.0
END DESCRIPTION:
XS GIS Cut Line= 3
      2298807.11      7104538.02      2298415.21      7104546.86
      2298085.71      7104588.37
#Sta/Elev= 30
  4608.0  813.21  4706.1  812.07  4746.1  810.16  4786.2  808.87  4796.2  808.99
  4826.2  807.74  4836.2  806.91  4896.2  805.77  4936.2  804.18  4966.2  803.58
  4976.2  802.68  4986.2  802.53  4993.6  800.25  4993.9  799.75  4997.4  799.75
  4997.6  800.25  5006.3  800.32  5016.3  802.05  5026.4  802.98  5076.8  802.79
  5117.1  804.79  5127.2  805.99  5187.7  806.80  5197.8  807.68  5229.1  809.26
  5238.1  810.49  5278.4  809.52  5298.5  810.56  5318.7  812.56  5332.1  812.07
#Mann=3,-1,0
  4608.0    0.05       0  4993.6    0.04       0  4997.6    0.05       0
Bank Sta=4993.6,4997.6
Exp/Cntr=0.3,0.1

Type RM Length L Ch R = 1,1926,196,196,196
BEGIN DESCRIPTION:
MDW T 032 4.0
END DESCRIPTION:
XS GIS Cut Line= 3
      2298822.76      7104320.14      2298379.08      7104309.97
      2297992.96      7104410.16
#Sta/Elev= 30
  4556.2  809.84  4690.0  808.88  4720.0  807.51  4782.7  806.03  4850.0  803.28
  4900.0  802.32  4930.1  801.06  4960.1  800.85  4980.1  799.06  4990.1  797.26
  4995.5  797.25  4995.8  796.75  4999.3  796.75  4999.5  797.25  5017.8  799.21
  5051.7  799.40  5093.1  801.06  5104.1  802.44  5113.7  802.77  5124.1  803.86
  5165.4  803.65  5206.7  804.50  5220.6  806.13  5227.4  805.73  5289.4  807.10
  5342.4  809.87  5351.3  810.94  5361.7  810.31  5392.7  810.10  5398.9  810.69
#Mann=3,-1,0
  4556.2    0.05       0  4995.5    0.04       0  4999.5    0.05       0
Bank Sta=4995.5,4999.5
Exp/Cntr=0.3,0.1

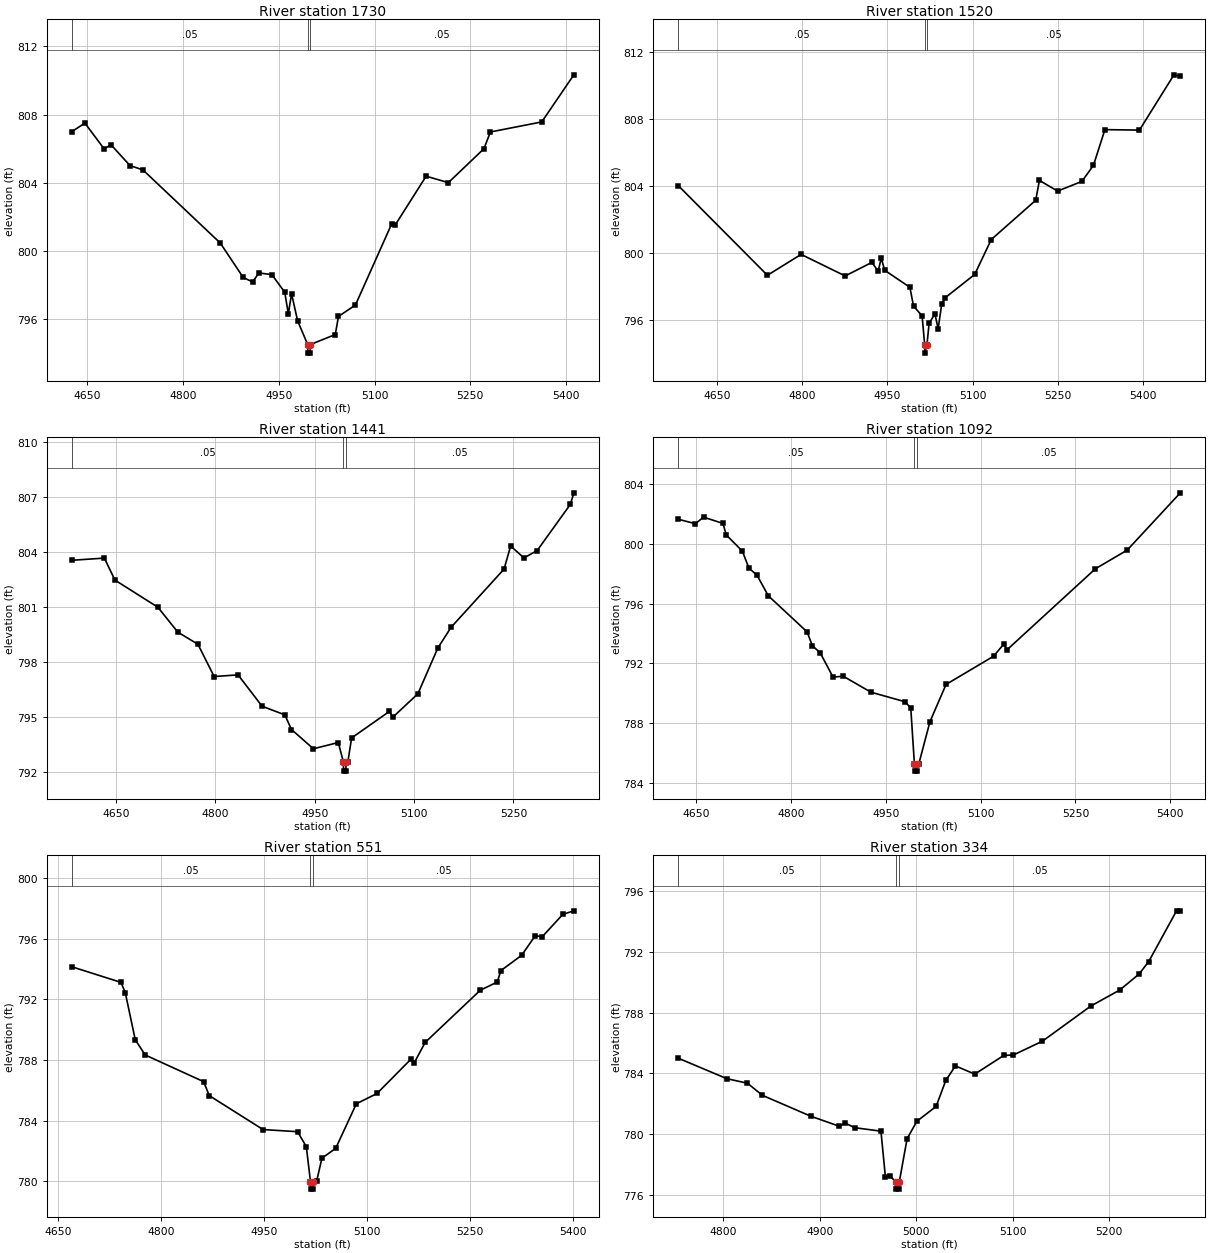
Type RM Length L Ch R = 1,1730,210,210,210
BEGIN DESCRIPTION:
MDW T 032 3.0
END DESCRIPTION:
XS GIS Cut Line= 3
      2298699.43      7104182.98      2298328.68      7104130.13
      2297919.04      7104177.78
#Sta/Elev= 30
  4625.5  807.00  4646.1  807.50  4676.4  805.98  4686.8  806.24  4716.8  805.01
  4737.0  804.76  4858.3  800.47  4894.1  798.46  4908.8  798.19  4918.9  798.72
  4939.1  798.62  4959.3  797.59  4964.9  796.33  4970.0  797.50  4979.5  795.91
  4995.3  794.52  4995.6  794.02  4999.1  794.02  4999.3  794.52  5038.5  795.11
  5043.5  796.17  5070.1  796.84  5127.1  801.61  5132.1  801.51  5180.9  804.39
  5215.7  804.01  5271.5  806.00  5281.6  806.98  5362.1  807.57  5412.4  810.33
#Mann=3,-1,0
  4625.5    0.05       0  4995.3    0.04       0  4999.3    0.05       0
Bank Sta=4995.3,4999.3
Exp/Cntr=0.3,0.1

Type RM Length L Ch R = 1,1520,79,79,79
BEGIN DESCRIPTION:
Mapping XS 170f66e3
END DESCRIPTION:
XS GIS Cut Line= 6
      2298588.16      7104112.10      2298395.56      7104091.21
      2298347.40      7103949.38      2298291.45      7103928.78
      2298109.79      7104117.21      2297897.91      7104149.53
#Sta/Elev= 30
  4582.2  804.02  4739.0  798.65  4798.3  799.90  4875.8  798.61  4922.7  799.42
  4933.9  798.90  4939.2  799.68  4945.3  798.95  4989.6  797.93  4996.0  796.81
  5011.1  796.22  5015.6  794.49  5015.9  793.99  5019.6  794.49  5023.4  795.77
  5033.6  796.34  5039.3  795.45  5045.5  796.91  5051.8  797.31  5103.6  798.70
  5132.7  800.79  5210.9  803.14  5217.4  804.33  5249.4  803.69  5292.1  804.27
  5312.4  805.23  5332.6  807.37  5393.3  807.34  5454.0  810.65  5465.2  810.55
#Mann=3,-1,0
  4582.2    0.05       0  5015.6    0.04       0  5019.6    0.05       0
Bank Sta=5015.6,5019.6
Exp/Cntr=0.3,0.1

Type RM Length L Ch R = 1,1441,349,349,349
BEGIN DESCRIPTION:
MDW T 032 2.0
END DESCRIPTION:
XS GIS Cut Line= 3
      2298697.78      7103913.89      2298284.68      7103857.69
      2297943.68      7103843.58
#Sta/Elev= 30
  4583.1  803.54  4632.3  803.66  4648.3  802.46  4713.1  800.98  4743.3  799.62
  4773.6  798.96  4798.1  797.20  4834.2  797.29  4870.5  795.58  4904.8  795.11
  4914.9  794.31  4948.0  793.26  4985.6  793.60  4993.3  792.54  4993.5  792.04
  4997.0  792.04  4997.3  792.54  5000.0  792.54  5005.7  793.85  5062.9  795.30
  5067.9  794.98  5105.8  796.26  5135.8  798.75  5155.8  799.88  5235.9  803.06
  5245.9  804.32  5265.9  803.67  5285.9  804.07  5336.0  806.59  5341.3  807.22
#Mann=3,-1,0
  4583.1    0.05       0  4993.3    0.04       0  4997.3    0.05       0
Bank Sta=4993.3,4997.3
Exp/Cntr=0.3,0.1

Type RM Length L Ch R = 1,1092,541,541,541
BEGIN DESCRIPTION:
MDW T 032 1.5
END DESCRIPTION:
XS GIS Cut Line= 3
      2298748.06      7103621.35      2298378.93      7103539.97
      2297965.48      7103494.85
#Sta/Elev= 30
  4622.0  801.65  4649.1  801.35  4662.0  801.79  4692.7  801.37  4697.9  800.60
  4723.4  799.51  4733.7  798.38  4746.7  797.89  4764.4  796.52  4825.8  794.10
  4834.1  793.17  4846.3  792.71  4866.8  791.07  4882.9  791.13  4926.7  790.06
  4980.6  789.42  4989.7  789.00  4995.4  785.27  4995.7  784.77  4999.2  784.77
  4999.4  785.27  5002.5  785.27  5020.0  788.08  5045.5  790.58  5120.6  792.47
  5136.9  793.29  5141.9  792.90  5281.6  798.33  5331.9  799.58  5415.9  803.42
#Mann=3,-1,0
  4622.0    0.05       0  4995.4    0.04       0  4999.4    0.05       0
Bank Sta=4995.4,4999.4
Exp/Cntr=0.3,0.1

Type RM Length L Ch R = 1,551,217,217,217
BEGIN DESCRIPTION:
MDW T 032 1.0
END DESCRIPTION:
XS GIS Cut Line= 3
      2298740.08      7103249.23      2298458.88      7103033.10
      2298083.04      7103064.27
#Sta/Elev= 30
  4669.5  794.15  4741.2  793.12  4747.5  792.44  4762.0  789.34  4776.5  788.33
  4861.7  786.57  4869.9  785.65  4948.3  783.41  4998.6  783.27  5011.4  782.28
  5017.4  779.98  5017.6  779.48  5021.1  779.48  5021.4  779.98  5026.6  780.04
  5034.1  781.52  5054.2  782.17  5084.3  785.11  5114.4  785.79  5163.8  788.05
  5168.9  787.83  5184.6  789.16  5264.9  792.60  5289.6  793.14  5295.0  793.90
  5325.1  794.90  5345.1  796.20  5355.2  796.13  5385.3  797.61  5401.3  797.84
#Mann=3,-1,0
  4669.5    0.05       0  5017.4    0.04       0  5021.4    0.05       0
Bank Sta=5017.4,5021.4
Exp/Cntr=0.3,0.1

Type RM Length L Ch R = 1,334,167,167,167
BEGIN DESCRIPTION:
Mapping XS 2cea3087
END DESCRIPTION:
XS GIS Cut Line= 3
      2298646.88      7102950.90      2298468.26      7102844.47
      2298156.30      7102862.42
#Sta/Elev= 30
  4753.2  785.01  4803.5  783.66  4824.9  783.36  4840.5  782.56  4890.4  781.19
  4920.3  780.52  4926.1  780.74  4935.9  780.43  4963.3  780.20  4967.9  777.20
  4972.9  777.24  4978.4  776.88  4978.7  776.38  4982.2  776.38  4982.4  776.88
  4990.4  779.70  5000.5  780.85  5020.5  781.83  5030.5  783.54  5040.5  784.50
  5060.6  783.96  5090.6  785.19  5100.6  785.22  5130.7  786.13  5180.7  788.44
  5210.8  789.50  5230.8  790.55  5240.8  791.37  5269.7  794.72  5273.6  794.72
#Mann=3,-1,0
  4753.2    0.05       0  4978.4    0.04       0  4982.4    0.05       0
Bank Sta=4978.4,4982.4
Exp/Cntr=0.3,0.1

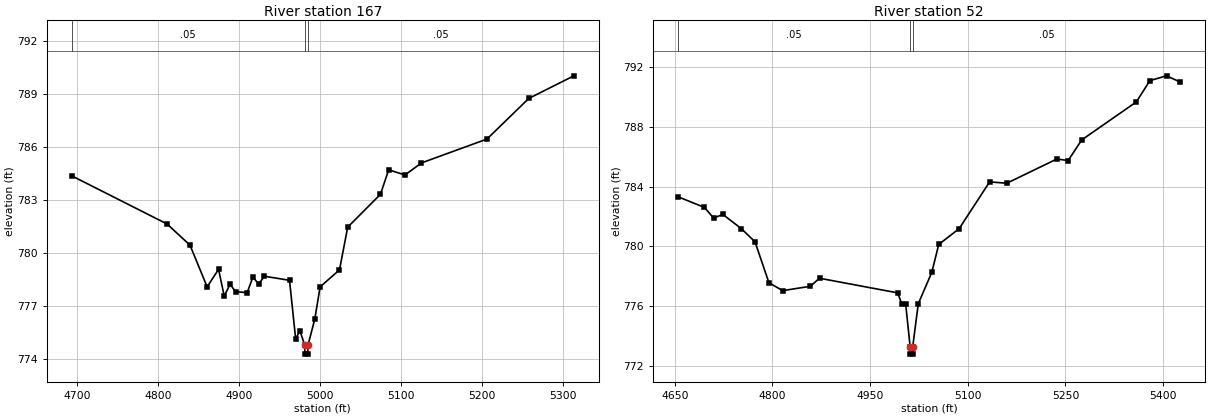
Type RM Length L Ch R = 1,167,115,115,115
BEGIN DESCRIPTION:
Mapping XS 3688c313
END DESCRIPTION:
XS GIS Cut Line= 4
      2298664.27      7102901.01      2298477.03      7102719.92
      2298431.29      7102707.21      2298122.97      7102753.95
#Sta/Elev= 30
  4693.4  784.36  4811.1  781.64  4839.4  780.44  4860.5  778.09  4874.6  779.08
  4881.6  777.57  4888.8  778.23  4895.7  777.82  4909.9  777.76  4917.1  778.65
  4924.0  778.24  4931.2  778.69  4962.2  778.46  4969.8  775.14  4975.0  775.62
  4981.0  774.79  4981.2  774.29  4984.7  774.29  4985.0  774.79  4993.4  776.27
  5000.0  778.09  5023.9  779.05  5034.0  781.46  5074.5  783.32  5084.6  784.70
  5104.8  784.41  5125.1  785.09  5206.0  786.44  5257.5  788.73  5313.2  790.01
#Mann=3,-1,0
  4693.4    0.05       0  4981.0    0.04       0  4985.0    0.05       0
Bank Sta=4981,4985
Exp/Cntr=0.3,0.1

Type RM Length L Ch R = 1,52,0,0,0
BEGIN DESCRIPTION:
MDW T 032 0.5
END DESCRIPTION:
XS GIS Cut Line= 3
      2298690.62      7102835.18      2298440.86      7102596.03
      2298034.37      7102721.46
#Sta/Elev= 30
  4655.3  783.31  4695.5  782.60  4709.7  781.89  4723.9  782.13  4752.2  781.18
  4773.2  780.30  4794.6  777.56  4815.7  777.03  4858.1  777.32  4872.3  777.86
  4992.4  776.88  4998.9  776.11  5004.7  776.11  5011.5  773.28  5011.8  772.78
  5015.3  772.78  5015.5  773.28  5024.0  776.15  5044.9  778.27  5055.4  780.12
  5086.8  781.18  5133.6  784.31  5160.0  784.22  5236.8  785.84  5254.2  785.74
  5275.1  787.12  5358.9  789.66  5379.8  791.09  5405.3  791.41  5426.5  790.99
#Mann=3,-1,0
  4655.3    0.05       0  5011.5    0.04       0  5015.5    0.05       0
Bank Sta=5011.5,5015.5
Exp/Cntr=0.3,0.1

Chan Stop Cuts=-1