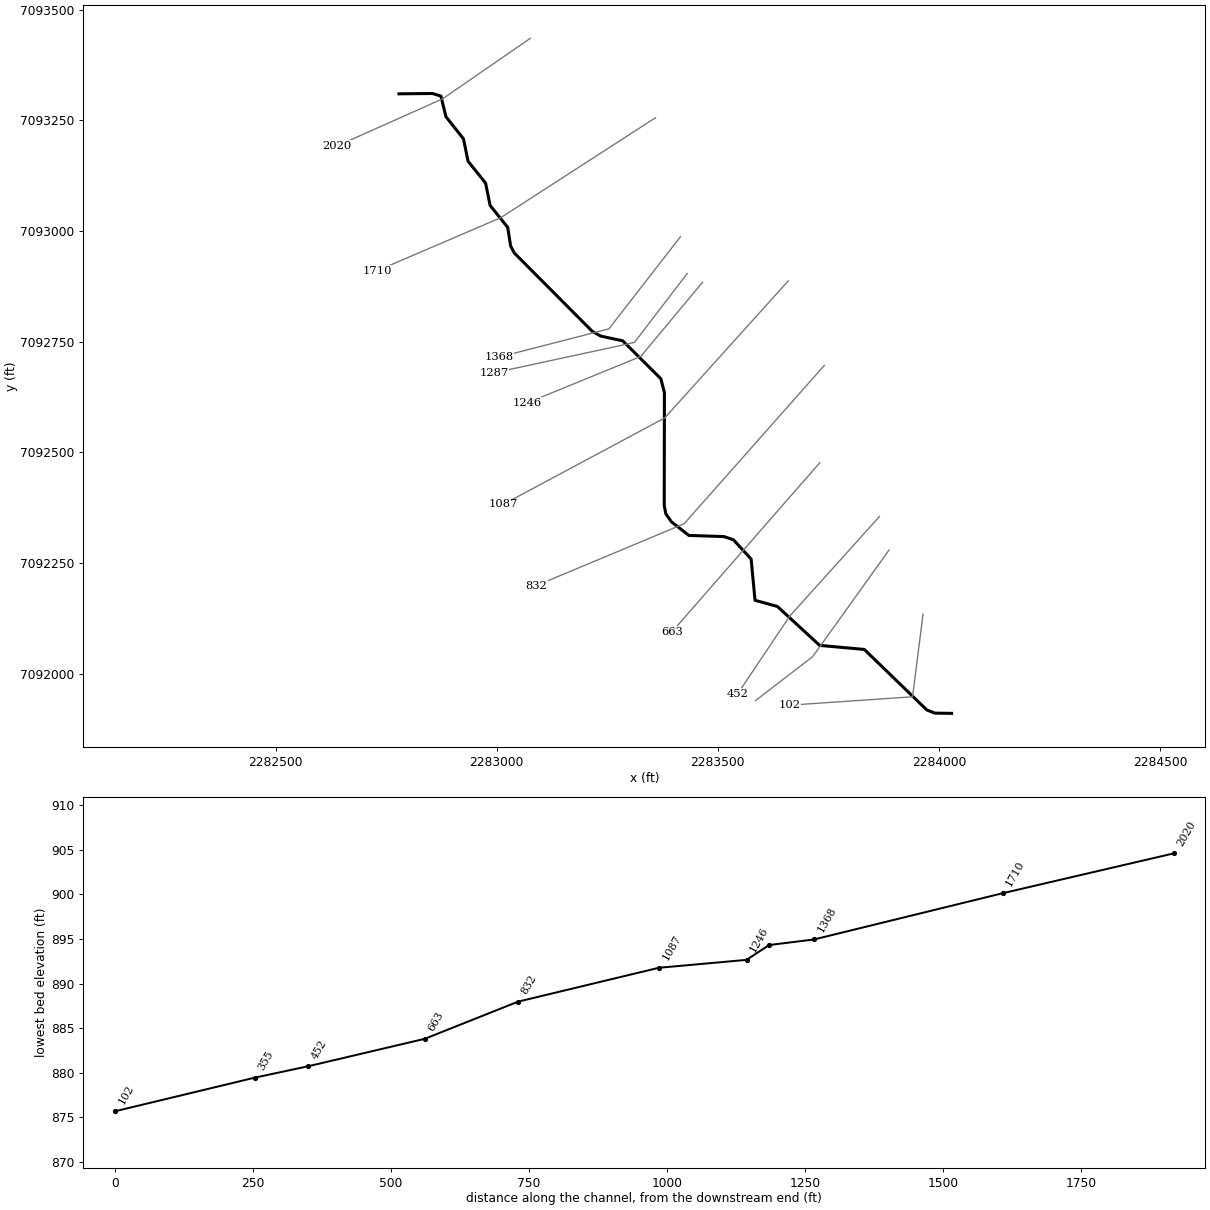
--- MDW T 034.prj (project) ---

Proj Title=MDW T 034 Base Level Engineering
Current Plan=p01
Default Exp/Contr=0.3,0.1
English Units
Geom File=g01
Flow File=f01
Plan File=p01
BEGIN DESCRIPTION:
MDW T 034
END DESCRIPTION:

--- MDW T 034.p01 (plan) ---

Plan Title=Multiple Run
Short Identifier=Multiple
Geom File=g01
Flow File=f01
Subcritical Flow
K Sum by GR= 0
Std Step Tol= 0.01
Critical Tol= 0.01
Num of Std Step Trials= 20
Max Error Tol= 0.3
Flow Tol Ratio= 0.001
Split Flow NTrial= 30
Split Flow Tol= 0.02
Split Flow Ratio= 0.02
Log Output Level= 0
Friction Slope Method= 1
Unsteady Friction Slope Method= 2
Unsteady Bridges Friction Slope Method= 1
Parabolic Critical Depth
Global Vel Dist=  1 , 1 , 1
Global Log Level= 0
CheckData=True
Encroach Param= -1, 0, 0, 0
BEGIN DESCRIPTION:
Multiple Run
END DESCRIPTION:

--- MDW T 034.f01 (steady flow) ---

Flow Title=Multiple
Number of Profiles=7
Profile Names=10-year,25-year,50-year,1pct_min,100-year,1pct_plu,500-year
River Rch & RM= MDW T 034,Reach-1,2020
     180     229     268     156     312     623     422
Boundary for River Rch & Prof#=MDW T 034,Reach-1,1
Up Type=0
Dn Type=3
Dn Slope=0.005
Boundary for River Rch & Prof#=MDW T 034,Reach-1,2
Up Type=0
Dn Type=3
Dn Slope=0.005
Boundary for River Rch & Prof#=MDW T 034,Reach-1,3
Up Type=0
Dn Type=3
Dn Slope=0.005
Boundary for River Rch & Prof#=MDW T 034,Reach-1,4
Up Type=0
Dn Type=3
Dn Slope=0.005
Boundary for River Rch & Prof#=MDW T 034,Reach-1,5
Up Type=0
Dn Type=3
Dn Slope=0.005
Boundary for River Rch & Prof#=MDW T 034,Reach-1,6
Up Type=0
Dn Type=3
Dn Slope=0.005
Boundary for River Rch & Prof#=MDW T 034,Reach-1,7
Up Type=0
Dn Type=3
Dn Slope=0.005

--- MDW T 034.g01 (geometry) ---

Geom Title=Existing Conditions

River Reach=MDW T 034,Reach-1
Reach XY= 30
      2282779.00      7093310.00      2282854.57      7093310.73
      2282873.73      7093305.01      2282885.22      7093258.17
      2282924.85      7093208.31      2282935.08      7093157.81
      2282974.84      7093108.28      2282985.08      7093057.80
      2283024.81      7093008.26      2283031.50      7092966.03
      2283039.76      7092950.32      2283215.79      7092773.63
      2283235.05      7092762.54      2283285.07      7092751.85
      2283371.20      7092666.21      2283379.30      7092635.13
      2283378.91      7092379.87      2283382.44      7092361.22
      2283395.24      7092342.78      2283434.69      7092312.07
      2283513.92      7092309.53      2283535.49      7092302.27
      2283575.46      7092258.67      2283584.26      7092165.47
      2283634.70      7092151.68      2283730.50      7092063.63
      2283831.43      7092054.48      2283972.79      7091917.76
      2283990.84      7091910.59      2284029.00      7091910.00

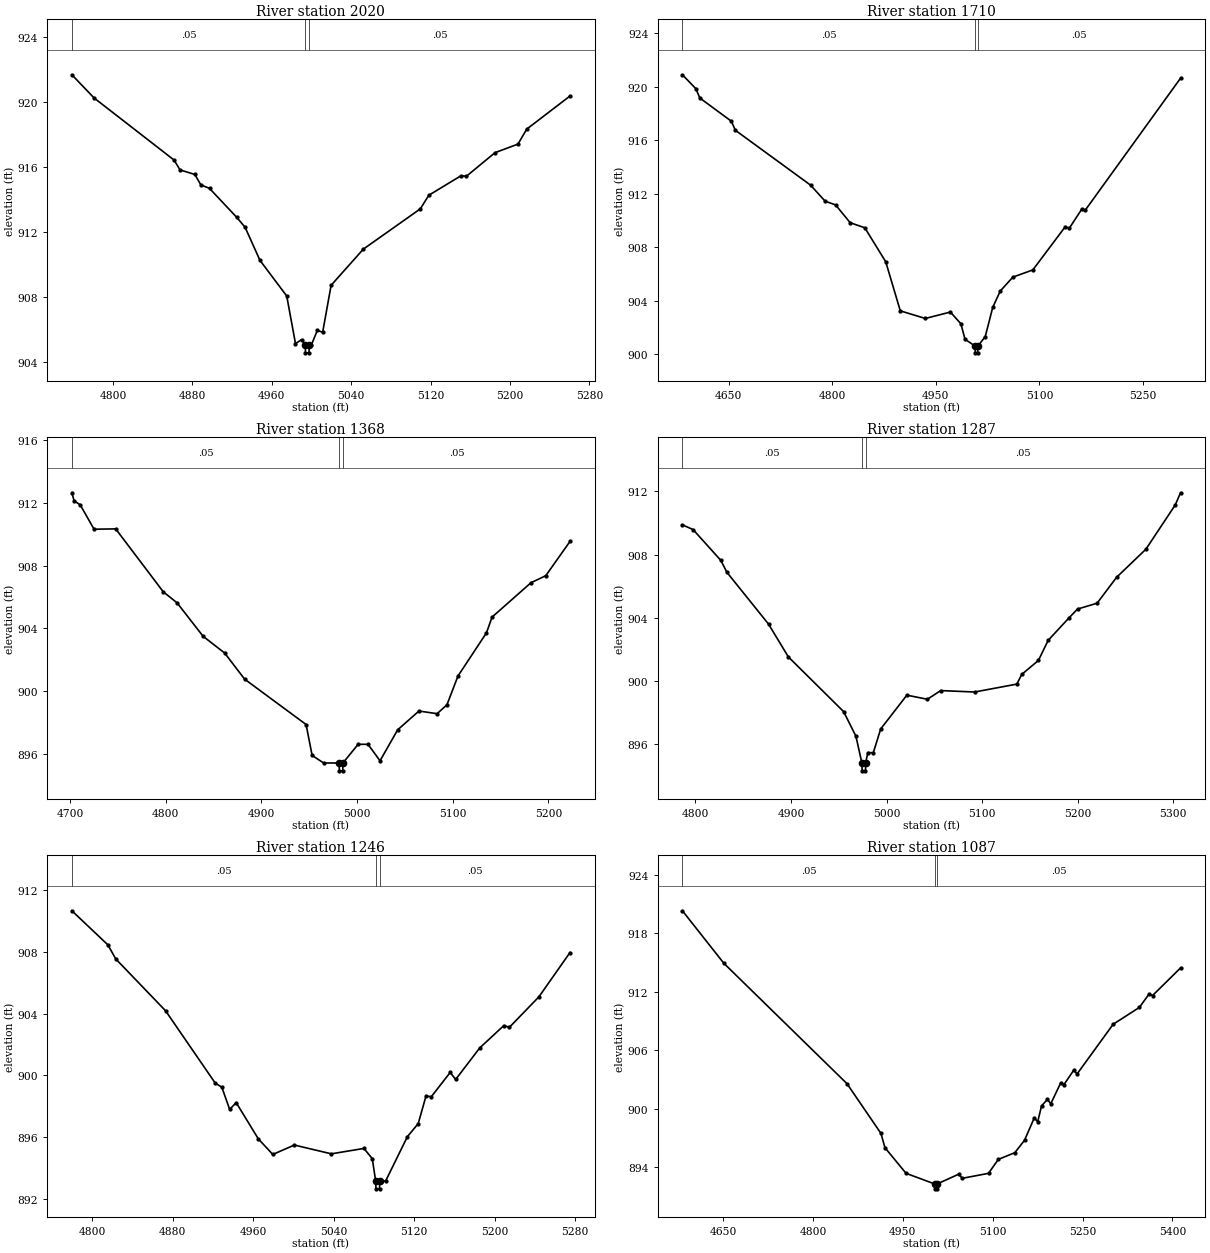
Type RM Length L Ch R = 1,2020,310,310,310
BEGIN DESCRIPTION:
MDW T 034 7.0
END DESCRIPTION:
XS GIS Cut Line= 3
      2283075.85      7093435.38      2282877.08      7093298.39
      2282639.16      7093192.30
#Sta/Elev= 30
  4758.6  921.70  4781.0  920.27  4861.5  916.45  4867.6  915.84  4882.5  915.56
  4888.5  914.92  4897.3  914.70  4924.8  912.91  4933.2  912.30  4948.1  910.27
  4975.1  908.07  4983.9  905.14  4990.0  905.38  4993.8  905.07  4994.0  904.57
  4997.5  904.57  4997.8  905.07  5000.0  905.07  5005.9  905.95  5011.3  905.84
  5019.8  908.73  5052.3  910.96  5109.7  913.44  5118.3  914.28  5150.7  915.48
  5156.2  915.45  5184.9  916.90  5208.1  917.43  5216.9  918.35  5260.5  920.39
#Mann=3,-1,0
  4758.6    0.05       0  4993.8   0.033       0  4997.8    0.05       0
Bank Sta=4993.8,4997.8
Exp/Cntr=0.3,0.1

Type RM Length L Ch R = 1,1710,342,342,342
BEGIN DESCRIPTION:
MDW T 034 6.0
END DESCRIPTION:
XS GIS Cut Line= 3
      2283359.30      7093256.06      2283008.82      7093029.93
      2282729.03      7092910.01
#Sta/Elev= 30
  4582.9  920.90  4602.2  919.87  4608.2  919.16  4653.7  917.43  4659.6  916.75
  4768.5  912.65  4789.6  911.45  4804.8  911.17  4825.9  909.84  4847.1  909.46
  4877.4  906.92  4898.5  903.25  4934.8  902.68  4971.1  903.16  4986.3  902.28
  4992.2  901.13  5006.9  900.61  5007.1  900.11  5010.6  900.11  5010.9  900.61
  5021.6  901.33  5032.4  903.51  5043.3  904.73  5061.5  905.77  5090.5  906.31
  5137.6  909.55  5143.1  909.41  5161.2  910.84  5166.6  910.79  5304.4  920.64
#Mann=3,-1,0
  4582.9    0.05       0  5006.9   0.033       0  5010.9    0.05       0
Bank Sta=5006.9,5010.9
Exp/Cntr=0.3,0.1

Type RM Length L Ch R = 1,1368,81,81,81
BEGIN DESCRIPTION:
Mapping XS a2bfc87c
END DESCRIPTION:
XS GIS Cut Line= 3
      2283415.41      7092986.90      2283253.72      7092778.86
      2283004.48      7092714.87
#Sta/Elev= 30
  4701.8  912.64  4704.1  912.13  4710.5  911.87  4725.0  910.32  4747.6  910.34
  4797.4  906.33  4811.8  905.63  4839.0  903.50  4861.6  902.43  4882.4  900.77
  4946.7  897.88  4953.0  895.91  4965.0  895.43  4981.2  895.43  4981.5  894.93
  4985.0  894.93  4985.2  895.43  5001.1  896.62  5011.4  896.62  5024.0  895.57
  5042.4  897.54  5064.7  898.74  5083.7  898.57  5094.0  899.14  5105.5  900.97
  5135.3  903.72  5141.1  904.72  5181.8  906.91  5197.3  907.36  5222.6  909.54
#Mann=3,-1,0
  4701.8    0.05       0  4981.2   0.033       0  4985.2    0.05       0
Bank Sta=4981.2,4985.2
Exp/Cntr=0.3,0.1

Type RM Length L Ch R = 1,1287,41,41,41
BEGIN DESCRIPTION:
Mapping XS c55ac014
END DESCRIPTION:
XS GIS Cut Line= 4
      2283430.80      7092903.89      2283311.66      7092748.37
      2283273.32      7092739.78      2282993.63      7092679.55
#Sta/Elev= 30
  4786.4  909.88  4797.6  909.58  4826.6  907.63  4832.9  906.88  4876.5  903.60
  4897.3  901.52  4955.1  898.06  4968.0  896.50  4974.2  894.81  4974.5  894.31
  4978.0  894.31  4978.2  894.81  4980.4  895.46  4986.2  895.46  4993.9  896.96
  5021.3  899.10  5042.8  898.84  5056.7  899.39  5092.2  899.30  5136.4  899.80
  5141.5  900.41  5159.0  901.30  5169.2  902.57  5190.8  903.98  5199.9  904.55
  5220.4  904.92  5240.8  906.56  5271.5  908.34  5302.2  911.14  5307.7  911.91
#Mann=3,-1,0
  4786.4    0.05       0  4974.2   0.033       0  4978.2    0.05       0
Bank Sta=4974.2,4978.2
Exp/Cntr=0.3,0.1

Type RM Length L Ch R = 1,1246,159,159,159
BEGIN DESCRIPTION:
Mapping XS f231d789
END DESCRIPTION:
XS GIS Cut Line= 3
      2283465.58      7092884.14      2283325.81      7092716.54
      2283069.33      7092611.72
#Sta/Elev= 30
  4779.7  910.68  4815.5  908.47  4823.3  907.56  4872.8  904.20  4922.2  899.51
  4928.8  899.24  4936.6  897.80  4943.1  898.24  4965.2  895.88  4979.5  894.88
  5000.9  895.49  5037.7  894.92  5070.1  895.27  5078.4  894.61  5081.8  893.15
  5082.1  892.65  5085.6  892.65  5085.8  893.15  5091.7  893.16  5113.3  896.03
  5124.1  896.88  5131.8  898.66  5137.2  898.63  5155.9  900.20  5161.3  899.74
  5185.3  901.79  5209.3  903.24  5214.7  903.12  5244.1  905.10  5275.0  907.97
#Mann=3,-1,0
  4779.7    0.05       0  5081.8   0.033       0  5085.8    0.05       0
Bank Sta=5081.8,5085.8
Exp/Cntr=0.3,0.1

Type RM Length L Ch R = 1,1087,255,255,255
BEGIN DESCRIPTION:
MDW T 034 4.0
END DESCRIPTION:
XS GIS Cut Line= 3
      2283659.45      7092887.32      2283379.98      7092577.59
      2283014.46      7092382.08
#Sta/Elev= 30
  4581.9  920.30  4651.1  914.91  4856.6  902.56  4913.4  897.45  4920.1  895.98
  4955.4  893.35  5003.2  892.26  5003.5  891.76  5007.0  891.76  5007.2  892.26
  5043.4  893.27  5049.1  892.84  5093.0  893.35  5109.3  894.78  5136.9  895.47
  5153.1  896.74  5169.4  899.04  5175.1  898.64  5181.6  900.28  5191.3  900.93
  5197.0  900.50  5213.3  902.60  5219.0  902.46  5235.2  903.93  5240.9  903.55
  5301.1  908.65  5344.9  910.38  5361.2  911.76  5366.9  911.60  5413.6  914.43
#Mann=3,-1,0
  4581.9    0.05       0  5003.2   0.033       0  5007.2    0.05       0
Bank Sta=5003.2,5007.2
Exp/Cntr=0.3,0.1

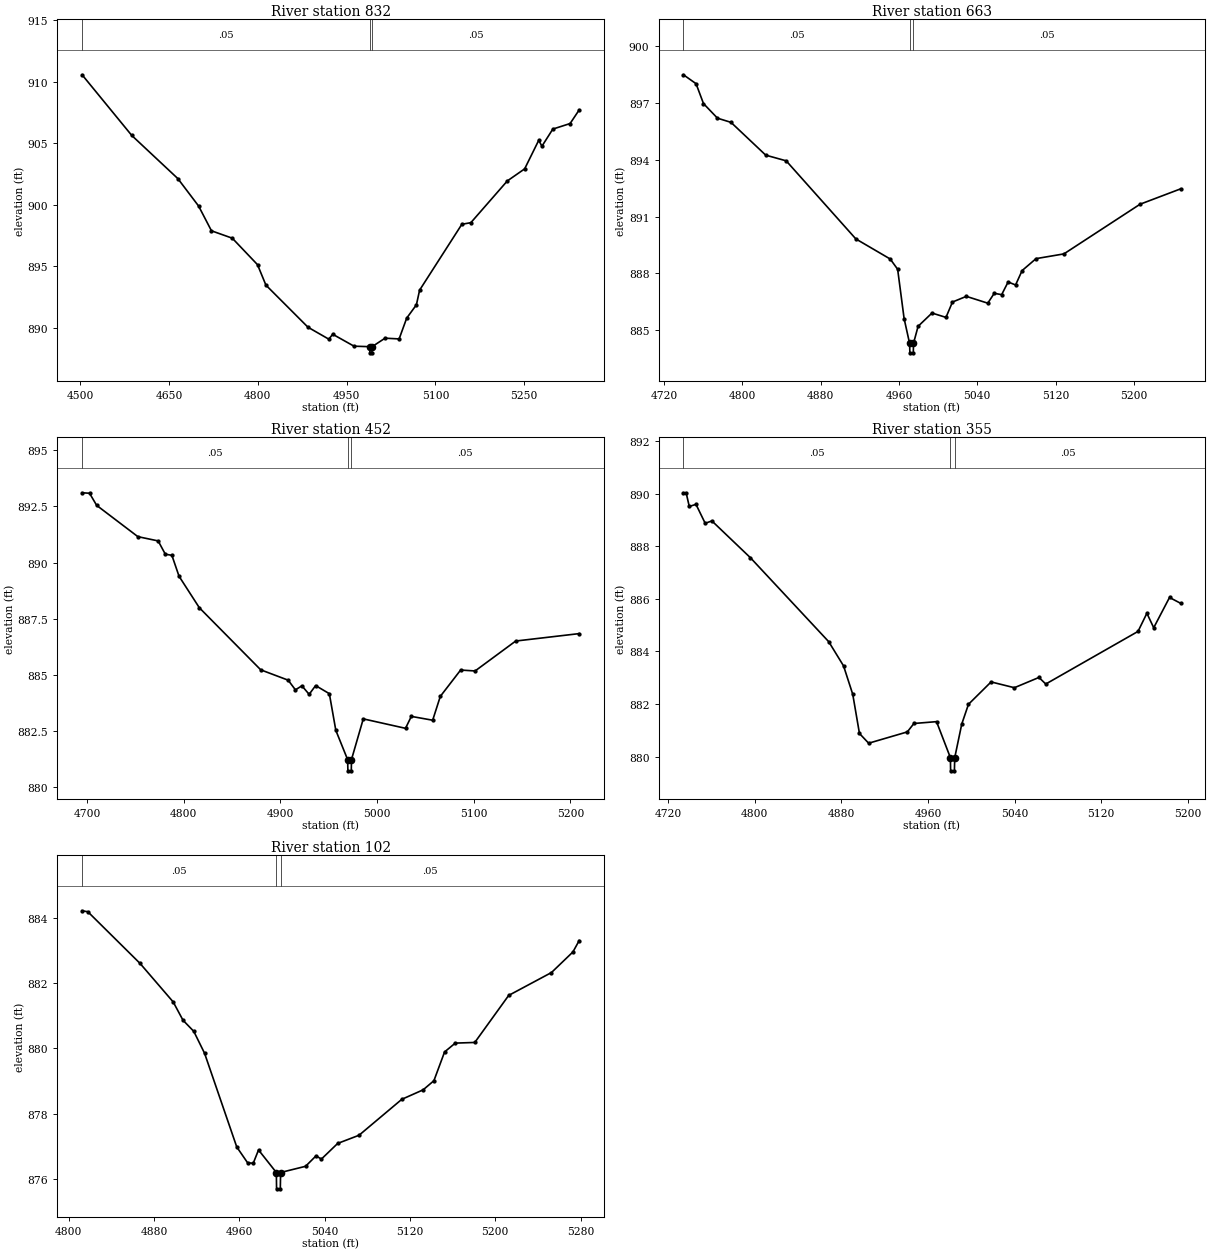
Type RM Length L Ch R = 1,832,169,169,169
BEGIN DESCRIPTION:
MDW T 034 3.0
END DESCRIPTION:
XS GIS Cut Line= 3
      2283741.05      7092696.34      2283423.80      7092338.45
      2283090.04      7092198.95
#Sta/Elev= 30
  4503.0  910.55  4587.0  905.62  4664.8  902.12  4699.9  899.89  4721.6  897.88
  4756.8  897.28  4799.4  895.13  4813.6  893.47  4884.7  890.05  4919.9  889.08
  4926.5  889.48  4962.5  888.51  4989.0  888.47  4989.3  887.97  4992.8  887.97
  4993.0  888.47  5014.9  889.16  5038.7  889.10  5051.5  890.79  5067.9  891.87
  5073.3  893.06  5144.7  898.41  5159.9  898.54  5221.5  901.93  5250.8  902.91
  5274.6  905.23  5280.0  904.75  5298.4  906.14  5327.6  906.59  5343.0  907.70
#Mann=3,-1,0
  4503.0    0.05       0  4989.0   0.033       0  4993.0    0.05       0
Bank Sta=4989,4993
Exp/Cntr=0.3,0.1

Type RM Length L Ch R = 1,663,211,211,211
BEGIN DESCRIPTION:
Mapping XS 0da2319f
END DESCRIPTION:
XS GIS Cut Line= 2
      2283730.90      7092476.58      2283396.46      7092094.20
#Sta/Elev= 30
  4739.7  898.48  4752.6  898.01  4760.2  896.96  4774.5  896.19  4788.3  895.97
  4823.8  894.24  4844.7  893.94  4915.9  889.82  4951.0  888.76  4958.6  888.22
  4965.2  885.62  4970.8  884.31  4971.1  883.81  4974.6  883.81  4974.8  884.31
  4979.5  885.21  4993.7  885.91  5008.0  885.68  5014.6  886.49  5028.8  886.79
  5050.7  886.43  5057.3  886.95  5064.9  886.88  5071.5  887.55  5079.1  887.39
  5085.8  888.15  5100.0  888.78  5128.5  889.03  5206.3  891.65  5247.7  892.46
#Mann=3,-1,0
  4739.7    0.05       0  4970.8   0.033       0  4974.8    0.05       0
Bank Sta=4970.8,4974.8
Exp/Cntr=0.3,0.1

Type RM Length L Ch R = 1,452,97,97,97
BEGIN DESCRIPTION:
MDW T 034 2.0
END DESCRIPTION:
XS GIS Cut Line= 3
      2283865.53      7092354.70      2283662.85      7092129.79
      2283544.94      7091954.16
#Sta/Elev= 30
  4694.8  893.10  4702.5  893.08  4709.9  892.54  4752.5  891.15  4773.5  890.96
  4780.9  890.37  4787.7  890.32  4795.1  889.39  4816.1  887.99  4879.6  885.23
  4908.0  884.77  4915.5  884.34  4922.2  884.52  4929.7  884.14  4936.4  884.53
  4950.6  884.17  4957.3  882.54  4969.5  881.24  4969.8  880.74  4973.3  880.74
  4973.5  881.24  4985.7  883.05  5029.4  882.63  5035.4  883.16  5057.5  882.99
  5065.4  884.05  5086.4  885.22  5101.4  885.18  5143.4  886.51  5209.1  886.84
#Mann=3,-1,0
  4694.8    0.05       0  4969.5   0.033       0  4973.5    0.05       0
Bank Sta=4969.5,4973.5
Exp/Cntr=0.3,0.1

Type RM Length L Ch R = 1,355,253,253,253
BEGIN DESCRIPTION:
Mapping XS a0ff1be0
END DESCRIPTION:
XS GIS Cut Line= 3
      2283887.38      7092279.05      2283714.47      7092038.00
      2283585.55      7091939.01
#Sta/Elev= 30
  4734.1  890.03  4736.6  890.03  4739.5  889.51  4745.7  889.59  4754.2  888.87
  4760.4  888.96  4796.0  887.56  4868.3  884.37  4882.0  883.45  4890.5  882.37
  4896.7  880.88  4905.2  880.51  4940.9  880.94  4947.0  881.26  4967.9  881.33
  4980.7  879.96  4980.9  879.46  4984.4  879.46  4984.7  879.96  4991.2  881.24
  4997.4  881.99  5018.3  882.84  5039.8  882.62  5062.5  883.01  5068.8  882.76
  5154.0  884.76  5162.2  885.45  5168.5  884.90  5183.1  886.05  5193.3  885.83
#Mann=3,-1,0
  4734.1    0.05       0  4980.7   0.033       0  4984.7    0.05       0
Bank Sta=4980.7,4984.7
Exp/Cntr=0.3,0.1

Type RM Length L Ch R = 1,102,0,0,0
BEGIN DESCRIPTION:
MDW T 034 1.0
END DESCRIPTION:
XS GIS Cut Line= 3
      2283964.23      7092133.84      2283940.56      7091947.46
      2283663.08      7091928.57
#Sta/Elev= 30
  4812.7  884.21  4818.1  884.18  4867.0  882.60  4898.1  881.42  4907.3  880.86
  4917.4  880.52  4927.5  879.85  4957.7  876.98  4967.8  876.50  4973.1  876.48
  4978.1  876.89  4994.8  876.20  4995.0  875.70  4998.5  875.70  4998.8  876.20
  5022.2  876.39  5032.0  876.71  5037.0  876.61  5052.3  877.09  5072.3  877.34
  5112.4  878.44  5132.4  878.73  5142.5  879.01  5152.5  879.89  5162.5  880.16
  5180.8  880.18  5212.6  881.62  5252.7  882.32  5272.8  882.95  5278.7  883.30
#Mann=3,-1,0
  4812.7    0.05       0  4994.8    0.04       0  4998.8    0.05       0
Bank Sta=4994.8,4998.8
Exp/Cntr=0.3,0.1

Chan Stop Cuts=-1