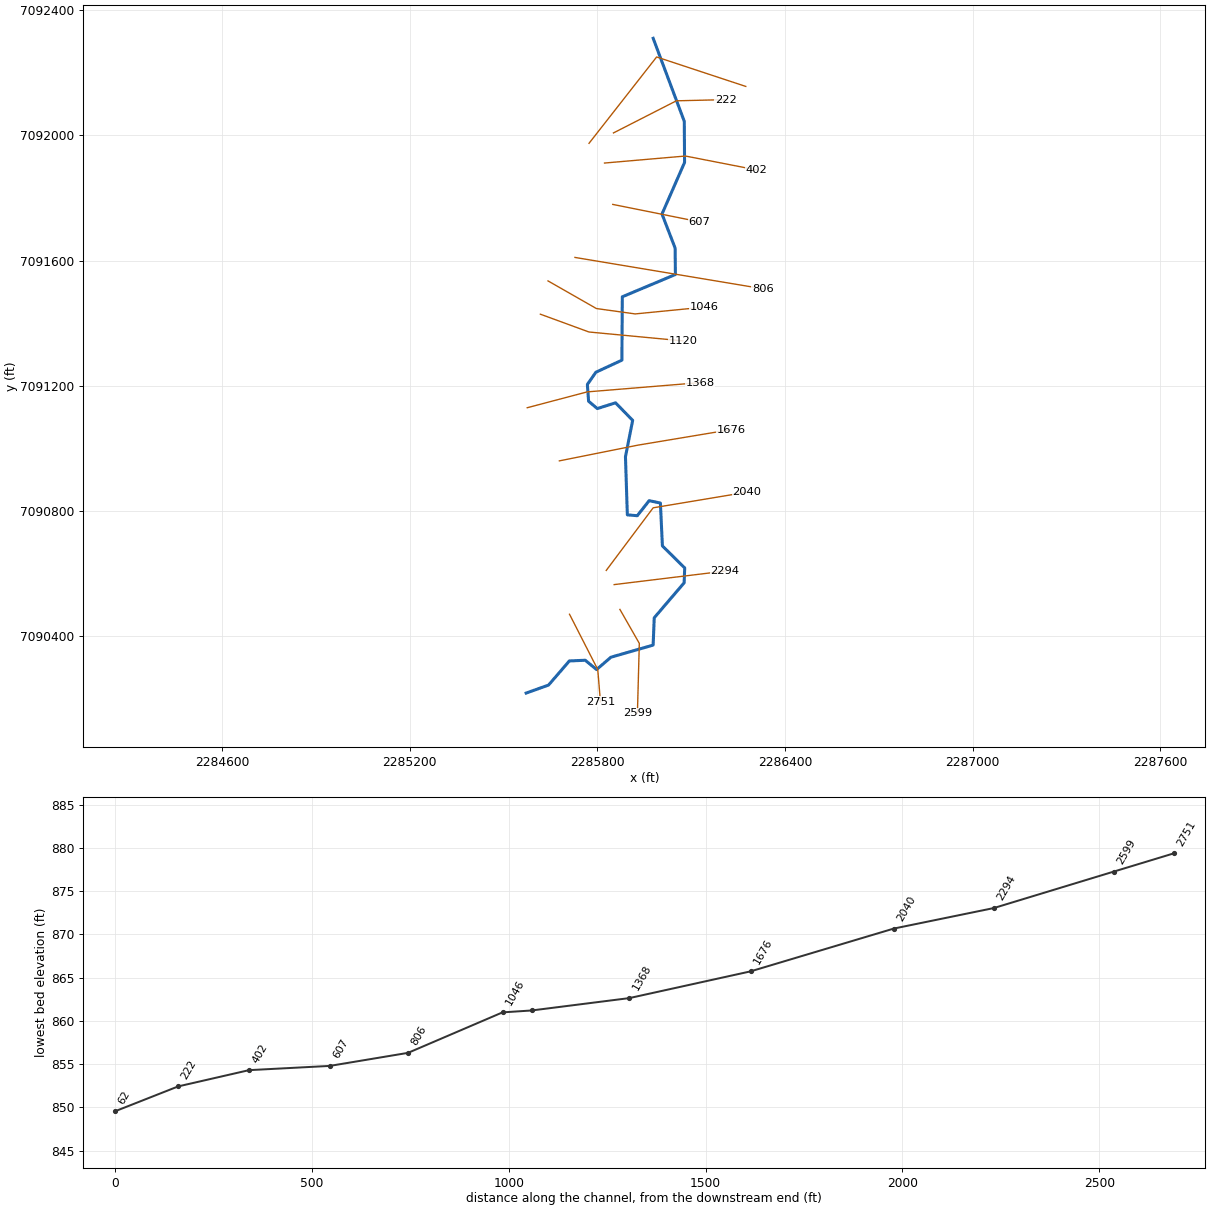
--- MDW T 035.prj (project) ---

Proj Title=MDW T 035 Base Level Engineering
Current Plan=p01
Default Exp/Contr=0.3,0.1
English Units
Geom File=g01
Flow File=f01
Plan File=p01
BEGIN DESCRIPTION:
MDW T 035
END DESCRIPTION:

--- MDW T 035.p01 (plan) ---

Plan Title=Multiple Run
Short Identifier=Multiple
Geom File=g01
Flow File=f01
Subcritical Flow
K Sum by GR= 0
Std Step Tol= 0.01
Critical Tol= 0.01
Num of Std Step Trials= 20
Max Error Tol= 0.3
Flow Tol Ratio= 0.001
Split Flow NTrial= 30
Split Flow Tol= 0.02
Split Flow Ratio= 0.02
Log Output Level= 0
Friction Slope Method= 1
Unsteady Friction Slope Method= 2
Unsteady Bridges Friction Slope Method= 1
Parabolic Critical Depth
Global Vel Dist=  1 , 1 , 1
Global Log Level= 0
CheckData=True
Encroach Param= -1, 0, 0, 0
BEGIN DESCRIPTION:
Multiple Run
END DESCRIPTION:

--- MDW T 035.f01 (steady flow) ---

Flow Title=Multiple
Number of Profiles=7
Profile Names=10-year,25-year,50-year,1pct_min,100-year,1pct_plu,500-year
River Rch & RM= MDW T 035,Reach-1,2751
     509     697     852     518    1034    2064    1527
Boundary for River Rch & Prof#=MDW T 035,Reach-1,1
Up Type=0
Dn Type=3
Dn Slope=0.005
Boundary for River Rch & Prof#=MDW T 035,Reach-1,2
Up Type=0
Dn Type=3
Dn Slope=0.005
Boundary for River Rch & Prof#=MDW T 035,Reach-1,3
Up Type=0
Dn Type=3
Dn Slope=0.005
Boundary for River Rch & Prof#=MDW T 035,Reach-1,4
Up Type=0
Dn Type=3
Dn Slope=0.005
Boundary for River Rch & Prof#=MDW T 035,Reach-1,5
Up Type=0
Dn Type=3
Dn Slope=0.005
Boundary for River Rch & Prof#=MDW T 035,Reach-1,6
Up Type=0
Dn Type=3
Dn Slope=0.005
Boundary for River Rch & Prof#=MDW T 035,Reach-1,7
Up Type=0
Dn Type=3
Dn Slope=0.005

--- MDW T 035.g01 (geometry) ---

Geom Title=Existing Conditions

River Reach=MDW T 035,Reach-1
Reach XY= 30
      2285573.01      7090218.08      2285644.51      7090243.65
      2285711.03      7090320.70      2285761.84      7090322.98
      2285798.02      7090293.13      2285843.97      7090332.67
      2285978.90      7090371.36      2285982.39      7090458.59
      2286078.06      7090570.48      2286079.80      7090617.86
      2286008.50      7090688.30      2286002.13      7090825.24
      2285966.13      7090832.83      2285928.18      7090784.80
      2285896.40      7090787.47      2285890.40      7090973.06
      2285913.48      7091089.44      2285858.62      7091145.49
      2285800.32      7091127.05      2285772.52      7091150.60
      2285768.65      7091204.17      2285795.83      7091243.16
      2285879.00      7091281.70      2285880.34      7091484.25
      2286050.06      7091555.42      2286049.23      7091639.80
      2286007.22      7091748.59      2286079.39      7091913.39
      2286078.48      7092044.78      2285979.00      7092310.00

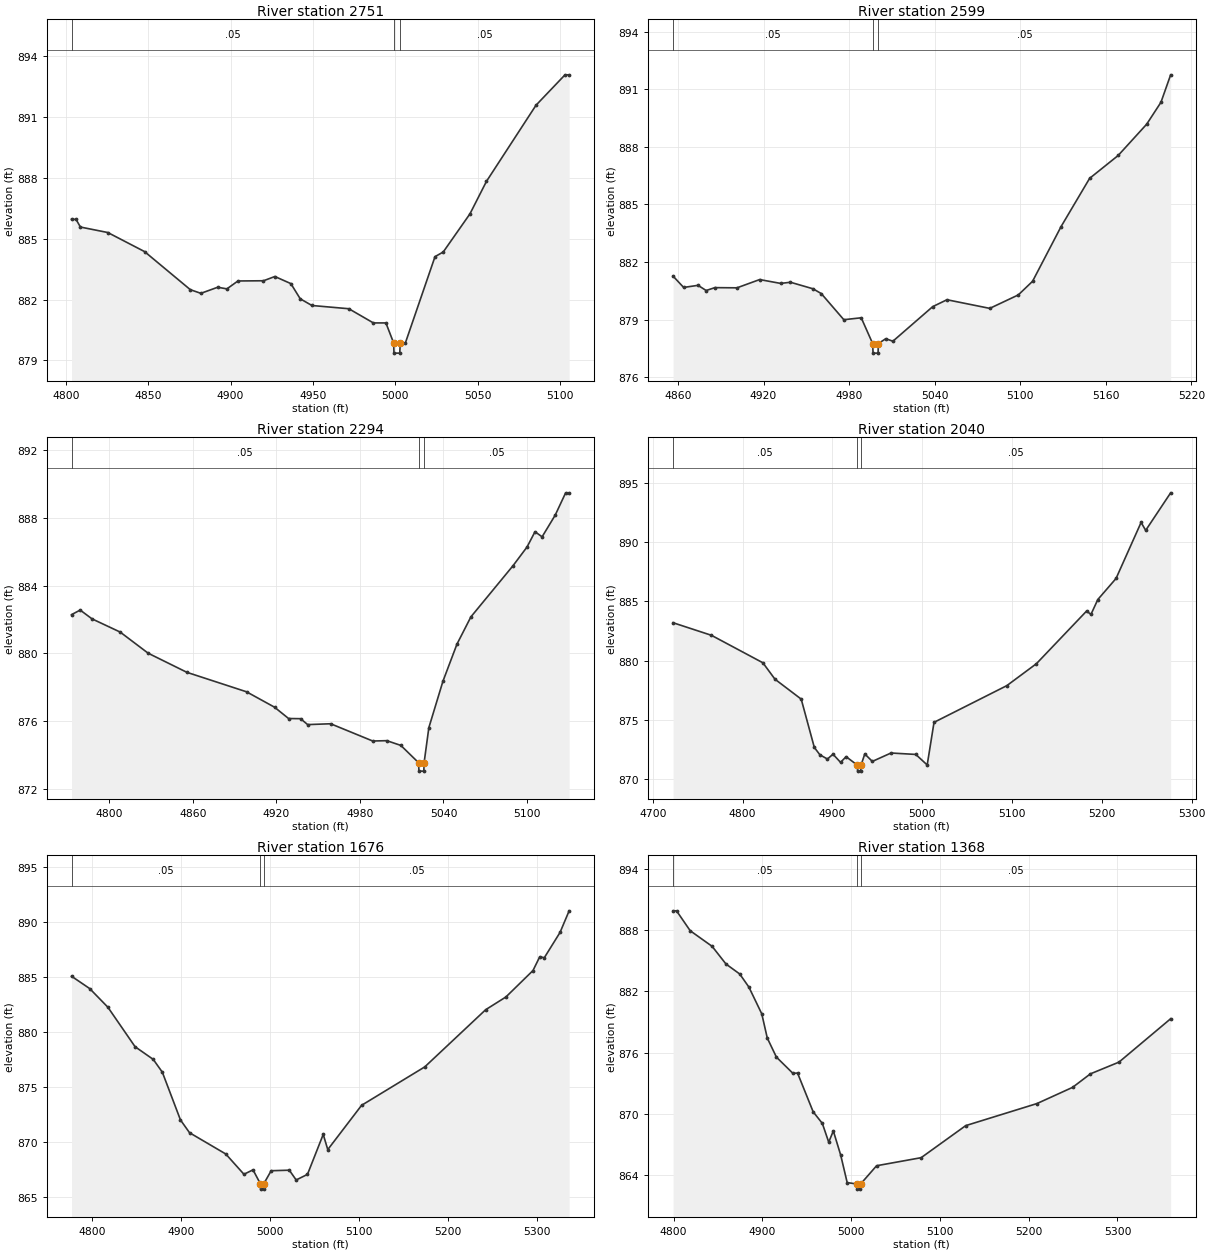
Type RM Length L Ch R = 1,2751,152,152,152
BEGIN DESCRIPTION:
MDW T 035 6.0
END DESCRIPTION:
XS GIS Cut Line= 3
      2285711.57      7090469.91      2285801.86      7090293.12
      2285810.40      7090189.99
#Sta/Elev= 30
  4803.5  885.96  4806.2  885.96  4808.9  885.58  4825.5  885.31  4847.8  884.37
  4875.6  882.49  4882.0  882.31  4892.2  882.61  4897.8  882.53  4904.5  882.92
  4920.0  882.93  4926.9  883.14  4936.6  882.79  4942.3  882.04  4949.4  881.71
  4971.8  881.55  4986.7  880.85  4994.3  880.85  4999.0  879.86  4999.2  879.36
  5002.7  879.36  5003.0  879.86  5006.1  879.86  5024.1  884.12  5029.1  884.35
  5045.3  886.23  5055.3  887.83  5085.4  891.59  5103.0  893.09  5105.5  893.09
#Mann=3,-1,0
  4803.5    0.05       0  4999.0   0.033       0  5003.0    0.05       0
Bank Sta=4999,5003
Exp/Cntr=0.3,0.1

Type RM Length L Ch R = 1,2599,305,305,305
BEGIN DESCRIPTION:
Mapping XS bcf9fb54
END DESCRIPTION:
XS GIS Cut Line= 3
      2285872.64      7090485.45      2285934.71      7090376.83
      2285928.63      7090153.22
#Sta/Elev= 30
  4856.6  881.27  4864.0  880.68  4874.1  880.79  4879.8  880.52  4885.9  880.67
  4901.4  880.66  4917.3  881.09  4932.0  880.89  4938.9  880.95  4954.7  880.61
  4960.5  880.36  4976.3  879.00  4988.5  879.10  4996.5  877.76  4996.8  877.26
  5000.3  877.26  5000.5  877.76  5005.7  878.01  5010.7  877.88  5038.6  879.68
  5048.6  880.04  5078.6  879.59  5098.6  880.29  5108.6  881.00  5128.6  883.85
  5148.6  886.36  5168.6  887.55  5188.6  889.18  5198.6  890.32  5205.4  891.75
#Mann=3,-1,0
  4856.6    0.05       0  4996.5    0.04       0  5000.5    0.05       0
Bank Sta=4996.5,5000.5
Exp/Cntr=0.3,0.1

Type RM Length L Ch R = 1,2294,254,254,254
BEGIN DESCRIPTION:
Mapping XS 23ffc346
END DESCRIPTION:
XS GIS Cut Line= 2
      2285854.36      7090564.67      2286208.94      7090607.88
#Sta/Elev= 30
  4773.0  882.29  4779.2  882.56  4787.7  882.04  4807.9  881.26  4828.0  880.01
  4855.8  878.88  4898.6  877.73  4918.7  876.82  4928.8  876.15  4937.4  876.14
  4942.5  875.79  4959.0  875.84  4989.2  874.82  4999.3  874.84  5009.4  874.56
  5022.1  873.54  5022.4  873.04  5025.9  873.04  5026.1  873.54  5029.5  875.61
  5039.6  878.35  5049.7  880.55  5059.7  882.16  5090.0  885.19  5100.0  886.29
  5105.7  887.19  5110.8  886.89  5120.2  888.17  5127.7  889.49  5130.2  889.49
#Mann=3,-1,0
  4773.0    0.05       0  5022.1   0.033       0  5026.1    0.05       0
Bank Sta=5022.1,5026.1
Exp/Cntr=0.3,0.1

Type RM Length L Ch R = 1,2040,364,364,364
BEGIN DESCRIPTION:
MDW T 035 5.0
END DESCRIPTION:
XS GIS Cut Line= 3
      2285829.00      7090610.00      2285979.00      7090810.00
      2286278.96      7090859.99
#Sta/Elev= 30
  4722.5  883.20  4765.2  882.14  4822.5  879.82  4836.0  878.43  4865.2  876.75
  4879.8  872.67  4886.0  872.05  4894.4  871.69  4900.6  872.10  4909.0  871.41
  4915.2  871.89  4927.8  871.17  4928.0  870.67  4931.5  870.67  4931.8  871.17
  4936.0  872.12  4944.4  871.49  4965.2  872.20  4992.8  872.08  5005.5  871.19
  5013.1  874.79  5094.2  877.89  5127.1  879.74  5182.9  884.18  5187.9  883.91
  5195.5  885.16  5215.8  886.94  5243.7  891.67  5248.8  891.00  5276.6  894.17
#Mann=3,-1,0
  4722.5    0.05       0  4927.8   0.033       0  4931.8    0.05       0
Bank Sta=4927.8,4931.8
Exp/Cntr=0.3,0.1

Type RM Length L Ch R = 1,1676,308,308,308
BEGIN DESCRIPTION:
MDW T 035 4.0
END DESCRIPTION:
XS GIS Cut Line= 3
      2285679.02      7090960.00      2285929.00      7091010.00
      2286229.03      7091060.01
#Sta/Elev= 30
  4776.6  885.05  4797.0  883.93  4817.4  882.24  4848.0  878.65  4868.4  877.50
  4878.6  876.34  4899.0  872.00  4909.2  870.84  4949.9  868.91  4970.3  867.07
  4980.5  867.47  4988.7  866.22  4989.0  865.72  4992.5  865.72  4992.7  866.22
  5000.9  867.39  5021.3  867.44  5029.0  866.55  5041.7  867.06  5059.4  870.69
  5064.5  869.31  5102.5  873.33  5173.5  876.82  5241.9  882.01  5264.7  883.17
  5295.1  885.57  5302.7  886.82  5307.8  886.73  5325.5  889.03  5335.7  890.99
#Mann=3,-1,0
  4776.6    0.05       0  4988.7   0.033       0  4992.7    0.05       0
Bank Sta=4988.7,4992.7
Exp/Cntr=0.3,0.1

Type RM Length L Ch R = 1,1368,248,248,248
BEGIN DESCRIPTION:
MDW T 035 3.0
END DESCRIPTION:
XS GIS Cut Line= 3
      2285576.41      7091129.81      2285768.05      7091180.34
      2286129.05      7091210.00
#Sta/Elev= 30
  4799.5  889.89  4803.4  889.89  4818.8  887.94  4843.5  886.41  4859.1  884.68
  4874.6  883.70  4884.9  882.42  4899.4  879.80  4905.6  877.43  4915.9  875.56
  4934.5  873.97  4939.7  874.00  4957.3  870.20  4967.6  869.07  4974.8  867.23
  4980.0  868.33  4988.3  865.96  4995.6  863.27  5006.7  863.13  5006.9  862.63
  5010.4  862.63  5010.7  863.13  5028.7  864.92  5078.9  865.71  5129.1  868.85
  5209.3  871.01  5249.5  872.60  5269.5  873.92  5301.7  875.07  5359.9  879.32
#Mann=3,-1,0
  4799.5    0.05       0  5006.7   0.033       0  5010.7    0.05       0
Bank Sta=5006.7,5010.7
Exp/Cntr=0.3,0.1

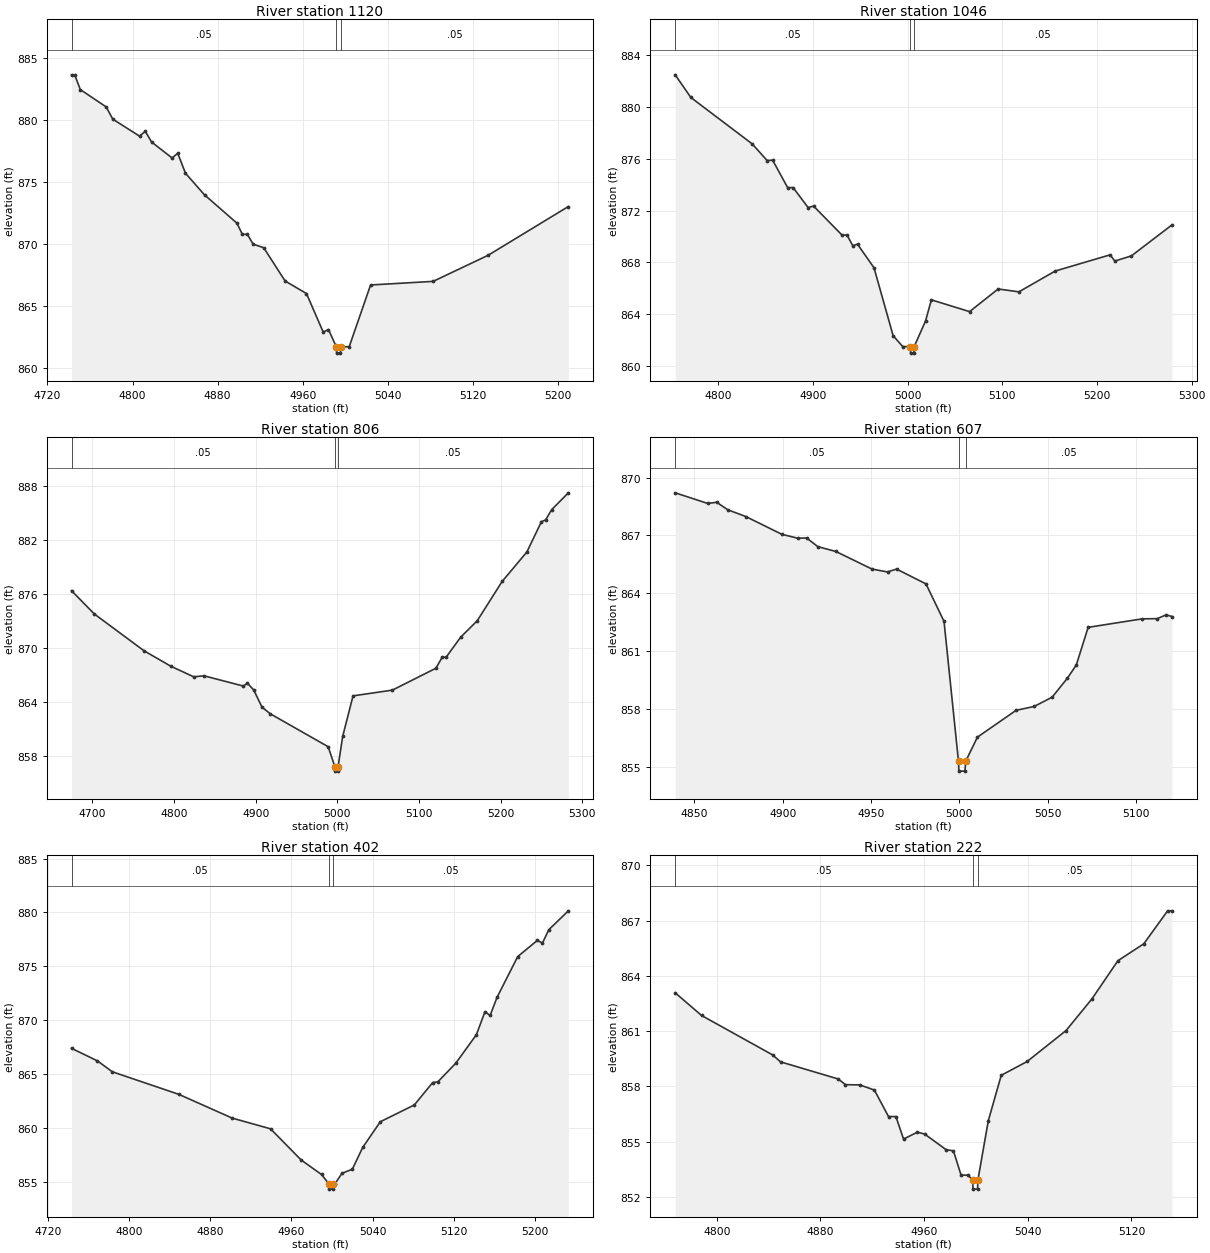
Type RM Length L Ch R = 1,1120,74,74,74
BEGIN DESCRIPTION:
Mapping XS fd752b36
END DESCRIPTION:
XS GIS Cut Line= 3
      2285618.33      7091428.66      2285773.68      7091371.76
      2286074.20      7091343.37
#Sta/Elev= 30
  4742.6  883.62  4745.6  883.62  4750.9  882.43  4775.3  881.03  4781.4  880.05
  4806.6  878.68  4812.0  879.07  4817.9  878.21  4837.2  876.92  4842.5  877.30
  4849.8  875.69  4867.7  873.95  4898.2  871.67  4903.3  870.77  4908.0  870.77
  4913.4  869.98  4923.4  869.69  4943.5  867.01  4963.6  866.00  4979.3  862.90
  4984.3  863.10  4991.7  861.70  4992.0  861.20  4995.5  861.20  4995.7  861.70
  5003.8  861.72  5023.9  866.69  5082.7  866.98  5134.4  869.08  5209.9  873.01
#Mann=3,-1,0
  4742.6    0.05       0  4991.7   0.033       0  4995.7    0.05       0
Bank Sta=4991.7,4995.7
Exp/Cntr=0.3,0.1

Type RM Length L Ch R = 1,1046,240,240,240
BEGIN DESCRIPTION:
Mapping XS 48bc5bcf
END DESCRIPTION:
XS GIS Cut Line= 4
      2285642.80      7091534.94      2285797.53      7091446.67
      2285921.54      7091429.49      2286141.74      7091451.15
#Sta/Elev= 30
  4754.7  882.50  4771.2  880.75  4836.0  877.16  4851.8  875.87  4857.6  875.90
  4873.4  873.78  4879.2  873.78  4895.0  872.24  4900.8  872.35  4930.8  870.11
  4936.1  870.11  4942.2  869.29  4947.2  869.40  4964.6  867.58  4984.8  862.33
  4994.9  861.49  5003.0  861.48  5003.2  860.98  5006.7  860.98  5007.0  861.48
  5019.0  863.46  5025.2  865.10  5065.5  864.19  5095.7  865.94  5117.6  865.72
  5156.0  867.33  5213.9  868.58  5218.9  868.10  5236.4  868.50  5279.3  870.90
#Mann=3,-1,0
  4754.7    0.05       0  5003.0   0.033       0  5007.0    0.05       0
Bank Sta=5003,5007
Exp/Cntr=0.3,0.1

Type RM Length L Ch R = 1,806,199,199,199
BEGIN DESCRIPTION:
MDW T 035 2.0
END DESCRIPTION:
XS GIS Cut Line= 3
      2285728.98      7091610.00      2286029.00      7091560.00
      2286329.01      7091510.00
#Sta/Elev= 30
  4674.5  876.37  4702.4  873.78  4763.2  869.69  4796.2  867.96  4824.1  866.79
  4836.7  866.90  4884.9  865.76  4889.9  866.08  4897.6  865.32  4907.7  863.42
  4917.8  862.68  4988.8  859.01  4996.9  856.80  4997.2  856.30  5000.7  856.30
  5000.9  856.80  5006.5  860.16  5019.2  864.67  5067.4  865.31  5120.6  867.74
  5128.2  868.94  5133.3  868.99  5151.0  871.20  5171.3  873.03  5201.7  877.39
  5232.1  880.68  5249.8  884.04  5254.9  884.23  5262.5  885.39  5282.8  887.25
#Mann=3,-1,0
  4674.5    0.05       0  4996.9   0.033       0  5000.9    0.05       0
Bank Sta=4996.9,5000.9
Exp/Cntr=0.3,0.1

Type RM Length L Ch R = 1,607,205,205,205
BEGIN DESCRIPTION:
Mapping XS 22d4ca8d
END DESCRIPTION:
XS GIS Cut Line= 2
      2285849.79      7091779.41      2286125.58      7091724.03
#Sta/Elev= 30
  4839.1  869.21  4857.5  868.66  4862.6  868.72  4868.9  868.33  4879.1  867.98
  4899.5  867.06  4908.4  866.86  4913.5  866.87  4919.9  866.42  4930.1  866.17
  4950.5  865.26  4959.3  865.11  4964.4  865.26  4981.1  864.49  4991.3  862.55
  4999.5  855.29  4999.7  854.79  5003.2  854.79  5003.5  855.29  5010.2  856.55
  5032.1  857.94  5042.3  858.14  5052.5  858.62  5061.1  859.60  5066.2  860.29
  5072.9  862.24  5103.5  862.68  5112.0  862.69  5117.1  862.89  5120.4  862.80
#Mann=3,-1,0
  4839.1    0.05       0  4999.5   0.033       0  5003.5    0.05       0
Bank Sta=4999.5,5003.5
Exp/Cntr=0.3,0.1

Type RM Length L Ch R = 1,402,180,180,180
BEGIN DESCRIPTION:
MDW T 035 1.0
END DESCRIPTION:
XS GIS Cut Line= 3
      2285823.50      7091911.58      2286082.25      7091933.99
      2286307.96      7091889.89
#Sta/Elev= 30
  4743.3  867.38  4768.9  866.21  4783.5  865.20  4849.2  863.10  4901.6  860.90
  4939.5  859.90  4969.6  857.01  4989.7  855.66  4996.9  854.80  4997.1  854.30
  5000.6  854.30  5000.9  854.80  5003.0  854.80  5009.9  855.77  5020.1  856.15
  5030.3  858.17  5047.7  860.56  5081.2  862.12  5099.3  864.20  5104.4  864.27
  5122.0  865.99  5142.4  868.65  5150.8  870.78  5155.9  870.43  5162.7  872.11
  5183.1  875.90  5202.4  877.40  5207.5  877.16  5213.7  878.39  5233.0  880.15
#Mann=3,-1,0
  4743.3    0.05       0  4996.9   0.033       0  5000.9    0.05       0
Bank Sta=4996.9,5000.9
Exp/Cntr=0.3,0.1

Type RM Length L Ch R = 1,222,160,160,160
BEGIN DESCRIPTION:
Mapping XS bb9041c3
END DESCRIPTION:
XS GIS Cut Line= 3
      2285852.07      7092007.76      2286053.24      7092110.40
      2286210.76      7092114.12
#Sta/Elev= 30
  4767.9  863.08  4788.2  861.85  4843.0  859.71  4849.2  859.33  4893.7  858.40
  4899.3  858.09  4910.3  858.08  4921.6  857.80  4932.5  856.36  4938.2  856.36
  4944.1  855.14  4954.8  855.51  4960.4  855.41  4977.0  854.56  4982.6  854.50
  4988.5  853.18  4993.7  853.18  4997.5  852.92  4997.7  852.42  5001.2  852.42
  5001.5  852.92  5009.5  856.13  5019.5  858.60  5039.5  859.35  5069.5  861.03
  5089.5  862.75  5109.5  864.82  5129.5  865.74  5147.9  867.53  5151.3  867.53
#Mann=3,-1,0
  4767.9    0.05       0  4997.5   0.033       0  5001.5    0.05       0
Bank Sta=4997.5,5001.5
Exp/Cntr=0.3,0.1

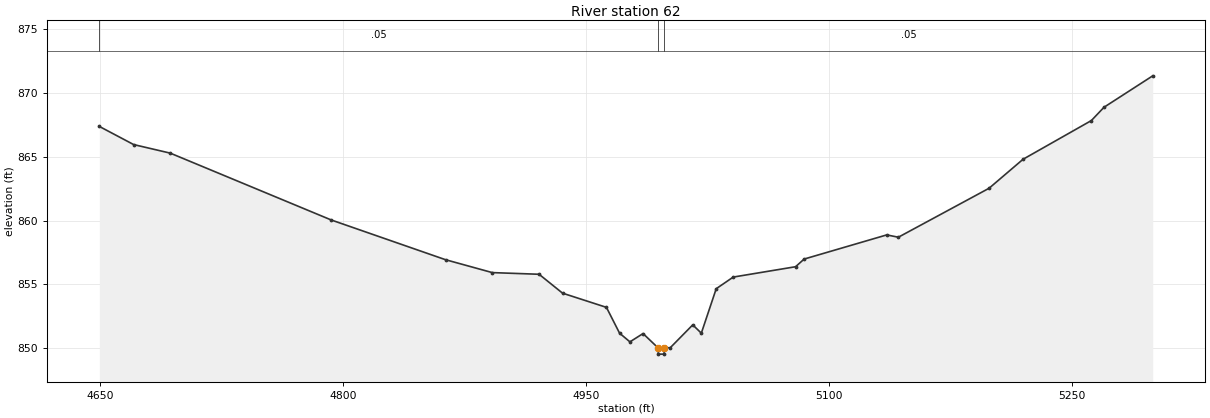
Type RM Length L Ch R = 1,62,0,0,0
BEGIN DESCRIPTION:
MDW T 035 0.5
END DESCRIPTION:
XS GIS Cut Line= 3
      2285773.87      7091974.54      2285990.05      7092250.44
      2286275.03      7092156.38
#Sta/Elev= 30
  4649.5  867.37  4670.7  865.95  4693.3  865.28  4792.7  860.05  4863.3  856.94
  4892.2  855.93  4921.1  855.80  4935.6  854.32  4962.7  853.21  4970.8  851.19
  4977.2  850.51  4985.3  851.16  4994.5  850.05  4994.8  849.55  4998.3  849.55
  4998.5  850.05  5002.1  850.05  5016.0  851.84  5021.3  851.19  5030.5  854.67
  5041.0  855.58  5079.5  856.39  5084.8  856.99  5135.8  858.88  5143.0  858.70
  5199.0  862.53  5220.0  864.80  5262.2  867.83  5270.0  868.87  5300.1  871.33
#Mann=3,-1,0
  4649.5    0.05       0  4994.5   0.033       0  4998.5    0.05       0
Bank Sta=4994.5,4998.5
Exp/Cntr=0.3,0.1

Chan Stop Cuts=-1