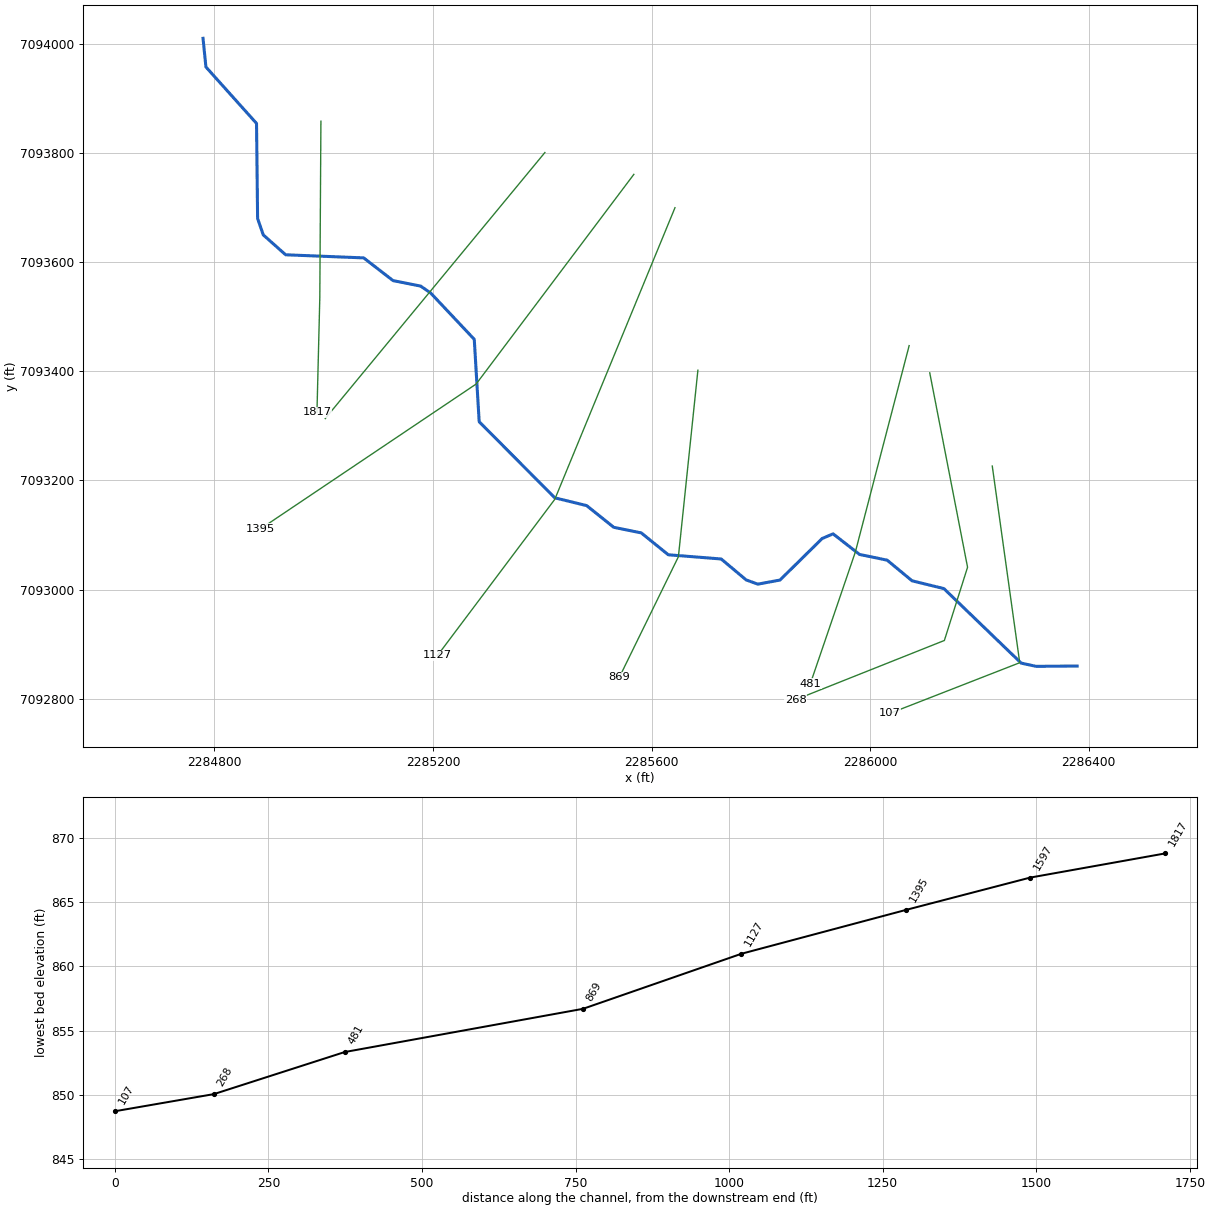
--- MDW T 036.prj (project) ---

Proj Title=MDW T 036 Base Level Engineering
Current Plan=p01
Default Exp/Contr=0.3,0.1
English Units
Geom File=g01
Flow File=f01
Plan File=p01
BEGIN DESCRIPTION:
MDW T 036
END DESCRIPTION:

--- MDW T 036.p01 (plan) ---

Plan Title=Multiple Run
Short Identifier=Multiple
Geom File=g01
Flow File=f01
Subcritical Flow
K Sum by GR= 0
Std Step Tol= 0.01
Critical Tol= 0.01
Num of Std Step Trials= 20
Max Error Tol= 0.3
Flow Tol Ratio= 0.001
Split Flow NTrial= 30
Split Flow Tol= 0.02
Split Flow Ratio= 0.02
Log Output Level= 0
Friction Slope Method= 1
Unsteady Friction Slope Method= 2
Unsteady Bridges Friction Slope Method= 1
Parabolic Critical Depth
Global Vel Dist=  1 , 1 , 1
Global Log Level= 0
CheckData=True
Encroach Param= -1, 0, 0, 0
BEGIN DESCRIPTION:
Multiple Run
END DESCRIPTION:

--- MDW T 036.f01 (steady flow) ---

Flow Title=Multiple
Number of Profiles=7
Profile Names=10-year,25-year,50-year,1pct_min,100-year,1pct_plu,500-year
River Rch & RM= MDW T 036,Reach-1,1817
     239     311     368     218     435     867     604
Boundary for River Rch & Prof#=MDW T 036,Reach-1,1
Up Type=0
Dn Type=3
Dn Slope=0.005
Boundary for River Rch & Prof#=MDW T 036,Reach-1,2
Up Type=0
Dn Type=3
Dn Slope=0.005
Boundary for River Rch & Prof#=MDW T 036,Reach-1,3
Up Type=0
Dn Type=3
Dn Slope=0.005
Boundary for River Rch & Prof#=MDW T 036,Reach-1,4
Up Type=0
Dn Type=3
Dn Slope=0.005
Boundary for River Rch & Prof#=MDW T 036,Reach-1,5
Up Type=0
Dn Type=3
Dn Slope=0.005
Boundary for River Rch & Prof#=MDW T 036,Reach-1,6
Up Type=0
Dn Type=3
Dn Slope=0.005
Boundary for River Rch & Prof#=MDW T 036,Reach-1,7
Up Type=0
Dn Type=3
Dn Slope=0.005

--- MDW T 036.g01 (geometry) ---

Geom Title=Existing Conditions

River Reach=MDW T 036,Reach-1
Reach XY= 30
      2284779.00      7094010.00      2284784.33      7093957.49
      2284876.94      7093854.15      2284878.91      7093679.87
      2284889.32      7093649.82      2284930.22      7093613.44
      2285073.07      7093607.75      2285126.83      7093566.14
      2285177.38      7093556.06      2285195.71      7093543.37
      2285275.46      7093458.54      2285284.47      7093307.55
      2285422.94      7093168.14      2285481.19      7093153.90
      2285530.72      7093114.16      2285581.18      7093103.88
      2285630.58      7093063.83      2285727.42      7093056.11
      2285773.09      7093017.79      2285794.42      7093010.03
      2285835.06      7093017.52      2285912.31      7093093.68
      2285932.23      7093102.15      2285980.63      7093064.44
      2286031.19      7093053.95      2286076.81      7093016.11
      2286135.06      7093001.86      2286276.50      7092865.35
      2286303.75      7092859.41      2286379.00      7092860.00

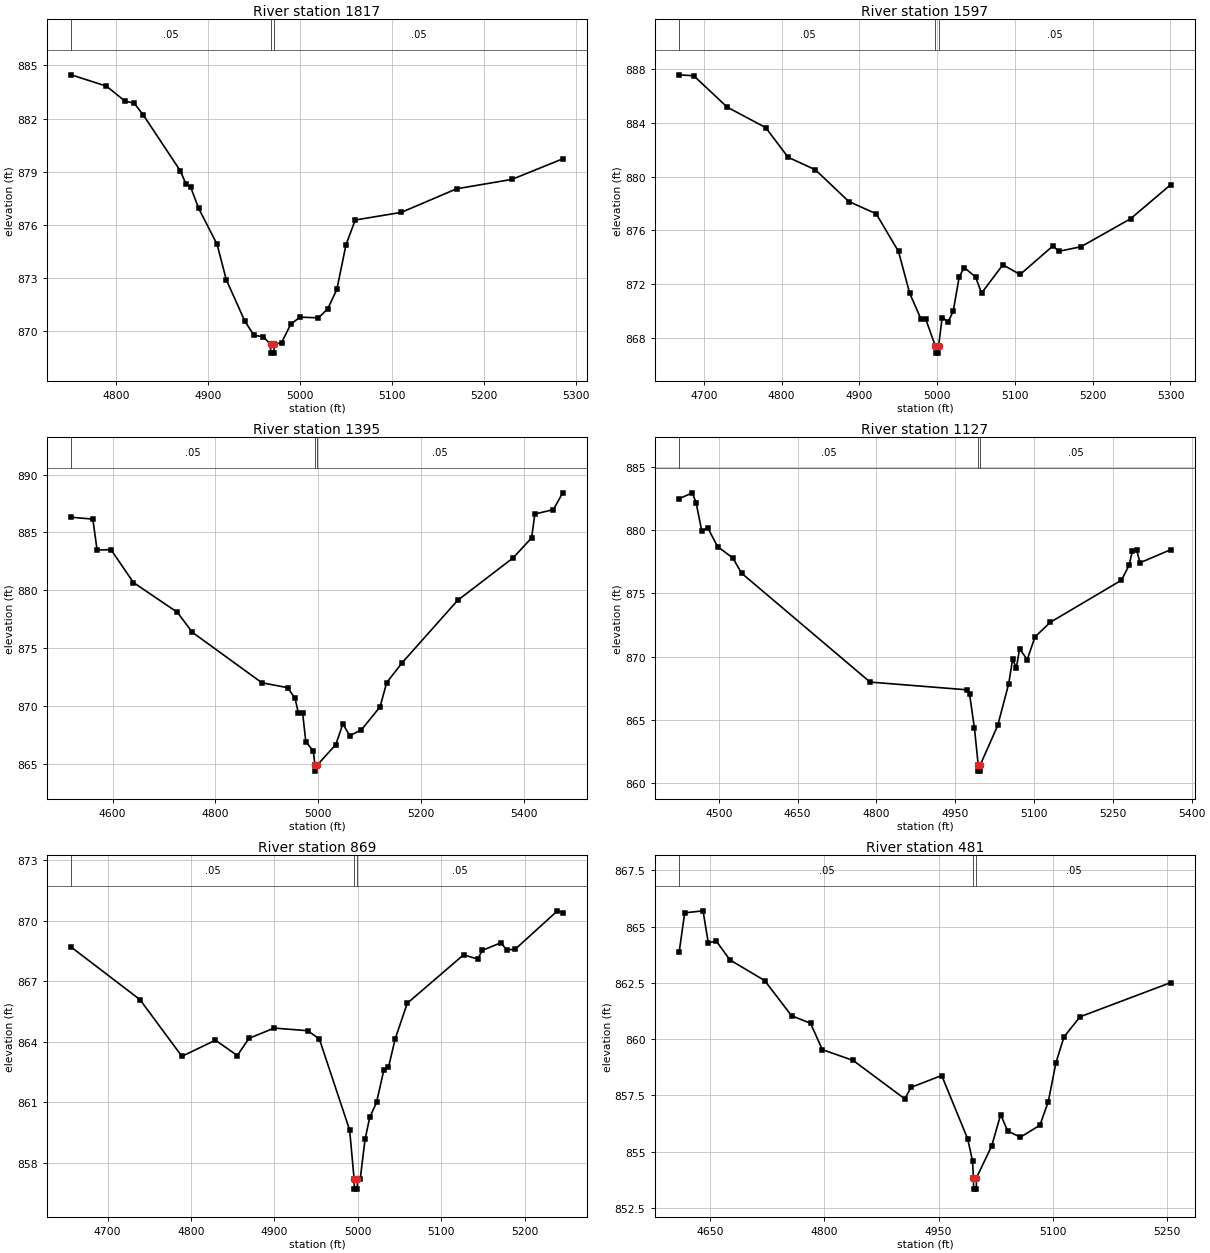
Type RM Length L Ch R = 1,1817,220,220,220
BEGIN DESCRIPTION:
Mapping XS 62e1d371
END DESCRIPTION:
XS GIS Cut Line= 3
      2284994.79      7093858.25      2284992.76      7093535.17
      2284987.54      7093324.82
#Sta/Elev= 30
  4751.6  884.47  4789.8  883.83  4809.9  882.99  4819.9  882.87  4829.9  882.20
  4869.9  879.06  4876.1  878.32  4881.1  878.15  4889.9  876.94  4909.9  874.91
  4919.9  872.91  4939.9  870.59  4949.9  869.77  4959.9  869.70  4967.9  869.27
  4968.1  868.77  4971.6  868.77  4971.9  869.27  4979.9  869.36  4989.9  870.40
  4999.9  870.80  5019.9  870.76  5029.9  871.26  5039.9  872.36  5049.9  874.89
  5059.9  876.28  5109.9  876.71  5169.9  878.04  5229.9  878.57  5285.1  879.73
#Mann=3,-1,0
  4751.6    0.05       0  4967.9    0.05       0  4971.9    0.05       0
Bank Sta=4967.9,4971.9
Exp/Cntr=0.3,0.1

Type RM Length L Ch R = 1,1597,202,202,202
BEGIN DESCRIPTION:
Mapping XS 92f2806b
END DESCRIPTION:
XS GIS Cut Line= 2
      2285404.73      7093800.78      2285002.73      7093313.37
#Sta/Elev= 30
  4668.5  887.56  4687.2  887.49  4730.2  885.16  4779.7  883.64  4808.4  881.44
  4843.5  880.51  4886.5  878.15  4921.7  877.24  4950.4  874.44  4964.7  871.35
  4979.0  869.46  4985.5  869.40  4997.9  867.39  4998.1  866.89  5001.6  866.89
  5001.9  867.39  5006.5  869.53  5014.2  869.22  5020.7  869.99  5028.5  872.58
  5035.0  873.24  5049.4  872.55  5057.2  871.35  5084.5  873.45  5106.7  872.73
  5149.1  874.86  5156.2  874.45  5184.9  874.79  5248.7  876.87  5300.3  879.40
#Mann=3,-1,0
  4668.5    0.05       0  4997.9   0.033       0  5001.9    0.05       0
Bank Sta=4997.9,5001.9
Exp/Cntr=0.3,0.1

Type RM Length L Ch R = 1,1395,268,268,268
BEGIN DESCRIPTION:
MDW T 036 5.0
END DESCRIPTION:
XS GIS Cut Line= 3
      2285567.55      7093760.80      2285278.91      7093376.65
      2284884.00      7093111.08
#Sta/Elev= 30
  4519.5  886.31  4561.5  886.15  4569.8  883.48  4596.9  883.51  4640.6  880.67
  4726.0  878.10  4755.2  876.37  4890.6  872.01  4940.6  871.59  4955.1  870.66
  4961.4  869.43  4969.7  869.42  4976.0  866.92  4990.5  866.12  4993.8  864.88
  4994.0  864.38  4997.8  864.88  5034.4  866.68  5048.1  868.46  5061.4  867.44
  5084.2  867.95  5120.4  869.93  5133.4  872.03  5163.4  873.74  5271.4  879.13
  5379.4  882.80  5415.4  884.53  5421.7  886.59  5457.8  886.97  5475.9  888.42
#Mann=3,-1,0
  4519.5    0.05       0  4993.8   0.033       0  4997.8    0.05       0
Bank Sta=4993.8,4997.8
Exp/Cntr=0.3,0.1

Type RM Length L Ch R = 1,1127,258,258,258
BEGIN DESCRIPTION:
MDW T 036 4.0
END DESCRIPTION:
XS GIS Cut Line= 3
      2285642.85      7093699.70      2285422.81      7093165.32
      2285208.18      7092879.30
#Sta/Elev= 30
  4424.6  882.48  4449.6  882.94  4456.7  882.16  4467.5  879.93  4478.9  880.18
  4497.5  878.70  4526.8  877.79  4543.2  876.60  4787.9  868.00  4971.8  867.39
  4977.2  867.06  4986.6  864.34  4993.7  861.47  4994.0  860.97  4997.5  860.97
  4997.7  861.47  5030.9  864.58  5051.7  867.86  5059.2  869.80  5066.3  869.13
  5072.5  870.62  5087.1  869.78  5101.7  871.56  5130.9  872.72  5266.3  876.04
  5280.9  877.22  5287.1  878.35  5295.4  878.41  5301.7  877.42  5360.1  878.45
#Mann=3,-1,0
  4424.6    0.05       0  4993.7   0.033       0  4997.7    0.05       0
Bank Sta=4993.7,4997.7
Exp/Cntr=0.3,0.1

Type RM Length L Ch R = 1,869,388,388,388
BEGIN DESCRIPTION:
MDW T 036 3.0
END DESCRIPTION:
XS GIS Cut Line= 3
      2285684.79      7093401.97      2285649.10      7093060.23
      2285541.10      7092839.53
#Sta/Elev= 30
  4656.4  868.68  4738.8  866.08  4789.1  863.27  4829.3  864.07  4855.5  863.31
  4869.5  864.16  4899.7  864.67  4939.9  864.54  4953.9  864.13  4990.2  859.62
  4995.6  857.19  4995.9  856.69  4999.4  856.69  4999.6  857.19  5002.9  857.19
  5008.7  859.16  5014.3  860.24  5022.5  860.99  5031.2  862.59  5036.8  862.73
  5044.8  864.13  5059.3  865.90  5126.8  868.30  5143.8  868.09  5149.3  868.52
  5171.8  868.90  5178.4  868.54  5188.8  868.58  5239.4  870.48  5245.7  870.38
#Mann=3,-1,0
  4656.4    0.05       0  4995.6   0.033       0  4999.6    0.05       0
Bank Sta=4995.6,4999.6
Exp/Cntr=0.3,0.1

Type RM Length L Ch R = 1,481,213,213,213
BEGIN DESCRIPTION:
MDW T 036 2.0
END DESCRIPTION:
XS GIS Cut Line= 3
      2286071.44      7093446.99      2285972.94      7093068.80
      2285890.47      7092827.30
#Sta/Elev= 30
  4609.2  863.88  4616.4  865.61  4640.5  865.70  4647.4  864.27  4657.8  864.36
  4675.8  863.52  4721.5  862.60  4756.8  861.04  4781.8  860.70  4797.3  859.53
  4837.8  859.05  4905.8  857.34  4913.7  857.85  4954.2  858.38  4988.4  855.56
  4994.7  854.59  4995.9  853.83  4996.2  853.33  4999.7  853.33  4999.9  853.83
  5019.9  855.25  5031.7  856.64  5041.0  855.91  5057.7  855.64  5083.3  856.17
  5094.3  857.22  5104.4  858.95  5115.0  860.10  5136.1  860.99  5255.2  862.51
#Mann=3,-1,0
  4609.2    0.05       0  4995.9   0.033       0  4999.9    0.05       0
Bank Sta=4995.9,4999.9
Exp/Cntr=0.3,0.1

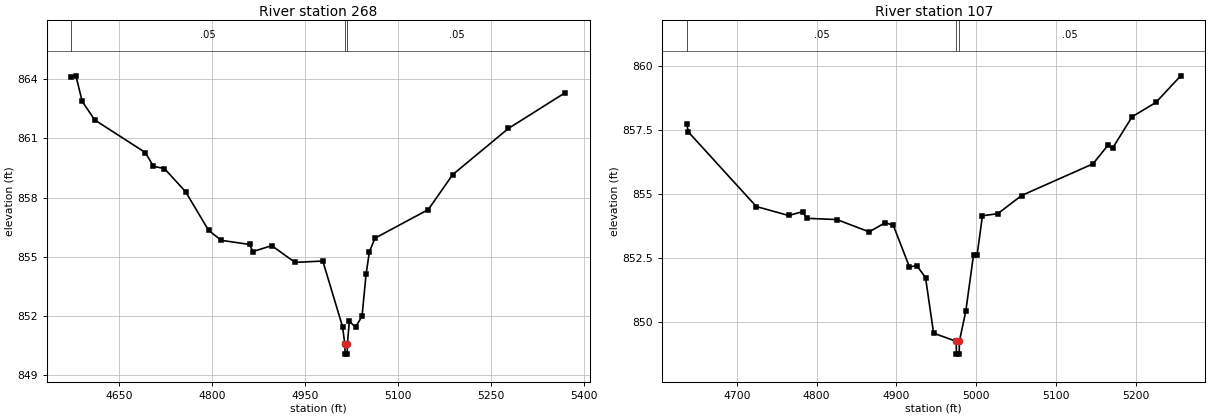
Type RM Length L Ch R = 1,268,161,161,161
BEGIN DESCRIPTION:
Mapping XS a7d3597c
END DESCRIPTION:
XS GIS Cut Line= 4
      2286109.16      7093397.14      2286178.35      7093041.01
      2286135.90      7092906.81      2285863.66      7092798.33
#Sta/Elev= 30
  4573.6  864.13  4580.9  864.17  4591.1  862.87  4611.4  861.93  4692.9  860.28
  4706.0  859.58  4723.5  859.47  4757.7  858.30  4794.8  856.34  4815.2  855.83
  4861.1  855.62  4866.2  855.26  4896.7  855.56  4934.4  854.71  4979.1  854.78
  5010.9  851.45  5014.6  850.56  5014.9  850.06  5018.4  850.06  5018.6  850.56
  5021.9  851.72  5031.8  851.43  5042.3  851.98  5048.9  854.12  5054.2  855.25
  5063.3  855.94  5149.2  857.39  5188.5  859.16  5278.3  861.50  5370.2  863.32
#Mann=3,-1,0
  4573.6    0.05       0  5014.6   0.033       0  5018.6    0.05       0
Bank Sta=5014.6,5018.6
Exp/Cntr=0.3,0.1

Type RM Length L Ch R = 1,107,0,0,0
BEGIN DESCRIPTION:
MDW T 036 1.0
END DESCRIPTION:
XS GIS Cut Line= 3
      2286223.58      7093226.37      2286273.84      7092866.07
      2286036.21      7092773.25
#Sta/Elev= 30
  4637.3  857.71  4639.5  857.41  4724.5  854.50  4764.9  854.15  4782.6  854.30
  4787.6  854.04  4825.5  853.99  4865.9  853.51  4886.1  853.87  4896.2  853.76
  4916.3  852.14  4925.6  852.19  4936.5  851.72  4946.6  849.55  4974.9  849.23
  4975.2  848.73  4978.7  848.73  4978.9  849.23  4987.0  850.42  4996.6  852.61
  5001.1  852.61  5007.8  854.14  5027.0  854.22  5056.8  854.93  5146.3  856.17
  5165.4  856.91  5170.8  856.78  5195.3  858.01  5225.1  858.57  5256.2  859.61
#Mann=3,-1,0
  4637.3    0.05       0  4974.9   0.033       0  4978.9    0.05       0
Bank Sta=4974.9,4978.9
Exp/Cntr=0.3,0.1

Chan Stop Cuts=-1