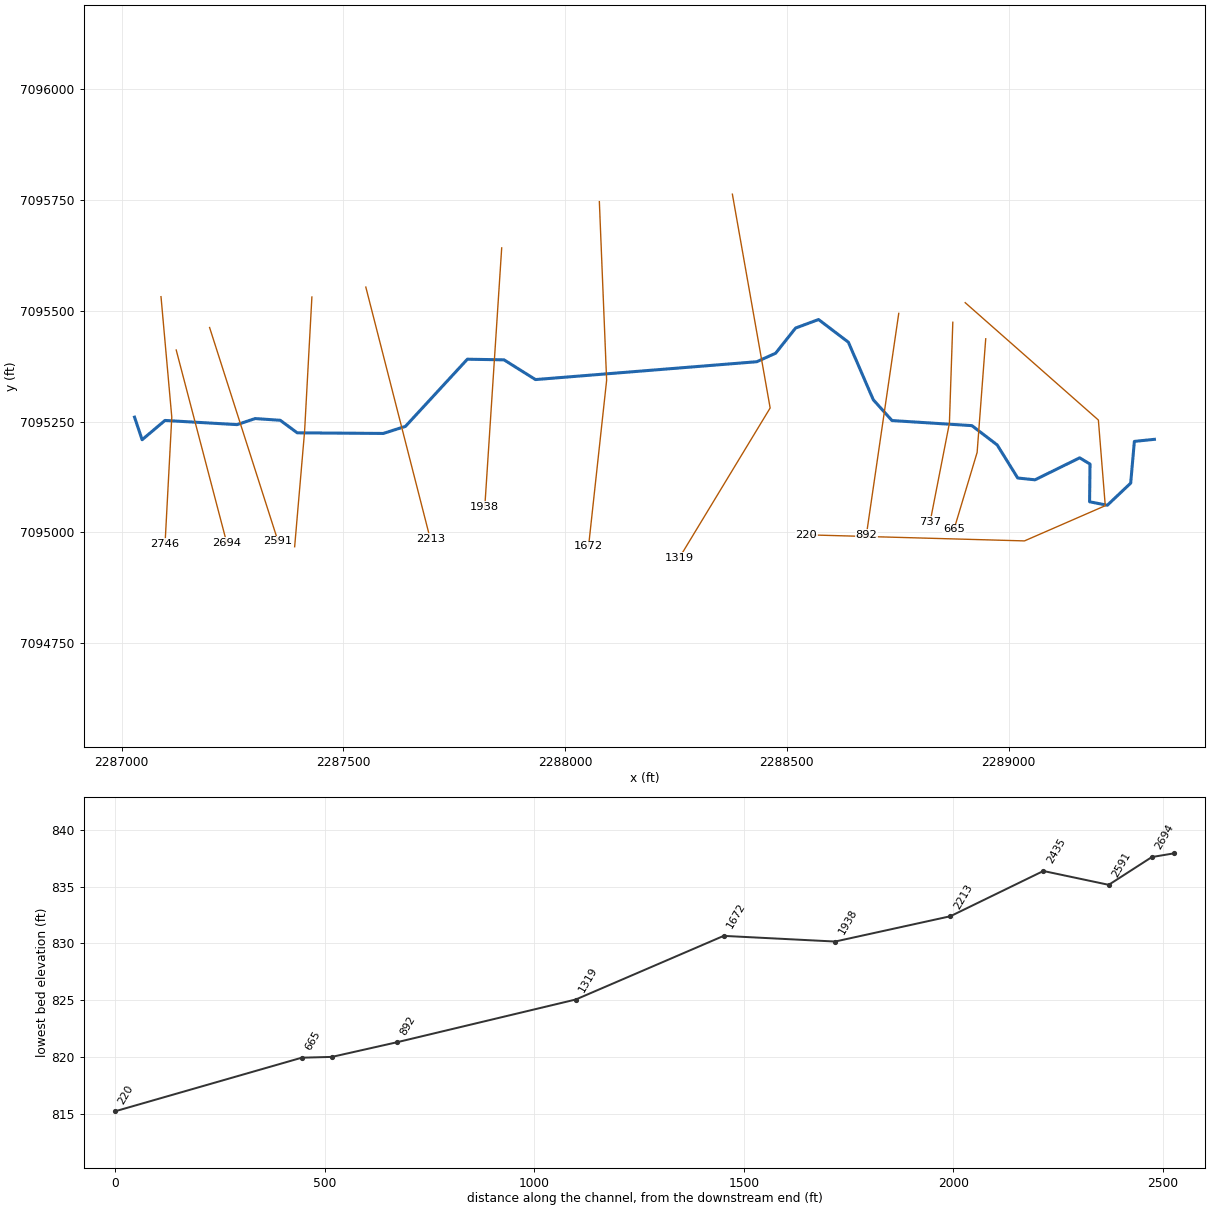
--- MDW T 037.prj (project) ---

Proj Title=MDW T 037 Base Level Engineering
Current Plan=p01
Default Exp/Contr=0.3,0.1
English Units
Geom File=g01
Flow File=f01
Plan File=p01
BEGIN DESCRIPTION:
MDW T 037
END DESCRIPTION:

--- MDW T 037.p01 (plan) ---

Plan Title=Multiple Run
Short Identifier=Multiple
Geom File=g01
Flow File=f01
Subcritical Flow
K Sum by GR= 0
Std Step Tol= 0.01
Critical Tol= 0.01
Num of Std Step Trials= 20
Max Error Tol= 0.3
Flow Tol Ratio= 0.001
Split Flow NTrial= 30
Split Flow Tol= 0.02
Split Flow Ratio= 0.02
Log Output Level= 0
Friction Slope Method= 1
Unsteady Friction Slope Method= 2
Unsteady Bridges Friction Slope Method= 1
Parabolic Critical Depth
Global Vel Dist=  1 , 1 , 1
Global Log Level= 0
CheckData=True
Encroach Param= -1, 0, 0, 0
BEGIN DESCRIPTION:
Multiple Run
END DESCRIPTION:

--- MDW T 037.f01 (steady flow) ---

Flow Title=Multiple
Number of Profiles=7
Profile Names=10-year,25-year,50-year,1pct_min,100-year,1pct_plu,500-year
River Rch & RM= MDW T 037,Reach-1,2746
     512     700     855     519    1037    2068    1525
Boundary for River Rch & Prof#=MDW T 037,Reach-1,1
Up Type=0
Dn Type=3
Dn Slope=0.005
Boundary for River Rch & Prof#=MDW T 037,Reach-1,2
Up Type=0
Dn Type=3
Dn Slope=0.005
Boundary for River Rch & Prof#=MDW T 037,Reach-1,3
Up Type=0
Dn Type=3
Dn Slope=0.005
Boundary for River Rch & Prof#=MDW T 037,Reach-1,4
Up Type=0
Dn Type=3
Dn Slope=0.005
Boundary for River Rch & Prof#=MDW T 037,Reach-1,5
Up Type=0
Dn Type=3
Dn Slope=0.005
Boundary for River Rch & Prof#=MDW T 037,Reach-1,6
Up Type=0
Dn Type=3
Dn Slope=0.005
Boundary for River Rch & Prof#=MDW T 037,Reach-1,7
Up Type=0
Dn Type=3
Dn Slope=0.005

--- MDW T 037.g01 (geometry) ---

Geom Title=Existing Conditions

River Reach=MDW T 037,Reach-1
Reach XY= 30
      2287029.00      7095260.00      2287046.08      7095209.05
      2287097.64      7095252.59      2287260.20      7095243.17
      2287300.91      7095256.81      2287357.58      7095252.96
      2287395.93      7095224.65      2287589.98      7095223.26
      2287639.95      7095239.21      2287779.56      7095390.66
      2287862.20      7095389.27      2287933.20      7095344.74
      2288432.28      7095385.01      2288474.79      7095404.19
      2288519.72      7095460.91      2288571.52      7095480.18
      2288638.87      7095428.99      2288694.94      7095299.35
      2288737.18      7095252.32      2288917.41      7095240.88
      2288974.47      7095197.31      2289020.71      7095122.74
      2289059.74      7095118.72      2289160.44      7095168.27
      2289183.79      7095154.16      2289182.78      7095069.19
      2289222.77      7095061.34      2289275.49      7095111.23
      2289283.75      7095205.32      2289329.00      7095210.00

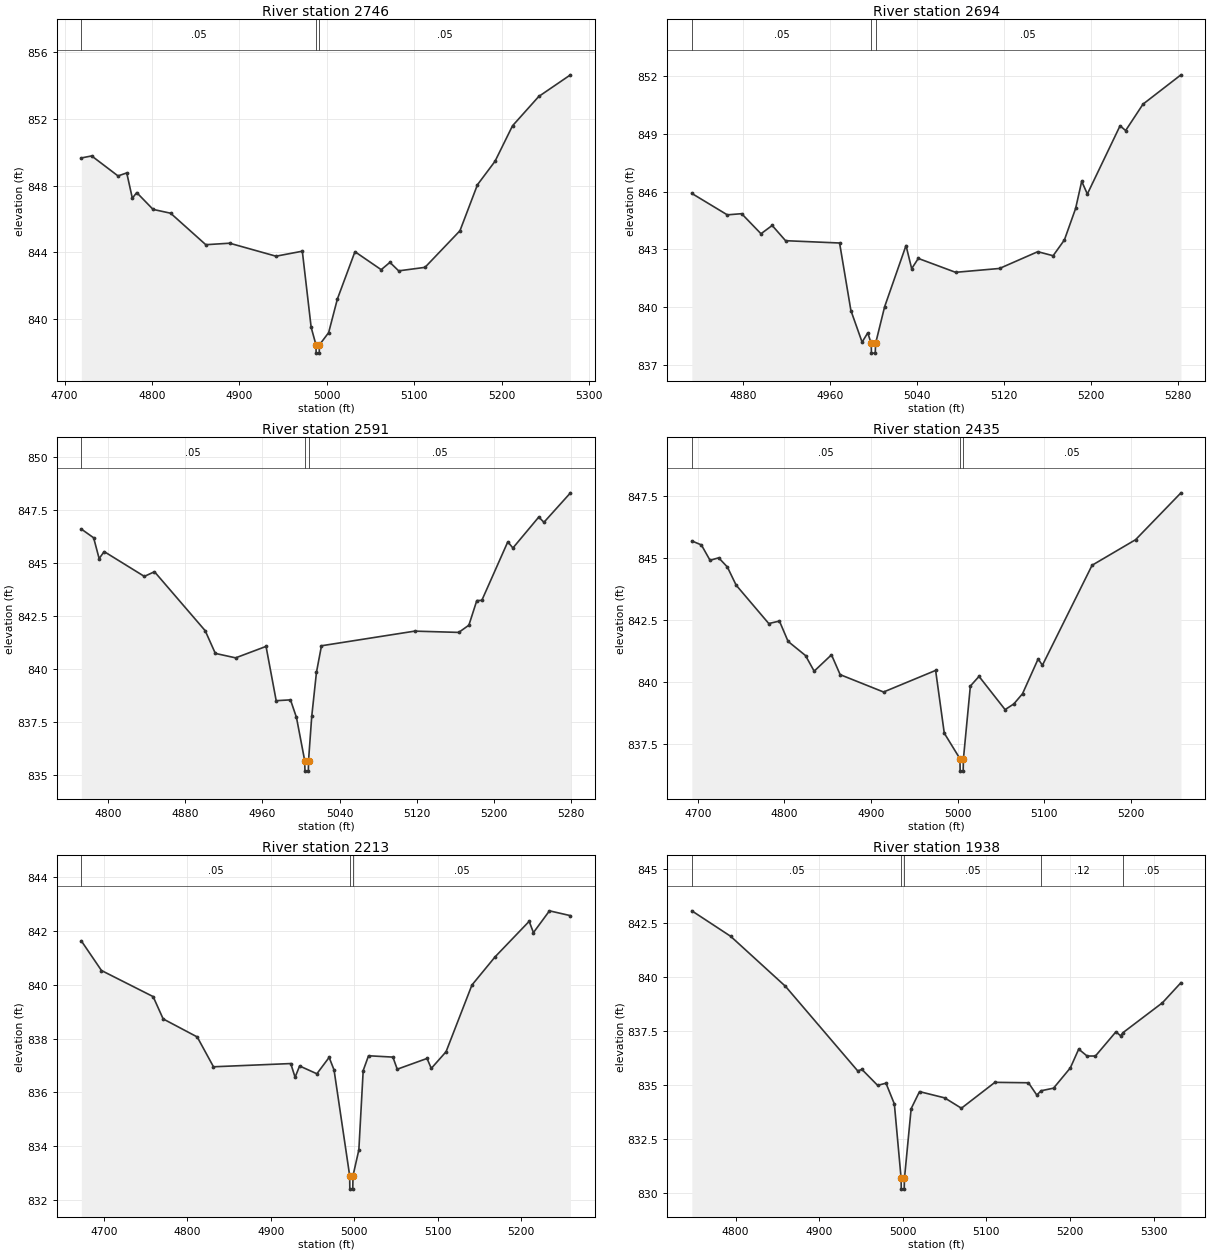
Type RM Length L Ch R = 1,2746,52,52,52
BEGIN DESCRIPTION:
MDW T 037 6.0
END DESCRIPTION:
XS GIS Cut Line= 3
      2287088.69      7095531.71      2287113.00      7095260.01
      2287097.78      7094973.80
#Sta/Elev= 30
  4719.2  849.66  4731.0  849.78  4761.1  848.58  4771.1  848.76  4777.5  847.24
  4782.5  847.58  4801.2  846.57  4821.3  846.34  4861.5  844.45  4888.8  844.54
  4941.8  843.76  4971.9  844.06  4982.0  839.49  4987.5  838.44  4987.7  837.94
  4991.2  837.94  4991.5  838.44  5002.0  839.17  5012.0  841.19  5032.1  844.03
  5062.1  842.95  5072.1  843.39  5082.1  842.88  5112.2  843.09  5152.2  845.29
  5172.2  848.05  5192.3  849.46  5212.3  851.59  5242.3  853.35  5278.6  854.65
#Mann=3,-1,0
  4719.2    0.05       0  4987.5   0.033       0  4991.5    0.05       0
Bank Sta=4987.5,4991.5
Exp/Cntr=0.3,0.1

Type RM Length L Ch R = 1,2694,103,103,103
BEGIN DESCRIPTION:
Mapping XS 6233a188
END DESCRIPTION:
XS GIS Cut Line= 2
      2287122.97      7095411.49      2287237.03      7094976.29
#Sta/Elev= 30
  4833.0  845.90  4865.6  844.79  4878.8  844.85  4896.6  843.81  4906.9  844.24
  4919.2  843.45  4968.9  843.33  4979.3  839.83  4989.6  838.19  4994.8  838.67
  4998.0  838.12  4998.2  837.62  5001.7  837.62  5002.0  838.12  5010.3  840.02
  5030.0  843.20  5035.2  842.00  5041.3  842.53  5075.6  841.81  5116.0  842.01
  5151.2  842.88  5165.3  842.67  5175.7  843.49  5186.0  845.12  5191.6  846.53
  5196.8  845.87  5226.9  849.41  5232.0  849.16  5248.0  850.53  5282.9  852.05
#Mann=3,-1,0
  4833.0    0.05       0  4998.0   0.033       0  5002.0    0.05       0
Bank Sta=4998,5002
Exp/Cntr=0.3,0.1

Type RM Length L Ch R = 1,2591,156,156,156
BEGIN DESCRIPTION:
Mapping XS 6d85b758
END DESCRIPTION:
XS GIS Cut Line= 2
      2287198.28      7095462.12      2287352.72      7094979.84
#Sta/Elev= 30
  4772.7  846.58  4785.4  846.17  4791.1  845.19  4796.3  845.52  4837.9  844.35
  4848.4  844.57  4900.9  841.79  4911.4  840.72  4932.4  840.51  4963.9  841.05
  4974.4  838.49  4989.2  838.53  4995.4  837.70  5003.9  835.67  5004.2  835.17
  5007.7  835.17  5007.9  835.67  5011.2  837.75  5016.1  839.83  5021.3  841.08
  5117.8  841.77  5163.4  841.71  5173.9  842.05  5182.1  843.21  5187.3  843.22
  5214.2  845.98  5219.5  845.69  5246.3  847.15  5251.6  846.90  5279.1  848.29
#Mann=3,-1,0
  4772.7    0.05       0  5003.9   0.033       0  5007.9    0.05       0
Bank Sta=5003.9,5007.9
Exp/Cntr=0.3,0.1

Type RM Length L Ch R = 1,2435,222,222,222
BEGIN DESCRIPTION:
MDW T 037 5.0
END DESCRIPTION:
XS GIS Cut Line= 3
      2287428.97      7095530.98      2287412.43      7095226.89
      2287390.08      7094967.79
#Sta/Elev= 30
  4693.1  845.67  4704.1  845.51  4714.1  844.89  4724.1  844.99  4734.1  844.62
  4744.2  843.89  4781.9  842.34  4794.2  842.44  4804.2  841.62  4824.3  841.05
  4834.3  840.42  4854.3  841.08  4864.3  840.28  4914.4  839.58  4974.5  840.45
  4984.5  837.92  5002.6  836.89  5002.8  836.39  5006.3  836.39  5006.6  836.89
  5014.6  839.82  5024.6  840.21  5054.7  838.87  5064.8  839.10  5074.8  839.51
  5092.8  840.91  5097.8  840.66  5155.1  844.69  5205.3  845.72  5257.7  847.61
#Mann=3,-1,0
  4693.1    0.05       0  5002.6   0.033       0  5006.6    0.05       0
Bank Sta=5002.6,5006.6
Exp/Cntr=0.3,0.1

Type RM Length L Ch R = 1,2213,275,275,275
BEGIN DESCRIPTION:
Mapping XS df728a5a
END DESCRIPTION:
XS GIS Cut Line= 2
      2287550.57      7095553.35      2287695.90      7094985.55
#Sta/Elev= 30
  4673.0  841.63  4697.1  840.53  4759.0  839.56  4771.0  838.73  4811.8  838.06
  4831.3  836.95  4923.9  837.07  4929.1  836.56  4934.5  836.98  4955.2  836.69
  4969.9  837.30  4975.8  836.83  4994.5  832.90  4994.7  832.40  4998.2  832.40
  4998.5  832.90  5005.5  833.86  5010.7  836.81  5017.1  837.36  5046.3  837.31
  5051.5  836.86  5087.2  837.26  5092.3  836.89  5110.0  837.51  5141.0  839.99
  5168.8  841.04  5209.6  842.36  5214.7  841.94  5233.9  842.75  5259.1  842.57
#Mann=3,-1,0
  4673.0    0.05       0  4994.5   0.033       0  4998.5    0.05       0
Bank Sta=4994.5,4998.5
Exp/Cntr=0.3,0.1

Type RM Length L Ch R = 1,1938,266,266,266
BEGIN DESCRIPTION:
Mapping XS d5f2cc5c
END DESCRIPTION:
XS GIS Cut Line= 2
      2287857.00      7095641.72      2287818.90      7095057.96
#Sta/Elev= 30
  4747.7  843.07  4794.1  841.89  4859.7  839.57  4946.1  835.65  4951.1  835.72
  4969.9  834.98  4979.9  835.08  4989.9  834.12  4998.0  830.67  4998.2  830.17
  5001.7  830.17  5002.0  830.67  5010.0  833.90  5020.0  834.69  5050.1  834.40
  5070.1  833.92  5110.2  835.12  5150.3  835.10  5160.3  834.53  5165.4  834.73
  5180.3  834.85  5200.4  835.79  5210.4  836.66  5220.4  836.34  5230.4  836.34
  5254.9  837.46  5260.5  837.28  5263.6  837.43  5310.6  838.81  5332.7  839.74
#Mann=5,-1,0
  4747.7    0.05       0  4998.0   0.033       0  5002.0    0.05       0
  5165.4    0.12       0  5263.6    0.05       0
Bank Sta=4998,5002
Exp/Cntr=0.3,0.1

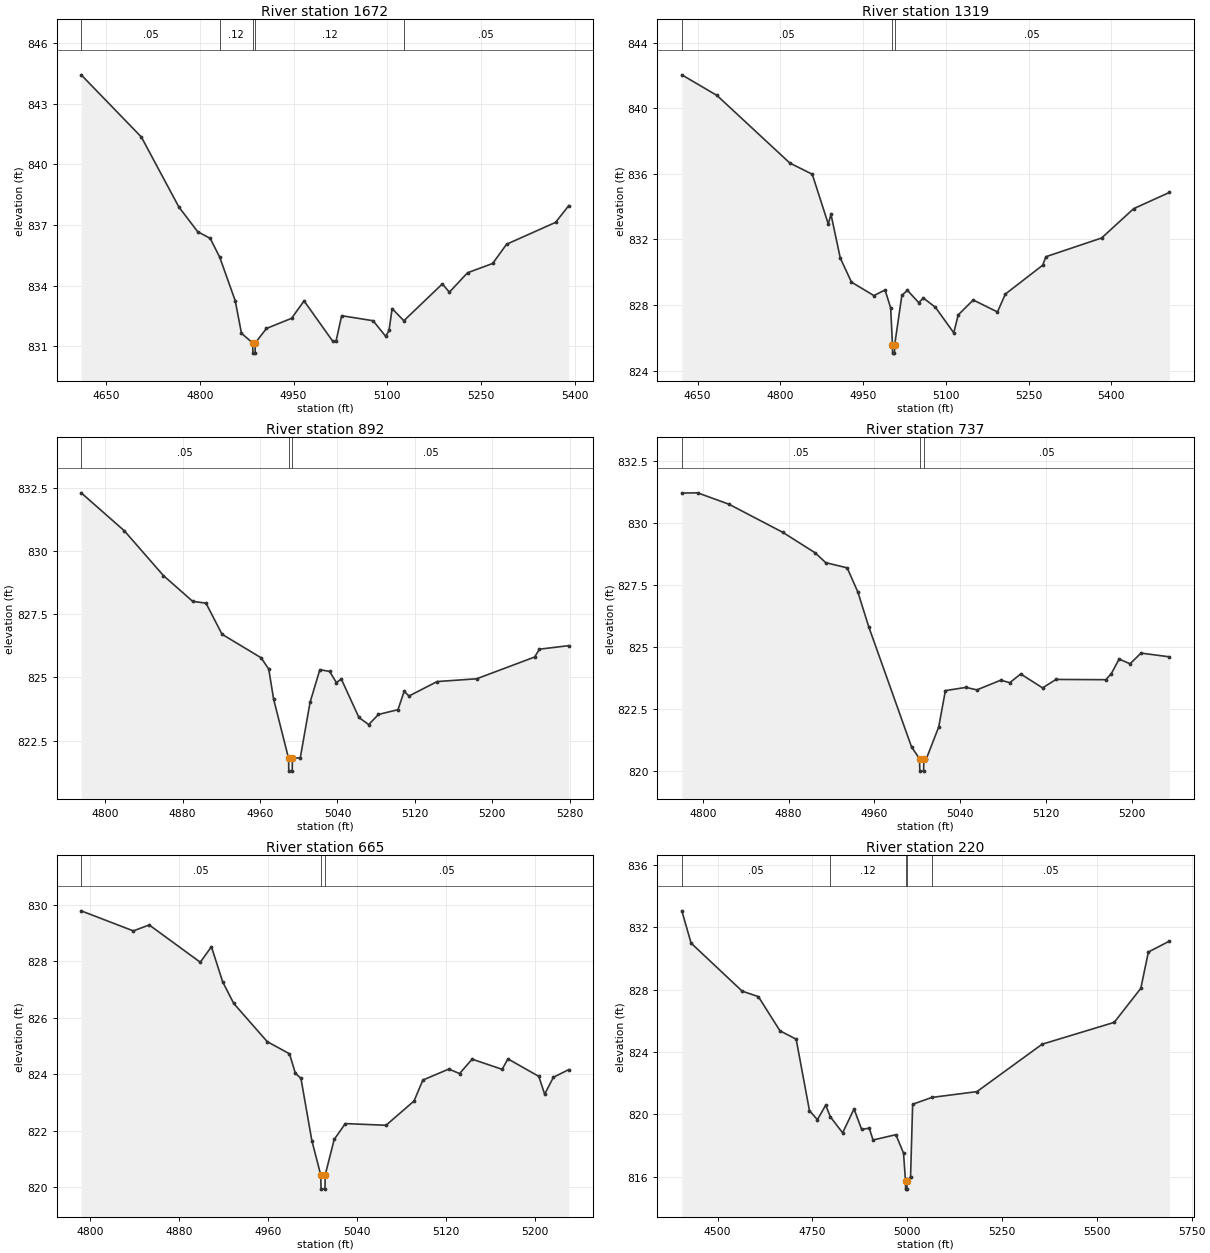
Type RM Length L Ch R = 1,1672,353,353,353
BEGIN DESCRIPTION:
MDW T 037 3.0
END DESCRIPTION:
XS GIS Cut Line= 3
      2288077.23      7095746.10      2288093.64      7095343.16
      2288052.93      7094969.04
#Sta/Elev= 30
  4610.4  844.42  4706.6  841.35  4766.6  837.89  4796.7  836.67  4816.7  836.34
  4831.9  835.41  4856.7  833.26  4866.7  831.65  4884.7  831.17  4885.0  830.67
  4888.5  830.67  4888.7  831.17  4906.7  831.89  4946.8  832.39  4966.8  833.25
  5012.8  831.25  5017.8  831.25  5026.9  832.52  5077.2  832.27  5097.3  831.50
  5102.6  831.79  5107.6  832.87  5126.3  832.27  5187.9  834.09  5199.1  833.68
  5228.1  834.64  5268.3  835.10  5290.6  836.05  5368.9  837.13  5390.0  837.96
#Mann=5,-1,0
  4610.4    0.05       0  4831.9    0.12       0  4884.7    0.07       0
  4888.7    0.12       0  5126.3    0.05       0
Bank Sta=4884.7,4888.7
Exp/Cntr=0.3,0.1

Type RM Length L Ch R = 1,1319,427,427,427
BEGIN DESCRIPTION:
MDW T 037 2.0
END DESCRIPTION:
XS GIS Cut Line= 3
      2288377.23      7095762.81      2288462.39      7095280.66
      2288258.02      7094943.47
#Sta/Elev= 30
  4621.3  842.03  4685.1  840.77  4817.1  836.65  4857.7  835.97  4886.7  832.94
  4891.7  833.52  4908.5  830.86  4928.8  829.39  4969.4  828.57  4989.7  828.91
  4999.9  827.81  5003.1  825.56  5003.3  825.06  5006.8  825.06  5007.1  825.56
  5020.2  828.59  5030.3  828.89  5050.7  828.14  5059.2  828.42  5081.1  827.85
  5114.2  826.30  5122.3  827.39  5149.5  828.30  5193.5  827.57  5207.7  828.66
  5275.4  830.42  5281.3  830.94  5382.2  832.08  5440.4  833.87  5505.2  834.86
#Mann=3,-1,0
  4621.3    0.05       0  5003.1   0.033       0  5007.1    0.05       0
Bank Sta=5003.1,5007.1
Exp/Cntr=0.3,0.1

Type RM Length L Ch R = 1,892,155,155,155
BEGIN DESCRIPTION:
Mapping XS 6002e450
END DESCRIPTION:
XS GIS Cut Line= 2
      2288752.42      7095494.08      2288679.58      7094995.37
#Sta/Elev= 30
  4775.1  832.29  4819.7  830.79  4860.1  829.02  4890.4  828.00  4904.1  827.93
  4920.7  826.70  4961.1  825.77  4969.0  825.32  4974.0  824.14  4989.5  821.79
  4989.7  821.29  4993.2  821.29  4993.5  821.79  5001.6  821.82  5011.7  824.01
  5021.8  825.30  5031.9  825.23  5038.9  824.79  5044.0  824.93  5062.2  823.41
  5072.3  823.13  5082.4  823.53  5102.6  823.72  5108.9  824.44  5114.0  824.26
  5143.0  824.83  5183.9  824.94  5243.8  825.80  5248.8  826.11  5279.1  826.25
#Mann=3,-1,0
  4775.1    0.05       0  4989.5   0.033       0  4993.5    0.05       0
Bank Sta=4989.5,4993.5
Exp/Cntr=0.3,0.1

Type RM Length L Ch R = 1,737,72,72,72
BEGIN DESCRIPTION:
Mapping XS 950b1543
END DESCRIPTION:
XS GIS Cut Line= 3
      2288874.35      7095474.02      2288866.64      7095246.23
      2288823.19      7095023.96
#Sta/Elev= 30
  4780.5  831.19  4795.2  831.20  4824.5  830.74  4874.6  829.61  4904.6  828.79
  4914.6  828.39  4934.6  828.18  4944.6  827.20  4954.6  825.82  4994.6  820.97
  5002.0  820.50  5002.3  820.00  5005.8  820.00  5006.0  820.50  5008.4  820.50
  5019.9  821.78  5026.1  823.24  5045.3  823.37  5055.5  823.27  5077.7  823.66
  5086.1  823.56  5096.3  823.91  5116.7  823.35  5129.2  823.69  5175.6  823.68
  5180.7  823.92  5188.0  824.51  5198.2  824.32  5208.4  824.75  5234.9  824.60
#Mann=3,-1,0
  4780.5    0.05       0  5002.0   0.033       0  5006.0    0.05       0
Bank Sta=5002,5006
Exp/Cntr=0.3,0.1

Type RM Length L Ch R = 1,665,445,445,445
BEGIN DESCRIPTION:
Mapping XS 81d76621
END DESCRIPTION:
XS GIS Cut Line= 3
      2288948.56      7095436.80      2288929.16      7095180.45
      2288877.01      7095006.80
#Sta/Elev= 30
  4791.7  829.78  4838.6  829.07  4852.9  829.28  4898.8  827.96  4908.8  828.51
  4918.9  827.27  4928.9  826.50  4959.0  825.15  4979.0  824.72  4984.3  824.03
  4989.3  823.85  4999.1  821.65  5007.1  820.43  5007.4  819.93  5010.9  819.93
  5011.1  820.43  5019.2  821.69  5029.2  822.25  5065.8  822.19  5091.0  823.05
  5098.9  823.79  5122.3  824.18  5131.9  824.02  5143.2  824.53  5170.2  824.17
  5175.4  824.54  5203.2  823.92  5208.4  823.29  5216.3  823.89  5230.1  824.16
#Mann=3,-1,0
  4791.7    0.05       0  5007.1   0.033       0  5011.1    0.05       0
Bank Sta=5007.1,5011.1
Exp/Cntr=0.3,0.1

Type RM Length L Ch R = 1,220,0,0,0
BEGIN DESCRIPTION:
MDW T 037 0.5
END DESCRIPTION:
XS GIS Cut Line= 5
      2288902.29      7095518.18      2289202.60      7095253.49
      2289218.15      7095060.32      2289035.93      7094980.93
      2288543.49      7094994.71
#Sta/Elev= 30
  4405.9  833.05  4430.3  830.98  4565.0  827.90  4607.7  827.55  4664.6  825.36
  4707.3  824.82  4742.4  820.24  4763.3  819.66  4785.1  820.59  4797.6  819.84
  4829.8  818.82  4859.9  820.35  4879.9  819.04  4900.0  819.12  4910.0  818.36
  4970.2  818.70  4990.3  817.52  4995.7  815.71  4995.9  815.21  4999.4  815.21
  4999.7  815.71  5008.9  816.00  5014.4  820.65  5065.3  821.09  5183.8  821.46
  5355.8  824.50  5545.8  825.90  5615.9  828.08  5635.9  830.41  5691.4  831.11
#Mann=5,-1,0
  4405.9    0.05       0  4797.6    0.12       0  4995.7    0.07       0
  4999.7    0.12       0  5065.3    0.05       0
Bank Sta=4995.7,4999.7
Exp/Cntr=0.3,0.1

Chan Stop Cuts=-1