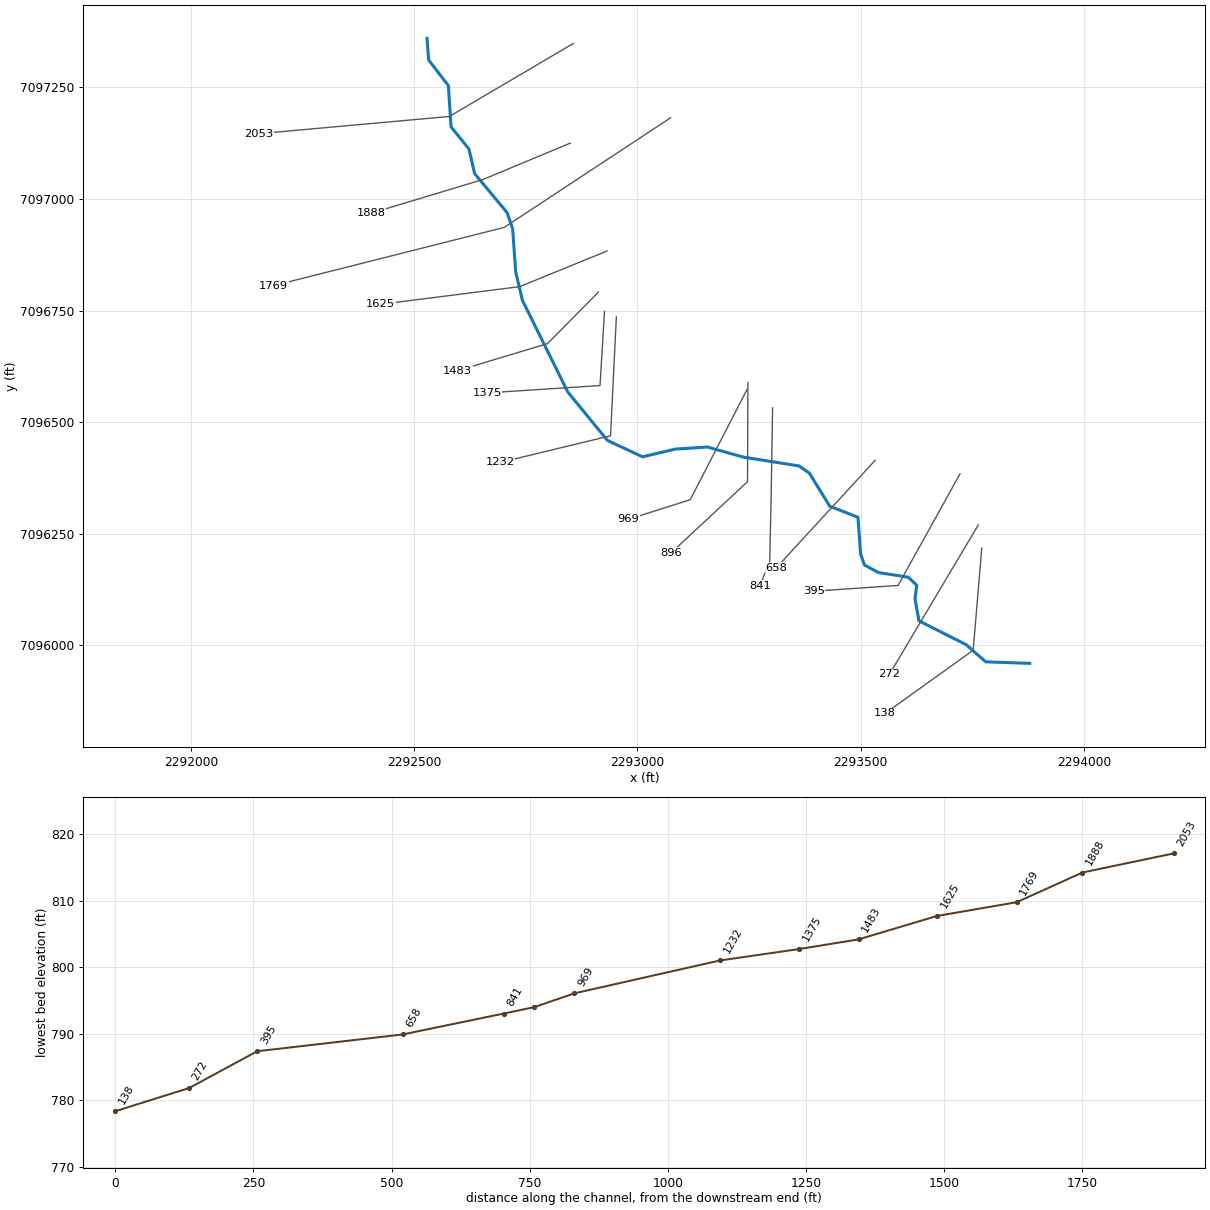
--- MDW T 038.prj (project) ---

Proj Title=MDW T 038 Base Level Engineering
Current Plan=p01
Default Exp/Contr=0.3,0.1
English Units
Geom File=g01
Flow File=f01
Plan File=p01
BEGIN DESCRIPTION:
MDW T 038
END DESCRIPTION:

--- MDW T 038.p01 (plan) ---

Plan Title=Multiple Run
Short Identifier=Multiple
Geom File=g01
Flow File=f01
Subcritical Flow
K Sum by GR= 0
Std Step Tol= 0.01
Critical Tol= 0.01
Num of Std Step Trials= 20
Max Error Tol= 0.3
Flow Tol Ratio= 0.001
Split Flow NTrial= 30
Split Flow Tol= 0.02
Split Flow Ratio= 0.02
Log Output Level= 0
Friction Slope Method= 1
Unsteady Friction Slope Method= 2
Unsteady Bridges Friction Slope Method= 1
Parabolic Critical Depth
Global Vel Dist=  1 , 1 , 1
Global Log Level= 0
CheckData=True
Encroach Param= -1, 0, 0, 0
BEGIN DESCRIPTION:
Multiple Run
END DESCRIPTION:

--- MDW T 038.f01 (steady flow) ---

Flow Title=Multiple
Number of Profiles=7
Profile Names=10-year,25-year,50-year,1pct_min,100-year,1pct_plu,500-year
River Rch & RM= MDW T 038,Reach-1,2053
     150     189     219     127     253     504     335
Boundary for River Rch & Prof#=MDW T 038,Reach-1,1
Up Type=0
Dn Type=3
Dn Slope=0.01
Boundary for River Rch & Prof#=MDW T 038,Reach-1,2
Up Type=0
Dn Type=3
Dn Slope=0.01
Boundary for River Rch & Prof#=MDW T 038,Reach-1,3
Up Type=0
Dn Type=3
Dn Slope=0.01
Boundary for River Rch & Prof#=MDW T 038,Reach-1,4
Up Type=0
Dn Type=3
Dn Slope=0.01
Boundary for River Rch & Prof#=MDW T 038,Reach-1,5
Up Type=0
Dn Type=3
Dn Slope=0.01
Boundary for River Rch & Prof#=MDW T 038,Reach-1,6
Up Type=0
Dn Type=3
Dn Slope=0.01
Boundary for River Rch & Prof#=MDW T 038,Reach-1,7
Up Type=0
Dn Type=3
Dn Slope=0.01

--- MDW T 038.g01 (geometry) ---

Geom Title=Existing Conditions

River Reach=MDW T 038,Reach-1
Reach XY= 30
      2292529.00      7097360.00      2292532.64      7097311.51
      2292576.77      7097254.08      2292582.82      7097161.58
      2292622.88      7097112.18      2292635.54      7097057.06
      2292708.39      7096969.47      2292720.71      7096933.69
      2292727.65      7096836.40      2292742.75      7096772.88
      2292844.31      7096567.72      2292933.22      7096459.24
      2293011.65      7096422.63      2293085.45      7096439.94
      2293156.78      7096444.54      2293236.95      7096422.10
      2293362.15      7096402.14      2293385.27      7096386.21
      2293431.09      7096311.88      2293494.27      7096287.25
      2293500.21      7096204.43      2293508.95      7096180.26
      2293539.74      7096163.39      2293607.02      7096152.96
      2293625.91      7096134.96      2293621.97      7096104.60
      2293630.97      7096055.16      2293736.77      7096001.78
      2293780.40      7095963.38      2293879.00      7095960.00

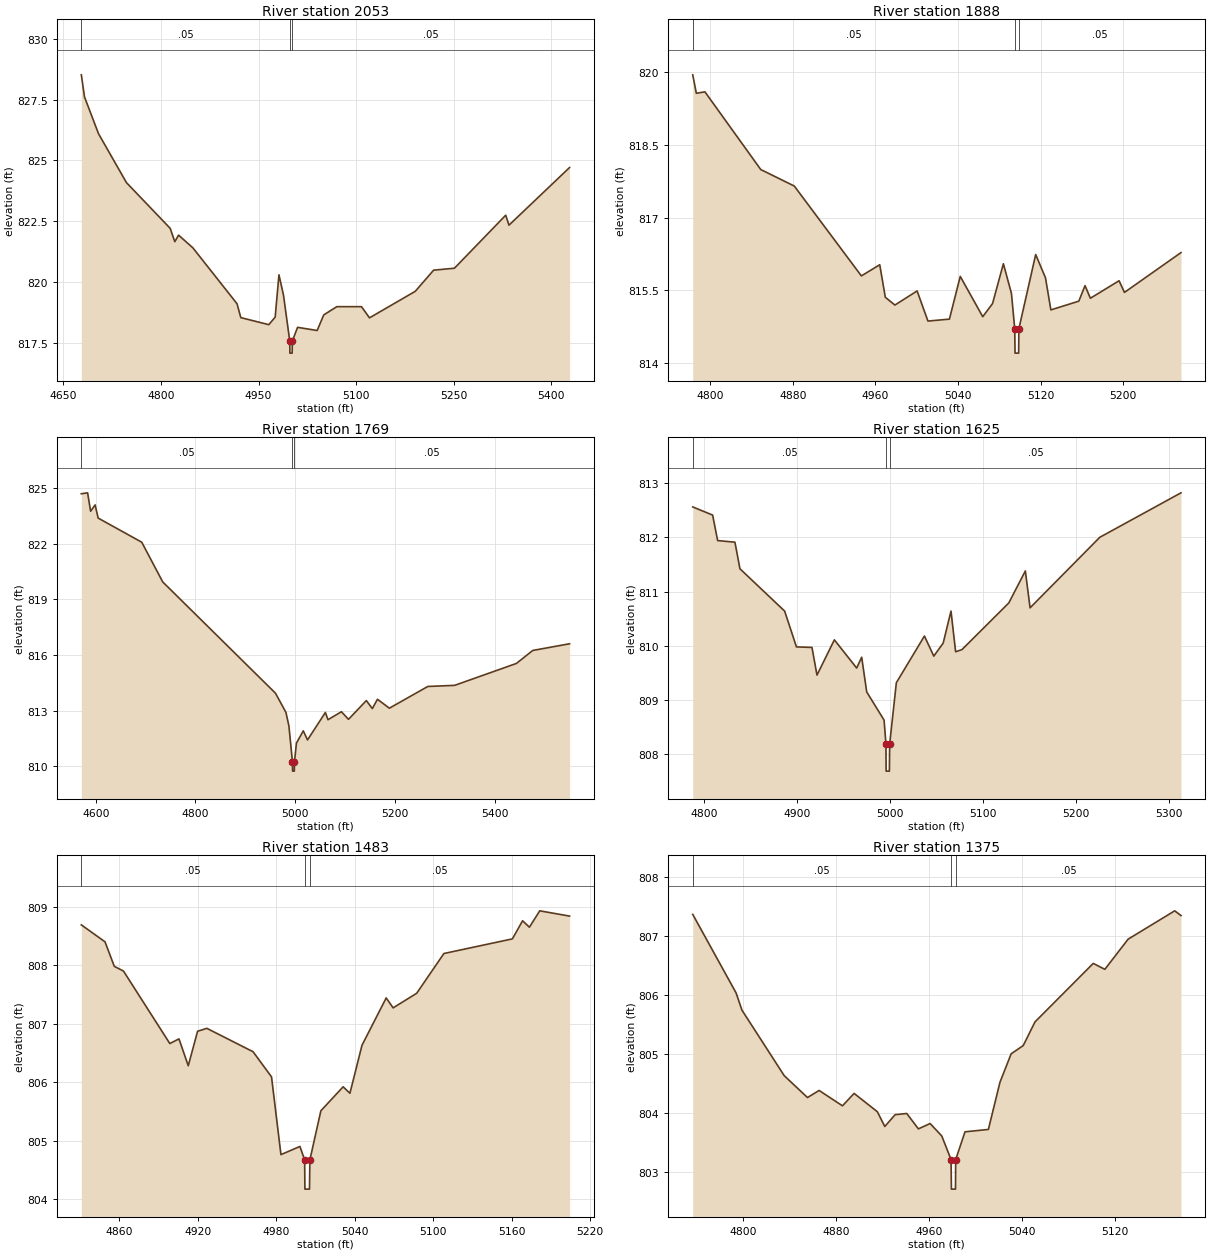
Type RM Length L Ch R = 1,2053,165,165,165
BEGIN DESCRIPTION:
MDW T 038 5.0
END DESCRIPTION:
XS GIS Cut Line= 3
      2292856.64      7097348.46      2292578.98      7097184.99
      2292152.82      7097146.48
#Sta/Elev= 30
  4677.8  828.52  4682.7  827.61  4704.2  826.10  4747.1  824.09  4814.3  822.21
  4821.4  821.66  4827.2  821.93  4849.1  821.41  4917.0  819.11  4922.8  818.54
  4965.8  818.25  4975.6  818.56  4981.4  820.30  4988.4  819.46  4998.0  817.58
  4998.2  817.08  5001.7  817.08  5002.0  817.58  5010.0  818.14  5040.1  818.01
  5050.2  818.65  5070.3  818.99  5108.2  818.99  5120.5  818.53  5190.8  819.62
  5219.0  820.49  5251.0  820.57  5329.8  822.75  5334.8  822.34  5427.9  824.71
#Mann=3,-1,0
  4677.8    0.05       0  4998.0    0.04       0  5002.0    0.05       0
Bank Sta=4998,5002
Exp/Cntr=0.3,0.1

Type RM Length L Ch R = 1,1888,119,119,119
BEGIN DESCRIPTION:
Mapping XS f2732f8c
END DESCRIPTION:
XS GIS Cut Line= 3
      2292849.86      7097125.26      2292653.98      7097043.62
      2292404.18      7096968.38
#Sta/Elev= 30
  4783.0  819.94  4786.5  819.56  4794.8  819.59  4848.9  817.99  4881.4  817.65
  4946.4  815.80  4964.2  816.03  4969.6  815.36  4978.9  815.20  5000.4  815.49
  5010.9  814.87  5031.7  814.91  5042.2  815.79  5064.0  814.96  5073.5  815.23
  5084.0  816.05  5091.8  815.44  5095.0  814.71  5095.3  814.21  5098.8  814.21
  5099.0  814.71  5115.3  816.24  5124.8  815.76  5130.0  815.10  5157.1  815.28
  5163.1  815.60  5168.3  815.34  5196.1  815.70  5201.3  815.46  5256.1  816.28
#Mann=3,-1,0
  4783.0    0.05       0  5095.0   0.033       0  5099.0    0.05       0
Bank Sta=5095,5099
Exp/Cntr=0.3,0.1

Type RM Length L Ch R = 1,1769,144,144,144
BEGIN DESCRIPTION:
MDW T 038 4.0
END DESCRIPTION:
XS GIS Cut Line= 3
      2293074.50      7097181.99      2292702.01      7096936.53
      2292185.62      7096806.12
#Sta/Elev= 30
  4571.2  824.69  4583.8  824.74  4589.8  823.75  4598.9  824.09  4604.9  823.38
  4692.3  822.08  4734.4  819.94  4960.3  813.95  4981.4  812.91  4987.3  812.18
  4994.4  810.25  4994.7  809.75  4998.2  809.75  4998.4  810.25  5002.4  811.26
  5016.1  811.92  5024.6  811.43  5060.4  812.91  5065.6  812.52  5092.6  812.95
  5106.7  812.54  5142.5  813.55  5154.5  813.12  5164.8  813.62  5188.7  813.14
  5265.7  814.31  5319.5  814.37  5443.3  815.55  5476.1  816.25  5549.9  816.61
#Mann=3,-1,0
  4571.2    0.05       0  4994.4   0.033       0  4998.4    0.05       0
Bank Sta=4994.4,4998.4
Exp/Cntr=0.3,0.1

Type RM Length L Ch R = 1,1625,142,142,142
BEGIN DESCRIPTION:
Mapping XS a4c707c9
END DESCRIPTION:
XS GIS Cut Line= 3
      2292932.36      7096883.66      2292736.52      7096803.78
      2292425.13      7096764.27
#Sta/Elev= 30
  4787.4  812.56  4808.8  812.41  4814.2  811.94  4832.8  811.91  4838.2  811.42
  4886.3  810.64  4899.0  809.98  4915.7  809.97  4921.1  809.46  4939.8  810.11
  4963.8  809.59  4969.2  809.79  4974.6  809.15  4993.3  808.63  4995.3  808.19
  4995.5  807.69  4999.0  807.69  4999.3  808.19  5006.5  809.32  5036.7  810.18
  5046.8  809.81  5056.9  810.05  5065.3  810.64  5070.3  809.89  5077.1  809.93
  5127.5  810.79  5145.3  811.38  5150.4  810.70  5225.4  812.00  5312.8  812.82
#Mann=3,-1,0
  4787.4    0.05       0  4995.3    0.04       0  4999.3    0.05       0
Bank Sta=4995.3,4999.3
Exp/Cntr=0.3,0.1

Type RM Length L Ch R = 1,1483,108,108,108
BEGIN DESCRIPTION:
Mapping XS 1a9b25de
END DESCRIPTION:
XS GIS Cut Line= 3
      2292912.90      7096791.69      2292798.99      7096676.28
      2292597.13      7096615.38
#Sta/Elev= 30
  4831.2  808.69  4849.3  808.40  4856.4  807.98  4863.4  807.90  4898.8  806.66
  4905.8  806.74  4912.9  806.28  4920.0  806.87  4927.1  806.92  4962.4  806.52
  4976.5  806.09  4983.7  804.76  4998.2  804.90  5001.8  804.67  5002.0  804.17
  5005.5  804.17  5005.8  804.67  5014.2  805.51  5031.2  805.92  5036.4  805.81
  5045.6  806.63  5064.1  807.44  5069.4  807.27  5087.4  807.52  5108.2  808.20
  5160.5  808.45  5168.3  808.76  5173.5  808.65  5181.4  808.93  5204.2  808.84
#Mann=3,-1,0
  4831.2    0.05       0  5001.8    0.04       0  5005.8    0.05       0
Bank Sta=5001.8,5005.8
Exp/Cntr=0.3,0.1

Type RM Length L Ch R = 1,1375,143,143,143
BEGIN DESCRIPTION:
Mapping XS 50ea701c
END DESCRIPTION:
XS GIS Cut Line= 3
      2292926.46      7096748.53      2292916.48      7096582.23
      2292663.61      7096565.85
#Sta/Elev= 30
  4756.5  807.36  4793.8  806.03  4798.8  805.74  4835.2  804.63  4855.2  804.26
  4865.2  804.38  4885.3  804.12  4895.3  804.33  4915.3  804.02  4921.7  803.77
  4930.6  803.97  4940.6  803.99  4950.6  803.73  4960.7  803.82  4970.7  803.61
  4978.7  803.21  4979.0  802.71  4982.5  802.71  4982.7  803.21  4990.7  803.68
  5010.8  803.72  5020.8  804.52  5030.4  805.00  5040.8  805.14  5050.9  805.54
  5101.0  806.53  5111.0  806.43  5131.0  806.94  5171.1  807.42  5176.5  807.34
#Mann=3,-1,0
  4756.5    0.05       0  4978.7    0.04       0  4982.7    0.05       0
Bank Sta=4978.7,4982.7
Exp/Cntr=0.3,0.1

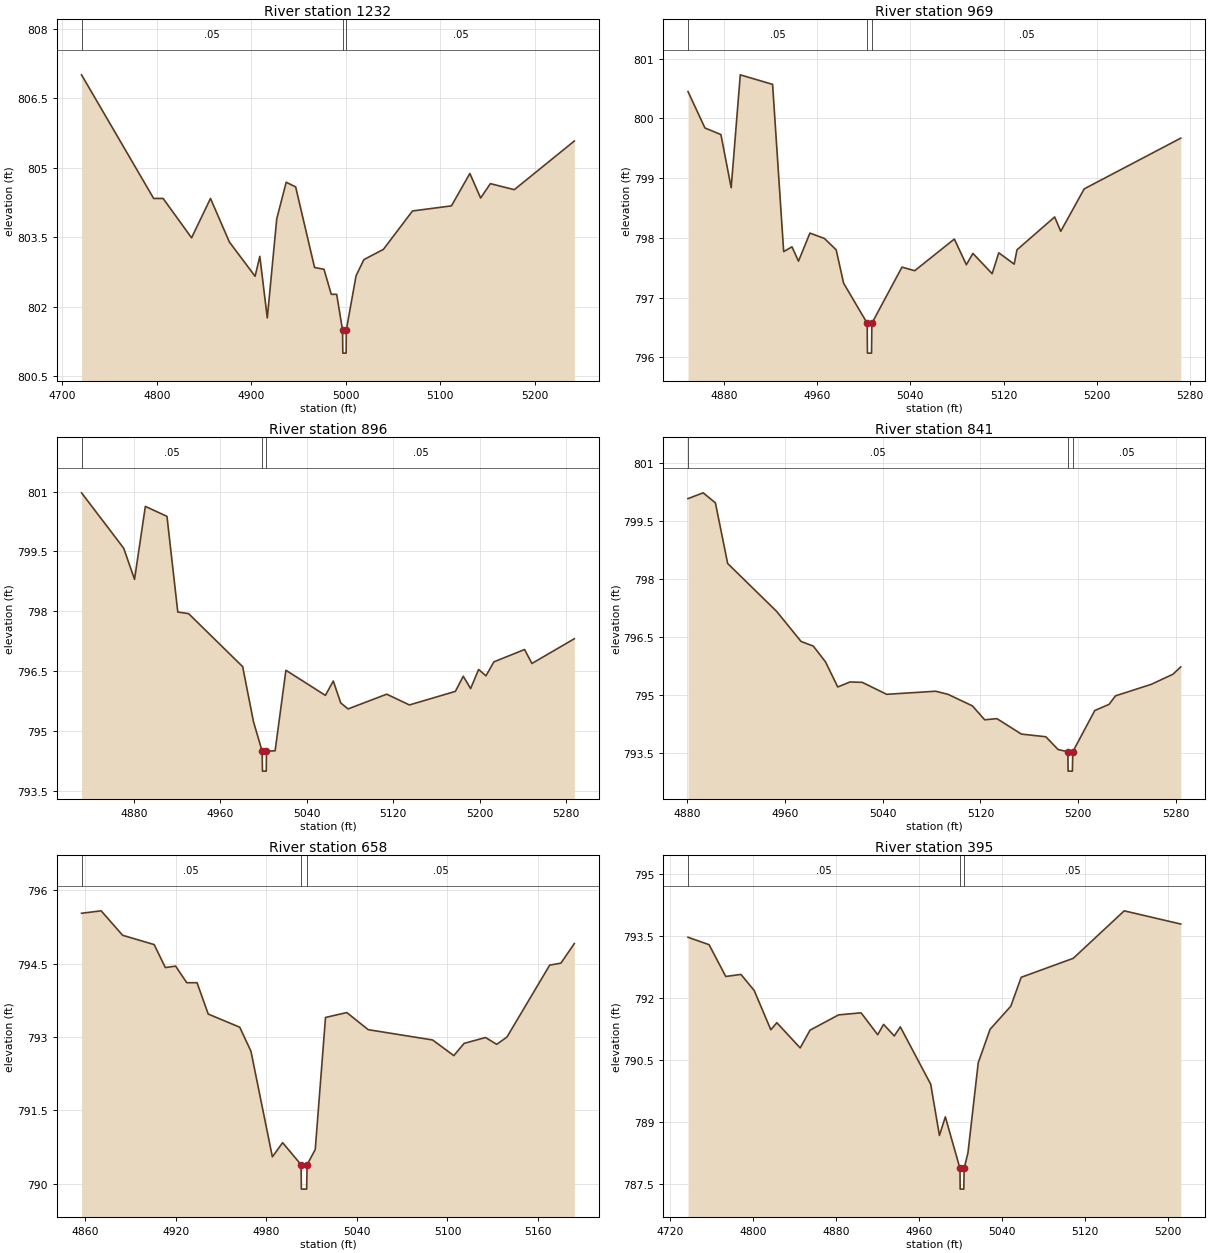
Type RM Length L Ch R = 1,1232,263,263,263
BEGIN DESCRIPTION:
Mapping XS a9206d1f
END DESCRIPTION:
XS GIS Cut Line= 3
      2292953.09      7096736.24      2292940.04      7096469.79
      2292692.64      7096409.98
#Sta/Elev= 30
  4720.5  807.01  4796.8  804.34  4806.8  804.34  4836.9  803.49  4856.9  804.34
  4876.9  803.40  4904.1  802.66  4909.1  803.09  4917.0  801.76  4927.0  803.90
  4937.0  804.69  4947.0  804.59  4967.0  802.85  4977.0  802.81  4984.7  802.27
  4990.4  802.27  4996.6  801.50  4996.9  801.00  5000.4  801.00  5000.6  801.50
  5010.9  802.67  5019.2  803.02  5039.8  803.24  5070.6  804.07  5111.8  804.18
  5131.3  804.88  5142.7  804.35  5153.0  804.66  5178.3  804.53  5241.8  805.58
#Mann=3,-1,0
  4720.5    0.05       0  4996.6    0.04       0  5000.6    0.05       0
Bank Sta=4996.6,5000.6
Exp/Cntr=0.3,0.1

Type RM Length L Ch R = 1,969,73,73,73
BEGIN DESCRIPTION:
Mapping XS 3f6cbc95
END DESCRIPTION:
XS GIS Cut Line= 3
      2293245.49      7096572.88      2293118.45      7096326.48
      2292980.06      7096282.60
#Sta/Elev= 30
  4849.4  800.45  4863.9  799.84  4877.6  799.73  4886.4  798.84  4894.2  800.73
  4921.9  800.57  4931.4  797.77  4938.5  797.85  4944.1  797.61  4953.9  798.08
  4966.3  797.99  4976.4  797.80  4982.8  797.24  5003.0  796.57  5003.2  796.07
  5006.7  796.07  5007.0  796.57  5032.8  797.51  5043.7  797.45  5077.7  797.98
  5088.0  797.55  5093.6  797.74  5110.1  797.40  5115.8  797.75  5129.0  797.56
  5131.4  797.80  5163.7  798.35  5168.9  798.11  5189.0  798.82  5271.8  799.67
#Mann=3,-1,0
  4849.4    0.05       0  5003.0    0.04       0  5007.0    0.05       0
Bank Sta=5003,5007
Exp/Cntr=0.3,0.1

Type RM Length L Ch R = 1,896,55,55,55
BEGIN DESCRIPTION:
Mapping XS aed50d55
END DESCRIPTION:
XS GIS Cut Line= 3
      2293247.74      7096589.04      2293246.89      7096366.99
      2293075.93      7096207.72
#Sta/Elev= 30
  4831.7  800.97  4870.7  799.58  4880.7  798.80  4890.7  800.63  4910.7  800.38
  4920.7  797.98  4930.7  797.94  4980.7  796.61  4990.7  795.23  4998.7  794.49
  4999.0  793.99  5002.5  793.99  5002.7  794.49  5010.7  794.50  5020.7  796.52
  5057.2  795.89  5064.5  796.25  5071.4  795.70  5078.2  795.55  5113.9  795.92
  5134.9  795.65  5177.4  795.99  5184.7  796.37  5191.5  796.06  5198.9  796.54
  5205.7  796.38  5213.0  796.73  5241.4  797.04  5248.2  796.69  5287.4  797.31
#Mann=3,-1,0
  4831.7    0.05       0  4998.7   0.033       0  5002.7    0.05       0
Bank Sta=4998.7,5002.7
Exp/Cntr=0.3,0.1

Type RM Length L Ch R = 1,841,183,183,183
BEGIN DESCRIPTION:
Mapping XS 64e71835
END DESCRIPTION:
XS GIS Cut Line= 4
      2293303.04      7096532.42      2293299.85      7096339.86
      2293296.59      7096188.29      2293274.41      7096134.04
#Sta/Elev= 30
  4881.0  800.09  4893.4  800.24  4903.4  799.98  4913.4  798.41  4953.4  797.17
  4973.4  796.39  4983.4  796.27  4993.4  795.86  5003.4  795.21  5013.4  795.34
  5023.4  795.33  5043.4  795.02  5083.4  795.10  5093.5  795.02  5113.5  794.72
  5123.5  794.36  5133.5  794.39  5153.5  793.99  5173.5  793.92  5183.5  793.59
  5191.5  793.53  5191.7  793.03  5195.2  793.03  5195.5  793.53  5213.5  794.60
  5225.2  794.76  5230.4  794.98  5259.8  795.28  5277.4  795.54  5283.8  795.73
#Mann=3,-1,0
  4881.0    0.05       0  5191.5    0.04       0  5195.5    0.05       0
Bank Sta=5191.5,5195.5
Exp/Cntr=0.3,0.1

Type RM Length L Ch R = 1,658,263,263,263
BEGIN DESCRIPTION:
Mapping XS cfea01f9
END DESCRIPTION:
XS GIS Cut Line= 2
      2293532.67      7096414.67      2293311.71      7096174.43
#Sta/Elev= 30
  4857.6  795.53  4870.6  795.58  4884.8  795.08  4905.7  794.89  4913.1  794.42
  4919.9  794.45  4927.3  794.11  4934.1  794.11  4941.5  793.47  4962.4  793.20
  4969.8  792.71  4984.0  790.55  4990.8  790.84  5003.0  790.39  5003.2  789.89
  5006.7  789.89  5007.0  790.39  5012.4  790.70  5019.2  793.40  5033.3  793.50
  5047.5  793.15  5090.1  792.94  5104.2  792.62  5111.0  792.87  5125.2  792.99
  5132.6  792.85  5139.4  793.00  5167.7  794.47  5175.1  794.51  5184.0  794.91
#Mann=3,-1,0
  4857.6    0.05       0  5003.0    0.04       0  5007.0    0.05       0
Bank Sta=5003,5007
Exp/Cntr=0.3,0.1

Type RM Length L Ch R = 1,395,123,123,123
BEGIN DESCRIPTION:
Mapping XS 5470caab
END DESCRIPTION:
XS GIS Cut Line= 3
      2293722.88      7096384.55      2293584.14      7096134.56
      2293395.60      7096121.51
#Sta/Elev= 30
  4737.2  793.47  4757.5  793.29  4773.6  792.52  4788.2  792.57  4801.0  792.18
  4817.0  791.23  4822.8  791.40  4845.3  790.79  4854.8  791.22  4882.3  791.59
  4904.0  791.64  4920.0  791.11  4925.7  791.36  4936.0  791.08  4941.8  791.30
  4971.1  789.91  4979.5  788.67  4985.2  789.12  4999.3  787.87  4999.5  787.37
  5003.0  787.37  5003.3  787.87  5007.0  788.25  5016.9  790.43  5028.3  791.24
  5048.3  791.80  5058.3  792.50  5108.5  792.96  5157.6  794.11  5212.1  793.79
#Mann=3,-1,0
  4737.2    0.05       0  4999.3    0.04       0  5003.3    0.05       0
Bank Sta=4999.3,5003.3
Exp/Cntr=0.3,0.1

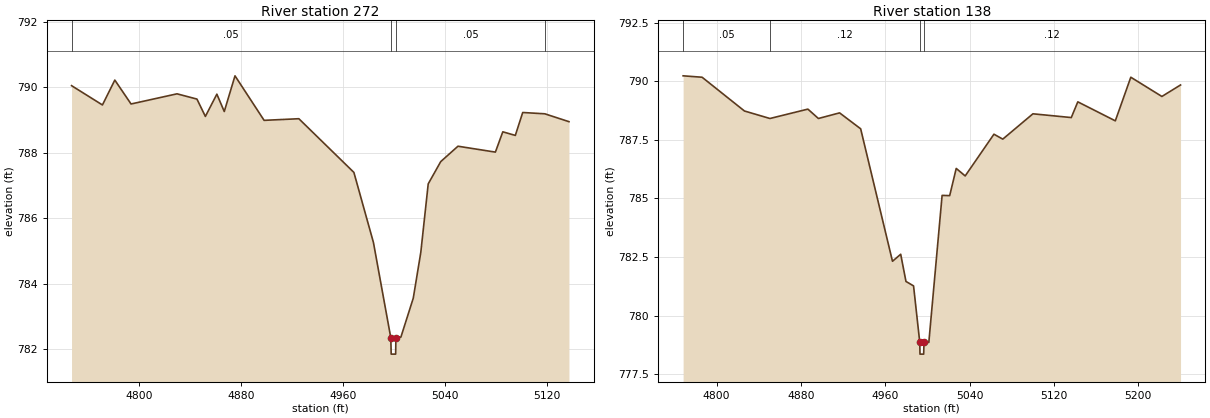
Type RM Length L Ch R = 1,272,134,134,134
BEGIN DESCRIPTION:
Mapping XS 0d1901c1
END DESCRIPTION:
XS GIS Cut Line= 2
      2293763.83      7096270.03      2293564.64      7095935.31
#Sta/Elev= 30
  4747.4  790.05  4771.6  789.46  4781.3  790.22  4794.0  789.49  4830.0  789.80
  4845.6  789.64  4852.2  789.11  4861.2  789.79  4867.0  789.26  4875.4  790.35
  4898.2  788.99  4925.4  789.04  4968.5  787.40  4983.8  785.26  4997.4  782.35
  4997.7  781.85  5001.2  781.85  5001.4  782.35  5005.3  782.37  5015.0  783.56
  5020.9  784.96  5026.7  787.05  5036.5  787.73  5050.0  788.20  5079.3  788.02
  5085.1  788.64  5094.9  788.53  5100.7  789.23  5118.0  789.19  5136.9  788.95
#Mann=4,-1,0
  4747.4    0.05       0  4997.4   0.033       0  5001.4    0.05       0
  5118.0    0.12       0
Bank Sta=4997.4,5001.4
Exp/Cntr=0.3,0.1

Type RM Length L Ch R = 1,138,0,0,0
BEGIN DESCRIPTION:
MDW T 038 1.0
END DESCRIPTION:
XS GIS Cut Line= 3
      2293771.54      7096217.96      2293752.32      7095989.32
      2293555.10      7095847.94
#Sta/Elev= 30
  4768.2  790.23  4786.2  790.17  4826.4  788.73  4850.6  788.41  4886.6  788.81
  4896.6  788.41  4916.7  788.65  4936.7  787.97  4966.9  782.32  4974.7  782.62
  4979.7  781.46  4986.9  781.27  4992.8  778.86  4993.0  778.36  4996.5  778.36
  4996.8  778.86  5001.4  778.86  5014.0  785.13  5021.2  785.12  5027.4  786.28
  5035.9  785.96  5063.2  787.74  5071.6  787.53  5100.2  788.61  5136.6  788.45
  5142.8  789.12  5178.4  788.31  5193.1  790.17  5222.6  789.35  5240.3  789.84
#Mann=4,-1,0
  4768.2    0.05       0  4850.6    0.12       0  4992.8    0.07       0
  4996.8    0.12       0
Bank Sta=4992.8,4996.8
Exp/Cntr=0.3,0.1

Chan Stop Cuts=-1