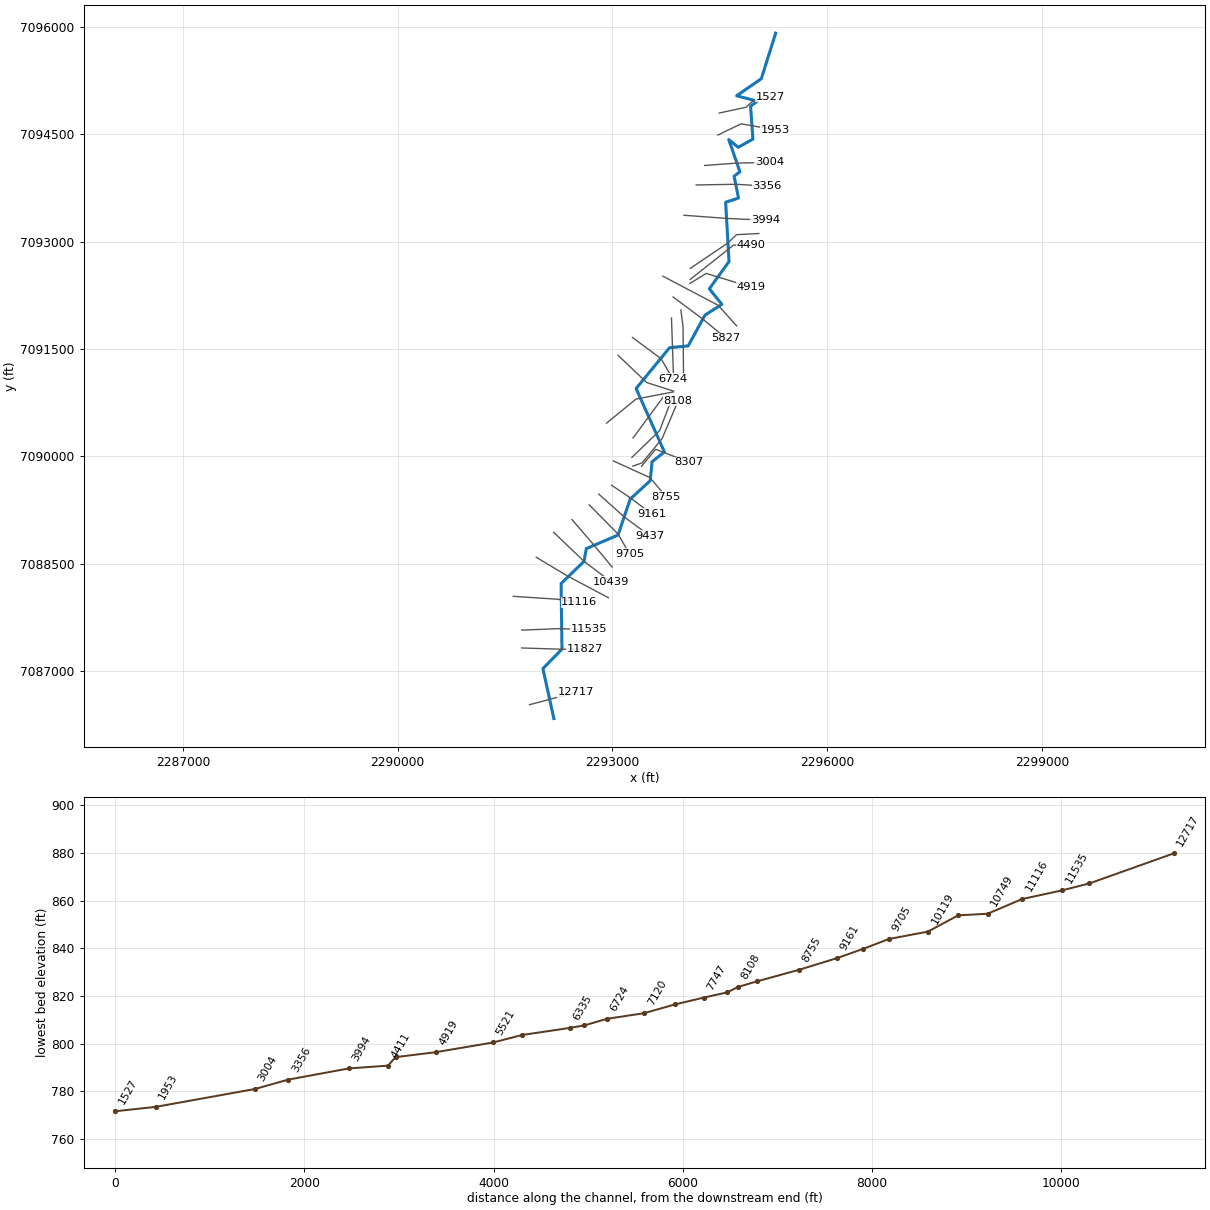
--- MDW T 039.prj (project) ---

Proj Title=MDW T 039 Base Level Engineering
Current Plan=p01
Default Exp/Contr=0.3,0.1
English Units
Geom File=g01
Flow File=f01
Plan File=p01
BEGIN DESCRIPTION:
MDW T 039
END DESCRIPTION:

--- MDW T 039.p01 (plan) ---

Plan Title=Multiple Run
Short Identifier=Multiple
Geom File=g01
Flow File=f01
Subcritical Flow
K Sum by GR= 0
Std Step Tol= 0.01
Critical Tol= 0.01
Num of Std Step Trials= 20
Max Error Tol= 0.3
Flow Tol Ratio= 0.001
Split Flow NTrial= 30
Split Flow Tol= 0.02
Split Flow Ratio= 0.02
Log Output Level= 0
Friction Slope Method= 1
Unsteady Friction Slope Method= 2
Unsteady Bridges Friction Slope Method= 1
Parabolic Critical Depth
Global Vel Dist=  1 , 1 , 1
Global Log Level= 0
CheckData=True
Encroach Param= -1, 0, 0, 0
BEGIN DESCRIPTION:
Multiple Run
END DESCRIPTION:

--- MDW T 039.f01 (steady flow) ---

Flow Title=Multiple
Number of Profiles=7
Profile Names=10-year,25-year,50-year,1pct_min,100-year,1pct_plu,500-year
River Rch & RM= MDW T 039,Reach-1,12717
     335     443     530     316     630    1257     890
River Rch & RM= MDW T 039,Reach-1,11827
     783    1095    1359     837    1670    3332    2528
River Rch & RM= MDW T 039,Reach-1,8307
     795    1113    1382     851    1699    3389    2574
River Rch & RM= MDW T 039,Reach-1,7120
    1206    1727    2176    1359    2711    5409    4223
River Rch & RM= MDW T 039,Reach-1,6335
    1401    2020    2557    1604    3200    6384    5025
River Rch & RM= MDW T 039,Reach-1,1527
    1508    2181    2766    1737    3467    6917    5463
River Rch & RM= MDW T 039,Reach-1,59
    2647    3911    5030    3197    6379   12728   10300
Boundary for River Rch & Prof#=MDW T 039,Reach-1,1
Up Type=0
Dn Type=3
Dn Slope=0.01
Boundary for River Rch & Prof#=MDW T 039,Reach-1,2
Up Type=0
Dn Type=3
Dn Slope=0.01
Boundary for River Rch & Prof#=MDW T 039,Reach-1,3
Up Type=0
Dn Type=3
Dn Slope=0.01
Boundary for River Rch & Prof#=MDW T 039,Reach-1,4
Up Type=0
Dn Type=3
Dn Slope=0.01
Boundary for River Rch & Prof#=MDW T 039,Reach-1,5
Up Type=0
Dn Type=3
Dn Slope=0.01
Boundary for River Rch & Prof#=MDW T 039,Reach-1,6
Up Type=0
Dn Type=3
Dn Slope=0.01
Boundary for River Rch & Prof#=MDW T 039,Reach-1,7
Up Type=0
Dn Type=3
Dn Slope=0.01

--- MDW T 039.g01 (geometry) ---

Geom Title=Existing Conditions

River Reach=MDW T 039,Reach-1
Reach XY= 30
      2292181.12      7086337.88      2292028.52      7087035.20
      2292294.87      7087307.31      2292282.12      7088223.62
      2292603.29      7088533.59      2292633.99      7088711.27
      2293077.17      7088900.43      2293247.54      7089403.05
      2293526.37      7089659.11      2293553.11      7089925.22
      2293725.56      7090061.25      2293330.04      7090947.07
      2293797.23      7091517.13      2294057.18      7091542.14
      2294292.62      7091973.21      2294528.00      7092121.74
      2294352.86      7092339.86      2294627.81      7092720.50
      2294580.39      7093548.42      2294760.32      7093607.43
      2294698.37      7093911.81      2294780.15      7093974.21
      2294623.71      7094424.55      2294756.30      7094315.94
      2294961.52      7094430.77      2294928.70      7094890.14
      2295022.09      7094960.04      2294734.06      7095035.70
      2295078.93      7095274.26      2295279.00      7095910.00

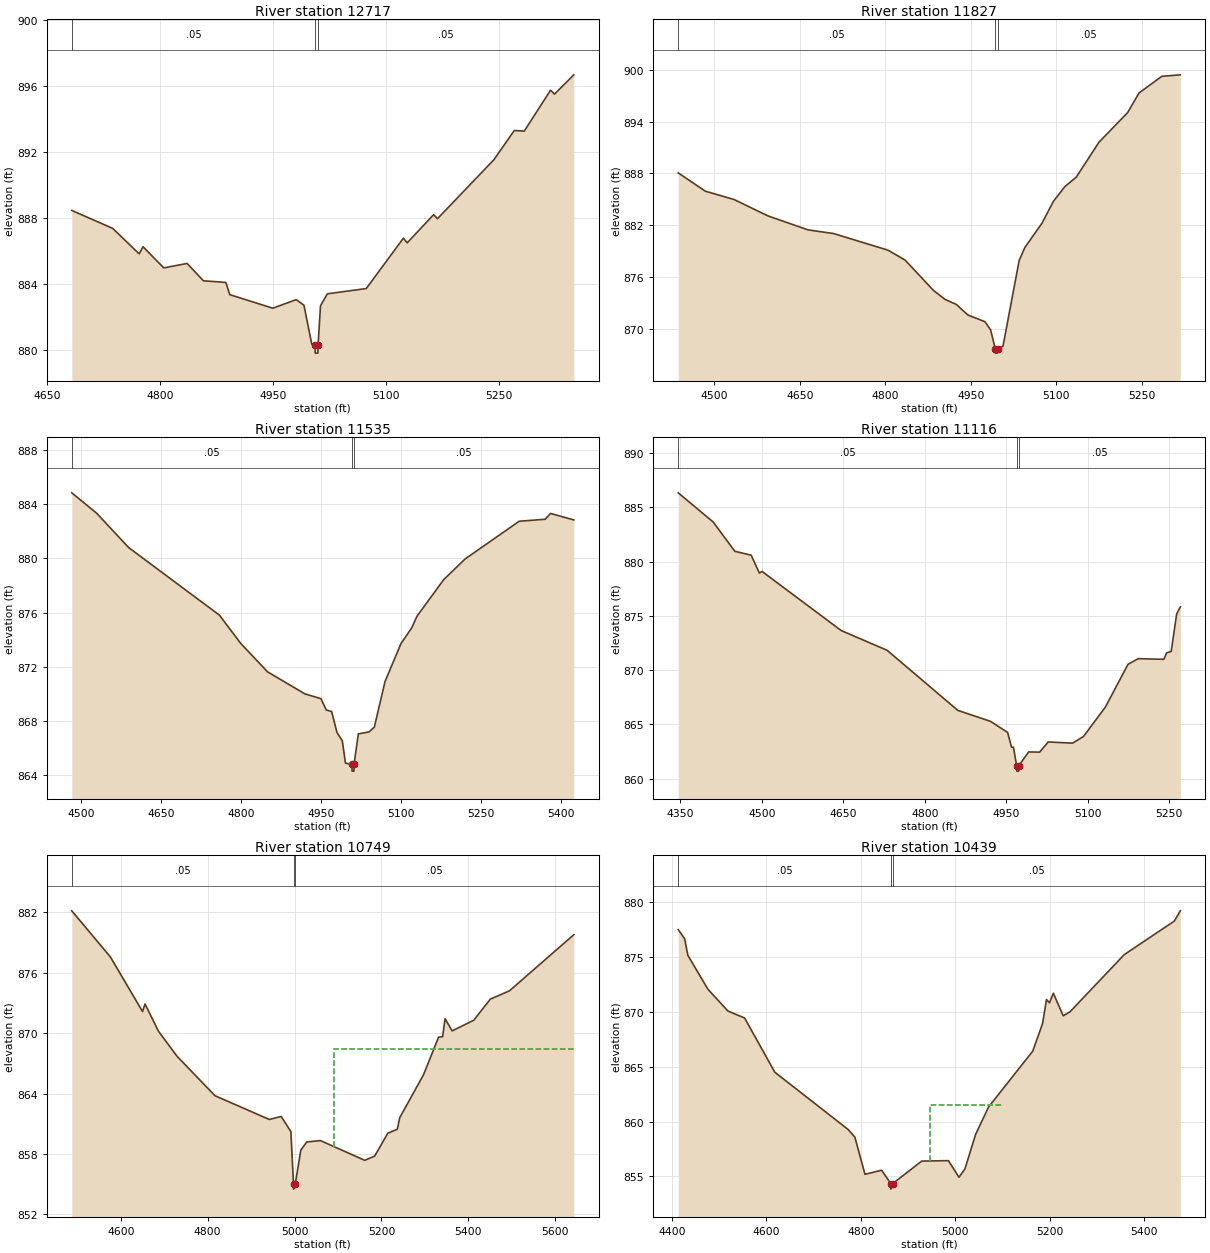
Type RM Length L Ch R = 1,12717,890,890,890
BEGIN DESCRIPTION:
MDW T 039 27.0
END DESCRIPTION:
XS GIS Cut Line= 2
      2291840.94      7086531.09      2292485.43      7086702.52
#Sta/Elev= 30
  4682.7  888.46  4737.2  887.37  4772.2  885.83  4777.4  886.26  4804.9  884.98
  4835.9  885.25  4857.6  884.20  4887.4  884.10  4892.6  883.36  4949.7  882.54
  4980.8  883.06  4991.1  882.72  5001.5  880.36  5005.9  880.32  5006.1  879.82
  5009.6  879.82  5009.9  880.32  5013.1  882.69  5022.2  883.41  5073.9  883.73
  5123.2  886.78  5128.3  886.50  5163.3  888.20  5168.5  887.96  5243.6  891.54
  5270.5  893.30  5283.7  893.26  5318.7  895.74  5323.9  895.50  5349.6  896.67
#Mann=3,-1,0
  4682.7    0.05       0  5005.9   0.033       0  5009.9    0.05       0
Bank Sta=5005.9,5009.9
Exp/Cntr=0.3,0.1

Type RM Length L Ch R = 1,11827,292,292,292
BEGIN DESCRIPTION:
MDW T 039 26.0
END DESCRIPTION:
XS GIS Cut Line= 3
      2291731.44      7087323.52      2292297.07      7087305.78
      2292611.44      7087309.42
#Sta/Elev= 30
  4437.0  888.07  4484.6  885.95  4534.6  885.00  4594.6  883.09  4664.7  881.48
  4709.3  881.06  4804.7  879.14  4834.8  877.99  4884.8  874.47  4904.8  873.45
  4924.8  872.86  4944.8  871.65  4974.8  870.87  4984.8  869.91  4992.8  867.74
  4993.1  867.24  4996.6  867.24  4996.8  867.74  5006.4  868.04  5034.8  877.95
  5044.8  879.45  5074.8  882.26  5094.8  884.78  5114.8  886.48  5134.8  887.57
  5174.8  891.62  5224.9  895.03  5244.9  897.30  5284.9  899.23  5317.3  899.40
#Mann=3,-1,0
  4437.0    0.05       0  4992.8   0.033       0  4996.8    0.05       0
Bank Sta=4992.8,4996.8
Exp/Cntr=0.3,0.1

Type RM Length L Ch R = 1,11535,419,419,419
BEGIN DESCRIPTION:
MDW T 039 25.0
END DESCRIPTION:
XS GIS Cut Line= 3
      2291732.52      7087572.66      2292245.87      7087593.44
      2292672.65      7087582.20
#Sta/Elev= 30
  4482.8  884.84  4529.3  883.34  4589.4  880.80  4759.5  875.81  4799.5  873.72
  4849.6  871.63  4919.6  870.00  4949.7  869.65  4959.7  868.81  4969.7  868.70
  4979.7  867.15  4989.7  866.54  4995.6  864.89  5007.7  864.80  5008.0  864.30
  5011.5  864.30  5011.7  864.80  5019.7  867.05  5039.7  867.19  5049.7  867.55
  5069.7  870.91  5099.7  873.72  5119.7  874.87  5129.7  875.74  5179.8  878.44
  5219.8  879.96  5321.0  882.74  5369.8  882.89  5379.8  883.32  5423.5  882.84
#Mann=3,-1,0
  4482.8    0.05       0  5007.7   0.033       0  5011.7    0.05       0
Bank Sta=5007.7,5011.7
Exp/Cntr=0.3,0.1

Type RM Length L Ch R = 1,11116,367,367,367
BEGIN DESCRIPTION:
MDW T 039 24.0
END DESCRIPTION:
XS GIS Cut Line= 3
      2291614.90      7088044.88      2292231.25      7088004.06
      2292535.61      7087960.98
#Sta/Elev= 30
  4345.9  886.35  4410.1  883.67  4450.2  880.96  4480.3  880.60  4495.4  878.95
  4500.4  879.10  4646.2  873.65  4730.8  871.83  4861.1  866.29  4921.3  865.28
  4952.8  864.26  4960.0  862.90  4963.6  862.90  4969.4  861.19  4969.7  860.69
  4973.2  860.69  4973.4  861.19  4991.6  862.46  5011.8  862.44  5027.6  863.38
  5072.4  863.27  5092.6  863.88  5133.0  866.60  5174.7  870.54  5193.6  871.06
  5240.7  871.00  5245.7  871.59  5254.2  871.73  5264.3  875.18  5271.0  875.83
#Mann=3,-1,0
  4345.9    0.05       0  4969.4   0.033       0  4973.4    0.05       0
Bank Sta=4969.4,4973.4
Exp/Cntr=0.3,0.1

Type RM Length L Ch R = 1,10749,310,310,310
BEGIN DESCRIPTION:
MDW T 039 23.0
END DESCRIPTION:
XS GIS Cut Line= 3
      2291936.04      7088589.60      2292377.98      7088325.71
      2292943.89      7088024.95
#Sta/Elev= 30
  4487.2  882.16  4576.1  877.58  4650.1  872.15  4655.9  872.90  4687.0  870.18
  4729.8  867.70  4816.8  863.79  4941.9  861.43  4969.2  861.73  4991.5  860.23
  4997.6  855.01  4997.9  854.51  5001.6  855.01  5014.4  858.39  5028.1  859.20
  5059.7  859.33  5161.6  857.37  5184.3  857.79  5214.6  860.06  5236.5  860.46
  5242.2  861.62  5296.8  865.87  5331.5  869.61  5340.8  869.66  5346.4  871.44
  5362.7  870.23  5412.4  871.29  5450.7  873.39  5494.6  874.21  5642.8  879.79
#Mann=3,-1,0
  4487.2    0.05       0  4997.6   0.033       0  5001.6    0.05       0
#XS Ineff=2,0
       0                 5091.10    0.00  868.44
Permanent Ineff=
       F       F
Bank Sta=4997.6,5001.6
Exp/Cntr=0.3,0.1

Type RM Length L Ch R = 1,10439,320,320,320
BEGIN DESCRIPTION:
MDW T 039 22.0
END DESCRIPTION:
XS GIS Cut Line= 3
      2292179.14      7088938.96      2292602.83      7088533.13
      2292983.14      7088246.71
#Sta/Elev= 30
  4413.3  877.46  4426.8  876.64  4433.7  875.12  4476.1  872.04  4518.6  870.05
  4553.8  869.42  4617.7  864.49  4773.1  859.27  4787.2  858.58  4808.6  855.20
  4843.8  855.57  4863.2  854.35  4863.4  853.85  4867.2  854.35  4928.7  856.40
  4985.3  856.44  5007.5  854.93  5020.2  855.69  5042.9  858.84  5070.3  861.33
  5163.7  866.40  5184.5  868.91  5192.8  871.10  5199.1  870.80  5207.4  871.67
  5228.2  869.62  5242.8  869.99  5357.3  875.18  5463.5  878.24  5476.1  879.17
#Mann=3,-1,0
  4413.3    0.05       0  4863.2   0.033       0  4867.2    0.05       0
#XS Ineff=1,-1
 4946.50 5100.00  861.50
Permanent Ineff=
       F
Bank Sta=4863.2,4867.2
Exp/Cntr=0.3,0.1

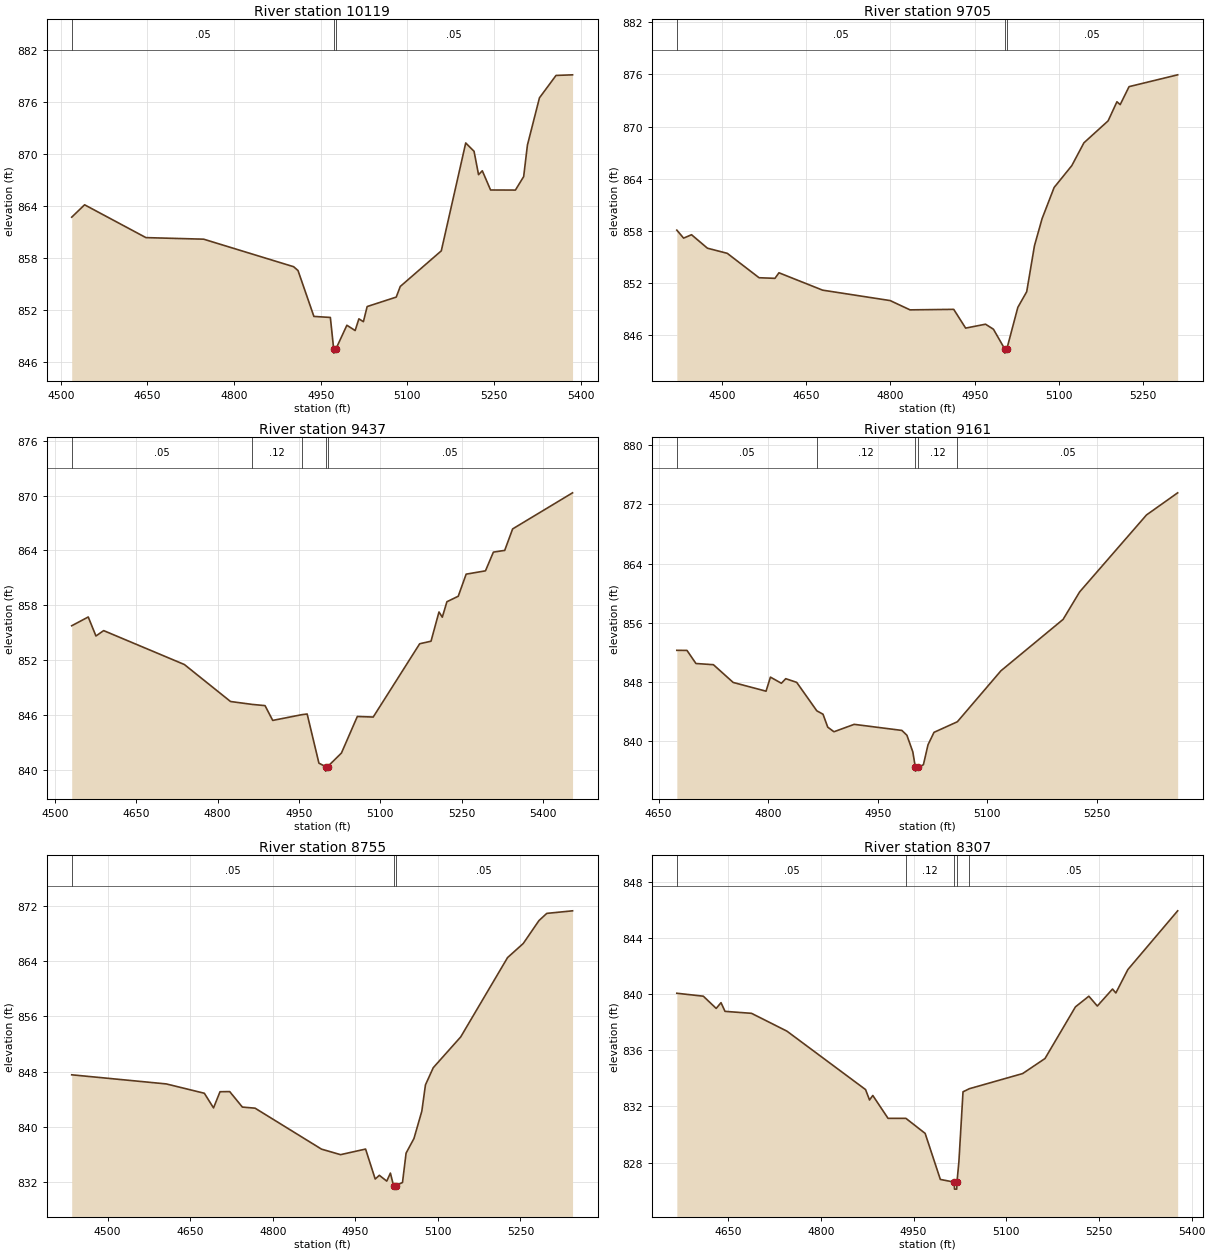
Type RM Length L Ch R = 1,10119,414,414,414
BEGIN DESCRIPTION:
MDW T 039 21.0
END DESCRIPTION:
XS GIS Cut Line= 3
      2292434.12      7089116.91      2292735.67      7088766.53
      2292994.08      7088455.17
#Sta/Elev= 30
  4519.0  862.73  4541.3  864.16  4647.5  860.37  4747.3  860.19  4903.1  857.01
  4910.7  856.57  4938.2  851.27  4966.7  851.15  4972.4  847.53  4972.7  847.03
  4976.4  847.53  4995.3  850.25  5009.6  849.64  5016.1  850.99  5023.9  850.66
  5030.4  852.41  5080.7  853.50  5087.7  854.73  5158.7  858.84  5201.0  871.30
  5215.4  870.34  5223.2  867.64  5229.7  868.09  5244.0  865.87  5287.0  865.86
  5301.3  867.42  5307.8  871.06  5328.6  876.51  5357.3  879.10  5385.9  879.17
#Mann=3,-1,0
  4519.0    0.05       0  4972.4   0.033       0  4976.4    0.05       0
Bank Sta=4972.4,4976.4
Exp/Cntr=0.3,0.1

Type RM Length L Ch R = 1,9705,268,268,268
BEGIN DESCRIPTION:
MDW T 039 20.0
END DESCRIPTION:
XS GIS Cut Line= 3
      2292675.01      7089323.07      2293076.94      7088915.68
      2293237.04      7088639.52
#Sta/Elev= 30
  4419.8  858.07  4431.9  857.15  4446.0  857.54  4474.3  855.99  4509.6  855.40
  4566.2  852.59  4594.5  852.52  4601.6  853.16  4679.3  851.16  4799.6  849.96
  4834.9  848.89  4912.7  848.95  4933.9  846.79  4969.3  847.24  4983.4  846.66
  5003.3  844.41  5003.6  843.91  5007.3  844.41  5026.8  849.18  5042.6  850.98
  5056.4  856.27  5069.9  859.38  5091.4  862.98  5122.9  865.50  5144.4  868.12
  5187.5  870.65  5203.2  872.85  5209.0  872.52  5224.8  874.59  5311.3  875.95
#Mann=3,-1,0
  4419.8    0.05       0  5003.3   0.033       0  5007.3    0.05       0
Bank Sta=5003.3,5007.3
Exp/Cntr=0.3,0.1

Type RM Length L Ch R = 1,9437,276,276,276
BEGIN DESCRIPTION:
MDW T 039 19.0
END DESCRIPTION:
XS GIS Cut Line= 3
      2292808.35      7089472.72      2293169.31      7089149.23
      2293523.47      7088889.99
#Sta/Elev= 30
  4530.9  855.75  4561.4  856.71  4575.6  854.63  4589.8  855.22  4738.6  851.51
  4823.8  847.46  4864.1  847.14  4887.4  847.01  4901.6  845.39  4955.4  846.02
  4965.1  846.09  4986.8  840.71  4999.0  840.34  4999.2  839.84  5003.0  840.34
  5028.3  841.82  5057.6  845.82  5086.9  845.76  5172.6  853.78  5193.5  854.06
  5208.2  857.26  5214.3  856.69  5222.8  858.38  5243.7  858.98  5258.3  861.40
  5293.9  861.76  5308.5  863.81  5329.4  864.00  5344.0  866.35  5454.5  870.30
#Mann=5,-1,0
  4530.9    0.05       0  4864.1    0.12       0  4955.4    0.05       0
  4999.0   0.033       0  5003.0    0.05       0
Bank Sta=4999,5003
Exp/Cntr=0.3,0.1

Type RM Length L Ch R = 1,9161,406,406,406
BEGIN DESCRIPTION:
MDW T 039 18.0
END DESCRIPTION:
XS GIS Cut Line= 3
      2292987.44      7089596.38      2293263.15      7089411.07
      2293543.99      7089196.05
#Sta/Elev= 30
  4675.0  852.27  4688.9  852.26  4701.2  850.49  4725.1  850.33  4752.2  847.93
  4797.2  846.75  4803.2  848.65  4818.2  847.82  4824.2  848.44  4839.2  847.94
  4866.7  844.10  4875.2  843.64  4881.7  841.89  4890.2  841.27  4917.9  842.27
  4983.2  841.45  4990.1  840.80  4998.2  838.55  5001.7  836.45  5001.9  835.95
  5005.7  836.45  5012.7  836.82  5019.0  839.51  5027.2  841.19  5059.2  842.62
  5118.8  849.50  5204.0  856.45  5226.7  860.17  5318.2  870.56  5360.9  873.55
#Mann=5,-1,0
  4675.0    0.05       0  4866.7    0.12       0  5001.7    0.07       0
  5005.7    0.12       0  5059.2    0.05       0
Bank Sta=5001.7,5005.7
Exp/Cntr=0.3,0.1

Type RM Length L Ch R = 1,8755,448,448,448
BEGIN DESCRIPTION:
MDW T 039 17.0
END DESCRIPTION:
XS GIS Cut Line= 3
      2293014.53      7089934.94      2293521.19      7089703.81
      2293751.28      7089435.82
#Sta/Elev= 30
  4434.7  847.55  4606.6  846.23  4675.7  844.88  4692.4  842.76  4704.2  845.10
  4721.8  845.12  4744.8  842.88  4767.9  842.72  4888.6  836.79  4923.2  835.99
  4968.7  836.80  4986.2  832.46  4993.7  833.00  5007.2  832.16  5013.8  833.32
  5019.5  831.50  5019.7  831.00  5023.5  831.50  5035.8  831.96  5042.3  836.21
  5056.6  838.33  5070.9  842.28  5077.5  846.09  5091.7  848.58  5141.6  853.04
  5226.7  864.52  5255.2  866.56  5283.8  869.88  5298.0  870.92  5344.8  871.29
#Mann=3,-1,0
  4434.7    0.05       0  5019.5   0.033       0  5023.5    0.05       0
Bank Sta=5019.5,5023.5
Exp/Cntr=0.3,0.1

Type RM Length L Ch R = 1,8307,199,199,199
BEGIN DESCRIPTION:
Mapping XS b290c918
END DESCRIPTION:
XS GIS Cut Line= 3
      2293406.37      7089862.28      2293603.60      7090098.01
      2294073.14      7089917.50
#Sta/Elev= 30
  4567.0  840.06  4609.9  839.85  4630.7  838.98  4638.5  839.39  4645.0  838.77
  4687.9  838.63  4745.2  837.36  4872.4  833.20  4878.8  832.46  4884.1  832.78
  4908.8  831.15  4937.7  831.15  4968.8  830.08  4993.4  826.80  5015.8  826.61
  5016.3  826.11  5019.9  826.11  5020.3  826.61  5023.4  828.05  5030.1  833.04
  5040.2  833.26  5126.6  834.34  5162.7  835.41  5212.0  839.09  5233.7  839.85
  5247.4  839.15  5272.0  840.36  5277.4  840.08  5296.7  841.74  5377.4  845.93
#Mann=5,-1,0
  4567.0    0.05       0  4937.7    0.12       0  5015.8    0.07       0
  5020.3    0.12       0  5040.2    0.05       0
Bank Sta=5015.8,5020.3
Exp/Cntr=0.3,0.1

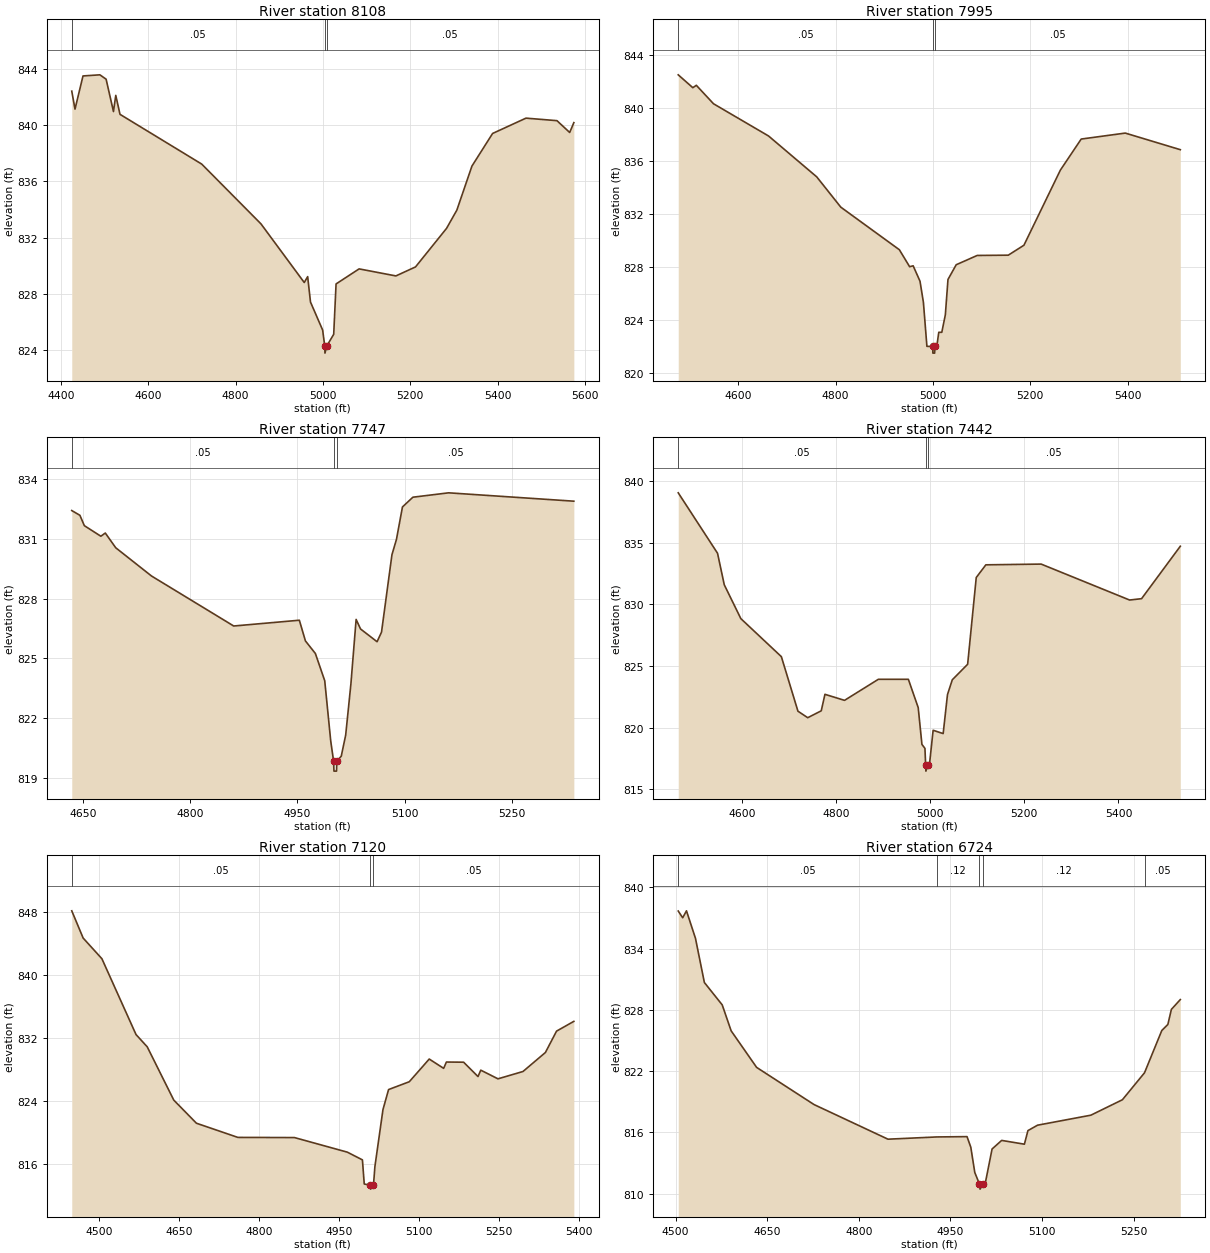
Type RM Length L Ch R = 1,8108,113,113,113
BEGIN DESCRIPTION:
MDW T 039 15.5
END DESCRIPTION:
XS GIS Cut Line= 4
      2293284.75      7089863.34      2293412.85      7089907.93
      2293692.84      7090246.90      2293917.31      7090774.77
#Sta/Elev= 30
  4425.3  842.41  4432.7  841.13  4451.0  843.49  4489.6  843.57  4503.9  843.26
  4520.7  840.96  4526.0  842.11  4535.7  840.76  4722.8  837.22  4858.3  832.97
  4957.3  828.80  4965.1  829.22  4971.6  827.41  4999.4  825.42  5004.2  824.28
  5004.7  823.78  5008.7  824.28  5024.7  825.12  5030.1  828.70  5082.8  829.77
  5167.0  829.27  5211.9  829.91  5282.9  832.65  5306.5  833.95  5341.0  837.08
  5388.3  839.40  5464.7  840.49  5535.6  840.31  5564.7  839.47  5574.2  840.17
#Mann=3,-1,0
  4425.3    0.05       0  5004.2   0.033       0  5008.7    0.05       0
Bank Sta=5004.2,5008.7
Exp/Cntr=0.3,0.1

Type RM Length L Ch R = 1,7995,248,248,248
BEGIN DESCRIPTION:
MDW T 039 15.0
END DESCRIPTION:
XS GIS Cut Line= 3
      2293271.68      7089984.84      2293658.78      7090359.59
      2293834.43      7090820.36
#Sta/Elev= 30
  4476.6  842.49  4506.6  841.52  4513.8  841.70  4549.1  840.31  4662.3  837.88
  4761.3  834.80  4810.7  832.52  4931.1  829.31  4952.2  828.03  4959.4  828.10
  4973.5  826.94  4980.5  825.35  4987.7  822.03  4999.5  822.02  5000.0  821.52
  5003.6  821.52  5004.0  822.02  5008.8  822.23  5012.1  823.09  5018.3  823.09
  5025.6  824.41  5031.0  827.07  5047.9  828.18  5091.1  828.88  5154.9  828.90
  5187.1  829.65  5262.0  835.31  5304.8  837.65  5395.4  838.10  5508.5  836.85
#Mann=3,-1,0
  4476.6    0.05       0  4999.5   0.033       0  5004.0    0.05       0
Bank Sta=4999.5,5004
Exp/Cntr=0.3,0.1

Type RM Length L Ch R = 1,7747,305,305,305
BEGIN DESCRIPTION:
Mapping XS 90c180a7
END DESCRIPTION:
XS GIS Cut Line= 2
      2293287.26      7090255.83      2293704.04      7090820.96
#Sta/Elev= 30
  4634.4  832.43  4645.8  832.19  4652.0  831.67  4675.1  831.14  4681.3  831.30
  4695.9  830.56  4746.0  829.14  4860.9  826.63  4952.7  826.92  4961.2  825.88
  4975.1  825.25  4988.2  823.88  4996.6  820.85  5000.6  819.84  5001.1  819.34
  5004.7  819.34  5005.1  819.84  5011.3  820.09  5017.5  821.15  5024.8  823.72
  5032.1  826.96  5038.3  826.48  5061.4  825.84  5067.6  826.32  5082.2  830.21
  5088.5  830.98  5096.9  832.61  5111.5  833.10  5161.5  833.32  5336.6  832.90
#Mann=3,-1,0
  4634.4    0.05       0  5000.6   0.033       0  5005.1    0.05       0
Bank Sta=5000.6,5005.1
Exp/Cntr=0.3,0.1

Type RM Length L Ch R = 1,7442,322,322,322
BEGIN DESCRIPTION:
MDW T 039 14.0
END DESCRIPTION:
XS GIS Cut Line= 3
      2292917.93      7090463.34      2293328.41      7090799.76
      2293854.73      7090900.51
#Sta/Elev= 30
  4464.8  839.07  4548.3  834.16  4562.6  831.60  4597.8  828.85  4683.9  825.76
  4719.1  821.33  4739.9  820.80  4768.6  821.36  4776.5  822.70  4818.1  822.21
  4889.9  823.92  4953.7  823.92  4974.6  821.62  4982.5  818.63  4988.9  818.31
  4990.4  816.96  4990.9  816.46  4994.9  816.96  4998.4  816.96  5006.3  819.78
  5027.6  819.51  5036.8  822.68  5047.0  823.88  5079.6  825.14  5097.9  832.19
  5118.3  833.22  5235.8  833.28  5423.7  830.36  5449.1  830.47  5531.4  834.73
#Mann=3,-1,0
  4464.8    0.05       0  4990.4   0.033       0  4994.9    0.05       0
Bank Sta=4990.4,4994.9
Exp/Cntr=0.3,0.1

Type RM Length L Ch R = 1,7120,396,396,396
BEGIN DESCRIPTION:
MDW T 039 13.0
END DESCRIPTION:
XS GIS Cut Line= 3
      2293078.97      7091410.03      2293478.79      7091030.25
      2293849.83      7090911.90
#Sta/Elev= 30
  4449.1  848.14  4470.4  844.69  4505.6  842.06  4569.5  832.45  4590.5  830.89
  4640.3  824.13  4682.7  821.20  4760.4  819.40  4866.4  819.38  4965.5  817.53
  4993.8  816.55  4997.2  813.49  5008.1  813.34  5009.1  812.84  5014.5  813.34
  5017.2  815.71  5032.3  822.93  5042.8  825.47  5081.6  826.46  5119.0  829.34
  5146.0  828.16  5151.2  828.96  5183.4  828.94  5210.4  827.12  5215.6  827.93
  5247.8  826.83  5294.7  827.76  5336.7  830.17  5357.6  832.88  5390.0  834.12
#Mann=3,-1,0
  4449.1    0.05       0  5008.1   0.033       0  5014.5    0.05       0
Bank Sta=5008.1,5014.5
Exp/Cntr=0.3,0.1

Type RM Length L Ch R = 1,6724,237,237,237
BEGIN DESCRIPTION:
MDW T 039 12.0
END DESCRIPTION:
XS GIS Cut Line= 3
      2293279.00      7091660.00      2293678.32      7091364.07
      2293842.00      7091083.55
#Sta/Elev= 30
  4504.4  837.67  4511.7  837.01  4517.9  837.69  4532.6  835.00  4547.2  830.67
  4576.4  828.48  4591.0  825.94  4632.7  822.36  4726.7  818.72  4847.7  815.33
  4927.9  815.55  4977.1  815.58  4983.3  814.54  4989.8  812.07  4997.4  810.94
  4998.4  810.44  5003.9  810.94  5006.7  810.94  5018.1  814.37  5033.8  815.21
  5071.0  814.84  5076.8  816.17  5092.5  816.70  5179.8  817.68  5231.4  819.19
  5267.6  821.83  5295.9  825.97  5305.8  826.56  5311.6  828.04  5326.2  829.00
#Mann=5,-1,0
  4504.4    0.05       0  4927.9    0.12       0  4997.4    0.07       0
  5003.9    0.12       0  5267.6    0.05       0
Bank Sta=4997.4,5003.9
Exp/Cntr=0.3,0.1

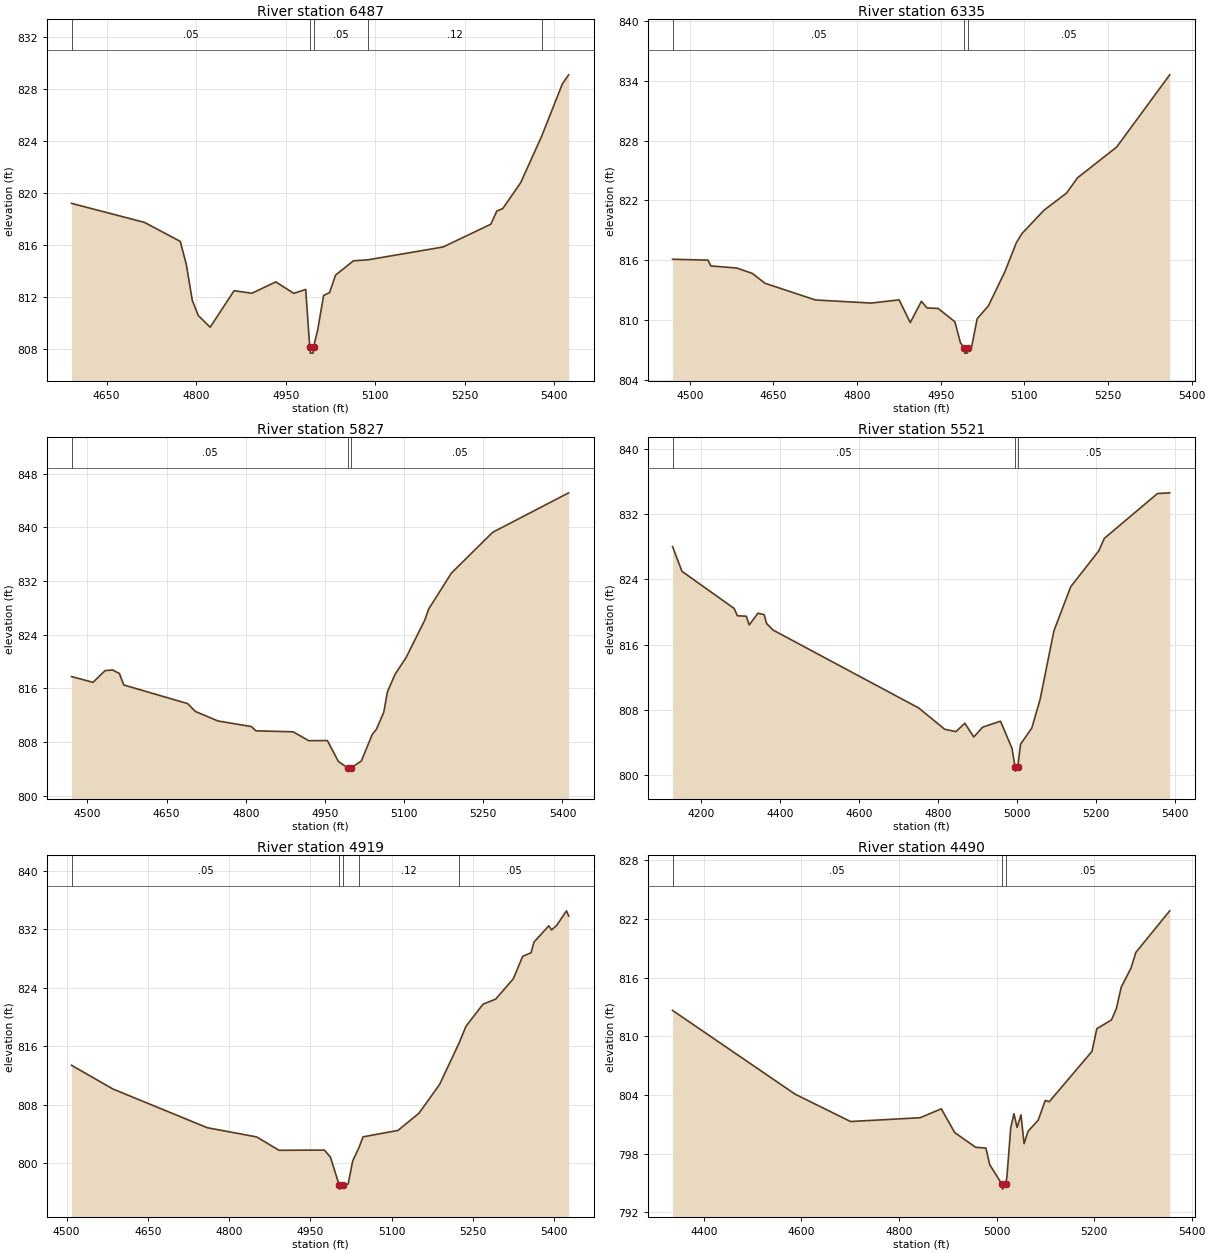
Type RM Length L Ch R = 1,6487,152,152,152
BEGIN DESCRIPTION:
Mapping XS 894a312d
END DESCRIPTION:
XS GIS Cut Line= 2
      2293824.01      7091932.14      2293852.83      7091099.63
#Sta/Elev= 30
  4591.1  819.20  4713.3  817.74  4773.3  816.28  4783.4  814.52  4793.4  811.77
  4803.4  810.59  4823.4  809.69  4863.4  812.49  4893.4  812.30  4933.4  813.17
  4963.5  812.29  4983.5  812.59  4990.2  808.20  4991.3  807.70  4995.7  807.70
  4996.7  808.20  5003.5  809.46  5013.5  812.13  5023.5  812.35  5033.5  813.69
  5063.5  814.79  5088.4  814.87  5213.6  815.85  5293.7  817.60  5303.7  818.61
  5313.7  818.80  5343.7  820.79  5379.1  824.38  5413.7  828.39  5424.1  829.07
#Mann=5,-1,0
  4591.1    0.05       0  4990.2   0.033       0  4996.7    0.05       0
  5088.4    0.12       0  5379.1    0.05       0
Bank Sta=4990.2,4996.7
Exp/Cntr=0.3,0.1

Type RM Length L Ch R = 1,6335,508,508,508
BEGIN DESCRIPTION:
Mapping XS 770edfaf
END DESCRIPTION:
XS GIS Cut Line= 3
      2293955.46      7092044.28      2293985.53      7091809.11
      2293992.15      7091154.83
#Sta/Elev= 30
  4469.3  816.09  4532.8  816.00  4537.9  815.42  4584.5  815.21  4612.6  814.66
  4634.9  813.68  4725.5  812.00  4825.5  811.69  4875.5  812.01  4895.5  809.73
  4915.5  811.87  4925.5  811.20  4945.5  811.15  4975.5  809.81  4985.5  807.70
  4992.2  807.16  4993.3  806.66  4997.7  806.66  4998.8  807.16  5005.5  807.28
  5015.5  810.12  5035.5  811.40  5065.5  814.88  5085.5  817.73  5095.5  818.66
  5135.5  821.03  5175.5  822.73  5195.5  824.28  5265.5  827.36  5360.7  834.62
#Mann=3,-1,0
  4469.3    0.05       0  4992.2   0.033       0  4998.8    0.05       0
Bank Sta=4992.2,4998.8
Exp/Cntr=0.3,0.1

Type RM Length L Ch R = 1,5827,306,306,306
BEGIN DESCRIPTION:
MDW T 039 10.0
END DESCRIPTION:
XS GIS Cut Line= 3
      2293846.74      7092225.88      2294272.91      7091907.78
      2294588.95      7091646.44
#Sta/Elev= 30
  4469.9  817.76  4510.6  816.90  4533.6  818.65  4547.6  818.74  4560.6  818.22
  4569.0  816.50  4689.9  813.73  4704.5  812.56  4747.2  811.14  4810.8  810.30
  4819.2  809.67  4890.0  809.52  4919.2  808.20  4954.7  808.22  4975.5  805.10
  4992.8  804.16  4993.9  803.66  4999.5  804.16  5018.9  805.16  5039.7  809.13
  5047.6  809.91  5061.5  812.44  5068.4  815.47  5082.7  818.07  5103.6  820.57
  5139.4  826.21  5146.6  827.83  5189.6  833.18  5267.7  839.26  5411.8  845.15
#Mann=3,-1,0
  4469.9    0.05       0  4992.8   0.033       0  4999.5    0.05       0
Bank Sta=4992.8,4999.5
Exp/Cntr=0.3,0.1

Type RM Length L Ch R = 1,5521,602,602,602
BEGIN DESCRIPTION:
MDW T 039 9.0
END DESCRIPTION:
XS GIS Cut Line= 3
      2293703.51      7092516.25      2294475.28      7092109.93
      2294734.36      7091821.37
#Sta/Elev= 30
  4127.8  828.00  4151.5  824.98  4283.7  820.44  4292.2  819.54  4314.8  819.48
  4322.1  818.42  4344.1  819.85  4360.0  819.68  4366.1  818.59  4382.5  817.79
  4751.5  808.26  4817.6  805.65  4846.0  805.36  4868.6  806.39  4891.2  804.71
  4913.8  805.91  4959.0  806.64  4988.2  803.30  4995.9  801.03  4997.0  800.53
  5002.6  801.03  5009.8  803.83  5038.2  805.79  5059.2  809.28  5094.3  817.69
  5136.9  823.09  5207.9  827.47  5222.1  829.01  5356.7  834.49  5387.8  834.58
#Mann=3,-1,0
  4127.8    0.05       0  4995.9   0.033       0  5002.6    0.05       0
Bank Sta=4995.9,5002.6
Exp/Cntr=0.3,0.1

Type RM Length L Ch R = 1,4919,429,429,429
BEGIN DESCRIPTION:
Mapping XS bebc612f
END DESCRIPTION:
XS GIS Cut Line= 3
      2294080.55      7092413.98      2294310.45      7092554.85
      2294930.28      7092364.60
#Sta/Elev= 30
  4509.1  813.42  4585.6  810.17  4759.7  804.88  4851.0  803.62  4892.3  801.79
  4976.0  801.82  4987.2  800.86  5003.6  796.98  5004.7  796.48  5011.1  796.98
  5019.9  797.18  5028.3  800.34  5039.9  802.16  5047.4  803.63  5111.9  804.51
  5150.8  806.87  5188.8  810.80  5224.6  816.44  5237.5  818.75  5268.9  821.77
  5292.2  822.46  5324.9  825.25  5342.1  828.31  5357.7  828.81  5363.0  830.26
  5390.4  832.49  5395.6  831.92  5404.8  832.54  5423.1  834.54  5427.1  833.83
#Mann=5,-1,0
  4509.1    0.05       0  5003.6   0.033       0  5011.1    0.05       0
  5039.9    0.12       0  5224.6    0.05       0
Bank Sta=5003.6,5011.1
Exp/Cntr=0.3,0.1

Type RM Length L Ch R = 1,4490,79,79,79
BEGIN DESCRIPTION:
Mapping XS cc96959e
END DESCRIPTION:
XS GIS Cut Line= 3
      2294085.50      7092470.35      2294688.92      7092948.27
      2294938.35      7092950.80
#Sta/Elev= 30
  4335.8  812.65  4587.0  804.09  4700.7  801.29  4843.4  801.68  4886.7  802.59
  4914.3  800.16  4957.1  798.66  4978.1  798.58  4986.0  796.88  5011.1  794.88
  5012.3  794.38  5018.6  794.88  5021.2  795.59  5029.1  800.66  5035.7  802.10
  5042.1  800.69  5050.1  801.97  5056.5  799.03  5064.5  800.29  5085.4  801.43
  5099.8  803.44  5108.1  803.32  5195.6  808.46  5205.6  810.78  5235.6  811.68
  5245.6  812.83  5255.6  815.03  5275.6  816.97  5285.6  818.58  5355.0  822.83
#Mann=3,-1,0
  4335.8    0.05       0  5011.1   0.033       0  5018.6    0.05       0
Bank Sta=5011.1,5018.6
Exp/Cntr=0.3,0.1

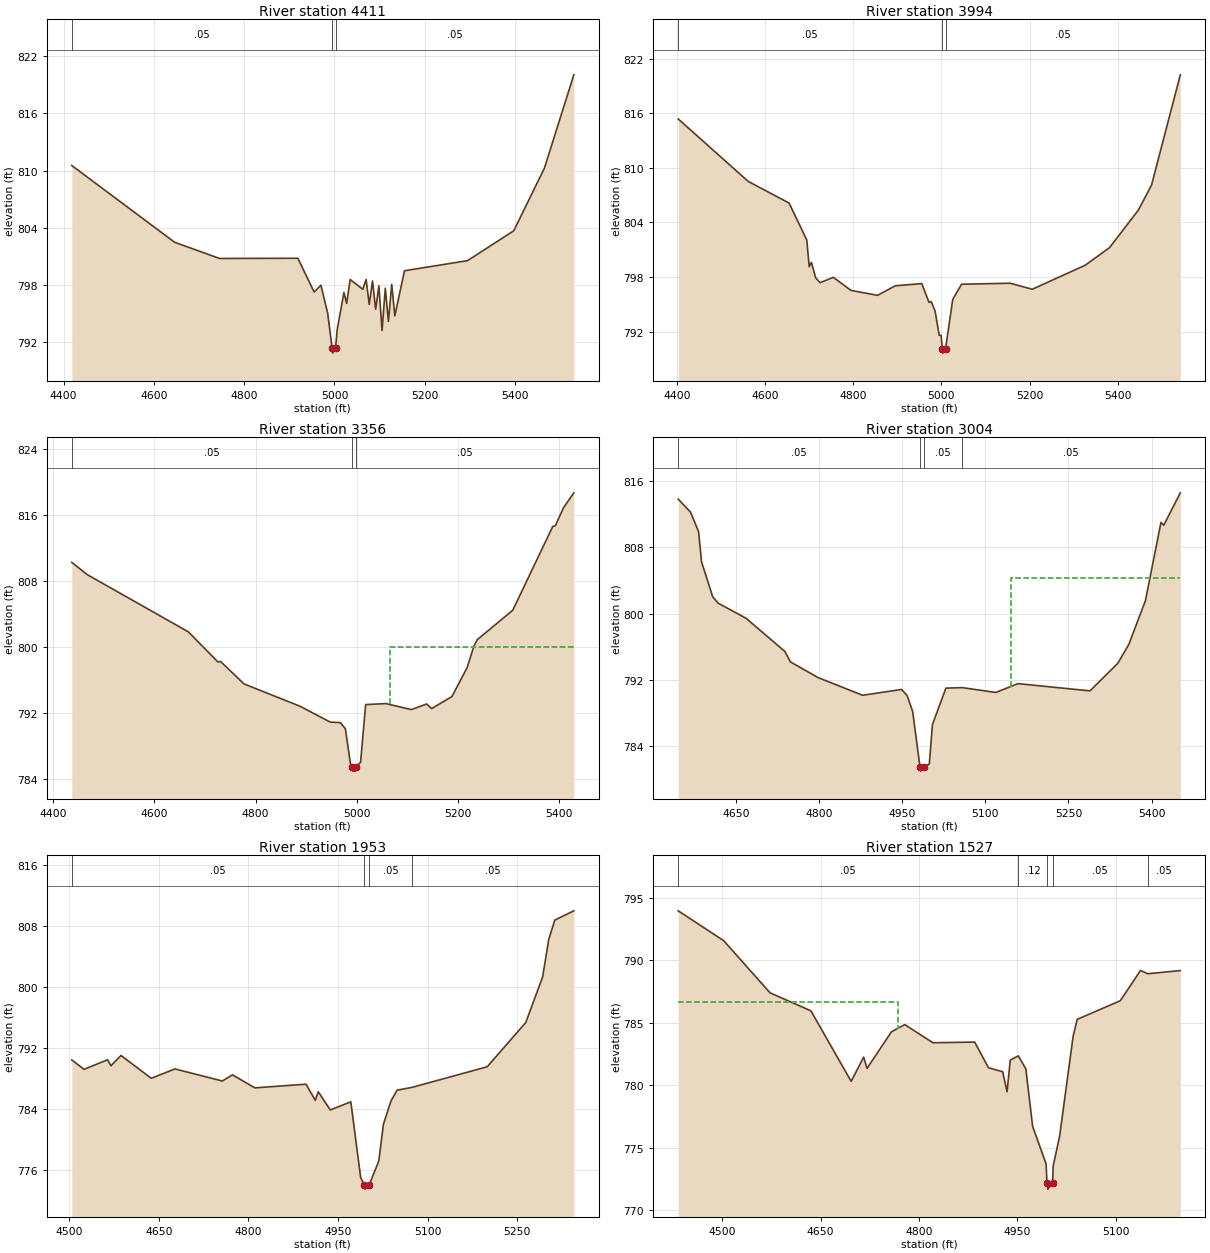
Type RM Length L Ch R = 1,4411,417,417,417
BEGIN DESCRIPTION:
Mapping XS 1e4a1513
END DESCRIPTION:
XS GIS Cut Line= 4
      2294087.52      7092626.17      2294606.68      7092975.57
      2294732.95      7093095.89      2295044.13      7093112.03
#Sta/Elev= 30
  4418.3  810.53  4646.1  802.47  4745.5  800.77  4919.0  800.79  4955.0  797.25
  4970.0  797.96  4985.0  795.03  4994.9  791.33  4996.1  790.83  5002.4  791.33
  5006.0  793.29  5021.0  797.20  5027.0  796.05  5034.8  798.56  5062.9  797.53
  5070.1  798.56  5077.0  795.95  5084.3  798.41  5091.2  795.44  5098.4  797.89
  5105.4  793.21  5112.6  797.65  5119.5  794.16  5126.8  798.05  5133.7  794.75
  5155.1  799.48  5294.7  800.54  5397.1  803.68  5464.9  810.25  5530.1  820.05
#Mann=3,-1,0
  4418.3    0.05       0  4994.9   0.033       0  5002.4    0.05       0
Bank Sta=4994.9,5002.4
Exp/Cntr=0.3,0.1

Type RM Length L Ch R = 1,3994,638,638,638
BEGIN DESCRIPTION:
MDW T 039 6.0
END DESCRIPTION:
XS GIS Cut Line= 3
      2293998.34      7093366.83      2294592.62      7093323.07
      2295134.22      7093297.40
#Sta/Elev= 30
  4403.4  815.37  4562.0  808.51  4654.7  806.13  4694.8  802.07  4700.3  799.14
  4705.3  799.61  4714.9  797.92  4724.9  797.38  4755.0  797.97  4795.1  796.53
  4855.3  795.99  4895.4  797.04  4955.6  797.28  4971.8  795.22  4976.8  795.31
  4985.6  794.27  4995.0  791.60  4999.3  791.60  5001.9  790.14  5003.1  789.64
  5009.4  790.14  5025.7  795.55  5045.7  797.21  5155.8  797.32  5205.9  796.66
  5326.0  799.30  5381.0  801.23  5446.2  805.34  5476.2  808.09  5541.5  820.22
#Mann=3,-1,0
  4403.4    0.05       0  5001.9   0.033       0  5009.4    0.05       0
Bank Sta=5001.9,5009.4
Exp/Cntr=0.3,0.1

Type RM Length L Ch R = 1,3356,352,352,352
BEGIN DESCRIPTION:
MDW T 039 5.0
END DESCRIPTION:
XS GIS Cut Line= 3
      2294168.70      7093790.01      2294727.62      7093799.56
      2295159.38      7093772.65
#Sta/Elev= 30
  4436.9  810.25  4467.2  808.77  4667.2  801.83  4725.6  798.18  4730.6  798.25
  4777.2  795.52  4887.3  792.83  4947.3  790.90  4967.3  790.84  4977.3  790.09
  4987.3  785.86  4990.2  785.46  4991.4  784.96  4996.8  784.96  4998.0  785.46
  5007.3  786.03  5017.3  793.02  5057.4  793.14  5107.5  792.41  5137.6  793.09
  5147.6  792.54  5187.7  793.99  5217.7  797.49  5231.3  800.14  5237.7  800.88
  5307.9  804.45  5386.9  814.60  5391.9  814.68  5408.1  816.87  5428.5  818.67
#Mann=3,-1,0
  4436.9    0.05       0  4990.2   0.033       0  4998.0    0.05       0
#XS Ineff=2,0
       0                 5064.80    0.00  800.05
Permanent Ineff=
       F       F
Bank Sta=4990.2,4998
Exp/Cntr=0.3,0.1

Type RM Length L Ch R = 1,3004,1051,1051,1051
BEGIN DESCRIPTION:
MDW T 039 4.0
END DESCRIPTION:
XS GIS Cut Line= 3
      2294286.97      7094062.36      2294728.11      7094094.58
      2295191.96      7094105.77
#Sta/Elev= 30
  4545.7  813.80  4567.8  812.25  4582.4  809.89  4587.8  806.24  4607.9  802.04
  4617.9  801.26  4668.1  799.45  4738.2  795.45  4748.3  794.19  4798.4  792.29
  4878.6  790.17  4948.8  790.87  4958.8  790.14  4968.9  788.21  4982.1  781.53
  4983.2  781.03  4989.9  781.53  4998.9  781.88  5004.6  786.65  5028.9  791.03
  5058.3  791.09  5118.9  790.51  5159.0  791.57  5289.0  790.70  5339.0  794.01
  5359.0  796.29  5389.0  801.56  5417.1  811.00  5422.1  810.65  5452.0  814.56
#Mann=4,-1,0
  4545.7    0.05       0  4982.1   0.033       0  4989.9    0.05       0
  5058.3    0.05       0
#XS Ineff=2,0
       0                 5145.90    0.00  804.29
Permanent Ineff=
       F       F
Bank Sta=4982.1,4989.9
Exp/Cntr=0.3,0.1

Type RM Length L Ch R = 1,1953,426,426,426
BEGIN DESCRIPTION:
Mapping XS 757162aa
END DESCRIPTION:
XS GIS Cut Line= 4
      2294473.24      7094487.14      2294619.47      7094558.79
      2294797.09      7094643.25      2295270.43      7094560.71
#Sta/Elev= 30
  4504.5  790.44  4525.0  789.21  4564.4  790.46  4570.0  789.67  4586.9  791.02
  4637.5  788.03  4677.1  789.26  4756.3  787.68  4773.5  788.48  4810.8  786.78
  4896.4  787.26  4911.9  785.15  4916.9  786.27  4937.0  783.89  4971.4  784.95
  4987.8  775.06  4994.0  774.02  4995.2  773.52  5001.9  774.02  5018.2  777.22
  5025.9  782.00  5038.5  785.05  5048.7  786.47  5073.6  786.84  5199.5  789.54
  5264.1  795.34  5292.3  801.31  5302.4  806.18  5312.6  808.75  5344.5  809.96
#Mann=4,-1,0
  4504.5    0.05       0  4994.0   0.033       0  5001.9    0.05       0
  5073.6    0.05       0
Bank Sta=4994,5001.9
Exp/Cntr=0.3,0.1

Type RM Length L Ch R = 1,1527,334,334,334
BEGIN DESCRIPTION:
Mapping XS d440b94c
END DESCRIPTION:
XS GIS Cut Line= 4
      2294491.12      7094794.57      2294862.99      7094874.76
      2294959.22      7094961.52      2295207.95      7095021.75
#Sta/Elev= 30
  4432.9  793.96  4502.3  791.57  4573.0  787.40  4635.3  785.96  4696.7  780.32
  4715.8  782.26  4720.9  781.36  4758.1  784.28  4778.5  784.86  4821.4  783.41
  4885.2  783.46  4906.1  781.41  4927.8  781.09  4934.5  779.49  4939.4  782.02
  4951.7  782.36  4963.2  781.31  4973.5  776.73  4994.1  773.71  4995.4  772.20
  4996.7  771.70  5004.0  772.20  5004.8  773.54  5014.7  775.93  5035.3  783.93
  5041.5  785.28  5107.3  786.77  5138.1  789.19  5149.2  788.93  5198.8  789.18
#Mann=5,-1,0
  4432.9    0.05       0  4951.7    0.12       0  4995.4   0.033       0
  5004.0    0.05       0  5149.2    0.05       0
#XS Ineff=2,0
    0.00 4767.40  786.69 5232.60    0.00  786.69
Permanent Ineff=
       F       F
Bank Sta=4995.4,5004
Exp/Cntr=0.3,0.1