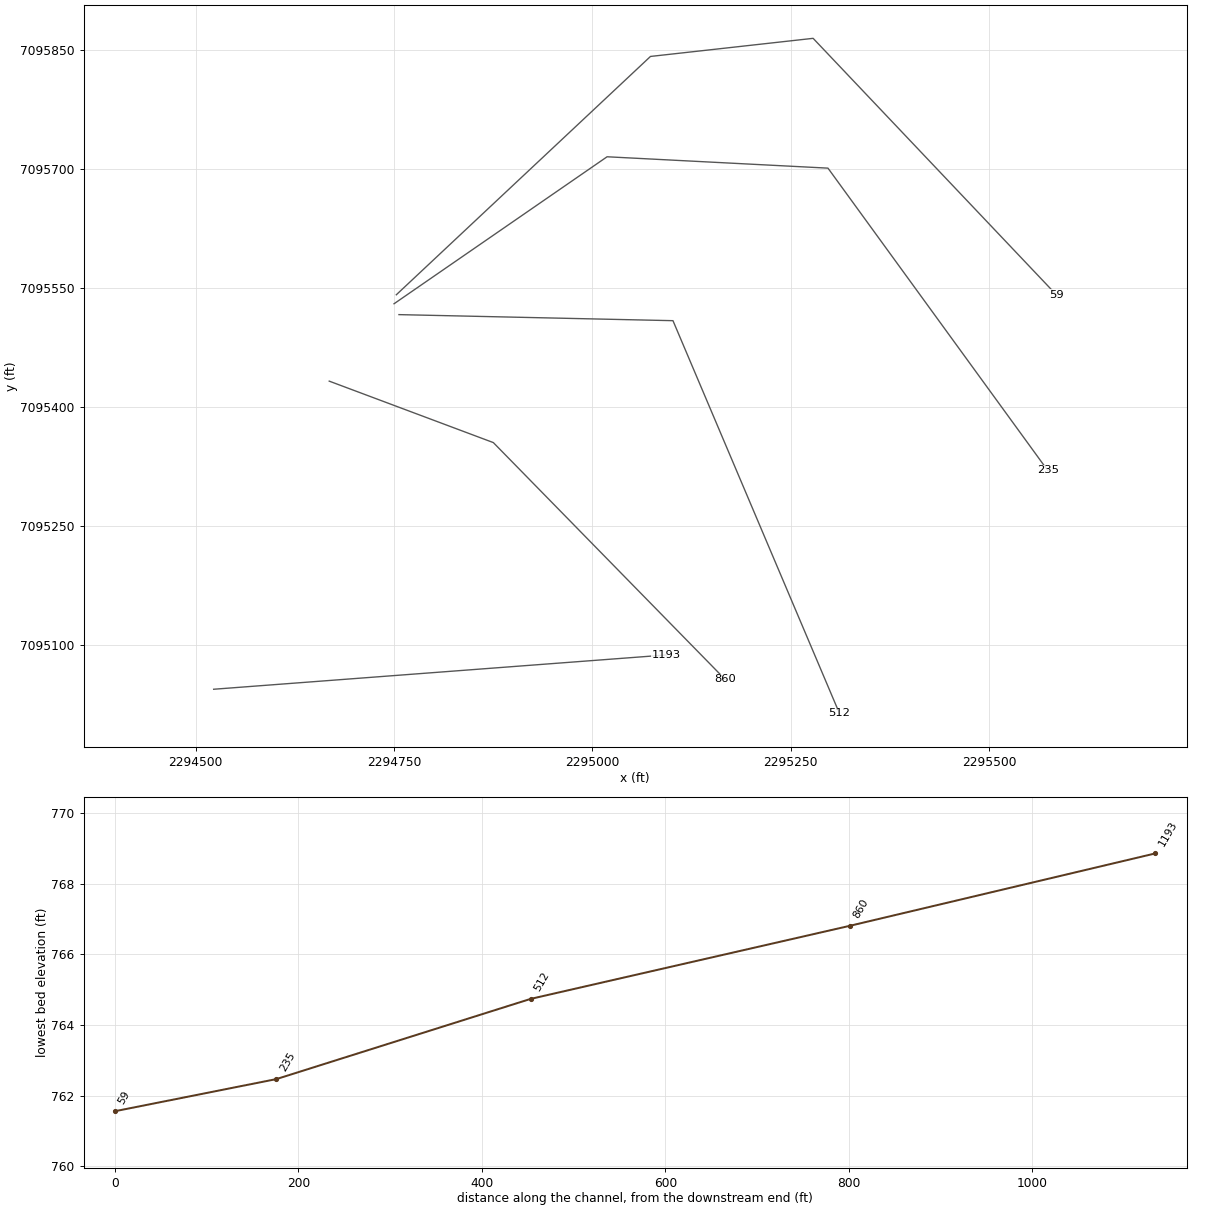
HEC-RAS study MDW T 039.prj: MDW T 039 Base Level Engineering

--- MDW T 039.g01 (geometry) --- (continued)

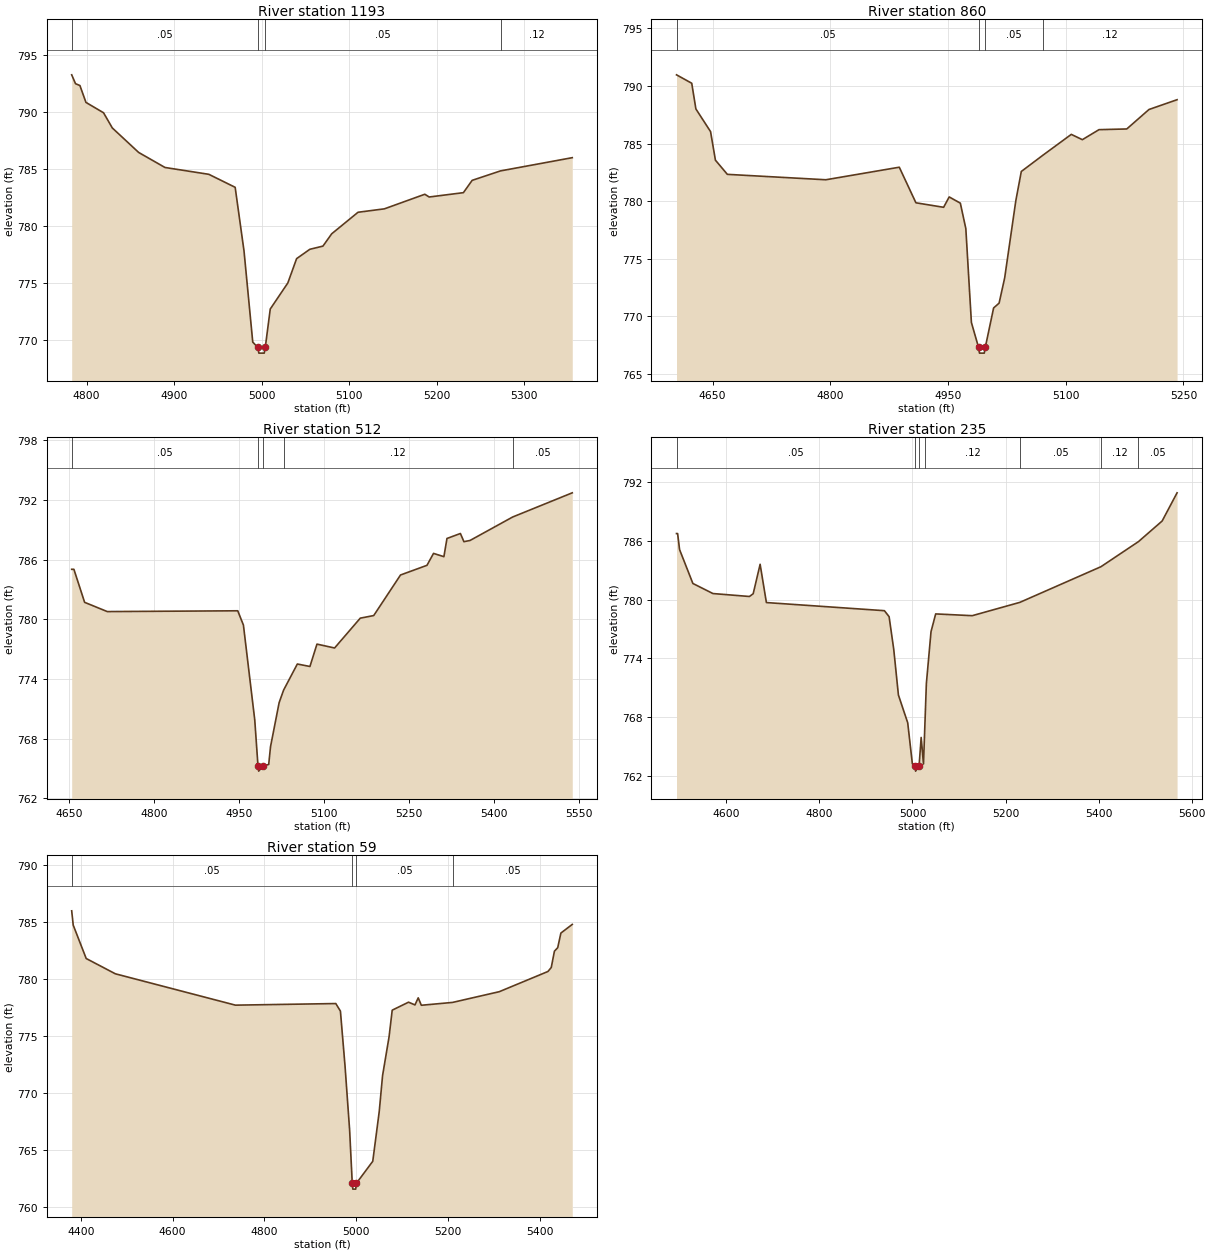
Type RM Length L Ch R = 1,1193,333,333,333
BEGIN DESCRIPTION:
Mapping XS ca78620f
END DESCRIPTION:
XS GIS Cut Line= 2
      2294522.70      7095044.44      2295093.06      7095087.65
#Sta/Elev= 30
  4783.0  793.28  4787.4  792.50  4792.4  792.34  4799.3  790.86  4819.4  789.95
  4829.4  788.62  4859.5  786.47  4889.6  785.15  4939.7  784.55  4969.8  783.41
  4979.9  777.83  4989.9  769.83  4995.6  769.36  4996.9  768.86  5003.0  768.86
  5004.2  769.36  5009.9  772.73  5030.0  775.02  5040.0  777.15  5055.1  777.97
  5070.1  778.25  5080.1  779.33  5110.2  781.22  5140.3  781.52  5186.5  782.80
  5191.5  782.56  5230.6  782.94  5240.6  784.02  5273.0  784.85  5355.0  786.01
#Mann=4,-1,0
  4783.0    0.05       0  4995.6   0.033       0  5004.2    0.05       0
  5273.0    0.12       0
Bank Sta=4995.6,5004.2
Exp/Cntr=0.3,0.1

Type RM Length L Ch R = 1,860,348,348,348
BEGIN DESCRIPTION:
Mapping XS de3ff036
END DESCRIPTION:
XS GIS Cut Line= 3
      2294668.34      7095432.72      2294875.17      7095355.27
      2295166.89      7095057.24
#Sta/Elev= 30
  4604.0  790.97  4623.4  790.24  4628.7  788.01  4647.4  786.04  4653.6  783.56
  4668.8  782.33  4794.3  781.86  4887.9  782.95  4909.1  779.86  4944.4  779.47
  4951.5  780.37  4965.7  779.83  4972.7  777.62  4979.8  769.47  4988.9  767.31
  4990.1  766.81  4996.2  766.81  4997.5  767.31  5008.1  770.73  5015.1  771.15
  5022.2  773.34  5036.4  780.04  5043.4  782.58  5071.1  784.00  5107.1  785.80
  5121.2  785.34  5142.4  786.21  5177.8  786.27  5206.1  787.96  5241.9  788.81
#Mann=4,-1,0
  4604.0    0.05       0  4988.9   0.033       0  4997.5    0.05       0
  5071.1    0.12       0
Bank Sta=4988.9,4997.5
Exp/Cntr=0.3,0.1

Type RM Length L Ch R = 1,512,277,277,277
BEGIN DESCRIPTION:
MDW T 039 0.5
END DESCRIPTION:
XS GIS Cut Line= 3
      2294756.21      7095516.54      2295101.51      7095508.91
      2295311.31      7095014.04
#Sta/Elev= 30
  4655.0  785.03  4658.9  785.03  4677.8  781.71  4717.8  780.78  4947.9  780.86
  4957.9  779.42  4977.9  769.88  4983.6  765.24  4984.8  764.74  4992.2  765.24
  5002.5  765.41  5005.7  767.20  5020.9  771.63  5028.8  772.89  5053.0  775.51
  5075.2  775.26  5087.6  777.51  5118.7  777.12  5164.0  780.12  5187.7  780.38
  5235.0  784.46  5281.6  785.43  5293.2  786.63  5311.5  786.30  5316.9  788.13
  5340.6  788.63  5346.8  787.81  5357.6  787.93  5432.8  790.29  5537.9  792.72
#Mann=5,-1,0
  4655.0    0.05       0  4983.6   0.033       0  4992.2    0.05       0
  5028.8    0.12       0  5432.8    0.05       0
Bank Sta=4983.6,4992.2
Exp/Cntr=0.3,0.1

Type RM Length L Ch R = 1,235,176,176,176
BEGIN DESCRIPTION:
Mapping XS 29ed4d0c
END DESCRIPTION:
XS GIS Cut Line= 4
      2294750.01      7095530.23      2295018.49      7095715.46
      2295296.85      7095701.13      2295573.71      7095320.22
#Sta/Elev= 30
  4492.9  786.74  4495.3  786.74  4499.5  785.10  4528.1  781.64  4571.2  780.61
  4649.6  780.31  4657.7  780.59  4672.6  783.60  4686.1  779.69  4939.7  778.86
  4949.8  778.25  4959.8  774.90  4969.8  770.25  4989.8  767.41  4999.8  763.21
  5005.4  762.97  5006.7  762.47  5014.2  762.97  5018.7  765.91  5023.7  763.20
  5027.6  768.37  5029.9  771.42  5039.9  776.72  5049.9  778.53  5128.5  778.35
  5230.8  779.71  5405.0  783.35  5485.6  785.91  5536.6  788.02  5568.7  790.90
#Mann=7,-1,0
  4492.9    0.05       0  5005.4   0.033       0  5014.2    0.05       0
  5027.6    0.12       0  5230.8    0.05       0  5405.0    0.12       0
  5485.6    0.05       0
Bank Sta=5005.4,5014.2
Exp/Cntr=0.3,0.1

Type RM Length L Ch R = 1,59,0,0,0
BEGIN DESCRIPTION:
MDW T 039 0.3
END DESCRIPTION:
XS GIS Cut Line= 4
      2294752.88      7095541.55      2295073.18      7095841.89
      2295278.13      7095864.71      2295584.98      7095541.18
#Sta/Elev= 30
  4379.9  785.96  4383.2  784.71  4411.5  781.78  4475.0  780.44  4736.8  777.69
  4955.6  777.83  4965.7  777.17  4975.8  772.33  4985.8  766.72  4991.5  762.06
  4992.8  761.56  4999.0  761.56  5000.3  762.06  5036.2  764.00  5050.3  768.36
  5057.6  771.52  5071.7  774.90  5078.6  777.25  5114.2  777.95  5128.2  777.71
  5135.3  778.33  5142.1  777.68  5210.2  777.93  5312.0  778.87  5418.0  780.64
  5425.3  780.99  5432.2  782.42  5439.4  782.73  5446.3  784.01  5471.1  784.77
#Mann=4,-1,0
  4379.9    0.05       0  4991.5   0.033       0  5000.3    0.05       0
  5210.2    0.05       0
Bank Sta=4991.5,5000.3
Exp/Cntr=0.3,0.1

Chan Stop Cuts=-1