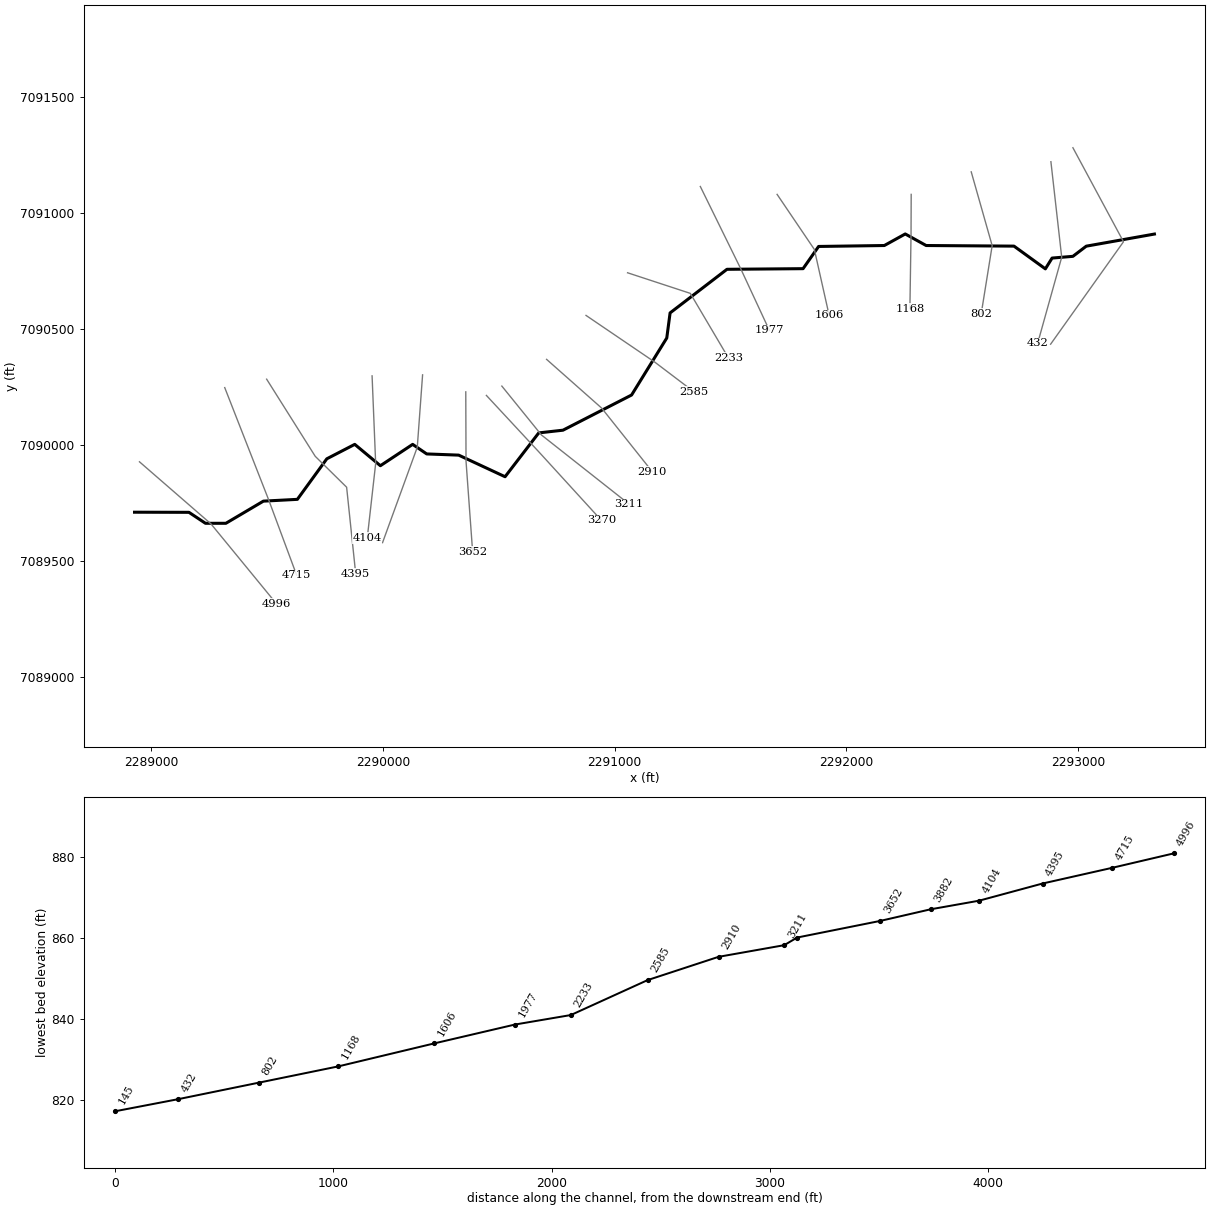
--- MDW T 040.prj (project) ---

Proj Title=MDW T 040 Base Level Engineering
Current Plan=p01
Default Exp/Contr=0.3,0.1
English Units
Geom File=g01
Flow File=f01
Plan File=p01
Y Axis Title=Elevation
X Axis Title(PF)=Main Channel Distance
X Axis Title(XS)=Station
BEGIN DESCRIPTION:
MDW T 040
END DESCRIPTION:
DSS Export Rating Curves= 0
DSS Export Rating Curve Sorted= 0
DSS Export Volume Flow Curves= 0
DXF OffsetX= 0
DXF OffsetY= 0
DXF ScaleX= 1
DXF ScaleY= 10

--- MDW T 040.p01 (plan) ---

Plan Title=Multiple Run
Short Identifier=Multiple
Geom File=g01
Flow File=f01
Subcritical Flow
K Sum by GR= 0
Std Step Tol= 0.01
Critical Tol= 0.01
Num of Std Step Trials= 20
Max Error Tol= 0.3
Flow Tol Ratio= 0.001
Split Flow NTrial= 30
Split Flow Tol= 0.02
Split Flow Ratio= 0.02
Log Output Level= 0
Friction Slope Method= 1
Unsteady Friction Slope Method= 2
Unsteady Bridges Friction Slope Method= 1
Parabolic Critical Depth
Global Vel Dist=  1 , 1 , 1
Global Log Level= 0
CheckData=True
Encroach Param= -1, 0, 0, 0
BEGIN DESCRIPTION:
Multiple Run
END DESCRIPTION:

--- MDW T 040.f01 (steady flow) ---

Flow Title=Multiple
Number of Profiles=7
Profile Names=10-year,25-year,50-year,1pct_min,100-year,1pct_plu,500-year
River Rch & RM= MDW T 040,Reach-1,4996
     626     865    1064     650    1297    2589    1934
Boundary for River Rch & Prof#=MDW T 040,Reach-1,1
Up Type=0
Dn Type=3
Dn Slope=0.005
Boundary for River Rch & Prof#=MDW T 040,Reach-1,2
Up Type=0
Dn Type=3
Dn Slope=0.005
Boundary for River Rch & Prof#=MDW T 040,Reach-1,3
Up Type=0
Dn Type=3
Dn Slope=0.005
Boundary for River Rch & Prof#=MDW T 040,Reach-1,4
Up Type=0
Dn Type=3
Dn Slope=0.005
Boundary for River Rch & Prof#=MDW T 040,Reach-1,5
Up Type=0
Dn Type=3
Dn Slope=0.005
Boundary for River Rch & Prof#=MDW T 040,Reach-1,6
Up Type=0
Dn Type=3
Dn Slope=0.005
Boundary for River Rch & Prof#=MDW T 040,Reach-1,7
Up Type=0
Dn Type=3
Dn Slope=0.005

--- MDW T 040.g01 (geometry) ---

Geom Title=Existing Conditions

River Reach=MDW T 040,Reach-1
Reach XY= 30
      2288929.00      7089710.00      2289163.78      7089709.48
      2289234.98      7089662.17      2289323.03      7089662.14
      2289484.93      7089757.75      2289631.46      7089765.46
      2289758.53      7089940.38      2289879.08      7090002.70
      2289989.64      7089910.57      2290128.90      7090002.67
      2290189.44      7089961.40      2290327.44      7089956.24
      2290527.58      7089863.04      2290672.81      7090052.15
      2290777.41      7090063.83      2291073.39      7090215.59
      2291225.17      7090461.59      2291239.51      7090569.81
      2291484.86      7090757.94      2291813.16      7090760.68
      2291880.26      7090856.52      2292163.79      7090860.54
      2292254.00      7090910.40      2292344.21      7090860.54
      2292723.15      7090857.93      2292858.53      7090759.86
      2292887.48      7090806.38      2292977.33      7090813.88
      2293034.94      7090857.73      2293329.00      7090910.00

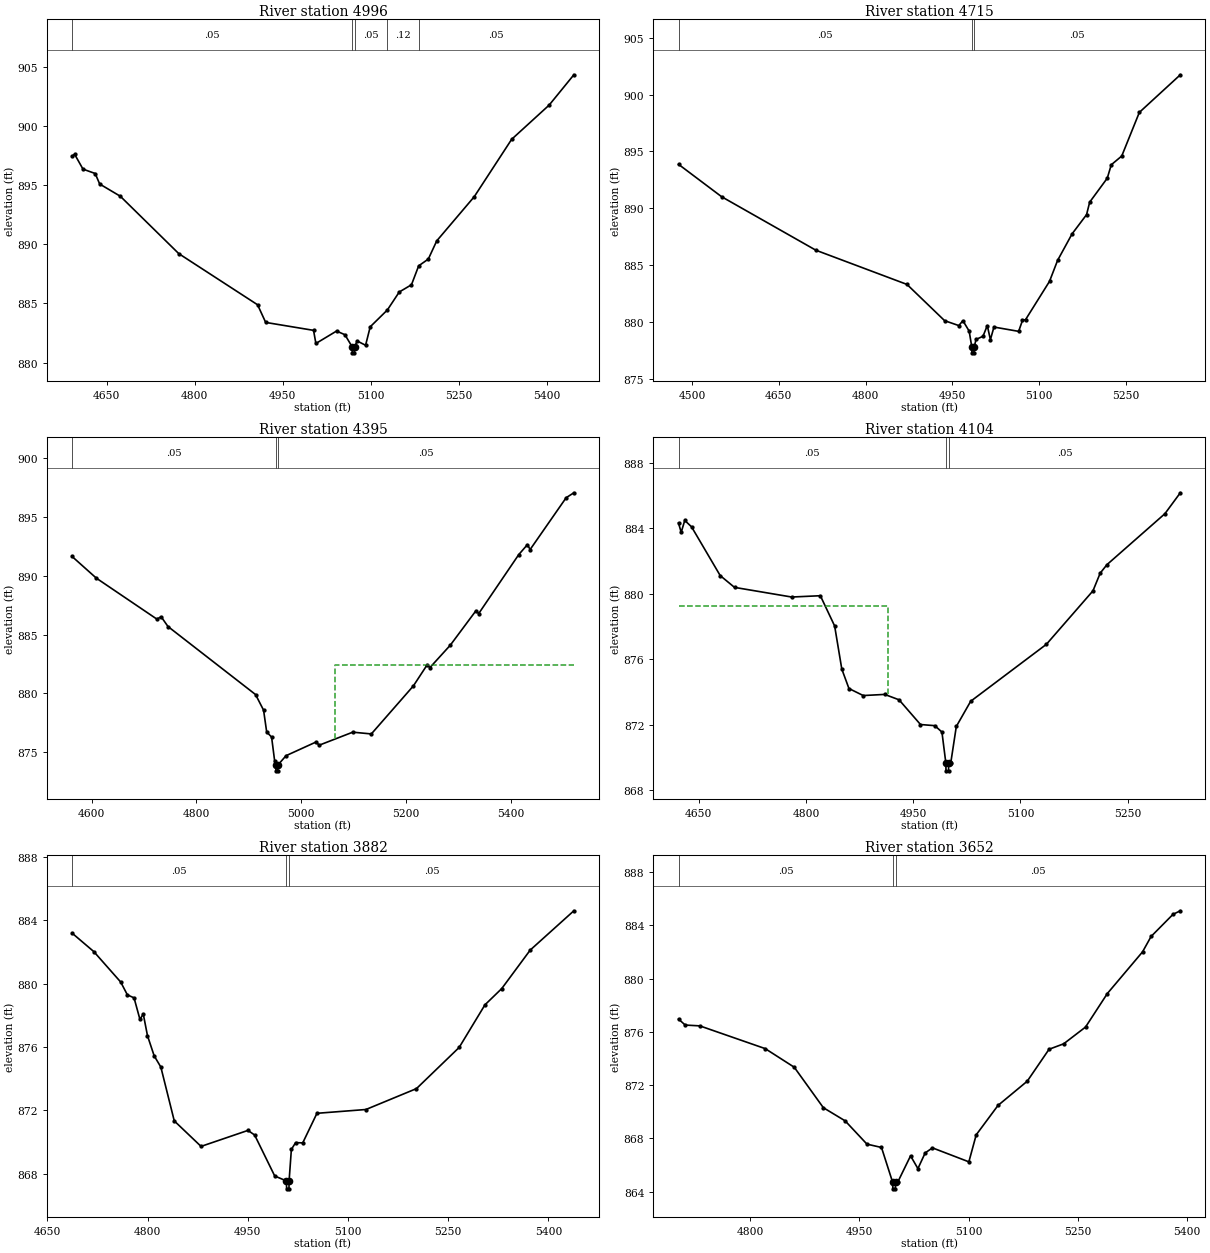
Type RM Length L Ch R = 1,4996,281,281,281
BEGIN DESCRIPTION:
MDW T 040 15.0
END DESCRIPTION:
XS GIS Cut Line= 3
      2288950.29      7089927.45      2289258.95      7089659.40
      2289542.06      7089314.13
#Sta/Elev= 30
  4591.2  897.44  4595.5  897.60  4609.8  896.34  4630.6  895.97  4638.3  895.08
  4673.4  894.05  4773.1  889.20  4907.4  884.88  4921.2  883.39  5002.8  882.72
  5006.8  881.61  5042.0  882.66  5056.3  882.35  5068.7  881.32  5069.0  880.82
  5072.5  880.82  5072.7  881.32  5077.2  881.82  5091.5  881.46  5099.4  883.02
  5128.6  884.44  5148.9  885.96  5169.7  886.57  5182.0  888.17  5198.4  888.74
  5212.8  890.28  5276.7  894.01  5340.5  898.86  5404.4  901.75  5446.5  904.31
#Mann=5,-1,0
  4591.2    0.05       0  5068.7   0.033       0  5072.7    0.05       0
  5128.6    0.12       0  5182.0    0.05       0
Bank Sta=5068.7,5072.7
Exp/Cntr=0.3,0.1

Type RM Length L Ch R = 1,4715,320,320,320
BEGIN DESCRIPTION:
MDW T 040 14.0
END DESCRIPTION:
XS GIS Cut Line= 3
      2289318.14      7090247.53      2289508.86      7089760.33
      2289628.46      7089438.11
#Sta/Elev= 30
  4476.8  893.87  4551.2  891.02  4714.1  886.31  4871.5  883.30  4936.5  880.11
  4961.0  879.68  4968.1  880.11  4978.9  879.19  4983.5  877.78  4983.7  877.28
  4987.2  877.28  4987.5  877.78  4990.8  878.46  5002.8  878.74  5010.2  879.68
  5015.6  878.44  5021.7  879.55  5064.4  879.17  5071.0  880.14  5076.3  880.20
  5117.7  883.57  5131.7  885.42  5156.7  887.75  5181.7  889.44  5187.1  890.54
  5217.5  892.65  5224.4  893.83  5242.5  894.60  5272.9  898.44  5343.7  901.75
#Mann=3,-1,0
  4476.8    0.05       0  4983.5   0.033       0  4987.5    0.05       0
Bank Sta=4983.5,4987.5
Exp/Cntr=0.3,0.1

Type RM Length L Ch R = 1,4395,291,291,291
BEGIN DESCRIPTION:
MDW T 040 13.0
END DESCRIPTION:
XS GIS Cut Line= 4
      2289498.93      7090283.96      2289708.52      7089951.18
      2289844.00      7089817.78      2289883.07      7089445.34
#Sta/Elev= 30
  4562.7  891.64  4609.2  889.79  4724.6  886.31  4732.8  886.51  4745.8  885.68
  4913.0  879.89  4928.3  878.56  4934.2  876.71  4943.6  876.27  4949.5  874.21
  4951.7  873.90  4952.0  873.40  4955.5  873.40  4955.7  873.90  4971.2  874.69
  5027.8  875.84  5034.9  875.59  5098.5  876.69  5134.0  876.54  5214.3  880.63
  5240.7  882.43  5245.7  882.18  5284.7  884.09  5333.8  887.03  5338.9  886.78
  5415.4  891.80  5432.0  892.65  5437.1  892.23  5505.9  896.64  5520.6  897.06
#Mann=3,-1,0
  4562.7    0.05       0  4951.7   0.033       0  4955.7    0.05       0
#XS Ineff=2,0
       0                 5064.60    0.00  882.40
Permanent Ineff=
       F       F
Bank Sta=4951.7,4955.7
Exp/Cntr=0.3,0.1

Type RM Length L Ch R = 1,4104,222,222,222
BEGIN DESCRIPTION:
MDW T 040 12.0
END DESCRIPTION:
XS GIS Cut Line= 3
      2289953.83      7090298.20      2289969.32      7089920.22
      2289933.00      7089598.56
#Sta/Elev= 30
  4621.7  884.31  4625.4  883.74  4630.4  884.47  4639.9  884.08  4680.0  881.10
  4700.0  880.38  4780.0  879.79  4820.1  879.87  4840.1  878.02  4850.1  875.39
  4860.1  874.20  4880.1  873.77  4910.1  873.84  4930.2  873.51  4960.2  872.00
  4980.2  871.93  4990.2  871.54  4995.6  869.67  4995.9  869.17  4999.4  869.17
  4999.6  869.67  5002.6  869.67  5010.3  871.88  5030.4  873.42  5136.3  876.90
  5201.5  880.17  5211.6  881.25  5221.1  881.77  5302.1  884.88  5323.7  886.16
#Mann=3,-1,0
  4621.7    0.05       0  4995.6   0.033       0  4999.6    0.05       0
#XS Ineff=2,0
    0.00 4915.10  879.25               0
Permanent Ineff=
       F       F
Bank Sta=4995.6,4999.6
Exp/Cntr=0.3,0.1

Type RM Length L Ch R = 1,3882,230,230,230
BEGIN DESCRIPTION:
MDW T 040 11.0
END DESCRIPTION:
XS GIS Cut Line= 3
      2290171.71      7090302.56      2290148.80      7089990.30
      2289998.97      7089578.61
#Sta/Elev= 30
  4686.9  883.20  4719.5  882.03  4759.7  880.11  4769.7  879.30  4779.7  879.11
  4788.5  877.75  4793.5  878.09  4799.8  876.72  4809.8  875.45  4819.8  874.74
  4839.9  871.34  4880.0  869.73  4950.2  870.74  4960.2  870.45  4990.3  867.86
  5007.8  867.55  5008.1  867.05  5011.6  867.05  5011.8  867.55  5015.2  869.54
  5021.6  869.97  5032.2  869.95  5053.5  871.82  5126.8  872.06  5202.5  873.38
  5266.4  875.98  5305.0  878.67  5330.2  879.70  5372.8  882.13  5438.1  884.61
#Mann=3,-1,0
  4686.9    0.05       0  5007.8   0.033       0  5011.8    0.05       0
Bank Sta=5007.8,5011.8
Exp/Cntr=0.3,0.1

Type RM Length L Ch R = 1,3652,382,382,382
BEGIN DESCRIPTION:
MDW T 040 10.0
END DESCRIPTION:
XS GIS Cut Line= 3
      2290358.03      7090229.17      2290359.11      7089930.27
      2290387.55      7089539.91
#Sta/Elev= 30
  4701.1  876.96  4710.3  876.51  4730.3  876.45  4820.3  874.74  4860.3  873.34
  4900.3  870.30  4930.3  869.31  4960.3  867.56  4980.3  867.31  4995.6  864.70
  4995.9  864.20  4999.4  864.20  4999.6  864.70  5002.6  864.70  5020.3  866.68
  5030.4  865.72  5040.4  866.90  5050.4  867.28  5100.5  866.23  5110.6  868.26
  5140.6  870.47  5180.8  872.29  5210.8  874.69  5230.9  875.10  5261.0  876.36
  5291.0  878.88  5339.4  882.01  5351.2  883.17  5381.3  884.83  5391.4  885.10
#Mann=3,-1,0
  4701.1    0.05       0  4995.6   0.033       0  4999.6    0.05       0
Bank Sta=4995.6,4999.6
Exp/Cntr=0.3,0.1

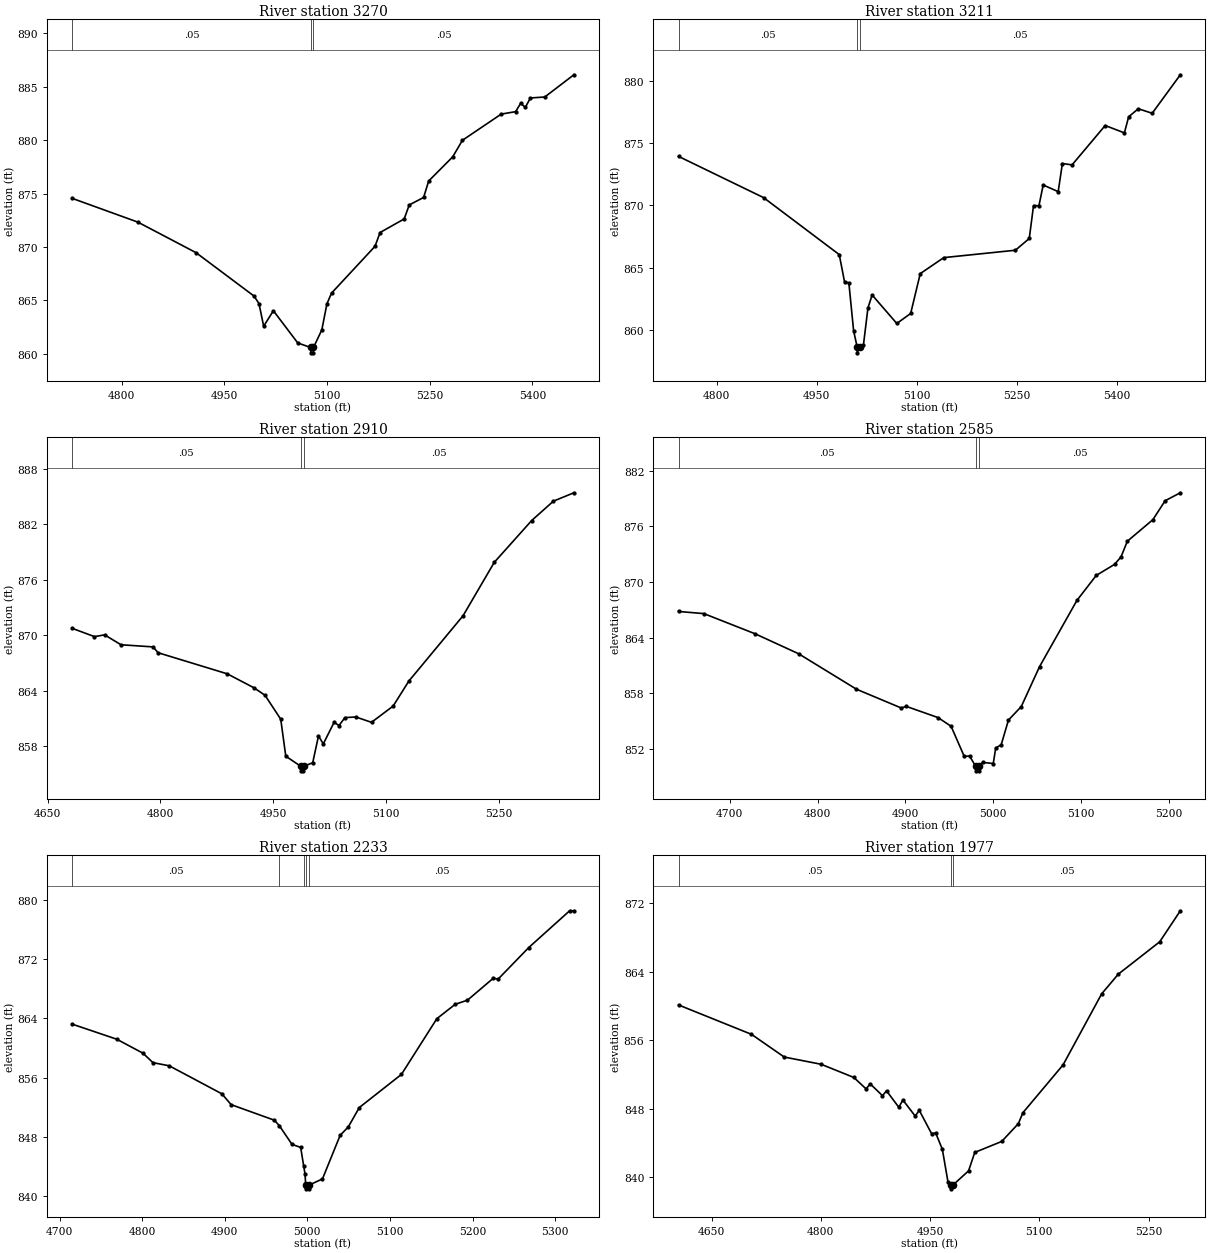
Type RM Length L Ch R = 1,3270,59,59,59
BEGIN DESCRIPTION:
MDW T 040 9.0
END DESCRIPTION:
XS GIS Cut Line= 3
      2290446.99      7090213.82      2290679.65      7089963.37
      2290943.46      7089674.43
#Sta/Elev= 30
  4727.5  874.55  4823.7  872.32  4908.7  869.46  4993.2  865.41  5000.6  864.70
  5007.4  862.58  5021.6  864.03  5057.3  861.01  5076.2  860.59  5076.5  860.09
  5080.0  860.09  5080.2  860.59  5092.4  862.24  5099.8  864.67  5106.6  865.68
  5170.1  870.06  5177.5  871.35  5212.7  872.62  5220.1  873.93  5241.1  874.63
  5248.5  876.17  5283.6  878.43  5297.8  879.98  5354.5  882.43  5375.5  882.66
  5382.9  883.44  5389.7  883.06  5397.1  883.94  5418.1  884.03  5460.6  886.11
#Mann=3,-1,0
  4727.5    0.05       0  5076.2   0.033       0  5080.2    0.05       0
Bank Sta=5076.2,5080.2
Exp/Cntr=0.3,0.1

Type RM Length L Ch R = 1,3211,301,301,301
BEGIN DESCRIPTION:
MDW T 040 8.5
END DESCRIPTION:
XS GIS Cut Line= 3
      2290513.68      7090254.08      2290684.42      7090043.23
      2291062.32      7089745.03
#Sta/Elev= 30
  4742.5  873.93  4870.1  870.63  4983.6  866.07  4991.5  863.89  4998.0  863.81
  5005.1  859.98  5010.3  858.71  5010.6  858.21  5014.3  858.71  5019.9  858.85
  5026.6  861.80  5032.9  862.84  5069.9  860.56  5090.7  861.36  5105.1  864.55
  5140.4  865.83  5247.8  866.42  5268.6  867.36  5275.0  869.99  5283.1  869.98
  5289.5  871.64  5312.0  871.11  5318.3  873.36  5332.8  873.25  5382.5  876.40
  5411.3  875.81  5417.7  877.10  5432.2  877.74  5453.0  877.38  5495.2  880.46
#Mann=3,-1,0
  4742.5    0.05       0  5010.3   0.033       0  5014.3    0.05       0
Bank Sta=5010.3,5014.3
Exp/Cntr=0.3,0.1

Type RM Length L Ch R = 1,2910,325,325,325
BEGIN DESCRIPTION:
MDW T 040 8.0
END DESCRIPTION:
XS GIS Cut Line= 3
      2290706.70      7090369.39      2290944.40      7090159.06
      2291162.31      7089885.30
#Sta/Elev= 30
  4682.6  870.74  4712.4  869.84  4725.9  870.03  4747.7  868.96  4790.3  868.73
  4797.0  868.10  4889.0  865.82  4925.0  864.29  4939.2  863.50  4960.1  860.92
  4966.8  856.92  4986.6  855.84  4986.8  855.34  4990.3  855.34  4990.6  855.84
  5002.6  856.21  5010.3  859.11  5016.7  858.25  5031.1  860.59  5037.5  860.23
  5045.5  861.09  5059.9  861.16  5080.8  860.58  5109.6  862.34  5130.4  865.03
  5202.5  872.09  5244.1  877.87  5293.8  882.38  5322.6  884.47  5349.9  885.38
#Mann=3,-1,0
  4682.6    0.05       0  4986.6   0.033       0  4990.6    0.05       0
Bank Sta=4986.6,4990.6
Exp/Cntr=0.3,0.1

Type RM Length L Ch R = 1,2585,352,352,352
BEGIN DESCRIPTION:
MDW T 040 7.0
END DESCRIPTION:
XS GIS Cut Line= 3
      2290876.84      7090558.96      2291173.16      7090357.71
      2291342.82      7090229.10
#Sta/Elev= 30
  4641.8  866.81  4670.6  866.58  4729.0  864.40  4778.4  862.25  4844.3  858.42
  4895.1  856.40  4901.2  856.56  4937.1  855.36  4952.0  854.42  4967.0  851.16
  4973.0  851.22  4979.9  850.11  4980.2  849.61  4983.7  849.61  4983.9  850.11
  4988.0  850.52  5000.0  850.40  5002.8  852.08  5009.0  852.42  5017.3  855.09
  5031.9  856.55  5052.7  860.86  5095.2  868.00  5117.2  870.70  5138.0  871.89
  5145.4  872.70  5152.6  874.39  5181.7  876.72  5195.6  878.76  5212.9  879.62
#Mann=3,-1,0
  4641.8    0.05       0  4979.9   0.033       0  4983.9    0.05       0
Bank Sta=4979.9,4983.9
Exp/Cntr=0.3,0.1

Type RM Length L Ch R = 1,2233,256,256,256
BEGIN DESCRIPTION:
MDW T 040 6.0
END DESCRIPTION:
XS GIS Cut Line= 3
      2291056.00      7090742.98      2291326.70      7090654.15
      2291490.77      7090376.28
#Sta/Elev= 30
  4715.1  863.23  4769.2  861.19  4801.0  859.30  4813.0  858.03  4832.8  857.60
  4896.5  853.82  4907.7  852.36  4960.1  850.26  4966.2  849.50  4981.4  847.00
  4991.9  846.59  4995.5  844.13  4997.2  842.97  4998.0  841.50  4998.3  841.00
  5001.8  841.00  5002.0  841.50  5018.3  842.34  5039.7  848.22  5049.6  849.36
  5062.9  851.97  5113.9  856.44  5156.8  863.96  5179.0  865.90  5193.9  866.46
  5225.2  869.42  5231.0  869.30  5268.1  873.56  5317.6  878.52  5322.7  878.52
#Mann=5,-1,0
  4715.1    0.05       0  4966.2    0.12       0  4995.5    0.05       0
  4998.0   0.033       0  5002.0    0.05       0
Bank Sta=4998,5002
Exp/Cntr=0.3,0.1

Type RM Length L Ch R = 1,1977,371,371,371
BEGIN DESCRIPTION:
MDW T 040 5.0
END DESCRIPTION:
XS GIS Cut Line= 3
      2291369.93      7091115.19      2291544.29      7090760.30
      2291668.07      7090493.97
#Sta/Elev= 30
  4604.6  860.12  4704.8  856.69  4749.8  854.04  4800.3  853.20  4845.3  851.66
  4862.2  850.32  4867.7  850.92  4884.7  849.53  4890.2  850.10  4907.1  848.18
  4912.7  849.03  4929.6  847.15  4935.2  847.82  4952.1  845.10  4957.7  845.19
  4966.9  843.27  4974.6  839.48  4978.2  839.16  4978.4  838.66  4982.2  839.16
  5002.9  840.76  5011.4  842.91  5048.4  844.19  5071.3  846.27  5077.5  847.54
  5132.7  853.13  5185.7  861.42  5208.6  863.72  5265.4  867.49  5293.7  871.11
#Mann=3,-1,0
  4604.6    0.05       0  4978.2   0.033       0  4982.2    0.05       0
Bank Sta=4978.2,4982.2
Exp/Cntr=0.3,0.1

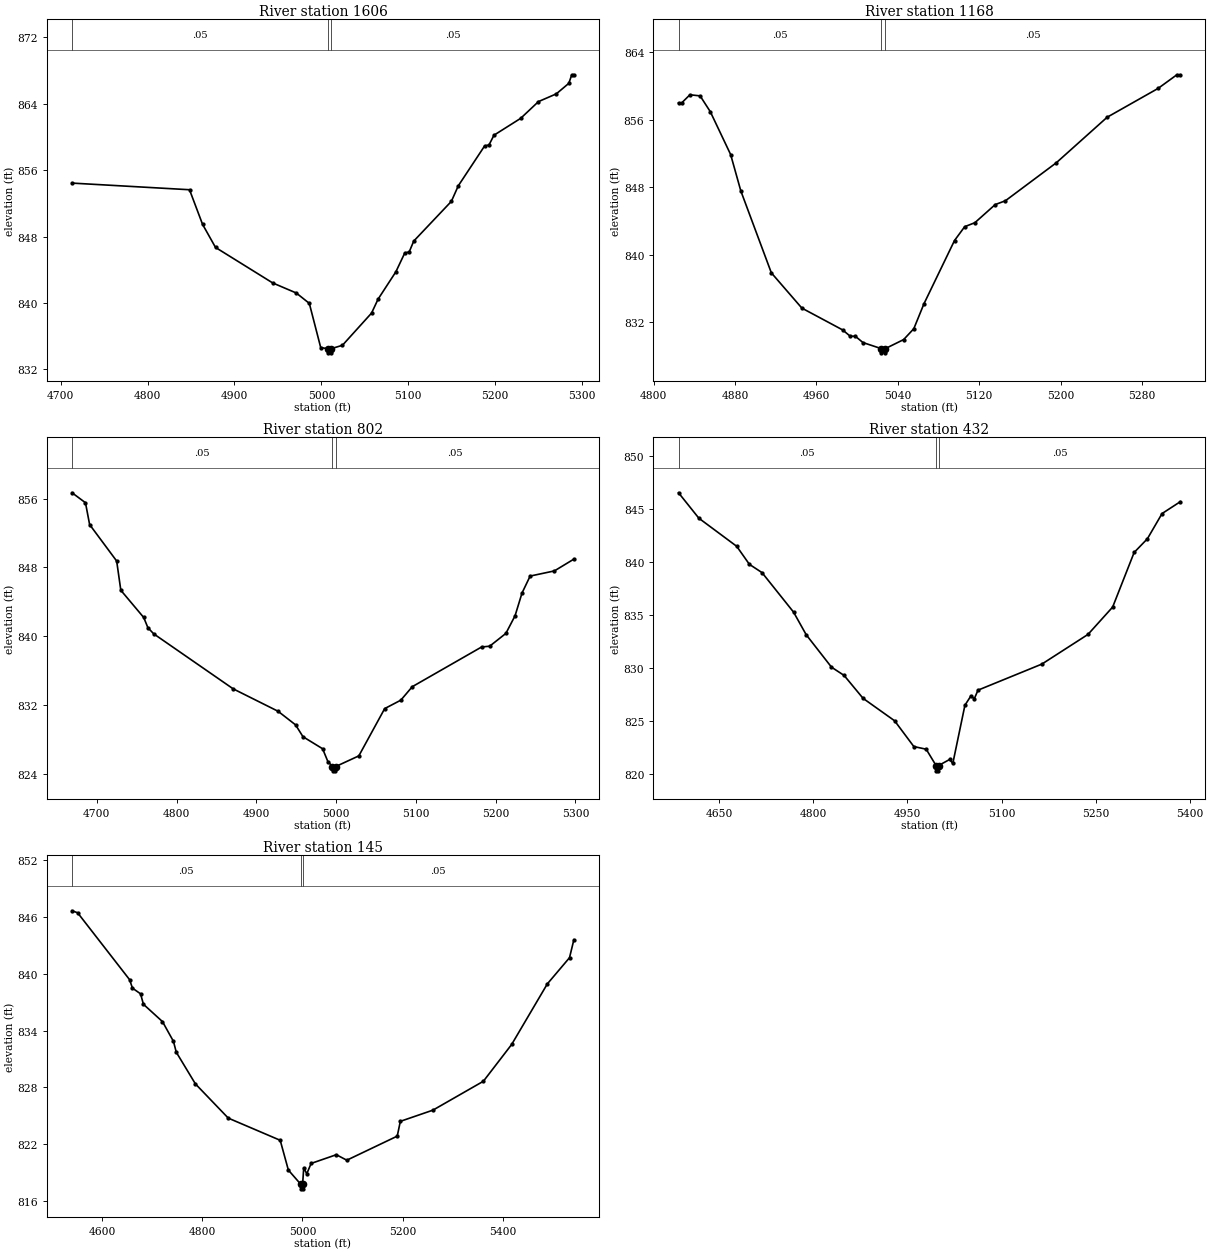
Type RM Length L Ch R = 1,1606,438,438,438
BEGIN DESCRIPTION:
MDW T 040 4.0
END DESCRIPTION:
XS GIS Cut Line= 3
      2291701.17      7091081.17      2291861.90      7090843.64
      2291925.49      7090560.29
#Sta/Elev= 30
  4713.2  854.45  4848.3  853.65  4863.3  849.48  4878.2  846.70  4944.0  842.42
  4971.1  841.21  4986.1  839.96  4999.2  834.64  5007.2  834.50  5007.5  834.00
  5011.0  834.00  5011.2  834.50  5024.2  834.91  5057.7  838.79  5065.2  840.47
  5085.7  843.77  5095.9  846.03  5101.0  846.16  5106.2  847.46  5149.5  852.25
  5157.5  854.13  5187.7  858.92  5192.8  859.05  5198.5  860.22  5229.2  862.25
  5249.7  864.27  5270.2  865.20  5284.6  866.47  5288.0  867.50  5290.4  867.50
#Mann=3,-1,0
  4713.2    0.05       0  5007.2   0.033       0  5011.2    0.05       0
Bank Sta=5007.2,5011.2
Exp/Cntr=0.3,0.1

Type RM Length L Ch R = 1,1168,366,366,366
BEGIN DESCRIPTION:
MDW T 040 3.0
END DESCRIPTION:
XS GIS Cut Line= 3
      2292279.65      7091081.17      2292279.00      7090910.00
      2292274.09      7090588.11
#Sta/Elev= 30
  4824.6  857.98  4827.7  857.98  4835.8  858.94  4845.8  858.81  4855.8  856.94
  4875.8  851.86  4885.8  847.55  4915.8  837.84  4945.8  833.66  4985.8  831.08
  4993.3  830.33  4998.3  830.33  5005.8  829.58  5023.8  828.86  5024.0  828.36
  5027.5  828.36  5027.8  828.86  5045.8  829.93  5055.8  831.22  5065.8  834.18
  5095.8  841.67  5105.8  843.31  5115.8  843.78  5135.8  845.93  5145.8  846.38
  5195.8  850.88  5245.8  856.28  5295.8  859.69  5314.3  861.31  5317.7  861.31
#Mann=3,-1,0
  4824.6    0.05       0  5023.8   0.033       0  5027.8    0.05       0
Bank Sta=5023.8,5027.8
Exp/Cntr=0.3,0.1

Type RM Length L Ch R = 1,802,370,370,370
BEGIN DESCRIPTION:
MDW T 040 2.0
END DESCRIPTION:
XS GIS Cut Line= 3
      2292538.66      7091178.43      2292629.00      7090860.00
      2292581.73      7090565.87
#Sta/Elev= 30
  4669.1  856.68  4685.9  855.52  4691.1  852.98  4725.0  848.74  4730.2  845.34
  4758.9  842.17  4764.1  840.99  4771.4  840.27  4871.0  833.87  4927.3  831.26
  4949.2  829.68  4958.5  828.30  4983.1  826.90  4989.7  825.41  4995.5  824.83
  4995.7  824.33  4999.2  824.33  4999.5  824.83  5028.5  826.07  5060.9  831.57
  5081.1  832.55  5095.5  834.12  5182.4  838.74  5192.5  838.83  5212.8  840.32
  5224.3  842.37  5233.0  845.01  5243.2  846.99  5273.6  847.59  5298.0  848.96
#Mann=3,-1,0
  4669.1    0.05       0  4995.5   0.033       0  4999.5    0.05       0
Bank Sta=4995.5,4999.5
Exp/Cntr=0.3,0.1

Type RM Length L Ch R = 1,432,287,287,287
BEGIN DESCRIPTION:
MDW T 040 1.0
END DESCRIPTION:
XS GIS Cut Line= 3
      2292882.42      7091222.15      2292929.00      7090810.00
      2292825.47      7090439.47
#Sta/Elev= 30
  4585.3  846.49  4617.7  844.09  4678.0  841.44  4698.2  839.74  4718.3  838.96
  4768.6  835.23  4788.7  833.10  4829.0  830.04  4849.1  829.26  4879.3  827.10
  4929.6  824.98  4960.2  822.55  4979.9  822.30  4995.6  820.76  4995.8  820.26
  4999.3  820.26  4999.6  820.76  5017.2  821.33  5022.3  820.96  5041.6  826.45
  5051.3  827.34  5056.5  827.05  5062.4  827.87  5164.2  830.33  5237.7  833.13
  5277.0  835.71  5311.2  840.86  5332.3  842.15  5355.7  844.53  5384.8  845.65
#Mann=3,-1,0
  4585.3    0.05       0  4995.6   0.033       0  4999.6    0.05       0
Bank Sta=4995.6,4999.6
Exp/Cntr=0.3,0.1

Type RM Length L Ch R = 1,145,0,0,0
BEGIN DESCRIPTION:
MDW T 040 0.5
END DESCRIPTION:
XS GIS Cut Line= 3
      2292977.40      7091282.36      2293195.60      7090876.83
      2292881.15      7090434.88
#Sta/Elev= 30
  4539.5  846.63  4550.6  846.42  4654.5  839.36  4660.2  838.47  4676.4  837.87
  4682.1  836.77  4720.2  834.94  4742.1  832.86  4747.8  831.71  4786.0  828.37
  4851.7  824.76  4955.5  822.42  4971.8  819.28  4996.3  817.80  4996.6  817.30
  5000.1  817.30  5000.3  817.80  5002.5  819.51  5008.6  818.89  5017.3  819.98
  5067.7  820.90  5088.6  820.32  5189.4  822.86  5195.6  824.42  5260.7  825.60
  5361.6  828.65  5418.1  832.53  5489.4  838.92  5533.7  841.68  5542.4  843.57
#Mann=3,-1,0
  4539.5    0.05       0  4996.3   0.033       0  5000.3    0.05       0
Bank Sta=4996.3,5000.3
Exp/Cntr=0.3,0.1

Chan Stop Cuts=-1