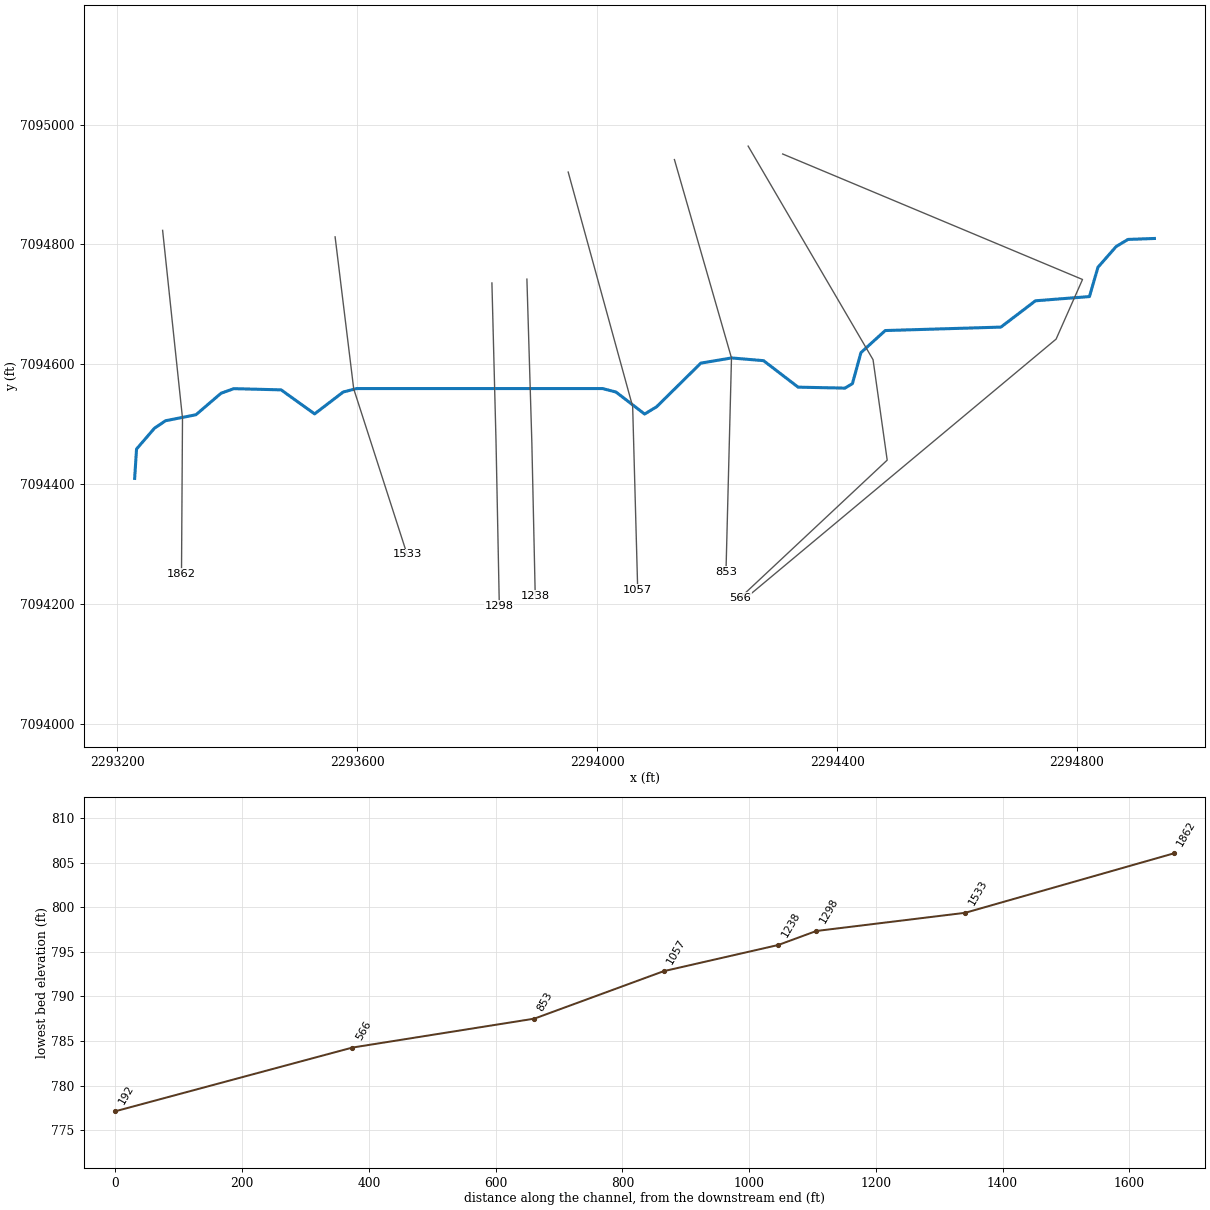
--- MDW T 041.prj (project) ---

Proj Title=MDW T 041 Base Level Engineering
Current Plan=p01
Default Exp/Contr=0.3,0.1
English Units
Geom File=g01
Flow File=f01
Plan File=p01
BEGIN DESCRIPTION:
MDW T 041
END DESCRIPTION:

--- MDW T 041.p01 (plan) ---

Plan Title=Multiple Run
Short Identifier=Multiple
Geom File=g01
Flow File=f01
Subcritical Flow
K Sum by GR= 0
Std Step Tol= 0.01
Critical Tol= 0.01
Num of Std Step Trials= 20
Max Error Tol= 0.3
Flow Tol Ratio= 0.001
Split Flow NTrial= 30
Split Flow Tol= 0.02
Split Flow Ratio= 0.02
Log Output Level= 0
Friction Slope Method= 1
Unsteady Friction Slope Method= 2
Unsteady Bridges Friction Slope Method= 1
Parabolic Critical Depth
Global Vel Dist=  1 , 1 , 1
Global Log Level= 0
CheckData=True
Encroach Param= -1, 0, 0, 0
BEGIN DESCRIPTION:
Multiple Run
END DESCRIPTION:

--- MDW T 041.f01 (steady flow) ---

Flow Title=Multiple
Number of Profiles=7
Profile Names=10-year,25-year,50-year,1pct_min,100-year,1pct_plu,500-year
River Rch & RM= MDW T 041,Reach-1,1862
     269     354     421     250     499     996     701
Boundary for River Rch & Prof#=MDW T 041,Reach-1,1
Up Type=0
Dn Type=3
Dn Slope=0.005
Boundary for River Rch & Prof#=MDW T 041,Reach-1,2
Up Type=0
Dn Type=3
Dn Slope=0.005
Boundary for River Rch & Prof#=MDW T 041,Reach-1,3
Up Type=0
Dn Type=3
Dn Slope=0.005
Boundary for River Rch & Prof#=MDW T 041,Reach-1,4
Up Type=0
Dn Type=3
Dn Slope=0.005
Boundary for River Rch & Prof#=MDW T 041,Reach-1,5
Up Type=0
Dn Type=3
Dn Slope=0.005
Boundary for River Rch & Prof#=MDW T 041,Reach-1,6
Up Type=0
Dn Type=3
Dn Slope=0.005
Boundary for River Rch & Prof#=MDW T 041,Reach-1,7
Up Type=0
Dn Type=3
Dn Slope=0.005

--- MDW T 041.g01 (geometry) ---

Geom Title=Existing Conditions

River Reach=MDW T 041,Reach-1
Reach XY= 30
      2293229.00      7094410.00      2293232.14      7094458.97
      2293261.96      7094493.63      2293280.45      7094506.17
      2293331.16      7094516.13      2293372.94      7094551.96
      2293394.27      7094559.63      2293473.11      7094557.64
      2293529.00      7094517.56      2293576.55      7094553.98
      2293598.98      7094559.82      2294009.02      7094559.81
      2294031.45      7094553.97      2294079.10      7094517.33
      2294099.02      7094529.34      2294172.83      7094602.20
      2294223.95      7094610.84      2294277.41      7094606.29
      2294335.06      7094562.13      2294413.10      7094560.54
      2294425.57      7094568.08      2294439.75      7094619.75
      2294480.26      7094656.52      2294673.07      7094662.26
      2294730.67      7094706.11      2294820.68      7094713.16
      2294834.89      7094762.07      2294865.26      7094796.63
      2294884.88      7094808.40      2294929.00      7094810.00

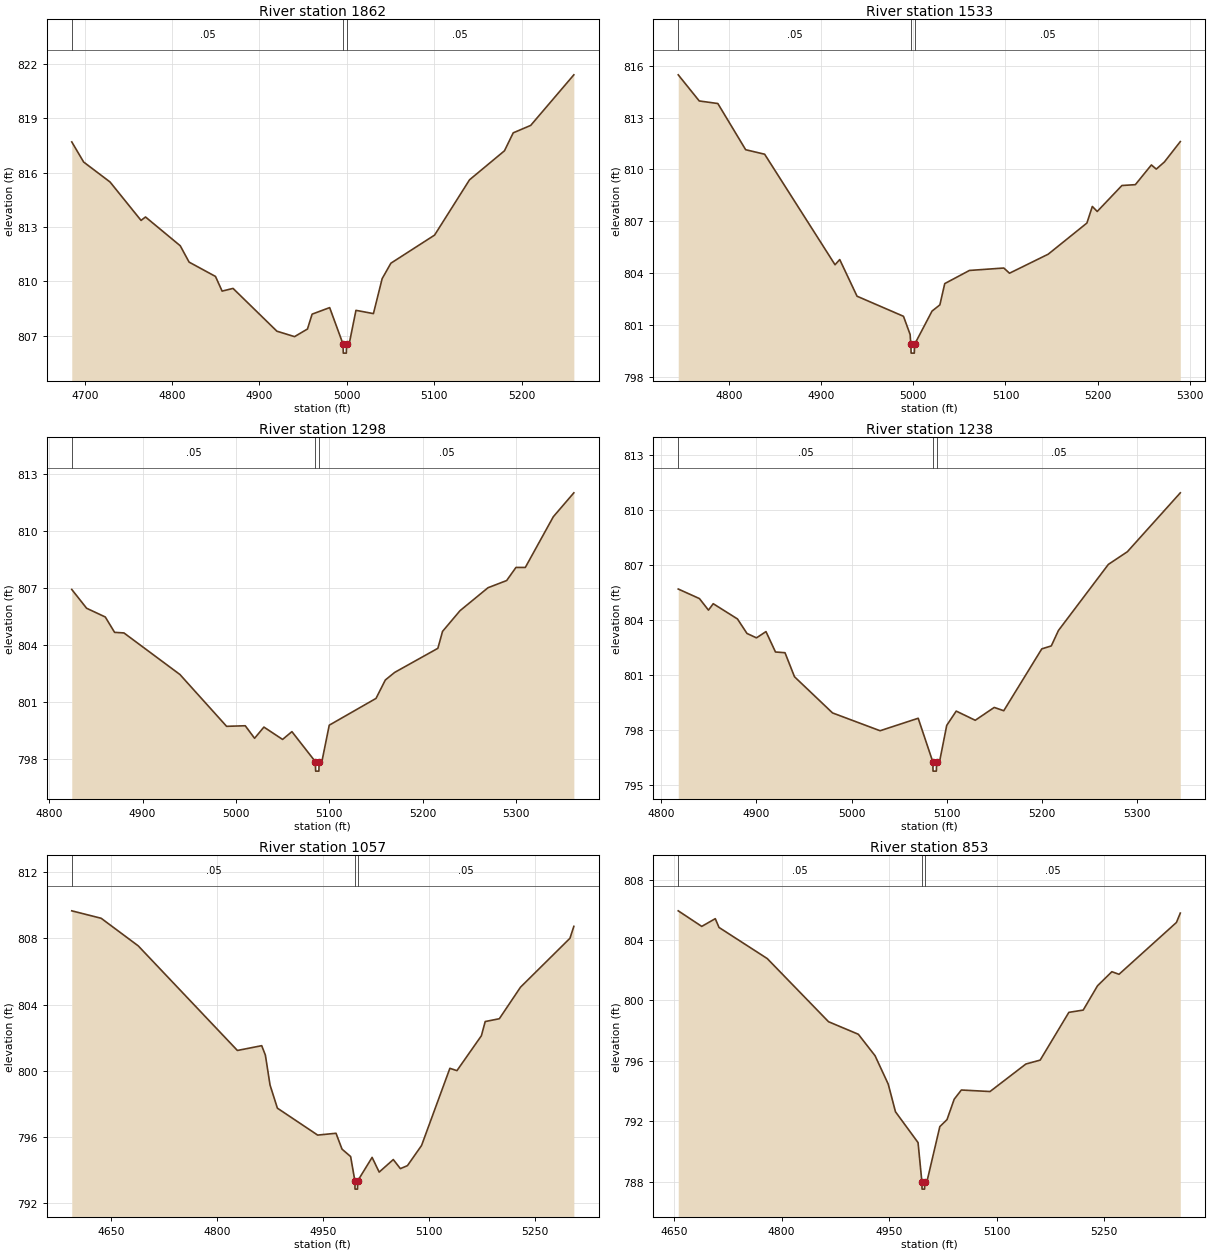
Type RM Length L Ch R = 1,1862,329,329,329
BEGIN DESCRIPTION:
MDW T 041 4.0
END DESCRIPTION:
XS GIS Cut Line= 3
      2293275.61      7094823.54      2293308.75      7094510.49
      2293307.08      7094250.60
#Sta/Elev= 30
  4685.2  817.69  4698.8  816.58  4729.0  815.48  4764.5  813.36  4769.6  813.55
  4809.4  811.96  4819.5  811.06  4849.7  810.27  4857.3  809.46  4869.8  809.61
  4920.0  807.25  4940.2  806.95  4955.0  807.37  4960.3  808.19  4980.4  808.55
  4995.7  806.54  4996.0  806.04  4999.5  806.04  4999.7  806.54  5002.7  806.54
  5010.5  808.40  5030.5  808.22  5040.5  810.15  5050.5  811.00  5100.5  812.55
  5140.5  815.60  5180.5  817.20  5190.5  818.19  5210.5  818.60  5259.9  821.39
#Mann=3,-1,0
  4685.2    0.05       0  4995.7   0.033       0  4999.7    0.05       0
Bank Sta=4995.7,4999.7
Exp/Cntr=0.3,0.1

Type RM Length L Ch R = 1,1533,235,235,235
BEGIN DESCRIPTION:
MDW T 041 3.5
END DESCRIPTION:
XS GIS Cut Line= 3
      2293563.16      7094812.65      2293594.16      7094559.34
      2293683.13      7094283.54
#Sta/Elev= 30
  4744.8  815.47  4767.6  813.96  4787.8  813.81  4818.0  811.14  4838.6  810.88
  4915.0  804.49  4920.1  804.79  4938.9  802.67  4989.3  801.51  4996.5  800.46
  4997.3  799.88  4997.6  799.38  5001.1  799.38  5001.3  799.88  5020.3  801.81
  5028.8  802.17  5034.1  803.40  5060.9  804.16  5098.2  804.30  5104.4  804.00
  5146.4  805.10  5188.4  806.90  5194.3  807.86  5199.6  807.57  5226.4  809.07
  5241.0  809.12  5258.4  810.26  5263.7  810.02  5272.5  810.43  5289.8  811.61
#Mann=3,-1,0
  4744.8    0.05       0  4997.3   0.033       0  5001.3    0.05       0
Bank Sta=4997.3,5001.3
Exp/Cntr=0.3,0.1

Type RM Length L Ch R = 1,1298,60,60,60
BEGIN DESCRIPTION:
MDW T 041 3.0
END DESCRIPTION:
XS GIS Cut Line= 3
      2293824.57      7094735.85      2293831.42      7094470.85
      2293836.90      7094198.00
#Sta/Elev= 30
  4824.1  806.91  4840.0  805.92  4860.0  805.46  4870.0  804.65  4880.0  804.62
  4940.0  802.43  4990.0  799.70  5010.0  799.73  5020.0  799.07  5030.0  799.66
  5050.0  799.01  5060.0  799.42  5085.1  797.84  5085.4  797.34  5088.9  797.34
  5089.1  797.84  5092.1  797.84  5100.0  799.76  5150.1  801.17  5160.1  802.14
  5170.1  802.54  5216.4  803.81  5221.4  804.70  5240.1  805.79  5270.1  807.00
  5290.1  807.38  5300.1  808.07  5310.1  808.07  5340.1  810.74  5362.1  812.00
#Mann=3,-1,0
  4824.1    0.05       0  5085.1   0.033       0  5089.1    0.05       0
Bank Sta=5085.1,5089.1
Exp/Cntr=0.3,0.1

Type RM Length L Ch R = 1,1238,181,181,181
BEGIN DESCRIPTION:
MDW T 041 2.5
END DESCRIPTION:
XS GIS Cut Line= 3
      2293882.90      7094742.25      2293891.13      7094470.17
      2293896.78      7094214.34
#Sta/Elev= 30
  4817.7  805.69  4840.0  805.17  4849.5  804.54  4854.5  804.89  4880.0  804.06
  4890.0  803.27  4900.0  803.03  4910.0  803.37  4920.0  802.26  4930.0  802.22
  4940.0  800.91  4980.0  798.94  5030.0  797.97  5070.1  798.65  5085.5  796.27
  5085.7  795.77  5089.2  795.77  5089.5  796.27  5092.5  796.27  5100.1  798.26
  5110.1  799.04  5130.1  798.54  5150.1  799.24  5160.1  799.06  5200.1  802.43
  5210.1  802.59  5217.6  803.43  5270.1  807.03  5290.1  807.72  5345.8  810.93
#Mann=3,-1,0
  4817.7    0.05       0  5085.5   0.033       0  5089.5    0.05       0
Bank Sta=5085.5,5089.5
Exp/Cntr=0.3,0.1

Type RM Length L Ch R = 1,1057,204,204,204
BEGIN DESCRIPTION:
MDW T 041 2.0
END DESCRIPTION:
XS GIS Cut Line= 3
      2293951.74      7094920.70      2294059.20      7094529.70
      2294067.61      7094224.52
#Sta/Elev= 30
  4594.5  809.67  4636.1  809.22  4688.6  807.55  4829.0  801.22  4863.4  801.51
  4868.6  800.94  4875.2  799.13  4885.6  797.73  4942.6  796.10  4968.6  796.21
  4977.1  795.25  4989.3  794.80  4995.3  793.33  4995.5  792.83  4999.0  792.83
  4999.3  793.33  5019.7  794.75  5029.7  793.86  5049.7  794.62  5059.7  794.07
  5069.7  794.25  5089.7  795.47  5129.8  800.14  5139.8  800.00  5174.4  802.11
  5179.8  802.97  5199.8  803.14  5229.8  805.05  5299.8  808.01  5305.3  808.73
#Mann=3,-1,0
  4594.5    0.05       0  4995.3    0.04       0  4999.3    0.05       0
Bank Sta=4995.3,4999.3
Exp/Cntr=0.3,0.1

Type RM Length L Ch R = 1,853,287,287,287
BEGIN DESCRIPTION:
MDW T 041 1.0
END DESCRIPTION:
XS GIS Cut Line= 3
      2294128.82      7094941.53      2294223.95      7094610.84
      2294214.77      7094254.56
#Sta/Elev= 30
  4655.9  805.93  4688.7  804.90  4707.6  805.41  4712.8  804.83  4780.1  802.77
  4865.6  798.59  4907.2  797.76  4930.5  796.34  4948.9  794.46  4959.0  792.63
  4990.5  790.59  4995.8  788.01  4996.1  787.51  4999.6  787.51  4999.8  788.01
  5002.9  788.01  5020.9  791.65  5030.9  792.11  5040.9  793.46  5050.9  794.07
  5090.9  793.97  5140.9  795.79  5160.9  796.05  5200.9  799.21  5220.9  799.36
  5240.9  800.97  5260.9  801.90  5270.9  801.73  5351.0  805.16  5356.4  805.78
#Mann=3,-1,0
  4655.9    0.05       0  4995.8    0.04       0  4999.8    0.05       0
Bank Sta=4995.8,4999.8
Exp/Cntr=0.3,0.1

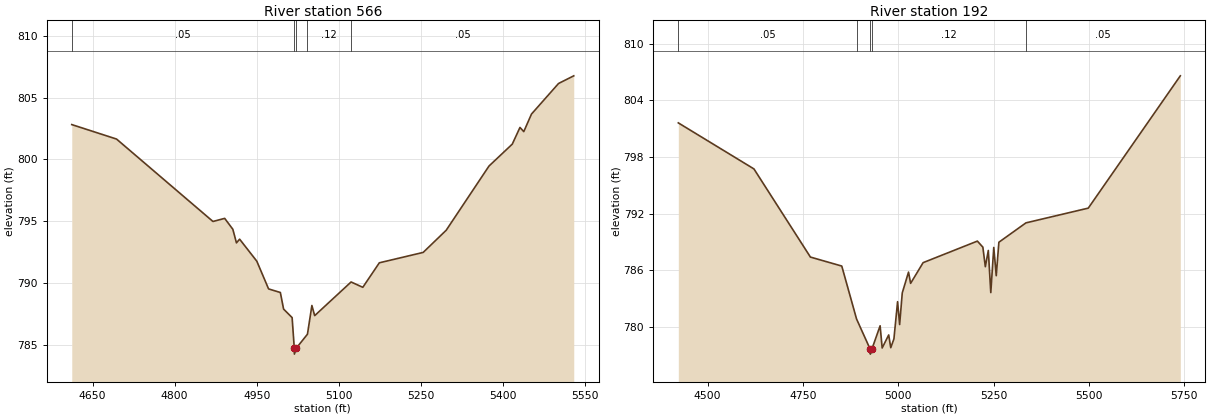
Type RM Length L Ch R = 1,566,374,374,374
BEGIN DESCRIPTION:
MDW T 041 0.5
END DESCRIPTION:
XS GIS Cut Line= 4
      2294251.72      7094963.97      2294459.93      7094607.93
      2294483.51      7094440.49      2294238.70      7094211.30
#Sta/Elev= 30
  4612.1  802.82  4693.9  801.65  4870.0  794.99  4891.4  795.24  4906.3  794.36
  4912.9  793.26  4918.7  793.56  4950.1  791.78  4971.6  789.54  4993.1  789.25
  4999.0  787.91  5014.6  787.22  5018.5  784.77  5018.7  784.27  5022.5  784.77
  5042.6  785.88  5050.7  788.20  5055.8  787.38  5122.3  790.10  5143.7  789.67
  5173.9  791.65  5254.0  792.49  5296.0  794.28  5374.2  799.47  5416.7  801.24
  5430.8  802.59  5437.7  802.25  5451.8  803.67  5501.2  806.14  5529.0  806.76
#Mann=5,-1,0
  4612.1    0.05       0  5018.5    0.04       0  5022.5    0.05       0
  5042.6    0.12       0  5122.3    0.05       0
Bank Sta=5018.5,5022.5
Exp/Cntr=0.3,0.1

Type RM Length L Ch R = 1,192,0,0,0
BEGIN DESCRIPTION:
MDW T 041 0.3
END DESCRIPTION:
XS GIS Cut Line= 4
      2294309.31      7094950.83      2294809.12      7094741.63
      2294765.07      7094642.22      2294253.64      7094215.39
#Sta/Elev= 30
  4423.2  801.60  4621.5  796.73  4769.7  787.40  4851.9  786.45  4890.7  780.85
  4926.7  777.63  4926.9  777.13  4930.7  777.63  4952.5  780.13  4957.9  777.78
  4975.0  779.16  4980.4  777.81  4988.7  778.74  4998.3  782.68  5003.7  780.26
  5010.6  783.61  5027.0  785.81  5032.5  784.62  5065.3  786.81  5207.6  789.09
  5222.0  788.45  5228.5  786.38  5236.3  788.10  5242.8  783.64  5250.6  788.42
  5257.1  785.43  5264.0  788.97  5335.0  791.02  5498.5  792.58  5739.9  806.58
#Mann=5,-1,0
  4423.2    0.05       0  4890.7    0.12       0  4926.7    0.07       0
  4930.7    0.12       0  5335.0    0.05       0
Bank Sta=4926.7,4930.7
Exp/Cntr=0.3,0.1

Chan Stop Cuts=-1