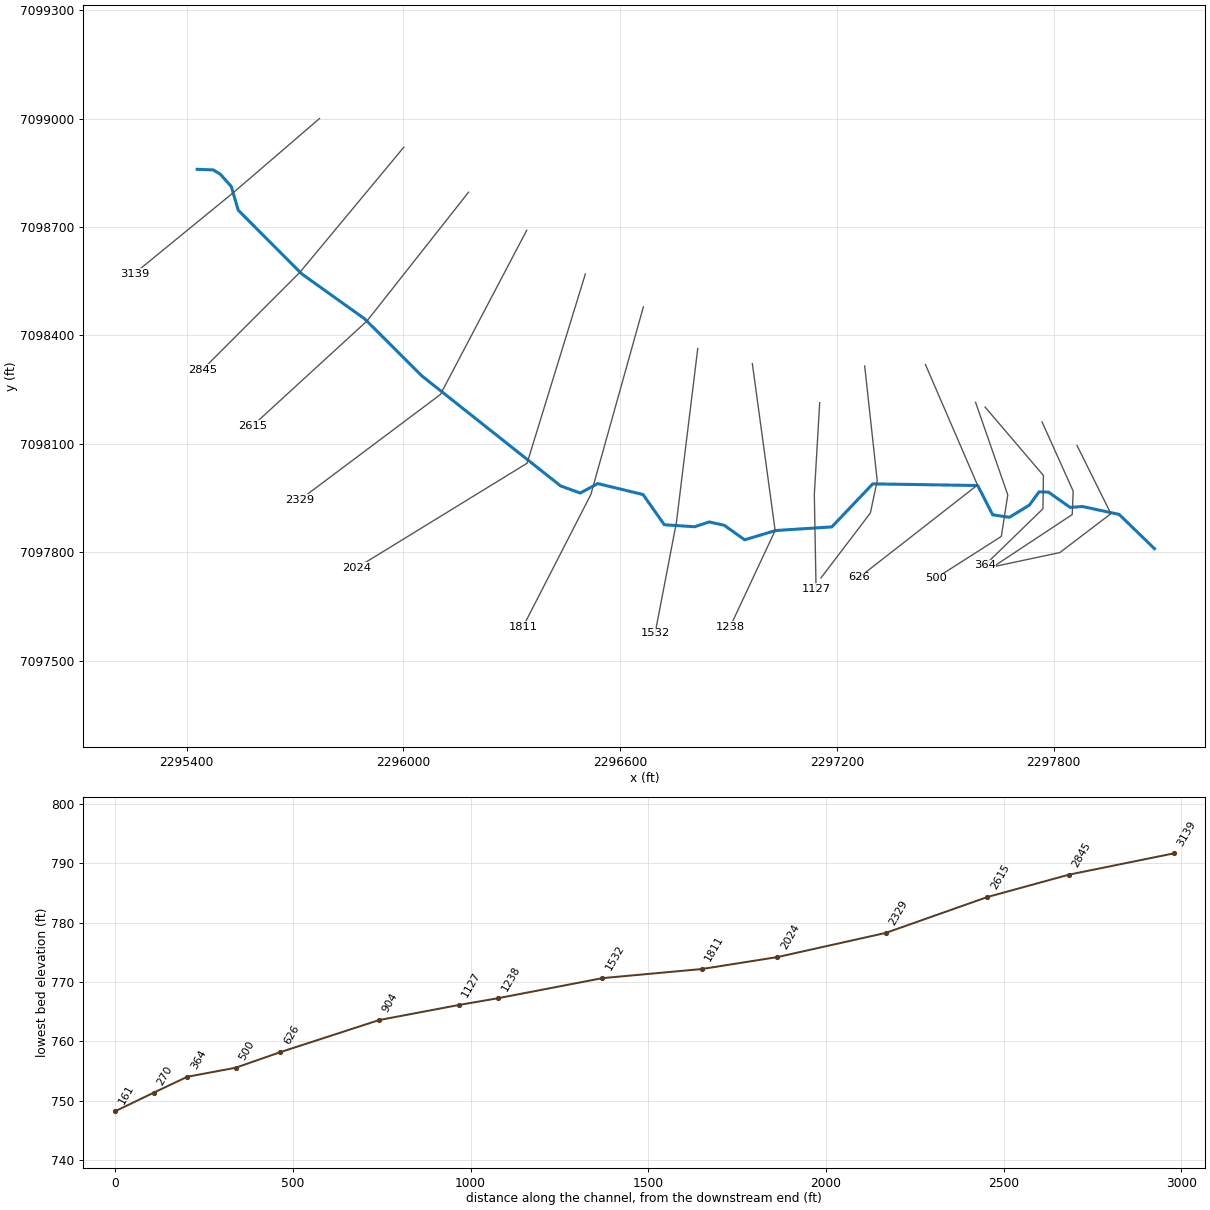
--- MDW T 042.prj (project) ---

Proj Title=MDW T 042 Base Level Engineering
Current Plan=p01
Default Exp/Contr=0.3,0.1
English Units
Geom File=g01
Flow File=f01
Plan File=p01
BEGIN DESCRIPTION:
MDW T 042
END DESCRIPTION:

--- MDW T 042.p01 (plan) ---

Plan Title=Multiple Run
Short Identifier=Multiple
Geom File=g01
Flow File=f01
Subcritical Flow
K Sum by GR= 0
Std Step Tol= 0.01
Critical Tol= 0.01
Num of Std Step Trials= 20
Max Error Tol= 0.3
Flow Tol Ratio= 0.001
Split Flow NTrial= 30
Split Flow Tol= 0.02
Split Flow Ratio= 0.02
Log Output Level= 0
Friction Slope Method= 1
Unsteady Friction Slope Method= 2
Unsteady Bridges Friction Slope Method= 1
Parabolic Critical Depth
Global Vel Dist=  1 , 1 , 1
Global Log Level= 0
CheckData=True
Encroach Param= -1, 0, 0, 0
BEGIN DESCRIPTION:
Multiple Run
END DESCRIPTION:

--- MDW T 042.f01 (steady flow) ---

Flow Title=Multiple
Number of Profiles=7
Profile Names=10-year,25-year,50-year,1pct_min,100-year,1pct_plu,500-year
River Rch & RM= MDW T 042,Reach-1,3139
     253     331     394     233     466     929     652
Boundary for River Rch & Prof#=MDW T 042,Reach-1,1
Up Type=0
Dn Type=3
Dn Slope=0.005
Boundary for River Rch & Prof#=MDW T 042,Reach-1,2
Up Type=0
Dn Type=3
Dn Slope=0.005
Boundary for River Rch & Prof#=MDW T 042,Reach-1,3
Up Type=0
Dn Type=3
Dn Slope=0.005
Boundary for River Rch & Prof#=MDW T 042,Reach-1,4
Up Type=0
Dn Type=3
Dn Slope=0.005
Boundary for River Rch & Prof#=MDW T 042,Reach-1,5
Up Type=0
Dn Type=3
Dn Slope=0.005
Boundary for River Rch & Prof#=MDW T 042,Reach-1,6
Up Type=0
Dn Type=3
Dn Slope=0.005
Boundary for River Rch & Prof#=MDW T 042,Reach-1,7
Up Type=0
Dn Type=3
Dn Slope=0.005

--- MDW T 042.g01 (geometry) ---

Geom Title=Existing Conditions

River Reach=MDW T 042,Reach-1
Reach XY= 30
      2295429.00      7098860.00      2295473.13      7098858.44
      2295492.78      7098846.73      2295523.29      7098812.51
      2295542.63      7098746.80      2295718.19      7098570.77
      2295892.21      7098446.37      2296050.44      7098288.53
      2296435.02      7097983.60      2296489.46      7097963.84
      2296537.80      7097990.01      2296663.38      7097959.65
      2296722.10      7097876.08      2296806.06      7097870.50
      2296846.52      7097883.78      2296888.11      7097874.56
      2296944.46      7097834.39      2297030.33      7097859.97
      2297185.87      7097870.09      2297299.23      7097989.21
      2297589.77      7097984.67      2297631.20      7097903.60
      2297677.28      7097896.57      2297732.87      7097930.38
      2297759.56      7097967.11      2297785.73      7097966.30
      2297845.70      7097924.03      2297879.96      7097926.52
      2297981.45      7097904.54      2298079.00      7097810.00

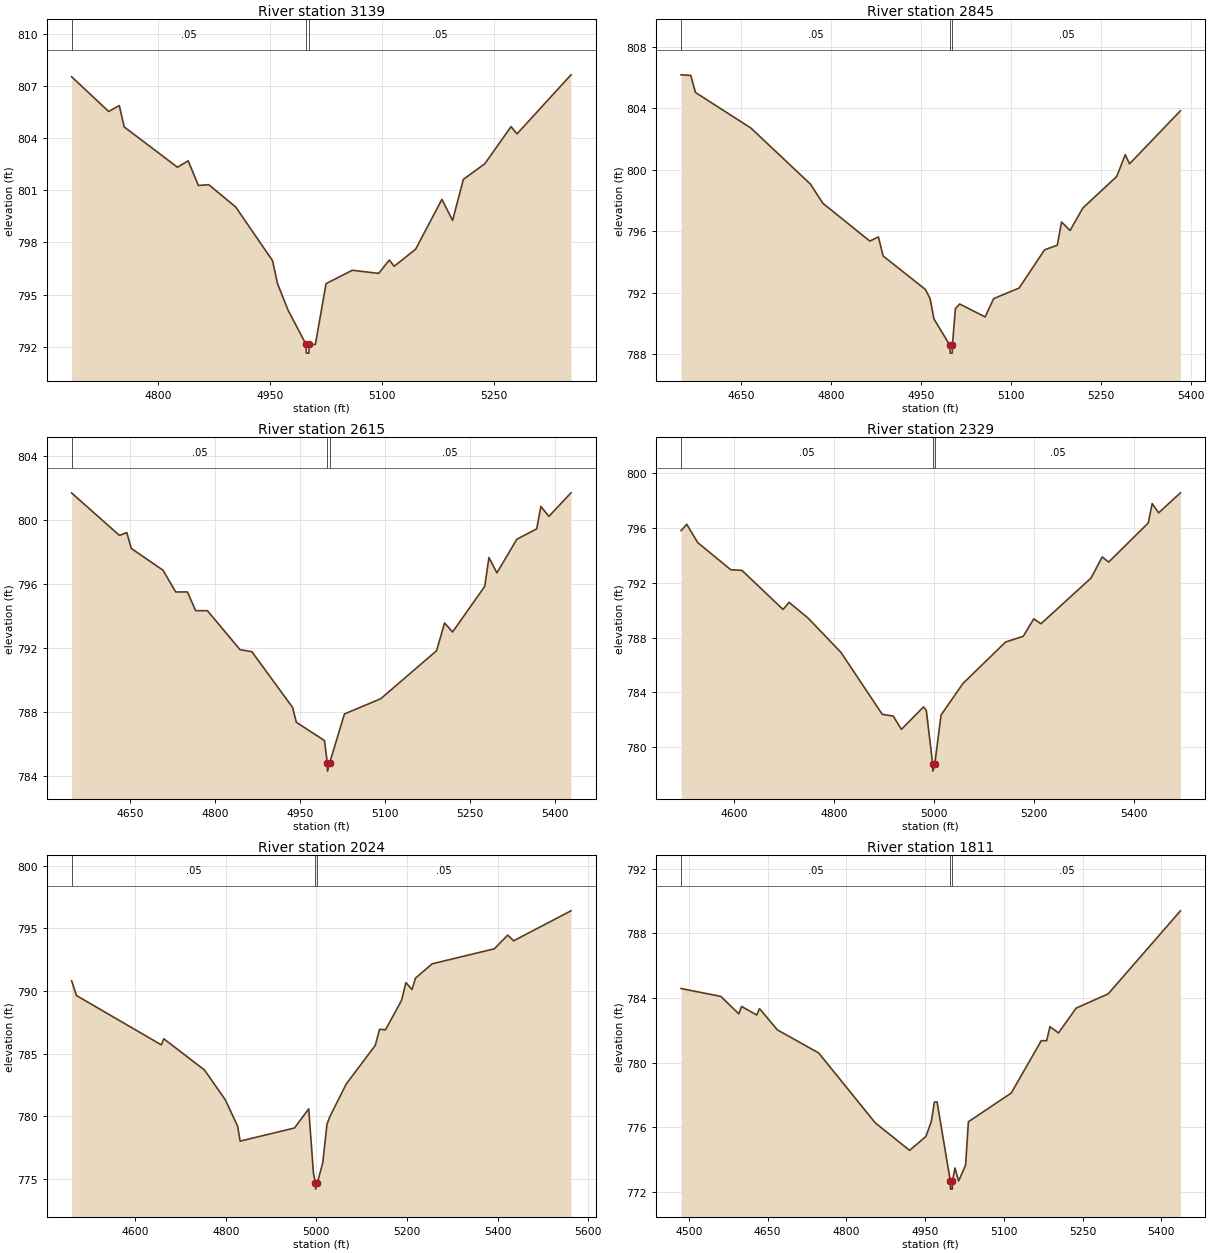
Type RM Length L Ch R = 1,3139,294,294,294
BEGIN DESCRIPTION:
MDW T 042 8.0
END DESCRIPTION:
XS GIS Cut Line= 3
      2295767.68      7099000.68      2295528.15      7098794.73
      2295255.19      7098571.52
#Sta/Elev= 30
  4684.1  807.54  4733.7  805.54  4747.9  805.88  4754.5  804.65  4825.8  802.33
  4840.1  802.70  4853.8  801.28  4867.6  801.33  4903.8  800.04  4953.1  796.95
  4959.7  795.63  4974.0  794.09  4998.0  792.13  4998.3  791.63  5001.8  791.63
  5002.0  792.13  5010.4  792.13  5024.7  795.63  5059.9  796.40  5095.1  796.22
  5109.4  796.99  5115.9  796.63  5144.6  797.61  5179.8  800.48  5194.1  799.27
  5208.5  801.63  5237.2  802.53  5272.4  804.67  5280.3  804.25  5352.6  807.65
#Mann=3,-1,0
  4684.1    0.05       0  4998.0    0.04       0  5002.0    0.05       0
Bank Sta=4998,5002
Exp/Cntr=0.3,0.1

Type RM Length L Ch R = 1,2845,230,230,230
BEGIN DESCRIPTION:
MDW T 042 7.0
END DESCRIPTION:
XS GIS Cut Line= 3
      2296001.07      7098921.30      2295713.66      7098575.30
      2295443.69      7098305.33
#Sta/Elev= 30
  4550.2  806.19  4566.3  806.15  4574.2  805.04  4666.6  802.72  4765.6  799.07
  4786.4  797.82  4864.5  795.36  4878.8  795.63  4886.7  794.39  4957.0  792.21
  4964.8  791.62  4971.3  790.29  4998.0  788.56  4998.3  788.06  5001.8  788.06
  5002.0  788.56  5007.0  790.96  5014.1  791.26  5056.5  790.42  5070.7  791.61
  5113.1  792.30  5155.5  794.79  5176.7  795.09  5183.8  796.60  5198.0  796.05
  5219.2  797.51  5275.7  799.57  5289.9  800.99  5297.0  800.39  5381.8  803.85
#Mann=3,-1,0
  4550.2    0.05       0  4998.0    0.04       0  5002.0    0.05       0
Bank Sta=4998,5002
Exp/Cntr=0.3,0.1

Type RM Length L Ch R = 1,2615,286,286,286
BEGIN DESCRIPTION:
MDW T 042 6.0
END DESCRIPTION:
XS GIS Cut Line= 3
      2296180.11      7098796.53      2295899.09      7098440.21
      2295583.11      7098150.63
#Sta/Elev= 30
  4546.2  801.66  4630.7  799.01  4643.7  799.19  4651.5  798.20  4707.6  796.84
  4730.1  795.48  4750.9  795.48  4765.3  794.31  4786.1  794.31  4843.9  791.87
  4864.7  791.75  4936.6  788.27  4943.3  787.34  4993.0  786.20  4998.0  784.79
  4998.3  784.29  5002.0  784.79  5028.3  787.86  5092.4  788.81  5191.1  791.81
  5205.2  793.54  5219.4  792.98  5276.2  795.83  5283.6  797.63  5297.7  796.67
  5332.9  798.77  5368.0  799.42  5375.4  800.82  5389.6  800.20  5428.6  801.67
#Mann=3,-1,0
  4546.2    0.05       0  4998.0    0.04       0  5002.0    0.05       0
Bank Sta=4998,5002
Exp/Cntr=0.3,0.1

Type RM Length L Ch R = 1,2329,305,305,305
BEGIN DESCRIPTION:
MDW T 042 5.0
END DESCRIPTION:
XS GIS Cut Line= 3
      2296341.27      7098691.25      2296102.31      7098236.62
      2295713.79      7097945.34
#Sta/Elev= 30
  4494.5  795.82  4505.8  796.28  4527.9  794.94  4594.0  792.96  4616.1  792.92
  4698.6  790.06  4710.6  790.58  4748.3  789.44  4814.5  786.92  4897.0  782.40
  4919.0  782.27  4935.4  781.30  4979.5  782.94  4985.2  782.69  4998.0  778.75
  4998.3  778.25  5002.0  778.75  5014.7  782.35  5058.4  784.65  5143.8  787.68
  5179.2  788.10  5200.1  789.37  5214.7  789.02  5314.7  792.35  5337.2  793.90
  5350.1  793.52  5429.3  796.38  5437.2  797.80  5450.1  797.12  5493.7  798.58
#Mann=3,-1,0
  4494.5    0.05       0  4998.0    0.04       0  5002.0    0.05       0
Bank Sta=4998,5002
Exp/Cntr=0.3,0.1

Type RM Length L Ch R = 1,2024,213,213,213
BEGIN DESCRIPTION:
MDW T 042 4.0
END DESCRIPTION:
XS GIS Cut Line= 3
      2296503.58      7098570.23      2296342.25      7098046.34
      2295869.89      7097756.43
#Sta/Elev= 30
  4459.7  790.81  4470.4  789.63  4657.8  785.69  4663.1  786.18  4752.9  783.69
  4799.0  781.31  4826.2  779.20  4831.7  778.01  4951.7  779.06  4983.1  780.59
  4993.6  775.43  4998.0  774.68  4998.3  774.18  5002.0  774.68  5014.0  776.26
  5023.4  779.35  5029.4  779.94  5066.1  782.58  5130.0  785.65  5139.6  786.94
  5152.5  786.89  5188.0  789.24  5197.6  790.66  5211.1  790.11  5218.9  791.02
  5255.6  792.16  5392.9  793.36  5422.3  794.45  5435.5  794.00  5562.1  796.39
#Mann=3,-1,0
  4459.7    0.05       0  4998.0    0.04       0  5002.0    0.05       0
Bank Sta=4998,5002
Exp/Cntr=0.3,0.1

Type RM Length L Ch R = 1,1811,279,279,279
BEGIN DESCRIPTION:
MDW T 042 3.0
END DESCRIPTION:
XS GIS Cut Line= 3
      2296664.16      7098479.05      2296518.85      7097959.85
      2296330.88      7097593.29
#Sta/Elev= 30
  4485.2  784.59  4561.0  784.10  4595.2  783.02  4600.4  783.48  4629.3  782.95
  4634.5  783.35  4668.6  782.03  4747.3  780.60  4854.8  776.28  4920.4  774.57
  4951.5  775.43  4961.9  776.37  4967.6  777.56  4972.8  777.57  4998.0  772.67
  4998.3  772.17  5001.8  772.17  5002.0  772.67  5006.9  773.48  5013.8  772.67
  5027.1  773.66  5032.4  776.34  5114.1  778.12  5171.2  781.36  5181.5  781.36
  5187.8  782.23  5204.0  781.84  5237.8  783.38  5298.7  784.26  5436.3  789.40
#Mann=3,-1,0
  4485.2    0.05       0  4998.0    0.04       0  5002.0    0.05       0
Bank Sta=4998,5002
Exp/Cntr=0.3,0.1

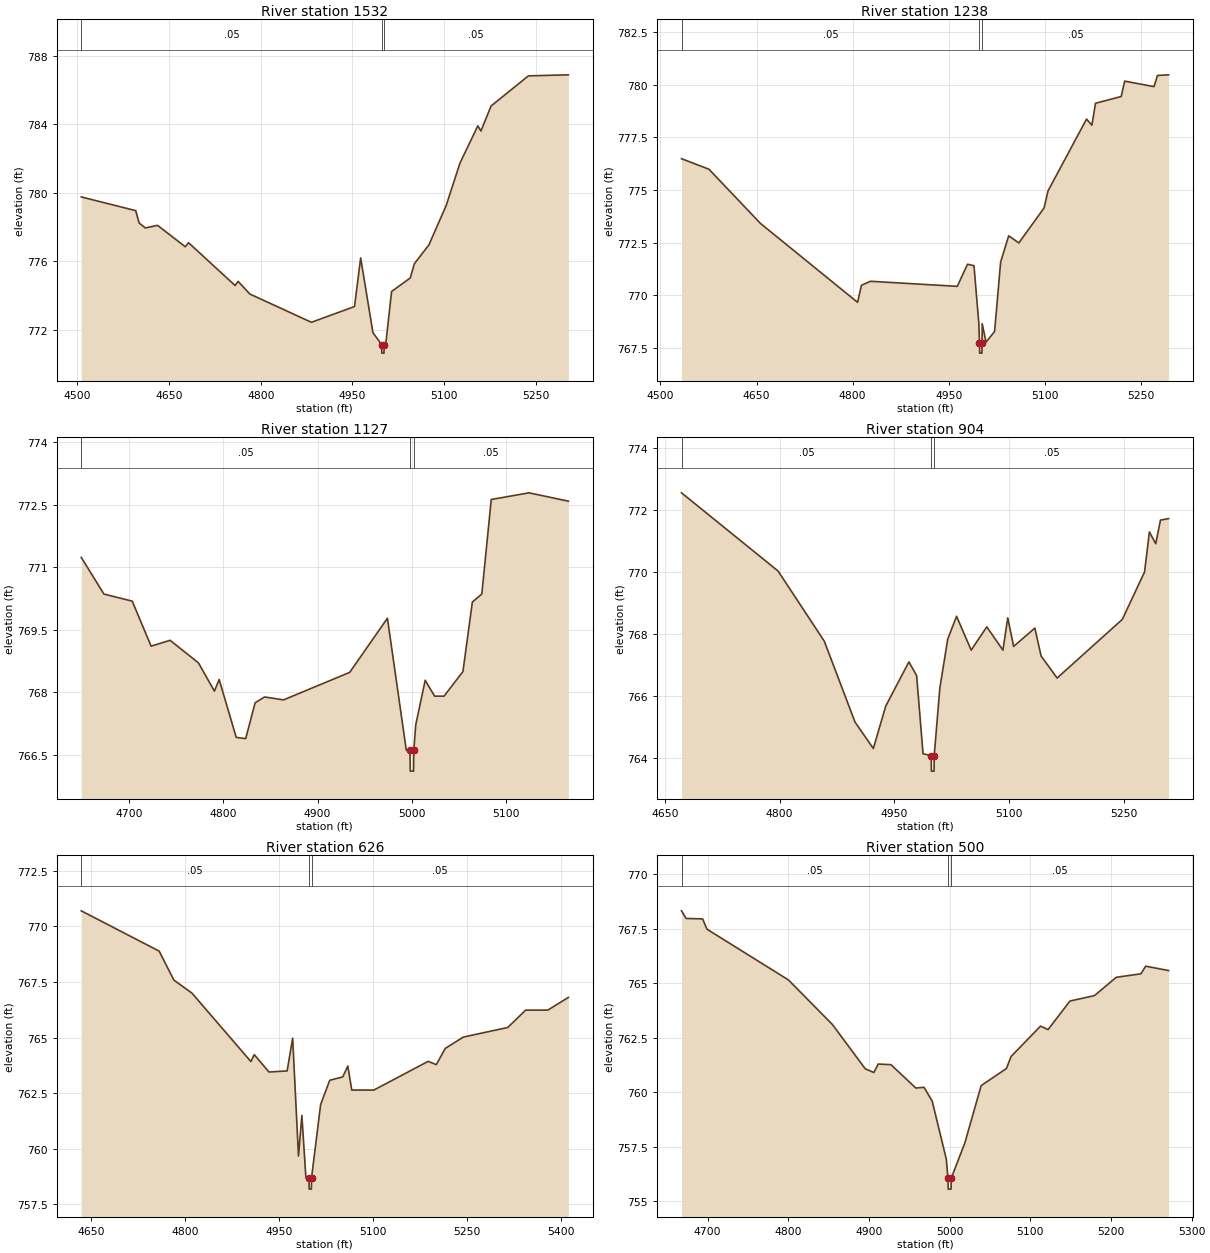
Type RM Length L Ch R = 1,1532,294,294,294
BEGIN DESCRIPTION:
MDW T 042 2.0
END DESCRIPTION:
XS GIS Cut Line= 3
      2296814.79      7098363.99      2296755.69      7097882.57
      2296696.74      7097575.81
#Sta/Elev= 30
  4506.2  779.76  4595.3  778.96  4600.9  778.24  4611.0  777.95  4631.1  778.10
  4676.6  776.85  4681.7  777.09  4758.0  774.59  4763.0  774.83  4782.2  774.09
  4883.0  772.44  4953.5  773.36  4963.6  776.20  4983.7  771.83  4998.0  771.14
  4998.3  770.64  5001.8  770.64  5002.0  771.14  5004.6  771.14  5014.2  774.24
  5044.8  775.03  5051.5  775.86  5075.3  776.96  5103.5  779.25  5126.2  781.74
  5155.4  783.91  5160.5  783.61  5177.1  785.07  5238.2  786.83  5303.6  786.89
#Mann=3,-1,0
  4506.2    0.05       0  4998.0    0.04       0  5002.0    0.05       0
Bank Sta=4998,5002
Exp/Cntr=0.3,0.1

Type RM Length L Ch R = 1,1238,111,111,111
BEGIN DESCRIPTION:
MDW T 042 1.5
END DESCRIPTION:
XS GIS Cut Line= 3
      2296965.84      7098322.38      2297029.02      7097859.97
      2296904.52      7097593.97
#Sta/Elev= 30
  4532.8  776.49  4575.6  775.99  4656.3  773.41  4807.7  769.67  4813.7  770.48
  4827.9  770.67  4963.3  770.43  4979.3  771.48  4989.4  771.41  4997.0  768.66
  4998.0  767.76  4998.3  767.26  5001.8  767.26  5002.0  767.76  5002.2  768.66
  5008.2  767.78  5021.6  768.29  5031.0  771.58  5043.6  772.83  5059.4  772.49
  5098.8  774.15  5105.0  774.96  5165.1  778.37  5173.5  778.08  5179.1  779.12
  5219.2  779.44  5224.7  780.17  5270.4  779.91  5275.9  780.44  5293.2  780.47
#Mann=3,-1,0
  4532.8    0.05       0  4998.0    0.04       0  5002.0    0.05       0
Bank Sta=4998,5002
Exp/Cntr=0.3,0.1

Type RM Length L Ch R = 1,1127,223,223,223
BEGIN DESCRIPTION:
Mapping XS ceef6b77
END DESCRIPTION:
XS GIS Cut Line= 3
      2297152.34      7098213.92      2297137.46      7097959.27
      2297142.32      7097698.30
#Sta/Elev= 30
  4649.7  771.24  4673.7  770.36  4703.7  770.19  4723.7  769.11  4743.8  769.25
  4773.8  768.71  4790.8  768.03  4795.8  768.31  4813.9  766.92  4823.9  766.89
  4833.9  767.75  4843.9  767.89  4864.0  767.82  4934.1  768.48  4974.1  769.78
  4994.1  766.61  4998.0  766.61  4998.3  766.11  5001.8  766.11  5002.0  766.61
  5004.1  767.22  5014.1  768.29  5024.1  767.91  5034.1  767.91  5054.1  768.50
  5064.1  770.17  5074.1  770.36  5084.1  772.63  5124.1  772.79  5165.8  772.59
#Mann=3,-1,0
  4649.7    0.05       0  4998.0    0.04       0  5002.0    0.05       0
Bank Sta=4998,5002
Exp/Cntr=0.3,0.1

Type RM Length L Ch R = 1,904,278,278,278
BEGIN DESCRIPTION:
MDW T 042 1.0
END DESCRIPTION:
XS GIS Cut Line= 4
      2297276.88      7098315.45      2297311.58      7097998.18
      2297292.61      7097908.47      2297155.92      7097728.82
#Sta/Elev= 30
  4671.7  772.56  4797.9  770.04  4858.3  767.78  4898.5  765.17  4922.4  764.32
  4938.7  765.69  4968.9  767.11  4979.0  766.67  4987.4  764.15  4998.0  764.09
  4998.3  763.59  5001.8  763.59  5002.0  764.09  5009.4  766.28  5019.7  767.85
  5031.2  768.58  5050.3  767.49  5070.7  768.24  5091.8  767.49  5098.1  768.53
  5105.8  767.61  5133.5  768.20  5141.7  767.30  5162.6  766.59  5247.8  768.48
  5276.9  770.01  5283.2  771.30  5291.5  770.92  5297.7  771.68  5308.3  771.73
#Mann=3,-1,0
  4671.7    0.05       0  4998.0    0.04       0  5002.0    0.05       0
Bank Sta=4998,5002
Exp/Cntr=0.3,0.1

Type RM Length L Ch R = 1,626,126,126,126
BEGIN DESCRIPTION:
MDW T 042 0.5
END DESCRIPTION:
XS GIS Cut Line= 3
      2297444.96      7098319.90      2297589.18      7097985.95
      2297262.71      7097731.14
#Sta/Elev= 30
  4634.3  770.69  4758.7  768.88  4782.2  767.58  4811.2  766.99  4905.2  763.92
  4910.6  764.23  4934.1  763.45  4963.1  763.50  4971.9  764.97  4981.2  759.68
  4986.6  761.50  4993.1  758.69  4998.0  758.69  4998.3  758.19  5001.8  758.19
  5002.0  758.69  5016.6  761.99  5031.1  763.08  5051.9  763.23  5060.0  763.72
  5066.3  762.64  5101.6  762.64  5188.4  763.93  5201.3  763.78  5215.6  764.51
  5244.5  765.02  5315.4  765.45  5344.0  766.23  5379.3  766.23  5412.2  766.80
#Mann=3,-1,0
  4634.3    0.05       0  4998.0    0.04       0  5002.0    0.05       0
Bank Sta=4998,5002
Exp/Cntr=0.3,0.1

Type RM Length L Ch R = 1,500,136,136,136
BEGIN DESCRIPTION:
Mapping XS bd306b7e
END DESCRIPTION:
XS GIS Cut Line= 4
      2297583.81      7098215.14      2297673.03      7097958.72
      2297655.27      7097843.80      2297473.22      7097727.70
#Sta/Elev= 30
  4667.7  768.33  4673.4  767.98  4693.9  767.96  4699.2  767.49  4800.2  765.16
  4854.6  763.12  4895.5  761.08  4906.1  760.91  4911.5  761.30  4927.3  761.27
  4958.1  760.20  4968.3  760.23  4978.4  759.60  4995.9  756.94  4998.0  756.06
  4998.3  755.56  5001.8  755.56  5002.0  756.06  5018.9  757.68  5039.1  760.31
  5070.3  761.09  5076.3  761.65  5112.7  763.04  5122.0  762.88  5149.1  764.19
  5179.5  764.44  5206.6  765.28  5237.1  765.44  5243.0  765.79  5271.4  765.59
#Mann=3,-1,0
  4667.7    0.05       0  4998.0   0.033       0  5002.0    0.05       0
Bank Sta=4998,5002
Exp/Cntr=0.3,0.1

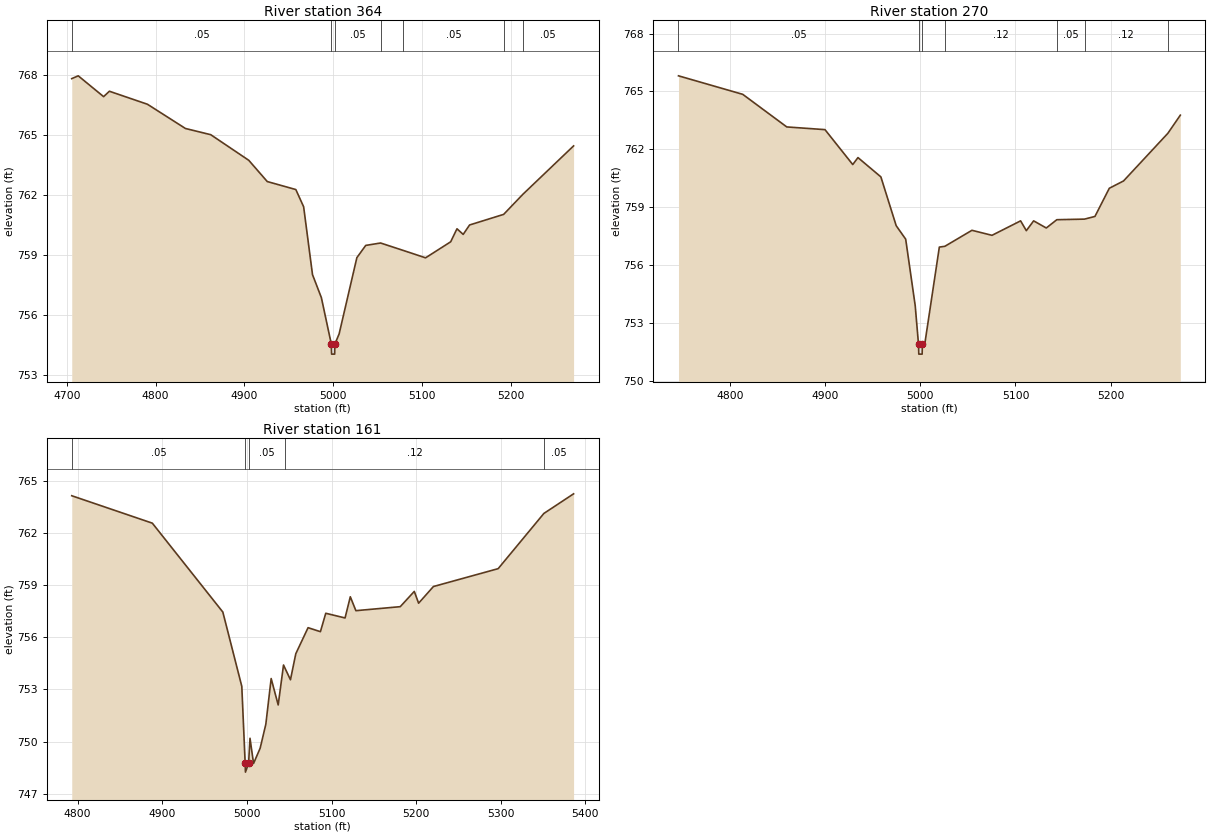
Type RM Length L Ch R = 1,364,94,94,94
BEGIN DESCRIPTION:
Mapping XS 4604058a
END DESCRIPTION:
XS GIS Cut Line= 4
      2297610.26      7098201.74      2297771.70      7098012.51
      2297770.46      7097920.30      2297609.33      7097763.91
#Sta/Elev= 30
  4705.5  767.80  4712.8  767.94  4741.4  766.90  4747.9  767.17  4790.8  766.52
  4833.6  765.31  4862.1  765.00  4905.0  763.72  4925.8  762.66  4958.0  762.26
  4966.8  761.40  4976.8  758.01  4986.8  756.86  4998.0  754.54  4998.3  754.04
  5001.8  754.04  5002.0  754.54  5006.8  755.05  5026.8  758.86  5036.8  759.47
  5053.5  759.59  5079.0  759.22  5104.2  758.85  5132.5  759.65  5139.6  760.30
  5146.6  760.02  5153.8  760.49  5192.2  761.02  5213.8  762.02  5271.0  764.44
#Mann=7,-1,0
  4705.5    0.05       0  4998.0   0.033       0  5002.0    0.05       0
  5053.5    0.12       0  5079.0    0.05       0  5192.2    0.12       0
  5213.8    0.05       0
Bank Sta=4998,5002
Exp/Cntr=0.3,0.1

Type RM Length L Ch R = 1,270,109,109,109
BEGIN DESCRIPTION:
Mapping XS 8dee79c3
END DESCRIPTION:
XS GIS Cut Line= 4
      2297768.01      7098160.50      2297854.09      7097969.20
      2297851.47      7097904.25      2297640.28      7097764.71
#Sta/Elev= 30
  4745.5  765.81  4813.1  764.85  4859.4  763.16  4899.6  763.02  4928.8  761.21
  4934.3  761.57  4958.4  760.57  4974.5  758.04  4984.5  757.34  4994.5  753.90
  4998.0  751.88  4998.3  751.38  5001.8  751.38  5002.0  751.88  5004.5  751.88
  5019.9  756.93  5025.7  756.97  5054.2  757.80  5075.3  757.54  5105.4  758.29
  5111.4  757.78  5119.1  758.29  5132.4  757.92  5143.5  758.35  5172.6  758.38
  5183.6  758.52  5198.7  759.98  5213.7  760.36  5260.3  762.83  5273.4  763.77
#Mann=7,-1,0
  4745.5    0.05       0  4998.0   0.033       0  5002.0    0.05       0
  5025.7    0.12       0  5143.5    0.05       0  5172.6    0.12       0
  5260.3    0.05       0
Bank Sta=4998,5002
Exp/Cntr=0.3,0.1

Type RM Length L Ch R = 1,161,0,0,0
BEGIN DESCRIPTION:
MDW T 042 0.3
END DESCRIPTION:
XS GIS Cut Line= 4
      2297864.82      7098095.27      2297958.52      7097906.64
      2297817.35      7097799.10      2297617.03      7097756.41
#Sta/Elev= 30
  4793.1  764.16  4888.3  762.58  4971.6  757.46  4994.0  753.18  4998.0  748.74
  4998.3  748.24  5002.0  748.74  5003.7  750.19  5007.9  748.74  5015.7  749.62
  5022.4  751.00  5028.7  753.63  5037.0  752.11  5043.3  754.41  5045.3  754.20
  5051.5  753.56  5057.8  755.06  5072.3  756.56  5086.9  756.33  5093.2  757.39
  5116.0  757.12  5122.2  758.34  5128.8  757.54  5181.2  757.77  5197.8  758.65
  5202.9  757.97  5220.4  758.93  5296.9  759.96  5350.9  763.14  5386.0  764.27
#Mann=5,-1,0
  4793.1    0.05       0  4998.0   0.033       0  5002.0    0.05       0
  5045.3    0.12       0  5350.9    0.05       0
Bank Sta=4998,5002
Exp/Cntr=0.3,0.1

Chan Stop Cuts=-1