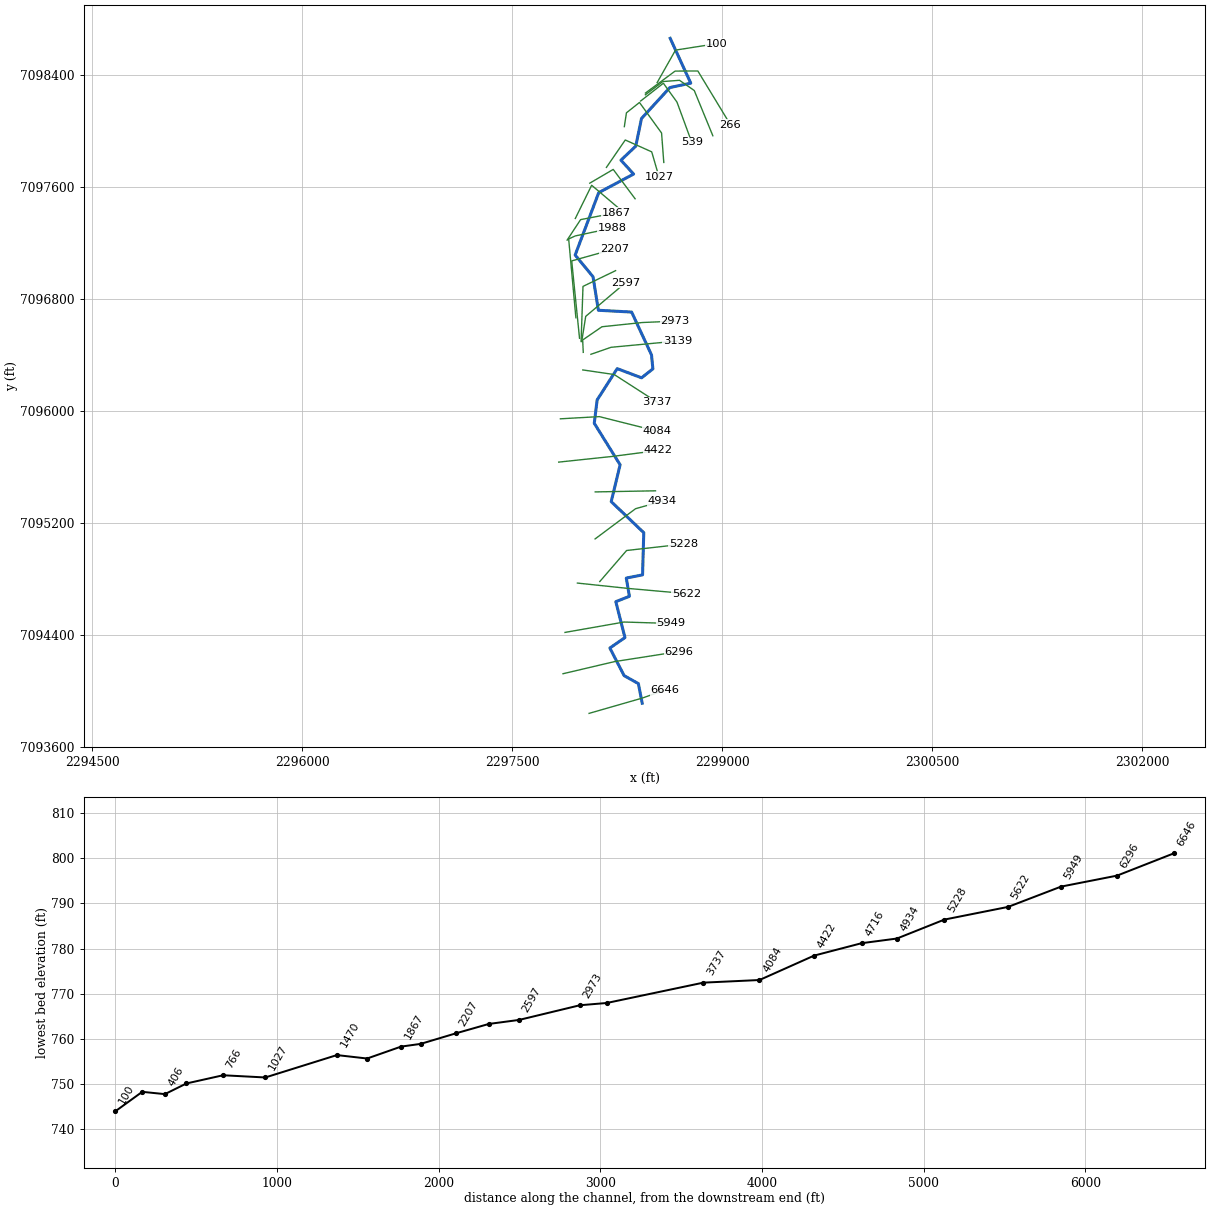
--- MDW T 043.prj (project) ---

Proj Title=MDW T 043 Base Level Engineering
Current Plan=p01
Default Exp/Contr=0.3,0.1
English Units
Geom File=g01
Flow File=f01
Plan File=p01
BEGIN DESCRIPTION:
MDW T 043
END DESCRIPTION:

--- MDW T 043.p01 (plan) ---

Plan Title=Multiple Run
Short Identifier=Multiple
Geom File=g01
Flow File=f01
Subcritical Flow
K Sum by GR= 0
Std Step Tol= 0.01
Critical Tol= 0.01
Num of Std Step Trials= 20
Max Error Tol= 0.3
Flow Tol Ratio= 0.001
Split Flow NTrial= 30
Split Flow Tol= 0.02
Split Flow Ratio= 0.02
Log Output Level= 0
Friction Slope Method= 1
Unsteady Friction Slope Method= 2
Unsteady Bridges Friction Slope Method= 1
Parabolic Critical Depth
Global Vel Dist=  1 , 1 , 1
Global Log Level= 0
CheckData=True
Encroach Param= -1, 0, 0, 0
BEGIN DESCRIPTION:
Multiple Run
END DESCRIPTION:

--- MDW T 043.f01 (steady flow) ---

Flow Title=Multiple
Number of Profiles=7
Profile Names=10-year,25-year,50-year,1pct_min,100-year,1pct_plu,500-year
River Rch & RM= MDW T 043,Reach-1,6646
     914    1336    1711    1092    2178    4346    3535
River Rch & RM= MDW T 043,Reach-1,4934
     693     977    1218     756    1509    3011    2319
River Rch & RM= MDW T 043,Reach-1,766
     737    1041    1301     808    1613    3218    2484
Boundary for River Rch & Prof#=MDW T 043,Reach-1,1
Up Type=0
Dn Type=3
Dn Slope=0.02
Boundary for River Rch & Prof#=MDW T 043,Reach-1,2
Up Type=0
Dn Type=3
Dn Slope=0.02
Boundary for River Rch & Prof#=MDW T 043,Reach-1,3
Up Type=0
Dn Type=3
Dn Slope=0.02
Boundary for River Rch & Prof#=MDW T 043,Reach-1,4
Up Type=0
Dn Type=3
Dn Slope=0.02
Boundary for River Rch & Prof#=MDW T 043,Reach-1,5
Up Type=0
Dn Type=3
Dn Slope=0.02
Boundary for River Rch & Prof#=MDW T 043,Reach-1,6
Up Type=0
Dn Type=3
Dn Slope=0.02
Boundary for River Rch & Prof#=MDW T 043,Reach-1,7
Up Type=0
Dn Type=3
Dn Slope=0.02

--- MDW T 043.g01 (geometry) ---

Geom Title=Existing Conditions

River Reach=MDW T 043,Reach-1
Reach XY= 30
      2298429.00      7093910.00      2298401.62      7094050.21
      2298299.78      7094107.17      2298197.96      7094304.38
      2298305.73      7094379.08      2298240.45      7094635.53
      2298337.67      7094673.76      2298315.21      7094804.25
      2298431.53      7094827.09      2298440.09      7095128.46
      2298207.63      7095350.30      2298271.19      7095613.41
      2298086.53      7095909.99      2298106.95      7096076.49
      2298250.33      7096300.46      2298424.37      7096234.71
      2298505.30      7096298.74      2298495.53      7096398.20
      2298353.43      7096704.55      2298115.89      7096717.32
      2298077.67      7096956.61      2297950.04      7097112.08
      2298118.41      7097557.64      2298367.60      7097690.38
      2298276.83      7097789.53      2298383.13      7097889.59
      2298423.67      7098086.86      2298626.57      7098308.38
      2298775.73      7098339.88      2298629.00      7098660.00

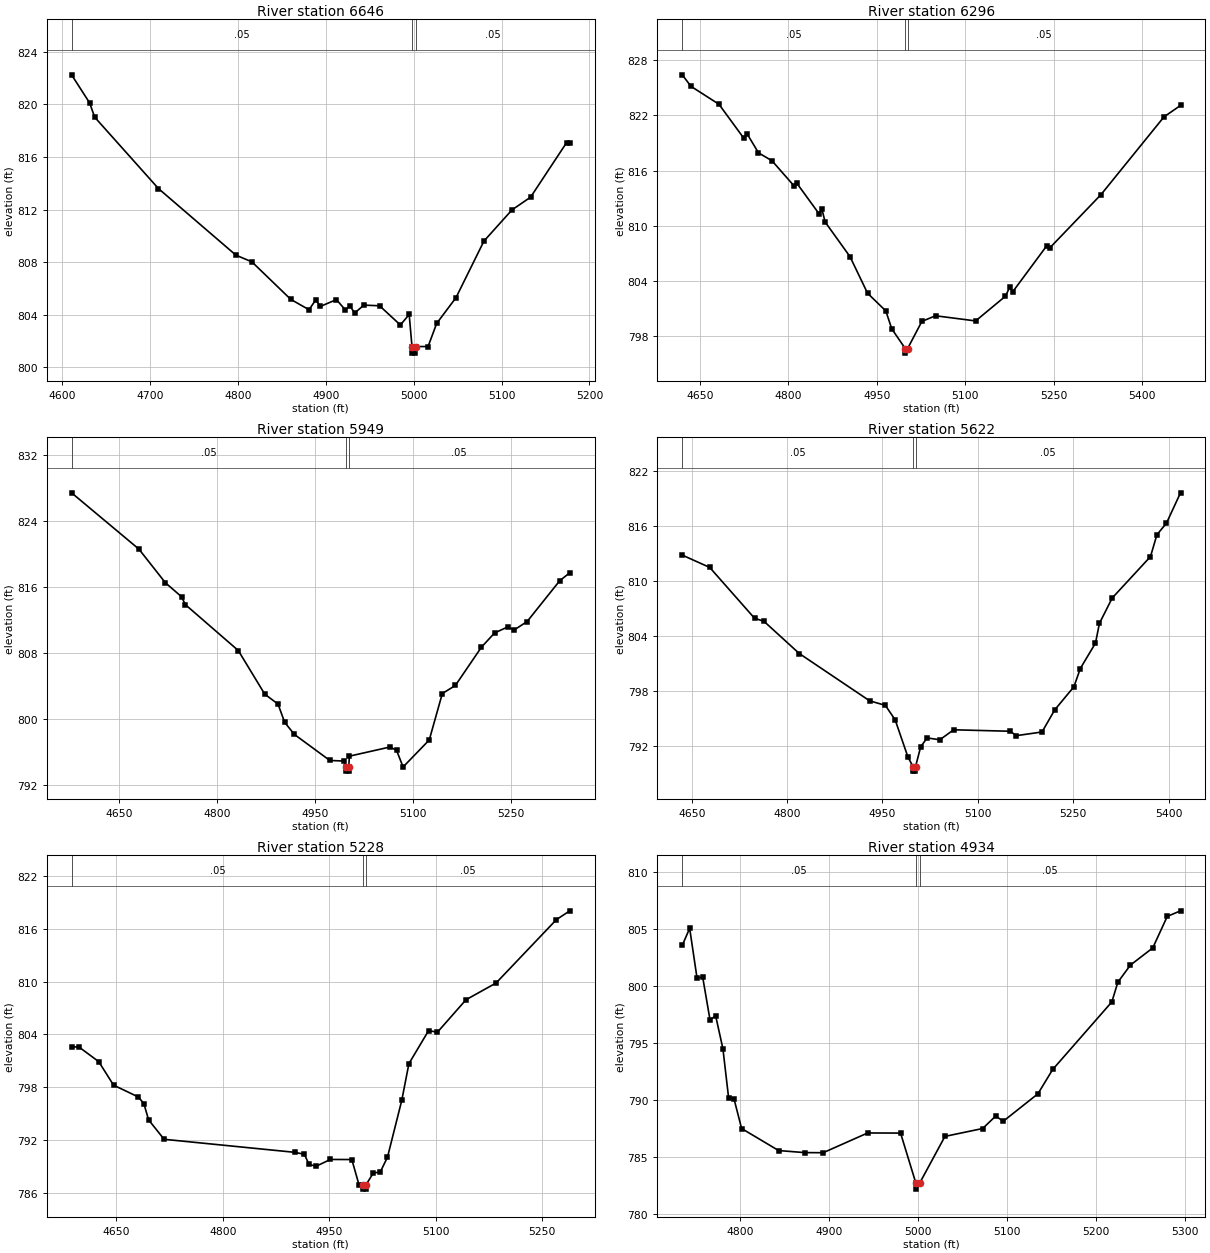
Type RM Length L Ch R = 1,6646,350,350,350
BEGIN DESCRIPTION:
MDW T 043 11.0
END DESCRIPTION:
XS GIS Cut Line= 3
      2298049.31      7093837.59      2298429.47      7093946.80
      2298591.02      7094004.27
#Sta/Elev= 30
  4610.6  822.24  4631.1  820.11  4636.9  819.02  4709.5  813.59  4797.6  808.53
  4815.8  808.02  4860.0  805.17  4880.8  804.38  4888.5  805.13  4893.7  804.63
  4912.0  805.15  4922.2  804.36  4927.4  804.66  4932.8  804.13  4943.2  804.73
  4961.1  804.68  4984.8  803.22  4994.8  804.02  4998.0  801.58  4998.3  801.08
  5001.8  801.08  5002.0  801.58  5016.3  801.58  5026.1  803.34  5048.1  805.30
  5079.9  809.60  5111.8  811.97  5133.0  812.94  5173.9  817.08  5177.6  817.08
#Mann=3,-1,0
  4610.6    0.05       0  4998.0   0.033       0  5002.0    0.05       0
Bank Sta=4998,5002
Exp/Cntr=0.3,0.1

Type RM Length L Ch R = 1,6296,347,347,347
BEGIN DESCRIPTION:
MDW T 043 10.0
END DESCRIPTION:
XS GIS Cut Line= 3
      2297863.21      7094120.82      2298231.50      7094207.49
      2298692.19      7094279.24
#Sta/Elev= 30
  4620.0  826.41  4634.7  825.16  4682.2  823.21  4724.5  819.50  4729.7  820.02
  4749.2  817.93  4772.1  817.07  4809.3  814.35  4814.4  814.61  4851.7  811.32
  4856.8  811.78  4862.2  810.41  4904.3  806.65  4934.1  802.67  4965.0  800.75
  4975.2  798.79  4998.0  796.66  4998.3  796.16  5002.0  796.66  5026.2  799.61
  5049.3  800.22  5117.3  799.66  5167.9  802.35  5175.0  803.32  5180.1  802.82
  5237.9  807.83  5242.9  807.59  5329.8  813.39  5436.6  821.84  5464.6  823.08
#Mann=3,-1,0
  4620.0    0.05       0  4998.0   0.033       0  5002.0    0.05       0
Bank Sta=4998,5002
Exp/Cntr=0.3,0.1

Type RM Length L Ch R = 1,5949,327,327,327
BEGIN DESCRIPTION:
MDW T 043 9.0
END DESCRIPTION:
XS GIS Cut Line= 3
      2297877.37      7094415.97      2298299.51      7094490.13
      2298634.35      7094480.00
#Sta/Elev= 30
  4577.2  827.39  4680.4  820.58  4721.0  816.51  4745.7  814.82  4751.5  813.87
  4832.7  808.31  4873.3  803.03  4893.6  801.83  4903.8  799.62  4918.7  798.16
  4973.0  795.01  4995.1  794.94  4998.0  794.22  4998.3  793.72  5001.8  793.72
  5002.0  794.22  5003.0  795.53  5065.3  796.64  5075.3  796.23  5085.3  794.22
  5125.4  797.49  5145.4  803.11  5165.4  804.08  5205.4  808.72  5225.4  810.43
  5245.4  811.16  5255.4  810.79  5275.4  811.82  5325.4  816.76  5340.8  817.72
#Mann=3,-1,0
  4577.2    0.05       0  4998.0   0.033       0  5002.0    0.05       0
Bank Sta=4998,5002
Exp/Cntr=0.3,0.1

Type RM Length L Ch R = 1,5622,394,394,394
BEGIN DESCRIPTION:
MDW T 043 8.0
END DESCRIPTION:
XS GIS Cut Line= 3
      2297966.03      7094768.44      2298328.80      7094730.21
      2298745.97      7094693.01
#Sta/Elev= 30
  4635.1  812.85  4678.3  811.50  4748.7  805.95  4763.6  805.61  4819.1  802.09
  4929.7  796.92  4954.5  796.42  4969.9  794.84  4990.0  790.77  4998.0  789.73
  4998.3  789.23  5001.8  789.23  5002.0  789.73  5010.1  791.90  5020.2  792.86
  5040.2  792.66  5061.9  793.75  5150.7  793.59  5160.7  793.11  5200.9  793.51
  5220.9  795.93  5251.1  798.46  5261.1  800.45  5285.0  803.23  5291.2  805.39
  5311.3  808.16  5371.5  812.69  5381.6  815.08  5396.5  816.33  5418.7  819.66
#Mann=3,-1,0
  4635.1    0.05       0  4998.0   0.033       0  5002.0    0.05       0
Bank Sta=4998,5002
Exp/Cntr=0.3,0.1

Type RM Length L Ch R = 1,5228,294,294,294
BEGIN DESCRIPTION:
Mapping XS cddb3f98
END DESCRIPTION:
XS GIS Cut Line= 3
      2298126.04      7094779.34      2298317.56      7095001.23
      2298724.49      7095046.91
#Sta/Elev= 30
  4586.7  802.53  4596.5  802.60  4625.0  800.90  4645.9  798.23  4681.0  796.88
  4688.7  796.12  4695.3  794.29  4717.2  792.08  4901.4  790.60  4915.0  790.38
  4921.5  789.23  4931.6  789.02  4951.7  789.79  4981.9  789.78  4992.0  786.92
  4998.0  786.92  4998.3  786.42  5001.8  786.42  5002.0  786.92  5012.1  788.24
  5022.1  788.38  5032.2  790.05  5052.3  796.49  5062.4  800.67  5090.2  804.43
  5102.6  804.24  5142.9  807.93  5185.3  809.83  5270.4  817.03  5289.3  818.03
#Mann=3,-1,0
  4586.7    0.05       0  4998.0   0.033       0  5002.0    0.05       0
Bank Sta=4998,5002
Exp/Cntr=0.3,0.1

Type RM Length L Ch R = 1,4934,218,218,218
BEGIN DESCRIPTION:
Mapping XS 143a71c6
END DESCRIPTION:
XS GIS Cut Line= 3
      2298092.37      7095083.78      2298381.52      7095299.70
      2298573.31      7095353.63
#Sta/Elev= 30
  4735.3  803.57  4743.6  805.07  4751.9  800.70  4758.2  800.81  4766.5  797.04
  4772.8  797.41  4781.0  794.51  4787.4  790.21  4793.6  790.08  4802.0  787.53
  4843.6  785.60  4872.8  785.42  4893.7  785.41  4943.7  787.14  4980.7  787.13
  4998.0  782.72  4998.3  782.22  5002.0  782.72  5030.6  786.84  5073.0  787.53
  5087.6  788.62  5096.2  788.17  5135.1  790.57  5151.7  792.70  5218.2  798.62
  5225.0  800.35  5239.0  801.84  5264.2  803.35  5280.5  806.11  5295.4  806.60
#Mann=3,-1,0
  4735.3    0.05       0  4998.0   0.033       0  5002.0    0.05       0
Bank Sta=4998,5002
Exp/Cntr=0.3,0.1

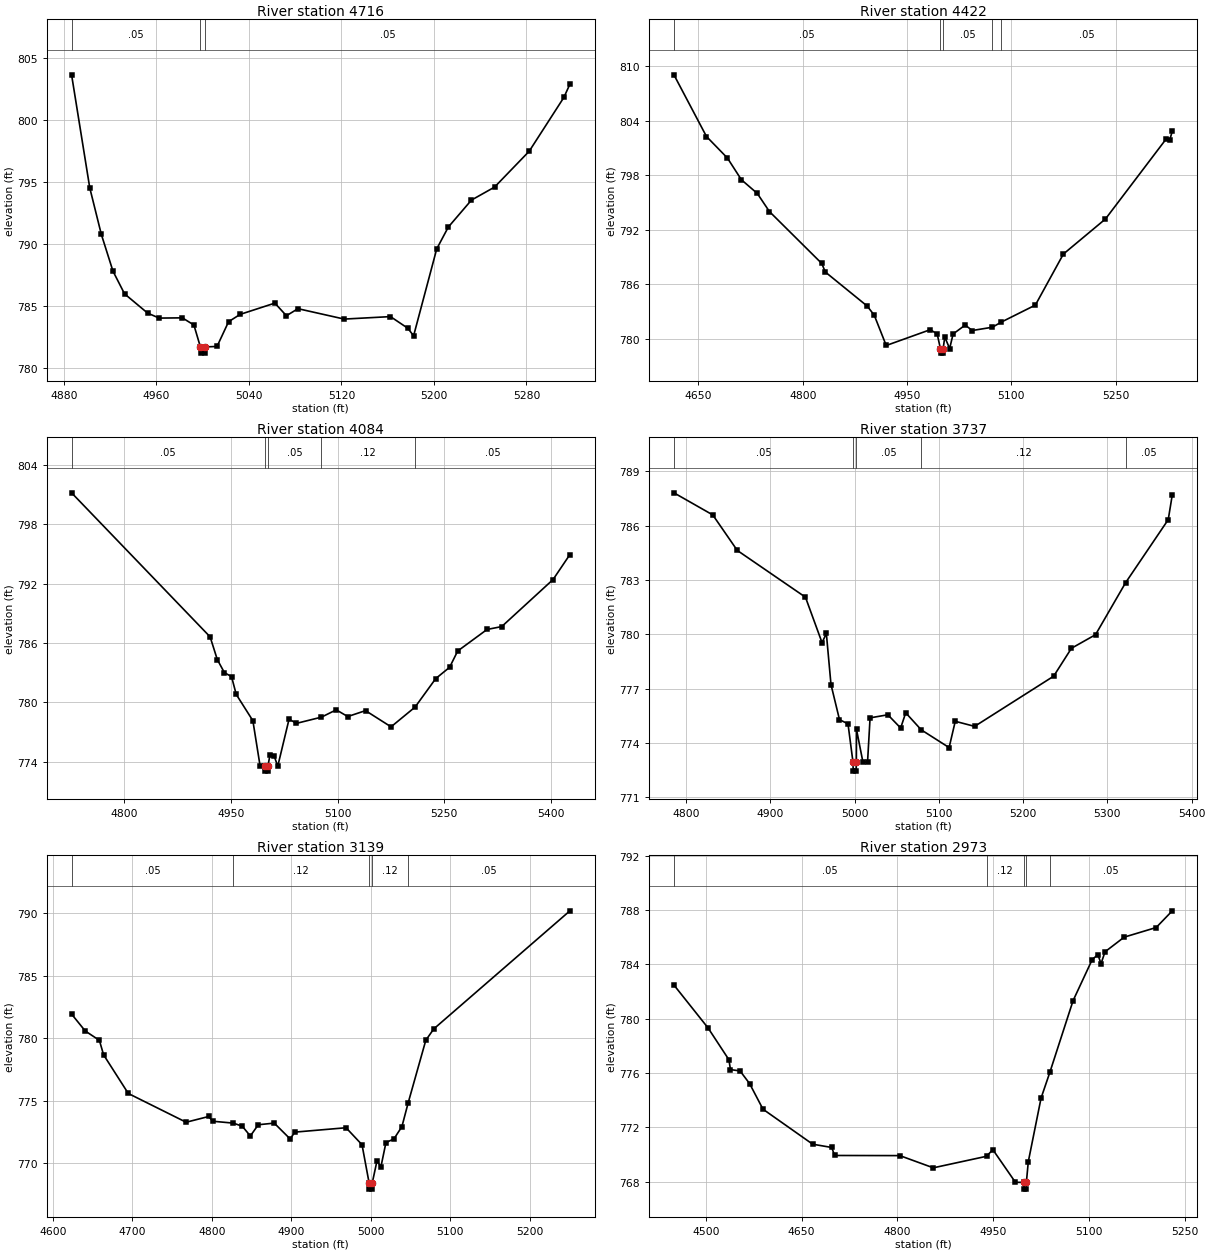
Type RM Length L Ch R = 1,4716,294,294,294
BEGIN DESCRIPTION:
Mapping XS 58d526e4
END DESCRIPTION:
XS GIS Cut Line= 2
      2298093.25      7095419.68      2298524.18      7095427.56
#Sta/Elev= 30
  4886.6  803.67  4902.3  794.55  4912.3  790.79  4922.4  787.81  4932.4  785.98
  4952.4  784.42  4962.4  784.02  4982.4  784.04  4992.4  783.46  4998.0  781.69
  4998.3  781.19  5001.8  781.19  5002.0  781.69  5012.4  781.73  5022.4  783.73
  5032.4  784.32  5062.4  785.23  5072.4  784.21  5082.4  784.78  5122.4  783.94
  5162.4  784.14  5177.4  783.20  5182.4  782.59  5202.4  789.61  5212.4  791.37
  5232.4  793.55  5252.4  794.60  5282.4  797.50  5312.4  801.85  5317.6  802.92
#Mann=3,-1,0
  4886.6    0.05       0  4998.0   0.033       0  5002.0    0.05       0
Bank Sta=4998,5002
Exp/Cntr=0.3,0.1

Type RM Length L Ch R = 1,4422,338,338,338
BEGIN DESCRIPTION:
MDW T 043 5.0
END DESCRIPTION:
XS GIS Cut Line= 3
      2297832.50      7095632.60      2298215.55      7095673.19
      2298544.29      7095715.91
#Sta/Elev= 30
  4614.8  809.08  4661.6  802.29  4691.7  799.92  4711.8  797.53  4734.7  796.02
  4752.1  794.03  4827.4  788.31  4832.5  787.37  4892.9  783.61  4902.9  782.61
  4920.1  779.28  4983.4  781.02  4993.4  780.55  4998.0  778.94  4998.3  778.44
  5001.8  778.44  5002.0  778.94  5004.3  780.22  5011.3  778.94  5016.3  780.55
  5033.7  781.53  5043.8  780.93  5072.7  781.29  5085.7  781.86  5134.6  783.73
  5174.9  789.35  5235.4  793.21  5322.8  802.03  5327.8  801.91  5331.5  802.87
#Mann=5,-1,0
  4614.8    0.05       0  4998.0   0.033       0  5002.0    0.05       0
  5072.7    0.12       0  5085.7    0.05       0
Bank Sta=4998,5002
Exp/Cntr=0.3,0.1

Type RM Length L Ch R = 1,4084,347,347,347
BEGIN DESCRIPTION:
MDW T 043 4.0
END DESCRIPTION:
XS GIS Cut Line= 3
      2297844.46      7095941.97      2298122.97      7095957.56
      2298532.00      7095854.74
#Sta/Elev= 30
  4726.0  801.18  4920.8  786.61  4930.9  784.31  4940.9  782.99  4950.9  782.59
  4957.5  780.79  4980.9  778.13  4991.0  773.58  4998.0  773.53  4998.3  773.03
  5001.8  773.03  5002.0  773.53  5004.9  774.63  5010.7  774.58  5015.9  773.53
  5031.8  778.29  5042.1  777.86  5077.3  778.49  5098.1  779.23  5114.3  778.55
  5139.3  779.15  5175.2  777.51  5209.0  779.51  5238.0  782.39  5257.5  783.53
  5268.9  785.18  5310.2  787.36  5330.8  787.65  5403.0  792.41  5426.7  794.94
#Mann=5,-1,0
  4726.0    0.05       0  4998.0   0.033       0  5002.0    0.05       0
  5077.3    0.12       0  5209.0    0.05       0
Bank Sta=4998,5002
Exp/Cntr=0.3,0.1

Type RM Length L Ch R = 1,3737,598,598,598
BEGIN DESCRIPTION:
MDW T 043 3.0
END DESCRIPTION:
XS GIS Cut Line= 3
      2298004.56      7096291.10      2298228.90      7096258.29
      2298535.63      7096060.87
#Sta/Elev= 30
  4785.5  787.81  4831.6  786.59  4860.7  784.63  4941.6  782.05  4961.3  779.54
  4966.4  780.05  4971.9  777.23  4982.0  775.29  4992.1  775.06  4998.0  772.95
  4998.3  772.45  5001.8  772.45  5002.0  772.95  5002.2  774.75  5009.8  772.95
  5015.3  772.95  5018.3  775.39  5039.4  775.56  5054.6  774.83  5060.6  775.67
  5079.0  774.73  5112.1  773.75  5119.4  775.20  5142.4  774.92  5236.2  777.69
  5257.3  779.23  5285.9  779.98  5321.6  782.85  5372.2  786.33  5377.0  787.70
#Mann=5,-1,0
  4785.5    0.05       0  4998.0    0.04       0  5002.0    0.05       0
  5079.0    0.12       0  5321.6    0.05       0
Bank Sta=4998,5002
Exp/Cntr=0.3,0.1

Type RM Length L Ch R = 1,3139,166,166,166
BEGIN DESCRIPTION:
Mapping XS e6e3bfbc
END DESCRIPTION:
XS GIS Cut Line= 3
      2298062.79      7096402.85      2298206.52      7096452.81
      2298679.55      7096497.49
#Sta/Elev= 30
  4623.5  781.94  4640.7  780.59  4658.5  779.84  4663.8  778.68  4694.9  775.59
  4767.7  773.29  4796.1  773.75  4801.1  773.37  4827.1  773.22  4838.4  772.97
  4848.5  772.19  4858.5  773.09  4878.6  773.22  4898.7  771.95  4904.5  772.50
  4969.0  772.85  4989.1  771.49  4998.0  768.44  4998.3  767.94  5001.8  767.94
  5002.0  768.44  5007.9  770.19  5012.9  769.73  5019.2  771.66  5029.3  771.96
  5039.3  772.94  5047.1  774.82  5069.4  779.85  5079.5  780.76  5250.8  790.20
#Mann=5,-1,0
  4623.5    0.05       0  4827.1    0.12       0  4998.0    0.07       0
  5002.0    0.12       0  5047.1    0.05       0
Bank Sta=4998,5002
Exp/Cntr=0.3,0.1

Type RM Length L Ch R = 1,2973,376,376,376
BEGIN DESCRIPTION:
MDW T 043 2.0
END DESCRIPTION:
XS GIS Cut Line= 5
      2298007.80      7096416.64      2298003.77      7096505.10
      2298141.50      7096599.65      2298429.42      7096629.81
      2298664.20      7096639.78
#Sta/Elev= 30
  4450.3  782.48  4503.7  779.32  4536.3  776.98  4538.8  776.25  4553.8  776.15
  4568.7  775.22  4589.7  773.33  4667.5  770.75  4697.3  770.51  4701.8  769.92
  4803.9  769.91  4856.3  769.01  4939.6  769.86  4949.5  770.35  4984.9  767.94
  4998.0  767.94  4998.3  767.44  5001.8  767.44  5002.0  767.94  5005.0  769.46
  5025.0  774.15  5038.9  776.07  5075.1  781.33  5105.1  784.36  5113.9  784.72
  5118.9  784.06  5125.1  784.93  5155.1  786.01  5205.2  786.72  5230.4  787.95
#Mann=5,-1,0
  4450.3    0.05       0  4939.6    0.12       0  4998.0    0.07       0
  5002.0    0.12       0  5038.9    0.05       0
Bank Sta=4998,5002
Exp/Cntr=0.3,0.1

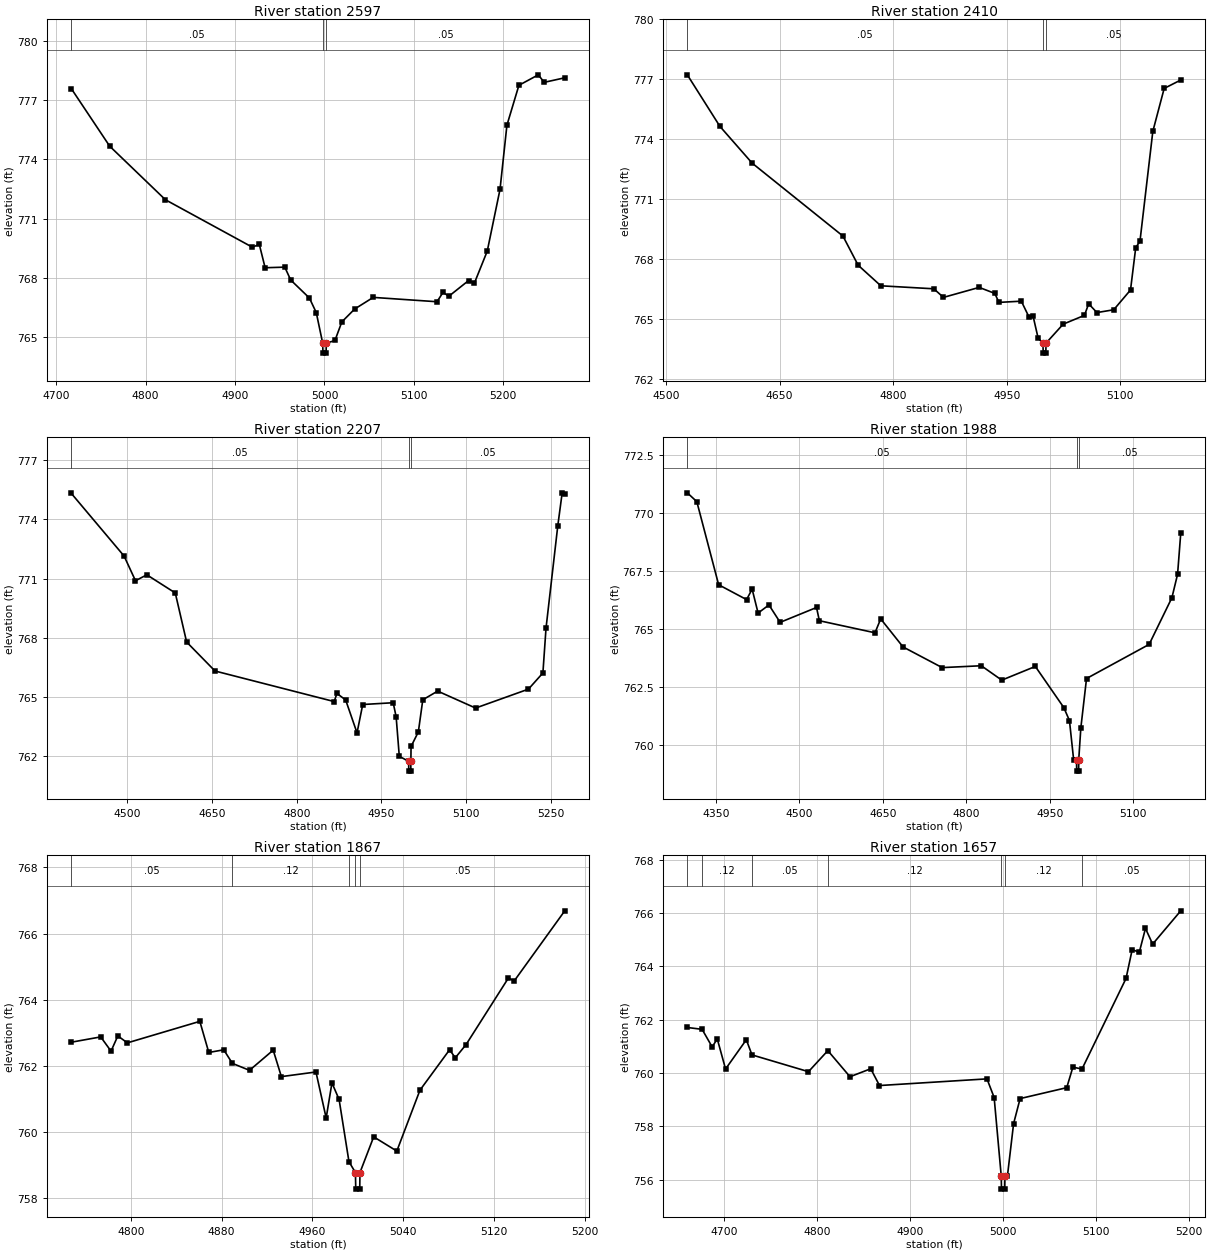
Type RM Length L Ch R = 1,2597,187,187,187
BEGIN DESCRIPTION:
Mapping XS 733361c9
END DESCRIPTION:
XS GIS Cut Line= 3
      2297996.98      7096494.43      2298025.48      7096673.91
      2298308.18      7096912.72
#Sta/Elev= 30
  4716.9  777.57  4759.8  774.66  4822.1  771.95  4919.3  769.55  4927.1  769.69
  4933.6  768.51  4955.6  768.54  4962.2  767.89  4983.1  766.98  4990.8  766.24
  4998.0  764.69  4998.3  764.19  5001.8  764.19  5002.0  764.69  5011.7  764.83
  5019.4  765.77  5033.7  766.42  5054.5  767.01  5125.8  766.79  5132.5  767.26
  5139.1  767.07  5161.1  767.86  5167.7  767.74  5182.0  769.35  5196.3  772.48
  5204.0  775.72  5217.4  777.74  5239.1  778.27  5245.7  777.89  5268.7  778.12
#Mann=3,-1,0
  4716.9    0.05       0  4998.0   0.033       0  5002.0    0.05       0
Bank Sta=4998,5002
Exp/Cntr=0.3,0.1

Type RM Length L Ch R = 1,2410,203,203,203
BEGIN DESCRIPTION:
Mapping XS a50bb244
END DESCRIPTION:
XS GIS Cut Line= 3
      2297992.43      7096494.38      2298005.97      7096887.83
      2298238.75      7097000.27
#Sta/Elev= 30
  4527.9  777.23  4571.0  774.65  4613.6  772.81  4733.6  769.16  4753.7  767.70
  4783.7  766.67  4853.7  766.52  4866.5  766.09  4913.7  766.59  4934.3  766.29
  4939.8  765.84  4969.4  765.90  4979.5  765.11  4985.0  765.14  4991.6  764.05
  4998.0  763.80  4998.3  763.30  5001.8  763.30  5002.0  763.80  5024.7  764.75
  5052.8  765.19  5058.4  765.77  5069.3  765.33  5091.5  765.47  5113.7  766.46
  5120.6  768.58  5126.2  768.90  5143.2  774.40  5158.2  776.55  5180.1  776.97
#Mann=3,-1,0
  4527.9    0.05       0  4998.0   0.033       0  5002.0    0.05       0
Bank Sta=4998,5002
Exp/Cntr=0.3,0.1

Type RM Length L Ch R = 1,2207,219,219,219
BEGIN DESCRIPTION:
Mapping XS eb5faa2d
END DESCRIPTION:
XS GIS Cut Line= 3
      2297981.27      7096517.06      2297925.35      7097069.99
      2298230.95      7097155.54
#Sta/Elev= 30
  4401.2  775.32  4494.6  772.14  4514.7  770.89  4534.8  771.19  4585.1  770.27
  4605.2  767.78  4655.4  766.31  4866.2  764.76  4871.2  765.17  4886.6  764.84
  4906.7  763.17  4916.8  764.61  4970.7  764.70  4975.9  763.99  4981.5  761.98
  4998.0  761.73  4998.3  761.23  5001.8  761.23  5002.0  761.73  5002.3  762.48
  5015.2  763.22  5023.1  764.85  5049.4  765.29  5116.5  764.43  5210.0  765.39
  5235.6  766.21  5241.1  768.48  5261.9  773.67  5269.7  775.35  5274.3  775.28
#Mann=3,-1,0
  4401.2    0.05       0  4998.0    0.04       0  5002.0    0.05       0
Bank Sta=4998,5002
Exp/Cntr=0.3,0.1

Type RM Length L Ch R = 1,1988,121,121,121
BEGIN DESCRIPTION:
Mapping XS ac751592
END DESCRIPTION:
XS GIS Cut Line= 4
      2297955.19      7096663.94      2297903.68      7097226.67
      2297950.71      7097248.40      2298214.59      7097304.65
#Sta/Elev= 30
  4298.6  770.87  4315.7  770.49  4354.9  766.91  4405.1  766.27  4415.1  766.72
  4425.8  765.69  4445.3  766.04  4465.4  765.29  4530.8  765.93  4535.9  765.36
  4635.9  764.84  4646.1  765.44  4686.3  764.23  4756.6  763.34  4826.9  763.42
  4863.7  762.80  4924.0  763.39  4975.1  761.62  4985.3  761.06  4992.8  759.38
  4998.0  759.38  4998.3  758.88  5001.8  758.88  5002.0  759.38  5005.8  760.75
  5016.0  762.87  5128.5  764.34  5169.4  766.35  5179.6  767.36  5185.3  769.13
#Mann=3,-1,0
  4298.6    0.05       0  4998.0   0.033       0  5002.0    0.05       0
Bank Sta=4998,5002
Exp/Cntr=0.3,0.1

Type RM Length L Ch R = 1,1867,210,210,210
BEGIN DESCRIPTION:
Mapping XS cf20410a
END DESCRIPTION:
XS GIS Cut Line= 3
      2297892.74      7097218.77      2297988.85      7097364.80
      2298244.42      7097414.11
#Sta/Elev= 30
  4747.5  762.72  4773.4  762.88  4782.5  762.45  4788.5  762.91  4796.9  762.70
  4860.8  763.35  4868.7  762.41  4881.9  762.49  4889.5  762.08  4904.6  761.87
  4925.5  762.48  4932.7  761.68  4963.2  761.82  4972.2  760.43  4977.3  761.49
  4983.6  760.99  4992.3  759.11  4998.0  758.78  4998.3  758.28  5001.8  758.28
  5002.0  758.78  5014.1  759.86  5034.5  759.43  5054.9  761.27  5081.0  762.49
  5086.1  762.25  5095.6  762.65  5132.9  764.66  5138.0  764.57  5182.6  766.69
#Mann=5,-1,0
  4747.5    0.05       0  4889.5    0.12       0  4992.3    0.05       0
  4998.0   0.033       0  5002.0    0.05       0
Bank Sta=4998,5002
Exp/Cntr=0.3,0.1

Type RM Length L Ch R = 1,1657,187,187,187
BEGIN DESCRIPTION:
Mapping XS b6d2c69c
END DESCRIPTION:
XS GIS Cut Line= 3
      2297951.20      7097373.14      2298067.89      7097610.40
      2298270.75      7097438.65
#Sta/Elev= 30
  4660.7  761.71  4676.6  761.64  4687.4  760.98  4692.9  761.28  4701.8  760.15
  4724.1  761.25  4730.2  760.68  4790.9  760.05  4811.7  760.84  4835.5  759.86
  4857.8  760.16  4867.2  759.53  4982.7  759.78  4990.4  759.08  4998.0  756.14
  4998.3  755.64  5001.8  755.64  5002.0  756.14  5004.7  756.14  5011.3  758.10
  5018.3  759.04  5068.4  759.45  5075.0  760.22  5084.8  760.15  5132.1  763.55
  5138.7  764.63  5146.4  764.54  5153.0  765.43  5160.7  764.84  5190.9  766.09
#Mann=7,-1,0
  4660.7    0.05       0  4676.6    0.12       0  4730.2    0.05       0
  4811.7    0.12       0  4998.0    0.07       0  5002.0    0.12       0
  5084.8    0.05       0
Bank Sta=4998,5002
Exp/Cntr=0.3,0.1

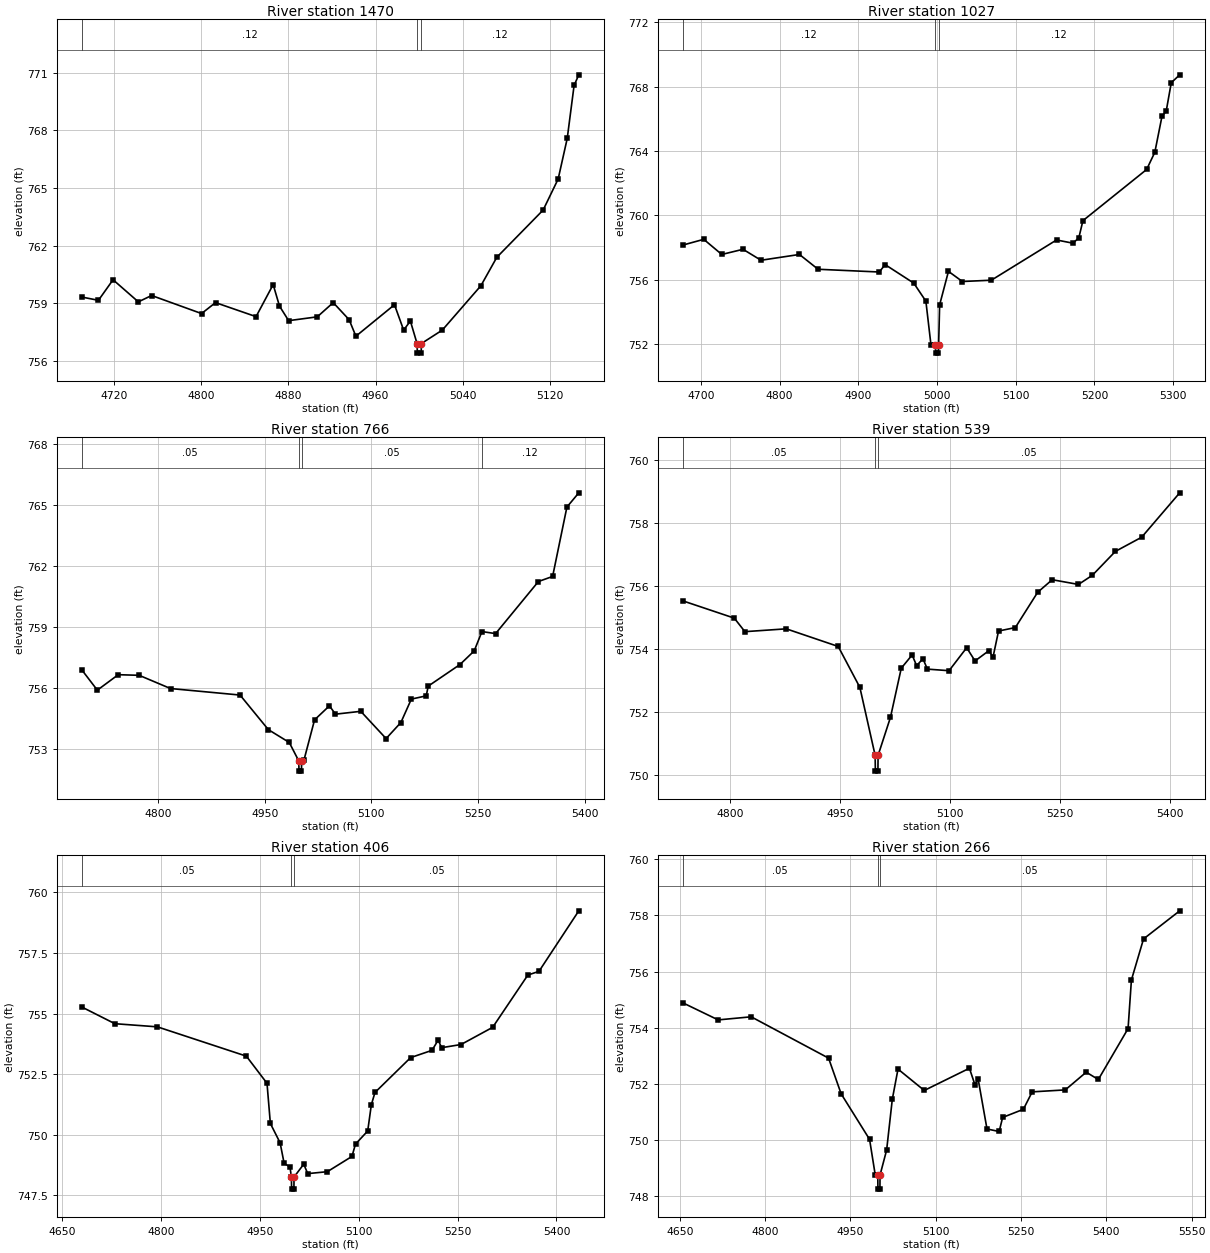
Type RM Length L Ch R = 1,1470,443,443,443
BEGIN DESCRIPTION:
Mapping XS ff5ce618
END DESCRIPTION:
XS GIS Cut Line= 3
      2298054.21      7097625.23      2298221.91      7097723.54
      2298378.26      7097513.79
#Sta/Elev= 30
  4690.4  759.32  4705.7  759.15  4719.1  760.22  4742.3  759.07  4754.5  759.40
  4800.3  758.46  4813.1  759.03  4850.3  758.30  4866.0  759.97  4871.8  758.85
  4880.2  758.09  4906.5  758.29  4921.1  759.03  4935.7  758.14  4941.9  757.28
  4977.3  758.92  4985.7  757.60  4991.9  758.07  4998.0  756.90  4998.3  756.40
  5001.8  756.40  5002.0  756.90  5021.2  757.60  5056.6  759.91  5071.2  761.39
  5113.7  763.85  5127.5  765.47  5135.8  767.58  5142.1  770.34  5146.4  770.89
#Mann=3,-1,0
  4690.4    0.12       0  4998.0    0.07       0  5002.0    0.12       0
Bank Sta=4998,5002
Exp/Cntr=0.3,0.1

Type RM Length L Ch R = 1,1027,261,261,261
BEGIN DESCRIPTION:
Mapping XS 357d3705
END DESCRIPTION:
XS GIS Cut Line= 4
      2298173.23      7097737.89      2298307.91      7097933.79
      2298496.97      7097849.05      2298549.13      7097669.69
#Sta/Elev= 30
  4676.7  758.15  4703.5  758.51  4726.4  757.57  4753.4  757.89  4776.3  757.21
  4825.1  757.57  4848.8  756.65  4926.6  756.48  4934.0  756.94  4970.4  755.79
  4985.8  754.67  4992.3  751.94  4998.0  751.94  4998.3  751.44  5001.8  751.44
  5002.0  751.94  5003.3  754.44  5014.5  756.52  5032.2  755.89  5069.0  755.97
  5151.9  758.47  5172.7  758.27  5180.2  758.60  5185.4  759.67  5266.4  762.85
  5276.8  763.92  5286.0  766.18  5291.2  766.46  5297.7  768.24  5308.4  768.73
#Mann=3,-1,0
  4676.7    0.12       0  4998.0    0.07       0  5002.0    0.12       0
Bank Sta=4998,5002
Exp/Cntr=0.3,0.1

Type RM Length L Ch R = 1,766,227,227,227
BEGIN DESCRIPTION:
Mapping XS 09a803f4
END DESCRIPTION:
XS GIS Cut Line= 5
      2298301.37      7098029.25      2298316.22      7098127.71
      2298409.44      7098201.90      2298567.38      7097983.53
      2298583.19      7097773.33
#Sta/Elev= 30
  4692.8  756.91  4714.7  755.91  4744.1  756.67  4773.5  756.64  4817.6  755.99
  4915.4  755.67  4955.2  753.97  4984.6  753.34  4998.0  752.43  4998.3  751.93
  5001.8  751.93  5002.0  752.43  5005.5  752.50  5020.2  754.45  5041.1  755.14
  5049.6  754.73  5085.2  754.87  5120.8  753.53  5141.6  754.32  5156.3  755.47
  5177.2  755.63  5180.1  756.11  5224.7  757.17  5244.7  757.84  5255.6  758.79
  5274.8  758.69  5335.0  761.25  5355.0  761.50  5375.1  764.91  5391.8  765.61
#Mann=4,-1,0
  4692.8    0.05       0  4998.0    0.04       0  5002.0    0.05       0
  5255.6    0.12       0
Bank Sta=4998,5002
Exp/Cntr=0.3,0.1

Type RM Length L Ch R = 1,539,133,133,133
BEGIN DESCRIPTION:
Mapping XS 8ccd50c9
END DESCRIPTION:
XS GIS Cut Line= 4
      2298417.84      7098212.25      2298580.22      7098339.21
      2298677.35      7098204.56      2298782.57      7097918.34
#Sta/Elev= 30
  4735.8  755.52  4806.1  754.97  4820.6  754.54  4876.9  754.63  4947.7  754.07
  4977.2  752.77  4998.0  750.61  4998.3  750.11  5001.8  750.11  5002.0  750.61
  5018.9  751.82  5033.6  753.38  5048.4  753.80  5054.5  753.46  5063.1  753.68
  5069.2  753.35  5098.7  753.30  5122.7  754.03  5134.1  753.61  5153.2  753.94
  5158.5  753.72  5166.1  754.56  5189.0  754.67  5219.4  755.79  5239.2  756.19
  5275.0  756.04  5293.9  756.33  5325.3  757.09  5361.1  757.54  5412.9  758.95
#Mann=3,-1,0
  4735.8    0.05       0  4998.0    0.04       0  5002.0    0.05       0
Bank Sta=4998,5002
Exp/Cntr=0.3,0.1

Type RM Length L Ch R = 1,406,140,140,140
BEGIN DESCRIPTION:
Mapping XS fabff152
END DESCRIPTION:
XS GIS Cut Line= 5
      2298451.55      7098256.52      2298576.40      7098351.27
      2298695.66      7098360.19      2298800.89      7098287.27
      2298933.56      7097964.09
#Sta/Elev= 30
  4680.1  755.27  4730.3  754.58  4794.8  754.45  4929.7  753.24  4961.0  752.12
  4966.1  750.46  4980.9  749.66  4987.0  748.81  4995.8  748.67  4998.0  748.25
  4998.3  747.75  5001.8  747.75  5002.0  748.25  5016.7  748.78  5022.8  748.39
  5052.5  748.47  5089.8  749.10  5095.2  749.61  5113.7  750.15  5119.2  751.23
  5124.7  751.74  5178.8  753.18  5211.2  753.48  5220.5  753.90  5225.9  753.59
  5255.2  753.72  5303.2  754.43  5356.6  756.59  5373.4  756.74  5433.8  759.24
#Mann=3,-1,0
  4680.1    0.05       0  4998.0    0.04       0  5002.0    0.05       0
Bank Sta=4998,5002
Exp/Cntr=0.3,0.1

Type RM Length L Ch R = 1,266,166,166,166
BEGIN DESCRIPTION:
Mapping XS 92105c50
END DESCRIPTION:
XS GIS Cut Line= 4
      2298452.17      7098269.05      2298664.16      7098426.10
      2298826.45      7098426.73      2299058.86      7098043.75
#Sta/Elev= 30
  4654.9  754.89  4717.3  754.28  4775.4  754.39  4911.5  752.92  4933.6  751.65
  4983.6  750.03  4993.6  748.76  4998.0  748.76  4998.3  748.26  5001.8  748.26
  5002.0  748.76  5013.6  749.65  5023.6  751.46  5033.6  752.53  5079.8  751.77
  5159.2  752.56  5168.8  751.98  5174.6  752.17  5190.1  750.40  5211.5  750.31
  5217.6  750.81  5254.1  751.10  5269.6  751.72  5327.8  751.79  5364.6  752.42
  5385.9  752.16  5438.2  753.97  5444.1  755.70  5465.4  757.16  5529.0  758.16
#Mann=3,-1,0
  4654.9    0.05       0  4998.0    0.04       0  5002.0    0.05       0
Bank Sta=4998,5002
Exp/Cntr=0.3,0.1

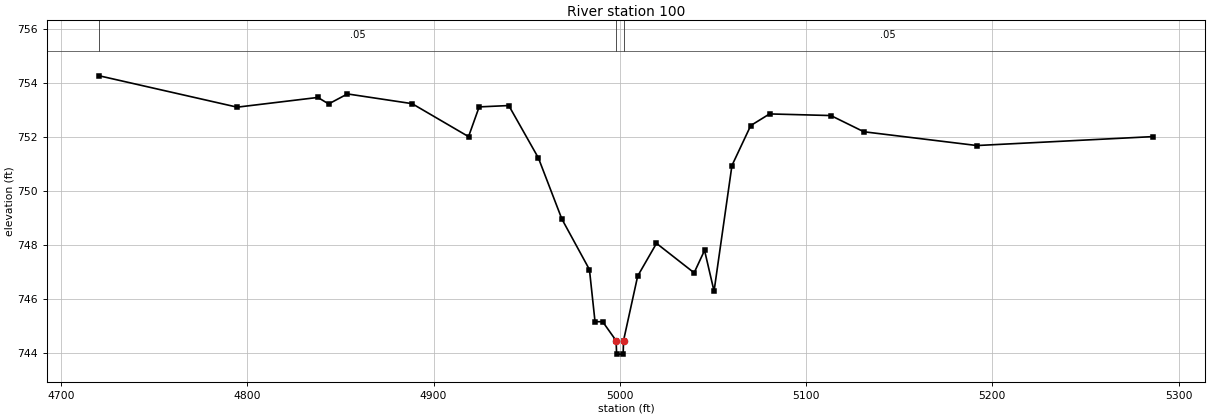
Type RM Length L Ch R = 1,100,0,0,0
BEGIN DESCRIPTION:
MDW T 043 1.0
END DESCRIPTION:
XS GIS Cut Line= 3
      2298535.78      7098343.79      2298666.89      7098575.90
      2298962.22      7098622.09
#Sta/Elev= 30
  4720.6  754.26  4794.6  753.10  4837.9  753.46  4843.7  753.22  4853.8  753.59
  4888.5  753.23  4918.8  752.01  4924.5  753.11  4940.4  753.16  4956.3  751.22
  4968.9  748.96  4983.7  747.09  4986.7  745.16  4990.8  745.16  4998.0  744.46
  4998.3  743.96  5001.8  743.96  5002.0  744.46  5009.6  746.85  5019.7  748.06
  5039.9  746.97  5045.5  747.80  5050.6  746.29  5060.2  750.94  5070.3  752.42
  5080.4  752.85  5113.3  752.79  5131.0  752.19  5191.7  751.68  5286.1  752.01
#Mann=3,-1,0
  4720.6    0.05       0  4998.0    0.04       0  5002.0    0.05       0
Bank Sta=4998,5002
Exp/Cntr=0.3,0.1

Chan Stop Cuts=-1