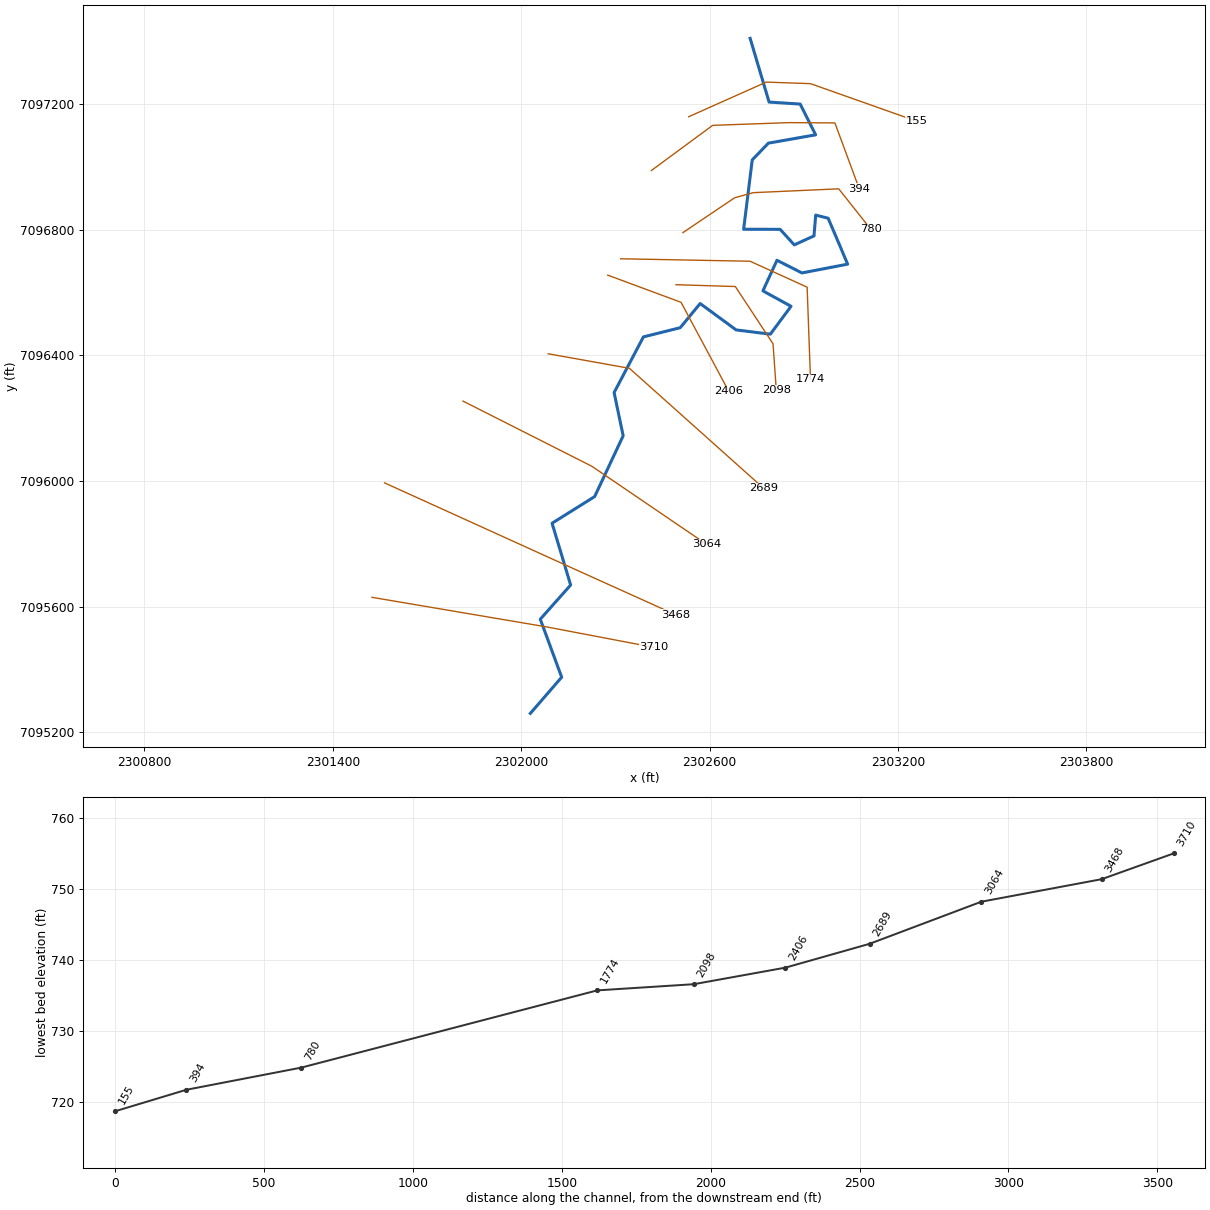
--- MDW T 044.prj (project) ---

Proj Title=MDW T 044 Base Level Engineering
Current Plan=p01
Default Exp/Contr=0.3,0.1
English Units
Geom File=g01
Flow File=f01
Plan File=p01
BEGIN DESCRIPTION:
MDW T 044
END DESCRIPTION:

--- MDW T 044.p01 (plan) ---

Plan Title=Multiple Run
Short Identifier=Multiple
Geom File=g01
Flow File=f01
Subcritical Flow
K Sum by GR= 0
Std Step Tol= 0.01
Critical Tol= 0.01
Num of Std Step Trials= 20
Max Error Tol= 0.3
Flow Tol Ratio= 0.001
Split Flow NTrial= 30
Split Flow Tol= 0.02
Split Flow Ratio= 0.02
Log Output Level= 0
Friction Slope Method= 1
Unsteady Friction Slope Method= 2
Unsteady Bridges Friction Slope Method= 1
Parabolic Critical Depth
Global Vel Dist=  1 , 1 , 1
Global Log Level= 0
CheckData=True
Encroach Param= -1, 0, 0, 0
BEGIN DESCRIPTION:
Multiple Run
END DESCRIPTION:

--- MDW T 044.f01 (steady flow) ---

Flow Title=Multiple
Number of Profiles=7
Profile Names=10-year,25-year,50-year,1pct_min,100-year,1pct_plu,500-year
River Rch & RM= MDW T 044,Reach-1,3710
     544     747     915     558    1113    2221    1648
Boundary for River Rch & Prof#=MDW T 044,Reach-1,1
Up Type=0
Dn Type=3
Dn Slope=0.005
Boundary for River Rch & Prof#=MDW T 044,Reach-1,2
Up Type=0
Dn Type=3
Dn Slope=0.005
Boundary for River Rch & Prof#=MDW T 044,Reach-1,3
Up Type=0
Dn Type=3
Dn Slope=0.005
Boundary for River Rch & Prof#=MDW T 044,Reach-1,4
Up Type=0
Dn Type=3
Dn Slope=0.005
Boundary for River Rch & Prof#=MDW T 044,Reach-1,5
Up Type=0
Dn Type=3
Dn Slope=0.005
Boundary for River Rch & Prof#=MDW T 044,Reach-1,6
Up Type=0
Dn Type=3
Dn Slope=0.005
Boundary for River Rch & Prof#=MDW T 044,Reach-1,7
Up Type=0
Dn Type=3
Dn Slope=0.005

--- MDW T 044.g01 (geometry) ---

Geom Title=Existing Conditions

River Reach=MDW T 044,Reach-1
Reach XY= 30
      2302029.00      7095260.00      2302128.78      7095375.21
      2302060.62      7095560.00      2302157.32      7095668.79
      2302098.21      7095865.59      2302233.88      7095950.57
      2302324.60      7096144.08      2302295.77      7096281.80
      2302389.14      7096459.14      2302506.31      7096488.28
      2302569.81      7096565.36      2302684.45      7096481.31
      2302793.41      7096467.75      2302859.26      7096556.61
      2302769.72      7096605.65      2302814.46      7096703.12
      2302894.01      7096662.79      2303039.64      7096690.76
      2302977.52      7096837.08      2302937.85      7096846.96
      2302932.36      7096780.77      2302869.59      7096752.19
      2302824.56      7096801.69      2302708.32      7096801.95
      2302735.70      7097022.69      2302787.08      7097076.13
      2302937.66      7097102.68      2302888.42      7097200.64
      2302789.43      7097206.96      2302729.00      7097410.00

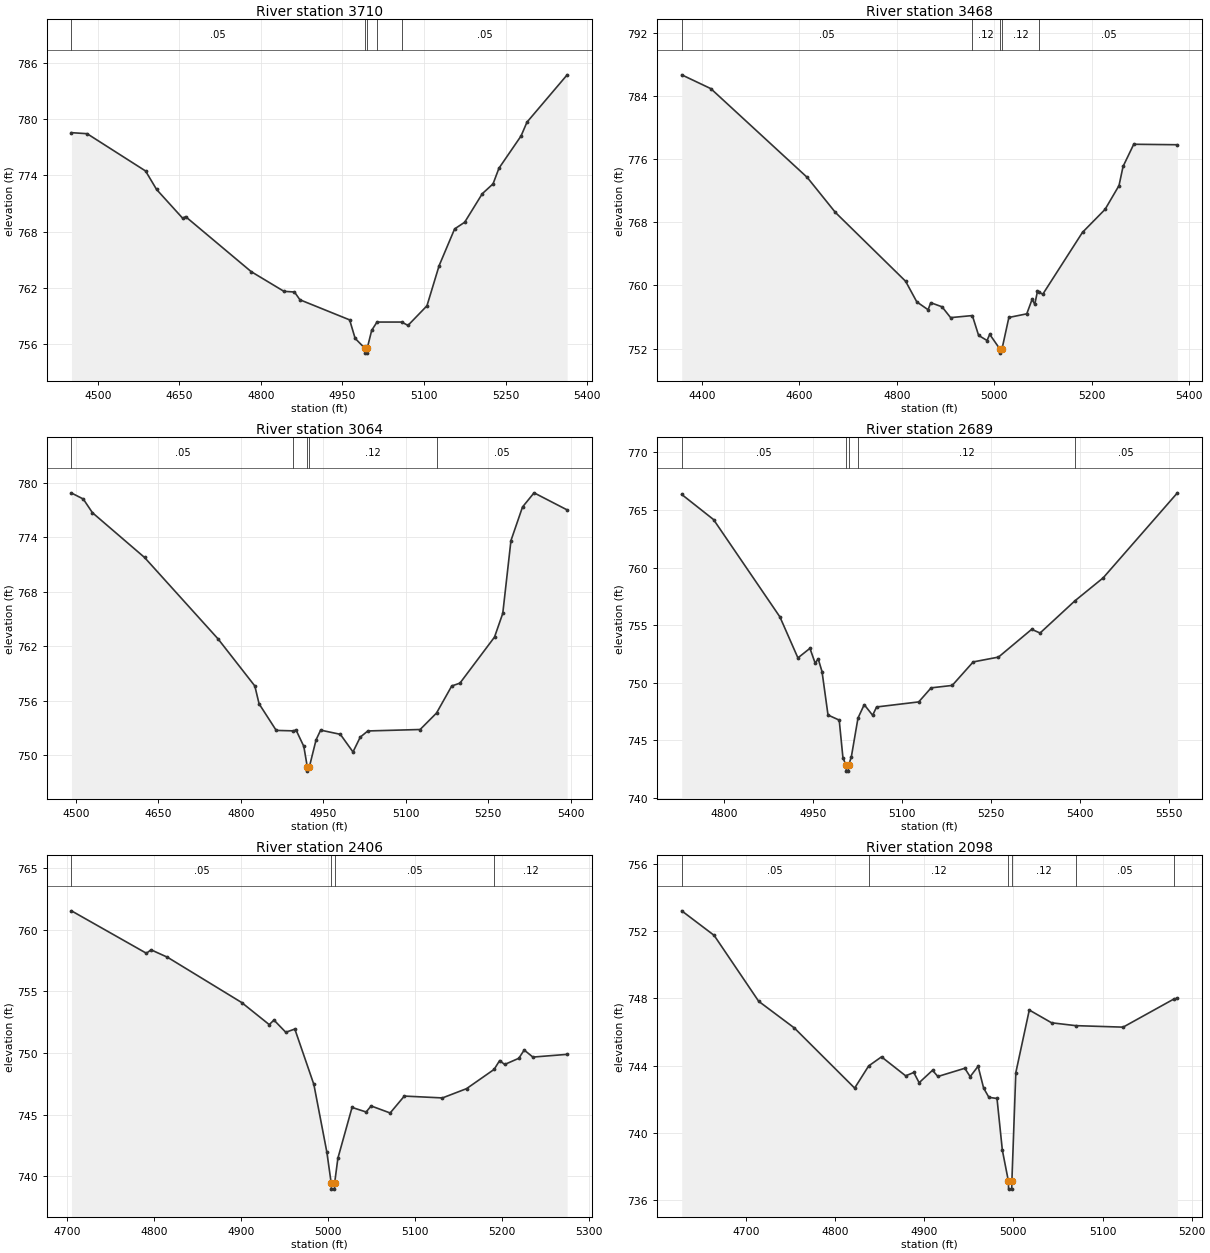
Type RM Length L Ch R = 1,3710,242,242,242
BEGIN DESCRIPTION:
MDW T 044 8.0
END DESCRIPTION:
XS GIS Cut Line= 3
      2301524.58      7095629.64      2302080.86      7095535.38
      2302422.31      7095470.35
#Sta/Elev= 30
  4451.5  778.53  4480.3  778.42  4587.8  774.45  4608.1  772.48  4656.3  769.40
  4661.4  769.59  4782.1  763.73  4842.4  761.63  4861.7  761.56  4871.8  760.73
  4963.2  758.59  4973.3  756.62  4991.5  755.55  4991.8  755.05  4995.3  755.05
  4995.5  755.55  5003.7  757.47  5013.5  758.36  5059.0  758.36  5070.5  758.00
  5105.4  760.09  5127.8  764.37  5156.3  768.28  5174.8  768.99  5207.2  772.03
  5227.0  773.08  5237.8  774.74  5278.5  778.18  5289.4  779.65  5363.3  784.69
#Mann=5,-1,0
  4451.5    0.05       0  4991.5   0.033       0  4995.5    0.05       0
  5013.5    0.12       0  5059.0    0.05       0
Bank Sta=4991.5,4995.5
Exp/Cntr=0.3,0.1

Type RM Length L Ch R = 1,3468,404,404,404
BEGIN DESCRIPTION:
MDW T 044 7.0
END DESCRIPTION:
XS GIS Cut Line= 3
      2301564.60      7095994.20      2302177.20      7095716.11
      2302490.64      7095574.53
#Sta/Elev= 30
  4358.9  786.69  4418.6  784.94  4616.3  773.69  4674.1  769.25  4818.1  760.53
  4841.1  757.91  4864.2  756.92  4869.7  757.81  4892.8  757.29  4910.4  755.92
  4955.0  756.18  4967.8  753.67  4985.1  753.02  4990.6  753.80  5011.7  751.92
  5011.9  751.42  5015.7  751.92  5029.9  755.94  5066.6  756.40  5077.5  758.23
  5083.0  757.61  5088.5  759.24  5092.5  759.11  5099.5  758.89  5180.9  766.73
  5227.2  769.64  5255.8  772.66  5264.1  775.08  5286.0  777.89  5375.6  777.83
#Mann=5,-1,0
  4358.9    0.05       0  4955.0    0.12       0  5011.7    0.07       0
  5015.7    0.12       0  5092.5    0.05       0
Bank Sta=5011.7,5015.7
Exp/Cntr=0.3,0.1

Type RM Length L Ch R = 1,3064,375,375,375
BEGIN DESCRIPTION:
MDW T 044 6.0
END DESCRIPTION:
XS GIS Cut Line= 3
      2301814.60      7096254.61      2302225.20      7096046.86
      2302590.10      7095798.61
#Sta/Elev= 30
  4491.9  778.85  4513.4  778.19  4530.1  776.68  4624.8  771.76  4758.5  762.80
  4825.4  757.62  4833.1  755.66  4864.3  752.73  4895.7  752.68  4900.3  752.78
  4914.5  750.97  4920.7  748.75  4921.0  748.25  4924.7  748.75  4936.8  751.70
  4945.1  752.76  4980.9  752.30  5003.9  750.36  5017.1  751.99  5030.9  752.67
  5126.0  752.83  5155.8  754.64  5183.5  757.62  5198.4  757.93  5261.3  763.00
  5276.3  765.61  5291.2  773.62  5312.2  777.31  5333.2  778.87  5393.4  776.99
#Mann=5,-1,0
  4491.9    0.05       0  4895.7    0.12       0  4920.7    0.07       0
  4924.7    0.12       0  5155.8    0.05       0
Bank Sta=4920.7,4924.7
Exp/Cntr=0.3,0.1

Type RM Length L Ch R = 1,2689,283,283,283
BEGIN DESCRIPTION:
MDW T 044 5.0
END DESCRIPTION:
XS GIS Cut Line= 3
      2302085.94      7096405.34      2302344.56      7096359.04
      2302772.39      7095976.57
#Sta/Elev= 30
  4728.3  766.35  4782.0  764.17  4894.0  755.72  4924.4  752.16  4944.7  752.99
  4953.5  751.70  4958.6  752.08  4965.1  750.97  4975.2  747.20  4994.1  746.76
  5000.4  743.48  5005.9  742.83  5006.1  742.33  5009.6  742.33  5009.9  742.83
  5014.6  743.58  5025.8  746.94  5036.3  748.10  5050.5  747.18  5057.2  747.90
  5128.3  748.34  5149.2  749.56  5184.8  749.77  5220.2  751.81  5262.9  752.23
  5318.9  754.64  5333.1  754.32  5391.8  757.11  5439.6  759.11  5564.9  766.49
#Mann=5,-1,0
  4728.3    0.05       0  5005.9   0.033       0  5009.9    0.05       0
  5025.8    0.12       0  5391.8    0.05       0
Bank Sta=5005.9,5009.9
Exp/Cntr=0.3,0.1

Type RM Length L Ch R = 1,2406,308,308,308
BEGIN DESCRIPTION:
MDW T 044 4.0
END DESCRIPTION:
XS GIS Cut Line= 3
      2302275.46      7096655.81      2302508.98      7096569.23
      2302660.51      7096286.42
#Sta/Elev= 30
  4705.0  761.52  4791.2  758.08  4796.5  758.36  4815.4  757.76  4900.7  754.09
  4932.4  752.30  4937.8  752.67  4951.4  751.68  4961.8  751.94  4983.7  747.45
  4998.6  741.98  5003.6  739.47  5003.9  738.97  5007.4  738.97  5007.6  739.47
  5011.3  741.47  5027.6  745.59  5043.8  745.22  5049.5  745.71  5071.4  745.14
  5087.7  746.51  5131.5  746.36  5159.2  747.11  5190.9  748.67  5197.3  749.39
  5203.0  749.07  5219.3  749.57  5225.5  750.24  5235.5  749.67  5274.9  749.89
#Mann=4,-1,0
  4705.0    0.05       0  5003.6   0.033       0  5007.6    0.05       0
  5190.9    0.12       0
Bank Sta=5003.6,5007.6
Exp/Cntr=0.3,0.1

Type RM Length L Ch R = 1,2098,324,324,324
BEGIN DESCRIPTION:
Mapping XS c697e8ed
END DESCRIPTION:
XS GIS Cut Line= 4
      2302492.73      7096625.30      2302681.87      7096619.51
      2302801.94      7096437.09      2302812.36      7096289.28
#Sta/Elev= 30
  4628.2  753.22  4664.5  751.76  4714.5  747.83  4754.5  746.24  4822.1  742.66
  4837.8  743.98  4852.2  744.52  4879.3  743.39  4888.4  743.59  4894.4  742.98
  4909.4  743.72  4915.4  743.35  4945.6  743.84  4951.6  743.34  4960.5  743.96
  4966.7  742.66  4972.6  742.11  4981.7  742.04  4987.7  738.96  4994.4  737.14
  4994.7  736.64  4998.2  736.64  4998.4  737.14  5002.8  743.58  5017.9  747.31
  5042.9  746.55  5069.9  746.38  5123.1  746.29  5180.5  747.98  5184.0  748.00
#Mann=6,-1,0
  4628.2    0.05       0  4837.8    0.12       0  4994.4    0.07       0
  4998.4    0.12       0  5069.9    0.05       0  5180.5    0.12       0
Bank Sta=4994.4,4998.4
Exp/Cntr=0.3,0.1

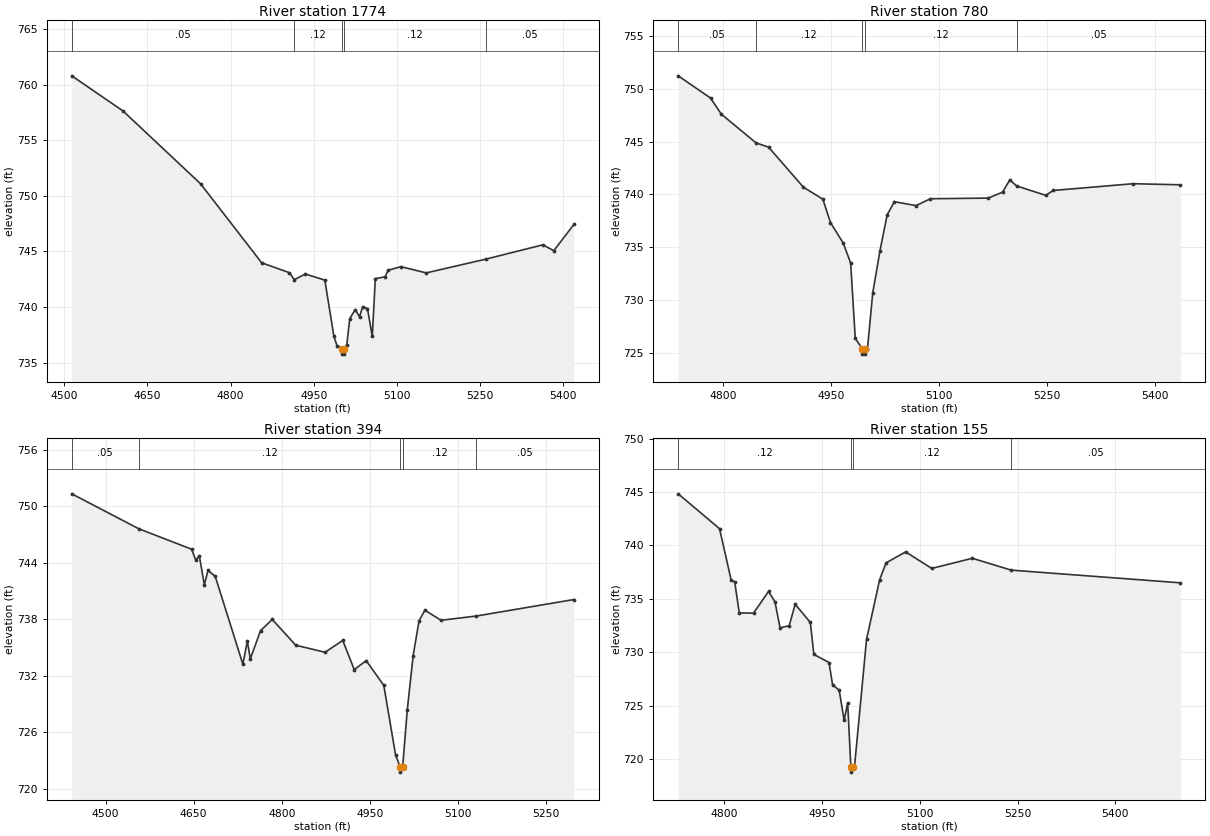
Type RM Length L Ch R = 1,1774,994,994,994
BEGIN DESCRIPTION:
Mapping XS b85fdf0c
END DESCRIPTION:
XS GIS Cut Line= 4
      2302316.54      7096707.91      2302728.85      7096700.07
      2302910.56      7096617.40      2302921.24      7096323.91
#Sta/Elev= 30
  4513.5  760.78  4606.0  757.62  4746.0  751.07  4856.0  743.98  4906.0  743.09
  4915.0  742.46  4934.8  742.97  4970.0  742.42  4986.4  737.36  4992.0  736.52
  5001.0  736.27  5001.2  735.77  5004.7  735.77  5005.0  736.27  5009.5  736.58
  5015.0  738.97  5024.9  739.77  5032.6  739.12  5038.1  740.03  5046.9  739.87
  5055.6  737.36  5061.1  742.55  5078.7  742.72  5084.2  743.31  5107.2  743.63
  5152.9  743.07  5259.9  744.30  5363.1  745.59  5383.1  745.07  5419.2  747.42
#Mann=5,-1,0
  4513.5    0.05       0  4915.0    0.12       0  5001.0    0.07       0
  5005.0    0.12       0  5259.9    0.05       0
Bank Sta=5001,5005
Exp/Cntr=0.3,0.1

Type RM Length L Ch R = 1,780,386,386,386
BEGIN DESCRIPTION:
MDW T 044 2.0
END DESCRIPTION:
XS GIS Cut Line= 5
      2302514.94      7096791.26      2302679.67      7096902.17
      2302739.10      7096918.48      2303011.20      7096930.67
      2303113.39      7096801.75
#Sta/Elev= 30
  4737.6  751.21  4782.4  749.11  4797.4  747.59  4845.6  744.87  4863.0  744.47
  4911.4  740.68  4938.4  739.55  4949.0  737.33  4966.6  735.41  4977.0  733.51
  4983.4  726.39  4993.2  725.40  4993.4  724.90  4996.9  724.90  4997.2  725.40
  5000.3  725.40  5007.7  730.70  5017.7  734.67  5027.7  738.07  5037.8  739.31
  5067.8  738.94  5087.8  739.59  5167.9  739.65  5187.9  740.21  5197.9  741.37
  5207.4  740.80  5248.0  739.91  5258.0  740.37  5369.0  741.01  5434.7  740.91
#Mann=5,-1,0
  4737.6    0.05       0  4845.6    0.12       0  4993.2    0.07       0
  4997.2    0.12       0  5207.4    0.05       0
Bank Sta=4993.2,4997.2
Exp/Cntr=0.3,0.1

Type RM Length L Ch R = 1,394,239,239,239
BEGIN DESCRIPTION:
Mapping XS 478aa5f9
END DESCRIPTION:
XS GIS Cut Line= 5
      2302414.69      7096989.19      2302609.84      7097132.90
      2302853.29      7097141.49      2302999.02      7097140.58
      2303076.61      7096930.65
#Sta/Elev= 30
  4442.3  751.34  4556.4  747.63  4646.4  745.46  4653.5  744.31  4659.7  744.74
  4668.2  741.67  4674.4  743.20  4686.7  742.58  4733.8  733.25  4741.5  735.69
  4746.5  733.81  4763.9  736.80  4783.9  738.00  4823.9  735.26  4873.9  734.51
  4904.0  735.77  4923.6  732.67  4944.0  733.62  4974.0  730.99  4994.0  723.62
  5002.0  722.28  5002.2  721.78  5006.0  722.28  5014.0  728.40  5024.0  734.16
  5034.0  737.85  5044.0  738.98  5071.5  737.91  5131.6  738.36  5297.8  740.11
#Mann=5,-1,0
  4442.3    0.05       0  4556.4    0.12       0  5002.0    0.07       0
  5006.0    0.12       0  5131.6    0.05       0
Bank Sta=5002,5006
Exp/Cntr=0.3,0.1

Type RM Length L Ch R = 1,155,0,0,0
BEGIN DESCRIPTION:
MDW T 044 1.0
END DESCRIPTION:
XS GIS Cut Line= 4
      2302533.39      7097160.33      2302780.48      7097270.61
      2302921.49      7097265.64      2303260.02      7097145.79
#Sta/Elev= 30
  4729.0  744.84  4792.4  741.57  4810.2  736.78  4815.7  736.59  4822.7  733.68
  4844.6  733.66  4867.6  735.69  4877.5  734.72  4885.3  732.28  4899.4  732.48
  4908.5  734.49  4931.8  732.79  4937.2  729.79  4960.5  729.03  4965.9  726.96
  4976.1  726.43  4983.7  723.61  4989.1  725.25  4994.0  719.26  4994.3  718.76
  4998.0  719.26  4999.6  719.26  5018.1  731.20  5038.1  736.77  5048.1  738.37
  5078.1  739.40  5118.2  737.85  5180.5  738.80  5240.2  737.69  5499.8  736.50
#Mann=4,-1,0
  4729.0    0.12       0  4994.0    0.07       0  4998.0    0.12       0
  5240.2    0.05       0
Bank Sta=4994,4998
Exp/Cntr=0.3,0.1

Chan Stop Cuts=-1