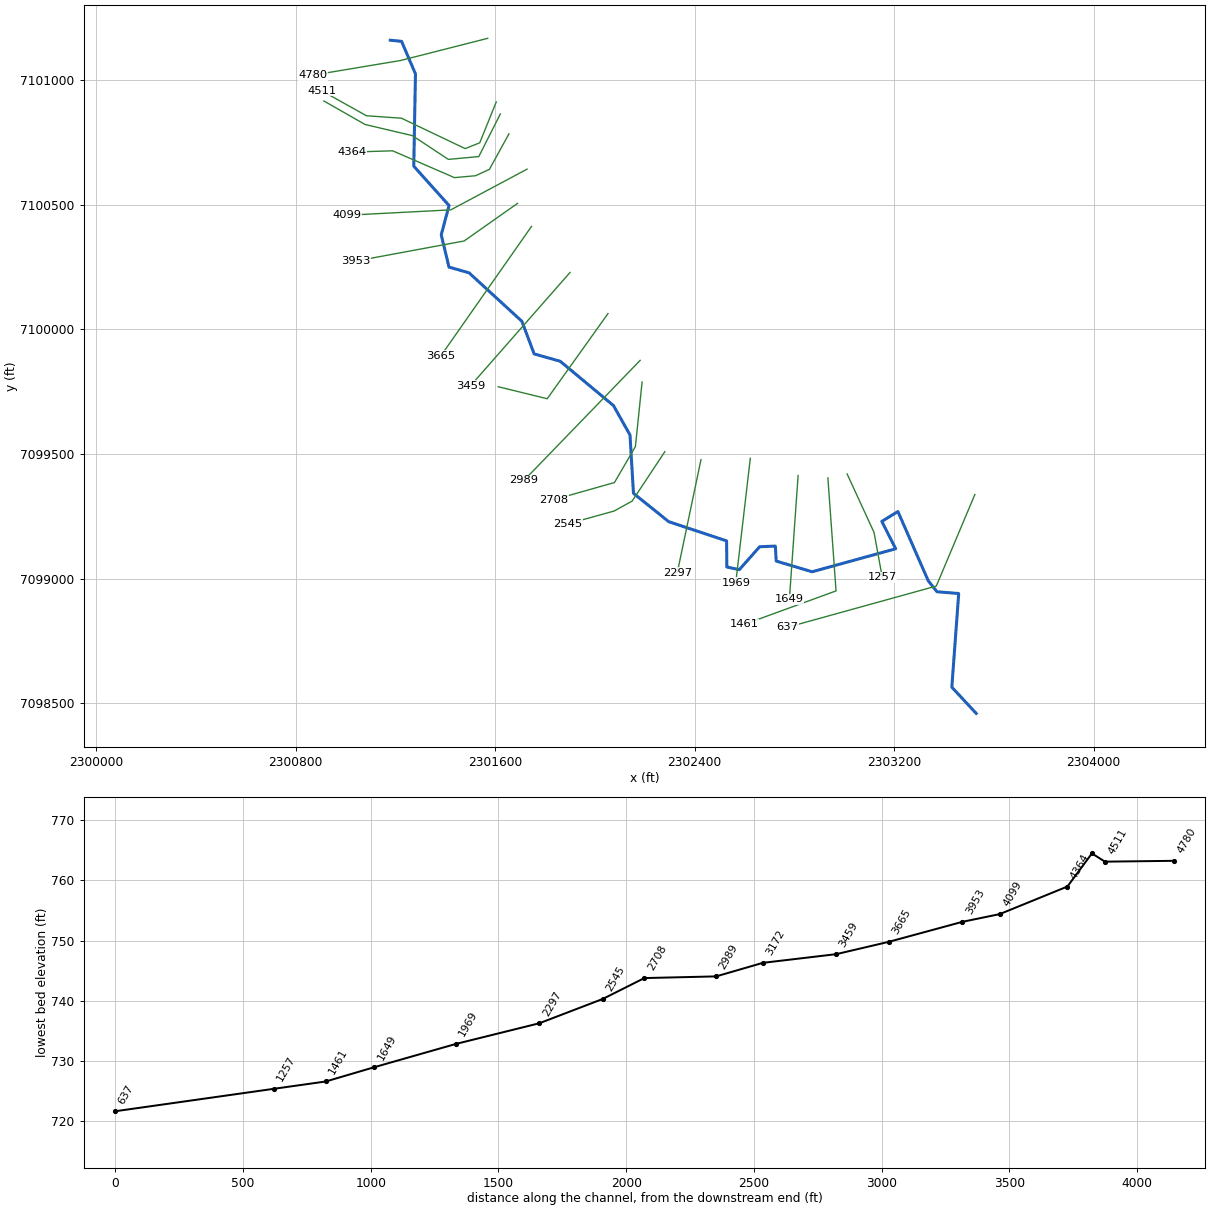
--- MDW T 045.prj (project) ---

Proj Title=MDW T 045 Base Level Engineering
Current Plan=p01
Default Exp/Contr=0.3,0.1
English Units
Geom File=g01
Flow File=f01
Plan File=p01
BEGIN DESCRIPTION:
MDW T 045
END DESCRIPTION:

--- MDW T 045.p01 (plan) ---

Plan Title=Multiple Run
Short Identifier=Multiple
Geom File=g01
Flow File=f01
Subcritical Flow
K Sum by GR= 0
Std Step Tol= 0.01
Critical Tol= 0.01
Num of Std Step Trials= 20
Max Error Tol= 0.3
Flow Tol Ratio= 0.001
Split Flow NTrial= 30
Split Flow Tol= 0.02
Split Flow Ratio= 0.02
Log Output Level= 0
Friction Slope Method= 1
Unsteady Friction Slope Method= 2
Unsteady Bridges Friction Slope Method= 1
Parabolic Critical Depth
Global Vel Dist=  1 , 1 , 1
Global Log Level= 0
CheckData=True
Encroach Param= -1, 0, 0, 0
BEGIN DESCRIPTION:
Multiple Run
END DESCRIPTION:

--- MDW T 045.f01 (steady flow) ---

Flow Title=Multiple
Number of Profiles=7
Profile Names=10-year,25-year,50-year,1pct_min,100-year,1pct_plu,500-year
River Rch & RM= MDW T 045,Reach-1,4780
     547     749     915     556    1109    2213    1632
Boundary for River Rch & Prof#=MDW T 045,Reach-1,1
Up Type=0
Dn Type=3
Dn Slope=0.005
Boundary for River Rch & Prof#=MDW T 045,Reach-1,2
Up Type=0
Dn Type=3
Dn Slope=0.005
Boundary for River Rch & Prof#=MDW T 045,Reach-1,3
Up Type=0
Dn Type=3
Dn Slope=0.005
Boundary for River Rch & Prof#=MDW T 045,Reach-1,4
Up Type=0
Dn Type=3
Dn Slope=0.005
Boundary for River Rch & Prof#=MDW T 045,Reach-1,5
Up Type=0
Dn Type=3
Dn Slope=0.005
Boundary for River Rch & Prof#=MDW T 045,Reach-1,6
Up Type=0
Dn Type=3
Dn Slope=0.005
Boundary for River Rch & Prof#=MDW T 045,Reach-1,7
Up Type=0
Dn Type=3
Dn Slope=0.005

--- MDW T 045.g01 (geometry) ---

Geom Title=Existing Conditions

River Reach=MDW T 045,Reach-1
Reach XY= 30
      2301179.00      7101160.00      2301224.38      7101155.37
      2301280.06      7101024.81      2301273.24      7100654.82
      2301414.78      7100496.98      2301383.44      7100379.43
      2301414.47      7100250.00      2301495.13      7100226.94
      2301706.82      7100032.64      2301756.06      7099901.86
      2301860.74      7099872.22      2302074.18      7099694.61
      2302140.51      7099576.93      2302154.43      7099342.62
      2302295.41      7099229.13      2302527.93      7099151.88
      2302529.01      7099047.18      2302578.92      7099036.32
      2302660.31      7099128.21      2302723.47      7099131.15
      2302726.97      7099070.86      2302871.04      7099027.97
      2303206.17      7099120.23      2303150.45      7099230.05
      2303215.15      7099269.42      2303336.77      7098991.85
      2303371.70      7098947.82      2303458.91      7098940.77
      2303431.31      7098564.98      2303529.00      7098460.00

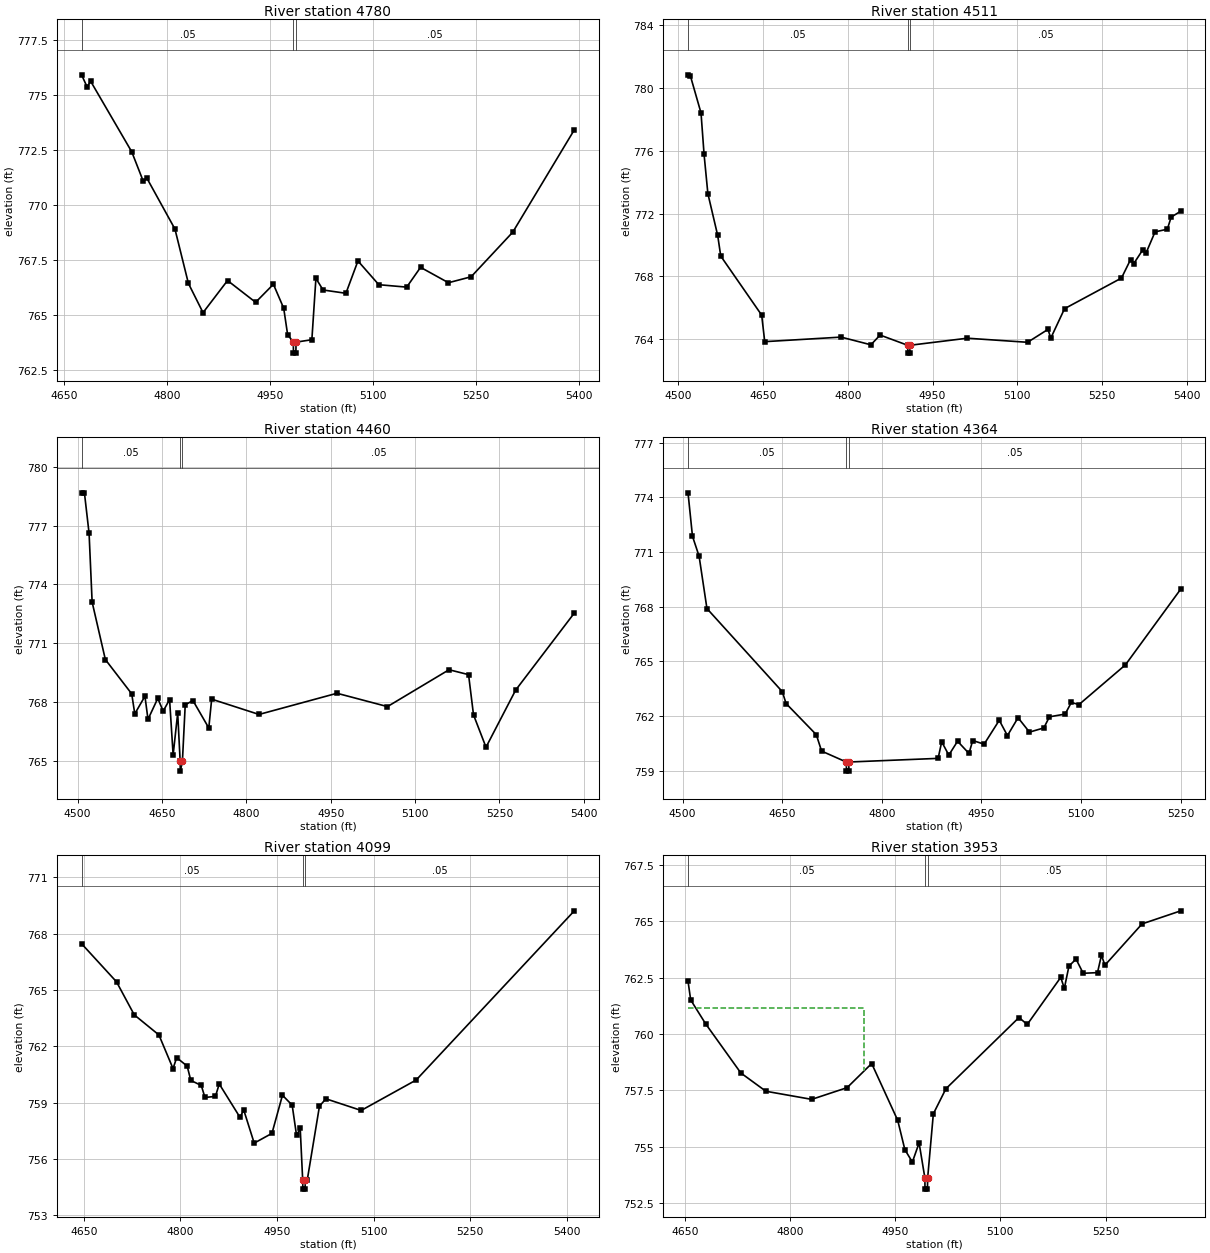
Type RM Length L Ch R = 1,4780,269,269,269
BEGIN DESCRIPTION:
MDW T 045 8.0
END DESCRIPTION:
XS GIS Cut Line= 3
      2301569.80      7101167.50      2301221.17      7101078.79
      2300868.20      7101019.80
#Sta/Elev= 30
  4675.6  775.90  4683.7  775.35  4688.8  775.61  4748.7  772.40  4765.5  771.06
  4770.6  771.21  4811.6  768.89  4831.2  766.42  4852.5  765.09  4888.2  766.55
  4929.1  765.56  4955.0  766.38  4970.0  765.29  4975.7  764.09  4984.0  763.75
  4984.2  763.25  4987.7  763.25  4988.0  763.75  5011.0  763.86  5016.9  766.65
  5027.3  766.12  5060.6  765.97  5078.1  767.44  5108.5  766.36  5149.1  766.25
  5169.3  767.15  5209.9  766.45  5242.9  766.72  5303.6  768.75  5393.2  773.40
#Mann=3,-1,0
  4675.6    0.05       0  4984.0    0.04       0  4988.0    0.05       0
Bank Sta=4984,4988
Exp/Cntr=0.3,0.1

Type RM Length L Ch R = 1,4511,51,51,51
BEGIN DESCRIPTION:
Mapping XS 44f2b6ab
END DESCRIPTION:
XS GIS Cut Line= 6
      2301604.17      7100912.53      2301537.83      7100748.47
      2301479.55      7100725.21      2301223.79      7100847.13
      2301083.51      7100857.01      2300904.17      7100957.08
#Sta/Elev= 30
  4517.5  780.83  4521.8  780.75  4540.5  778.40  4545.9  775.76  4552.6  773.27
  4570.0  770.60  4575.4  769.29  4647.8  765.53  4653.2  763.84  4788.3  764.13
  4841.0  763.64  4857.3  764.26  4906.1  763.61  4906.4  763.11  4909.9  763.11
  4910.1  763.61  5011.5  764.06  5118.2  763.80  5154.2  764.62  5159.3  764.07
  5183.6  765.94  5284.3  767.89  5300.3  769.06  5306.0  768.81  5322.0  769.69
  5327.8  769.49  5343.7  770.83  5365.4  771.00  5372.2  771.77  5389.2  772.15
#Mann=3,-1,0
  4517.5    0.05       0  4906.1   0.033       0  4910.1    0.05       0
Bank Sta=4906.1,4910.1
Exp/Cntr=0.3,0.1

Type RM Length L Ch R = 1,4460,96,96,96
BEGIN DESCRIPTION:
Mapping XS 2a4013aa
END DESCRIPTION:
XS GIS Cut Line= 6
      2301620.61      7100864.33      2301533.96      7100693.26
      2301411.96      7100681.99      2301267.80      7100777.27
      2301077.85      7100822.02      2300912.64      7100916.27
#Sta/Elev= 30
  4507.1  778.67  4512.2  778.67  4520.5  776.60  4525.9  773.10  4549.4  770.17
  4596.3  768.42  4601.7  767.40  4619.8  768.30  4625.2  767.12  4642.6  768.19
  4652.2  767.54  4663.6  768.13  4669.9  765.30  4678.0  767.44  4682.4  764.98
  4682.6  764.48  4686.4  764.98  4691.4  767.86  4705.1  768.08  4733.3  766.68
  4738.4  768.15  4822.6  767.37  4961.2  768.45  5050.9  767.77  5160.4  769.65
  5195.1  769.40  5203.9  767.35  5226.1  765.70  5278.8  768.61  5383.1  772.54
#Mann=3,-1,0
  4507.1    0.05       0  4682.4   0.033       0  4686.4    0.05       0
Bank Sta=4682.4,4686.4
Exp/Cntr=0.3,0.1

Type RM Length L Ch R = 1,4364,265,265,265
BEGIN DESCRIPTION:
Mapping XS 2972d916
END DESCRIPTION:
XS GIS Cut Line= 6
      2301655.14      7100784.64      2301576.60      7100641.98
      2301520.72      7100616.38      2301436.58      7100608.83
      2301188.42      7100716.38      2301025.67      7100711.36
#Sta/Elev= 30
  4508.2  774.25  4514.9  771.87  4524.9  770.77  4536.7  767.90  4650.2  763.34
  4655.9  762.69  4701.4  760.98  4709.4  760.08  4746.6  759.48  4746.9  758.98
  4750.4  758.98  4750.6  759.48  4884.9  759.68  4890.3  760.59  4901.0  759.86
  4914.2  760.62  4931.4  759.95  4937.0  760.66  4954.2  760.46  4977.0  761.77
  4989.3  760.93  5005.3  761.91  5022.5  761.12  5044.1  761.35  5052.6  761.96
  5076.2  762.11  5085.6  762.75  5097.0  762.63  5167.0  764.81  5250.4  768.97
#Mann=3,-1,0
  4508.2    0.05       0  4746.6   0.033       0  4750.6    0.05       0
Bank Sta=4746.6,4750.6
Exp/Cntr=0.3,0.1

Type RM Length L Ch R = 1,4099,146,146,146
BEGIN DESCRIPTION:
Mapping XS 8f3be923
END DESCRIPTION:
XS GIS Cut Line= 3
      2301727.70      7100642.82      2301421.71      7100479.50
      2301003.62      7100457.88
#Sta/Elev= 30
  4646.4  767.47  4700.7  765.44  4728.3  763.68  4766.6  762.61  4788.5  760.82
  4794.2  761.40  4810.5  760.95  4816.1  760.19  4832.4  759.92  4838.1  759.28
  4854.4  759.34  4860.3  760.00  4892.6  758.22  4898.3  758.62  4914.6  756.85
  4942.2  757.37  4958.5  759.40  4973.6  758.87  4980.4  757.26  4986.1  757.63
  4989.9  754.90  4990.2  754.40  4993.7  754.40  4993.9  754.90  4997.1  754.90
  5016.0  758.82  5026.0  759.21  5080.8  758.59  5166.2  760.21  5411.9  769.22
#Mann=3,-1,0
  4646.4    0.05       0  4989.9   0.033       0  4993.9    0.05       0
Bank Sta=4989.9,4993.9
Exp/Cntr=0.3,0.1

Type RM Length L Ch R = 1,3953,288,288,288
BEGIN DESCRIPTION:
Mapping XS 50e98c0c
END DESCRIPTION:
XS GIS Cut Line= 3
      2301689.51      7100505.53      2301475.22      7100354.70
      2301042.24      7100274.48
#Sta/Elev= 30
  4654.7  762.34  4658.5  761.51  4679.8  760.45  4730.0  758.27  4765.7  757.46
  4831.0  757.10  4881.5  757.62  4916.5  758.69  4953.6  756.17  4963.8  754.87
  4974.5  754.32  4984.1  755.17  4992.3  753.62  4992.5  753.12  4996.0  753.12
  4996.3  753.62  5004.4  756.46  5022.3  757.57  5126.5  760.73  5138.2  760.42
  5186.0  762.51  5191.1  762.02  5197.7  763.01  5207.8  763.32  5218.0  762.69
  5238.4  762.72  5244.0  763.49  5249.0  763.05  5301.9  764.88  5357.1  765.46
#Mann=3,-1,0
  4654.7    0.05       0  4992.3    0.04       0  4996.3    0.05       0
#XS Ineff=2,0
    0.00 4905.10  761.14               0
Permanent Ineff=
       F       F
Bank Sta=4992.3,4996.3
Exp/Cntr=0.3,0.1

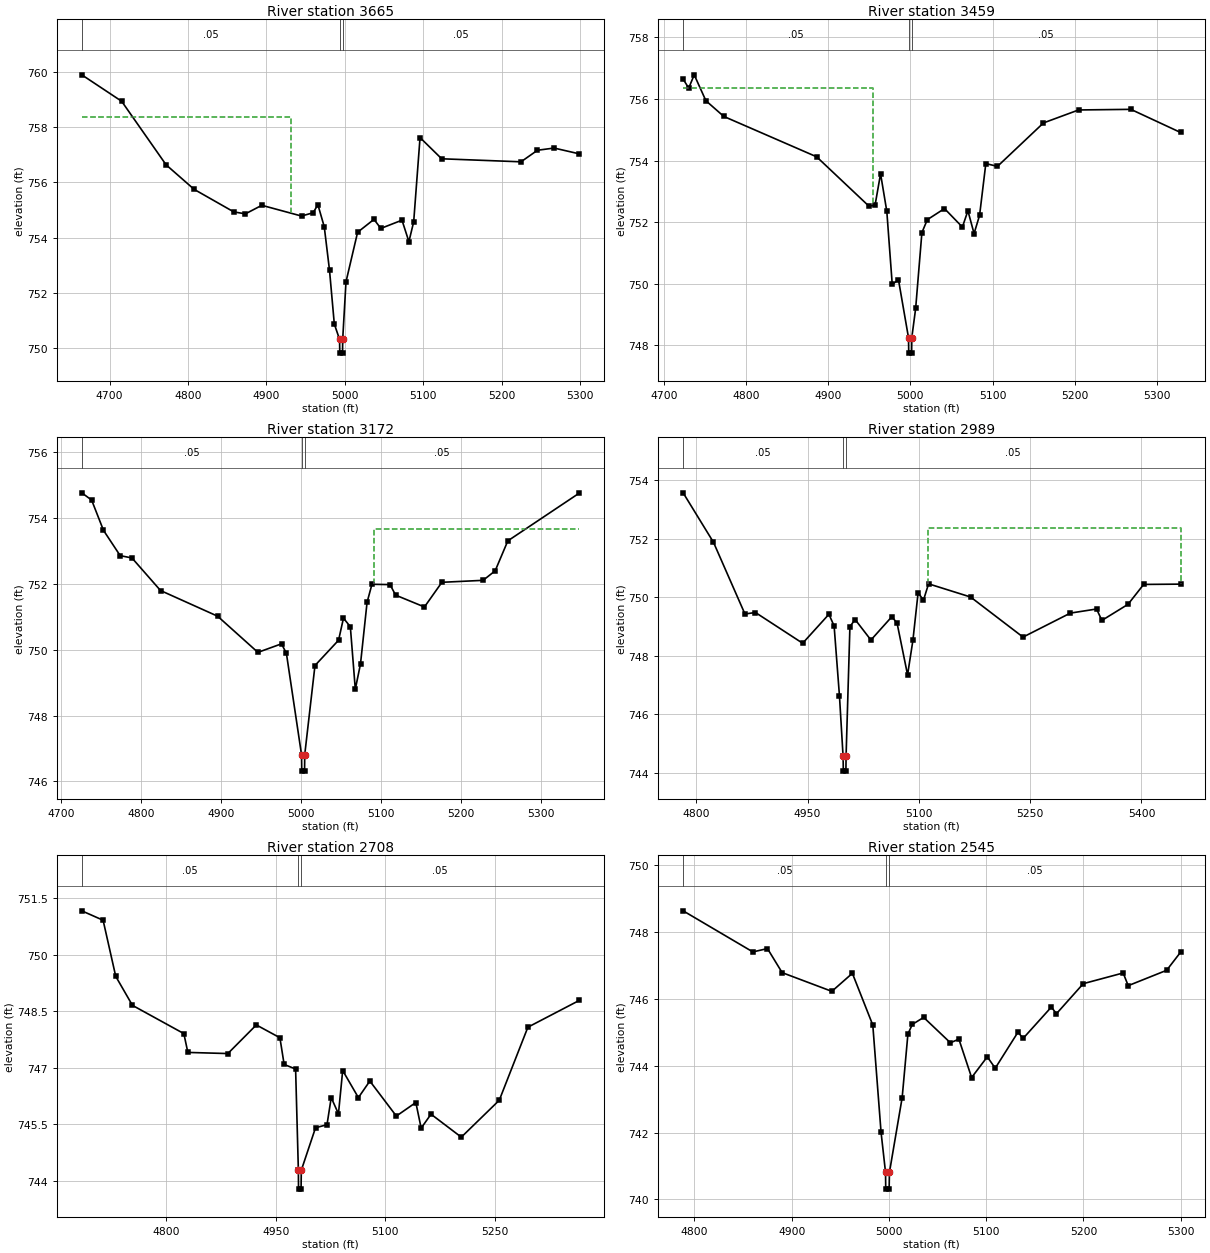
Type RM Length L Ch R = 1,3665,206,206,206
BEGIN DESCRIPTION:
Mapping XS a691e966
END DESCRIPTION:
XS GIS Cut Line= 2
      2301745.52      7100413.21      2301381.77      7099893.81
#Sta/Elev= 30
  4664.6  759.91  4715.4  758.95  4772.1  756.64  4807.8  755.75  4858.4  754.93
  4873.2  754.86  4894.1  755.17  4944.7  754.78  4959.5  754.90  4965.6  755.19
  4973.7  754.39  4980.4  752.81  4986.5  750.86  4993.2  750.30  4993.5  749.80
  4997.0  749.80  4997.2  750.30  5001.4  752.39  5016.2  754.19  5037.1  754.66
  5045.8  754.33  5072.8  754.63  5081.6  753.85  5087.7  754.57  5095.8  757.63
  5123.4  756.86  5224.5  756.75  5245.5  757.17  5266.7  757.25  5298.7  757.04
#Mann=3,-1,0
  4664.6    0.05       0  4993.2    0.04       0  4997.2    0.05       0
#XS Ineff=2,0
    0.00 4930.70  758.37               0
Permanent Ineff=
       F       F
Bank Sta=4993.2,4997.2
Exp/Cntr=0.3,0.1

Type RM Length L Ch R = 1,3459,287,287,287
BEGIN DESCRIPTION:
Mapping XS 73c3eac5
END DESCRIPTION:
XS GIS Cut Line= 2
      2301900.01      7100228.45      2301500.52      7099773.57
#Sta/Elev= 30
  4723.4  756.64  4730.2  756.35  4736.9  756.78  4751.1  755.94  4772.9  755.43
  4885.9  754.12  4949.5  752.52  4957.0  752.55  4963.7  753.57  4971.3  752.35
  4977.9  749.98  4985.5  750.13  4997.7  748.25  4998.0  747.75  5001.5  747.75
  5001.7  748.25  5006.4  749.20  5014.0  751.66  5020.6  752.08  5041.5  752.44
  5063.3  751.84  5070.0  752.37  5077.5  751.63  5084.2  752.22  5091.8  753.90
  5106.0  753.81  5162.0  755.22  5204.7  755.64  5268.3  755.66  5328.8  754.91
#Mann=3,-1,0
  4723.4    0.05       0  4997.7    0.04       0  5001.7    0.05       0
#XS Ineff=2,0
    0.00 4954.70  756.35               0
Permanent Ineff=
       F       F
Bank Sta=4997.7,5001.7
Exp/Cntr=0.3,0.1

Type RM Length L Ch R = 1,3172,183,183,183
BEGIN DESCRIPTION:
Mapping XS ea867a43
END DESCRIPTION:
XS GIS Cut Line= 3
      2302052.22      7100063.57      2301808.56      7099722.00
      2301612.32      7099770.04
#Sta/Elev= 30
  4726.1  754.77  4738.4  754.55  4753.2  753.63  4774.1  752.86  4788.8  752.79
  4824.5  751.80  4895.8  751.02  4946.2  749.92  4975.7  750.18  4981.8  749.89
  5000.7  746.81  5001.0  746.31  5004.5  746.31  5004.7  746.81  5017.5  749.52
  5047.0  750.29  5053.1  750.96  5061.7  750.70  5067.9  748.80  5074.4  749.57
  5082.6  751.44  5088.7  751.99  5111.3  751.98  5118.3  751.66  5154.3  751.30
  5176.1  752.05  5227.6  752.11  5242.7  752.40  5258.5  753.31  5347.7  754.76
#Mann=3,-1,0
  4726.1    0.05       0  5000.7    0.04       0  5004.7    0.05       0
#XS Ineff=2,0
       0                 5091.00    0.00  753.67
Permanent Ineff=
       F       F
Bank Sta=5000.7,5004.7
Exp/Cntr=0.3,0.1

Type RM Length L Ch R = 1,2989,281,281,281
BEGIN DESCRIPTION:
Mapping XS fe2412c5
END DESCRIPTION:
XS GIS Cut Line= 2
      2302181.12      7099875.75      2301714.86      7099394.05
#Sta/Elev= 30
  4782.3  753.57  4823.2  751.88  4865.6  749.43  4879.8  749.48  4943.4  748.43
  4978.8  749.42  4985.8  749.02  4993.0  746.63  4997.9  744.56  4998.2  744.06
  5001.7  744.06  5001.9  744.56  5007.1  749.00  5014.1  749.24  5035.4  748.54
  5063.7  749.34  5070.7  749.11  5084.8  747.35  5092.0  748.53  5099.0  750.16
  5106.2  749.90  5113.1  750.46  5169.7  750.01  5240.4  748.64  5304.2  749.46
  5339.5  749.60  5346.7  749.21  5381.9  749.76  5403.0  750.44  5452.7  750.45
#Mann=3,-1,0
  4782.3    0.05       0  4997.9    0.04       0  5001.9    0.05       0
#XS Ineff=2,0
       0                 5112.90    0.00  752.37
Permanent Ineff=
       F       F
Bank Sta=4997.9,5001.9
Exp/Cntr=0.3,0.1

Type RM Length L Ch R = 1,2708,163,163,163
BEGIN DESCRIPTION:
Mapping XS aa3c8b0a
END DESCRIPTION:
XS GIS Cut Line= 4
      2302189.01      7099789.02      2302162.23      7099530.16
      2302078.10      7099385.80      2301833.62      7099316.65
#Sta/Elev= 30
  4684.2  751.17  4713.4  750.92  4730.7  749.43  4753.6  748.66  4824.0  747.91
  4829.5  747.41  4884.3  747.38  4923.3  748.14  4955.6  747.80  4961.4  747.09
  4977.1  746.97  4980.9  744.28  4981.1  743.78  4984.6  743.78  4984.9  744.28
  5004.4  745.41  5020.1  745.49  5025.9  746.21  5035.8  745.78  5041.6  746.93
  5063.1  746.21  5078.8  746.65  5115.1  745.72  5141.8  746.08  5149.1  745.40
  5162.6  745.77  5204.1  745.16  5256.1  746.14  5295.3  748.08  5365.6  748.79
#Mann=3,-1,0
  4684.2    0.05       0  4980.9    0.04       0  4984.9    0.05       0
Bank Sta=4980.9,4984.9
Exp/Cntr=0.3,0.1

Type RM Length L Ch R = 1,2545,248,248,248
BEGIN DESCRIPTION:
Mapping XS 972a4174
END DESCRIPTION:
XS GIS Cut Line= 4
      2302280.33      7099509.67      2302149.06      7099311.45
      2302076.20      7099271.36      2301892.62      7099220.50
#Sta/Elev= 30
  4788.4  748.64  4860.1  747.41  4875.1  747.51  4890.2  746.79  4941.3  746.23
  4962.4  746.77  4983.4  745.22  4991.9  742.01  4996.5  740.81  4996.7  740.31
  5000.2  740.31  5000.5  740.81  5013.6  743.05  5019.5  744.95  5024.0  745.24
  5035.7  745.45  5063.2  744.69  5071.9  744.80  5085.0  743.65  5101.1  744.27
  5109.3  743.93  5132.7  745.01  5137.9  744.82  5167.0  745.76  5172.2  745.56
  5199.8  746.46  5240.8  746.78  5246.0  746.40  5285.5  746.86  5299.8  747.40
#Mann=3,-1,0
  4788.4    0.05       0  4996.5   0.033       0  5000.5    0.05       0
Bank Sta=4996.5,5000.5
Exp/Cntr=0.3,0.1

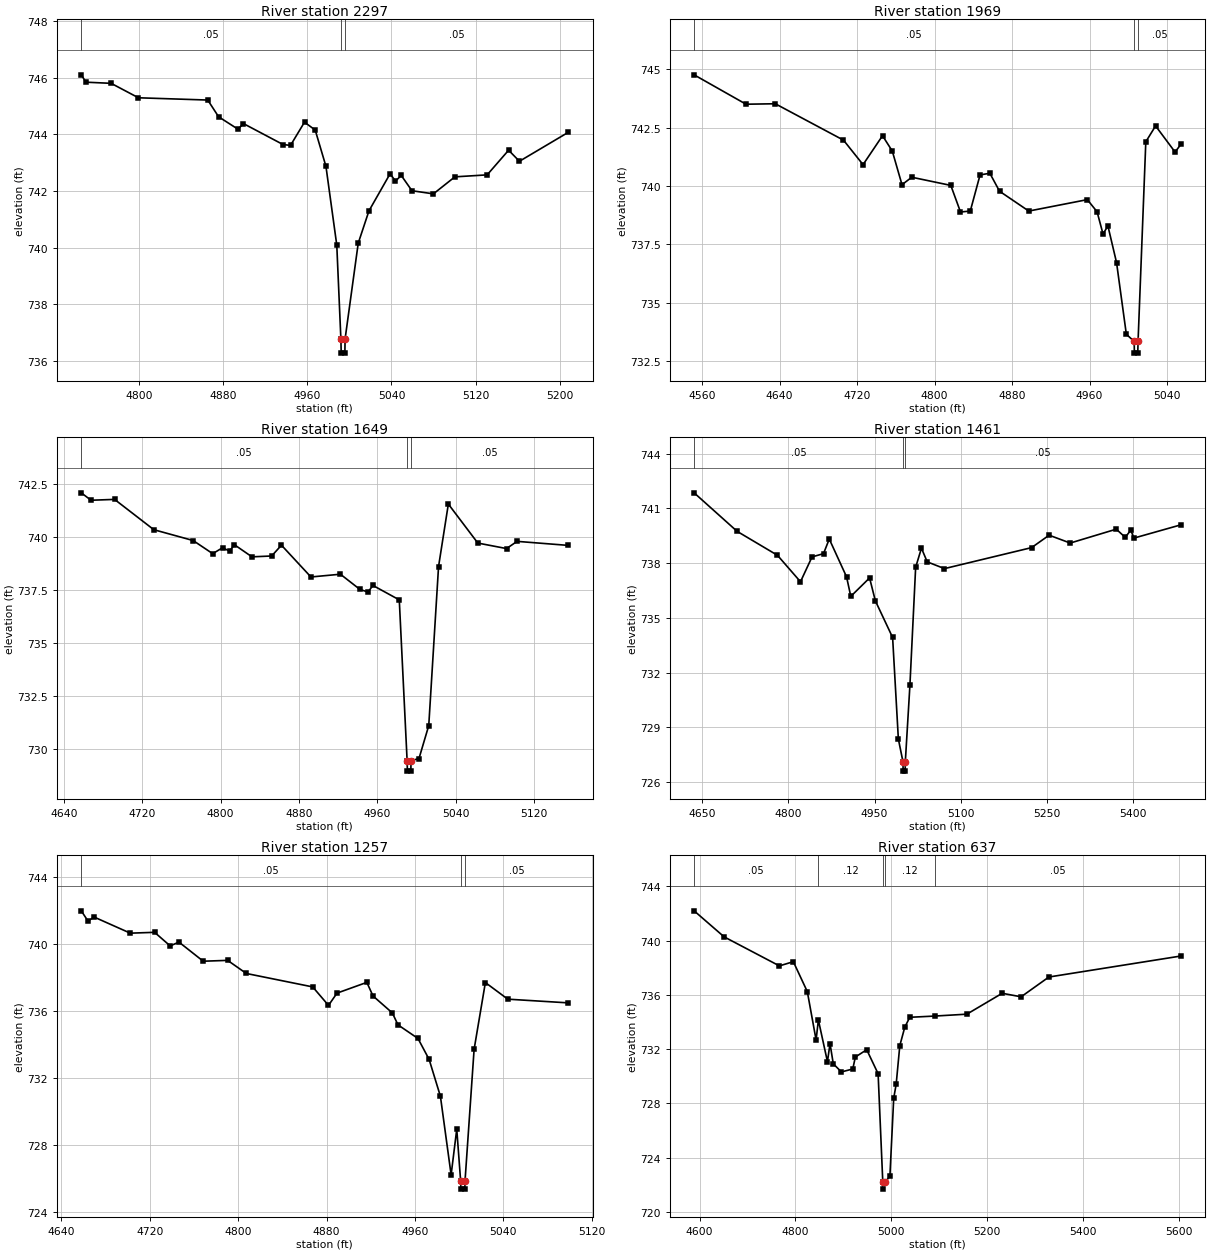
Type RM Length L Ch R = 1,2297,328,328,328
BEGIN DESCRIPTION:
Mapping XS 5dd75b8e
END DESCRIPTION:
XS GIS Cut Line= 2
      2302425.25      7099477.78      2302330.22      7099024.54
#Sta/Elev= 30
  4745.0  746.10  4749.5  745.84  4773.4  745.80  4799.4  745.29  4865.3  745.21
  4875.6  744.62  4894.1  744.18  4899.2  744.38  4936.9  743.64  4944.0  743.61
  4957.3  744.43  4967.5  744.15  4977.7  742.87  4988.0  740.09  4991.9  736.78
  4992.2  736.28  4995.7  736.28  4995.9  736.78  5008.4  740.16  5018.6  741.30
  5038.7  742.61  5043.8  742.35  5049.3  742.55  5059.5  742.01  5079.9  741.90
  5100.3  742.50  5131.0  742.57  5151.4  743.44  5161.7  743.05  5208.1  744.07
#Mann=3,-1,0
  4745.0    0.05       0  4991.9    0.04       0  4995.9    0.05       0
Bank Sta=4991.9,4995.9
Exp/Cntr=0.3,0.1

Type RM Length L Ch R = 1,1969,320,320,320
BEGIN DESCRIPTION:
Mapping XS c5a30445
END DESCRIPTION:
XS GIS Cut Line= 2
      2302623.12      7099483.19      2302564.77      7098983.89
#Sta/Elev= 30
  4551.8  744.76  4605.4  743.50  4635.6  743.52  4706.0  741.96  4726.2  740.91
  4746.3  742.15  4756.4  741.49  4766.4  740.05  4776.5  740.37  4816.8  740.02
  4826.8  738.88  4836.9  738.92  4847.0  740.47  4857.1  740.54  4867.1  739.77
  4897.3  738.92  4957.7  739.41  4967.8  738.89  4973.9  737.94  4979.0  738.28
  4987.9  736.71  4998.0  733.64  5006.1  733.33  5006.3  732.83  5009.8  732.83
  5010.1  733.33  5018.1  741.89  5028.2  742.57  5048.3  741.45  5054.5  741.79
#Mann=3,-1,0
  4551.8    0.05       0  5006.1    0.04       0  5010.1    0.05       0
Bank Sta=5006.1,5010.1
Exp/Cntr=0.3,0.1

Type RM Length L Ch R = 1,1649,188,188,188
BEGIN DESCRIPTION:
Mapping XS 5c67fda1
END DESCRIPTION:
XS GIS Cut Line= 2
      2302814.78      7099413.91      2302779.88      7098917.93
#Sta/Elev= 30
  4657.7  742.09  4667.7  741.74  4691.7  741.78  4731.8  740.35  4771.9  739.84
  4791.9  739.22  4802.0  739.50  4809.1  739.34  4814.1  739.64  4832.0  739.07
  4852.1  739.11  4862.1  739.62  4892.2  738.12  4922.3  738.25  4942.3  737.53
  4950.5  737.41  4955.5  737.72  4982.4  737.04  4990.4  729.46  4990.7  728.96
  4994.2  728.96  4994.4  729.46  5002.5  729.55  5012.5  731.11  5022.5  738.61
  5032.5  741.56  5062.6  739.72  5091.9  739.46  5102.7  739.80  5154.9  739.61
#Mann=3,-1,0
  4657.7    0.05       0  4990.4   0.033       0  4994.4    0.05       0
Bank Sta=4990.4,4994.4
Exp/Cntr=0.3,0.1

Type RM Length L Ch R = 1,1461,204,204,204
BEGIN DESCRIPTION:
Mapping XS 8cdb1186
END DESCRIPTION:
XS GIS Cut Line= 3
      2302934.16      7099404.72      2302966.95      7098951.21
      2302597.64      7098816.51
#Sta/Elev= 30
  4635.9  741.85  4710.8  739.74  4781.0  738.43  4821.1  736.98  4841.2  738.34
  4861.2  738.52  4871.2  739.32  4901.3  737.25  4908.7  736.18  4941.4  737.19
  4951.4  735.94  4981.5  733.93  4991.5  728.37  4999.6  727.11  4999.8  726.61
  5003.3  726.61  5003.6  727.11  5011.6  731.30  5021.6  737.77  5031.7  738.82
  5041.7  738.07  5071.8  737.70  5223.5  738.85  5254.0  739.53  5290.7  739.10
  5370.9  739.86  5386.5  739.41  5396.2  739.81  5401.5  739.37  5483.7  740.10
#Mann=3,-1,0
  4635.9    0.05       0  4999.6   0.033       0  5003.6    0.05       0
Bank Sta=4999.6,5003.6
Exp/Cntr=0.3,0.1

Type RM Length L Ch R = 1,1257,620,620,620
BEGIN DESCRIPTION:
Mapping XS 466afc04
END DESCRIPTION:
XS GIS Cut Line= 3
      2303011.36      7099420.33      2303119.42      7099185.52
      2303152.25      7099006.18
#Sta/Elev= 30
  4658.0  741.96  4664.1  741.35  4669.6  741.59  4702.4  740.63  4724.4  740.68
  4738.5  739.87  4746.4  740.10  4768.4  738.96  4790.5  739.01  4807.4  738.23
  4867.5  737.43  4881.8  736.33  4889.5  737.06  4916.5  737.70  4922.1  736.89
  4939.6  735.88  4944.7  735.17  4962.8  734.36  4972.9  733.11  4983.1  730.92
  4992.8  726.24  4997.9  728.96  5001.4  725.89  5001.7  725.39  5005.2  725.39
  5005.4  725.89  5013.6  733.71  5023.8  737.69  5044.1  736.70  5098.8  736.48
#Mann=3,-1,0
  4658.0    0.05       0  5001.4   0.033       0  5005.4    0.05       0
Bank Sta=5001.4,5005.4
Exp/Cntr=0.3,0.1

Type RM Length L Ch R = 1,637,0,0,0
BEGIN DESCRIPTION:
MDW T 045 1.0
END DESCRIPTION:
XS GIS Cut Line= 3
      2303523.71      7099337.76      2303369.02      7098970.65
      2302773.00      7098805.67
#Sta/Elev= 30
  4588.5  742.19  4651.2  740.27  4766.6  738.13  4795.7  738.44  4824.9  736.23
  4843.2  732.67  4848.0  734.14  4866.9  731.07  4872.3  732.40  4879.1  730.91
  4896.1  730.31  4919.8  730.53  4925.2  731.41  4948.9  731.95  4972.7  730.18
  4982.5  722.17  4982.8  721.67  4986.5  722.17  4997.3  722.61  5005.3  728.38
  5010.4  729.40  5018.0  732.25  5028.4  733.61  5038.8  734.34  5090.6  734.43
  5158.0  734.57  5231.8  736.11  5271.3  735.85  5329.3  737.31  5605.3  738.86
#Mann=5,-1,0
  4588.5    0.05       0  4848.0    0.12       0  4982.5    0.07       0
  4986.5    0.12       0  5090.6    0.05       0
Bank Sta=4982.5,4986.5
Exp/Cntr=0.3,0.1

Chan Stop Cuts=-1