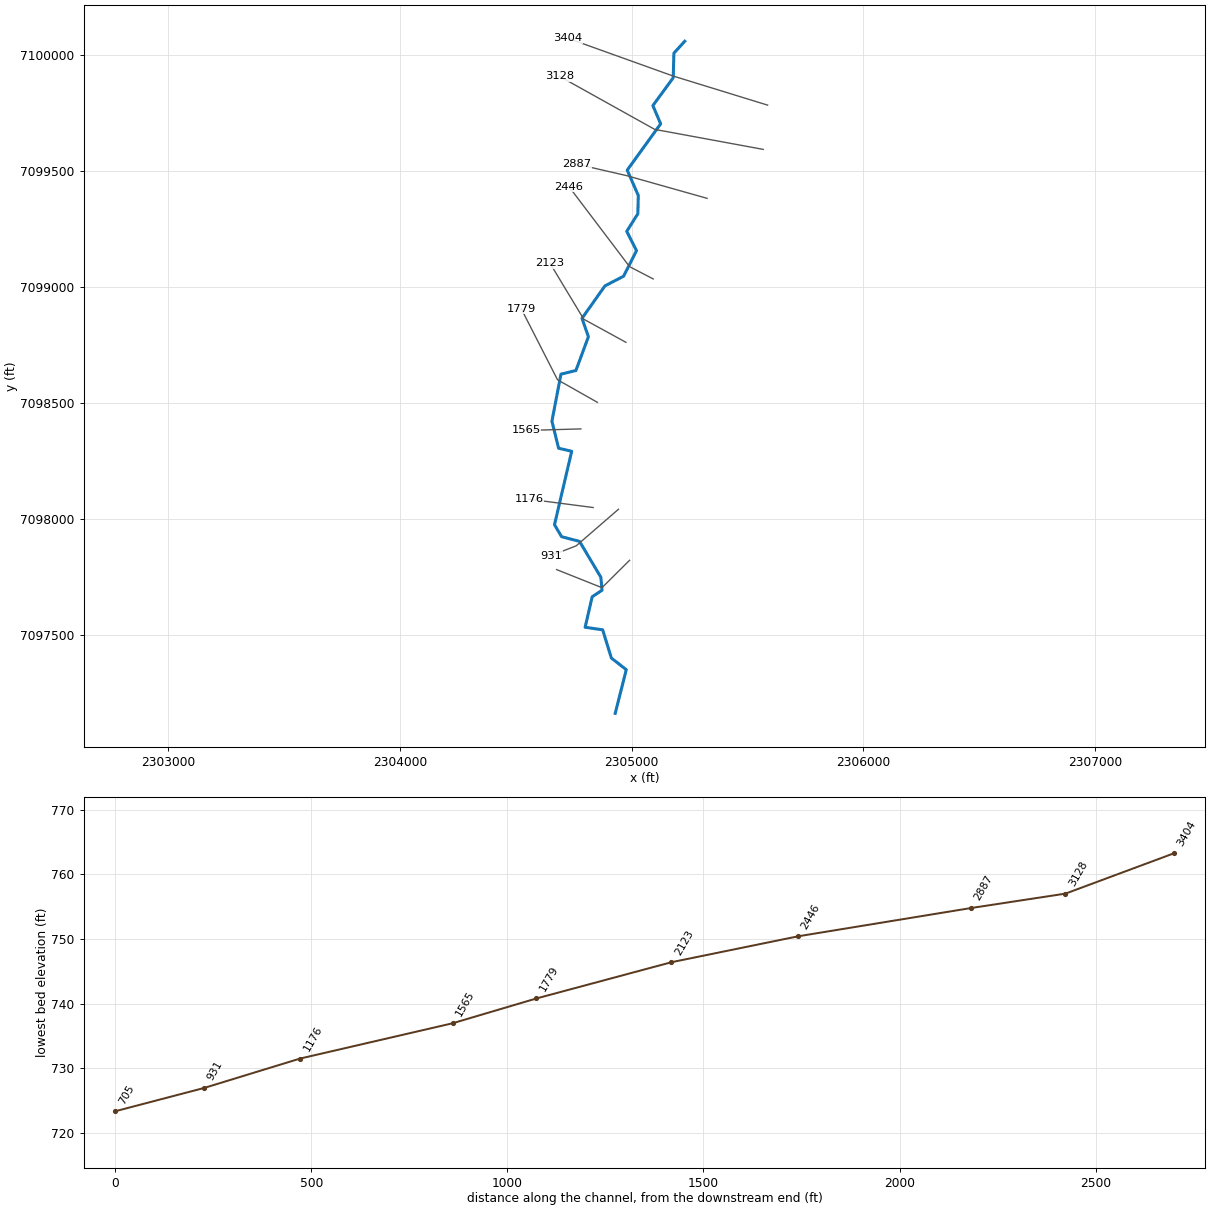
--- MDW T 047.prj (project) ---

Proj Title=MDW T 047 Base Level Engineering
Current Plan=p01
Default Exp/Contr=0.3,0.1
English Units
Geom File=g01
Flow File=f01
Plan File=p01
BEGIN DESCRIPTION:
MDW T 047
END DESCRIPTION:

--- MDW T 047.p01 (plan) ---

Plan Title=Multiple Run
Short Identifier=Multiple
Geom File=g01
Flow File=f01
Subcritical Flow
K Sum by GR= 0
Std Step Tol= 0.01
Critical Tol= 0.01
Num of Std Step Trials= 20
Max Error Tol= 0.3
Flow Tol Ratio= 0.001
Split Flow NTrial= 30
Split Flow Tol= 0.02
Split Flow Ratio= 0.02
Log Output Level= 0
Friction Slope Method= 1
Unsteady Friction Slope Method= 2
Unsteady Bridges Friction Slope Method= 1
Parabolic Critical Depth
Global Vel Dist=  1 , 1 , 1
Global Log Level= 0
CheckData=True
Encroach Param= -1, 0, 0, 0
BEGIN DESCRIPTION:
Multiple Run
END DESCRIPTION:

--- MDW T 047.f01 (steady flow) ---

Flow Title=Multiple
Number of Profiles=7
Profile Names=10-year,25-year,50-year,1pct_min,100-year,1pct_plu,500-year
River Rch & RM= MDW T 047,Reach-1,3404
     197     252     295     172     343     685     465
Boundary for River Rch & Prof#=MDW T 047,Reach-1,1
Up Type=0
Dn Type=3
Dn Slope=0.005
Boundary for River Rch & Prof#=MDW T 047,Reach-1,2
Up Type=0
Dn Type=3
Dn Slope=0.005
Boundary for River Rch & Prof#=MDW T 047,Reach-1,3
Up Type=0
Dn Type=3
Dn Slope=0.005
Boundary for River Rch & Prof#=MDW T 047,Reach-1,4
Up Type=0
Dn Type=3
Dn Slope=0.005
Boundary for River Rch & Prof#=MDW T 047,Reach-1,5
Up Type=0
Dn Type=3
Dn Slope=0.005
Boundary for River Rch & Prof#=MDW T 047,Reach-1,6
Up Type=0
Dn Type=3
Dn Slope=0.005
Boundary for River Rch & Prof#=MDW T 047,Reach-1,7
Up Type=0
Dn Type=3
Dn Slope=0.005

--- MDW T 047.g01 (geometry) ---

Geom Title=Existing Conditions

River Reach=MDW T 047,Reach-1
Reach XY= 30
      2305229.00      7100060.00      2305182.30      7100008.63
      2305179.38      7099902.52      2305091.58      7099782.39
      2305125.18      7099703.74      2304980.80      7099503.89
      2305028.60      7099394.73      2305026.81      7099315.97
      2304978.79      7099239.79      2305020.93      7099156.69
      2304965.47      7099046.47      2304884.65      7099004.37
      2304785.78      7098864.51      2304813.41      7098784.95
      2304759.39      7098639.37      2304694.91      7098623.55
      2304656.06      7098420.77      2304684.60      7098304.20
      2304741.19      7098290.72      2304667.11      7097973.95
      2304697.69      7097922.32      2304775.00      7097902.08
      2304867.05      7097747.70      2304872.19      7097691.48
      2304829.69      7097662.90      2304799.20      7097531.63
      2304874.89      7097520.52      2304912.58      7097398.63
      2304976.84      7097348.44      2304929.00      7097160.00

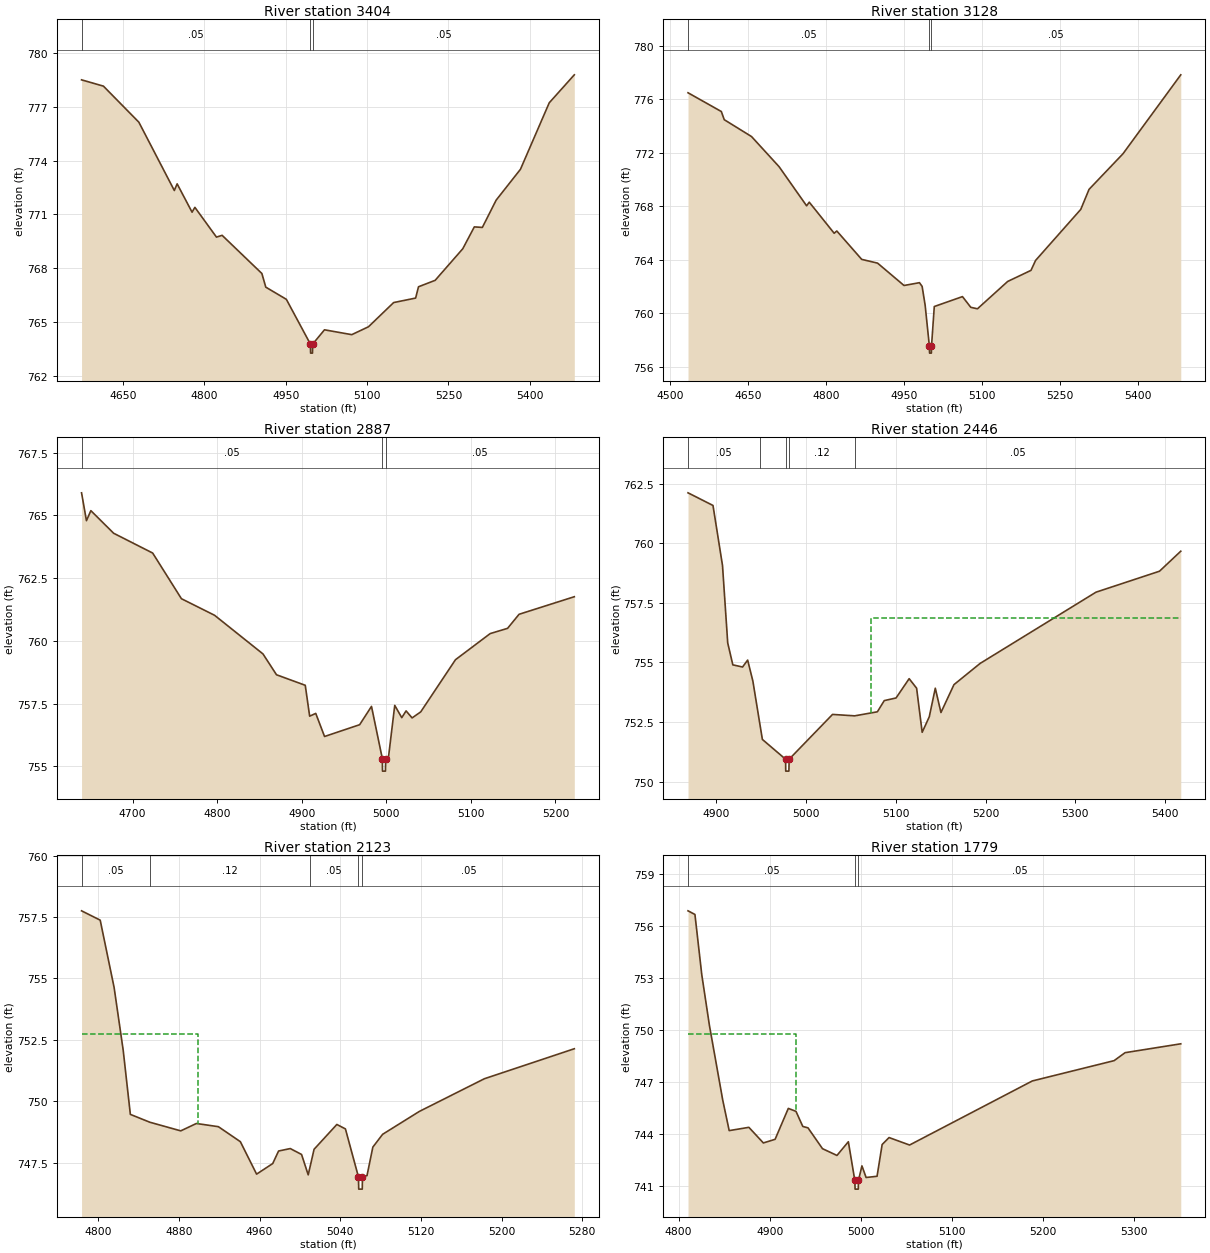
Type RM Length L Ch R = 1,3404,276,276,276
BEGIN DESCRIPTION:
MDW T 047 6.0
END DESCRIPTION:
XS GIS Cut Line= 3
      2305586.67      7099784.45      2305179.00      7099910.00
      2304725.55      7100072.64
#Sta/Elev= 30
  4573.8  778.50  4614.1  778.15  4679.4  776.14  4744.8  772.33  4750.0  772.70
  4777.5  771.12  4782.7  771.39  4822.5  769.73  4832.9  769.83  4906.2  767.70
  4913.4  766.94  4951.3  766.26  4995.7  763.76  4996.0  763.26  4999.5  763.26
  4999.7  763.76  5021.6  764.56  5071.9  764.29  5102.7  764.73  5149.1  766.08
  5189.6  766.33  5194.9  766.96  5225.6  767.32  5276.5  769.08  5297.8  770.30
  5312.6  770.27  5338.0  771.79  5382.8  773.51  5435.9  777.22  5482.1  778.78
#Mann=3,-1,0
  4573.8    0.05       0  4995.7    0.04       0  4999.7    0.05       0
Bank Sta=4995.7,4999.7
Exp/Cntr=0.3,0.1

Type RM Length L Ch R = 1,3128,241,241,241
BEGIN DESCRIPTION:
MDW T 047 5.0
END DESCRIPTION:
XS GIS Cut Line= 3
      2305567.58      7099593.47      2305099.41      7099679.83
      2304687.34      7099909.46
#Sta/Elev= 30
  4534.0  776.48  4598.1  775.08  4603.7  774.47  4656.2  773.21  4709.2  770.96
  4762.1  768.04  4767.2  768.31  4815.1  765.99  4820.2  766.16  4868.1  764.04
  4898.6  763.76  4949.5  762.09  4979.2  762.30  4984.3  762.02  4990.1  760.62
  4998.3  757.54  4998.6  757.04  5002.1  757.04  5002.3  757.54  5007.7  760.52
  5061.9  761.26  5077.9  760.46  5090.7  760.35  5148.8  762.39  5193.7  763.22
  5202.5  763.96  5289.4  767.77  5305.4  769.27  5370.5  771.92  5481.8  777.82
#Mann=3,-1,0
  4534.0    0.05       0  4998.3    0.04       0  5002.3    0.05       0
Bank Sta=4998.3,5002.3
Exp/Cntr=0.3,0.1

Type RM Length L Ch R = 1,2887,441,441,441
BEGIN DESCRIPTION:
MDW T 047 4.0
END DESCRIPTION:
XS GIS Cut Line= 3
      2305325.45      7099382.27      2304978.71      7099480.18
      2304762.07      7099530.01
#Sta/Elev= 30
  4639.7  765.90  4645.5  764.79  4650.7  765.19  4677.6  764.29  4723.8  763.50
  4757.8  761.68  4797.0  761.02  4854.2  759.48  4870.2  758.65  4904.2  758.23
  4909.4  757.00  4916.6  757.11  4927.0  756.19  4968.5  756.66  4982.5  757.39
  4995.3  755.31  4995.5  754.81  4999.0  754.81  4999.3  755.31  5002.4  755.31
  5010.0  757.43  5018.3  756.94  5023.4  757.21  5030.5  756.93  5040.7  757.17
  5081.8  759.25  5122.8  760.29  5143.4  760.50  5157.0  761.06  5222.3  761.76
#Mann=3,-1,0
  4639.7    0.05       0  4995.3    0.04       0  4999.3    0.05       0
Bank Sta=4995.3,4999.3
Exp/Cntr=0.3,0.1

Type RM Length L Ch R = 1,2446,323,323,323
BEGIN DESCRIPTION:
MDW T 047 3.0
END DESCRIPTION:
XS GIS Cut Line= 3
      2305093.04      7099034.49      2304991.09      7099087.45
      2304729.16      7099433.14
#Sta/Elev= 30
  4868.7  762.12  4896.5  761.59  4907.1  759.07  4912.9  755.82  4918.6  754.90
  4929.4  754.81  4935.1  755.10  4940.9  754.22  4948.8  752.39  4951.5  751.77
  4977.3  750.94  4977.5  750.44  4981.0  750.44  4981.3  750.94  5029.6  752.82
  5054.3  752.76  5079.5  752.93  5087.2  753.40  5100.3  753.51  5114.9  754.32
  5123.2  753.92  5129.4  752.07  5137.3  752.72  5144.0  753.92  5150.3  752.90
  5164.8  754.07  5193.9  754.96  5322.9  757.95  5393.6  758.83  5417.3  759.67
#Mann=5,-1,0
  4868.7    0.05       0  4948.8    0.12       0  4977.3    0.07       0
  4981.3    0.12       0  5054.3    0.05       0
#XS Ineff=2,0
       0                 5072.70    0.00  756.85
Permanent Ineff=
       F       F
Bank Sta=4977.3,4981.3
Exp/Cntr=0.3,0.1

Type RM Length L Ch R = 1,2123,344,344,344
BEGIN DESCRIPTION:
MDW T 047 2.0
END DESCRIPTION:
XS GIS Cut Line= 3
      2304975.25      7098761.06      2304793.40      7098860.71
      2304648.11      7099101.63
#Sta/Elev= 30
  4783.4  757.75  4801.9  757.37  4815.7  754.63  4824.7  752.08  4831.8  749.47
  4851.2  749.15  4881.8  748.80  4897.3  749.10  4919.1  748.97  4940.9  748.36
  4957.0  747.04  4973.0  747.47  4978.8  747.98  4990.4  748.08  5001.6  747.84
  5008.2  747.01  5010.1  747.35  5014.0  748.05  5036.6  749.06  5045.1  748.88
  5058.0  746.93  5058.3  746.43  5061.8  746.43  5062.0  746.93  5066.5  746.98
  5072.3  748.14  5082.0  748.66  5118.4  749.59  5182.9  750.92  5272.1  752.14
#Mann=5,-1,0
  4783.4    0.05       0  4851.2    0.12       0  5010.1    0.05       0
  5058.0    0.07       0  5062.0    0.05       0
#XS Ineff=2,0
    0.00 4899.20  752.73               0
Permanent Ineff=
       F       F
Bank Sta=5058,5062
Exp/Cntr=0.3,0.1

Type RM Length L Ch R = 1,1779,214,214,214
BEGIN DESCRIPTION:
MDW T 047 1.0
END DESCRIPTION:
XS GIS Cut Line= 3
      2304852.14      7098502.08      2304680.06      7098599.56
      2304524.04      7098905.17
#Sta/Elev= 30
  4810.4  756.86  4818.0  756.65  4825.5  753.18  4833.9  750.26  4848.5  745.96
  4855.6  744.20  4877.2  744.39  4893.1  743.49  4906.0  743.70  4920.5  745.48
  4928.9  745.31  4936.4  744.44  4942.1  744.36  4958.0  743.16  4973.9  742.77
  4986.4  743.56  4993.5  741.33  4993.8  740.83  4997.3  740.83  4997.5  741.33
  5001.3  742.17  5005.9  741.50  5017.9  741.57  5023.5  743.40  5031.1  743.80
  5053.6  743.37  5188.3  747.06  5278.1  748.23  5290.2  748.69  5351.3  749.20
#Mann=3,-1,0
  4810.4    0.05       0  4993.5   0.033       0  4997.5    0.05       0
#XS Ineff=2,0
    0.00 4929.30  749.76               0
Permanent Ineff=
       F       F
Bank Sta=4993.5,4997.5
Exp/Cntr=0.3,0.1

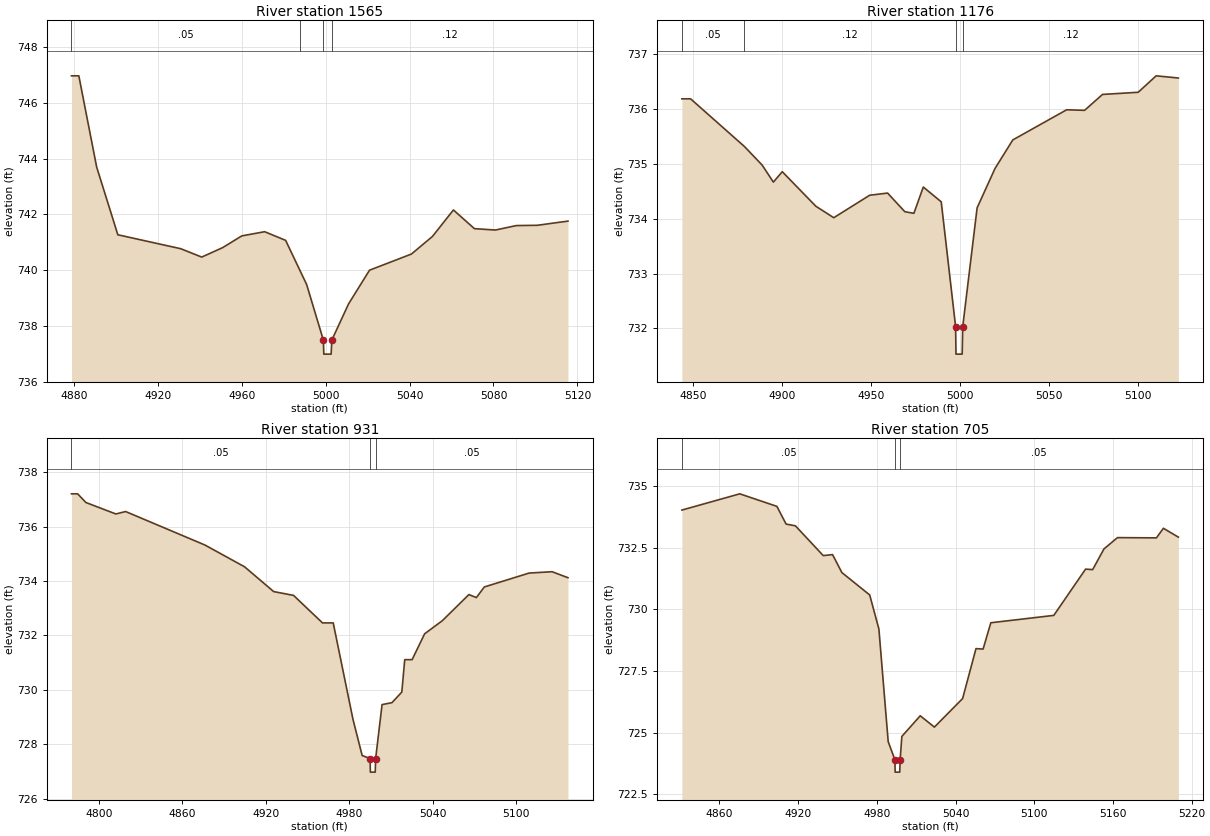
Type RM Length L Ch R = 1,1565,389,389,389
BEGIN DESCRIPTION:
Mapping XS faae3d8a
END DESCRIPTION:
XS GIS Cut Line= 2
      2304781.04      7098387.45      2304544.44      7098380.65
#Sta/Elev= 26
  4878.8  746.97  4882.3  746.97  4890.8  743.70  4900.9  741.27  4930.9  740.77
  4940.9  740.47  4950.9  740.81  4960.0  741.23  4970.9  741.38  4980.9  741.07
  4987.6  740.01  4990.9  739.49  4998.9  737.49  4999.1  736.99  5002.6  736.99
  5002.9  737.49  5010.9  738.79  5020.9  740.00  5040.9  740.58  5050.9  741.21
  5060.9  742.16  5070.9  741.49  5080.9  741.44  5090.9  741.60  5100.9  741.61
  5115.5  741.76
#Mann=4,-1,0
  4878.8    0.05       0  4987.6    0.12       0  4998.9    0.07       0
  5002.9    0.12       0
Bank Sta=4998.9,5002.9
Exp/Cntr=0.3,0.1

Type RM Length L Ch R = 1,1176,245,245,245
BEGIN DESCRIPTION:
Mapping XS 3f60db72
END DESCRIPTION:
XS GIS Cut Line= 2
      2304833.79      7098048.19      2304556.63      7098084.25
#Sta/Elev= 27
  4843.5  736.19  4848.4  736.19  4878.7  735.32  4888.7  734.98  4895.0  734.67
  4900.0  734.86  4918.9  734.23  4929.0  734.02  4949.2  734.43  4959.3  734.47
  4969.0  734.13  4974.1  734.10  4979.4  734.58  4989.5  734.31  4997.6  732.03
  4997.8  731.53  5001.3  731.53  5001.6  732.03  5009.7  734.20  5019.8  734.92
  5029.8  735.44  5060.1  735.99  5070.2  735.98  5080.3  736.27  5100.4  736.31
  5110.5  736.61  5123.0  736.57
#Mann=4,-1,0
  4843.5    0.05       0  4878.7    0.12       0  4997.6    0.07       0
  5001.6    0.12       0
Bank Sta=4997.6,5001.6
Exp/Cntr=0.3,0.1

Type RM Length L Ch R = 1,931,226,226,226
BEGIN DESCRIPTION:
Mapping XS 52f80f63
END DESCRIPTION:
XS GIS Cut Line= 3
      2304943.14      7098040.71      2304760.84      7097882.94
      2304652.98      7097841.05
#Sta/Elev= 30
  4780.4  737.20  4784.8  737.20  4790.8  736.88  4812.3  736.46  4819.3  736.55
  4876.3  735.32  4904.8  734.52  4925.7  733.61  4940.0  733.47  4960.8  732.46
  4968.5  732.46  4982.7  728.92  4989.3  727.59  4995.0  727.48  4995.2  726.98
  4998.7  726.98  4999.0  727.48  5003.6  729.46  5010.7  729.53  5017.8  729.92
  5019.9  731.11  5025.2  731.11  5034.2  732.06  5046.9  732.54  5066.0  733.50
  5071.4  733.39  5077.1  733.78  5109.3  734.29  5125.8  734.34  5137.2  734.12
#Mann=3,-1,0
  4780.4    0.05       0  4995.0   0.033       0  4999.0    0.05       0
Bank Sta=4995,4999
Exp/Cntr=0.3,0.1

Type RM Length L Ch R = 1,705,0,0,0
BEGIN DESCRIPTION:
MDW T 047 0.5
END DESCRIPTION:
XS GIS Cut Line= 3
      2304990.92      7097820.41      2304871.98      7097702.30
      2304676.30      7097780.34
#Sta/Elev= 30
  4831.5  734.04  4875.6  734.70  4903.9  734.19  4910.9  733.47  4918.0  733.40
  4939.2  732.19  4946.3  732.23  4953.4  731.50  4974.6  730.59  4981.6  729.21
  4988.7  724.63  4993.8  723.89  4994.0  723.39  4997.5  723.39  4997.8  723.89
  4999.1  724.84  5013.1  725.68  5023.9  725.22  5045.4  726.38  5055.6  728.41
  5061.0  728.39  5066.9  729.46  5114.9  729.76  5139.1  731.64  5144.5  731.62
  5153.1  732.46  5163.4  732.92  5193.1  732.91  5198.4  733.30  5209.8  732.94
#Mann=3,-1,0
  4831.5    0.05       0  4993.8   0.033       0  4997.8    0.05       0
Bank Sta=4993.8,4997.8
Exp/Cntr=0.3,0.1

Chan Stop Cuts=-1