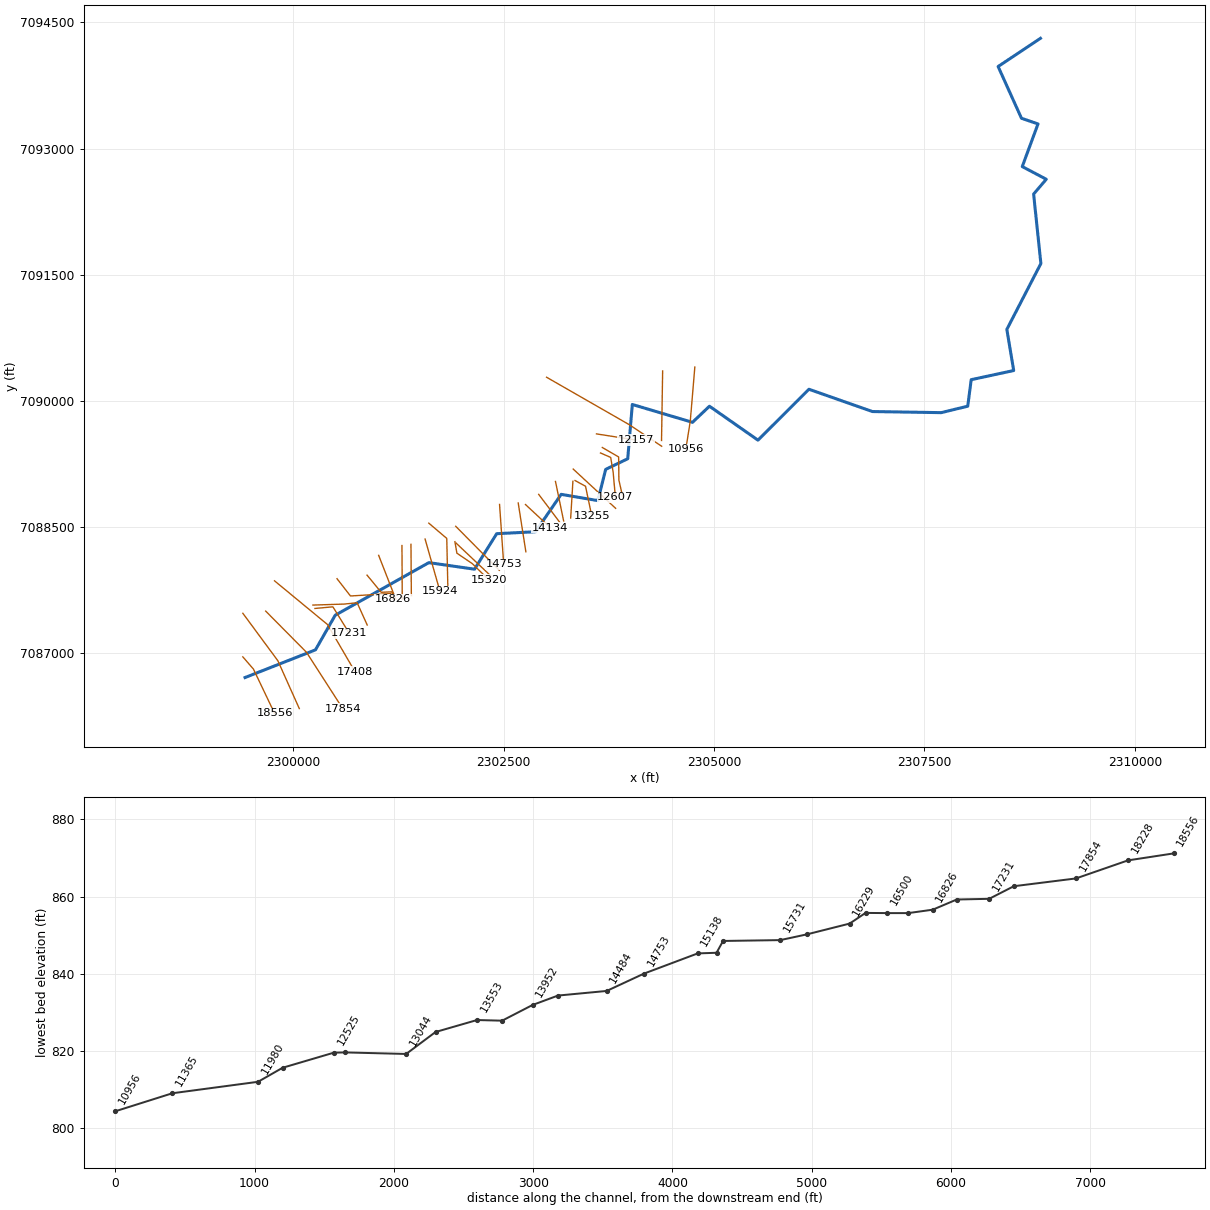
--- MDW T 049.prj (project) ---

Proj Title=MDW T 049 Base Level Engineering
Current Plan=p01
Default Exp/Contr=0.3,0.1
English Units
Geom File=g01
Flow File=f01
Plan File=p01
BEGIN DESCRIPTION:
MDW T 049
END DESCRIPTION:

--- MDW T 049.p01 (plan) ---

Plan Title=Multiple Run
Short Identifier=Multiple
Geom File=g01
Flow File=f01
Subcritical Flow
K Sum by GR= 0
Std Step Tol= 0.01
Critical Tol= 0.01
Num of Std Step Trials= 20
Max Error Tol= 0.3
Flow Tol Ratio= 0.001
Split Flow NTrial= 30
Split Flow Tol= 0.02
Split Flow Ratio= 0.02
Log Output Level= 0
Friction Slope Method= 1
Unsteady Friction Slope Method= 2
Unsteady Bridges Friction Slope Method= 1
Parabolic Critical Depth
Global Vel Dist=  1 , 1 , 1
Global Log Level= 0
CheckData=True
Encroach Param= -1, 0, 0, 0
BEGIN DESCRIPTION:
Multiple Run
END DESCRIPTION:

--- MDW T 049.f01 (steady flow) ---

Flow Title=Multiple
Number of Profiles=7
Profile Names=10-year,25-year,50-year,1pct_min,100-year,1pct_plu,500-year
River Rch & RM= MDW T 049,Reach-1,18556
     555     754     917     554    1105    2204    1607
River Rch & RM= MDW T 049,Reach-1,15320
     940    1320    1641    1012    2019    4028    3063
River Rch & RM= MDW T 049,Reach-1,6124
    1131    1605    2010    1247    2489    4966    3827
Boundary for River Rch & Prof#=MDW T 049,Reach-1,1
Up Type=0
Dn Type=3
Dn Slope=0.005
Boundary for River Rch & Prof#=MDW T 049,Reach-1,2
Up Type=0
Dn Type=3
Dn Slope=0.005
Boundary for River Rch & Prof#=MDW T 049,Reach-1,3
Up Type=0
Dn Type=3
Dn Slope=0.005
Boundary for River Rch & Prof#=MDW T 049,Reach-1,4
Up Type=0
Dn Type=3
Dn Slope=0.005
Boundary for River Rch & Prof#=MDW T 049,Reach-1,5
Up Type=0
Dn Type=3
Dn Slope=0.005
Boundary for River Rch & Prof#=MDW T 049,Reach-1,6
Up Type=0
Dn Type=3
Dn Slope=0.005
Boundary for River Rch & Prof#=MDW T 049,Reach-1,7
Up Type=0
Dn Type=3
Dn Slope=0.005

--- MDW T 049.g01 (geometry) ---

Geom Title=Existing Conditions

River Reach=MDW T 049,Reach-1
Reach XY= 30
      2299429.00      7086710.00      2300265.55      7087039.02
      2300500.39      7087450.97      2301612.78      7088076.15
      2302155.93      7087998.15      2302418.58      7088420.24
      2302879.94      7088443.48      2303184.78      7088888.15
      2303620.82      7088813.43      2303713.66      7089185.13
      2303975.55      7089311.25      2304030.22      7089956.57
      2304744.86      7089744.39      2304946.74      7089935.89
      2305523.29      7089532.40      2306128.60      7090137.67
      2306882.76      7089872.58      2307699.54      7089859.47
      2308015.36      7089936.16      2308056.53      7090251.43
      2308561.47      7090360.07      2308479.89      7090849.41
      2308884.35      7091632.66      2308798.00      7092458.18
      2308948.26      7092634.41      2308663.11      7092785.12
      2308850.23      7093292.55      2308653.94      7093359.34
      2308376.30      7093975.01      2308879.00      7094310.00

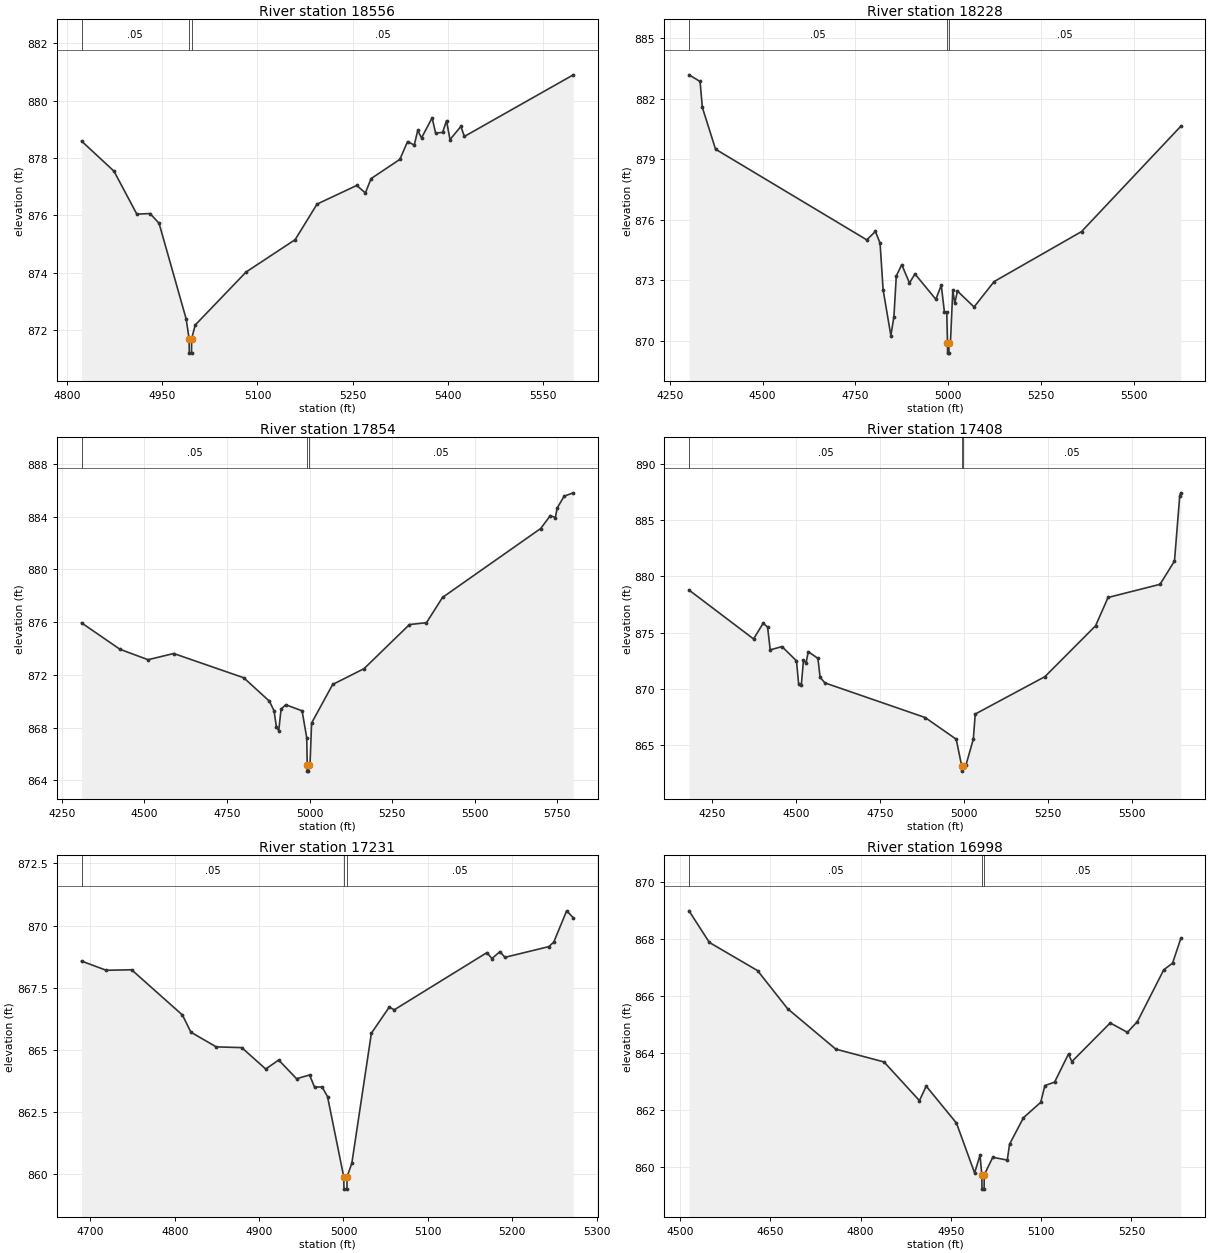
Type RM Length L Ch R = 1,18556,328,328,328
BEGIN DESCRIPTION:
MDW T 049 40.0
END DESCRIPTION:
XS GIS Cut Line= 3
      2299402.50      7086956.00      2299529.00      7086810.00
      2299779.85      7086283.82
#Sta/Elev= 30
  4822.3  878.59  4873.5  877.54  4909.6  876.04  4930.5  876.06  4944.7  875.72
  4987.5  872.38  4992.1  871.69  4992.4  871.19  4995.9  871.19  4996.1  871.69
  5001.7  872.17  5082.0  874.02  5159.5  875.15  5194.0  876.39  5256.6  877.04
  5270.3  876.78  5279.3  877.28  5324.7  877.95  5336.8  878.57  5347.4  878.45
  5352.9  878.96  5358.9  878.70  5375.6  879.40  5381.1  878.87  5392.1  878.89
  5398.3  879.30  5403.8  878.64  5421.0  879.10  5426.5  878.75  5598.4  880.90
#Mann=3,-1,0
  4822.3    0.05       0  4992.1   0.033       0  4996.1    0.05       0
Bank Sta=4992.1,4996.1
Exp/Cntr=0.3,0.1

Type RM Length L Ch R = 1,18228,374,374,374
BEGIN DESCRIPTION:
MDW T 049 39.0
END DESCRIPTION:
XS GIS Cut Line= 3
      2299402.80      7087474.04      2299818.81      7086909.55
      2300073.40      7086341.19
#Sta/Elev= 30
  4301.9  883.19  4331.6  882.86  4337.8  881.57  4373.3  879.50  4780.5  875.00
  4803.6  875.42  4816.2  874.84  4824.4  872.53  4845.3  870.25  4853.5  871.19
  4859.9  873.21  4874.6  873.77  4895.4  872.86  4910.1  873.31  4966.4  872.05
  4981.0  872.75  4989.5  871.41  4995.7  871.43  4997.7  869.88  4998.0  869.38
  5001.5  869.38  5001.7  869.88  5005.6  869.88  5012.0  872.51  5017.4  871.86
  5024.5  872.46  5069.3  871.67  5123.2  872.93  5358.5  875.41  5625.9  880.64
#Mann=3,-1,0
  4301.9    0.05       0  4997.7   0.033       0  5001.7    0.05       0
Bank Sta=4997.7,5001.7
Exp/Cntr=0.3,0.1

Type RM Length L Ch R = 1,17854,446,446,446
BEGIN DESCRIPTION:
MDW T 049 38.0
END DESCRIPTION:
XS GIS Cut Line= 3
      2299674.10      7087500.03      2300158.87      7087010.31
      2300592.04      7086336.87
#Sta/Elev= 30
  4309.3  875.95  4425.9  873.94  4510.8  873.15  4588.6  873.62  4800.7  871.78
  4878.5  870.00  4892.6  869.27  4899.7  868.04  4906.8  867.77  4913.9  869.40
  4928.0  869.73  4977.5  869.27  4991.6  867.22  4993.1  865.19  4993.3  864.69
  4996.8  864.69  4997.1  865.19  5001.5  865.19  5006.3  868.34  5070.1  871.27
  5165.2  872.47  5302.8  875.82  5354.3  875.96  5403.0  877.88  5700.3  883.11
  5729.4  884.09  5744.6  883.94  5750.5  884.68  5771.6  885.57  5799.1  885.82
#Mann=3,-1,0
  4309.3    0.05       0  4993.1   0.033       0  4997.1    0.05       0
Bank Sta=4993.1,4997.1
Exp/Cntr=0.3,0.1

Type RM Length L Ch R = 1,17408,177,177,177
BEGIN DESCRIPTION:
MDW T 049 37.0
END DESCRIPTION:
XS GIS Cut Line= 3
      2299778.99      7087860.00      2300408.69      7087340.14
      2300734.66      7086780.63
#Sta/Elev= 30
  4182.2  878.78  4374.4  874.43  4402.7  875.82  4416.0  875.50  4423.9  873.46
  4459.0  873.75  4502.1  872.48  4508.5  870.43  4516.4  870.29  4522.9  872.53
  4530.7  872.30  4537.2  873.30  4565.9  872.70  4572.4  871.02  4586.7  870.52
  4885.1  867.44  4977.6  865.51  4993.7  863.17  4994.0  862.67  4997.7  863.17
  5007.0  863.25  5028.5  865.51  5034.3  867.75  5241.9  871.08  5392.5  875.60
  5429.7  878.12  5584.4  879.29  5627.4  881.36  5643.1  887.17  5646.3  887.43
#Mann=3,-1,0
  4182.2    0.05       0  4993.7   0.033       0  4997.7    0.05       0
Bank Sta=4993.7,4997.7
Exp/Cntr=0.3,0.1

Type RM Length L Ch R = 1,17231,233,233,233
BEGIN DESCRIPTION:
Mapping XS 179dbb92
END DESCRIPTION:
XS GIS Cut Line= 3
      2300259.82      7087531.23      2300472.71      7087550.74
      2300667.20      7087236.78
#Sta/Elev= 30
  4689.4  868.57  4718.7  868.20  4748.8  868.22  4809.1  866.40  4819.1  865.71
  4849.2  865.12  4879.4  865.09  4907.8  864.23  4923.2  864.59  4944.4  863.84
  4959.8  863.99  4965.7  863.50  4974.6  863.51  4981.1  863.12  5000.3  859.90
  5000.6  859.40  5004.1  859.40  5004.3  859.90  5009.9  860.44  5033.1  865.67
  5054.3  866.72  5060.2  866.61  5170.1  868.91  5176.0  868.67  5185.5  868.95
  5191.4  868.72  5243.4  869.15  5249.3  869.33  5264.6  870.59  5272.5  870.31
#Mann=3,-1,0
  4689.4    0.05       0  5000.3   0.033       0  5004.3    0.05       0
Bank Sta=5000.3,5004.3
Exp/Cntr=0.3,0.1

Type RM Length L Ch R = 1,16998,172,172,172
BEGIN DESCRIPTION:
Mapping XS 3c0938c9
END DESCRIPTION:
XS GIS Cut Line= 4
      2300235.29      7087571.58      2300605.30      7087583.36
      2300760.91      7087598.90      2300880.53      7087334.25
#Sta/Elev= 30
  4515.0  869.00  4548.7  867.89  4628.8  866.90  4678.8  865.56  4758.8  864.14
  4838.9  863.69  4897.8  862.33  4909.0  862.84  4959.3  861.54  4989.4  859.79
  4998.4  860.41  5001.4  859.72  5001.7  859.22  5005.2  859.22  5005.4  859.72
  5019.6  860.34  5043.7  860.24  5047.5  860.80  5070.6  861.73  5099.2  862.27
  5106.2  862.86  5122.3  862.98  5145.4  863.97  5150.9  863.70  5214.7  865.06
  5243.3  864.73  5259.9  865.11  5303.7  866.93  5318.2  867.16  5332.0  868.03
#Mann=3,-1,0
  4515.0    0.05       0  5001.4   0.033       0  5005.4    0.05       0
Bank Sta=5001.4,5005.4
Exp/Cntr=0.3,0.1

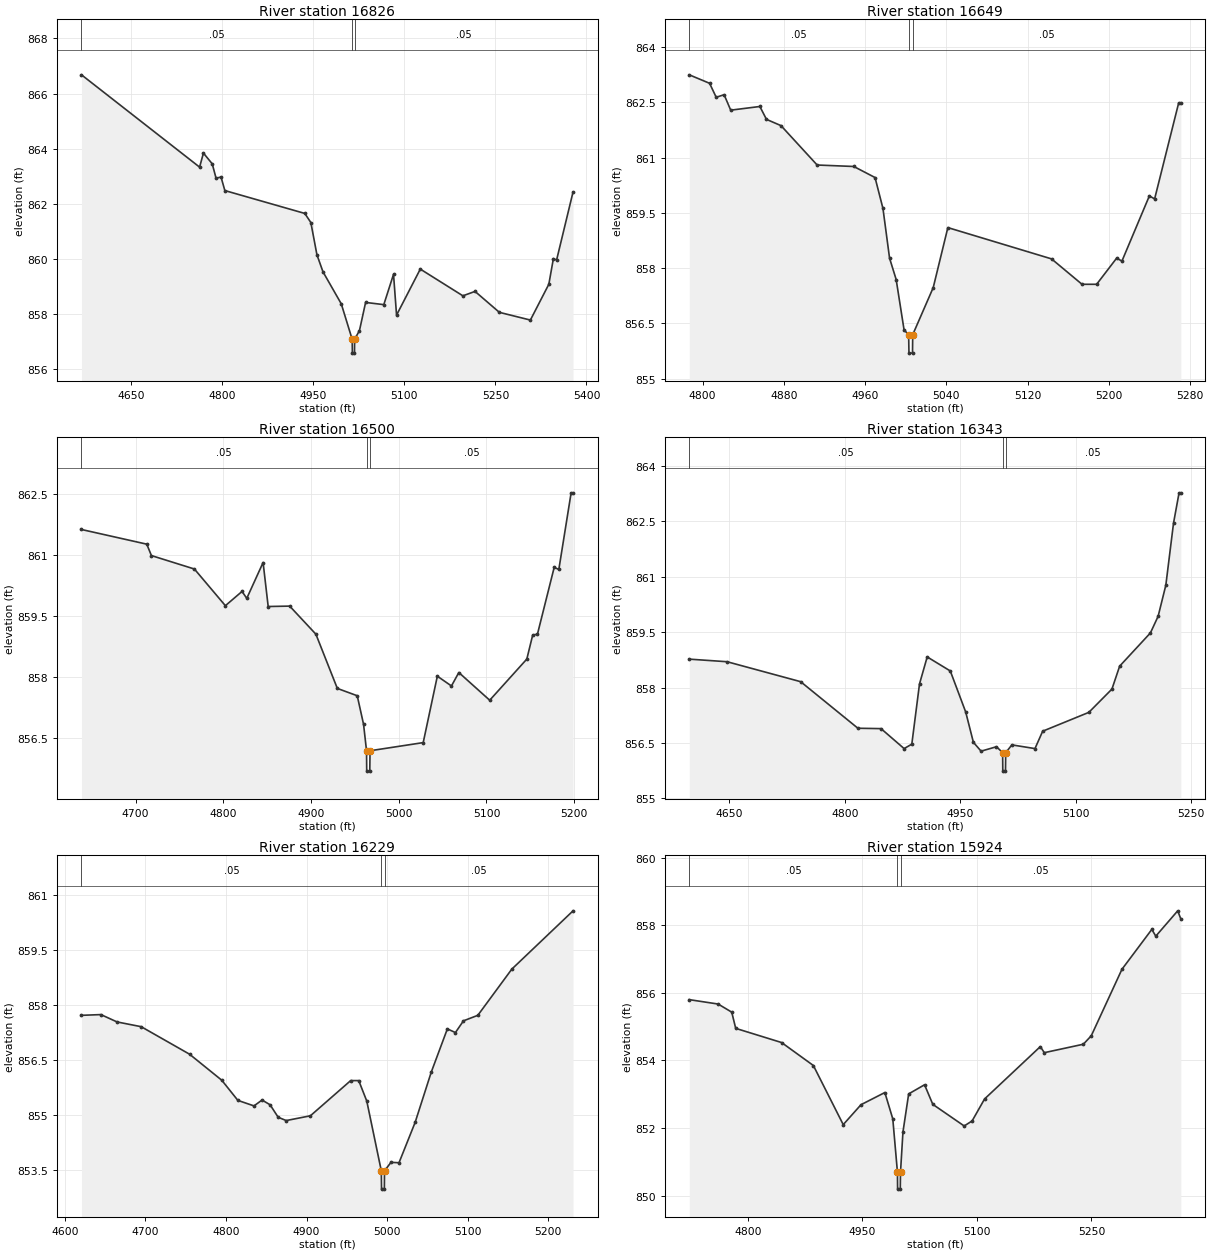
Type RM Length L Ch R = 1,16826,177,177,177
BEGIN DESCRIPTION:
Mapping XS 2d16469f
END DESCRIPTION:
XS GIS Cut Line= 4
      2300521.79      7087885.00      2300681.35      7087679.67
      2301160.08      7087708.50      2301184.53      7087642.63
#Sta/Elev= 30
  4568.0  866.68  4762.6  863.33  4768.9  863.84  4783.4  863.45  4789.7  862.93
  4797.9  862.97  4804.2  862.48  4935.9  861.65  4945.9  861.32  4955.9  860.15
  4965.9  859.53  4996.0  858.37  5014.0  857.08  5014.3  856.58  5017.8  856.58
  5018.0  857.08  5026.0  857.40  5036.1  858.42  5066.1  858.34  5082.1  859.44
  5087.1  857.96  5126.2  859.63  5196.4  858.66  5216.4  858.82  5256.5  858.06
  5307.6  857.78  5338.0  859.08  5345.5  860.01  5350.8  859.96  5377.9  862.43
#Mann=3,-1,0
  4568.0    0.05       0  5014.0   0.033       0  5018.0    0.05       0
Bank Sta=5014,5018
Exp/Cntr=0.3,0.1

Type RM Length L Ch R = 1,16649,149,149,149
BEGIN DESCRIPTION:
Mapping XS 24aee1d6
END DESCRIPTION:
XS GIS Cut Line= 4
      2300878.64      7087927.23      2301046.53      7087723.32
      2301173.98      7087728.97      2301202.03      7087641.04
#Sta/Elev= 30
  4786.8  863.25  4806.8  863.02  4813.3  862.64  4821.1  862.71  4827.6  862.29
  4856.3  862.39  4862.8  862.04  4877.1  861.87  4912.7  860.80  4948.8  860.76
  4969.7  860.46  4977.5  859.62  4984.0  858.27  4990.5  857.69  4998.3  856.32
  5002.8  856.19  5003.1  855.69  5006.6  855.69  5006.8  856.19  5027.0  857.47
  5041.4  859.10  5143.5  858.25  5173.5  857.56  5187.9  857.56  5207.6  858.27
  5212.8  858.19  5239.8  859.96  5245.0  859.88  5268.7  862.49  5270.8  862.49
#Mann=3,-1,0
  4786.8    0.05       0  5002.8   0.033       0  5006.8    0.05       0
Bank Sta=5002.8,5006.8
Exp/Cntr=0.3,0.1

Type RM Length L Ch R = 1,16500,157,157,157
BEGIN DESCRIPTION:
Mapping XS c56ecdcc
END DESCRIPTION:
XS GIS Cut Line= 2
      2301016.36      7088162.79      2301220.27      7087640.91
#Sta/Elev= 30
  4638.4  861.62  4712.8  861.26  4718.1  860.98  4767.1  860.65  4802.4  859.75
  4821.4  860.10  4826.8  859.93  4845.4  860.81  4851.2  859.73  4875.7  859.74
  4905.6  859.05  4930.0  857.72  4952.7  857.54  4959.9  856.84  4963.3  856.19
  4963.5  855.69  4967.0  855.69  4967.3  856.19  5027.9  856.39  5044.0  858.02
  5060.1  857.78  5068.5  858.11  5103.7  857.43  5146.0  858.44  5152.7  859.03
  5158.1  859.05  5177.2  860.69  5182.5  860.64  5196.5  862.52  5198.7  862.52
#Mann=3,-1,0
  4638.4    0.05       0  4963.3   0.033       0  4967.3    0.05       0
Bank Sta=4963.3,4967.3
Exp/Cntr=0.3,0.1

Type RM Length L Ch R = 1,16343,114,114,114
BEGIN DESCRIPTION:
Mapping XS 25519c4c
END DESCRIPTION:
XS GIS Cut Line= 2
      2301293.20      7088279.05      2301296.72      7087640.46
#Sta/Elev= 30
  4597.8  858.77  4646.9  858.70  4742.5  858.16  4816.9  856.90  4846.9  856.89
  4876.9  856.35  4886.9  856.47  4896.9  858.10  4906.9  858.83  4936.9  858.45
  4956.9  857.34  4966.9  856.52  4976.9  856.28  4996.9  856.40  5004.9  856.24
  5005.1  855.74  5008.6  855.74  5008.9  856.24  5016.9  856.45  5046.9  856.35
  5056.9  856.82  5116.9  857.33  5146.9  857.96  5156.9  858.58  5196.9  859.48
  5206.9  859.93  5216.9  860.77  5226.9  862.45  5234.1  863.27  5236.4  863.27
#Mann=3,-1,0
  4597.8    0.05       0  5004.9   0.033       0  5008.9    0.05       0
Bank Sta=5004.9,5008.9
Exp/Cntr=0.3,0.1

Type RM Length L Ch R = 1,16229,305,305,305
BEGIN DESCRIPTION:
Mapping XS e7443886
END DESCRIPTION:
XS GIS Cut Line= 2
      2301400.24      7088294.12      2301404.88      7087684.04
#Sta/Elev= 30
  4620.6  857.71  4644.7  857.73  4664.7  857.53  4694.7  857.40  4754.7  856.65
  4794.7  855.94  4814.7  855.39  4834.7  855.24  4844.7  855.40  4854.7  855.27
  4864.7  854.93  4874.7  854.84  4904.7  854.97  4954.7  855.93  4964.7  855.93
  4974.7  855.37  4992.7  853.47  4993.0  852.97  4996.5  852.97  4996.7  853.47
  5004.7  853.70  5014.7  853.69  5034.7  854.79  5054.7  856.16  5074.7  857.34
  5084.7  857.24  5094.7  857.56  5112.5  857.71  5154.7  858.97  5230.7  860.56
#Mann=3,-1,0
  4620.6    0.05       0  4992.7   0.033       0  4996.7    0.05       0
Bank Sta=4992.7,4996.7
Exp/Cntr=0.3,0.1

Type RM Length L Ch R = 1,15924,193,193,193
BEGIN DESCRIPTION:
Mapping XS 3aaf9ba2
END DESCRIPTION:
XS GIS Cut Line= 2
      2301568.23      7088356.35      2301744.01      7087737.11
#Sta/Elev= 30
  4723.3  855.80  4761.1  855.67  4778.9  855.43  4784.1  854.95  4844.2  854.53
  4885.8  853.85  4924.9  852.10  4948.2  852.69  4979.4  853.05  4989.8  852.27
  4995.9  850.69  4996.1  850.19  4999.6  850.19  4999.9  850.69  5003.1  851.88
  5010.6  853.01  5031.4  853.28  5042.2  852.70  5083.3  852.06  5093.7  852.21
  5110.0  852.86  5183.0  854.41  5188.2  854.23  5239.3  854.48  5249.7  854.73
  5289.9  856.70  5329.0  857.88  5334.2  857.68  5362.9  858.43  5367.0  858.19
#Mann=3,-1,0
  4723.3    0.05       0  4995.9   0.033       0  4999.9    0.05       0
Bank Sta=4995.9,4999.9
Exp/Cntr=0.3,0.1

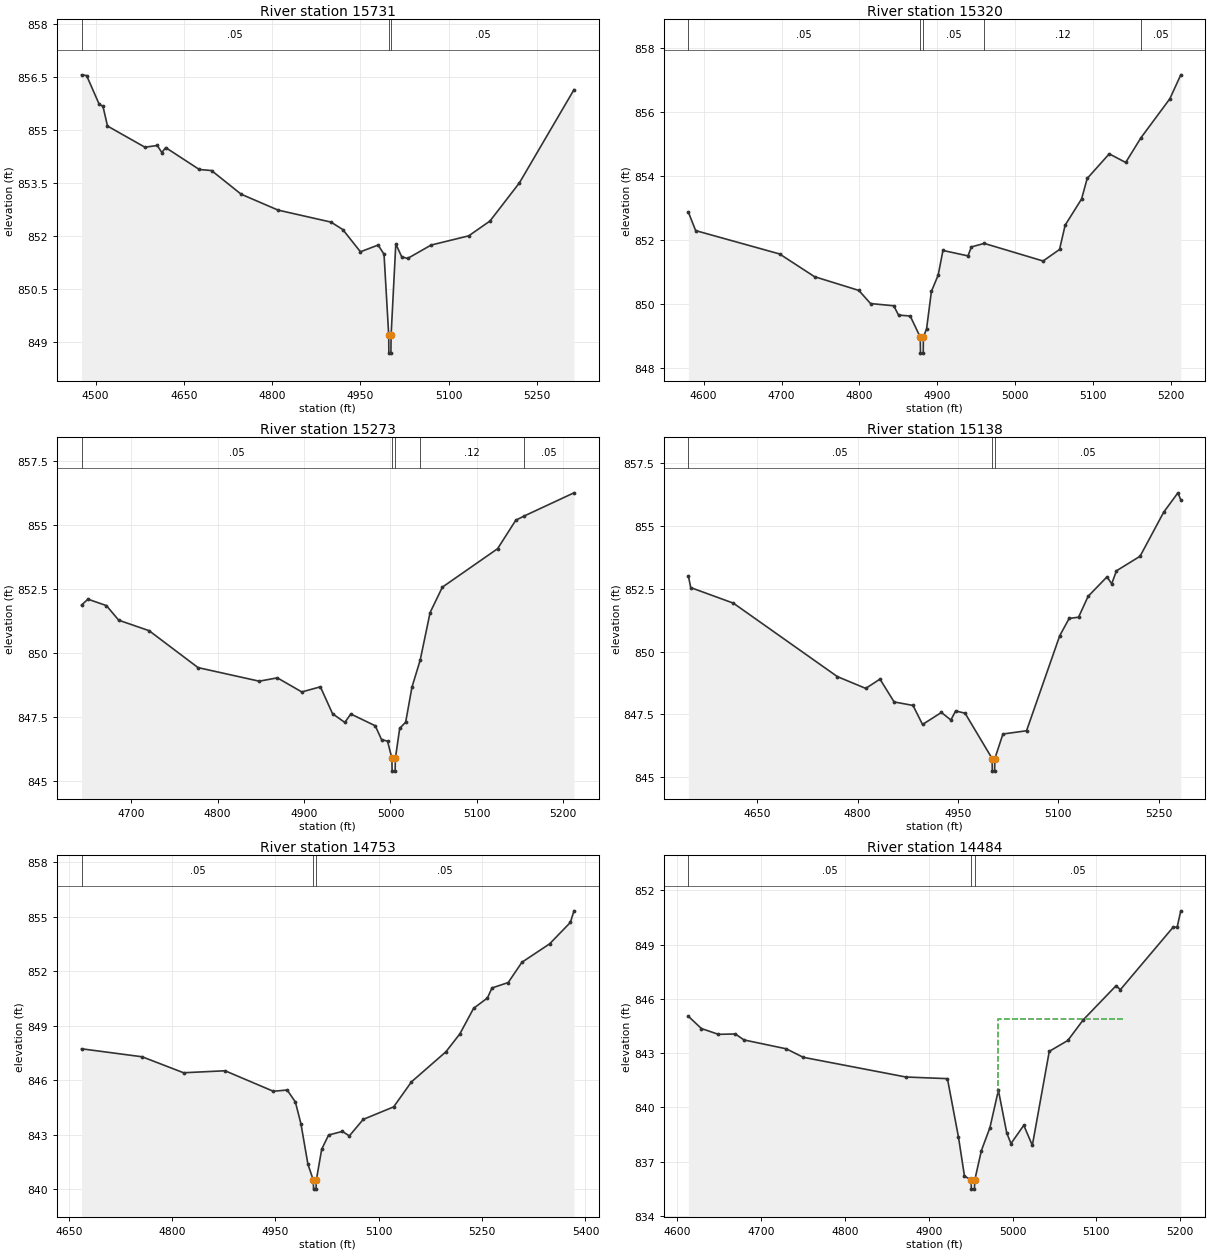
Type RM Length L Ch R = 1,15731,411,411,411
BEGIN DESCRIPTION:
Mapping XS e3a3f742
END DESCRIPTION:
XS GIS Cut Line= 3
      2301612.42      7088545.35      2301825.58      7088364.09
      2301838.03      7087807.24
#Sta/Elev= 30
  4476.0  856.56  4484.6  856.54  4505.9  855.73  4512.4  855.67  4520.1  855.11
  4583.8  854.51  4604.7  854.56  4612.4  854.36  4619.0  854.50  4676.1  853.88
  4696.9  853.85  4747.2  853.18  4809.9  852.73  4899.9  852.39  4919.9  852.18
  4949.9  851.55  4980.0  851.74  4990.0  851.48  4998.0  849.18  4998.2  848.68
  5001.7  848.68  5002.0  849.18  5010.0  851.77  5020.0  851.41  5030.0  851.36
  5070.0  851.74  5133.8  852.00  5170.0  852.42  5220.0  853.50  5312.8  856.14
#Mann=3,-1,0
  4476.0    0.05       0  4998.0   0.033       0  5002.0    0.05       0
Bank Sta=4998,5002
Exp/Cntr=0.3,0.1

Type RM Length L Ch R = 1,15320,47,47,47
BEGIN DESCRIPTION:
Mapping XS 41b6b503
END DESCRIPTION:
XS GIS Cut Line= 4
      2301922.63      7088325.44      2301945.81      7088188.46
      2302127.79      7088065.10      2302322.96      7087874.03
#Sta/Elev= 30
  4580.4  852.87  4589.8  852.29  4697.5  851.56  4742.3  850.85  4799.2  850.42
  4814.2  850.01  4844.0  849.94  4850.1  849.65  4865.1  849.62  4878.0  848.96
  4878.3  848.46  4881.8  848.46  4882.0  848.96  4886.1  849.22  4892.3  850.39
  4901.0  850.90  4907.1  851.67  4939.2  851.50  4943.6  851.78  4960.1  851.89
  5035.6  851.34  5056.7  851.70  5063.9  852.46  5085.0  853.28  5092.2  853.92
  5120.5  854.69  5141.6  854.42  5161.1  855.19  5198.2  856.41  5212.3  857.16
#Mann=5,-1,0
  4580.4    0.05       0  4878.0    0.07       0  4882.0    0.05       0
  4960.1    0.12       0  5161.1    0.05       0
Bank Sta=4878,4882
Exp/Cntr=0.3,0.1

Type RM Length L Ch R = 1,15273,135,135,135
BEGIN DESCRIPTION:
Mapping XS 61191769
END DESCRIPTION:
XS GIS Cut Line= 2
      2301936.69      7088308.22      2302350.58      7087916.46
#Sta/Elev= 30
  4642.5  851.87  4649.9  852.10  4671.3  851.85  4685.5  851.28  4720.7  850.87
  4777.3  849.43  4848.1  848.90  4869.1  849.03  4897.4  848.48  4918.9  848.68
  4933.0  847.63  4947.2  847.29  4954.1  847.62  4982.4  847.16  4989.7  846.62
  4996.6  846.56  5001.7  845.89  5001.9  845.39  5005.4  845.39  5005.7  845.89
  5010.7  847.06  5017.6  847.30  5024.9  848.67  5034.4  849.72  5045.9  851.58
  5060.1  852.57  5124.0  854.07  5145.0  855.18  5154.4  855.34  5212.4  856.25
#Mann=5,-1,0
  4642.5    0.05       0  5001.7   0.033       0  5005.7    0.05       0
  5034.4    0.12       0  5154.4    0.05       0
Bank Sta=5001.7,5005.7
Exp/Cntr=0.3,0.1

Type RM Length L Ch R = 1,15138,385,385,385
BEGIN DESCRIPTION:
Mapping XS 974b52f9
END DESCRIPTION:
XS GIS Cut Line= 3
      2301932.15      7088508.24      2302043.22      7088395.93
      2302449.84      7087984.80
#Sta/Elev= 30
  4547.0  853.02  4550.6  852.55  4614.3  851.93  4769.8  849.00  4812.2  848.53
  4833.5  848.90  4854.6  847.99  4882.9  847.85  4897.1  847.09  4925.3  847.57
  4939.5  847.27  4946.6  847.63  4960.7  847.54  5001.2  845.73  5001.4  845.23
  5004.9  845.23  5005.2  845.73  5017.3  846.71  5052.6  846.84  5102.2  850.63
  5116.3  851.32  5130.4  851.37  5144.6  852.20  5172.9  852.98  5179.9  852.70
  5187.0  853.22  5222.3  853.80  5257.7  855.56  5278.9  856.33  5283.2  856.05
#Mann=3,-1,0
  4547.0    0.05       0  5001.2   0.033       0  5005.2    0.05       0
Bank Sta=5001.2,5005.2
Exp/Cntr=0.3,0.1

Type RM Length L Ch R = 1,14753,269,269,269
BEGIN DESCRIPTION:
Mapping XS 466ffe3d
END DESCRIPTION:
XS GIS Cut Line= 3
      2302452.81      7088767.79      2302463.56      7088612.40
      2302502.12      7088054.69
#Sta/Elev= 30
  4668.5  847.73  4756.5  847.29  4816.6  846.41  4876.8  846.52  4946.9  845.39
  4967.0  845.46  4978.9  844.80  4987.0  843.59  4997.1  841.37  5004.9  840.50
  5005.3  840.00  5008.9  840.00  5009.3  840.50  5017.1  842.20  5027.1  842.98
  5047.2  843.18  5057.2  842.93  5077.3  843.84  5121.5  844.53  5147.4  845.91
  5197.5  847.57  5217.6  848.55  5237.6  849.96  5257.7  850.53  5264.2  851.08
  5287.8  851.38  5307.8  852.50  5347.9  853.51  5378.0  854.69  5383.3  855.33
#Mann=3,-1,0
  4668.5    0.05       0  5004.9   0.033       0  5009.3    0.05       0
Bank Sta=5004.9,5009.3
Exp/Cntr=0.3,0.1

Type RM Length L Ch R = 1,14484,350,350,350
BEGIN DESCRIPTION:
Mapping XS 0e89e2b0
END DESCRIPTION:
XS GIS Cut Line= 3
      2302674.48      7088785.43      2302697.33      7088639.50
      2302765.34      7088205.00
#Sta/Elev= 30
  4613.2  845.04  4628.8  844.36  4649.1  844.04  4669.3  844.06  4679.6  843.73
  4730.0  843.24  4750.3  842.77  4872.8  841.68  4922.3  841.59  4935.5  838.35
  4942.6  836.21  4950.5  835.98  4950.9  835.48  4954.5  835.48  4954.9  835.98
  4962.8  837.61  4973.0  838.88  4983.1  840.95  4993.1  838.58  4998.1  838.00
  5013.4  839.01  5023.6  837.90  5043.8  843.10  5065.9  843.70  5084.3  844.84
  5123.5  846.73  5128.6  846.51  5191.3  849.95  5196.4  849.98  5200.7  850.87
#Mann=3,-1,0
  4613.2    0.05       0  4950.5   0.033       0  4954.9    0.05       0
#XS Ineff=1,-1
 4982.20 5131.70  844.87
Permanent Ineff=
       F
Bank Sta=4950.5,4954.9
Exp/Cntr=0.3,0.1

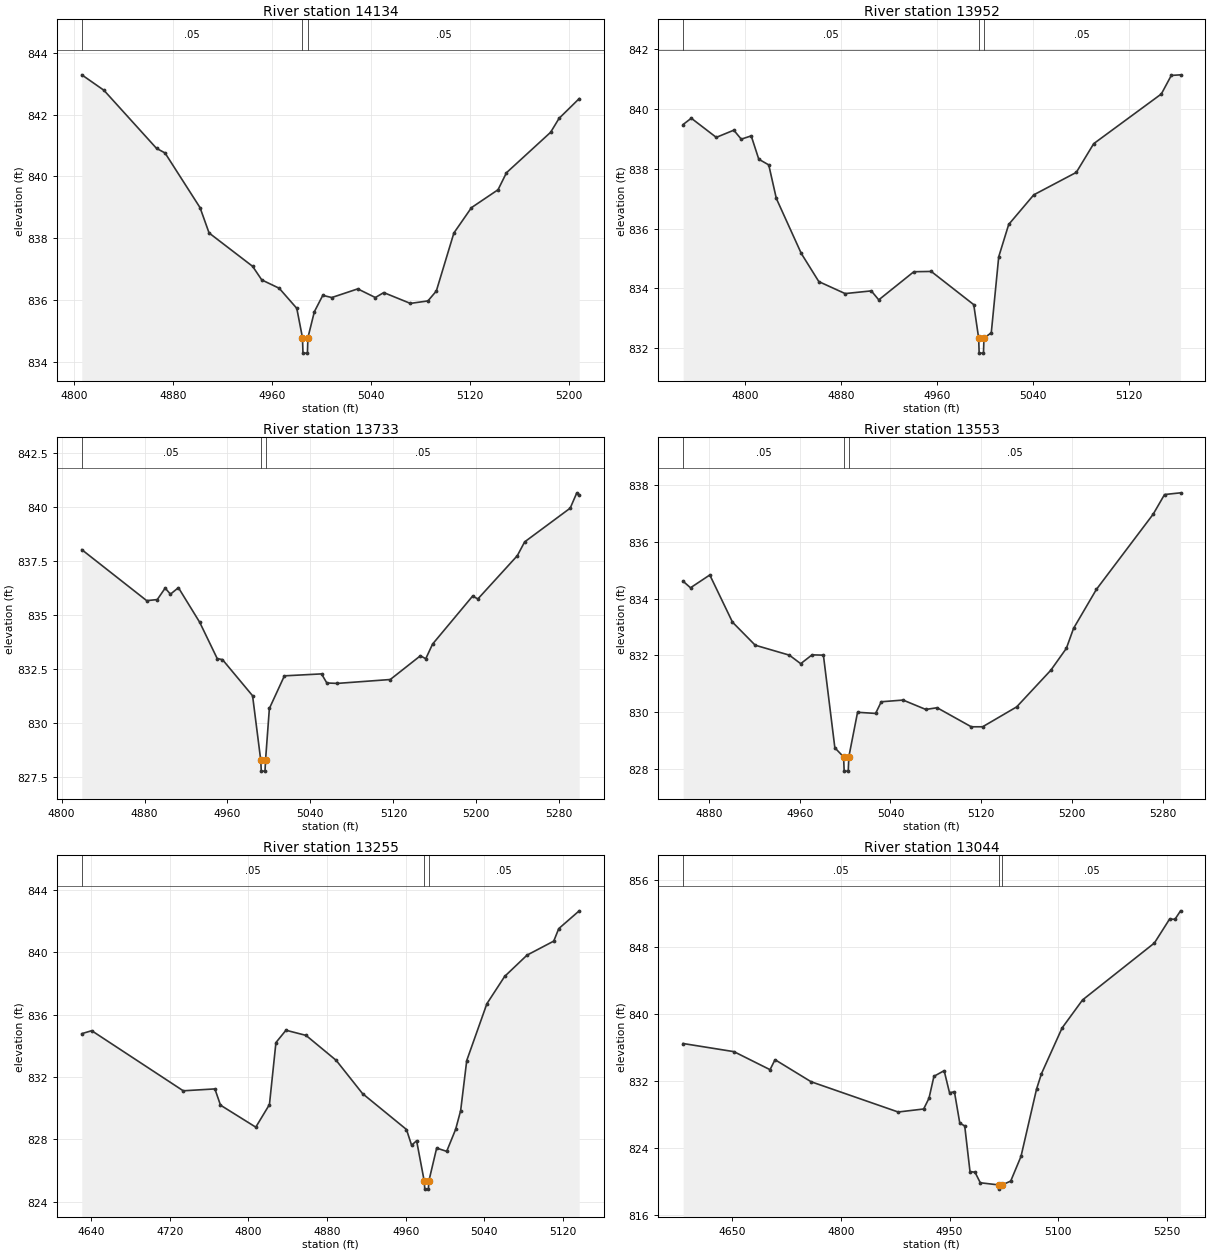
Type RM Length L Ch R = 1,14134,182,182,182
BEGIN DESCRIPTION:
Mapping XS 7745579c
END DESCRIPTION:
XS GIS Cut Line= 2
      2302760.65      7088767.01      2303054.95      7088493.02
#Sta/Elev= 30
  4806.1  843.29  4824.0  842.79  4866.5  840.91  4873.4  840.76  4901.7  838.99
  4909.0  838.17  4944.2  837.09  4951.6  836.65  4965.7  836.38  4979.9  835.73
  4984.5  834.78  4984.9  834.28  4988.5  834.28  4988.9  834.78  4994.1  835.62
  5000.9  836.15  5008.2  836.08  5029.2  836.36  5043.4  836.08  5050.2  836.24
  5071.7  835.89  5085.9  835.97  5092.7  836.29  5106.9  838.17  5121.1  838.99
  5142.6  839.57  5149.4  840.12  5185.1  841.43  5191.9  841.88  5208.2  842.52
#Mann=3,-1,0
  4806.1    0.05       0  4984.5   0.033       0  4988.9    0.05       0
Bank Sta=4984.5,4988.9
Exp/Cntr=0.3,0.1

Type RM Length L Ch R = 1,13952,219,219,219
BEGIN DESCRIPTION:
Mapping XS 316f4e21
END DESCRIPTION:
XS GIS Cut Line= 2
      2302917.88      7088887.68      2303167.23      7088556.94
#Sta/Elev= 30
  4748.7  839.48  4755.5  839.69  4776.3  839.05  4790.9  839.29  4797.1  838.99
  4805.4  839.10  4811.7  838.32  4820.0  838.13  4826.3  837.01  4847.1  835.17
  4861.7  834.23  4883.6  833.83  4905.4  833.92  4911.6  833.62  4940.8  834.56
  4955.3  834.57  4990.7  833.46  4994.8  832.34  4995.2  831.84  4998.8  831.84
  4999.2  832.34  5005.3  832.52  5011.5  835.06  5019.8  836.14  5040.7  837.13
  5076.1  837.88  5090.6  838.84  5146.9  840.50  5155.2  841.12  5162.9  841.14
#Mann=3,-1,0
  4748.7    0.05       0  4994.8   0.033       0  4999.2    0.05       0
Bank Sta=4994.8,4999.2
Exp/Cntr=0.3,0.1

Type RM Length L Ch R = 1,13733,180,180,180
BEGIN DESCRIPTION:
Mapping XS b730cb58
END DESCRIPTION:
XS GIS Cut Line= 2
      2303117.27      7089041.32      2303214.22      7088571.52
#Sta/Elev= 30
  4819.5  838.01  4882.1  835.65  4892.3  835.70  4899.9  836.23  4905.0  835.95
  4912.7  836.25  4933.2  834.65  4950.1  832.97  4955.2  832.92  4984.2  831.25
  4992.1  828.26  4992.6  827.76  4996.2  827.76  4996.7  828.26  5000.4  830.66
  5014.9  832.17  5050.7  832.26  5055.8  831.84  5065.9  831.82  5117.0  832.00
  5146.1  833.10  5151.2  832.96  5157.8  833.64  5196.4  835.86  5201.5  835.73
  5239.5  837.73  5246.6  838.37  5290.5  839.93  5296.9  840.64  5299.2  840.55
#Mann=3,-1,0
  4819.5    0.05       0  4992.1   0.033       0  4996.7    0.05       0
Bank Sta=4992.1,4996.7
Exp/Cntr=0.3,0.1

Type RM Length L Ch R = 1,13553,298,298,298
BEGIN DESCRIPTION:
Mapping XS e33e2b74
END DESCRIPTION:
XS GIS Cut Line= 2
      2303324.27      7089043.41      2303297.86      7088605.91
#Sta/Elev= 30
  4857.3  834.61  4863.8  834.38  4880.8  834.83  4900.8  833.17  4920.8  832.36
  4950.9  832.01  4960.9  831.71  4970.9  832.02  4980.9  832.01  4991.0  828.75
  4998.7  828.43  4999.2  827.93  5002.8  827.93  5003.3  828.43  5011.0  830.00
  5026.9  829.96  5031.9  830.37  5051.1  830.43  5071.1  830.10  5081.1  830.16
  5111.2  829.49  5121.2  829.49  5151.2  830.19  5181.3  831.48  5195.0  832.25
  5201.3  832.95  5221.4  834.32  5271.5  836.97  5281.5  837.66  5295.6  837.72
#Mann=3,-1,0
  4857.3    0.05       0  4998.7   0.033       0  5003.3    0.05       0
Bank Sta=4998.7,5003.3
Exp/Cntr=0.3,0.1

Type RM Length L Ch R = 1,13255,211,211,211
BEGIN DESCRIPTION:
Mapping XS 9e235e00
END DESCRIPTION:
XS GIS Cut Line= 3
      2303349.64      7089052.34      2303474.24      7088984.36
      2303548.99      7088628.05
#Sta/Elev= 30
  4630.5  834.78  4640.6  834.97  4733.7  831.12  4765.9  831.24  4771.6  830.20
  4807.5  828.79  4821.4  830.24  4828.0  834.21  4838.2  835.00  4858.6  834.67
  4889.3  833.07  4916.1  830.94  4960.8  828.64  4966.0  827.63  4971.1  827.92
  4978.9  825.32  4979.4  824.82  4983.1  824.82  4983.5  825.32  4991.5  827.45
  5001.7  827.24  5010.8  828.65  5015.9  829.85  5022.1  833.06  5042.6  836.70
  5060.7  838.45  5083.4  839.81  5110.6  840.71  5115.7  841.51  5136.5  842.65
#Mann=3,-1,0
  4630.5    0.05       0  4978.9   0.033       0  4983.5    0.05       0
Bank Sta=4978.9,4983.5
Exp/Cntr=0.3,0.1

Type RM Length L Ch R = 1,13044,437,437,437
BEGIN DESCRIPTION:
Mapping XS db2749b5
END DESCRIPTION:
XS GIS Cut Line= 2
      2303327.96      7089188.44      2303831.93      7088721.84
#Sta/Elev= 30
  4582.2  836.49  4652.4  835.52  4702.2  833.37  4709.1  834.56  4758.9  831.93
  4879.1  828.32  4914.3  828.68  4921.7  829.97  4928.5  832.58  4942.6  833.25
  4950.0  830.62  4956.8  830.73  4964.2  826.99  4971.0  826.66  4978.3  821.21
  4985.2  821.14  4992.5  819.88  5018.0  819.62  5018.5  819.12  5022.6  819.62
  5034.5  820.08  5048.7  823.02  5070.2  831.06  5077.0  832.90  5105.4  838.34
  5133.7  841.69  5232.9  848.48  5253.9  851.34  5261.3  851.31  5269.0  852.32
#Mann=3,-1,0
  4582.2    0.05       0  5018.0   0.033       0  5022.6    0.05       0
Bank Sta=5018,5022.6
Exp/Cntr=0.3,0.1

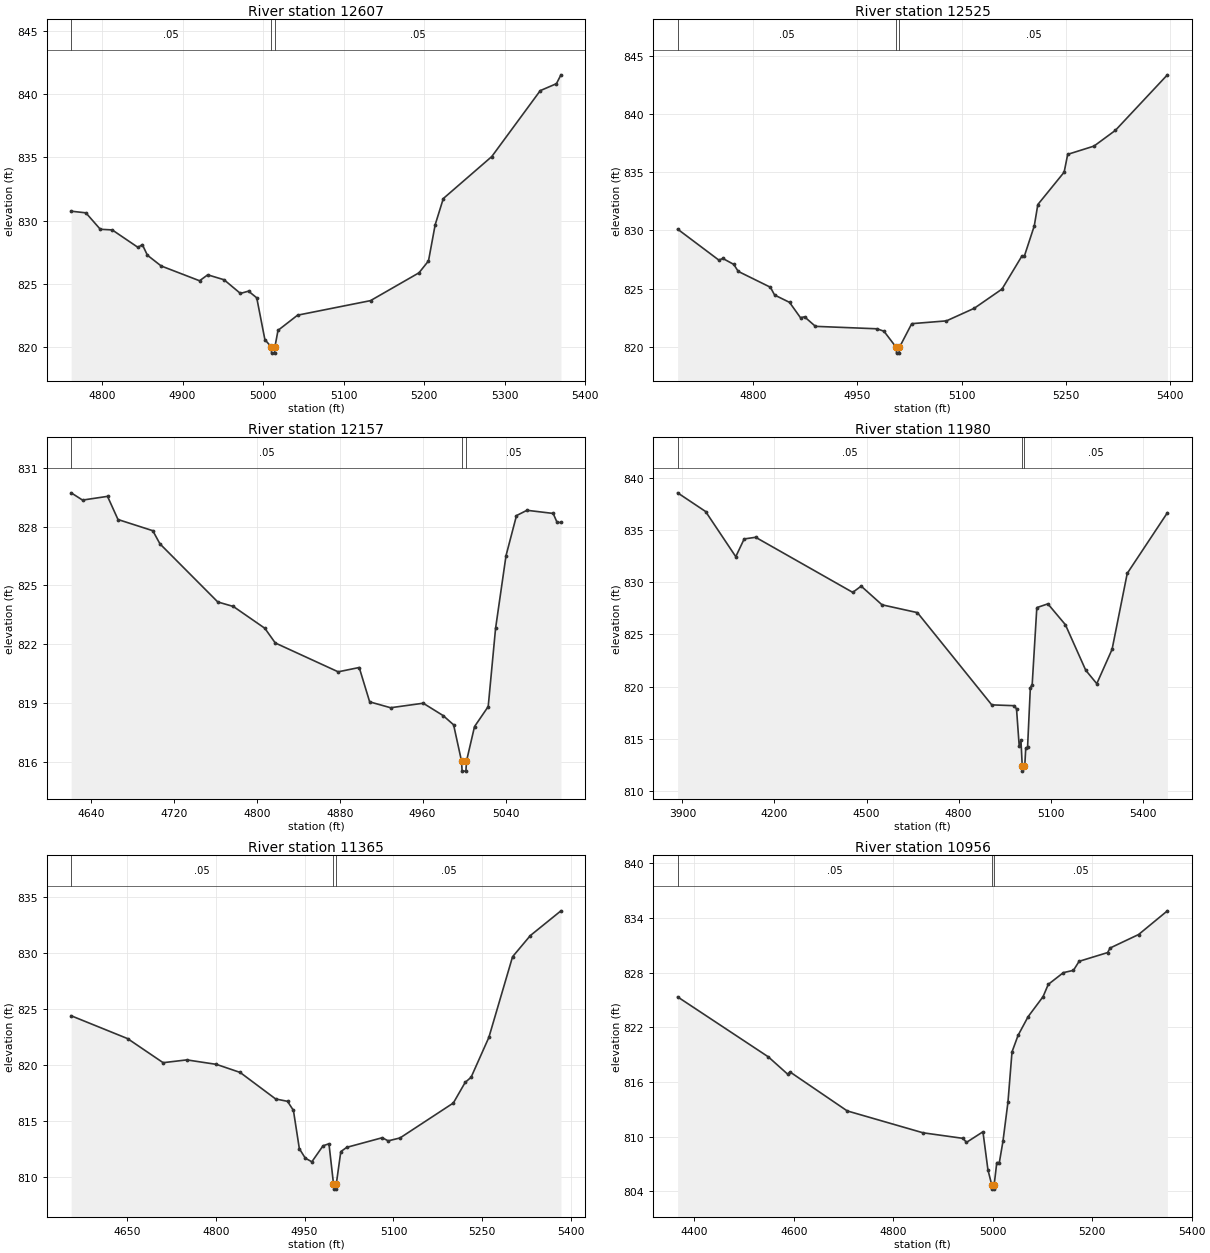
Type RM Length L Ch R = 1,12607,82,82,82
BEGIN DESCRIPTION:
Mapping XS 673fa076
END DESCRIPTION:
XS GIS Cut Line= 4
      2303652.25      7089380.13      2303773.03      7089327.28
      2303802.16      7089154.43      2303828.92      7088854.44
#Sta/Elev= 30
  4761.6  830.74  4779.9  830.61  4797.8  829.31  4812.6  829.26  4844.6  827.88
  4850.0  828.10  4856.3  827.26  4873.4  826.41  4921.1  825.24  4931.2  825.71
  4951.5  825.32  4971.8  824.24  4981.9  824.42  4992.1  823.89  5002.2  820.59
  5010.0  820.02  5010.5  819.52  5014.2  819.52  5014.7  820.02  5018.5  821.32
  5042.8  822.52  5133.4  823.67  5193.6  825.87  5205.4  826.81  5213.7  829.67
  5223.8  831.74  5284.0  835.06  5344.2  840.27  5364.3  840.82  5369.9  841.52
#Mann=3,-1,0
  4761.6    0.05       0  5010.0   0.033       0  5014.7    0.05       0
Bank Sta=5010,5014.7
Exp/Cntr=0.3,0.1

Type RM Length L Ch R = 1,12525,368,368,368
BEGIN DESCRIPTION:
Mapping XS fa88d7ce
END DESCRIPTION:
XS GIS Cut Line= 4
      2303673.45      7089445.28      2303867.69      7089332.59
      2303870.56      7089057.75      2303916.37      7088856.93
#Sta/Elev= 30
  4691.0  830.11  4750.4  827.45  4756.2  827.59  4771.9  827.08  4778.3  826.48
  4824.6  825.12  4830.7  824.45  4852.2  823.82  4868.0  822.50  4873.8  822.58
  4889.5  821.76  4978.2  821.55  4988.2  821.34  5005.8  819.96  5006.3  819.46
  5010.0  819.46  5010.5  819.96  5028.2  821.99  5078.2  822.23  5118.2  823.31
  5158.2  824.96  5186.8  827.79  5190.4  827.79  5204.7  830.39  5209.8  832.22
  5247.7  835.00  5252.8  836.53  5290.7  837.24  5321.5  838.59  5396.4  843.36
#Mann=3,-1,0
  4691.0    0.05       0  5005.8   0.033       0  5010.5    0.05       0
Bank Sta=5005.8,5010.5
Exp/Cntr=0.3,0.1

Type RM Length L Ch R = 1,12157,177,177,177
BEGIN DESCRIPTION:
Mapping XS 2766252a
END DESCRIPTION:
XS GIS Cut Line= 2
      2303604.36      7089606.89      2304071.38      7089533.84
#Sta/Elev= 30
  4620.8  829.72  4631.8  829.35  4655.9  829.54  4666.0  828.36  4699.6  827.79
  4706.5  827.12  4762.3  824.16  4777.3  823.93  4807.7  822.82  4817.8  822.07
  4878.5  820.60  4898.8  820.82  4908.9  819.07  4929.1  818.77  4960.6  819.00
  4979.8  818.37  4989.9  817.90  4997.6  816.04  4998.1  815.54  5001.8  815.54
  5002.3  816.04  5010.1  817.81  5023.3  818.83  5030.4  822.81  5040.5  826.52
  5050.6  828.56  5060.7  828.83  5086.0  828.67  5089.8  828.21  5093.5  828.21
#Mann=3,-1,0
  4620.8    0.05       0  4997.6   0.033       0  5002.3    0.05       0
Bank Sta=4997.6,5002.3
Exp/Cntr=0.3,0.1

Type RM Length L Ch R = 1,11980,615,615,615
BEGIN DESCRIPTION:
MDW T 049 25.0
END DESCRIPTION:
XS GIS Cut Line= 3
      2303011.54      7090280.40      2303990.36      7089718.50
      2304379.01      7089460.00
#Sta/Elev= 30
  3884.5  838.56  3975.7  836.77  4074.0  832.44  4101.3  834.14  4138.7  834.30
  4455.0  829.02  4482.4  829.62  4550.3  827.83  4665.6  827.08  4907.8  818.24
  4981.4  818.16  4988.5  817.85  4997.2  814.29  5002.9  814.83  5007.1  812.39
  5007.6  811.89  5011.8  812.39  5015.3  812.39  5018.5  814.07  5024.5  814.21
  5033.5  819.88  5039.5  820.19  5054.6  827.56  5090.6  827.92  5147.7  825.92
  5213.9  821.56  5249.9  820.27  5299.7  823.56  5349.1  830.84  5479.9  836.65
#Mann=3,-1,0
  3884.5    0.05       0  5007.1   0.033       0  5011.8    0.05       0
Bank Sta=5007.1,5011.8
Exp/Cntr=0.3,0.1

Type RM Length L Ch R = 1,11365,409,409,409
BEGIN DESCRIPTION:
Mapping XS 506349d6
END DESCRIPTION:
XS GIS Cut Line= 2
      2304390.43      7090355.25      2304377.21      7089528.36
#Sta/Elev= 30
  4555.8  824.40  4651.1  822.36  4711.1  820.21  4751.1  820.46  4801.1  820.06
  4841.1  819.34  4901.1  816.97  4921.1  816.76  4931.1  815.95  4941.1  812.53
  4951.1  811.69  4962.2  811.36  4981.1  812.79  4991.1  812.97  4998.7  809.42
  4999.3  808.92  5003.0  808.92  5003.6  809.42  5011.1  812.27  5021.1  812.65
  5081.1  813.51  5091.1  813.23  5111.1  813.49  5201.1  816.61  5221.1  818.45
  5231.1  818.91  5261.1  822.47  5301.1  829.67  5331.1  831.56  5382.8  833.77
#Mann=3,-1,0
  4555.8    0.05       0  4998.7   0.033       0  5003.6    0.05       0
Bank Sta=4998.7,5003.6
Exp/Cntr=0.3,0.1

Type RM Length L Ch R = 1,10956,488,488,488
BEGIN DESCRIPTION:
MDW T 049 23.0
END DESCRIPTION:
XS GIS Cut Line= 3
      2304772.81      7090401.72      2304718.84      7089759.50
      2304665.64      7089423.46
#Sta/Elev= 30
  4366.5  825.34  4548.9  818.76  4587.6  816.87  4592.6  817.10  4707.5  812.83
  4859.9  810.43  4940.2  809.82  4947.3  809.38  4980.4  810.54  4990.4  806.37
  4997.9  804.75  4998.5  804.25  5002.3  804.25  5003.0  804.75  5008.2  807.16
  5013.3  807.16  5020.6  809.49  5030.7  813.81  5038.8  819.30  5051.0  821.12
  5071.2  823.17  5101.2  825.36  5111.7  826.71  5142.1  828.00  5162.3  828.25
  5173.7  829.24  5231.0  830.20  5236.0  830.70  5293.3  832.18  5351.2  834.78
#Mann=3,-1,0
  4366.5    0.05       0  4997.9   0.033       0  5003.0    0.05       0
Bank Sta=4997.9,5003
Exp/Cntr=0.3,0.1