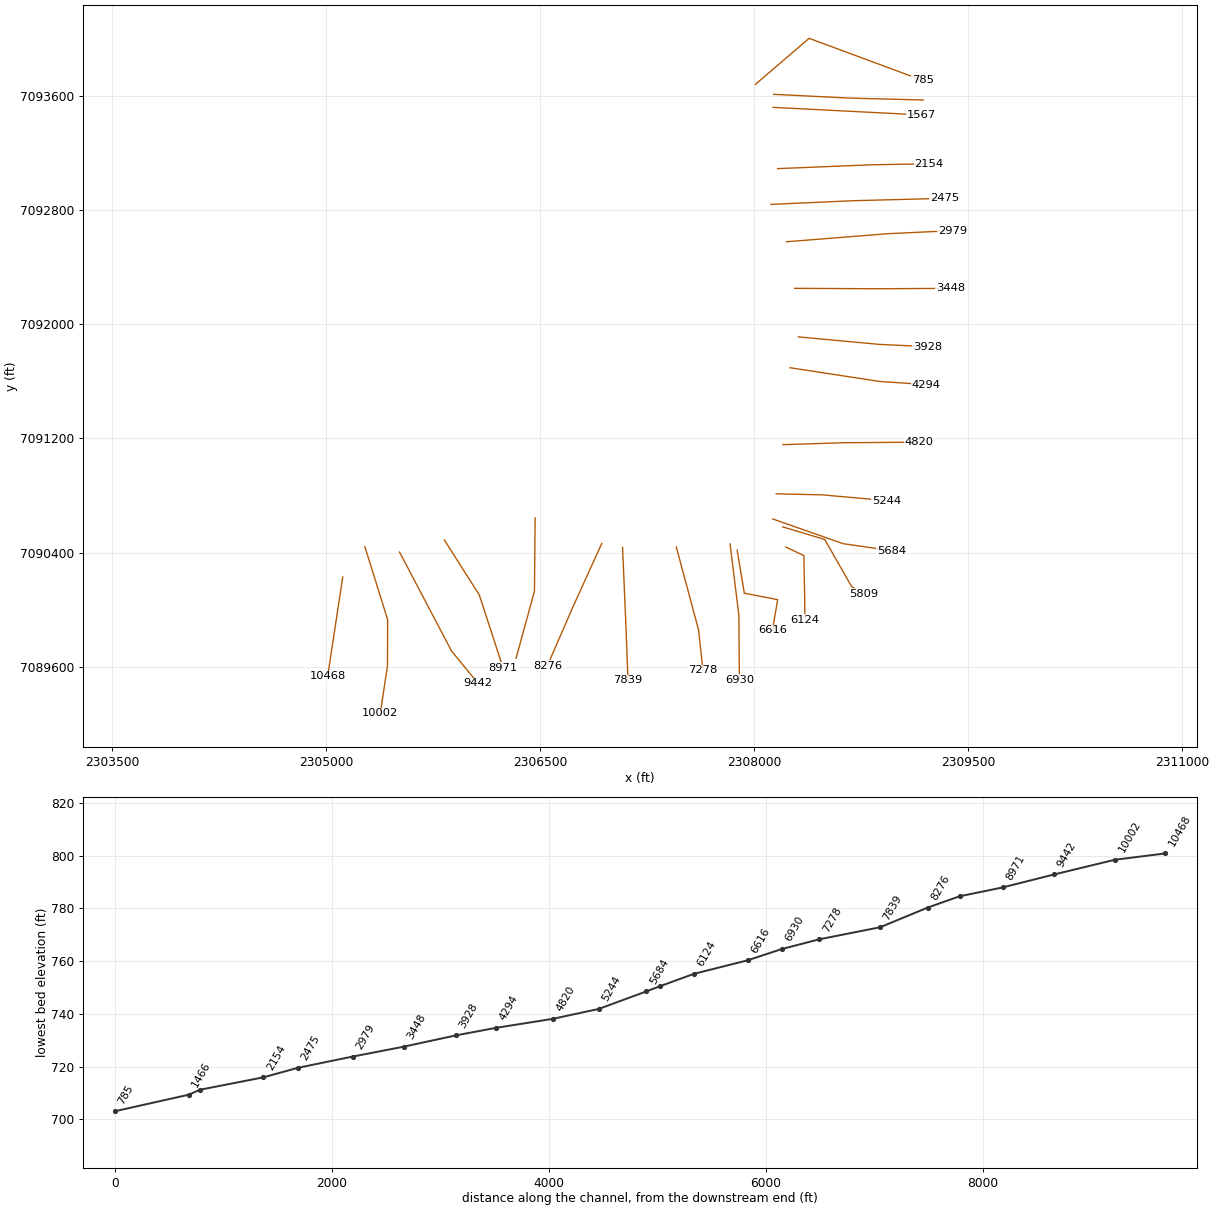
HEC-RAS study MDW T 049.prj: MDW T 049 Base Level Engineering

--- MDW T 049.g01 (geometry) --- (continued)

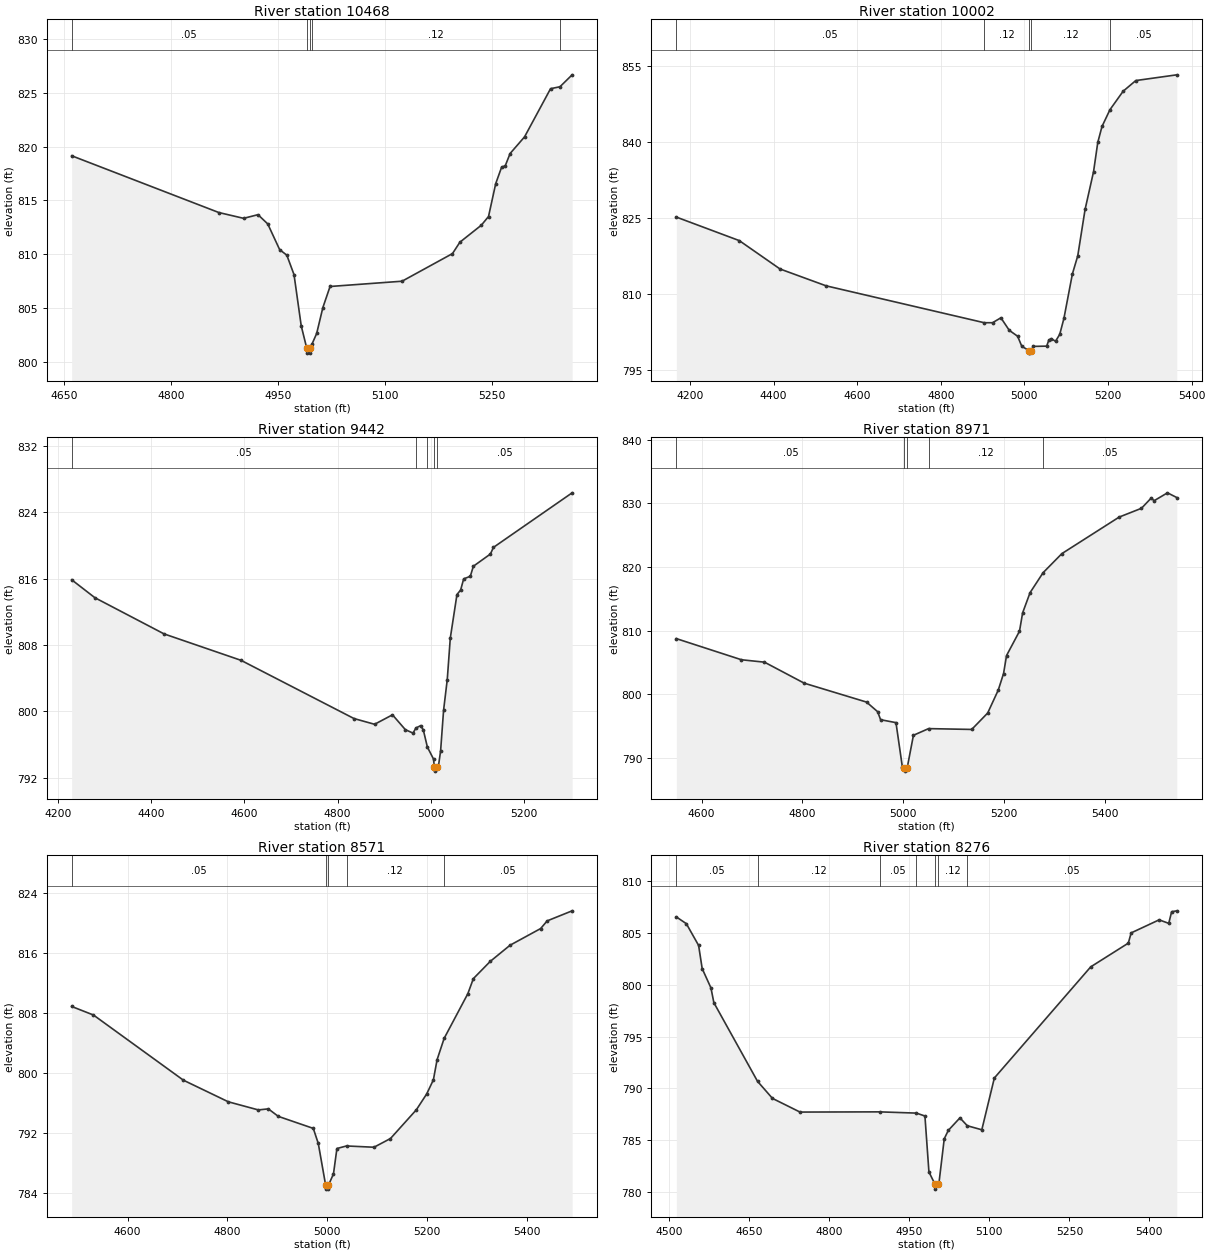
Type RM Length L Ch R = 1,10468,466,466,466
BEGIN DESCRIPTION:
Mapping XS 438a9bf3
END DESCRIPTION:
XS GIS Cut Line= 2
      2305115.10      7090228.66      2305009.63      7089533.92
#Sta/Elev= 30
  4660.3  819.16  4866.9  813.88  4901.7  813.34  4921.9  813.68  4935.6  812.82
  4952.3  810.43  4962.4  809.91  4972.5  808.10  4982.6  803.34  4990.2  801.30
  4990.8  800.80  4994.6  800.80  4995.3  801.30  4997.6  801.62  5004.3  802.63
  5013.0  805.04  5023.1  807.00  5124.2  807.49  5195.0  810.06  5205.4  811.12
  5235.5  812.70  5245.6  813.51  5255.7  816.57  5264.0  818.10  5269.1  818.23
  5275.9  819.37  5296.2  820.92  5332.7  825.40  5345.9  825.58  5363.0  826.69
#Mann=5,-1,0
  4660.3    0.05       0  4990.2    0.07       0  4995.3    0.05       0
  4997.6    0.12       0  5345.9    0.05       0
Bank Sta=4990.2,4995.3
Exp/Cntr=0.3,0.1

Type RM Length L Ch R = 1,10002,560,560,560
BEGIN DESCRIPTION:
MDW T 049 21.0
END DESCRIPTION:
XS GIS Cut Line= 4
      2305270.21      7090441.88      2305429.93      7089929.71
      2305429.00      7089610.00      2305378.58      7089273.06
#Sta/Elev= 30
  4167.6  825.23  4318.1  820.59  4415.6  814.99  4525.7  811.67  4903.9  804.39
  4923.8  804.39  4943.8  805.36  4963.8  802.89  4983.8  801.72  4993.8  799.73
  5011.2  798.89  5011.9  798.39  5016.4  798.89  5021.3  799.72  5053.3  799.77
  5058.4  800.95  5064.3  801.25  5074.4  800.73  5084.5  802.08  5094.6  805.27
  5114.8  814.02  5127.6  817.58  5145.1  826.73  5165.4  834.19  5175.5  839.96
  5185.6  843.11  5204.7  846.43  5236.1  850.06  5266.5  852.17  5364.5  853.30
#Mann=5,-1,0
  4167.6    0.05       0  4903.9    0.12       0  5011.2    0.07       0
  5016.4    0.12       0  5204.7    0.05       0
Bank Sta=5011.2,5016.4
Exp/Cntr=0.3,0.1

Type RM Length L Ch R = 1,9442,471,471,471
BEGIN DESCRIPTION:
MDW T 049 20.0
END DESCRIPTION:
XS GIS Cut Line= 3
      2305513.26      7090403.68      2305877.88      7089709.89
      2306061.86      7089485.29
#Sta/Elev= 30
  4229.1  815.86  4278.9  813.70  4427.5  809.34  4592.6  806.16  4835.1  799.15
  4879.2  798.46  4917.6  799.60  4945.3  797.81  4961.7  797.40  4967.9  798.01
  4978.1  798.30  4983.8  797.78  4992.5  795.72  5005.8  794.26  5007.3  793.32
  5008.1  792.82  5012.6  793.32  5016.0  793.32  5020.9  795.25  5027.3  800.15
  5035.2  803.85  5041.7  808.84  5056.0  814.08  5063.9  814.63  5070.4  815.97
  5084.7  816.28  5091.2  817.49  5127.8  818.96  5134.3  819.76  5303.2  826.33
#Mann=5,-1,0
  4229.1    0.05       0  4967.9    0.12       0  4992.5    0.05       0
  5007.3   0.033       0  5012.6    0.05       0
Bank Sta=5007.3,5012.6
Exp/Cntr=0.3,0.1

Type RM Length L Ch R = 1,8971,400,400,400
BEGIN DESCRIPTION:
MDW T 049 19.0
END DESCRIPTION:
XS GIS Cut Line= 3
      2305827.50      7090488.31      2306072.24      7090103.52
      2306238.40      7089593.32
#Sta/Elev= 30
  4550.1  808.76  4679.2  805.44  4724.9  805.06  4803.7  801.76  4927.3  798.79
  4949.3  797.28  4955.2  796.02  4985.7  795.56  4998.4  788.58  5002.6  788.44
  5003.4  787.94  5007.9  788.44  5020.3  793.57  5050.4  794.62  5135.9  794.49
  5167.6  797.07  5188.6  800.68  5199.1  803.28  5205.0  806.10  5230.7  809.93
  5236.9  812.81  5251.7  815.99  5277.5  819.12  5314.8  822.12  5428.4  827.86
  5472.6  829.24  5492.3  830.88  5497.5  830.42  5524.2  831.67  5542.7  830.93
#Mann=5,-1,0
  4550.1    0.05       0  5002.6   0.033       0  5007.9    0.05       0
  5050.4    0.12       0  5277.5    0.05       0
Bank Sta=5002.6,5007.9
Exp/Cntr=0.3,0.1

Type RM Length L Ch R = 1,8571,295,295,295
BEGIN DESCRIPTION:
MDW T 049 18.0
END DESCRIPTION:
XS GIS Cut Line= 3
      2306463.76      7090643.62      2306459.05      7090130.12
      2306330.09      7089659.28
#Sta/Elev= 30
  4488.2  808.88  4531.8  807.74  4711.8  799.06  4801.8  796.18  4861.8  795.10
  4881.8  795.24  4901.8  794.24  4971.8  792.64  4981.8  790.63  4996.6  785.05
  4997.4  784.55  5001.2  784.55  5002.0  785.05  5012.2  786.58  5019.1  789.96
  5038.3  790.30  5093.3  790.13  5126.3  791.29  5178.1  795.12  5198.8  797.23
  5212.2  799.11  5219.6  801.79  5233.7  804.63  5281.2  810.59  5292.2  812.59
  5326.1  814.89  5365.7  817.04  5426.9  819.26  5439.9  820.28  5489.9  821.62
#Mann=5,-1,0
  4488.2    0.05       0  4996.6   0.033       0  5002.0    0.05       0
  5038.3    0.12       0  5233.7    0.05       0
Bank Sta=4996.6,5002
Exp/Cntr=0.3,0.1

Type RM Length L Ch R = 1,8276,437,437,437
BEGIN DESCRIPTION:
MDW T 049 17.0
END DESCRIPTION:
XS GIS Cut Line= 3
      2306930.81      7090464.02      2306727.15      7090016.24
      2306549.71      7089607.18
#Sta/Elev= 30
  4513.5  806.55  4532.2  805.90  4555.2  803.80  4561.9  801.56  4578.3  799.70
  4583.8  798.27  4665.6  790.68  4693.6  789.03  4745.2  787.71  4894.6  787.73
  4963.3  787.61  4979.3  787.33  4986.8  781.93  4997.9  780.77  4998.7  780.27
  5003.3  780.77  5005.4  780.77  5015.5  785.13  5023.1  785.94  5044.9  787.15
  5058.7  786.39  5085.9  786.00  5109.4  791.00  5290.0  801.73  5360.4  804.02
  5365.8  805.01  5418.2  806.27  5436.2  805.93  5441.6  807.05  5451.3  807.14
#Mann=7,-1,0
  4513.5    0.05       0  4665.6    0.12       0  4894.6    0.05       0
  4963.3    0.12       0  4997.9    0.07       0  5003.3    0.12       0
  5058.7    0.05       0
Bank Sta=4997.9,5003.3
Exp/Cntr=0.3,0.1

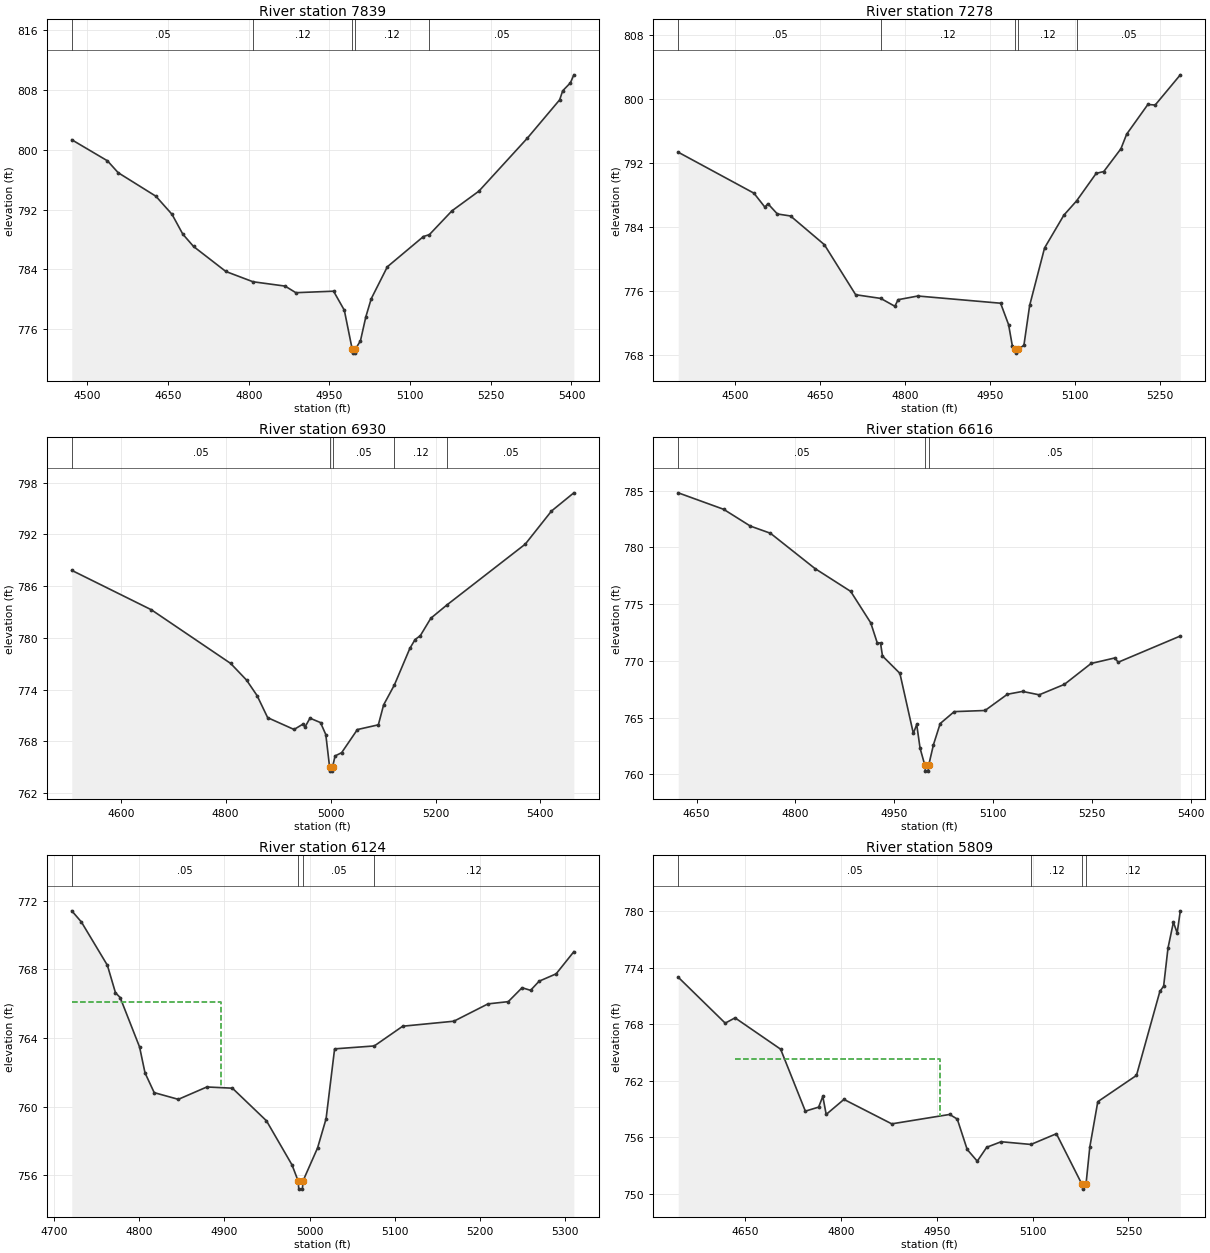
Type RM Length L Ch R = 1,7839,561,561,561
BEGIN DESCRIPTION:
MDW T 049 16.0
END DESCRIPTION:
XS GIS Cut Line= 3
      2307076.63      7090436.22      2307098.99      7089910.03
      2307114.77      7089503.60
#Sta/Elev= 30
  4471.0  801.32  4537.3  798.51  4557.3  796.92  4627.4  793.78  4657.4  791.36
  4677.4  788.72  4697.4  787.07  4757.5  783.73  4807.9  782.36  4867.6  781.78
  4887.6  780.90  4957.7  781.10  4977.7  778.56  4992.4  773.33  4993.2  772.83
  4997.1  772.83  4998.0  773.33  5007.7  774.48  5017.7  777.68  5027.7  780.09
  5057.7  784.36  5124.8  788.40  5135.8  788.65  5177.8  791.83  5227.9  794.46
  5317.9  801.53  5378.0  806.65  5383.7  807.86  5398.0  808.92  5404.4  809.99
#Mann=5,-1,0
  4471.0    0.05       0  4807.9    0.12       0  4992.4    0.07       0
  4998.0    0.12       0  5135.8    0.05       0
Bank Sta=4992.4,4998
Exp/Cntr=0.3,0.1

Type RM Length L Ch R = 1,7278,348,348,348
BEGIN DESCRIPTION:
MDW T 049 15.0
END DESCRIPTION:
XS GIS Cut Line= 3
      2307453.37      7090438.83      2307608.82      7089859.74
      2307640.01      7089575.94
#Sta/Elev= 30
  4400.4  793.35  4533.8  788.24  4553.2  786.49  4558.4  786.93  4575.2  785.64
  4598.4  785.39  4658.0  781.81  4713.2  775.56  4757.4  775.10  4782.3  774.12
  4788.0  774.94  4822.8  775.40  4968.7  774.50  4982.8  771.82  4989.4  769.17
  4994.5  768.77  4995.3  768.27  5000.1  768.77  5009.8  769.25  5019.9  774.22
  5046.2  781.40  5080.2  785.49  5102.7  787.28  5137.2  790.71  5150.6  790.94
  5180.8  793.78  5190.9  795.60  5228.3  799.31  5241.2  799.24  5285.5  803.01
#Mann=5,-1,0
  4400.4    0.05       0  4757.4    0.12       0  4994.5    0.07       0
  5000.1    0.12       0  5102.7    0.05       0
Bank Sta=4994.5,5000.1
Exp/Cntr=0.3,0.1

Type RM Length L Ch R = 1,6930,314,314,314
BEGIN DESCRIPTION:
MDW T 049 14.0
END DESCRIPTION:
XS GIS Cut Line= 3
      2307830.10      7090460.56      2307891.78      7089959.91
      2307895.21      7089507.36
#Sta/Elev= 30
  4506.7  787.83  4658.4  783.26  4809.5  777.04  4839.8  775.11  4859.9  773.31
  4880.1  770.75  4930.4  769.38  4946.5  769.97  4951.6  769.70  4960.7  770.69
  4980.8  770.18  4990.9  768.79  4998.1  765.05  4999.0  764.55  5002.9  764.55
  5003.8  765.05  5008.6  766.31  5021.1  766.69  5051.1  769.37  5091.1  769.92
  5101.1  772.23  5121.7  774.55  5151.1  778.78  5161.1  779.81  5171.1  780.26
  5191.1  782.28  5222.4  783.85  5371.1  790.87  5421.1  794.71  5463.7  796.82
#Mann=5,-1,0
  4506.7    0.05       0  4998.1   0.033       0  5003.8    0.05       0
  5121.7    0.12       0  5222.4    0.05       0
Bank Sta=4998.1,5003.8
Exp/Cntr=0.3,0.1

Type RM Length L Ch R = 1,6616,492,492,492
BEGIN DESCRIPTION:
Mapping XS 7b00a767
END DESCRIPTION:
XS GIS Cut Line= 4
      2307879.54      7090417.89      2307930.09      7090115.41
      2308163.71      7090070.26      2308127.52      7089856.62
#Sta/Elev= 30
  4622.2  784.80  4691.0  783.35  4731.6  781.87  4762.0  781.24  4829.6  778.13
  4883.7  776.12  4914.1  773.35  4924.0  771.58  4928.9  771.58  4931.9  770.43
  4958.3  768.90  4978.7  763.61  4983.8  764.40  4988.9  762.31  4996.2  760.79
  4997.1  760.29  5001.0  760.29  5001.9  760.79  5009.2  762.62  5019.4  764.48
  5040.7  765.53  5087.4  765.63  5121.3  767.06  5144.3  767.31  5169.5  767.01
  5207.7  767.93  5248.2  769.77  5284.3  770.26  5289.3  769.88  5383.5  772.19
#Mann=3,-1,0
  4622.2    0.05       0  4996.2   0.033       0  5001.9    0.05       0
Bank Sta=4996.2,5001.9
Exp/Cntr=0.3,0.1

Type RM Length L Ch R = 1,6124,315,315,315
BEGIN DESCRIPTION:
Mapping XS 4e49cfca
END DESCRIPTION:
XS GIS Cut Line= 3
      2308221.26      7090438.67      2308347.57      7090378.83
      2308355.35      7089929.17
#Sta/Elev= 30
  4720.7  771.41  4732.0  770.76  4762.5  768.24  4772.0  766.64  4777.5  766.36
  4800.3  763.48  4806.7  761.97  4817.5  760.82  4845.8  760.43  4879.3  761.15
  4909.3  761.08  4949.3  759.18  4979.3  756.61  4986.3  755.70  4987.3  755.20
  4991.4  755.20  4992.4  755.70  5009.3  757.60  5019.3  759.30  5029.3  763.37
  5075.9  763.54  5109.3  764.69  5169.3  764.98  5209.4  765.99  5233.2  766.12
  5249.4  766.93  5259.4  766.78  5269.4  767.31  5289.4  767.74  5310.2  769.03
#Mann=4,-1,0
  4720.7    0.05       0  4986.3   0.033       0  4992.4    0.05       0
  5075.9    0.12       0
#XS Ineff=2,0
    0.00 4895.60  766.09               0
Permanent Ineff=
       F       F
Bank Sta=4986.3,4992.4
Exp/Cntr=0.3,0.1

Type RM Length L Ch R = 1,5809,125,125,125
BEGIN DESCRIPTION:
Mapping XS 13248a72
END DESCRIPTION:
XS GIS Cut Line= 4
      2308198.57      7090580.55      2308493.23      7090491.90
      2308681.40      7090162.88      2308765.36      7090110.68
#Sta/Elev= 30
  4545.6  773.01  4619.1  768.13  4634.5  768.69  4705.8  765.36  4744.5  758.77
  4765.3  759.20  4771.8  760.34  4777.1  758.42  4804.9  760.02  4879.7  757.42
  4970.3  758.42  4982.2  757.93  4997.7  754.70  5013.5  753.45  5028.3  754.93
  5050.9  755.52  5097.5  755.23  5137.3  756.37  5177.4  750.98  5178.4  750.48
  5183.6  750.98  5189.6  754.96  5202.1  759.78  5262.6  762.57  5299.2  771.50
  5305.1  772.06  5311.9  776.10  5320.4  778.86  5326.3  777.72  5331.2  780.07
#Mann=4,-1,0
  4545.6    0.05       0  5097.5    0.12       0  5177.4   0.033       0
  5183.6    0.12       0
#XS Ineff=1,-1
 4635.10 4954.50  764.29
Permanent Ineff=
       F
Bank Sta=5177.4,5183.6
Exp/Cntr=0.3,0.1

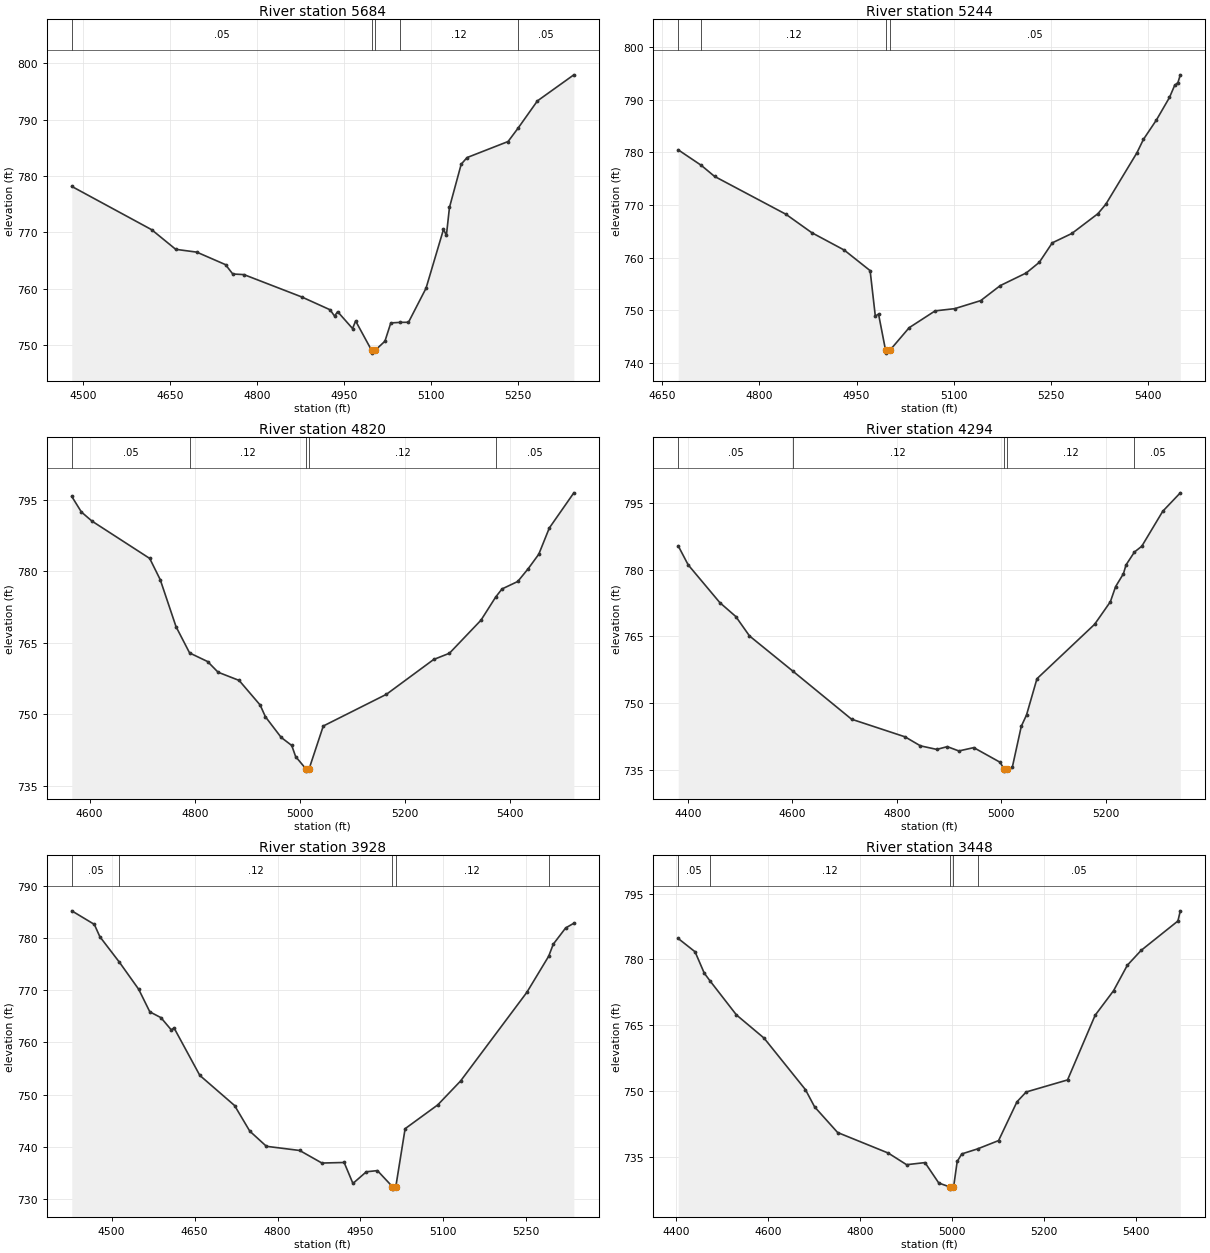
Type RM Length L Ch R = 1,5684,440,440,440
BEGIN DESCRIPTION:
MDW T 049 12.0
END DESCRIPTION:
XS GIS Cut Line= 3
      2308129.05      7090635.70      2308623.21      7090462.35
      2308961.14      7090413.66
#Sta/Elev= 30
  4481.0  778.13  4618.7  770.44  4660.1  766.96  4696.4  766.46  4745.9  764.24
  4758.4  762.58  4777.7  762.47  4877.1  758.51  4926.0  756.23  4933.8  755.11
  4939.1  755.89  4964.8  752.90  4970.1  754.24  4997.6  749.03  4998.6  748.53
  5003.8  749.03  5020.6  750.65  5030.7  753.89  5046.7  753.99  5061.2  754.01
  5091.4  760.05  5121.5  770.50  5126.5  769.45  5131.8  774.40  5152.0  782.07
  5162.1  783.25  5232.8  786.10  5250.2  788.50  5283.3  793.31  5346.1  797.94
#Mann=5,-1,0
  4481.0    0.05       0  4997.6   0.033       0  5003.8    0.05       0
  5046.7    0.12       0  5250.2    0.05       0
Bank Sta=4997.6,5003.8
Exp/Cntr=0.3,0.1

Type RM Length L Ch R = 1,5244,424,424,424
BEGIN DESCRIPTION:
MDW T 049 11.0
END DESCRIPTION:
XS GIS Cut Line= 3
      2308153.06      7090812.09      2308477.97      7090804.58
      2308925.68      7090764.49
#Sta/Elev= 30
  4675.0  780.50  4710.5  777.56  4731.0  775.46  4841.0  768.27  4881.0  764.76
  4931.0  761.46  4971.0  757.55  4979.0  748.92  4984.0  749.28  4994.9  742.37
  4995.9  741.87  5001.2  742.37  5031.2  746.70  5071.3  749.90  5101.4  750.32
  5141.6  751.85  5171.7  754.70  5211.9  757.11  5232.0  759.13  5252.0  762.83
  5282.2  764.61  5322.3  768.36  5334.5  770.15  5382.6  779.95  5392.6  782.49
  5412.7  786.19  5432.8  790.46  5440.8  792.76  5445.8  793.28  5449.5  794.76
#Mann=4,-1,0
  4675.0    0.05       0  4710.5    0.12       0  4994.9   0.033       0
  5001.2    0.05       0
Bank Sta=4994.9,5001.2
Exp/Cntr=0.3,0.1

Type RM Length L Ch R = 1,4820,526,526,526
BEGIN DESCRIPTION:
MDW T 049 10.0
END DESCRIPTION:
XS GIS Cut Line= 3
      2308200.74      7091156.71      2308628.89      7091170.05
      2309155.72      7091174.05
#Sta/Elev= 30
  4566.1  795.72  4584.4  792.46  4604.4  790.56  4714.4  782.72  4734.4  778.27
  4764.5  768.40  4790.3  762.90  4824.5  761.10  4844.5  758.86  4884.5  757.14
  4924.5  751.98  4934.5  749.52  4964.5  745.19  4984.6  743.50  4992.0  741.17
  5011.4  738.62  5012.4  738.12  5017.7  738.62  5044.6  747.58  5164.6  754.22
  5254.6  761.53  5284.6  762.84  5344.6  769.77  5372.5  774.61  5384.6  776.32
  5414.6  777.89  5434.6  780.59  5454.6  783.61  5474.6  789.10  5521.3  796.48
#Mann=5,-1,0
  4566.1    0.05       0  4790.3    0.12       0  5011.4    0.07       0
  5017.7    0.12       0  5372.5    0.05       0
Bank Sta=5011.4,5017.7
Exp/Cntr=0.3,0.1

Type RM Length L Ch R = 1,4294,366,366,366
BEGIN DESCRIPTION:
MDW T 049 9.0
END DESCRIPTION:
XS GIS Cut Line= 3
      2308250.21      7091695.77      2308879.77      7091599.37
      2309202.55      7091577.71
#Sta/Elev= 30
  4381.8  785.39  4400.8  781.12  4461.5  772.60  4491.9  769.49  4518.1  765.12
  4600.6  757.24  4713.3  746.38  4815.6  742.41  4845.1  740.38  4876.3  739.58
  4896.5  740.20  4918.6  739.23  4947.1  739.98  4997.7  736.67  5004.6  735.19
  5005.7  734.69  5011.0  735.19  5020.8  735.54  5038.0  744.78  5048.0  747.32
  5068.0  755.49  5178.3  767.74  5208.4  772.81  5218.4  776.21  5233.4  779.13
  5238.4  781.11  5254.5  784.01  5268.5  785.31  5308.6  793.18  5342.2  797.33
#Mann=5,-1,0
  4381.8    0.05       0  4600.6    0.12       0  5004.6    0.07       0
  5011.0    0.12       0  5254.5    0.05       0
Bank Sta=5004.6,5011
Exp/Cntr=0.3,0.1

Type RM Length L Ch R = 1,3928,480,480,480
BEGIN DESCRIPTION:
MDW T 049 8.0
END DESCRIPTION:
XS GIS Cut Line= 3
      2308308.41      7091911.91      2308871.97      7091859.79
      2309213.81      7091843.34
#Sta/Elev= 30
  4427.8  785.22  4468.6  782.62  4478.6  780.26  4514.1  775.35  4548.9  770.17
  4569.0  765.85  4589.1  764.74  4607.8  762.39  4612.8  762.77  4659.4  753.67
  4722.3  747.89  4749.8  742.98  4779.9  740.07  4840.1  739.27  4880.3  736.86
  4920.5  736.97  4936.4  732.95  4960.7  735.19  4980.7  735.41  5007.6  732.36
  5008.6  731.86  5014.0  732.36  5030.8  743.45  5089.7  748.00  5131.0  752.58
  5251.1  769.61  5290.5  776.52  5298.8  778.83  5321.2  781.94  5336.0  782.84
#Mann=5,-1,0
  4427.8    0.05       0  4514.1    0.12       0  5007.6    0.07       0
  5014.0    0.12       0  5290.5    0.05       0
Bank Sta=5007.6,5014
Exp/Cntr=0.3,0.1

Type RM Length L Ch R = 1,3448,469,469,469
BEGIN DESCRIPTION:
MDW T 049 7.0
END DESCRIPTION:
XS GIS Cut Line= 3
      2308282.39      7092252.19      2308878.28      7092249.29
      2309374.17      7092252.19
#Sta/Elev= 30
  4404.1  784.74  4440.7  781.71  4460.7  776.84  4473.2  775.08  4530.7  767.31
  4590.7  762.03  4680.7  750.28  4700.7  746.34  4750.7  740.50  4860.7  735.82
  4900.7  733.16  4940.7  733.64  4970.7  728.98  4994.6  728.09  4995.7  727.59
  5001.1  728.09  5002.9  728.09  5010.7  733.89  5020.7  735.62  5054.9  736.76
  5100.7  738.66  5140.7  747.50  5160.7  749.74  5250.7  752.49  5310.7  767.24
  5350.7  772.83  5380.7  778.64  5410.7  782.03  5490.7  788.73  5495.9  791.05
#Mann=5,-1,0
  4404.1    0.05       0  4473.2    0.12       0  4994.6    0.07       0
  5001.1    0.12       0  5054.9    0.05       0
Bank Sta=4994.6,5001.1
Exp/Cntr=0.3,0.1

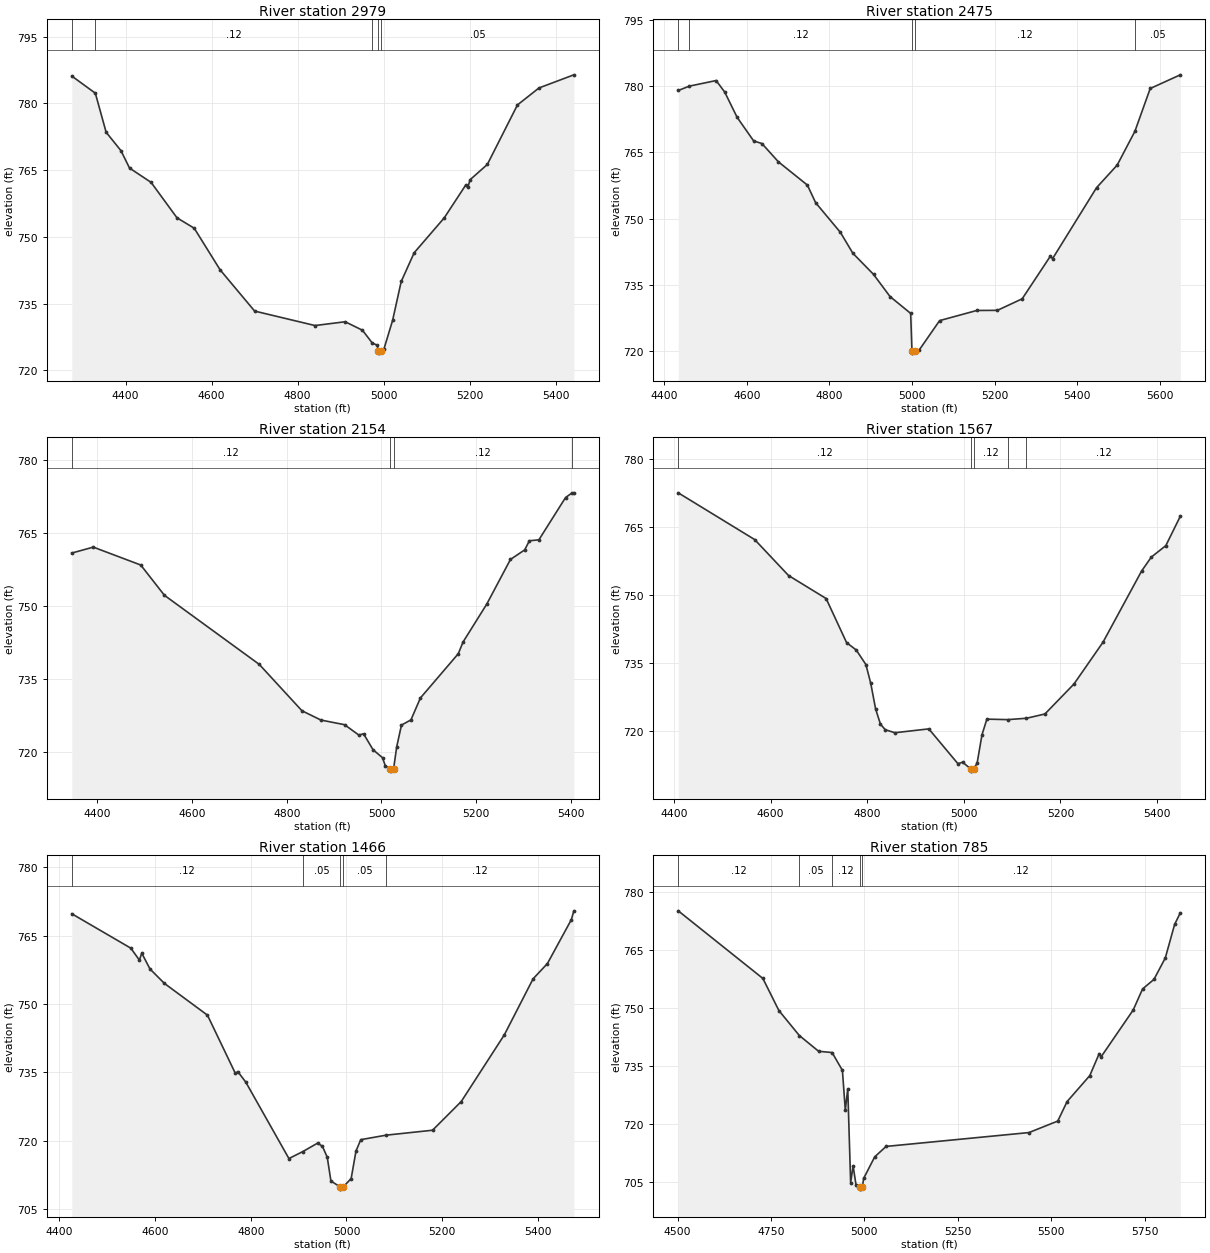
Type RM Length L Ch R = 1,2979,504,504,504
BEGIN DESCRIPTION:
MDW T 049 6.0
END DESCRIPTION:
XS GIS Cut Line= 3
      2308225.08      7092578.58      2308929.50      7092634.82
      2309390.02      7092656.71
#Sta/Elev= 30
  4274.8  786.13  4329.6  782.27  4354.7  773.50  4389.1  769.37  4409.1  765.45
  4459.3  762.23  4519.5  754.27  4559.6  751.93  4619.8  742.58  4700.1  733.31
  4840.5  730.06  4910.7  730.91  4950.9  729.00  4973.6  726.15  4985.6  725.61
  4987.7  724.36  4988.7  723.86  4994.3  724.36  5001.0  724.84  5021.0  731.23
  5041.0  739.96  5071.1  746.41  5141.1  754.26  5191.1  761.64  5196.1  761.16
  5201.2  762.83  5241.3  766.26  5311.3  779.63  5361.4  783.45  5442.5  786.40
#Mann=5,-1,0
  4274.8    0.05       0  4329.6    0.12       0  4973.6    0.05       0
  4987.7   0.033       0  4994.3    0.05       0
Bank Sta=4987.7,4994.3
Exp/Cntr=0.3,0.1

Type RM Length L Ch R = 1,2475,321,321,321
BEGIN DESCRIPTION:
MDW T 049 5.0
END DESCRIPTION:
XS GIS Cut Line= 3
      2308116.52      7092840.73      2308686.77      7092866.12
      2309331.83      7092883.27
#Sta/Elev= 30
  4433.7  778.97  4460.5  779.95  4525.5  781.22  4546.3  778.61  4576.3  772.91
  4616.4  767.57  4636.4  766.98  4676.4  762.84  4746.5  757.59  4766.5  753.61
  4826.6  746.89  4856.6  742.19  4906.7  737.41  4946.7  732.40  4996.7  728.59
  4999.8  720.11  5000.9  719.61  5006.4  720.11  5016.8  720.24  5066.8  726.96
  5156.8  729.25  5206.8  729.28  5266.8  731.89  5335.3  741.56  5340.3  740.95
  5446.9  757.00  5496.9  762.11  5539.8  769.74  5576.9  779.42  5649.8  782.51
#Mann=5,-1,0
  4433.7    0.05       0  4460.5    0.12       0  4999.8    0.07       0
  5006.4    0.12       0  5539.8    0.05       0
Bank Sta=4999.8,5006.4
Exp/Cntr=0.3,0.1

Type RM Length L Ch R = 1,2154,587,587,587
BEGIN DESCRIPTION:
MDW T 049 4.0
END DESCRIPTION:
XS GIS Cut Line= 3
      2308163.54      7093091.33      2308825.91      7093118.31
      2309222.83      7093125.28
#Sta/Elev= 30
  4346.2  760.84  4391.7  762.06  4491.8  758.38  4541.8  752.15  4742.0  737.94
  4832.1  728.40  4872.1  726.49  4922.1  725.53  4952.2  723.40  4962.2  723.66
  4982.2  720.38  5002.2  718.74  5008.2  717.05  5018.9  716.48  5019.9  715.98
  5025.6  716.48  5032.2  721.01  5042.2  725.45  5062.2  726.52  5082.2  731.03
  5162.2  740.14  5172.2  742.54  5222.2  750.33  5272.3  759.53  5302.3  761.49
  5312.3  763.37  5332.3  763.56  5388.6  772.26  5402.6  773.23  5406.1  773.23
#Mann=4,-1,0
  4346.2    0.12       0  5018.9    0.07       0  5025.6    0.12       0
  5402.6    0.05       0
Bank Sta=5018.9,5025.6
Exp/Cntr=0.3,0.1

Type RM Length L Ch R = 1,1567,101,101,101
BEGIN DESCRIPTION:
Mapping XS 7439bf51
END DESCRIPTION:
XS GIS Cut Line= 2
      2308130.97      7093520.78      2309168.92      7093467.69
#Sta/Elev= 30
  4408.8  772.58  4567.0  762.28  4637.1  754.36  4714.9  749.29  4757.3  739.57
  4777.3  737.94  4797.3  734.73  4807.3  730.59  4817.4  724.94  4827.4  721.60
  4837.4  720.37  4857.4  719.71  4927.5  720.56  4987.6  712.91  4997.6  713.20
  5014.3  711.75  5015.3  711.25  5021.0  711.75  5027.6  713.07  5037.6  719.28
  5047.7  722.71  5090.6  722.60  5129.7  722.90  5167.8  723.84  5227.9  730.44
  5288.0  739.65  5368.1  755.37  5388.1  758.42  5418.1  760.94  5448.1  767.42
#Mann=5,-1,0
  4408.8    0.12       0  5014.3    0.07       0  5021.0    0.12       0
  5090.6    0.05       0  5129.7    0.12       0
Bank Sta=5014.3,5021
Exp/Cntr=0.3,0.1

Type RM Length L Ch R = 1,1466,681,681,681
BEGIN DESCRIPTION:
MDW T 049 3.0
END DESCRIPTION:
XS GIS Cut Line= 3
      2308135.74      7093612.16      2308679.29      7093585.12
      2309184.20      7093572.23
#Sta/Elev= 30
  4425.9  769.81  4549.3  762.26  4567.2  759.64  4572.2  761.16  4589.4  757.69
  4619.4  754.54  4709.5  747.56  4767.9  734.77  4772.9  735.18  4789.6  732.87
  4879.7  716.11  4908.8  717.64  4939.8  719.50  4949.8  718.78  4959.8  716.41
  4967.5  711.19  4986.5  709.90  4987.5  709.40  4993.2  709.90  5009.8  711.72
  5019.9  717.76  5029.9  720.25  5083.0  721.24  5179.9  722.32  5239.9  728.62
  5330.0  743.26  5390.0  755.53  5420.0  758.89  5470.0  768.52  5475.2  770.45
#Mann=5,-1,0
  4425.9    0.12       0  4908.8    0.05       0  4986.5   0.033       0
  4993.2    0.05       0  5083.0    0.12       0
Bank Sta=4986.5,4993.2
Exp/Cntr=0.3,0.1

Type RM Length L Ch R = 1,785,214,214,214
BEGIN DESCRIPTION:
MDW T 049 2.0
END DESCRIPTION:
XS GIS Cut Line= 3
      2308007.23      7093681.58      2308384.10      7094004.53
      2309178.98      7093710.01
#Sta/Elev= 30
  4501.6  775.07  4728.2  757.59  4771.0  749.30  4825.8  742.83  4877.5  738.76
  4913.5  738.44  4941.1  733.82  4948.8  723.55  4955.4  729.09  4963.1  704.84
  4969.7  709.13  4977.4  704.30  4987.8  703.63  4988.9  703.13  4994.6  703.63
  4997.8  705.88  5027.6  711.48  5058.0  714.17  5440.4  717.75  5517.5  720.72
  5542.6  725.77  5603.3  732.48  5628.4  738.14  5633.7  737.35  5719.5  749.44
  5744.6  754.88  5775.0  757.34  5805.4  762.88  5830.4  771.57  5845.6  774.55
#Mann=5,-1,0
  4501.6    0.12       0  4825.8    0.05       0  4913.5    0.12       0
  4987.8    0.07       0  4994.6    0.12       0
Bank Sta=4987.8,4994.6
Exp/Cntr=0.3,0.1