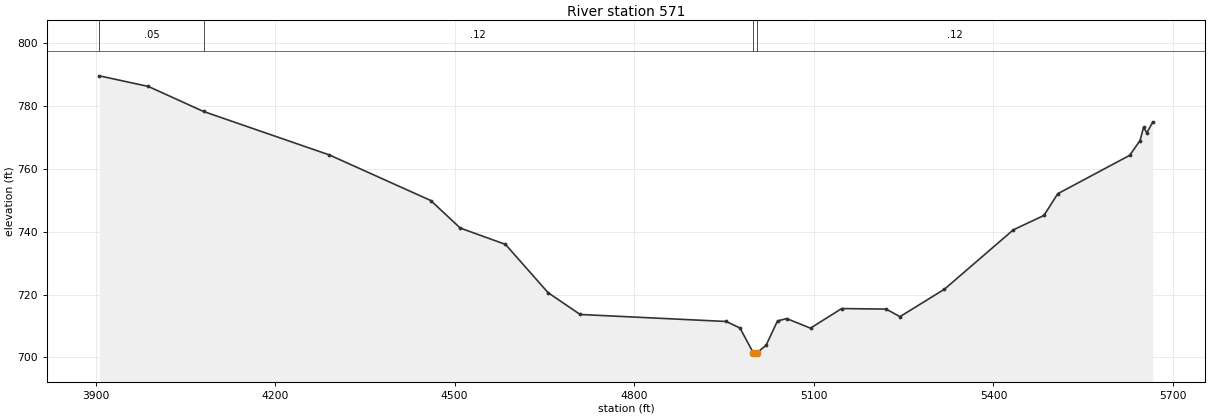
HEC-RAS study MDW T 049.prj: MDW T 049 Base Level Engineering

--- MDW T 049.g01 (geometry) --- (continued)

Type RM Length L Ch R = 1,571,0,0,0
BEGIN DESCRIPTION:
MDW T 049 1.0
END DESCRIPTION:
XS GIS Cut Line= 4
      2307893.98      7093504.05      2308297.63      7094233.22
      2308558.97      7094140.09      2309148.28      7093868.66
#Sta/Elev= 30
  3906.4  789.55  3988.3  786.17  4080.5  778.21  4290.4  764.41  4460.0  749.90
  4509.3  741.14  4584.8  735.95  4656.1  720.58  4709.6  713.66  4953.6  711.43
  4976.5  709.37  4998.6  701.55  4999.7  701.05  5005.4  701.55  5020.1  703.83
  5039.3  711.61  5054.6  712.35  5094.4  709.31  5146.4  715.54  5220.8  715.37
  5243.8  712.96  5318.2  721.70  5433.0  740.55  5484.4  745.16  5507.4  752.06
  5627.7  764.28  5644.9  768.98  5650.7  773.14  5656.2  771.45  5666.1  774.83
#Mann=4,-1,0
  3906.4    0.05       0  4080.5    0.12       0  4998.6    0.07       0
  5005.4    0.12       0
Bank Sta=4998.6,5005.4
Exp/Cntr=0.3,0.1

Chan Stop Cuts=-1