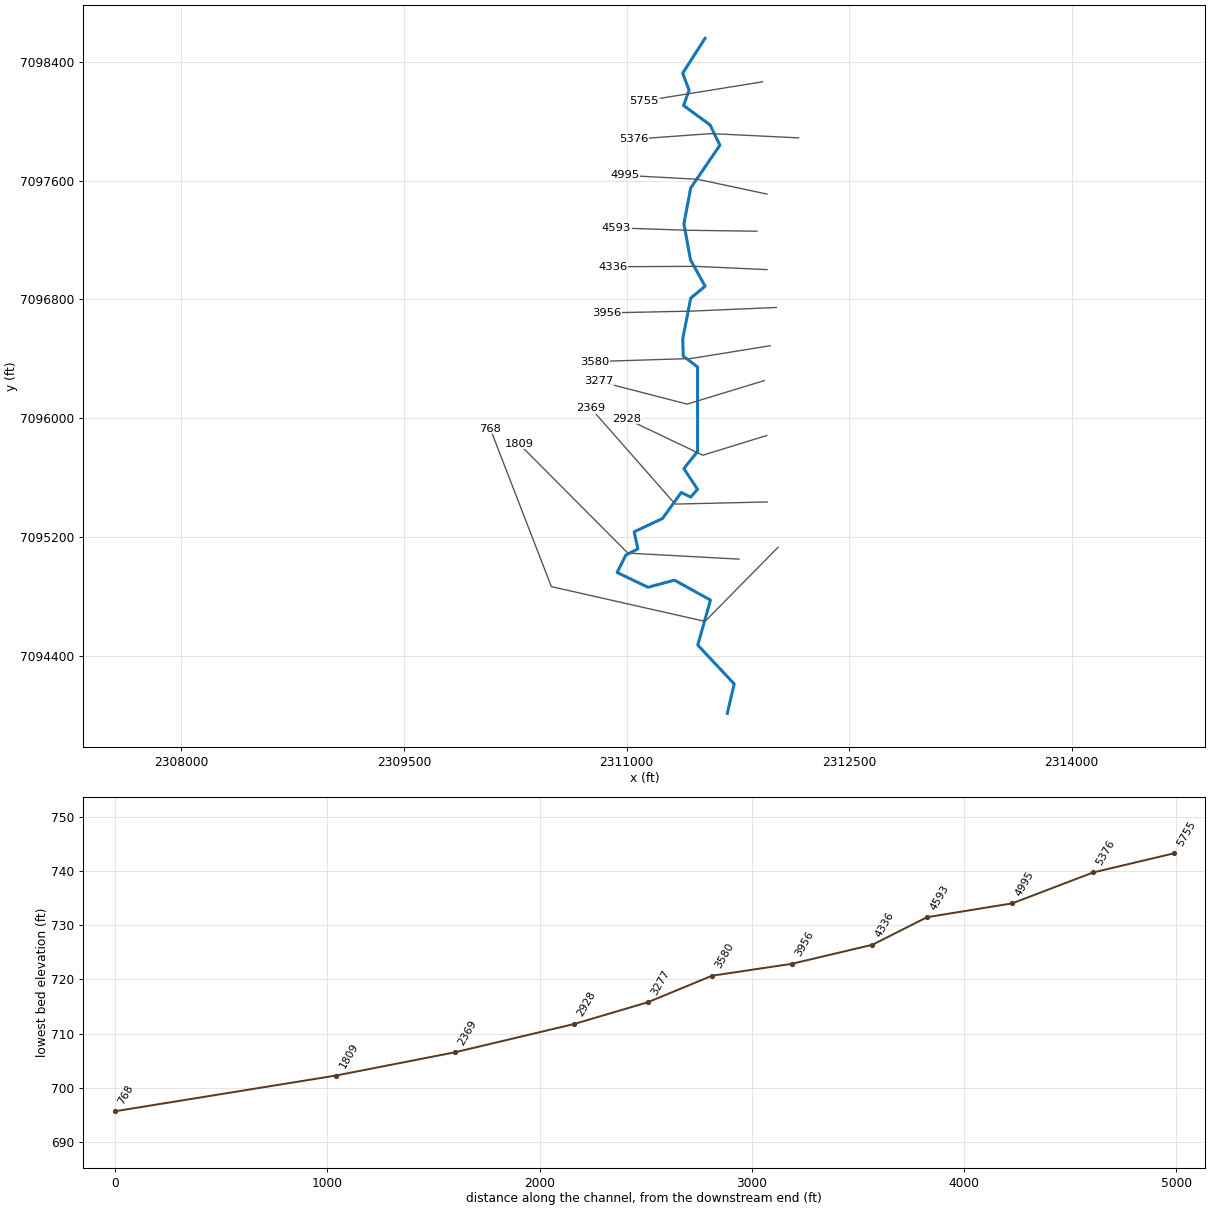
--- MDW T 050.prj (project) ---

Proj Title=MDW T 050 Base Level Engineering
Current Plan=p01
Default Exp/Contr=0.3,0.1
English Units
Geom File=g01
Flow File=f01
Plan File=p01
BEGIN DESCRIPTION:
MDW T 050
END DESCRIPTION:

--- MDW T 050.p01 (plan) ---

Plan Title=Multiple Run
Short Identifier=Multiple
Geom File=g01
Flow File=f01
Subcritical Flow
K Sum by GR= 0
Std Step Tol= 0.01
Critical Tol= 0.01
Num of Std Step Trials= 20
Max Error Tol= 0.3
Flow Tol Ratio= 0.001
Split Flow NTrial= 30
Split Flow Tol= 0.02
Split Flow Ratio= 0.02
Log Output Level= 0
Friction Slope Method= 1
Unsteady Friction Slope Method= 2
Unsteady Bridges Friction Slope Method= 1
Parabolic Critical Depth
Global Vel Dist=  1 , 1 , 1
Global Log Level= 0
CheckData=True
Encroach Param= -1, 0, 0, 0
BEGIN DESCRIPTION:
Multiple Run
END DESCRIPTION:

--- MDW T 050.f01 (steady flow) ---

Flow Title=Multiple
Number of Profiles=7
Profile Names=10-year,25-year,50-year,1pct_min,100-year,1pct_plu,500-year
River Rch & RM= MDW T 050,Reach-1,5755
     639     882    1084     662    1320    2634    1962
River Rch & RM= MDW T 050,Reach-1,768
     645     890    1094     668    1332    2658    1980
Boundary for River Rch & Prof#=MDW T 050,Reach-1,1
Up Type=0
Dn Type=3
Dn Slope=0.005
Boundary for River Rch & Prof#=MDW T 050,Reach-1,2
Up Type=0
Dn Type=3
Dn Slope=0.005
Boundary for River Rch & Prof#=MDW T 050,Reach-1,3
Up Type=0
Dn Type=3
Dn Slope=0.005
Boundary for River Rch & Prof#=MDW T 050,Reach-1,4
Up Type=0
Dn Type=3
Dn Slope=0.005
Boundary for River Rch & Prof#=MDW T 050,Reach-1,5
Up Type=0
Dn Type=3
Dn Slope=0.005
Boundary for River Rch & Prof#=MDW T 050,Reach-1,6
Up Type=0
Dn Type=3
Dn Slope=0.005
Boundary for River Rch & Prof#=MDW T 050,Reach-1,7
Up Type=0
Dn Type=3
Dn Slope=0.005

--- MDW T 050.g01 (geometry) ---

Geom Title=Existing Conditions

River Reach=MDW T 050,Reach-1
Reach XY= 30
      2311529.00      7098560.00      2311378.30      7098325.06
      2311421.40      7098209.99      2311384.01      7098107.46
      2311562.37      7097976.71      2311629.37      7097839.80
      2311432.46      7097551.54      2311386.56      7097310.00
      2311431.24      7097065.93      2311529.47      7096889.54
      2311432.48      7096808.74      2311378.76      7096535.05
      2311382.09      7096418.32      2311478.66      7096344.96
      2311478.61      7095775.16      2311386.10      7095660.00
      2311478.45      7095520.31      2311432.65      7095467.90
      2311368.69      7095498.89      2311242.24      7095323.61
      2311051.30      7095233.73      2311076.30      7095118.51
      2310995.57      7095077.01      2310936.18      7094959.67
      2311144.39      7094860.09      2311323.03      7094907.86
      2311565.62      7094773.74      2311479.89      7094470.34
      2311725.54      7094208.51      2311679.00      7094010.00

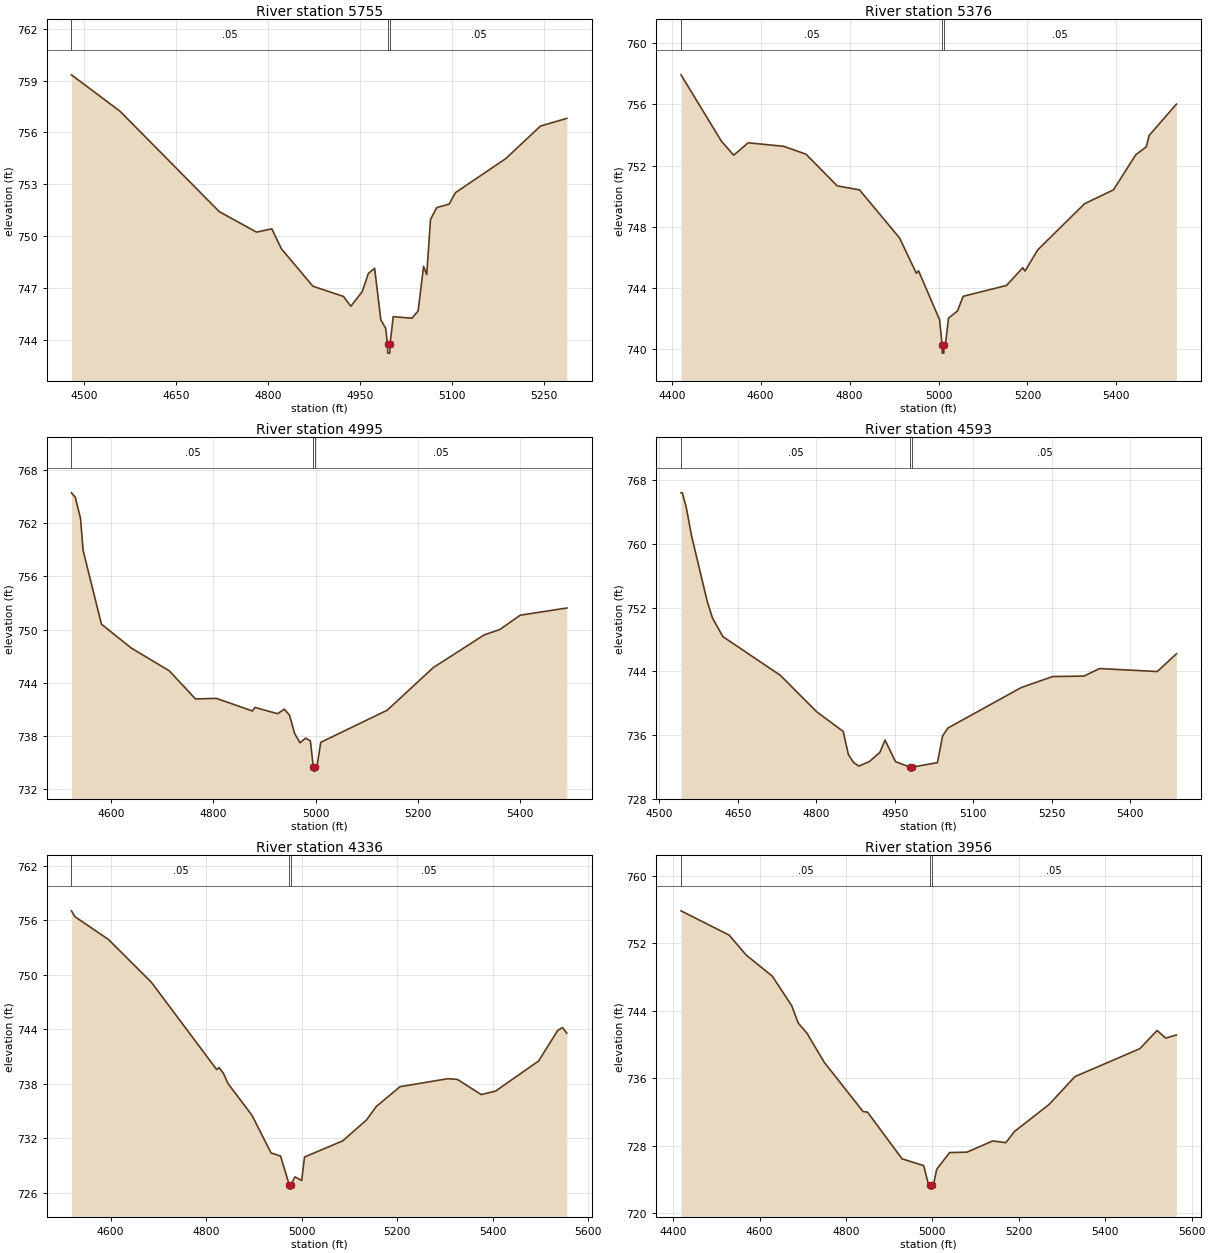
Type RM Length L Ch R = 1,5755,379,379,379
BEGIN DESCRIPTION:
MDW T 050 12.0
END DESCRIPTION:
XS GIS Cut Line= 2
      2311916.77      7098266.88      2311119.74      7098138.52
#Sta/Elev= 30
  4480.0  759.33  4559.3  757.22  4720.8  751.42  4781.6  750.23  4806.6  750.42
  4822.1  749.27  4873.5  747.10  4923.4  746.51  4935.3  745.94  4953.8  746.78
  4963.9  747.84  4974.1  748.14  4984.2  745.16  4992.1  744.67  4995.2  743.73
  4995.4  743.23  4998.9  743.23  4999.2  743.73  5004.4  745.34  5034.8  745.25
  5045.0  745.67  5053.9  748.25  5059.0  747.77  5065.2  750.97  5075.3  751.65
  5095.6  751.85  5105.7  752.51  5187.7  754.48  5244.5  756.37  5287.3  756.81
#Mann=3,-1,0
  4480.0    0.05       0  4995.2   0.033       0  4999.2    0.05       0
Bank Sta=4995.2,4999.2
Exp/Cntr=0.3,0.1

Type RM Length L Ch R = 1,5376,381,381,381
BEGIN DESCRIPTION:
MDW T 050 11.0
END DESCRIPTION:
XS GIS Cut Line= 3
      2312159.92      7097889.12      2311568.54      7097917.93
      2311047.90      7097880.00
#Sta/Elev= 30
  4420.9  757.94  4511.9  753.59  4539.4  752.68  4572.0  753.49  4652.1  753.26
  4702.2  752.74  4772.2  750.67  4822.3  750.41  4912.4  747.26  4950.1  744.95
  4955.1  745.11  5002.5  741.90  5008.2  740.22  5008.5  739.72  5012.0  739.72
  5012.2  740.22  5015.3  740.22  5022.5  742.01  5042.6  742.48  5055.5  743.44
  5152.9  744.15  5189.5  745.31  5194.5  745.09  5223.1  746.48  5328.4  749.50
  5393.5  750.41  5443.7  752.71  5467.4  753.23  5473.7  753.97  5535.0  756.02
#Mann=3,-1,0
  4420.9    0.05       0  5008.2   0.033       0  5012.2    0.05       0
Bank Sta=5008.2,5012.2
Exp/Cntr=0.3,0.1

Type RM Length L Ch R = 1,4995,402,402,402
BEGIN DESCRIPTION:
MDW T 050 10.0
END DESCRIPTION:
XS GIS Cut Line= 3
      2311946.42      7097510.20      2311479.00      7097610.00
      2310988.07      7097636.51
#Sta/Elev= 30
  4522.1  765.43  4529.7  764.93  4539.9  762.53  4545.0  758.92  4580.8  750.61
  4639.0  747.92  4713.7  745.34  4764.9  742.17  4805.8  742.23  4876.3  740.81
  4881.4  741.21  4925.8  740.50  4938.7  741.01  4948.9  740.34  4959.1  738.25
  4969.4  737.22  4980.4  737.74  4989.8  737.44  4995.5  734.52  4995.7  734.02
  4999.2  734.02  4999.5  734.52  5002.6  734.52  5010.1  737.27  5140.3  740.90
  5230.4  745.71  5330.5  749.41  5360.6  750.00  5400.6  751.62  5491.7  752.43
#Mann=3,-1,0
  4522.1    0.05       0  4995.5   0.033       0  4999.5    0.05       0
Bank Sta=4995.5,4999.5
Exp/Cntr=0.3,0.1

Type RM Length L Ch R = 1,4593,257,257,257
BEGIN DESCRIPTION:
MDW T 050 9.0
END DESCRIPTION:
XS GIS Cut Line= 3
      2311879.00      7097260.00      2311420.55      7097266.18
      2310932.41      7097282.29
#Sta/Elev= 30
  4541.5  766.42  4544.0  766.42  4551.5  764.60  4561.5  761.07  4591.5  752.81
  4601.5  750.72  4621.5  748.36  4731.5  743.49  4801.5  738.88  4851.5  736.45
  4861.5  733.53  4871.5  732.54  4881.5  732.09  4901.5  732.66  4921.5  733.80
  4931.5  735.36  4951.5  732.65  4979.5  731.96  4979.8  731.46  4983.3  731.46
  4983.5  731.96  5031.6  732.53  5041.6  735.89  5051.6  736.87  5191.6  741.95
  5251.7  743.34  5311.7  743.40  5341.7  744.35  5451.8  743.97  5488.4  746.19
#Mann=3,-1,0
  4541.5    0.05       0  4979.5   0.033       0  4983.5    0.05       0
Bank Sta=4979.5,4983.5
Exp/Cntr=0.3,0.1

Type RM Length L Ch R = 1,4336,380,380,380
BEGIN DESCRIPTION:
MDW T 050 8.0
END DESCRIPTION:
XS GIS Cut Line= 3
      2311946.36      7097001.10      2311464.96      7097023.04
      2310909.97      7097020.63
#Sta/Elev= 30
  4518.1  757.05  4525.5  756.40  4595.5  753.90  4685.6  749.17  4822.1  739.56
  4827.1  739.77  4835.8  739.18  4845.8  738.02  4895.9  734.53  4935.9  730.37
  4955.9  730.02  4973.9  726.88  4974.2  726.38  4977.7  726.38  4977.9  726.88
  4985.9  727.73  5000.0  727.34  5006.0  729.92  5086.0  731.70  5136.0  734.02
  5156.0  735.48  5206.0  737.67  5306.0  738.55  5326.0  738.47  5376.0  736.80
  5406.0  737.19  5496.0  740.50  5536.0  743.87  5546.0  744.19  5555.0  743.56
#Mann=3,-1,0
  4518.1    0.05       0  4973.9   0.033       0  4977.9    0.05       0
Bank Sta=4973.9,4977.9
Exp/Cntr=0.3,0.1

Type RM Length L Ch R = 1,3956,376,376,376
BEGIN DESCRIPTION:
MDW T 050 7.0
END DESCRIPTION:
XS GIS Cut Line= 3
      2312010.16      7096745.89      2311428.89      7096721.12
      2310864.31      7096709.43
#Sta/Elev= 30
  4418.2  755.82  4529.5  752.95  4569.5  750.56  4629.6  748.08  4674.3  744.59
  4689.6  742.52  4709.6  741.34  4749.7  737.88  4839.7  732.04  4849.8  731.98
  4929.8  726.45  4979.9  725.64  4989.9  723.60  4995.4  723.36  4995.7  722.86
  4999.2  722.86  4999.4  723.36  5002.4  723.36  5009.9  725.20  5039.9  727.19
  5079.9  727.24  5139.9  728.57  5169.9  728.36  5189.9  729.68  5269.9  732.88
  5330.0  736.19  5480.0  739.49  5520.0  741.65  5540.0  740.75  5564.7  741.12
#Mann=3,-1,0
  4418.2    0.05       0  4995.4   0.033       0  4999.4    0.05       0
Bank Sta=4995.4,4999.4
Exp/Cntr=0.3,0.1

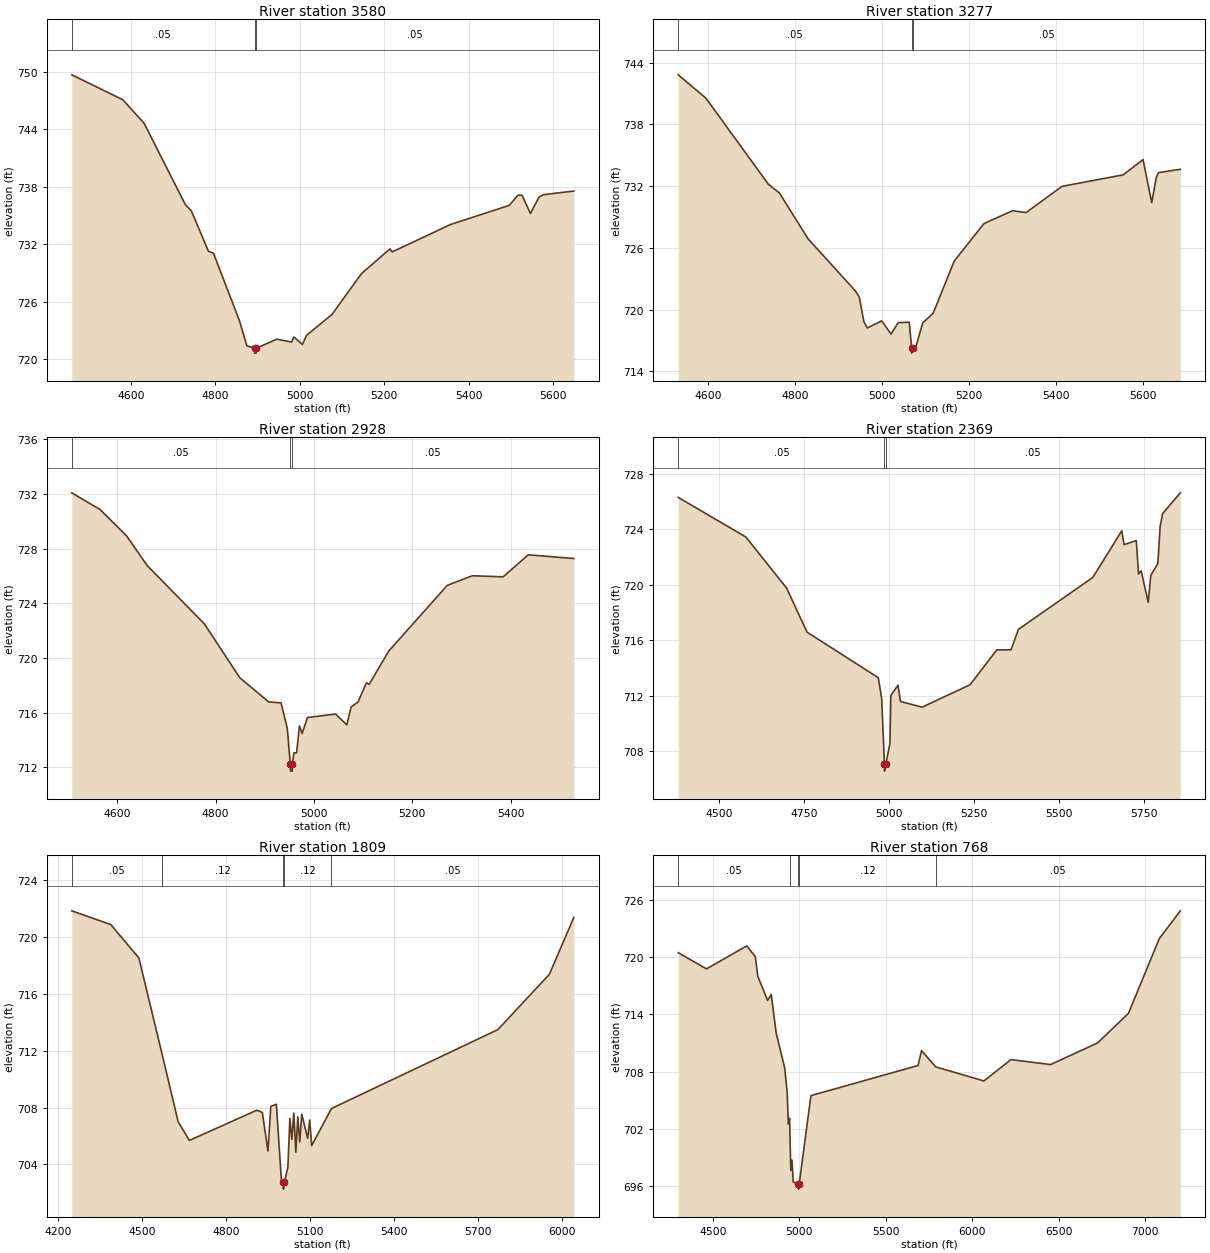
Type RM Length L Ch R = 1,3580,303,303,303
BEGIN DESCRIPTION:
MDW T 050 6.0
END DESCRIPTION:
XS GIS Cut Line= 3
      2311968.50      7096488.07      2311435.03      7096401.83
      2310786.25      7096381.30
#Sta/Elev= 30
  4459.6  749.68  4580.7  747.08  4631.3  744.61  4728.5  736.16  4742.7  735.51
  4783.3  731.29  4795.3  731.08  4857.0  724.03  4874.4  721.43  4892.7  721.16
  4892.9  720.66  4896.4  720.66  4896.7  721.16  4945.3  722.12  4980.5  721.81
  4985.8  722.34  5006.0  721.56  5016.0  722.52  5076.1  724.69  5146.1  728.96
  5213.6  731.53  5218.6  731.21  5356.2  734.06  5496.3  736.07  5516.3  737.12
  5526.3  737.13  5546.3  735.22  5566.3  736.91  5576.3  737.18  5649.1  737.56
#Mann=3,-1,0
  4459.6    0.05       0  4892.7   0.033       0  4896.7    0.05       0
Bank Sta=4892.7,4896.7
Exp/Cntr=0.3,0.1

Type RM Length L Ch R = 1,3277,349,349,349
BEGIN DESCRIPTION:
MDW T 050 5.0
END DESCRIPTION:
XS GIS Cut Line= 3
      2311927.33      7096252.74      2311408.50      7096094.55
      2310815.42      7096247.53
#Sta/Elev= 30
  4531.3  742.83  4594.8  740.57  4738.6  732.19  4764.2  731.33  4829.8  726.89
  4938.8  721.81  4947.7  721.23  4958.2  718.83  4966.4  718.21  4999.2  718.90
  5020.9  717.61  5037.2  718.72  5062.7  718.77  5068.1  716.26  5068.3  715.76
  5072.1  716.26  5076.9  716.26  5093.8  718.70  5117.6  719.63  5166.1  724.71
  5234.5  728.36  5300.4  729.61  5331.4  729.43  5414.0  731.98  5554.7  733.10
  5600.5  734.58  5620.5  730.40  5630.9  732.84  5636.0  733.32  5686.2  733.64
#Mann=3,-1,0
  4531.3    0.05       0  5068.1   0.033       0  5072.1    0.05       0
Bank Sta=5068.1,5072.1
Exp/Cntr=0.3,0.1

Type RM Length L Ch R = 1,2928,559,559,559
BEGIN DESCRIPTION:
MDW T 050 4.0
END DESCRIPTION:
XS GIS Cut Line= 3
      2311945.59      7095882.96      2311513.92      7095750.14
      2311000.31      7095994.92
#Sta/Elev= 30
  4507.8  732.07  4565.3  730.85  4619.3  728.92  4661.2  726.75  4777.2  722.50
  4849.5  718.55  4908.0  716.79  4933.2  716.72  4945.9  714.87  4952.1  712.23
  4952.4  711.73  4955.9  711.73  4956.1  712.23  4959.4  713.07  4964.9  713.07
  4970.6  715.04  4976.1  714.48  4987.0  715.65  5044.2  715.90  5066.9  715.11
  5075.7  716.42  5089.6  716.78  5106.8  718.19  5112.3  718.07  5152.2  720.51
  5271.2  725.31  5322.2  726.01  5384.7  725.93  5435.7  727.54  5528.4  727.27
#Mann=3,-1,0
  4507.8    0.05       0  4952.1   0.033       0  4956.1    0.05       0
Bank Sta=4952.1,4956.1
Exp/Cntr=0.3,0.1

Type RM Length L Ch R = 1,2369,560,560,560
BEGIN DESCRIPTION:
MDW T 050 3.0
END DESCRIPTION:
XS GIS Cut Line= 3
      2311948.19      7095435.04      2311327.45      7095420.73
      2310760.80      7096065.12
#Sta/Elev= 30
  4379.1  726.31  4578.3  723.45  4698.4  719.76  4758.4  716.58  4968.4  713.29
  4978.4  711.79  4986.5  707.04  4986.7  706.54  4990.5  707.04  5002.6  708.53
  5005.5  712.01  5026.3  712.74  5033.9  711.57  5097.5  711.16  5238.9  712.78
  5317.6  715.30  5359.4  715.30  5381.2  716.78  5600.4  720.53  5685.8  723.90
  5692.4  722.90  5728.4  723.19  5735.1  720.78  5742.7  721.01  5763.6  718.73
  5771.1  720.67  5792.0  721.54  5798.7  724.22  5806.2  725.15  5858.1  726.64
#Mann=3,-1,0
  4379.1    0.05       0  4986.5   0.033       0  4990.5    0.05       0
Bank Sta=4986.5,4990.5
Exp/Cntr=0.3,0.1

Type RM Length L Ch R = 1,1809,1041,1041,1041
BEGIN DESCRIPTION:
MDW T 050 2.0
END DESCRIPTION:
XS GIS Cut Line= 3
      2311758.13      7095049.62      2311008.73      7095090.30
      2310273.82      7095828.15
#Sta/Elev= 30
  4249.5  721.86  4388.8  720.89  4489.0  718.54  4572.6  711.70  4629.2  707.00
  4669.2  705.68  4909.6  707.81  4929.6  707.65  4949.7  704.94  4959.7  708.08
  4979.7  708.23  4997.4  702.95  5004.7  702.75  5004.9  702.25  5008.7  702.75
  5020.8  703.81  5027.9  707.23  5035.0  705.75  5042.0  707.61  5049.1  704.86
  5056.2  707.35  5063.2  705.58  5070.3  707.54  5091.5  705.83  5098.6  707.12
  5105.7  705.32  5176.4  707.93  5770.3  713.49  5954.2  717.39  6041.4  721.40
#Mann=5,-1,0
  4249.5    0.05       0  4572.6    0.12       0  5004.7    0.07       0
  5008.7    0.12       0  5176.4    0.05       0
Bank Sta=5004.7,5008.7
Exp/Cntr=0.3,0.1

Type RM Length L Ch R = 1,768,0,0,0
BEGIN DESCRIPTION:
MDW T 050 1.0
END DESCRIPTION:
XS GIS Cut Line= 4
      2312020.93      7095129.14      2311528.77      7094630.10
      2310493.14      7094864.37      2310080.82      7095929.88
#Sta/Elev= 30
  4299.1  720.47  4462.5  718.77  4695.8  721.18  4745.4  720.04  4759.5  717.99
  4816.1  715.46  4837.3  716.08  4865.5  712.07  4915.1  708.38  4929.2  705.87
  4936.3  702.49  4943.4  703.11  4946.3  700.84  4950.4  697.64  4957.5  698.71
  4964.5  696.40  4994.6  696.16  4994.8  695.66  4998.6  696.16  5067.0  705.47
  5686.7  708.63  5707.2  710.20  5788.7  708.49  6067.8  707.01  6224.5  709.25
  6453.8  708.73  6725.9  711.00  6904.2  714.10  7082.9  721.95  7204.3  724.86
#Mann=5,-1,0
  4299.1    0.05       0  4946.3    0.12       0  4994.6    0.07       0
  4998.6    0.12       0  5788.7    0.05       0
Bank Sta=4994.6,4998.6
Exp/Cntr=0.3,0.1

Chan Stop Cuts=-1