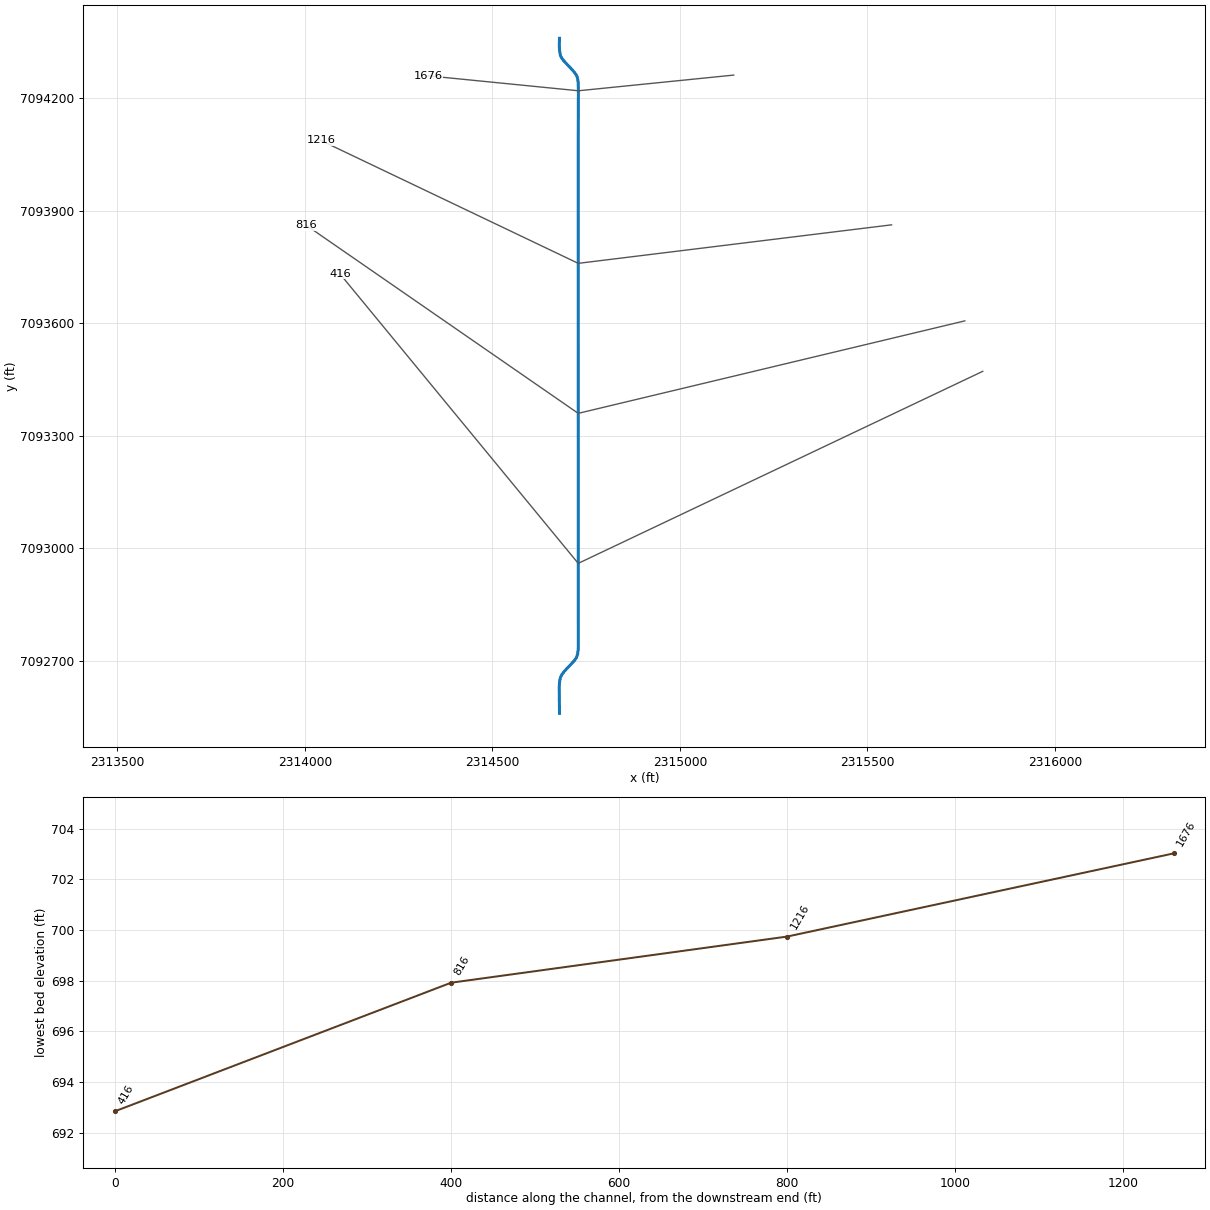
--- MDW T 052.prj (project) ---

Proj Title=MDW T 052 Base Level Engineering
Current Plan=p01
Default Exp/Contr=0.3,0.1
English Units
Geom File=g01
Flow File=f01
Plan File=p01
BEGIN DESCRIPTION:
MDW T 052
END DESCRIPTION:

--- MDW T 052.p01 (plan) ---

Plan Title=Multiple Run
Short Identifier=Multiple
Geom File=g01
Flow File=f01
Subcritical Flow
K Sum by GR= 0
Std Step Tol= 0.01
Critical Tol= 0.01
Num of Std Step Trials= 20
Max Error Tol= 0.3
Flow Tol Ratio= 0.001
Split Flow NTrial= 30
Split Flow Tol= 0.02
Split Flow Ratio= 0.02
Log Output Level= 0
Friction Slope Method= 1
Unsteady Friction Slope Method= 2
Unsteady Bridges Friction Slope Method= 1
Parabolic Critical Depth
Global Vel Dist=  1 , 1 , 1
Global Log Level= 0
CheckData=True
Encroach Param= -1, 0, 0, 0
BEGIN DESCRIPTION:
Multiple Run
END DESCRIPTION:

--- MDW T 052.f01 (steady flow) ---

Flow Title=Multiple
Number of Profiles=7
Profile Names=10-year,25-year,50-year,1pct_min,100-year,1pct_plu,500-year
River Rch & RM= MDW T 052,Reach-1,1676
     500     680     828     502    1001    1997    1462
Boundary for River Rch & Prof#=MDW T 052,Reach-1,1
Up Type=0
Dn Type=3
Dn Slope=0.005
Boundary for River Rch & Prof#=MDW T 052,Reach-1,2
Up Type=0
Dn Type=3
Dn Slope=0.005
Boundary for River Rch & Prof#=MDW T 052,Reach-1,3
Up Type=0
Dn Type=3
Dn Slope=0.005
Boundary for River Rch & Prof#=MDW T 052,Reach-1,4
Up Type=0
Dn Type=3
Dn Slope=0.005
Boundary for River Rch & Prof#=MDW T 052,Reach-1,5
Up Type=0
Dn Type=3
Dn Slope=0.005
Boundary for River Rch & Prof#=MDW T 052,Reach-1,6
Up Type=0
Dn Type=3
Dn Slope=0.005
Boundary for River Rch & Prof#=MDW T 052,Reach-1,7
Up Type=0
Dn Type=3
Dn Slope=0.005

--- MDW T 052.g01 (geometry) ---

Geom Title=Existing Conditions

River Reach=MDW T 052,Reach-1
Reach XY= 30
      2314679.00      7094360.00      2314678.59      7094341.08
      2314679.12      7094328.20      2314680.99      7094316.27
      2314682.65      7094311.51      2314684.74      7094307.66
      2314690.06      7094300.44      2314715.52      7094273.27
      2314721.11      7094266.16      2314723.47      7094262.42
      2314725.40      7094258.51      2314726.88      7094254.12
      2314727.88      7094249.54      2314728.98      7094239.99
      2314729.46      7094220.19      2314729.00      7094075.00
      2314729.21      7092734.91      2314727.80      7092720.50
      2314725.25      7092711.55      2314723.29      7092707.65
      2314720.90      7092703.93      2314715.26      7092696.83
      2314695.94      7092676.55      2314689.86      7092669.64
      2314684.68      7092662.36      2314682.67      7092658.48
      2314681.10      7092654.13      2314679.29      7092644.88
      2314678.37      7092630.26      2314679.00      7092560.00

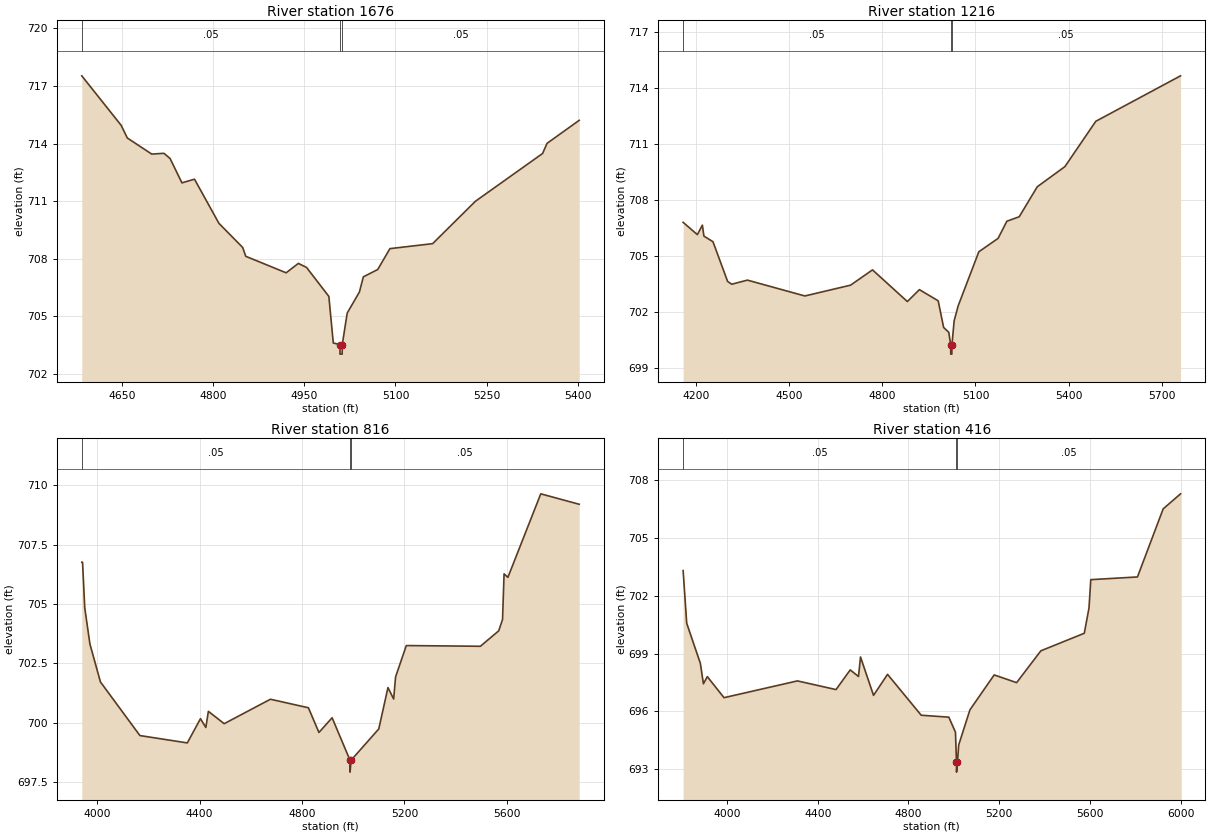
Type RM Length L Ch R = 1,1676,460,460,460
BEGIN DESCRIPTION:
MDW T 052 4.0
END DESCRIPTION:
XS GIS Cut Line= 3
      2315143.55      7094262.00      2314729.46      7094220.19
      2314329.03      7094260.00
#Sta/Elev= 30
  4583.8  717.53  4648.6  714.95  4658.7  714.29  4698.9  713.45  4719.0  713.49
  4729.1  713.22  4748.6  711.95  4769.3  712.14  4809.5  709.84  4848.6  708.58
  4853.7  708.12  4920.1  707.26  4940.2  707.75  4953.7  707.54  4990.4  706.03
  4997.7  703.60  5008.5  703.52  5008.8  703.02  5012.3  703.02  5012.5  703.52
  5020.6  705.16  5040.7  706.26  5047.2  707.05  5070.8  707.43  5090.9  708.52
  5161.2  708.78  5231.6  710.99  5342.1  713.48  5349.5  714.01  5402.4  715.21
#Mann=3,-1,0
  4583.8    0.05       0  5008.5   0.033       0  5012.5    0.05       0
Bank Sta=5008.5,5012.5
Exp/Cntr=0.3,0.1

Type RM Length L Ch R = 1,1216,400,400,400
BEGIN DESCRIPTION:
MDW T 052 3.0
END DESCRIPTION:
XS GIS Cut Line= 3
      2315564.52      7093862.69      2314729.00      7093760.00
      2314042.51      7094087.71
#Sta/Elev= 30
  4158.2  706.81  4204.1  706.15  4220.2  706.66  4225.2  706.07  4254.4  705.77
  4301.5  703.64  4314.9  703.49  4365.3  703.71  4550.4  702.86  4697.7  703.44
  4768.3  704.26  4880.6  702.56  4919.4  703.20  4979.9  702.60  4997.5  701.17
  5014.1  700.91  5020.2  700.24  5020.4  699.74  5023.9  699.74  5024.2  700.24
  5031.3  701.52  5044.3  702.33  5110.8  705.23  5172.9  705.95  5201.2  706.87
  5241.0  707.11  5299.2  708.72  5388.2  709.80  5487.6  712.23  5760.7  714.67
#Mann=3,-1,0
  4158.2    0.05       0  5020.2   0.033       0  5024.2    0.05       0
Bank Sta=5020.2,5024.2
Exp/Cntr=0.3,0.1

Type RM Length L Ch R = 1,816,400,400,400
BEGIN DESCRIPTION:
MDW T 052 2.0
END DESCRIPTION:
XS GIS Cut Line= 3
      2315759.82      7093606.61      2314729.00      7093360.00
      2314002.98      7093862.04
#Sta/Elev= 30
  3940.1  706.76  3943.1  706.76  3951.7  704.84  3971.8  703.32  4012.9  701.72
  4167.1  699.46  4352.2  699.15  4403.6  700.17  4424.6  699.80  4434.5  700.48
  4496.2  699.96  4676.9  700.99  4825.2  700.63  4866.3  699.59  4917.7  700.21
  4987.7  698.42  4988.0  697.92  4991.7  698.42  5100.0  699.74  5135.8  701.48
  5158.1  701.00  5165.6  701.93  5207.5  703.25  5496.7  703.22  5568.4  703.87
  5583.3  704.35  5589.3  706.27  5604.2  706.12  5732.6  709.64  5882.7  709.20
#Mann=3,-1,0
  3940.1    0.05       0  4987.7   0.033       0  4991.7    0.05       0
Bank Sta=4987.7,4991.7
Exp/Cntr=0.3,0.1

Type RM Length L Ch R = 1,416,0,0,0
BEGIN DESCRIPTION:
MDW T 052 1.0
END DESCRIPTION:
XS GIS Cut Line= 3
      2315807.62      7093472.08      2314729.00      7092960.00
      2314093.57      7093732.02
#Sta/Elev= 30
  3806.0  703.30  3821.8  700.57  3882.0  698.49  3895.5  697.43  3912.7  697.80
  3986.4  696.71  4310.2  697.58  4480.3  697.13  4543.0  698.15  4579.4  697.81
  4588.4  698.82  4645.8  696.83  4707.6  697.92  4856.1  695.80  4977.9  695.70
  5007.2  694.92  5011.7  693.35  5011.9  692.85  5015.7  693.35  5021.5  694.26
  5071.0  696.08  5177.9  697.89  5276.9  697.49  5383.8  699.14  5575.4  700.05
  5596.2  701.37  5604.0  702.83  5809.9  702.97  5923.3  706.50  5999.9  707.28
#Mann=3,-1,0
  3806.0    0.05       0  5011.7   0.033       0  5015.7    0.05       0
Bank Sta=5011.7,5015.7
Exp/Cntr=0.3,0.1

Chan Stop Cuts=-1