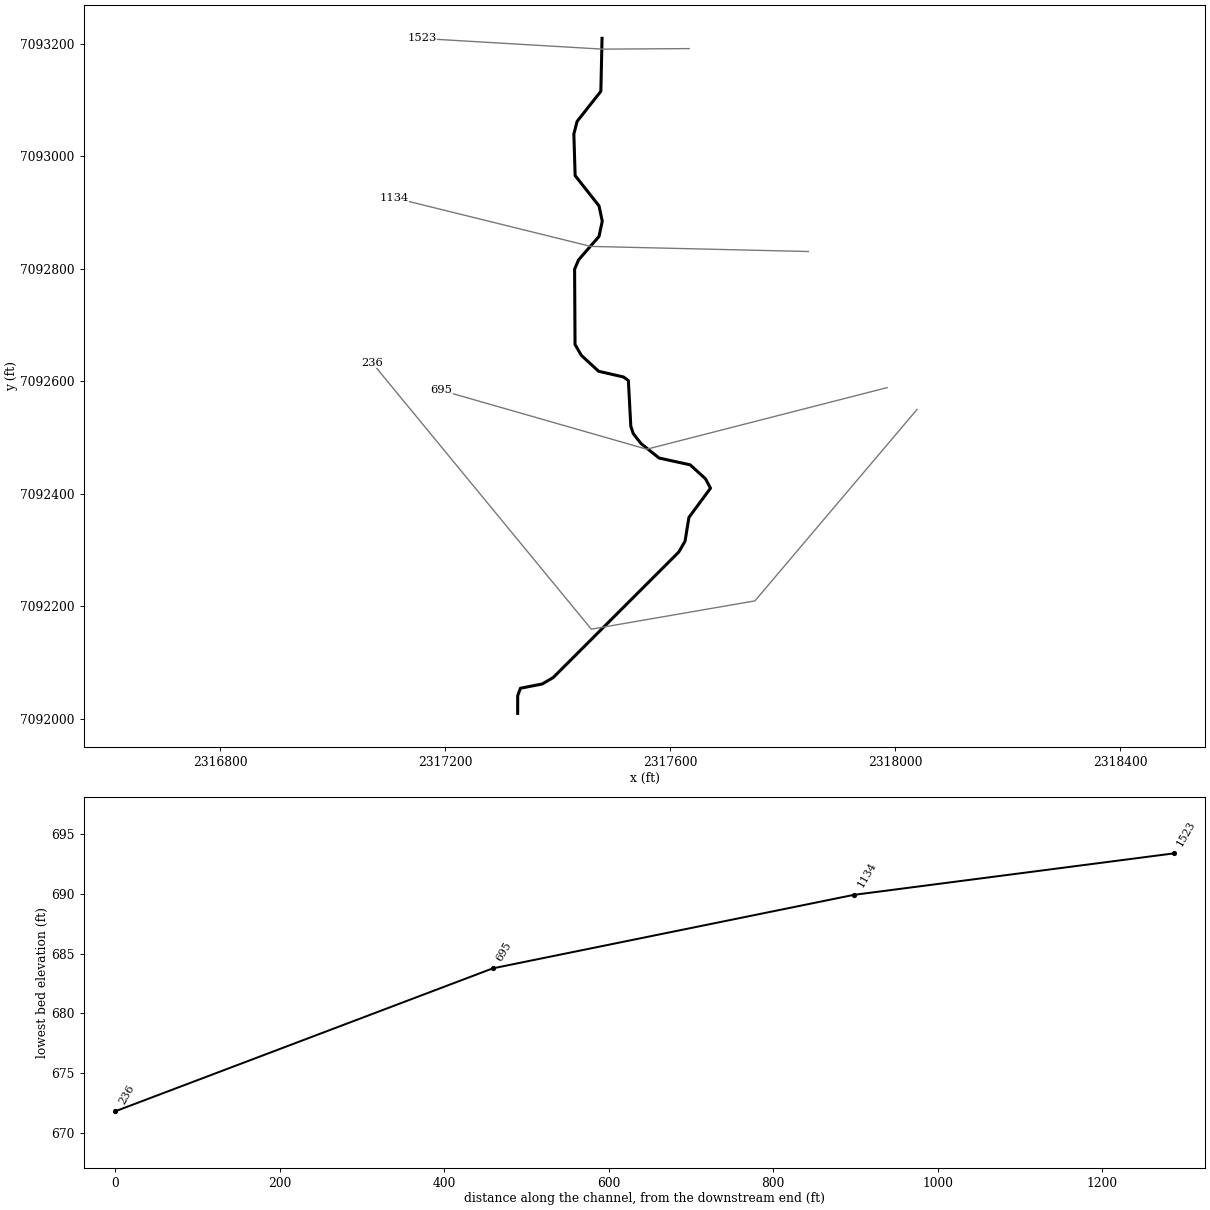
--- MDW T 053.prj (project) ---

Proj Title=MDW T 053 Base Level Engineering
Current Plan=p01
Default Exp/Contr=0.3,0.1
English Units
Geom File=g01
Flow File=f01
Plan File=p01
BEGIN DESCRIPTION:
MDW T 053
END DESCRIPTION:

--- MDW T 053.p01 (plan) ---

Plan Title=Multiple Run
Short Identifier=Multiple
Geom File=g01
Flow File=f01
Subcritical Flow
K Sum by GR= 0
Std Step Tol= 0.01
Critical Tol= 0.01
Num of Std Step Trials= 20
Max Error Tol= 0.3
Flow Tol Ratio= 0.001
Split Flow NTrial= 30
Split Flow Tol= 0.02
Split Flow Ratio= 0.02
Log Output Level= 0
Friction Slope Method= 1
Unsteady Friction Slope Method= 2
Unsteady Bridges Friction Slope Method= 1
Parabolic Critical Depth
Global Vel Dist=  1 , 1 , 1
Global Log Level= 0
CheckData=True
Encroach Param= -1, 0, 0, 0
BEGIN DESCRIPTION:
Multiple Run
END DESCRIPTION:

--- MDW T 053.f01 (steady flow) ---

Flow Title=Multiple
Number of Profiles=7
Profile Names=10-year,25-year,50-year,1pct_min,100-year,1pct_plu,500-year
River Rch & RM= MDW T 053,Reach-1,1523
     460     624     757     457     912    1820    1326
Boundary for River Rch & Prof#=MDW T 053,Reach-1,1
Up Type=0
Dn Type=3
Dn Slope=0.005
Boundary for River Rch & Prof#=MDW T 053,Reach-1,2
Up Type=0
Dn Type=3
Dn Slope=0.005
Boundary for River Rch & Prof#=MDW T 053,Reach-1,3
Up Type=0
Dn Type=3
Dn Slope=0.005
Boundary for River Rch & Prof#=MDW T 053,Reach-1,4
Up Type=0
Dn Type=3
Dn Slope=0.005
Boundary for River Rch & Prof#=MDW T 053,Reach-1,5
Up Type=0
Dn Type=3
Dn Slope=0.005
Boundary for River Rch & Prof#=MDW T 053,Reach-1,6
Up Type=0
Dn Type=3
Dn Slope=0.005
Boundary for River Rch & Prof#=MDW T 053,Reach-1,7
Up Type=0
Dn Type=3
Dn Slope=0.005

--- MDW T 053.g01 (geometry) ---

Geom Title=Existing Conditions

River Reach=MDW T 053,Reach-1
Reach XY= 30
      2317479.00      7093210.00      2317476.89      7093115.87
      2317434.64      7093062.32      2317428.90      7093039.90
      2317431.19      7092965.97      2317473.62      7092912.18
      2317479.40      7092885.00      2317473.62      7092857.82
      2317437.18      7092816.07      2317430.23      7092799.50
      2317431.00      7092665.69      2317442.29      7092646.36
      2317472.96      7092618.17      2317517.21      7092607.97
      2317525.81      7092601.64      2317530.15      7092520.44
      2317534.45      7092507.38      2317548.48      7092489.48
      2317580.47      7092463.88      2317635.67      7092451.84
      2317662.87      7092427.08      2317671.80      7092410.30
      2317633.47      7092358.36      2317626.55      7092316.05
      2317615.40      7092296.79      2317392.08      7092073.60
      2317372.79      7092062.30      2317333.92      7092054.67
      2317329.07      7092041.54      2317329.00      7092010.00

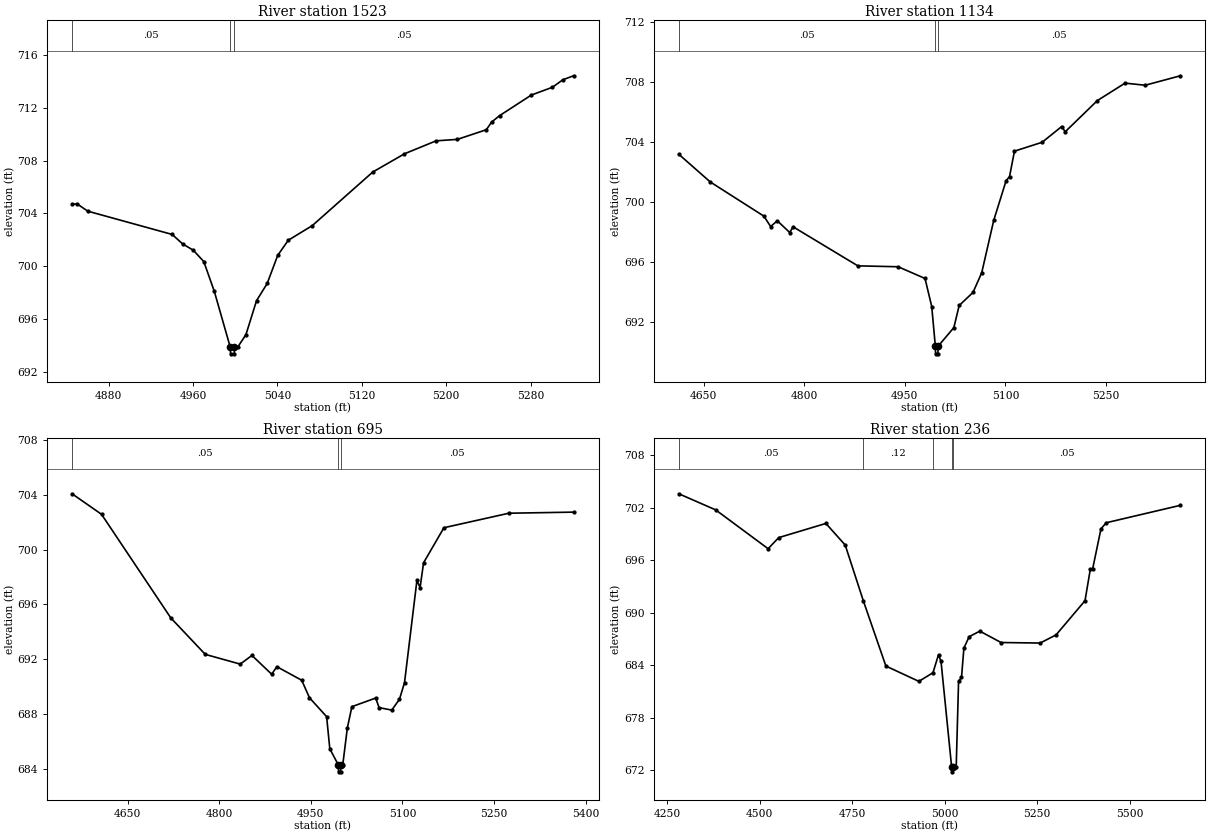
Type RM Length L Ch R = 1,1523,389,389,389
BEGIN DESCRIPTION:
MDW T 053 3.0
END DESCRIPTION:
XS GIS Cut Line= 3
      2317633.90      7093191.76      2317479.72      7093190.79
      2317158.96      7093209.73
#Sta/Elev= 30
  4845.3  704.71  4850.3  704.71  4860.2  704.17  4940.2  702.41  4950.2  701.69
  4960.2  701.22  4970.2  700.36  4980.2  698.10  4995.3  693.88  4995.6  693.38
  4999.1  693.38  4999.3  693.88  5002.3  693.88  5010.2  694.84  5020.2  697.40
  5030.3  698.70  5040.3  700.83  5050.3  701.97  5073.1  703.08  5130.4  707.13
  5160.5  708.51  5190.5  709.49  5210.6  709.60  5238.1  710.33  5243.1  710.91
  5250.6  711.39  5280.7  712.95  5300.7  713.54  5310.7  714.11  5320.8  714.41
#Mann=3,-1,0
  4845.3    0.05       0  4995.3    0.04       0  4999.3    0.05       0
Bank Sta=4995.3,4999.3
Exp/Cntr=0.3,0.1

Type RM Length L Ch R = 1,1134,439,439,439
BEGIN DESCRIPTION:
MDW T 053 2.0
END DESCRIPTION:
XS GIS Cut Line= 3
      2317845.77      7092831.04      2317459.08      7092840.11
      2317108.99      7092926.54
#Sta/Elev= 30
  4613.2  703.20  4660.0  701.36  4740.0  699.08  4750.0  698.39  4760.0  698.77
  4778.5  697.99  4783.5  698.37  4880.0  695.77  4940.1  695.71  4980.1  694.93
  4990.1  693.06  4995.5  690.41  4995.8  689.91  4999.3  689.91  4999.5  690.41
  5023.1  691.66  5031.0  693.13  5051.6  694.00  5064.6  695.31  5082.5  698.80
  5100.9  701.44  5106.0  701.71  5113.4  703.41  5154.6  704.00  5183.8  705.05
  5189.0  704.70  5237.0  706.78  5278.2  707.94  5308.2  707.80  5360.6  708.43
#Mann=3,-1,0
  4613.2    0.05       0  4995.5    0.04       0  4999.5    0.05       0
Bank Sta=4995.5,4999.5
Exp/Cntr=0.3,0.1

Type RM Length L Ch R = 1,695,459,459,459
BEGIN DESCRIPTION:
MDW T 053 1.0
END DESCRIPTION:
XS GIS Cut Line= 3
      2317985.75      7092589.07      2317558.45      7092479.60
      2317192.76      7092584.37
#Sta/Elev= 30
  4558.9  704.07  4607.2  702.57  4720.7  695.00  4777.1  692.34  4834.3  691.63
  4853.6  692.26  4885.9  690.89  4894.4  691.44  4935.1  690.45  4947.8  689.17
  4975.9  687.79  4981.1  685.45  4995.1  684.26  4995.4  683.76  4998.9  683.76
  4999.1  684.26  5002.3  684.26  5009.8  686.96  5017.3  688.52  5056.3  689.15
  5061.8  688.45  5082.6  688.27  5095.2  689.06  5103.5  690.28  5123.8  697.74
  5129.0  697.22  5134.7  699.03  5168.0  701.59  5274.4  702.65  5380.4  702.73
#Mann=3,-1,0
  4558.9    0.05       0  4995.1   0.033       0  4999.1    0.05       0
Bank Sta=4995.1,4999.1
Exp/Cntr=0.3,0.1

Type RM Length L Ch R = 1,236,0,0,0
BEGIN DESCRIPTION:
MDW T 053 0.5
END DESCRIPTION:
XS GIS Cut Line= 4
      2318038.94      7092550.25      2317750.73      7092209.95
      2317459.95      7092159.69      2317070.18      7092633.54
#Sta/Elev= 30
  4282.0  703.58  4381.5  701.74  4523.2  697.30  4551.8  698.57  4679.2  700.19
  4731.4  697.72  4780.5  691.33  4841.3  683.89  4930.4  682.14  4968.5  683.13
  4983.4  685.19  4990.2  684.42  5019.0  672.30  5019.2  671.80  5023.0  672.30
  5031.2  672.35  5037.6  682.15  5045.5  682.59  5052.0  685.95  5066.3  687.25
  5095.0  687.88  5152.4  686.58  5257.9  686.52  5300.9  687.45  5379.1  691.36
  5393.5  694.97  5399.9  695.03  5422.2  699.57  5436.5  700.27  5636.6  702.26
#Mann=5,-1,0
  4282.0    0.05       0  4780.5    0.12       0  4968.5    0.05       0
  5019.0   0.033       0  5023.0    0.05       0
Bank Sta=5019,5023
Exp/Cntr=0.3,0.1

Chan Stop Cuts=-1