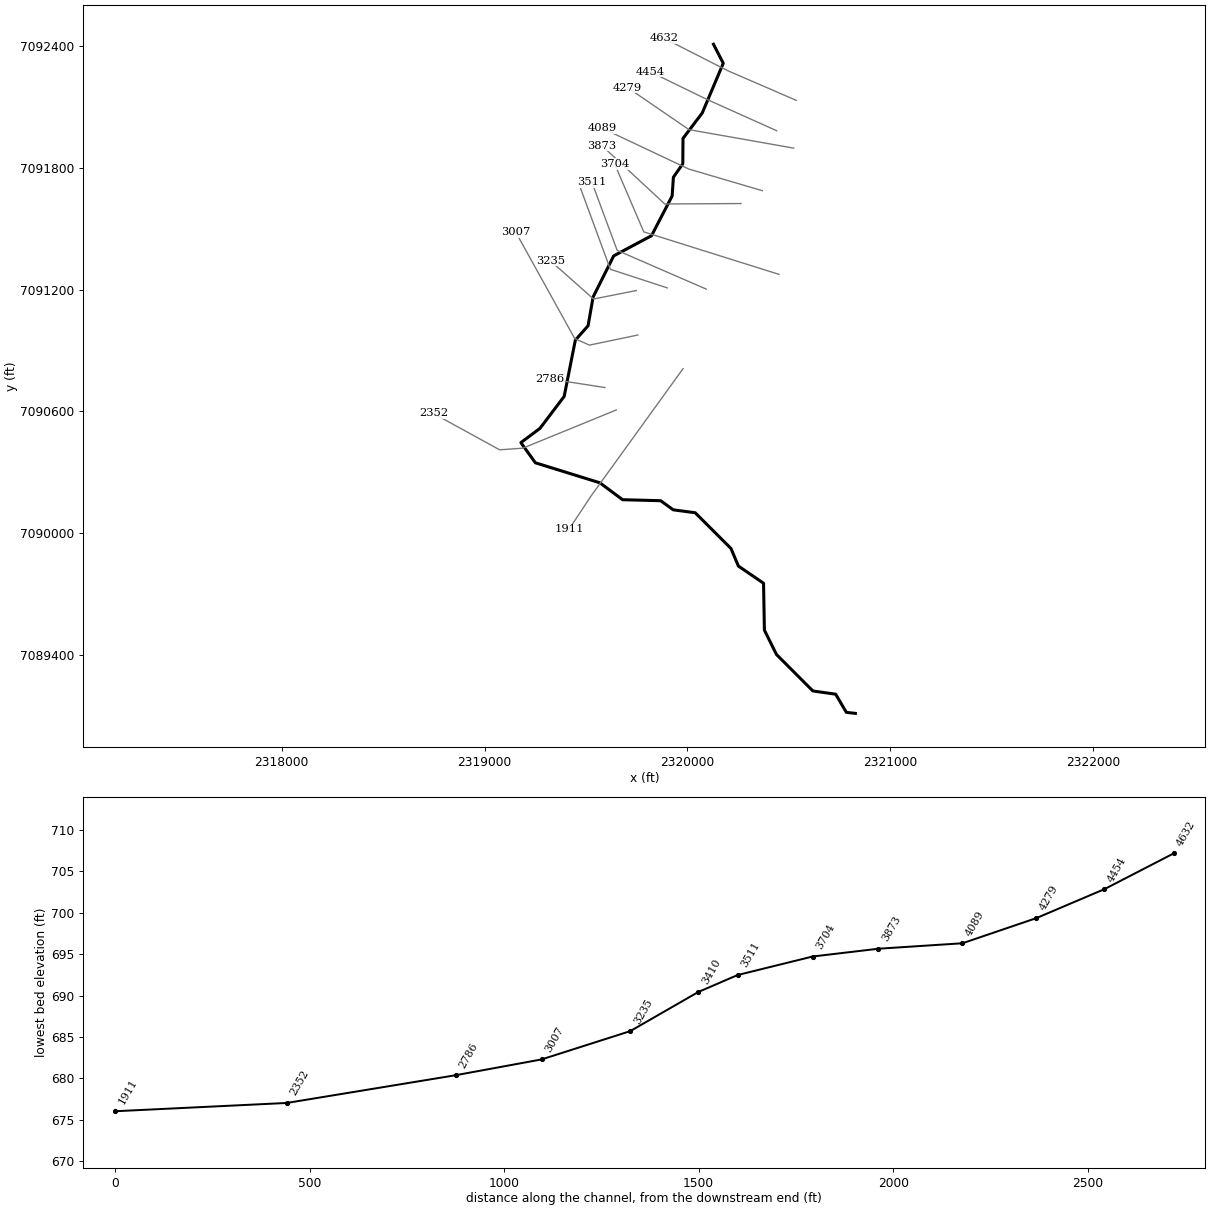
--- MDW T 054.prj (project) ---

Proj Title=MDW T 054 Base Level Engineering
Current Plan=p01
Default Exp/Contr=0.3,0.1
English Units
Geom File=g01
Flow File=f01
Plan File=p01
BEGIN DESCRIPTION:
MDW T 054
END DESCRIPTION:

--- MDW T 054.p01 (plan) ---

Plan Title=Multiple Run
Short Identifier=Multiple
Geom File=g01
Flow File=f01
Subcritical Flow
K Sum by GR= 0
Std Step Tol= 0.01
Critical Tol= 0.01
Num of Std Step Trials= 20
Max Error Tol= 0.3
Flow Tol Ratio= 0.001
Split Flow NTrial= 30
Split Flow Tol= 0.02
Split Flow Ratio= 0.02
Log Output Level= 0
Friction Slope Method= 1
Unsteady Friction Slope Method= 2
Unsteady Bridges Friction Slope Method= 1
Parabolic Critical Depth
Global Vel Dist=  1 , 1 , 1
Global Log Level= 0
CheckData=True
Encroach Param= -1, 0, 0, 0
BEGIN DESCRIPTION:
Multiple Run
END DESCRIPTION:

--- MDW T 054.f01 (steady flow) ---

Flow Title=Multiple
Number of Profiles=7
Profile Names=10-year,25-year,50-year,1pct_min,100-year,1pct_plu,500-year
River Rch & RM= MDW T 054,Reach-1,4632
     175     220     255     148     295     588     392
River Rch & RM= MDW T 054,Reach-1,2352
     234     302     355     208     415     829     568
Boundary for River Rch & Prof#=MDW T 054,Reach-1,1
Up Type=0
Dn Type=3
Dn Slope=0.005
Boundary for River Rch & Prof#=MDW T 054,Reach-1,2
Up Type=0
Dn Type=3
Dn Slope=0.005
Boundary for River Rch & Prof#=MDW T 054,Reach-1,3
Up Type=0
Dn Type=3
Dn Slope=0.005
Boundary for River Rch & Prof#=MDW T 054,Reach-1,4
Up Type=0
Dn Type=3
Dn Slope=0.005
Boundary for River Rch & Prof#=MDW T 054,Reach-1,5
Up Type=0
Dn Type=3
Dn Slope=0.005
Boundary for River Rch & Prof#=MDW T 054,Reach-1,6
Up Type=0
Dn Type=3
Dn Slope=0.005
Boundary for River Rch & Prof#=MDW T 054,Reach-1,7
Up Type=0
Dn Type=3
Dn Slope=0.005

--- MDW T 054.g01 (geometry) ---

Geom Title=Existing Conditions

River Reach=MDW T 054,Reach-1
Reach XY= 30
      2320129.00      7092410.00      2320177.26      7092316.05
      2320073.66      7092071.19      2319978.69      7091945.58
      2319977.78      7091820.50      2319931.36      7091754.02
      2319925.17      7091661.58      2319823.42      7091465.58
      2319637.02      7091366.34      2319535.36      7091163.24
      2319510.55      7091021.51      2319447.73      7090950.66
      2319392.68      7090673.10      2319273.35      7090515.64
      2319179.22      7090445.31      2319250.69      7090345.78
      2319568.88      7090247.09      2319680.57      7090163.78
      2319868.50      7090158.78      2319930.60      7090113.86
      2320038.79      7090099.48      2320215.37      7089923.21
      2320252.00      7089836.49      2320375.93      7089751.70
      2320380.20      7089520.50      2320439.76      7089400.32
      2320619.22      7089220.52      2320731.67      7089204.57
      2320784.35      7089114.96      2320829.00      7089110.00

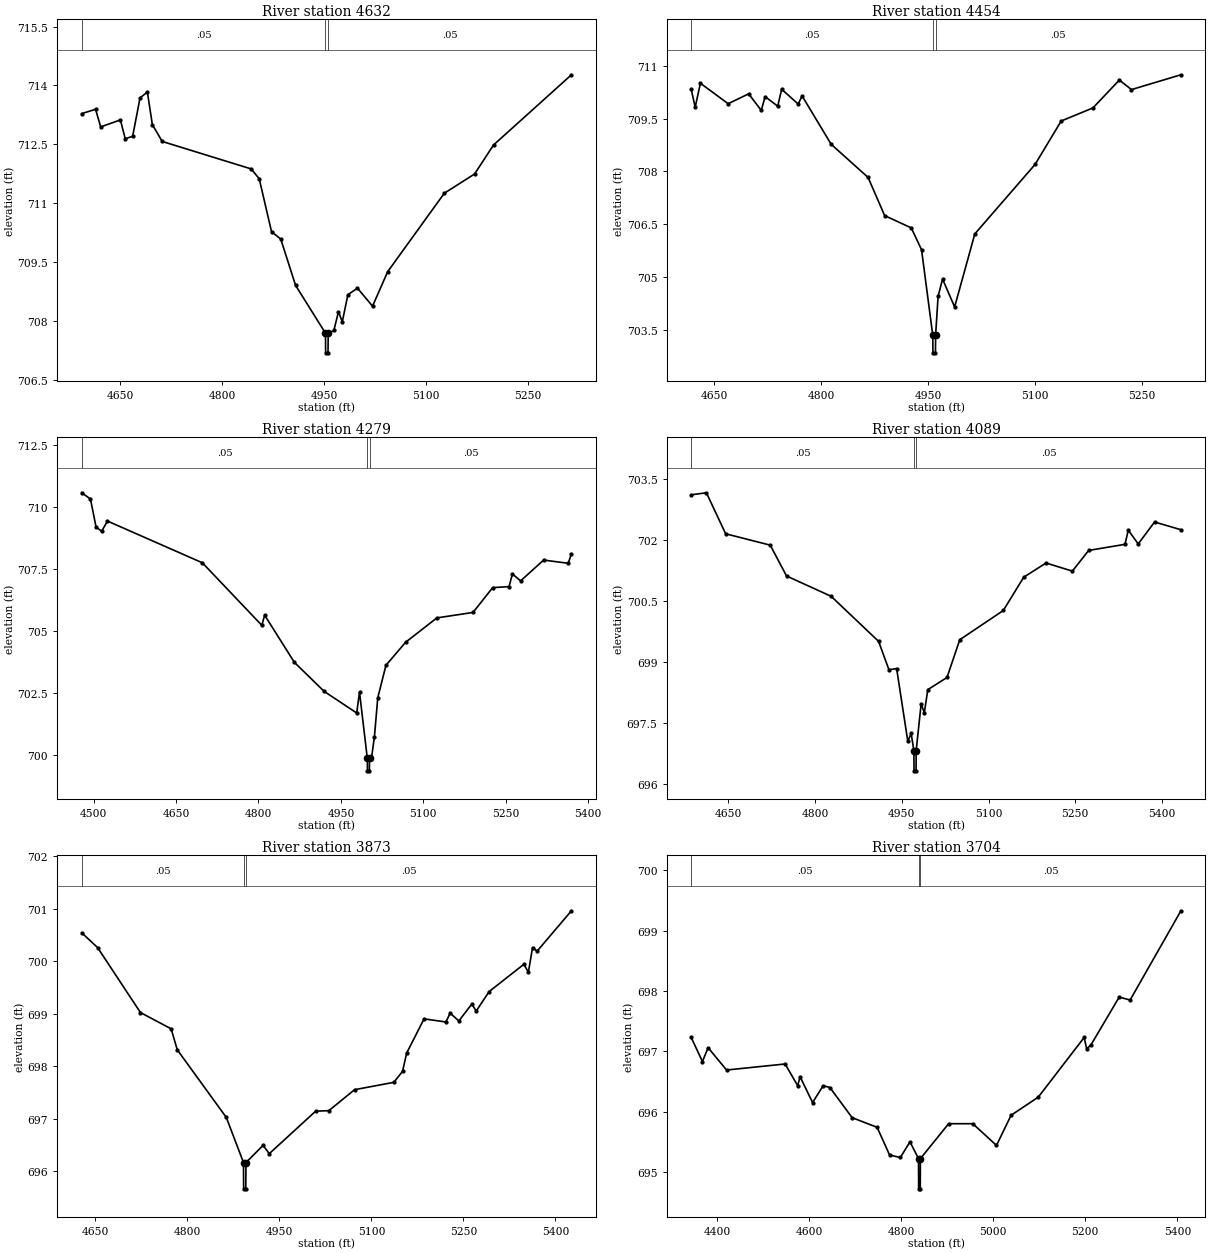
Type RM Length L Ch R = 1,4632,178,178,178
BEGIN DESCRIPTION:
MDW T 054 7.0
END DESCRIPTION:
XS GIS Cut Line= 3
      2320537.71      7092133.07      2320200.71      7092278.83
      2319885.93      7092439.10
#Sta/Elev= 30
  4593.2  713.28  4613.6  713.39  4621.1  712.94  4650.1  713.12  4657.2  712.64
  4668.1  712.70  4679.0  713.68  4689.8  713.83  4697.1  713.00  4711.6  712.57
  4842.4  711.87  4854.3  711.62  4872.4  710.27  4886.0  710.08  4907.8  708.90
  4951.8  707.68  4952.0  707.18  4955.5  707.18  4955.8  707.68  4964.1  707.75
  4970.9  708.23  4976.5  707.97  4984.7  708.66  4998.8  708.83  5021.0  708.37
  5043.3  709.25  5126.6  711.25  5171.1  711.74  5199.0  712.48  5313.6  714.27
#Mann=3,-1,0
  4593.2    0.05       0  4951.8    0.04       0  4955.8    0.05       0
Bank Sta=4951.8,4955.8
Exp/Cntr=0.3,0.1

Type RM Length L Ch R = 1,4454,175,175,175
BEGIN DESCRIPTION:
Mapping XS 079adecd
END DESCRIPTION:
XS GIS Cut Line= 3
      2320440.74      7091983.45      2320095.42      7092138.48
      2319818.01      7092273.62
#Sta/Elev= 30
  4617.5  710.33  4623.1  709.82  4630.4  710.50  4669.4  709.92  4698.1  710.20
  4715.8  709.73  4721.2  710.12  4738.9  709.85  4744.4  710.33  4767.6  709.91
  4773.1  710.14  4813.9  708.77  4865.7  707.83  4888.9  706.75  4926.3  706.40
  4940.7  705.78  4956.4  703.36  4956.7  702.86  4960.2  702.86  4960.4  703.36
  4963.9  704.46  4970.2  704.95  4987.1  704.16  5015.4  706.23  5100.0  708.20
  5136.6  709.43  5181.1  709.80  5218.2  710.59  5235.2  710.32  5304.6  710.74
#Mann=3,-1,0
  4617.5    0.05       0  4956.4    0.04       0  4960.4    0.05       0
Bank Sta=4956.4,4960.4
Exp/Cntr=0.3,0.1

Type RM Length L Ch R = 1,4279,190,190,190
BEGIN DESCRIPTION:
MDW T 054 6.0
END DESCRIPTION:
XS GIS Cut Line= 3
      2320524.68      7091897.62      2320008.00      7091988.90
      2319705.88      7092196.05
#Sta/Elev= 30
  4478.4  710.56  4494.3  710.31  4504.5  709.18  4514.6  709.01  4525.3  709.42
  4697.9  707.74  4806.1  705.22  4811.2  705.63  4865.3  703.73  4919.5  702.56
  4978.7  701.69  4983.8  702.53  4998.0  699.86  4998.3  699.36  5001.8  699.36
  5002.0  699.86  5005.5  699.86  5010.9  700.72  5017.0  702.30  5031.9  703.61
  5067.7  704.54  5124.6  705.52  5190.3  705.74  5226.1  706.74  5255.9  706.78
  5262.0  707.29  5276.9  707.01  5318.8  707.85  5363.5  707.72  5369.4  708.10
#Mann=3,-1,0
  4478.4    0.05       0  4998.0    0.04       0  5002.0    0.05       0
Bank Sta=4998,5002
Exp/Cntr=0.3,0.1

Type RM Length L Ch R = 1,4089,216,216,216
BEGIN DESCRIPTION:
MDW T 054 5.0
END DESCRIPTION:
XS GIS Cut Line= 3
      2320369.87      7091687.77      2320007.09      7091794.54
      2319583.09      7091994.61
#Sta/Elev= 30
  4585.7  703.12  4612.0  703.17  4645.3  702.16  4722.4  701.88  4750.6  701.12
  4827.7  700.62  4909.8  699.51  4927.7  698.81  4941.0  698.84  4960.3  697.05
  4966.1  697.24  4970.8  696.82  4971.1  696.32  4974.6  696.32  4974.8  696.82
  4983.4  697.97  4988.9  697.75  4994.9  698.32  5028.1  698.62  5050.2  699.55
  5125.5  700.27  5160.8  701.09  5199.4  701.44  5244.9  701.24  5273.2  701.75
  5336.0  701.90  5341.6  702.25  5358.8  701.91  5387.1  702.45  5432.7  702.26
#Mann=3,-1,0
  4585.7    0.05       0  4970.8    0.04       0  4974.8    0.05       0
Bank Sta=4970.8,4974.8
Exp/Cntr=0.3,0.1

Type RM Length L Ch R = 1,3873,169,169,169
BEGIN DESCRIPTION:
Mapping XS d57b6f01
END DESCRIPTION:
XS GIS Cut Line= 3
      2320264.76      7091624.34      2319888.59      7091622.21
      2319579.15      7091909.62
#Sta/Elev= 30
  4627.6  700.54  4653.4  700.26  4723.4  699.02  4773.4  698.71  4783.4  698.31
  4863.4  697.02  4891.4  696.16  4891.6  695.66  4895.1  695.66  4895.4  696.16
  4923.4  696.49  4933.4  696.33  5009.0  697.14  5030.5  697.15  5072.5  697.55
  5136.5  697.69  5150.7  697.90  5157.5  698.25  5185.8  698.90  5221.5  698.84
  5228.3  699.01  5242.5  698.86  5263.5  699.18  5270.9  699.05  5291.9  699.42
  5348.5  699.94  5355.9  699.79  5362.7  700.26  5370.1  700.19  5426.1  700.96
#Mann=3,-1,0
  4627.6    0.05       0  4891.4    0.04       0  4895.4    0.05       0
Bank Sta=4891.4,4895.4
Exp/Cntr=0.3,0.1

Type RM Length L Ch R = 1,3704,193,193,193
BEGIN DESCRIPTION:
MDW T 054 4.0
END DESCRIPTION:
XS GIS Cut Line= 3
      2320452.30      7091275.02      2319785.22      7091484.58
      2319641.73      7091819.30
#Sta/Elev= 30
  4344.3  697.23  4368.7  696.83  4381.0  697.06  4421.1  696.69  4548.3  696.79
  4575.5  696.43  4580.7  696.58  4607.9  696.15  4630.8  696.43  4645.5  696.40
  4693.7  695.90  4748.0  695.74  4775.1  695.28  4798.5  695.24  4819.4  695.50
  4837.9  695.22  4838.2  694.72  4841.7  694.72  4841.9  695.22  4903.3  695.80
  4955.7  695.80  5007.2  695.44  5038.9  695.94  5097.9  696.24  5197.6  697.23
  5203.0  697.04  5212.6  697.11  5273.8  697.90  5297.3  697.85  5407.7  699.33
#Mann=3,-1,0
  4344.3    0.05       0  4837.9    0.04       0  4841.9    0.05       0
Bank Sta=4837.9,4841.9
Exp/Cntr=0.3,0.1

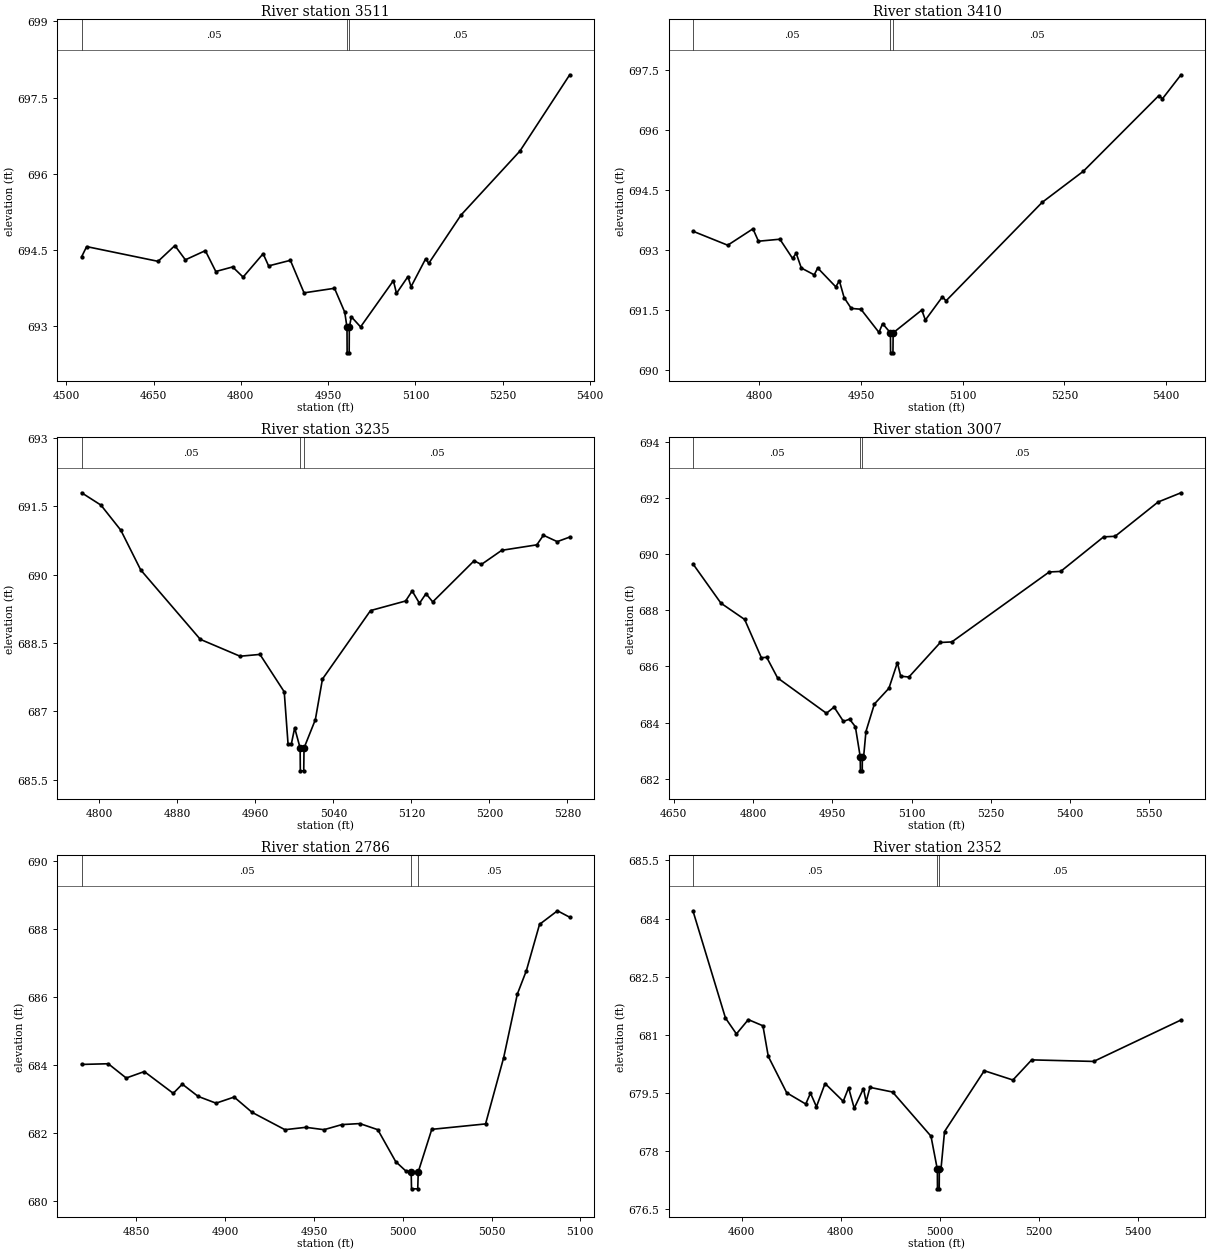
Type RM Length L Ch R = 1,3511,101,101,101
BEGIN DESCRIPTION:
Mapping XS 81f496c5
END DESCRIPTION:
XS GIS Cut Line= 3
      2320093.51      7091202.24      2319654.12      7091393.34
      2319528.96      7091730.19
#Sta/Elev= 30
  4526.5  694.37  4535.1  694.57  4657.8  694.28  4686.7  694.59  4704.7  694.31
  4739.0  694.49  4757.0  694.08  4785.9  694.17  4803.9  693.97  4838.3  694.43
  4847.7  694.19  4885.1  694.30  4908.6  693.66  4960.9  693.75  4978.5  693.28
  4982.4  692.98  4982.6  692.48  4986.1  692.48  4986.4  692.98  4989.8  693.19
  5005.7  692.99  5062.1  693.90  5067.4  693.65  5087.1  693.98  5092.4  693.78
  5117.5  694.33  5122.8  694.24  5178.2  695.19  5279.5  696.45  5365.0  697.95
#Mann=3,-1,0
  4526.5    0.05       0  4982.4    0.04       0  4986.4    0.05       0
Bank Sta=4982.4,4986.4
Exp/Cntr=0.3,0.1

Type RM Length L Ch R = 1,3410,175,175,175
BEGIN DESCRIPTION:
Mapping XS cfc880c3
END DESCRIPTION:
XS GIS Cut Line= 3
      2319900.82      7091208.38      2319620.43      7091300.18
      2319473.79      7091698.61
#Sta/Elev= 30
  4702.3  693.47  4753.6  693.12  4790.8  693.53  4798.9  693.22  4830.5  693.27
  4849.2  692.79  4854.5  692.92  4862.1  692.55  4881.1  692.38  4886.3  692.55
  4912.9  692.08  4918.2  692.23  4925.2  691.81  4935.7  691.54  4950.0  691.52
  4976.6  690.94  4981.9  691.16  4993.5  690.93  4993.7  690.43  4997.2  690.43
  4997.5  690.93  5039.7  691.50  5045.0  691.25  5070.1  691.83  5075.5  691.73
  5217.1  694.19  5278.0  694.97  5389.2  696.86  5394.5  696.78  5421.9  697.38
#Mann=3,-1,0
  4702.3    0.05       0  4993.5    0.04       0  4997.5    0.05       0
Bank Sta=4993.5,4997.5
Exp/Cntr=0.3,0.1

Type RM Length L Ch R = 1,3235,228,228,228
BEGIN DESCRIPTION:
Mapping XS 72fc0529
END DESCRIPTION:
XS GIS Cut Line= 3
      2319748.41      7091195.34      2319537.45      7091153.47
      2319323.94      7091343.05
#Sta/Elev= 30
  4781.8  691.79  4801.6  691.52  4822.0  690.97  4842.4  690.10  4903.5  688.58
  4944.3  688.21  4964.7  688.25  4989.6  687.43  4993.5  686.29  4996.9  686.29
  5000.3  686.64  5005.9  686.20  5006.1  685.70  5009.6  685.70  5009.9  686.20
  5021.5  686.82  5028.8  687.71  5078.1  689.21  5114.1  689.42  5120.8  689.64
  5128.3  689.37  5135.0  689.58  5141.9  689.40  5184.3  690.30  5191.8  690.22
  5212.7  690.53  5248.7  690.65  5255.4  690.86  5269.6  690.72  5282.4  690.82
#Mann=3,-1,0
  4781.8    0.05       0  5005.9    0.04       0  5009.9    0.05       0
Bank Sta=5005.9,5009.9
Exp/Cntr=0.3,0.1

Type RM Length L Ch R = 1,3007,221,221,221
BEGIN DESCRIPTION:
Mapping XS 5889512f
END DESCRIPTION:
XS GIS Cut Line= 4
      2319755.79      7090975.83      2319517.40      7090926.14
      2319444.69      7090958.59      2319153.46      7091484.04
#Sta/Elev= 30
  4686.1  689.65  4739.1  688.25  4784.0  687.67  4815.6  686.31  4825.8  686.32
  4846.3  685.59  4938.8  684.33  4953.3  684.55  4971.0  684.04  4982.6  684.12
  4993.6  683.85  5002.8  682.78  5003.1  682.28  5006.6  682.28  5006.8  682.78
  5009.2  682.78  5013.6  683.68  5029.6  684.66  5057.1  685.22  5073.1  686.13
  5079.4  685.65  5094.9  685.62  5154.4  686.85  5176.2  686.87  5360.5  689.36
  5382.2  689.38  5463.5  690.61  5485.2  690.63  5566.5  691.85  5610.0  692.18
#Mann=3,-1,0
  4686.1    0.05       0  5002.8    0.04       0  5006.8    0.05       0
Bank Sta=5002.8,5006.8
Exp/Cntr=0.3,0.1

Type RM Length L Ch R = 1,2786,434,434,434
BEGIN DESCRIPTION:
Mapping XS d118504e
END DESCRIPTION:
XS GIS Cut Line= 2
      2319593.85      7090716.88      2319322.21      7090759.11
#Sta/Elev= 30
  4819.1  684.03  4834.1  684.05  4844.2  683.63  4854.4  683.82  4870.7  683.18
  4875.8  683.45  4884.7  683.09  4894.8  682.89  4905.0  683.07  4915.1  682.62
  4933.6  682.11  4945.4  682.18  4955.6  682.11  4965.7  682.26  4975.8  682.29
  4985.9  682.11  4996.0  681.17  5001.6  680.90  5004.7  680.87  5004.9  680.37
  5008.4  680.37  5008.7  680.87  5016.3  682.12  5046.6  682.28  5056.8  684.23
  5064.5  686.10  5069.6  686.79  5077.0  688.15  5087.1  688.55  5094.0  688.36
#Mann=3,-1,0
  4819.1    0.05       0  5004.7    0.04       0  5008.7    0.05       0
Bank Sta=5004.7,5008.7
Exp/Cntr=0.3,0.1

Type RM Length L Ch R = 1,2352,441,441,441
BEGIN DESCRIPTION:
Mapping XS efd9d8ac
END DESCRIPTION:
XS GIS Cut Line= 4
      2319649.80      7090606.37      2319188.53      7090417.82
      2319074.38      7090409.79      2318747.86      7090588.96
#Sta/Elev= 30
  4501.8  684.20  4567.5  681.43  4589.6  681.02  4613.6  681.39  4643.1  681.23
  4653.9  680.44  4691.1  679.50  4729.5  679.21  4739.1  679.49  4751.1  679.14
  4768.5  679.74  4805.2  679.28  4816.0  679.63  4827.4  679.10  4846.0  679.61
  4851.4  679.27  4859.2  679.64  4904.8  679.52  4982.3  678.38  4995.2  677.52
  4995.4  677.02  4998.9  677.02  4999.2  677.52  5002.4  677.52  5009.7  678.50
  5089.9  680.07  5147.7  679.83  5185.6  680.35  5310.7  680.31  5487.0  681.38
#Mann=3,-1,0
  4501.8    0.05       0  4995.2    0.04       0  4999.2    0.05       0
Bank Sta=4995.2,4999.2
Exp/Cntr=0.3,0.1

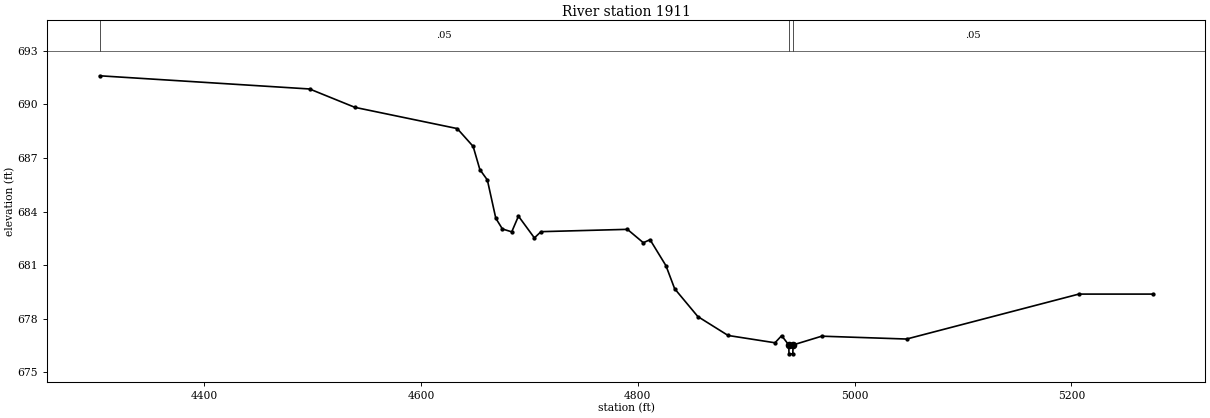
Type RM Length L Ch R = 1,1911,0,0,0
BEGIN DESCRIPTION:
MDW T 054 2.0
END DESCRIPTION:
XS GIS Cut Line= 3
      2319978.97      7090809.96      2319526.04      7090183.10
      2319416.60      7090017.82
#Sta/Elev= 30
  4303.5  691.61  4497.2  690.87  4539.0  689.84  4633.4  688.65  4648.1  687.65
  4654.3  686.35  4661.2  685.77  4669.0  683.62  4675.1  683.02  4683.7  682.86
  4689.9  683.74  4704.6  682.52  4710.7  682.87  4790.4  683.00  4805.1  682.25
  4811.3  682.42  4826.0  680.96  4834.0  679.67  4855.4  678.11  4883.3  677.05
  4926.6  676.64  4932.7  677.04  4939.3  676.52  4939.5  676.02  4943.0  676.02
  4943.3  676.52  4969.7  677.01  5048.0  676.85  5206.9  679.37  5275.1  679.37
#Mann=3,-1,0
  4303.5    0.05       0  4939.3    0.04       0  4943.3    0.05       0
Bank Sta=4939.3,4943.3
Exp/Cntr=0.3,0.1

Chan Stop Cuts=-1