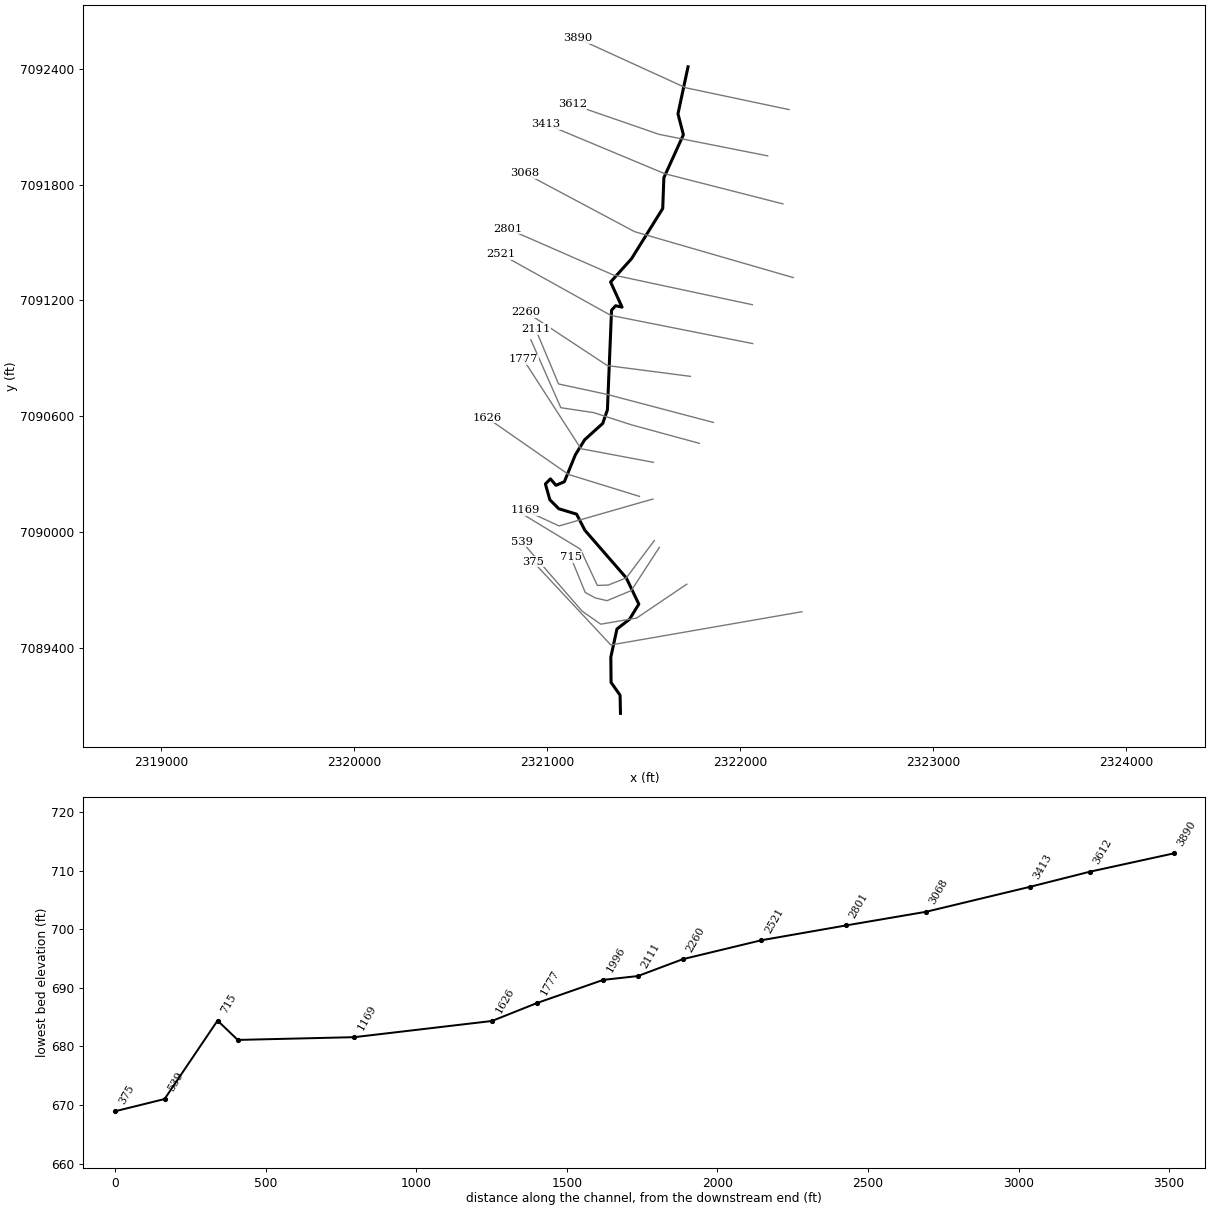
--- MDW T 055.prj (project) ---

Proj Title=MDW T 055 Base Level Engineering
Current Plan=p01
Default Exp/Contr=0.3,0.1
English Units
Geom File=g01
Flow File=f01
Plan File=p01
BEGIN DESCRIPTION:
MDW T 055
END DESCRIPTION:

--- MDW T 055.p01 (plan) ---

Plan Title=Multiple Run
Short Identifier=Multiple
Geom File=g01
Flow File=f01
Subcritical Flow
K Sum by GR= 0
Std Step Tol= 0.01
Critical Tol= 0.01
Num of Std Step Trials= 20
Max Error Tol= 0.3
Flow Tol Ratio= 0.001
Split Flow NTrial= 30
Split Flow Tol= 0.02
Split Flow Ratio= 0.02
Log Output Level= 0
Friction Slope Method= 1
Unsteady Friction Slope Method= 2
Unsteady Bridges Friction Slope Method= 1
Parabolic Critical Depth
Global Vel Dist=  1 , 1 , 1
Global Log Level= 0
CheckData=True
Encroach Param= -1, 0, 0, 0
BEGIN DESCRIPTION:
Multiple Run
END DESCRIPTION:

--- MDW T 055.f01 (steady flow) ---

Flow Title=Multiple
Number of Profiles=7
Profile Names=10-year,25-year,50-year,1pct_min,100-year,1pct_plu,500-year
River Rch & RM= MDW T 055,Reach-1,3890
     260     339     402     237     473     944     655
Boundary for River Rch & Prof#=MDW T 055,Reach-1,1
Up Type=0
Dn Type=3
Dn Slope=0.005
Boundary for River Rch & Prof#=MDW T 055,Reach-1,2
Up Type=0
Dn Type=3
Dn Slope=0.005
Boundary for River Rch & Prof#=MDW T 055,Reach-1,3
Up Type=0
Dn Type=3
Dn Slope=0.005
Boundary for River Rch & Prof#=MDW T 055,Reach-1,4
Up Type=0
Dn Type=3
Dn Slope=0.005
Boundary for River Rch & Prof#=MDW T 055,Reach-1,5
Up Type=0
Dn Type=3
Dn Slope=0.005
Boundary for River Rch & Prof#=MDW T 055,Reach-1,6
Up Type=0
Dn Type=3
Dn Slope=0.005
Boundary for River Rch & Prof#=MDW T 055,Reach-1,7
Up Type=0
Dn Type=3
Dn Slope=0.005

--- MDW T 055.g01 (geometry) ---

Geom Title=Existing Conditions

River Reach=MDW T 055,Reach-1
Reach XY= 30
      2321729.00      7092410.00      2321676.86      7092166.43
      2321704.98      7092057.94      2321603.76      7091835.33
      2321597.87      7091675.97      2321436.47      7091416.07
      2321327.77      7091294.94      2321387.16      7091164.86
      2321353.87      7091171.96      2321332.69      7091148.81
      2321311.32      7090632.84      2321286.96      7090562.17
      2321193.63      7090477.95      2321145.12      7090399.55
      2321088.30      7090260.27      2321044.52      7090241.65
      2321016.01      7090274.93      2320990.00      7090248.49
      2321013.03      7090166.64      2321059.32      7090120.22
      2321151.59      7090092.23      2321194.81      7090008.33
      2321408.98      7089761.99      2321474.04      7089626.13
      2321425.96      7089547.71      2321360.70      7089497.19
      2321328.96      7089351.53      2321330.20      7089220.50
      2321376.90      7089154.13      2321379.00      7089060.00

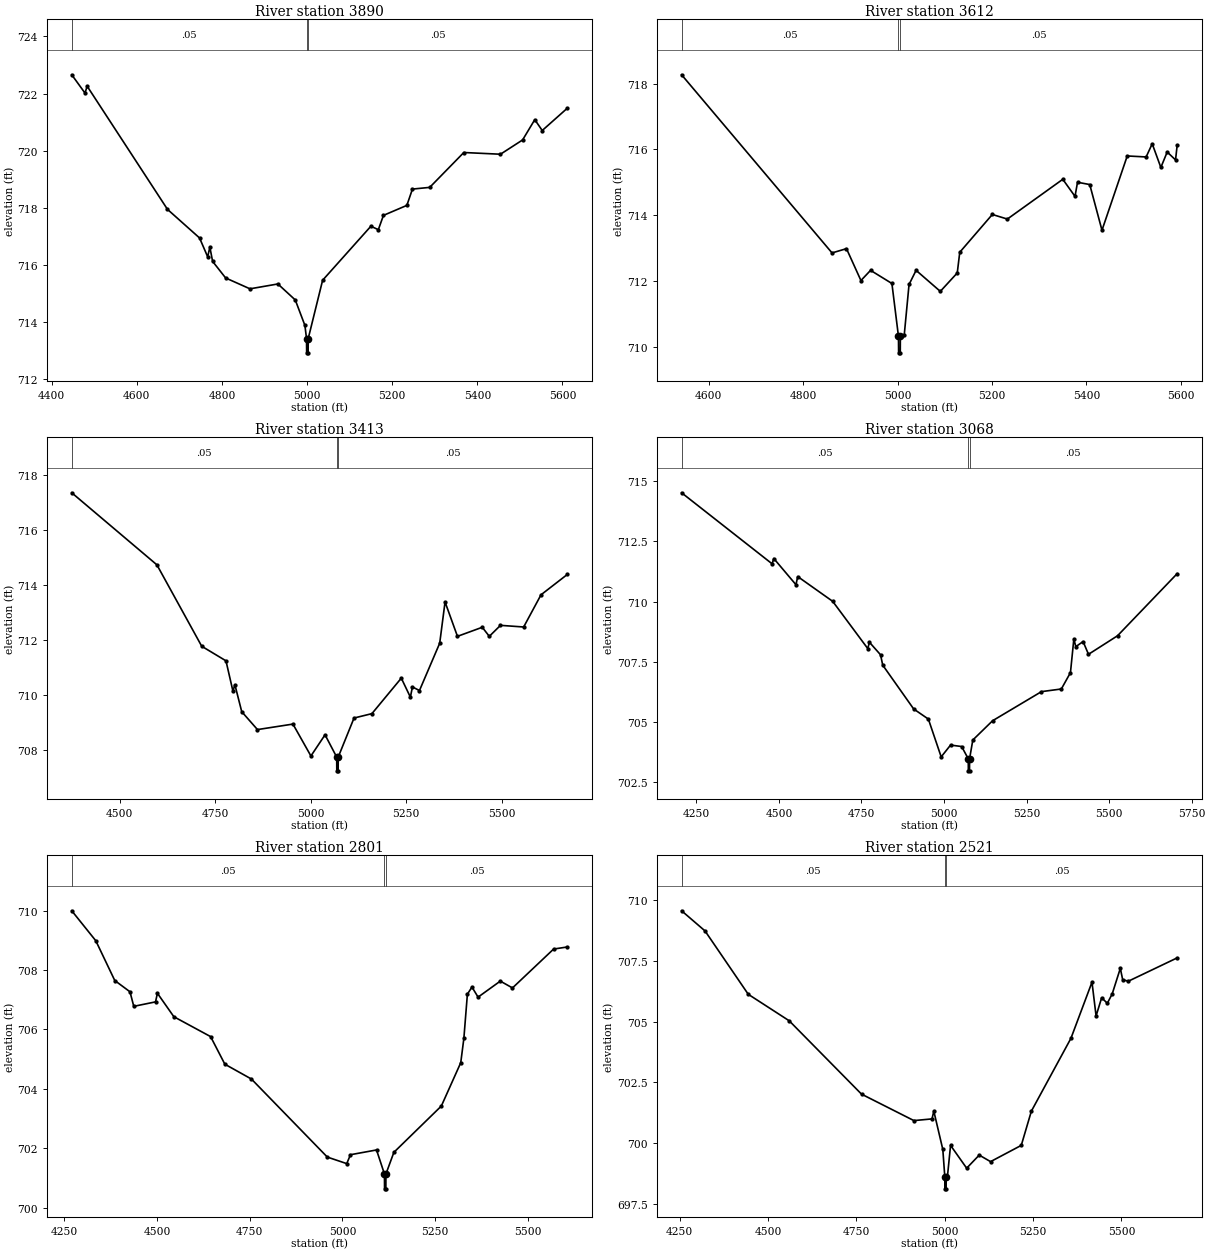
Type RM Length L Ch R = 1,3890,278,278,278
BEGIN DESCRIPTION:
MDW T 055 10.0
END DESCRIPTION:
XS GIS Cut Line= 3
      2322252.70      7092188.20      2321716.87      7092301.46
      2321156.14      7092557.52
#Sta/Elev= 30
  4447.2  722.66  4478.3  722.02  4483.4  722.26  4672.1  717.95  4747.4  716.95
  4766.5  716.29  4771.6  716.63  4778.1  716.13  4808.7  715.55  4865.9  715.17
  4931.4  715.34  4972.3  714.78  4994.9  713.89  4998.7  713.43  4999.0  712.93
  5002.5  712.93  5002.7  713.43  5036.5  715.47  5149.9  717.36  5167.4  717.24
  5179.4  717.74  5234.4  718.09  5247.5  718.66  5288.1  718.72  5368.2  719.94
  5454.3  719.88  5506.3  720.38  5534.9  721.09  5552.4  720.71  5611.3  721.49
#Mann=3,-1,0
  4447.2    0.05       0  4998.7    0.04       0  5002.7    0.05       0
Bank Sta=4998.7,5002.7
Exp/Cntr=0.3,0.1

Type RM Length L Ch R = 1,3612,199,199,199
BEGIN DESCRIPTION:
MDW T 055 9.0
END DESCRIPTION:
XS GIS Cut Line= 3
      2322141.56      7091948.63      2321579.00      7092060.00
      2321129.09      7092215.50
#Sta/Elev= 30
  4542.7  718.27  4861.3  712.85  4891.9  712.98  4922.5  712.01  4942.9  712.32
  4988.1  711.92  5002.0  710.31  5002.3  709.81  5005.8  709.81  5006.0  710.31
  5014.2  710.35  5024.4  711.89  5039.3  712.32  5090.6  711.68  5126.5  712.24
  5131.8  712.87  5200.8  714.02  5232.6  713.88  5350.0  715.09  5375.9  714.57
  5381.2  715.00  5407.1  714.93  5433.0  713.54  5486.5  715.80  5526.5  715.77
  5539.4  716.17  5557.7  715.45  5571.1  715.92  5588.8  715.68  5592.2  716.12
#Mann=3,-1,0
  4542.7    0.05       0  5002.0    0.04       0  5006.0    0.05       0
Bank Sta=5002,5006
Exp/Cntr=0.3,0.1

Type RM Length L Ch R = 1,3413,345,345,345
BEGIN DESCRIPTION:
MDW T 055 8.0
END DESCRIPTION:
XS GIS Cut Line= 3
      2322220.32      7091699.90      2321608.36      7091856.14
      2320993.49      7092112.85
#Sta/Elev= 30
  4374.2  717.34  4597.2  714.72  4714.6  711.76  4778.1  711.23  4796.3  710.13
  4801.5  710.36  4819.4  709.38  4860.6  708.73  4953.5  708.93  5000.6  707.77
  5037.6  708.54  5068.1  707.73  5068.4  707.23  5071.9  707.23  5072.1  707.73
  5113.5  709.15  5160.4  709.31  5237.3  710.60  5261.1  709.91  5266.5  710.28
  5284.9  710.15  5337.9  711.87  5351.9  713.37  5384.4  712.12  5449.4  712.45
  5467.8  712.12  5497.1  712.52  5557.8  712.46  5603.2  713.63  5672.1  714.37
#Mann=3,-1,0
  4374.2    0.05       0  5068.1   0.033       0  5072.1    0.05       0
Bank Sta=5068.1,5072.1
Exp/Cntr=0.3,0.1

Type RM Length L Ch R = 1,3068,267,267,267
BEGIN DESCRIPTION:
MDW T 055 7.0
END DESCRIPTION:
XS GIS Cut Line= 3
      2322274.13      7091317.96      2321452.11      7091555.80
      2320882.88      7091859.04
#Sta/Elev= 30
  4205.4  714.52  4479.4  711.57  4484.6  711.79  4551.8  710.70  4557.0  711.04
  4663.0  710.01  4769.1  708.05  4774.3  708.31  4807.9  707.79  4814.5  707.36
  4908.2  705.54  4952.7  705.12  4991.5  703.55  5019.9  704.04  5053.5  703.98
  5073.5  703.47  5073.8  702.97  5077.3  702.97  5077.5  703.47  5087.3  704.25
  5147.1  705.05  5295.2  706.26  5355.4  706.37  5383.0  707.05  5393.2  708.44
  5399.3  708.13  5421.3  708.34  5437.6  707.81  5525.5  708.58  5706.1  711.16
#Mann=3,-1,0
  4205.4    0.05       0  5073.5    0.04       0  5077.5    0.05       0
Bank Sta=5073.5,5077.5
Exp/Cntr=0.3,0.1

Type RM Length L Ch R = 1,2801,280,280,280
BEGIN DESCRIPTION:
MDW T 055 6.0
END DESCRIPTION:
XS GIS Cut Line= 3
      2322062.38      7091177.32      2321342.22      7091331.32
      2320793.64      7091571.26
#Sta/Elev= 30
  4270.6  710.00  4335.4  708.99  4386.5  707.65  4427.5  707.27  4437.7  706.78
  4496.3  706.93  4501.4  707.22  4545.7  706.43  4644.7  705.76  4683.1  704.83
  4754.7  704.33  4959.2  701.70  5011.5  701.48  5021.6  701.78  5091.8  701.94
  5113.1  701.13  5113.4  700.63  5116.9  700.63  5117.1  701.13  5138.5  701.86
  5266.4  703.42  5318.7  704.88  5327.1  705.70  5336.6  707.19  5348.9  707.43
  5365.4  707.09  5425.3  707.63  5458.1  707.40  5568.9  708.71  5605.8  708.78
#Mann=3,-1,0
  4270.6    0.05       0  5113.1    0.04       0  5117.1    0.05       0
Bank Sta=5113.1,5117.1
Exp/Cntr=0.3,0.1

Type RM Length L Ch R = 1,2521,261,261,261
BEGIN DESCRIPTION:
MDW T 055 5.0
END DESCRIPTION:
XS GIS Cut Line= 3
      2322064.05      7090975.94      2321329.20      7091121.94
      2320758.51      7091439.49
#Sta/Elev= 30
  4255.3  709.56  4321.6  708.73  4444.0  706.12  4559.8  705.03  4764.4  702.01
  4912.7  700.92  4963.9  700.99  4969.0  701.31  4994.5  699.73  5000.1  698.61
  5000.3  698.11  5003.8  698.11  5004.1  698.61  5007.5  698.61  5016.4  699.90
  5062.0  698.96  5097.5  699.50  5129.6  699.23  5216.5  699.90  5245.1  701.31
  5357.1  704.31  5416.6  706.62  5428.2  705.23  5444.0  705.98  5460.0  705.75
  5473.9  706.14  5496.8  707.19  5503.5  706.72  5519.5  706.66  5657.6  707.62
#Mann=3,-1,0
  4255.3    0.05       0  5000.1    0.04       0  5004.1    0.05       0
Bank Sta=5000.1,5004.1
Exp/Cntr=0.3,0.1

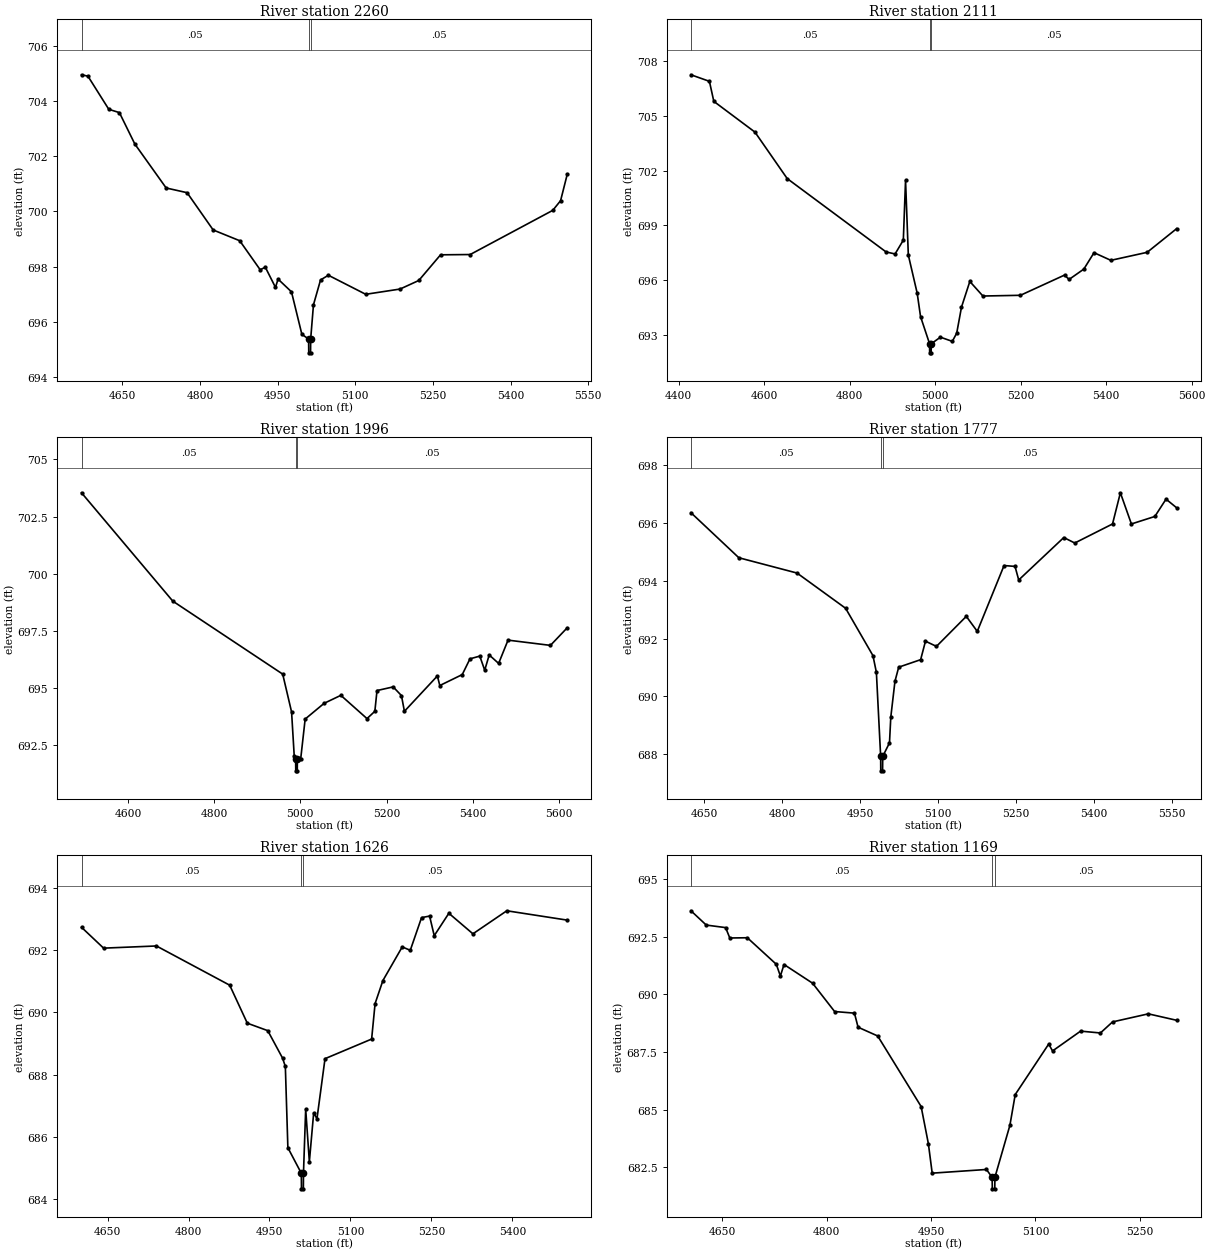
Type RM Length L Ch R = 1,2260,149,149,149
BEGIN DESCRIPTION:
Mapping XS 9f4c98a2
END DESCRIPTION:
XS GIS Cut Line= 3
      2321741.28      7090806.18      2321310.84      7090862.06
      2320889.64      7091139.65
#Sta/Elev= 30
  4571.0  704.95  4583.4  704.90  4623.7  703.70  4644.2  703.58  4674.1  702.44
  4734.6  700.85  4775.0  700.68  4825.4  699.33  4876.7  698.94  4916.2  697.89
  4926.2  697.98  4945.8  697.25  4950.8  697.55  4976.7  697.09  4996.8  695.55
  5009.8  695.38  5010.1  694.88  5013.6  694.88  5013.8  695.38  5019.2  696.62
  5032.9  697.52  5048.0  697.69  5120.2  697.00  5186.5  697.19  5222.7  697.50
  5264.8  698.43  5322.0  698.44  5481.6  700.04  5496.7  700.39  5509.5  701.34
#Mann=3,-1,0
  4571.0    0.05       0  5009.8    0.04       0  5013.8    0.05       0
Bank Sta=5009.8,5013.8
Exp/Cntr=0.3,0.1

Type RM Length L Ch R = 1,2111,115,115,115
BEGIN DESCRIPTION:
MDW T 055 3.0
END DESCRIPTION:
XS GIS Cut Line= 4
      2321860.78      7090567.31      2321310.59      7090712.39
      2321058.22      7090766.68      2320938.66      7091051.89
#Sta/Elev= 30
  4428.5  707.27  4471.7  706.91  4482.0  705.81  4578.3  704.12  4653.7  701.57
  4885.1  697.54  4906.1  697.43  4925.4  698.19  4930.6  701.47  4937.1  697.37
  4957.8  695.28  4965.7  693.99  4986.8  692.50  4987.0  692.00  4990.5  692.00
  4990.8  692.50  5012.2  692.86  5040.0  692.63  5050.3  693.08  5061.5  694.51
  5081.0  695.92  5111.6  695.12  5199.4  695.16  5302.6  696.27  5313.2  696.03
  5347.8  696.60  5371.6  697.50  5411.0  697.08  5495.9  697.52  5564.9  698.82
#Mann=3,-1,0
  4428.5    0.05       0  4986.8    0.04       0  4990.8    0.05       0
Bank Sta=4986.8,4990.8
Exp/Cntr=0.3,0.1

Type RM Length L Ch R = 1,1996,219,219,219
BEGIN DESCRIPTION:
Mapping XS 567beeee
END DESCRIPTION:
XS GIS Cut Line= 5
      2321787.60      7090459.17      2321438.16      7090554.33
      2321240.54      7090618.16      2321069.98      7090643.69
      2320914.78      7090995.59
#Sta/Elev= 30
  4492.3  703.54  4704.1  698.79  4959.1  695.59  4979.7  693.93  4985.9  691.98
  4989.1  691.85  4989.4  691.35  4992.9  691.35  4993.1  691.85  5000.7  691.85
  5011.2  693.62  5055.2  694.31  5094.0  694.66  5154.7  693.64  5172.9  693.96
  5177.9  694.87  5215.4  695.03  5234.6  694.65  5241.5  693.96  5318.0  695.51
  5323.6  695.09  5375.7  695.57  5393.6  696.26  5416.4  696.38  5427.8  695.76
  5438.2  696.43  5460.1  696.06  5481.9  697.08  5580.3  696.85  5619.2  697.62
#Mann=3,-1,0
  4492.3    0.05       0  4989.1    0.04       0  4993.1    0.05       0
Bank Sta=4989.1,4993.1
Exp/Cntr=0.3,0.1

Type RM Length L Ch R = 1,1777,151,151,151
BEGIN DESCRIPTION:
Mapping XS 3482d608
END DESCRIPTION:
XS GIS Cut Line= 3
      2321549.50      7090360.81      2321174.23      7090431.15
      2320874.92      7090895.19
#Sta/Elev= 30
  4624.8  696.36  4716.9  694.80  4828.8  694.27  4922.2  693.05  4974.8  691.41
  4981.4  690.83  4989.6  687.92  4989.8  687.42  4993.3  687.42  4993.6  687.92
  5006.6  688.39  5009.1  689.28  5017.1  690.52  5024.3  691.01  5066.5  691.27
  5075.8  691.91  5096.9  691.73  5154.3  692.77  5175.4  692.25  5226.9  694.53
  5248.0  694.50  5255.1  694.03  5341.8  695.50  5362.9  695.31  5435.5  695.97
  5450.6  697.05  5471.8  695.97  5516.9  696.23  5538.4  696.83  5558.8  696.53
#Mann=3,-1,0
  4624.8    0.05       0  4989.6    0.04       0  4993.6    0.05       0
Bank Sta=4989.6,4993.6
Exp/Cntr=0.3,0.1

Type RM Length L Ch R = 1,1626,457,457,457
BEGIN DESCRIPTION:
MDW T 055 2.0
END DESCRIPTION:
XS GIS Cut Line= 3
      2321477.31      7090184.26      2321109.92      7090297.77
      2320686.76      7090592.13
#Sta/Elev= 30
  4601.7  692.73  4642.6  692.06  4740.5  692.13  4876.3  690.87  4908.9  689.65
  4946.8  689.41  4974.2  688.53  4979.4  688.26  4984.1  685.65  5009.0  684.83
  5009.3  684.33  5012.8  684.33  5013.0  684.83  5017.1  686.89  5023.9  685.20
  5031.9  686.77  5038.0  686.58  5052.9  688.51  5139.3  689.14  5145.7  690.28
  5160.2  691.02  5196.0  692.10  5210.9  691.99  5231.8  693.04  5246.7  693.09
  5255.3  692.46  5282.4  693.18  5327.0  692.52  5389.8  693.26  5501.7  692.96
#Mann=3,-1,0
  4601.7    0.05       0  5009.0    0.04       0  5013.0    0.05       0
Bank Sta=5009,5013
Exp/Cntr=0.3,0.1

Type RM Length L Ch R = 1,1169,387,387,387
BEGIN DESCRIPTION:
MDW T 055 1.0
END DESCRIPTION:
XS GIS Cut Line= 3
      2321546.89      7090170.58      2321060.78      7090031.21
      2320886.39      7090111.77
#Sta/Elev= 30
  4605.1  693.63  4627.1  693.01  4654.9  692.90  4660.9  692.45  4686.1  692.46
  4727.7  691.31  4733.6  690.80  4738.8  691.30  4779.8  690.49  4811.5  689.26
  4840.0  689.19  4845.2  688.58  4873.4  688.20  4935.8  685.14  4946.2  683.53
  4951.7  682.25  5029.6  682.41  5037.8  682.07  5038.1  681.57  5041.6  681.57
  5041.8  682.07  5063.3  684.32  5071.0  685.66  5119.1  687.85  5124.6  687.55
  5164.9  688.41  5193.4  688.33  5210.8  688.81  5262.2  689.16  5302.9  688.88
#Mann=3,-1,0
  4605.1    0.05       0  5037.8   0.033       0  5041.8    0.05       0
Bank Sta=5037.8,5041.8
Exp/Cntr=0.3,0.1

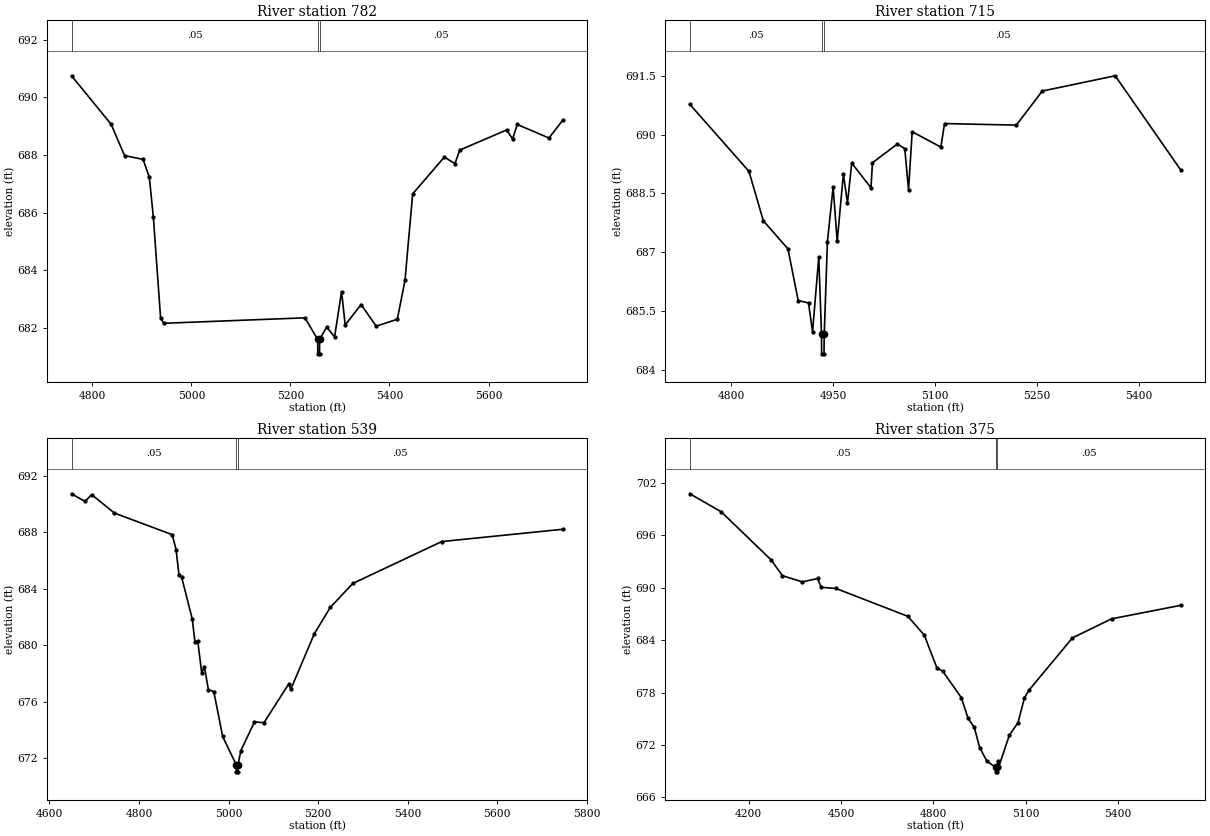
Type RM Length L Ch R = 1,782,67,67,67
BEGIN DESCRIPTION:
Mapping XS 0d02e241
END DESCRIPTION:
XS GIS Cut Line= 6
      2321554.54      7089955.58      2321408.98      7089761.99
      2321315.97      7089724.97      2321259.19      7089722.85
      2321171.29      7089910.89      2320842.46      7090110.31
#Sta/Elev= 30
  4757.8  690.75  4837.7  689.07  4864.9  687.98  4902.3  687.85  4914.9  687.23
  4923.1  685.84  4937.7  682.34  4944.0  682.16  5229.3  682.35  5254.9  681.60
  5255.2  681.10  5258.7  681.10  5258.9  681.60  5273.1  682.03  5289.1  681.69
  5303.2  683.26  5310.5  682.10  5342.6  682.81  5373.2  682.06  5415.8  682.30
  5431.3  683.65  5446.8  686.65  5510.8  687.93  5532.2  687.70  5541.8  688.17
  5636.6  688.87  5648.5  688.56  5658.1  689.06  5722.1  688.59  5749.5  689.20
#Mann=3,-1,0
  4757.8    0.05       0  5254.9   0.033       0  5258.9    0.05       0
Bank Sta=5254.9,5258.9
Exp/Cntr=0.3,0.1

Type RM Length L Ch R = 1,715,176,176,176
BEGIN DESCRIPTION:
Mapping XS f81799ca
END DESCRIPTION:
XS GIS Cut Line= 6
      2321580.18      7089919.86      2321434.95      7089696.28
      2321309.29      7089643.90      2321248.54      7089658.23
      2321196.48      7089686.16      2321121.23      7089869.87
#Sta/Elev= 30
  4739.2  690.77  4826.2  689.06  4847.3  687.80  4883.6  687.08  4898.7  685.76
  4913.9  685.70  4919.8  684.96  4929.0  686.88  4933.0  684.90  4933.2  684.40
  4936.7  684.40  4937.0  684.90  4941.7  687.26  4950.1  688.66  4956.1  687.27
  4965.2  688.99  4971.2  688.25  4977.5  689.27  5005.8  688.64  5008.0  689.28
  5044.8  689.76  5055.6  689.64  5061.1  688.59  5066.5  690.07  5108.7  689.68
  5114.1  690.28  5219.8  690.24  5258.0  691.11  5365.3  691.50  5462.0  689.09
#Mann=3,-1,0
  4739.2    0.05       0  4933.0    0.04       0  4937.0    0.05       0
Bank Sta=4933,4937
Exp/Cntr=0.3,0.1

Type RM Length L Ch R = 1,539,164,164,164
BEGIN DESCRIPTION:
Mapping XS c1ea4f15
END DESCRIPTION:
XS GIS Cut Line= 5
      2321722.41      7089729.43      2321463.02      7089554.08
      2321276.54      7089522.03      2321179.86      7089589.98
      2320867.92      7089949.54
#Sta/Elev= 30
  4649.3  690.74  4679.3  690.20  4694.3  690.68  4745.2  689.37  4874.1  687.84
  4882.8  686.78  4889.1  685.01  4895.1  684.83  4919.0  681.84  4925.0  680.20
  4931.1  680.31  4940.0  678.03  4946.0  678.46  4954.9  676.85  4967.0  676.70
  4986.8  673.52  5017.1  671.51  5017.4  671.01  5020.9  671.01  5021.1  671.51
  5027.4  672.51  5057.8  674.55  5079.1  674.50  5134.0  677.23  5139.1  676.88
  5191.5  680.81  5227.2  682.68  5277.6  684.38  5476.1  687.35  5745.8  688.22
#Mann=3,-1,0
  4649.3    0.05       0  5017.1    0.04       0  5021.1    0.05       0
Bank Sta=5017.1,5021.1
Exp/Cntr=0.3,0.1

Type RM Length L Ch R = 1,375,0,0,0
BEGIN DESCRIPTION:
MDW T 055 0.5
END DESCRIPTION:
XS GIS Cut Line= 3
      2322319.25      7089586.66      2321329.02      7089414.44
      2320926.55      7089845.45
#Sta/Elev= 30
  4009.3  700.77  4111.1  698.71  4273.5  693.19  4309.9  691.39  4375.0  690.68
  4424.1  691.07  4435.9  690.06  4483.7  689.93  4717.2  686.74  4770.8  684.58
  4811.4  680.86  4831.3  680.42  4891.0  677.43  4912.9  675.07  4933.2  674.01
  4950.6  671.71  4973.8  670.18  5002.3  669.43  5002.5  668.93  5006.0  668.93
  5006.3  669.43  5010.2  670.17  5012.8  669.53  5046.8  673.10  5075.1  674.57
  5096.1  677.40  5110.3  678.26  5252.0  684.27  5379.0  686.45  5604.1  688.00
#Mann=3,-1,0
  4009.3    0.05       0  5002.3    0.04       0  5006.3    0.05       0
Bank Sta=5002.3,5006.3
Exp/Cntr=0.3,0.1

Chan Stop Cuts=-1