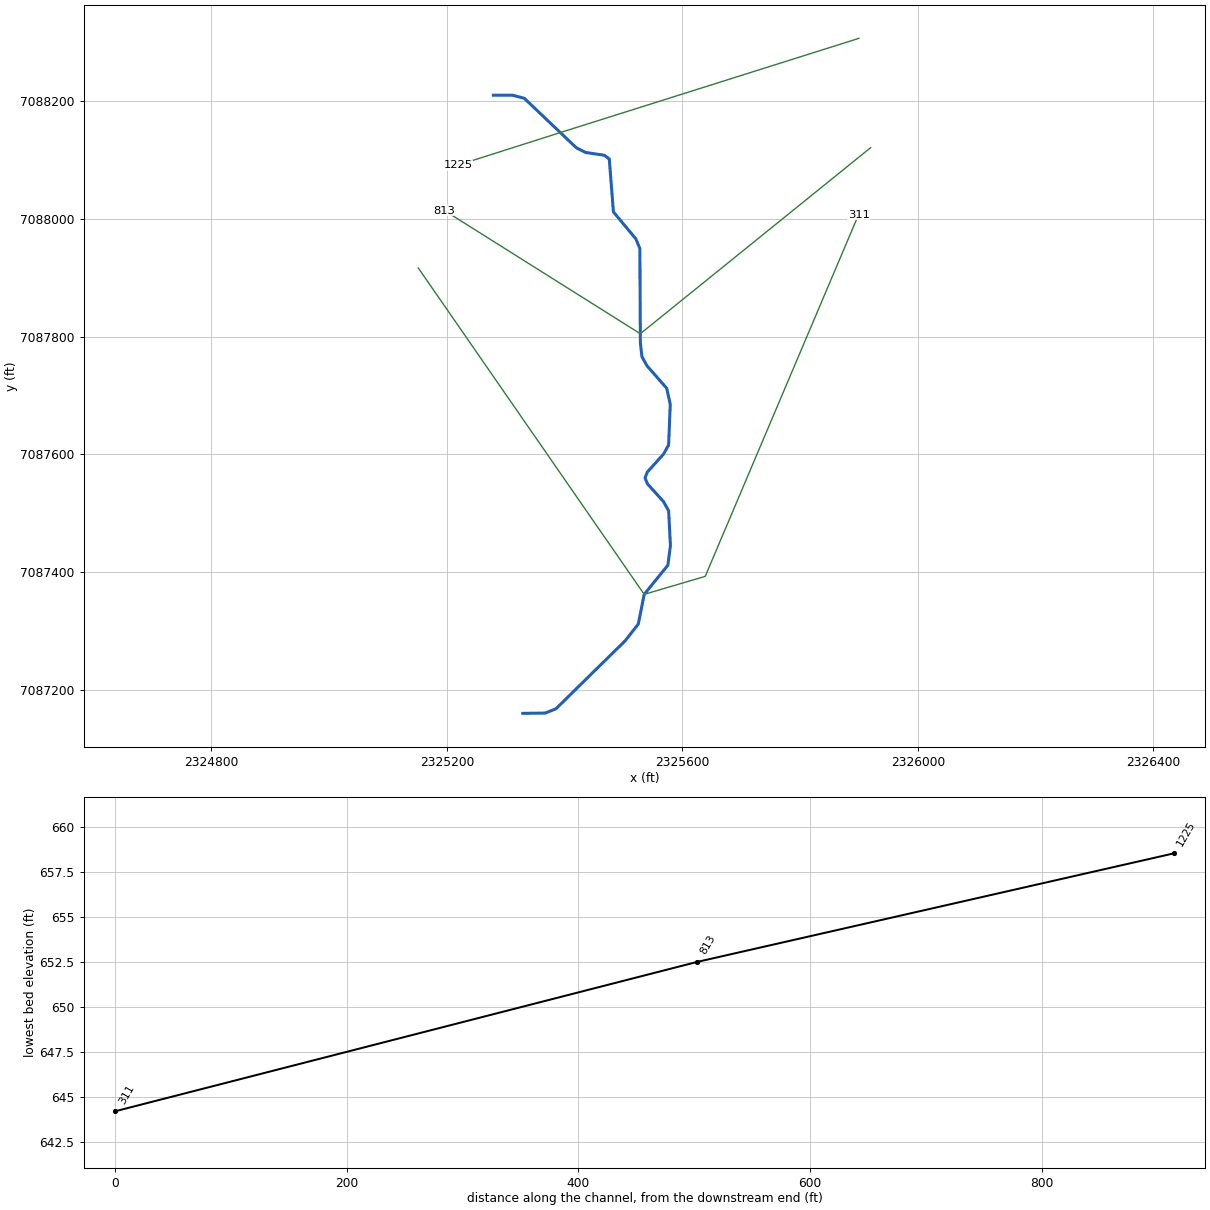
--- MDW T 056.prj (project) ---

Proj Title=MDW T 056 Base Level Engineering
Current Plan=p01
Default Exp/Contr=0.3,0.1
English Units
Geom File=g01
Flow File=f01
Plan File=p01
BEGIN DESCRIPTION:
MDW T 056
END DESCRIPTION:

--- MDW T 056.p01 (plan) ---

Plan Title=Multiple Run
Short Identifier=Multiple
Geom File=g01
Flow File=f01
Subcritical Flow
K Sum by GR= 0
Std Step Tol= 0.01
Critical Tol= 0.01
Num of Std Step Trials= 20
Max Error Tol= 0.3
Flow Tol Ratio= 0.001
Split Flow NTrial= 30
Split Flow Tol= 0.02
Split Flow Ratio= 0.02
Log Output Level= 0
Friction Slope Method= 1
Unsteady Friction Slope Method= 2
Unsteady Bridges Friction Slope Method= 1
Parabolic Critical Depth
Global Vel Dist=  1 , 1 , 1
Global Log Level= 0
CheckData=True
Encroach Param= -1, 0, 0, 0
BEGIN DESCRIPTION:
Multiple Run
END DESCRIPTION:

--- MDW T 056.f01 (steady flow) ---

Flow Title=Multiple
Number of Profiles=7
Profile Names=10-year,25-year,50-year,1pct_min,100-year,1pct_plu,500-year
River Rch & RM= MDW T 056,Reach-1,1225
     390     522     628     376     750    1496    1071
Boundary for River Rch & Prof#=MDW T 056,Reach-1,1
Up Type=0
Dn Type=3
Dn Slope=0.005
Boundary for River Rch & Prof#=MDW T 056,Reach-1,2
Up Type=0
Dn Type=3
Dn Slope=0.005
Boundary for River Rch & Prof#=MDW T 056,Reach-1,3
Up Type=0
Dn Type=3
Dn Slope=0.005
Boundary for River Rch & Prof#=MDW T 056,Reach-1,4
Up Type=0
Dn Type=3
Dn Slope=0.005
Boundary for River Rch & Prof#=MDW T 056,Reach-1,5
Up Type=0
Dn Type=3
Dn Slope=0.005
Boundary for River Rch & Prof#=MDW T 056,Reach-1,6
Up Type=0
Dn Type=3
Dn Slope=0.005
Boundary for River Rch & Prof#=MDW T 056,Reach-1,7
Up Type=0
Dn Type=3
Dn Slope=0.005

--- MDW T 056.g01 (geometry) ---

Geom Title=Existing Conditions

River Reach=MDW T 056,Reach-1
Reach XY= 30
      2325279.00      7088210.00      2325310.88      7088210.07
      2325331.51      7088204.67      2325419.63      7088120.91
      2325435.52      7088112.73      2325467.26      7088108.00
      2325475.84      7088101.66      2325482.89      7088011.67
      2325520.86      7087966.06      2325527.78      7087949.50
      2325528.65      7087789.85      2325531.26      7087765.94
      2325539.86      7087750.35      2325573.31      7087712.31
      2325579.39      7087685.00      2325576.64      7087615.89
      2325567.83      7087600.22      2325540.48      7087569.91
      2325536.57      7087560.00      2325540.48      7087550.09
      2325567.83      7087519.78      2325576.64      7087504.11
      2325579.70      7087444.94      2325575.32      7087411.59
      2325535.15      7087362.17      2325525.06      7087311.63
      2325502.71      7087283.18      2325385.21      7087167.76
      2325367.16      7087160.59      2325329.00      7087160.00

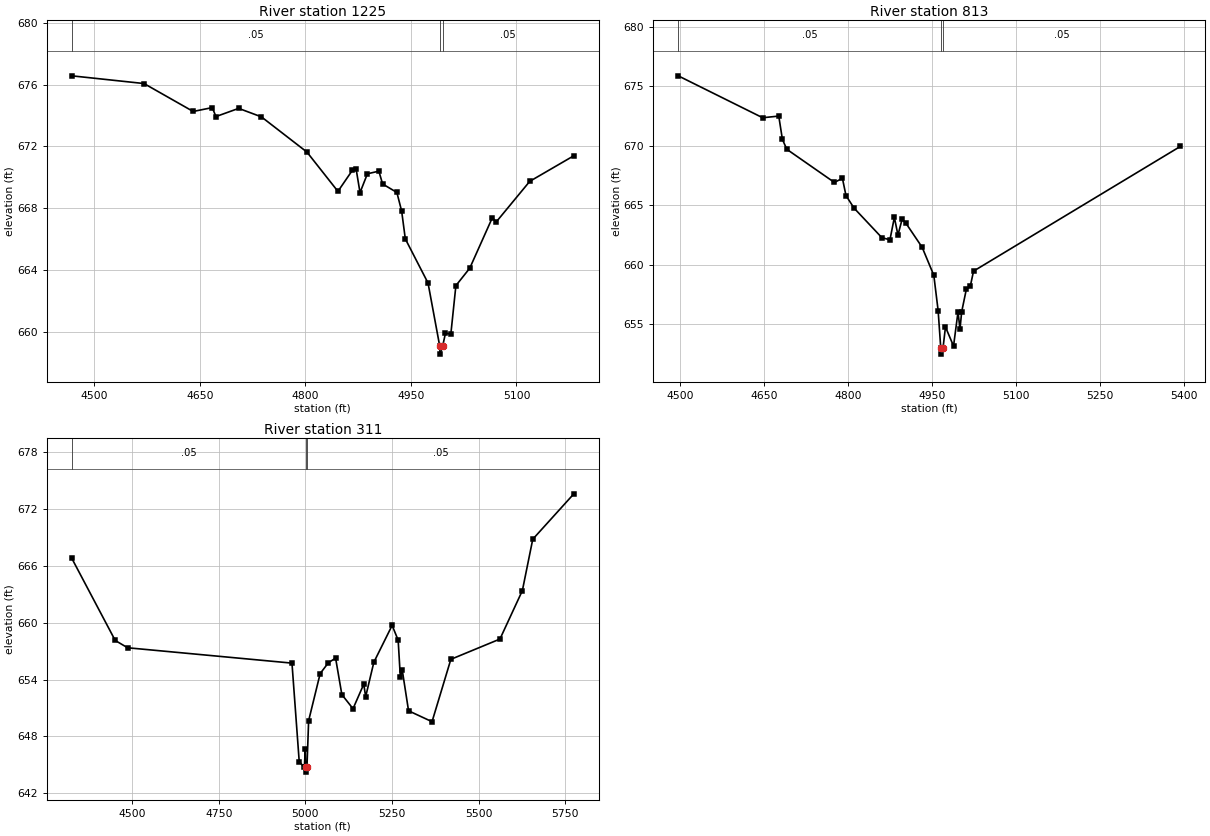
Type RM Length L Ch R = 1,1225,412,412,412
BEGIN DESCRIPTION:
MDW T 056 2.0
END DESCRIPTION:
XS GIS Cut Line= 3
      2325899.82      7088306.56      2325392.29      7088146.41
      2325219.26      7088091.28
#Sta/Elev= 30
  4467.8  676.58  4570.5  676.08  4640.4  674.27  4667.5  674.52  4672.8  673.94
  4705.1  674.47  4737.4  673.92  4802.1  671.64  4846.2  669.09  4866.8  670.46
  4872.1  670.53  4877.6  669.01  4888.1  670.23  4904.4  670.40  4909.7  669.57
  4930.0  669.02  4936.8  667.81  4942.0  666.01  4974.3  663.15  4991.0  659.04
  4991.2  658.54  4995.0  659.04  4999.1  659.90  5006.7  659.83  5013.9  662.98
  5033.6  664.11  5065.8  667.39  5071.1  667.10  5118.9  669.74  5181.6  671.40
#Mann=3,-1,0
  4467.8    0.05       0  4991.0    0.04       0  4995.0    0.05       0
Bank Sta=4991,4995
Exp/Cntr=0.3,0.1

Type RM Length L Ch R = 1,813,502,502,502
BEGIN DESCRIPTION:
MDW T 056 1.0
END DESCRIPTION:
XS GIS Cut Line= 3
      2325919.76      7088120.86      2325528.57      7087804.82
      2325195.81      7088014.11
#Sta/Elev= 30
  4497.1  675.88  4647.8  672.36  4676.5  672.50  4683.0  670.54  4690.9  669.71
  4775.7  666.93  4790.1  667.27  4796.5  665.82  4810.9  664.77  4860.5  662.29
  4874.9  662.11  4882.8  663.99  4889.2  662.51  4896.6  663.83  4903.6  663.49
  4932.4  661.48  4953.2  659.13  4960.9  656.17  4965.6  653.01  4965.8  652.51
  4969.6  653.01  4974.0  654.79  4988.4  653.19  4996.4  656.06  4999.9  654.60
  5002.9  656.06  5011.3  657.97  5018.2  658.19  5024.1  659.48  5393.1  669.95
#Mann=3,-1,0
  4497.1    0.05       0  4965.6    0.04       0  4969.6    0.05       0
Bank Sta=4965.6,4969.6
Exp/Cntr=0.3,0.1

Type RM Length L Ch R = 1,311,0,0,0
BEGIN DESCRIPTION:
MDW T 056 0.5
END DESCRIPTION:
XS GIS Cut Line= 4
      2325151.48      7087916.44      2325535.15      7087362.17
      2325638.77      7087392.70      2325899.18      7088006.85
#Sta/Elev= 30
  4325.9  666.79  4451.3  658.12  4487.1  657.35  4961.5  655.73  4982.4  645.34
  4997.3  644.73  5000.0  646.71  5000.7  644.73  5001.0  644.23  5004.7  644.73
  5009.6  649.66  5042.9  654.63  5066.6  655.77  5087.4  656.26  5105.5  652.41
  5137.7  650.92  5168.7  653.51  5174.2  652.19  5197.8  655.82  5250.6  659.71
  5268.0  658.15  5274.3  654.25  5279.7  655.02  5298.0  650.70  5365.8  649.55
  5420.1  656.13  5561.8  658.27  5626.5  663.38  5656.5  668.80  5775.1  673.59
#Mann=3,-1,0
  4325.9    0.05       0  5000.7    0.04       0  5004.7    0.05       0
Bank Sta=5000.7,5004.7
Exp/Cntr=0.3,0.1

Chan Stop Cuts=-1