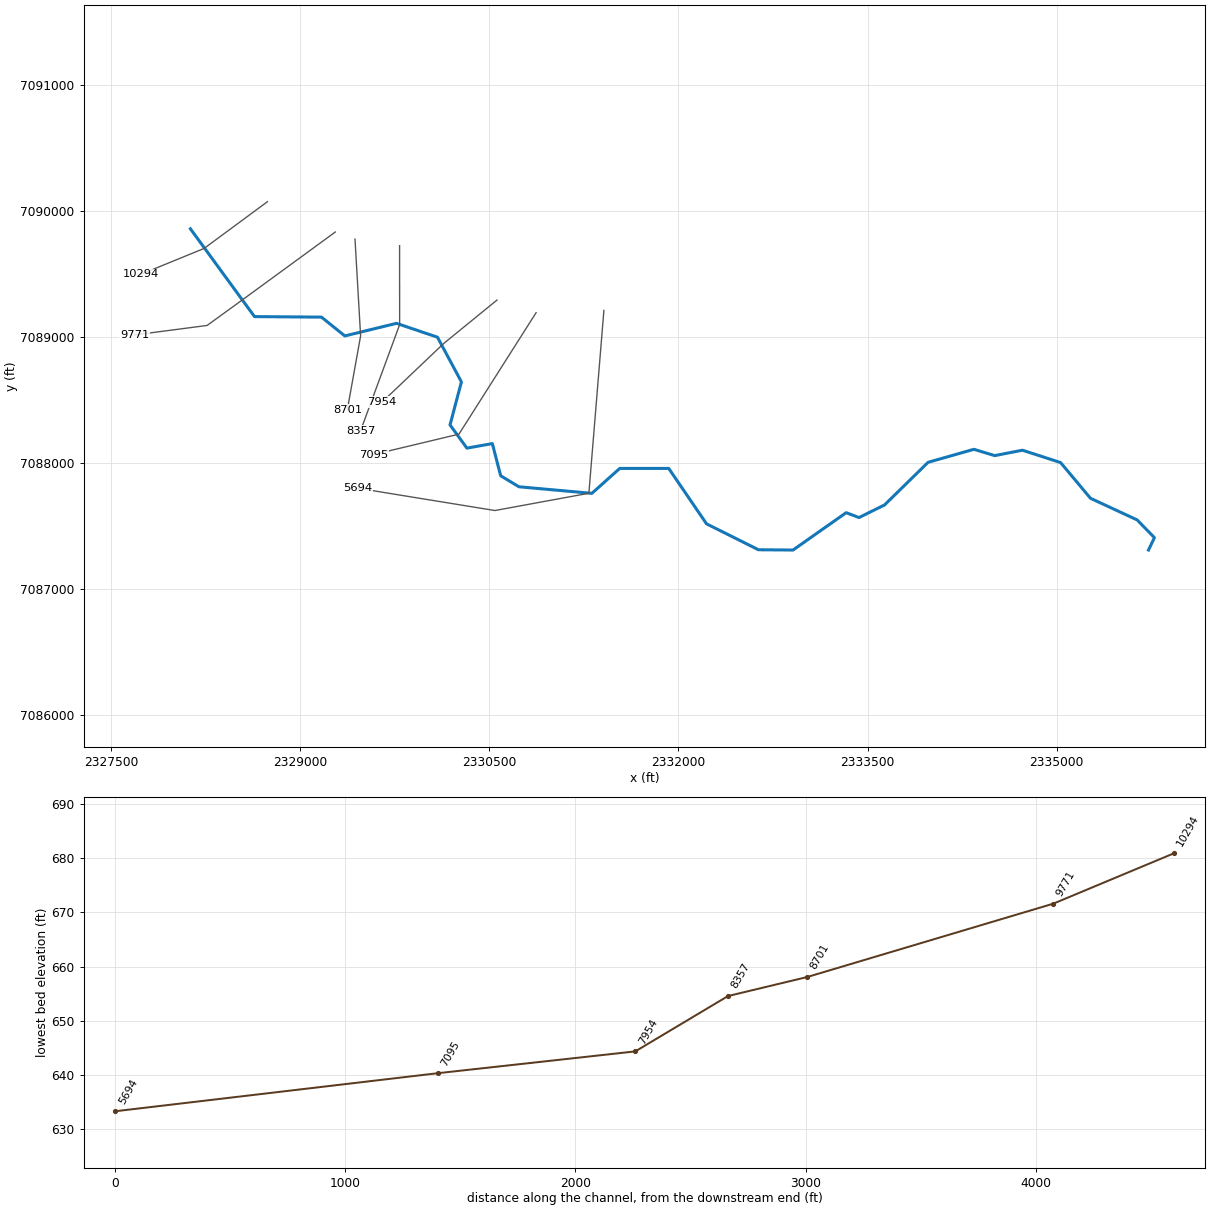
--- MDW T 057.prj (project) ---

Proj Title=MDW T 057 Base Level Engineering
Current Plan=p01
Default Exp/Contr=0.3,0.1
English Units
Geom File=g01
Flow File=f01
Plan File=p01
BEGIN DESCRIPTION:
MDW T 057
END DESCRIPTION:

--- MDW T 057.p01 (plan) ---

Plan Title=Multiple Run
Short Identifier=Multiple
Geom File=g01
Flow File=f01
Subcritical Flow
K Sum by GR= 0
Std Step Tol= 0.01
Critical Tol= 0.01
Num of Std Step Trials= 20
Max Error Tol= 0.3
Flow Tol Ratio= 0.001
Split Flow NTrial= 30
Split Flow Tol= 0.02
Split Flow Ratio= 0.02
Log Output Level= 0
Friction Slope Method= 1
Unsteady Friction Slope Method= 2
Unsteady Bridges Friction Slope Method= 1
Parabolic Critical Depth
Global Vel Dist=  1 , 1 , 1
Global Log Level= 0
CheckData=True
Encroach Param= -1, 0, 0, 0
BEGIN DESCRIPTION:
Multiple Run
END DESCRIPTION:

--- MDW T 057.f01 (steady flow) ---

Flow Title=Multiple
Number of Profiles=7
Profile Names=10-year,25-year,50-year,1pct_min,100-year,1pct_plu,500-year
River Rch & RM= MDW T 057,Reach-1,10294
     528     717     871     526    1050    2095    1526
Boundary for River Rch & Prof#=MDW T 057,Reach-1,1
Up Type=0
Dn Type=3
Dn Slope=0.005
Boundary for River Rch & Prof#=MDW T 057,Reach-1,2
Up Type=0
Dn Type=3
Dn Slope=0.005
Boundary for River Rch & Prof#=MDW T 057,Reach-1,3
Up Type=0
Dn Type=3
Dn Slope=0.005
Boundary for River Rch & Prof#=MDW T 057,Reach-1,4
Up Type=0
Dn Type=3
Dn Slope=0.005
Boundary for River Rch & Prof#=MDW T 057,Reach-1,5
Up Type=0
Dn Type=3
Dn Slope=0.005
Boundary for River Rch & Prof#=MDW T 057,Reach-1,6
Up Type=0
Dn Type=3
Dn Slope=0.005
Boundary for River Rch & Prof#=MDW T 057,Reach-1,7
Up Type=0
Dn Type=3
Dn Slope=0.005

--- MDW T 057.g01 (geometry) ---

Geom Title=Existing Conditions

River Reach=MDW T 057,Reach-1
Reach XY= 30
      2328129.00      7089860.00      2328637.30      7089163.07
      2329168.57      7089158.95      2329353.89      7089009.68
      2329763.73      7089109.62      2330088.81      7088999.49
      2330278.64      7088644.73      2330188.31      7088303.34
      2330321.98      7088119.01      2330523.92      7088154.97
      2330590.11      7087899.68      2330734.92      7087812.24
      2331313.61      7087760.08      2331534.67      7087958.02
      2331923.15      7087957.94      2332222.93      7087518.13
      2332634.90      7087312.23      2332909.02      7087309.96
      2333330.74      7087606.63      2333432.40      7087567.83
      2333635.17      7087667.86      2333980.50      7088006.39
      2334344.27      7088109.62      2334508.85      7088059.64
      2334729.00      7088102.44      2335031.43      7088004.48
      2335269.00      7087720.63      2335638.68      7087549.22
      2335775.93      7087408.42      2335729.00      7087310.00

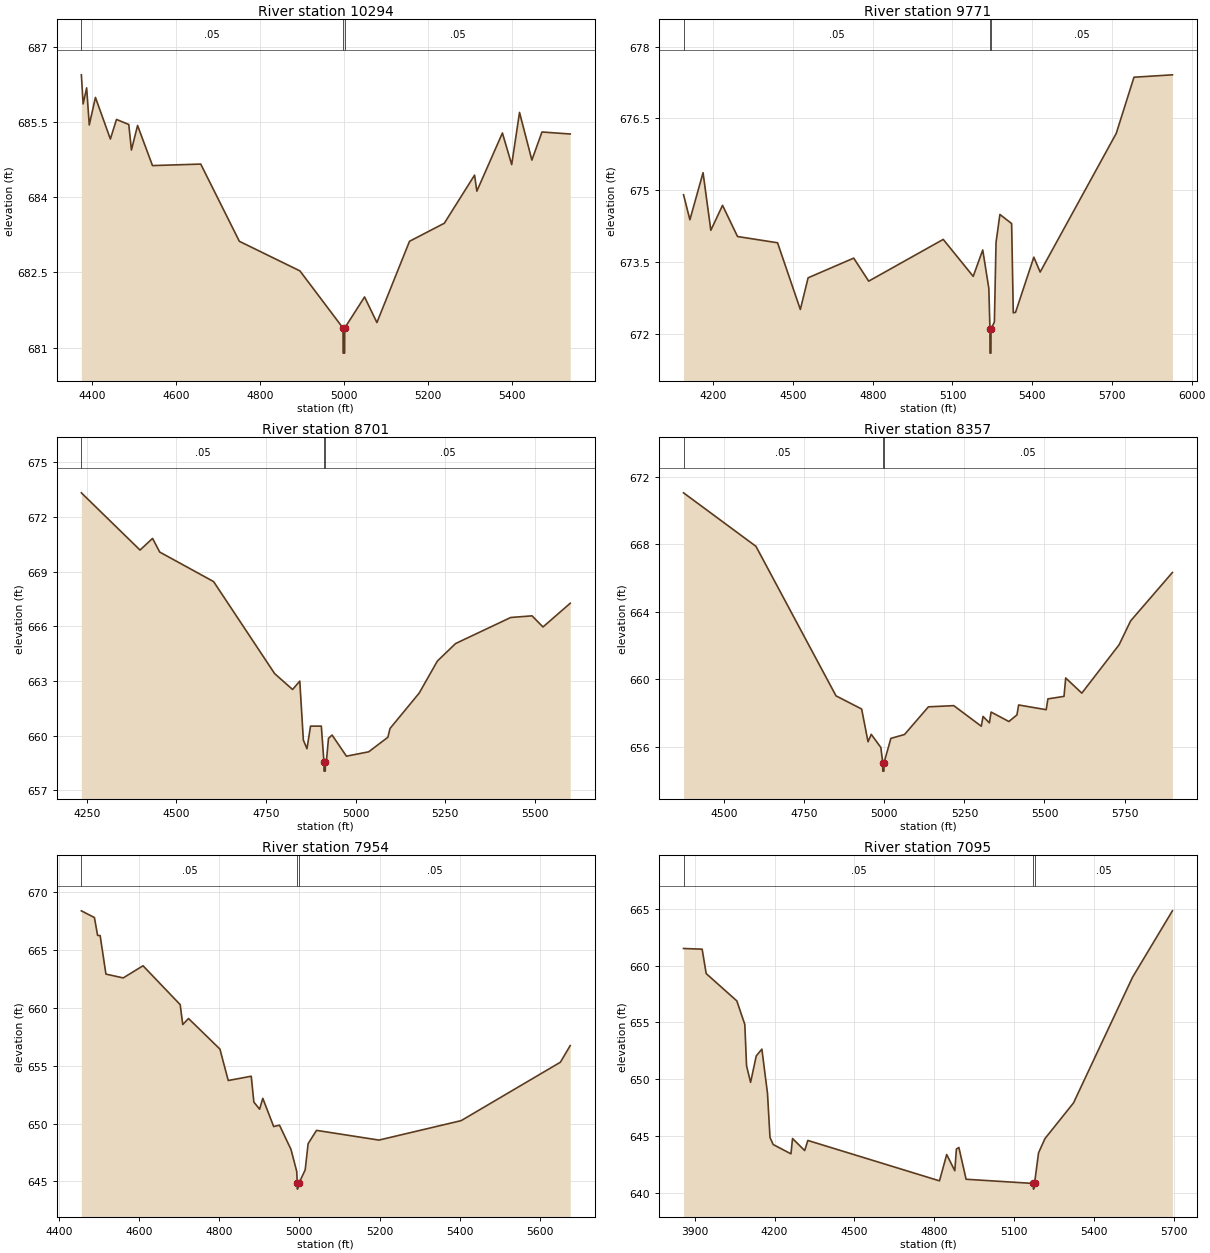
Type RM Length L Ch R = 1,10294,523,523,523
BEGIN DESCRIPTION:
MDW T 057 9.0
END DESCRIPTION:
XS GIS Cut Line= 3
      2328740.08      7090075.51      2328237.15      7089703.95
      2327739.67      7089500.44
#Sta/Elev= 30
  4374.7  686.44  4378.9  685.86  4387.3  686.18  4393.5  685.44  4408.2  685.99
  4443.7  685.16  4458.3  685.55  4487.5  685.45  4493.8  684.94  4508.4  685.43
  4543.9  684.63  4658.7  684.66  4750.5  683.12  4894.6  682.53  4997.1  681.39
  4997.4  680.89  5000.9  680.89  5001.1  681.39  5048.3  682.01  5077.7  681.50
  5155.2  683.12  5238.0  683.48  5310.0  684.44  5315.4  684.12  5376.2  685.28
  5398.3  684.65  5416.9  685.69  5446.3  684.74  5470.3  685.30  5537.5  685.26
#Mann=3,-1,0
  4374.7    0.05       0  4997.1   0.035       0  5001.1    0.05       0
Bank Sta=4997.1,5001.1
Exp/Cntr=0.3,0.1

Type RM Length L Ch R = 1,9771,1070,1070,1070
BEGIN DESCRIPTION:
MDW T 057 8.0
END DESCRIPTION:
XS GIS Cut Line= 4
      2329278.29      7089834.63      2328542.25      7089296.63
      2328261.17      7089092.87      2327685.67      7089017.35
#Sta/Elev= 30
  4088.3  674.91  4112.2  674.39  4161.7  675.37  4191.0  674.17  4235.0  674.69
  4291.4  674.04  4442.0  673.91  4527.7  672.52  4557.0  673.18  4728.5  673.59
  4784.9  673.11  5065.3  673.98  5178.1  673.21  5214.0  673.76  5236.9  672.96
  5241.1  672.11  5241.3  671.61  5244.8  671.61  5245.1  672.11  5257.8  672.26
  5264.0  673.92  5278.6  674.50  5322.7  674.31  5328.9  672.45  5337.4  672.46
  5406.2  673.61  5430.0  673.30  5716.3  676.19  5783.0  677.36  5927.6  677.41
#Mann=3,-1,0
  4088.3    0.05       0  5241.1   0.035       0  5245.1    0.05       0
Bank Sta=5241.1,5245.1
Exp/Cntr=0.3,0.1

Type RM Length L Ch R = 1,8701,344,344,344
BEGIN DESCRIPTION:
MDW T 057 7.0
END DESCRIPTION:
XS GIS Cut Line= 3
      2329434.53      7089778.25      2329479.00      7089010.00
      2329373.98      7088425.19
#Sta/Elev= 30
  4234.9  673.33  4398.6  670.19  4433.5  670.83  4453.5  670.08  4603.8  668.46
  4774.1  663.41  4824.1  662.54  4844.2  663.00  4854.2  659.76  4864.2  659.29
  4874.2  660.53  4904.3  660.53  4911.6  658.56  4911.8  658.06  4915.3  658.06
  4915.6  658.56  4918.6  658.63  4924.3  659.86  4934.3  660.04  4974.4  658.88
  5036.4  659.12  5090.0  659.92  5095.9  660.40  5177.2  662.34  5228.0  664.10
  5278.8  665.06  5432.5  666.49  5492.1  666.58  5522.6  665.97  5598.6  667.27
#Mann=3,-1,0
  4234.9    0.05       0  4911.6    0.04       0  4915.6    0.05       0
Bank Sta=4911.6,4915.6
Exp/Cntr=0.3,0.1

Type RM Length L Ch R = 1,8357,403,403,403
BEGIN DESCRIPTION:
MDW T 057 6.0
END DESCRIPTION:
XS GIS Cut Line= 3
      2329788.27      7089726.09      2329788.63      7089099.19
      2329477.99      7088254.93
#Sta/Elev= 30
  4373.1  671.04  4599.2  667.87  4849.2  659.01  4929.2  658.23  4949.2  656.29
  4959.2  656.73  4989.2  655.95  4995.1  655.05  4995.3  654.55  4998.8  654.55
  4999.1  655.05  5020.5  656.49  5063.1  656.72  5137.7  658.36  5216.9  658.43
  5302.9  657.21  5308.2  657.79  5328.1  657.41  5333.4  658.05  5389.0  657.49
  5414.1  657.88  5419.4  658.47  5505.5  658.19  5510.8  658.83  5561.1  658.98
  5566.4  660.07  5616.7  659.17  5733.2  662.04  5769.0  663.45  5899.6  666.32
#Mann=3,-1,0
  4373.1    0.05       0  4995.1   0.033       0  4999.1    0.05       0
Bank Sta=4995.1,4999.1
Exp/Cntr=0.3,0.1

Type RM Length L Ch R = 1,7954,859,859,859
BEGIN DESCRIPTION:
MDW T 057 5.0
END DESCRIPTION:
XS GIS Cut Line= 3
      2330560.83      7089294.27      2330139.12      7088950.62
      2329649.44      7088484.87
#Sta/Elev= 30
  4456.0  668.39  4488.6  667.81  4496.5  666.27  4502.9  666.25  4517.3  662.92
  4560.4  662.59  4609.9  663.64  4702.6  660.28  4709.0  658.56  4723.4  659.08
  4801.7  656.44  4822.5  653.72  4879.9  654.09  4886.4  651.86  4900.7  651.24
  4908.7  652.18  4935.9  649.74  4950.3  649.86  4979.0  647.77  4993.4  645.86
  4994.8  644.83  4995.1  644.33  4998.8  644.83  5014.5  646.00  5021.8  648.26
  5042.8  649.41  5198.5  648.57  5403.6  650.25  5651.2  655.30  5675.8  656.74
#Mann=3,-1,0
  4456.0    0.05       0  4994.8    0.04       0  4998.8    0.05       0
Bank Sta=4994.8,4998.8
Exp/Cntr=0.3,0.1

Type RM Length L Ch R = 1,7095,1401,1401,1401
BEGIN DESCRIPTION:
MDW T 057 4.0
END DESCRIPTION:
XS GIS Cut Line= 3
      2330871.17      7089194.45      2330259.12      7088230.07
      2329583.09      7088068.37
#Sta/Elev= 30
  3857.8  661.51  3927.7  661.45  3942.9  659.30  4058.1  656.89  4088.1  654.81
  4094.6  651.17  4109.8  649.71  4131.0  652.04  4152.2  652.64  4173.3  648.74
  4182.7  644.86  4194.7  644.23  4261.5  643.41  4267.4  644.76  4313.1  643.70
  4325.0  644.59  4819.7  641.03  4846.8  643.35  4877.3  641.92  4883.2  643.83
  4892.6  643.97  4919.7  641.17  5172.9  640.80  5173.2  640.30  5176.9  640.80
  5192.0  643.50  5216.0  644.75  5323.4  647.90  5545.1  658.97  5695.1  664.83
#Mann=3,-1,0
  3857.8    0.05       0  5172.9   0.033       0  5176.9    0.05       0
Bank Sta=5172.9,5176.9
Exp/Cntr=0.3,0.1

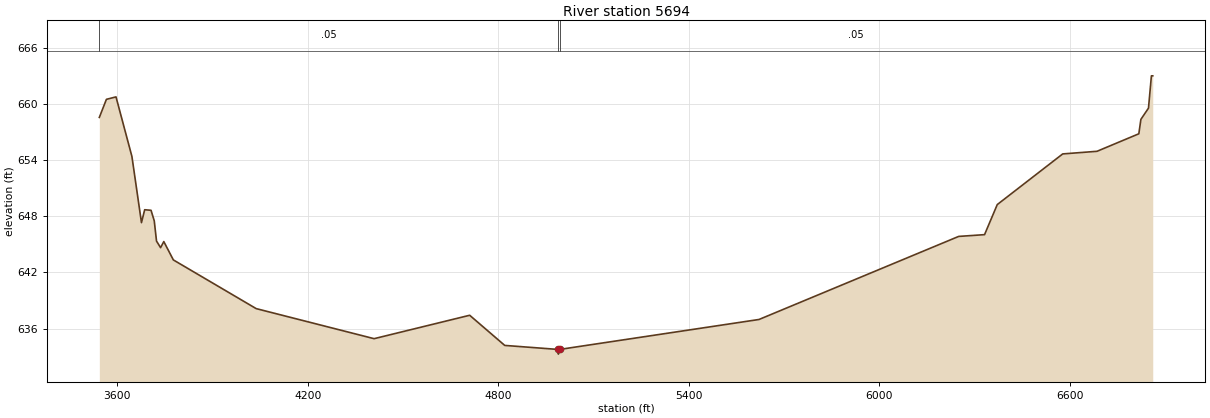
Type RM Length L Ch R = 1,5694,0,0,0
BEGIN DESCRIPTION:
MDW T 057 3.0
END DESCRIPTION:
XS GIS Cut Line= 4
      2331408.93      7089212.27      2331289.69      7087760.76
      2330544.34      7087623.69      2329455.80      7087800.78
#Sta/Elev= 30
  3543.6  658.56  3565.9  660.49  3596.1  660.75  3646.2  654.39  3676.3  647.32
  3686.4  648.70  3706.4  648.64  3716.5  647.52  3723.7  645.35  3736.5  644.65
  3746.6  645.30  3776.7  643.34  4037.5  638.14  4408.8  634.93  4709.8  637.43
  4820.2  634.21  4988.7  633.78  4989.0  633.28  4992.7  633.78  5620.9  636.98
  6249.6  645.85  6331.1  646.04  6371.1  649.25  6577.2  654.66  6685.2  654.94
  6816.9  656.81  6823.4  658.35  6847.3  659.55  6856.5  663.00  6860.7  663.00
#Mann=3,-1,0
  3543.6    0.05       0  4988.7   0.035       0  4992.7    0.05       0
Bank Sta=4988.7,4992.7
Exp/Cntr=0.3,0.1

Chan Stop Cuts=-1