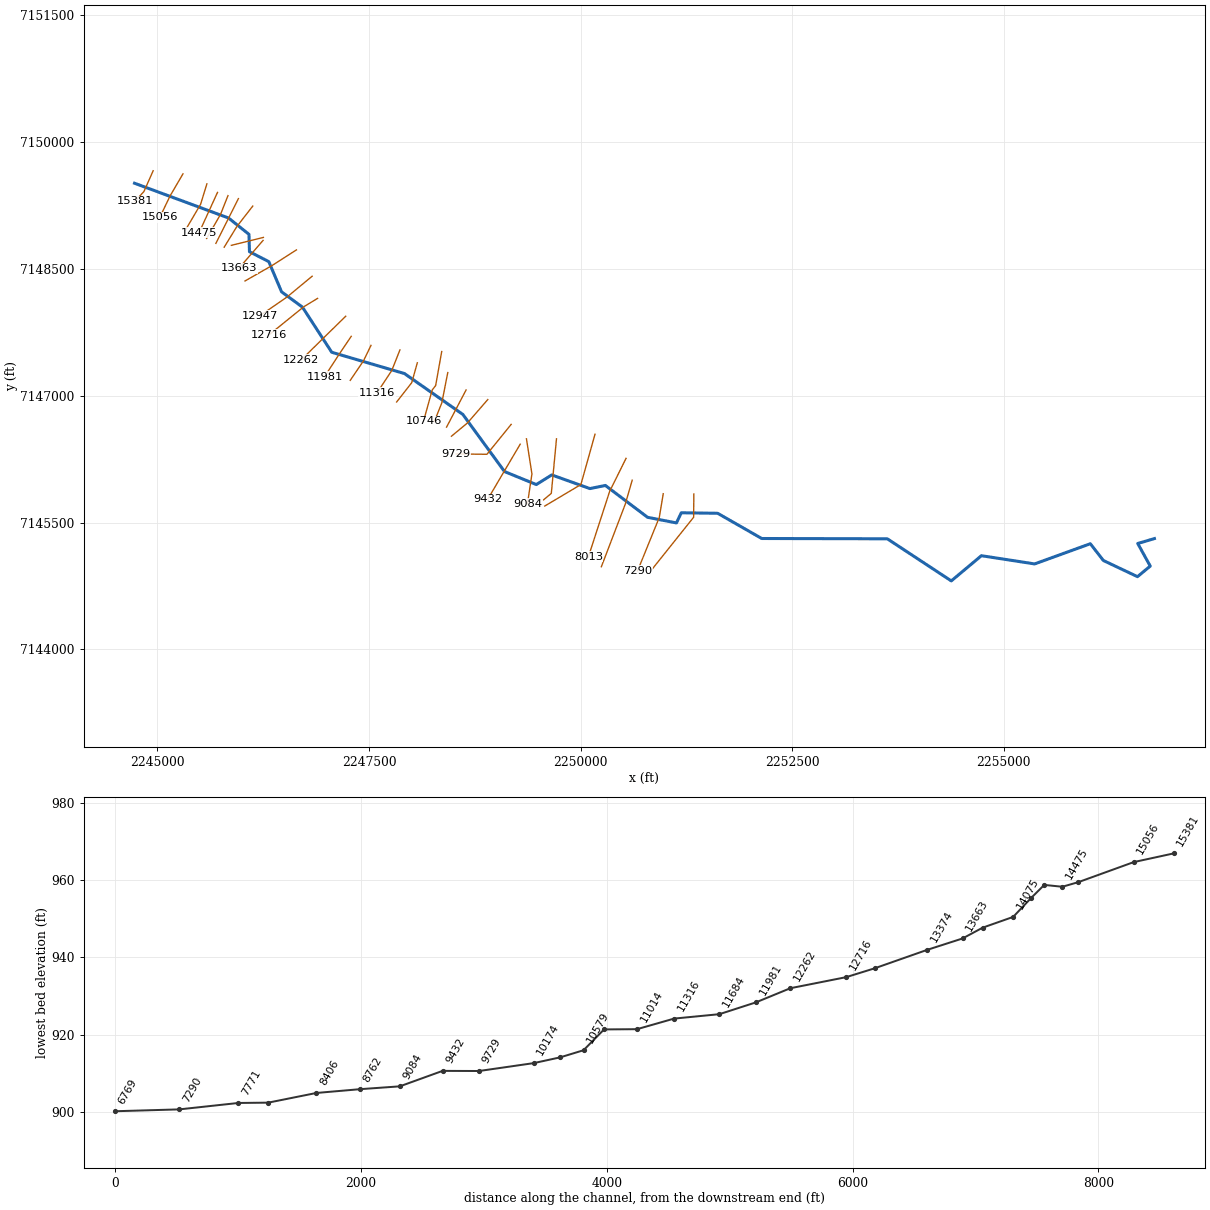
--- MDW T 059.prj (project) ---

Proj Title=MDW T 059 Base Level Engineering
Current Plan=p01
Default Exp/Contr=0.3,0.1
English Units
Geom File=g01
Flow File=f01
Plan File=p01
BEGIN DESCRIPTION:
MDW T 059
END DESCRIPTION:

--- MDW T 059.p01 (plan) ---

Plan Title=Multiple Run
Short Identifier=Multiple
Geom File=g01
Flow File=f01
Subcritical Flow
K Sum by GR= 0
Std Step Tol= 0.01
Critical Tol= 0.01
Num of Std Step Trials= 20
Max Error Tol= 0.3
Flow Tol Ratio= 0.001
Split Flow NTrial= 30
Split Flow Tol= 0.02
Split Flow Ratio= 0.02
Log Output Level= 0
Friction Slope Method= 1
Unsteady Friction Slope Method= 2
Unsteady Bridges Friction Slope Method= 1
Parabolic Critical Depth
Global Vel Dist=  1 , 1 , 1
Global Log Level= 0
CheckData=True
Encroach Param= -1, 0, 0, 0
BEGIN DESCRIPTION:
Multiple Run
END DESCRIPTION:

--- MDW T 059.f01 (steady flow) ---

Flow Title=Multiple
Number of Profiles=7
Profile Names=10-year,25-year,50-year,1pct_min,100-year,1pct_plu,500-year
River Rch & RM= MDW T 059,Reach-1,15381
     664     920    1135     696    1388    2770    2082
River Rch & RM= MDW T 059,Reach-1,12262
     871    1225    1525     943    1881    3754    2869
River Rch & RM= MDW T 059,Reach-1,9432
    1116    1590    1997    1244    2482    4953    3845
River Rch & RM= MDW T 059,Reach-1,7771
    1455    2099    2659    1669    3329    6643    5236
River Rch & RM= MDW T 059,Reach-1,6319
    1580    2286    2902    1824    3640    7262    5743
River Rch & RM= MDW T 059,Reach-1,5437
    1611    2328    2951    1852    3695    7373    5813
River Rch & RM= MDW T 059,Reach-1,3213
    1761    2557    3252    2048    4086    8152    6468
River Rch & RM= MDW T 059,Reach-1,283
    2613    3864    4975    3168    6321   12611   10235
Boundary for River Rch & Prof#=MDW T 059,Reach-1,1
Up Type=0
Dn Type=3
Dn Slope=0.005
Boundary for River Rch & Prof#=MDW T 059,Reach-1,2
Up Type=0
Dn Type=3
Dn Slope=0.005
Boundary for River Rch & Prof#=MDW T 059,Reach-1,3
Up Type=0
Dn Type=3
Dn Slope=0.005
Boundary for River Rch & Prof#=MDW T 059,Reach-1,4
Up Type=0
Dn Type=3
Dn Slope=0.005
Boundary for River Rch & Prof#=MDW T 059,Reach-1,5
Up Type=0
Dn Type=3
Dn Slope=0.005
Boundary for River Rch & Prof#=MDW T 059,Reach-1,6
Up Type=0
Dn Type=3
Dn Slope=0.005
Boundary for River Rch & Prof#=MDW T 059,Reach-1,7
Up Type=0
Dn Type=3
Dn Slope=0.005

--- MDW T 059.g01 (geometry) ---

Geom Title=Existing Conditions

River Reach=MDW T 059,Reach-1
Reach XY= 30
      2244729.00      7149510.00      2245838.98      7149099.31
      2246081.18      7148906.29      2246086.92      7148700.73
      2246315.23      7148583.36      2246466.21      7148226.64
      2246712.93      7148045.62      2247059.00      7147512.16
      2247917.77      7147260.85      2248607.86      7146777.66
      2249100.13      7146102.52      2249475.69      7145948.65
      2249658.33      7146062.50      2250109.40      7145901.03
      2250291.72      7145938.08      2250790.83      7145561.62
      2251131.40      7145495.26      2251188.91      7145615.11
      2251618.54      7145609.18      2252139.54      7145311.09
      2253623.03      7145307.67      2254379.00      7144810.00
      2254734.85      7145107.94      2255363.79      7145010.51
      2256021.67      7145249.47      2256176.18      7145050.86
      2256579.00      7144860.00      2256729.66      7144985.00
      2256581.92      7145252.03      2256779.00      7145310.00

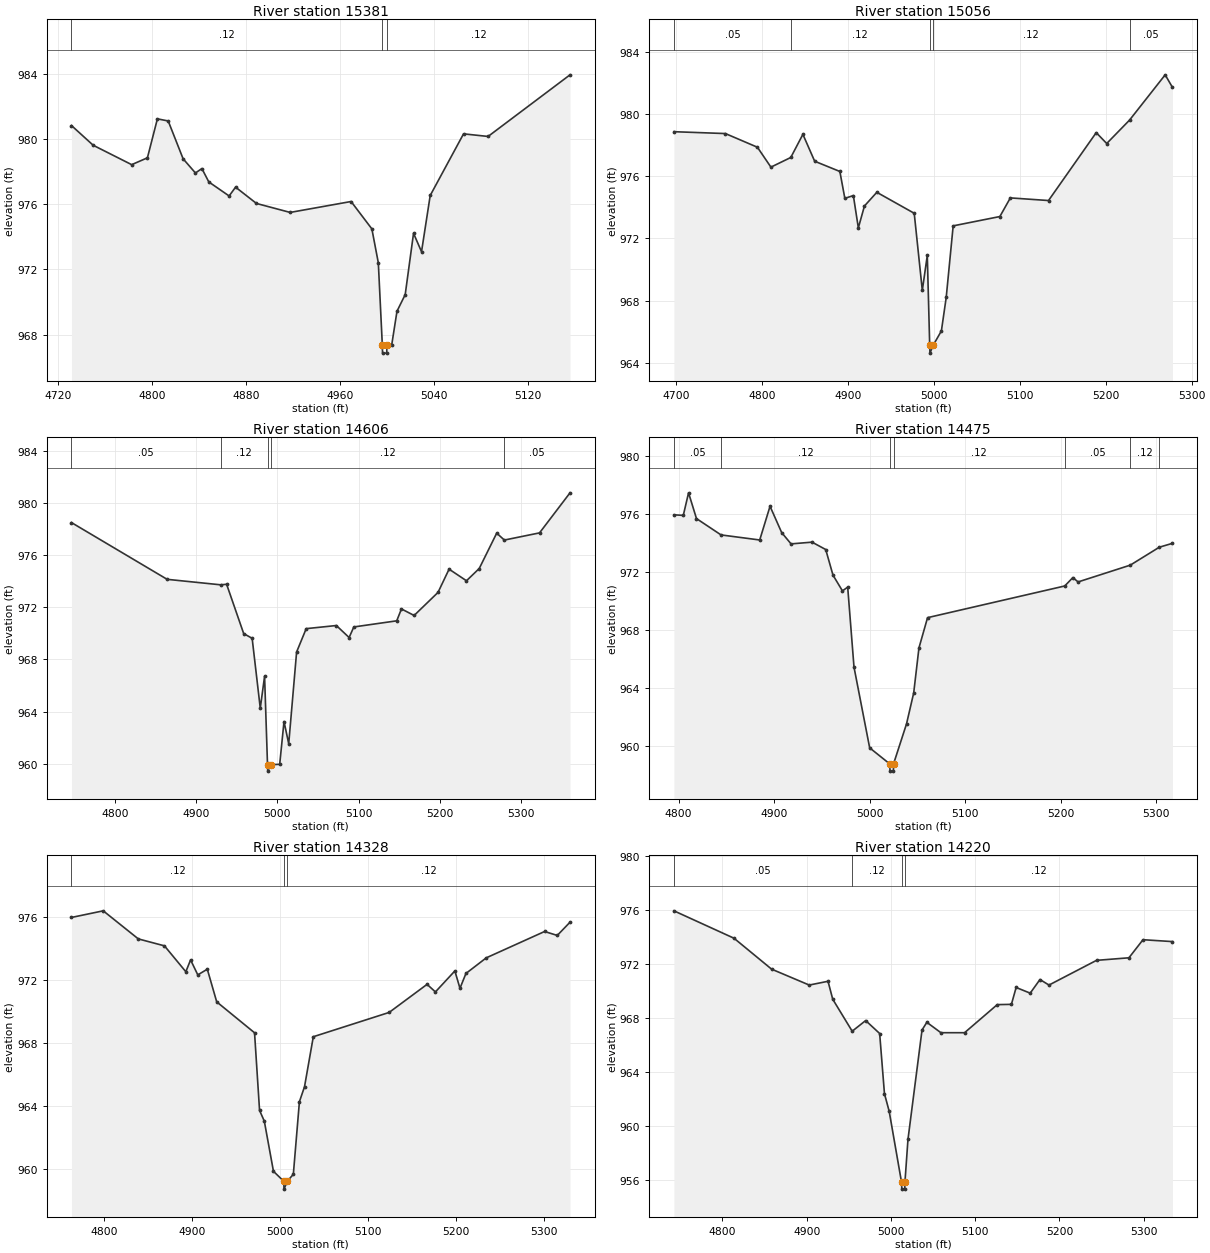
Type RM Length L Ch R = 1,15381,325,325,325
BEGIN DESCRIPTION:
MDW T 059 36.0
END DESCRIPTION:
XS GIS Cut Line= 3
      2244949.06      7149656.90      2244839.62      7149411.49
      2244733.90      7149296.78
#Sta/Elev= 30
  4731.3  980.83  4749.8  979.62  4782.6  978.43  4796.0  978.85  4804.5  981.24
  4813.7  981.11  4826.4  978.79  4836.9  977.92  4842.4  978.19  4848.3  977.37
  4865.6  976.51  4871.1  977.05  4888.9  976.05  4917.6  975.50  4969.5  976.17
  4987.2  974.49  4992.7  972.41  4996.1  967.37  4996.3  966.87  4999.8  966.87
  5000.1  967.37  5004.1  967.37  5008.6  969.44  5015.6  970.46  5022.7  974.22
  5029.5  973.09  5036.9  976.54  5065.3  980.32  5086.2  980.16  5156.0  983.94
#Mann=3,-1,0
  4731.3    0.12       0  4996.1    0.07       0  5000.1    0.12       0
Bank Sta=4996.1,5000.1
Exp/Cntr=0.3,0.1

Type RM Length L Ch R = 1,15056,450,450,450
BEGIN DESCRIPTION:
MDW T 059 35.0
END DESCRIPTION:
XS GIS Cut Line= 3
      2245301.51      7149621.35      2245149.16      7149360.37
      2245029.00      7149110.01
#Sta/Elev= 30
  4697.8  978.87  4757.7  978.75  4794.9  977.87  4810.6  976.59  4833.7  977.21
  4847.8  978.70  4861.5  976.97  4890.8  976.31  4896.6  974.58  4906.5  974.76
  4912.3  972.68  4919.4  974.09  4933.8  974.97  4977.3  973.62  4986.7  968.66
  4992.5  970.91  4995.3  965.12  4995.6  964.62  4999.3  965.12  5008.9  966.05
  5014.5  968.20  5022.6  972.81  5076.9  973.41  5089.1  974.61  5133.5  974.44
  5189.0  978.81  5201.2  978.11  5227.8  979.62  5269.2  982.53  5277.7  981.72
#Mann=5,-1,0
  4697.8    0.05       0  4833.7    0.12       0  4995.3    0.07       0
  4999.3    0.12       0  5227.8    0.05       0
Bank Sta=4995.3,4999.3
Exp/Cntr=0.3,0.1

Type RM Length L Ch R = 1,14606,131,131,131
BEGIN DESCRIPTION:
MDW T 059 34.0
END DESCRIPTION:
XS GIS Cut Line= 3
      2245583.75      7149502.48      2245509.37      7149260.78
      2245326.58      7148950.04
#Sta/Elev= 30
  4746.7  978.49  4864.4  974.14  4930.2  973.72  4937.6  973.76  4958.6  969.98
  4969.0  969.62  4979.0  964.26  4984.3  966.71  4987.9  959.94  4988.2  959.44
  4991.9  959.94  5002.9  959.96  5008.2  963.24  5014.0  961.54  5023.7  968.57
  5035.5  970.36  5072.6  970.60  5088.3  969.68  5094.1  970.49  5146.9  970.96
  5152.7  971.87  5168.3  971.37  5197.7  973.14  5211.3  974.92  5232.7  974.03
  5248.4  974.97  5269.9  977.68  5279.3  977.15  5322.6  977.70  5360.1  980.77
#Mann=5,-1,0
  4746.7    0.05       0  4930.2    0.12       0  4987.9    0.07       0
  4991.9    0.12       0  5279.3    0.05       0
Bank Sta=4987.9,4991.9
Exp/Cntr=0.3,0.1

Type RM Length L Ch R = 1,14475,147,147,147
BEGIN DESCRIPTION:
Mapping XS f256793a
END DESCRIPTION:
XS GIS Cut Line= 2
      2245709.16      7149401.46      2245492.17      7148926.81
#Sta/Elev= 30
  4795.2  975.96  4805.0  975.92  4810.5  977.48  4818.8  975.70  4844.5  974.57
  4885.0  974.22  4895.8  976.55  4908.0  974.73  4917.8  973.95  4939.8  974.07
  4954.1  973.56  4961.7  971.79  4971.6  970.70  4977.1  970.96  4983.7  965.43
  5000.1  959.85  5021.1  958.74  5021.4  958.24  5024.9  958.24  5025.1  958.74
  5038.7  961.51  5046.2  963.65  5051.7  966.76  5060.7  968.85  5204.3  971.04
  5212.8  971.62  5218.3  971.32  5272.9  972.48  5303.3  973.72  5317.1  973.99
#Mann=7,-1,0
  4795.2    0.05       0  4844.5    0.12       0  5021.1    0.07       0
  5025.1    0.12       0  5204.3    0.05       0  5272.9    0.12       0
  5303.3    0.05       0
Bank Sta=5021.1,5025.1
Exp/Cntr=0.3,0.1

Type RM Length L Ch R = 1,14328,108,108,108
BEGIN DESCRIPTION:
MDW T 059 33.0
END DESCRIPTION:
XS GIS Cut Line= 3
      2245832.76      7149363.55      2245745.52      7149142.98
      2245581.03      7148857.47
#Sta/Elev= 30
  4762.8  975.94  4798.9  976.36  4838.8  974.58  4868.5  974.14  4892.8  972.50
  4898.2  973.25  4906.4  972.30  4917.2  972.66  4927.9  970.59  4970.9  968.63
  4976.6  963.71  4982.0  963.03  4992.4  959.85  5004.1  959.22  5004.4  958.72
  5008.1  959.22  5015.0  959.66  5021.9  964.26  5027.7  965.21  5037.7  968.38
  5123.9  969.92  5167.0  971.70  5176.5  971.22  5198.6  972.55  5204.4  971.45
  5211.2  972.39  5234.3  973.38  5300.6  975.05  5315.0  974.80  5329.5  975.64
#Mann=3,-1,0
  4762.8    0.12       0  5004.1    0.07       0  5008.1    0.12       0
Bank Sta=5004.1,5008.1
Exp/Cntr=0.3,0.1

Type RM Length L Ch R = 1,14220,145,145,145
BEGIN DESCRIPTION:
Mapping XS 1624cf78
END DESCRIPTION:
XS GIS Cut Line= 2
      2245956.27      7149328.20      2245690.45      7148799.45
#Sta/Elev= 30
  4742.4  975.92  4813.7  973.89  4858.3  971.60  4903.0  970.42  4925.3  970.70
  4930.9  969.37  4954.0  967.00  4970.0  967.79  4986.6  966.83  4992.3  962.37
  4997.9  961.07  5012.6  955.80  5012.9  955.30  5016.4  955.30  5016.6  955.80
  5020.2  958.98  5036.9  967.09  5042.6  967.66  5059.3  966.89  5087.4  966.89
  5126.2  968.97  5143.0  968.99  5148.6  970.24  5165.3  969.82  5176.9  970.83
  5187.6  970.42  5244.0  972.25  5282.5  972.44  5299.2  973.78  5334.2  973.64
#Mann=4,-1,0
  4742.4    0.05       0  4954.0    0.12       0  5012.6    0.07       0
  5016.6    0.12       0
Bank Sta=5012.6,5016.6
Exp/Cntr=0.3,0.1

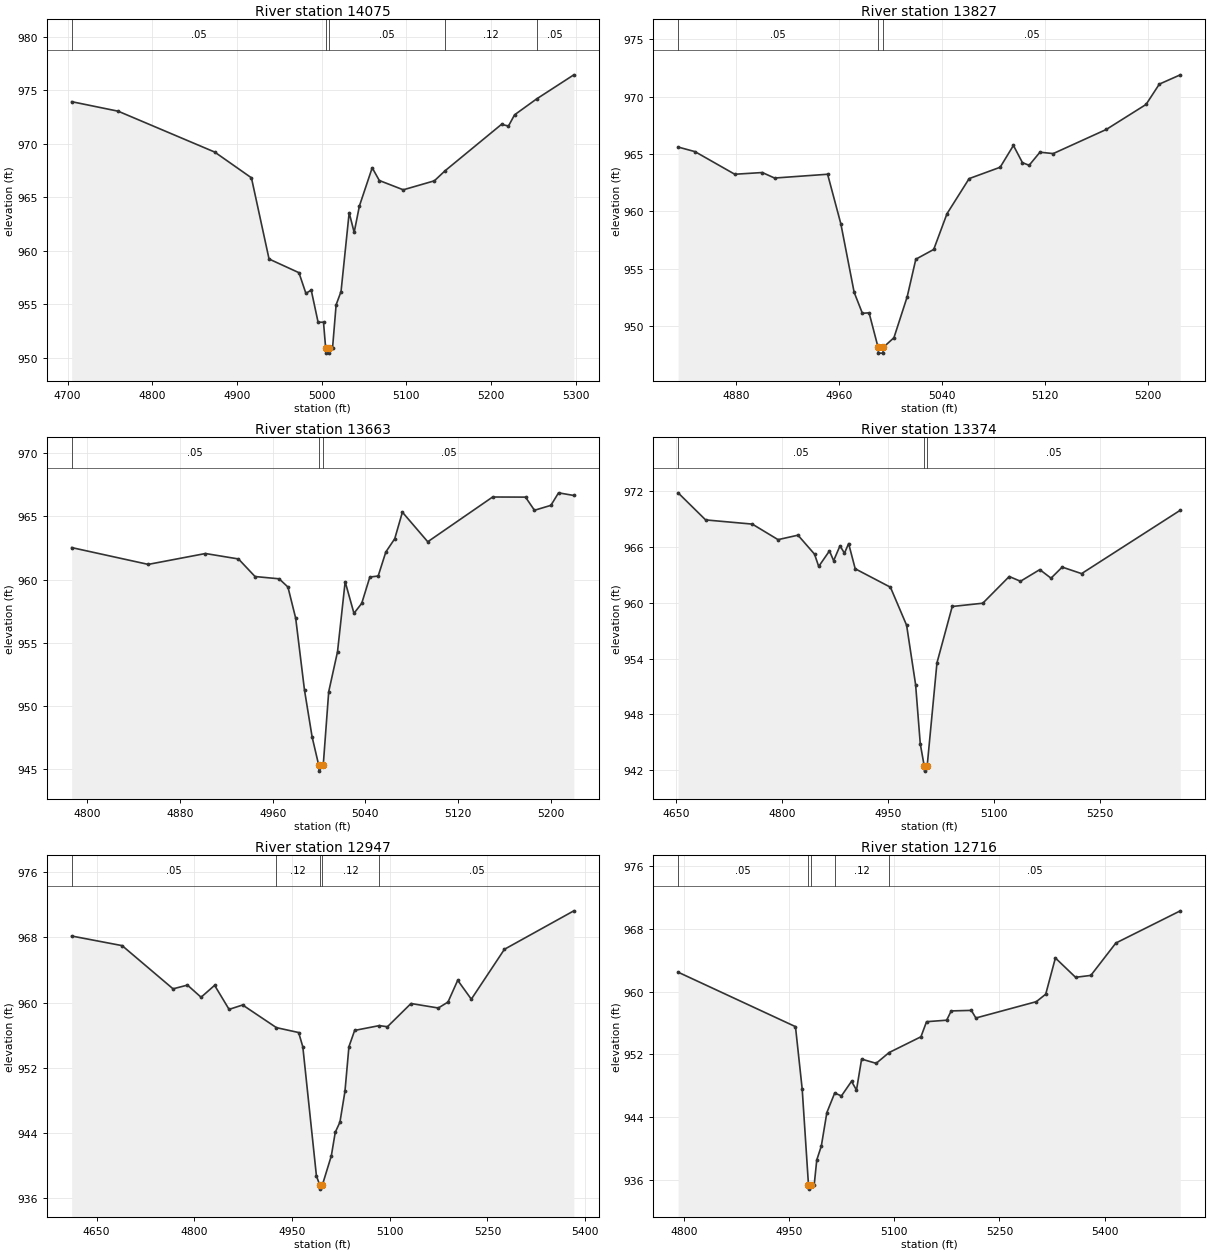
Type RM Length L Ch R = 1,14075,248,248,248
BEGIN DESCRIPTION:
MDW T 059 32.0
END DESCRIPTION:
XS GIS Cut Line= 3
      2246126.18      7149240.28      2245938.42      7148999.11
      2245788.16      7148754.17
#Sta/Elev= 30
  4704.7  973.95  4759.6  973.06  4873.6  969.24  4917.0  966.83  4937.8  959.24
  4973.1  957.96  4981.3  956.03  4987.6  956.33  4995.7  953.33  5002.1  953.33
  5004.6  950.94  5004.9  950.44  5008.4  950.44  5008.6  950.94  5012.8  950.94
  5017.0  954.96  5022.8  956.20  5032.4  963.57  5038.3  961.73  5044.5  964.20
  5059.6  967.77  5068.0  966.58  5096.3  965.71  5133.0  966.55  5145.5  967.48
  5212.3  971.83  5220.5  971.67  5227.7  972.72  5253.8  974.21  5297.7  976.46
#Mann=5,-1,0
  4704.7    0.05       0  5004.6   0.033       0  5008.6    0.05       0
  5145.5    0.12       0  5253.8    0.05       0
Bank Sta=5004.6,5008.6
Exp/Cntr=0.3,0.1

Type RM Length L Ch R = 1,13827,164,164,164
BEGIN DESCRIPTION:
Mapping XS 393d764c
END DESCRIPTION:
XS GIS Cut Line= 2
      2246251.74      7148869.66      2245873.14      7148776.04
#Sta/Elev= 30
  4835.1  965.61  4848.2  965.21  4879.1  963.24  4900.5  963.39  4910.0  962.91
  4951.2  963.24  4961.5  958.91  4971.8  952.96  4978.2  951.13  4983.4  951.17
  4990.4  948.16  4990.7  947.66  4994.2  947.66  4994.4  948.16  5002.7  949.00
  5013.0  952.57  5019.7  955.84  5033.6  956.69  5043.9  959.80  5061.1  962.86
  5085.2  963.85  5095.5  965.75  5102.5  964.25  5107.7  964.02  5116.1  965.16
  5126.4  965.04  5167.6  967.14  5198.5  969.32  5208.8  971.09  5225.1  971.90
#Mann=3,-1,0
  4835.1    0.05       0  4990.4   0.033       0  4994.4    0.05       0
Bank Sta=4990.4,4994.4
Exp/Cntr=0.3,0.1

Type RM Length L Ch R = 1,13663,289,289,289
BEGIN DESCRIPTION:
Mapping XS 8b69770c
END DESCRIPTION:
XS GIS Cut Line= 2
      2246247.83      7148834.41      2245963.67      7148507.03
#Sta/Elev= 30
  4786.5  962.54  4852.6  961.21  4902.0  962.07  4930.5  961.64  4944.8  960.25
  4965.6  960.07  4973.2  959.42  4979.9  956.95  4987.5  951.26  4994.1  947.55
  4999.7  945.36  5000.0  944.86  5003.7  945.36  5008.4  951.14  5016.0  954.30
  5022.6  959.84  5030.2  957.34  5036.9  958.13  5043.9  960.21  5051.1  960.29
  5057.7  962.19  5065.4  963.24  5072.0  965.34  5093.9  963.00  5149.9  966.54
  5178.3  966.53  5186.0  965.49  5200.2  965.88  5206.8  966.87  5220.0  966.66
#Mann=3,-1,0
  4786.5    0.05       0  4999.7   0.033       0  5003.7    0.05       0
Bank Sta=4999.7,5003.7
Exp/Cntr=0.3,0.1

Type RM Length L Ch R = 1,13374,427,427,427
BEGIN DESCRIPTION:
MDW T 059 30.0
END DESCRIPTION:
XS GIS Cut Line= 3
      2246641.76      7148722.00      2246352.86      7148536.93
      2246034.15      7148354.96
#Sta/Elev= 30
  4653.2  971.80  4692.1  968.89  4758.1  968.44  4794.5  966.77  4822.7  967.25
  4846.1  965.21  4852.0  963.89  4867.2  965.56  4873.1  964.51  4882.1  966.11
  4888.4  965.31  4894.3  966.35  4903.6  963.64  4953.4  961.66  4976.3  957.57
  4989.0  951.20  4995.6  944.84  5001.3  942.40  5001.6  941.90  5005.3  942.40
  5019.2  953.53  5040.8  959.59  5084.0  959.94  5121.4  962.81  5137.3  962.30
  5164.6  963.55  5180.5  962.63  5196.3  963.82  5223.7  963.12  5363.3  969.93
#Mann=3,-1,0
  4653.2    0.05       0  5001.3   0.033       0  5005.3    0.05       0
Bank Sta=5001.3,5005.3
Exp/Cntr=0.3,0.1

Type RM Length L Ch R = 1,12947,231,231,231
BEGIN DESCRIPTION:
MDW T 059 29.0
END DESCRIPTION:
XS GIS Cut Line= 3
      2246827.56      7148411.27      2246531.45      7148165.85
      2246213.46      7147946.32
#Sta/Elev= 30
  4611.7  968.18  4689.2  967.00  4767.4  961.70  4789.5  962.16  4810.4  960.67
  4831.2  962.13  4853.4  959.18  4874.2  959.72  4926.1  956.94  4960.2  956.34
  4966.6  954.59  4987.5  938.75  4992.6  937.63  4992.9  937.13  4996.6  937.63
  5010.4  941.22  5016.4  944.10  5023.6  945.35  5031.3  949.12  5037.4  954.60
  5046.2  956.60  5084.0  957.19  5096.5  957.05  5132.7  959.90  5174.6  959.35
  5189.5  960.08  5204.4  962.75  5225.3  960.43  5276.1  966.55  5382.7  971.27
#Mann=5,-1,0
  4611.7    0.05       0  4926.1    0.12       0  4992.6    0.07       0
  4996.6    0.12       0  5084.0    0.05       0
Bank Sta=4992.6,4996.6
Exp/Cntr=0.3,0.1

Type RM Length L Ch R = 1,12716,454,454,454
BEGIN DESCRIPTION:
MDW T 059 28.0
END DESCRIPTION:
XS GIS Cut Line= 3
      2246891.80      7148149.11      2246728.01      7148049.73
      2246319.69      7147719.38
#Sta/Elev= 30
  4791.4  962.46  4958.9  955.53  4968.5  947.59  4977.5  935.35  4977.7  934.85
  4981.5  935.35  4985.6  935.35  4989.3  938.56  4995.8  940.33  5003.7  944.59
  5014.9  947.08  5024.5  946.71  5038.9  948.57  5046.0  947.46  5053.3  951.40
  5074.1  950.86  5092.5  952.23  5138.0  954.24  5146.0  956.16  5174.7  956.35
  5181.2  957.53  5209.9  957.60  5216.4  956.63  5302.7  958.71  5316.1  959.66
  5329.9  964.27  5358.7  961.81  5380.5  962.05  5416.2  966.17  5508.2  970.27
#Mann=5,-1,0
  4791.4    0.05       0  4977.5   0.033       0  4981.5    0.05       0
  5014.9    0.12       0  5092.5    0.05       0
Bank Sta=4977.5,4981.5
Exp/Cntr=0.3,0.1

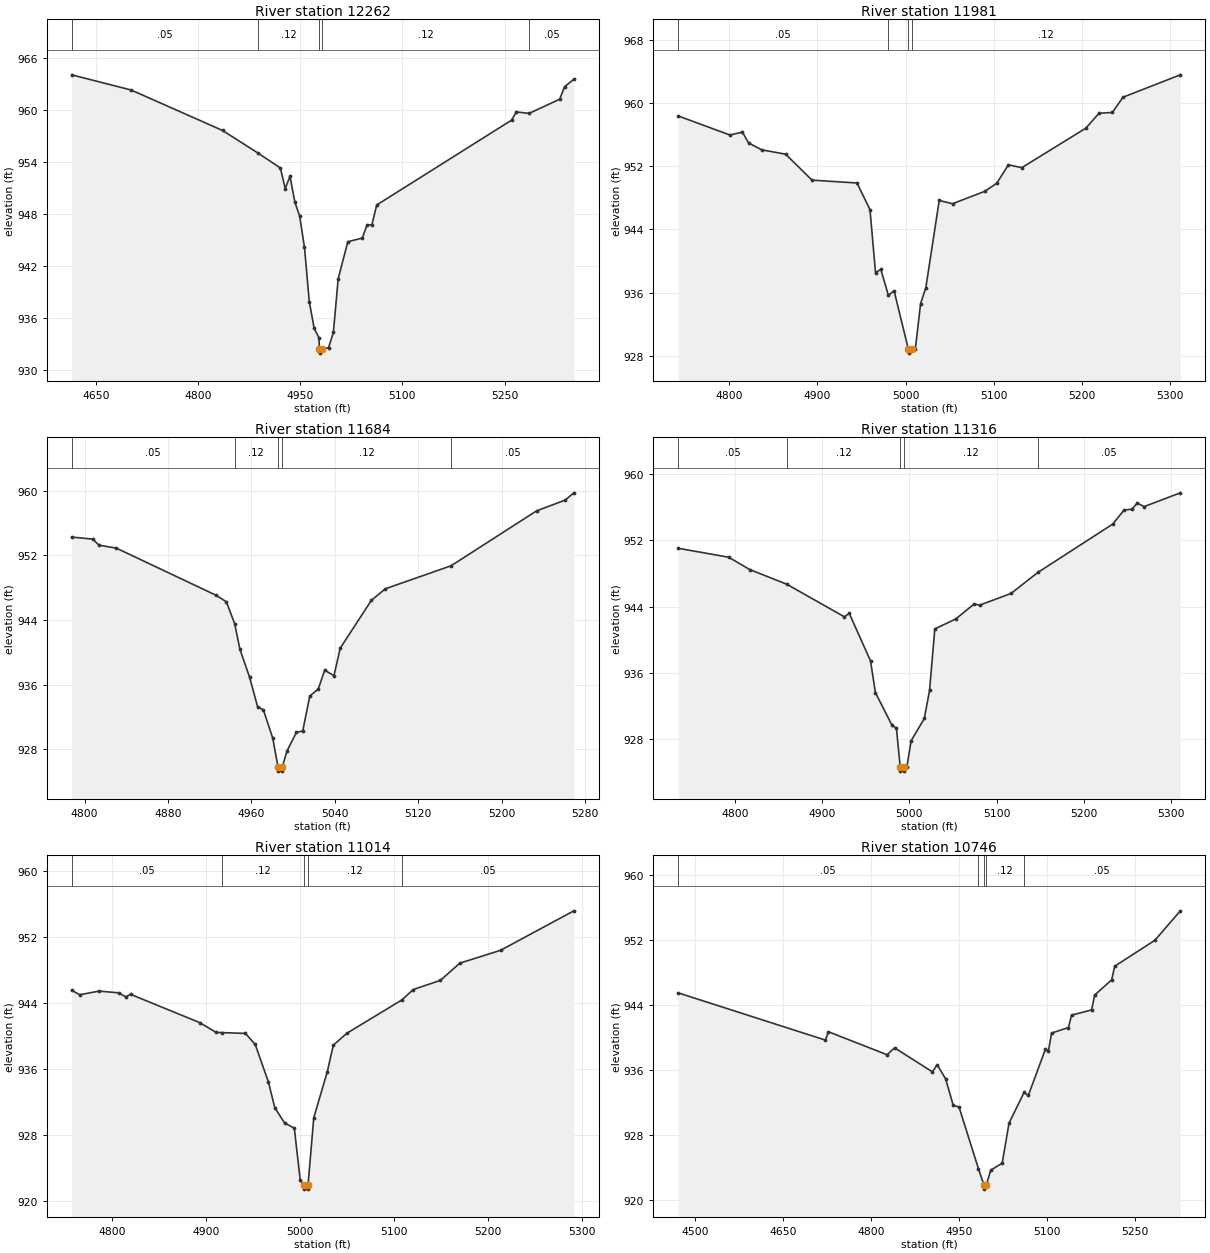
Type RM Length L Ch R = 1,12262,281,281,281
BEGIN DESCRIPTION:
MDW T 059 27.0
END DESCRIPTION:
XS GIS Cut Line= 3
      2247224.26      7147938.18      2246961.70      7147681.16
      2246697.94      7147421.70
#Sta/Elev= 30
  4614.4  964.10  4701.7  962.35  4836.0  957.68  4888.5  955.05  4920.9  953.35
  4928.0  950.98  4935.0  952.39  4942.2  949.40  4949.2  947.80  4956.3  944.19
  4963.3  937.94  4970.5  934.84  4977.5  933.78  4978.2  932.49  4978.5  931.99
  4982.2  932.49  4991.6  932.61  4998.7  934.38  5005.8  940.58  5019.9  944.84
  5041.2  945.27  5048.2  946.80  5055.3  946.79  5062.3  949.08  5260.3  958.87
  5267.4  959.82  5286.1  959.65  5331.1  961.29  5338.1  962.72  5351.8  963.59
#Mann=5,-1,0
  4614.4    0.05       0  4888.5    0.12       0  4978.2    0.07       0
  4982.2    0.12       0  5286.1    0.05       0
Bank Sta=4978.2,4982.2
Exp/Cntr=0.3,0.1

Type RM Length L Ch R = 1,11981,297,297,297
BEGIN DESCRIPTION:
MDW T 059 26.0
END DESCRIPTION:
XS GIS Cut Line= 3
      2247289.08      7147700.48      2247140.49      7147479.68
      2246975.22      7147225.53
#Sta/Elev= 30
  4742.0  958.39  4800.8  955.97  4814.9  956.34  4821.8  954.97  4836.8  954.09
  4863.9  953.54  4893.8  950.25  4944.8  949.89  4959.5  946.51  4965.8  938.53
  4971.8  938.93  4980.4  935.63  4986.8  936.24  5003.0  928.82  5003.2  928.32
  5007.0  928.82  5010.9  928.82  5016.9  934.61  5022.8  936.61  5038.0  947.67
  5053.1  947.26  5089.4  948.82  5103.2  949.85  5116.4  952.19  5131.6  951.83
  5204.0  956.82  5219.2  958.73  5234.3  958.83  5246.3  960.76  5311.3  963.60
#Mann=4,-1,0
  4742.0    0.05       0  4980.4    0.12       0  5003.0    0.07       0
  5007.0    0.12       0
Bank Sta=5003,5007
Exp/Cntr=0.3,0.1

Type RM Length L Ch R = 1,11684,368,368,368
BEGIN DESCRIPTION:
MDW T 059 25.0
END DESCRIPTION:
XS GIS Cut Line= 3
      2247522.58      7147593.58      2247434.94      7147412.27
      2247277.79      7147180.38
#Sta/Elev= 30
  4787.6  954.28  4807.8  954.02  4813.8  953.27  4830.4  952.91  4926.3  947.05
  4936.0  946.25  4943.9  943.54  4948.9  940.39  4958.2  936.91  4965.9  933.24
  4971.5  932.85  4980.4  929.36  4985.5  925.77  4985.7  925.27  4989.2  925.27
  4989.5  925.77  4994.2  927.80  5003.1  930.07  5009.2  930.25  5015.9  934.57
  5024.1  935.46  5030.2  937.78  5039.1  937.10  5045.1  940.51  5075.0  946.44
  5088.4  947.87  5151.4  950.72  5233.3  957.52  5260.8  958.86  5269.1  959.76
#Mann=5,-1,0
  4787.6    0.05       0  4943.9    0.12       0  4985.5    0.07       0
  4989.5    0.12       0  5151.4    0.05       0
Bank Sta=4985.5,4989.5
Exp/Cntr=0.3,0.1

Type RM Length L Ch R = 1,11316,302,302,302
BEGIN DESCRIPTION:
MDW T 059 24.0
END DESCRIPTION:
XS GIS Cut Line= 3
      2247864.57      7147540.24      2247769.37      7147298.43
      2247595.83      7147035.39
#Sta/Elev= 30
  4735.2  951.06  4793.0  949.98  4817.4  948.48  4859.7  946.71  4925.7  942.77
  4931.1  943.20  4955.5  937.45  4961.1  933.62  4979.9  929.71  4985.2  929.29
  4989.5  924.63  4989.8  924.13  4993.3  924.13  4993.5  924.63  4997.1  924.63
  5002.0  927.80  5017.1  930.49  5023.1  933.89  5029.1  941.31  5053.1  942.52
  5074.3  944.34  5080.3  944.18  5116.4  945.60  5147.1  948.14  5232.8  953.98
  5245.8  955.68  5254.9  955.78  5260.9  956.53  5268.7  956.09  5310.2  957.76
#Mann=5,-1,0
  4735.2    0.05       0  4859.7    0.12       0  4989.5    0.07       0
  4993.5    0.12       0  5147.1    0.05       0
Bank Sta=4989.5,4993.5
Exp/Cntr=0.3,0.1

Type RM Length L Ch R = 1,11014,268,268,268
BEGIN DESCRIPTION:
MDW T 059 23.0
END DESCRIPTION:
XS GIS Cut Line= 3
      2248070.14      7147388.18      2248004.16      7147152.75
      2247825.55      7146924.29
#Sta/Elev= 30
  4757.0  945.50  4765.5  944.95  4786.3  945.39  4807.0  945.18  4814.5  944.70
  4819.7  945.00  4893.1  941.58  4910.9  940.38  4917.1  940.36  4942.0  940.26
  4952.4  938.92  4966.5  934.35  4973.2  931.26  4983.6  929.42  4994.0  928.78
  5000.3  922.46  5004.6  921.89  5004.8  921.39  5008.3  921.39  5008.6  921.89
  5014.7  930.05  5029.1  935.62  5035.5  938.84  5049.9  940.28  5108.6  944.33
  5120.5  945.58  5149.4  946.69  5170.2  948.78  5213.6  950.34  5291.5  955.12
#Mann=5,-1,0
  4757.0    0.05       0  4917.1    0.12       0  5004.6    0.07       0
  5008.6    0.12       0  5108.6    0.05       0
Bank Sta=5004.6,5008.6
Exp/Cntr=0.3,0.1

Type RM Length L Ch R = 1,10746,167,167,167
BEGIN DESCRIPTION:
MDW T 059 22.5
END DESCRIPTION:
XS GIS Cut Line= 4
      2248358.32      7147520.94      2248286.72      7147118.84
      2248245.92      7147066.46      2248143.75      7146698.40
#Sta/Elev= 30
  4470.4  945.50  4721.7  939.68  4726.8  940.71  4826.9  937.88  4839.7  938.73
  4904.3  935.77  4912.4  936.66  4926.9  934.89  4939.8  931.64  4949.6  931.45
  4982.7  923.87  4992.2  921.83  4992.5  921.33  4996.2  921.83  5003.8  923.66
  5023.3  924.53  5035.0  929.46  5060.6  933.23  5067.9  932.87  5097.0  938.55
  5102.2  938.33  5107.6  940.55  5136.4  941.23  5141.6  942.75  5175.9  943.40
  5181.1  945.23  5210.1  947.10  5215.3  948.78  5283.9  951.98  5327.2  955.60
#Mann=5,-1,0
  4470.4    0.05       0  4982.7    0.12       0  4992.2    0.07       0
  4996.2    0.12       0  5060.6    0.05       0
Bank Sta=4992.2,4996.2
Exp/Cntr=0.3,0.1

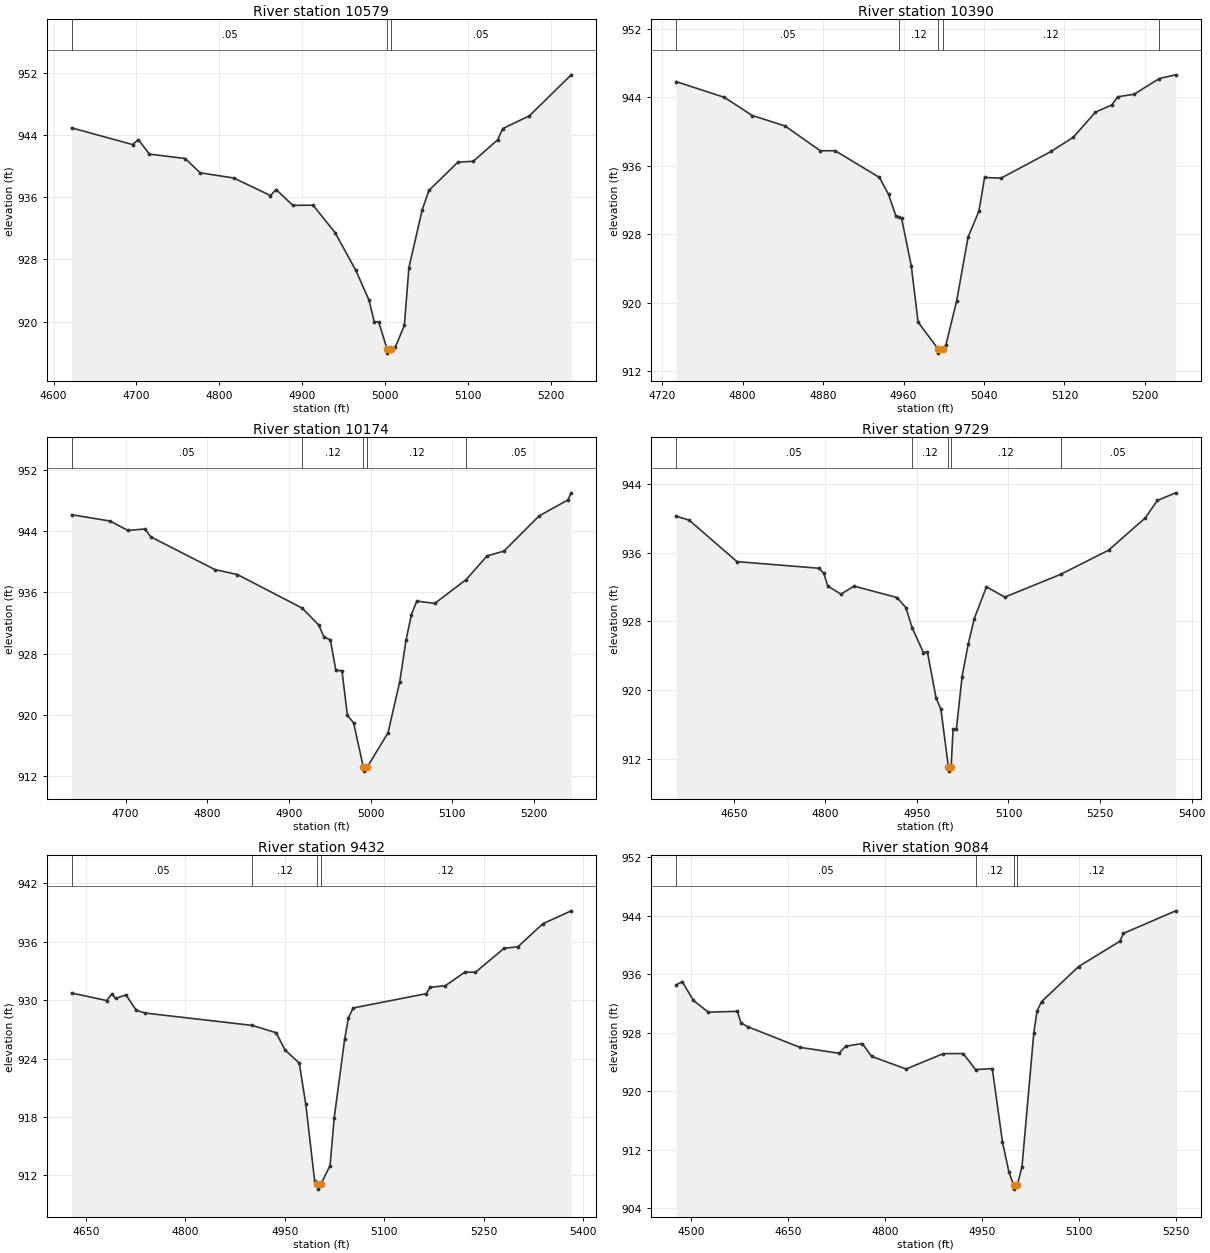
Type RM Length L Ch R = 1,10579,189,189,189
BEGIN DESCRIPTION:
MDW T 059 22.0
END DESCRIPTION:
XS GIS Cut Line= 3
      2248429.93      7147272.24      2248359.28      7146912.35
      2248270.50      7146693.31
#Sta/Elev= 30
  4621.6  944.93  4695.2  942.78  4702.3  943.41  4715.6  941.55  4758.8  940.98
  4776.7  939.15  4817.5  938.47  4861.7  936.22  4868.5  936.99  4888.8  934.95
  4913.1  934.98  4939.8  931.43  4964.6  926.61  4980.6  922.78  4987.0  919.97
  4992.3  919.97  5002.5  916.44  5002.9  915.94  5007.0  916.44  5012.5  916.74
  5023.3  919.50  5028.8  926.93  5044.8  934.37  5052.9  936.87  5088.0  940.52
  5106.5  940.62  5136.0  943.40  5142.0  944.83  5174.3  946.48  5224.7  951.75
#Mann=3,-1,0
  4621.6    0.05       0  5002.5   0.033       0  5007.0    0.05       0
Bank Sta=5002.5,5007
Exp/Cntr=0.3,0.1

Type RM Length L Ch R = 1,10390,216,216,216
BEGIN DESCRIPTION:
Mapping XS 16595df8
END DESCRIPTION:
XS GIS Cut Line= 2
      2248646.50      7147067.06      2248415.34      7146627.31
#Sta/Elev= 30
  4733.8  945.82  4781.7  943.99  4809.6  941.86  4842.2  940.64  4877.3  937.74
  4892.0  937.75  4936.0  934.63  4945.1  932.65  4952.4  930.13  4955.7  929.96
  4958.1  929.84  4967.7  924.32  4974.5  917.73  4994.3  914.61  4994.7  914.11
  4998.8  914.61  5002.2  915.08  5012.9  920.25  5024.2  927.67  5035.0  930.70
  5040.6  934.62  5057.0  934.55  5106.7  937.66  5128.8  939.32  5150.8  942.25
  5167.2  943.10  5172.9  944.04  5189.3  944.35  5214.4  946.18  5230.6  946.61
#Mann=5,-1,0
  4733.8    0.05       0  4955.7    0.12       0  4994.3    0.07       0
  4998.8    0.12       0  5214.4    0.05       0
Bank Sta=4994.3,4998.8
Exp/Cntr=0.3,0.1

Type RM Length L Ch R = 1,10174,445,445,445
BEGIN DESCRIPTION:
MDW T 059 21.0
END DESCRIPTION:
XS GIS Cut Line= 3
      2248902.59      7146953.26      2248662.32      7146676.66
      2248473.45      7146520.12
#Sta/Elev= 30
  4633.8  946.17  4680.9  945.34  4702.8  944.11  4723.7  944.30  4730.8  943.27
  4809.2  938.99  4836.8  938.34  4916.2  933.94  4936.4  931.74  4943.0  930.13
  4950.6  929.81  4957.3  925.85  4964.9  925.72  4971.5  919.91  4979.1  918.93
  4991.1  913.11  4991.6  912.61  4995.6  913.11  5021.2  917.62  5035.6  924.31
  5043.4  929.82  5049.9  933.10  5056.4  934.86  5078.5  934.56  5116.9  937.68
  5142.4  940.77  5163.2  941.41  5206.2  946.01  5241.3  948.09  5245.5  949.03
#Mann=5,-1,0
  4633.8    0.05       0  4916.2    0.12       0  4991.1    0.07       0
  4995.6    0.12       0  5116.9    0.05       0
Bank Sta=4991.1,4995.6
Exp/Cntr=0.3,0.1

Type RM Length L Ch R = 1,9729,297,297,297
BEGIN DESCRIPTION:
MDW T 059 20.0
END DESCRIPTION:
XS GIS Cut Line= 3
      2249179.01      7146660.02      2248892.62      7146306.46
      2248529.04      7146310.00
#Sta/Elev= 30
  4555.3  940.26  4576.9  939.79  4655.2  934.96  4789.5  934.19  4797.5  933.59
  4803.9  932.11  4825.6  931.18  4847.1  932.11  4917.4  930.78  4931.8  929.61
  4942.4  927.22  4960.6  924.38  4967.1  924.48  4981.4  919.07  4989.3  917.77
  5001.5  911.07  5001.9  910.57  5006.0  911.07  5009.2  915.44  5014.6  915.44
  5023.9  921.55  5033.9  925.32  5043.9  928.33  5063.9  932.03  5093.9  930.83
  5185.4  933.48  5263.9  936.29  5323.9  940.04  5343.9  942.08  5373.9  942.97
#Mann=5,-1,0
  4555.3    0.05       0  4942.4    0.12       0  5001.5    0.07       0
  5006.0    0.12       0  5185.4    0.05       0
Bank Sta=5001.5,5006
Exp/Cntr=0.3,0.1

Type RM Length L Ch R = 1,9432,348,348,348
BEGIN DESCRIPTION:
MDW T 059 19.0
END DESCRIPTION:
XS GIS Cut Line= 3
      2249285.71      7146425.75      2249095.39      7146103.47
      2248903.09      7145776.51
#Sta/Elev= 30
  4628.4  930.73  4681.5  929.95  4689.1  930.64  4694.9  930.17  4710.5  930.53
  4726.1  928.95  4739.6  928.67  4901.1  927.40  4937.0  926.65  4950.4  924.88
  4971.9  923.53  4981.7  919.30  4995.1  911.42  4999.2  911.10  4999.9  910.60
  5004.4  911.10  5018.3  913.02  5024.6  917.94  5040.3  925.98  5046.1  928.19
  5053.1  929.19  5163.3  930.66  5169.1  931.31  5192.3  931.48  5221.9  932.88
  5237.5  932.85  5280.5  935.30  5301.9  935.49  5339.1  937.83  5382.0  939.16
#Mann=4,-1,0
  4628.4    0.05       0  4901.1    0.12       0  4999.2    0.07       0
  5004.4    0.12       0
Bank Sta=4999.2,5004.4
Exp/Cntr=0.3,0.1

Type RM Length L Ch R = 1,9084,322,322,322
BEGIN DESCRIPTION:
Mapping XS e30b0d29
END DESCRIPTION:
XS GIS Cut Line= 3
      2249359.50      7146489.52      2249424.22      7146074.49
      2249372.06      7145724.60
#Sta/Elev= 30
  4476.5  934.49  4486.1  934.97  4503.5  932.39  4526.6  930.79  4571.4  930.90
  4577.2  929.34  4587.3  928.81  4668.3  925.98  4729.0  925.17  4739.2  926.13
  4764.9  926.50  4779.6  924.74  4832.8  923.02  4890.5  925.12  4921.3  925.13
  4940.4  922.94  4966.3  923.07  4982.0  913.08  4992.1  908.92  4999.5  907.10
  5000.3  906.60  5004.8  907.10  5012.3  909.68  5030.6  927.97  5035.6  930.96
  5042.6  932.23  5099.9  937.02  5164.0  940.49  5169.2  941.55  5250.3  944.64
#Mann=4,-1,0
  4476.5    0.05       0  4940.4    0.12       0  4999.5    0.07       0
  5004.8    0.12       0
Bank Sta=4999.5,5004.8
Exp/Cntr=0.3,0.1

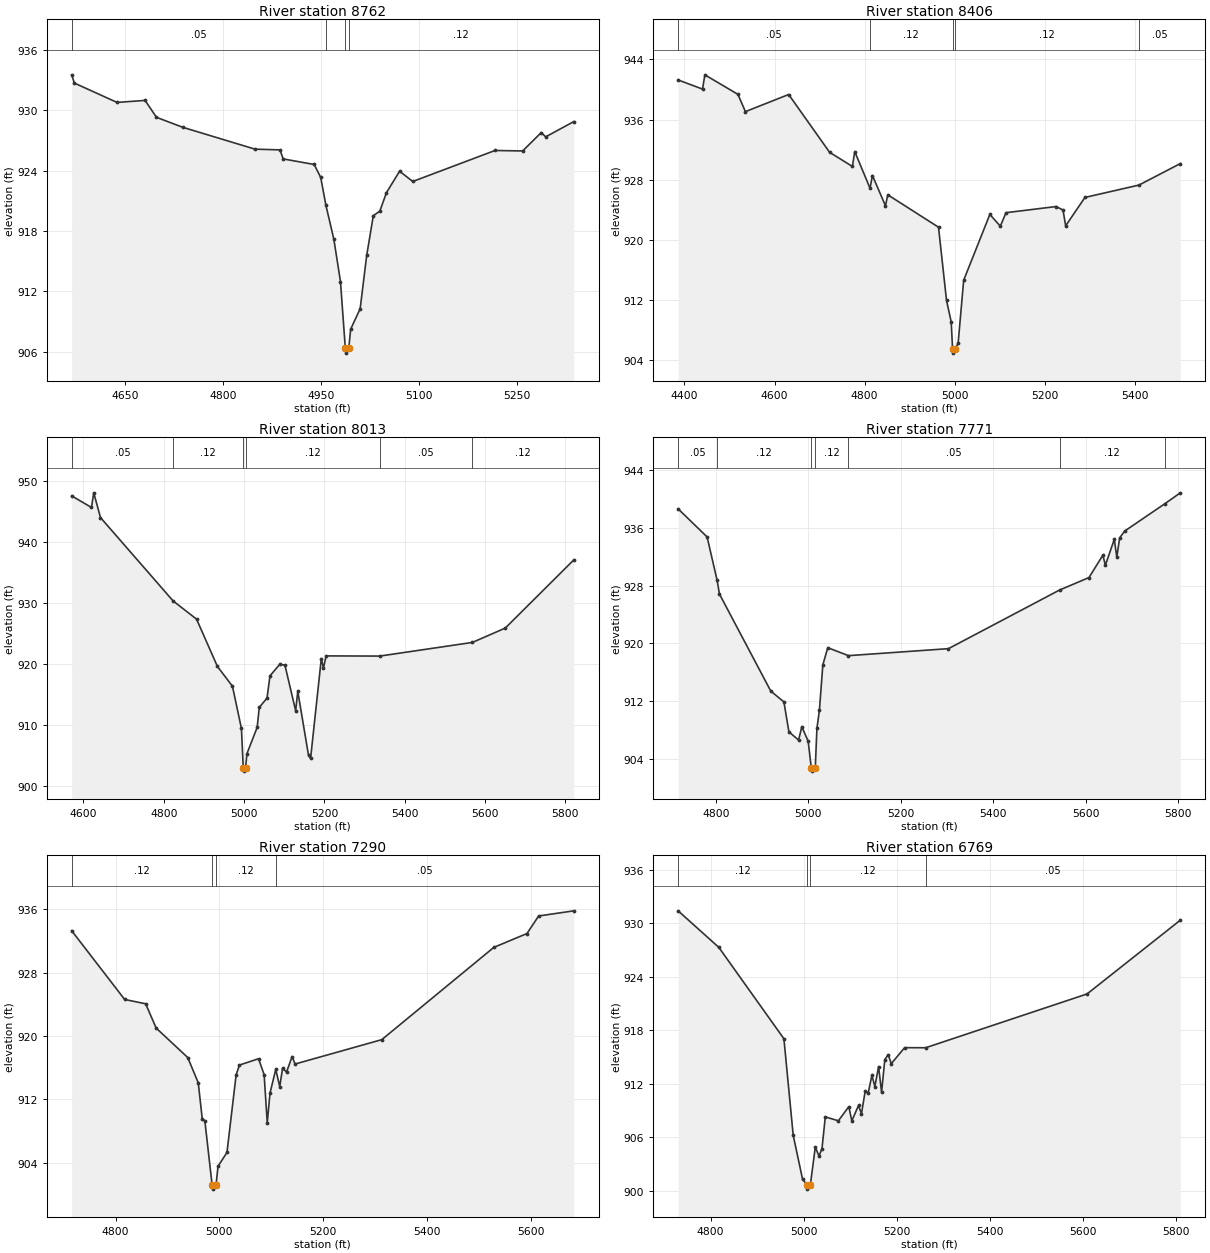
Type RM Length L Ch R = 1,8762,356,356,356
BEGIN DESCRIPTION:
Mapping XS 86ab096c
END DESCRIPTION:
XS GIS Cut Line= 3
      2249714.40      7146489.13      2249653.14      7145844.47
      2249560.76      7145767.51
#Sta/Elev= 30
  4568.6  933.50  4572.8  932.68  4638.0  930.76  4680.9  930.96  4698.3  929.28
  4738.5  928.29  4849.0  926.12  4887.1  926.05  4892.1  925.15  4939.4  924.60
  4949.4  923.31  4957.4  920.53  4969.5  917.17  4979.6  912.98  4987.0  906.37
  4987.7  905.87  4992.3  906.37  4995.2  908.25  5009.7  910.28  5019.7  915.57
  5029.8  919.51  5039.8  919.97  5049.9  921.80  5070.0  923.93  5090.1  922.91
  5215.9  925.99  5258.1  925.94  5286.6  927.77  5293.3  927.34  5336.4  928.86
#Mann=4,-1,0
  4568.6    0.05       0  4957.4    0.12       0  4987.0    0.07       0
  4992.3    0.12       0
Bank Sta=4987,4992.3
Exp/Cntr=0.3,0.1

Type RM Length L Ch R = 1,8406,393,393,393
BEGIN DESCRIPTION:
MDW T 059 17.0
END DESCRIPTION:
XS GIS Cut Line= 3
      2250169.59      7146543.88      2250002.57      7145948.59
      2249575.58      7145694.60
#Sta/Elev= 30
  4385.9  941.27  4440.1  940.05  4445.3  941.95  4518.7  939.35  4535.3  937.05
  4631.4  939.33  4722.3  931.63  4772.9  929.75  4778.1  931.73  4812.0  926.85
  4817.4  928.54  4846.3  924.51  4851.5  925.97  4964.1  921.66  4981.9  911.90
  4992.3  909.05  4995.4  905.39  4996.2  904.89  5001.0  905.39  5007.7  906.22
  5020.0  914.60  5078.1  923.36  5101.4  921.79  5113.9  923.59  5225.0  924.41
  5240.6  923.95  5246.4  921.84  5289.2  925.62  5409.2  927.27  5501.0  930.13
#Mann=5,-1,0
  4385.9    0.05       0  4812.0    0.12       0  4995.4    0.07       0
  5001.0    0.12       0  5409.2    0.05       0
Bank Sta=4995.4,5001
Exp/Cntr=0.3,0.1

Type RM Length L Ch R = 1,8013,242,242,242
BEGIN DESCRIPTION:
MDW T 059 16.5
END DESCRIPTION:
XS GIS Cut Line= 3
      2250536.34      7146258.48      2250343.20      7145870.02
      2250090.96      7145093.48
#Sta/Elev= 30
  4570.7  947.55  4620.1  945.65  4625.7  948.05  4642.5  943.99  4823.3  930.31
  4881.7  927.32  4933.6  919.56  4971.0  916.32  4993.4  909.38  4998.0  902.88
  4998.9  902.38  5003.6  902.88  5007.2  905.26  5032.6  909.56  5037.8  912.84
  5057.1  914.36  5064.5  918.02  5088.7  919.89  5101.7  919.77  5128.4  912.29
  5133.7  915.48  5160.4  904.98  5165.6  904.48  5192.3  920.86  5197.6  919.29
  5204.3  921.29  5337.7  921.26  5568.4  923.50  5650.2  925.85  5821.0  937.05
#Mann=6,-1,0
  4570.7    0.05       0  4823.3    0.12       0  4998.0    0.07       0
  5003.6    0.12       0  5337.7    0.05       0  5568.4    0.12       0
Bank Sta=4998,5003.6
Exp/Cntr=0.3,0.1

Type RM Length L Ch R = 1,7771,481,481,481
BEGIN DESCRIPTION:
MDW T 059 16.0
END DESCRIPTION:
XS GIS Cut Line= 3
      2250609.04      7146000.26      2250526.42      7145715.15
      2250244.63      7144977.48
#Sta/Elev= 30
  4718.3  938.64  4781.0  934.75  4802.6  928.76  4807.7  926.84  4918.8  913.39
  4947.2  911.89  4958.0  907.74  4978.9  906.61  4986.0  908.46  4999.7  906.43
  5006.3  902.80  5007.4  902.30  5013.8  902.80  5015.1  902.80  5018.6  908.21
  5024.0  910.74  5031.4  917.02  5042.1  919.40  5086.9  918.30  5303.2  919.27
  5543.5  927.39  5607.2  929.12  5637.3  932.22  5642.7  930.83  5662.0  934.42
  5667.4  931.94  5673.6  934.62  5684.4  935.56  5771.8  939.37  5804.8  940.86
#Mann=7,-1,0
  4718.3    0.05       0  4802.6    0.12       0  5006.3    0.07       0
  5013.8    0.12       0  5086.9    0.05       0  5543.5    0.12       0
  5771.8    0.05       0
Bank Sta=5006.3,5013.8
Exp/Cntr=0.3,0.1

Type RM Length L Ch R = 1,7290,521,521,521
BEGIN DESCRIPTION:
MDW T 059 15.0
END DESCRIPTION:
XS GIS Cut Line= 3
      2250975.78      7145840.70      2250929.00      7145560.00
      2250671.73      7144927.17
#Sta/Elev= 30
  4715.5  933.30  4817.6  924.61  4858.1  924.06  4878.4  920.99  4939.2  917.27
  4959.5  914.07  4967.1  909.55  4972.2  909.26  4986.2  901.14  4987.3  900.64
  4993.7  901.14  4997.5  903.51  5014.8  905.28  5032.5  915.10  5038.9  916.32
  5075.6  917.12  5086.4  915.11  5092.4  909.04  5097.8  912.80  5108.8  915.77
  5116.5  913.60  5121.9  915.90  5129.6  915.44  5140.4  917.40  5146.0  916.45
  5313.1  919.53  5529.0  931.19  5592.9  932.94  5615.4  935.16  5683.2  935.81
#Mann=4,-1,0
  4715.5    0.12       0  4986.2    0.07       0  4993.7    0.12       0
  5108.8    0.05       0
Bank Sta=4986.2,4993.7
Exp/Cntr=0.3,0.1

Type RM Length L Ch R = 1,6769,297,297,297
BEGIN DESCRIPTION:
MDW T 059 14.0
END DESCRIPTION:
XS GIS Cut Line= 3
      2251337.11      7145837.47      2251334.93      7145562.28
      2250832.52      7144933.70
#Sta/Elev= 30
  4730.1  931.40  4817.6  927.30  4957.6  917.04  4977.6  906.20  4997.6  901.29
  5006.9  900.66  5008.1  900.16  5014.5  900.66  5025.1  904.88  5033.1  903.86
  5039.5  904.72  5046.6  908.27  5074.7  907.83  5097.2  909.42  5103.6  907.82
  5118.0  909.55  5124.4  908.63  5132.4  911.17  5138.8  910.93  5146.8  912.94
  5153.2  911.68  5161.2  913.92  5167.6  911.03  5174.6  914.71  5182.0  915.26
  5188.4  914.24  5217.2  916.04  5262.3  916.03  5609.5  922.07  5810.0  930.35
#Mann=4,-1,0
  4730.1    0.12       0  5006.9    0.07       0  5014.5    0.12       0
  5262.3    0.05       0
Bank Sta=5006.9,5014.5
Exp/Cntr=0.3,0.1