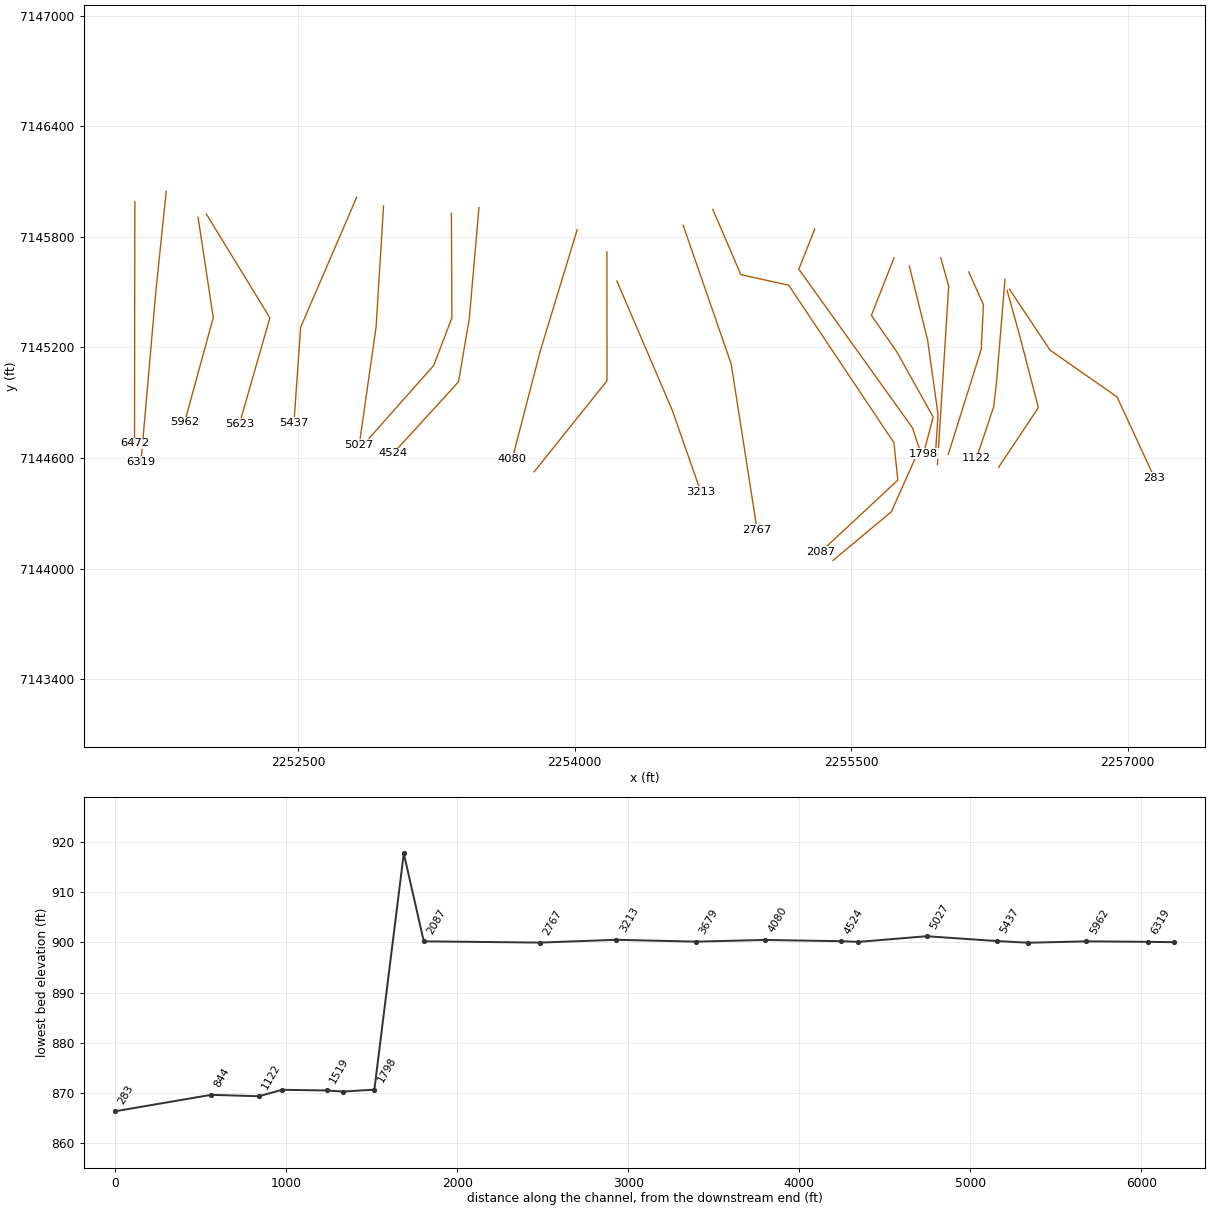
HEC-RAS study MDW T 059.prj: MDW T 059 Base Level Engineering

--- MDW T 059.g01 (geometry) --- (continued)

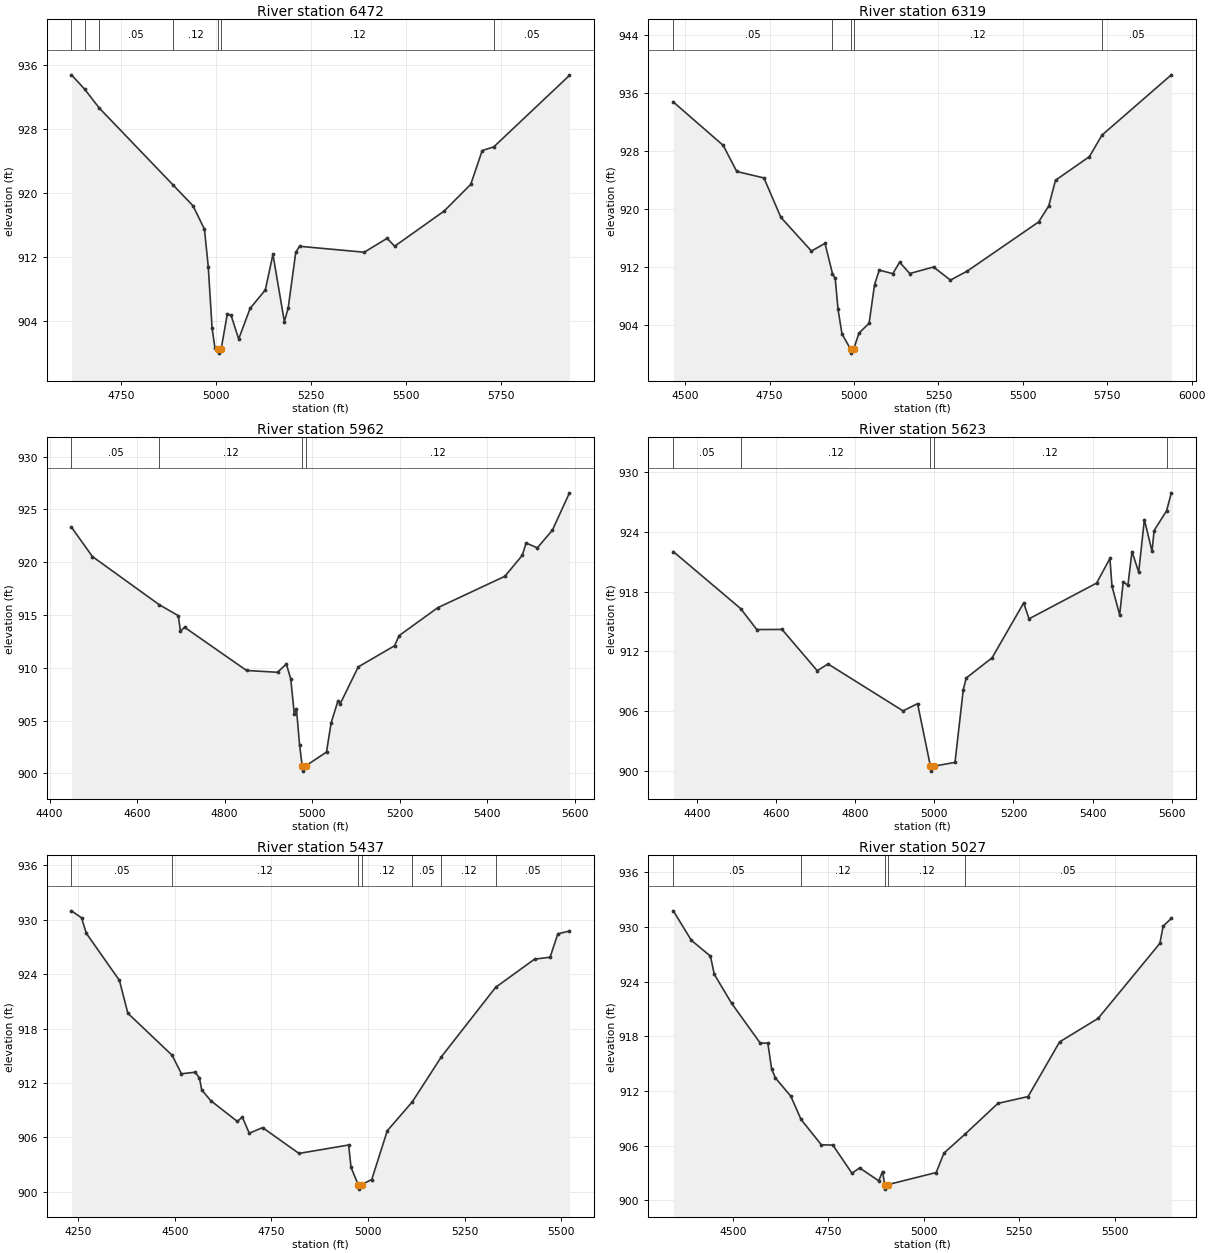
Type RM Length L Ch R = 1,6472,153,153,153
BEGIN DESCRIPTION:
MDW T 059 13.5
END DESCRIPTION:
XS GIS Cut Line= 3
      2251614.43      7145989.61      2251613.78      7145609.81
      2251612.69      7144680.61
#Sta/Elev= 30
  4620.2  934.72  4654.6  932.95  4693.2  930.59  4887.3  921.00  4939.8  918.40
  4969.8  915.49  4979.8  910.83  4989.8  903.22  4997.4  900.68  5006.0  900.55
  5007.2  900.05  5013.7  900.55  5029.8  904.91  5039.8  904.76  5059.8  901.81
  5089.8  905.62  5129.8  907.92  5149.8  912.35  5179.8  903.99  5189.8  905.64
  5209.8  912.62  5219.8  913.36  5389.8  912.62  5449.8  914.35  5469.8  913.37
  5599.8  917.75  5669.8  921.08  5699.8  925.28  5730.4  925.75  5929.2  934.65
#Mann=7,-1,0
  4620.2    0.05       0  4654.6    0.12       0  4693.2    0.05       0
  4887.3    0.12       0  5006.0    0.07       0  5013.7    0.12       0
  5730.4    0.05       0
Bank Sta=5006,5013.7
Exp/Cntr=0.3,0.1

Type RM Length L Ch R = 1,6319,357,357,357
BEGIN DESCRIPTION:
MDW T 059 13.0
END DESCRIPTION:
XS GIS Cut Line= 3
      2251784.57      7146046.95      2251729.00      7145510.00
      2251647.41      7144578.18
#Sta/Elev= 30
  4464.6  934.73  4612.3  928.75  4652.5  925.15  4733.0  924.26  4783.2  918.83
  4873.7  914.19  4913.9  915.24  4936.1  911.07  4944.1  910.43  4952.5  906.16
  4964.2  902.78  4990.2  900.62  4991.4  900.12  4998.5  900.62  5014.5  902.88
  5044.6  904.24  5060.7  909.57  5074.7  911.56  5114.8  911.07  5134.9  912.65
  5165.0  911.09  5235.3  911.99  5285.5  910.18  5335.7  911.44  5546.5  918.19
  5576.6  920.40  5596.7  923.94  5697.1  927.20  5734.3  930.16  5939.8  938.47
#Mann=5,-1,0
  4464.6    0.05       0  4936.1    0.12       0  4990.2    0.07       0
  4998.5    0.12       0  5734.3    0.05       0
Bank Sta=4990.2,4998.5
Exp/Cntr=0.3,0.1

Type RM Length L Ch R = 1,5962,339,339,339
BEGIN DESCRIPTION:
MDW T 059 12.0
END DESCRIPTION:
XS GIS Cut Line= 3
      2251957.33      7145905.65      2252039.68      7145361.65
      2251884.62      7144794.36
#Sta/Elev= 30
  4449.8  923.32  4497.7  920.54  4650.7  915.97  4694.0  914.94  4699.0  913.47
  4708.4  913.84  4850.0  909.75  4920.8  909.58  4941.0  910.36  4951.1  908.95
  4959.1  905.64  4964.1  906.12  4971.3  902.68  4977.2  900.72  4978.5  900.22
  4985.6  900.72  5032.8  902.03  5043.2  904.76  5059.1  906.89  5064.3  906.61
  5105.4  910.09  5188.3  912.09  5198.7  913.05  5286.9  915.69  5440.5  918.67
  5480.2  920.65  5489.0  921.82  5514.7  921.36  5549.3  923.05  5588.1  926.57
#Mann=4,-1,0
  4449.8    0.05       0  4650.7    0.12       0  4977.2    0.07       0
  4985.6    0.12       0
Bank Sta=4977.2,4985.6
Exp/Cntr=0.3,0.1

Type RM Length L Ch R = 1,5623,186,186,186
BEGIN DESCRIPTION:
MDW T 059 11.5
END DESCRIPTION:
XS GIS Cut Line= 3
      2252002.57      7145922.75      2252346.83      7145360.35
      2252181.58      7144784.49
#Sta/Elev= 30
  4340.6  922.02  4510.7  916.29  4551.5  914.18  4615.4  914.19  4704.3  910.04
  4731.5  910.72  4921.1  906.00  4957.8  906.73  4990.3  900.44  4991.5  899.94
  4998.9  900.44  5052.4  900.82  5073.2  908.09  5080.6  909.30  5146.0  911.33
  5225.9  916.85  5239.6  915.26  5410.2  918.85  5443.9  921.33  5449.1  918.54
  5468.5  915.66  5477.6  918.99  5489.3  918.62  5499.7  922.02  5516.6  919.96
  5531.0  925.24  5550.3  922.04  5555.5  924.14  5587.1  926.12  5599.1  927.93
#Mann=5,-1,0
  4340.6    0.05       0  4510.7    0.12       0  4990.3    0.07       0
  4998.9    0.12       0  5587.1    0.05       0
Bank Sta=4990.3,4998.9
Exp/Cntr=0.3,0.1

Type RM Length L Ch R = 1,5437,410,410,410
BEGIN DESCRIPTION:
MDW T 059 11.0
END DESCRIPTION:
XS GIS Cut Line= 3
      2252817.57      7146013.99      2252513.83      7145309.59
      2252477.27      7144789.97
#Sta/Elev= 30
  4232.9  930.99  4259.0  930.22  4271.3  928.52  4357.0  923.31  4378.8  919.69
  4493.3  915.05  4517.3  913.01  4553.1  913.18  4564.0  912.54  4569.8  911.23
  4593.3  910.04  4662.0  907.75  4674.8  908.23  4692.8  906.45  4727.3  907.07
  4821.3  904.22  4949.8  905.15  4956.0  902.68  4974.3  900.78  4975.6  900.28
  4983.3  900.78  5009.6  901.34  5049.7  906.72  5114.6  909.92  5189.9  914.90
  5330.0  922.55  5430.7  925.66  5470.8  925.87  5490.8  928.45  5520.9  928.76
#Mann=7,-1,0
  4232.9    0.05       0  4493.3    0.12       0  4974.3    0.07       0
  4983.3    0.12       0  5114.6    0.05       0  5189.9    0.12       0
  5330.0    0.05       0
Bank Sta=4974.3,4983.3
Exp/Cntr=0.3,0.1

Type RM Length L Ch R = 1,5027,399,399,399
BEGIN DESCRIPTION:
MDW T 059 10.0
END DESCRIPTION:
XS GIS Cut Line= 3
      2252963.39      7145967.08      2252923.06      7145312.26
      2252831.45      7144670.23
#Sta/Elev= 30
  4343.7  931.75  4390.9  928.52  4441.0  926.78  4451.0  924.79  4496.3  921.62
  4571.2  917.26  4591.3  917.24  4601.3  914.40  4611.3  913.42  4651.4  911.43
  4678.3  908.88  4731.5  906.10  4761.6  906.07  4811.7  902.98  4831.7  903.57
  4881.8  902.15  4891.8  903.17  4897.3  901.74  4898.6  901.24  4906.3  901.74
  5032.3  903.06  5052.6  905.19  5107.7  907.26  5194.0  910.64  5273.0  911.39
  5355.6  917.38  5456.6  919.96  5618.2  928.18  5626.8  930.07  5648.3  930.93
#Mann=5,-1,0
  4343.7    0.05       0  4678.3    0.12       0  4897.3    0.07       0
  4906.3    0.12       0  5107.7    0.05       0
Bank Sta=4897.3,4906.3
Exp/Cntr=0.3,0.1

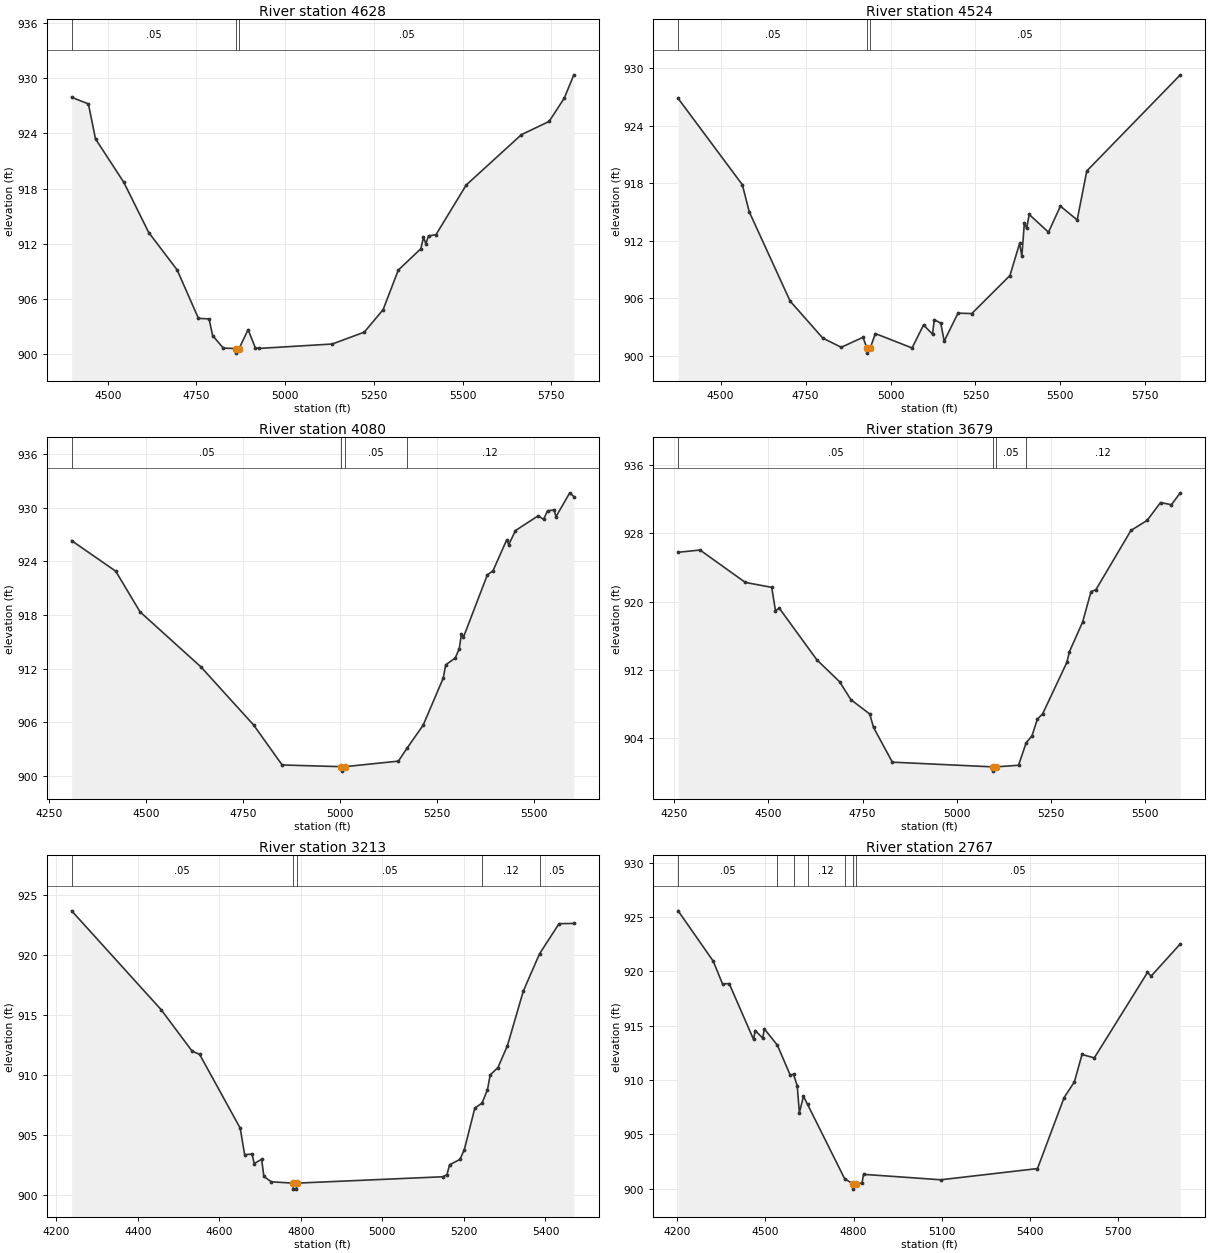
Type RM Length L Ch R = 1,4628,104,104,104
BEGIN DESCRIPTION:
MDW T 059 9.5
END DESCRIPTION:
XS GIS Cut Line= 4
      2253331.44      7145927.19      2253334.00      7145360.01
      2253235.59      7145102.30      2252856.32      7144674.31
#Sta/Elev= 30
  4398.3  927.92  4445.5  927.20  4465.5  923.40  4545.5  918.66  4615.5  913.22
  4695.5  909.16  4755.5  903.89  4785.5  903.83  4795.5  902.02  4825.5  900.66
  4860.9  900.61  4862.2  900.11  4870.0  900.61  4895.5  902.67  4915.5  900.71
  4925.5  900.62  5132.5  901.10  5222.8  902.39  5275.9  904.84  5318.5  909.13
  5382.1  911.46  5389.6  912.70  5396.3  912.00  5403.8  912.86  5424.7  912.98
  5510.1  918.39  5665.6  923.86  5743.4  925.29  5786.0  927.81  5813.2  930.36
#Mann=3,-1,0
  4398.3    0.05       0  4860.9   0.033       0  4870.0    0.05       0
Bank Sta=4860.9,4870
Exp/Cntr=0.3,0.1

Type RM Length L Ch R = 1,4524,444,444,444
BEGIN DESCRIPTION:
MDW T 059 9.0
END DESCRIPTION:
XS GIS Cut Line= 4
      2253480.75      7145958.44      2253429.00      7145360.00
      2253370.13      7145013.32      2253015.45      7144625.04
#Sta/Elev= 30
  4374.8  926.83  4563.9  917.82  4584.0  915.01  4704.5  905.68  4800.6  901.82
  4855.0  900.86  4918.9  901.90  4930.8  900.75  4932.1  900.25  4939.9  900.75
  4955.4  902.29  5063.4  900.79  5097.2  903.19  5123.7  902.23  5128.8  903.74
  5147.9  903.38  5158.0  901.50  5198.6  904.42  5239.2  904.38  5351.5  908.35
  5379.9  911.69  5386.6  910.37  5394.0  913.86  5400.8  913.26  5408.2  914.72
  5465.0  912.87  5500.1  915.59  5549.4  914.15  5577.8  919.26  5853.0  929.29
#Mann=3,-1,0
  4374.8    0.05       0  4930.8   0.033       0  4939.9    0.05       0
Bank Sta=4930.8,4939.9
Exp/Cntr=0.3,0.1

Type RM Length L Ch R = 1,4080,401,401,401
BEGIN DESCRIPTION:
MDW T 059 8.0
END DESCRIPTION:
XS GIS Cut Line= 3
      2254013.74      7145838.61      2253812.34      7145176.67
      2253661.46      7144594.41
#Sta/Elev= 30
  4308.1  926.33  4421.6  922.91  4484.3  918.35  4641.1  912.18  4777.0  905.66
  4850.2  901.19  5002.2  901.00  5003.6  900.50  5011.5  901.00  5149.6  901.62
  5171.4  903.04  5213.5  905.66  5265.2  910.93  5271.4  912.41  5296.1  913.18
  5306.5  914.24  5312.0  915.87  5317.1  915.50  5378.8  922.50  5393.2  922.95
  5428.6  926.42  5433.8  925.87  5451.1  927.46  5509.8  929.12  5523.4  928.71
  5533.7  929.66  5550.4  929.78  5555.5  929.02  5591.0  931.69  5601.5  931.27
#Mann=4,-1,0
  4308.1    0.05       0  5002.2   0.033       0  5011.5    0.05       0
  5171.4    0.12       0
Bank Sta=5002.2,5011.5
Exp/Cntr=0.3,0.1

Type RM Length L Ch R = 1,3679,466,466,466
BEGIN DESCRIPTION:
MDW T 059 7.0
END DESCRIPTION:
XS GIS Cut Line= 3
      2254174.99      7145718.20      2254175.40      7145018.64
      2253780.30      7144525.06
#Sta/Elev= 30
  4261.0  925.79  4319.2  926.05  4439.2  922.26  4509.2  921.68  4519.2  918.95
  4529.2  919.25  4629.2  913.18  4689.2  910.63  4719.2  908.53  4769.2  906.85
  4779.2  905.28  4829.2  901.21  5095.1  900.66  5096.4  900.16  5104.4  900.66
  5163.8  900.85  5184.2  903.50  5199.3  904.27  5213.7  906.25  5227.8  906.88
  5291.9  912.89  5298.6  914.13  5333.8  917.63  5355.9  921.17  5369.0  921.41
  5461.8  928.34  5505.0  929.53  5540.3  931.61  5569.1  931.36  5592.8  932.75
#Mann=4,-1,0
  4261.0    0.05       0  5095.1   0.033       0  5104.4    0.05       0
  5184.2    0.12       0
Bank Sta=5095.1,5104.4
Exp/Cntr=0.3,0.1

Type RM Length L Ch R = 1,3213,446,446,446
BEGIN DESCRIPTION:
MDW T 059 6.0
END DESCRIPTION:
XS GIS Cut Line= 3
      2254229.01      7145559.98      2254529.00      7144860.00
      2254684.43      7144416.29
#Sta/Elev= 30
  4237.9  923.71  4457.3  915.48  4533.4  912.02  4551.6  911.76  4651.3  905.61
  4662.2  903.40  4680.3  903.45  4685.8  902.66  4703.9  903.02  4709.3  901.59
  4727.5  901.14  4780.6  901.03  4781.9  900.53  4789.0  900.53  4790.4  901.03
  5147.8  901.56  5158.4  901.73  5164.8  902.56  5190.2  903.00  5201.1  903.83
  5226.8  907.29  5244.4  907.69  5257.8  908.82  5264.4  910.04  5283.5  910.66
  5306.7  912.48  5345.6  917.02  5385.6  920.14  5433.3  922.64  5469.6  922.66
#Mann=5,-1,0
  4237.9    0.05       0  4780.6   0.033       0  4790.4    0.05       0
  5244.4    0.12       0  5385.6    0.05       0
Bank Sta=4780.6,4790.4
Exp/Cntr=0.3,0.1

Type RM Length L Ch R = 1,2767,680,680,680
BEGIN DESCRIPTION:
MDW T 059 5.0
END DESCRIPTION:
XS GIS Cut Line= 3
      2254588.38      7145862.71      2254848.99      7145110.05
      2254989.70      7144209.68
#Sta/Elev= 30
  4203.5  925.56  4322.8  920.94  4354.5  918.84  4377.2  918.87  4460.1  913.73
  4465.4  914.55  4491.3  913.86  4496.6  914.71  4541.0  913.21  4584.7  910.46
  4595.9  910.53  4608.5  909.48  4615.9  907.00  4629.7  908.50  4643.6  907.77
  4770.1  900.91  4797.9  900.47  4799.3  899.97  4807.8  900.47  4828.7  900.51
  4834.0  901.33  5096.7  900.83  5425.6  901.86  5516.2  908.39  5551.1  909.83
  5577.0  912.35  5618.9  912.04  5799.6  919.89  5812.2  919.56  5911.3  922.52
#Mann=7,-1,0
  4203.5    0.05       0  4541.0    0.12       0  4595.9    0.05       0
  4643.6    0.12       0  4770.1    0.05       0  4797.9   0.033       0
  4807.8    0.05       0
Bank Sta=4797.9,4807.8
Exp/Cntr=0.3,0.1

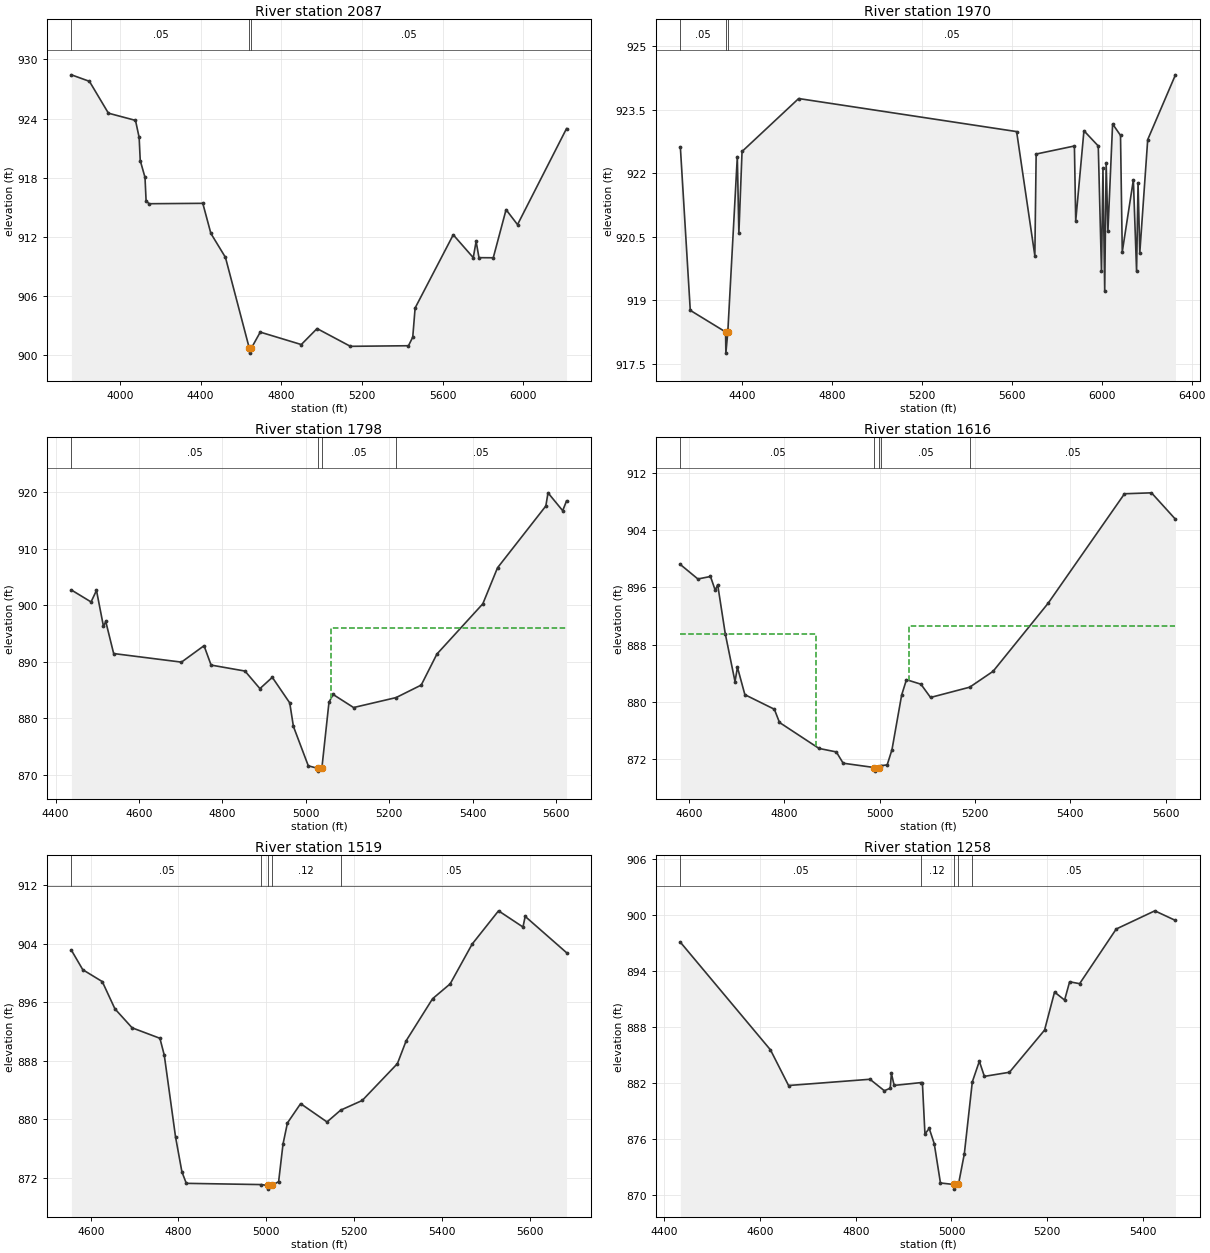
Type RM Length L Ch R = 1,2087,117,117,117
BEGIN DESCRIPTION:
Mapping XS c8d61e35
END DESCRIPTION:
XS GIS Cut Line= 6
      2254749.46      7145948.40      2254901.33      7145594.67
      2255161.06      7145537.17      2255731.80      7144682.72
      2255752.77      7144480.00      2255334.85      7144090.93
#Sta/Elev= 30
  3760.0  928.44  3849.2  927.78  3943.3  924.55  4077.5  923.82  4095.6  922.09
  4101.0  919.75  4124.6  918.04  4130.0  915.67  4144.8  915.37  4411.0  915.41
  4451.0  912.36  4523.2  909.93  4641.4  900.72  4642.8  900.22  4651.4  900.72
  4695.7  902.35  4899.0  901.09  4977.2  902.71  5142.4  900.91  5430.2  900.97
  5451.3  901.84  5463.1  904.80  5652.0  912.22  5751.2  909.90  5765.3  911.55
  5779.5  909.90  5850.3  909.89  5913.8  914.77  5970.5  913.25  6213.3  922.99
#Mann=3,-1,0
  3760.0    0.05       0  4641.4   0.033       0  4651.4    0.05       0
Bank Sta=4641.4,4651.4
Exp/Cntr=0.3,0.1

Type RM Length L Ch R = 1,1970,172,172,172
BEGIN DESCRIPTION:
Mapping XS de655aec
END DESCRIPTION:
XS GIS Cut Line= 6
      2255302.00      7145841.69      2255215.83      7145624.29
      2255832.59      7144763.42      2255870.00      7144649.76
      2255717.91      7144308.69      2255401.19      7144044.30
#Sta/Elev= 30
  4125.2  922.62  4169.4  918.76  4326.4  918.25  4327.8  917.75  4336.4  918.25
  4378.7  922.39  4385.6  920.58  4399.7  922.51  4651.6  923.76  5621.3  922.98
  5702.4  920.05  5708.2  922.45  5878.4  922.64  5884.2  920.87  5920.8  923.00
  5984.5  922.64  5998.8  919.69  6005.4  922.11  6013.2  919.21  6019.7  922.24
  6027.5  920.63  6048.3  923.16  6083.5  922.89  6091.3  920.14  6140.7  921.84
  6155.0  919.68  6161.5  921.77  6169.3  920.12  6204.5  922.79  6327.9  924.32
#Mann=3,-1,0
  4125.2    0.05       0  4326.4   0.033       0  4336.4    0.05       0
Bank Sta=4326.4,4336.4
Exp/Cntr=0.3,0.1

Type RM Length L Ch R = 1,1798,182,182,182
BEGIN DESCRIPTION:
MDW T 059 3.0
END DESCRIPTION:
XS GIS Cut Line= 5
      2255732.41      7145685.94      2255609.58      7145373.65
      2255745.25      7145179.28      2255944.65      7144822.46
      2255892.37      7144623.38
#Sta/Elev= 30
  4437.8  902.73  4484.9  900.62  4497.9  902.66  4514.7  896.27  4520.1  897.17
  4539.1  891.48  4701.7  889.96  4755.8  892.87  4772.7  889.44  4854.0  888.38
  4889.8  885.27  4919.5  887.27  4961.3  882.74  4970.1  878.58  5005.8  871.60
  5028.2  871.16  5029.6  870.66  5038.3  871.16  5055.4  882.86  5065.2  884.24
  5114.4  881.92  5216.2  883.68  5276.6  885.90  5314.2  891.39  5424.3  900.29
  5459.5  906.66  5575.4  917.61  5580.6  919.94  5615.8  916.78  5625.0  918.51
#Mann=4,-1,0
  4437.8    0.05       0  5028.2    0.04       0  5038.3    0.05       0
  5216.2    0.05       0
#XS Ineff=2,0
       0                 5060.00    0.00  896.04
Permanent Ineff=
       F       F
Bank Sta=5028.2,5038.3
Exp/Cntr=0.3,0.1

Type RM Length L Ch R = 1,1616,97,97,97
BEGIN DESCRIPTION:
Mapping XS b919ef4e
END DESCRIPTION:
XS GIS Cut Line= 4
      2255815.32      7145641.35      2255914.11      7145241.42
      2255971.14      7144835.62      2255956.82      7144619.93
#Sta/Elev= 30
  4582.4  899.22  4619.2  897.19  4645.6  897.54  4655.5  895.61  4660.7  896.38
  4676.5  889.55  4697.0  882.82  4702.1  884.82  4717.7  880.98  4779.5  878.94
  4790.2  877.09  4873.1  873.45  4909.4  872.96  4923.7  871.38  4989.3  870.77
  4990.7  870.27  4999.4  870.77  5003.1  871.04  5016.0  871.14  5026.1  873.29
  5046.3  880.92  5056.4  883.08  5086.7  882.45  5106.9  880.59  5189.0  882.03
  5238.1  884.26  5353.5  893.80  5513.5  909.13  5570.1  909.26  5620.3  905.56
#Mann=5,-1,0
  4582.4    0.05       0  4989.3    0.04       0  4999.4    0.05       0
  5003.1    0.05       0  5189.0    0.05       0
#XS Ineff=2,0
    0.00 4867.30  889.51 5062.30    0.00  890.60
Permanent Ineff=
       F       F
Bank Sta=4989.3,4999.4
Exp/Cntr=0.3,0.1

Type RM Length L Ch R = 1,1519,261,261,261
BEGIN DESCRIPTION:
MDW T 059 2.0
END DESCRIPTION:
XS GIS Cut Line= 3
      2255985.75      7145685.52      2256028.95      7145532.20
      2255967.77      7144565.42
#Sta/Elev= 30
  4556.1  903.10  4582.0  900.44  4626.4  898.82  4655.2  895.10  4694.4  892.51
  4757.7  891.08  4767.7  888.76  4793.3  877.62  4807.8  872.86  4817.8  871.28
  4989.0  871.11  5003.1  870.99  5004.5  870.49  5013.2  870.99  5028.2  871.52
  5038.2  876.65  5048.3  879.53  5078.3  882.16  5138.4  879.66  5169.5  881.27
  5218.6  882.59  5298.8  887.62  5318.8  890.75  5378.9  896.48  5419.0  898.51
  5469.1  903.94  5529.2  908.48  5584.9  906.27  5589.9  907.72  5684.1  902.77
#Mann=5,-1,0
  4556.1    0.05       0  4989.0    0.12       0  5003.1    0.05       0
  5013.2    0.12       0  5169.5    0.05       0
Bank Sta=5003.1,5013.2
Exp/Cntr=0.3,0.1

Type RM Length L Ch R = 1,1258,136,136,136
BEGIN DESCRIPTION:
Mapping XS 3c2d9129
END DESCRIPTION:
XS GIS Cut Line= 4
      2256137.47      7145608.95      2256217.23      7145432.22
      2256205.20      7145189.74      2256026.33      7144618.88
#Sta/Elev= 30
  4433.3  897.10  4621.7  885.55  4659.5  881.73  4829.7  882.40  4859.7  881.17
  4872.0  881.44  4874.5  883.03  4880.2  881.74  4935.8  882.04  4939.3  881.97
  4944.6  876.53  4953.5  877.13  4964.0  875.50  4977.0  871.28  5004.4  871.12
  5005.8  870.62  5014.6  871.12  5026.9  874.40  5043.6  882.12  5058.3  884.33
  5068.8  882.71  5121.2  883.15  5194.6  887.67  5215.5  891.75  5236.5  890.89
  5247.0  892.85  5267.9  892.65  5344.4  898.51  5425.1  900.46  5468.2  899.43
#Mann=5,-1,0
  4433.3    0.05       0  4935.8    0.12       0  5004.4    0.05       0
  5014.6    0.12       0  5043.6    0.05       0
Bank Sta=5004.4,5014.6
Exp/Cntr=0.3,0.1

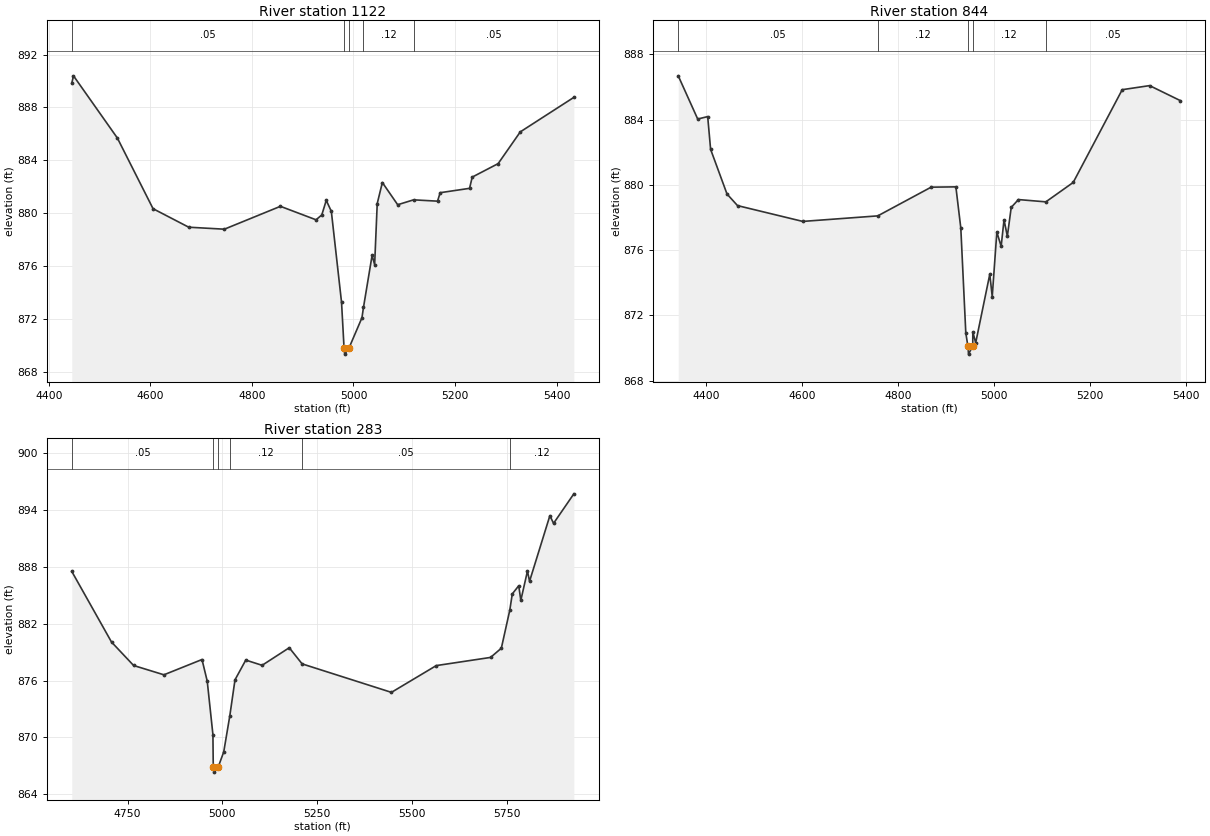
Type RM Length L Ch R = 1,1122,278,278,278
BEGIN DESCRIPTION:
Mapping XS 987615ff
END DESCRIPTION:
XS GIS Cut Line= 4
      2256334.18      7145569.58      2256288.26      7145012.96
      2256273.10      7144878.64      2256179.25      7144598.63
#Sta/Elev= 30
  4445.1  889.83  4448.5  890.39  4535.0  885.68  4605.2  880.34  4675.5  878.94
  4745.7  878.79  4856.1  880.52  4926.3  879.50  4937.6  879.87  4946.4  880.97
  4956.4  880.14  4976.5  873.26  4981.4  869.84  4982.8  869.34  4991.6  869.84
  5016.7  872.09  5019.7  872.87  5036.7  876.81  5041.7  876.11  5046.8  880.73
  5056.9  882.32  5087.1  880.64  5118.4  881.01  5165.6  880.91  5170.8  881.55
  5228.7  881.88  5233.9  882.73  5285.0  883.75  5328.6  886.15  5434.1  888.76
#Mann=5,-1,0
  4445.1    0.05       0  4981.4   0.033       0  4991.6    0.05       0
  5019.7    0.12       0  5118.4    0.05       0
Bank Sta=4981.4,4991.6
Exp/Cntr=0.3,0.1

Type RM Length L Ch R = 1,844,561,561,561
BEGIN DESCRIPTION:
MDW T 059 1.0
END DESCRIPTION:
XS GIS Cut Line= 4
      2256345.64      7145509.10      2256410.48      7145276.35
      2256515.26      7144873.37      2256299.70      7144549.91
#Sta/Elev= 30
  4342.0  886.69  4382.6  884.04  4403.4  884.19  4409.5  882.18  4443.7  879.44
  4465.6  878.73  4601.6  877.76  4758.0  878.10  4869.2  879.86  4920.8  879.88
  4931.1  877.35  4941.5  870.92  4945.8  870.12  4947.2  869.62  4956.0  870.12
  4956.1  870.99  4962.1  870.31  4991.5  874.52  4996.6  873.15  5006.2  877.11
  5015.2  876.23  5021.2  877.86  5028.1  876.85  5036.2  878.62  5051.2  879.10
  5108.4  878.96  5165.4  880.15  5267.6  885.84  5324.7  886.09  5388.7  885.17
#Mann=5,-1,0
  4342.0    0.05       0  4758.0    0.12       0  4945.8    0.07       0
  4956.0    0.12       0  5108.4    0.05       0
Bank Sta=4945.8,4956
Exp/Cntr=0.3,0.1

Type RM Length L Ch R = 1,283,0,0,0
BEGIN DESCRIPTION:
MDW T 059 0.5
END DESCRIPTION:
XS GIS Cut Line= 4
      2256358.27      7145515.77      2256578.49      7145185.20
      2256942.27      7144931.20      2257144.69      7144492.64
#Sta/Elev= 30
  4602.8  887.49  4707.6  880.05  4765.9  877.58  4845.8  876.60  4946.2  878.21
  4960.0  875.93  4975.0  870.30  4975.9  866.85  4977.7  866.35  4988.6  866.85
  5003.5  868.48  5019.4  872.25  5033.2  876.07  5061.6  878.15  5104.7  877.60
  5176.3  879.45  5210.2  877.75  5445.7  874.75  5563.9  877.57  5707.1  878.43
  5735.5  879.40  5757.8  883.41  5764.4  885.12  5781.4  885.98  5786.9  884.44
  5804.4  887.53  5809.9  886.45  5863.5  893.36  5873.2  892.55  5926.7  895.66
#Mann=6,-1,0
  4602.8    0.05       0  4975.9   0.033       0  4988.6    0.05       0
  5019.4    0.12       0  5210.2    0.05       0  5757.8    0.12       0
Bank Sta=4975.9,4988.6
Exp/Cntr=0.3,0.1

Chan Stop Cuts=-1