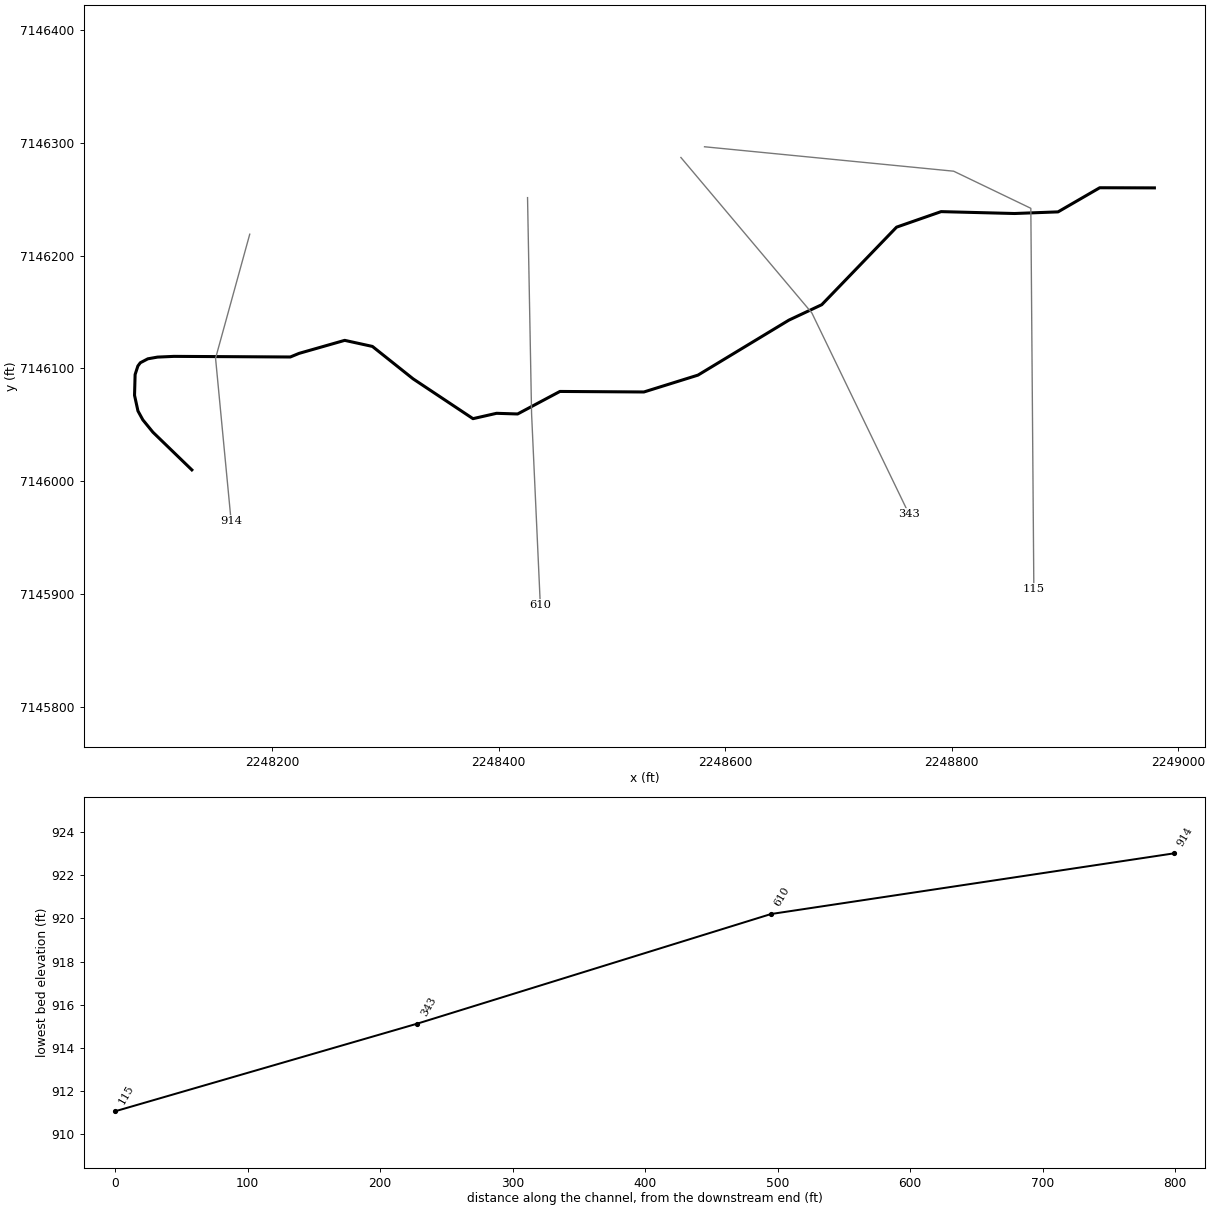
--- MDW T 060.prj (project) ---

Proj Title=MDW T 060 Base Level Engineering
Current Plan=p01
Default Exp/Contr=0.3,0.1
English Units
Geom File=g01
Flow File=f01
Plan File=p01
BEGIN DESCRIPTION:
MDW T 060
END DESCRIPTION:

--- MDW T 060.p01 (plan) ---

Plan Title=Multiple Run
Short Identifier=Multiple
Geom File=g01
Flow File=f01
Subcritical Flow
K Sum by GR= 0
Std Step Tol= 0.01
Critical Tol= 0.01
Num of Std Step Trials= 20
Max Error Tol= 0.3
Flow Tol Ratio= 0.001
Split Flow NTrial= 30
Split Flow Tol= 0.02
Split Flow Ratio= 0.02
Log Output Level= 0
Friction Slope Method= 1
Unsteady Friction Slope Method= 2
Unsteady Bridges Friction Slope Method= 1
Parabolic Critical Depth
Global Vel Dist=  1 , 1 , 1
Global Log Level= 0
CheckData=True
Encroach Param= -1, 0, 0, 0
BEGIN DESCRIPTION:
Multiple Run
END DESCRIPTION:

--- MDW T 060.f01 (steady flow) ---

Flow Title=Multiple
Number of Profiles=7
Profile Names=10-year,25-year,50-year,1pct_min,100-year,1pct_plu,500-year
River Rch & RM= MDW T 060,Reach-1,914
     305     402     480     286     570    1138     804
Boundary for River Rch & Prof#=MDW T 060,Reach-1,1
Up Type=0
Dn Type=3
Dn Slope=0.005
Boundary for River Rch & Prof#=MDW T 060,Reach-1,2
Up Type=0
Dn Type=3
Dn Slope=0.005
Boundary for River Rch & Prof#=MDW T 060,Reach-1,3
Up Type=0
Dn Type=3
Dn Slope=0.005
Boundary for River Rch & Prof#=MDW T 060,Reach-1,4
Up Type=0
Dn Type=3
Dn Slope=0.005
Boundary for River Rch & Prof#=MDW T 060,Reach-1,5
Up Type=0
Dn Type=3
Dn Slope=0.005
Boundary for River Rch & Prof#=MDW T 060,Reach-1,6
Up Type=0
Dn Type=3
Dn Slope=0.005
Boundary for River Rch & Prof#=MDW T 060,Reach-1,7
Up Type=0
Dn Type=3
Dn Slope=0.005

--- MDW T 060.g01 (geometry) ---

Geom Title=Existing Conditions

River Reach=MDW T 060,Reach-1
Reach XY= 30
      2248129.00      7146010.00      2248094.60      7146043.42
      2248085.71      7146054.37      2248081.41      7146062.24
      2248078.39      7146076.12      2248078.90      7146094.52
      2248081.34      7146102.09      2248083.50      7146104.98
      2248090.13      7146108.46      2248098.71      7146109.99
      2248113.19      7146110.63      2248215.94      7146110.09
      2248223.72      7146113.30      2248263.99      7146124.83
      2248288.45      7146119.45      2248324.38      7146090.71
      2248377.26      7146055.41      2248398.07      7146060.16
      2248416.68      7146059.57      2248454.03      7146079.54
      2248528.21      7146079.07      2248575.96      7146094.02
      2248656.27      7146142.78      2248685.26      7146156.44
      2248751.31      7146225.19      2248790.62      7146238.95
      2248855.42      7146237.28      2248893.90      7146238.73
      2248930.71      7146260.12      2248979.00      7146260.00

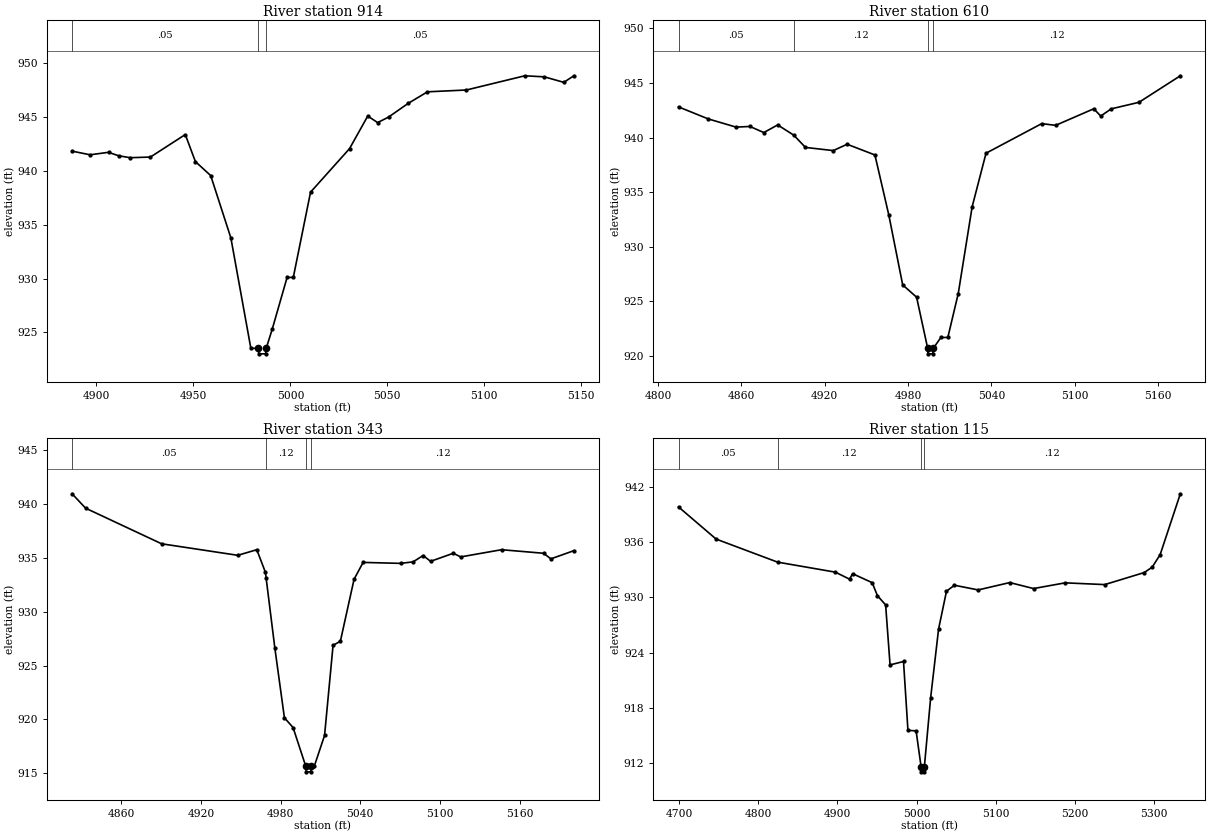
Type RM Length L Ch R = 1,914,304,304,304
BEGIN DESCRIPTION:
MDW T 060 3.0
END DESCRIPTION:
XS GIS Cut Line= 3
      2248180.13      7146218.94      2248149.94      7146108.95
      2248163.66      7145964.86
#Sta/Elev= 30
  4887.4  941.84  4896.7  941.50  4906.2  941.73  4911.4  941.41  4917.4  941.23
  4927.8  941.29  4945.8  943.38  4951.0  940.87  4958.9  939.57  4969.3  933.78
  4979.6  923.53  4983.5  923.51  4983.7  923.01  4987.2  923.01  4987.5  923.51
  4990.6  925.28  4998.3  930.11  5001.5  930.11  5010.4  938.03  5030.5  942.07
  5039.9  945.10  5045.0  944.49  5050.6  945.00  5060.7  946.27  5070.7  947.35
  5090.8  947.52  5120.9  948.84  5131.0  948.74  5141.0  948.23  5146.2  948.84
#Mann=3,-1,0
  4887.4    0.05       0  4983.5   0.033       0  4987.5    0.05       0
Bank Sta=4983.5,4987.5
Exp/Cntr=0.3,0.1

Type RM Length L Ch R = 1,610,267,267,267
BEGIN DESCRIPTION:
MDW T 060 2.0
END DESCRIPTION:
XS GIS Cut Line= 3
      2248425.44      7146251.36      2248429.00      7146060.00
      2248436.72      7145890.27
#Sta/Elev= 30
  4814.7  942.81  4836.1  941.71  4856.1  940.96  4866.1  941.02  4876.1  940.46
  4886.1  941.16  4897.7  940.22  4906.1  939.10  4926.1  938.81  4936.1  939.39
  4956.1  938.41  4966.1  932.91  4976.1  926.51  4986.1  925.39  4994.1  920.70
  4994.3  920.20  4997.8  920.20  4998.1  920.70  5003.6  921.70  5008.6  921.70
  5016.1  925.72  5026.1  933.66  5036.1  938.57  5076.2  941.28  5086.2  941.12
  5113.7  942.64  5118.7  941.97  5126.2  942.63  5146.2  943.23  5176.0  945.66
#Mann=4,-1,0
  4814.7    0.05       0  4897.7    0.12       0  4994.1    0.07       0
  4998.1    0.12       0
Bank Sta=4994.1,4998.1
Exp/Cntr=0.3,0.1

Type RM Length L Ch R = 1,343,228,228,228
BEGIN DESCRIPTION:
MDW T 060 1.0
END DESCRIPTION:
XS GIS Cut Line= 3
      2248560.88      7146286.93      2248676.50      7146149.14
      2248762.25      7145970.97
#Sta/Elev= 30
  4823.1  940.97  4833.3  939.63  4890.5  936.32  4947.8  935.25  4962.1  935.77
  4968.6  933.67  4969.1  933.17  4975.7  926.62  4982.9  920.14  4989.4  919.24
  4999.0  915.62  4999.3  915.12  5002.8  915.12  5003.0  915.62  5005.3  915.62
  5013.1  918.50  5019.5  926.88  5025.0  927.26  5035.3  933.02  5042.1  934.59
  5070.3  934.50  5079.7  934.64  5087.3  935.23  5092.9  934.69  5110.0  935.44
  5115.5  935.10  5146.3  935.77  5177.9  935.44  5183.4  934.92  5200.7  935.68
#Mann=4,-1,0
  4823.1    0.05       0  4969.1    0.12       0  4999.0    0.07       0
  5003.0    0.12       0
Bank Sta=4999,5003
Exp/Cntr=0.3,0.1

Type RM Length L Ch R = 1,115,0,0,0
BEGIN DESCRIPTION:
MDW T 060 0.5
END DESCRIPTION:
XS GIS Cut Line= 4
      2248581.73      7146296.45      2248801.74      7146274.79
      2248869.88      7146241.89      2248872.54      7145904.54
#Sta/Elev= 30
  4699.2  939.82  4746.7  936.33  4824.3  933.83  4897.4  932.74  4915.3  931.98
  4919.2  932.57  4943.9  931.60  4950.5  930.19  4960.9  929.18  4966.5  922.67
  4983.5  923.04  4989.1  915.56  4999.4  915.51  5005.8  911.56  5006.1  911.06
  5009.6  911.06  5009.8  911.56  5017.8  919.11  5027.8  926.56  5037.8  930.67
  5047.8  931.32  5077.8  930.81  5117.8  931.61  5147.8  930.96  5187.8  931.58
  5237.8  931.39  5287.8  932.70  5297.8  933.29  5307.8  934.64  5333.3  941.25
#Mann=4,-1,0
  4699.2    0.05       0  4824.3    0.12       0  5005.8    0.07       0
  5009.8    0.12       0
Bank Sta=5005.8,5009.8
Exp/Cntr=0.3,0.1

Chan Stop Cuts=-1