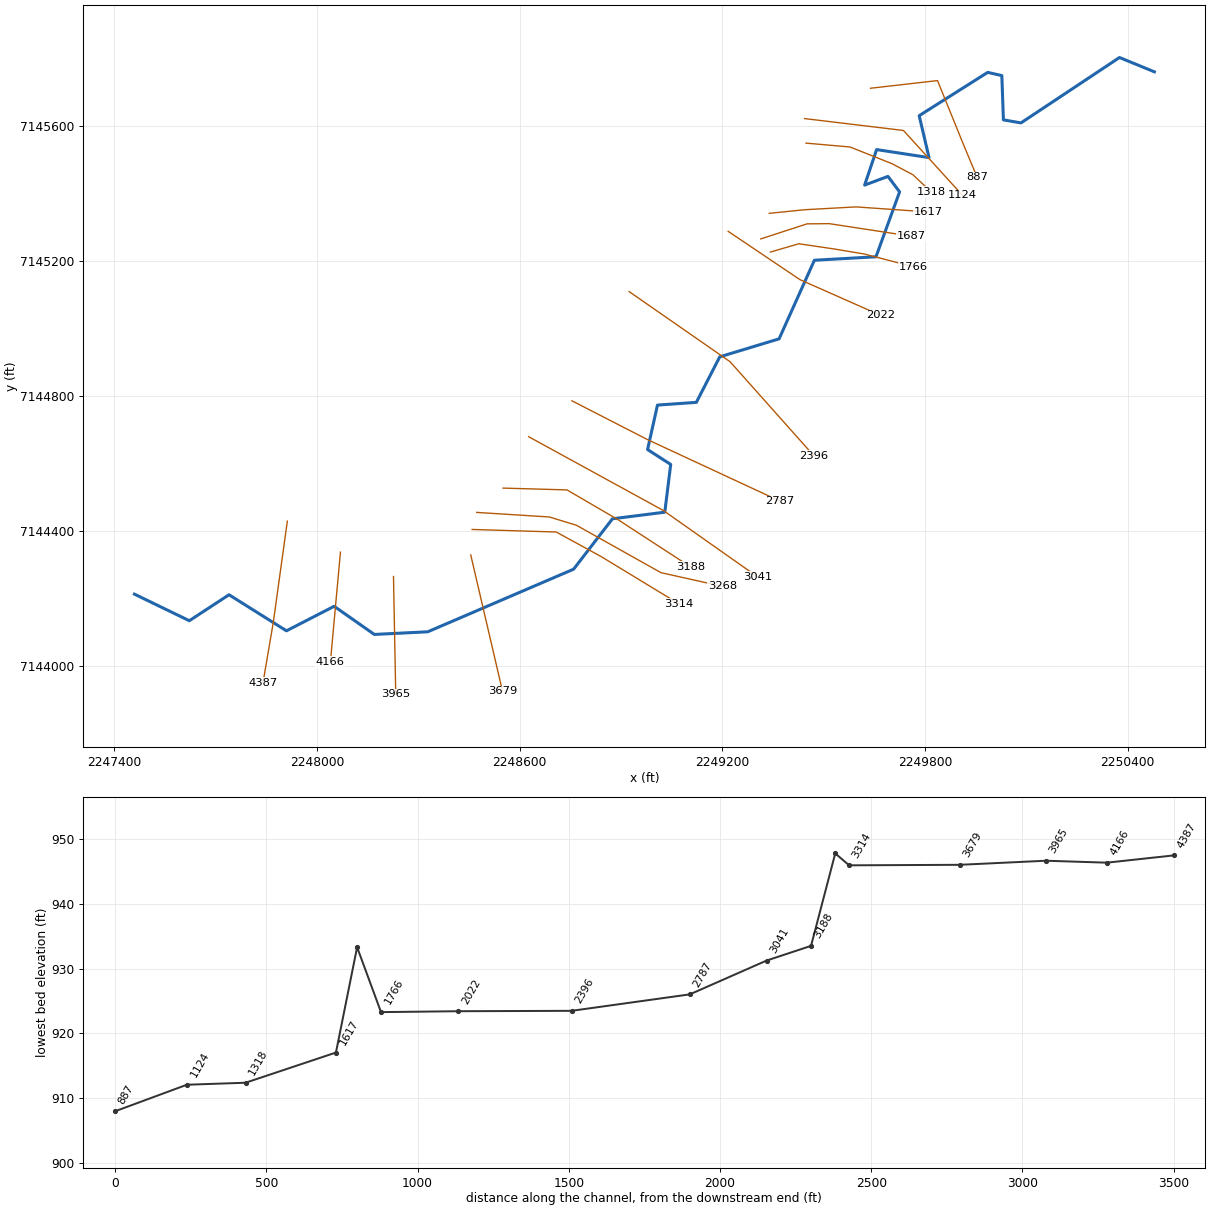
--- MDW T 061.prj (project) ---

Proj Title=MDW T 061 Base Level Engineering
Current Plan=p01
Default Exp/Contr=0.3,0.1
English Units
Geom File=g01
Flow File=f01
Plan File=p01
BEGIN DESCRIPTION:
MDW T 061
END DESCRIPTION:

--- MDW T 061.p01 (plan) ---

Plan Title=Multiple Run
Short Identifier=Multiple
Geom File=g01
Flow File=f01
Subcritical Flow
K Sum by GR= 0
Std Step Tol= 0.01
Critical Tol= 0.01
Num of Std Step Trials= 20
Max Error Tol= 0.3
Flow Tol Ratio= 0.001
Split Flow NTrial= 30
Split Flow Tol= 0.02
Split Flow Ratio= 0.02
Log Output Level= 0
Friction Slope Method= 1
Unsteady Friction Slope Method= 2
Unsteady Bridges Friction Slope Method= 1
Parabolic Critical Depth
Global Vel Dist=  1 , 1 , 1
Global Log Level= 0
CheckData=True
Encroach Param= -1, 0, 0, 0
BEGIN DESCRIPTION:
Multiple Run
END DESCRIPTION:

--- MDW T 061.f01 (steady flow) ---

Flow Title=Multiple
Number of Profiles=7
Profile Names=10-year,25-year,50-year,1pct_min,100-year,1pct_plu,500-year
River Rch & RM= MDW T 061,Reach-1,4387
     614     847    1041     637    1271    2535    1894
Boundary for River Rch & Prof#=MDW T 061,Reach-1,1
Up Type=0
Dn Type=3
Dn Slope=0.005
Boundary for River Rch & Prof#=MDW T 061,Reach-1,2
Up Type=0
Dn Type=3
Dn Slope=0.005
Boundary for River Rch & Prof#=MDW T 061,Reach-1,3
Up Type=0
Dn Type=3
Dn Slope=0.005
Boundary for River Rch & Prof#=MDW T 061,Reach-1,4
Up Type=0
Dn Type=3
Dn Slope=0.005
Boundary for River Rch & Prof#=MDW T 061,Reach-1,5
Up Type=0
Dn Type=3
Dn Slope=0.005
Boundary for River Rch & Prof#=MDW T 061,Reach-1,6
Up Type=0
Dn Type=3
Dn Slope=0.005
Boundary for River Rch & Prof#=MDW T 061,Reach-1,7
Up Type=0
Dn Type=3
Dn Slope=0.005

--- MDW T 061.g01 (geometry) ---

Geom Title=Existing Conditions

River Reach=MDW T 061,Reach-1
Reach XY= 30
      2247459.77      7144213.83      2247622.28      7144135.16
      2247739.80      7144211.93      2247909.83      7144105.19
      2248051.02      7144177.85      2248169.93      7144094.47
      2248328.06      7144102.34      2248759.86      7144287.69
      2248874.81      7144436.87      2249029.65      7144456.39
      2249047.20      7144597.73      2248978.71      7144641.86
      2249008.09      7144773.52      2249123.10      7144781.51
      2249192.38      7144916.31      2249368.06      7144969.57
      2249472.55      7145202.25      2249654.81      7145212.51
      2249724.75      7145404.63      2249690.30      7145450.46
      2249621.24      7145424.69      2249656.72      7145529.84
      2249811.94      7145506.04      2249782.67      7145630.19
      2249985.61      7145758.42      2250027.37      7145748.82
      2250032.01      7145617.84      2250084.02      7145608.81
      2250375.62      7145802.40      2250479.00      7145760.00

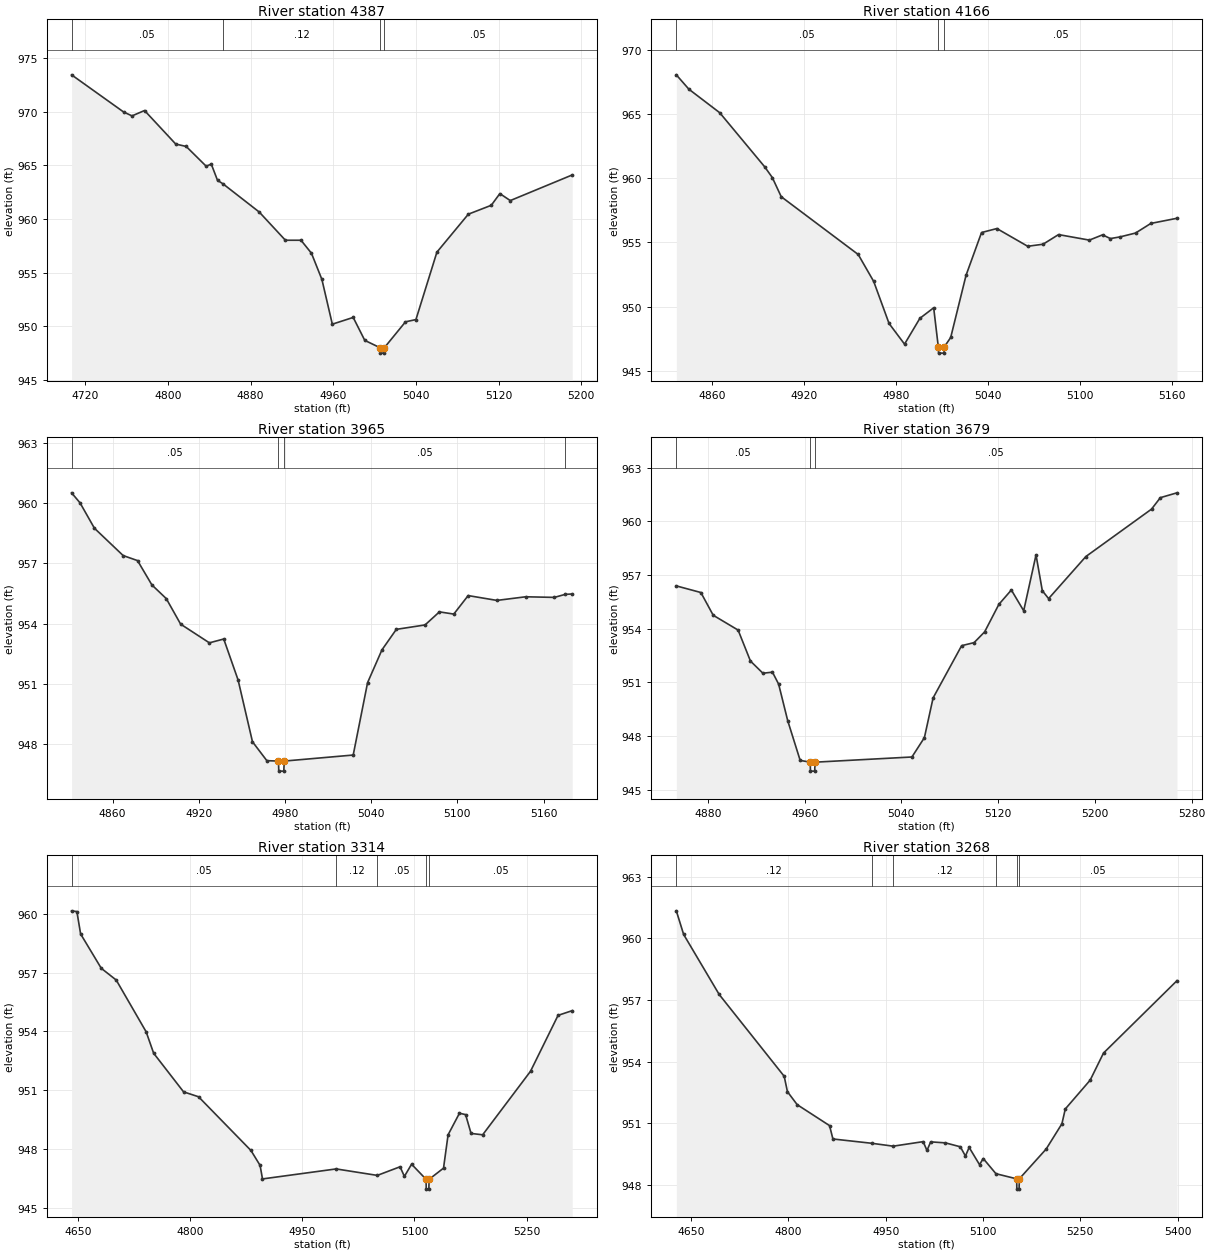
Type RM Length L Ch R = 1,4387,221,221,221
BEGIN DESCRIPTION:
MDW T 061 8.0
END DESCRIPTION:
XS GIS Cut Line= 3
      2247912.46      7144429.89      2247870.74      7144129.33
      2247840.26      7143950.96
#Sta/Elev= 30
  4706.8  973.45  4757.2  969.98  4765.3  969.62  4777.4  970.12  4807.6  966.99
  4817.7  966.77  4837.0  964.93  4842.0  965.12  4848.0  963.61  4853.2  963.29
  4888.4  960.65  4913.7  958.02  4928.8  958.02  4938.9  956.81  4949.0  954.37
  4959.1  950.19  4979.3  950.82  4990.5  948.68  5005.4  947.99  5005.6  947.49
  5009.1  947.49  5009.4  947.99  5029.9  950.41  5040.0  950.62  5060.3  956.91
  5090.7  960.45  5112.9  961.28  5121.2  962.37  5131.3  961.72  5191.2  964.11
#Mann=4,-1,0
  4706.8    0.05       0  4853.2    0.12       0  5005.4    0.07       0
  5009.4    0.05       0
Bank Sta=5005.4,5009.4
Exp/Cntr=0.3,0.1

Type RM Length L Ch R = 1,4166,201,201,201
BEGIN DESCRIPTION:
Mapping XS 726ad04c
END DESCRIPTION:
XS GIS Cut Line= 2
      2248069.62      7144338.14      2248039.93      7144013.09
#Sta/Elev= 30
  4836.7  968.04  4844.9  966.92  4865.0  965.09  4894.3  960.88  4899.3  960.04
  4905.1  958.55  4955.3  954.05  4965.4  951.95  4975.4  948.68  4985.5  947.07
  4995.5  949.08  5004.5  949.90  5007.5  946.87  5007.7  946.37  5011.2  946.37
  5011.5  946.87  5015.6  947.59  5025.6  952.43  5035.7  955.76  5045.7  956.07
  5065.8  954.69  5075.8  954.85  5085.9  955.60  5106.0  955.17  5114.6  955.58
  5119.7  955.29  5126.0  955.42  5136.1  955.72  5146.1  956.47  5163.1  956.87
#Mann=3,-1,0
  4836.7    0.05       0  5007.5   0.033       0  5011.5    0.05       0
Bank Sta=5007.5,5011.5
Exp/Cntr=0.3,0.1

Type RM Length L Ch R = 1,3965,286,286,286
BEGIN DESCRIPTION:
Mapping XS 476fdd15
END DESCRIPTION:
XS GIS Cut Line= 2
      2248226.63      7144265.92      2248233.30      7143917.59
#Sta/Elev= 30
  4831.5  960.51  4837.4  960.01  4847.4  958.75  4867.4  957.39  4877.4  957.14
  4887.4  955.93  4897.4  955.25  4907.4  953.98  4927.4  953.05  4937.4  953.24
  4947.4  951.20  4957.4  948.13  4967.4  947.19  4975.5  947.17  4975.7  946.67
  4979.2  946.67  4979.5  947.17  5027.5  947.47  5037.5  951.07  5047.5  952.70
  5057.5  953.72  5077.5  953.94  5087.5  954.59  5097.5  954.48  5107.5  955.40
  5127.5  955.16  5147.5  955.34  5167.5  955.31  5175.0  955.46  5179.9  955.48
#Mann=4,-1,0
  4831.5    0.05       0  4975.5   0.033       0  4979.5    0.05       0
  5175.0    0.12       0
Bank Sta=4975.5,4979.5
Exp/Cntr=0.3,0.1

Type RM Length L Ch R = 1,3679,365,365,365
BEGIN DESCRIPTION:
Mapping XS 0ed03d2a
END DESCRIPTION:
XS GIS Cut Line= 2
      2248455.35      7144329.74      2248549.27      7143926.63
#Sta/Elev= 30
  4853.9  956.39  4874.2  956.02  4884.4  954.75  4905.0  953.92  4915.2  952.19
  4925.5  951.51  4933.4  951.57  4938.5  950.90  4946.0  948.86  4956.3  946.64
  4964.6  946.54  4964.8  946.04  4968.3  946.04  4968.6  946.54  5048.7  946.83
  5059.0  947.91  5066.2  950.13  5089.8  953.05  5100.1  953.22  5108.8  953.82
  5120.6  955.36  5130.9  956.16  5141.1  955.00  5151.3  958.12  5156.5  956.12
  5161.7  955.68  5192.5  958.03  5246.8  960.68  5254.1  961.32  5267.8  961.59
#Mann=3,-1,0
  4853.9    0.05       0  4964.6   0.033       0  4968.6    0.05       0
Bank Sta=4964.6,4968.6
Exp/Cntr=0.3,0.1

Type RM Length L Ch R = 1,3314,46,46,46
BEGIN DESCRIPTION:
Mapping XS 886477a9
END DESCRIPTION:
XS GIS Cut Line= 4
      2248459.33      7144405.29      2248708.40      7144397.68
      2248841.73      7144324.75      2249070.80      7144185.55
#Sta/Elev= 30
  4641.6  960.15  4648.7  960.11  4653.7  958.97  4681.3  957.22  4701.3  956.62
  4741.3  953.98  4751.3  952.89  4791.3  950.92  4811.3  950.67  4881.4  947.93
  4893.6  947.17  4896.8  946.48  4995.3  946.99  5050.3  946.66  5080.7  947.10
  5086.5  946.61  5096.1  947.23  5115.5  946.46  5115.7  945.96  5119.2  945.96
  5119.5  946.46  5138.8  947.03  5144.9  948.73  5160.1  949.83  5168.3  949.76
  5175.6  948.80  5191.1  948.73  5255.1  951.97  5291.9  954.82  5310.8  955.06
#Mann=5,-1,0
  4641.6    0.05       0  4995.3    0.12       0  5050.3    0.05       0
  5115.5    0.07       0  5119.5    0.05       0
Bank Sta=5115.5,5119.5
Exp/Cntr=0.3,0.1

Type RM Length L Ch R = 1,3268,80,80,80
BEGIN DESCRIPTION:
Mapping XS 051d199f
END DESCRIPTION:
XS GIS Cut Line= 5
      2248473.02      7144455.73      2248688.05      7144442.23
      2248768.11      7144417.77      2249018.30      7144277.37
      2249199.50      7144237.02
#Sta/Elev= 30
  4627.2  961.34  4638.5  960.19  4693.3  957.27  4793.5  953.29  4798.5  952.54
  4813.5  951.91  4863.4  950.89  4868.6  950.24  4928.6  950.03  4961.5  949.89
  5007.7  950.11  5013.6  949.68  5019.3  950.10  5042.1  950.05  5065.0  949.86
  5072.9  949.41  5078.6  949.83  5094.6  948.99  5100.3  949.29  5119.9  948.55
  5151.9  948.30  5152.1  947.80  5155.6  947.80  5155.9  948.30  5197.3  949.75
  5221.6  950.98  5226.8  951.70  5265.1  953.10  5285.7  954.42  5398.9  957.94
#Mann=6,-1,0
  4627.2    0.12       0  4928.6    0.05       0  4961.5    0.12       0
  5119.9    0.05       0  5151.9    0.07       0  5155.9    0.05       0
Bank Sta=5151.9,5155.9
Exp/Cntr=0.3,0.1

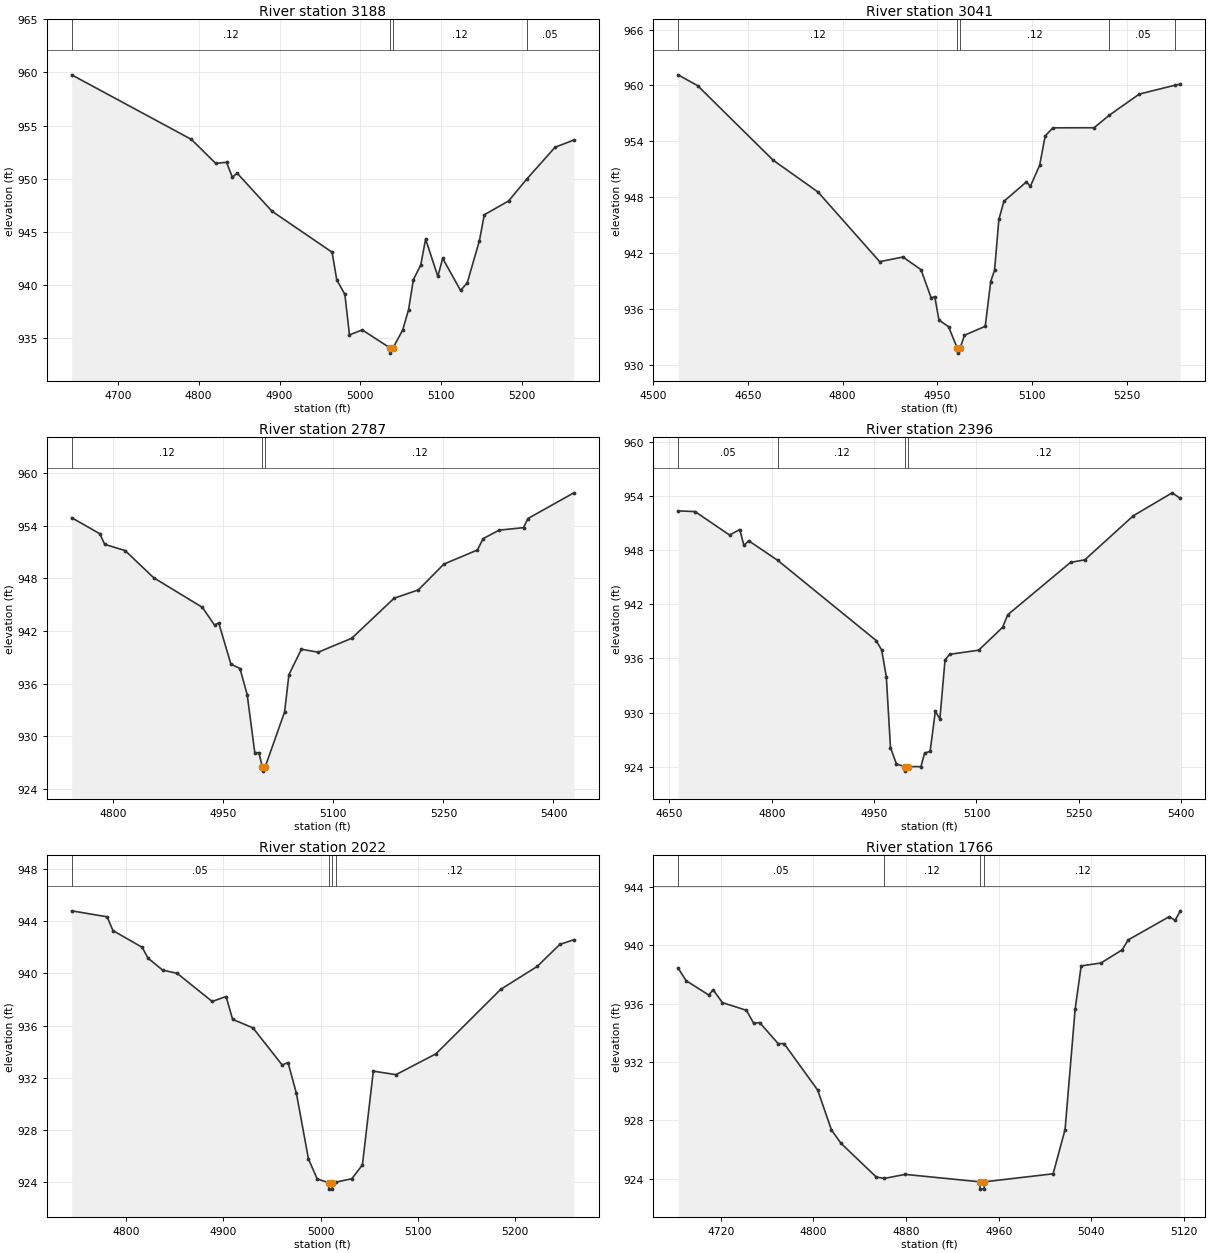
Type RM Length L Ch R = 1,3188,147,147,147
BEGIN DESCRIPTION:
Mapping XS 2ce382f8
END DESCRIPTION:
XS GIS Cut Line= 4
      2248551.04      7144527.70      2248740.19      7144522.36
      2248891.27      7144434.22      2249106.29      7144294.25
#Sta/Elev= 30
  4643.1  959.78  4791.1  953.69  4821.1  951.43  4834.5  951.53  4841.8  950.11
  4847.6  950.51  4890.6  946.92  4965.0  943.05  4970.8  940.44  4980.8  939.07
  4986.5  935.25  5002.3  935.72  5036.4  934.03  5036.7  933.53  5040.4  934.03
  5052.3  935.72  5059.5  937.62  5065.5  940.46  5074.6  941.85  5080.6  944.29
  5095.7  940.77  5101.7  942.47  5123.8  939.44  5132.0  940.15  5147.1  944.14
  5153.1  946.58  5183.3  947.89  5205.4  949.93  5240.6  952.95  5263.8  953.63
#Mann=4,-1,0
  4643.1    0.12       0  5036.4    0.07       0  5040.4    0.12       0
  5205.4    0.05       0
Bank Sta=5036.4,5040.4
Exp/Cntr=0.3,0.1

Type RM Length L Ch R = 1,3041,254,254,254
BEGIN DESCRIPTION:
MDW T 061 6.0
END DESCRIPTION:
XS GIS Cut Line= 3
      2248626.77      7144679.83      2249024.87      7144461.74
      2249303.93      7144265.28
#Sta/Elev= 30
  4539.7  961.14  4570.7  959.97  4690.1  951.98  4761.2  948.56  4858.9  941.08
  4895.7  941.58  4924.3  940.22  4940.4  937.19  4946.1  937.32  4952.7  934.81
  4967.9  934.10  4982.0  931.76  4982.3  931.26  4986.0  931.76  4993.1  933.18
  5026.0  934.14  5034.7  938.95  5040.8  940.18  5047.6  945.61  5055.6  947.56
  5091.3  949.65  5097.4  949.16  5112.2  951.43  5120.9  954.58  5133.2  955.45
  5198.4  955.46  5222.5  956.81  5269.9  959.07  5327.2  960.04  5334.9  960.12
#Mann=5,-1,0
  4539.7    0.12       0  4982.0    0.07       0  4986.0    0.12       0
  5222.5    0.05       0  5327.2    0.12       0
Bank Sta=4982,4986
Exp/Cntr=0.3,0.1

Type RM Length L Ch R = 1,2787,391,391,391
BEGIN DESCRIPTION:
MDW T 061 5.0
END DESCRIPTION:
XS GIS Cut Line= 3
      2248754.89      7144786.13      2248979.89      7144670.60
      2249371.20      7144488.82
#Sta/Elev= 30
  4743.4  954.92  4781.7  953.09  4788.5  951.88  4816.3  951.17  4855.1  948.08
  4921.6  944.70  4938.2  942.67  4943.8  942.94  4960.4  938.24  4972.8  937.73
  4982.6  934.77  4993.0  928.14  4998.6  928.14  5003.2  926.54  5003.5  926.04
  5007.2  926.54  5033.6  932.78  5039.5  937.03  5056.5  939.93  5079.4  939.59
  5125.2  941.18  5182.8  945.74  5215.9  946.69  5250.7  949.63  5296.5  951.24
  5304.1  952.53  5326.1  953.50  5359.2  953.78  5365.2  954.82  5427.8  957.75
#Mann=3,-1,0
  4743.4    0.12       0  5003.2    0.07       0  5007.2    0.12       0
Bank Sta=5003.2,5007.2
Exp/Cntr=0.3,0.1

Type RM Length L Ch R = 1,2396,374,374,374
BEGIN DESCRIPTION:
MDW T 061 4.0
END DESCRIPTION:
XS GIS Cut Line= 3
      2248924.14      7145109.48      2249222.95      7144901.84
      2249470.27      7144624.20
#Sta/Elev= 30
  4662.9  952.36  4687.7  952.28  4738.3  949.68  4753.2  950.29  4759.3  948.52
  4766.2  949.05  4808.7  946.88  4953.1  937.98  4961.1  936.92  4967.9  933.98
  4974.0  926.12  4982.8  924.28  4995.6  924.00  4995.9  923.50  4999.6  924.00
  5018.6  924.00  5024.0  925.49  5032.1  925.70  5039.7  930.13  5046.4  929.30
  5053.9  935.81  5060.6  936.45  5103.2  936.91  5138.3  939.45  5145.8  940.84
  5237.8  946.65  5258.7  946.93  5329.8  951.82  5386.7  954.36  5398.6  953.75
#Mann=4,-1,0
  4662.9    0.05       0  4808.7    0.12       0  4995.6    0.07       0
  4999.6    0.12       0
Bank Sta=4995.6,4999.6
Exp/Cntr=0.3,0.1

Type RM Length L Ch R = 1,2022,256,256,256
BEGIN DESCRIPTION:
MDW T 061 3.0
END DESCRIPTION:
XS GIS Cut Line= 3
      2249217.29      7145287.79      2249429.76      7145144.80
      2249667.78      7145039.44
#Sta/Elev= 30
  4743.9  944.81  4780.4  944.35  4786.4  943.29  4816.4  942.01  4822.4  941.18
  4837.4  940.26  4852.4  940.01  4888.4  937.85  4902.7  938.23  4909.4  936.48
  4930.4  935.82  4960.4  932.97  4966.4  933.16  4975.0  930.80  4987.4  925.76
  4996.4  924.22  5008.1  923.94  5008.4  923.44  5011.9  923.44  5012.1  923.94
  5015.7  923.98  5032.0  924.24  5042.9  925.30  5054.1  932.50  5077.4  932.23
  5118.5  933.83  5185.1  938.78  5222.6  940.54  5245.9  942.23  5260.3  942.59
#Mann=4,-1,0
  4743.9    0.05       0  5008.1   0.033       0  5012.1    0.05       0
  5015.7    0.12       0
Bank Sta=5008.1,5012.1
Exp/Cntr=0.3,0.1

Type RM Length L Ch R = 1,1766,79,79,79
BEGIN DESCRIPTION:
Mapping XS 1fb91791
END DESCRIPTION:
XS GIS Cut Line= 5
      2249342.33      7145226.55      2249426.66      7145251.05
      2249533.66      7145235.21      2249620.68      7145220.60
      2249765.27      7145183.09
#Sta/Elev= 30
  4683.2  938.43  4690.1  937.57  4709.6  936.59  4713.5  936.94  4721.4  936.07
  4742.2  935.54  4748.4  934.66  4753.6  934.70  4769.6  933.26  4774.7  933.26
  4803.7  930.08  4815.6  927.35  4823.9  926.43  4854.3  924.13  4861.1  924.03
  4879.2  924.31  4943.7  923.80  4943.9  923.30  4947.4  923.30  4947.7  923.80
  5007.0  924.35  5017.3  927.38  5026.0  935.62  5031.2  938.58  5048.3  938.78
  5066.6  939.68  5071.8  940.36  5107.2  941.95  5112.3  941.70  5116.8  942.35
#Mann=4,-1,0
  4683.2    0.05       0  4861.1    0.12       0  4943.7    0.07       0
  4947.7    0.12       0
Bank Sta=4943.7,4947.7
Exp/Cntr=0.3,0.1

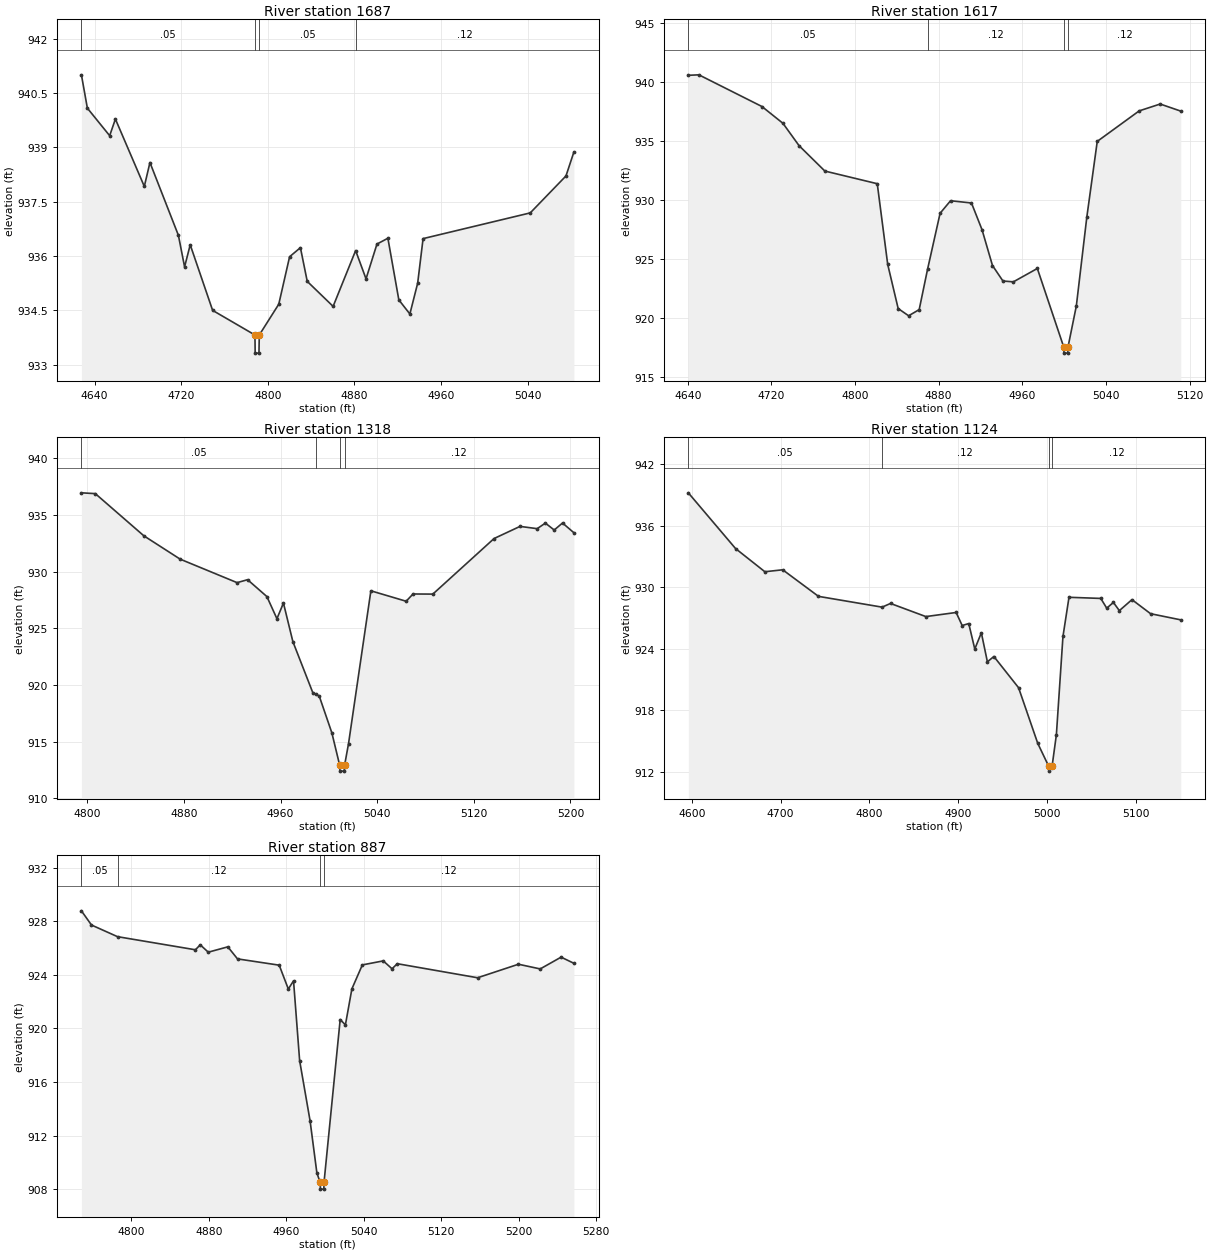
Type RM Length L Ch R = 1,1687,70,70,70
BEGIN DESCRIPTION:
Mapping XS ab1b1631
END DESCRIPTION:
XS GIS Cut Line= 4
      2249313.78      7145265.43      2249450.80      7145309.97
      2249516.56      7145310.55      2249758.80      7145273.53
#Sta/Elev= 30
  4627.8  941.00  4633.3  940.08  4653.9  939.32  4659.2  939.78  4685.9  937.92
  4691.1  938.58  4717.4  936.57  4723.1  935.70  4728.3  936.31  4749.0  934.50
  4788.1  933.82  4788.3  933.32  4791.8  933.32  4792.1  933.82  4810.1  934.67
  4820.1  935.98  4830.1  936.23  4836.4  935.30  4860.3  934.61  4881.1  936.15
  4890.7  935.37  4900.8  936.33  4910.9  936.49  4921.0  934.79  4931.2  934.40
  4938.4  935.25  4943.4  936.48  5042.4  937.19  5075.4  938.21  5082.7  938.87
#Mann=4,-1,0
  4627.8    0.05       0  4788.1    0.07       0  4792.1    0.05       0
  4881.1    0.12       0
Bank Sta=4788.1,4792.1
Exp/Cntr=0.3,0.1

Type RM Length L Ch R = 1,1617,299,299,299
BEGIN DESCRIPTION:
Mapping XS ed0c7212
END DESCRIPTION:
XS GIS Cut Line= 4
      2249338.96      7145341.14      2249444.56      7145351.85
      2249595.97      7145360.17      2249808.67      7145345.26
#Sta/Elev= 30
  4640.6  940.56  4650.7  940.60  4711.0  937.92  4731.1  936.50  4746.5  934.61
  4771.2  932.46  4821.3  931.39  4831.3  924.56  4841.3  920.83  4851.3  920.22
  4861.4  920.74  4869.4  924.15  4881.4  928.89  4891.4  929.95  4911.4  929.76
  4921.5  927.50  4931.5  924.47  4941.5  923.16  4951.5  923.09  4974.4  924.22
  4999.7  917.56  4999.9  917.06  5003.4  917.06  5003.7  917.56  5011.7  921.05
  5021.7  928.55  5031.7  934.97  5071.8  937.55  5091.9  938.13  5111.6  937.53
#Mann=4,-1,0
  4640.6    0.05       0  4869.4    0.12       0  4999.7    0.07       0
  5003.7    0.12       0
Bank Sta=4999.7,5003.7
Exp/Cntr=0.3,0.1

Type RM Length L Ch R = 1,1318,194,194,194
BEGIN DESCRIPTION:
Mapping XS 89c319aa
END DESCRIPTION:
XS GIS Cut Line= 5
      2249447.54      7145548.98      2249577.98      7145537.54
      2249701.71      7145488.30      2249764.24      7145455.30
      2249817.53      7145405.43
#Sta/Elev= 30
  4795.1  936.94  4806.6  936.87  4846.8  933.15  4876.9  931.09  4924.0  929.02
  4932.7  929.28  4948.7  927.79  4957.0  925.84  4962.4  927.22  4970.2  923.82
  4986.7  919.32  4989.1  919.19  4992.0  919.03  5002.5  915.77  5009.0  912.90
  5009.2  912.40  5012.7  912.40  5013.0  912.90  5016.3  914.83  5034.8  928.30
  5064.0  927.38  5069.7  928.02  5086.1  928.01  5136.8  932.91  5158.3  933.98
  5172.5  933.78  5179.3  934.27  5186.6  933.66  5193.5  934.28  5202.9  933.42
#Mann=4,-1,0
  4795.1    0.05       0  4989.1    0.12       0  5009.0    0.07       0
  5013.0    0.12       0
Bank Sta=5009,5013
Exp/Cntr=0.3,0.1

Type RM Length L Ch R = 1,1124,237,237,237
BEGIN DESCRIPTION:
Mapping XS 1170427a
END DESCRIPTION:
XS GIS Cut Line= 3
      2249443.42      7145621.62      2249736.08      7145586.45
      2249910.99      7145394.31
#Sta/Elev= 30
  4596.0  939.21  4649.2  933.78  4682.2  931.52  4702.3  931.71  4742.6  929.12
  4814.2  928.07  4823.7  928.43  4863.5  927.15  4897.6  927.55  4904.4  926.28
  4911.8  926.47  4918.6  923.99  4926.0  925.57  4932.8  922.74  4940.1  923.26
  4967.9  920.22  4989.5  914.80  5001.7  912.59  5002.0  912.09  5005.7  912.59
  5010.5  915.64  5017.9  925.21  5024.7  929.03  5060.5  928.92  5067.2  927.97
  5074.7  928.53  5081.4  927.73  5095.6  928.80  5116.6  927.43  5150.6  926.83
#Mann=4,-1,0
  4596.0    0.05       0  4814.2    0.12       0  5001.7    0.07       0
  5005.7    0.12       0
Bank Sta=5001.7,5005.7
Exp/Cntr=0.3,0.1

Type RM Length L Ch R = 1,887,0,0,0
BEGIN DESCRIPTION:
MDW T 061 1.0
END DESCRIPTION:
XS GIS Cut Line= 4
      2249638.72      7145711.41      2249836.95      7145734.11
      2249911.33      7145550.79      2249954.26      7145447.84
#Sta/Elev= 30
  4748.3  928.79  4758.7  927.73  4785.6  926.86  4866.1  925.88  4871.1  926.25
  4879.4  925.70  4899.6  926.10  4909.6  925.20  4952.7  924.73  4962.1  922.95
  4967.5  923.56  4973.8  917.60  4984.6  913.10  4991.6  909.22  4995.0  908.50
  4995.3  908.00  4998.8  908.00  4999.0  908.50  5015.7  920.67  5021.1  920.27
  5027.8  922.96  5038.6  924.75  5060.2  925.05  5069.3  924.46  5074.7  924.84
  5157.7  923.79  5199.9  924.80  5222.4  924.45  5244.0  925.33  5257.2  924.87
#Mann=4,-1,0
  4748.3    0.05       0  4785.6    0.12       0  4995.0    0.07       0
  4999.0    0.12       0
Bank Sta=4995,4999
Exp/Cntr=0.3,0.1

Chan Stop Cuts=-1