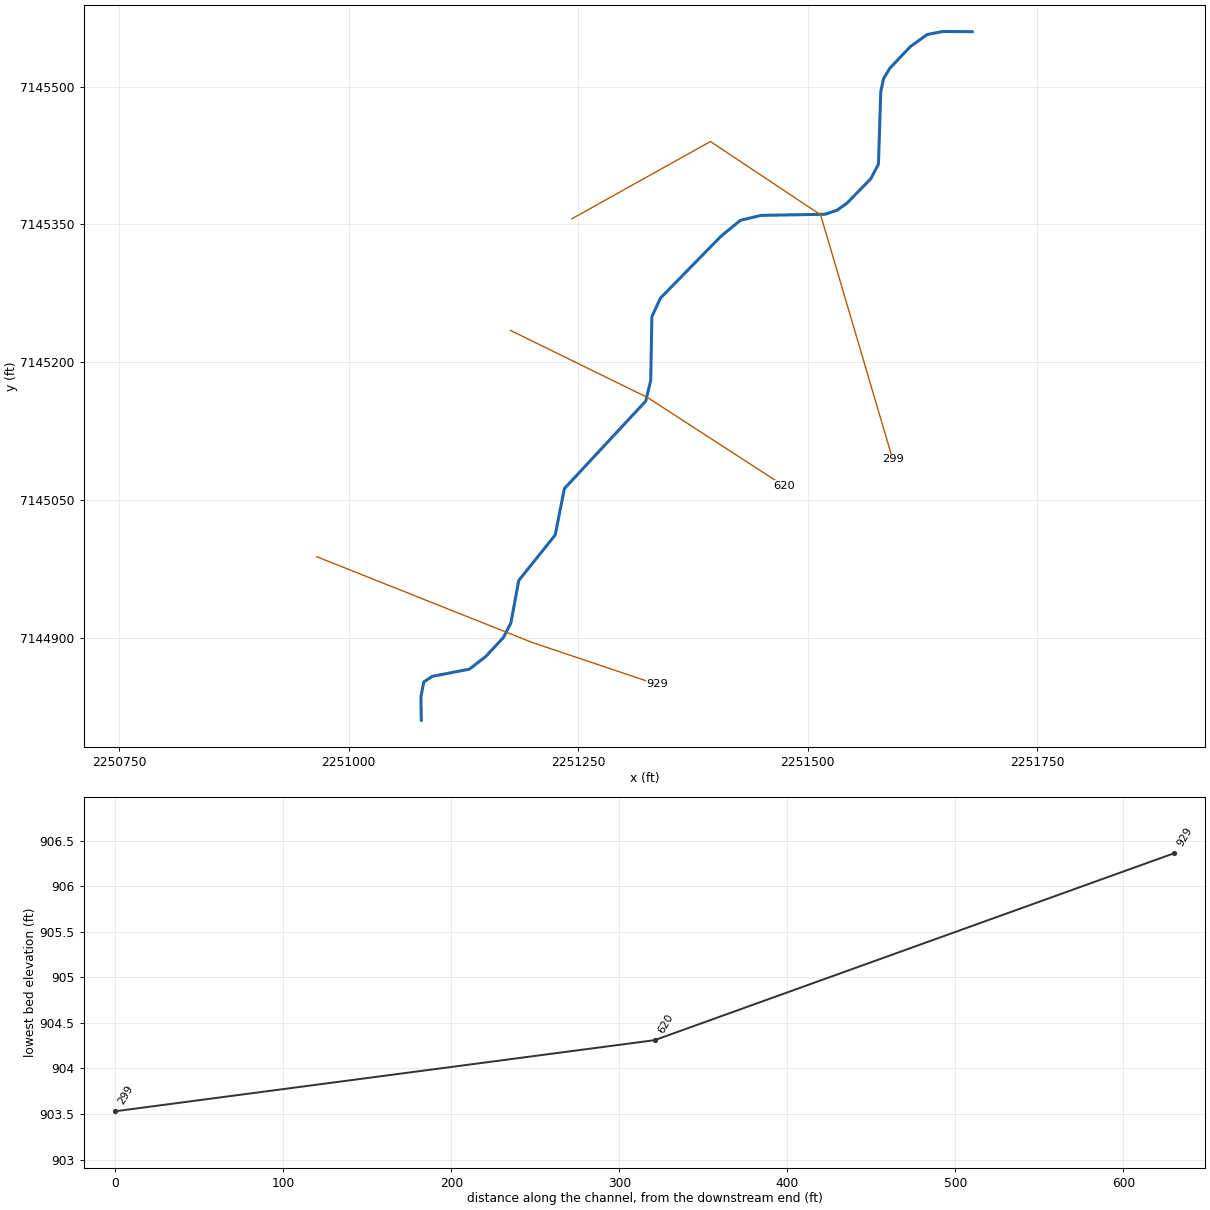
--- MDW T 062.prj (project) ---

Proj Title=MDW T 062 Base Level Engineering
Current Plan=p01
Default Exp/Contr=0.3,0.1
English Units
Geom File=g01
Flow File=f01
Plan File=p01
BEGIN DESCRIPTION:
MDW T 062
END DESCRIPTION:

--- MDW T 062.p01 (plan) ---

Plan Title=Multiple Run
Short Identifier=Multiple
Geom File=g01
Flow File=f01
Subcritical Flow
K Sum by GR= 0
Std Step Tol= 0.01
Critical Tol= 0.01
Num of Std Step Trials= 20
Max Error Tol= 0.3
Flow Tol Ratio= 0.001
Split Flow NTrial= 30
Split Flow Tol= 0.02
Split Flow Ratio= 0.02
Log Output Level= 0
Friction Slope Method= 1
Unsteady Friction Slope Method= 2
Unsteady Bridges Friction Slope Method= 1
Parabolic Critical Depth
Global Vel Dist=  1 , 1 , 1
Global Log Level= 0
CheckData=True
Encroach Param= -1, 0, 0, 0
BEGIN DESCRIPTION:
Multiple Run
END DESCRIPTION:

--- MDW T 062.f01 (steady flow) ---

Flow Title=Multiple
Number of Profiles=7
Profile Names=10-year,25-year,50-year,1pct_min,100-year,1pct_plu,500-year
River Rch & RM= MDW T 062,Reach-1,929
     298     393     470     280     558    1114     788
Boundary for River Rch & Prof#=MDW T 062,Reach-1,1
Up Type=0
Dn Type=3
Dn Slope=0.005
Boundary for River Rch & Prof#=MDW T 062,Reach-1,2
Up Type=0
Dn Type=3
Dn Slope=0.005
Boundary for River Rch & Prof#=MDW T 062,Reach-1,3
Up Type=0
Dn Type=3
Dn Slope=0.005
Boundary for River Rch & Prof#=MDW T 062,Reach-1,4
Up Type=0
Dn Type=3
Dn Slope=0.005
Boundary for River Rch & Prof#=MDW T 062,Reach-1,5
Up Type=0
Dn Type=3
Dn Slope=0.005
Boundary for River Rch & Prof#=MDW T 062,Reach-1,6
Up Type=0
Dn Type=3
Dn Slope=0.005
Boundary for River Rch & Prof#=MDW T 062,Reach-1,7
Up Type=0
Dn Type=3
Dn Slope=0.005

--- MDW T 062.g01 (geometry) ---

Geom Title=Existing Conditions

River Reach=MDW T 062,Reach-1
Reach XY= 30
      2251079.00      7144810.00      2251078.56      7144835.46
      2251081.66      7144851.55      2251090.82      7144857.75
      2251131.42      7144865.60      2251149.41      7144879.62
      2251168.35      7144900.01      2251176.56      7144915.86
      2251185.11      7144962.16      2251224.81      7145011.73
      2251234.85      7145062.29      2251323.46      7145157.58
      2251328.86      7145180.06      2251330.16      7145249.52
      2251339.51      7145269.81      2251405.42      7145337.15
      2251426.56      7145354.48      2251449.06      7145359.87
      2251518.69      7145361.10      2251531.71      7145365.41
      2251542.72      7145373.23      2251568.64      7145399.84
      2251576.94      7145415.69      2251579.47      7145494.88
      2251582.46      7145508.70      2251589.27      7145520.09
      2251611.66      7145543.69      2251629.99      7145556.88
      2251646.93      7145560.15      2251679.00      7145560.00

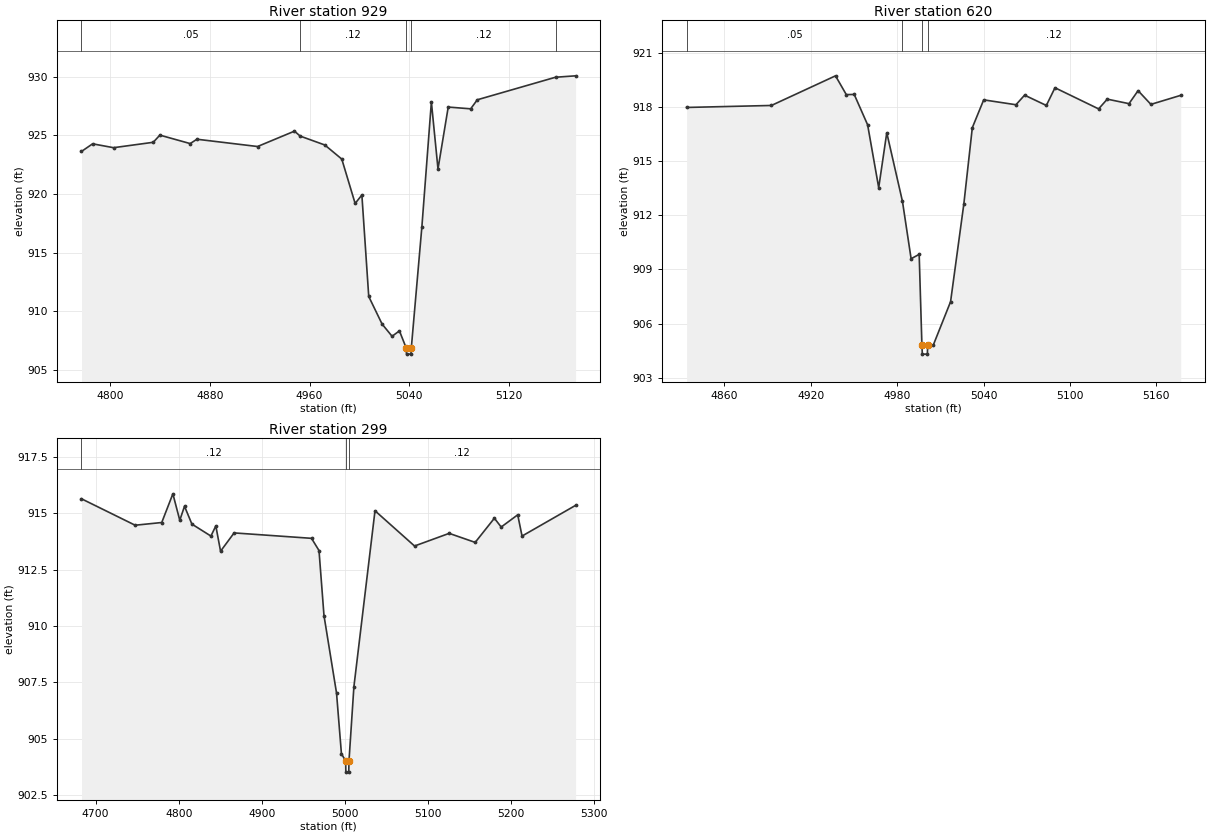
Type RM Length L Ch R = 1,929,309,309,309
BEGIN DESCRIPTION:
MDW T 062 2.0
END DESCRIPTION:
XS GIS Cut Line= 3
      2250965.16      7144988.06      2251199.87      7144894.62
      2251335.77      7144848.91
#Sta/Elev= 30
  4777.2  923.62  4786.1  924.27  4802.9  923.94  4834.7  924.40  4840.0  925.01
  4864.3  924.29  4869.7  924.66  4918.3  924.04  4947.9  925.35  4952.4  924.93
  4972.2  924.17  4985.8  922.97  4996.5  919.19  5001.9  919.91  5007.4  911.27
  5018.1  908.92  5026.1  907.88  5032.0  908.34  5037.5  906.86  5037.7  906.36
  5041.2  906.36  5041.5  906.86  5050.0  917.22  5057.6  927.83  5062.9  922.13
  5071.1  927.40  5089.1  927.25  5094.4  928.02  5157.1  929.94  5173.2  930.06
#Mann=5,-1,0
  4777.2    0.05       0  4952.4    0.12       0  5037.5    0.07       0
  5041.5    0.12       0  5157.1    0.05       0
Bank Sta=5037.5,5041.5
Exp/Cntr=0.3,0.1

Type RM Length L Ch R = 1,620,321,321,321
BEGIN DESCRIPTION:
MDW T 062 1.0
END DESCRIPTION:
XS GIS Cut Line= 3
      2251176.11      7145234.59      2251325.37      7145161.50
      2251473.84      7145065.32
#Sta/Elev= 30
  4833.8  917.96  4892.7  918.07  4937.2  919.71  4944.7  918.67  4950.2  918.68
  4959.5  917.00  4967.2  913.52  4972.8  916.56  4983.7  912.76  4989.7  909.59
  4995.3  909.83  4997.2  904.81  4997.5  904.31  5001.0  904.31  5001.2  904.81
  5005.1  904.81  5017.1  907.21  5026.3  912.61  5032.2  916.84  5040.1  918.38
  5062.5  918.11  5068.5  918.64  5083.6  918.07  5089.6  919.05  5119.9  917.88
  5125.9  918.42  5141.0  918.17  5147.3  918.89  5156.2  918.13  5176.9  918.63
#Mann=4,-1,0
  4833.8    0.05       0  4983.7    0.12       0  4997.2    0.07       0
  5001.2    0.12       0
Bank Sta=4997.2,5001.2
Exp/Cntr=0.3,0.1

Type RM Length L Ch R = 1,299,0,0,0
BEGIN DESCRIPTION:
MDW T 062 0.5
END DESCRIPTION:
XS GIS Cut Line= 4
      2251242.95      7145356.14      2251393.97      7145440.33
      2251513.92      7145360.47      2251592.49      7145094.01
#Sta/Elev= 30
  4683.0  915.63  4747.6  914.46  4779.6  914.58  4793.0  915.85  4801.3  914.68
  4807.0  915.30  4815.9  914.51  4838.8  913.98  4844.7  914.43  4850.4  913.31
  4866.7  914.12  4959.9  913.88  4968.9  913.34  4974.9  910.46  4990.0  907.03
  4995.9  904.34  5001.0  904.03  5001.2  903.53  5004.7  903.53  5005.0  904.03
  5010.9  907.31  5036.3  915.10  5083.9  913.54  5125.6  914.10  5156.9  913.70
  5180.0  914.77  5188.2  914.38  5208.1  914.92  5213.3  913.98  5277.8  915.34
#Mann=3,-1,0
  4683.0    0.12       0  5001.0    0.07       0  5005.0    0.12       0
Bank Sta=5001,5005
Exp/Cntr=0.3,0.1

Chan Stop Cuts=-1