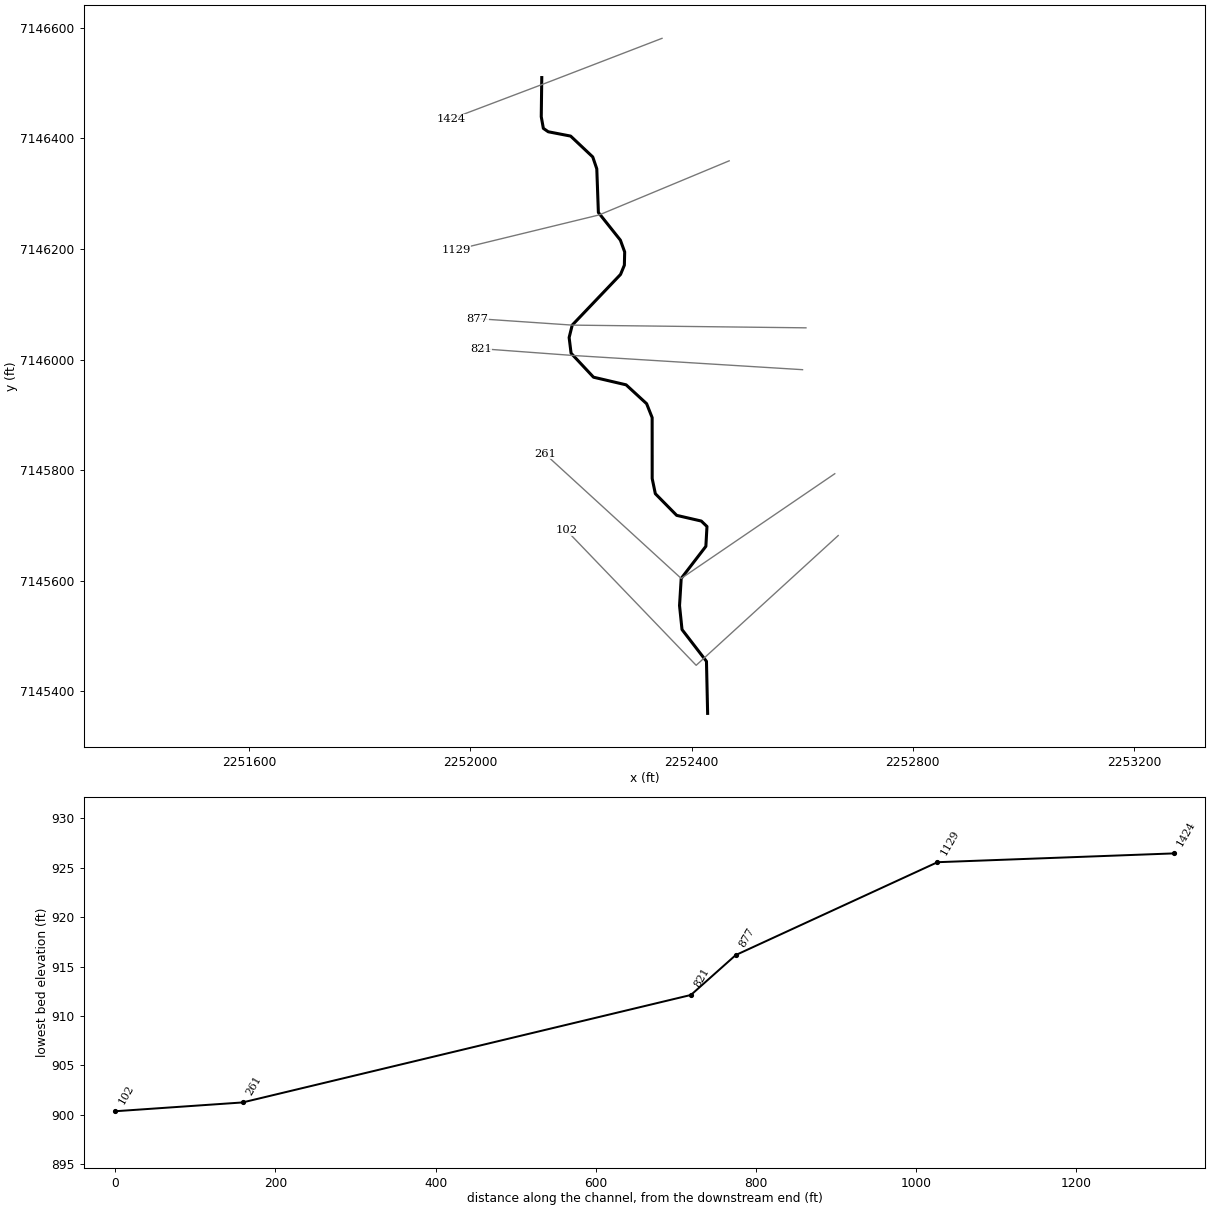
--- MDW T 063.prj (project) ---

Proj Title=MDW T 063 Base Level Engineering
Current Plan=p01
Default Exp/Contr=0.3,0.1
English Units
Geom File=g01
Flow File=f01
Plan File=p01
BEGIN DESCRIPTION:
MDW T 063
END DESCRIPTION:

--- MDW T 063.p01 (plan) ---

Plan Title=Multiple Run
Short Identifier=Multiple
Geom File=g01
Flow File=f01
Subcritical Flow
K Sum by GR= 0
Std Step Tol= 0.01
Critical Tol= 0.01
Num of Std Step Trials= 20
Max Error Tol= 0.3
Flow Tol Ratio= 0.001
Split Flow NTrial= 30
Split Flow Tol= 0.02
Split Flow Ratio= 0.02
Log Output Level= 0
Friction Slope Method= 1
Unsteady Friction Slope Method= 2
Unsteady Bridges Friction Slope Method= 1
Parabolic Critical Depth
Global Vel Dist=  1 , 1 , 1
Global Log Level= 0
CheckData=True
Encroach Param= -1, 0, 0, 0
BEGIN DESCRIPTION:
Multiple Run
END DESCRIPTION:

--- MDW T 063.f01 (steady flow) ---

Flow Title=Multiple
Number of Profiles=7
Profile Names=10-year,25-year,50-year,1pct_min,100-year,1pct_plu,500-year
River Rch & RM= MDW T 063,Reach-1,1424
     174     220     255     148     296     590     396
Boundary for River Rch & Prof#=MDW T 063,Reach-1,1
Up Type=0
Dn Type=3
Dn Slope=0.005
Boundary for River Rch & Prof#=MDW T 063,Reach-1,2
Up Type=0
Dn Type=3
Dn Slope=0.005
Boundary for River Rch & Prof#=MDW T 063,Reach-1,3
Up Type=0
Dn Type=3
Dn Slope=0.005
Boundary for River Rch & Prof#=MDW T 063,Reach-1,4
Up Type=0
Dn Type=3
Dn Slope=0.005
Boundary for River Rch & Prof#=MDW T 063,Reach-1,5
Up Type=0
Dn Type=3
Dn Slope=0.005
Boundary for River Rch & Prof#=MDW T 063,Reach-1,6
Up Type=0
Dn Type=3
Dn Slope=0.005
Boundary for River Rch & Prof#=MDW T 063,Reach-1,7
Up Type=0
Dn Type=3
Dn Slope=0.005

--- MDW T 063.g01 (geometry) ---

Geom Title=Existing Conditions

River Reach=MDW T 063,Reach-1
Reach XY= 30
      2252129.00      7146510.00      2252128.07      7146439.20
      2252131.86      7146418.12      2252140.68      7146411.99
      2252181.22      7146404.16      2252221.21      7146366.44
      2252228.52      7146344.90      2252231.39      7146265.97
      2252271.21      7146215.91      2252278.97      7146194.58
      2252278.40      7146170.62      2252271.50      7146153.95
      2252184.07      7146062.26      2252178.50      7146039.77
      2252182.01      7146011.43      2252222.59      7145968.05
      2252281.55      7145954.25      2252318.65      7145920.12
      2252328.65      7145894.96      2252328.71      7145784.81
      2252334.41      7145757.32      2252373.02      7145718.15
      2252417.58      7145707.86      2252427.81      7145697.98
      2252425.80      7145662.11      2252381.20      7145604.06
      2252378.19      7145554.97      2252382.67      7145511.59
      2252426.89      7145454.13      2252429.00      7145360.00

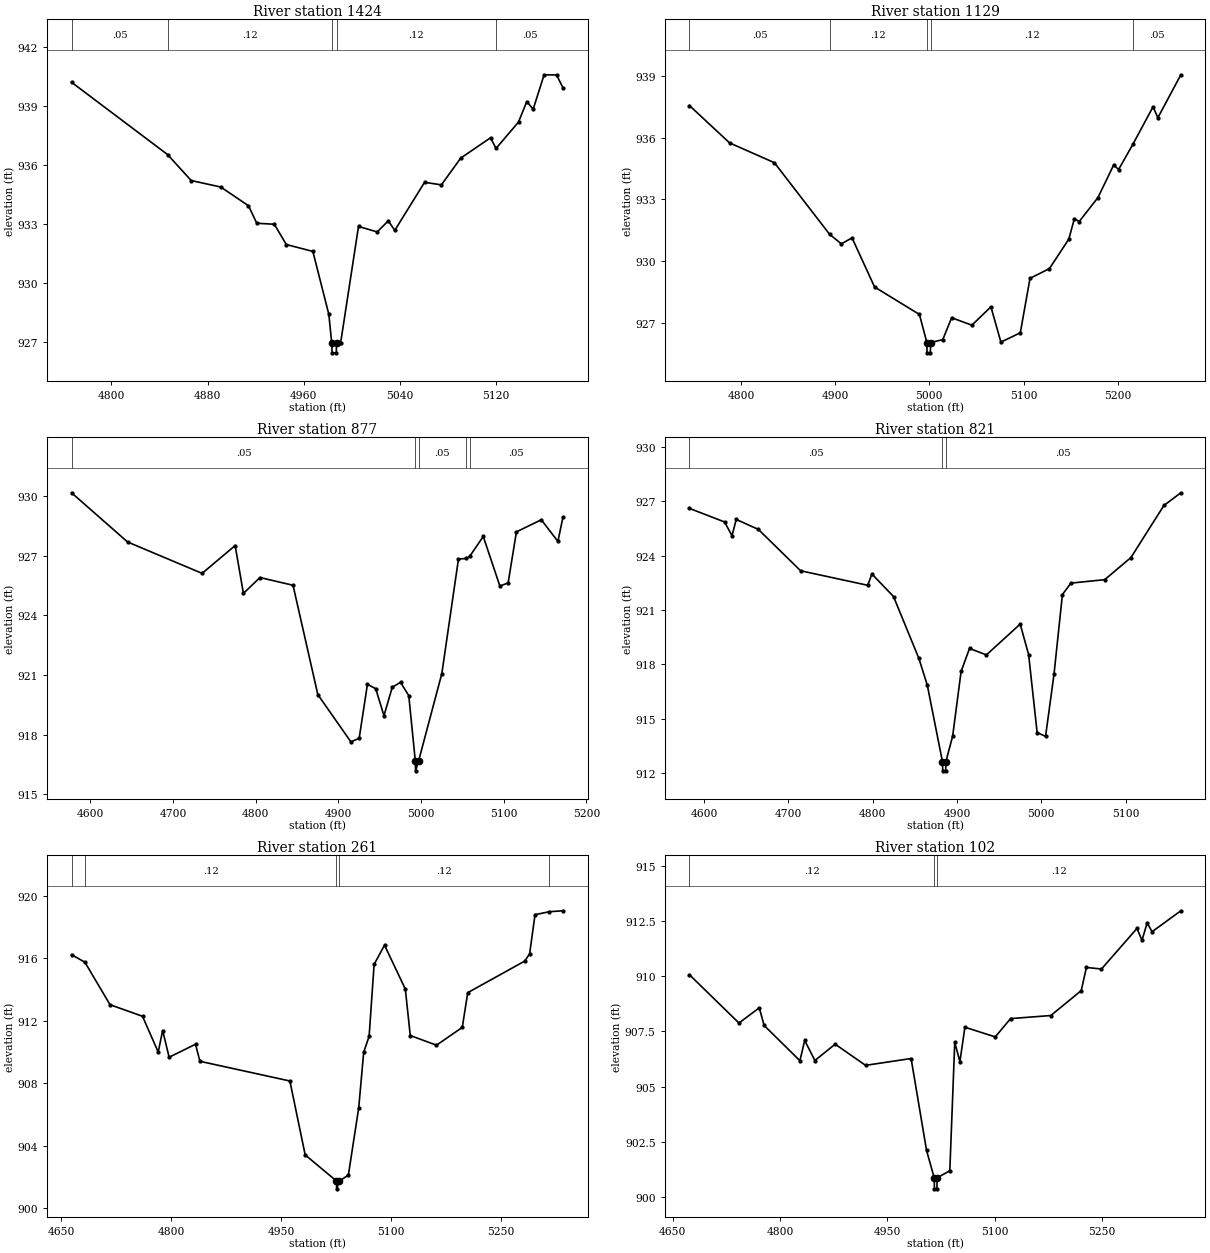
Type RM Length L Ch R = 1,1424,295,295,295
BEGIN DESCRIPTION:
MDW T 063 4.0
END DESCRIPTION:
XS GIS Cut Line= 3
      2252346.49      7146580.97      2252140.90      7146501.79
      2251964.36      7146434.90
#Sta/Elev= 30
  4766.8  940.20  4846.7  936.53  4866.4  935.21  4891.0  934.88  4914.1  933.93
  4921.0  933.04  4935.6  932.99  4945.6  931.96  4967.7  931.61  4981.0  928.41
  4983.4  926.96  4983.7  926.46  4987.2  926.46  4987.4  926.96  4990.8  926.96
  5005.7  932.88  5021.2  932.60  5030.5  933.16  5035.9  932.68  5060.7  935.12
  5074.7  934.99  5090.8  936.35  5115.6  937.38  5120.2  936.84  5138.9  938.18
  5145.8  939.22  5151.1  938.83  5160.2  940.58  5170.6  940.57  5175.9  939.92
#Mann=5,-1,0
  4766.8    0.05       0  4846.7    0.12       0  4983.4    0.07       0
  4987.4    0.12       0  5120.2    0.05       0
Bank Sta=4983.4,4987.4
Exp/Cntr=0.3,0.1

Type RM Length L Ch R = 1,1129,252,252,252
BEGIN DESCRIPTION:
MDW T 063 3.0
END DESCRIPTION:
XS GIS Cut Line= 3
      2252467.95      7146359.41      2252232.89      7146261.59
      2251973.46      7146198.47
#Sta/Elev= 30
  4745.4  937.55  4788.0  935.74  4835.6  934.78  4894.2  931.31  4906.7  930.85
  4918.0  931.14  4941.9  928.76  4989.5  927.43  4997.4  926.07  4997.6  925.57
  5001.1  925.57  5001.4  926.07  5014.3  926.21  5023.7  927.27  5045.2  926.91
  5065.4  927.80  5076.0  926.09  5096.6  926.54  5106.9  929.18  5127.5  929.65
  5148.1  931.08  5154.0  932.07  5159.1  931.93  5179.0  933.09  5195.7  934.67
  5200.9  934.45  5216.3  935.69  5237.5  937.49  5242.6  936.96  5267.0  939.04
#Mann=5,-1,0
  4745.4    0.05       0  4894.2    0.12       0  4997.4    0.07       0
  5001.4    0.12       0  5216.3    0.05       0
Bank Sta=4997.4,5001.4
Exp/Cntr=0.3,0.1

Type RM Length L Ch R = 1,877,56,56,56
BEGIN DESCRIPTION:
MDW T 063 2.0
END DESCRIPTION:
XS GIS Cut Line= 3
      2252606.84      7146057.35      2252184.07      7146062.26
      2252012.87      7146073.93
#Sta/Elev= 30
  4577.2  930.18  4645.0  927.70  4735.1  926.12  4775.1  927.52  4785.1  925.11
  4805.1  925.91  4845.1  925.52  4875.1  920.01  4915.1  917.63  4925.1  917.81
  4935.1  920.53  4945.1  920.31  4955.1  918.95  4965.1  920.38  4975.1  920.63
  4985.1  919.96  4993.0  916.67  4993.3  916.17  4997.0  916.67  5025.1  921.07
  5045.2  926.84  5054.2  926.87  5058.7  926.97  5075.2  927.98  5095.3  925.48
  5105.3  925.64  5115.3  928.21  5145.4  928.82  5165.5  927.73  5171.6  928.95
#Mann=5,-1,0
  4577.2    0.05       0  4993.0   0.033       0  4997.0    0.05       0
  5054.2    0.12       0  5058.7    0.05       0
Bank Sta=4993,4997
Exp/Cntr=0.3,0.1

Type RM Length L Ch R = 1,821,560,560,560
BEGIN DESCRIPTION:
MDW T 063 1.5
END DESCRIPTION:
XS GIS Cut Line= 3
      2252600.66      7145981.65      2252183.96      7146007.46
      2252018.91      7146019.66
#Sta/Elev= 30
  4582.5  926.60  4624.2  925.85  4633.0  925.09  4638.0  925.99  4664.3  925.44
  4714.4  923.16  4794.0  922.36  4799.0  922.98  4824.6  921.74  4854.7  918.33
  4864.7  916.85  4882.7  912.63  4883.0  912.13  4886.5  912.13  4886.7  912.63
  4894.8  914.05  4904.8  917.61  4914.8  918.88  4934.8  918.52  4974.9  920.22
  4984.9  918.54  4995.0  914.24  5005.0  914.03  5015.0  917.45  5025.0  921.85
  5035.1  922.48  5075.2  922.67  5106.3  923.89  5145.4  926.76  5165.5  927.46
#Mann=3,-1,0
  4582.5    0.05       0  4882.7   0.033       0  4886.7    0.05       0
Bank Sta=4882.7,4886.7
Exp/Cntr=0.3,0.1

Type RM Length L Ch R = 1,261,159,159,159
BEGIN DESCRIPTION:
MDW T 063 1.0
END DESCRIPTION:
XS GIS Cut Line= 3
      2252658.97      7145793.47      2252381.20      7145604.06
      2252134.67      7145829.55
#Sta/Elev= 30
  4663.8  916.23  4682.0  915.75  4716.3  913.03  4760.6  912.29  4782.0  910.00
  4788.1  911.38  4796.9  909.67  4832.9  910.50  4838.9  909.41  4961.6  908.15
  4982.5  903.42  5025.2  901.75  5025.4  901.25  5029.2  901.75  5041.4  902.13
  5055.5  906.43  5062.3  909.99  5069.7  911.01  5076.5  915.61  5090.7  916.84
  5119.1  914.03  5125.8  911.06  5161.6  910.44  5196.8  911.58  5204.2  913.80
  5281.9  915.82  5288.6  916.28  5296.0  918.79  5315.5  918.98  5334.1  919.04
#Mann=5,-1,0
  4663.8    0.05       0  4682.0    0.12       0  5025.2    0.07       0
  5029.2    0.12       0  5315.5    0.05       0
Bank Sta=5025.2,5029.2
Exp/Cntr=0.3,0.1

Type RM Length L Ch R = 1,102,0,0,0
BEGIN DESCRIPTION:
MDW T 063 0.5
END DESCRIPTION:
XS GIS Cut Line= 3
      2252665.19      7145681.64      2252408.26      7145446.93
      2252173.50      7145691.21
#Sta/Elev= 30
  4673.2  910.07  4742.4  907.88  4770.8  908.57  4777.6  907.77  4827.6  906.17
  4834.3  907.09  4848.5  906.18  4876.9  906.92  4919.4  905.96  4983.0  906.27
  5004.6  902.10  5015.3  900.86  5015.6  900.36  5019.1  900.36  5019.3  900.86
  5037.1  901.18  5044.0  907.00  5051.2  906.13  5058.2  907.69  5100.6  907.25
  5122.0  908.08  5178.3  908.22  5220.8  909.35  5228.0  910.40  5249.1  910.33
  5298.7  912.17  5305.7  911.63  5312.9  912.42  5319.8  912.02  5360.0  912.97
#Mann=3,-1,0
  4673.2    0.12       0  5015.3    0.07       0  5019.3    0.12       0
Bank Sta=5015.3,5019.3
Exp/Cntr=0.3,0.1

Chan Stop Cuts=-1