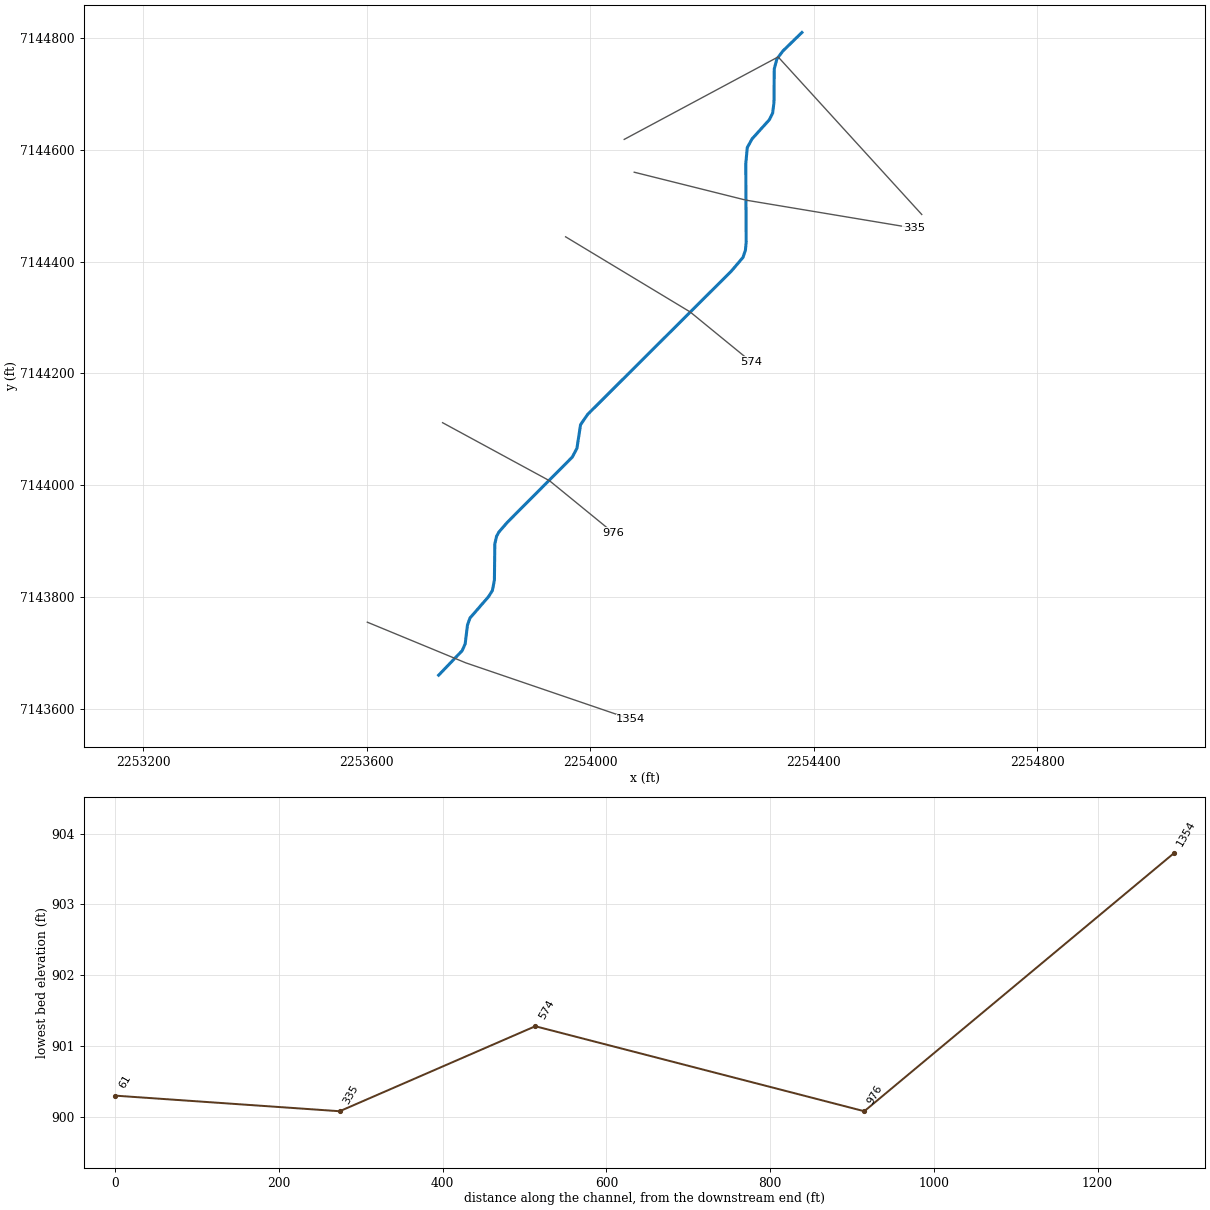
--- MDW T 064.prj (project) ---

Proj Title=MDW T 064 Base Level Engineering
Current Plan=p01
Default Exp/Contr=0.3,0.1
English Units
Geom File=g01
Flow File=f01
Plan File=p01
BEGIN DESCRIPTION:
MDW T 064
END DESCRIPTION:

--- MDW T 064.p01 (plan) ---

Plan Title=Multiple Run
Short Identifier=Multiple
Geom File=g01
Flow File=f01
Subcritical Flow
K Sum by GR= 0
Std Step Tol= 0.01
Critical Tol= 0.01
Num of Std Step Trials= 20
Max Error Tol= 0.3
Flow Tol Ratio= 0.001
Split Flow NTrial= 30
Split Flow Tol= 0.02
Split Flow Ratio= 0.02
Log Output Level= 0
Friction Slope Method= 1
Unsteady Friction Slope Method= 2
Unsteady Bridges Friction Slope Method= 1
Parabolic Critical Depth
Global Vel Dist=  1 , 1 , 1
Global Log Level= 0
CheckData=True
Encroach Param= -1, 0, 0, 0
BEGIN DESCRIPTION:
Multiple Run
END DESCRIPTION:

--- MDW T 064.f01 (steady flow) ---

Flow Title=Multiple
Number of Profiles=7
Profile Names=10-year,25-year,50-year,1pct_min,100-year,1pct_plu,500-year
River Rch & RM= MDW T 064,Reach-1,1354
     223     288     339     200     398     794     546
Boundary for River Rch & Prof#=MDW T 064,Reach-1,1
Up Type=0
Dn Type=3
Dn Slope=0.005
Boundary for River Rch & Prof#=MDW T 064,Reach-1,2
Up Type=0
Dn Type=3
Dn Slope=0.005
Boundary for River Rch & Prof#=MDW T 064,Reach-1,3
Up Type=0
Dn Type=3
Dn Slope=0.005
Boundary for River Rch & Prof#=MDW T 064,Reach-1,4
Up Type=0
Dn Type=3
Dn Slope=0.005
Boundary for River Rch & Prof#=MDW T 064,Reach-1,5
Up Type=0
Dn Type=3
Dn Slope=0.005
Boundary for River Rch & Prof#=MDW T 064,Reach-1,6
Up Type=0
Dn Type=3
Dn Slope=0.005
Boundary for River Rch & Prof#=MDW T 064,Reach-1,7
Up Type=0
Dn Type=3
Dn Slope=0.005

--- MDW T 064.g01 (geometry) ---

Geom Title=Existing Conditions

River Reach=MDW T 064,Reach-1
Reach XY= 30
      2253729.00      7143660.00      2253771.09      7143703.85
      2253776.49      7143716.04      2253780.51      7143749.37
      2253785.03      7143762.22      2253818.18      7143800.34
      2253825.18      7143811.58      2253828.77      7143830.10
      2253829.52      7143894.78      2253832.61      7143908.50
      2253836.86      7143916.17      2253851.88      7143933.52
      2253968.22      7144050.32      2253976.46      7144066.05
      2253982.98      7144108.35      2253995.65      7144126.67
      2254252.83      7144383.13      2254273.54      7144407.55
      2254277.95      7144420.43      2254279.29      7144434.88
      2254278.57      7144575.18      2254281.26      7144604.06
      2254289.85      7144619.65      2254320.82      7144653.96
      2254326.68      7144665.96      2254329.06      7144684.97
      2254329.53      7144744.78      2254334.22      7144762.55
      2254345.12      7144777.05      2254379.00      7144810.00

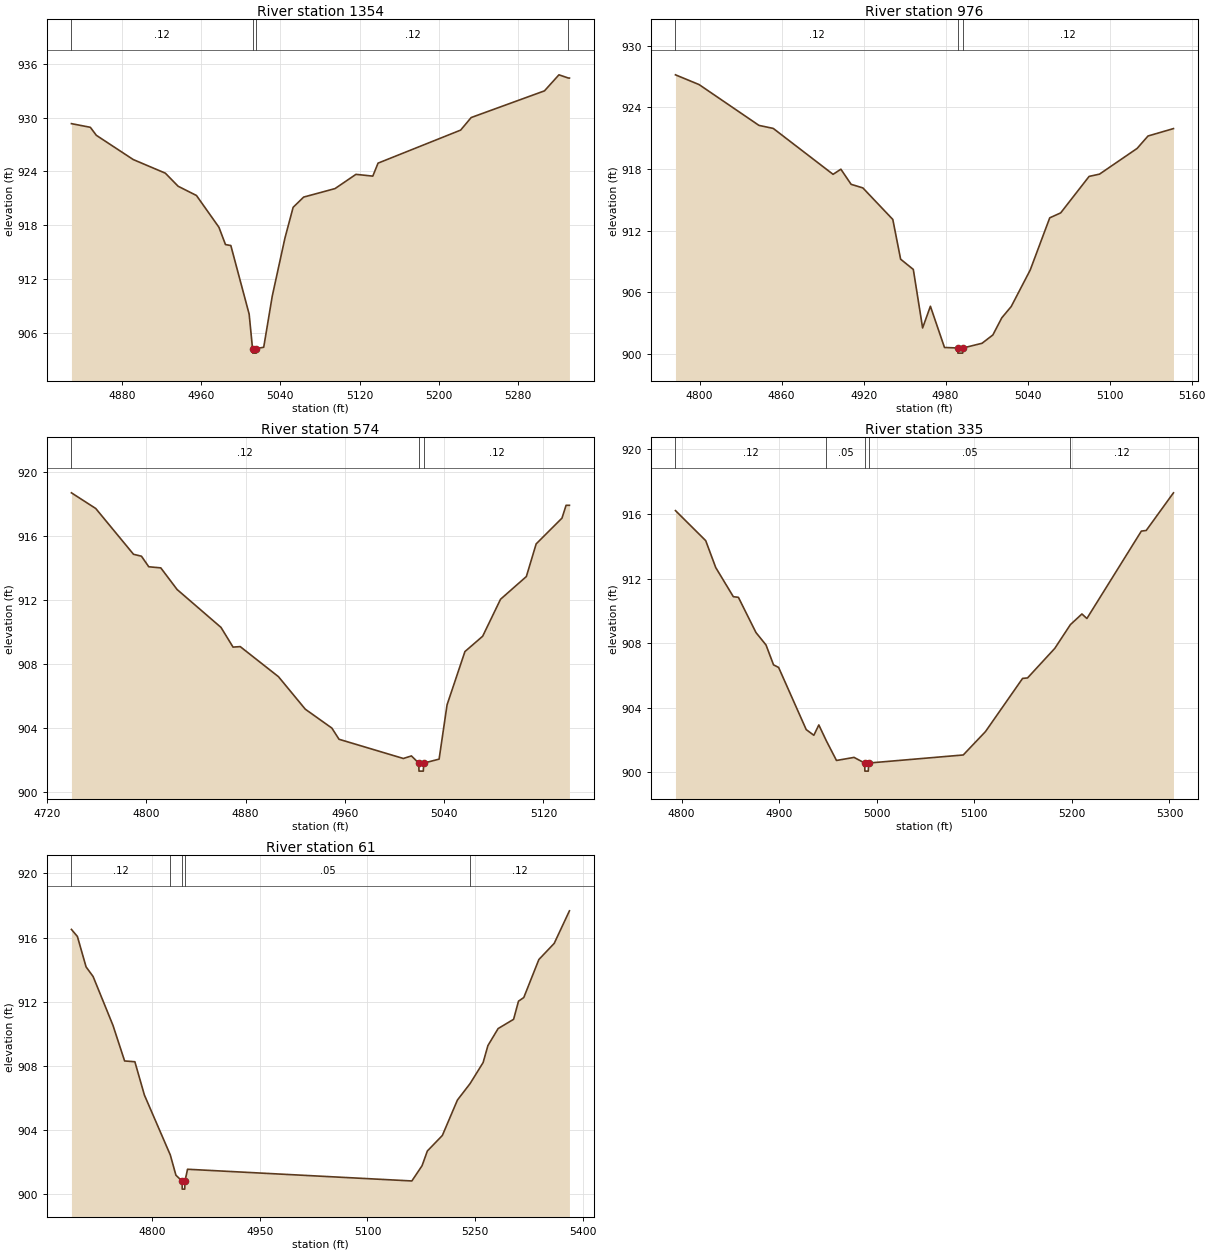
Type RM Length L Ch R = 1,1354,378,378,378
BEGIN DESCRIPTION:
MDW T 064 4.0
END DESCRIPTION:
XS GIS Cut Line= 3
      2253601.37      7143754.82      2253777.66      7143682.02
      2254072.89      7143581.21
#Sta/Elev= 30
  4829.1  929.34  4848.2  928.93  4854.2  928.04  4891.5  925.33  4923.9  923.81
  4936.8  922.35  4955.3  921.32  4978.0  917.77  4984.6  915.84  4990.0  915.73
  5008.5  908.07  5011.9  904.22  5012.2  903.72  5015.7  903.72  5015.9  904.22
  5023.2  904.38  5031.8  910.08  5044.6  916.56  5052.9  920.00  5063.5  921.14
  5095.2  922.09  5116.3  923.68  5133.3  923.48  5138.6  924.93  5222.0  928.62
  5232.6  930.02  5306.6  933.00  5321.2  934.79  5330.8  934.43  5331.8  934.43
#Mann=4,-1,0
  4829.1    0.12       0  5011.9    0.07       0  5015.9    0.12       0
  5330.8    0.05       0
Bank Sta=5011.9,5015.9
Exp/Cntr=0.3,0.1

Type RM Length L Ch R = 1,976,402,402,402
BEGIN DESCRIPTION:
MDW T 064 3.0
END DESCRIPTION:
XS GIS Cut Line= 3
      2253736.03      7144111.79      2253927.28      7144008.00
      2254040.93      7143915.24
#Sta/Elev= 30
  4782.4  927.15  4799.7  926.20  4843.5  922.23  4853.9  921.94  4897.7  917.47
  4903.4  917.97  4910.9  916.50  4919.5  916.15  4941.4  913.08  4947.1  909.22
  4956.4  908.22  4963.2  902.53  4968.9  904.64  4979.2  900.63  4988.8  900.58
  4989.0  900.08  4992.5  900.08  4992.8  900.58  5006.7  901.04  5014.6  901.85
  5021.1  903.51  5028.0  904.61  5041.9  908.16  5056.2  913.24  5064.2  913.72
  5085.0  917.27  5092.6  917.49  5120.1  919.99  5128.1  921.20  5146.7  921.92
#Mann=3,-1,0
  4782.4    0.12       0  4988.8    0.07       0  4992.8    0.12       0
Bank Sta=4988.8,4992.8
Exp/Cntr=0.3,0.1

Type RM Length L Ch R = 1,574,239,239,239
BEGIN DESCRIPTION:
MDW T 064 2.0
END DESCRIPTION:
XS GIS Cut Line= 3
      2253956.15      7144444.44      2254179.00      7144310.00
      2254288.13      7144220.81
#Sta/Elev= 30
  4739.7  918.67  4759.3  917.69  4789.7  914.83  4796.1  914.71  4802.0  914.05
  4811.7  913.98  4824.8  912.63  4860.2  910.26  4869.9  909.03  4875.7  909.06
  4906.5  907.18  4928.1  905.15  4949.5  903.97  4955.3  903.27  5007.1  902.07
  5013.6  902.23  5019.5  901.78  5019.7  901.28  5023.2  901.28  5023.5  901.78
  5035.9  902.03  5042.3  905.42  5056.7  908.75  5071.0  909.71  5085.4  912.02
  5106.2  913.44  5114.1  915.48  5134.9  917.09  5138.2  917.89  5140.9  917.89
#Mann=3,-1,0
  4739.7    0.12       0  5019.5    0.07       0  5023.5    0.12       0
Bank Sta=5019.5,5023.5
Exp/Cntr=0.3,0.1

Type RM Length L Ch R = 1,335,274,274,274
BEGIN DESCRIPTION:
MDW T 064 1.0
END DESCRIPTION:
XS GIS Cut Line= 3
      2254078.97      7144560.01      2254279.00      7144510.00
      2254578.98      7144460.00
#Sta/Elev= 30
  4793.8  916.21  4824.8  914.35  4835.1  912.68  4853.1  910.88  4858.3  910.84
  4876.3  908.66  4886.6  907.89  4894.3  906.66  4899.5  906.50  4927.8  902.65
  4935.6  902.30  4940.7  902.94  4948.3  901.97  4958.8  900.74  4976.8  900.93
  4987.7  900.58  4987.9  900.08  4991.4  900.08  4991.7  900.58  5088.7  901.08
  5111.5  902.53  5149.5  905.82  5154.6  905.85  5182.5  907.68  5198.5  909.15
  5210.3  909.81  5215.4  909.53  5271.2  914.94  5276.2  914.98  5304.1  917.31
#Mann=5,-1,0
  4793.8    0.12       0  4948.3    0.05       0  4987.7   0.033       0
  4991.7    0.05       0  5198.5    0.12       0
Bank Sta=4987.7,4991.7
Exp/Cntr=0.3,0.1

Type RM Length L Ch R = 1,61,0,0,0
BEGIN DESCRIPTION:
MDW T 064 0.5
END DESCRIPTION:
XS GIS Cut Line= 3
      2254061.05      7144618.73      2254336.50      7144766.32
      2254593.48      7144484.36
#Sta/Elev= 30
  4687.5  916.51  4695.8  916.07  4707.9  914.17  4717.7  913.57  4745.4  910.52
  4761.6  908.30  4775.9  908.25  4789.2  906.17  4825.3  902.43  4833.1  901.17
  4841.7  900.80  4841.9  900.30  4845.4  900.30  4845.7  900.80  4849.3  901.54
  5161.9  900.81  5176.1  901.76  5183.5  902.68  5204.4  903.65  5225.4  905.86
  5243.1  906.89  5261.2  908.20  5267.9  909.26  5282.1  910.32  5303.7  910.90
  5310.5  912.03  5317.9  912.26  5338.9  914.63  5360.3  915.64  5381.5  917.67
#Mann=5,-1,0
  4687.5    0.12       0  4825.3    0.05       0  4841.7   0.033       0
  4845.7    0.05       0  5243.1    0.12       0
Bank Sta=4841.7,4845.7
Exp/Cntr=0.3,0.1

Chan Stop Cuts=-1