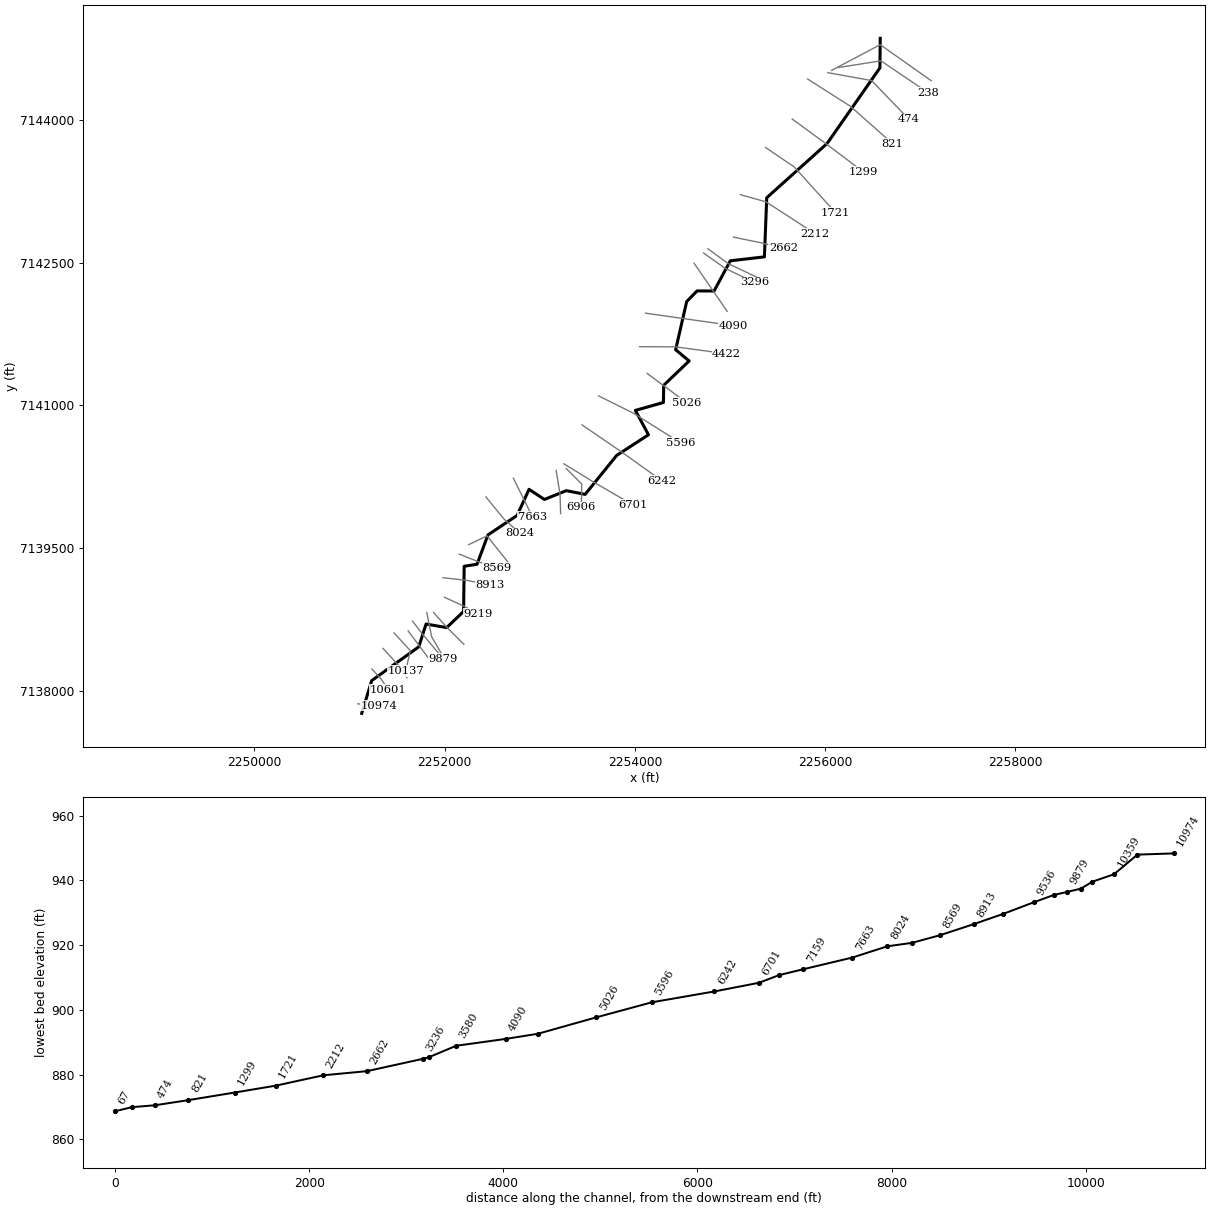
--- MDW T 065.prj (project) ---

Proj Title=MDW T 065 Base Level Engineering
Current Plan=p01
Default Exp/Contr=0.3,0.1
English Units
Geom File=g01
Flow File=f01
Plan File=p01
BEGIN DESCRIPTION:
MDW T 065
END DESCRIPTION:

--- MDW T 065.p01 (plan) ---

Plan Title=Multiple Run
Short Identifier=Multiple
Geom File=g01
Flow File=f01
Subcritical Flow
K Sum by GR= 0
Std Step Tol= 0.01
Critical Tol= 0.01
Num of Std Step Trials= 20
Max Error Tol= 0.3
Flow Tol Ratio= 0.001
Split Flow NTrial= 30
Split Flow Tol= 0.02
Split Flow Ratio= 0.02
Log Output Level= 0
Friction Slope Method= 1
Unsteady Friction Slope Method= 2
Unsteady Bridges Friction Slope Method= 1
Parabolic Critical Depth
Global Vel Dist=  1 , 1 , 1
Global Log Level= 0
CheckData=True
Encroach Param= -1, 0, 0, 0
BEGIN DESCRIPTION:
Multiple Run
END DESCRIPTION:

--- MDW T 065.f01 (steady flow) ---

Flow Title=Multiple
Number of Profiles=7
Profile Names=10-year,25-year,50-year,1pct_min,100-year,1pct_plu,500-year
River Rch & RM= MDW T 065,Reach-1,10974
     515     706     865     528    1053    2101    1560
River Rch & RM= MDW T 065,Reach-1,10016
     732    1025    1273     786    1568    3128    2382
River Rch & RM= MDW T 065,Reach-1,8024
     924    1310    1641    1021    2036    4063    3143
River Rch & RM= MDW T 065,Reach-1,6701
    1269    1829    2315    1454    2900    5787    4564
River Rch & RM= MDW T 065,Reach-1,4422
    1474    2134    2708    1704    3399    6783    5371
Boundary for River Rch & Prof#=MDW T 065,Reach-1,1
Up Type=0
Dn Type=3
Dn Slope=0.005
Boundary for River Rch & Prof#=MDW T 065,Reach-1,2
Up Type=0
Dn Type=3
Dn Slope=0.005
Boundary for River Rch & Prof#=MDW T 065,Reach-1,3
Up Type=0
Dn Type=3
Dn Slope=0.005
Boundary for River Rch & Prof#=MDW T 065,Reach-1,4
Up Type=0
Dn Type=3
Dn Slope=0.005
Boundary for River Rch & Prof#=MDW T 065,Reach-1,5
Up Type=0
Dn Type=3
Dn Slope=0.005
Boundary for River Rch & Prof#=MDW T 065,Reach-1,6
Up Type=0
Dn Type=3
Dn Slope=0.005
Boundary for River Rch & Prof#=MDW T 065,Reach-1,7
Up Type=0
Dn Type=3
Dn Slope=0.005

--- MDW T 065.g01 (geometry) ---

Geom Title=Existing Conditions

River Reach=MDW T 065,Reach-1
Reach XY= 30
      2251129.00      7137760.00      2251234.11      7138104.89
      2251729.00      7138460.00      2251805.15      7138699.84
      2252021.72      7138662.05      2252199.66      7138832.00
      2252205.81      7139307.07      2252341.34      7139328.80
      2252455.85      7139637.35      2252762.57      7139842.38
      2252887.61      7140116.67      2253049.10      7140009.91
      2253278.99      7140102.47      2253477.55      7140063.48
      2253808.04      7140472.54      2254143.10      7140690.44
      2254005.11      7140946.58      2254300.02      7141029.77
      2254302.95      7141210.69      2254570.33      7141466.53
      2254428.46      7141584.88      2254544.68      7142091.70
      2254654.09      7142203.56      2254832.37      7142202.41
      2255003.20      7142520.16      2255361.65      7142561.69
      2255386.00      7143183.41      2256020.56      7143754.07
      2256575.57      7144549.31      2256579.00      7144860.00

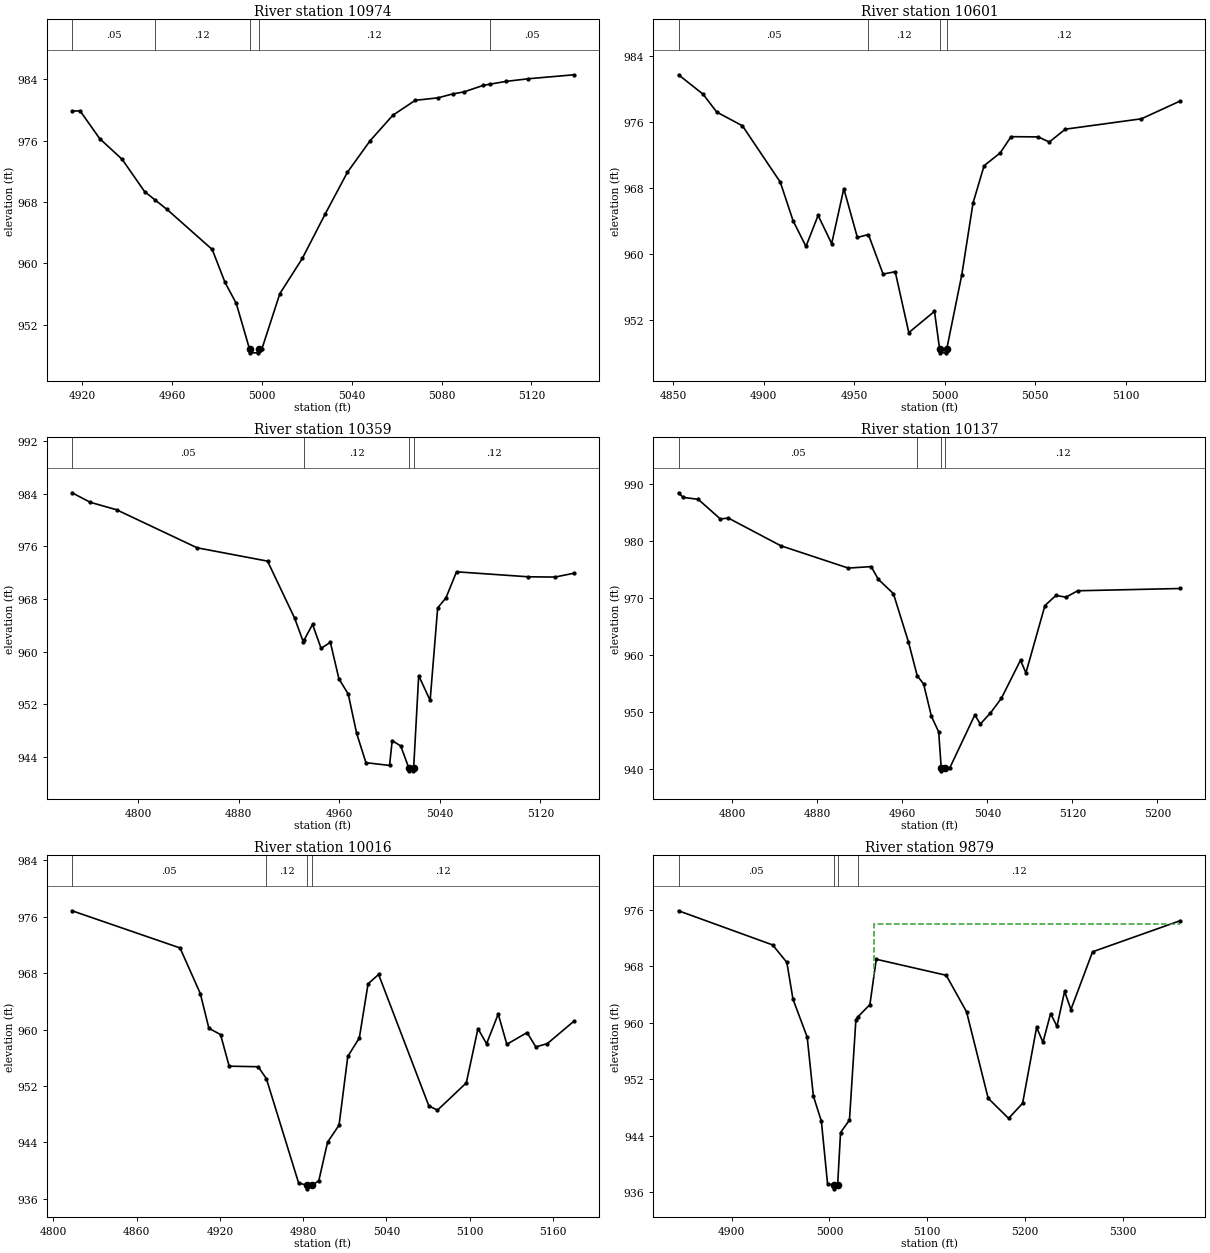
Type RM Length L Ch R = 1,10974,373,373,373
BEGIN DESCRIPTION:
MDW T 065 26.0
END DESCRIPTION:
XS GIS Cut Line= 3
      2251086.78      7137860.00      2251171.05      7137853.86
      2251309.22      7137839.60
#Sta/Elev= 30
  4915.5  979.87  4919.1  979.87  4927.8  976.26  4937.8  973.56  4947.8  969.35
  4952.5  968.25  4957.8  967.02  4977.9  961.80  4983.6  957.50  4988.6  954.77
  4994.5  948.82  4994.7  948.32  4998.2  948.32  4998.5  948.82  5000.0  948.82
  5008.0  956.04  5018.0  960.63  5028.1  966.38  5038.1  971.88  5048.2  975.99
  5058.3  979.31  5068.3  981.26  5078.4  981.58  5084.9  982.09  5089.9  982.35
  5098.5  983.20  5101.5  983.36  5108.5  983.72  5118.6  984.07  5138.9  984.59
#Mann=5,-1,0
  4915.5    0.05       0  4952.5    0.12       0  4994.5    0.07       0
  4998.5    0.12       0  5101.5    0.05       0
Bank Sta=4994.5,4998.5
Exp/Cntr=0.3,0.1

Type RM Length L Ch R = 1,10601,242,242,242
BEGIN DESCRIPTION:
MDW T 065 25.0
END DESCRIPTION:
XS GIS Cut Line= 3
      2251236.54      7138226.96      2251335.11      7138117.90
      2251407.95      7138009.98
#Sta/Elev= 30
  4853.0  981.74  4866.6  979.37  4874.1  977.21  4888.3  975.54  4909.2  968.70
  4916.3  963.99  4923.4  960.88  4930.1  964.65  4937.6  961.22  4944.3  967.90
  4951.8  961.97  4957.9  962.33  4966.0  957.52  4972.7  957.81  4980.2  950.41
  4994.4  952.99  4997.2  948.45  4997.4  947.95  5000.9  947.95  5001.2  948.45
  5009.5  957.46  5015.7  966.17  5021.8  970.69  5030.7  972.25  5036.7  974.22
  5051.7  974.19  5057.8  973.57  5066.7  975.13  5108.7  976.39  5130.2  978.56
#Mann=4,-1,0
  4853.0    0.05       0  4957.9    0.12       0  4997.2    0.07       0
  5001.2    0.12       0
Bank Sta=4997.2,5001.2
Exp/Cntr=0.3,0.1

Type RM Length L Ch R = 1,10359,222,222,222
BEGIN DESCRIPTION:
MDW T 065 24.0
END DESCRIPTION:
XS GIS Cut Line= 3
      2251352.37      7138443.60      2251523.27      7138257.46
      2251604.01      7138134.98
#Sta/Elev= 30
  4747.3  984.14  4761.7  982.70  4782.7  981.56  4846.8  975.78  4902.9  973.75
  4924.5  965.06  4931.3  961.51  4932.2  961.83  4938.7  964.14  4945.5  960.50
  4952.9  961.41  4959.7  955.86  4967.1  953.56  4973.8  947.58  4981.2  943.12
  5000.0  942.70  5002.1  946.47  5008.9  945.66  5015.2  942.38  5015.5  941.88
  5019.0  941.88  5019.2  942.38  5023.2  956.35  5032.3  952.58  5038.3  966.64
  5044.9  968.17  5053.3  972.13  5110.5  971.37  5131.6  971.33  5146.7  971.91
#Mann=4,-1,0
  4747.3    0.05       0  4932.2    0.12       0  5015.2    0.07       0
  5019.2    0.12       0
Bank Sta=5015.2,5019.2
Exp/Cntr=0.3,0.1

Type RM Length L Ch R = 1,10137,121,121,121
BEGIN DESCRIPTION:
MDW T 065 23.5
END DESCRIPTION:
XS GIS Cut Line= 3
      2251469.05      7138605.94      2251639.97      7138419.77
      2251591.07      7138205.82
#Sta/Elev= 30
  4749.3  988.48  4753.6  987.67  4767.8  987.33  4788.7  983.87  4796.1  984.04
  4845.5  979.17  4909.0  975.24  4930.6  975.50  4937.3  973.26  4951.5  970.75
  4965.7  962.23  4973.9  956.30  4979.9  954.88  4987.3  949.16  4994.1  946.44
  4996.5  940.09  4996.7  939.59  5000.5  940.09  5004.5  940.09  5028.1  949.41
  5033.3  947.83  5042.8  949.75  5053.1  952.34  5071.1  959.04  5076.2  956.81
  5094.1  968.65  5104.4  970.42  5114.0  970.13  5124.9  971.25  5221.5  971.65
#Mann=4,-1,0
  4749.3    0.05       0  4973.9    0.12       0  4996.5    0.07       0
  5000.5    0.12       0
Bank Sta=4996.5,5000.5
Exp/Cntr=0.3,0.1

Type RM Length L Ch R = 1,10016,137,137,137
BEGIN DESCRIPTION:
Mapping XS a845a431
END DESCRIPTION:
XS GIS Cut Line= 2
      2251617.17      7138626.97      2251833.65      7138337.32
#Sta/Elev= 30
  4813.5  976.85  4891.3  971.58  4905.9  965.12  4912.1  960.19  4920.5  959.30
  4926.7  954.82  4947.6  954.74  4953.5  953.06  4976.7  938.29  4982.5  937.93
  4982.7  937.43  4986.5  937.93  4991.3  938.58  4997.6  944.03  5005.9  946.47
  5012.2  956.21  5020.5  958.82  5026.8  966.50  5034.4  967.82  5070.6  949.19
  5076.8  948.58  5097.6  952.45  5106.0  960.14  5112.2  958.00  5120.6  962.21
  5126.8  957.92  5141.4  959.58  5147.7  957.55  5156.0  958.02  5175.1  961.19
#Mann=4,-1,0
  4813.5    0.05       0  4953.5    0.12       0  4982.5    0.07       0
  4986.5    0.12       0
Bank Sta=4982.5,4986.5
Exp/Cntr=0.3,0.1

Type RM Length L Ch R = 1,9879,138,138,138
BEGIN DESCRIPTION:
MDW T 065 23.0
END DESCRIPTION:
XS GIS Cut Line= 3
      2251663.96      7138729.24      2251765.00      7138596.97
      2251987.77      7138331.63
#Sta/Elev= 30
  4845.7  975.85  4941.9  971.01  4956.4  968.54  4962.7  963.32  4977.2  957.95
  4983.5  949.61  4991.7  946.03  4998.0  937.19  5004.3  936.95  5004.5  936.45
  5008.3  936.95  5011.3  944.43  5020.4  946.19  5027.0  960.43  5028.8  960.79
  5041.3  962.55  5047.8  968.98  5119.3  966.71  5140.1  961.53  5162.2  949.28
  5183.1  946.43  5197.4  948.58  5211.7  959.33  5218.2  957.22  5226.0  961.28
  5232.5  959.48  5240.3  964.42  5246.8  961.86  5268.9  970.04  5358.6  974.45
#Mann=4,-1,0
  4845.7    0.05       0  5004.3   0.033       0  5008.3    0.05       0
  5028.8    0.12       0
#XS Ineff=2,0
       0                 5045.20    0.00  973.99
Permanent Ineff=
       F       F
Bank Sta=5004.3,5008.3
Exp/Cntr=0.3,0.1

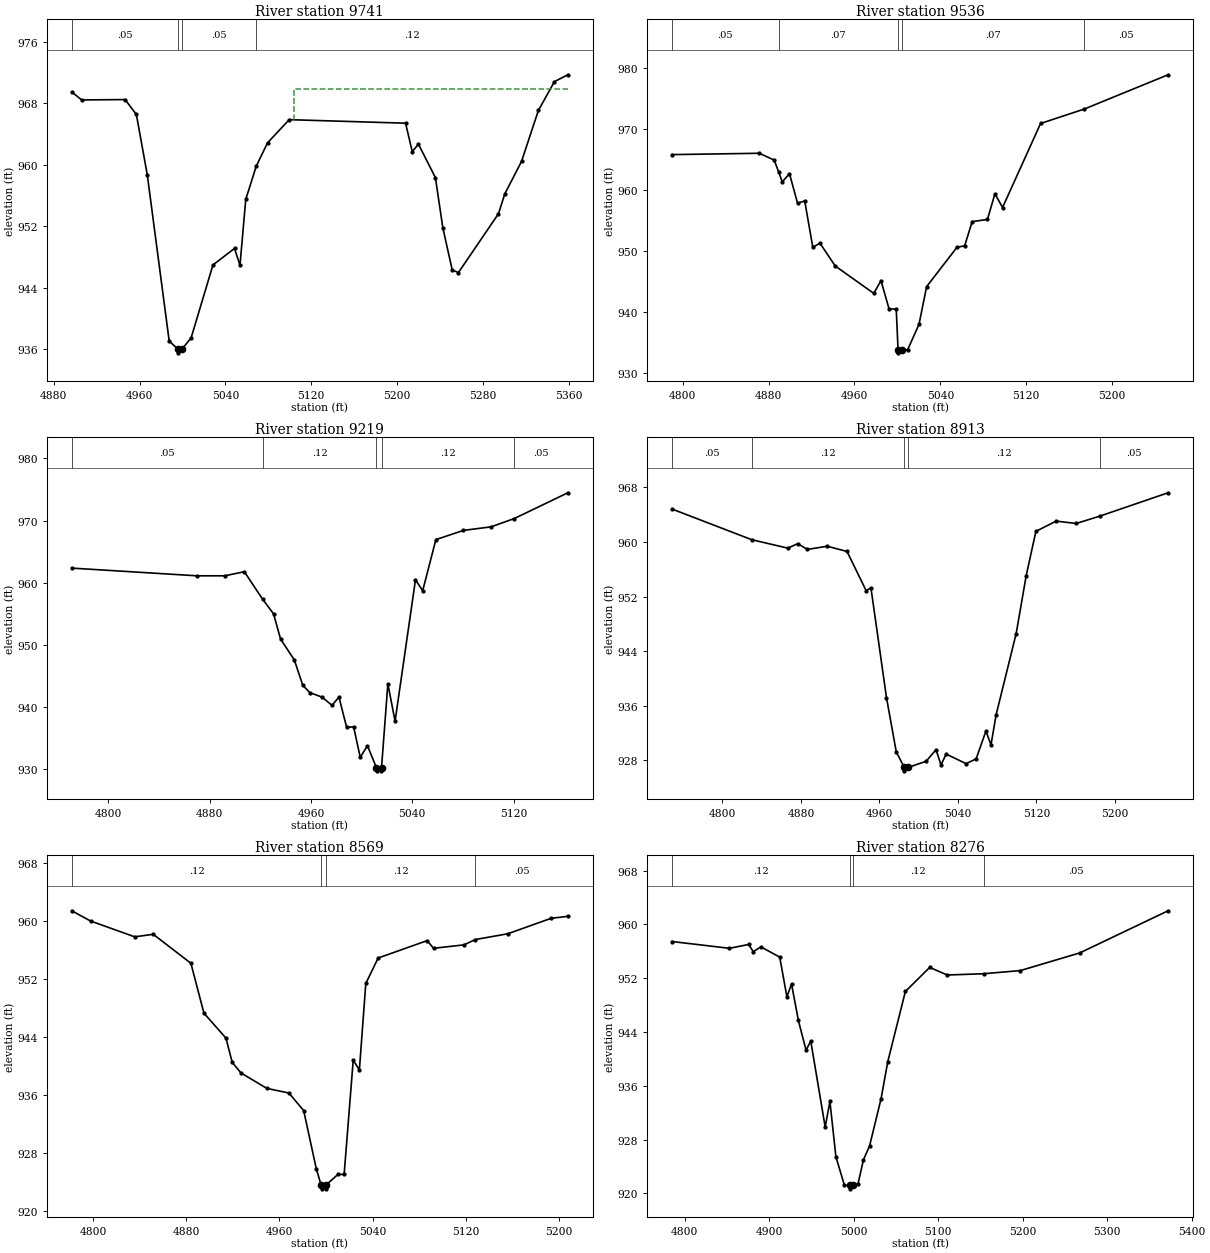
Type RM Length L Ch R = 1,9741,205,205,205
BEGIN DESCRIPTION:
Mapping XS dcdb74e6
END DESCRIPTION:
XS GIS Cut Line= 3
      2251813.30      7138819.01      2251863.84      7138566.20
      2251966.60      7138389.17
#Sta/Elev= 30
  4896.7  969.50  4905.9  968.46  4946.4  968.51  4956.9  966.57  4967.1  958.69
  4987.5  937.05  4995.4  936.00  4995.7  935.50  4999.4  936.00  5007.9  937.42
  5028.3  946.95  5048.4  949.11  5053.5  946.91  5058.9  955.50  5068.7  959.84
  5079.2  962.87  5099.4  965.89  5207.9  965.43  5214.1  961.73  5219.9  962.69
  5235.7  958.34  5242.6  951.82  5251.4  946.29  5257.2  945.97  5294.5  953.63
  5300.4  956.22  5316.0  960.45  5331.7  967.09  5346.7  970.85  5359.2  971.74
#Mann=4,-1,0
  4896.7    0.05       0  4995.4   0.033       0  4999.4    0.05       0
  5068.7    0.12       0
#XS Ineff=2,0
       0                 5104.30    0.00  969.89
Permanent Ineff=
       F       F
Bank Sta=4995.4,4999.4
Exp/Cntr=0.3,0.1

Type RM Length L Ch R = 1,9536,317,317,317
BEGIN DESCRIPTION:
MDW T 065 22.0
END DESCRIPTION:
XS GIS Cut Line= 3
      2251884.46      7138820.36      2252029.00      7138660.00
      2252203.06      7138486.14
#Sta/Elev= 30
  4790.1  965.75  4871.4  965.97  4885.3  964.85  4889.3  962.95  4892.8  961.28
  4899.5  962.63  4907.0  957.80  4913.7  958.15  4921.2  950.58  4927.9  951.23
  4942.1  947.50  4978.0  943.01  4984.7  945.11  4992.2  940.48  4998.9  940.43
  5000.6  933.77  5000.9  933.27  5004.6  933.77  5009.5  933.77  5020.1  937.94
  5027.2  944.12  5055.5  950.57  5062.6  950.80  5069.6  954.77  5083.8  955.13
  5090.8  959.33  5097.9  957.08  5133.3  970.85  5173.9  973.21  5252.0  978.83
#Mann=5,-1,0
  4790.1    0.05       0  4889.3    0.07       0  5000.6    0.05       0
  5004.6    0.07       0  5173.9    0.05       0
Bank Sta=5000.6,5004.6
Exp/Cntr=0.3,0.1

Type RM Length L Ch R = 1,9219,306,306,306
BEGIN DESCRIPTION:
MDW T 065 21.0
END DESCRIPTION:
XS GIS Cut Line= 3
      2251999.03      7138980.95      2252198.93      7138890.02
      2252349.74      7138807.34
#Sta/Elev= 30
  4771.2  962.33  4870.0  961.09  4892.0  961.09  4907.4  961.75  4921.8  957.33
  4930.5  954.95  4936.0  950.90  4946.9  947.52  4953.5  943.47  4959.0  942.27
  4968.9  941.53  4976.6  940.21  4982.1  941.55  4988.1  936.72  4993.7  936.72
  4998.9  931.84  5004.6  933.71  5011.7  930.16  5011.9  929.66  5015.4  929.66
  5015.7  930.16  5020.7  943.68  5026.4  937.66  5042.5  960.45  5048.2  958.69
  5058.6  966.92  5080.4  968.41  5102.2  968.98  5120.5  970.32  5162.8  974.47
#Mann=5,-1,0
  4771.2    0.05       0  4921.8    0.12       0  5011.7    0.07       0
  5015.7    0.12       0  5120.5    0.05       0
Bank Sta=5011.7,5015.7
Exp/Cntr=0.3,0.1

Type RM Length L Ch R = 1,8913,344,344,344
BEGIN DESCRIPTION:
MDW T 065 20.0
END DESCRIPTION:
XS GIS Cut Line= 3
      2251981.68      7139186.68      2252229.00      7139160.00
      2252480.81      7139109.42
#Sta/Elev= 30
  4748.6  964.83  4829.8  960.34  4866.6  959.10  4876.7  959.75  4886.7  958.91
  4906.8  959.38  4927.0  958.61  4946.4  952.89  4951.4  953.26  4967.2  937.21
  4977.2  929.25  4985.3  926.97  4985.5  926.47  4989.3  926.97  5007.6  927.87
  5017.7  929.57  5022.8  927.33  5028.0  928.93  5048.4  927.52  5058.6  928.23
  5068.6  932.31  5073.7  930.27  5079.0  934.71  5099.4  946.59  5109.6  955.06
  5119.5  961.56  5140.2  963.06  5160.6  962.71  5185.3  963.82  5254.2  967.21
#Mann=5,-1,0
  4748.6    0.05       0  4829.8    0.12       0  4985.3    0.07       0
  4989.3    0.12       0  5185.3    0.05       0
Bank Sta=4985.3,4989.3
Exp/Cntr=0.3,0.1

Type RM Length L Ch R = 1,8569,293,293,293
BEGIN DESCRIPTION:
MDW T 065 19.0
END DESCRIPTION:
XS GIS Cut Line= 3
      2252154.01      7139435.00      2252368.67      7139349.83
      2252553.72      7139289.11
#Sta/Elev= 30
  4781.8  961.40  4797.9  959.99  4835.8  957.81  4851.7  958.16  4884.0  954.17
  4895.2  947.29  4914.1  943.85  4919.5  940.50  4927.0  939.05  4949.2  936.92
  4968.1  936.29  4980.8  933.86  4991.6  925.86  4995.8  923.58  4996.1  923.08
  4999.6  923.08  4999.8  923.58  5010.2  925.07  5015.5  925.07  5023.3  940.80
  5028.6  939.48  5034.1  951.39  5044.7  954.89  5086.8  957.29  5092.2  956.23
  5118.3  956.70  5128.2  957.44  5155.9  958.23  5192.9  960.35  5207.5  960.64
#Mann=4,-1,0
  4781.8    0.12       0  4995.8    0.07       0  4999.8    0.12       0
  5128.2    0.05       0
Bank Sta=4995.8,4999.8
Exp/Cntr=0.3,0.1

Type RM Length L Ch R = 1,8276,252,252,252
BEGIN DESCRIPTION:
MDW T 065 18.5
END DESCRIPTION:
XS GIS Cut Line= 3
      2252254.02      7139535.01      2252445.63      7139626.68
      2252679.82      7139334.20
#Sta/Elev= 30
  4784.9  957.46  4852.9  956.45  4875.6  957.02  4881.1  955.96  4890.2  956.66
  4912.4  955.14  4920.9  949.25  4926.4  951.14  4934.5  945.72  4943.6  941.28
  4949.1  942.68  4966.2  929.89  4971.8  933.69  4978.9  925.46  4988.9  921.25
  4995.3  921.19  4995.6  920.69  4999.3  921.19  5005.1  921.44  5011.5  925.02
  5018.7  927.05  5032.3  934.06  5040.3  939.61  5061.1  950.03  5089.9  953.61
  5110.7  952.48  5153.7  952.67  5197.2  953.14  5267.6  955.77  5372.0  962.03
#Mann=4,-1,0
  4784.9    0.12       0  4995.3    0.07       0  4999.3    0.12       0
  5153.7    0.05       0
Bank Sta=4995.3,4999.3
Exp/Cntr=0.3,0.1

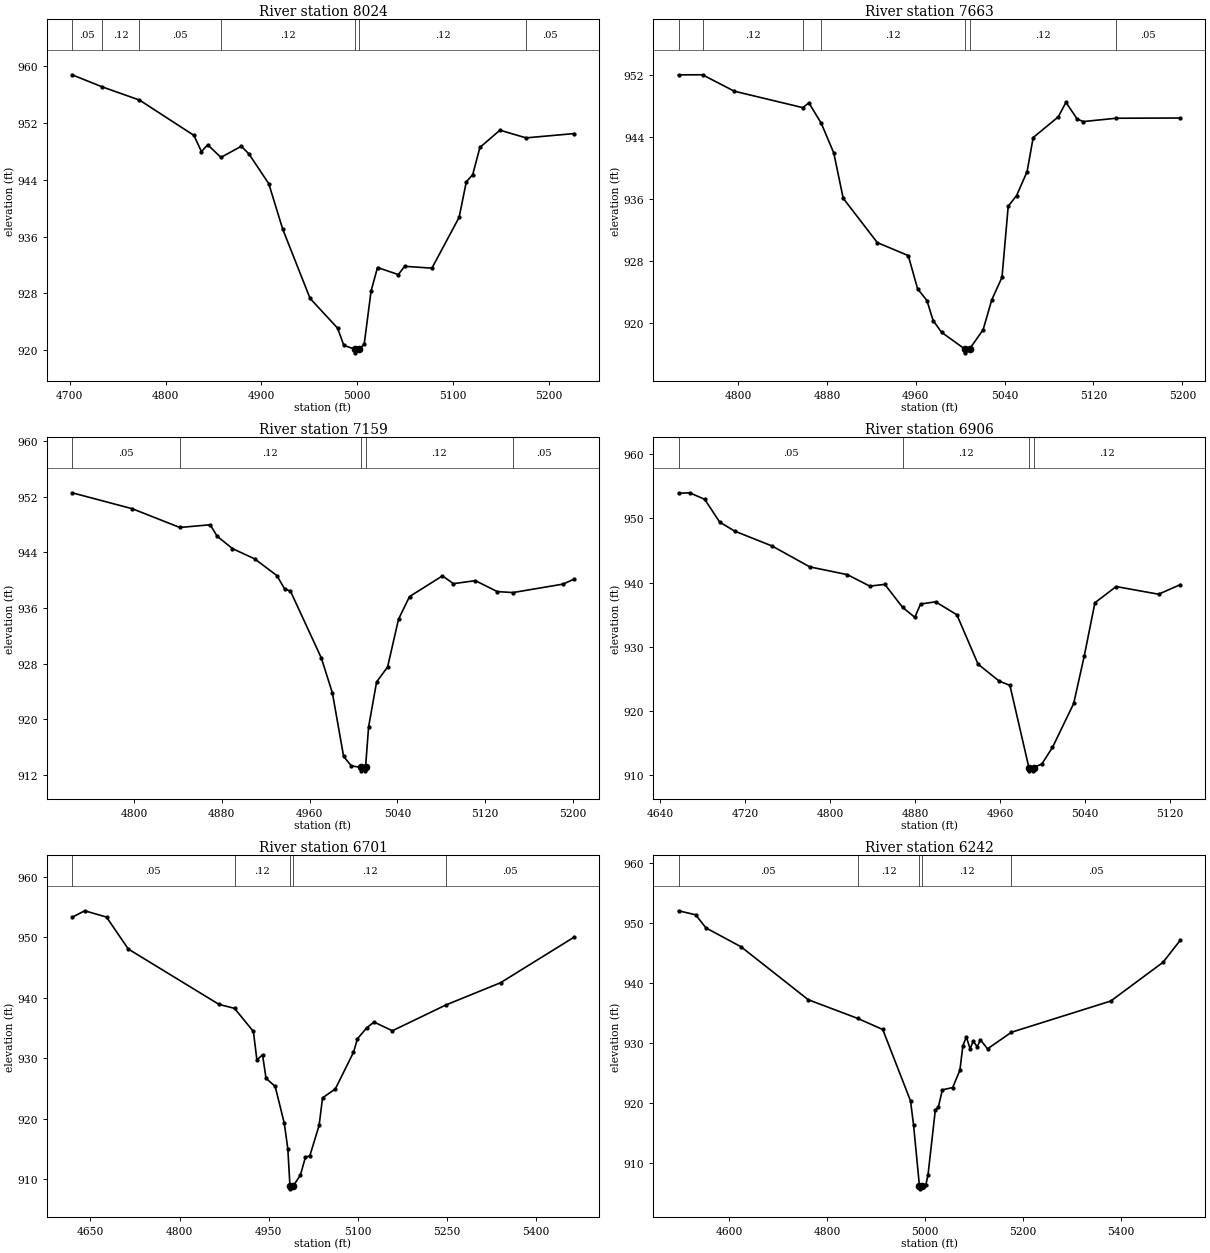
Type RM Length L Ch R = 1,8024,361,361,361
BEGIN DESCRIPTION:
MDW T 065 18.0
END DESCRIPTION:
XS GIS Cut Line= 3
      2252434.89      7140035.25      2252623.46      7139805.01
      2252791.86      7139653.84
#Sta/Elev= 30
  4702.4  958.78  4734.0  957.07  4772.8  955.22  4829.6  950.25  4837.5  947.96
  4844.0  948.93  4857.8  947.15  4879.1  948.72  4887.0  947.65  4907.8  943.44
  4922.2  937.10  4950.9  927.30  4979.6  923.12  4986.1  920.70  4997.8  920.14
  4998.2  919.64  5002.1  920.14  5007.4  920.86  5014.6  928.35  5021.3  931.65
  5043.0  930.66  5049.7  931.82  5078.1  931.56  5106.5  938.71  5114.0  943.71
  5120.7  944.73  5128.2  948.55  5149.1  950.98  5176.4  949.90  5226.3  950.50
#Mann=7,-1,0
  4702.4    0.05       0  4734.0    0.12       0  4772.8    0.05       0
  4857.8    0.12       0  4997.8    0.07       0  5002.1    0.12       0
  5176.4    0.05       0
Bank Sta=4997.8,5002.1
Exp/Cntr=0.3,0.1

Type RM Length L Ch R = 1,7663,504,504,504
BEGIN DESCRIPTION:
MDW T 065 17.0
END DESCRIPTION:
XS GIS Cut Line= 3
      2252722.98      7140232.73      2252830.78      7140016.31
      2252922.64      7139827.33
#Sta/Elev= 30
  4746.3  952.04  4767.9  952.05  4796.5  949.93  4858.2  947.81  4863.7  948.42
  4874.8  945.80  4886.1  941.96  4894.6  936.11  4925.3  930.39  4953.2  928.71
  4961.6  924.42  4970.0  922.91  4975.6  920.32  4983.2  918.81  5004.0  916.66
  5004.4  916.16  5008.4  916.66  5020.6  919.14  5028.4  923.01  5037.6  925.90
  5043.2  935.09  5050.7  936.45  5060.2  939.55  5065.7  943.95  5088.3  946.62
  5095.2  948.49  5105.3  946.34  5110.8  946.01  5140.3  946.44  5198.2  946.47
#Mann=7,-1,0
  4746.3    0.05       0  4767.9    0.12       0  4858.2    0.05       0
  4874.8    0.12       0  5004.0    0.07       0  5008.4    0.12       0
  5140.3    0.05       0
Bank Sta=5004,5008.4
Exp/Cntr=0.3,0.1

Type RM Length L Ch R = 1,7159,253,253,253
BEGIN DESCRIPTION:
MDW T 065 16.0
END DESCRIPTION:
XS GIS Cut Line= 3
      2253172.66      7140314.29      2253213.66      7140061.09
      2253219.53      7139860.27
#Sta/Elev= 30
  4743.5  952.56  4798.5  950.26  4841.7  947.57  4869.4  947.96  4875.7  946.32
  4889.7  944.53  4909.9  943.06  4930.2  940.65  4937.4  938.70  4942.5  938.44
  4970.7  928.80  4980.8  923.77  4991.0  914.66  4998.0  913.29  5006.6  913.07
  5007.0  912.57  5010.6  912.57  5011.0  913.07  5013.8  918.89  5021.1  925.36
  5031.1  927.50  5041.1  934.39  5051.1  937.63  5081.1  940.61  5091.1  939.49
  5111.1  939.92  5131.1  938.35  5145.4  938.21  5191.2  939.43  5200.9  940.13
#Mann=5,-1,0
  4743.5    0.05       0  4841.7    0.12       0  5006.6    0.07       0
  5011.0    0.12       0  5145.4    0.05       0
Bank Sta=5006.6,5011
Exp/Cntr=0.3,0.1

Type RM Length L Ch R = 1,6906,205,205,205
BEGIN DESCRIPTION:
Mapping XS f65b536d
END DESCRIPTION:
XS GIS Cut Line= 3
      2253279.13      7140335.03      2253441.67      7140172.43
      2253436.66      7139929.48
#Sta/Elev= 30
  4657.1  953.90  4667.6  953.98  4681.8  952.96  4695.9  949.41  4710.1  948.01
  4745.4  945.69  4780.8  942.45  4816.1  941.25  4837.3  939.46  4851.5  939.73
  4868.3  936.15  4879.8  934.60  4885.2  936.68  4899.4  937.01  4919.4  935.00
  4939.4  927.31  4959.4  924.67  4969.4  924.02  4987.3  911.22  4987.7  910.72
  4991.3  910.72  4991.7  911.22  4999.5  911.79  5009.5  914.36  5029.5  921.20
  5039.5  928.61  5049.5  936.87  5069.5  939.39  5109.5  938.20  5130.0  939.69
#Mann=4,-1,0
  4657.1    0.05       0  4868.3    0.12       0  4987.3    0.07       0
  4991.7    0.12       0
Bank Sta=4987.3,4991.7
Exp/Cntr=0.3,0.1

Type RM Length L Ch R = 1,6701,459,459,459
BEGIN DESCRIPTION:
MDW T 065 15.0
END DESCRIPTION:
XS GIS Cut Line= 3
      2253253.96      7140385.02      2253578.54      7140185.49
      2253980.08      7139952.58
#Sta/Elev= 30
  4619.0  953.31  4640.3  954.39  4677.0  953.35  4713.7  948.06  4866.4  938.90
  4892.6  938.24  4924.4  934.42  4930.3  929.71  4939.8  930.55  4945.7  926.66
  4961.1  925.32  4976.5  919.20  4982.4  914.99  4986.0  908.87  4986.9  908.37
  4991.7  908.87  5003.6  910.64  5012.1  913.63  5019.4  913.82  5035.1  918.86
  5040.9  923.43  5062.4  924.90  5093.0  930.96  5099.7  933.20  5115.5  935.05
  5127.7  935.97  5158.5  934.53  5248.6  938.80  5340.7  942.48  5464.2  950.00
#Mann=5,-1,0
  4619.0    0.05       0  4892.6    0.12       0  4986.0    0.07       0
  4991.7    0.12       0  5248.6    0.05       0
Bank Sta=4986,4991.7
Exp/Cntr=0.3,0.1

Type RM Length L Ch R = 1,6242,646,646,646
BEGIN DESCRIPTION:
MDW T 065 14.0
END DESCRIPTION:
XS GIS Cut Line= 3
      2253444.56      7140794.44      2253858.73      7140510.52
      2254284.72      7140205.80
#Sta/Elev= 30
  4496.4  952.03  4531.4  951.36  4552.4  949.18  4624.2  946.03  4761.6  937.21
  4862.3  934.11  4913.9  932.25  4970.7  920.35  4976.8  916.41  4988.9  906.20
  4989.8  905.70  4994.6  906.20  5001.8  906.29  5006.5  908.05  5021.3  918.78
  5027.4  919.26  5035.8  922.19  5056.9  922.58  5071.6  925.46  5077.8  929.57
  5084.9  931.01  5092.5  929.02  5098.7  930.27  5107.3  929.38  5113.4  930.53
  5128.2  929.03  5177.0  931.79  5380.0  936.99  5486.9  943.44  5522.3  947.14
#Mann=5,-1,0
  4496.4    0.05       0  4862.3    0.12       0  4988.9    0.07       0
  4994.6    0.12       0  5177.0    0.05       0
Bank Sta=4988.9,4994.6
Exp/Cntr=0.3,0.1

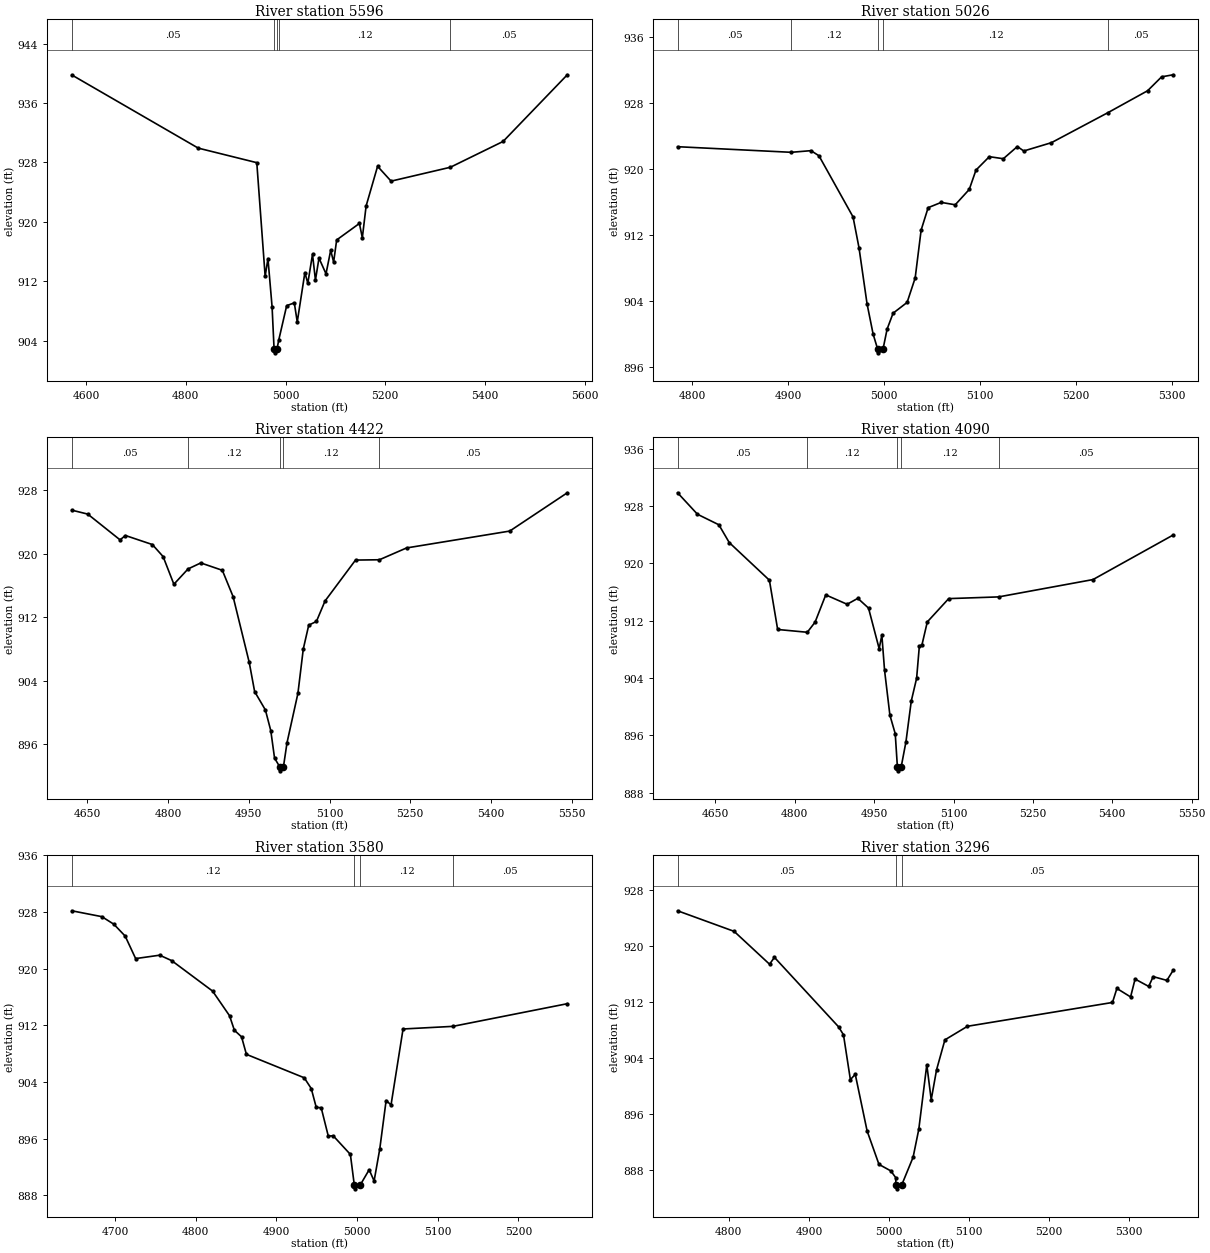
Type RM Length L Ch R = 1,5596,570,570,570
BEGIN DESCRIPTION:
MDW T 065 13.0
END DESCRIPTION:
XS GIS Cut Line= 3
      2253619.22      7141099.37      2253986.34      7140916.41
      2254480.49      7140604.76
#Sta/Elev= 30
  4571.0  939.78  4824.8  929.92  4942.3  927.96  4959.1  912.65  4964.7  915.04
  4973.0  908.54  4977.0  902.84  4977.9  902.34  4982.8  902.84  4986.5  904.10
  5002.3  908.70  5017.6  909.07  5023.5  906.50  5038.8  913.15  5044.7  911.71
  5054.1  915.61  5060.0  912.14  5067.1  915.10  5081.2  912.99  5090.6  916.15
  5096.5  914.57  5102.6  917.55  5148.2  919.77  5154.1  917.85  5161.7  922.13
  5184.7  927.47  5211.8  925.47  5330.7  927.34  5436.6  930.82  5565.4  939.80
#Mann=5,-1,0
  4571.0    0.05       0  4977.0    0.07       0  4982.8    0.05       0
  4986.5    0.12       0  5330.7    0.05       0
Bank Sta=4977,4982.8
Exp/Cntr=0.3,0.1

Type RM Length L Ch R = 1,5026,604,604,604
BEGIN DESCRIPTION:
Mapping XS f3b4bde1
END DESCRIPTION:
XS GIS Cut Line= 2
      2254129.41      7141335.45      2254543.86      7141028.07
#Sta/Elev= 30
  4784.9  922.73  4903.2  922.05  4923.8  922.25  4932.1  921.63  4967.6  914.21
  4973.8  910.47  4982.2  903.65  4988.5  899.99  4993.1  898.21  4994.0  897.71
  4998.9  898.21  5003.1  900.60  5009.3  902.52  5023.9  903.83  5032.3  906.80
  5038.5  912.61  5045.8  915.33  5059.4  915.97  5074.0  915.68  5088.6  917.54
  5095.6  919.89  5109.5  921.52  5124.1  921.27  5138.7  922.75  5145.4  922.21
  5174.2  923.22  5233.3  926.88  5274.3  929.52  5288.9  931.21  5300.9  931.46
#Mann=5,-1,0
  4784.9    0.05       0  4903.2    0.12       0  4993.1    0.07       0
  4998.9    0.12       0  5233.3    0.05       0
Bank Sta=4993.1,4998.9
Exp/Cntr=0.3,0.1

Type RM Length L Ch R = 1,4422,332,332,332
BEGIN DESCRIPTION:
MDW T 065 10.0
END DESCRIPTION:
XS GIS Cut Line= 3
      2254049.33      7141616.97      2254428.12      7141615.01
      2254964.94      7141542.45
#Sta/Elev= 30
  4621.2  925.51  4650.9  925.01  4710.9  921.76  4720.9  922.31  4770.9  921.17
  4790.9  919.65  4810.9  916.16  4837.2  918.09  4860.9  918.85  4900.9  917.92
  4920.9  914.60  4950.9  906.29  4960.9  902.62  4980.9  900.30  4990.9  897.69
  4997.9  894.23  5007.6  893.12  5008.6  892.62  5014.4  893.12  5021.1  896.18
  5041.3  902.39  5051.3  908.00  5061.4  911.00  5075.7  911.47  5091.7  914.05
  5148.3  919.21  5192.7  919.25  5243.1  920.74  5434.8  922.87  5541.7  927.70
#Mann=5,-1,0
  4621.2    0.05       0  4837.2    0.12       0  5007.6    0.07       0
  5014.4    0.12       0  5192.7    0.05       0
Bank Sta=5007.6,5014.4
Exp/Cntr=0.3,0.1

Type RM Length L Ch R = 1,4090,510,510,510
BEGIN DESCRIPTION:
MDW T 065 9.0
END DESCRIPTION:
XS GIS Cut Line= 3
      2254111.80      7141969.40      2254529.00      7141910.00
      2255038.86      7141837.46
#Sta/Elev= 30
  4578.6  929.87  4616.2  926.87  4656.6  925.40  4676.2  922.92  4752.1  917.66
  4767.7  910.78  4823.7  910.39  4838.4  911.80  4858.6  915.61  4899.0  914.30
  4919.2  915.13  4939.4  913.77  4959.5  908.10  4964.6  909.99  4969.7  905.08
  4979.8  898.81  4989.9  896.22  4994.0  891.54  4995.1  891.04  5001.0  891.54
  5010.1  895.08  5020.2  900.79  5030.3  903.97  5035.4  908.42  5040.5  908.67
  5050.5  911.84  5090.9  915.09  5185.3  915.33  5363.6  917.75  5515.0  923.97
#Mann=5,-1,0
  4578.6    0.05       0  4823.7    0.12       0  4994.0    0.07       0
  5001.0    0.12       0  5185.3    0.05       0
Bank Sta=4994,5001
Exp/Cntr=0.3,0.1

Type RM Length L Ch R = 1,3580,284,284,284
BEGIN DESCRIPTION:
Mapping XS 920184e4
END DESCRIPTION:
XS GIS Cut Line= 2
      2254622.09      7142494.57      2254970.27      7141988.48
#Sta/Elev= 30
  4646.4  928.18  4683.7  927.35  4698.6  926.28  4712.6  924.61  4725.6  921.43
  4755.4  921.91  4770.3  921.14  4821.0  916.84  4842.0  913.36  4848.0  911.31
  4856.9  910.38  4862.9  907.91  4934.6  904.60  4943.3  903.08  4949.5  900.41
  4955.6  900.38  4964.4  896.37  4970.5  896.41  4991.8  893.78  4996.7  889.42
  4997.8  888.92  5003.8  889.42  5015.1  891.62  5021.2  890.03  5028.2  894.53
  5036.1  901.39  5042.2  900.77  5057.1  911.49  5118.8  911.86  5260.7  915.06
#Mann=4,-1,0
  4646.4    0.12       0  4996.7    0.07       0  5003.8    0.12       0
  5118.8    0.05       0
Bank Sta=4996.7,5003.8
Exp/Cntr=0.3,0.1

Type RM Length L Ch R = 1,3296,60,60,60
BEGIN DESCRIPTION:
MDW T 065 7.5
END DESCRIPTION:
XS GIS Cut Line= 3
      2254721.35      7142602.05      2254949.31      7142440.69
      2255255.04      7142293.51
#Sta/Elev= 30
  4736.1  925.04  4806.7  922.10  4850.9  917.41  4857.0  918.39  4937.0  908.48
  4943.2  907.33  4951.8  900.93  4957.9  901.69  4972.7  893.60  4987.5  888.83
  5002.3  887.90  5008.4  886.94  5008.6  885.84  5009.7  885.34  5015.7  885.84
  5030.1  889.85  5037.2  893.84  5047.2  903.06  5052.7  898.06  5059.4  902.34
  5069.8  906.61  5098.0  908.55  5279.0  911.95  5284.5  913.95  5301.6  912.74
  5307.2  915.29  5324.2  914.24  5329.8  915.64  5346.9  915.10  5354.7  916.53
#Mann=3,-1,0
  4736.1    0.05       0  5008.6   0.033       0  5015.7    0.05       0
Bank Sta=5008.6,5015.7
Exp/Cntr=0.3,0.1

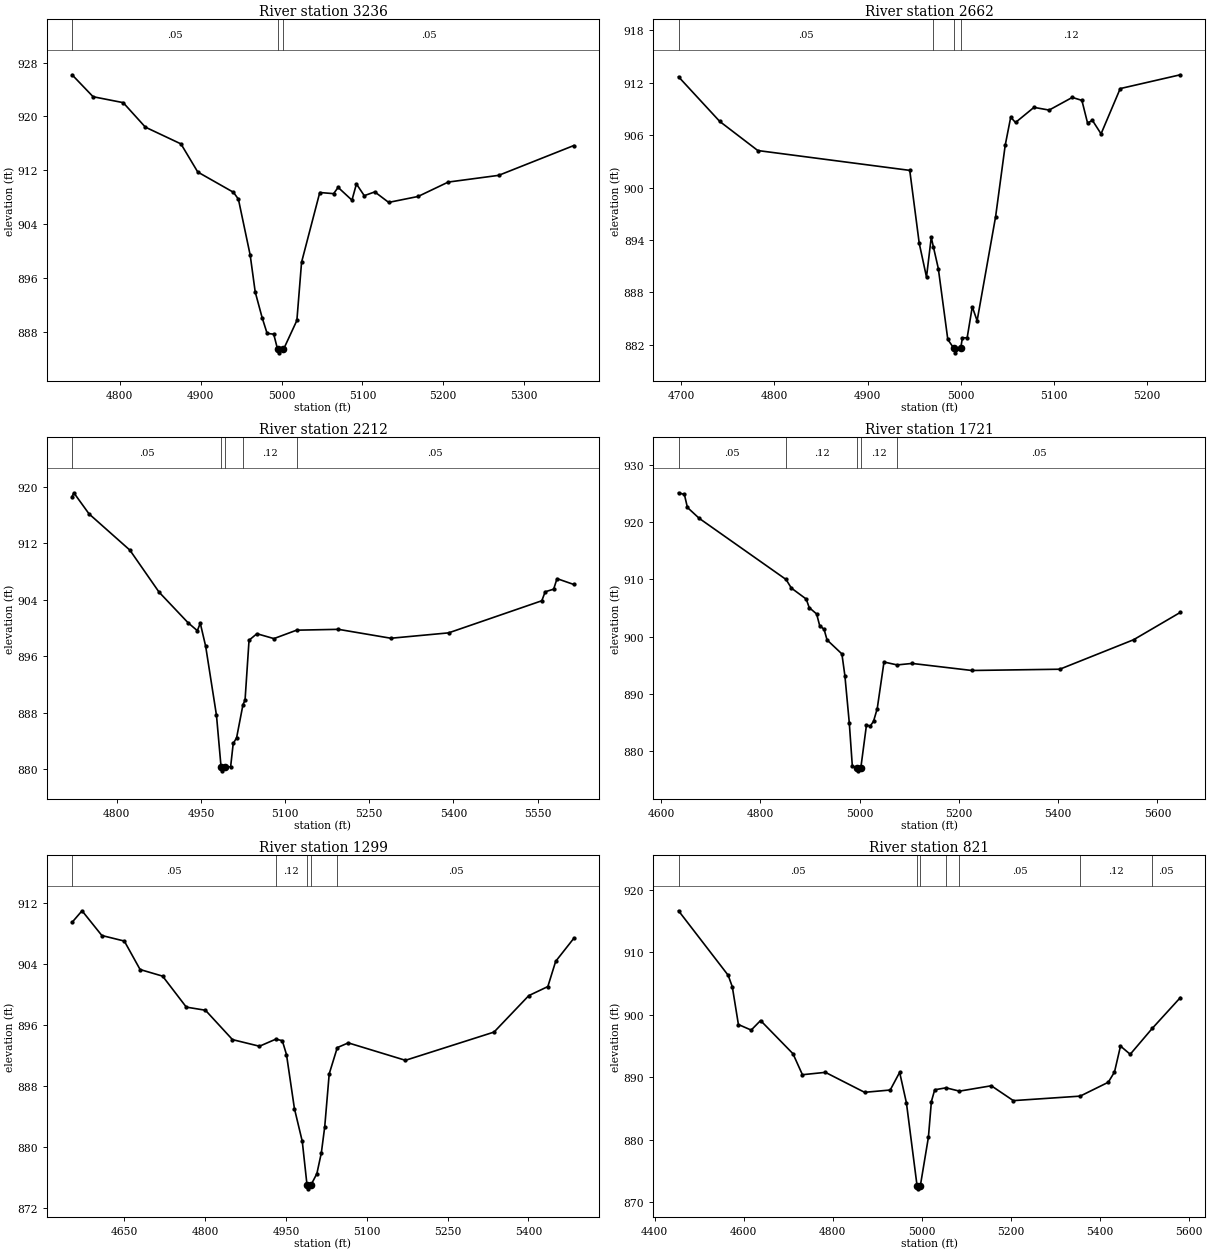
Type RM Length L Ch R = 1,3236,574,574,574
BEGIN DESCRIPTION:
MDW T 065 7.0
END DESCRIPTION:
XS GIS Cut Line= 3
      2254768.05      7142646.49      2254977.26      7142492.83
      2255302.80      7142337.44
#Sta/Elev= 30
  4741.1  926.19  4767.1  922.93  4804.3  922.05  4831.7  918.41  4875.7  915.92
  4896.5  911.74  4940.5  908.74  4946.7  907.72  4961.3  899.39  4967.5  893.92
  4976.0  890.13  4982.2  887.77  4990.4  887.65  4995.2  885.38  4996.4  884.88
  5002.4  885.38  5019.0  889.69  5024.8  898.34  5047.3  908.70  5064.4  908.53
  5070.0  909.46  5087.1  907.56  5092.6  909.97  5102.3  908.23  5115.3  908.79
  5132.5  907.23  5168.8  908.11  5206.1  910.25  5268.5  911.25  5361.4  915.68
#Mann=3,-1,0
  4741.1    0.05       0  4995.2   0.033       0  5002.4    0.05       0
Bank Sta=4995.2,5002.4
Exp/Cntr=0.3,0.1

Type RM Length L Ch R = 1,2662,450,450,450
BEGIN DESCRIPTION:
MDW T 065 6.0
END DESCRIPTION:
XS GIS Cut Line= 3
      2255035.60      7142769.40      2255334.79      7142707.65
      2255561.67      7142651.16
#Sta/Elev= 30
  4696.9  912.68  4741.2  907.57  4782.1  904.24  4945.4  901.97  4955.6  893.62
  4963.4  889.76  4968.5  894.30  4970.8  893.22  4976.1  890.74  4986.3  882.62
  4992.9  881.59  4994.0  881.09  5000.1  881.59  5002.0  882.81  5007.1  882.81
  5012.6  886.36  5017.8  884.76  5037.7  896.69  5048.0  904.85  5053.9  908.05
  5059.1  907.45  5078.9  909.18  5095.2  908.87  5120.1  910.32  5130.4  909.98
  5136.5  907.39  5141.7  907.70  5151.0  906.15  5171.6  911.33  5236.2  912.91
#Mann=4,-1,0
  4696.9    0.05       0  4970.8    0.12       0  4992.9    0.07       0
  5000.1    0.12       0
Bank Sta=4992.9,5000.1
Exp/Cntr=0.3,0.1

Type RM Length L Ch R = 1,2212,491,491,491
BEGIN DESCRIPTION:
MDW T 065 5.0
END DESCRIPTION:
XS GIS Cut Line= 3
      2255109.84      7143215.48      2255378.96      7143140.02
      2255894.51      7142805.63
#Sta/Elev= 30
  4720.5  918.57  4723.6  919.13  4750.8  916.14  4823.5  911.02  4875.5  905.08
  4927.3  900.74  4943.7  899.63  4948.9  900.69  4958.5  897.43  4977.8  887.65
  4986.0  880.31  4987.2  879.81  4993.3  880.31  5003.0  880.40  5007.6  883.68
  5013.6  884.47  5025.0  889.17  5028.7  889.82  5035.8  898.28  5049.8  899.20
  5080.1  898.51  5120.5  899.70  5194.9  899.82  5288.5  898.56  5391.3  899.32
  5557.4  903.86  5563.4  905.13  5578.5  905.50  5584.5  906.99  5614.5  906.16
#Mann=5,-1,0
  4720.5    0.05       0  4986.0   0.033       0  4993.3    0.05       0
  5025.0    0.12       0  5120.5    0.05       0
Bank Sta=4986,4993.3
Exp/Cntr=0.3,0.1

Type RM Length L Ch R = 1,1721,422,422,422
BEGIN DESCRIPTION:
MDW T 065 4.0
END DESCRIPTION:
XS GIS Cut Line= 3
      2255374.17      7143711.56      2255675.66      7143506.68
      2256108.54      7143026.65
#Sta/Elev= 30
  4635.2  925.09  4647.0  924.79  4653.1  922.53  4676.9  920.63  4851.8  909.97
  4862.5  908.47  4892.4  906.56  4898.5  905.06  4913.4  903.96  4919.5  901.93
  4928.4  901.28  4934.4  899.43  4964.3  896.99  4970.3  893.22  4979.2  884.96
  4985.3  877.44  4995.1  877.10  4996.2  876.60  5002.4  877.10  5013.8  884.59
  5021.3  884.40  5028.0  885.23  5035.5  887.45  5049.1  895.58  5075.5  895.07
  5105.7  895.33  5226.1  894.10  5403.2  894.32  5551.9  899.46  5646.1  904.23
#Mann=5,-1,0
  4635.2    0.05       0  4851.8    0.12       0  4995.1    0.07       0
  5002.4    0.12       0  5075.5    0.05       0
Bank Sta=4995.1,5002.4
Exp/Cntr=0.3,0.1

Type RM Length L Ch R = 1,1299,478,478,478
BEGIN DESCRIPTION:
MDW T 065 3.0
END DESCRIPTION:
XS GIS Cut Line= 3
      2255654.05      7144011.09      2256015.02      7143746.93
      2256401.49      7143455.06
#Sta/Elev= 30
  4552.7  909.51  4571.2  911.03  4608.0  907.78  4649.7  907.05  4679.0  903.31
  4720.8  902.44  4764.8  898.37  4800.3  897.96  4850.5  894.10  4900.6  893.23
  4931.0  894.16  4943.0  893.96  4950.8  892.13  4965.5  885.04  4980.1  880.72
  4988.9  874.99  4990.0  874.49  4996.2  874.99  5007.2  876.49  5015.5  879.22
  5021.8  882.66  5030.1  889.60  5045.1  893.05  5065.5  893.67  5171.6  891.38
  5336.1  895.09  5400.6  899.88  5436.0  901.07  5450.5  904.38  5484.3  907.42
#Mann=5,-1,0
  4552.7    0.05       0  4931.0    0.12       0  4988.9    0.07       0
  4996.2    0.12       0  5045.1    0.05       0
Bank Sta=4988.9,4996.2
Exp/Cntr=0.3,0.1

Type RM Length L Ch R = 1,821,347,347,347
BEGIN DESCRIPTION:
MDW T 065 2.0
END DESCRIPTION:
XS GIS Cut Line= 3
      2255815.51      7144432.09      2256264.88      7144145.93
      2256709.64      7143751.51
#Sta/Elev= 30
  4453.6  916.68  4565.1  906.35  4574.4  904.50  4588.1  898.46  4616.8  897.57
  4637.9  899.10  4710.7  893.78  4731.9  890.42  4783.5  890.80  4871.6  887.60
  4929.1  887.97  4950.3  890.80  4965.5  885.92  4989.4  872.64  4990.6  872.14
  4996.8  872.64  5014.9  880.40  5021.6  886.13  5029.1  888.01  5054.5  888.32
  5084.7  887.79  5156.2  888.65  5205.7  886.27  5355.8  886.99  5418.9  889.21
  5432.9  890.85  5446.4  895.01  5468.2  893.69  5517.6  897.83  5580.8  902.77
#Mann=7,-1,0
  4453.6    0.05       0  4989.4   0.033       0  4996.8    0.05       0
  5054.5    0.12       0  5084.7    0.05       0  5355.8    0.12       0
  5517.6    0.05       0
Bank Sta=4989.4,4996.8
Exp/Cntr=0.3,0.1

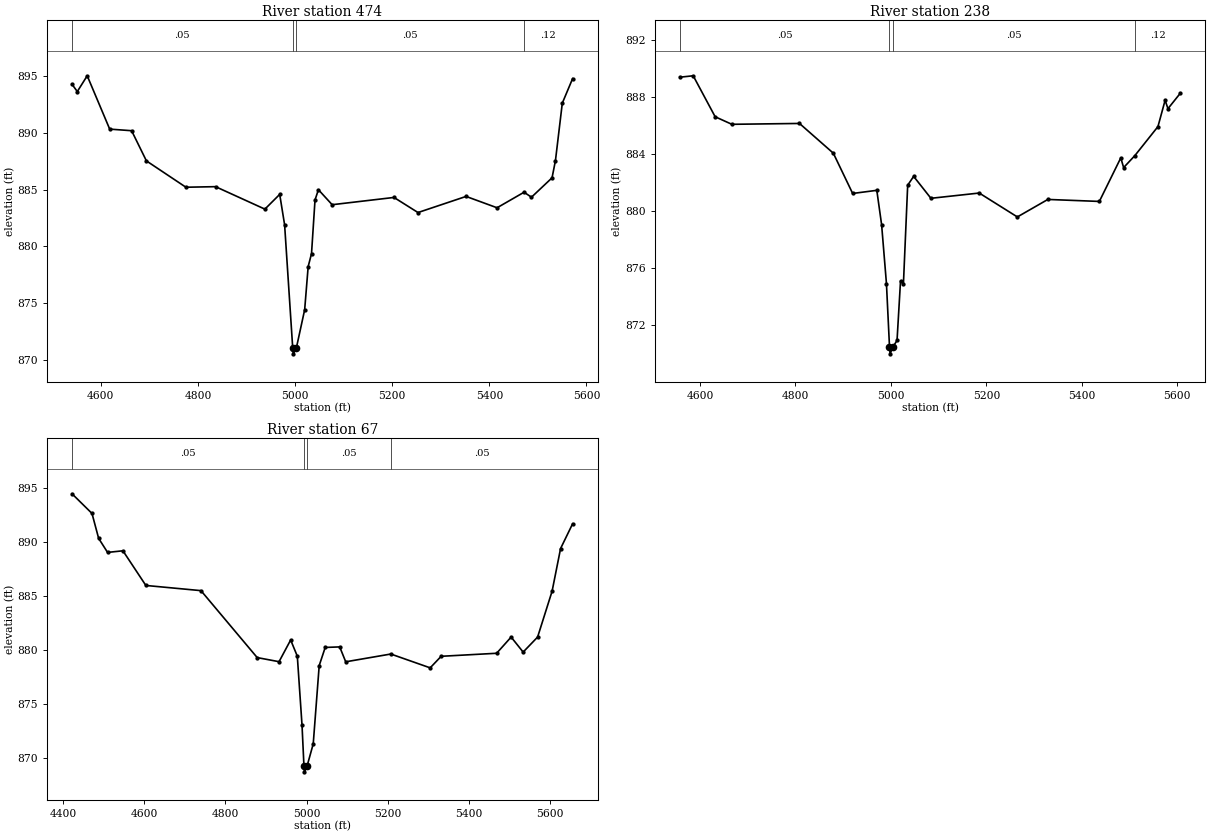
Type RM Length L Ch R = 1,474,236,236,236
BEGIN DESCRIPTION:
MDW T 065 1.0
END DESCRIPTION:
XS GIS Cut Line= 3
      2256028.24      7144498.91      2256487.44      7144415.95
      2256878.97      7144010.04
#Sta/Elev= 30
  4540.8  894.29  4551.7  893.65  4572.1  895.04  4618.4  890.34  4663.5  890.20
  4694.0  887.54  4775.3  885.22  4836.3  885.27  4937.9  883.29  4968.4  884.59
  4978.5  881.91  4995.2  871.04  4996.3  870.54  5002.6  871.04  5019.8  874.43
  5027.0  878.23  5033.9  879.37  5041.1  884.10  5048.1  885.00  5076.4  883.68
  5203.7  884.32  5253.1  882.99  5352.1  884.41  5415.9  883.41  5471.5  884.78
  5486.7  884.34  5529.1  886.05  5536.1  887.57  5550.2  892.63  5571.4  894.79
#Mann=4,-1,0
  4540.8    0.05       0  4995.2   0.033       0  5002.6    0.05       0
  5471.5    0.12       0
Bank Sta=4995.2,5002.6
Exp/Cntr=0.3,0.1

Type RM Length L Ch R = 1,238,171,171,171
BEGIN DESCRIPTION:
Mapping XS 060d8cad
END DESCRIPTION:
XS GIS Cut Line= 3
      2256141.21      7144553.44      2256586.25      7144623.25
      2257082.02      7144288.11
#Sta/Elev= 30
  4557.7  889.41  4585.8  889.51  4631.8  886.63  4666.8  886.10  4808.5  886.16
  4879.4  884.07  4919.9  881.24  4970.5  881.46  4980.6  879.04  4990.7  874.91
  4997.1  870.47  4998.3  869.97  5004.5  870.47  5012.9  870.91  5020.2  875.09
  5026.3  874.90  5035.2  881.82  5047.7  882.44  5083.9  880.90  5185.1  881.27
  5265.0  879.59  5328.9  880.82  5436.8  880.68  5481.7  883.74  5487.7  883.06
  5511.2  883.90  5559.6  885.94  5574.6  887.79  5580.6  887.20  5606.6  888.29
#Mann=4,-1,0
  4557.7    0.05       0  4997.1   0.033       0  5004.5    0.05       0
  5511.2    0.12       0
Bank Sta=4997.1,5004.5
Exp/Cntr=0.3,0.1

Type RM Length L Ch R = 1,67,0,0,0
BEGIN DESCRIPTION:
MDW T 065 0.5
END DESCRIPTION:
XS GIS Cut Line= 3
      2256068.16      7144523.22      2256579.01      7144793.18
      2257113.86      7144414.91
#Sta/Elev= 30
  4422.2  894.46  4471.4  892.64  4487.8  890.33  4509.8  889.03  4547.6  889.18
  4604.1  885.97  4739.8  885.49  4878.3  879.29  4932.1  878.91  4960.7  880.92
  4977.1  879.42  4988.7  873.03  4993.5  869.21  4994.6  868.71  5000.9  869.21
  5016.3  871.30  5031.0  878.55  5045.8  880.23  5081.5  880.28  5096.3  878.90
  5207.4  879.62  5304.3  878.34  5331.4  879.41  5468.0  879.69  5503.7  881.19
  5533.3  879.80  5568.9  881.19  5604.6  885.44  5625.5  889.39  5655.1  891.68
#Mann=4,-1,0
  4422.2    0.05       0  4993.5   0.033       0  5000.9    0.05       0
  5207.4    0.05       0
Bank Sta=4993.5,5000.9
Exp/Cntr=0.3,0.1

Chan Stop Cuts=-1