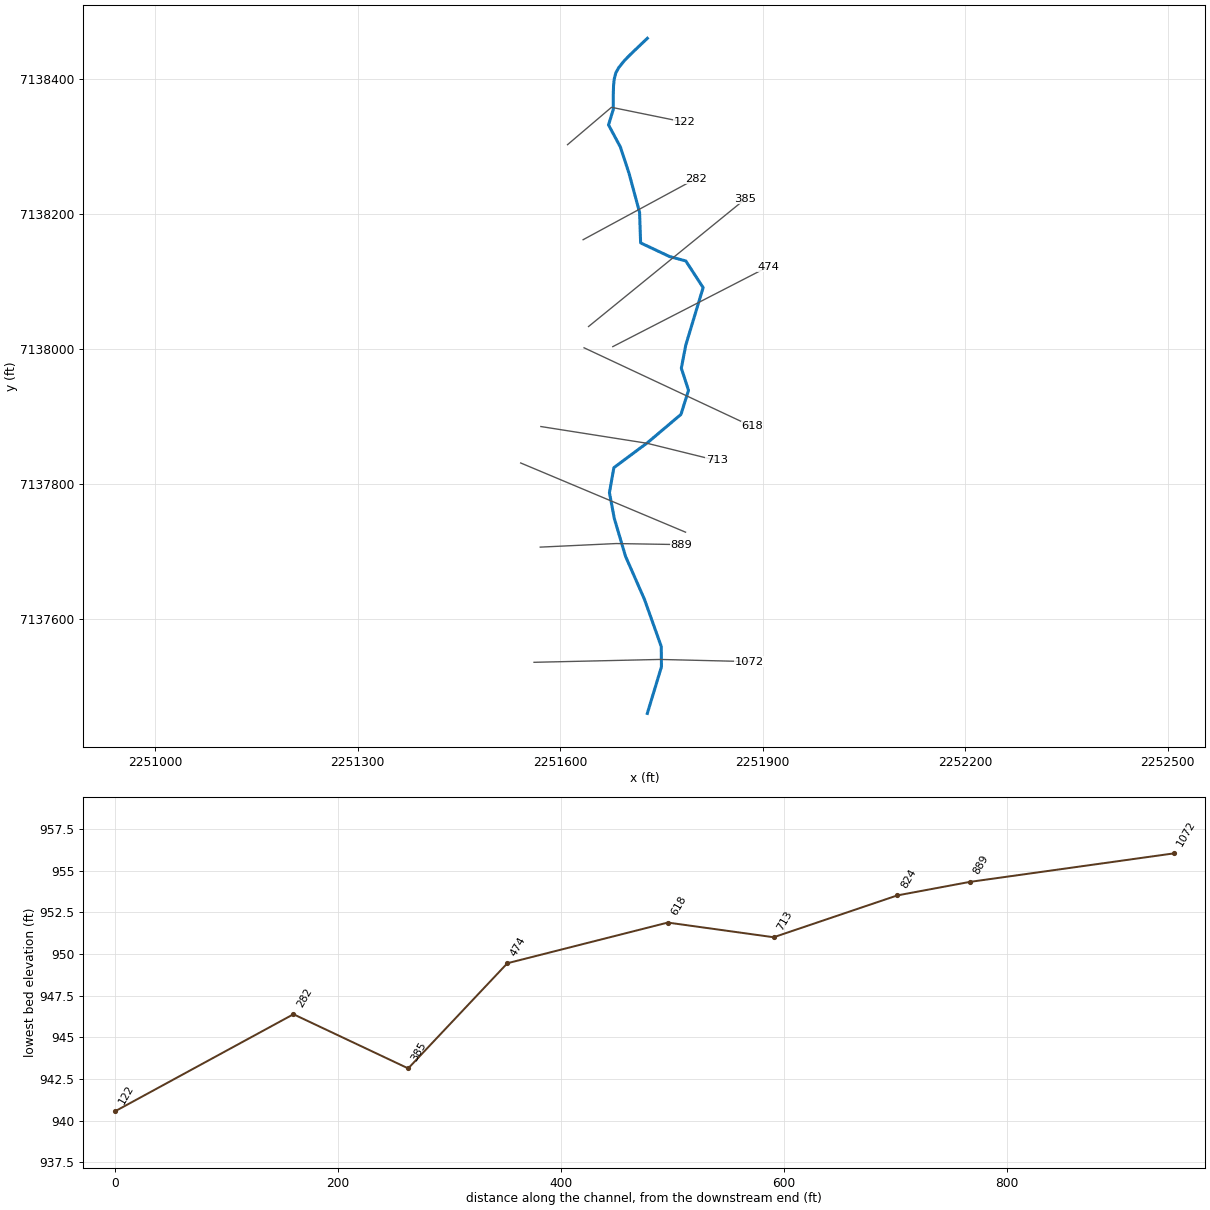
--- MDW T 066.prj (project) ---

Proj Title=MDW T 066 Base Level Engineering
Current Plan=p01
Default Exp/Contr=0.3,0.1
English Units
Geom File=g01
Flow File=f01
Plan File=p01
BEGIN DESCRIPTION:
MDW T 066
END DESCRIPTION:

--- MDW T 066.p01 (plan) ---

Plan Title=Multiple Run
Short Identifier=Multiple
Geom File=g01
Flow File=f01
Subcritical Flow
K Sum by GR= 0
Std Step Tol= 0.01
Critical Tol= 0.01
Num of Std Step Trials= 20
Max Error Tol= 0.3
Flow Tol Ratio= 0.001
Split Flow NTrial= 30
Split Flow Tol= 0.02
Split Flow Ratio= 0.02
Log Output Level= 0
Friction Slope Method= 1
Unsteady Friction Slope Method= 2
Unsteady Bridges Friction Slope Method= 1
Parabolic Critical Depth
Global Vel Dist=  1 , 1 , 1
Global Log Level= 0
CheckData=True
Encroach Param= -1, 0, 0, 0
BEGIN DESCRIPTION:
Multiple Run
END DESCRIPTION:

--- MDW T 066.f01 (steady flow) ---

Flow Title=Multiple
Number of Profiles=7
Profile Names=10-year,25-year,50-year,1pct_min,100-year,1pct_plu,500-year
River Rch & RM= MDW T 066,Reach-1,1072
     333     444     534     320     638    1273     912
Boundary for River Rch & Prof#=MDW T 066,Reach-1,1
Up Type=0
Dn Type=3
Dn Slope=0.005
Boundary for River Rch & Prof#=MDW T 066,Reach-1,2
Up Type=0
Dn Type=3
Dn Slope=0.005
Boundary for River Rch & Prof#=MDW T 066,Reach-1,3
Up Type=0
Dn Type=3
Dn Slope=0.005
Boundary for River Rch & Prof#=MDW T 066,Reach-1,4
Up Type=0
Dn Type=3
Dn Slope=0.005
Boundary for River Rch & Prof#=MDW T 066,Reach-1,5
Up Type=0
Dn Type=3
Dn Slope=0.005
Boundary for River Rch & Prof#=MDW T 066,Reach-1,6
Up Type=0
Dn Type=3
Dn Slope=0.005
Boundary for River Rch & Prof#=MDW T 066,Reach-1,7
Up Type=0
Dn Type=3
Dn Slope=0.005

--- MDW T 066.g01 (geometry) ---

Geom Title=Existing Conditions

River Reach=MDW T 066,Reach-1
Reach XY= 30
      2251729.00      7137460.00      2251749.91      7137528.91
      2251749.65      7137559.02      2251724.88      7137628.62
      2251696.70      7137692.71      2251680.11      7137748.69
      2251672.87      7137786.96      2251679.44      7137823.98
      2251729.72      7137861.38      2251778.82      7137902.88
      2251790.01      7137938.58      2251779.37      7137971.34
      2251785.97      7138005.62      2251811.67      7138090.72
      2251786.02      7138130.19      2251761.80      7138136.82
      2251719.07      7138156.98      2251717.52      7138202.14
      2251702.06      7138259.50      2251689.06      7138299.08
      2251671.51      7138331.78      2251678.57      7138354.63
      2251678.54      7138375.15      2251678.96      7138390.00
      2251679.95      7138399.59      2251682.28      7138408.63
      2251686.42      7138416.35      2251695.08      7138427.06
      2251703.11      7138435.29      2251729.00      7138460.00

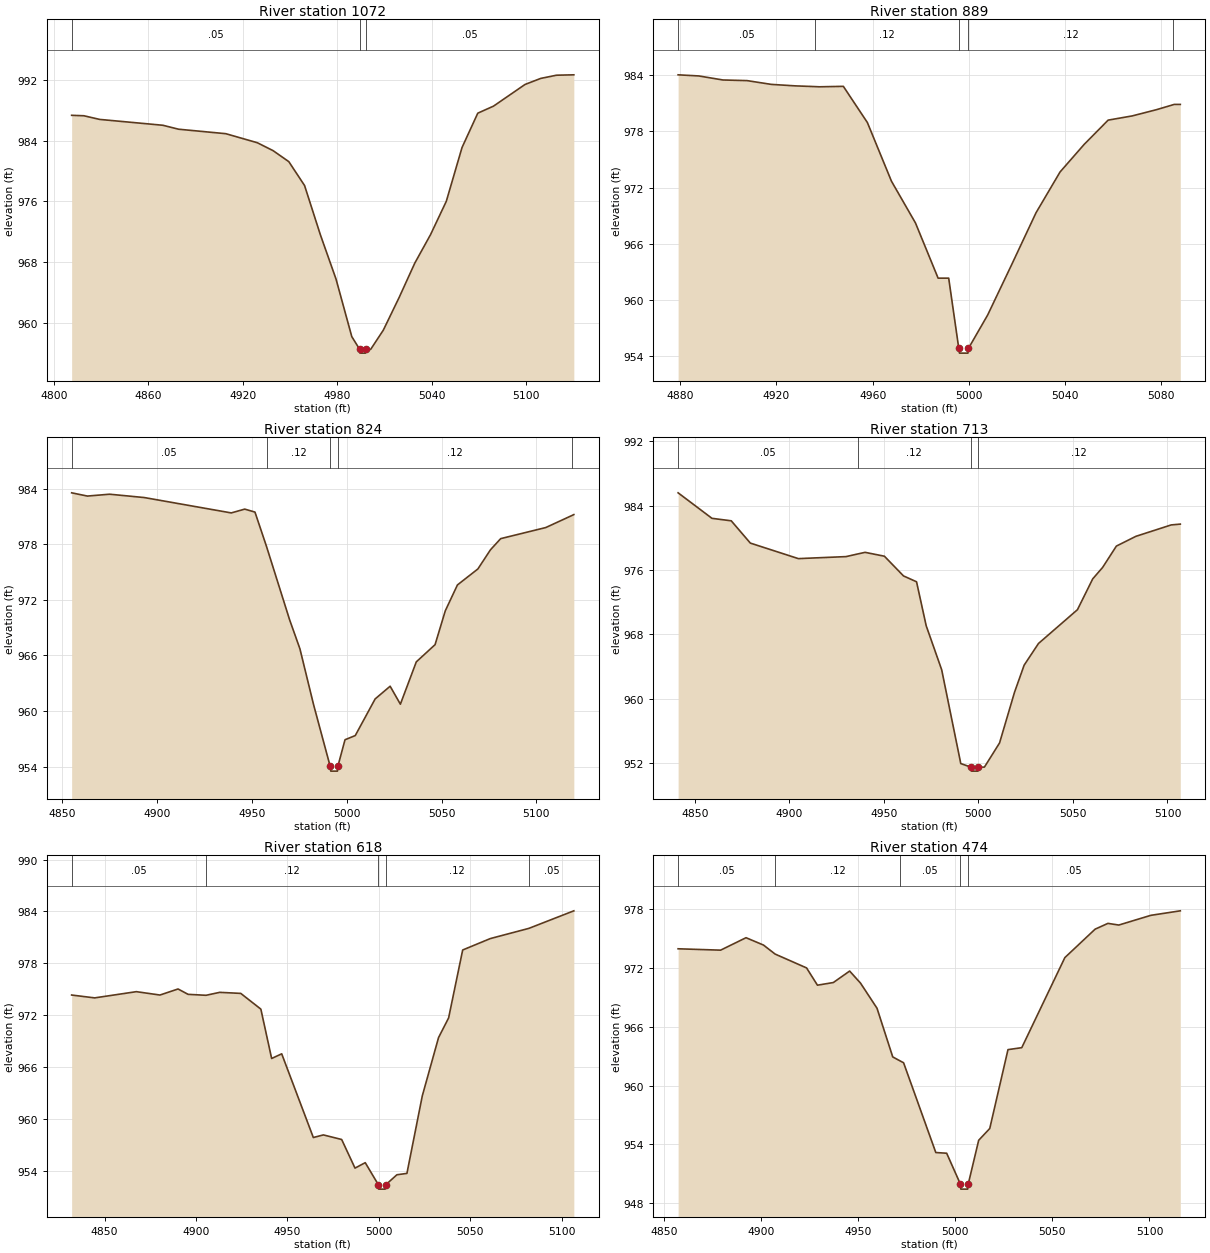
Type RM Length L Ch R = 1,1072,183,183,183
BEGIN DESCRIPTION:
MDW T 066 4.0
END DESCRIPTION:
XS GIS Cut Line= 3
      2251561.16      7137535.66      2251747.99      7137539.90
      2251879.98      7137536.70
#Sta/Elev= 30
  4811.3  987.34  4819.1  987.28  4829.1  986.80  4869.2  986.03  4879.2  985.51
  4909.2  984.92  4929.2  983.73  4939.2  982.69  4949.2  981.24  4959.2  978.10
  4969.2  971.64  4979.2  965.77  4989.2  958.20  4994.2  956.53  4994.4  956.03
  4997.9  956.03  4998.2  956.53  5001.2  956.53  5009.2  959.05  5019.2  963.33
  5029.2  967.88  5039.2  971.63  5049.2  976.01  5059.2  983.10  5069.2  987.62
  5079.2  988.55  5099.2  991.40  5109.2  992.20  5119.2  992.62  5130.2  992.67
#Mann=3,-1,0
  4811.3    0.05       0  4994.2   0.033       0  4998.2    0.05       0
Bank Sta=4994.2,4998.2
Exp/Cntr=0.3,0.1

Type RM Length L Ch R = 1,889,65,65,65
BEGIN DESCRIPTION:
MDW T 066 3.0
END DESCRIPTION:
XS GIS Cut Line= 3
      2251570.38      7137706.28      2251682.77      7137711.58
      2251779.04      7137710.00
#Sta/Elev= 29
  4879.1  984.05  4887.7  983.93  4897.7  983.50  4907.8  983.43  4917.8  983.03
  4927.8  982.87  4936.2  982.79  4937.8  982.77  4947.8  982.82  4957.8  978.95
  4967.8  972.69  4977.8  968.22  4987.2  962.33  4991.6  962.33  4995.8  954.82
  4996.1  954.32  4999.6  954.32  4999.8  954.82  5007.8  958.39  5017.8  963.78
  5027.9  969.31  5037.9  973.67  5047.9  976.61  5057.9  979.21  5067.9  979.66
  5077.9  980.32  5085.0  980.86  5085.4  980.89  5087.9  980.89
#Mann=5,-1,0
  4879.1    0.05       0  4936.2    0.12       0  4995.8    0.07       0
  4999.8    0.12       0  5085.0    0.05       0
Bank Sta=4995.8,4999.8
Exp/Cntr=0.3,0.1

Type RM Length L Ch R = 1,824,111,111,111
BEGIN DESCRIPTION:
Mapping XS 6618f3b4
END DESCRIPTION:
XS GIS Cut Line= 2
      2251541.38      7137830.96      2251785.63      7137728.42
#Sta/Elev= 30
  4854.9  983.57  4863.2  983.22  4874.9  983.42  4893.2  983.06  4939.1  981.40
  4946.2  981.81  4951.6  981.49  4957.7  977.77  4969.9  969.84  4975.3  966.73
  4982.5  960.70  4991.3  954.01  4991.6  953.51  4995.1  953.51  4995.3  954.01
  4999.1  956.90  5004.5  957.35  5015.0  961.31  5022.9  962.68  5028.3  960.74
  5036.7  965.31  5046.6  967.17  5052.0  970.83  5058.4  973.62  5069.2  975.35
  5075.8  977.41  5081.2  978.62  5105.0  979.82  5118.9  981.13  5119.8  981.22
#Mann=5,-1,0
  4854.9    0.05       0  4957.7    0.12       0  4991.3    0.07       0
  4995.3    0.12       0  5118.9    0.05       0
Bank Sta=4991.3,4995.3
Exp/Cntr=0.3,0.1

Type RM Length L Ch R = 1,713,95,95,95
BEGIN DESCRIPTION:
MDW T 066 2.0
END DESCRIPTION:
XS GIS Cut Line= 3
      2251571.28      7137884.92      2251728.42      7137860.16
      2251831.83      7137834.62
#Sta/Elev= 30
  4841.2  985.60  4859.1  982.43  4869.3  982.12  4879.4  979.35  4904.8  977.42
  4930.0  977.67  4936.2  978.00  4940.1  978.20  4950.3  977.72  4960.4  975.27
  4967.3  974.54  4972.4  969.08  4980.6  963.60  4990.7  951.94  4996.0  951.50
  4996.3  951.00  4999.8  951.00  5000.0  951.50  5003.2  951.50  5011.2  954.50
  5019.1  960.79  5024.2  964.17  5031.8  966.87  5052.4  971.07  5060.5  974.91
  5065.7  976.32  5073.0  978.98  5083.3  980.19  5102.0  981.61  5106.8  981.71
#Mann=4,-1,0
  4841.2    0.05       0  4936.2    0.12       0  4996.0    0.07       0
  5000.0    0.12       0
Bank Sta=4996,5000
Exp/Cntr=0.3,0.1

Type RM Length L Ch R = 1,618,144,144,144
BEGIN DESCRIPTION:
Mapping XS fbd91fa2
END DESCRIPTION:
XS GIS Cut Line= 2
      2251635.28      7138001.57      2251884.03      7137885.02
#Sta/Elev= 30
  4832.0  974.33  4844.6  974.00  4867.4  974.72  4880.3  974.33  4890.2  975.03
  4895.7  974.41  4905.5  974.30  4913.0  974.64  4924.5  974.52  4935.5  972.70
  4941.4  966.99  4946.9  967.53  4964.2  957.85  4969.7  958.15  4979.7  957.62
  4987.0  954.31  4992.6  954.94  4999.8  952.38  5000.0  951.88  5003.5  951.88
  5003.8  952.38  5009.9  953.54  5015.4  953.70  5023.8  962.66  5032.7  969.41
  5038.2  971.68  5045.9  979.54  5061.0  980.86  5082.1  982.04  5106.7  984.07
#Mann=5,-1,0
  4832.0    0.05       0  4905.5    0.12       0  4999.8    0.07       0
  5003.8    0.12       0  5082.1    0.05       0
Bank Sta=4999.8,5003.8
Exp/Cntr=0.3,0.1

Type RM Length L Ch R = 1,474,89,89,89
BEGIN DESCRIPTION:
Mapping XS 0e2a5724
END DESCRIPTION:
XS GIS Cut Line= 2
      2251677.86      7138003.29      2251908.00      7138121.67
#Sta/Elev= 30
  4857.1  973.94  4879.0  973.80  4892.1  975.07  4901.1  974.32  4907.1  973.40
  4923.3  971.99  4928.9  970.23  4937.1  970.50  4945.5  971.67  4951.1  970.44
  4959.6  967.88  4967.7  962.92  4971.4  962.52  4973.3  962.32  4989.9  953.17
  4995.5  953.10  5002.6  949.94  5002.8  949.44  5006.3  949.44  5006.6  949.94
  5012.0  954.42  5017.7  955.62  5027.1  963.66  5034.2  963.86  5056.4  973.04
  5072.0  975.94  5078.6  976.53  5084.2  976.36  5100.7  977.35  5115.9  977.81
#Mann=5,-1,0
  4857.1    0.05       0  4907.1    0.12       0  4971.4    0.05       0
  5002.6   0.033       0  5006.6    0.05       0
Bank Sta=5002.6,5006.6
Exp/Cntr=0.3,0.1

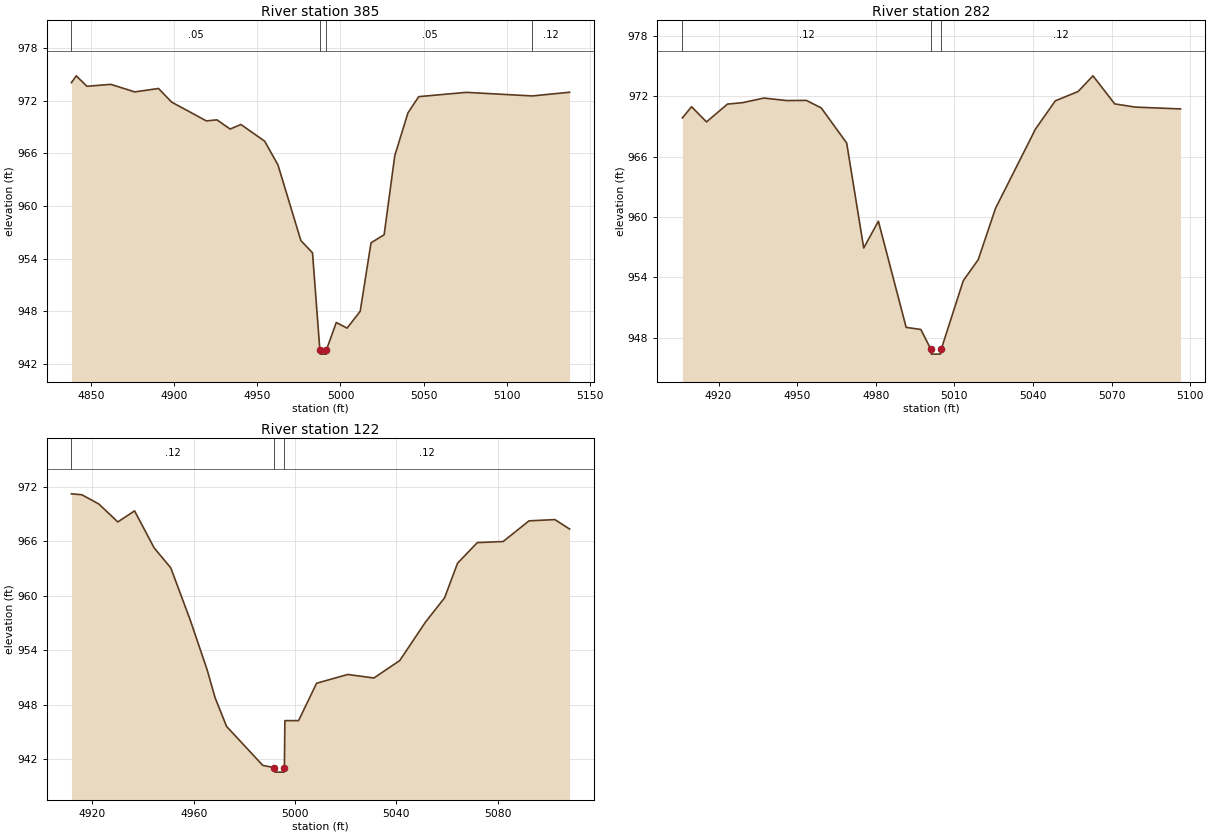
Type RM Length L Ch R = 1,385,103,103,103
BEGIN DESCRIPTION:
Mapping XS 733c2922
END DESCRIPTION:
XS GIS Cut Line= 2
      2251641.92      7138033.07      2251874.45      7138222.31
#Sta/Elev= 30
  4838.1  974.03  4841.0  974.81  4847.4  973.62  4861.8  973.84  4876.2  972.98
  4890.5  973.37  4898.4  971.82  4919.3  969.68  4925.7  969.80  4933.6  968.75
  4940.1  969.27  4954.4  967.37  4962.4  964.67  4976.2  956.05  4983.2  954.66
  4987.6  943.63  4987.9  943.13  4991.4  943.13  4991.6  943.63  4997.5  946.73
  5004.0  946.09  5011.9  948.01  5018.4  955.80  5026.3  956.72  5032.7  965.72
  5040.6  970.58  5047.1  972.44  5075.8  972.93  5115.4  972.52  5137.9  972.94
#Mann=4,-1,0
  4838.1    0.05       0  4987.6   0.033       0  4991.6    0.05       0
  5115.4    0.12       0
Bank Sta=4987.6,4991.6
Exp/Cntr=0.3,0.1

Type RM Length L Ch R = 1,282,160,160,160
BEGIN DESCRIPTION:
Mapping XS 7cbd2840
END DESCRIPTION:
XS GIS Cut Line= 2
      2251633.89      7138161.70      2251801.08      7138252.18
#Sta/Elev= 28
  4906.2  969.86  4909.7  970.97  4915.4  969.46  4923.4  971.23  4929.1  971.37
  4937.3  971.83  4946.1  971.58  4953.5  971.60  4959.2  970.85  4968.9  967.36
  4975.4  956.93  4981.0  959.59  4991.6  949.04  4997.2  948.83  5001.0  946.88
  5001.2  946.38  5004.7  946.38  5005.0  946.88  5013.4  953.68  5019.1  955.77
  5025.7  960.87  5041.0  968.77  5048.5  971.55  5057.2  972.48  5062.9  974.04
  5071.2  971.25  5079.1  970.93  5096.3  970.75
#Mann=3,-1,0
  4906.2    0.12       0  5001.0    0.07       0  5005.0    0.12       0
Bank Sta=5001,5005
Exp/Cntr=0.3,0.1

Type RM Length L Ch R = 1,122,0,0,0
BEGIN DESCRIPTION:
MDW T 066 0.5
END DESCRIPTION:
XS GIS Cut Line= 3
      2251610.78      7138302.47      2251675.89      7138357.83
      2251784.69      7138335.66
#Sta/Elev= 30
  4911.8  971.25  4915.9  971.15  4922.6  970.13  4930.1  968.15  4936.7  969.37
  4944.4  965.30  4951.0  963.08  4958.7  957.30  4965.3  951.87  4968.5  948.74
  4973.0  945.60  4987.3  941.30  4991.8  941.06  4992.1  940.56  4995.6  940.56
  4995.8  941.06  4996.0  946.24  5001.4  946.24  5008.5  950.36  5020.8  951.33
  5031.1  950.94  5041.3  952.86  5051.5  957.12  5059.0  959.78  5064.1  963.59
  5071.9  965.87  5082.1  965.99  5092.3  968.27  5102.5  968.41  5108.3  967.37
#Mann=3,-1,0
  4911.8    0.12       0  4991.8    0.07       0  4995.8    0.12       0
Bank Sta=4991.8,4995.8
Exp/Cntr=0.3,0.1

Chan Stop Cuts=-1