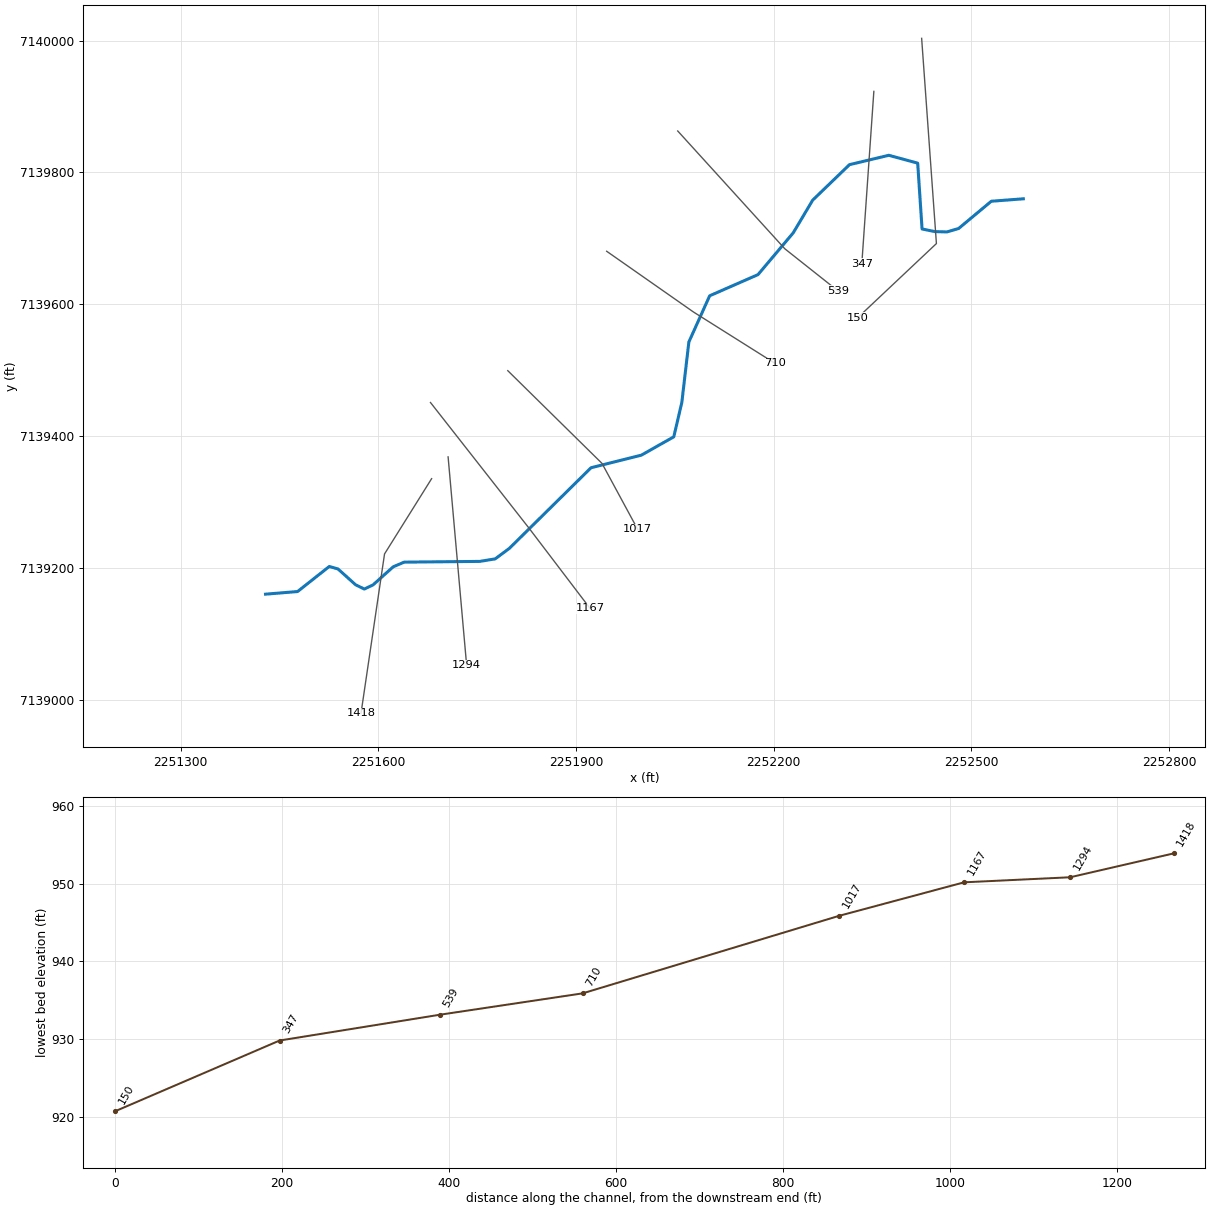
--- MDW T 067.prj (project) ---

Proj Title=MDW T 067 Base Level Engineering
Current Plan=p01
Default Exp/Contr=0.3,0.1
English Units
Geom File=g01
Flow File=f01
Plan File=p01
BEGIN DESCRIPTION:
MDW T 067
END DESCRIPTION:

--- MDW T 067.p01 (plan) ---

Plan Title=Multiple Run
Short Identifier=Multiple
Geom File=g01
Flow File=f01
Subcritical Flow
K Sum by GR= 0
Std Step Tol= 0.01
Critical Tol= 0.01
Num of Std Step Trials= 20
Max Error Tol= 0.3
Flow Tol Ratio= 0.001
Split Flow NTrial= 30
Split Flow Tol= 0.02
Split Flow Ratio= 0.02
Log Output Level= 0
Friction Slope Method= 1
Unsteady Friction Slope Method= 2
Unsteady Bridges Friction Slope Method= 1
Parabolic Critical Depth
Global Vel Dist=  1 , 1 , 1
Global Log Level= 0
CheckData=True
Encroach Param= -1, 0, 0, 0
BEGIN DESCRIPTION:
Multiple Run
END DESCRIPTION:

--- MDW T 067.f01 (steady flow) ---

Flow Title=Multiple
Number of Profiles=7
Profile Names=10-year,25-year,50-year,1pct_min,100-year,1pct_plu,500-year
River Rch & RM= MDW T 067,Reach-1,1418
     330     439     527     316     630    1257     899
Boundary for River Rch & Prof#=MDW T 067,Reach-1,1
Up Type=0
Dn Type=3
Dn Slope=0.005
Boundary for River Rch & Prof#=MDW T 067,Reach-1,2
Up Type=0
Dn Type=3
Dn Slope=0.005
Boundary for River Rch & Prof#=MDW T 067,Reach-1,3
Up Type=0
Dn Type=3
Dn Slope=0.005
Boundary for River Rch & Prof#=MDW T 067,Reach-1,4
Up Type=0
Dn Type=3
Dn Slope=0.005
Boundary for River Rch & Prof#=MDW T 067,Reach-1,5
Up Type=0
Dn Type=3
Dn Slope=0.005
Boundary for River Rch & Prof#=MDW T 067,Reach-1,6
Up Type=0
Dn Type=3
Dn Slope=0.005
Boundary for River Rch & Prof#=MDW T 067,Reach-1,7
Up Type=0
Dn Type=3
Dn Slope=0.005

--- MDW T 067.g01 (geometry) ---

Geom Title=Existing Conditions

River Reach=MDW T 067,Reach-1
Reach XY= 30
      2251429.00      7139160.00      2251477.64      7139163.98
      2251525.74      7139202.01      2251539.03      7139198.23
      2251565.62      7139174.30      2251578.90      7139167.77
      2251592.16      7139174.06      2251622.81      7139201.56
      2251639.44      7139208.61      2251754.11      7139209.73
      2251777.53      7139213.54      2251799.16      7139229.61
      2251922.95      7139351.84      2251999.36      7139370.96
      2252048.57      7139398.77      2252060.77      7139450.90
      2252071.46      7139542.71      2252103.04      7139612.81
      2252176.37      7139644.94      2252229.87      7139708.38
      2252259.34      7139757.93      2252315.22      7139811.81
      2252374.90      7139826.02      2252418.72      7139814.09
      2252425.35      7139714.22      2252444.99      7139710.19
      2252463.21      7139709.76      2252480.87      7139714.94
      2252530.45      7139756.29      2252579.00      7139760.00

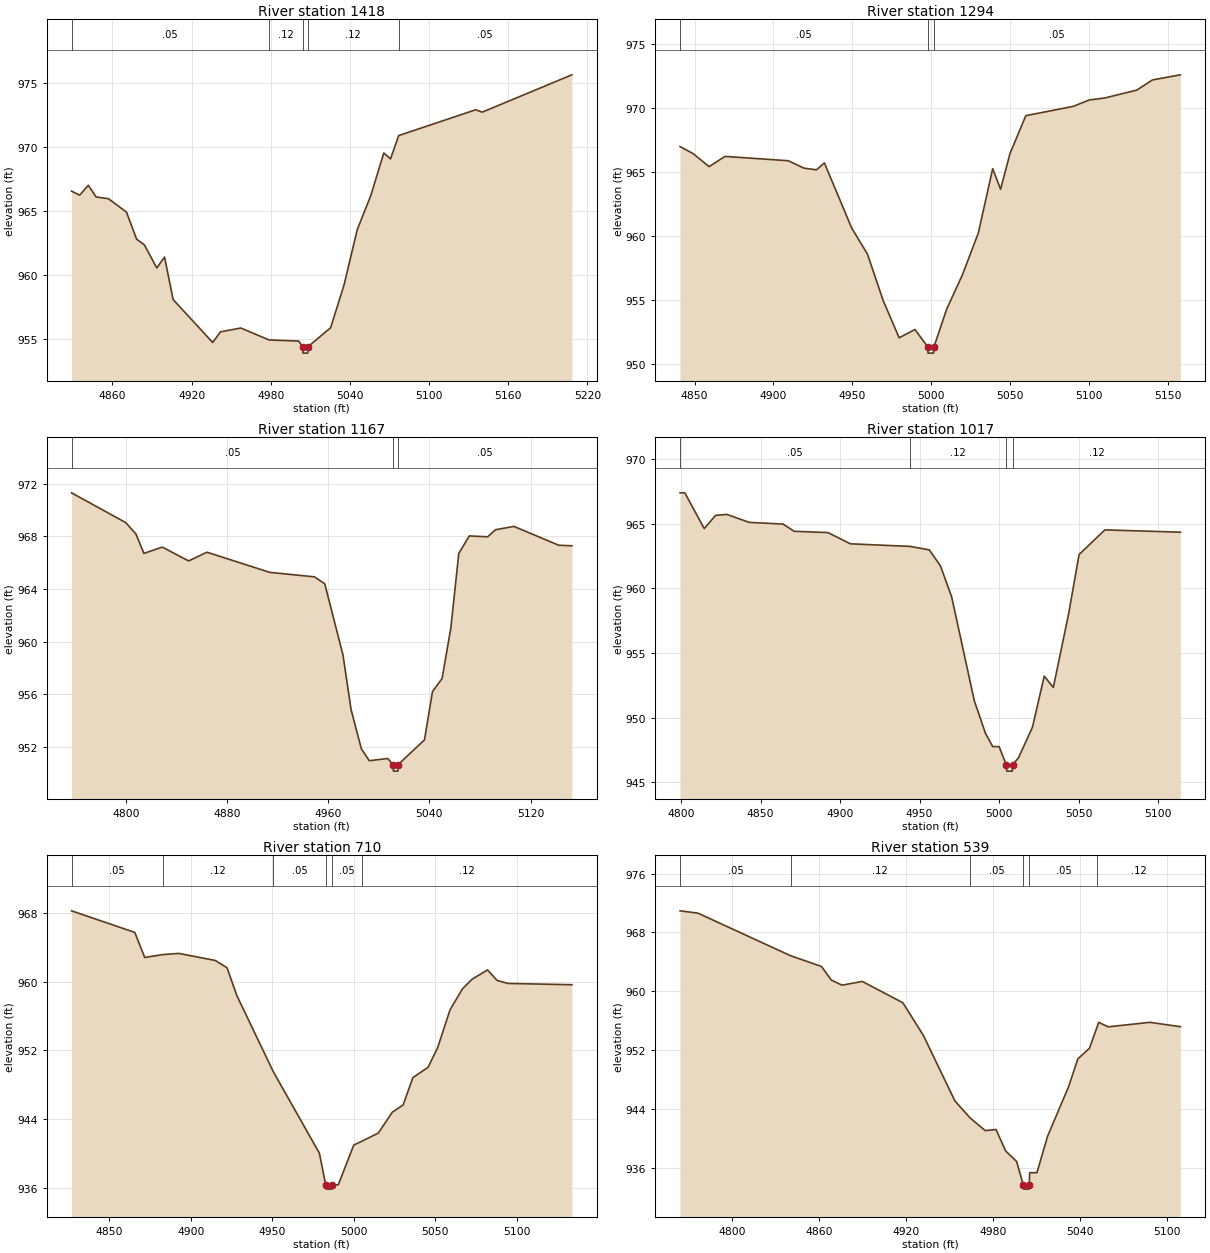
Type RM Length L Ch R = 1,1418,124,124,124
BEGIN DESCRIPTION:
MDW T 067 5.0
END DESCRIPTION:
XS GIS Cut Line= 3
      2251681.05      7139335.27      2251609.61      7139221.04
      2251573.89      7138979.09
#Sta/Elev= 30
  4829.0  966.53  4835.2  966.22  4841.7  966.99  4847.6  966.08  4857.0  965.94
  4870.6  964.90  4878.3  962.79  4884.2  962.34  4893.6  960.54  4899.5  961.39
  4906.0  958.07  4936.0  954.72  4941.9  955.55  4957.3  955.85  4978.7  954.92
  5001.2  954.83  5004.2  954.39  5004.5  953.89  5008.0  953.89  5008.2  954.39
  5025.4  955.87  5035.5  959.19  5045.6  963.53  5055.8  966.17  5065.7  969.51
  5070.8  969.05  5077.0  970.87  5135.3  972.88  5140.4  972.70  5208.3  975.61
#Mann=5,-1,0
  4829.0    0.05       0  4978.7    0.12       0  5004.2    0.07       0
  5008.2    0.12       0  5077.0    0.05       0
Bank Sta=5004.2,5008.2
Exp/Cntr=0.3,0.1

Type RM Length L Ch R = 1,1294,127,127,127
BEGIN DESCRIPTION:
Mapping XS 39e94df2
END DESCRIPTION:
XS GIS Cut Line= 2
      2251706.08      7139368.34      2251734.17      7139052.39
#Sta/Elev= 30
  4840.8  967.00  4849.2  966.44  4859.2  965.43  4869.3  966.23  4909.4  965.89
  4919.4  965.31  4927.3  965.18  4932.3  965.72  4949.6  960.62  4959.6  958.58
  4969.6  954.93  4979.7  952.02  4989.7  952.67  4997.8  951.32  4998.0  950.82
  5001.5  950.82  5001.8  951.32  5009.8  954.26  5019.8  956.95  5029.9  960.23
  5039.0  965.27  5044.0  963.66  5050.0  966.46  5060.0  969.42  5090.1  970.15
  5100.2  970.65  5110.2  970.81  5130.3  971.42  5140.3  972.22  5158.0  972.62
#Mann=3,-1,0
  4840.8    0.05       0  4997.8   0.033       0  5001.8    0.05       0
Bank Sta=4997.8,5001.8
Exp/Cntr=0.3,0.1

Type RM Length L Ch R = 1,1167,150,150,150
BEGIN DESCRIPTION:
MDW T 067 4.0
END DESCRIPTION:
XS GIS Cut Line= 3
      2251679.33      7139450.87      2251829.00      7139260.00
      2251921.54      7139138.35
#Sta/Elev= 30
  4757.2  971.30  4800.0  969.04  4808.1  968.17  4814.4  966.70  4828.9  967.18
  4849.7  966.13  4864.2  966.79  4913.9  965.26  4949.2  964.92  4957.3  964.39
  4971.7  958.99  4978.1  954.84  4986.2  951.87  4992.5  950.96  5007.0  951.13
  5011.3  950.67  5011.6  950.17  5015.1  950.17  5015.3  950.67  5036.1  952.54
  5042.4  956.20  5050.0  957.20  5056.9  961.01  5063.2  966.69  5071.5  968.03
  5086.0  967.96  5092.3  968.50  5106.8  968.75  5142.2  967.32  5152.6  967.28
#Mann=3,-1,0
  4757.2    0.05       0  5011.3   0.033       0  5015.3    0.05       0
Bank Sta=5011.3,5015.3
Exp/Cntr=0.3,0.1

Type RM Length L Ch R = 1,1017,307,307,307
BEGIN DESCRIPTION:
MDW T 067 3.0
END DESCRIPTION:
XS GIS Cut Line= 3
      2251796.67      7139499.16      2251939.64      7139358.45
      2251993.90      7139258.19
#Sta/Elev= 30
  4799.4  967.41  4802.4  967.41  4814.6  964.64  4821.7  965.66  4828.8  965.74
  4842.9  965.12  4864.1  964.99  4871.2  964.43  4892.4  964.33  4906.5  963.46
  4944.1  963.26  4956.1  962.99  4963.1  961.76  4970.2  959.34  4984.4  951.31
  4991.4  948.79  4996.0  947.75  5000.0  947.75  5004.5  946.35  5004.8  945.85
  5008.3  945.85  5008.5  946.35  5012.2  946.88  5021.0  949.26  5028.4  953.21
  5034.1  952.33  5043.7  958.02  5050.3  962.63  5066.5  964.54  5114.0  964.36
#Mann=4,-1,0
  4799.4    0.05       0  4944.1    0.12       0  5004.5    0.07       0
  5008.5    0.12       0
Bank Sta=5004.5,5008.5
Exp/Cntr=0.3,0.1

Type RM Length L Ch R = 1,710,171,171,171
BEGIN DESCRIPTION:
MDW T 067 2.0
END DESCRIPTION:
XS GIS Cut Line= 3
      2251946.73      7139680.37      2252078.41      7139588.23
      2252202.28      7139510.24
#Sta/Elev= 30
  4826.8  968.23  4865.6  965.72  4871.7  962.81  4882.7  963.14  4892.6  963.28
  4915.0  962.46  4922.2  961.62  4928.3  958.36  4950.6  949.54  4978.9  940.06
  4982.8  936.38  4983.1  935.88  4986.6  935.88  4986.8  936.38  4990.5  936.38
  5000.0  941.00  5005.2  941.47  5015.1  942.40  5023.7  944.83  5030.3  945.66
  5036.3  948.84  5045.6  950.04  5051.5  952.32  5059.1  956.72  5066.8  959.18
  5072.7  960.29  5082.1  961.36  5088.0  960.14  5094.6  959.79  5133.9  959.64
#Mann=6,-1,0
  4826.8    0.05       0  4882.7    0.12       0  4950.6    0.05       0
  4982.8   0.033       0  4986.8    0.05       0  5005.2    0.12       0
Bank Sta=4982.8,4986.8
Exp/Cntr=0.3,0.1

Type RM Length L Ch R = 1,539,192,192,192
BEGIN DESCRIPTION:
MDW T 067 1.0
END DESCRIPTION:
XS GIS Cut Line= 3
      2252054.57      7139862.92      2252217.08      7139684.15
      2252298.05      7139620.00
#Sta/Elev= 30
  4764.3  970.94  4776.7  970.62  4840.6  964.83  4861.8  963.38  4868.6  961.53
  4876.0  960.84  4889.9  961.35  4917.9  958.45  4932.1  953.99  4953.7  945.13
  4964.1  942.83  4974.7  941.08  4982.1  941.23  4988.8  938.30  4996.3  936.89
  5001.0  933.63  5001.3  933.13  5004.8  933.13  5005.0  933.63  5005.3  935.36
  5010.3  935.36  5017.7  940.34  5032.1  947.03  5038.5  950.82  5046.5  952.26
  5052.0  955.29  5052.9  955.79  5059.4  955.18  5088.2  955.79  5109.2  955.20
#Mann=6,-1,0
  4764.3    0.05       0  4840.6    0.12       0  4964.1    0.05       0
  5001.0   0.033       0  5005.0    0.05       0  5052.0    0.12       0
Bank Sta=5001,5005
Exp/Cntr=0.3,0.1

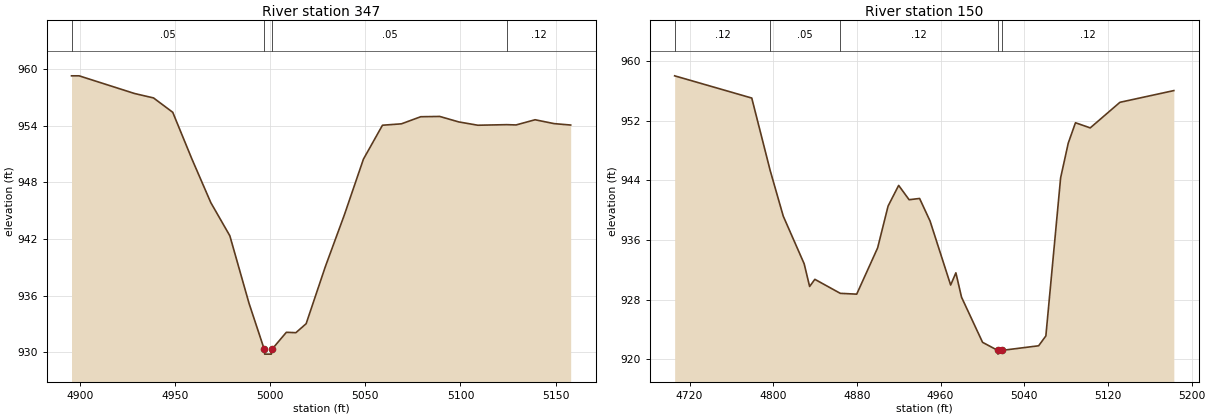
Type RM Length L Ch R = 1,347,197,197,197
BEGIN DESCRIPTION:
Mapping XS 1d0ff3ba
END DESCRIPTION:
XS GIS Cut Line= 2
      2252352.19      7139923.03      2252333.91      7139661.37
#Sta/Elev= 30
  4895.6  959.27  4899.6  959.27  4928.7  957.40  4938.7  956.93  4948.8  955.41
  4958.8  950.50  4968.8  945.85  4978.8  942.34  4988.9  935.18  4996.9  930.31
  4997.1  929.81  5000.6  929.81  5000.9  930.31  5008.5  932.12  5013.5  932.08
  5018.9  933.03  5029.0  939.08  5039.0  944.56  5049.0  950.45  5059.0  954.04
  5069.0  954.19  5079.1  954.94  5089.1  954.97  5099.1  954.39  5109.1  954.04
  5124.3  954.10  5129.2  954.07  5139.2  954.62  5149.2  954.21  5157.9  954.06
#Mann=4,-1,0
  4895.6    0.05       0  4996.9   0.033       0  5000.9    0.05       0
  5124.3    0.12       0
Bank Sta=4996.9,5000.9
Exp/Cntr=0.3,0.1

Type RM Length L Ch R = 1,150,0,0,0
BEGIN DESCRIPTION:
MDW T 067 0.5
END DESCRIPTION:
XS GIS Cut Line= 3
      2252424.72      7140003.52      2252447.14      7139692.08
      2252327.16      7139579.03
#Sta/Elev= 30
  4705.8  958.02  4779.5  955.04  4797.1  945.33  4809.6  939.21  4829.6  932.82
  4834.8  929.78  4839.8  930.74  4864.1  928.86  4879.8  928.75  4899.8  934.95
  4909.8  940.56  4919.9  943.33  4929.9  941.41  4939.9  941.58  4949.9  938.56
  4969.6  929.97  4974.6  931.61  4980.0  928.34  5000.1  922.29  5014.6  921.21
  5014.8  920.71  5018.6  921.21  5053.7  921.83  5060.6  923.15  5074.7  944.34
  5082.0  949.00  5088.9  951.73  5103.0  951.04  5131.4  954.47  5182.9  956.04
#Mann=5,-1,0
  4705.8    0.12       0  4797.1    0.05       0  4864.1    0.12       0
  5014.6    0.07       0  5018.6    0.12       0
Bank Sta=5014.6,5018.6
Exp/Cntr=0.3,0.1

Chan Stop Cuts=-1