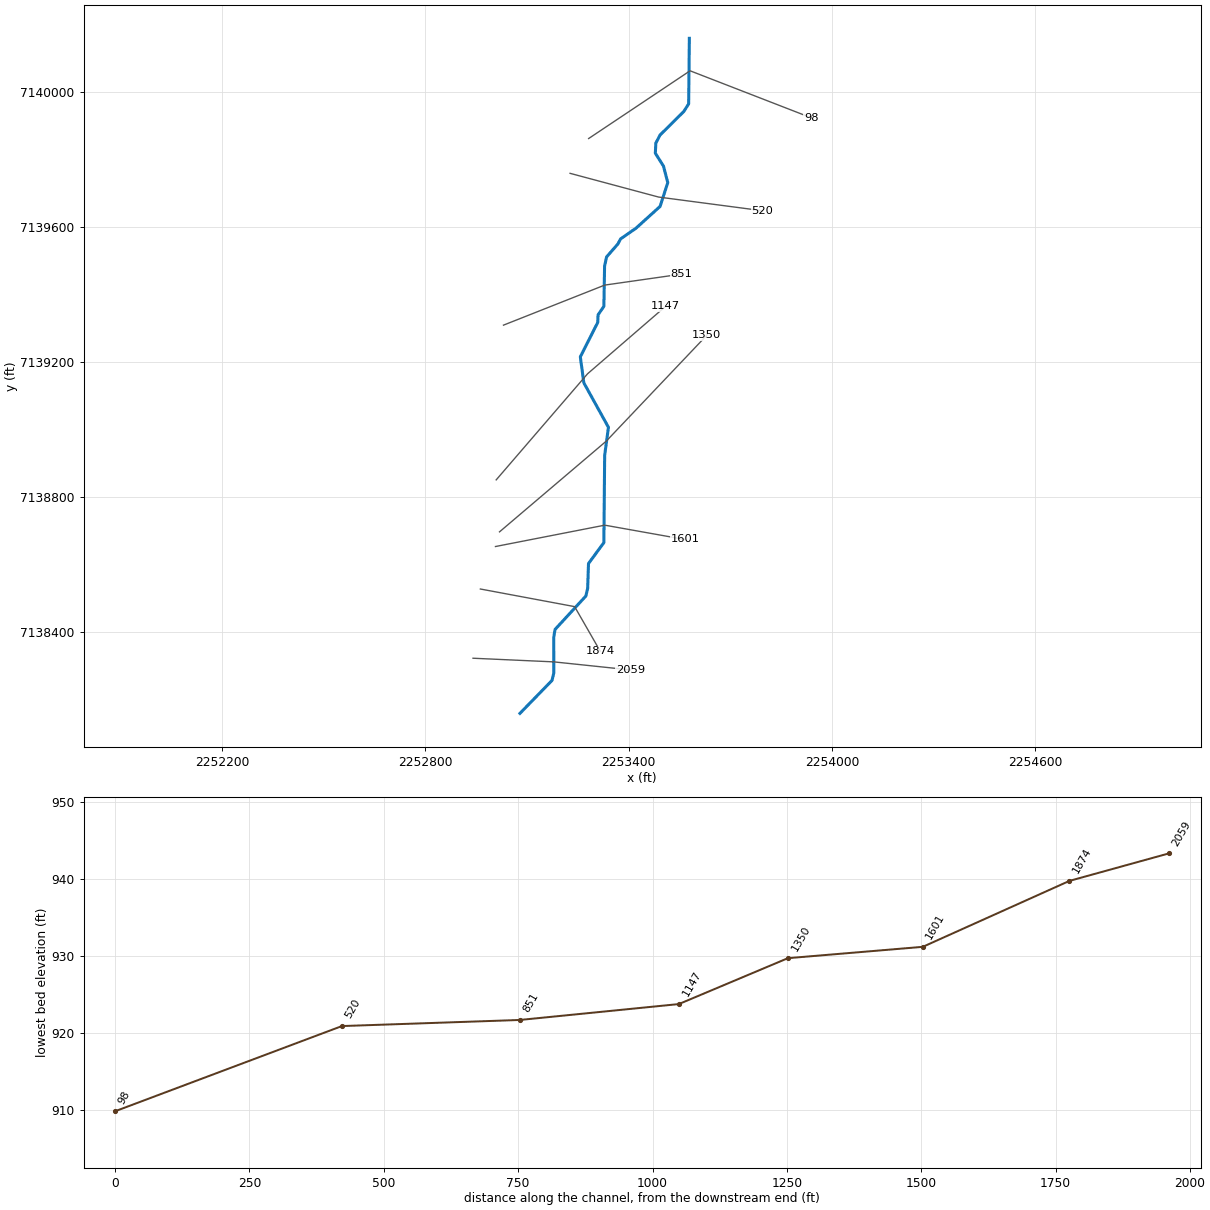
--- MDW T 068.prj (project) ---

Proj Title=MDW T 068 Base Level Engineering
Current Plan=p01
Default Exp/Contr=0.3,0.1
English Units
Geom File=g01
Flow File=f01
Plan File=p01
BEGIN DESCRIPTION:
MDW T 068
END DESCRIPTION:

--- MDW T 068.p01 (plan) ---

Plan Title=Multiple Run
Short Identifier=Multiple
Geom File=g01
Flow File=f01
Subcritical Flow
K Sum by GR= 0
Std Step Tol= 0.01
Critical Tol= 0.01
Num of Std Step Trials= 20
Max Error Tol= 0.3
Flow Tol Ratio= 0.001
Split Flow NTrial= 30
Split Flow Tol= 0.02
Split Flow Ratio= 0.02
Log Output Level= 0
Friction Slope Method= 1
Unsteady Friction Slope Method= 2
Unsteady Bridges Friction Slope Method= 1
Parabolic Critical Depth
Global Vel Dist=  1 , 1 , 1
Global Log Level= 0
CheckData=True
Encroach Param= -1, 0, 0, 0
BEGIN DESCRIPTION:
Multiple Run
END DESCRIPTION:

--- MDW T 068.f01 (steady flow) ---

Flow Title=Multiple
Number of Profiles=7
Profile Names=10-year,25-year,50-year,1pct_min,100-year,1pct_plu,500-year
River Rch & RM= MDW T 068,Reach-1,2059
     587     812    1001     614    1225    2445    1837
Boundary for River Rch & Prof#=MDW T 068,Reach-1,1
Up Type=0
Dn Type=3
Dn Slope=0.005
Boundary for River Rch & Prof#=MDW T 068,Reach-1,2
Up Type=0
Dn Type=3
Dn Slope=0.005
Boundary for River Rch & Prof#=MDW T 068,Reach-1,3
Up Type=0
Dn Type=3
Dn Slope=0.005
Boundary for River Rch & Prof#=MDW T 068,Reach-1,4
Up Type=0
Dn Type=3
Dn Slope=0.005
Boundary for River Rch & Prof#=MDW T 068,Reach-1,5
Up Type=0
Dn Type=3
Dn Slope=0.005
Boundary for River Rch & Prof#=MDW T 068,Reach-1,6
Up Type=0
Dn Type=3
Dn Slope=0.005
Boundary for River Rch & Prof#=MDW T 068,Reach-1,7
Up Type=0
Dn Type=3
Dn Slope=0.005

--- MDW T 068.g01 (geometry) ---

Geom Title=Existing Conditions

River Reach=MDW T 068,Reach-1
Reach XY= 30
      2253079.00      7138160.00      2253173.60      7138257.52
      2253179.03      7138279.99      2253178.73      7138385.11
      2253182.56      7138408.53      2253273.46      7138507.58
      2253278.87      7138530.05      2253281.36      7138604.02
      2253326.74      7138665.94      2253329.04      7138924.46
      2253340.22      7139007.53      2253267.53      7139139.47
      2253257.23      7139216.32      2253308.59      7139318.26
      2253309.61      7139340.83      2253326.73      7139365.94
      2253328.81      7139485.08      2253334.71      7139512.35
      2253367.84      7139550.48      2253376.17      7139565.85
      2253421.64      7139597.54      2253492.59      7139662.01
      2253515.34      7139732.60      2253502.53      7139781.59
      2253478.56      7139819.63      2253480.07      7139849.56
      2253492.40      7139873.30      2253562.54      7139943.25
      2253576.94      7139965.85      2253579.00      7140160.00

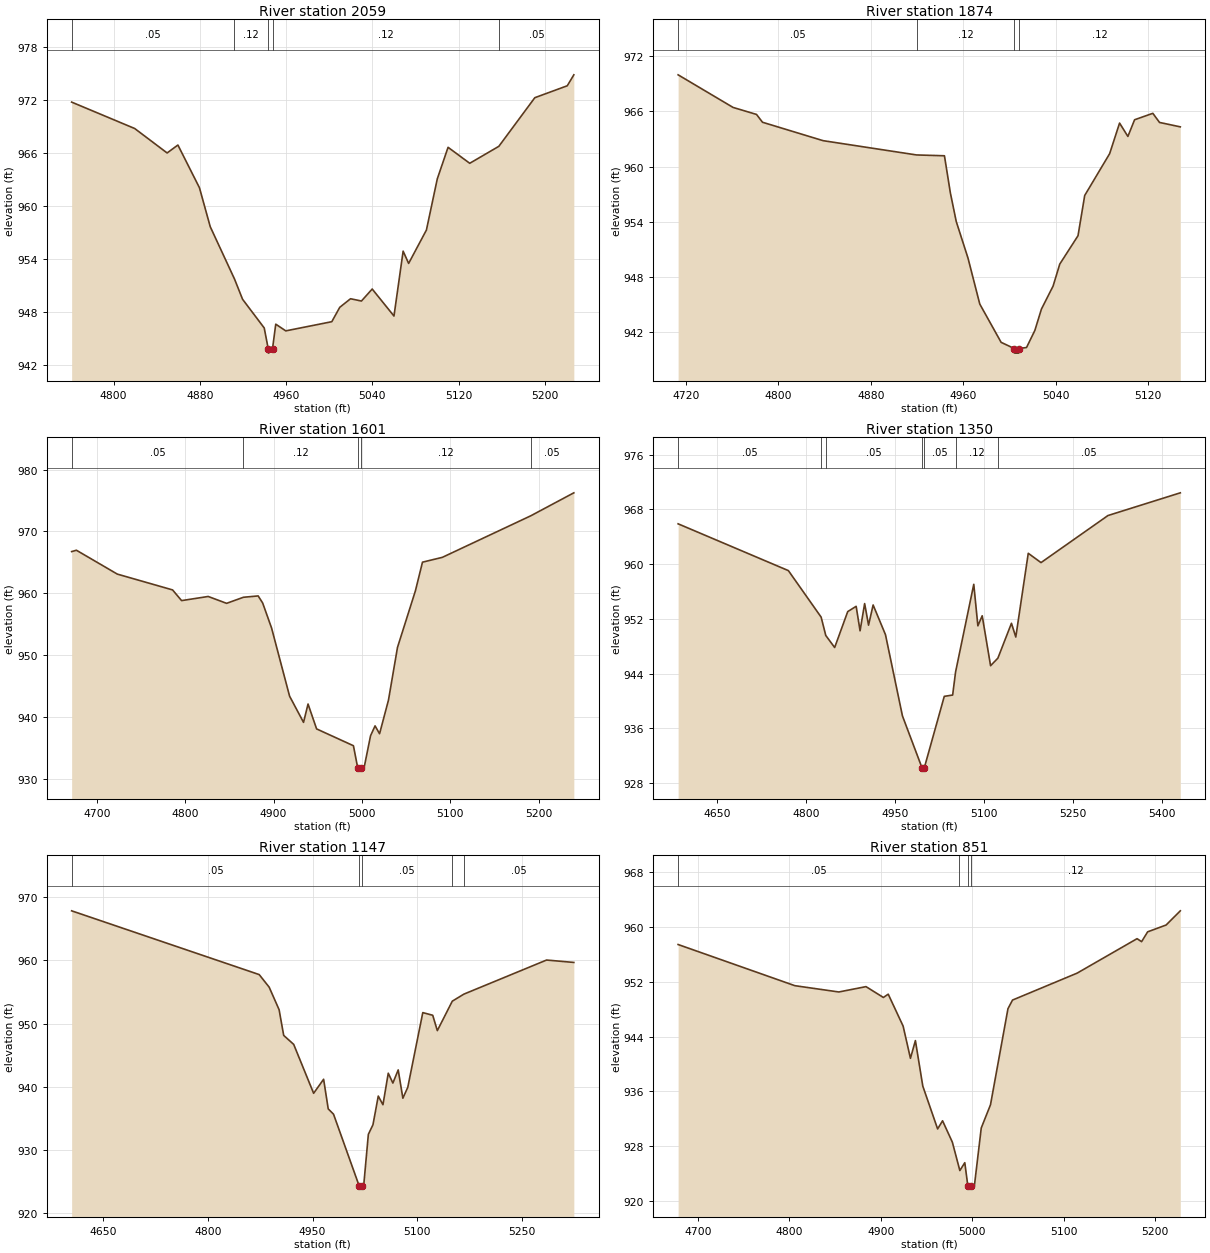
Type RM Length L Ch R = 1,2059,185,185,185
BEGIN DESCRIPTION:
MDW T 068 6.0
END DESCRIPTION:
XS GIS Cut Line= 3
      2252940.52      7138323.40      2253179.28      7138312.56
      2253405.03      7138288.78
#Sta/Elev= 30
  4761.0  971.75  4819.5  968.76  4849.6  965.99  4859.6  966.89  4879.6  962.05
  4889.6  957.64  4912.1  951.72  4919.6  949.42  4939.7  946.17  4943.4  943.82
  4943.7  943.32  4947.4  943.82  4950.4  946.60  4959.7  945.84  5002.4  946.88
  5009.8  948.51  5019.8  949.48  5029.9  949.22  5039.9  950.58  5060.1  947.52
  5068.6  954.87  5073.7  953.48  5090.2  957.26  5100.3  963.06  5110.3  966.63
  5130.4  964.82  5157.4  966.74  5190.8  972.25  5220.9  973.60  5227.0  974.84
#Mann=5,-1,0
  4761.0    0.05       0  4912.1    0.12       0  4943.4    0.07       0
  4947.4    0.12       0  5157.4    0.05       0
Bank Sta=4943.4,4947.4
Exp/Cntr=0.3,0.1

Type RM Length L Ch R = 1,1874,273,273,273
BEGIN DESCRIPTION:
MDW T 068 5.0
END DESCRIPTION:
XS GIS Cut Line= 3
      2252962.22      7138528.48      2253240.41      7138476.28
      2253315.84      7138344.36
#Sta/Elev= 30
  4713.1  969.98  4760.7  966.44  4781.0  965.68  4786.2  964.83  4838.7  962.83
  4919.6  961.28  4943.8  961.19  4948.9  957.18  4954.0  954.06  4964.2  950.08
  4974.4  945.09  4992.9  940.93  5004.3  940.26  5004.5  939.76  5008.0  939.76
  5008.3  940.26  5014.9  940.37  5022.1  942.22  5027.8  944.54  5037.9  947.04
  5043.7  949.43  5059.5  952.51  5065.3  956.88  5086.9  961.42  5095.5  964.74
  5102.7  963.29  5108.5  965.10  5124.3  965.80  5130.1  964.81  5148.1  964.33
#Mann=4,-1,0
  4713.1    0.05       0  4919.6    0.12       0  5004.3    0.07       0
  5008.3    0.12       0
Bank Sta=5004.3,5008.3
Exp/Cntr=0.3,0.1

Type RM Length L Ch R = 1,1601,251,251,251
BEGIN DESCRIPTION:
MDW T 068 4.0
END DESCRIPTION:
XS GIS Cut Line= 3
      2253006.79      7138654.35      2253329.34      7138717.63
      2253565.57      7138675.26
#Sta/Elev= 30
  4671.3  966.73  4676.7  966.95  4723.0  963.09  4785.6  960.53  4795.8  958.80
  4825.9  959.47  4846.8  958.36  4865.8  959.34  4882.5  959.56  4887.6  958.42
  4897.7  954.37  4918.1  943.34  4933.9  939.10  4939.0  942.07  4948.7  938.04
  4990.4  935.32  4995.3  931.71  4995.5  931.21  4999.3  931.71  5002.4  931.71
  5009.8  936.94  5014.9  938.53  5020.0  937.26  5030.1  942.71  5040.3  951.23
  5060.6  960.39  5068.6  965.02  5091.1  965.80  5191.2  972.52  5240.0  976.24
#Mann=5,-1,0
  4671.3    0.05       0  4865.8    0.12       0  4995.3    0.07       0
  4999.3    0.12       0  5191.2    0.05       0
Bank Sta=4995.3,4999.3
Exp/Cntr=0.3,0.1

Type RM Length L Ch R = 1,1350,203,203,203
BEGIN DESCRIPTION:
MDW T 068 3.5
END DESCRIPTION:
XS GIS Cut Line= 3
      2253018.69      7138697.75      2253333.71      7138966.54
      2253630.67      7139280.43
#Sta/Elev= 30
  4584.2  965.89  4770.0  959.05  4825.2  952.25  4833.0  949.57  4848.0  947.81
  4870.0  953.06  4884.2  953.83  4890.8  950.25  4898.5  954.23  4905.1  951.08
  4912.8  954.03  4933.6  949.69  4962.2  937.81  4995.1  930.24  4995.4  929.74
  4999.1  930.24  5032.7  940.67  5046.8  940.86  5051.7  944.22  5082.4  957.05
  5089.3  950.98  5096.6  952.45  5110.7  945.15  5123.0  946.25  5145.9  951.35
  5153.2  949.34  5174.2  961.58  5195.7  960.22  5308.5  967.10  5430.4  970.42
#Mann=7,-1,0
  4584.2    0.05       0  4825.2    0.12       0  4833.0    0.05       0
  4995.1   0.033       0  4999.1    0.05       0  5051.7    0.12       0
  5123.0    0.05       0
Bank Sta=4995.1,4999.1
Exp/Cntr=0.3,0.1

Type RM Length L Ch R = 1,1147,296,296,296
BEGIN DESCRIPTION:
MDW T 068 3.0
END DESCRIPTION:
XS GIS Cut Line= 3
      2253008.92      7138851.82      2253278.65      7139166.19
      2253508.49      7139365.58
#Sta/Elev= 30
  4605.3  967.84  4873.6  957.75  4887.9  955.76  4902.1  952.19  4908.7  948.12
  4923.0  946.70  4951.5  938.96  4965.8  941.18  4972.4  936.49  4980.0  935.65
  5016.7  924.29  5017.0  923.79  5020.7  924.29  5023.1  924.29  5029.8  932.46
  5036.4  933.98  5044.0  938.52  5050.7  937.15  5058.3  942.14  5064.9  940.58
  5072.5  942.66  5079.2  938.18  5086.2  939.90  5107.7  951.73  5121.9  951.31
  5128.5  948.88  5149.9  953.54  5166.6  954.66  5284.8  960.05  5323.8  959.67
#Mann=5,-1,0
  4605.3    0.05       0  5016.7   0.033       0  5020.7    0.05       0
  5149.9    0.12       0  5166.6    0.05       0
Bank Sta=5016.7,5020.7
Exp/Cntr=0.3,0.1

Type RM Length L Ch R = 1,851,331,331,331
BEGIN DESCRIPTION:
MDW T 068 2.0
END DESCRIPTION:
XS GIS Cut Line= 3
      2253030.39      7139310.23      2253329.09      7139428.88
      2253554.38      7139461.22
#Sta/Elev= 30
  4678.6  957.45  4806.2  951.44  4854.3  950.52  4884.0  951.30  4903.0  949.72
  4908.3  950.20  4924.6  945.53  4932.6  940.83  4938.0  943.42  4946.1  936.77
  4962.3  930.52  4967.7  931.71  4978.4  928.59  4985.3  925.10  4986.6  924.44
  4992.0  925.59  4995.3  922.23  4995.5  921.73  4999.3  922.23  5002.5  922.23
  5010.0  930.66  5020.1  934.05  5039.2  948.08  5044.2  949.34  5114.8  953.27
  5180.3  958.30  5185.3  957.87  5191.9  959.30  5212.1  960.30  5227.6  962.37
#Mann=4,-1,0
  4678.6    0.05       0  4985.3    0.12       0  4995.3    0.07       0
  4999.3    0.12       0
Bank Sta=4995.3,4999.3
Exp/Cntr=0.3,0.1

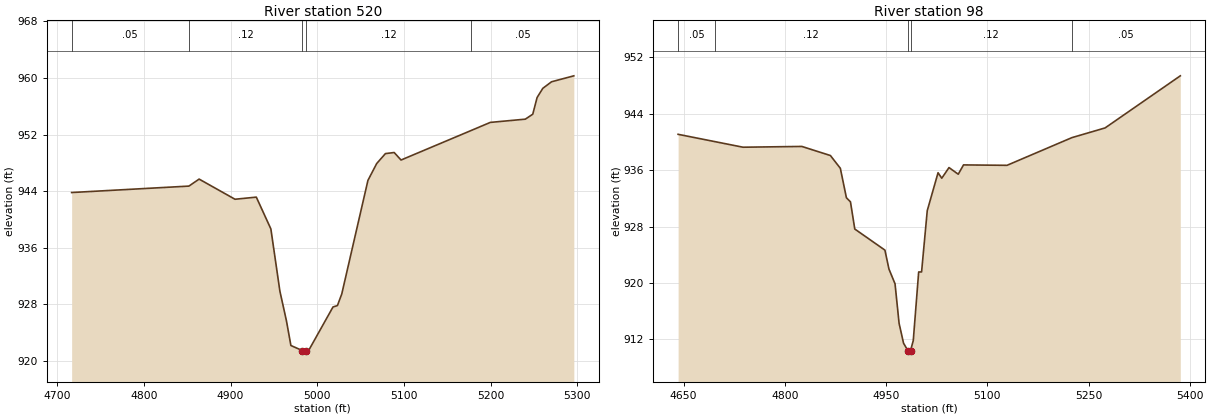
Type RM Length L Ch R = 1,520,422,422,422
BEGIN DESCRIPTION:
MDW T 068 1.0
END DESCRIPTION:
XS GIS Cut Line= 3
      2253226.99      7139760.03      2253488.12      7139689.76
      2253794.53      7139649.24
#Sta/Elev= 30
  4716.6  943.80  4851.9  944.71  4863.7  945.70  4905.1  942.85  4929.7  943.15
  4946.5  938.65  4956.9  929.85  4964.5  925.63  4969.6  922.16  4982.9  921.44
  4983.1  920.94  4986.6  920.94  4986.9  921.44  4990.0  921.44  5018.2  927.61
  5023.3  927.81  5028.3  929.45  5058.5  945.52  5068.6  947.90  5078.7  949.31
  5088.8  949.46  5096.7  948.40  5177.3  952.56  5199.7  953.72  5240.1  954.18
  5248.7  954.88  5253.7  957.24  5260.3  958.54  5270.4  959.47  5296.1  960.31
#Mann=5,-1,0
  4716.6    0.05       0  4851.9    0.12       0  4982.9    0.07       0
  4986.9    0.12       0  5177.3    0.05       0
Bank Sta=4982.9,4986.9
Exp/Cntr=0.3,0.1

Type RM Length L Ch R = 1,98,0,0,0
BEGIN DESCRIPTION:
MDW T 068 0.5
END DESCRIPTION:
XS GIS Cut Line= 3
      2253281.73      7139863.11      2253581.17      7140063.84
      2253938.15      7139924.79
#Sta/Elev= 30
  4642.0  941.09  4696.1  940.06  4738.1  939.26  4825.2  939.37  4867.5  938.08
  4882.2  936.27  4891.2  932.09  4897.2  931.51  4903.6  927.65  4948.2  924.66
  4954.2  921.97  4963.2  919.88  4969.2  914.27  4975.8  911.45  4982.2  910.40
  4982.5  909.90  4986.2  910.40  4990.2  911.83  4998.2  921.56  5002.5  921.56
  5010.9  930.26  5026.9  935.64  5032.4  934.86  5043.1  936.37  5056.8  935.43
  5064.6  936.75  5129.0  936.69  5225.1  940.62  5274.3  942.00  5385.6  949.39
#Mann=5,-1,0
  4642.0    0.05       0  4696.1    0.12       0  4982.2    0.07       0
  4986.2    0.12       0  5225.1    0.05       0
Bank Sta=4982.2,4986.2
Exp/Cntr=0.3,0.1

Chan Stop Cuts=-1