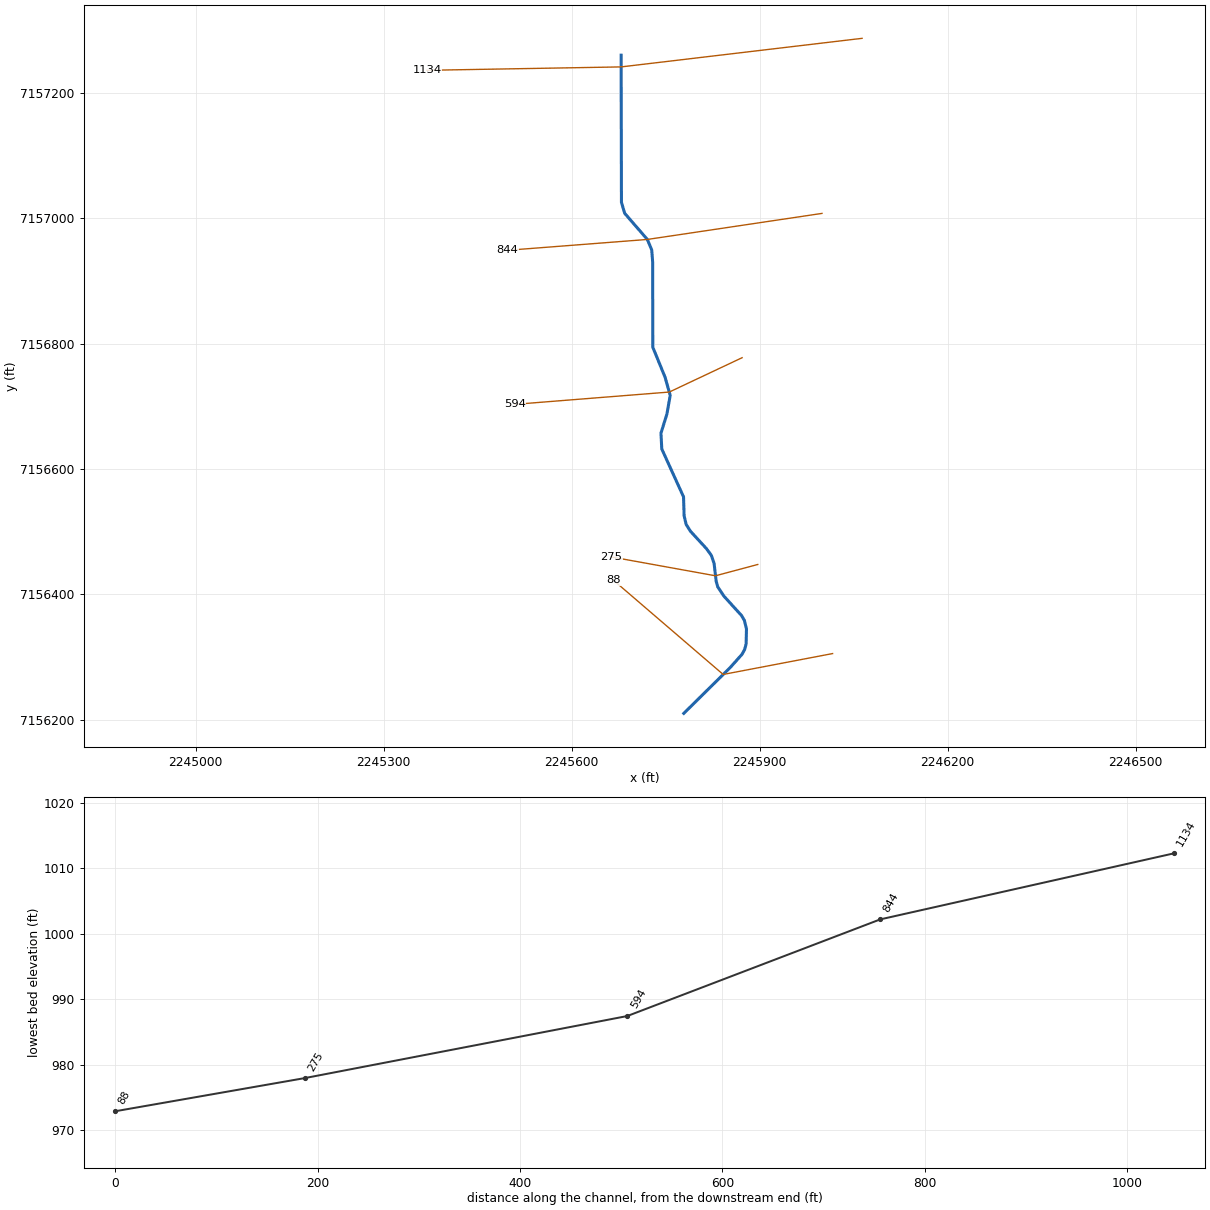
--- MDW T 070.prj (project) ---

Proj Title=MDW T 070 Base Level Engineering
Current Plan=p01
Default Exp/Contr=0.3,0.1
English Units
Geom File=g01
Flow File=f01
Plan File=p01
BEGIN DESCRIPTION:
MDW T 070
END DESCRIPTION:

--- MDW T 070.p01 (plan) ---

Plan Title=Multiple Run
Short Identifier=Multiple
Geom File=g01
Flow File=f01
Subcritical Flow
K Sum by GR= 0
Std Step Tol= 0.01
Critical Tol= 0.01
Num of Std Step Trials= 20
Max Error Tol= 0.3
Flow Tol Ratio= 0.001
Split Flow NTrial= 30
Split Flow Tol= 0.02
Split Flow Ratio= 0.02
Log Output Level= 0
Friction Slope Method= 1
Unsteady Friction Slope Method= 2
Unsteady Bridges Friction Slope Method= 1
Parabolic Critical Depth
Global Vel Dist=  1 , 1 , 1
Global Log Level= 0
CheckData=True
Encroach Param= -1, 0, 0, 0
BEGIN DESCRIPTION:
Multiple Run
END DESCRIPTION:

--- MDW T 070.f01 (steady flow) ---

Flow Title=Multiple
Number of Profiles=7
Profile Names=10-year,25-year,50-year,1pct_min,100-year,1pct_plu,500-year
River Rch & RM= MDW T 070,Reach-1,1134
     272     357     425     252     503    1003     704
Boundary for River Rch & Prof#=MDW T 070,Reach-1,1
Up Type=0
Dn Type=3
Dn Slope=0.005
Boundary for River Rch & Prof#=MDW T 070,Reach-1,2
Up Type=0
Dn Type=3
Dn Slope=0.005
Boundary for River Rch & Prof#=MDW T 070,Reach-1,3
Up Type=0
Dn Type=3
Dn Slope=0.005
Boundary for River Rch & Prof#=MDW T 070,Reach-1,4
Up Type=0
Dn Type=3
Dn Slope=0.005
Boundary for River Rch & Prof#=MDW T 070,Reach-1,5
Up Type=0
Dn Type=3
Dn Slope=0.005
Boundary for River Rch & Prof#=MDW T 070,Reach-1,6
Up Type=0
Dn Type=3
Dn Slope=0.005
Boundary for River Rch & Prof#=MDW T 070,Reach-1,7
Up Type=0
Dn Type=3
Dn Slope=0.005

--- MDW T 070.g01 (geometry) ---

Geom Title=Existing Conditions

River Reach=MDW T 070,Reach-1
Reach XY= 30
      2245679.00      7157260.00      2245679.52      7157025.22
      2245684.75      7157007.67      2245720.85      7156966.05
      2245727.77      7156949.49      2245729.32      7156930.13
      2245729.55      7156794.15      2245749.08      7156746.41
      2245757.33      7156717.33      2245752.12      7156687.81
      2245742.57      7156657.00      2245743.87      7156631.83
      2245778.58      7156555.45      2245779.51      7156525.21
      2245782.75      7156511.55      2245789.80      7156500.33
      2245814.96      7156473.04      2245822.89      7156462.18
      2245827.34      7156449.31      2245830.69      7156420.68
      2245833.22      7156411.72      2245843.11      7156396.93
      2245871.25      7156365.93      2245875.69      7156358.27
      2245879.00      7156344.59      2245878.45      7156320.62
      2245875.95      7156311.62      2245871.62      7156303.92
      2245853.09      7156283.14      2245779.00      7156210.00

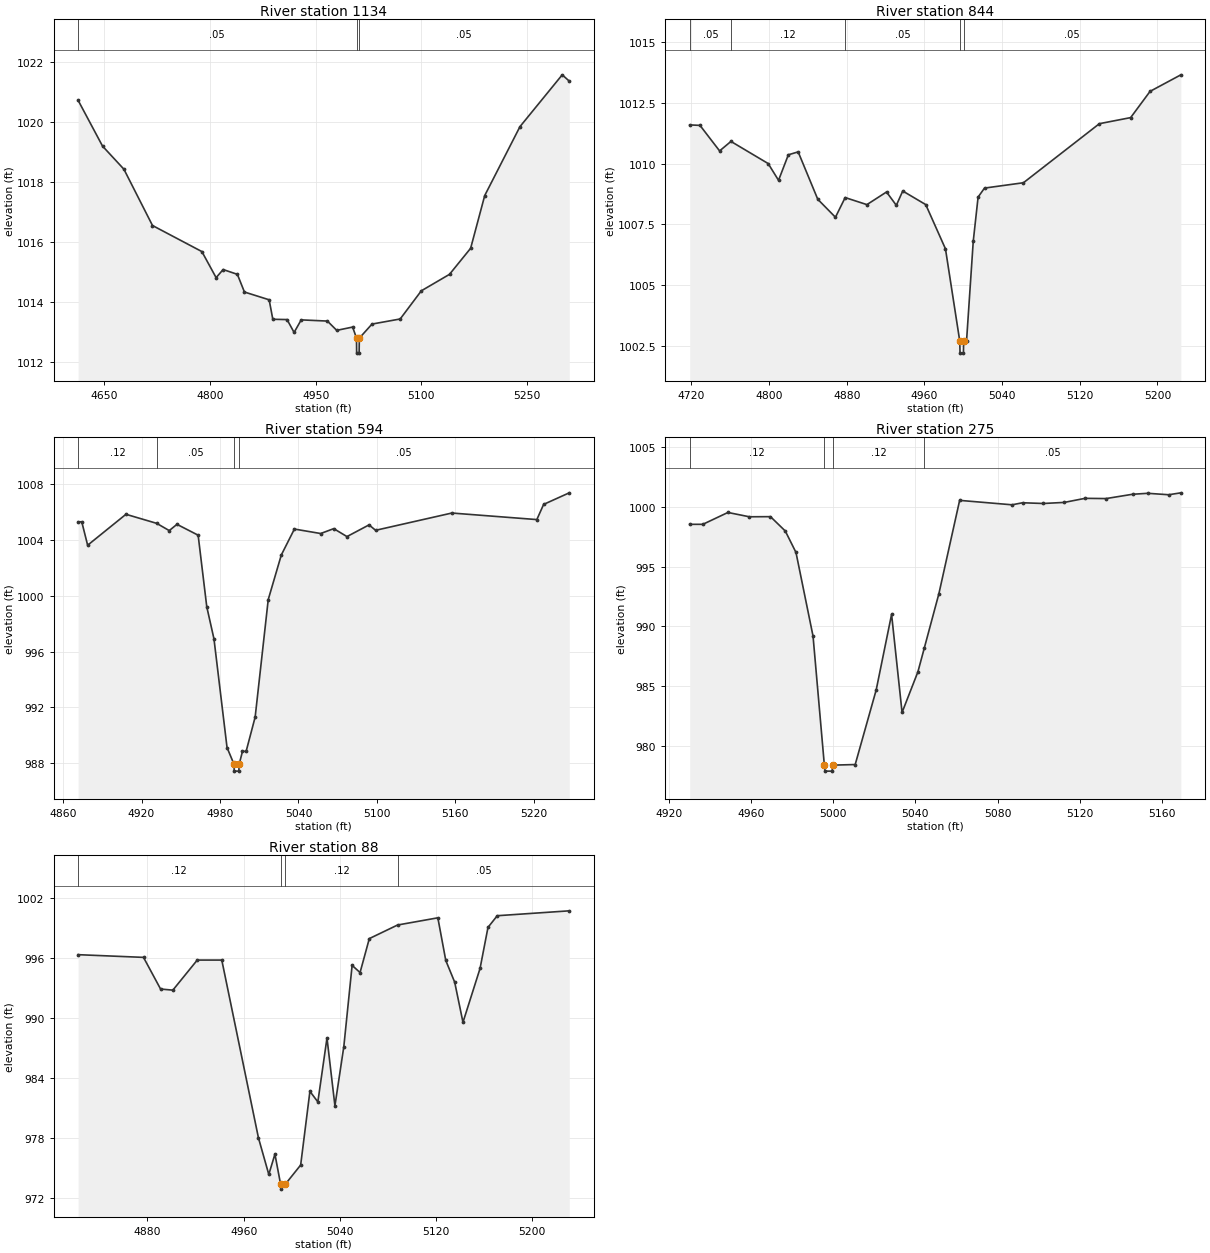
Type RM Length L Ch R = 1,1134,290,290,290
BEGIN DESCRIPTION:
MDW T 070 4.0
END DESCRIPTION:
XS GIS Cut Line= 3
      2246063.50      7157286.89      2245678.99      7157241.31
      2245369.04      7157235.89
#Sta/Elev= 30
  4612.8 1020.73  4647.5 1019.20  4677.8 1018.43  4718.4 1016.55  4788.5 1015.68
  4808.7 1014.81  4818.7 1015.08  4838.9 1014.92  4848.9 1014.33  4884.0 1014.07
  4889.2 1013.42  4909.4 1013.41  4919.4 1012.98  4929.5 1013.40  4966.7 1013.36
  4979.9 1013.05  5002.5 1013.16  5008.0 1012.79  5008.2 1012.29  5011.7 1012.29
  5012.0 1012.79  5030.0 1013.26  5070.0 1013.43  5100.0 1014.37  5140.0 1014.92
  5170.0 1015.79  5190.0 1017.55  5240.0 1019.85  5300.0 1021.58  5310.0 1021.37
#Mann=3,-1,0
  4612.8    0.05       0  5008.0   0.033       0  5012.0    0.05       0
Bank Sta=5008,5012
Exp/Cntr=0.3,0.1

Type RM Length L Ch R = 1,844,250,250,250
BEGIN DESCRIPTION:
MDW T 070 3.0
END DESCRIPTION:
XS GIS Cut Line= 3
      2245999.47      7157007.59      2245720.85      7156966.05
      2245497.42      7156948.74
#Sta/Elev= 30
  4718.3 1011.59  4728.9 1011.57  4749.1 1010.52  4760.8 1010.91  4799.1 1010.00
  4809.8 1009.31  4819.9 1010.36  4830.0 1010.48  4850.2 1008.53  4868.4 1007.79
  4878.4 1008.60  4900.8 1008.31  4921.0 1008.83  4931.1 1008.28  4937.7 1008.87
  4961.4 1008.31  4981.7 1006.49  4996.4 1002.70  4996.7 1002.20  5000.2 1002.20
  5000.4 1002.70  5003.4 1002.70  5010.3 1006.80  5015.3 1008.62  5021.9 1008.99
  5062.0 1009.21  5140.2 1011.64  5172.4 1011.89  5192.4 1012.97  5224.1 1013.65
#Mann=5,-1,0
  4718.3    0.05       0  4760.8    0.12       0  4878.4    0.05       0
  4996.4   0.033       0  5000.4    0.05       0
Bank Sta=4996.4,5000.4
Exp/Cntr=0.3,0.1

Type RM Length L Ch R = 1,594,319,319,319
BEGIN DESCRIPTION:
MDW T 070 2.0
END DESCRIPTION:
XS GIS Cut Line= 3
      2245872.06      7156777.40      2245755.83      7156722.61
      2245509.51      7156703.01
#Sta/Elev= 30
  4871.5 1005.31  4874.3 1005.31  4878.8 1003.63  4908.1 1005.85  4931.6 1005.20
  4941.2 1004.68  4947.1 1005.13  4963.3 1004.35  4969.9  999.21  4975.4  996.91
  4985.4  989.11  4990.7  987.92  4990.9  987.42  4994.4  987.42  4994.7  987.92
  4997.2  988.84  5000.0  988.84  5006.9  991.30  5016.9  999.73  5026.9 1002.93
  5036.9 1004.79  5057.0 1004.47  5067.0 1004.82  5077.1 1004.25  5094.0 1005.09
  5099.0 1004.70  5157.3 1005.94  5222.3 1005.47  5227.5 1006.56  5247.1 1007.39
#Mann=4,-1,0
  4871.5    0.12       0  4931.6    0.05       0  4990.7   0.033       0
  4994.7    0.05       0
Bank Sta=4990.7,4994.7
Exp/Cntr=0.3,0.1

Type RM Length L Ch R = 1,275,187,187,187
BEGIN DESCRIPTION:
MDW T 070 1.0
END DESCRIPTION:
XS GIS Cut Line= 3
      2245896.99      7156447.53      2245829.56      7156429.50
      2245663.16      7156459.61
#Sta/Elev= 30
  4930.2  998.53  4936.6  998.53  4948.8  999.52  4959.2  999.16  4969.5  999.17
  4976.7  997.97  4981.9  996.18  4990.2  989.19  4995.7  978.42  4996.0  977.92
  4999.5  977.92  4999.7  978.42  5010.7  978.47  5020.9  984.69  5028.4  991.01
  5033.5  982.82  5041.2  986.21  5044.3  988.19  5051.4  992.73  5061.5 1000.53
  5087.0 1000.16  5092.1 1000.33  5102.2 1000.27  5112.4 1000.36  5122.5 1000.70
  5132.7 1000.68  5145.6 1001.04  5153.0 1001.12  5163.2 1001.00  5169.1 1001.16
#Mann=4,-1,0
  4930.2    0.12       0  4995.7    0.07       0  4999.7    0.12       0
  5044.3    0.05       0
Bank Sta=4995.7,4999.7
Exp/Cntr=0.3,0.1

Type RM Length L Ch R = 1,88,0,0,0
BEGIN DESCRIPTION:
MDW T 070 0.5
END DESCRIPTION:
XS GIS Cut Line= 3
      2246016.38      7156305.40      2245841.83      7156272.09
      2245666.72      7156422.44
#Sta/Elev= 30
  4822.3  996.33  4876.7  996.06  4890.9  992.89  4901.1  992.78  4921.4  995.79
  4941.8  995.79  4972.3  977.99  4980.9  974.33  4986.0  976.36  4990.7  973.36
  4991.0  972.86  4994.7  973.36  5007.4  975.27  5015.1  982.65  5021.7  981.59
  5029.3  987.99  5035.9  981.20  5043.3  987.13  5050.2  995.26  5056.8  994.54
  5064.5  997.94  5088.0  999.30  5121.5 1000.02  5128.1  995.75  5135.5  993.58
  5142.4  989.56  5156.6  994.95  5163.2  999.06  5170.9 1000.23  5230.8 1000.72
#Mann=4,-1,0
  4822.3    0.12       0  4990.7    0.07       0  4994.7    0.12       0
  5088.0    0.05       0
Bank Sta=4990.7,4994.7
Exp/Cntr=0.3,0.1

Chan Stop Cuts=-1