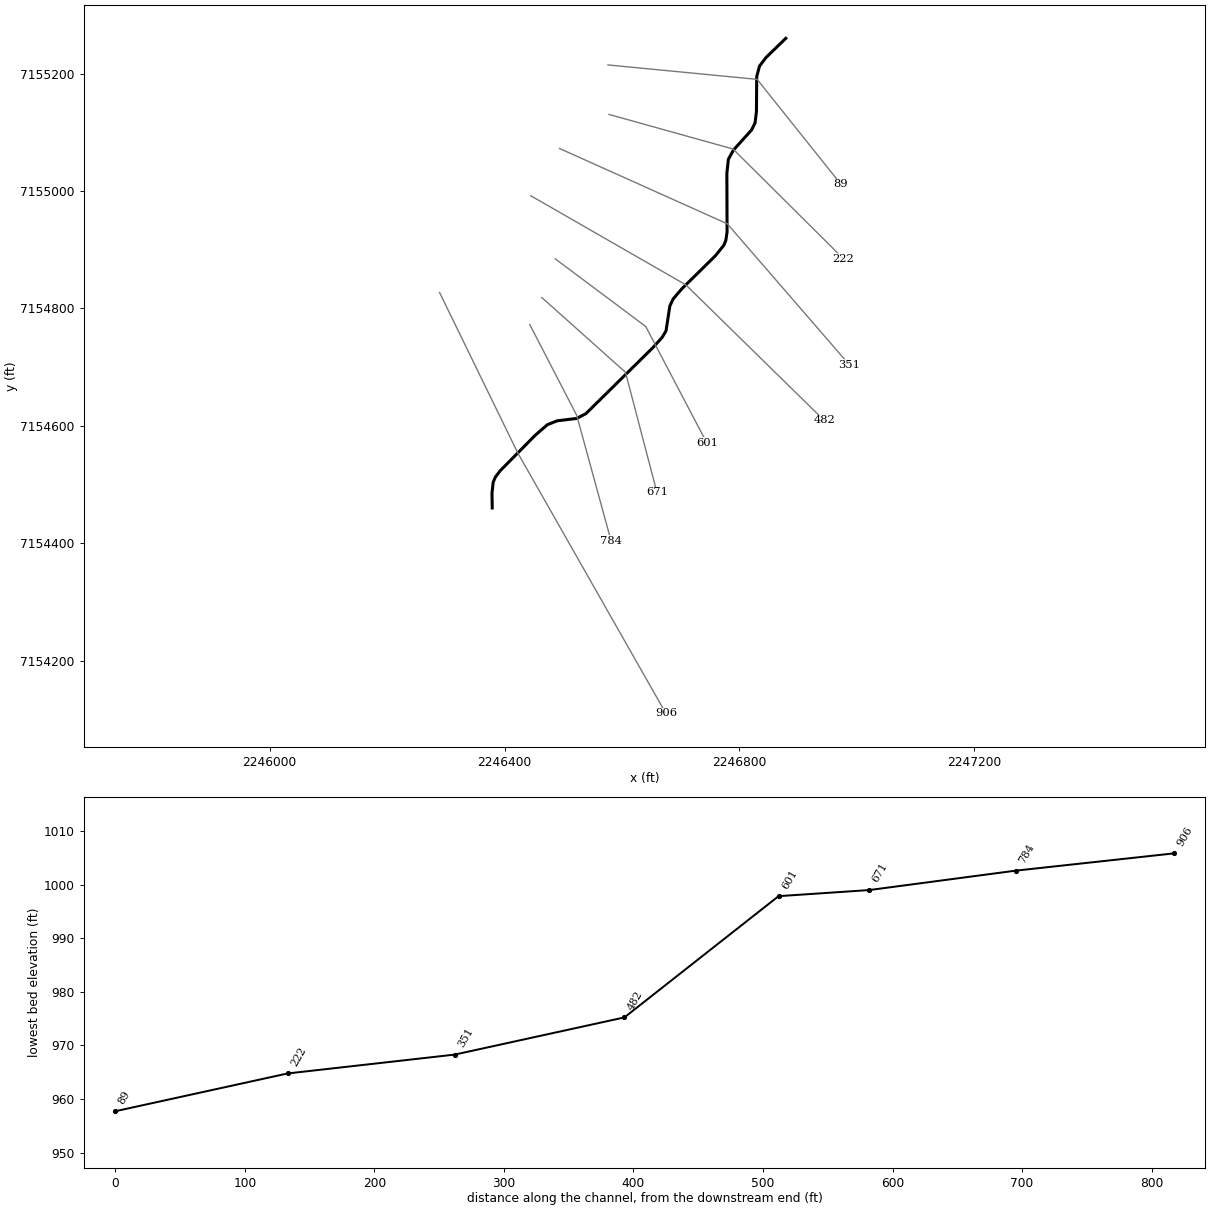
--- MDW T 071.prj (project) ---

Proj Title=MDW T 071 Base Level Engineering
Current Plan=p01
Default Exp/Contr=0.3,0.1
English Units
Geom File=g01
Flow File=f01
Plan File=p01
BEGIN DESCRIPTION:
MDW T 071
END DESCRIPTION:

--- MDW T 071.p01 (plan) ---

Plan Title=Multiple Run
Short Identifier=Multiple
Geom File=g01
Flow File=f01
Subcritical Flow
K Sum by GR= 0
Std Step Tol= 0.01
Critical Tol= 0.01
Num of Std Step Trials= 20
Max Error Tol= 0.3
Flow Tol Ratio= 0.001
Split Flow NTrial= 30
Split Flow Tol= 0.02
Split Flow Ratio= 0.02
Log Output Level= 0
Friction Slope Method= 1
Unsteady Friction Slope Method= 2
Unsteady Bridges Friction Slope Method= 1
Parabolic Critical Depth
Global Vel Dist=  1 , 1 , 1
Global Log Level= 0
CheckData=True
Encroach Param= -1, 0, 0, 0
BEGIN DESCRIPTION:
Multiple Run
END DESCRIPTION:

--- MDW T 071.f01 (steady flow) ---

Flow Title=Multiple
Number of Profiles=7
Profile Names=10-year,25-year,50-year,1pct_min,100-year,1pct_plu,500-year
River Rch & RM= MDW T 071,Reach-1,906
     170     217     254     148     296     591     402
Boundary for River Rch & Prof#=MDW T 071,Reach-1,1
Up Type=0
Dn Type=3
Dn Slope=0.005
Boundary for River Rch & Prof#=MDW T 071,Reach-1,2
Up Type=0
Dn Type=3
Dn Slope=0.005
Boundary for River Rch & Prof#=MDW T 071,Reach-1,3
Up Type=0
Dn Type=3
Dn Slope=0.005
Boundary for River Rch & Prof#=MDW T 071,Reach-1,4
Up Type=0
Dn Type=3
Dn Slope=0.005
Boundary for River Rch & Prof#=MDW T 071,Reach-1,5
Up Type=0
Dn Type=3
Dn Slope=0.005
Boundary for River Rch & Prof#=MDW T 071,Reach-1,6
Up Type=0
Dn Type=3
Dn Slope=0.005
Boundary for River Rch & Prof#=MDW T 071,Reach-1,7
Up Type=0
Dn Type=3
Dn Slope=0.005

--- MDW T 071.g01 (geometry) ---

Geom Title=Existing Conditions

River Reach=MDW T 071,Reach-1
Reach XY= 30
      2246379.00      7154460.00      2246378.59      7154485.37
      2246380.67      7154503.87      2246384.30      7154512.54
      2246392.46      7154523.31      2246452.13      7154583.74
      2246472.93      7154601.86      2246489.64      7154608.46
      2246522.95      7154612.53      2246538.68      7154620.78
      2246652.70      7154733.18      2246668.22      7154750.32
      2246675.03      7154761.65      2246681.54      7154803.95
      2246687.18      7154816.04      2246702.07      7154833.44
      2246759.35      7154889.85      2246773.52      7154907.56
      2246776.93      7154915.86      2246779.02      7154929.99
      2246778.68      7155030.13      2246781.27      7155054.06
      2246789.85      7155069.65      2246820.82      7155103.96
      2246826.68      7155115.96      2246829.06      7155134.97
      2246829.53      7155194.78      2246834.22      7155212.55
      2246845.12      7155227.05      2246879.00      7155260.00

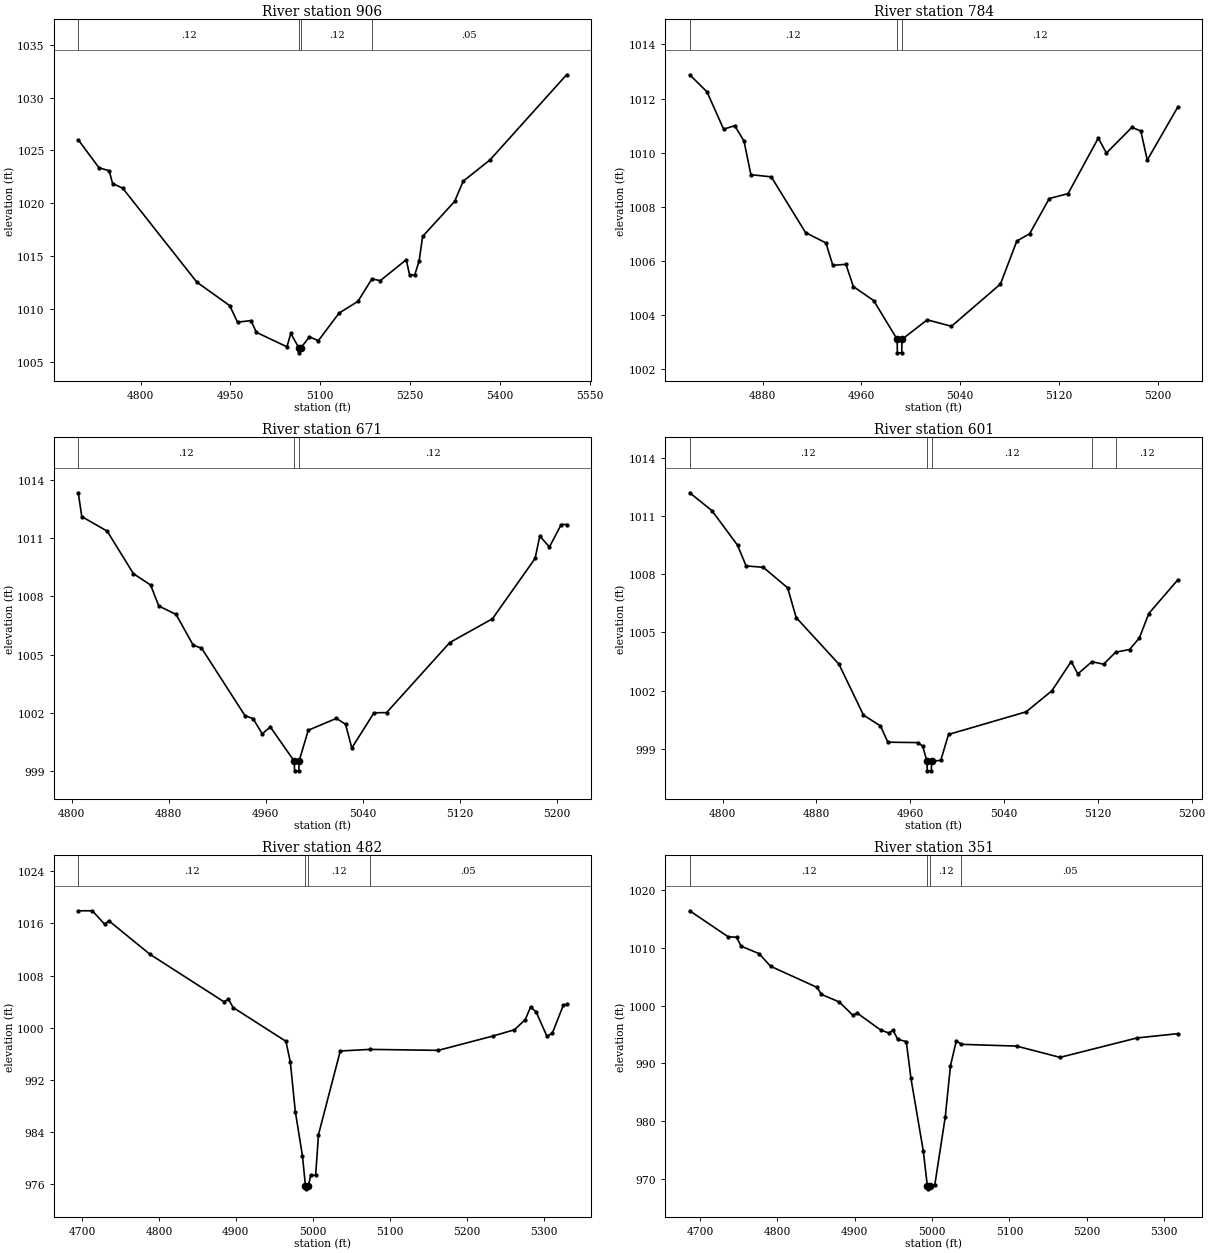
Type RM Length L Ch R = 1,906,122,122,122
BEGIN DESCRIPTION:
MDW T 071 3.0
END DESCRIPTION:
XS GIS Cut Line= 3
      2246289.27      7154827.05      2246422.39      7154553.97
      2246674.77      7154110.10
#Sta/Elev= 30
  4696.2 1026.01  4730.8 1023.36  4747.8 1023.08  4753.4 1021.87  4770.3 1021.43
  4894.1 1012.52  4948.8 1010.30  4961.8 1008.74  4984.3 1008.88  4993.3 1007.77
  5044.3 1006.40  5050.6 1007.67  5063.9 1006.33  5064.1 1005.83  5067.9 1006.33
  5081.8 1007.35  5096.6 1006.98  5131.1 1009.59  5162.5 1010.70  5186.0 1012.83
  5200.0 1012.67  5243.2 1014.65  5249.0 1013.16  5257.6 1013.24  5264.8 1014.57
  5270.6 1016.86  5323.9 1020.17  5338.2 1022.09  5383.0 1024.11  5510.6 1032.17
#Mann=4,-1,0
  4696.2    0.12       0  5063.9    0.07       0  5067.9    0.12       0
  5186.0    0.05       0
Bank Sta=5063.9,5067.9
Exp/Cntr=0.3,0.1

Type RM Length L Ch R = 1,784,113,113,113
BEGIN DESCRIPTION:
Mapping XS ed40029d
END DESCRIPTION:
XS GIS Cut Line= 3
      2246442.96      7154772.43      2246522.94      7154617.72
      2246581.42      7154404.04
#Sta/Elev= 30
  4820.9 1012.88  4834.9 1012.25  4848.4 1010.87  4857.4 1011.00  4864.9 1010.43
  4870.5 1009.19  4887.0 1009.11  4914.8 1007.05  4931.3 1006.67  4936.9 1005.84
  4947.5 1005.88  4953.5 1005.06  4970.0 1004.54  4989.0 1003.11  4989.2 1002.61
  4992.7 1002.61  4993.0 1003.11  5013.4 1003.83  5033.0 1003.59  5072.7 1005.15
  5086.0 1006.74  5096.4 1007.01  5112.3 1008.31  5127.5 1008.49  5152.0 1010.54
  5158.6 1009.99  5179.3 1010.94  5186.5 1010.80  5191.7 1009.73  5216.6 1011.70
#Mann=3,-1,0
  4820.9    0.12       0  4989.0    0.07       0  4993.0    0.12       0
Bank Sta=4989,4993
Exp/Cntr=0.3,0.1

Type RM Length L Ch R = 1,671,70,70,70
BEGIN DESCRIPTION:
Mapping XS 90fd08ad
END DESCRIPTION:
XS GIS Cut Line= 3
      2246463.50      7154818.42      2246605.97      7154691.16
      2246659.61      7154486.40
#Sta/Elev= 30
  4805.4 1013.36  4808.3 1012.13  4829.2 1011.38  4850.9 1009.18  4865.1 1008.59
  4871.8 1007.51  4886.1 1007.07  4900.3 1005.47  4907.0 1005.34  4942.9 1001.84
  4949.6 1001.69  4957.1 1000.90  4963.8 1001.26  4983.5  999.49  4983.8  998.99
  4987.3  998.99  4987.5  999.49  4995.1 1001.09  5018.3 1001.70  5025.8 1001.40
  5031.0 1000.17  5049.3 1001.99  5059.7 1002.00  5111.8 1005.62  5147.0 1006.85
  5182.2 1009.97  5186.0 1011.12  5194.0 1010.56  5203.7 1011.72  5208.1 1011.72
#Mann=3,-1,0
  4805.4    0.12       0  4983.5    0.07       0  4987.5    0.12       0
Bank Sta=4983.5,4987.5
Exp/Cntr=0.3,0.1

Type RM Length L Ch R = 1,601,119,119,119
BEGIN DESCRIPTION:
Mapping XS 932cd841
END DESCRIPTION:
XS GIS Cut Line= 3
      2246486.29      7154884.42      2246640.43      7154769.17
      2246744.51      7154570.89
#Sta/Elev= 30
  4771.9 1012.22  4790.8 1011.30  4812.7 1009.51  4820.0 1008.44  4834.6 1008.37
  4855.4 1007.31  4862.7 1005.77  4899.2 1003.36  4920.1 1000.73  4934.6 1000.17
  4940.9  999.33  4966.7  999.31  4970.6  999.12  4974.2  998.35  4974.5  997.85
  4978.0  997.85  4978.2  998.35  4986.0  998.39  4992.6  999.73  5058.8 1000.90
  5080.8 1001.99  5097.2 1003.50  5102.9 1002.86  5114.9 1003.49  5124.9 1003.36
  5135.1 1003.98  5147.0 1004.12  5155.4 1004.72  5163.4 1005.98  5188.3 1007.73
#Mann=5,-1,0
  4771.9    0.12       0  4974.2    0.07       0  4978.2    0.12       0
  5114.9    0.05       0  5135.1    0.12       0
Bank Sta=4974.2,4978.2
Exp/Cntr=0.3,0.1

Type RM Length L Ch R = 1,482,131,131,131
BEGIN DESCRIPTION:
MDW T 071 2.0
END DESCRIPTION:
XS GIS Cut Line= 3
      2246444.43      7154992.00      2246708.70      7154840.13
      2246944.28      7154609.33
#Sta/Elev= 30
  4695.2 1017.95  4713.5 1017.95  4729.3 1015.91  4735.1 1016.40  4788.3 1011.27
  4884.6 1003.96  4890.3 1004.36  4896.5 1003.08  4965.1  997.89  4970.8  994.70
  4977.3  987.08  4986.6  980.26  4990.4  975.72  4990.6  975.22  4994.4  975.72
  4997.3  977.30  5003.7  977.30  5007.4  983.55  5035.7  996.40  5074.0  996.65
  5163.0  996.50  5233.7  998.69  5262.0  999.66  5276.1 1001.22  5283.1 1003.17
  5290.3 1002.40  5304.4  998.64  5311.4  999.16  5325.5 1003.40  5329.8 1003.61
#Mann=4,-1,0
  4695.2    0.12       0  4990.4    0.07       0  4994.4    0.12       0
  5074.0    0.05       0
Bank Sta=4990.4,4994.4
Exp/Cntr=0.3,0.1

Type RM Length L Ch R = 1,351,129,129,129
BEGIN DESCRIPTION:
MDW T 071 1.5
END DESCRIPTION:
XS GIS Cut Line= 3
      2246493.69      7155072.34      2246779.42      7154944.07
      2246987.41      7154703.79
#Sta/Elev= 30
  4686.8 1016.44  4736.5 1011.94  4747.4 1011.86  4753.2 1010.31  4776.4 1009.02
  4791.3 1006.83  4851.4 1003.17  4857.0 1001.96  4880.0 1000.65  4897.7  998.34
  4903.2  998.72  4933.8  995.77  4944.1  995.28  4949.6  995.75  4955.7  994.16
  4966.7  993.79  4972.7  987.42  4988.6  974.89  4993.9  968.78  4994.2  968.28
  4997.9  968.78  5003.5  968.93  5017.1  980.78  5023.8  989.63  5031.4  993.94
  5037.9  993.31  5109.3  993.00  5165.3  991.05  5265.0  994.42  5317.8  995.16
#Mann=4,-1,0
  4686.8    0.12       0  4993.9    0.07       0  4997.9    0.12       0
  5037.9    0.05       0
Bank Sta=4993.9,4997.9
Exp/Cntr=0.3,0.1

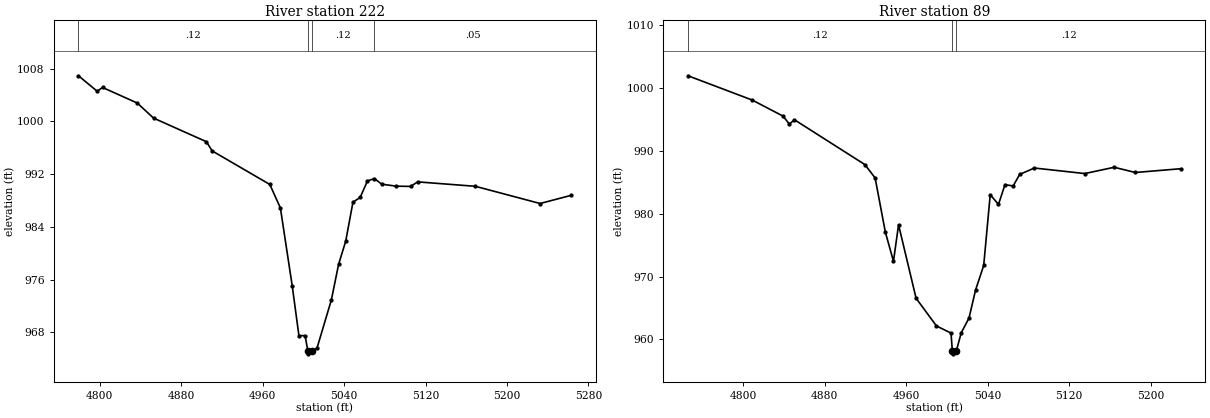
Type RM Length L Ch R = 1,222,133,133,133
BEGIN DESCRIPTION:
Mapping XS d990c358
END DESCRIPTION:
XS GIS Cut Line= 3
      2246577.93      7155130.38      2246789.13      7155071.49
      2246977.08      7154884.76
#Sta/Elev= 30
  4779.0 1006.93  4797.4 1004.58  4802.6 1005.16  4836.7 1002.80  4852.8 1000.51
  4904.7  996.93  4910.3  995.54  4967.0  990.45  4977.4  986.89  4989.1  974.99
  4995.6  967.52  5001.7  967.52  5004.3  965.26  5004.5  964.76  5008.3  965.26
  5013.3  965.59  5027.5  972.94  5034.6  978.34  5041.6  981.85  5048.7  987.76
  5055.8  988.48  5062.9  990.97  5069.7  991.35  5077.0  990.49  5091.1  990.19
  5105.3  990.15  5112.3  990.84  5168.9  990.17  5232.6  987.56  5263.2  988.80
#Mann=4,-1,0
  4779.0    0.12       0  5004.3    0.07       0  5008.3    0.12       0
  5069.7    0.05       0
Bank Sta=5004.3,5008.3
Exp/Cntr=0.3,0.1

Type RM Length L Ch R = 1,89,0,0,0
BEGIN DESCRIPTION:
MDW T 071 1.0
END DESCRIPTION:
XS GIS Cut Line= 3
      2246576.19      7155214.69      2246830.18      7155190.14
      2246972.89      7155011.53
#Sta/Elev= 30
  4745.8 1001.96  4808.9  998.09  4839.0  995.55  4845.3  994.27  4850.3  994.96
  4919.4  987.83  4929.5  985.70  4939.5  977.11  4947.5  972.44  4952.5  978.24
  4969.7  966.56  4989.7  962.15  5004.0  961.01  5005.3  958.21  5005.6  957.71
  5009.3  958.21  5014.0  961.04  5021.7  963.42  5028.1  967.86  5036.1  971.77
  5042.5  983.04  5050.6  981.49  5057.0  984.64  5065.0  984.42  5071.4  986.26
  5085.8  987.28  5135.4  986.40  5164.2  987.40  5185.0  986.57  5229.6  987.17
#Mann=3,-1,0
  4745.8    0.12       0  5005.3    0.07       0  5009.3    0.12       0
Bank Sta=5005.3,5009.3
Exp/Cntr=0.3,0.1

Chan Stop Cuts=-1