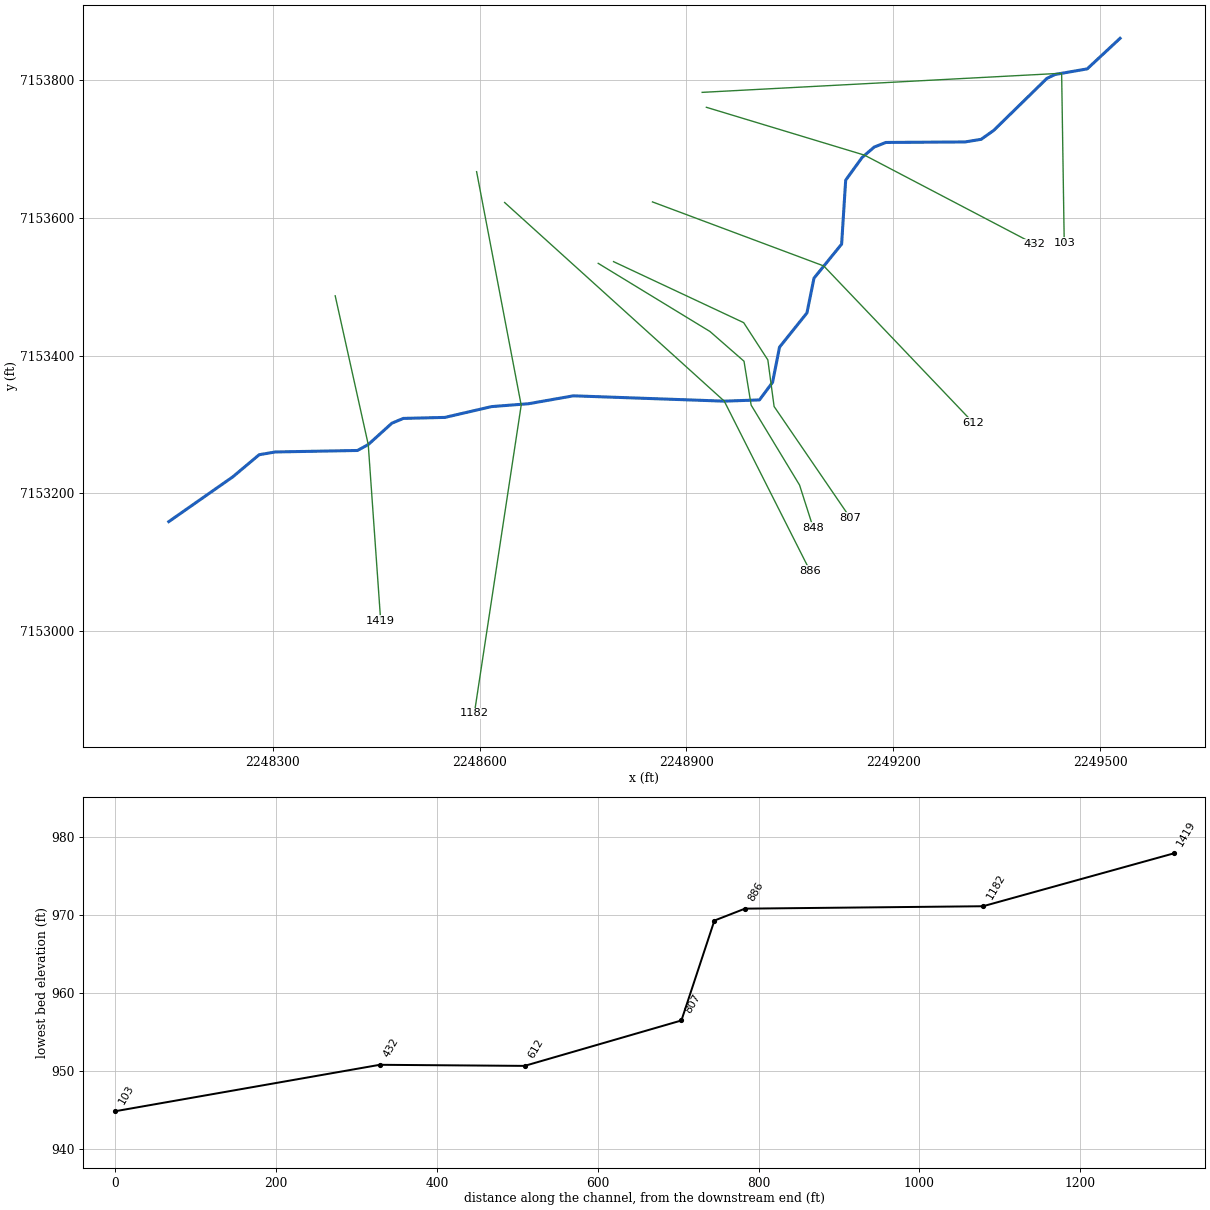
--- MDW T 072.prj (project) ---

Proj Title=MDW T 072 Base Level Engineering
Current Plan=p01
Default Exp/Contr=0.3,0.1
English Units
Geom File=g01
Flow File=f01
Plan File=p01
BEGIN DESCRIPTION:
MDW T 072
END DESCRIPTION:

--- MDW T 072.p01 (plan) ---

Plan Title=Multiple Run
Short Identifier=Multiple
Geom File=g01
Flow File=f01
Subcritical Flow
K Sum by GR= 0
Std Step Tol= 0.01
Critical Tol= 0.01
Num of Std Step Trials= 20
Max Error Tol= 0.3
Flow Tol Ratio= 0.001
Split Flow NTrial= 30
Split Flow Tol= 0.02
Split Flow Ratio= 0.02
Log Output Level= 0
Friction Slope Method= 1
Unsteady Friction Slope Method= 2
Unsteady Bridges Friction Slope Method= 1
Parabolic Critical Depth
Global Vel Dist=  1 , 1 , 1
Global Log Level= 0
CheckData=True
Encroach Param= -1, 0, 0, 0
BEGIN DESCRIPTION:
Multiple Run
END DESCRIPTION:

--- MDW T 072.f01 (steady flow) ---

Flow Title=Multiple
Number of Profiles=7
Profile Names=10-year,25-year,50-year,1pct_min,100-year,1pct_plu,500-year
River Rch & RM= MDW T 072,Reach-1,1419
     235     305     361     213     425     848     590
Boundary for River Rch & Prof#=MDW T 072,Reach-1,1
Up Type=0
Dn Type=3
Dn Slope=0.005
Boundary for River Rch & Prof#=MDW T 072,Reach-1,2
Up Type=0
Dn Type=3
Dn Slope=0.005
Boundary for River Rch & Prof#=MDW T 072,Reach-1,3
Up Type=0
Dn Type=3
Dn Slope=0.005
Boundary for River Rch & Prof#=MDW T 072,Reach-1,4
Up Type=0
Dn Type=3
Dn Slope=0.005
Boundary for River Rch & Prof#=MDW T 072,Reach-1,5
Up Type=0
Dn Type=3
Dn Slope=0.005
Boundary for River Rch & Prof#=MDW T 072,Reach-1,6
Up Type=0
Dn Type=3
Dn Slope=0.005
Boundary for River Rch & Prof#=MDW T 072,Reach-1,7
Up Type=0
Dn Type=3
Dn Slope=0.005

--- MDW T 072.g01 (geometry) ---

Geom Title=Existing Conditions

River Reach=MDW T 072,Reach-1
Reach XY= 30
      2248149.33      7153159.06      2248242.11      7153223.97
      2248280.45      7153256.10      2248303.89      7153260.11
      2248423.06      7153262.27      2248438.64      7153270.86
      2248472.94      7153301.86      2248489.51      7153308.78
      2248549.78      7153310.23      2248617.49      7153325.91
      2248671.13      7153330.08      2248736.24      7153341.54
      2248954.97      7153333.81      2249006.01      7153335.59
      2249025.06      7153361.16      2249035.10      7153412.13
      2249074.84      7153461.72      2249085.12      7153512.18
      2249125.17      7153561.59      2249131.06      7153654.32
      2249154.98      7153687.34      2249172.48      7153702.32
      2249189.27      7153709.01      2249304.11      7153709.73
      2249327.53      7153713.55      2249345.75      7153726.46
      2249422.92      7153801.93      2249434.97      7153807.65
      2249481.35      7153815.70      2249529.00      7153860.00

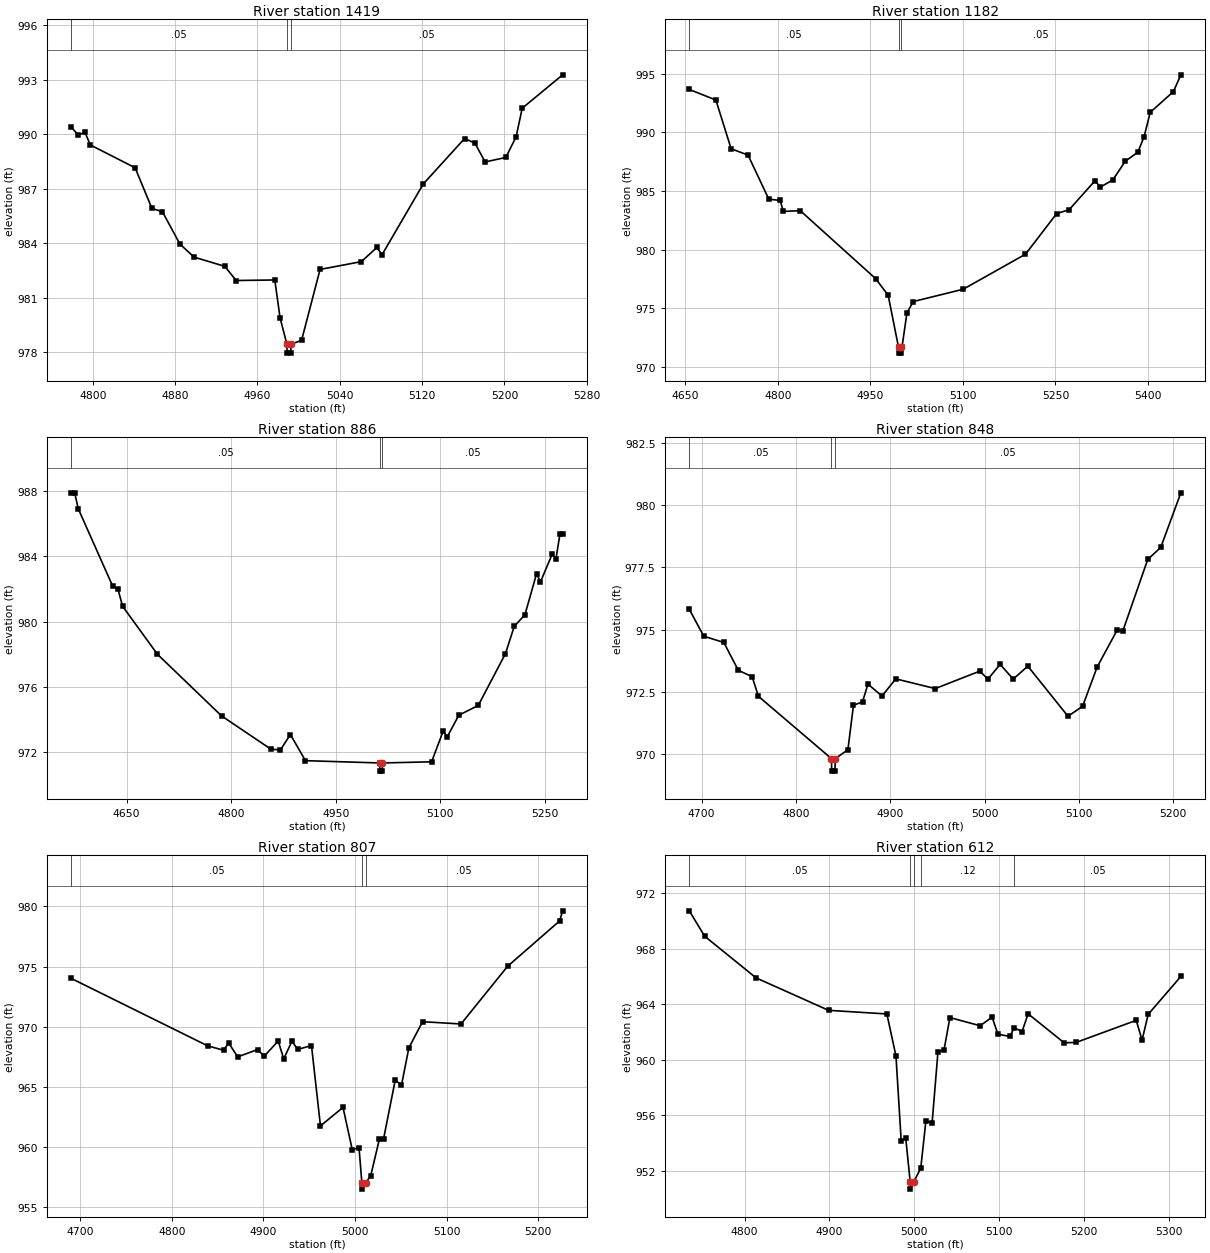
Type RM Length L Ch R = 1,1419,237,237,237
BEGIN DESCRIPTION:
MDW T 072 5.0
END DESCRIPTION:
XS GIS Cut Line= 3
      2248390.71      7153486.60      2248438.64      7153270.86
      2248456.70      7153014.89
#Sta/Elev= 30
  4779.0  990.42  4785.8  989.96  4792.5  990.11  4797.6  989.42  4841.2  988.16
  4857.5  985.92  4867.7  985.74  4884.7  983.96  4898.4  983.24  4928.3  982.73
  4939.4  981.95  4976.9  981.98  4982.0  979.90  4988.6  978.45  4988.9  977.95
  4992.4  977.95  4992.6  978.45  5002.9  978.65  5020.9  982.56  5061.0  982.99
  5076.1  983.77  5081.1  983.37  5121.2  987.27  5161.3  989.77  5171.3  989.52
  5181.3  988.48  5201.4  988.73  5211.4  989.87  5217.3  991.44  5256.6  993.28
#Mann=3,-1,0
  4779.0    0.05       0  4988.6   0.033       0  4992.6    0.05       0
Bank Sta=4988.6,4992.6
Exp/Cntr=0.3,0.1

Type RM Length L Ch R = 1,1182,296,296,296
BEGIN DESCRIPTION:
MDW T 072 4.0
END DESCRIPTION:
XS GIS Cut Line= 3
      2248595.78      7153666.64      2248660.46      7153327.95
      2248592.52      7152880.99
#Sta/Elev= 30
  4656.5  993.67  4699.6  992.77  4724.3  988.61  4751.7  988.07  4785.4  984.31
  4803.8  984.20  4808.9  983.26  4836.3  983.33  4958.5  977.53  4978.9  976.11
  4995.7  971.67  4996.0  971.17  4999.5  971.17  4999.7  971.67  5001.3  971.67
  5009.3  974.59  5019.5  975.57  5100.4  976.62  5201.5  979.61  5252.1  983.08
  5272.3  983.41  5314.2  985.88  5322.9  985.34  5343.1  985.95  5363.4  987.55
  5383.6  988.31  5393.7  989.62  5403.8  991.72  5441.4  993.49  5453.4  994.92
#Mann=3,-1,0
  4656.5    0.05       0  4995.7   0.033       0  4999.7    0.05       0
Bank Sta=4995.7,4999.7
Exp/Cntr=0.3,0.1

Type RM Length L Ch R = 1,886,38,38,38
BEGIN DESCRIPTION:
MDW T 072 3.0
END DESCRIPTION:
XS GIS Cut Line= 3
      2248636.43      7153621.91      2248954.97      7153333.81
      2249079.11      7153088.09
#Sta/Elev= 30
  4570.5  987.89  4575.6  987.89  4580.8  986.91  4630.1  982.18  4637.5  982.02
  4644.3  980.95  4694.3  978.01  4786.2  974.24  4857.1  972.20  4870.7  972.16
  4884.9  973.10  4906.5  971.50  5012.9  971.36  5013.2  970.86  5016.7  970.86
  5016.9  971.36  5087.4  971.43  5104.1  973.32  5109.7  972.95  5126.4  974.28
  5154.3  974.88  5193.3  978.05  5205.9  979.72  5221.2  980.43  5237.9  982.94
  5243.5  982.44  5260.2  984.13  5265.8  983.87  5271.4  985.36  5275.3  985.36
#Mann=3,-1,0
  4570.5    0.05       0  5012.9   0.033       0  5016.9    0.05       0
Bank Sta=5012.9,5016.9
Exp/Cntr=0.3,0.1

Type RM Length L Ch R = 1,848,41,41,41
BEGIN DESCRIPTION:
MDW T 072 2.7
END DESCRIPTION:
XS GIS Cut Line= 6
      2248772.16      7153533.66      2248934.27      7153434.81
      2248983.60      7153391.72      2248993.95      7153328.08
      2249064.15      7153212.12      2249084.14      7153149.76
#Sta/Elev= 30
  4686.9  975.82  4702.2  974.74  4723.5  974.49  4738.9  973.37  4753.5  973.12
  4760.2  972.33  4837.7  969.83  4837.9  969.33  4841.4  969.33  4841.7  969.83
  4855.1  970.19  4861.0  971.97  4870.6  972.11  4876.4  972.82  4891.2  972.34
  4905.9  973.03  4947.7  972.64  4995.0  973.34  5003.6  973.02  5016.6  973.61
  5030.4  973.02  5045.9  973.54  5088.5  971.53  5104.0  971.93  5119.5  973.51
  5140.9  975.00  5146.5  974.93  5173.1  977.82  5186.9  978.30  5208.2  980.49
#Mann=3,-1,0
  4686.9    0.05       0  4837.7   0.033       0  4841.7    0.05       0
Bank Sta=4837.7,4841.7
Exp/Cntr=0.3,0.1

Type RM Length L Ch R = 1,807,195,195,195
BEGIN DESCRIPTION:
MDW T 072 2.5
END DESCRIPTION:
XS GIS Cut Line= 5
      2248794.39      7153536.16      2248983.11      7153447.67
      2249018.18      7153393.57      2249027.25      7153326.04
      2249137.52      7153164.78
#Sta/Elev= 30
  4690.2  974.02  4839.3  968.41  4856.6  968.05  4862.1  968.65  4872.0  967.50
  4893.6  968.10  4901.0  967.56  4916.2  968.81  4922.2  967.33  4931.3  968.82
  4937.3  968.11  4952.5  968.44  4962.3  961.76  4986.9  963.30  4997.0  959.79
  5004.4  959.95  5007.5  957.01  5007.7  956.51  5011.5  957.01  5017.2  957.64
  5026.7  960.69  5031.2  960.69  5043.9  965.57  5050.7  965.14  5058.8  968.25
  5073.7  970.42  5115.7  970.23  5166.5  975.02  5223.3  978.79  5226.6  979.63
#Mann=3,-1,0
  4690.2    0.05       0  5007.5   0.033       0  5011.5    0.05       0
Bank Sta=5007.5,5011.5
Exp/Cntr=0.3,0.1

Type RM Length L Ch R = 1,612,180,180,180
BEGIN DESCRIPTION:
MDW T 072 2.0
END DESCRIPTION:
XS GIS Cut Line= 3
      2248850.86      7153622.77      2249099.26      7153529.89
      2249316.08      7153302.49
#Sta/Elev= 30
  4734.8  970.73  4752.9  968.90  4813.5  965.90  4899.0  963.56  4967.7  963.30
  4978.4  960.27  4984.6  954.12  4989.9  954.38  4995.2  951.18  4995.4  950.68
  4999.2  951.18  5007.6  952.18  5013.7  955.60  5021.0  955.45  5027.9  960.56
  5035.1  960.73  5042.0  963.04  5077.6  962.45  5091.7  963.07  5098.6  961.84
  5112.8  961.68  5117.7  962.31  5127.0  962.03  5134.2  963.31  5176.7  961.22
  5190.8  961.25  5261.6  962.84  5268.5  961.42  5275.7  963.27  5314.2  966.00
#Mann=5,-1,0
  4734.8    0.05       0  4995.2   0.033       0  4999.2    0.05       0
  5007.6    0.12       0  5117.7    0.05       0
Bank Sta=4995.2,4999.2
Exp/Cntr=0.3,0.1

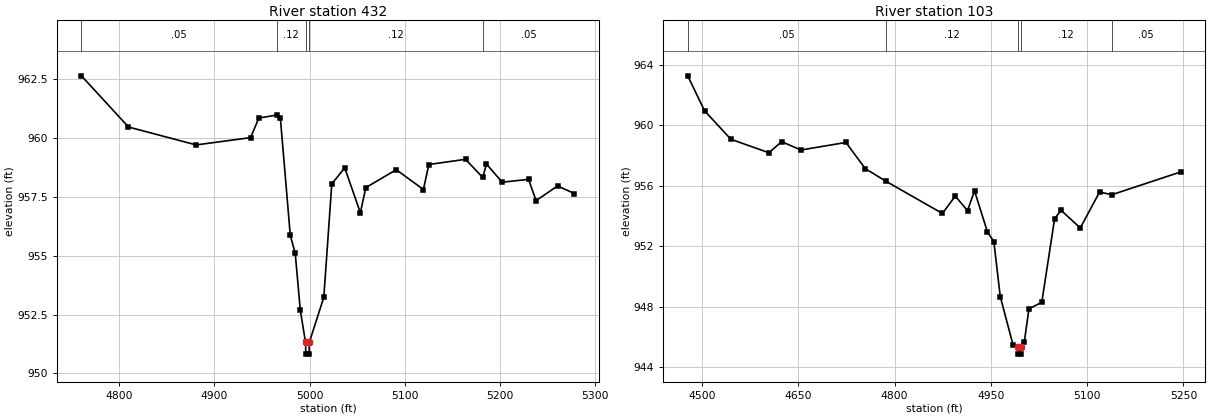
Type RM Length L Ch R = 1,432,329,329,329
BEGIN DESCRIPTION:
MDW T 072 1.0
END DESCRIPTION:
XS GIS Cut Line= 3
      2248929.03      7153759.99      2249158.36      7153690.59
      2249404.71      7153561.57
#Sta/Elev= 30
  4760.4  962.62  4809.8  960.45  4880.9  959.69  4938.0  960.00  4946.7  960.83
  4965.9  960.96  4969.3  960.82  4979.7  955.86  4984.9  955.09  4990.2  952.69
  4995.7  951.32  4996.0  950.82  4999.5  950.82  4999.7  951.32  5014.9  953.23
  5023.3  958.04  5036.9  958.72  5053.3  956.81  5059.0  957.88  5091.0  958.64
  5119.5  957.80  5125.2  958.86  5163.7  959.08  5181.8  958.31  5185.7  958.88
  5202.2  958.11  5229.9  958.23  5237.8  957.33  5260.4  957.95  5278.1  957.63
#Mann=5,-1,0
  4760.4    0.05       0  4965.9    0.12       0  4995.7    0.07       0
  4999.7    0.12       0  5181.8    0.05       0
Bank Sta=4995.7,4999.7
Exp/Cntr=0.3,0.1

Type RM Length L Ch R = 1,103,0,0,0
BEGIN DESCRIPTION:
MDW T 072 0.5
END DESCRIPTION:
XS GIS Cut Line= 3
      2248922.90      7153781.64      2249444.26      7153809.36
      2249448.02      7153563.49
#Sta/Elev= 30
  4477.9  963.28  4504.0  960.97  4545.1  959.08  4604.2  958.19  4624.2  958.92
  4654.2  958.37  4724.3  958.87  4754.4  957.14  4786.3  956.31  4874.6  954.17
  4894.6  955.32  4913.7  954.36  4924.6  955.67  4944.7  952.95  4954.7  952.31
  4964.7  948.67  4984.7  945.46  4992.7  945.36  4993.0  944.86  4996.5  944.86
  4996.7  945.36  5002.2  945.68  5009.4  947.86  5029.4  948.29  5049.4  953.83
  5059.4  954.38  5089.4  953.21  5119.4  955.59  5138.5  955.41  5245.9  956.92
#Mann=5,-1,0
  4477.9    0.05       0  4786.3    0.12       0  4992.7    0.07       0
  4996.7    0.12       0  5138.5    0.05       0
Bank Sta=4992.7,4996.7
Exp/Cntr=0.3,0.1

Chan Stop Cuts=-1