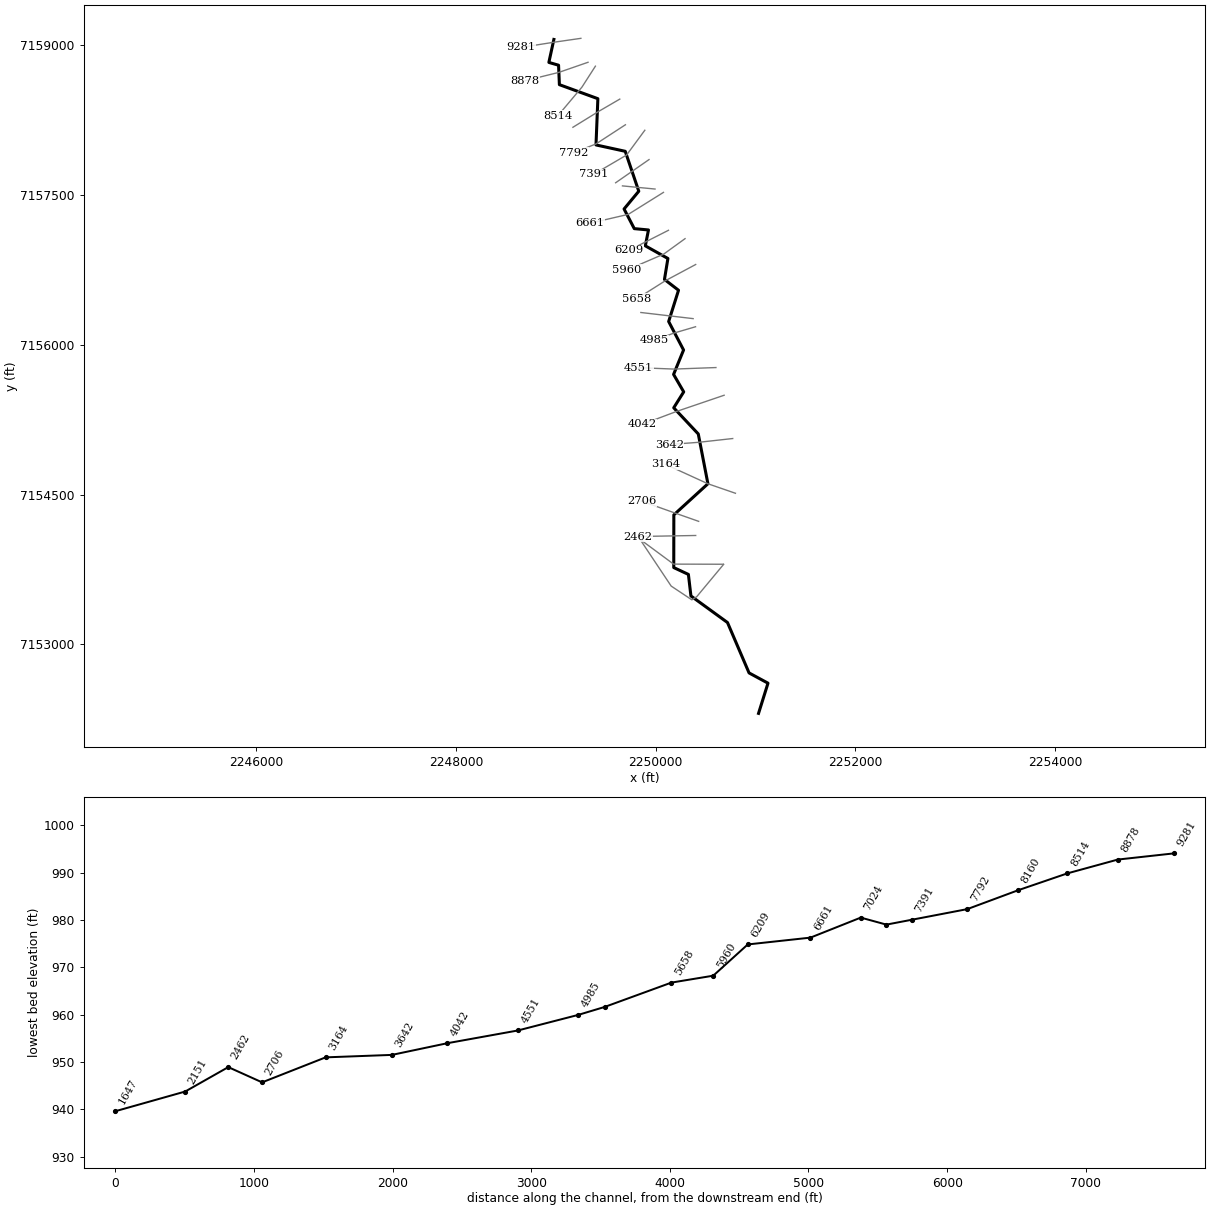
--- MDW T 073.prj (project) ---

Proj Title=MDW T 073 Base Level Engineering
Current Plan=p01
Default Exp/Contr=0.3,0.1
English Units
Geom File=g01
Flow File=f01
Plan File=p01
BEGIN DESCRIPTION:
MDW T 073
END DESCRIPTION:

--- MDW T 073.p01 (plan) ---

Plan Title=Multiple Run
Short Identifier=Multiple
Geom File=g01
Flow File=f01
Subcritical Flow
K Sum by GR= 0
Std Step Tol= 0.01
Critical Tol= 0.01
Num of Std Step Trials= 20
Max Error Tol= 0.3
Flow Tol Ratio= 0.001
Split Flow NTrial= 30
Split Flow Tol= 0.02
Split Flow Ratio= 0.02
Log Output Level= 0
Friction Slope Method= 1
Unsteady Friction Slope Method= 2
Unsteady Bridges Friction Slope Method= 1
Parabolic Critical Depth
Global Vel Dist=  1 , 1 , 1
Global Log Level= 0
CheckData=True
Encroach Param= -1, 0, 0, 0
BEGIN DESCRIPTION:
Multiple Run
END DESCRIPTION:

--- MDW T 073.f01 (steady flow) ---

Flow Title=Multiple
Number of Profiles=7
Profile Names=10-year,25-year,50-year,1pct_min,100-year,1pct_plu,500-year
River Rch & RM= MDW T 073,Reach-1,9281
     730    1016    1256     772    1540    3073    2319
River Rch & RM= MDW T 073,Reach-1,4042
     755    1050    1298     797    1589    3171    2388
Boundary for River Rch & Prof#=MDW T 073,Reach-1,1
Up Type=0
Dn Type=3
Dn Slope=0.005
Boundary for River Rch & Prof#=MDW T 073,Reach-1,2
Up Type=0
Dn Type=3
Dn Slope=0.005
Boundary for River Rch & Prof#=MDW T 073,Reach-1,3
Up Type=0
Dn Type=3
Dn Slope=0.005
Boundary for River Rch & Prof#=MDW T 073,Reach-1,4
Up Type=0
Dn Type=3
Dn Slope=0.005
Boundary for River Rch & Prof#=MDW T 073,Reach-1,5
Up Type=0
Dn Type=3
Dn Slope=0.005
Boundary for River Rch & Prof#=MDW T 073,Reach-1,6
Up Type=0
Dn Type=3
Dn Slope=0.005
Boundary for River Rch & Prof#=MDW T 073,Reach-1,7
Up Type=0
Dn Type=3
Dn Slope=0.005

--- MDW T 073.g01 (geometry) ---

Geom Title=Existing Conditions

River Reach=MDW T 073,Reach-1
Reach XY= 30
      2248979.00      7159060.00      2248928.82      7158830.05
      2249026.00      7158802.00      2249034.34      7158607.26
      2249419.71      7158466.69      2249400.90      7158003.45
      2249693.88      7157939.73      2249829.47      7157539.83
      2249682.16      7157362.10      2249784.42      7157165.18
      2249926.52      7157151.90      2249895.03      7156992.87
      2250121.20      7156866.21      2250086.79      7156656.57
      2250227.54      7156548.02      2250128.80      7156234.92
      2250278.06      7155949.51      2250178.13      7155704.96
      2250279.47      7155530.16      2250179.55      7155370.64
      2250425.46      7155108.54      2250522.00      7154609.78
      2250180.62      7154298.17      2250179.87      7153770.31
      2250326.46      7153701.83      2250351.80      7153486.05
      2250717.89      7153220.05      2250934.11      7152715.11
      2251123.61      7152612.44      2251029.00      7152310.00

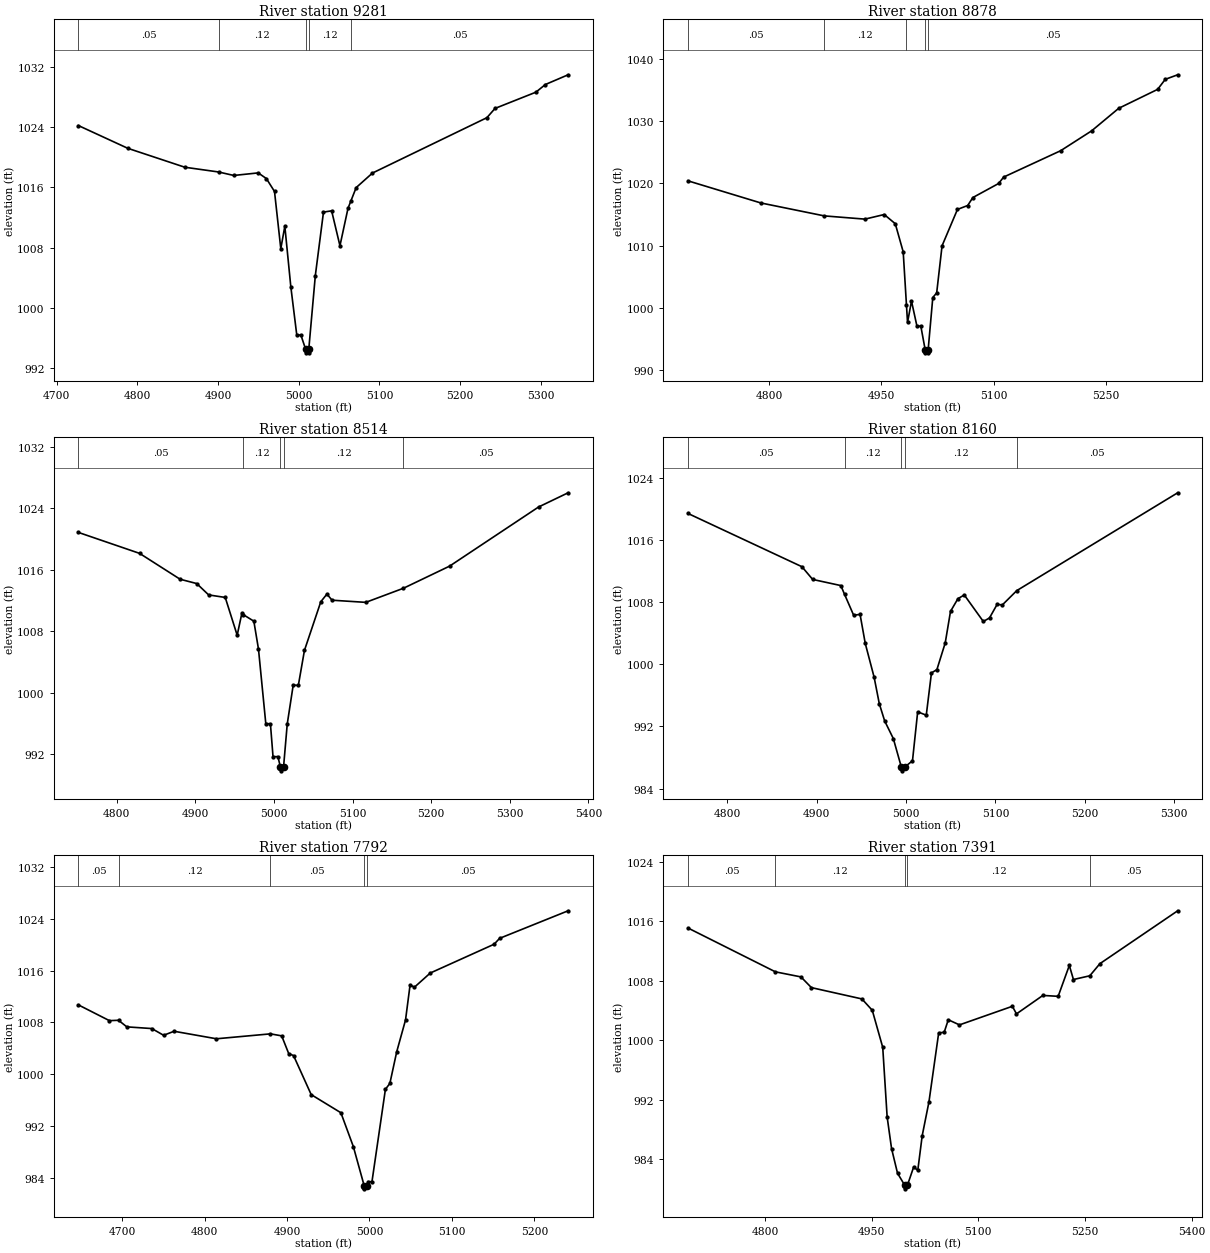
Type RM Length L Ch R = 1,9281,403,403,403
BEGIN DESCRIPTION:
MDW T 073 18.0
END DESCRIPTION:
XS GIS Cut Line= 3
      2249249.63      7159071.23      2248979.33      7159032.21
      2248649.52      7158980.07
#Sta/Elev= 30
  4726.9 1024.19  4788.2 1021.17  4858.9 1018.66  4900.8 1018.03  4919.5 1017.57
  4949.8 1017.91  4959.9 1017.16  4970.0 1015.45  4977.8 1007.86  4982.8 1010.84
  4990.2 1002.83  4997.6  996.41  5002.7  996.41  5008.5  994.55  5008.7  994.05
  5012.2  994.05  5012.5  994.55  5020.6 1004.30  5030.7 1012.71  5040.8 1012.88
  5051.1 1008.25  5061.1 1013.22  5064.5 1014.14  5071.2 1015.96  5091.4 1017.89
  5233.2 1025.23  5243.3 1026.46  5293.9 1028.61  5305.7 1029.63  5333.9 1030.92
#Mann=5,-1,0
  4726.9    0.05       0  4900.8    0.12       0  5008.5    0.07       0
  5012.5    0.12       0  5064.5    0.05       0
Bank Sta=5008.5,5012.5
Exp/Cntr=0.3,0.1

Type RM Length L Ch R = 1,8878,364,364,364
BEGIN DESCRIPTION:
MDW T 073 17.0
END DESCRIPTION:
XS GIS Cut Line= 3
      2249321.18      7158831.41      2249029.21      7158730.23
      2248692.91      7158647.22
#Sta/Elev= 30
  4691.0 1020.41  4788.6 1016.85  4873.5 1014.77  4927.9 1014.25  4953.7 1014.99
  4968.5 1013.51  4979.1 1008.99  4983.5 1000.38  4984.9  997.64  4990.2 1001.07
  4997.5  997.04  5002.7  997.04  5008.5  993.25  5008.8  992.75  5012.3  992.75
  5012.5  993.25  5018.7 1001.64  5023.9 1002.39  5031.1 1009.96  5051.7 1015.81
  5065.4 1016.44  5072.3 1017.72  5106.8 1019.98  5113.5 1021.01  5189.8 1025.25
  5231.2 1028.44  5267.5 1032.07  5319.5 1035.11  5329.8 1036.73  5346.4 1037.46
#Mann=5,-1,0
  4691.0    0.05       0  4873.5    0.12       0  4983.5    0.05       0
  5008.5   0.033       0  5012.5    0.05       0
Bank Sta=5008.5,5012.5
Exp/Cntr=0.3,0.1

Type RM Length L Ch R = 1,8514,354,354,354
BEGIN DESCRIPTION:
MDW T 073 16.0
END DESCRIPTION:
XS GIS Cut Line= 3
      2249394.99      7158792.35      2249260.45      7158582.94
      2249019.55      7158296.47
#Sta/Elev= 30
  4751.1 1020.88  4829.0 1018.15  4880.6 1014.78  4901.7 1014.22  4916.9 1012.74
  4938.0 1012.41  4953.2 1007.49  4959.2 1010.37  4960.8 1010.18  4974.4 1009.32
  4980.3 1005.69  4989.6  995.99  4995.5  995.95  4998.8  991.68  5005.0  991.68
  5008.2  990.33  5008.5  989.83  5012.2  990.33  5016.9  995.93  5024.5 1001.00
  5031.0 1000.95  5038.8 1005.52  5059.6 1011.85  5067.4 1012.85  5073.9 1012.05
  5116.8 1011.77  5164.8 1013.61  5223.5 1016.49  5336.7 1024.19  5374.3 1026.04
#Mann=5,-1,0
  4751.1    0.05       0  4960.8    0.12       0  5008.2    0.07       0
  5012.2    0.12       0  5164.8    0.05       0
Bank Sta=5008.2,5012.2
Exp/Cntr=0.3,0.1

Type RM Length L Ch R = 1,8160,368,368,368
BEGIN DESCRIPTION:
MDW T 073 15.0
END DESCRIPTION:
XS GIS Cut Line= 3
      2249639.17      7158462.52      2249428.47      7158339.87
      2249169.87      7158180.44
#Sta/Elev= 30
  4756.2 1019.46  4883.7 1012.59  4895.7 1010.95  4927.2 1010.16  4931.3 1009.04
  4941.5 1006.34  4948.7 1006.44  4954.5 1002.70  4964.4  998.35  4970.2  994.93
  4976.2  992.71  4985.9  990.43  4994.8  986.78  4995.1  986.28  4998.8  986.78
  5007.3  987.58  5013.1  993.89  5022.7  993.45  5028.5  998.90  5034.6  999.33
  5043.9 1002.77  5049.8 1006.83  5058.1 1008.47  5065.2 1008.95  5086.5 1005.53
  5093.4 1005.99  5101.9 1007.73  5107.8 1007.67  5123.9 1009.51  5303.8 1022.12
#Mann=5,-1,0
  4756.2    0.05       0  4931.3    0.12       0  4994.8    0.07       0
  4998.8    0.12       0  5123.9    0.05       0
Bank Sta=4994.8,4998.8
Exp/Cntr=0.3,0.1

Type RM Length L Ch R = 1,7792,401,401,401
BEGIN DESCRIPTION:
MDW T 073 14.0
END DESCRIPTION:
XS GIS Cut Line= 3
      2249695.68      7158205.52      2249399.84      7158012.94
      2249175.34      7157925.31
#Sta/Elev= 30
  4647.0 1010.71  4684.7 1008.27  4695.7 1008.33  4705.8 1007.31  4736.1 1007.05
  4750.4 1006.01  4763.1 1006.63  4814.5 1005.47  4880.0 1006.23  4893.6 1005.92
  4902.1 1003.19  4908.0 1002.87  4929.4  996.84  4965.4  994.04  4980.5  988.81
  4993.6  982.78  4993.9  982.28  4997.6  982.78  4998.1  983.39  5003.1  983.39
  5019.4  997.66  5024.8  998.57  5033.1 1003.46  5043.8 1008.38  5049.3 1013.78
  5054.6 1013.44  5073.8 1015.63  5151.2 1020.08  5157.9 1020.99  5241.0 1025.25
#Mann=5,-1,0
  4647.0    0.05       0  4695.7    0.12       0  4880.0    0.05       0
  4993.6   0.033       0  4997.6    0.05       0
Bank Sta=4993.6,4997.6
Exp/Cntr=0.3,0.1

Type RM Length L Ch R = 1,7391,182,182,182
BEGIN DESCRIPTION:
MDW T 073 13.0
END DESCRIPTION:
XS GIS Cut Line= 3
      2249890.06      7158150.67      2249707.16      7157902.23
      2249379.01      7157710.01
#Sta/Elev= 30
  4691.5 1015.10  4814.6 1009.20  4850.5 1008.52  4865.2 1007.08  4936.2 1005.56
  4950.8 1004.03  4965.5  999.05  4971.7  989.70  4977.9  985.45  4986.3  982.13
  4996.3  980.53  4996.5  980.03  5000.3  980.53  5009.0  982.97  5014.8  982.52
  5021.0  987.17  5030.5  991.72  5044.2 1001.00  5051.9 1001.07  5057.7 1002.76
  5073.4 1002.07  5147.8 1004.57  5153.6 1003.55  5190.7 1006.03  5212.2 1005.91
  5227.9 1010.06  5233.7 1008.17  5256.7 1008.67  5270.9 1010.30  5380.3 1017.41
#Mann=5,-1,0
  4691.5    0.05       0  4814.6    0.12       0  4996.3    0.07       0
  5000.3    0.12       0  5256.7    0.05       0
Bank Sta=4996.3,5000.3
Exp/Cntr=0.3,0.1

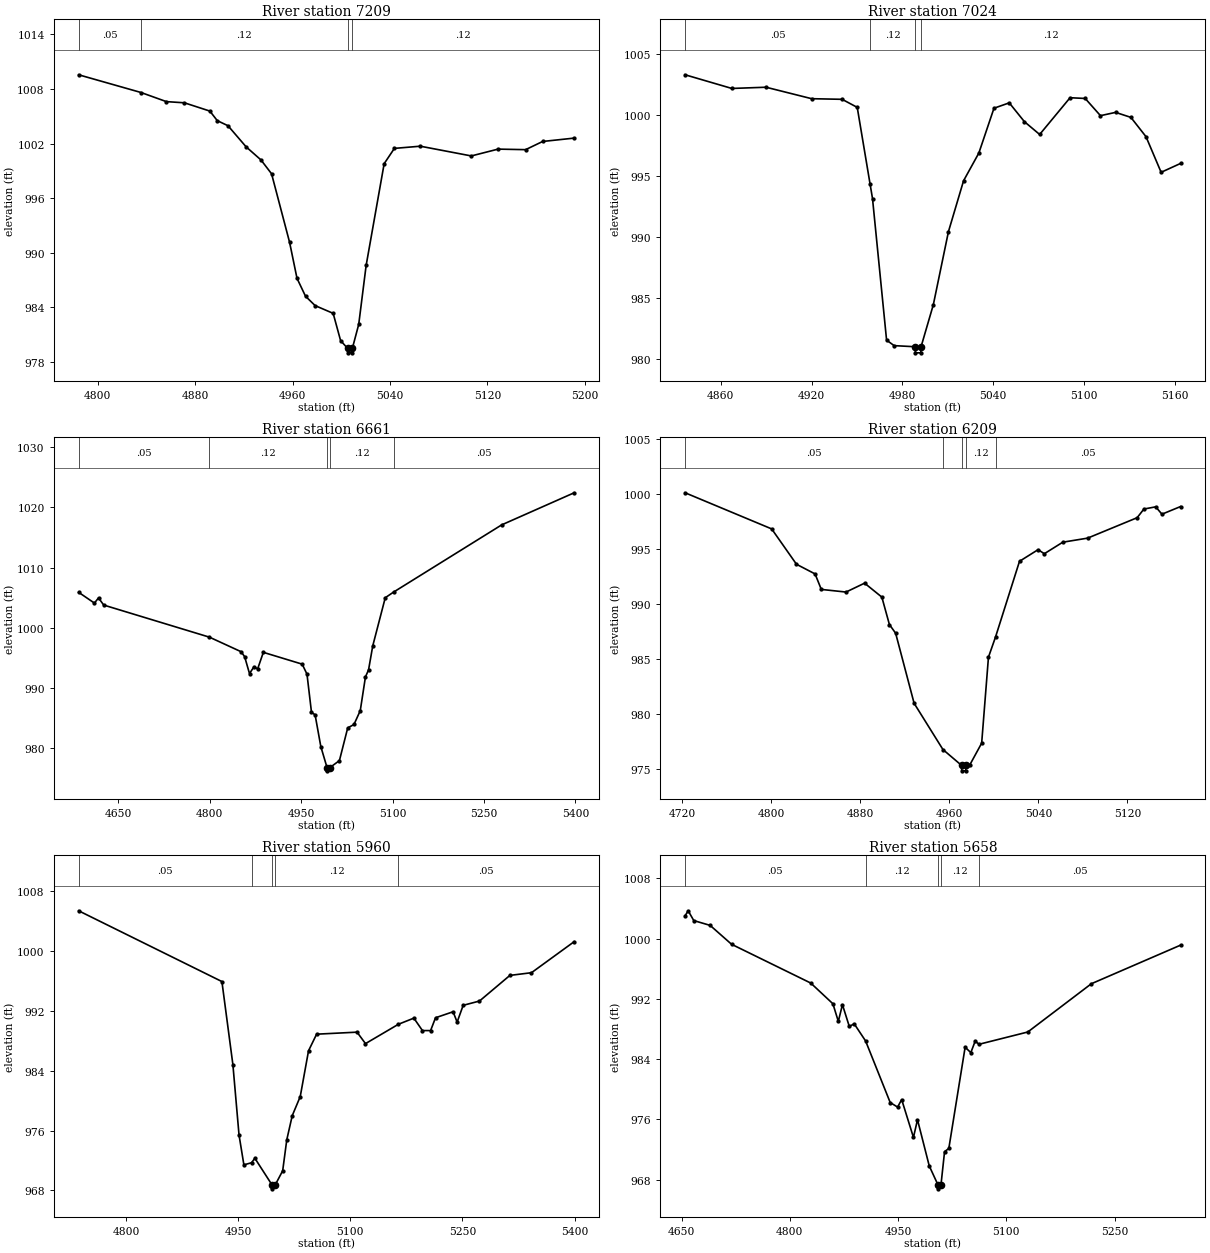
Type RM Length L Ch R = 1,7209,185,185,185
BEGIN DESCRIPTION:
Mapping XS c48e6d18
END DESCRIPTION:
XS GIS Cut Line= 2
      2249932.07      7157856.87      2249597.71      7157624.64
#Sta/Elev= 30
  4784.2 1009.57  4835.5 1007.62  4856.3 1006.62  4871.1 1006.49  4892.0 1005.58
  4898.1 1004.53  4906.9 1003.97  4921.8 1001.65  4934.0 1000.21  4942.7  998.69
  4957.5  991.16  4963.6  987.20  4970.6  985.23  4978.5  984.20  4993.3  983.35
  4999.4  980.36  5005.1  979.51  5005.3  979.01  5008.8  979.01  5009.1  979.51
  5014.3  982.14  5020.4  988.62  5035.2  999.80  5043.6 1001.48  5064.9 1001.72
  5106.8 1000.65  5128.8 1001.40  5151.4 1001.34  5165.4 1002.24  5191.3 1002.61
#Mann=4,-1,0
  4784.2    0.05       0  4835.5    0.12       0  5005.1    0.07       0
  5009.1    0.12       0
Bank Sta=5005.1,5009.1
Exp/Cntr=0.3,0.1

Type RM Length L Ch R = 1,7024,363,363,363
BEGIN DESCRIPTION:
Mapping XS a3ada163
END DESCRIPTION:
XS GIS Cut Line= 2
      2249992.29      7157561.79      2249666.21      7157593.25
#Sta/Elev= 30
  4836.4 1003.27  4867.3 1002.15  4889.9 1002.25  4920.1 1001.31  4940.2 1001.26
  4950.2 1000.60  4958.7  994.31  4960.3  993.13  4969.6  981.53  4974.6  981.08
  4988.4  980.99  4988.7  980.49  4992.2  980.49  4992.4  980.99  5000.5  984.43
  5010.5  990.42  5020.5  994.59  5030.6  996.86  5040.6 1000.53  5050.7 1000.97
  5060.7  999.43  5070.8  998.38  5090.9 1001.39  5100.9 1001.33  5111.0  999.92
  5121.0 1000.19  5131.1  999.78  5141.1  998.20  5151.1  995.28  5164.0  996.01
#Mann=4,-1,0
  4836.4    0.05       0  4958.7    0.12       0  4988.4    0.07       0
  4992.4    0.12       0
Bank Sta=4988.4,4992.4
Exp/Cntr=0.3,0.1

Type RM Length L Ch R = 1,6661,452,452,452
BEGIN DESCRIPTION:
MDW T 073 11.0
END DESCRIPTION:
XS GIS Cut Line= 3
      2250076.68      7157528.26      2249724.76      7157308.30
      2249337.16      7157218.39
#Sta/Elev= 30
  4585.0 1005.91  4610.9 1004.12  4617.6 1004.98  4626.2 1003.79  4799.6  998.46
  4851.4  996.05  4857.3  995.23  4865.3  992.41  4872.7  993.56  4878.6  993.17
  4888.0  995.94  4951.7  993.98  4959.6  992.32  4967.0  985.97  4972.9  985.57
  4982.3  980.29  4992.6  976.76  4992.8  976.26  4996.6  976.76  5012.8  977.96
  5026.4  983.39  5036.7  983.96  5047.0  986.26  5055.5  991.86  5060.6  993.03
  5067.5  997.02  5088.0 1005.01  5101.7 1005.95  5279.0 1017.11  5397.9 1022.44
#Mann=5,-1,0
  4585.0    0.05       0  4799.6    0.12       0  4992.6    0.07       0
  4996.6    0.12       0  5101.7    0.05       0
Bank Sta=4992.6,4996.6
Exp/Cntr=0.3,0.1

Type RM Length L Ch R = 1,6209,249,249,249
BEGIN DESCRIPTION:
Mapping XS c266caea
END DESCRIPTION:
XS GIS Cut Line= 2
      2250126.68      7157148.55      2249729.54      7156947.14
#Sta/Elev= 30
  4722.5 1000.14  4800.3  996.85  4822.6  993.63  4839.3  992.75  4844.9  991.34
  4867.1  991.10  4883.8  991.91  4899.3  990.64  4906.1  988.14  4911.7  987.35
  4928.3  980.97  4954.2  976.76  4970.9  975.32  4971.1  974.82  4974.6  974.82
  4974.9  975.32  4978.5  975.39  4989.0  977.34  4995.1  985.17  5001.5  987.02
  5023.0  993.90  5039.7  994.96  5045.3  994.59  5061.9  995.64  5084.2  996.01
  5128.7  997.87  5134.8  998.66  5145.4  998.86  5151.0  998.19  5167.8  998.89
#Mann=5,-1,0
  4722.5    0.05       0  4954.2    0.12       0  4970.9    0.07       0
  4974.9    0.12       0  5001.5    0.05       0
Bank Sta=4970.9,4974.9
Exp/Cntr=0.3,0.1

Type RM Length L Ch R = 1,5960,302,302,302
BEGIN DESCRIPTION:
MDW T 073 9.0
END DESCRIPTION:
XS GIS Cut Line= 3
      2250292.88      7157064.76      2250079.00      7156910.00
      2249712.63      7156751.96
#Sta/Elev= 30
  4736.5 1005.31  4928.2  995.87  4942.9  984.78  4951.1  975.40  4957.6  971.42
  4967.8  971.70  4972.3  972.30  4995.4  968.72  4995.7  968.22  4999.4  968.72
  5009.5  970.63  5015.0  974.77  5022.3  977.98  5033.0  980.53  5044.1  986.64
  5054.9  988.85  5109.0  989.12  5120.3  987.59  5164.3  990.17  5185.0  990.99
  5196.5  989.33  5207.4  989.33  5214.0  991.04  5237.5  991.84  5242.9  990.46
  5251.0  992.70  5272.8  993.27  5313.5  996.69  5342.4  997.05  5399.5 1001.19
#Mann=5,-1,0
  4736.5    0.05       0  4967.8    0.12       0  4995.4    0.07       0
  4999.4    0.12       0  5164.3    0.05       0
Bank Sta=4995.4,4999.4
Exp/Cntr=0.3,0.1

Type RM Length L Ch R = 1,5658,482,482,482
BEGIN DESCRIPTION:
MDW T 073 8.0
END DESCRIPTION:
XS GIS Cut Line= 3
      2250399.58      7156806.04      2250095.28      7156643.26
      2249806.75      7156460.58
#Sta/Elev= 30
  4654.9 1003.03  4659.2 1003.69  4666.9 1002.39  4689.6 1001.75  4719.3  999.24
  4829.0  994.09  4859.7  991.34  4867.2  989.00  4872.9  991.22  4882.4  988.33
  4889.2  988.68  4905.0  986.40  4939.1  978.22  4949.3  977.62  4955.0  978.61
  4971.3  973.59  4976.9  975.94  4993.2  969.80  5005.4  967.26  5005.7  966.76
  5009.4  967.26  5014.4  971.70  5020.3  972.12  5042.9  985.57  5050.8  984.85
  5056.8  986.37  5062.2  985.96  5129.7  987.59  5217.8  994.00  5341.5  999.13
#Mann=5,-1,0
  4654.9    0.05       0  4905.0    0.12       0  5005.4    0.07       0
  5009.4    0.12       0  5062.2    0.05       0
Bank Sta=5005.4,5009.4
Exp/Cntr=0.3,0.1

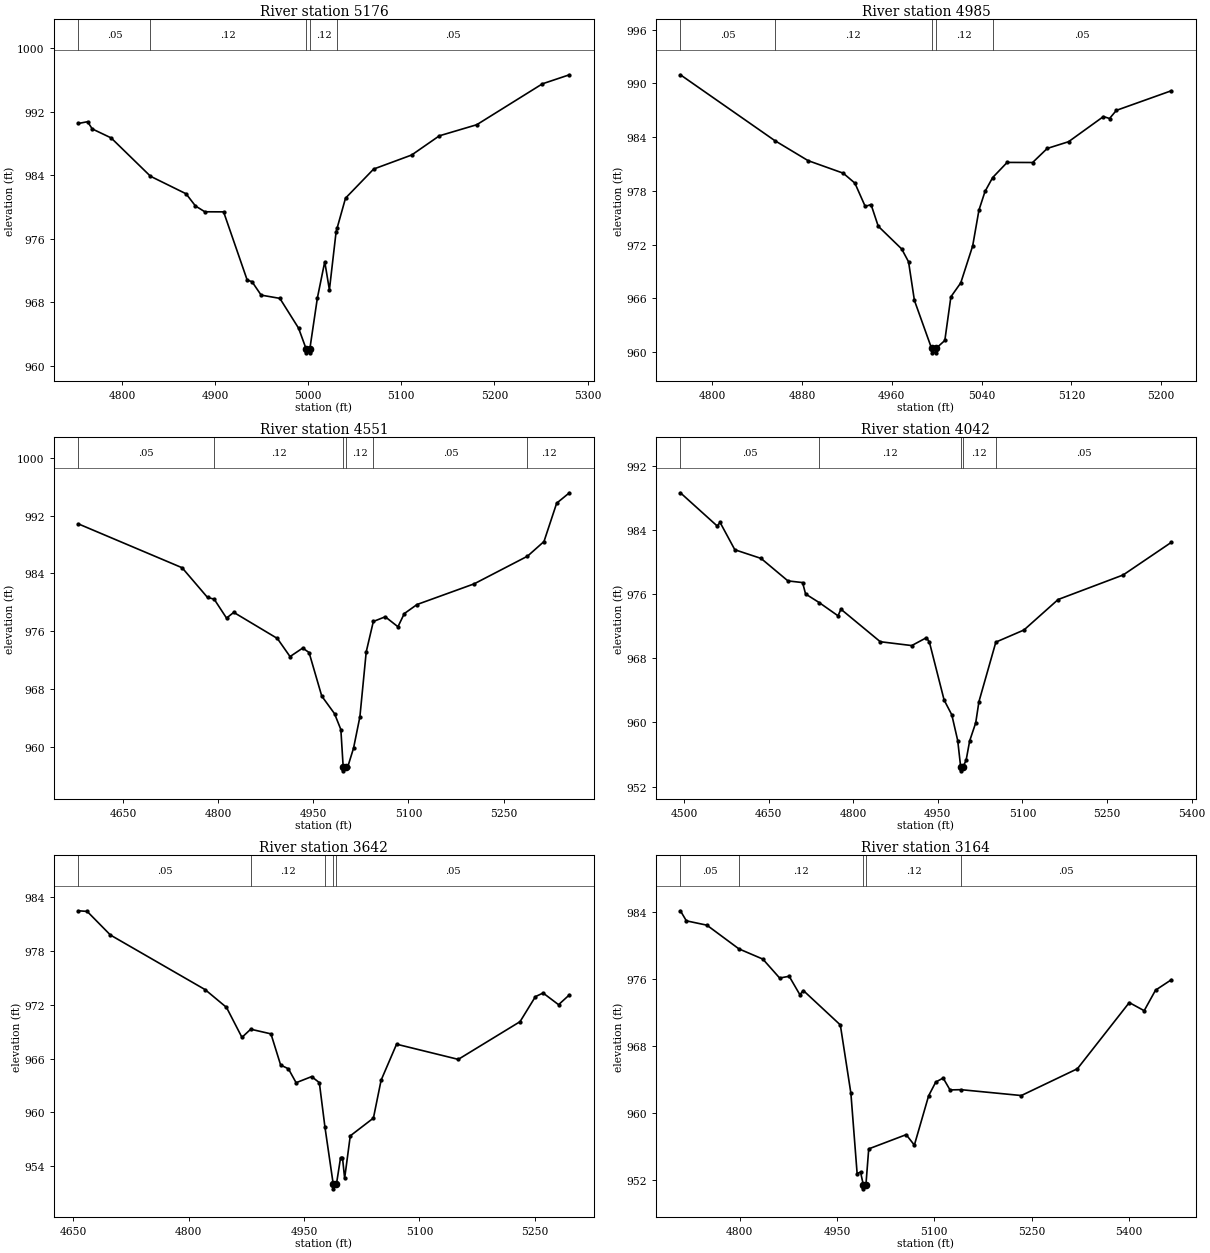
Type RM Length L Ch R = 1,5176,191,191,191
BEGIN DESCRIPTION:
Mapping XS 694ab5fa
END DESCRIPTION:
XS GIS Cut Line= 2
      2250373.83      7156263.87      2249850.21      7156325.26
#Sta/Elev= 30
  4753.3  990.54  4763.1  990.76  4768.2  989.85  4788.4  988.72  4830.7  983.88
  4868.9  981.67  4879.0  980.13  4889.1  979.40  4909.2  979.39  4934.6  970.76
  4939.6  970.60  4949.5  968.89  4969.6  968.48  4989.7  964.72  4997.8  962.11
  4998.1  961.61  5001.6  961.61  5001.8  962.11  5009.9  968.54  5017.8  973.10
  5022.8  969.56  5030.0  976.89  5031.0  977.31  5040.1  981.12  5070.3  984.79
  5111.1  986.56  5140.8  988.98  5181.0  990.38  5251.5  995.54  5280.5  996.68
#Mann=5,-1,0
  4753.3    0.05       0  4830.7    0.12       0  4997.8    0.07       0
  5001.8    0.12       0  5031.0    0.05       0
Bank Sta=4997.8,5001.8
Exp/Cntr=0.3,0.1

Type RM Length L Ch R = 1,4985,434,434,434
BEGIN DESCRIPTION:
MDW T 073 6.0
END DESCRIPTION:
XS GIS Cut Line= 3
      2250398.09      7156182.53      2250179.05      7156118.16
      2249983.06      7156045.56
#Sta/Elev= 30
  4771.7  990.96  4855.7  983.62  4885.4  981.38  4916.7  979.98  4927.1  978.87
  4936.3  976.27  4941.5  976.48  4947.9  974.06  4968.8  971.52  4974.9  970.09
  4980.1  965.79  4995.4  960.43  4995.7  959.93  4999.2  959.93  4999.4  960.43
  5007.2  961.31  5012.6  966.18  5021.4  967.74  5032.0  971.86  5037.6  975.86
  5043.0  977.94  5049.8  979.49  5062.7  981.18  5085.4  981.17  5098.4  982.74
  5117.4  983.49  5148.5  986.30  5153.9  986.08  5160.0  986.99  5209.0  989.18
#Mann=5,-1,0
  4771.7    0.05       0  4855.7    0.12       0  4995.4    0.07       0
  4999.4    0.12       0  5049.8    0.05       0
Bank Sta=4995.4,4999.4
Exp/Cntr=0.3,0.1

Type RM Length L Ch R = 1,4551,509,509,509
BEGIN DESCRIPTION:
MDW T 073 5.0
END DESCRIPTION:
XS GIS Cut Line= 3
      2250602.39      7155773.77      2250182.47      7155758.50
      2249828.94      7155772.46
#Sta/Elev= 30
  4579.8  990.84  4743.3  984.77  4783.3  980.66  4793.8  980.42  4813.3  977.80
  4824.7  978.59  4893.4  974.98  4913.4  972.47  4933.4  973.65  4943.4  973.03
  4963.4  967.00  4983.5  964.57  4993.5  962.37  4997.2  957.15  4997.5  956.65
  5001.2  957.15  5004.2  957.15  5013.5  959.79  5023.5  964.12  5033.5  973.13
  5044.7  977.33  5063.5  977.98  5083.5  976.60  5093.5  978.42  5113.6  979.68
  5203.6  982.54  5287.7  986.37  5313.7  988.40  5333.7  993.71  5353.8  995.15
#Mann=6,-1,0
  4579.8    0.05       0  4793.8    0.12       0  4997.2    0.07       0
  5001.2    0.12       0  5044.7    0.05       0  5287.7    0.12       0
Bank Sta=4997.2,5001.2
Exp/Cntr=0.3,0.1

Type RM Length L Ch R = 1,4042,400,400,400
BEGIN DESCRIPTION:
MDW T 073 4.0
END DESCRIPTION:
XS GIS Cut Line= 3
      2250684.40      7155496.43      2250205.04      7155333.18
      2249864.40      7155204.88
#Sta/Elev= 30
  4493.6  988.61  4558.7  984.48  4564.0  984.91  4590.1  981.51  4636.6  980.43
  4684.2  977.63  4710.2  977.42  4715.5  976.00  4739.6  974.93  4773.0  973.28
  4778.2  974.10  4847.9  970.05  4903.7  969.57  4929.7  970.55  4935.0  970.00
  4961.1  962.78  4974.7  960.94  4985.2  957.73  4990.4  954.46  4990.7  953.96
  4994.4  954.46  5000.0  955.25  5006.4  957.70  5017.1  959.94  5022.8  962.58
  5052.8  970.00  5102.6  971.51  5163.2  975.31  5278.5  978.37  5364.0  982.44
#Mann=5,-1,0
  4493.6    0.05       0  4739.6    0.12       0  4990.4    0.07       0
  4994.4    0.12       0  5052.8    0.05       0
Bank Sta=4990.4,4994.4
Exp/Cntr=0.3,0.1

Type RM Length L Ch R = 1,3642,478,478,478
BEGIN DESCRIPTION:
MDW T 073 3.0
END DESCRIPTION:
XS GIS Cut Line= 3
      2250770.32      7155062.83      2250429.11      7155025.04
      2250134.94      7155002.94
#Sta/Elev= 30
  4656.7  982.46  4668.1  982.39  4698.3  979.76  4821.4  973.68  4849.2  971.70
  4869.3  968.36  4880.7  969.27  4907.0  968.75  4919.6  965.28  4929.7  964.86
  4939.7  963.31  4959.9  963.99  4969.9  963.32  4977.2  958.36  4988.0  951.99
  4988.3  951.49  4992.1  951.99  4997.5  954.96  5000.0  954.96  5002.8  952.66
  5010.1  957.39  5040.2  959.37  5050.2  963.59  5070.3  967.60  5150.5  965.91
  5230.8  970.11  5250.8  972.90  5260.8  973.30  5280.9  972.00  5295.0  973.10
#Mann=5,-1,0
  4656.7    0.05       0  4880.7    0.12       0  4977.2    0.05       0
  4988.0   0.033       0  4992.1    0.05       0
Bank Sta=4988,4992.1
Exp/Cntr=0.3,0.1

Type RM Length L Ch R = 1,3164,458,458,458
BEGIN DESCRIPTION:
MDW T 073 2.0
END DESCRIPTION:
XS GIS Cut Line= 3
      2250797.65      7154514.66      2250522.00      7154609.78
      2250098.49      7154803.69
#Sta/Elev= 30
  4708.4  984.17  4717.6  982.97  4749.3  982.45  4798.7  979.62  4835.6  978.40
  4861.5  976.14  4876.2  976.35  4892.7  974.15  4898.0  974.65  4955.1  970.54
  4971.4  962.38  4981.0  952.80  4986.3  952.97  4990.5  951.47  4990.8  950.97
  4994.6  951.47  4998.9  955.74  5056.7  957.44  5069.3  956.19  5091.3  962.08
  5102.3  963.72  5113.7  964.20  5124.3  962.78  5141.2  962.81  5234.3  962.11
  5320.8  965.31  5400.8  973.21  5423.8  972.24  5441.3  974.69  5465.8  975.94
#Mann=5,-1,0
  4708.4    0.05       0  4798.7    0.12       0  4990.5    0.07       0
  4994.6    0.12       0  5141.2    0.05       0
Bank Sta=4990.5,4994.6
Exp/Cntr=0.3,0.1

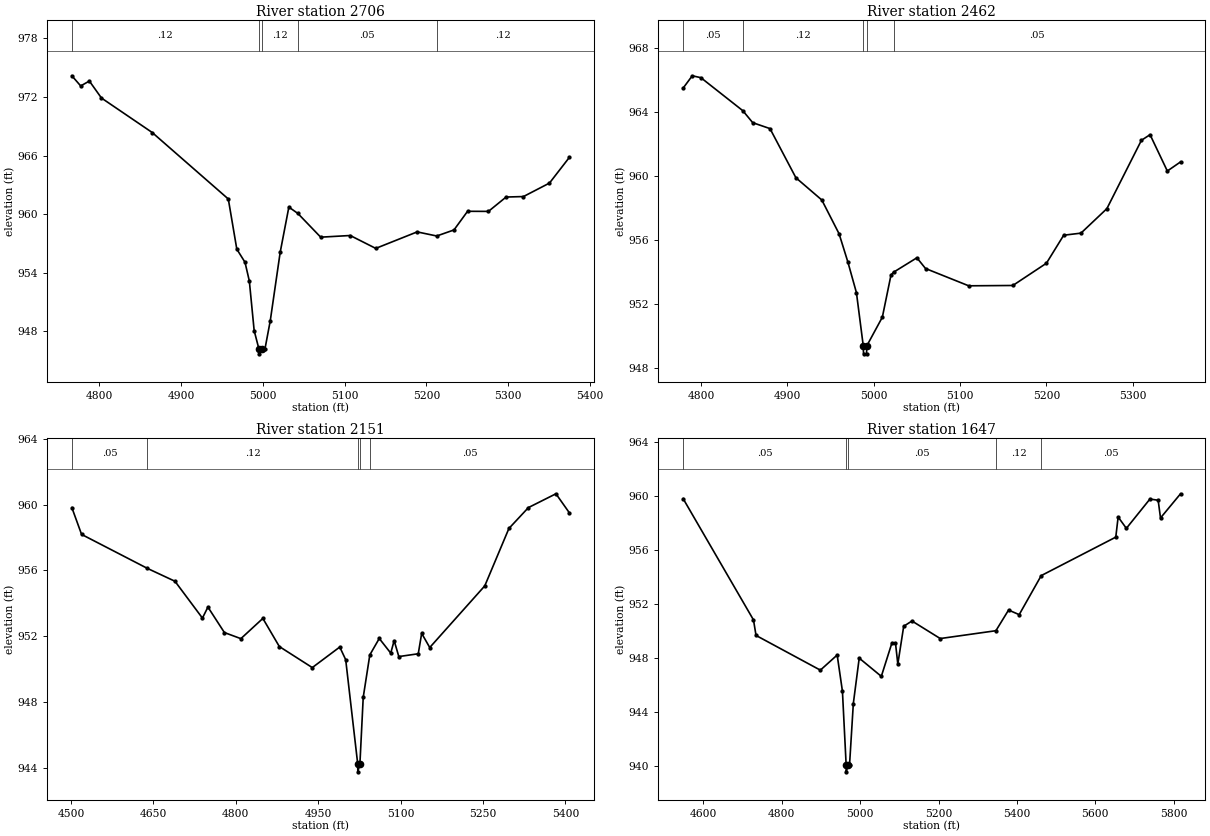
Type RM Length L Ch R = 1,2706,244,244,244
BEGIN DESCRIPTION:
MDW T 073 1.0
END DESCRIPTION:
XS GIS Cut Line= 3
      2250429.20      7154233.39      2250209.07      7154310.65
      2249856.25      7154436.53
#Sta/Elev= 30
  4766.7  974.17  4777.5  973.13  4788.1  973.63  4802.9  971.89  4864.9  968.36
  4957.9  961.55  4968.3  956.41  4978.3  955.07  4983.6  953.15  4989.5  948.07
  4995.3  946.19  4995.6  945.69  4999.4  946.19  5002.7  946.19  5009.2  949.09
  5021.3  956.09  5031.9  960.72  5042.9  960.07  5070.8  957.64  5106.9  957.81
  5138.1  956.49  5188.7  958.18  5212.6  957.76  5233.7  958.38  5250.3  960.29
  5275.8  960.28  5297.4  961.75  5318.6  961.80  5350.4  963.18  5374.6  965.80
#Mann=5,-1,0
  4766.7    0.12       0  4995.3    0.07       0  4999.4    0.12       0
  5042.9    0.05       0  5212.6    0.12       0
Bank Sta=4995.3,4999.4
Exp/Cntr=0.3,0.1

Type RM Length L Ch R = 1,2462,311,311,311
BEGIN DESCRIPTION:
Mapping XS 45f9a47f
END DESCRIPTION:
XS GIS Cut Line= 2
      2250399.62      7154091.78      2249823.71      7154081.45
#Sta/Elev= 30
  4779.3  965.51  4789.9  966.28  4799.9  966.16  4848.4  964.10  4859.9  963.35
  4879.9  962.98  4909.9  959.91  4939.9  958.52  4959.9  956.41  4970.0  954.66
  4980.0  952.73  4987.9  949.41  4988.2  948.91  4991.7  948.91  4992.0  949.41
  5010.0  951.20  5020.0  953.83  5023.0  954.01  5050.0  954.91  5060.0  954.24
  5110.0  953.16  5161.1  953.18  5200.0  954.57  5220.0  956.32  5240.0  956.45
  5270.0  957.98  5310.0  962.25  5320.0  962.60  5340.0  960.33  5355.3  960.90
#Mann=5,-1,0
  4779.3    0.05       0  4848.4    0.12       0  4987.9    0.07       0
  4992.0    0.12       0  5023.0    0.05       0
Bank Sta=4987.9,4992
Exp/Cntr=0.3,0.1

Type RM Length L Ch R = 1,2151,504,504,504
BEGIN DESCRIPTION:
MDW T 073 0.5
END DESCRIPTION:
XS GIS Cut Line= 3
      2250676.66      7153803.71      2250178.16      7153804.92
      2249850.82      7154046.78
#Sta/Elev= 30
  4501.5  959.82  4519.2  958.19  4639.2  956.12  4689.2  955.34  4739.2  953.10
  4749.2  953.77  4779.2  952.22  4809.2  951.85  4849.2  953.08  4879.2  951.37
  4939.2  950.09  4989.2  951.34  5000.0  950.57  5021.8  944.25  5022.1  943.75
  5025.9  944.25  5031.9  948.28  5043.9  950.86  5061.1  951.86  5082.0  950.97
  5088.2  951.73  5096.7  950.76  5132.1  950.93  5138.3  952.17  5153.0  951.31
  5253.2  955.06  5297.1  958.55  5332.6  959.82  5382.7  960.66  5407.0  959.51
#Mann=5,-1,0
  4501.5    0.05       0  4639.2    0.12       0  5021.8    0.07       0
  5025.9    0.12       0  5043.9    0.05       0
Bank Sta=5021.8,5025.9
Exp/Cntr=0.3,0.1

Type RM Length L Ch R = 1,1647,0,0,0
BEGIN DESCRIPTION:
MDW T 073 0.3
END DESCRIPTION:
XS GIS Cut Line= 5
      2250679.22      7153802.48      2250409.90      7153478.64
      2250361.29      7153447.13      2250154.00      7153585.00
      2249854.00      7154035.00
#Sta/Elev= 30
  4548.5  959.82  4728.0  950.84  4734.5  949.69  4898.6  947.12  4941.5  948.24
  4954.9  945.56  4964.4  940.09  4964.7  939.59  4968.6  940.09  4973.0  940.09
  4982.7  944.65  4997.7  948.01  5054.1  946.66  5081.2  949.14  5090.2  949.13
  5096.2  947.57  5111.2  950.37  5132.3  950.76  5204.4  949.46  5346.4  950.04
  5378.7  951.57  5405.8  951.23  5462.0  954.12  5652.2  956.97  5658.2  958.46
  5679.2  957.62  5739.3  959.79  5760.3  959.70  5766.3  958.39  5817.4  960.18
#Mann=5,-1,0
  4548.5    0.05       0  4964.4   0.033       0  4968.6    0.05       0
  5346.4    0.12       0  5462.0    0.05       0
Bank Sta=4964.4,4968.6
Exp/Cntr=0.3,0.1

Chan Stop Cuts=-1