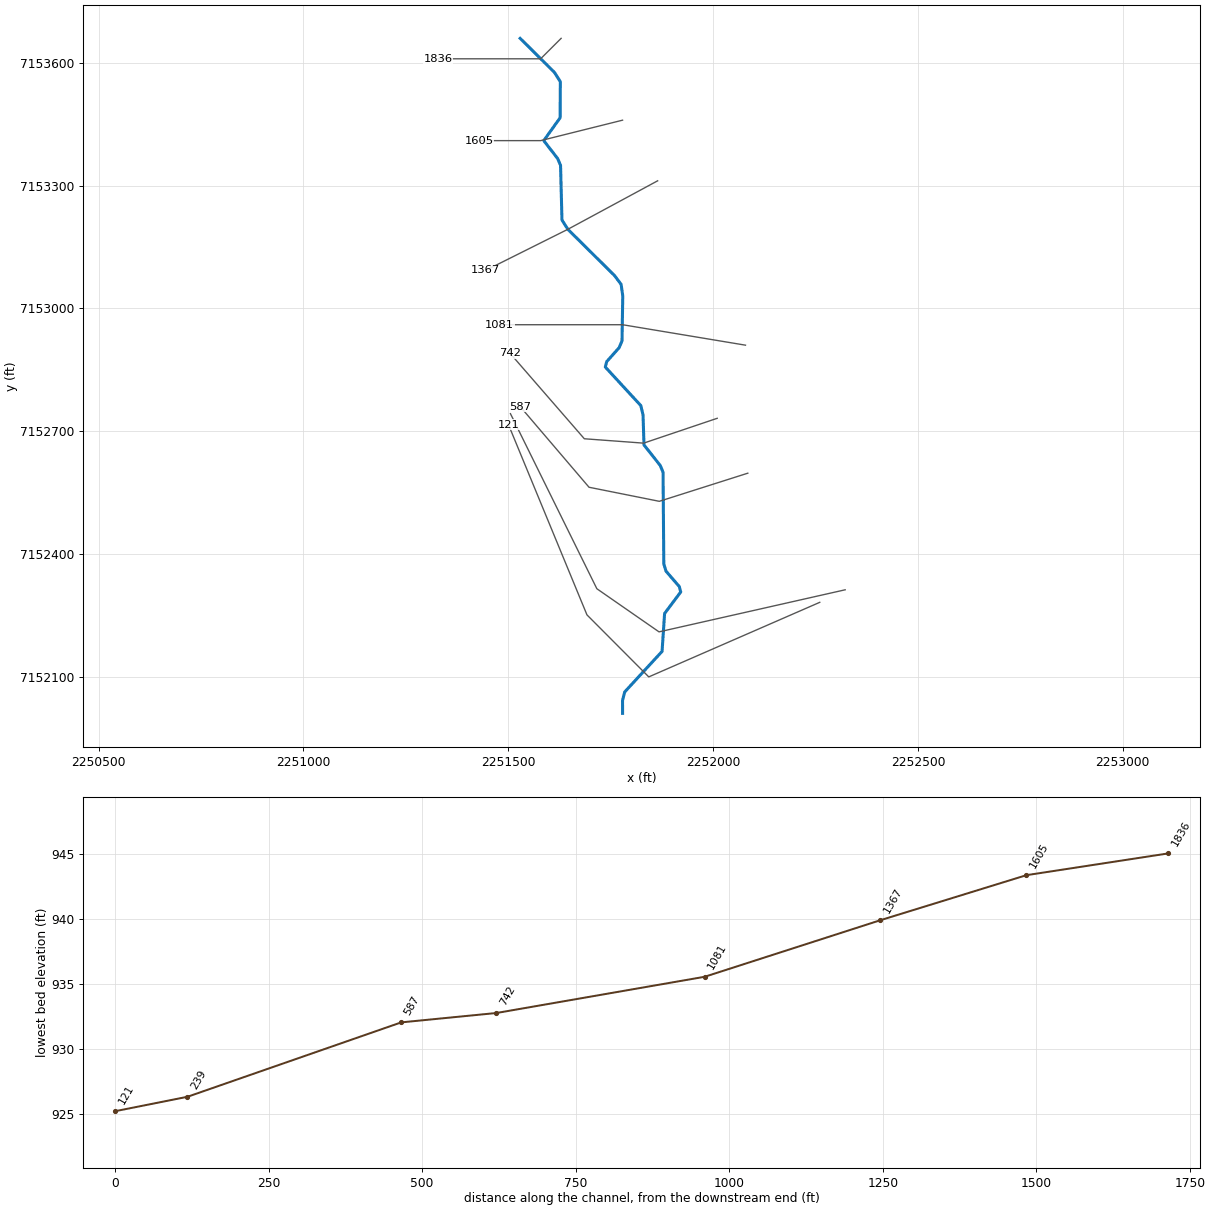
--- MDW T 074.prj (project) ---

Proj Title=MDW T 074 Base Level Engineering
Current Plan=p01
Default Exp/Contr=0.3,0.1
English Units
Geom File=g01
Flow File=f01
Plan File=p01
BEGIN DESCRIPTION:
MDW T 074
END DESCRIPTION:

--- MDW T 074.p01 (plan) ---

Plan Title=Multiple Run
Short Identifier=Multiple
Geom File=g01
Flow File=f01
Subcritical Flow
K Sum by GR= 0
Std Step Tol= 0.01
Critical Tol= 0.01
Num of Std Step Trials= 20
Max Error Tol= 0.3
Flow Tol Ratio= 0.001
Split Flow NTrial= 30
Split Flow Tol= 0.02
Split Flow Ratio= 0.02
Log Output Level= 0
Friction Slope Method= 1
Unsteady Friction Slope Method= 2
Unsteady Bridges Friction Slope Method= 1
Parabolic Critical Depth
Global Vel Dist=  1 , 1 , 1
Global Log Level= 0
CheckData=True
Encroach Param= -1, 0, 0, 0
BEGIN DESCRIPTION:
Multiple Run
END DESCRIPTION:

--- MDW T 074.f01 (steady flow) ---

Flow Title=Multiple
Number of Profiles=7
Profile Names=10-year,25-year,50-year,1pct_min,100-year,1pct_plu,500-year
River Rch & RM= MDW T 074,Reach-1,1836
     382     512     618     372     742    1480    1068
Boundary for River Rch & Prof#=MDW T 074,Reach-1,1
Up Type=0
Dn Type=3
Dn Slope=0.005
Boundary for River Rch & Prof#=MDW T 074,Reach-1,2
Up Type=0
Dn Type=3
Dn Slope=0.005
Boundary for River Rch & Prof#=MDW T 074,Reach-1,3
Up Type=0
Dn Type=3
Dn Slope=0.005
Boundary for River Rch & Prof#=MDW T 074,Reach-1,4
Up Type=0
Dn Type=3
Dn Slope=0.005
Boundary for River Rch & Prof#=MDW T 074,Reach-1,5
Up Type=0
Dn Type=3
Dn Slope=0.005
Boundary for River Rch & Prof#=MDW T 074,Reach-1,6
Up Type=0
Dn Type=3
Dn Slope=0.005
Boundary for River Rch & Prof#=MDW T 074,Reach-1,7
Up Type=0
Dn Type=3
Dn Slope=0.005

--- MDW T 074.g01 (geometry) ---

Geom Title=Existing Conditions

River Reach=MDW T 074,Reach-1
Reach XY= 30
      2251529.00      7153660.00      2251612.70      7153576.79
      2251627.07      7153554.12      2251626.64      7153465.89
      2251586.56      7153410.00      2251620.54      7153366.18
      2251627.60      7153349.56      2251631.07      7153215.86
      2251645.43      7153193.24      2251759.40      7153080.16
      2251775.47      7153058.53      2251779.46      7153030.17
      2251777.62      7152920.44      2251770.53      7152903.81
      2251740.34      7152869.85      2251736.81      7152856.59
      2251823.45      7152762.43      2251828.87      7152739.95
      2251831.36      7152665.98      2251870.86      7152616.06
      2251877.78      7152599.50      2251879.66      7152375.16
      2251885.02      7152357.55      2251917.53      7152319.90
      2251920.92      7152306.70      2251881.55      7152254.10
      2251875.39      7152161.50      2251784.33      7152062.51
      2251778.93      7152041.88      2251779.00      7152010.00

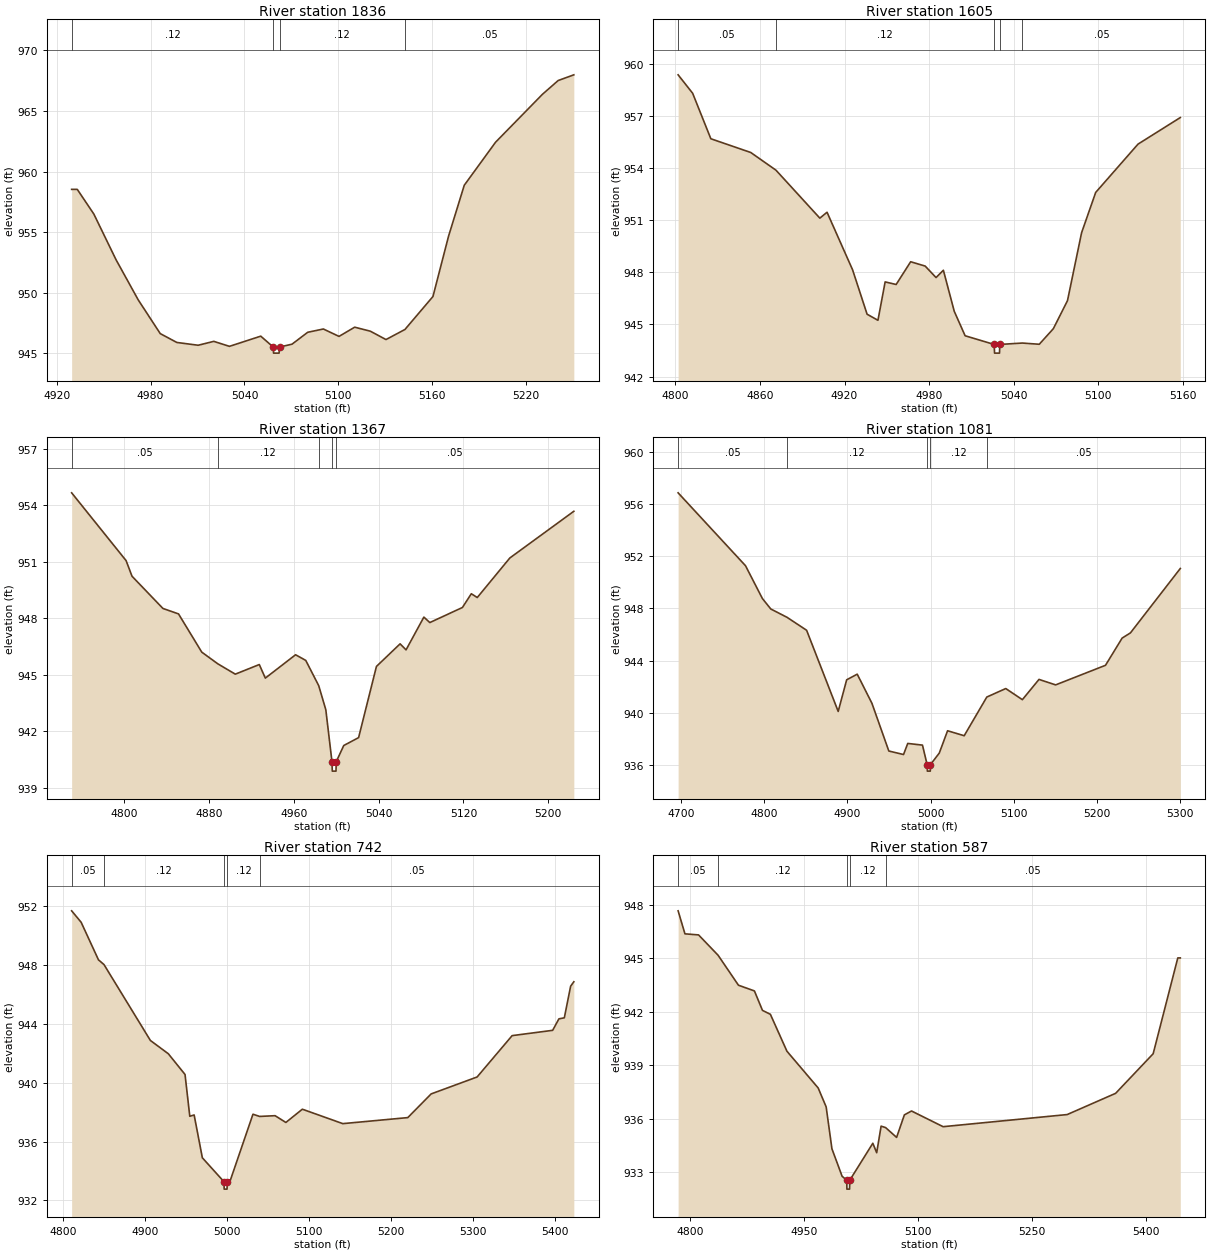
Type RM Length L Ch R = 1,1836,231,231,231
BEGIN DESCRIPTION:
MDW T 074 6.0
END DESCRIPTION:
XS GIS Cut Line= 3
      2251629.03      7153660.03      2251579.00      7153610.00
      2251328.95      7153610.00
#Sta/Elev= 30
  4929.6  958.53  4933.2  958.53  4943.8  956.49  4957.9  952.74  4972.1  949.42
  4986.2  946.63  4996.8  945.90  5010.4  945.67  5020.4  945.99  5030.4  945.58
  5050.4  946.42  5058.4  945.52  5058.6  945.02  5062.1  945.02  5062.4  945.52
  5070.4  945.76  5080.4  946.74  5090.4  947.01  5100.4  946.40  5110.4  947.16
  5120.4  946.83  5130.4  946.14  5142.5  946.97  5160.4  949.69  5170.4  954.68
  5180.4  958.87  5200.4  962.42  5230.4  966.38  5240.4  967.51  5250.4  967.98
#Mann=4,-1,0
  4929.6    0.12       0  5058.4    0.07       0  5062.4    0.12       0
  5142.5    0.05       0
Bank Sta=5058.4,5062.4
Exp/Cntr=0.3,0.1

Type RM Length L Ch R = 1,1605,238,238,238
BEGIN DESCRIPTION:
MDW T 074 5.0
END DESCRIPTION:
XS GIS Cut Line= 3
      2251778.96      7153459.99      2251579.00      7153410.00
      2251429.02      7153410.00
#Sta/Elev= 30
  4802.0  959.37  4812.3  958.31  4825.2  955.69  4853.5  954.90  4871.4  953.88
  4902.5  951.12  4907.6  951.46  4925.7  948.15  4936.0  945.59  4943.7  945.24
  4948.8  947.45  4956.6  947.30  4966.9  948.61  4977.2  948.36  4984.9  947.70
  4990.1  948.12  4997.8  945.76  5005.5  944.35  5026.1  943.85  5026.4  943.35
  5029.9  943.35  5030.1  943.85  5046.1  943.93  5058.1  943.86  5068.1  944.76
  5078.1  946.37  5088.1  950.28  5098.1  952.60  5128.1  955.38  5158.1  956.91
#Mann=5,-1,0
  4802.0    0.05       0  4871.4    0.12       0  5026.1    0.07       0
  5030.1    0.12       0  5046.1    0.05       0
Bank Sta=5026.1,5030.1
Exp/Cntr=0.3,0.1

Type RM Length L Ch R = 1,1367,286,286,286
BEGIN DESCRIPTION:
MDW T 074 4.0
END DESCRIPTION:
XS GIS Cut Line= 3
      2251864.62      7153311.79      2251645.43      7153193.24
      2251445.11      7153093.01
#Sta/Elev= 30
  4750.8  954.67  4802.1  951.07  4807.7  950.24  4836.8  948.53  4851.5  948.24
  4873.4  946.21  4888.5  945.59  4905.0  945.04  4927.6  945.55  4933.3  944.83
  4961.8  946.07  4971.4  945.77  4983.6  944.43  4990.3  943.15  4996.1  940.39
  4996.4  939.89  4999.9  939.89  5000.1  940.39  5007.2  941.25  5021.2  941.67
  5038.0  945.45  5060.3  946.65  5065.9  946.33  5082.7  948.07  5088.3  947.78
  5119.0  948.58  5127.4  949.31  5133.0  949.11  5163.7  951.21  5224.0  953.69
#Mann=5,-1,0
  4750.8    0.05       0  4888.5    0.12       0  4983.6    0.05       0
  4996.1    0.04       0  5000.1    0.05       0
Bank Sta=4996.1,5000.1
Exp/Cntr=0.3,0.1

Type RM Length L Ch R = 1,1081,339,339,339
BEGIN DESCRIPTION:
MDW T 074 3.0
END DESCRIPTION:
XS GIS Cut Line= 3
      2252079.02      7152910.00      2251779.00      7152960.00
      2251478.96      7152960.00
#Sta/Elev= 30
  4696.3  956.85  4777.4  951.27  4797.7  948.76  4807.8  947.96  4827.4  947.32
  4850.9  946.33  4888.9  940.12  4899.1  942.54  4911.8  942.97  4929.5  940.74
  4949.8  937.09  4967.5  936.82  4972.6  937.67  4990.3  937.54  4995.9  936.05
  4996.2  935.55  4999.7  935.55  4999.9  936.05  5010.5  936.93  5020.5  938.64
  5040.5  938.26  5067.7  941.22  5090.5  941.87  5110.5  941.02  5130.5  942.57
  5150.5  942.15  5210.5  943.65  5230.5  945.73  5240.5  946.13  5300.5  951.06
#Mann=5,-1,0
  4696.3    0.05       0  4827.4    0.12       0  4995.9    0.07       0
  4999.9    0.12       0  5067.7    0.05       0
Bank Sta=4995.9,4999.9
Exp/Cntr=0.3,0.1

Type RM Length L Ch R = 1,742,155,155,155
BEGIN DESCRIPTION:
MDW T 074 2.0
END DESCRIPTION:
XS GIS Cut Line= 4
      2252009.96      7152731.25      2251830.34      7152670.55
      2251685.64      7152681.25      2251503.85      7152890.79
#Sta/Elev= 30
  4810.4  951.68  4822.0  950.90  4843.1  948.35  4849.8  948.03  4906.4  942.87
  4928.2  941.97  4948.6  940.56  4954.4  937.72  4959.7  937.81  4969.7  934.90
  4996.1  933.27  4996.3  932.77  4999.8  932.77  5000.1  933.27  5003.2  933.27
  5031.4  937.86  5039.5  937.71  5058.4  937.76  5071.5  937.30  5091.6  938.20
  5140.9  937.22  5220.1  937.63  5248.6  939.24  5304.6  940.39  5347.3  943.20
  5396.7  943.56  5404.3  944.34  5410.9  944.41  5418.6  946.56  5422.5  946.86
#Mann=5,-1,0
  4810.4    0.05       0  4849.8    0.12       0  4996.1    0.07       0
  5000.1    0.12       0  5039.5    0.05       0
Bank Sta=4996.1,5000.1
Exp/Cntr=0.3,0.1

Type RM Length L Ch R = 1,587,348,348,348
BEGIN DESCRIPTION:
MDW T 074 1.0
END DESCRIPTION:
XS GIS Cut Line= 4
      2252084.65      7152597.10      2251868.65      7152528.34
      2251697.12      7152562.71      2251529.01      7152759.99
#Sta/Elev= 30
  4784.4  947.65  4793.4  946.36  4811.3  946.30  4837.0  945.16  4863.8  943.48
  4884.8  943.16  4895.4  942.07  4905.8  941.85  4927.6  939.78  4968.7  937.72
  4979.2  936.66  4986.8  934.31  5000.2  932.77  5006.3  932.55  5006.5  932.05
  5010.0  932.05  5010.3  932.55  5040.6  934.62  5045.7  934.09  5051.5  935.58
  5057.4  935.50  5071.9  934.95  5082.1  936.21  5091.5  936.43  5133.1  935.55
  5296.4  936.23  5360.1  937.42  5409.5  939.64  5441.9  945.01  5445.2  945.01
#Mann=5,-1,0
  4784.4    0.05       0  4837.0    0.12       0  5006.3    0.07       0
  5010.3    0.12       0  5057.4    0.05       0
Bank Sta=5006.3,5010.3
Exp/Cntr=0.3,0.1

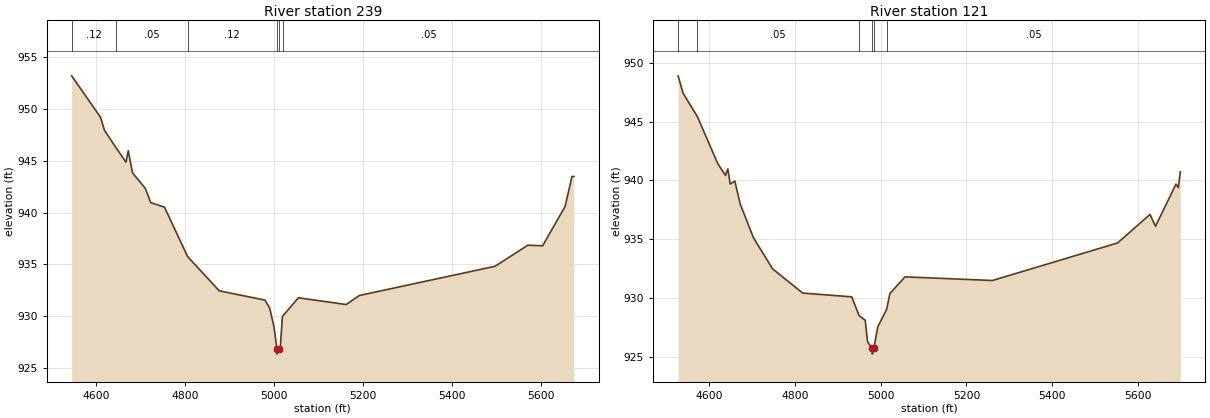
Type RM Length L Ch R = 1,239,118,118,118
BEGIN DESCRIPTION:
MDW T 074 0.5
END DESCRIPTION:
XS GIS Cut Line= 4
      2252322.32      7152312.08      2251867.95      7152209.24
      2251716.22      7152314.68      2251505.30      7152742.59
#Sta/Elev= 30
  4545.5  953.21  4610.4  949.21  4619.2  947.95  4645.8  946.23  4667.5  944.88
  4672.6  945.98  4682.2  943.84  4710.7  942.36  4723.2  940.96  4753.8  940.54
  4805.9  935.76  4877.0  932.45  4979.5  931.56  4990.1  930.80  5000.0  928.95
  5006.3  926.84  5006.5  926.34  5010.3  926.84  5013.8  926.84  5018.8  929.99
  5020.2  930.05  5054.6  931.78  5162.0  931.13  5191.4  932.00  5496.3  934.82
  5570.0  936.86  5603.1  936.80  5653.6  940.60  5669.0  943.49  5673.2  943.49
#Mann=6,-1,0
  4545.5    0.12       0  4645.8    0.05       0  4805.9    0.12       0
  5006.3    0.07       0  5010.3    0.12       0  5020.2    0.05       0
Bank Sta=5006.3,5010.3
Exp/Cntr=0.3,0.1

Type RM Length L Ch R = 1,121,0,0,0
BEGIN DESCRIPTION:
MDW T 074 0.2
END DESCRIPTION:
XS GIS Cut Line= 4
      2252260.30      7152281.44      2251842.95      7152099.17
      2251692.10      7152250.72      2251500.62      7152715.38
#Sta/Elev= 30
  4527.2  948.89  4538.7  947.42  4572.2  945.42  4619.8  941.42  4637.7  940.43
  4643.2  940.98  4648.7  939.69  4659.6  939.94  4672.1  937.99  4703.2  935.11
  4747.7  932.48  4818.0  930.42  4932.4  930.10  4949.4  928.51  4963.8  928.11
  4969.3  926.27  4980.0  925.73  4980.3  925.23  4984.0  925.73  4993.1  927.55
  5013.9  929.05  5021.3  930.38  5056.7  931.80  5260.6  931.49  5552.6  934.68
  5628.3  937.11  5641.1  936.10  5689.0  939.69  5694.4  939.39  5699.0  940.73
#Mann=6,-1,0
  4527.2    0.12       0  4572.2    0.05       0  4949.4    0.12       0
  4980.0    0.07       0  4984.0    0.12       0  5013.9    0.05       0
Bank Sta=4980,4984
Exp/Cntr=0.3,0.1

Chan Stop Cuts=-1