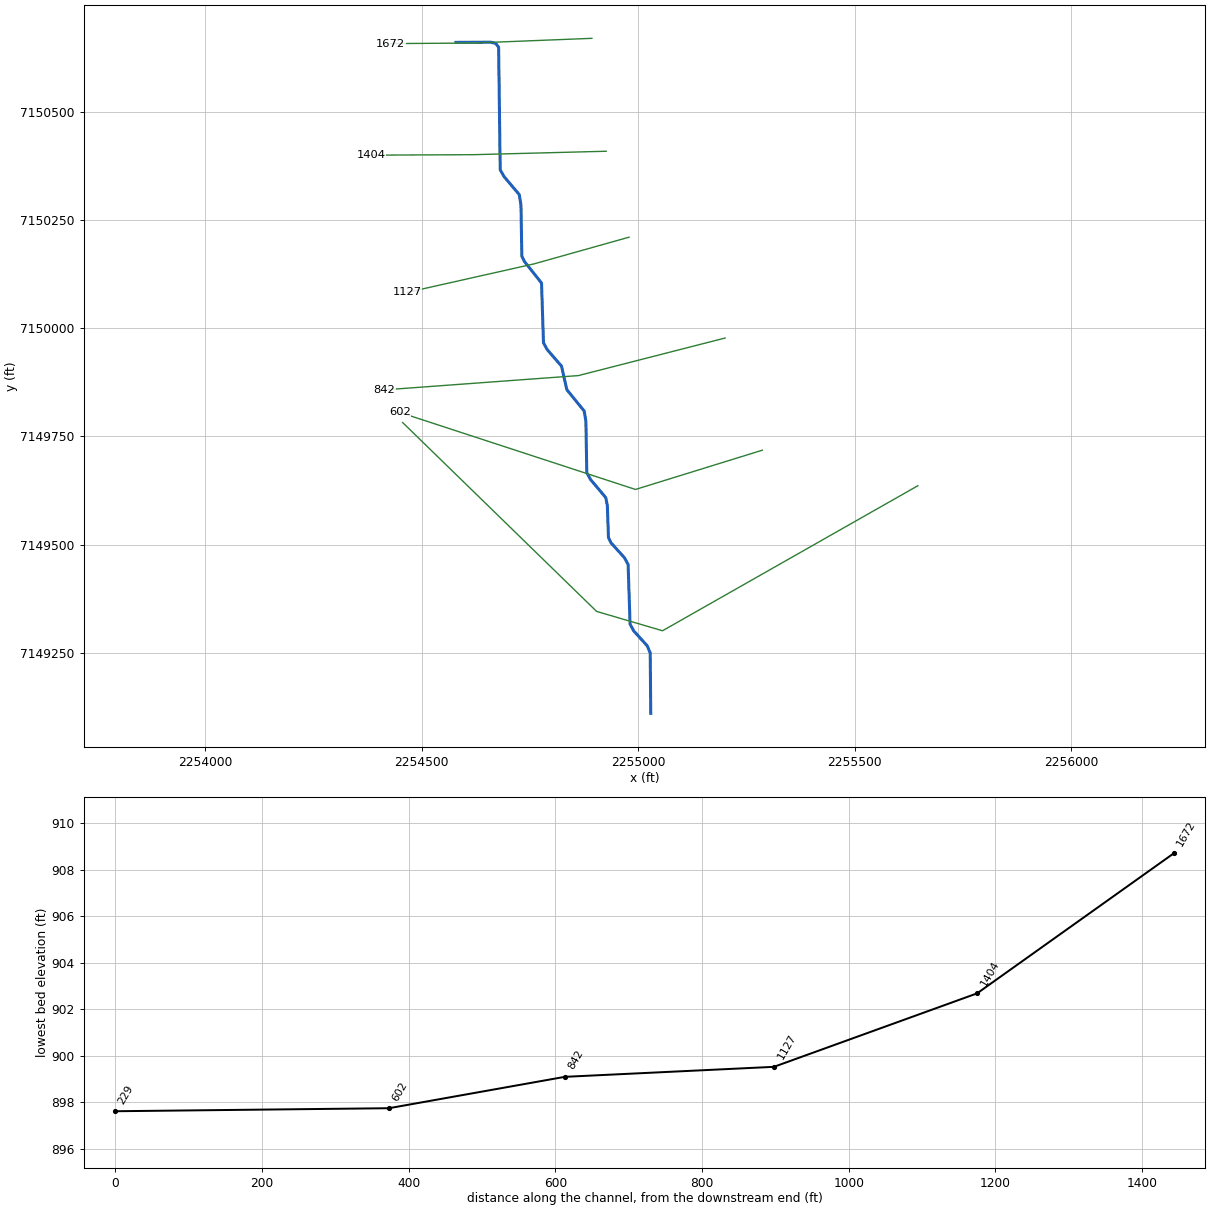
--- MDW T 075.prj (project) ---

Proj Title=MDW T 075 Base Level Engineering
Current Plan=p01
Default Exp/Contr=0.3,0.1
English Units
Geom File=g01
Flow File=f01
Plan File=p01
BEGIN DESCRIPTION:
MDW T 075
END DESCRIPTION:

--- MDW T 075.p01 (plan) ---

Plan Title=Multiple Run
Short Identifier=Multiple
Geom File=g01
Flow File=f01
Subcritical Flow
K Sum by GR= 0
Std Step Tol= 0.01
Critical Tol= 0.01
Num of Std Step Trials= 20
Max Error Tol= 0.3
Flow Tol Ratio= 0.001
Split Flow NTrial= 30
Split Flow Tol= 0.02
Split Flow Ratio= 0.02
Log Output Level= 0
Friction Slope Method= 1
Unsteady Friction Slope Method= 2
Unsteady Bridges Friction Slope Method= 1
Parabolic Critical Depth
Global Vel Dist=  1 , 1 , 1
Global Log Level= 0
CheckData=True
Encroach Param= -1, 0, 0, 0
BEGIN DESCRIPTION:
Multiple Run
END DESCRIPTION:

--- MDW T 075.f01 (steady flow) ---

Flow Title=Multiple
Number of Profiles=7
Profile Names=10-year,25-year,50-year,1pct_min,100-year,1pct_plu,500-year
River Rch & RM= MDW T 075,Reach-1,1672
     437     591     718     434     867    1729    1262
Boundary for River Rch & Prof#=MDW T 075,Reach-1,1
Up Type=0
Dn Type=3
Dn Slope=0.005
Boundary for River Rch & Prof#=MDW T 075,Reach-1,2
Up Type=0
Dn Type=3
Dn Slope=0.005
Boundary for River Rch & Prof#=MDW T 075,Reach-1,3
Up Type=0
Dn Type=3
Dn Slope=0.005
Boundary for River Rch & Prof#=MDW T 075,Reach-1,4
Up Type=0
Dn Type=3
Dn Slope=0.005
Boundary for River Rch & Prof#=MDW T 075,Reach-1,5
Up Type=0
Dn Type=3
Dn Slope=0.005
Boundary for River Rch & Prof#=MDW T 075,Reach-1,6
Up Type=0
Dn Type=3
Dn Slope=0.005
Boundary for River Rch & Prof#=MDW T 075,Reach-1,7
Up Type=0
Dn Type=3
Dn Slope=0.005

--- MDW T 075.g01 (geometry) ---

Geom Title=Existing Conditions

River Reach=MDW T 075,Reach-1
Reach XY= 30
      2254579.00      7150660.00      2254659.46      7150660.46
      2254671.37      7150657.37      2254677.62      7150648.62
      2254681.26      7150365.94      2254689.85      7150350.35
      2254725.21      7150308.43      2254729.18      7150285.07
      2254731.27      7150165.94      2254737.15      7150153.95
      2254776.73      7150104.06      2254781.25      7149965.93
      2254789.80      7149950.33      2254822.88      7149912.18
      2254835.12      7149857.82      2254875.24      7149808.44
      2254879.19      7149785.08      2254881.27      7149665.94
      2254889.85      7149650.35      2254925.14      7149608.40
      2254928.76      7149589.90      2254931.36      7149515.98
      2254937.19      7149503.97      2254968.15      7149469.65
      2254976.73      7149454.06      2254981.27      7149315.94
      2254989.85      7149300.35      2255020.87      7149266.06
      2255027.83      7149249.52      2255029.00      7149110.00

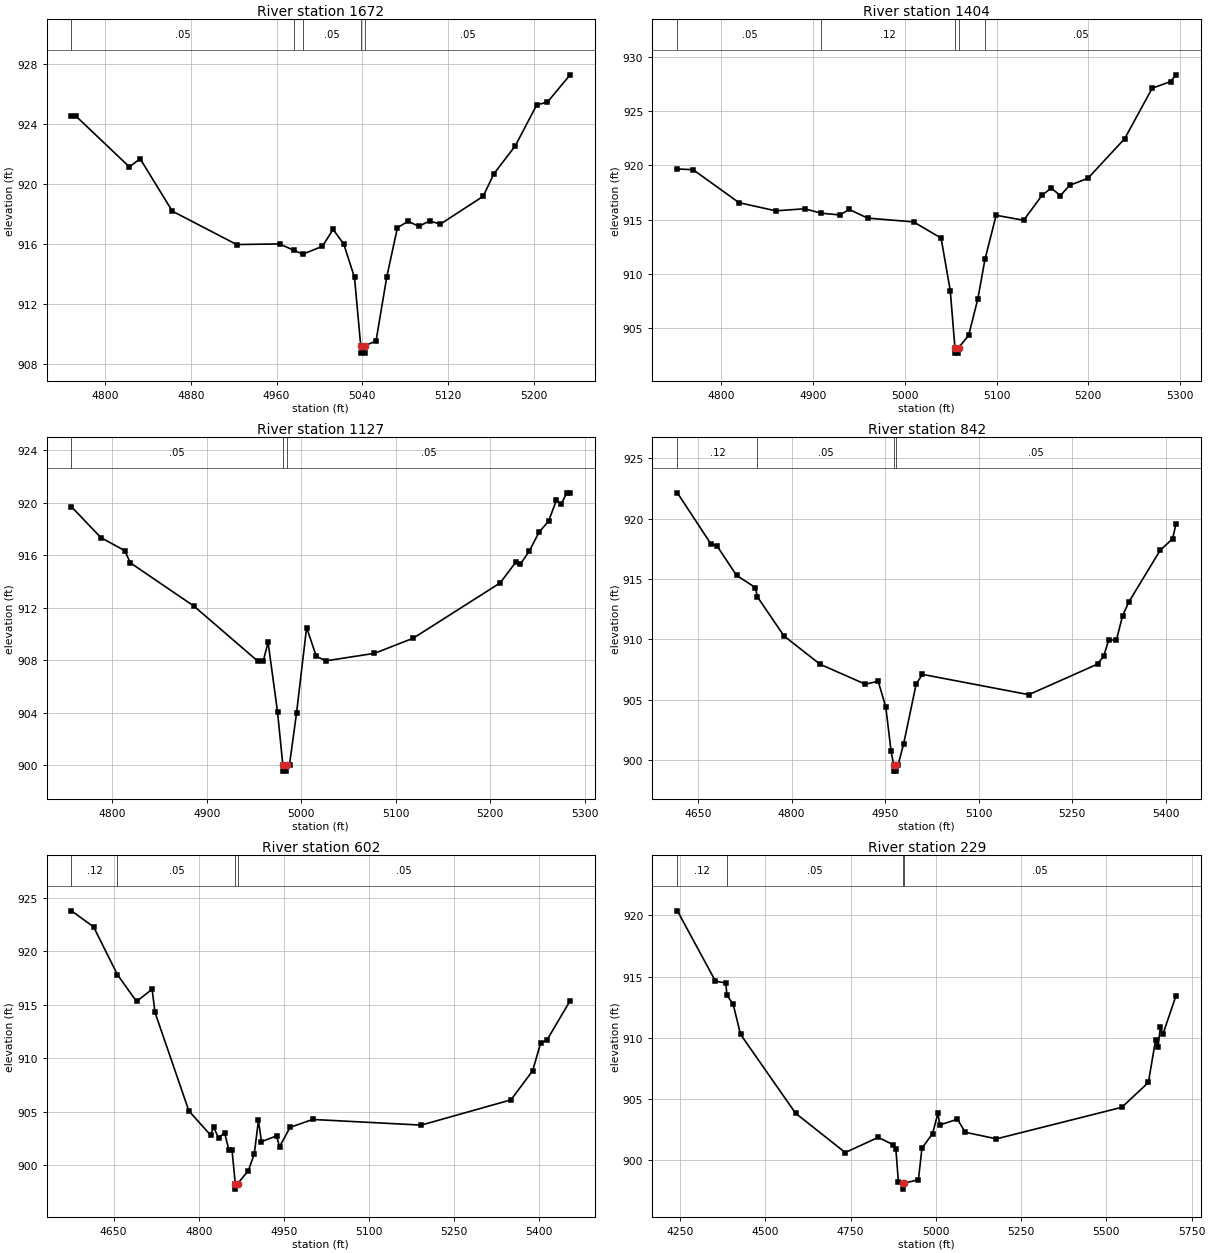
Type RM Length L Ch R = 1,1672,268,268,268
BEGIN DESCRIPTION:
MDW T 075 5.0
END DESCRIPTION:
XS GIS Cut Line= 3
      2254893.04      7150669.31      2254618.50      7150658.43
      2254427.76      7150657.16
#Sta/Elev= 30
  4768.5  924.51  4773.0  924.51  4822.6  921.14  4832.6  921.69  4862.6  918.19
  4922.7  915.96  4962.7  916.00  4975.9  915.58  4984.5  915.32  5002.7  915.84
  5012.7  916.97  5022.7  915.99  5032.7  913.76  5038.5  909.21  5038.7  908.71
  5042.2  908.71  5042.5  909.21  5052.8  909.52  5062.8  913.79  5072.8  917.09
  5082.8  917.51  5092.8  917.17  5102.8  917.54  5112.8  917.32  5152.8  919.18
  5162.8  920.68  5182.8  922.55  5202.8  925.28  5212.8  925.47  5234.0  927.29
#Mann=5,-1,0
  4768.5    0.05       0  4975.9    0.12       0  4984.5    0.05       0
  5038.5   0.033       0  5042.5    0.05       0
Bank Sta=5038.5,5042.5
Exp/Cntr=0.3,0.1

Type RM Length L Ch R = 1,1404,277,277,277
BEGIN DESCRIPTION:
MDW T 075 4.0
END DESCRIPTION:
XS GIS Cut Line= 3
      2254926.18      7150408.50      2254619.72      7150400.56
      2254382.99      7150399.48
#Sta/Elev= 30
  4752.3  919.67  4769.5  919.60  4819.5  916.56  4859.5  915.81  4891.0  916.00
  4909.2  915.59  4929.5  915.43  4939.5  915.94  4959.5  915.14  5009.6  914.79
  5039.6  913.30  5049.6  908.46  5054.7  903.19  5055.0  902.69  5058.5  902.69
  5058.7  903.19  5069.6  904.32  5079.6  907.67  5087.4  911.33  5099.6  915.40
  5129.6  914.94  5149.6  917.24  5159.6  917.91  5169.6  917.21  5179.6  918.16
  5199.6  918.81  5239.6  922.46  5269.6  927.11  5289.6  927.73  5295.6  928.35
#Mann=5,-1,0
  4752.3    0.05       0  4909.2    0.12       0  5054.7    0.07       0
  5058.7    0.12       0  5087.4    0.05       0
Bank Sta=5054.7,5058.7
Exp/Cntr=0.3,0.1

Type RM Length L Ch R = 1,1127,285,285,285
BEGIN DESCRIPTION:
MDW T 075 3.0
END DESCRIPTION:
XS GIS Cut Line= 3
      2254979.04      7150210.01      2254759.39      7150148.31
      2254466.74      7150082.51
#Sta/Elev= 30
  4756.6  919.69  4787.8  917.33  4812.9  916.35  4819.0  915.41  4886.3  912.11
  4954.0  907.91  4959.6  907.89  4964.8  909.36  4974.8  904.05  4980.4  900.03
  4980.6  899.53  4984.1  899.53  4984.4  900.03  4987.5  900.03  4995.0  903.99
  5005.6  910.48  5015.9  908.28  5026.1  907.94  5077.4  908.51  5118.4  909.66
  5210.6  913.88  5226.9  915.44  5232.0  915.32  5241.4  916.30  5251.6  917.73
  5261.9  918.60  5270.2  920.19  5275.3  919.87  5281.0  920.75  5284.7  920.75
#Mann=3,-1,0
  4756.6    0.05       0  4980.4   0.033       0  4984.4    0.05       0
Bank Sta=4980.4,4984.4
Exp/Cntr=0.3,0.1

Type RM Length L Ch R = 1,842,240,240,240
BEGIN DESCRIPTION:
MDW T 075 2.0
END DESCRIPTION:
XS GIS Cut Line= 3
      2255200.80      7149977.04      2254861.82      7149890.26
      2254413.54      7149857.29
#Sta/Elev= 30
  4616.9  922.14  4670.5  917.92  4680.7  917.72  4711.7  915.31  4741.8  914.30
  4745.3  913.52  4787.8  910.29  4845.9  907.94  4918.1  906.30  4938.8  906.54
  4951.0  904.41  4959.4  900.78  4963.7  899.60  4963.9  899.10  4967.4  899.10
  4967.7  899.60  4970.7  899.60  4979.7  901.38  4999.7  906.31  5009.7  907.11
  5180.2  905.43  5290.5  907.96  5300.5  908.64  5308.4  909.97  5320.6  909.93
  5330.6  911.96  5340.6  913.10  5390.8  917.38  5410.8  918.34  5416.3  919.59
#Mann=4,-1,0
  4616.9    0.12       0  4745.3    0.05       0  4963.7   0.033       0
  4967.7    0.05       0
Bank Sta=4963.7,4967.7
Exp/Cntr=0.3,0.1

Type RM Length L Ch R = 1,602,373,373,373
BEGIN DESCRIPTION:
MDW T 075 1.0
END DESCRIPTION:
XS GIS Cut Line= 3
      2255286.78      7149717.94      2254993.76      7149627.24
      2254449.74      7149805.10
#Sta/Elev= 30
  4575.7  923.79  4614.7  922.29  4656.8  917.81  4690.4  915.31  4717.8  916.45
  4723.0  914.28  4782.7  905.06  4820.9  902.81  4826.1  903.55  4835.1  902.54
  4845.6  903.01  4853.5  901.37  4858.7  901.41  4864.5  898.25  4864.7  897.75
  4868.5  898.25  4887.6  899.49  4898.0  901.05  4905.3  904.18  4910.6  902.19
  4937.2  902.73  4942.5  901.72  4961.1  903.53  5000.9  904.27  5192.2  903.74
  5350.4  906.10  5388.7  908.83  5403.0  911.46  5413.5  911.66  5454.8  915.38
#Mann=4,-1,0
  4575.7    0.12       0  4656.8    0.05       0  4864.5   0.033       0
  4868.5    0.05       0
Bank Sta=4864.5,4868.5
Exp/Cntr=0.3,0.1

Type RM Length L Ch R = 1,229,0,0,0
BEGIN DESCRIPTION:
MDW T 075 0.5
END DESCRIPTION:
XS GIS Cut Line= 4
      2255646.09      7149635.88      2255056.26      7149300.85
      2254903.93      7149345.54      2254456.02      7149781.73
#Sta/Elev= 30
  4242.0  920.37  4353.7  914.62  4384.0  914.47  4387.4  913.46  4405.6  912.74
  4427.2  910.27  4588.7  903.82  4734.3  900.61  4830.9  901.85  4874.2  901.26
  4882.7  900.88  4890.1  898.24  4903.7  898.12  4903.9  897.62  4907.7  898.12
  4948.8  898.38  4959.2  900.97  4990.4  902.16  5006.1  903.85  5011.3  902.86
  5063.4  903.34  5085.9  902.27  5177.7  901.73  5545.5  904.31  5623.2  906.34
  5644.3  909.82  5651.5  909.23  5658.4  910.87  5665.6  910.27  5704.3  913.44
#Mann=4,-1,0
  4242.0    0.12       0  4387.4    0.05       0  4903.7   0.033       0
  4907.7    0.05       0
Bank Sta=4903.7,4907.7
Exp/Cntr=0.3,0.1

Chan Stop Cuts=-1