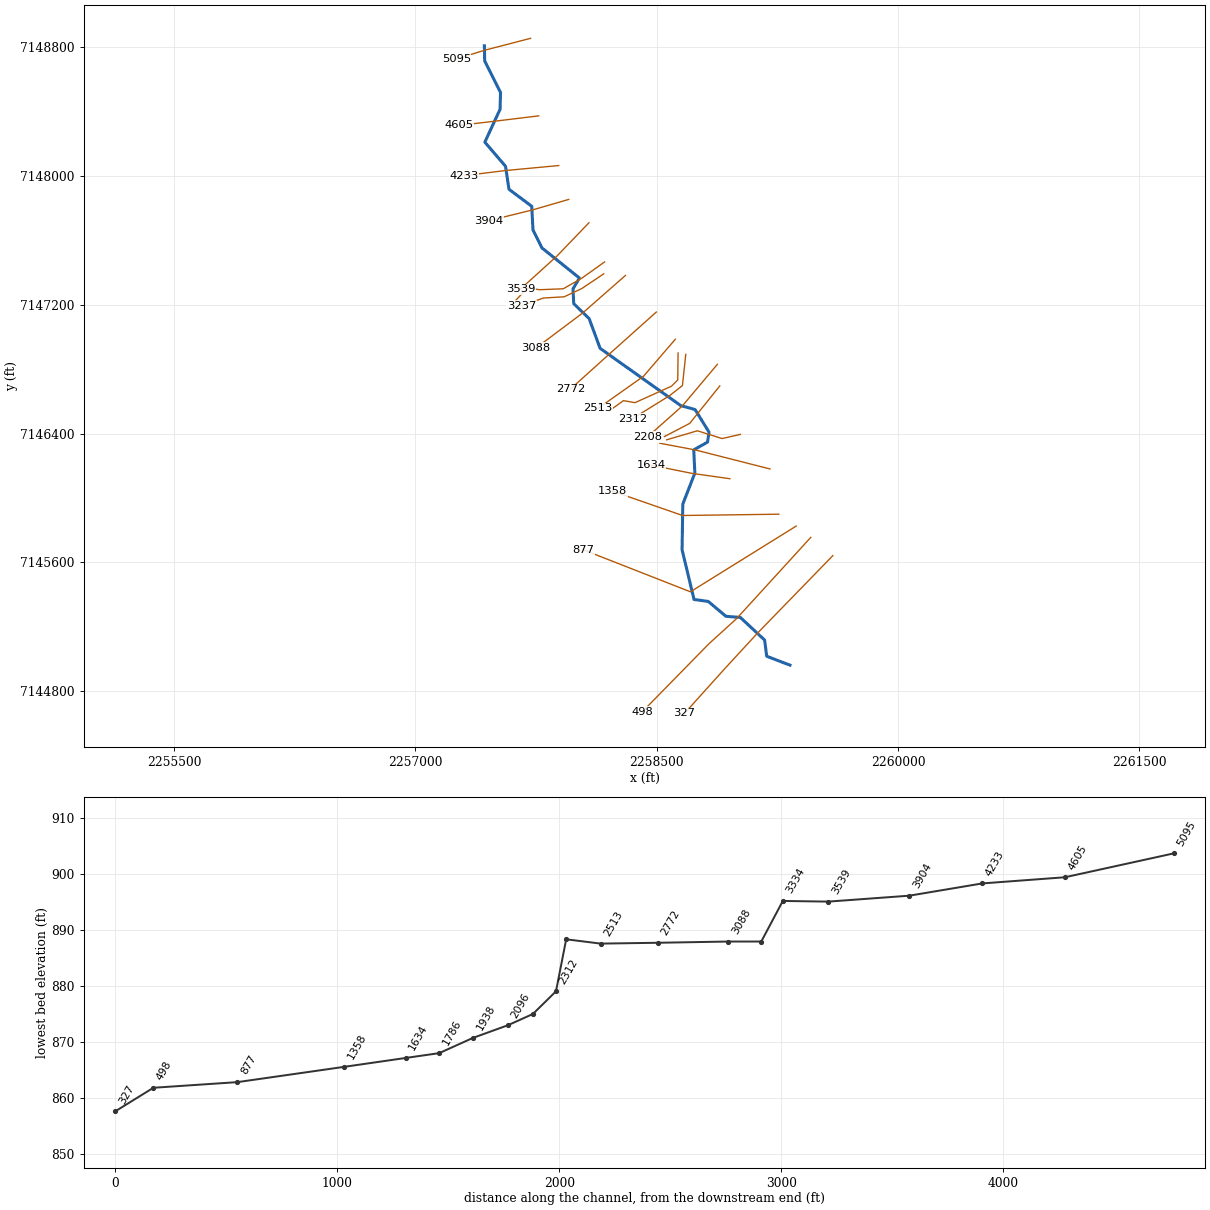
--- MDW T 076.prj (project) ---

Proj Title=MDW T 076 Base Level Engineering
Current Plan=p01
Default Exp/Contr=0.3,0.1
English Units
Geom File=g01
Flow File=f01
Plan File=p01
BEGIN DESCRIPTION:
MDW T 076
END DESCRIPTION:

--- MDW T 076.p01 (plan) ---

Plan Title=Multiple Run
Short Identifier=Multiple
Geom File=g01
Flow File=f01
Subcritical Flow
K Sum by GR= 0
Std Step Tol= 0.01
Critical Tol= 0.01
Num of Std Step Trials= 20
Max Error Tol= 0.3
Flow Tol Ratio= 0.001
Split Flow NTrial= 30
Split Flow Tol= 0.02
Split Flow Ratio= 0.02
Log Output Level= 0
Friction Slope Method= 1
Unsteady Friction Slope Method= 2
Unsteady Bridges Friction Slope Method= 1
Parabolic Critical Depth
Global Vel Dist=  1 , 1 , 1
Global Log Level= 0
CheckData=True
Encroach Param= -1, 0, 0, 0
BEGIN DESCRIPTION:
Multiple Run
END DESCRIPTION:

--- MDW T 076.f01 (steady flow) ---

Flow Title=Multiple
Number of Profiles=7
Profile Names=10-year,25-year,50-year,1pct_min,100-year,1pct_plu,500-year
River Rch & RM= MDW T 076,Reach-1,5095
     641     885    1088     665    1326    2646    1974
Boundary for River Rch & Prof#=MDW T 076,Reach-1,1
Up Type=0
Dn Type=3
Dn Slope=0.005
Boundary for River Rch & Prof#=MDW T 076,Reach-1,2
Up Type=0
Dn Type=3
Dn Slope=0.005
Boundary for River Rch & Prof#=MDW T 076,Reach-1,3
Up Type=0
Dn Type=3
Dn Slope=0.005
Boundary for River Rch & Prof#=MDW T 076,Reach-1,4
Up Type=0
Dn Type=3
Dn Slope=0.005
Boundary for River Rch & Prof#=MDW T 076,Reach-1,5
Up Type=0
Dn Type=3
Dn Slope=0.005
Boundary for River Rch & Prof#=MDW T 076,Reach-1,6
Up Type=0
Dn Type=3
Dn Slope=0.005
Boundary for River Rch & Prof#=MDW T 076,Reach-1,7
Up Type=0
Dn Type=3
Dn Slope=0.005

--- MDW T 076.g01 (geometry) ---

Geom Title=Existing Conditions

River Reach=MDW T 076,Reach-1
Reach XY= 30
      2257429.00      7148810.00      2257431.07      7148715.86
      2257529.50      7148520.17      2257526.77      7148415.93
      2257432.04      7148211.42      2257560.60      7148060.89
      2257582.07      7147918.30      2257723.54      7147812.46
      2257731.25      7147665.93      2257787.02      7147553.66
      2258019.87      7147366.74      2257980.27      7147299.52
      2257984.39      7147207.56      2258080.63      7147113.97
      2258148.49      7146929.49      2258650.84      7146572.97
      2258738.70      7146549.23      2258825.70      7146408.24
      2258815.95      7146346.46      2258730.63      7146298.16
      2258737.45      7146153.82      2258662.48      7145961.12
      2258658.14      7145677.27      2258732.43      7145368.17
      2258820.43      7145356.46      2258930.63      7145263.84
      2259020.52      7145256.51      2259171.12      7145116.14
      2259184.22      7145015.42      2259329.00      7144960.00

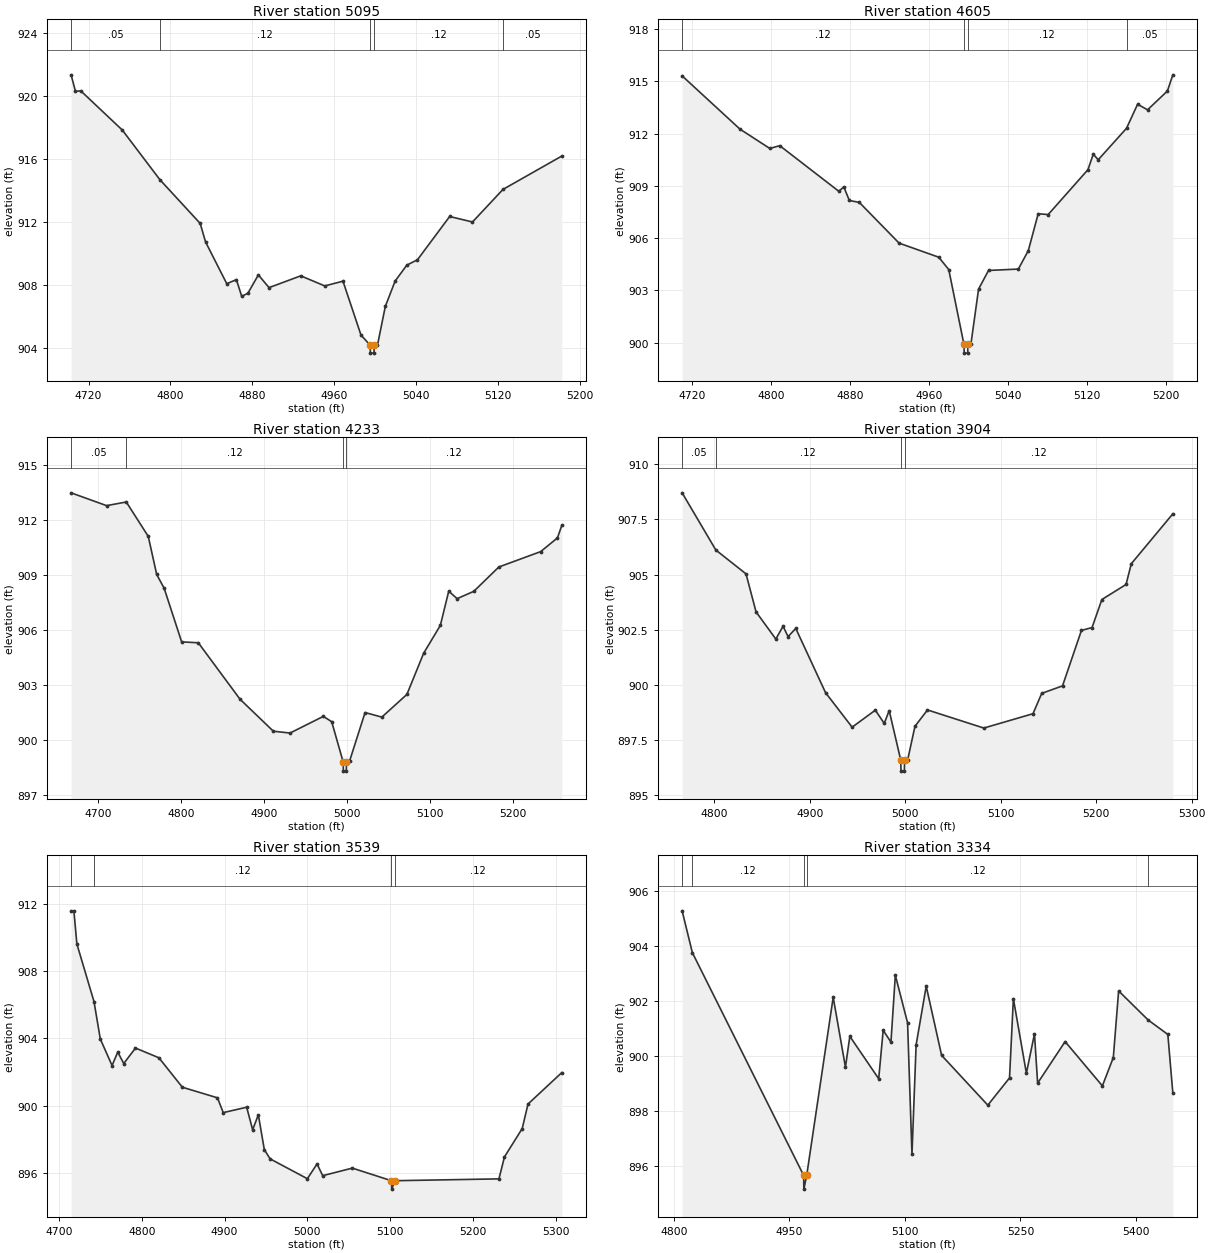
Type RM Length L Ch R = 1,5095,490,490,490
BEGIN DESCRIPTION:
MDW T 076 13.0
END DESCRIPTION:
XS GIS Cut Line= 3
      2257716.30      7148856.58      2257428.68      7148782.12
      2257254.30      7148727.93
#Sta/Elev= 30
  4702.9  921.33  4707.2  920.28  4712.4  920.31  4753.0  917.82  4789.7  914.67
  4829.1  911.89  4834.4  910.71  4855.1  908.06  4864.5  908.32  4869.7  907.26
  4875.7  907.45  4886.0  908.62  4896.4  907.81  4927.4  908.56  4950.9  907.92
  4968.7  908.22  4986.3  904.80  4995.3  904.15  4995.5  903.65  4999.0  903.65
  4999.3  904.15  5002.4  904.15  5010.1  906.62  5019.7  908.23  5031.1  909.24
  5041.5  909.58  5073.0  912.33  5095.3  911.98  5125.1  914.05  5182.6  916.17
#Mann=5,-1,0
  4702.9    0.05       0  4789.7    0.12       0  4995.3    0.07       0
  4999.3    0.12       0  5125.1    0.05       0
Bank Sta=4995.3,4999.3
Exp/Cntr=0.3,0.1

Type RM Length L Ch R = 1,4605,372,372,372
BEGIN DESCRIPTION:
MDW T 076 12.0
END DESCRIPTION:
XS GIS Cut Line= 3
      2257767.15      7148374.67      2257479.46      7148339.74
      2257273.56      7148315.68
#Sta/Elev= 30
  4710.2  915.32  4768.8  912.26  4799.0  911.15  4809.1  911.31  4868.9  908.69
  4874.0  908.94  4879.6  908.16  4889.7  908.05  4930.0  905.71  4970.2  904.90
  4980.3  904.19  4995.7  899.89  4996.0  899.39  4999.5  899.39  4999.7  899.89
  5002.7  899.89  5010.5  903.07  5020.6  904.14  5050.8  904.22  5060.9  905.28
  5070.9  907.40  5081.0  907.35  5121.3  909.93  5126.7  910.82  5131.7  910.50
  5160.4  912.31  5171.6  913.69  5181.7  913.37  5201.8  914.45  5207.3  915.38
#Mann=4,-1,0
  4710.2    0.12       0  4995.7    0.07       0  4999.7    0.12       0
  5160.4    0.05       0
Bank Sta=4995.7,4999.7
Exp/Cntr=0.3,0.1

Type RM Length L Ch R = 1,4233,329,329,329
BEGIN DESCRIPTION:
MDW T 076 11.0
END DESCRIPTION:
XS GIS Cut Line= 3
      2257891.61      7148065.86      2257560.96      7148034.86
      2257303.81      7148003.11
#Sta/Elev= 30
  4667.9  913.49  4710.7  912.79  4734.4  912.99  4760.9  911.11  4771.0  909.04
  4780.1  908.27  4801.1  905.35  4821.2  905.30  4871.4  902.22  4911.6  900.47
  4931.7  900.37  4971.8  901.28  4981.9  900.99  4995.7  898.79  4996.0  898.29
  4999.5  898.29  4999.7  898.79  5003.5  898.85  5022.1  901.49  5042.3  901.24
  5072.5  902.48  5092.7  904.73  5112.8  906.25  5122.9  908.12  5133.0  907.71
  5153.1  908.11  5183.3  909.44  5233.7  910.28  5253.9  911.03  5259.1  911.71
#Mann=4,-1,0
  4667.9    0.05       0  4734.4    0.12       0  4995.7    0.07       0
  4999.7    0.12       0
Bank Sta=4995.7,4999.7
Exp/Cntr=0.3,0.1

Type RM Length L Ch R = 1,3904,365,365,365
BEGIN DESCRIPTION:
MDW T 076 10.0
END DESCRIPTION:
XS GIS Cut Line= 3
      2257953.25      7147855.16      2257729.02      7147790.01
      2257456.80      7147723.23
#Sta/Elev= 30
  4766.5  908.70  4801.8  906.11  4833.4  905.03  4843.9  903.31  4864.6  902.08
  4872.2  902.66  4877.4  902.19  4885.5  902.56  4916.7  899.65  4944.5  898.09
  4968.8  898.86  4978.1  898.26  4983.3  898.84  4995.4  896.60  4995.7  896.10
  4999.2  896.10  4999.4  896.60  5002.6  896.60  5010.3  898.13  5023.4  898.87
  5082.4  898.05  5133.9  898.70  5143.0  899.62  5164.8  899.96  5184.6  902.47
  5195.7  902.60  5206.0  903.87  5231.3  904.55  5236.8  905.49  5280.3  907.75
#Mann=4,-1,0
  4766.5    0.05       0  4801.8    0.12       0  4995.4    0.07       0
  4999.4    0.12       0
Bank Sta=4995.4,4999.4
Exp/Cntr=0.3,0.1

Type RM Length L Ch R = 1,3539,205,205,205
BEGIN DESCRIPTION:
MDW T 076 9.0
END DESCRIPTION:
XS GIS Cut Line= 3
      2258078.97      7147709.97      2257881.27      7147504.13
      2257653.55      7147297.78
#Sta/Elev= 30
  4714.6  911.59  4718.0  911.59  4721.6  909.62  4742.3  906.19  4749.9  903.97
  4764.1  902.39  4771.0  903.19  4778.2  902.51  4792.4  903.43  4820.7  902.85
  4849.0  901.10  4891.4  900.47  4898.4  899.59  4926.7  899.91  4933.9  898.57
  4940.8  899.46  4948.0  897.39  4955.0  896.84  5000.0  895.66  5011.7  896.54
  5018.5  895.84  5054.3  896.29  5101.6  895.54  5101.9  895.04  5105.6  895.54
  5231.4  895.65  5238.1  896.96  5259.5  898.64  5266.5  900.10  5307.3  901.97
#Mann=4,-1,0
  4714.6    0.05       0  4742.3    0.12       0  5101.6    0.07       0
  5105.6    0.12       0
Bank Sta=5101.6,5105.6
Exp/Cntr=0.3,0.1

Type RM Length L Ch R = 1,3334,97,97,97
BEGIN DESCRIPTION:
Mapping XS faa0e120
END DESCRIPTION:
XS GIS Cut Line= 6
      2258176.11      7147466.49      2258035.21      7147365.65
      2257919.44      7147299.68      2257772.23      7147294.02
      2257695.77      7147304.16      2257622.96      7147226.66
#Sta/Elev= 30
  4810.7  905.27  4824.0  903.75  4968.5  895.66  4968.8  895.16  4972.5  895.66
  5006.9  902.13  5022.8  899.59  5028.5  900.71  5066.0  899.17  5071.8  900.93
  5081.9  900.50  5087.6  902.93  5103.5  901.20  5109.2  896.42  5114.6  900.40
  5127.7  902.53  5147.7  900.02  5207.7  898.21  5235.9  899.20  5240.9  902.08
  5257.8  899.37  5268.3  900.80  5272.4  899.01  5308.1  900.52  5356.5  898.91
  5370.7  899.94  5377.6  902.36  5416.1  901.30  5441.5  900.78  5448.0  898.65
#Mann=5,-1,0
  4810.7    0.05       0  4824.0    0.12       0  4968.5    0.07       0
  4972.5    0.12       0  5416.1    0.05       0
Bank Sta=4968.5,4972.5
Exp/Cntr=0.3,0.1

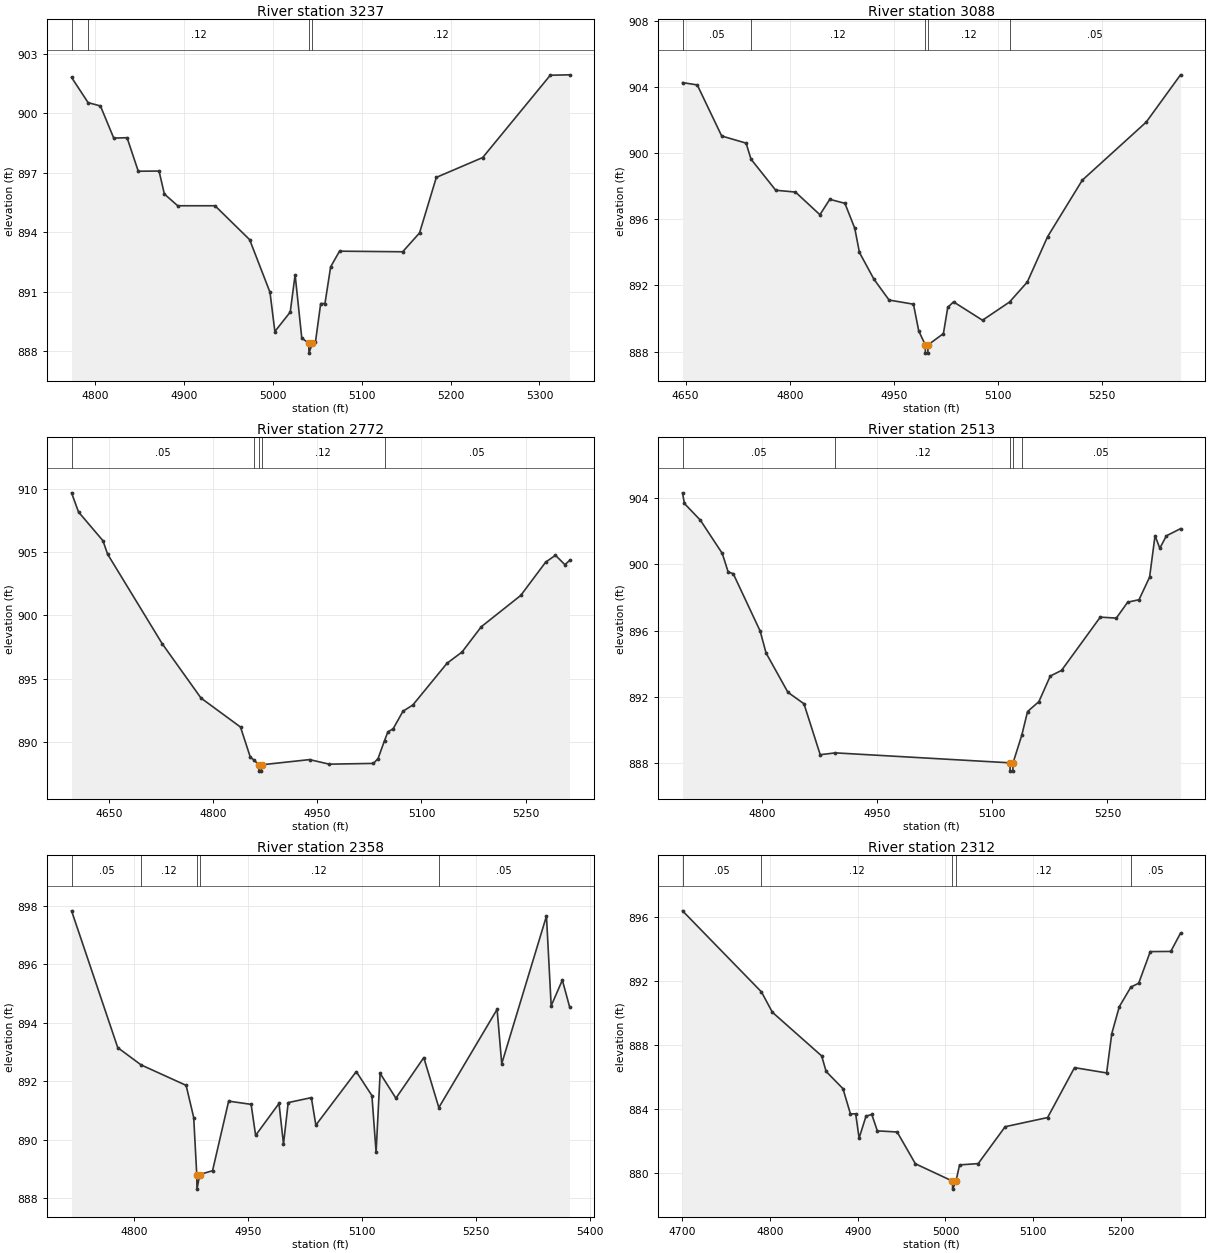
Type RM Length L Ch R = 1,3237,149,149,149
BEGIN DESCRIPTION:
Mapping XS 256ef877
END DESCRIPTION:
XS GIS Cut Line= 5
      2258171.33      7147392.86      2258033.97      7147300.71
      2257925.34      7147249.95      2257796.33      7147242.29
      2257658.59      7147193.44
#Sta/Elev= 30
  4773.2  901.81  4791.8  900.54  4805.7  900.37  4820.7  898.75  4835.7  898.77
  4848.3  897.08  4871.7  897.09  4877.7  895.93  4892.7  895.34  4934.7  895.34
  4973.7  893.63  4996.6  890.98  5002.1  889.00  5019.4  889.98  5024.9  891.86
  5032.4  888.67  5040.3  888.41  5040.5  887.91  5044.3  888.41  5047.8  888.47
  5053.7  890.41  5058.5  890.41  5064.9  892.26  5074.9  893.05  5146.0  893.02
  5165.0  893.97  5183.9  896.77  5236.1  897.77  5312.2  901.92  5333.9  901.94
#Mann=4,-1,0
  4773.2    0.05       0  4791.8    0.12       0  5040.3    0.07       0
  5044.3    0.12       0
Bank Sta=5040.3,5044.3
Exp/Cntr=0.3,0.1

Type RM Length L Ch R = 1,3088,316,316,316
BEGIN DESCRIPTION:
MDW T 076 8.0
END DESCRIPTION:
XS GIS Cut Line= 3
      2258305.91      7147382.57      2258039.59      7147148.75
      2257749.49      7146931.23
#Sta/Elev= 30
  4645.6  904.27  4666.8  904.13  4702.0  901.04  4737.1  900.61  4744.2  899.64
  4779.8  897.76  4808.2  897.65  4843.4  896.28  4857.6  897.21  4879.4  896.97
  4893.6  895.46  4900.3  894.00  4921.2  892.38  4943.0  891.12  4978.1  890.87
  4985.7  889.25  4995.1  888.41  4995.3  887.91  4998.8  887.91  4999.1  888.41
  5021.2  889.09  5027.5  890.68  5035.8  891.01  5077.5  889.90  5116.4  891.00
  5142.0  892.21  5171.2  894.95  5221.2  898.37  5313.2  901.88  5362.6  904.74
#Mann=5,-1,0
  4645.6    0.05       0  4744.2    0.12       0  4995.1    0.07       0
  4999.1    0.12       0  5116.4    0.05       0
Bank Sta=4995.1,4999.1
Exp/Cntr=0.3,0.1

Type RM Length L Ch R = 1,2772,259,259,259
BEGIN DESCRIPTION:
MDW T 076 7.0
END DESCRIPTION:
XS GIS Cut Line= 3
      2258497.69      7147155.08      2258196.69      7146885.76
      2257963.95      7146676.02
#Sta/Elev= 30
  4596.1  909.66  4606.1  908.15  4641.3  905.88  4648.0  904.82  4726.5  897.76
  4782.5  893.46  4839.4  891.17  4853.6  888.78  4858.2  888.59  4865.8  888.19
  4866.0  887.69  4869.5  887.69  4869.8  888.19  4938.8  888.60  4967.2  888.24
  5030.8  888.30  5037.5  888.68  5046.8  890.10  5051.7  890.79  5059.2  891.03
  5073.4  892.42  5087.6  892.91  5136.9  896.21  5158.4  897.09  5186.2  899.09
  5243.0  901.56  5278.9  904.19  5293.0  904.73  5306.6  903.99  5313.3  904.32
#Mann=5,-1,0
  4596.1    0.05       0  4858.2    0.12       0  4865.8    0.07       0
  4869.8    0.12       0  5046.8    0.05       0
Bank Sta=4865.8,4869.8
Exp/Cntr=0.3,0.1

Type RM Length L Ch R = 1,2513,155,155,155
BEGIN DESCRIPTION:
MDW T 076 6.0
END DESCRIPTION:
XS GIS Cut Line= 3
      2258616.14      7146986.18      2258418.10      7146755.67
      2258136.06      7146556.46
#Sta/Elev= 30
  4696.1  904.31  4698.5  903.67  4719.4  902.66  4747.9  900.66  4755.6  899.54
  4762.2  899.44  4797.3  895.98  4805.0  894.66  4833.5  892.29  4854.4  891.60
  4875.6  888.53  4895.5  888.64  5123.0  888.04  5123.2  887.54  5126.7  887.54
  5127.0  888.04  5138.4  889.71  5145.9  891.13  5160.7  891.73  5175.5  893.27
  5190.2  893.61  5240.7  896.82  5261.6  896.76  5276.4  897.72  5291.2  897.87
  5305.0  899.23  5312.1  901.73  5318.3  900.97  5326.9  901.72  5345.3  902.15
#Mann=5,-1,0
  4696.1    0.05       0  4895.5    0.12       0  5123.0    0.07       0
  5127.0    0.12       0  5138.4    0.05       0
Bank Sta=5123,5127
Exp/Cntr=0.3,0.1

Type RM Length L Ch R = 1,2358,46,46,46
BEGIN DESCRIPTION:
Mapping XS b4e05940
END DESCRIPTION:
XS GIS Cut Line= 6
      2258633.14      7146900.79      2258631.18      7146732.97
      2258592.37      7146694.29      2258365.30      7146591.75
      2258293.82      7146604.57      2258204.75      7146540.56
#Sta/Elev= 30
  4717.9  897.83  4778.7  893.15  4809.4  892.56  4868.7  891.86  4878.7  890.76
  4882.7  888.81  4883.0  888.31  4886.7  888.81  4903.5  888.94  4924.7  891.32
  4954.3  891.21  4960.2  890.15  4991.0  891.24  4996.9  889.85  5003.1  891.27
  5033.6  891.44  5039.5  890.50  5092.7  892.33  5113.3  891.51  5118.8  889.57
  5124.1  892.27  5144.9  891.42  5181.6  892.81  5201.4  891.10  5278.1  894.46
  5284.2  892.60  5343.1  897.65  5349.3  894.58  5364.0  895.46  5373.5  894.55
#Mann=5,-1,0
  4717.9    0.05       0  4809.4    0.12       0  4882.7    0.07       0
  4886.7    0.12       0  5201.4    0.05       0
Bank Sta=4882.7,4886.7
Exp/Cntr=0.3,0.1

Type RM Length L Ch R = 1,2312,104,104,104
BEGIN DESCRIPTION:
Mapping XS 9a9dc71c
END DESCRIPTION:
XS GIS Cut Line= 4
      2258681.08      7146891.91      2258660.21      7146698.01
      2258581.58      7146636.18      2258349.70      7146492.18
#Sta/Elev= 30
  4700.1  896.36  4790.1  891.31  4802.6  890.04  4858.8  887.32  4863.9  886.35
  4883.1  885.28  4891.6  883.71  4897.6  883.71  4901.5  882.20  4909.4  883.57
  4916.0  883.67  4922.3  882.65  4944.9  882.58  4965.7  880.60  5008.0  879.52
  5008.2  879.02  5012.0  879.52  5016.1  880.53  5037.3  880.61  5068.1  882.91
  5116.5  883.48  5147.2  886.59  5183.8  886.26  5189.7  888.71  5198.3  890.39
  5211.5  891.61  5220.4  891.85  5233.6  893.82  5257.0  893.83  5268.1  894.97
#Mann=5,-1,0
  4700.1    0.05       0  4790.1    0.12       0  5008.0    0.07       0
  5012.0    0.12       0  5211.5    0.05       0
Bank Sta=5008,5012
Exp/Cntr=0.3,0.1

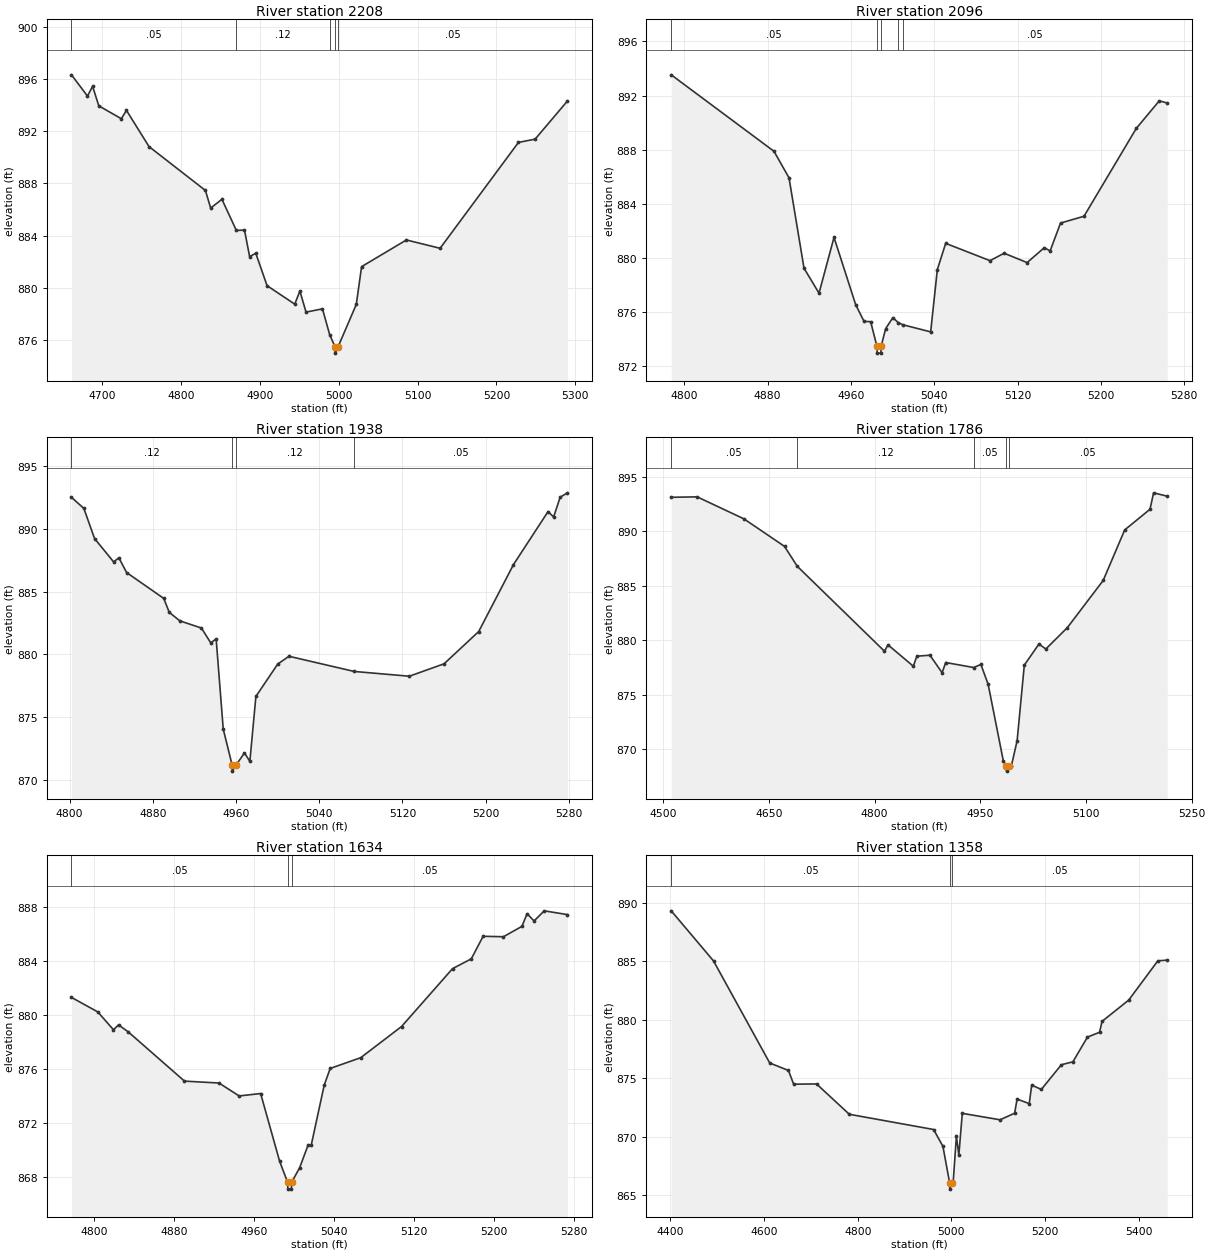
Type RM Length L Ch R = 1,2208,112,112,112
BEGIN DESCRIPTION:
MDW T 076 5.0
END DESCRIPTION:
XS GIS Cut Line= 3
      2258877.43      7146830.09      2258659.36      7146571.06
      2258442.61      7146378.41
#Sta/Elev= 30
  4661.4  896.34  4681.7  894.71  4688.2  895.46  4696.0  893.96  4724.6  892.97
  4731.1  893.61  4759.7  890.83  4831.2  887.46  4837.8  886.11  4852.1  886.78
  4870.4  884.39  4880.7  884.42  4887.2  882.38  4895.0  882.64  4909.3  880.15
  4944.4  878.73  4950.9  879.74  4958.7  878.12  4979.5  878.37  4988.8  876.36
  4995.4  875.47  4995.7  874.97  4999.4  875.47  5022.4  878.71  5029.1  881.61
  5085.9  883.66  5128.6  883.02  5227.9  891.15  5249.0  891.40  5290.0  894.33
#Mann=5,-1,0
  4661.4    0.05       0  4870.4    0.12       0  4988.8    0.05       0
  4995.4   0.033       0  4999.4    0.05       0
Bank Sta=4995.4,4999.4
Exp/Cntr=0.3,0.1

Type RM Length L Ch R = 1,2096,158,158,158
BEGIN DESCRIPTION:
Mapping XS 8b831a62
END DESCRIPTION:
XS GIS Cut Line= 3
      2258892.58      7146695.97      2258705.84      7146463.26
      2258548.17      7146381.02
#Sta/Elev= 30
  4787.4  893.53  4886.1  887.88  4900.5  885.92  4914.9  879.24  4929.3  877.40
  4943.7  881.52  4964.5  876.55  4972.5  875.32  4978.9  875.29  4984.9  873.47
  4985.2  872.97  4988.7  872.97  4988.9  873.47  4993.3  874.78  5000.2  875.59
  5005.3  875.23  5009.6  875.07  5036.5  874.54  5042.9  879.14  5050.9  881.08
  5093.5  879.80  5107.0  880.35  5129.1  879.66  5145.6  880.76  5151.2  880.52
  5161.2  882.58  5183.7  883.08  5233.9  889.57  5256.0  891.61  5263.6  891.45
#Mann=5,-1,0
  4787.4    0.05       0  4984.9   0.033       0  4988.9    0.05       0
  5005.3    0.12       0  5009.6    0.05       0
Bank Sta=4984.9,4988.9
Exp/Cntr=0.3,0.1

Type RM Length L Ch R = 1,1938,152,152,152
BEGIN DESCRIPTION:
Mapping XS 22ffe165
END DESCRIPTION:
XS GIS Cut Line= 4
      2259020.64      7146394.63      2258906.85      7146368.74
      2258753.25      7146417.07      2258562.26      7146360.92
#Sta/Elev= 30
  4801.8  892.51  4813.7  891.63  4824.0  889.23  4842.3  887.37  4847.4  887.69
  4854.8  886.52  4890.5  884.46  4895.8  883.35  4906.0  882.67  4926.7  882.10
  4935.7  880.92  4940.9  881.23  4947.7  874.05  4956.2  871.20  4956.4  870.70
  4960.2  871.20  4968.1  872.15  4973.3  871.48  4979.1  876.65  5000.1  879.23
  5010.9  879.85  5073.6  878.64  5126.6  878.26  5160.0  879.25  5193.3  881.82
  5226.7  887.15  5260.0  891.38  5265.3  890.94  5271.6  892.52  5278.6  892.87
#Mann=4,-1,0
  4801.8    0.12       0  4956.2    0.07       0  4960.2    0.12       0
  5073.6    0.05       0
Bank Sta=4956.2,4960.2
Exp/Cntr=0.3,0.1

Type RM Length L Ch R = 1,1786,152,152,152
BEGIN DESCRIPTION:
MDW T 076 4.0
END DESCRIPTION:
XS GIS Cut Line= 3
      2259204.69      7146179.73      2258740.01      7146298.06
      2258519.77      7146339.46
#Sta/Elev= 30
  4511.6  893.14  4548.4  893.18  4614.7  891.16  4672.3  888.63  4690.4  886.80
  4814.1  879.00  4819.2  879.58  4855.0  877.62  4860.1  878.54  4878.6  878.63
  4895.9  877.02  4901.0  877.96  4940.6  877.50  4950.9  877.78  4961.2  875.96
  4982.8  868.90  4987.0  868.48  4987.3  867.98  4991.0  868.48  4994.2  868.48
  5002.3  870.77  5012.5  877.72  5033.3  879.66  5043.0  879.20  5073.5  881.16
  5124.4  885.50  5154.9  890.14  5190.8  892.04  5195.9  893.55  5215.2  893.24
#Mann=5,-1,0
  4511.6    0.05       0  4690.4    0.12       0  4940.6    0.05       0
  4987.0   0.033       0  4991.0    0.05       0
Bank Sta=4987,4991
Exp/Cntr=0.3,0.1

Type RM Length L Ch R = 1,1634,276,276,276
BEGIN DESCRIPTION:
Mapping XS 0619ae64
END DESCRIPTION:
XS GIS Cut Line= 3
      2258955.14      7146119.05      2258717.60      7146152.61
      2258466.27      7146203.36
#Sta/Elev= 30
  4777.2  881.33  4803.6  880.25  4819.2  878.93  4824.3  879.29  4833.9  878.78
  4890.3  875.12  4924.8  874.98  4945.0  874.02  4966.5  874.20  4985.4  869.20
  4993.5  867.61  4993.7  867.11  4997.2  867.11  4997.5  867.61  5005.6  868.71
  5013.9  870.36  5017.1  870.36  5030.1  874.82  5036.1  876.06  5066.7  876.86
  5107.5  879.17  5158.5  883.46  5177.3  884.19  5189.1  885.86  5209.5  885.83
  5228.0  886.60  5233.1  887.54  5240.1  887.00  5250.3  887.75  5273.5  887.47
#Mann=3,-1,0
  4777.2    0.05       0  4993.5   0.033       0  4997.5    0.05       0
Bank Sta=4993.5,4997.5
Exp/Cntr=0.3,0.1

Type RM Length L Ch R = 1,1358,481,481,481
BEGIN DESCRIPTION:
MDW T 076 3.0
END DESCRIPTION:
XS GIS Cut Line= 3
      2259259.34      7145898.49      2258661.10      7145890.39
      2258225.53      7146041.71
#Sta/Elev= 30
  4401.7  889.29  4492.1  885.01  4612.1  876.30  4652.1  875.66  4663.2  874.49
  4712.1  874.51  4782.1  871.92  4962.1  870.62  4982.1  869.18  4996.5  866.03
  4996.8  865.53  5000.5  866.03  5003.8  866.03  5010.8  870.03  5016.1  868.45
  5023.4  872.00  5104.1  871.45  5135.2  872.01  5140.5  873.22  5166.4  872.83
  5171.7  874.41  5192.2  874.04  5235.1  876.15  5259.7  876.40  5290.8  878.51
  5316.6  878.92  5321.9  879.85  5378.9  881.67  5441.1  885.02  5461.1  885.08
#Mann=3,-1,0
  4401.7    0.05       0  4996.5   0.033       0  5000.5    0.05       0
Bank Sta=4996.5,5000.5
Exp/Cntr=0.3,0.1

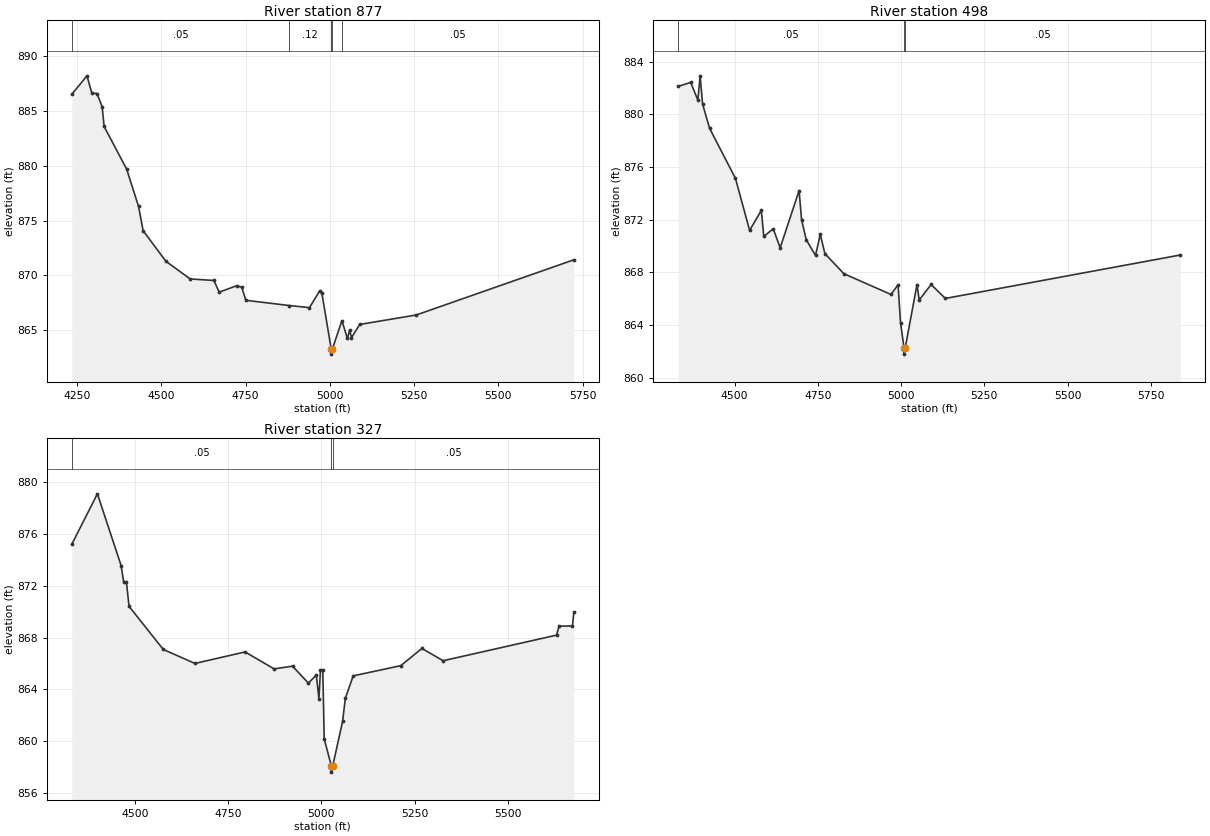
Type RM Length L Ch R = 1,877,379,379,379
BEGIN DESCRIPTION:
MDW T 076 2.0
END DESCRIPTION:
XS GIS Cut Line= 3
      2259367.34      7145824.58      2258709.88      7145416.11
      2258043.58      7145677.33
#Sta/Elev= 30
  4234.1  886.54  4279.2  888.23  4293.5  886.66  4308.9  886.61  4324.2  885.42
  4330.1  883.60  4397.0  879.70  4432.3  876.29  4445.8  874.08  4513.2  871.29
  4585.3  869.67  4656.0  869.53  4671.4  868.46  4723.3  869.05  4738.4  868.92
  4750.5  867.72  4879.7  867.24  4939.4  867.05  4970.1  868.60  4976.0  868.41
  5003.7  863.30  5003.9  862.80  5007.7  863.30  5035.6  865.85  5052.0  864.23
  5058.6  865.01  5064.0  864.30  5088.4  865.51  5256.6  866.38  5723.8  871.42
#Mann=5,-1,0
  4234.1    0.05       0  4879.7    0.12       0  5003.7    0.07       0
  5007.7    0.12       0  5035.6    0.05       0
Bank Sta=5003.7,5007.7
Exp/Cntr=0.3,0.1

Type RM Length L Ch R = 1,498,171,171,171
BEGIN DESCRIPTION:
MDW T 076 1.0
END DESCRIPTION:
XS GIS Cut Line= 4
      2259457.83      7145754.16      2258996.51      7145248.94
      2258825.78      7145093.81      2258410.44      7144670.04
#Sta/Elev= 30
  4330.5  882.13  4367.9  882.43  4389.5  881.08  4396.3  882.93  4403.7  880.78
  4424.7  878.94  4502.4  875.14  4544.9  871.19  4580.1  872.71  4587.5  870.73
  4615.8  871.31  4636.8  869.87  4693.5  874.21  4701.0  872.00  4715.1  870.47
  4742.9  869.29  4757.1  870.88  4771.2  869.42  4828.0  867.90  4969.8  866.32
  4990.8  867.06  4998.2  864.19  5008.5  862.29  5008.8  861.79  5012.5  862.29
  5047.7  867.07  5054.4  865.90  5090.2  867.08  5132.8  866.02  5838.7  869.32
#Mann=3,-1,0
  4330.5    0.05       0  5008.5   0.033       0  5012.5    0.05       0
Bank Sta=5008.5,5012.5
Exp/Cntr=0.3,0.1

Type RM Length L Ch R = 1,327,0,0,0
BEGIN DESCRIPTION:
MDW T 076 0.5
END DESCRIPTION:
XS GIS Cut Line= 4
      2259595.15      7145640.89      2259128.21      7145160.49
      2258922.23      7144936.99      2258673.20      7144660.35
#Sta/Elev= 30
  4330.7  875.21  4399.4  879.11  4463.0  873.57  4470.1  872.26  4477.1  872.31
  4484.3  870.41  4576.1  867.08  4661.0  866.00  4795.3  866.89  4873.2  865.58
  4922.6  865.79  4965.1  864.48  4986.4  865.10  4993.3  863.28  4997.5  865.51
  5003.7  865.51  5007.5  860.17  5026.5  858.10  5026.8  857.60  5030.5  858.10
  5056.8  861.52  5064.2  863.31  5085.2  865.04  5212.8  865.83  5269.5  867.16
  5326.3  866.21  5630.5  868.19  5637.2  868.88  5673.1  868.90  5676.8  869.98
#Mann=3,-1,0
  4330.7    0.05       0  5026.5   0.033       0  5030.5    0.05       0
Bank Sta=5026.5,5030.5
Exp/Cntr=0.3,0.1

Chan Stop Cuts=-1