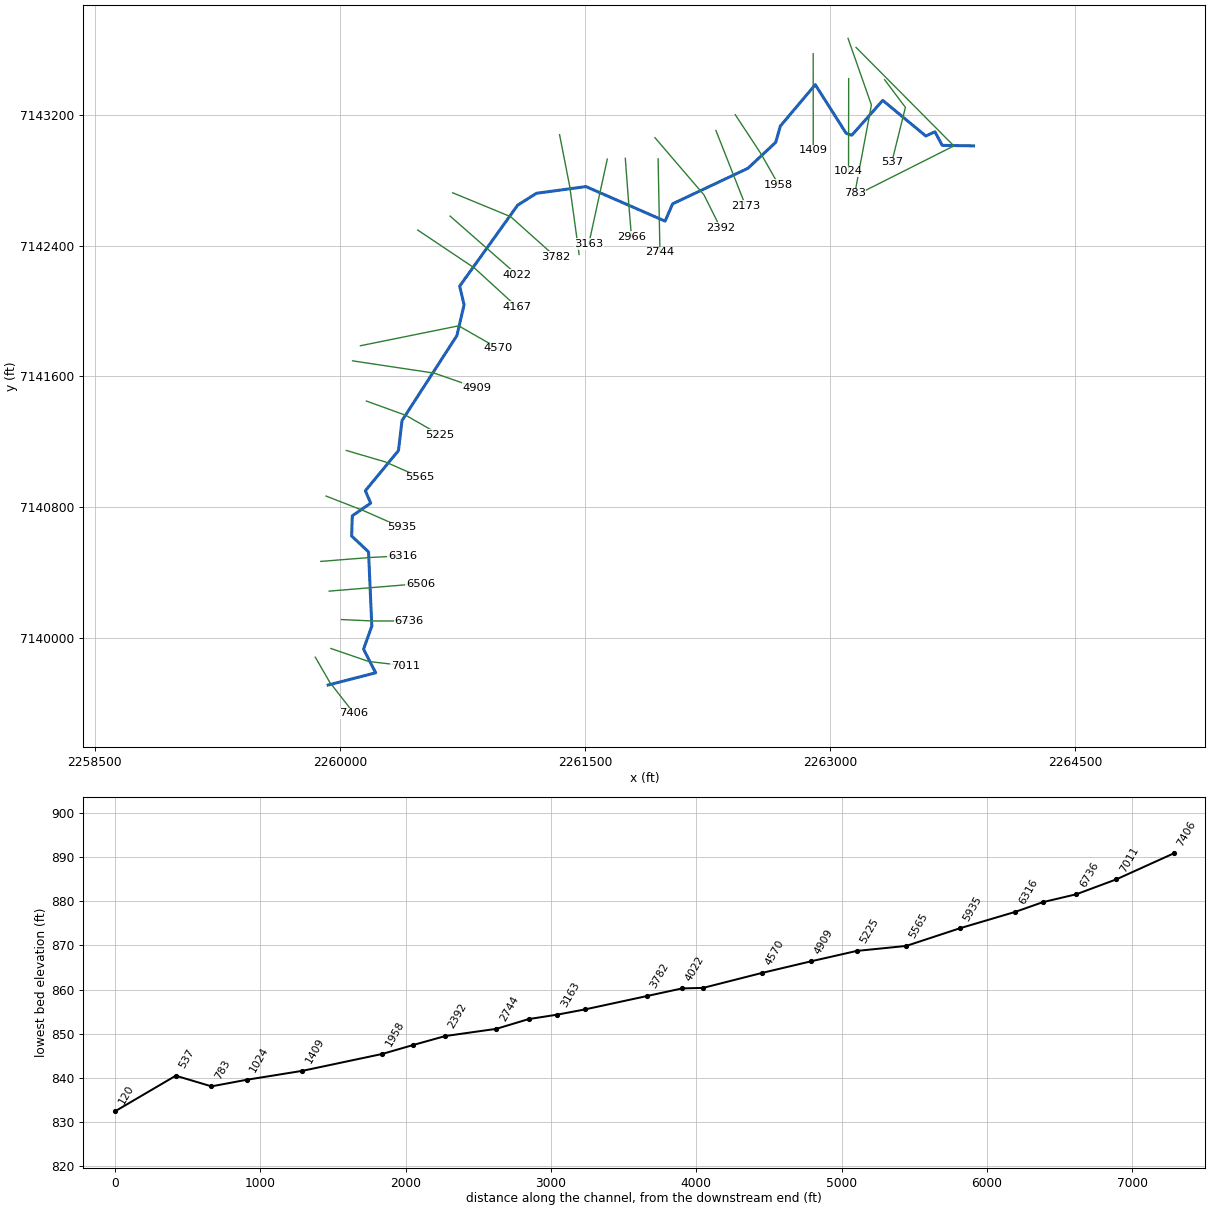
--- MDW T 077.prj (project) ---

Proj Title=MDW T 077 Base Level Engineering
Current Plan=p01
Default Exp/Contr=0.3,0.1
English Units
Geom File=g01
Flow File=f01
Plan File=p01
BEGIN DESCRIPTION:
MDW T 077
END DESCRIPTION:

--- MDW T 077.p01 (plan) ---

Plan Title=Multiple Run
Short Identifier=Multiple
Geom File=g01
Flow File=f01
Subcritical Flow
K Sum by GR= 0
Std Step Tol= 0.01
Critical Tol= 0.01
Num of Std Step Trials= 20
Max Error Tol= 0.3
Flow Tol Ratio= 0.001
Split Flow NTrial= 30
Split Flow Tol= 0.02
Split Flow Ratio= 0.02
Log Output Level= 0
Friction Slope Method= 1
Unsteady Friction Slope Method= 2
Unsteady Bridges Friction Slope Method= 1
Parabolic Critical Depth
Global Vel Dist=  1 , 1 , 1
Global Log Level= 0
CheckData=True
Encroach Param= -1, 0, 0, 0
BEGIN DESCRIPTION:
Multiple Run
END DESCRIPTION:

--- MDW T 077.f01 (steady flow) ---

Flow Title=Multiple
Number of Profiles=7
Profile Names=10-year,25-year,50-year,1pct_min,100-year,1pct_plu,500-year
River Rch & RM= MDW T 077,Reach-1,7406
     919    1308    1642    1024    2043    4076    3171
River Rch & RM= MDW T 077,Reach-1,4022
     919    1302    1629    1013    2021    4032    3116
Boundary for River Rch & Prof#=MDW T 077,Reach-1,1
Up Type=0
Dn Type=3
Dn Slope=0.005
Boundary for River Rch & Prof#=MDW T 077,Reach-1,2
Up Type=0
Dn Type=3
Dn Slope=0.005
Boundary for River Rch & Prof#=MDW T 077,Reach-1,3
Up Type=0
Dn Type=3
Dn Slope=0.005
Boundary for River Rch & Prof#=MDW T 077,Reach-1,4
Up Type=0
Dn Type=3
Dn Slope=0.005
Boundary for River Rch & Prof#=MDW T 077,Reach-1,5
Up Type=0
Dn Type=3
Dn Slope=0.005
Boundary for River Rch & Prof#=MDW T 077,Reach-1,6
Up Type=0
Dn Type=3
Dn Slope=0.005
Boundary for River Rch & Prof#=MDW T 077,Reach-1,7
Up Type=0
Dn Type=3
Dn Slope=0.005

--- MDW T 077.g01 (geometry) ---

Geom Title=Existing Conditions

River Reach=MDW T 077,Reach-1
Reach XY= 30
      2259929.00      7139710.00      2260219.66      7139784.89
      2260145.39      7139929.50      2260196.08      7140070.82
      2260175.92      7140524.77      2260072.61      7140622.25
      2260076.42      7140745.66      2260189.25      7140823.06
      2260156.48      7140899.14      2260359.10      7141144.81
      2260380.87      7141328.61      2260716.74      7141848.69
      2260760.68      7142037.09      2260733.73      7142151.42
      2261088.32      7142646.70      2261203.65      7142719.72
      2261506.83      7142760.68      2261991.26      7142549.19
      2262037.18      7142655.36      2262497.94      7142872.55
      2262668.01      7143031.28      2262696.71      7143131.42
      2262910.34      7143384.54      2263099.40      7143086.64
      2263134.06      7143075.21      2263323.37      7143288.45
      2263586.77      7143070.30      2263642.65      7143096.42
      2263687.29      7143013.11      2263879.00      7143010.00

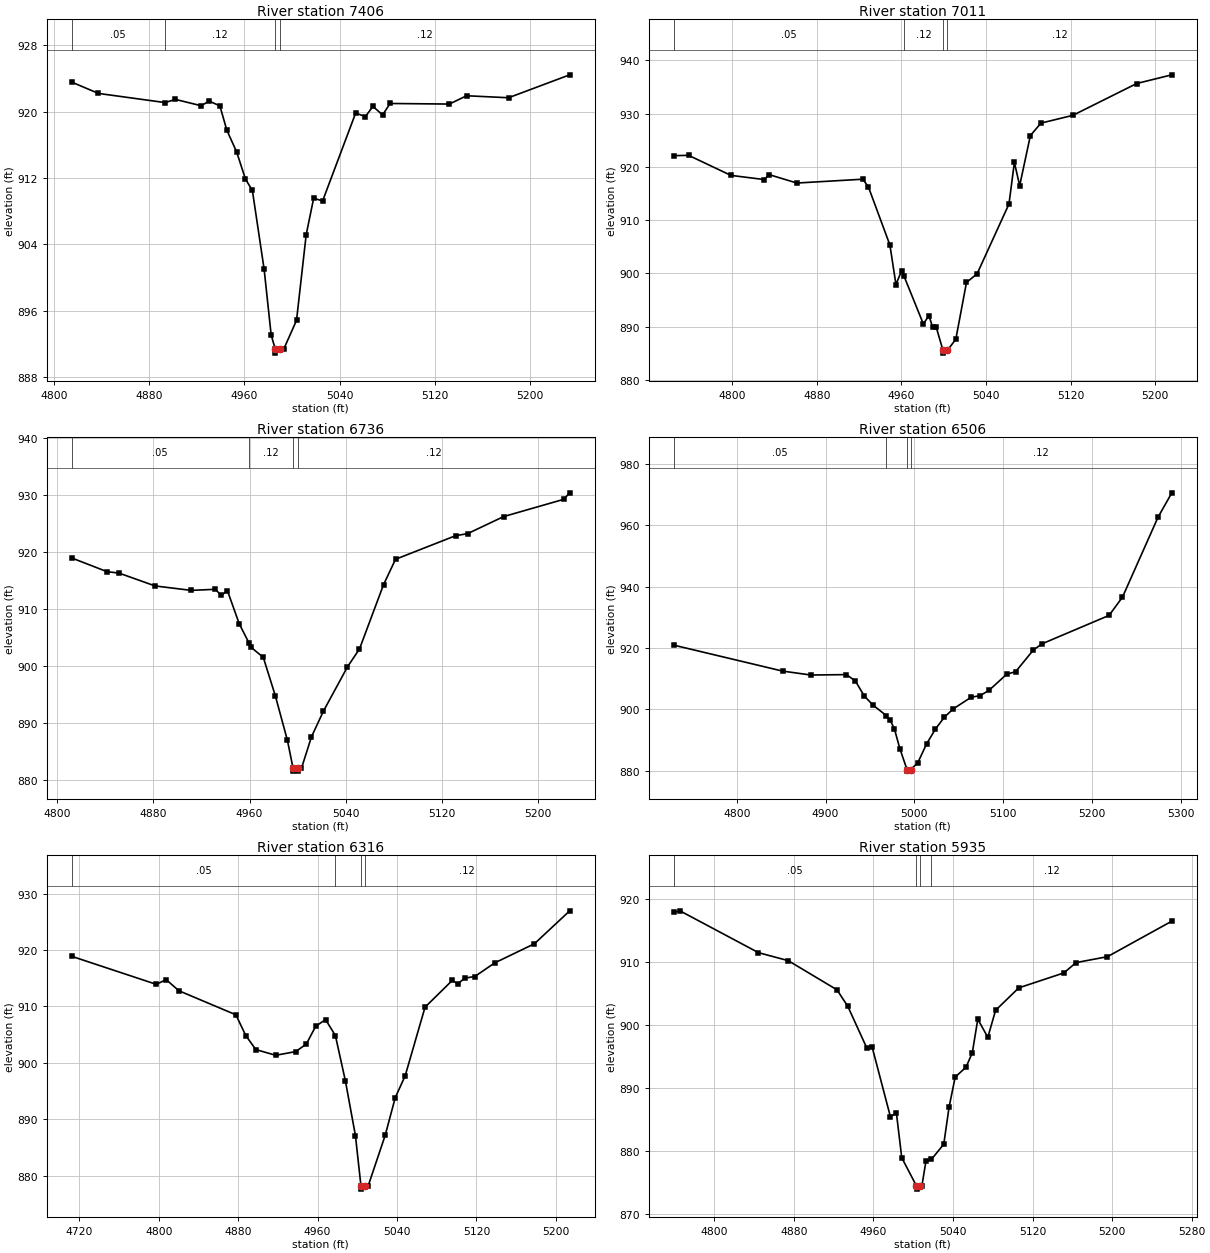
Type RM Length L Ch R = 1,7406,395,395,395
BEGIN DESCRIPTION:
MDW T 077 18.0
END DESCRIPTION:
XS GIS Cut Line= 3
      2259850.09      7139880.13      2259939.27      7139725.69
      2260087.06      7139536.39
#Sta/Elev= 30
  4814.8  923.56  4837.4  922.19  4893.3  921.09  4902.1  921.47  4923.6  920.71
  4930.4  921.27  4939.4  920.69  4945.2  917.78  4953.5  915.14  4960.9  911.87
  4966.7  910.51  4976.6  900.99  4982.5  893.09  4985.9  891.42  4986.1  890.92
  4989.9  891.42  4993.1  891.42  5003.8  894.87  5011.9  905.17  5018.2  909.58
  5025.7  909.24  5053.5  919.84  5061.6  919.39  5068.0  920.63  5076.1  919.60
  5082.4  920.98  5132.2  920.91  5146.7  921.91  5181.9  921.67  5233.3  924.43
#Mann=4,-1,0
  4814.8    0.05       0  4893.3    0.12       0  4985.9    0.07       0
  4989.9    0.12       0
Bank Sta=4985.9,4989.9
Exp/Cntr=0.3,0.1

Type RM Length L Ch R = 1,7011,275,275,275
BEGIN DESCRIPTION:
MDW T 077 17.0
END DESCRIPTION:
XS GIS Cut Line= 3
      2259945.68      7139933.57      2260177.21      7139853.84
      2260401.95      7139828.00
#Sta/Elev= 30
  4744.7  922.10  4758.8  922.16  4798.8  918.40  4830.0  917.62  4835.3  918.52
  4861.2  916.96  4923.6  917.68  4928.9  916.20  4949.2  905.31  4954.9  897.90
  4960.2  900.47  4962.5  899.49  4980.8  890.50  4986.1  892.06  4989.6  889.88
  4993.0  889.88  4999.4  885.52  4999.7  885.02  5003.4  885.52  5011.5  887.61
  5021.6  898.30  5031.6  899.90  5061.8  913.03  5066.9  920.84  5071.9  916.46
  5082.0  925.86  5092.0  928.21  5122.2  929.67  5182.6  935.65  5215.8  937.28
#Mann=4,-1,0
  4744.7    0.05       0  4962.5    0.12       0  4999.4    0.07       0
  5003.4    0.12       0
Bank Sta=4999.4,5003.4
Exp/Cntr=0.3,0.1

Type RM Length L Ch R = 1,6736,230,230,230
BEGIN DESCRIPTION:
MDW T 077 16.0
END DESCRIPTION:
XS GIS Cut Line= 3
      2260009.53      7140110.64      2260197.54      7140102.13
      2260424.04      7140101.96
#Sta/Elev= 30
  4811.8  918.99  4841.3  916.58  4851.3  916.33  4881.3  914.08  4911.4  913.30
  4931.4  913.49  4936.5  912.42  4941.5  913.28  4951.4  907.44  4959.4  904.13
  4961.4  903.30  4971.4  901.57  4981.4  894.86  4991.5  887.03  4996.2  882.14
  4996.5  881.64  5000.0  881.64  5000.2  882.14  5003.2  882.14  5011.5  887.64
  5021.5  892.16  5041.5  899.91  5051.5  903.04  5071.5  914.29  5081.5  918.75
  5131.5  922.88  5141.5  923.24  5171.5  926.23  5221.5  929.25  5226.5  930.39
#Mann=4,-1,0
  4811.8    0.05       0  4959.4    0.12       0  4996.2    0.07       0
  5000.2    0.12       0
Bank Sta=4996.2,5000.2
Exp/Cntr=0.3,0.1

Type RM Length L Ch R = 1,6506,190,190,190
BEGIN DESCRIPTION:
Mapping XS fa8eebb6
END DESCRIPTION:
XS GIS Cut Line= 2
      2259935.01      7140284.64      2260494.41      7140330.81
#Sta/Elev= 30
  4728.9  920.91  4851.6  912.45  4883.4  911.17  4923.5  911.30  4933.6  909.24
  4943.6  904.35  4953.6  901.34  4968.5  897.94  4972.5  896.64  4977.6  893.62
  4983.7  887.22  4991.8  880.35  4992.0  879.85  4995.8  880.35  5003.8  882.49
  5013.9  888.75  5023.9  893.58  5033.9  897.43  5044.0  900.16  5064.0  903.91
  5074.1  904.46  5084.1  906.14  5104.2  911.45  5114.2  912.25  5134.3  919.37
  5144.3  921.38  5219.5  930.60  5234.6  936.54  5274.7  962.62  5290.2  970.54
#Mann=4,-1,0
  4728.9    0.05       0  4968.5    0.12       0  4991.8    0.07       0
  4995.8    0.12       0
Bank Sta=4991.8,4995.8
Exp/Cntr=0.3,0.1

Type RM Length L Ch R = 1,6316,381,381,381
BEGIN DESCRIPTION:
MDW T 077 15.0
END DESCRIPTION:
XS GIS Cut Line= 3
      2259884.02      7140466.62      2260179.28      7140490.07
      2260384.48      7140501.32
#Sta/Elev= 30
  4712.2  918.89  4797.5  913.92  4807.5  914.75  4820.3  912.78  4877.7  908.52
  4887.7  904.83  4897.8  902.36  4917.8  901.35  4937.9  902.00  4948.7  903.35
  4958.0  906.47  4968.0  907.68  4977.9  904.85  4988.0  896.80  4998.1  887.12
  5003.7  878.14  5004.0  877.64  5007.7  878.14  5010.8  878.14  5028.1  887.19
  5038.2  893.85  5048.2  897.72  5068.2  909.87  5095.8  914.64  5100.9  913.98
  5108.3  915.02  5118.3  915.30  5138.3  917.71  5178.4  921.11  5213.9  926.94
#Mann=4,-1,0
  4712.2    0.05       0  4977.9    0.12       0  5003.7    0.07       0
  5007.7    0.12       0
Bank Sta=5003.7,5007.7
Exp/Cntr=0.3,0.1

Type RM Length L Ch R = 1,5935,370,370,370
BEGIN DESCRIPTION:
MDW T 077 14.0
END DESCRIPTION:
XS GIS Cut Line= 3
      2259916.03      7140866.49      2260146.41      7140776.70
      2260378.18      7140674.40
#Sta/Elev= 30
  4759.4  917.84  4765.7  918.10  4844.6  911.46  4874.5  910.19  4923.5  905.56
  4934.3  902.96  4953.3  896.38  4958.7  896.55  4977.2  885.40  4983.2  886.03
  4988.6  878.90  5003.4  874.42  5003.6  873.92  5007.4  874.42  5008.8  874.42
  5012.9  878.35  5018.4  878.64  5030.8  881.05  5036.2  886.99  5042.3  891.71
  5053.2  893.28  5059.5  895.57  5065.0  900.89  5075.1  898.02  5082.9  902.31
  5106.2  905.87  5151.6  908.25  5163.7  909.88  5195.3  910.82  5260.0  916.46
#Mann=4,-1,0
  4759.4    0.05       0  5003.4   0.033       0  5007.4    0.05       0
  5018.4    0.12       0
Bank Sta=5003.4,5007.4
Exp/Cntr=0.3,0.1

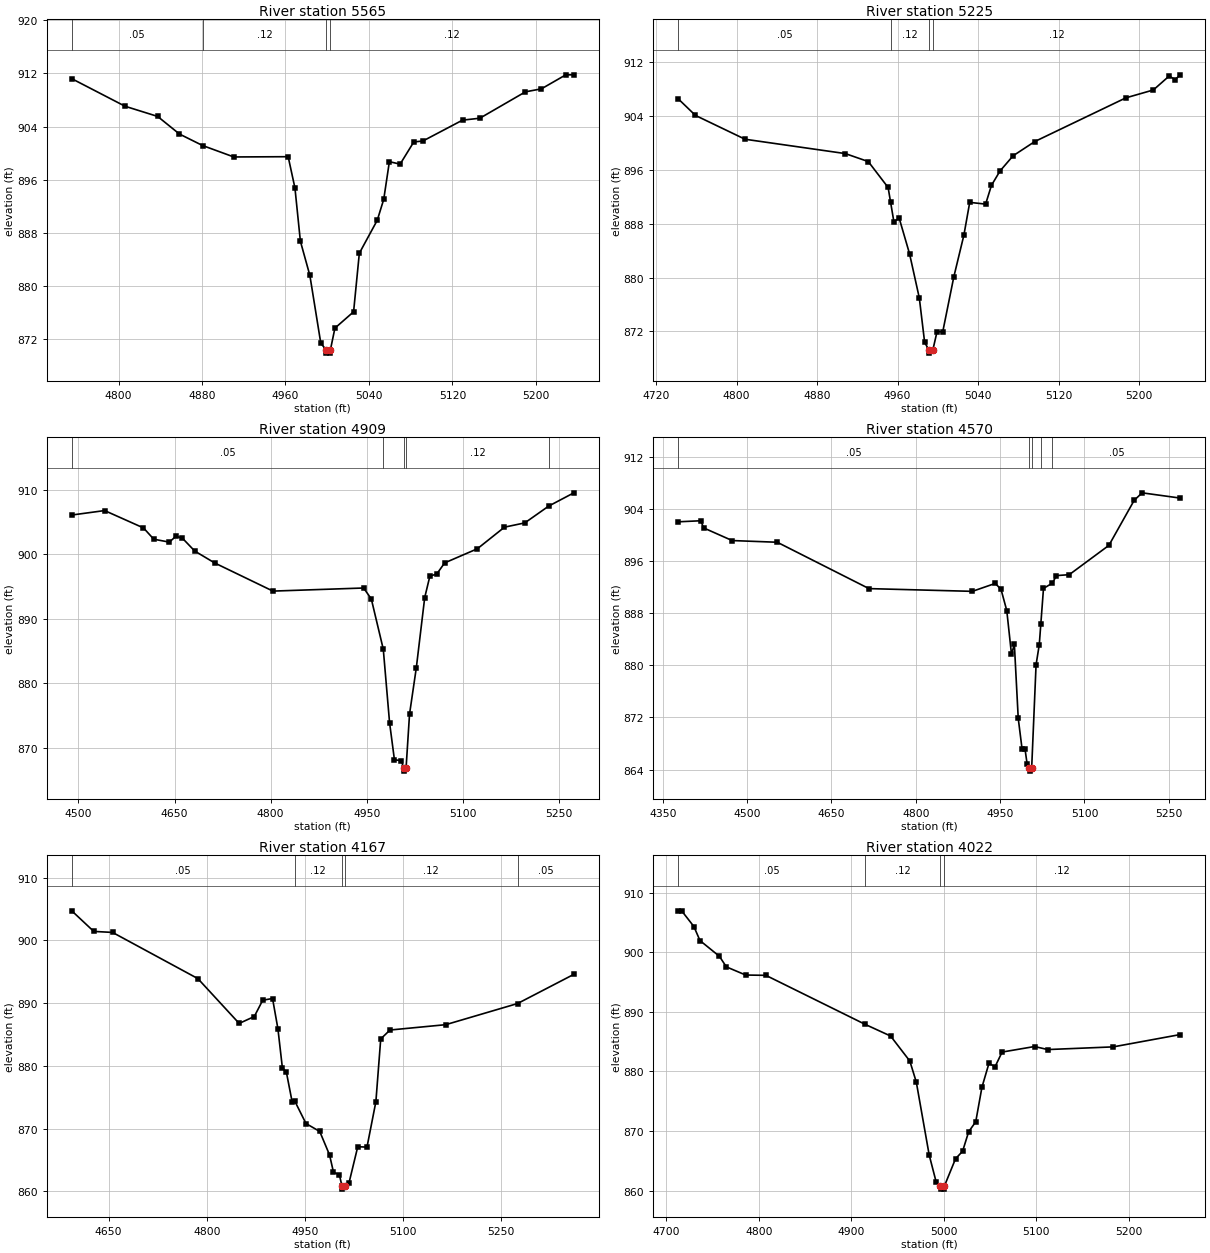
Type RM Length L Ch R = 1,5565,340,340,340
BEGIN DESCRIPTION:
MDW T 077 13.0
END DESCRIPTION:
XS GIS Cut Line= 3
      2260040.01      7141145.66      2260277.87      7141075.76
      2260491.54      7140982.13
#Sta/Elev= 30
  4755.2  911.20  4806.3  907.05  4837.5  905.52  4858.4  902.87  4880.6  901.14
  4910.5  899.42  4962.6  899.46  4969.1  894.75  4974.3  886.75  4983.4  881.59
  4993.9  871.36  4999.1  870.40  4999.3  869.90  5002.8  869.90  5003.1  870.40
  5007.4  873.66  5025.3  876.12  5030.8  884.93  5048.0  889.90  5054.2  893.05
  5059.6  898.71  5069.9  898.34  5083.0  901.68  5091.7  901.82  5129.7  904.96
  5146.3  905.25  5190.0  909.22  5205.3  909.67  5228.7  911.78  5236.4  911.78
#Mann=4,-1,0
  4755.2    0.05       0  4880.6    0.12       0  4999.1    0.07       0
  5003.1    0.12       0
Bank Sta=4999.1,5003.1
Exp/Cntr=0.3,0.1

Type RM Length L Ch R = 1,5225,316,316,316
BEGIN DESCRIPTION:
MDW T 077 12.0
END DESCRIPTION:
XS GIS Cut Line= 3
      2260162.90      7141448.14      2260405.41      7141360.23
      2260614.35      7141240.02
#Sta/Elev= 30
  4742.0  906.55  4759.1  904.09  4808.4  900.55  4908.0  898.42  4930.9  897.23
  4950.6  893.38  4953.0  891.25  4956.3  888.31  4961.6  888.82  4971.9  883.53
  4981.6  876.97  4986.9  870.35  4991.1  869.27  4991.4  868.77  4995.1  869.27
  4999.2  871.95  5004.9  871.95  5015.9  880.11  5025.9  886.30  5031.7  891.17
  5047.5  890.91  5053.3  893.70  5061.8  895.83  5074.8  898.09  5096.4  900.21
  5186.9  906.70  5214.2  907.87  5230.0  909.95  5235.8  909.40  5241.0  910.12
#Mann=4,-1,0
  4742.0    0.05       0  4953.0    0.12       0  4991.1    0.07       0
  4995.1    0.12       0
Bank Sta=4991.1,4995.1
Exp/Cntr=0.3,0.1

Type RM Length L Ch R = 1,4909,339,339,339
BEGIN DESCRIPTION:
MDW T 077 11.0
END DESCRIPTION:
XS GIS Cut Line= 3
      2260078.28      7141694.23      2260579.20      7141618.74
      2260841.32      7141527.55
#Sta/Elev= 30
  4489.5  906.09  4540.8  906.78  4601.5  904.09  4617.6  902.34  4641.9  901.89
  4652.0  902.79  4662.1  902.52  4681.5  900.51  4712.7  898.66  4803.7  894.30
  4945.3  894.78  4957.3  893.08  4976.0  885.29  4985.8  873.92  4993.4  868.16
  5004.3  868.02  5007.6  866.90  5007.8  866.40  5011.6  866.90  5017.0  875.24
  5027.6  882.43  5040.7  893.30  5048.8  896.64  5059.4  896.93  5071.8  898.67
  5122.9  900.86  5165.3  904.21  5197.0  904.87  5234.4  907.48  5273.6  909.53
#Mann=5,-1,0
  4489.5    0.05       0  4976.0    0.12       0  5007.6    0.07       0
  5011.6    0.12       0  5234.4    0.05       0
Bank Sta=5007.6,5011.6
Exp/Cntr=0.3,0.1

Type RM Length L Ch R = 1,4570,403,403,403
BEGIN DESCRIPTION:
MDW T 077 10.0
END DESCRIPTION:
XS GIS Cut Line= 3
      2260126.45      7141786.68      2260727.42      7141908.42
      2260970.23      7141769.73
#Sta/Elev= 30
  4377.6  902.04  4417.7  902.20  4422.8  901.10  4473.5  899.16  4553.7  898.90
  4716.8  891.78  4900.6  891.36  4941.4  892.58  4951.6  891.66  4961.8  888.41
  4970.2  881.69  4975.3  883.23  4982.2  871.85  4989.0  867.16  4994.2  867.16
  4998.0  864.86  5002.1  864.25  5002.4  863.75  5006.1  864.25  5013.9  880.08
  5019.6  883.17  5022.3  886.28  5027.1  891.81  5042.9  892.62  5050.2  893.78
  5072.9  893.92  5143.4  898.42  5188.4  905.34  5202.5  906.49  5270.4  905.68
#Mann=5,-1,0
  4377.6    0.05       0  5002.1   0.033       0  5006.1    0.05       0
  5022.3    0.12       0  5042.9    0.05       0
Bank Sta=5002.1,5006.1
Exp/Cntr=0.3,0.1

Type RM Length L Ch R = 1,4167,145,145,145
BEGIN DESCRIPTION:
MDW T 077 9.0
END DESCRIPTION:
XS GIS Cut Line= 3
      2260477.25      7142494.52      2260825.01      7142261.65
      2261082.20      7142026.24
#Sta/Elev= 30
  4593.7  904.71  4627.3  901.43  4656.0  901.27  4786.4  893.91  4849.5  886.77
  4872.6  887.87  4885.5  890.47  4900.5  890.74  4908.7  885.92  4915.5  879.72
  4921.6  879.02  4930.5  874.24  4934.3  874.43  4951.6  870.82  4972.6  869.56
  4987.6  865.82  4993.6  863.07  5002.6  862.65  5006.6  860.87  5006.9  860.37
  5010.6  860.87  5017.2  861.31  5030.7  867.13  5044.8  867.06  5058.4  874.30
  5065.8  884.30  5080.0  885.72  5165.1  886.57  5274.9  889.94  5360.9  894.59
#Mann=5,-1,0
  4593.7    0.05       0  4934.3    0.12       0  5006.6    0.07       0
  5010.6    0.12       0  5274.9    0.05       0
Bank Sta=5006.6,5010.6
Exp/Cntr=0.3,0.1

Type RM Length L Ch R = 1,4022,240,240,240
BEGIN DESCRIPTION:
Mapping XS 175ae800
END DESCRIPTION:
XS GIS Cut Line= 2
      2260675.50      7142579.81      2261083.55      7142222.16
#Sta/Elev= 30
  4713.0  906.93  4716.7  906.93  4729.9  904.30  4736.5  901.94  4757.5  899.30
  4765.0  897.53  4785.9  896.16  4807.7  896.11  4915.1  887.88  4942.5  885.93
  4963.3  881.73  4970.3  878.19  4984.2  865.98  4991.8  861.41  4996.4  860.75
  4996.7  860.25  5000.2  860.25  5000.6  860.75  5012.7  865.35  5020.3  866.60
  5026.9  869.89  5034.5  871.54  5041.2  877.33  5048.8  881.35  5055.4  880.78
  5063.0  883.24  5098.1  884.17  5112.3  883.66  5183.1  884.11  5255.6  886.18
#Mann=4,-1,0
  4713.0    0.05       0  4915.1    0.12       0  4996.4    0.07       0
  5000.6    0.12       0
Bank Sta=4996.4,5000.6
Exp/Cntr=0.3,0.1

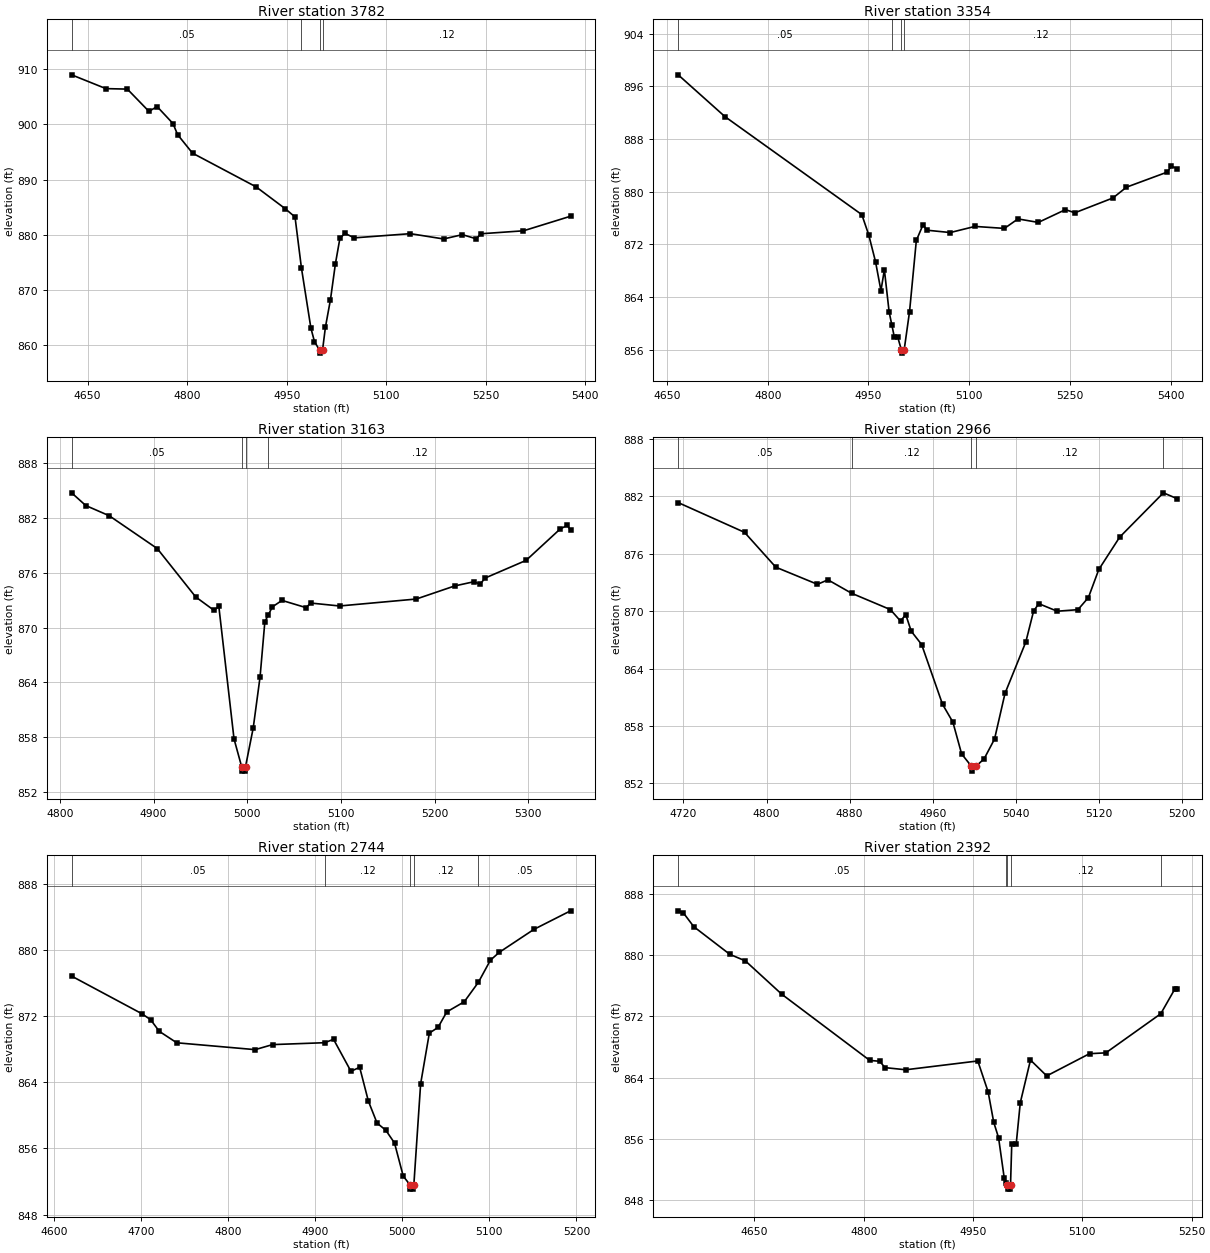
Type RM Length L Ch R = 1,3782,428,428,428
BEGIN DESCRIPTION:
MDW T 077 8.0
END DESCRIPTION:
XS GIS Cut Line= 3
      2260691.31      7142722.65      2261045.95      7142576.55
      2261320.46      7142330.95
#Sta/Elev= 30
  4625.9  908.99  4677.6  906.49  4709.9  906.40  4742.4  902.37  4754.8  903.23
  4778.7  900.15  4785.6  898.15  4808.1  894.79  4903.9  888.68  4947.9  884.71
  4962.6  883.21  4972.2  874.02  4986.5  863.08  4991.9  860.61  4999.8  859.03
  5000.1  858.53  5004.0  859.03  5008.4  863.24  5016.0  868.23  5023.5  874.77
  5030.2  879.32  5037.7  880.25  5051.9  879.43  5136.4  880.19  5186.5  879.23
  5214.8  880.01  5235.8  879.26  5242.6  880.17  5306.9  880.71  5377.8  883.35
#Mann=4,-1,0
  4625.9    0.05       0  4972.2    0.12       0  4999.8    0.07       0
  5004.0    0.12       0
Bank Sta=4999.8,5004
Exp/Cntr=0.3,0.1

Type RM Length L Ch R = 1,3354,191,191,191
BEGIN DESCRIPTION:
MDW T 077 7.0
END DESCRIPTION:
XS GIS Cut Line= 3
      2261345.20      7143078.34      2261407.71      7142760.05
      2261464.99      7142345.26
#Sta/Elev= 30
  4666.6  897.74  4736.3  891.39  4940.1  876.51  4950.3  873.47  4960.5  869.37
  4968.6  864.97  4973.7  868.14  4980.8  861.72  4984.7  859.81  4988.5  857.94
  4993.5  857.94  4999.0  855.98  4999.3  855.48  5003.2  855.98  5011.2  861.80
  5021.3  872.59  5031.4  875.00  5036.7  874.15  5071.8  873.79  5108.6  874.72
  5152.5  874.42  5172.7  875.86  5203.0  875.33  5243.4  877.27  5257.4  876.79
  5314.1  879.04  5334.3  880.68  5394.8  882.96  5401.2  883.87  5409.7  883.49
#Mann=4,-1,0
  4666.6    0.05       0  4984.7    0.12       0  4999.0    0.07       0
  5003.2    0.12       0
Bank Sta=4999,5003.2
Exp/Cntr=0.3,0.1

Type RM Length L Ch R = 1,3163,197,197,197
BEGIN DESCRIPTION:
Mapping XS f4b71d3e
END DESCRIPTION:
XS GIS Cut Line= 2
      2261637.33      7142929.31      2261523.81      7142409.16
#Sta/Elev= 30
  4812.6  884.74  4827.7  883.35  4852.8  882.23  4904.0  878.64  4945.0  873.35
  4964.6  871.88  4969.7  872.31  4985.9  857.82  4994.0  854.79  4994.3  854.29
  4997.9  854.29  4998.2  854.79  5006.4  859.02  5013.7  864.60  5018.8  870.63
  5022.4  871.36  5026.8  872.26  5037.1  872.97  5062.7  872.18  5067.8  872.68
  5098.5  872.36  5180.4  873.12  5221.3  874.55  5241.8  875.01  5248.6  874.74
  5253.7  875.41  5297.6  877.35  5333.9  880.78  5341.6  881.19  5345.0  880.64
#Mann=4,-1,0
  4812.6    0.05       0  4994.0   0.033       0  4998.2    0.05       0
  5022.4    0.12       0
Bank Sta=4994,4998.2
Exp/Cntr=0.3,0.1

Type RM Length L Ch R = 1,2966,222,222,222
BEGIN DESCRIPTION:
MDW T 077 6.0
END DESCRIPTION:
XS GIS Cut Line= 3
      2261747.54      7142933.77      2261768.31      7142658.35
      2261785.28      7142454.85
#Sta/Elev= 30
  4714.9  881.34  4778.8  878.23  4808.9  874.59  4849.0  872.80  4859.1  873.27
  4881.8  871.87  4919.2  870.16  4929.0  868.96  4934.0  869.64  4939.3  867.90
  4949.3  866.51  4969.4  860.27  4979.4  858.40  4987.8  855.08  4997.3  853.78
  4997.7  853.28  5001.6  853.78  5009.5  854.57  5019.5  856.63  5029.6  861.41
  5049.6  866.77  5057.1  870.00  5062.1  870.78  5079.8  869.99  5099.8  870.15
  5109.9  871.42  5119.9  874.35  5140.0  877.73  5182.1  882.36  5195.3  881.75
#Mann=5,-1,0
  4714.9    0.05       0  4881.8    0.12       0  4997.3    0.07       0
  5001.6    0.12       0  5182.1    0.05       0
Bank Sta=4997.3,5001.6
Exp/Cntr=0.3,0.1

Type RM Length L Ch R = 1,2744,352,352,352
BEGIN DESCRIPTION:
Mapping XS 8fb9a20e
END DESCRIPTION:
XS GIS Cut Line= 2
      2261948.29      7142930.66      2261959.69      7142357.98
#Sta/Elev= 30
  4620.4  876.82  4701.1  872.27  4711.1  871.55  4721.1  870.14  4741.1  868.76
  4831.1  867.93  4851.1  868.54  4911.1  868.77  4921.1  869.18  4941.1  865.31
  4951.1  865.80  4961.1  861.71  4971.1  859.05  4981.1  858.19  4991.1  856.65
  5001.1  852.65  5009.0  851.57  5009.3  851.07  5012.9  851.07  5013.3  851.57
  5021.1  863.80  5031.1  869.93  5041.1  870.62  5051.1  872.49  5071.2  873.72
  5087.4  876.07  5101.2  878.74  5111.2  879.68  5151.2  882.47  5193.2  884.71
#Mann=5,-1,0
  4620.4    0.05       0  4911.1    0.12       0  5009.0    0.07       0
  5013.3    0.12       0  5087.4    0.05       0
Bank Sta=5009,5013.3
Exp/Cntr=0.3,0.1

Type RM Length L Ch R = 1,2392,219,219,219
BEGIN DESCRIPTION:
MDW T 077 5.0
END DESCRIPTION:
XS GIS Cut Line= 3
      2261928.98      7143060.02      2262229.00      7142710.00
      2262328.99      7142510.01
#Sta/Elev= 30
  4545.4  885.78  4552.6  885.50  4566.8  883.71  4616.2  880.10  4637.6  879.24
  4687.6  874.88  4808.3  866.24  4822.0  866.13  4829.1  865.30  4857.7  865.02
  4956.5  866.17  4970.7  862.13  4978.4  858.15  4985.0  856.15  4992.7  850.94
  4995.8  850.23  4997.1  849.93  4997.5  849.43  5001.1  849.43  5001.4  849.93
  5003.1  855.31  5009.2  855.31  5014.8  860.71  5028.8  866.29  5051.1  864.22
  5109.8  867.12  5132.2  867.23  5207.6  872.34  5227.2  875.62  5230.0  875.62
#Mann=5,-1,0
  4545.4    0.05       0  4995.8    0.12       0  4997.1    0.07       0
  5001.4    0.12       0  5207.6    0.05       0
Bank Sta=4997.1,5001.4
Exp/Cntr=0.3,0.1

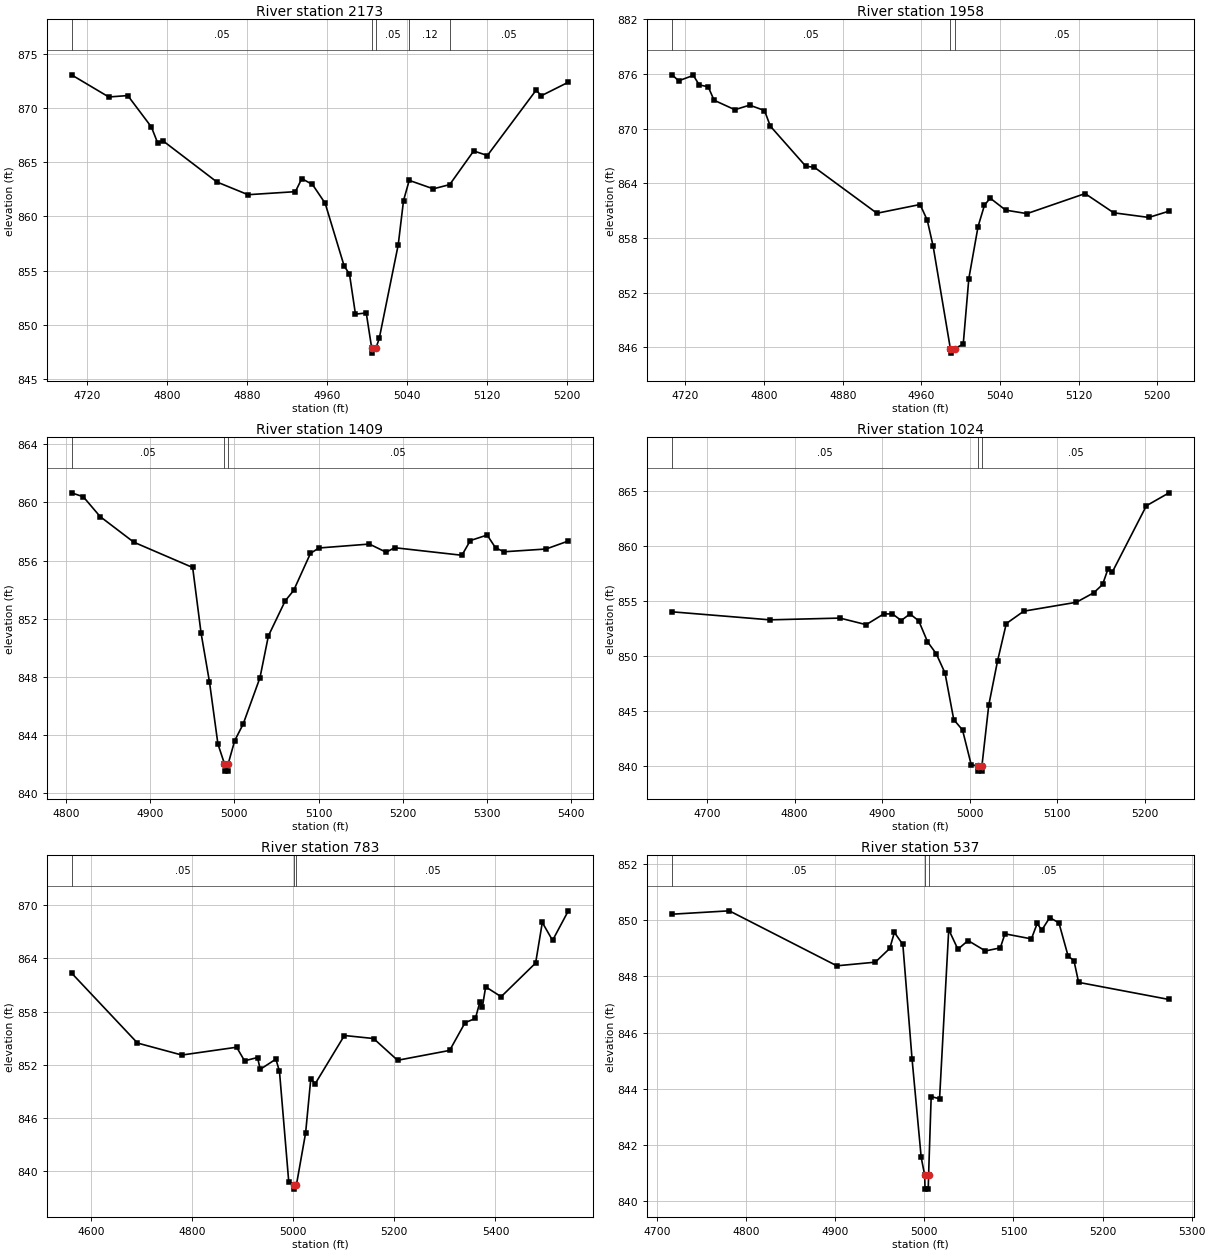
Type RM Length L Ch R = 1,2173,215,215,215
BEGIN DESCRIPTION:
Mapping XS 0b17d7d0
END DESCRIPTION:
XS GIS Cut Line= 2
      2262302.09      7143104.29      2262484.65      7142641.92
#Sta/Elev= 30
  4704.2  873.04  4741.5  871.00  4760.5  871.13  4784.1  868.24  4790.3  866.79
  4795.6  866.97  4849.7  863.17  4880.8  862.00  4928.2  862.28  4934.6  863.48
  4945.3  862.94  4958.0  861.21  4977.0  855.43  4982.3  854.70  4988.3  851.00
  4999.1  851.11  5004.5  847.91  5004.9  847.41  5008.9  847.91  5012.1  848.76
  5031.1  857.39  5036.4  861.46  5042.1  863.32  5066.2  862.54  5082.6  862.93
  5106.6  866.03  5120.3  865.61  5169.0  871.62  5174.4  871.12  5201.3  872.36
#Mann=5,-1,0
  4704.2    0.05       0  5004.5   0.033       0  5008.9    0.05       0
  5042.1    0.12       0  5082.6    0.05       0
Bank Sta=5004.5,5008.9
Exp/Cntr=0.3,0.1

Type RM Length L Ch R = 1,1958,549,549,549
BEGIN DESCRIPTION:
MDW T 077 4.0
END DESCRIPTION:
XS GIS Cut Line= 3
      2262420.70      7143200.77      2262579.00      7142960.00
      2262686.36      7142771.02
#Sta/Elev= 30
  4706.5  875.92  4713.0  875.26  4728.0  875.86  4734.0  874.81  4743.1  874.61
  4749.1  873.13  4770.2  872.09  4785.3  872.59  4800.4  872.00  4806.3  870.29
  4842.5  865.87  4851.0  865.78  4914.8  860.72  4958.7  861.68  4966.0  859.96
  4972.0  857.09  4989.5  845.86  4989.9  845.36  4993.9  845.86  5002.6  846.34
  5008.3  853.55  5017.7  859.26  5024.2  861.60  5030.0  862.38  5045.8  861.06
  5067.5  860.68  5126.6  862.88  5155.7  860.77  5191.4  860.26  5212.0  860.95
#Mann=3,-1,0
  4706.5    0.05       0  4989.5   0.033       0  4993.9    0.05       0
Bank Sta=4989.5,4993.9
Exp/Cntr=0.3,0.1

Type RM Length L Ch R = 1,1409,385,385,385
BEGIN DESCRIPTION:
Mapping XS 34c53021
END DESCRIPTION:
XS GIS Cut Line= 2
      2262897.50      7143573.95      2262897.99      7142983.45
#Sta/Elev= 30
  4806.4  860.65  4820.4  860.38  4840.4  859.02  4880.4  857.26  4950.4  855.52
  4960.4  851.01  4970.4  847.65  4980.4  843.40  4988.2  842.03  4988.6  841.53
  4992.2  841.53  4992.6  842.03  5000.4  843.63  5010.4  844.76  5030.4  847.95
  5040.4  850.82  5060.4  853.23  5070.4  853.94  5090.4  856.49  5100.4  856.86
  5160.4  857.13  5180.4  856.57  5190.4  856.88  5270.4  856.36  5280.4  857.37
  5300.4  857.75  5310.4  856.87  5320.4  856.60  5370.4  856.79  5396.9  857.34
#Mann=3,-1,0
  4806.4    0.05       0  4988.2   0.033       0  4992.6    0.05       0
Bank Sta=4988.2,4992.6
Exp/Cntr=0.3,0.1

Type RM Length L Ch R = 1,1024,241,241,241
BEGIN DESCRIPTION:
Mapping XS 1b2a184c
END DESCRIPTION:
XS GIS Cut Line= 2
      2263114.84      7143421.63      2263113.88      7142854.14
#Sta/Elev= 30
  4660.1  854.00  4771.7  853.27  4851.7  853.43  4881.7  852.83  4901.7  853.81
  4911.7  853.81  4921.7  853.21  4931.7  853.81  4941.7  853.18  4951.7  851.28
  4961.7  850.18  4971.7  848.43  4981.7  844.18  4991.7  843.24  5001.7  840.05
  5009.5  839.99  5009.9  839.49  5013.5  839.49  5013.9  839.99  5021.7  845.51
  5031.7  849.52  5041.7  852.93  5061.7  854.06  5121.7  854.87  5141.7  855.74
  5151.7  856.49  5157.8  857.89  5162.8  857.62  5201.7  863.66  5227.6  864.84
#Mann=3,-1,0
  4660.1    0.05       0  5009.5   0.033       0  5013.9    0.05       0
Bank Sta=5009.5,5013.9
Exp/Cntr=0.3,0.1

Type RM Length L Ch R = 1,783,246,246,246
BEGIN DESCRIPTION:
MDW T 077 2.0
END DESCRIPTION:
XS GIS Cut Line= 3
      2263110.83      7143668.16      2263253.89      7143260.32
      2263152.45      7142719.35
#Sta/Elev= 30
  4561.5  862.34  4692.0  854.45  4779.7  853.10  4888.1  853.98  4903.7  852.45
  4929.4  852.82  4934.7  851.49  4965.7  852.64  4972.8  851.26  4991.2  838.78
  5002.0  838.50  5002.4  838.00  5006.4  838.50  5024.5  844.33  5034.7  850.40
  5043.6  849.88  5101.2  855.30  5158.9  854.96  5206.4  852.51  5309.4  853.62
  5339.9  856.75  5360.3  857.22  5369.1  859.06  5374.2  858.56  5380.6  860.78
  5411.2  859.67  5479.4  863.46  5492.6  868.03  5512.9  866.01  5544.1  869.34
#Mann=3,-1,0
  4561.5    0.05       0  5002.0   0.033       0  5006.4    0.05       0
Bank Sta=5002,5006.4
Exp/Cntr=0.3,0.1

Type RM Length L Ch R = 1,537,417,417,417
BEGIN DESCRIPTION:
Mapping XS acab6bb5
END DESCRIPTION:
XS GIS Cut Line= 3
      2263334.52      7143414.91      2263461.97      7143245.66
      2263378.67      7142910.01
#Sta/Elev= 30
  4716.9  850.22  4781.0  850.34  4901.7  848.38  4944.9  848.51  4961.1  849.00
  4966.3  849.57  4975.8  849.14  4986.1  845.07  4996.4  841.55  5000.3  840.92
  5000.7  840.42  5004.3  840.42  5004.7  840.92  5007.6  843.72  5017.0  843.64
  5027.3  849.67  5037.6  848.97  5049.0  849.28  5068.5  848.91  5085.2  849.02
  5090.4  849.52  5120.1  849.34  5126.6  849.89  5131.7  849.65  5140.7  850.10
  5151.0  849.91  5161.3  848.73  5167.9  848.56  5173.1  847.79  5274.6  847.18
#Mann=3,-1,0
  4716.9    0.05       0  5000.3   0.033       0  5004.7    0.05       0
Bank Sta=5000.3,5004.7
Exp/Cntr=0.3,0.1

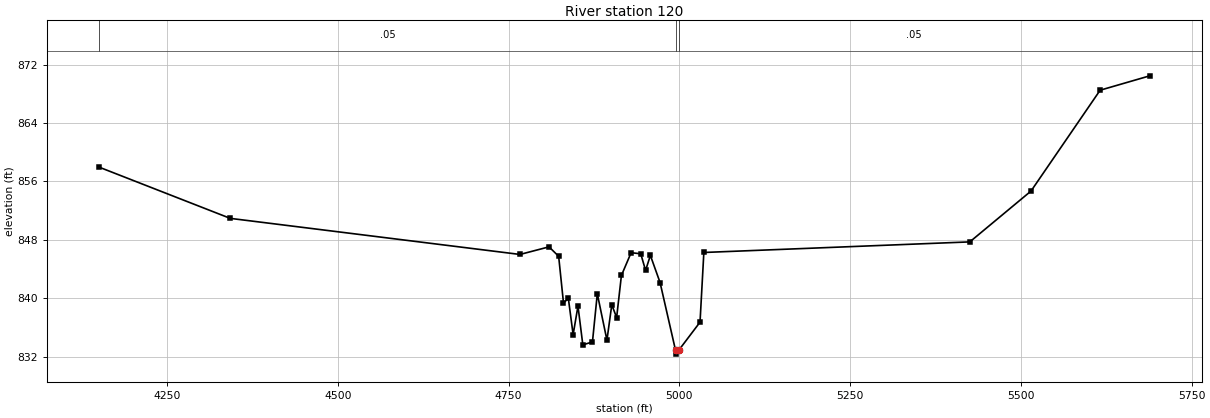
Type RM Length L Ch R = 1,120,0,0,0
BEGIN DESCRIPTION:
MDW T 077 1.0
END DESCRIPTION:
XS GIS Cut Line= 3
      2263160.00      7143612.36      2263758.75      7143009.74
      2263143.64      7142699.99
#Sta/Elev= 30
  4150.5  857.95  4342.4  850.94  4766.6  846.00  4809.1  847.04  4823.2  845.75
  4830.3  839.35  4837.4  839.99  4844.4  835.02  4851.5  838.93  4858.6  833.62
  4872.7  834.02  4879.8  840.62  4893.9  834.26  4901.0  839.11  4908.1  837.36
  4915.1  843.12  4929.3  846.24  4943.4  846.09  4950.5  843.81  4957.5  845.87
  4971.7  842.15  4994.4  832.85  4994.8  832.35  4998.8  832.85  5030.2  836.73
  5035.8  846.27  5425.2  847.72  5514.8  854.68  5616.0  868.49  5688.7  870.46
#Mann=3,-1,0
  4150.5    0.05       0  4994.4   0.033       0  4998.8    0.05       0
Bank Sta=4994.4,4998.8
Exp/Cntr=0.3,0.1

Chan Stop Cuts=-1