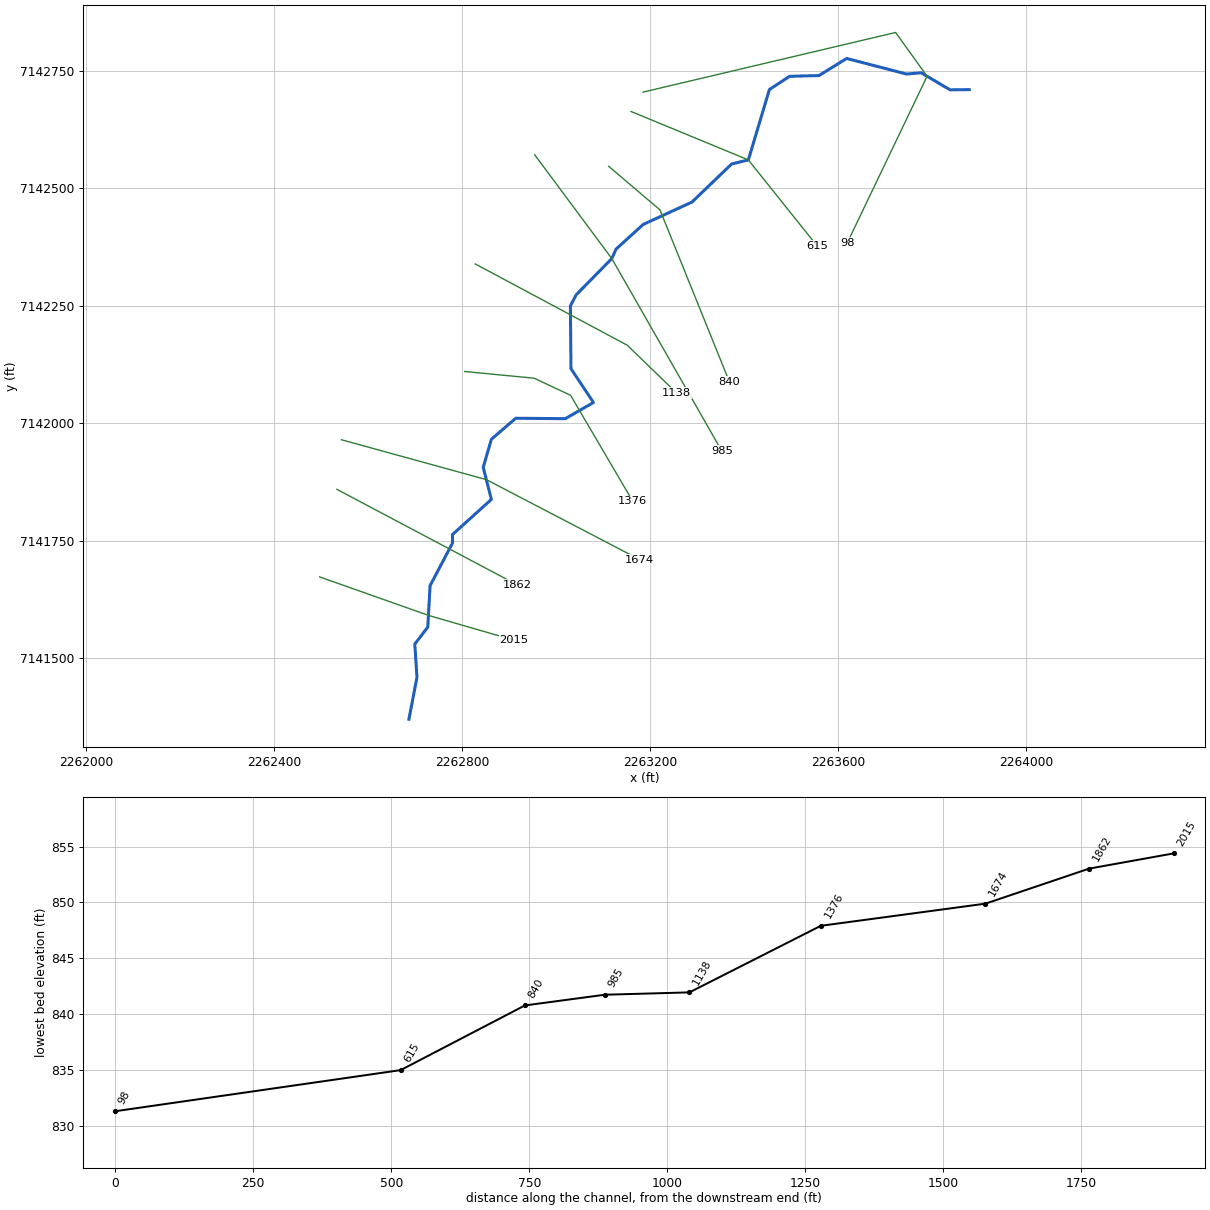
--- MDW T 078.prj (project) ---

Proj Title=MDW T 078 Base Level Engineering
Current Plan=p01
Default Exp/Contr=0.3,0.1
English Units
Geom File=g01
Flow File=f01
Plan File=p01
BEGIN DESCRIPTION:
MDW T 078
END DESCRIPTION:

--- MDW T 078.p01 (plan) ---

Plan Title=Multiple Run
Short Identifier=Multiple
Geom File=g01
Flow File=f01
Subcritical Flow
K Sum by GR= 0
Std Step Tol= 0.01
Critical Tol= 0.01
Num of Std Step Trials= 20
Max Error Tol= 0.3
Flow Tol Ratio= 0.001
Split Flow NTrial= 30
Split Flow Tol= 0.02
Split Flow Ratio= 0.02
Log Output Level= 0
Friction Slope Method= 1
Unsteady Friction Slope Method= 2
Unsteady Bridges Friction Slope Method= 1
Parabolic Critical Depth
Global Vel Dist=  1 , 1 , 1
Global Log Level= 0
CheckData=True
Encroach Param= -1, 0, 0, 0
BEGIN DESCRIPTION:
Multiple Run
END DESCRIPTION:

--- MDW T 078.f01 (steady flow) ---

Flow Title=Multiple
Number of Profiles=7
Profile Names=10-year,25-year,50-year,1pct_min,100-year,1pct_plu,500-year
River Rch & RM= MDW T 078,Reach-1,2015
     487     666     813     494     987    1968    1454
Boundary for River Rch & Prof#=MDW T 078,Reach-1,1
Up Type=0
Dn Type=3
Dn Slope=0.005
Boundary for River Rch & Prof#=MDW T 078,Reach-1,2
Up Type=0
Dn Type=3
Dn Slope=0.005
Boundary for River Rch & Prof#=MDW T 078,Reach-1,3
Up Type=0
Dn Type=3
Dn Slope=0.005
Boundary for River Rch & Prof#=MDW T 078,Reach-1,4
Up Type=0
Dn Type=3
Dn Slope=0.005
Boundary for River Rch & Prof#=MDW T 078,Reach-1,5
Up Type=0
Dn Type=3
Dn Slope=0.005
Boundary for River Rch & Prof#=MDW T 078,Reach-1,6
Up Type=0
Dn Type=3
Dn Slope=0.005
Boundary for River Rch & Prof#=MDW T 078,Reach-1,7
Up Type=0
Dn Type=3
Dn Slope=0.005

--- MDW T 078.g01 (geometry) ---

Geom Title=Existing Conditions

River Reach=MDW T 078,Reach-1
Reach XY= 30
      2262686.34      7141369.79      2262703.43      7141459.04
      2262698.85      7141529.80      2262726.46      7141565.89
      2262731.35      7141654.02      2262779.15      7141744.94
      2262778.97      7141762.82      2262861.85      7141837.73
      2262844.49      7141906.09      2262861.85      7141965.77
      2262913.74      7142010.51      2263019.18      7142009.55
      2263079.17      7142044.09      2263031.29      7142115.91
      2263030.04      7142249.56      2263042.39      7142273.31
      2263118.19      7142350.35      2263127.42      7142370.69
      2263185.15      7142423.12      2263288.78      7142470.54
      2263373.31      7142551.68      2263408.88      7142560.37
      2263453.67      7142710.21      2263496.62      7142738.34
      2263559.02      7142739.92      2263618.15      7142776.31
      2263745.60      7142743.17      2263776.57      7142745.93
      2263838.38      7142709.50      2263879.00      7142710.00

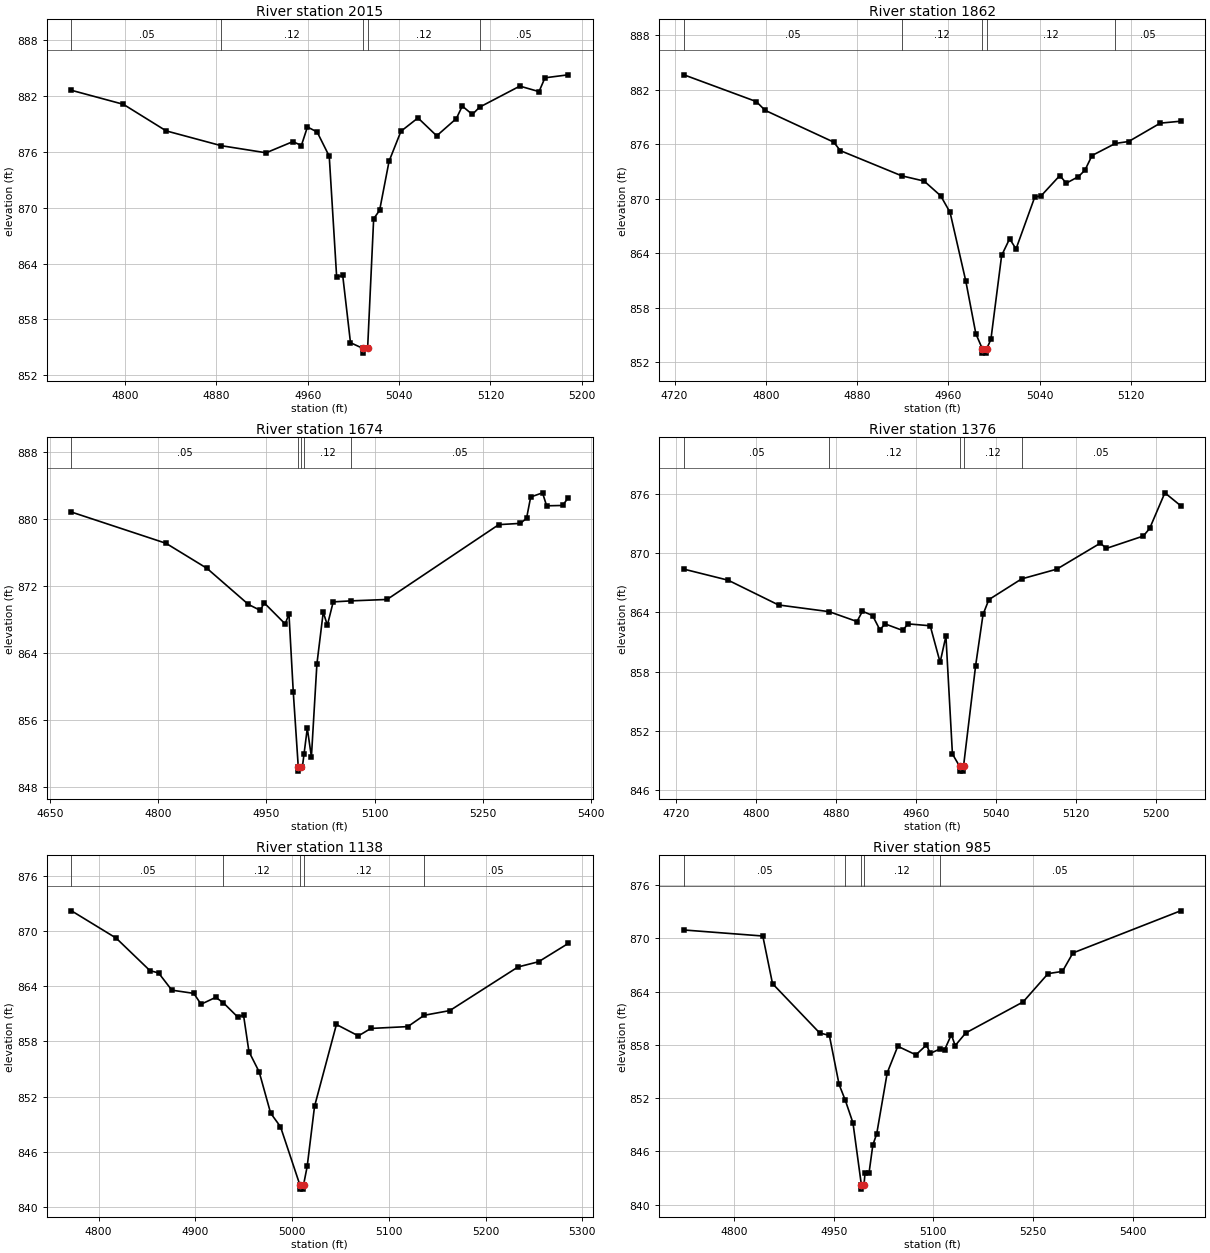
Type RM Length L Ch R = 1,2015,153,153,153
BEGIN DESCRIPTION:
MDW T 078 5.0
END DESCRIPTION:
XS GIS Cut Line= 3
      2262496.22      7141672.79      2262729.11      7141590.49
      2262909.60      7141538.25
#Sta/Elev= 30
  4753.1  882.57  4798.5  881.07  4836.0  878.22  4884.3  876.63  4923.5  875.87
  4947.0  877.07  4954.4  876.65  4959.7  878.64  4968.2  878.10  4978.8  875.50
  4985.3  862.54  4990.6  862.72  4997.4  855.51  5008.4  854.89  5008.6  854.39
  5012.4  854.89  5017.7  868.80  5022.9  869.70  5031.2  874.97  5041.6  878.18
  5056.5  879.61  5072.9  877.69  5090.1  879.54  5095.3  880.88  5104.1  879.98
  5110.4  880.76  5145.7  883.02  5162.5  882.43  5167.7  883.91  5188.0  884.23
#Mann=5,-1,0
  4753.1    0.05       0  4884.3    0.12       0  5008.4    0.07       0
  5012.4    0.12       0  5110.4    0.05       0
Bank Sta=5008.4,5012.4
Exp/Cntr=0.3,0.1

Type RM Length L Ch R = 1,1862,188,188,188
BEGIN DESCRIPTION:
Mapping XS c5f4a11d
END DESCRIPTION:
XS GIS Cut Line= 2
      2262532.96      7141859.19      2262917.54      7141655.47
#Sta/Elev= 30
  4728.2  883.62  4791.6  880.68  4799.3  879.72  4859.5  876.22  4865.2  875.29
  4919.0  872.52  4938.7  871.94  4953.2  870.32  4961.4  868.50  4975.2  860.94
  4984.0  855.16  4989.6  853.53  4989.8  853.03  4993.3  853.03  4993.6  853.53
  4997.2  854.55  5006.6  863.77  5013.6  865.60  5019.2  864.48  5035.6  870.18
  5041.2  870.32  5057.6  872.55  5063.2  871.71  5073.9  872.43  5079.6  873.14
  5085.8  874.75  5106.3  876.08  5117.9  876.29  5145.6  878.31  5163.4  878.52
#Mann=5,-1,0
  4728.2    0.05       0  4919.0    0.12       0  4989.6    0.07       0
  4993.6    0.12       0  5106.3    0.05       0
Bank Sta=4989.6,4993.6
Exp/Cntr=0.3,0.1

Type RM Length L Ch R = 1,1674,298,298,298
BEGIN DESCRIPTION:
MDW T 078 4.0
END DESCRIPTION:
XS GIS Cut Line= 3
      2262542.82      7141964.69      2262851.16      7141879.85
      2263177.58      7141709.71
#Sta/Elev= 30
  4680.2  880.84  4811.1  877.11  4867.8  874.12  4925.2  869.81  4941.8  869.09
  4947.0  870.00  4976.2  867.47  4981.4  868.68  4987.4  859.31  4994.3  850.39
  4994.5  849.89  4998.3  850.39  5000.0  850.39  5002.2  851.88  5006.8  855.01
  5012.5  851.60  5020.1  862.68  5028.9  868.89  5034.6  867.32  5042.7  870.11
  5067.2  870.23  5117.3  870.40  5272.0  879.34  5302.0  879.49  5310.5  880.10
  5316.2  882.64  5332.6  883.14  5338.3  881.59  5360.4  881.63  5368.1  882.53
#Mann=5,-1,0
  4680.2    0.05       0  4994.3   0.033       0  4998.3    0.05       0
  5002.2    0.12       0  5067.2    0.05       0
Bank Sta=4994.3,4998.3
Exp/Cntr=0.3,0.1

Type RM Length L Ch R = 1,1376,238,238,238
BEGIN DESCRIPTION:
Mapping XS e7db75d3
END DESCRIPTION:
XS GIS Cut Line= 4
      2262804.96      7142110.00      2262952.95      7142095.71
      2263030.49      7142059.27      2263163.05      7141833.34
#Sta/Elev= 30
  4728.2  868.39  4772.4  867.27  4822.7  864.76  4873.3  864.08  4901.1  863.08
  4906.6  864.12  4916.7  863.69  4923.9  862.26  4929.4  862.83  4946.7  862.18
  4952.2  862.84  4974.3  862.65  4984.2  858.94  4990.0  861.60  4996.5  849.65
  5003.6  848.41  5003.9  847.91  5007.4  847.91  5007.6  848.41  5019.7  858.62
  5027.1  863.80  5032.9  865.30  5065.6  867.40  5100.8  868.39  5144.4  871.03
  5150.2  870.49  5187.3  871.75  5193.6  872.52  5208.8  876.13  5224.5  874.83
#Mann=5,-1,0
  4728.2    0.05       0  4873.3    0.12       0  5003.6    0.07       0
  5007.6    0.12       0  5065.6    0.05       0
Bank Sta=5003.6,5007.6
Exp/Cntr=0.3,0.1

Type RM Length L Ch R = 1,1138,153,153,153
BEGIN DESCRIPTION:
Mapping XS 8cb47913
END DESCRIPTION:
XS GIS Cut Line= 3
      2262827.51      7142338.96      2263151.07      7142165.96
      2263256.27      7142064.15
#Sta/Elev= 30
  4772.0  872.19  4818.1  869.23  4853.1  865.69  4862.0  865.44  4875.7  863.57
  4898.4  863.22  4905.9  862.04  4921.1  862.79  4929.0  862.19  4943.8  860.65
  4949.8  860.86  4955.4  856.89  4966.0  854.68  4977.8  850.21  4988.0  848.73
  5007.9  842.45  5008.2  841.95  5011.7  841.95  5011.9  842.45  5015.6  844.42
  5023.2  850.95  5045.8  859.84  5068.5  858.60  5081.4  859.41  5119.6  859.61
  5136.5  860.84  5163.0  861.35  5233.5  866.09  5254.8  866.66  5285.3  868.64
#Mann=5,-1,0
  4772.0    0.05       0  4929.0    0.12       0  5007.9    0.07       0
  5011.9    0.12       0  5136.5    0.05       0
Bank Sta=5007.9,5011.9
Exp/Cntr=0.3,0.1

Type RM Length L Ch R = 1,985,145,145,145
BEGIN DESCRIPTION:
MDW T 078 2.0
END DESCRIPTION:
XS GIS Cut Line= 3
      2262954.07      7142571.26      2263118.19      7142350.35
      2263352.29      7141940.84
#Sta/Elev= 30
  4724.8  870.96  4843.4  870.28  4858.0  864.91  4928.9  859.35  4943.5  859.07
  4958.1  853.55  4967.5  851.75  4979.0  849.21  4991.6  842.24  4991.8  841.74
  4995.6  842.24  4997.1  843.53  5003.1  843.53  5008.9  846.72  5014.7  847.97
  5030.5  854.85  5046.4  857.85  5073.7  856.88  5089.5  857.99  5095.3  857.05
  5109.2  857.52  5116.9  857.46  5127.0  859.16  5132.7  857.92  5148.6  859.35
  5234.9  862.85  5272.4  866.04  5294.0  866.29  5309.8  868.37  5471.7  873.12
#Mann=5,-1,0
  4724.8    0.05       0  4967.5    0.12       0  4991.6    0.07       0
  4995.6    0.12       0  5109.2    0.05       0
Bank Sta=4991.6,4995.6
Exp/Cntr=0.3,0.1

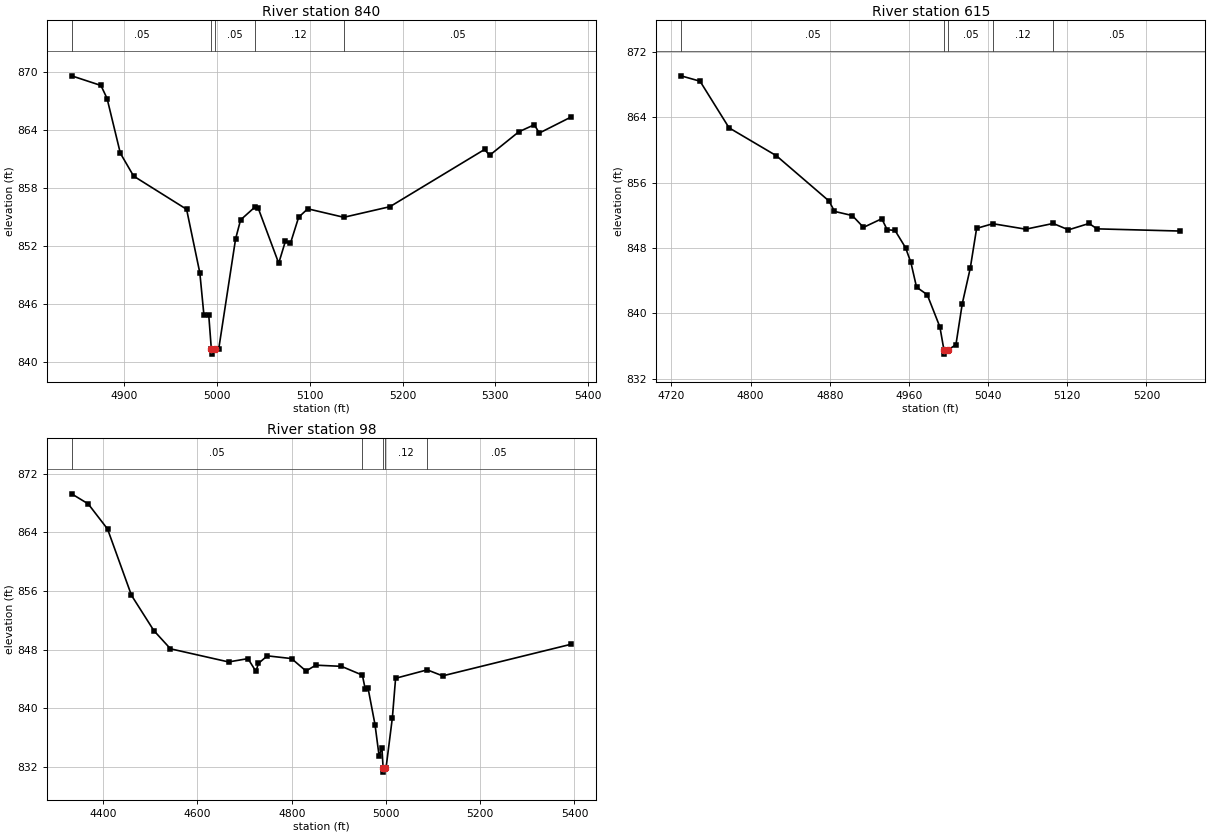
Type RM Length L Ch R = 1,840,225,225,225
BEGIN DESCRIPTION:
Mapping XS 13301fac
END DESCRIPTION:
XS GIS Cut Line= 3
      2263111.46      7142546.83      2263220.70      7142454.01
      2263368.61      7142087.80
#Sta/Elev= 30
  4843.3  869.62  4874.9  868.62  4881.5  867.27  4895.8  861.60  4910.1  859.23
  4967.2  855.79  4981.5  849.19  4985.9  844.81  4991.1  844.81  4993.9  841.28
  4994.2  840.78  4997.9  841.28  5001.8  841.29  5020.0  852.71  5025.4  854.69
  5040.6  856.00  5044.2  855.96  5066.5  850.20  5073.7  852.48  5079.1  852.25
  5088.0  854.97  5097.8  855.84  5136.7  854.96  5186.4  856.06  5288.4  861.99
  5293.8  861.38  5325.3  863.82  5342.0  864.55  5347.4  863.69  5381.6  865.35
#Mann=5,-1,0
  4843.3    0.05       0  4993.9   0.033       0  4997.9    0.05       0
  5040.6    0.12       0  5136.7    0.05       0
Bank Sta=4993.9,4997.9
Exp/Cntr=0.3,0.1

Type RM Length L Ch R = 1,615,517,517,517
BEGIN DESCRIPTION:
MDW T 078 1.0
END DESCRIPTION:
XS GIS Cut Line= 3
      2263159.13      7142663.48      2263408.88      7142560.37
      2263555.16      7142377.35
#Sta/Elev= 30
  4729.8  869.09  4749.0  868.43  4778.3  862.72  4826.1  859.30  4879.4  853.74
  4884.8  852.48  4902.8  851.97  4914.1  850.52  4932.6  851.58  4938.0  850.24
  4946.0  850.14  4956.6  848.03  4962.0  846.22  4967.7  843.20  4978.5  842.27
  4991.3  838.32  4995.4  835.49  4995.6  834.99  4999.4  835.49  5007.5  836.15
  5013.9  841.17  5022.0  845.54  5028.4  850.40  5044.8  850.97  5078.0  850.30
  5105.7  851.00  5121.2  850.22  5142.0  851.00  5150.0  850.34  5234.3  850.07
#Mann=5,-1,0
  4729.8    0.05       0  4995.4   0.033       0  4999.4    0.05       0
  5044.8    0.12       0  5105.7    0.05       0
Bank Sta=4995.4,4999.4
Exp/Cntr=0.3,0.1

Type RM Length L Ch R = 1,98,0,0,0
BEGIN DESCRIPTION:
MDW T 078 0.5
END DESCRIPTION:
XS GIS Cut Line= 4
      2263184.89      7142704.75      2263722.31      7142831.65
      2263789.30      7142738.43      2263619.60      7142384.29
#Sta/Elev= 30
  4333.0  869.27  4368.1  867.90  4409.2  864.47  4460.0  855.42  4507.5  850.61
  4542.7  848.13  4666.0  846.34  4707.1  846.79  4724.1  845.05  4729.3  846.14
  4748.2  847.17  4799.6  846.80  4830.4  845.10  4851.0  845.90  4905.5  845.74
  4949.9  844.54  4955.8  842.69  4962.0  842.75  4976.7  837.80  4985.3  833.57
  4991.4  834.58  4994.0  831.81  4994.2  831.31  4998.0  831.81  5000.0  831.81
  5013.6  838.75  5020.4  844.11  5087.5  845.26  5120.2  844.44  5392.7  848.75
#Mann=5,-1,0
  4333.0    0.05       0  4949.9    0.12       0  4994.0    0.07       0
  4998.0    0.12       0  5087.5    0.05       0
Bank Sta=4994,4998
Exp/Cntr=0.3,0.1

Chan Stop Cuts=-1