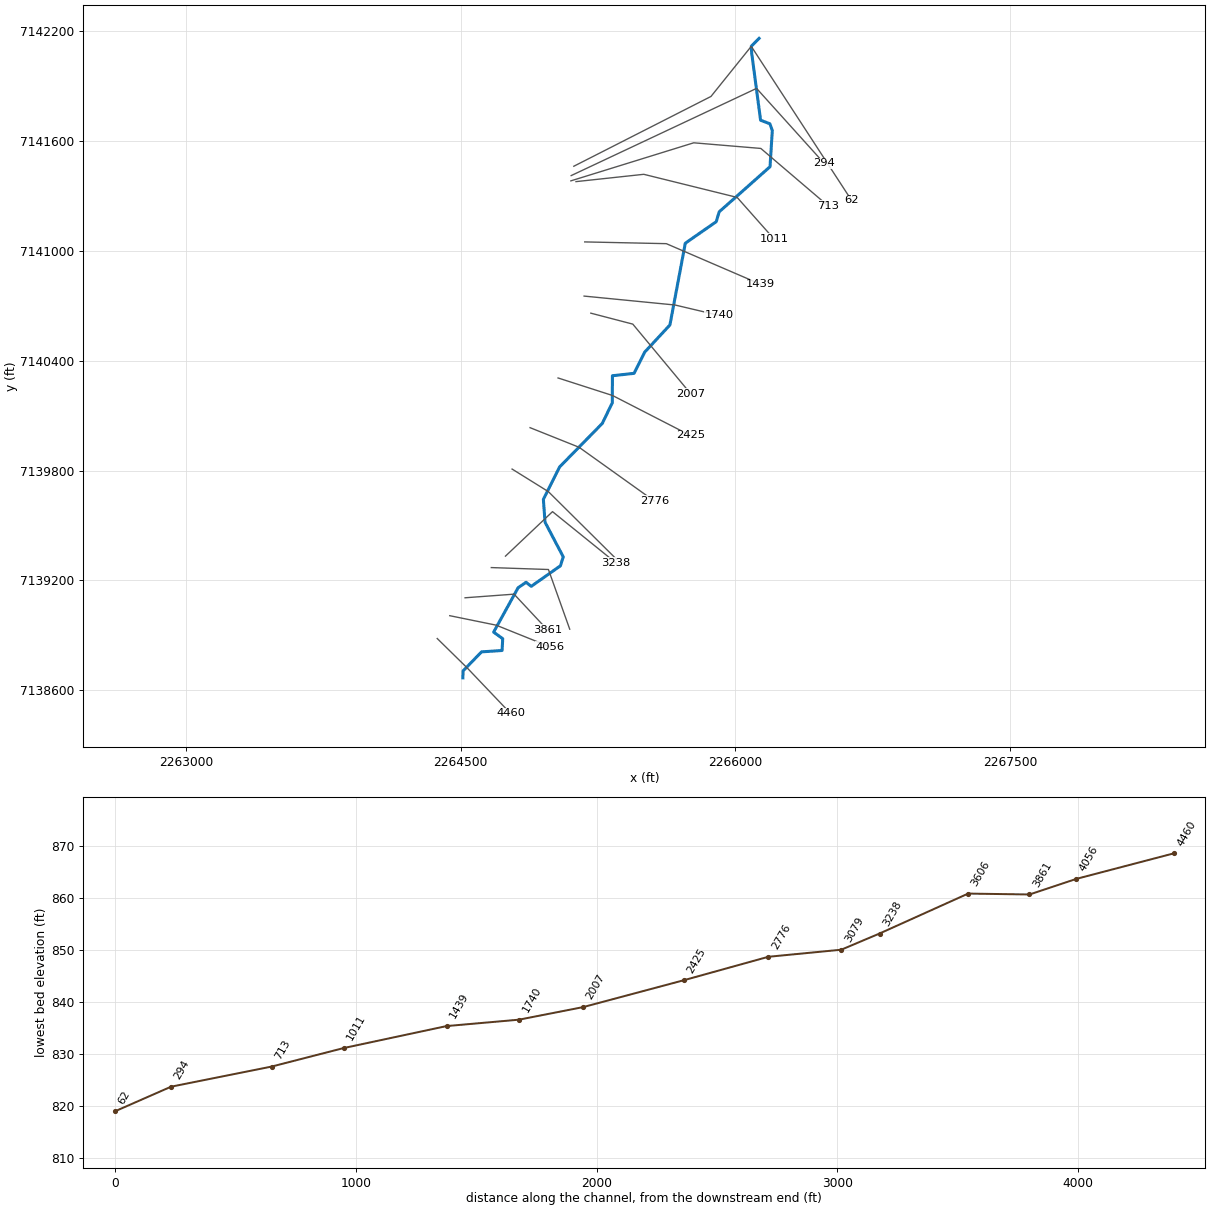
--- MDW T 079.prj (project) ---

Proj Title=MDW T 079 Base Level Engineering
Current Plan=p01
Default Exp/Contr=0.3,0.1
English Units
Geom File=g01
Flow File=f01
Plan File=p01
BEGIN DESCRIPTION:
MDW T 079
END DESCRIPTION:

--- MDW T 079.p01 (plan) ---

Plan Title=Multiple Run
Short Identifier=Multiple
Geom File=g01
Flow File=f01
Subcritical Flow
K Sum by GR= 0
Std Step Tol= 0.01
Critical Tol= 0.01
Num of Std Step Trials= 20
Max Error Tol= 0.3
Flow Tol Ratio= 0.001
Split Flow NTrial= 30
Split Flow Tol= 0.02
Split Flow Ratio= 0.02
Log Output Level= 0
Friction Slope Method= 1
Unsteady Friction Slope Method= 2
Unsteady Bridges Friction Slope Method= 1
Parabolic Critical Depth
Global Vel Dist=  1 , 1 , 1
Global Log Level= 0
CheckData=True
Encroach Param= -1, 0, 0, 0
BEGIN DESCRIPTION:
Multiple Run
END DESCRIPTION:

--- MDW T 079.f01 (steady flow) ---

Flow Title=Multiple
Number of Profiles=7
Profile Names=10-year,25-year,50-year,1pct_min,100-year,1pct_plu,500-year
River Rch & RM= MDW T 079,Reach-1,4460
     684     955    1183     729    1455    2903    2204
Boundary for River Rch & Prof#=MDW T 079,Reach-1,1
Up Type=0
Dn Type=3
Dn Slope=0.005
Boundary for River Rch & Prof#=MDW T 079,Reach-1,2
Up Type=0
Dn Type=3
Dn Slope=0.005
Boundary for River Rch & Prof#=MDW T 079,Reach-1,3
Up Type=0
Dn Type=3
Dn Slope=0.005
Boundary for River Rch & Prof#=MDW T 079,Reach-1,4
Up Type=0
Dn Type=3
Dn Slope=0.005
Boundary for River Rch & Prof#=MDW T 079,Reach-1,5
Up Type=0
Dn Type=3
Dn Slope=0.005
Boundary for River Rch & Prof#=MDW T 079,Reach-1,6
Up Type=0
Dn Type=3
Dn Slope=0.005
Boundary for River Rch & Prof#=MDW T 079,Reach-1,7
Up Type=0
Dn Type=3
Dn Slope=0.005

--- MDW T 079.g01 (geometry) ---

Geom Title=Existing Conditions

River Reach=MDW T 079,Reach-1
Reach XY= 30
      2264511.85      7138668.35      2264512.94      7138706.33
      2264613.85      7138810.43      2264726.09      7138817.91
      2264729.32      7138882.10      2264679.90      7138918.18
      2264813.44      7139160.41      2264856.90      7139190.27
      2264885.05      7139168.15      2265044.62      7139280.33
      2265059.81      7139329.16      2264960.32      7139518.48
      2264951.39      7139643.31      2265039.76      7139819.68
      2265273.17      7140057.70      2265327.80      7140170.50
      2265328.33      7140317.91      2265446.48      7140331.05
      2265505.00      7140447.25      2265642.27      7140595.03
      2265726.25      7141041.48      2265894.90      7141158.70
      2265911.24      7141212.83      2266188.82      7141459.06
      2266201.24      7141656.57      2266187.94      7141693.46
      2266137.23      7141713.03      2266088.47      7142081.15
      2266086.68      7142116.77      2266129.00      7142160.00

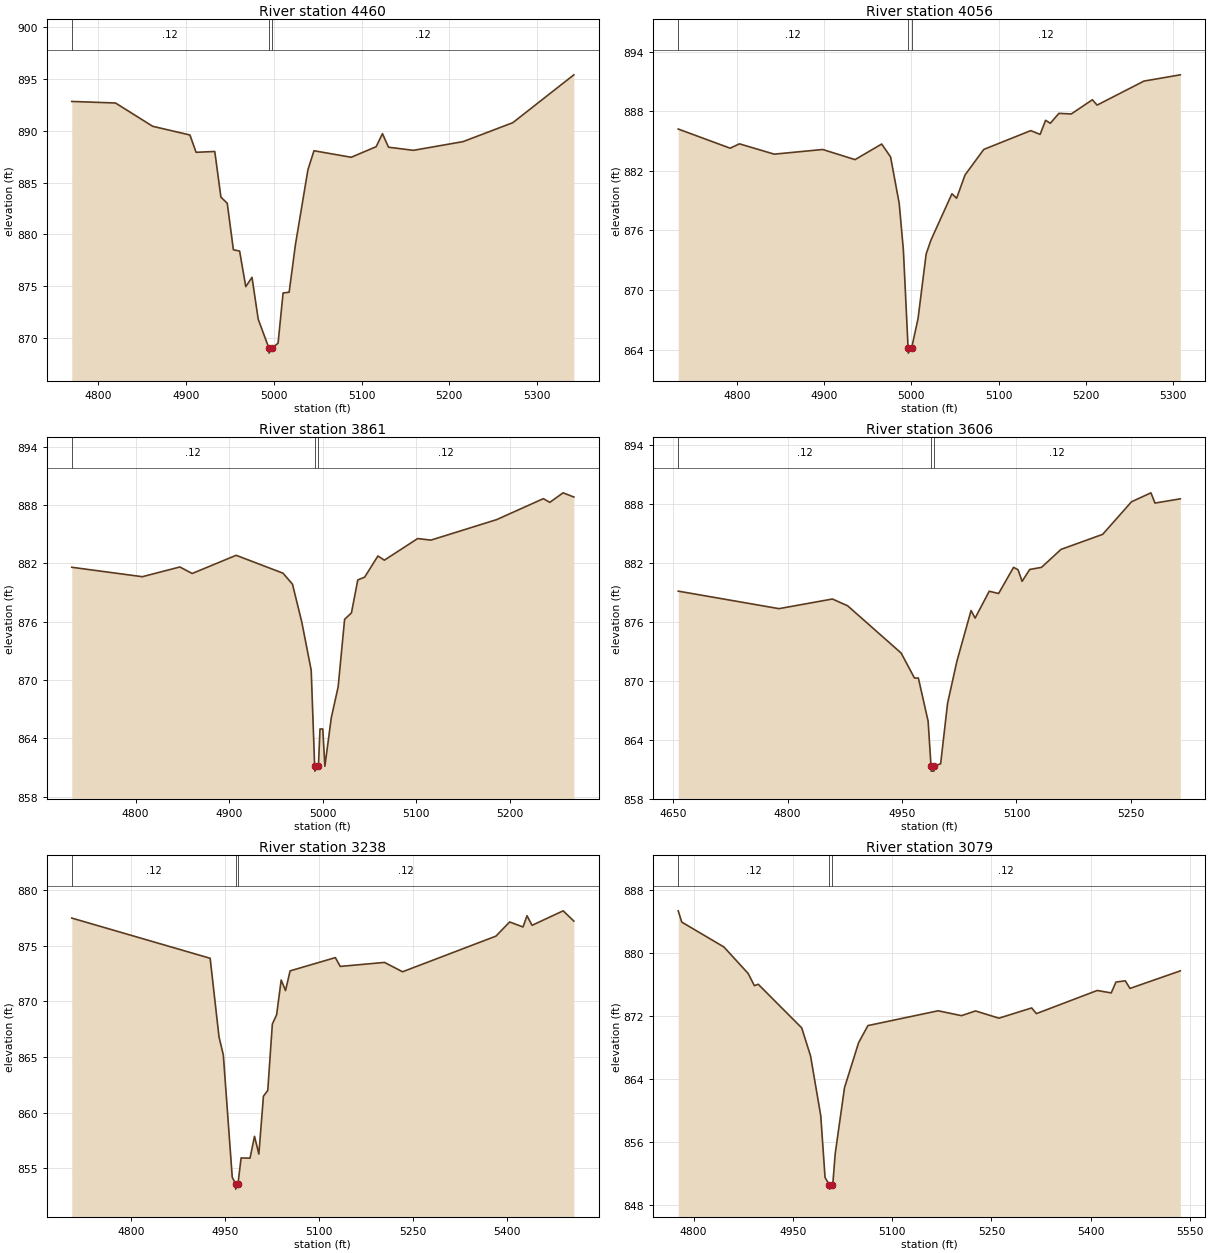
Type RM Length L Ch R = 1,4460,404,404,404
BEGIN DESCRIPTION:
MDW T 079 10.0
END DESCRIPTION:
XS GIS Cut Line= 3
      2264371.88      7138883.19      2264536.11      7138722.03
      2264771.87      7138474.55
#Sta/Elev= 30
  4769.9  892.83  4819.7  892.68  4862.1  890.43  4904.5  889.59  4911.5  887.92
  4932.8  888.00  4939.8  883.59  4947.0  883.00  4954.0  878.51  4961.1  878.38
  4968.1  874.95  4975.2  875.85  4982.3  871.80  4994.4  869.03  4994.6  868.53
  4998.4  869.03  5004.9  869.49  5010.6  874.34  5017.5  874.41  5024.7  879.02
  5038.9  886.24  5045.8  888.07  5088.2  887.44  5116.6  888.46  5123.8  889.72
  5130.7  888.41  5159.0  888.11  5215.6  888.95  5272.3  890.78  5341.8  895.40
#Mann=3,-1,0
  4769.9    0.12       0  4994.4    0.07       0  4998.4    0.12       0
Bank Sta=4994.4,4998.4
Exp/Cntr=0.3,0.1

Type RM Length L Ch R = 1,4056,195,195,195
BEGIN DESCRIPTION:
MDW T 079 9.0
END DESCRIPTION:
XS GIS Cut Line= 3
      2264440.21      7139007.87      2264693.40      7138956.22
      2264988.23      7138837.61
#Sta/Elev= 30
  4732.4  886.21  4792.0  884.28  4802.6  884.72  4842.6  883.68  4898.2  884.15
  4935.3  883.13  4965.9  884.70  4976.1  883.40  4986.0  878.72  4990.8  874.01
  4996.2  864.14  4996.4  863.64  5000.2  864.14  5007.6  867.11  5016.9  873.61
  5022.3  875.00  5046.5  879.69  5051.9  879.24  5061.5  881.58  5083.1  884.16
  5137.0  886.05  5147.7  885.67  5154.0  887.09  5159.4  886.79  5169.3  887.79
  5183.5  887.73  5207.7  889.16  5213.1  888.62  5266.9  891.04  5308.6  891.67
#Mann=3,-1,0
  4732.4    0.12       0  4996.2    0.07       0  5000.2    0.12       0
Bank Sta=4996.2,5000.2
Exp/Cntr=0.3,0.1

Type RM Length L Ch R = 1,3861,255,255,255
BEGIN DESCRIPTION:
MDW T 079 8.0
END DESCRIPTION:
XS GIS Cut Line= 3
      2264523.79      7139105.63      2264791.35      7139125.45
      2264974.56      7138929.43
#Sta/Elev= 30
  4731.7  881.59  4807.1  880.62  4847.2  881.62  4860.4  880.95  4907.4  882.82
  4957.5  880.98  4967.6  879.85  4977.6  875.93  4987.6  871.01  4991.3  861.14
  4991.5  860.64  4995.3  861.14  4997.0  864.97  5000.0  864.97  5002.2  861.14
  5009.1  866.14  5016.4  869.30  5023.3  876.24  5030.6  876.90  5037.4  880.29
  5044.7  880.57  5058.9  882.75  5065.8  882.32  5101.4  884.54  5115.6  884.38
  5185.9  886.49  5235.7  888.64  5242.6  888.26  5256.8  889.24  5268.3  888.81
#Mann=3,-1,0
  4731.7    0.12       0  4991.3    0.07       0  4995.3    0.12       0
Bank Sta=4991.3,4995.3
Exp/Cntr=0.3,0.1

Type RM Length L Ch R = 1,3606,368,368,368
BEGIN DESCRIPTION:
MDW T 079 7.0
END DESCRIPTION:
XS GIS Cut Line= 3
      2264667.00      7139270.57      2264979.00      7139260.00
      2265095.27      7138934.10
#Sta/Elev= 30
  4656.6  879.10  4788.7  877.32  4858.7  878.30  4878.7  877.61  4948.8  872.81
  4966.3  870.27  4971.4  870.27  4984.2  865.88  4988.0  861.31  4988.3  860.81
  4991.8  860.81  4992.0  861.31  5000.6  861.56  5009.7  867.71  5021.9  871.97
  5040.5  877.13  5045.8  876.36  5064.3  879.09  5076.6  878.86  5096.2  881.52
  5102.1  881.27  5107.4  880.10  5117.4  881.30  5132.9  881.52  5158.4  883.34
  5213.0  884.87  5250.8  888.18  5276.3  889.09  5281.6  888.05  5314.8  888.48
#Mann=3,-1,0
  4656.6    0.12       0  4988.0    0.07       0  4992.0    0.12       0
Bank Sta=4988,4992
Exp/Cntr=0.3,0.1

Type RM Length L Ch R = 1,3238,159,159,159
BEGIN DESCRIPTION:
Mapping XS 2f1bd0dc
END DESCRIPTION:
XS GIS Cut Line= 3
      2264744.38      7139333.01      2265001.25      7139575.92
      2265348.54      7139295.35
#Sta/Elev= 30
  4706.0  877.47  4926.5  873.86  4940.6  866.81  4947.5  865.18  4961.7  854.21
  4966.9  853.64  4967.2  853.14  4970.9  853.64  4975.8  855.94  4990.0  855.92
  4997.2  857.88  5004.1  856.29  5011.4  861.48  5018.3  862.00  5025.6  867.96
  5032.4  868.79  5039.7  871.91  5046.6  870.96  5053.9  872.73  5126.0  873.92
  5133.8  873.13  5204.3  873.49  5233.1  872.65  5381.9  875.85  5403.7  877.12
  5425.0  876.67  5431.4  877.68  5439.4  876.82  5489.0  878.12  5506.0  877.20
#Mann=3,-1,0
  4706.0    0.12       0  4966.9    0.07       0  4970.9    0.12       0
Bank Sta=4966.9,4970.9
Exp/Cntr=0.3,0.1

Type RM Length L Ch R = 1,3079,303,303,303
BEGIN DESCRIPTION:
MDW T 079 6.0
END DESCRIPTION:
XS GIS Cut Line= 3
      2264780.56      7139808.43      2264978.79      7139685.09
      2265351.69      7139315.06
#Sta/Elev= 30
  4776.7  885.39  4782.0  883.96  4845.7  880.80  4882.3  877.44  4891.8  875.88
  4897.6  876.06  4963.3  870.52  4976.7  866.95  4992.1  859.35  4998.6  851.51
  5005.3  850.53  5005.6  850.03  5009.3  850.53  5010.2  850.53  5013.9  854.51
  5028.0  862.92  5049.3  868.64  5063.4  870.81  5169.5  872.69  5204.8  872.07
  5226.0  872.67  5261.4  871.75  5310.9  873.05  5318.0  872.33  5409.9  875.27
  5431.1  874.96  5438.2  876.34  5452.3  876.50  5459.4  875.53  5535.5  877.76
#Mann=3,-1,0
  4776.7    0.12       0  5005.3    0.07       0  5009.3    0.12       0
Bank Sta=5005.3,5009.3
Exp/Cntr=0.3,0.1

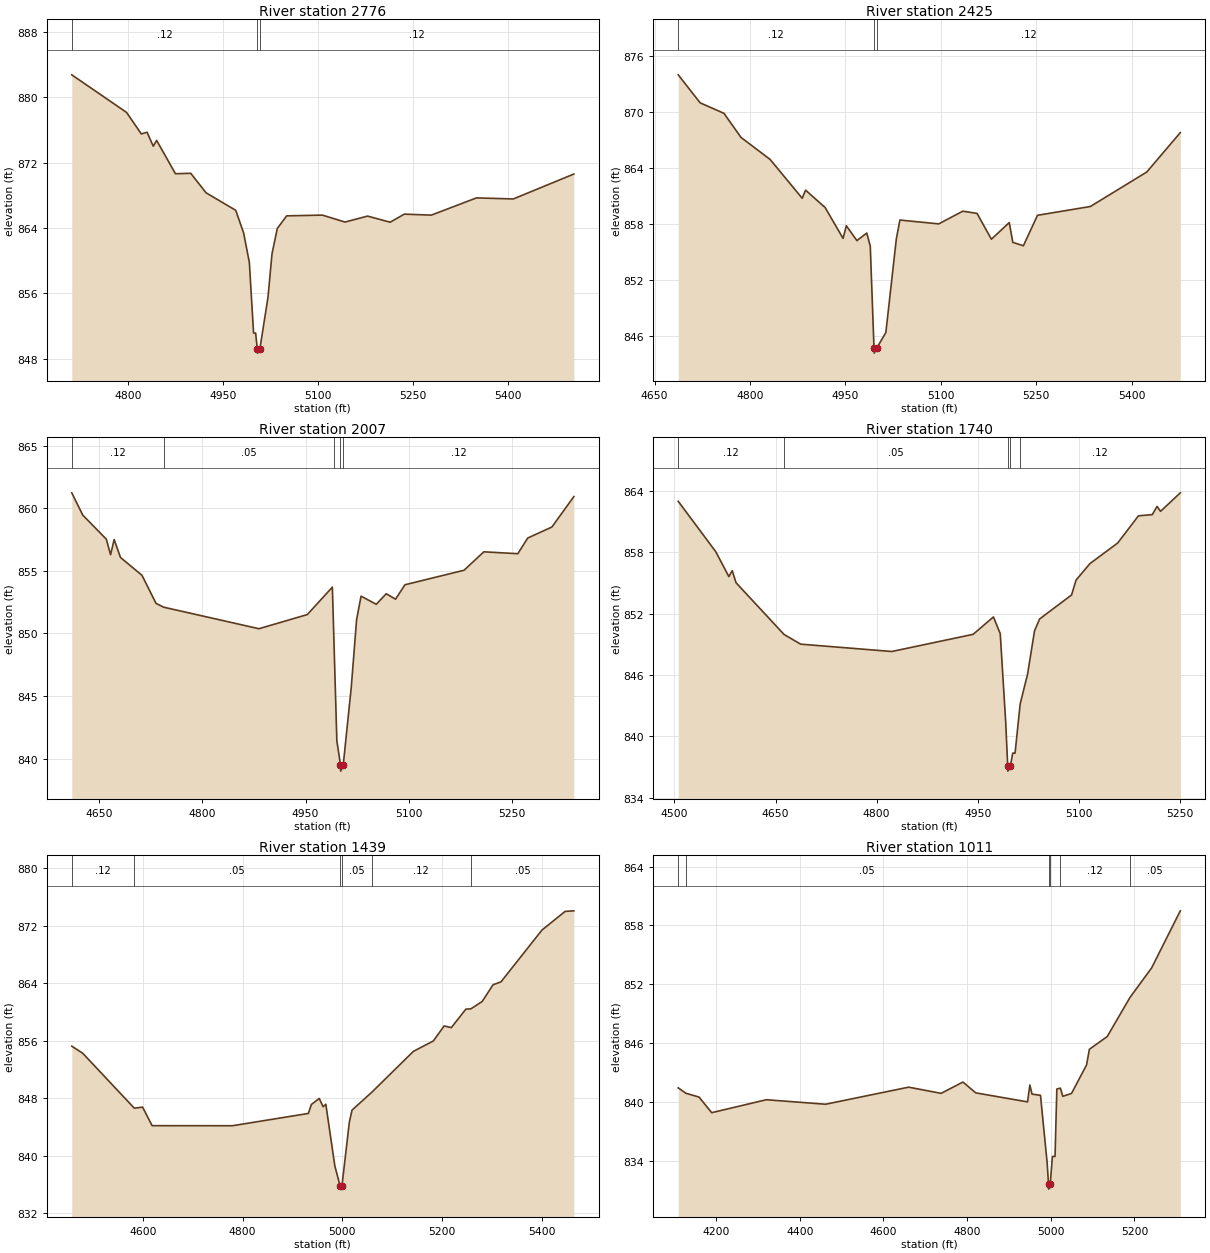
Type RM Length L Ch R = 1,2776,351,351,351
BEGIN DESCRIPTION:
MDW T 079 5.0
END DESCRIPTION:
XS GIS Cut Line= 3
      2264878.65      7140034.44      2265146.32      7139927.34
      2265556.80      7139634.04
#Sta/Elev= 30
  4711.7  882.75  4798.2  878.15  4821.5  875.51  4830.6  875.72  4840.4  874.01
  4845.7  874.72  4875.4  870.64  4899.6  870.69  4923.8  868.30  4970.6  866.16
  4983.1  863.38  4992.1  859.78  4998.8  851.13  5002.0  851.13  5004.7  849.17
  5005.0  848.67  5008.7  849.17  5021.5  855.49  5027.9  860.83  5036.2  863.93
  5051.0  865.48  5107.5  865.57  5143.1  864.72  5178.8  865.45  5214.4  864.70
  5236.8  865.69  5279.5  865.57  5350.8  867.68  5408.9  867.55  5504.5  870.60
#Mann=3,-1,0
  4711.7    0.12       0  5004.7    0.07       0  5008.7    0.12       0
Bank Sta=5004.7,5008.7
Exp/Cntr=0.3,0.1

Type RM Length L Ch R = 1,2425,418,418,418
BEGIN DESCRIPTION:
MDW T 079 4.0
END DESCRIPTION:
XS GIS Cut Line= 3
      2265031.58      7140305.73      2265329.00      7140210.00
      2265753.17      7139992.14
#Sta/Elev= 30
  4687.1  873.95  4721.6  870.95  4759.0  869.83  4785.8  867.25  4831.5  864.90
  4882.0  860.74  4887.3  861.61  4918.0  859.75  4946.2  856.45  4951.4  857.80
  4968.0  856.21  4983.5  857.02  4989.0  855.62  4994.9  844.67  4995.2  844.17
  4998.9  844.67  5013.5  846.38  5030.0  856.41  5035.6  858.41  5096.6  858.00
  5134.5  859.36  5156.9  859.12  5179.4  856.36  5207.5  858.14  5213.1  856.02
  5229.7  855.66  5251.9  858.92  5335.0  859.86  5423.7  863.55  5476.4  867.77
#Mann=3,-1,0
  4687.1    0.12       0  4994.9    0.07       0  4998.9    0.12       0
Bank Sta=4994.9,4998.9
Exp/Cntr=0.3,0.1

Type RM Length L Ch R = 1,2007,267,267,267
BEGIN DESCRIPTION:
Mapping XS 5f508744
END DESCRIPTION:
XS GIS Cut Line= 3
      2265210.47      7140659.54      2265439.60      7140599.72
      2265754.65      7140220.80
#Sta/Elev= 30
  4610.2  861.23  4626.2  859.45  4660.4  857.53  4666.6  856.29  4671.8  857.50
  4681.0  856.07  4712.3  854.64  4732.7  852.40  4743.7  852.10  4882.2  850.38
  4952.5  851.51  4988.9  853.70  4991.8  848.23  4995.4  841.44  5000.7  839.51
  5001.0  839.01  5004.7  839.51  5016.3  845.67  5024.1  851.10  5030.6  852.98
  5052.7  852.33  5067.1  853.17  5080.7  852.74  5094.4  853.89  5180.3  855.05
  5209.0  856.52  5258.4  856.37  5272.8  857.62  5307.9  858.50  5339.8  860.93
#Mann=5,-1,0
  4610.2    0.12       0  4743.7    0.05       0  4991.8    0.12       0
  5000.7    0.07       0  5004.7    0.12       0
Bank Sta=5000.7,5004.7
Exp/Cntr=0.3,0.1

Type RM Length L Ch R = 1,1740,301,301,301
BEGIN DESCRIPTION:
MDW T 079 2.0
END DESCRIPTION:
XS GIS Cut Line= 3
      2265173.70      7140752.77      2265670.86      7140703.94
      2265909.43      7140647.52
#Sta/Elev= 30
  4505.7  862.98  4561.3  858.06  4580.8  855.62  4585.8  856.20  4591.4  855.02
  4662.6  849.96  4687.2  849.01  4822.5  848.29  4943.1  849.97  4973.2  851.67
  4983.3  850.04  4991.4  841.40  4994.4  837.09  4994.6  836.59  4998.4  837.09
  5001.8  838.35  5005.3  838.35  5012.9  843.17  5023.9  846.09  5034.2  850.32
  5041.7  851.47  5089.1  853.82  5095.8  855.28  5116.4  856.89  5157.5  858.90
  5188.3  861.56  5208.9  861.68  5215.9  862.48  5221.1  862.00  5250.4  863.81
#Mann=5,-1,0
  4505.7    0.12       0  4662.6    0.05       0  4994.4   0.033       0
  4998.4    0.05       0  5012.9    0.12       0
Bank Sta=4994.4,4998.4
Exp/Cntr=0.3,0.1

Type RM Length L Ch R = 1,1439,428,428,428
BEGIN DESCRIPTION:
Mapping XS fbde96ee
END DESCRIPTION:
XS GIS Cut Line= 3
      2265177.12      7141048.55      2265622.62      7141038.98
      2266137.75      7140817.06
#Sta/Elev= 30
  4457.5  855.23  4479.4  854.25  4582.9  846.61  4599.4  846.76  4618.6  844.18
  4779.5  844.17  4931.8  845.88  4937.9  847.13  4953.6  847.96  4961.4  846.81
  4966.8  847.16  4984.9  838.58  4995.2  835.86  4995.4  835.36  4999.2  835.86
  5013.9  844.64  5019.3  846.34  5058.7  848.81  5142.4  854.51  5182.3  855.95
  5204.0  858.04  5218.4  857.81  5247.6  860.38  5257.4  860.41  5280.3  861.44
  5302.0  863.76  5318.0  864.17  5400.0  871.36  5446.5  873.96  5464.0  874.04
#Mann=6,-1,0
  4457.5    0.12       0  4582.9    0.05       0  4995.2   0.033       0
  4999.2    0.05       0  5058.7    0.12       0  5257.4    0.05       0
Bank Sta=4995.2,4999.2
Exp/Cntr=0.3,0.1

Type RM Length L Ch R = 1,1011,298,298,298
BEGIN DESCRIPTION:
MDW T 079 1.5
END DESCRIPTION:
XS GIS Cut Line= 4
      2265129.47      7141377.70      2265499.54      7141417.62
      2266009.27      7141291.48      2266210.38      7141064.74
#Sta/Elev= 30
  4109.3  841.45  4127.6  840.90  4159.1  840.51  4189.3  838.92  4320.0  840.24
  4461.5  839.78  4660.1  841.52  4737.8  840.89  4790.0  842.04  4820.6  840.94
  4944.5  840.02  4950.0  841.74  4955.2  840.81  4975.4  840.69  4991.4  833.78
  4994.6  831.63  4994.8  831.13  4998.6  831.63  5003.9  834.46  5010.2  834.46
  5014.5  841.33  5023.1  841.42  5028.7  840.59  5049.6  840.88  5085.6  843.79
  5092.3  845.38  5135.0  846.68  5189.2  850.65  5241.2  853.68  5309.7  859.49
#Mann=6,-1,0
  4109.3    0.12       0  4127.6    0.05       0  4994.6   0.033       0
  4998.6    0.05       0  5023.1    0.12       0  5189.2    0.05       0
Bank Sta=4994.6,4998.6
Exp/Cntr=0.3,0.1

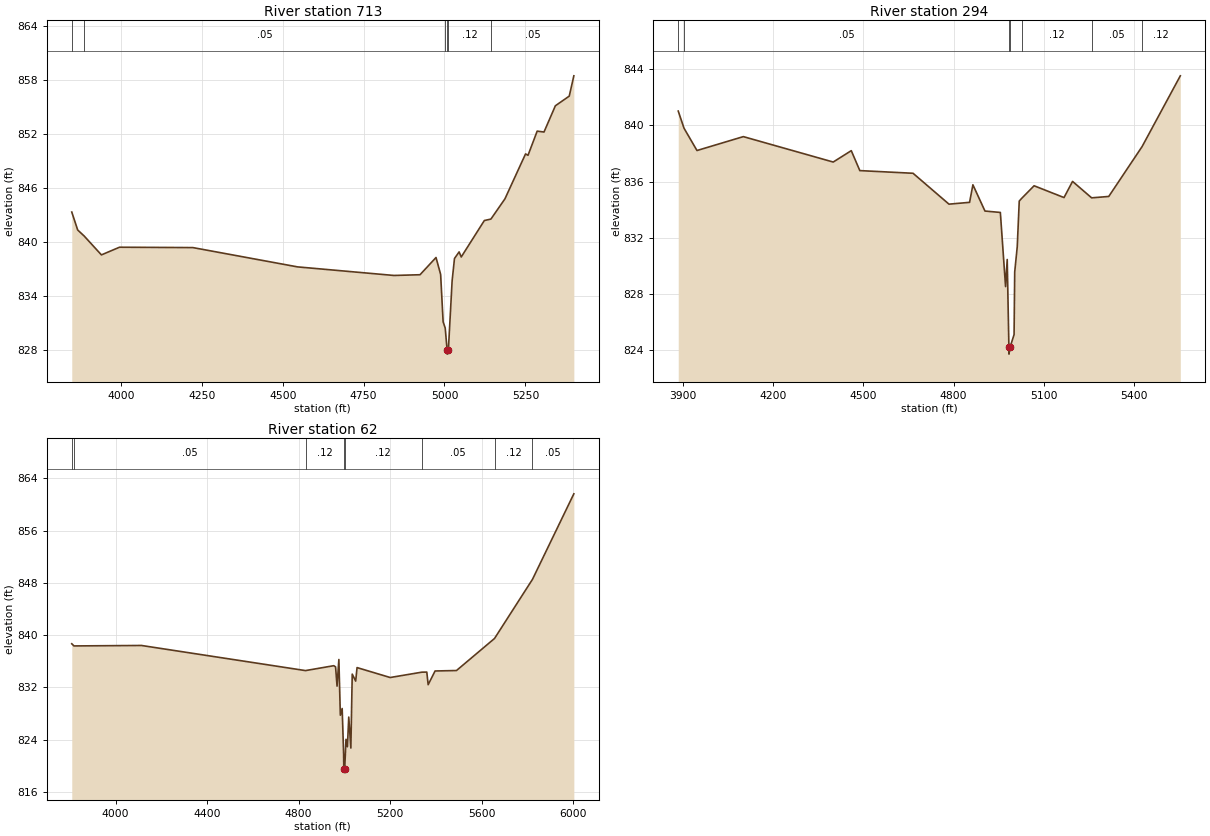
Type RM Length L Ch R = 1,713,419,419,419
BEGIN DESCRIPTION:
Mapping XS ea75a31c
END DESCRIPTION:
XS GIS Cut Line= 4
      2265101.53      7141381.86      2265772.27      7141589.64
      2266138.66      7141558.83      2266505.19      7141246.07
#Sta/Elev= 30
  3848.1  843.34  3866.4  841.35  3886.5  840.68  3939.7  838.59  3995.6  839.44
  4222.3  839.40  4546.0  837.26  4843.7  836.31  4924.4  836.39  4973.8  838.30
  4988.1  836.43  4995.8  831.17  5002.2  830.49  5008.1  828.09  5008.3  827.59
  5012.1  828.09  5023.6  835.71  5030.9  838.19  5045.2  838.92  5051.8  838.36
  5123.2  842.40  5143.5  842.56  5186.8  844.80  5250.5  849.78  5258.2  849.63
  5286.5  852.31  5307.6  852.21  5342.7  855.12  5385.6  856.19  5399.8  858.44
#Mann=6,-1,0
  3848.1    0.12       0  3886.5    0.05       0  5002.2    0.12       0
  5008.1   0.033       0  5012.1    0.12       0  5143.5    0.05       0
Bank Sta=5008.1,5012.1
Exp/Cntr=0.3,0.1

Type RM Length L Ch R = 1,294,232,232,232
BEGIN DESCRIPTION:
Mapping XS 547abb9d
END DESCRIPTION:
XS GIS Cut Line= 3
      2265103.11      7141410.62      2266115.32      7141886.74
      2266483.37      7141478.71
#Sta/Elev= 30
  3885.2  841.02  3904.4  839.80  3947.5  838.21  4101.5  839.20  4400.1  837.39
  4460.1  838.20  4488.5  836.78  4665.3  836.59  4784.8  834.39  4853.2  834.52
  4864.2  835.77  4904.3  833.90  4955.4  833.80  4972.7  828.52  4978.2  830.45
  4983.8  824.21  4984.0  823.71  4987.8  824.21  5001.0  825.10  5003.1  829.56
  5011.5  831.35  5018.2  834.61  5025.7  834.79  5067.5  835.70  5166.9  834.86
  5195.3  836.01  5258.7  834.84  5315.6  834.94  5426.3  838.49  5553.3  843.53
#Mann=7,-1,0
  3885.2    0.12       0  3904.4    0.05       0  4983.8   0.033       0
  4987.8    0.05       0  5025.7    0.12       0  5258.7    0.05       0
  5426.3    0.12       0
Bank Sta=4983.8,4987.8
Exp/Cntr=0.3,0.1

Type RM Length L Ch R = 1,62,0,0,0
BEGIN DESCRIPTION:
MDW T 079 1.0
END DESCRIPTION:
XS GIS Cut Line= 4
      2265117.53      7141461.64      2265866.42      7141842.73
      2266086.36      7142116.32      2266634.15      7141275.18
#Sta/Elev= 30
  3808.0  838.67  3817.7  838.34  4112.6  838.41  4829.9  834.56  4953.4  835.31
  4961.4  835.13  4967.8  832.18  4975.8  836.26  4982.2  827.72  4990.2  828.75
  4996.6  821.76  4997.3  819.50  4997.6  819.00  5001.3  819.50  5006.9  824.03
  5013.1  822.89  5019.0  827.44  5028.2  822.69  5034.2  834.02  5049.3  832.95
  5055.3  835.02  5200.2  833.50  5338.9  834.32  5360.2  834.33  5366.2  832.40
  5396.4  834.50  5490.0  834.57  5656.3  839.48  5822.2  848.54  6003.1  861.65
#Mann=8,-1,0
  3808.0    0.12       0  3817.7    0.05       0  4829.9    0.12       0
  4997.3    0.07       0  5001.3    0.12       0  5338.9    0.05       0
  5656.3    0.12       0  5822.2    0.05       0
Bank Sta=4997.3,5001.3
Exp/Cntr=0.3,0.1

Chan Stop Cuts=-1