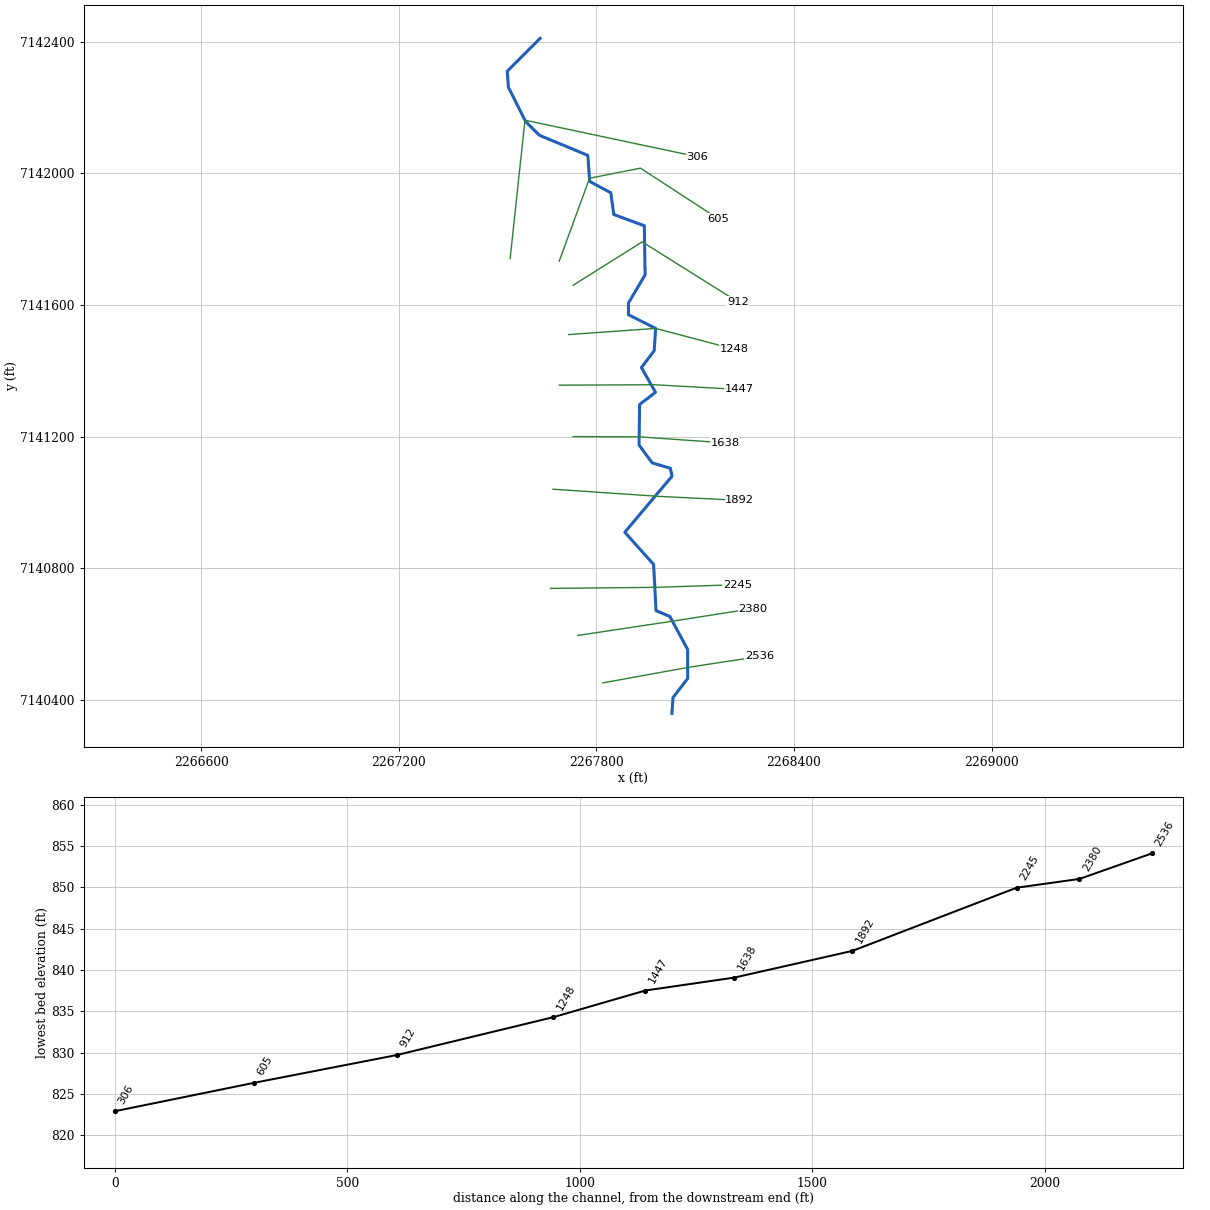
--- MDW T 080.prj (project) ---

Proj Title=MDW T 080 Base Level Engineering
Current Plan=p01
Default Exp/Contr=0.3,0.1
English Units
Geom File=g01
Flow File=f01
Plan File=p01
BEGIN DESCRIPTION:
MDW T 080
END DESCRIPTION:

--- MDW T 080.p01 (plan) ---

Plan Title=Multiple Run
Short Identifier=Multiple
Geom File=g01
Flow File=f01
Subcritical Flow
K Sum by GR= 0
Std Step Tol= 0.01
Critical Tol= 0.01
Num of Std Step Trials= 20
Max Error Tol= 0.3
Flow Tol Ratio= 0.001
Split Flow NTrial= 30
Split Flow Tol= 0.02
Split Flow Ratio= 0.02
Log Output Level= 0
Friction Slope Method= 1
Unsteady Friction Slope Method= 2
Unsteady Bridges Friction Slope Method= 1
Parabolic Critical Depth
Global Vel Dist=  1 , 1 , 1
Global Log Level= 0
CheckData=True
Encroach Param= -1, 0, 0, 0
BEGIN DESCRIPTION:
Multiple Run
END DESCRIPTION:

--- MDW T 080.f01 (steady flow) ---

Flow Title=Multiple
Number of Profiles=7
Profile Names=10-year,25-year,50-year,1pct_min,100-year,1pct_plu,500-year
River Rch & RM= MDW T 080,Reach-1,2536
     275     361     430     255     509    1017     715
Boundary for River Rch & Prof#=MDW T 080,Reach-1,1
Up Type=0
Dn Type=3
Dn Slope=0.005
Boundary for River Rch & Prof#=MDW T 080,Reach-1,2
Up Type=0
Dn Type=3
Dn Slope=0.005
Boundary for River Rch & Prof#=MDW T 080,Reach-1,3
Up Type=0
Dn Type=3
Dn Slope=0.005
Boundary for River Rch & Prof#=MDW T 080,Reach-1,4
Up Type=0
Dn Type=3
Dn Slope=0.005
Boundary for River Rch & Prof#=MDW T 080,Reach-1,5
Up Type=0
Dn Type=3
Dn Slope=0.005
Boundary for River Rch & Prof#=MDW T 080,Reach-1,6
Up Type=0
Dn Type=3
Dn Slope=0.005
Boundary for River Rch & Prof#=MDW T 080,Reach-1,7
Up Type=0
Dn Type=3
Dn Slope=0.005

--- MDW T 080.g01 (geometry) ---

Geom Title=Existing Conditions

River Reach=MDW T 080,Reach-1
Reach XY= 30
      2268029.00      7140360.00      2268032.65      7140408.49
      2268076.98      7140465.92      2268076.87      7140554.06
      2268022.97      7140654.21      2267980.93      7140671.95
      2267973.50      7140812.44      2267886.08      7140910.00
      2268029.57      7141080.41      2268024.23      7141104.36
      2267969.29      7141120.73      2267929.33      7141175.06
      2267931.00      7141298.05      2267979.23      7141335.00
      2267936.63      7141409.97      2267975.40      7141461.64
      2267979.70      7141529.11      2267897.06      7141570.78
      2267897.06      7141606.19      2267947.76      7141691.61
      2267945.33      7141840.77      2267852.62      7141874.94
      2267843.59      7141940.91      2267779.58      7141975.35
      2267773.75      7142054.56      2267626.46      7142115.73
      2267584.71      7142157.44      2267532.60      7142261.49
      2267529.00      7142310.00      2267629.00      7142410.00

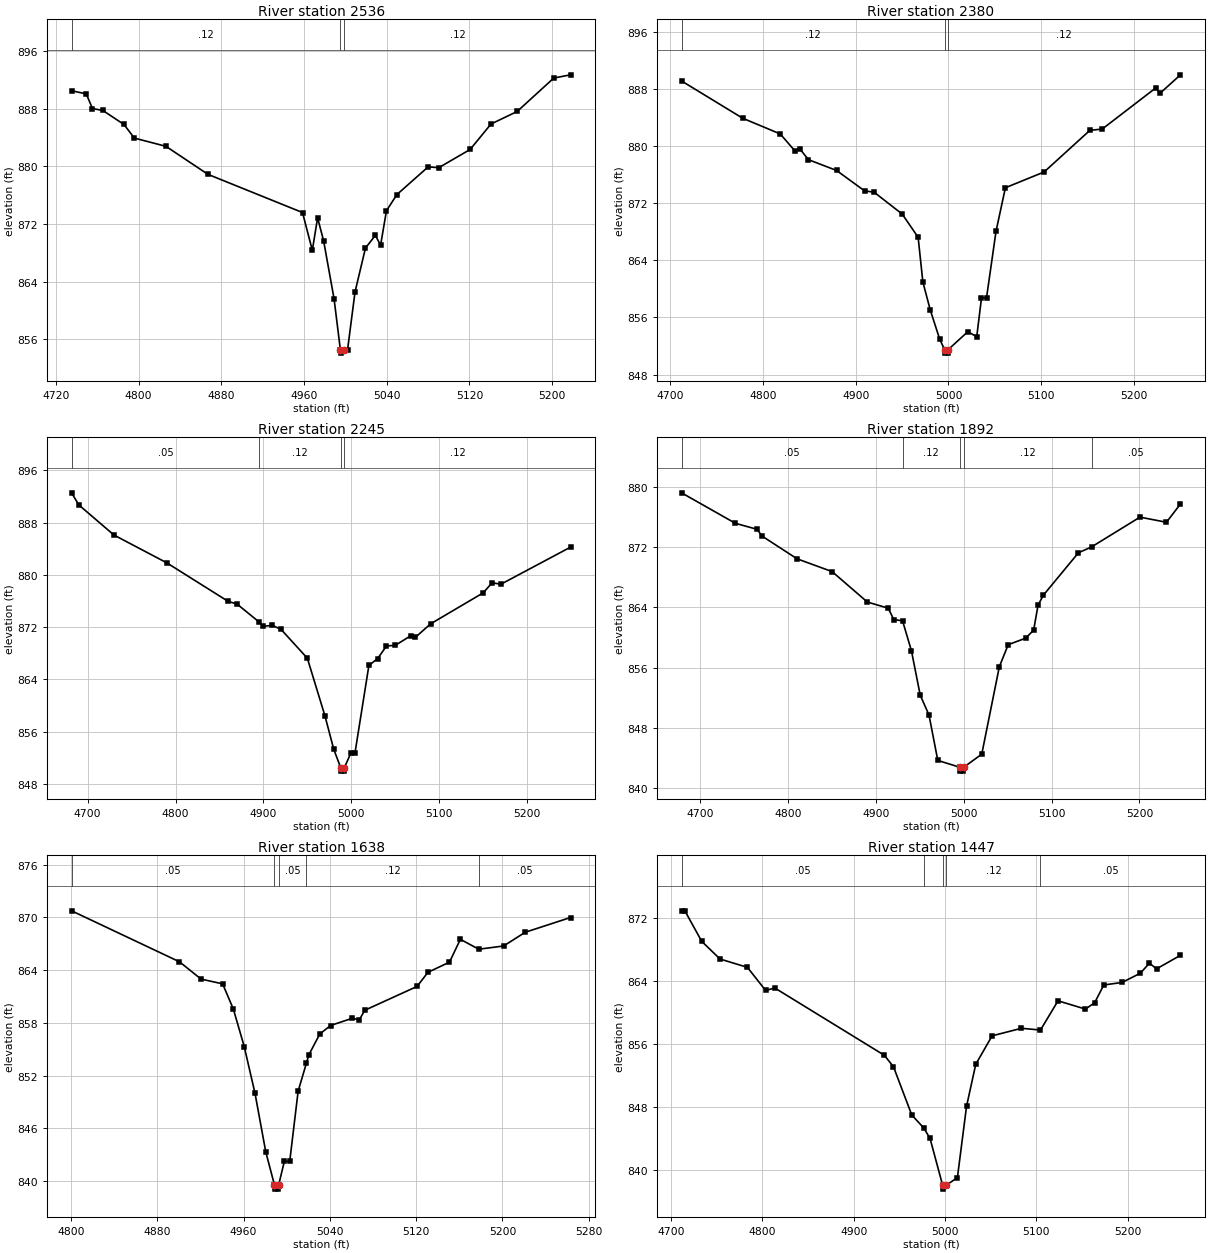
Type RM Length L Ch R = 1,2536,156,156,156
BEGIN DESCRIPTION:
MDW T 080 10.0
END DESCRIPTION:
XS GIS Cut Line= 3
      2267819.26      7140452.60      2268079.79      7140499.95
      2268295.00      7140532.79
#Sta/Elev= 30
  4735.2  890.46  4749.4  890.03  4755.3  888.00  4765.4  887.73  4785.8  885.79
  4795.9  883.90  4826.4  882.76  4867.1  878.87  4958.5  873.58  4968.0  868.34
  4973.1  872.85  4978.9  869.67  4989.0  861.65  4995.1  854.59  4995.3  854.09
  4999.1  854.59  5002.1  854.59  5009.3  862.57  5019.4  868.66  5029.0  870.42
  5034.0  869.04  5039.7  873.83  5049.8  876.07  5080.1  879.92  5090.2  879.79
  5120.6  882.32  5140.8  885.85  5166.1  887.59  5201.5  892.22  5217.7  892.67
#Mann=3,-1,0
  4735.2    0.12       0  4995.1    0.07       0  4999.1    0.12       0
Bank Sta=4995.1,4999.1
Exp/Cntr=0.3,0.1

Type RM Length L Ch R = 1,2380,135,135,135
BEGIN DESCRIPTION:
MDW T 080 9.0
END DESCRIPTION:
XS GIS Cut Line= 3
      2267743.76      7140596.70      2268028.35      7140639.56
      2268275.52      7140678.40
#Sta/Elev= 30
  4712.2  889.08  4778.2  883.86  4818.6  881.67  4834.4  879.30  4839.5  879.62
  4849.0  878.07  4879.3  876.56  4909.6  873.70  4919.8  873.52  4950.1  870.46
  4967.3  867.21  4972.4  860.96  4980.4  857.03  4990.5  852.97  4995.8  851.50
  4996.1  851.00  4999.6  851.00  4999.8  851.50  5020.9  854.00  5030.5  853.30
  5035.6  858.69  5041.1  858.78  5051.3  868.05  5061.4  874.14  5103.2  876.35
  5152.5  882.17  5165.8  882.35  5223.3  888.08  5228.4  887.39  5250.2  889.94
#Mann=3,-1,0
  4712.2    0.12       0  4995.8    0.07       0  4999.8    0.12       0
Bank Sta=4995.8,4999.8
Exp/Cntr=0.3,0.1

Type RM Length L Ch R = 1,2245,353,353,353
BEGIN DESCRIPTION:
MDW T 080 8.0
END DESCRIPTION:
XS GIS Cut Line= 3
      2267660.89      7140739.60      2267983.18      7140742.81
      2268228.14      7140750.88
#Sta/Elev= 30
  4681.8  892.56  4689.9  890.72  4729.9  886.10  4789.9  881.85  4859.9  875.93
  4869.9  875.53  4895.2  872.76  4899.9  872.12  4909.9  872.26  4919.9  871.66
  4949.9  867.23  4969.9  858.41  4979.9  853.30  4987.9  850.44  4988.2  849.94
  4991.7  849.94  4991.9  850.44  4999.5  852.74  5004.1  852.74  5019.9  866.13
  5029.9  867.18  5039.9  869.11  5049.9  869.20  5067.8  870.70  5072.8  870.43
  5090.0  872.49  5150.0  877.25  5160.0  878.79  5170.0  878.56  5249.2  884.24
#Mann=4,-1,0
  4681.8    0.05       0  4895.2    0.12       0  4987.9    0.07       0
  4991.9    0.12       0
Bank Sta=4987.9,4991.9
Exp/Cntr=0.3,0.1

Type RM Length L Ch R = 1,1892,254,254,254
BEGIN DESCRIPTION:
MDW T 080 7.0
END DESCRIPTION:
XS GIS Cut Line= 3
      2267667.84      7141040.81      2267988.61      7141019.09
      2268235.01      7141007.01
#Sta/Elev= 30
  4678.5  879.17  4739.8  875.13  4764.7  874.33  4769.9  873.46  4810.0  870.43
  4850.0  868.73  4890.1  864.70  4913.8  863.89  4920.2  862.38  4930.2  862.21
  4940.3  858.24  4950.3  852.36  4960.3  849.73  4970.3  843.72  4995.7  842.80
  4995.9  842.30  4999.4  842.30  4999.7  842.80  5020.4  844.55  5040.4  856.13
  5050.5  859.05  5070.5  859.92  5079.5  860.99  5084.5  864.29  5090.5  865.60
  5130.5  871.23  5145.4  872.00  5200.6  875.95  5230.7  875.27  5246.7  877.69
#Mann=5,-1,0
  4678.5    0.05       0  4930.2    0.12       0  4995.7    0.07       0
  4999.7    0.12       0  5145.4    0.05       0
Bank Sta=4995.7,4999.7
Exp/Cntr=0.3,0.1

Type RM Length L Ch R = 1,1638,191,191,191
BEGIN DESCRIPTION:
MDW T 080 6.0
END DESCRIPTION:
XS GIS Cut Line= 3
      2267729.02      7141200.54      2267928.42      7141199.82
      2268190.88      7141181.44
#Sta/Elev= 30
  4800.6  870.74  4900.6  864.94  4920.6  862.97  4940.6  862.43  4950.6  859.54
  4960.6  855.30  4970.6  849.98  4980.6  843.30  4988.6  839.57  4988.8  839.07
  4992.3  839.07  4992.6  839.57  4997.8  842.23  5002.8  842.23  5010.6  850.22
  5018.3  853.42  5020.6  854.37  5030.7  856.73  5040.7  857.69  5060.7  858.51
  5067.3  858.33  5072.3  859.42  5120.9  862.14  5130.9  863.74  5150.9  864.90
  5161.0  867.50  5178.0  866.37  5201.1  866.74  5221.1  868.30  5263.1  869.98
#Mann=5,-1,0
  4800.6    0.05       0  4988.6   0.033       0  4992.6    0.05       0
  5018.3    0.12       0  5178.0    0.05       0
Bank Sta=4988.6,4992.6
Exp/Cntr=0.3,0.1

Type RM Length L Ch R = 1,1447,199,199,199
BEGIN DESCRIPTION:
MDW T 080 5.0
END DESCRIPTION:
XS GIS Cut Line= 3
      2267686.90      7141356.71      2267975.50      7141358.02
      2268232.90      7141343.69
#Sta/Elev= 30
  4711.4  872.86  4715.0  872.86  4733.5  868.98  4753.5  866.74  4783.5  865.68
  4803.5  862.74  4813.5  863.06  4933.5  854.51  4943.5  853.05  4963.5  846.93
  4976.7  845.27  4983.5  843.96  4997.3  838.01  4997.5  837.51  5001.3  838.01
  5013.5  838.97  5023.5  848.03  5033.6  853.37  5051.5  856.98  5083.6  857.94
  5104.5  857.72  5123.7  861.43  5153.7  860.38  5163.8  861.18  5173.8  863.44
  5193.8  863.76  5213.8  864.93  5223.8  866.21  5231.6  865.49  5257.8  867.21
#Mann=5,-1,0
  4711.4    0.05       0  4976.7    0.12       0  4997.3    0.07       0
  5001.3    0.12       0  5104.5    0.05       0
Bank Sta=4997.3,5001.3
Exp/Cntr=0.3,0.1

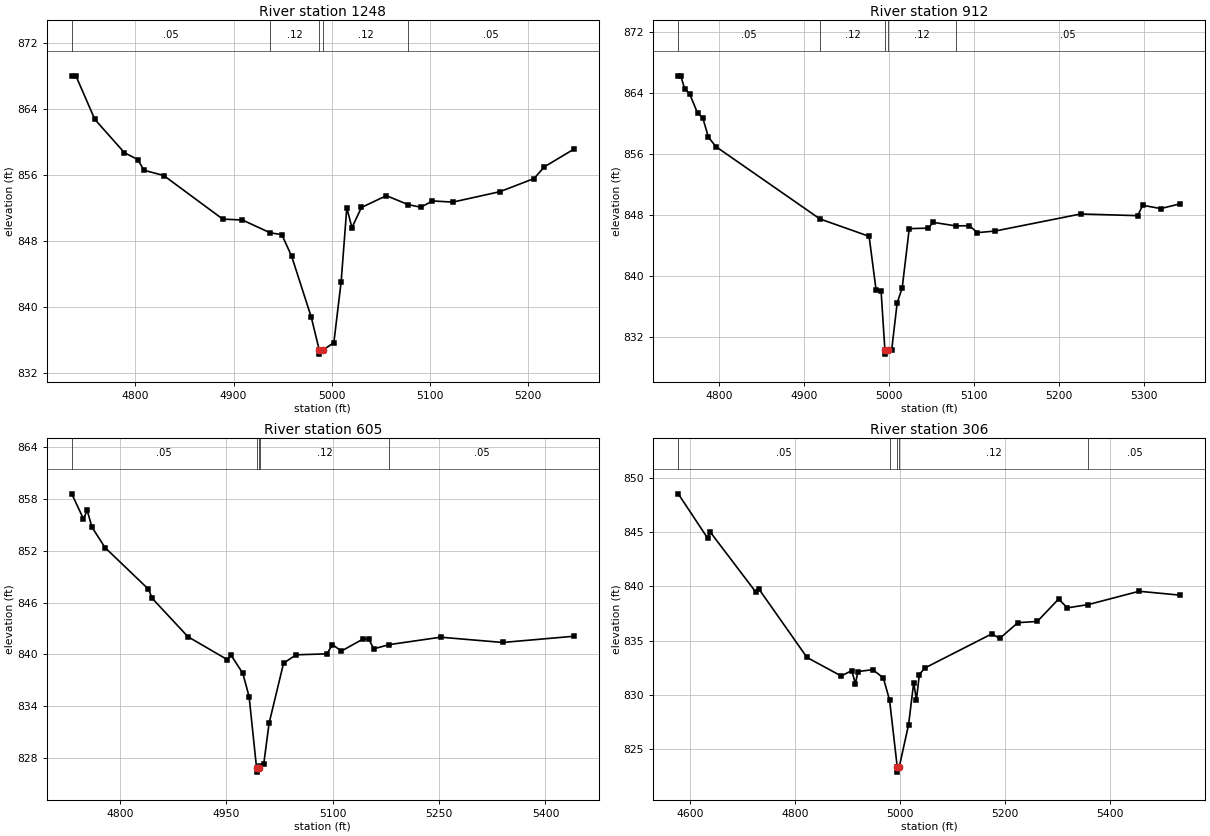
Type RM Length L Ch R = 1,1248,336,336,336
BEGIN DESCRIPTION:
MDW T 080 4.0
END DESCRIPTION:
XS GIS Cut Line= 3
      2267715.57      7141510.36      2267979.70      7141529.11
      2268218.21      7141466.08
#Sta/Elev= 30
  4735.2  867.99  4739.4  867.99  4758.7  862.71  4788.8  858.68  4802.3  857.85
  4808.8  856.55  4828.9  855.91  4889.0  850.63  4909.1  850.52  4937.3  848.97
  4949.2  848.75  4959.2  846.13  4979.2  838.74  4987.3  834.77  4987.5  834.27
  4991.3  834.77  5002.2  835.66  5009.6  843.01  5015.4  852.00  5020.6  849.59
  5030.3  852.04  5055.7  853.47  5077.8  852.39  5090.8  852.07  5102.7  852.83
  5123.4  852.69  5171.3  853.95  5206.1  855.54  5216.7  856.97  5246.7  859.10
#Mann=5,-1,0
  4735.2    0.05       0  4937.3    0.12       0  4987.3    0.07       0
  4991.3    0.12       0  5077.8    0.05       0
Bank Sta=4987.3,4991.3
Exp/Cntr=0.3,0.1

Type RM Length L Ch R = 1,912,307,307,307
BEGIN DESCRIPTION:
MDW T 080 3.0
END DESCRIPTION:
XS GIS Cut Line= 3
      2267729.03      7141660.02      2267938.93      7141791.92
      2268229.00      7141610.00
#Sta/Elev= 30
  4752.1  866.20  4755.0  866.20  4759.7  864.50  4765.6  863.81  4775.0  861.27
  4780.9  860.71  4787.5  858.18  4796.2  856.93  4918.7  847.43  4976.5  845.15
  4984.7  838.12  4990.6  837.96  4995.1  830.20  4995.3  829.70  4999.1  830.20
  5003.0  830.20  5009.5  836.43  5015.4  838.37  5023.7  846.16  5046.0  846.22
  5051.9  846.98  5078.4  846.52  5094.5  846.54  5103.8  845.63  5125.0  845.85
  5225.2  848.08  5292.3  847.86  5298.2  849.22  5319.4  848.79  5342.4  849.42
#Mann=5,-1,0
  4752.1    0.05       0  4918.7    0.12       0  4995.1    0.07       0
  4999.1    0.12       0  5078.4    0.05       0
Bank Sta=4995.1,4999.1
Exp/Cntr=0.3,0.1

Type RM Length L Ch R = 1,605,299,299,299
BEGIN DESCRIPTION:
MDW T 080 2.0
END DESCRIPTION:
XS GIS Cut Line= 4
      2267686.91      7141733.36      2267778.99      7141985.15
      2267933.64      7142015.79      2268170.22      7141861.68
#Sta/Elev= 30
  4731.9  858.60  4748.4  855.69  4753.7  856.68  4760.3  854.74  4778.9  852.36
  4840.0  847.55  4845.4  846.48  4895.7  842.04  4951.5  839.37  4956.8  839.87
  4973.2  837.78  4982.0  835.09  4992.5  826.84  4992.8  826.34  4996.5  826.84
  4997.9  827.01  5002.6  827.26  5010.2  832.01  5030.6  838.97  5048.3  839.94
  5091.8  840.05  5099.5  841.13  5112.1  840.37  5142.7  841.77  5150.7  841.79
  5157.7  840.63  5179.6  841.12  5252.1  841.98  5339.7  841.37  5440.0  842.09
#Mann=5,-1,0
  4731.9    0.05       0  4992.5    0.07       0  4996.5    0.05       0
  4997.9    0.12       0  5179.6    0.05       0
Bank Sta=4992.5,4996.5
Exp/Cntr=0.3,0.1

Type RM Length L Ch R = 1,306,0,0,0
BEGIN DESCRIPTION:
MDW T 080 1.0
END DESCRIPTION:
XS GIS Cut Line= 3
      2267537.88      7141741.00      2267582.84      7142161.41
      2268105.92      7142050.59
#Sta/Elev= 30
  4577.2  848.53  4633.1  844.46  4638.1  845.02  4725.4  839.47  4730.4  839.81
  4822.7  833.47  4888.0  831.76  4908.1  832.26  4915.0  831.06  4920.0  832.17
  4948.3  832.34  4968.4  831.58  4980.2  829.54  4994.8  823.41  4995.0  822.91
  4998.8  823.41  5016.5  827.29  5026.3  831.16  5031.4  829.55  5037.0  831.89
  5047.2  832.49  5175.3  835.64  5190.3  835.22  5225.0  836.67  5261.9  836.78
  5302.7  838.85  5319.2  838.03  5359.6  838.34  5456.1  839.56  5534.7  839.20
#Mann=5,-1,0
  4577.2    0.05       0  4980.2    0.12       0  4994.8    0.07       0
  4998.8    0.12       0  5359.6    0.05       0
Bank Sta=4994.8,4998.8
Exp/Cntr=0.3,0.1

Chan Stop Cuts=-1