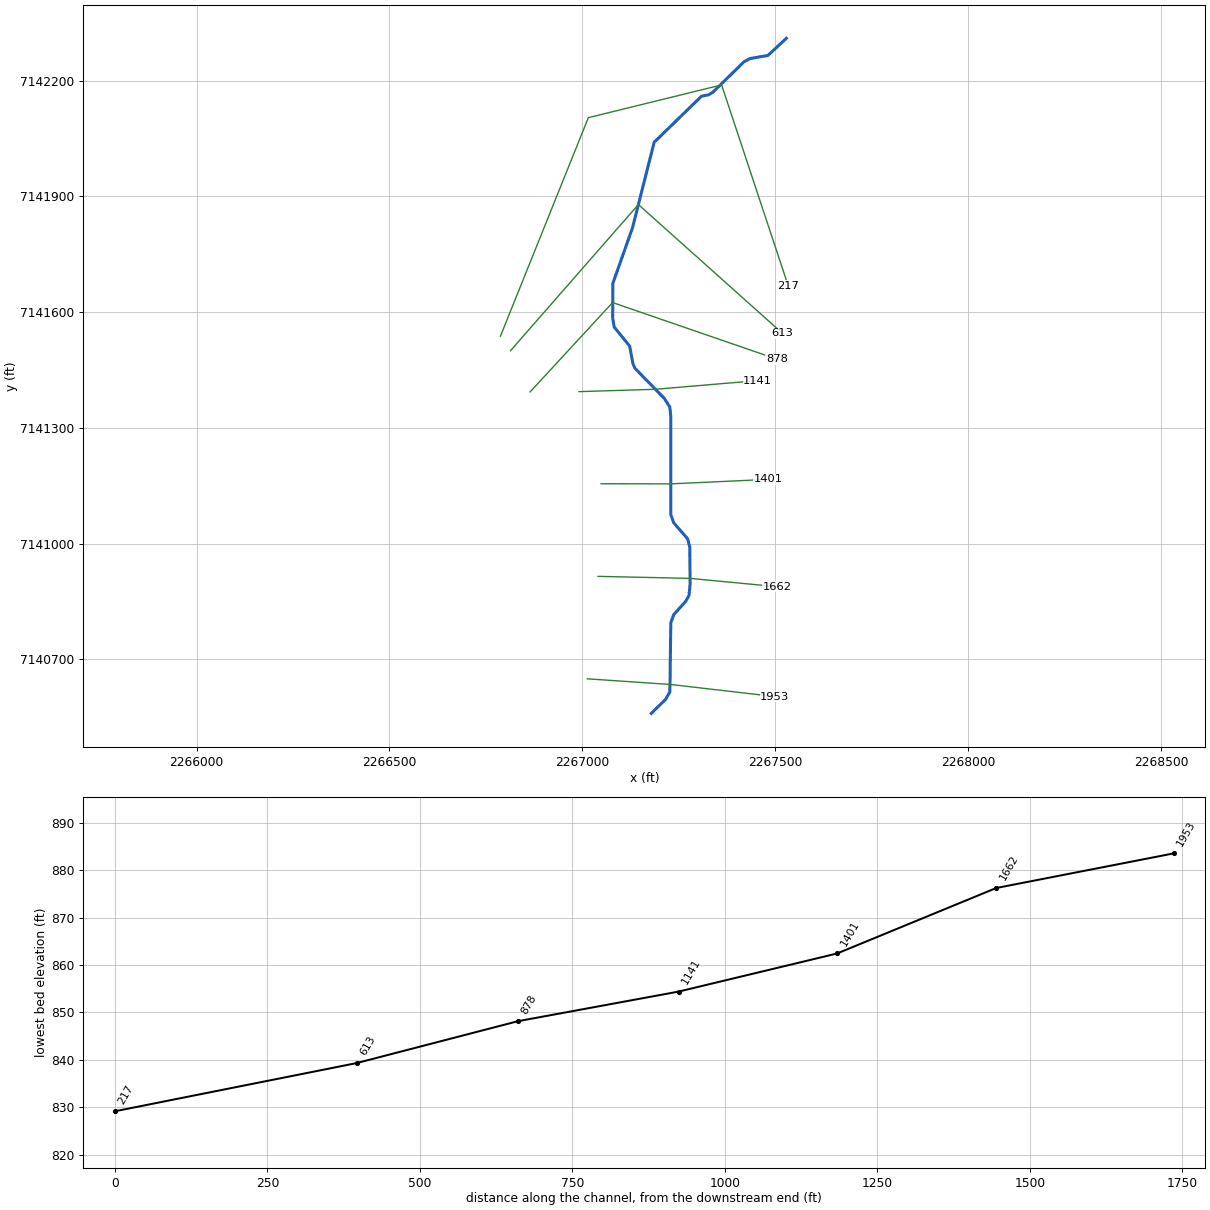
--- MDW T 081.prj (project) ---

Proj Title=MDW T 081 Base Level Engineering
Current Plan=p01
Default Exp/Contr=0.3,0.1
English Units
Geom File=g01
Flow File=f01
Plan File=p01
BEGIN DESCRIPTION:
MDW T 081
END DESCRIPTION:

--- MDW T 081.p01 (plan) ---

Plan Title=Multiple Run
Short Identifier=Multiple
Geom File=g01
Flow File=f01
Subcritical Flow
K Sum by GR= 0
Std Step Tol= 0.01
Critical Tol= 0.01
Num of Std Step Trials= 20
Max Error Tol= 0.3
Flow Tol Ratio= 0.001
Split Flow NTrial= 30
Split Flow Tol= 0.02
Split Flow Ratio= 0.02
Log Output Level= 0
Friction Slope Method= 1
Unsteady Friction Slope Method= 2
Unsteady Bridges Friction Slope Method= 1
Parabolic Critical Depth
Global Vel Dist=  1 , 1 , 1
Global Log Level= 0
CheckData=True
Encroach Param= -1, 0, 0, 0
BEGIN DESCRIPTION:
Multiple Run
END DESCRIPTION:

--- MDW T 081.f01 (steady flow) ---

Flow Title=Multiple
Number of Profiles=7
Profile Names=10-year,25-year,50-year,1pct_min,100-year,1pct_plu,500-year
River Rch & RM= MDW T 081,Reach-1,1953
     127     157     180     104     207     413     271
Boundary for River Rch & Prof#=MDW T 081,Reach-1,1
Up Type=0
Dn Type=3
Dn Slope=0.005
Boundary for River Rch & Prof#=MDW T 081,Reach-1,2
Up Type=0
Dn Type=3
Dn Slope=0.005
Boundary for River Rch & Prof#=MDW T 081,Reach-1,3
Up Type=0
Dn Type=3
Dn Slope=0.005
Boundary for River Rch & Prof#=MDW T 081,Reach-1,4
Up Type=0
Dn Type=3
Dn Slope=0.005
Boundary for River Rch & Prof#=MDW T 081,Reach-1,5
Up Type=0
Dn Type=3
Dn Slope=0.005
Boundary for River Rch & Prof#=MDW T 081,Reach-1,6
Up Type=0
Dn Type=3
Dn Slope=0.005
Boundary for River Rch & Prof#=MDW T 081,Reach-1,7
Up Type=0
Dn Type=3
Dn Slope=0.005

--- MDW T 081.g01 (geometry) ---

Geom Title=Existing Conditions

River Reach=MDW T 081,Reach-1
Reach XY= 30
      2267179.00      7140560.00      2267216.08      7140596.50
      2267227.11      7140615.78      2267229.52      7140794.78
      2267237.14      7140816.06      2267268.15      7140850.36
      2267276.75      7140865.94      2267279.47      7140894.84
      2267278.95      7140989.96      2267273.26      7141012.33
      2267237.14      7141053.94      2267229.52      7141075.22
      2267229.43      7141330.18      2267226.94      7141354.14
      2267212.54      7141376.75      2267137.16      7141453.95
      2267131.50      7141466.04      2267122.86      7141512.17
      2267082.76      7141561.56      2267078.81      7141584.92
      2267079.39      7141675.16      2267130.33      7141819.16
      2267186.32      7142040.51      2267309.02      7142159.96
      2267327.53      7142163.55      2267338.79      7142170.50
      2267419.30      7142249.27      2267434.97      7142257.65
      2267481.35      7142265.70      2267529.00      7142310.00

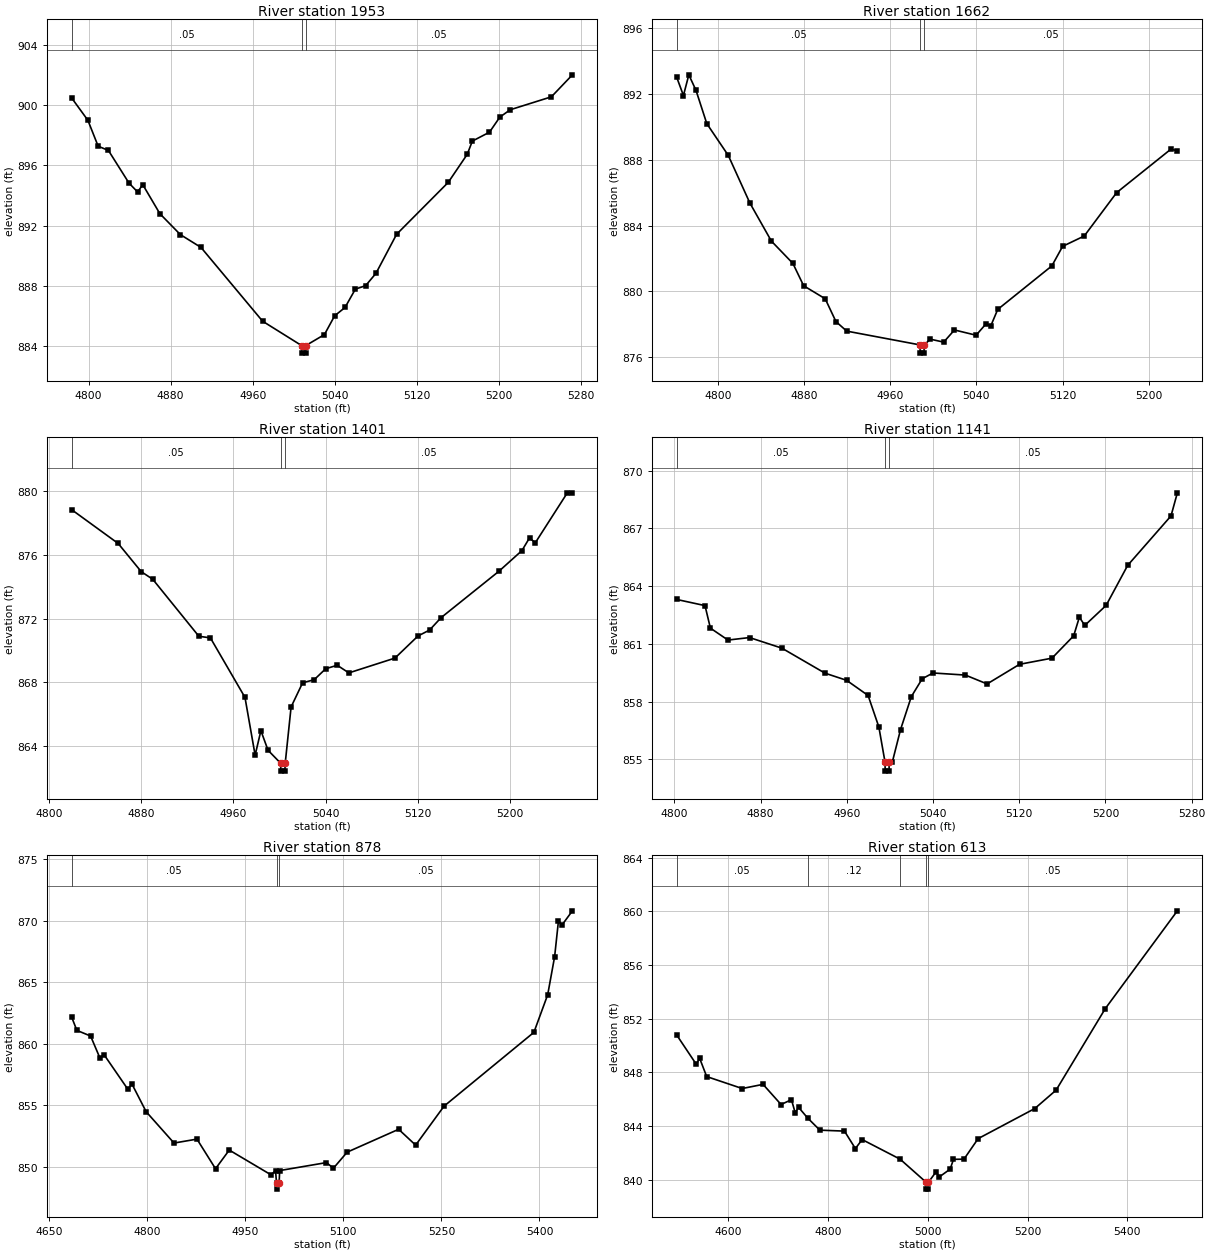
Type RM Length L Ch R = 1,1953,291,291,291
BEGIN DESCRIPTION:
MDW T 081 4.0
END DESCRIPTION:
XS GIS Cut Line= 3
      2267013.24      7140649.58      2267229.24      7140634.90
      2267499.33      7140603.58
#Sta/Elev= 30
  4783.5  900.48  4799.3  899.00  4809.3  897.28  4819.3  897.00  4839.4  894.83
  4847.8  894.24  4852.8  894.73  4869.5  892.80  4889.5  891.41  4909.6  890.56
  4969.7  885.66  5007.8  884.04  5008.1  883.54  5011.6  883.54  5011.8  884.04
  5030.0  884.77  5040.0  886.02  5050.1  886.57  5060.2  887.79  5070.2  888.02
  5080.3  888.84  5100.4  891.43  5150.8  894.88  5169.3  896.74  5174.3  897.62
  5191.0  898.21  5201.1  899.21  5211.2  899.70  5251.4  900.56  5271.9  902.02
#Mann=3,-1,0
  4783.5    0.05       0  5007.8   0.033       0  5011.8    0.05       0
Bank Sta=5007.8,5011.8
Exp/Cntr=0.3,0.1

Type RM Length L Ch R = 1,1662,261,261,261
BEGIN DESCRIPTION:
MDW T 081 3.0
END DESCRIPTION:
XS GIS Cut Line= 3
      2267041.00      7140915.21      2267279.00      7140910.00
      2267505.12      7140888.41
#Sta/Elev= 30
  4761.5  893.04  4767.8  891.92  4772.8  893.18  4779.5  892.23  4789.5  890.21
  4809.5  888.27  4829.5  885.38  4849.5  883.06  4869.5  881.70  4879.5  880.34
  4899.5  879.55  4909.5  878.16  4919.5  877.58  4987.6  876.74  4987.8  876.24
  4991.3  876.24  4991.6  876.74  4997.1  877.09  5009.6  876.91  5019.6  877.65
  5039.7  877.33  5048.5  877.99  5053.5  877.92  5059.8  878.90  5110.1  881.55
  5120.1  882.74  5140.2  883.37  5170.3  886.01  5220.6  888.65  5226.7  888.56
#Mann=3,-1,0
  4761.5    0.05       0  4987.6   0.033       0  4991.6    0.05       0
Bank Sta=4987.6,4991.6
Exp/Cntr=0.3,0.1

Type RM Length L Ch R = 1,1401,260,260,260
BEGIN DESCRIPTION:
MDW T 081 2.0
END DESCRIPTION:
XS GIS Cut Line= 3
      2267048.71      7141155.36      2267228.91      7141154.96
      2267482.74      7141166.64
#Sta/Elev= 30
  4819.8  878.85  4860.1  876.73  4880.1  874.96  4890.1  874.48  4930.1  870.90
  4940.1  870.80  4970.1  867.06  4978.9  863.43  4983.9  864.97  4990.1  863.74
  5001.0  862.93  5001.2  862.43  5004.7  862.43  5005.0  862.93  5010.1  866.46
  5020.1  867.98  5030.1  868.17  5040.1  868.86  5050.1  869.08  5060.2  868.60
  5100.2  869.53  5120.2  870.92  5130.2  871.29  5140.2  872.07  5190.3  874.98
  5210.3  876.28  5216.9  877.08  5221.9  876.77  5249.7  879.91  5254.1  879.91
#Mann=3,-1,0
  4819.8    0.05       0  5001.0   0.033       0  5005.0    0.05       0
Bank Sta=5001,5005
Exp/Cntr=0.3,0.1

Type RM Length L Ch R = 1,1141,263,263,263
BEGIN DESCRIPTION:
MDW T 081 1.0
END DESCRIPTION:
XS GIS Cut Line= 3
      2266991.44      7141394.07      2267189.15      7141400.17
      2267454.90      7141422.64
#Sta/Elev= 30
  4802.2  863.31  4828.5  862.99  4833.5  861.82  4849.8  861.20  4869.8  861.33
  4899.8  860.78  4939.8  859.48  4959.8  859.11  4979.8  858.32  4989.8  856.68
  4995.4  854.89  4995.7  854.39  4999.2  854.39  4999.4  854.89  5002.4  854.89
  5009.9  856.55  5019.9  858.26  5030.0  859.19  5040.0  859.49  5070.1  859.38
  5090.2  858.92  5120.3  859.94  5150.4  860.26  5170.5  861.42  5175.8  862.39
  5180.8  861.96  5200.6  863.00  5220.6  865.08  5260.8  867.65  5266.7  868.85
#Mann=3,-1,0
  4802.2    0.05       0  4995.4   0.033       0  4999.4    0.05       0
Bank Sta=4995.4,4999.4
Exp/Cntr=0.3,0.1

Type RM Length L Ch R = 1,878,265,265,265
BEGIN DESCRIPTION:
MDW T 081 0.9
END DESCRIPTION:
XS GIS Cut Line= 3
      2266864.74      7141393.41      2267078.63      7141625.01
      2267504.70      7141478.23
#Sta/Elev= 30
  4684.5  862.15  4692.4  861.08  4713.4  860.62  4727.6  858.84  4734.4  859.07
  4770.1  856.31  4776.9  856.69  4798.4  854.46  4841.0  851.91  4876.1  852.23
  4904.5  849.82  4925.5  851.34  4989.5  849.32  4996.3  849.67  4997.8  848.66
  4998.0  848.16  5001.8  848.66  5002.6  849.67  5074.2  850.32  5084.8  849.86
  5105.9  851.17  5184.6  853.03  5210.6  851.74  5254.0  854.91  5391.5  860.92
  5412.6  863.98  5423.2  867.08  5429.1  870.01  5434.4  869.65  5450.4  870.81
#Mann=3,-1,0
  4684.5    0.05       0  4997.8   0.033       0  5001.8    0.05       0
Bank Sta=4997.8,5001.8
Exp/Cntr=0.3,0.1

Type RM Length L Ch R = 1,613,396,396,396
BEGIN DESCRIPTION:
MDW T 081 0.8
END DESCRIPTION:
XS GIS Cut Line= 3
      2266813.91      7141500.13      2267145.51      7141879.15
      2267518.36      7141545.72
#Sta/Elev= 30
  4496.4  850.79  4535.8  848.60  4542.4  849.06  4556.6  847.69  4627.8  846.80
  4669.6  847.11  4705.7  845.61  4726.5  845.97  4734.1  844.99  4740.8  845.40
  4758.9  844.61  4783.5  843.70  4832.8  843.63  4854.7  842.33  4868.3  843.00
  4944.4  841.54  4996.9  839.81  4997.1  839.31  5000.6  839.31  5000.9  839.81
  5016.3  840.59  5023.0  840.22  5044.7  840.80  5051.4  841.53  5072.4  841.54
  5100.8  843.07  5214.4  845.31  5257.1  846.68  5355.7  852.75  5500.2  860.03
#Mann=5,-1,0
  4496.4    0.05       0  4758.9    0.12       0  4944.4    0.05       0
  4996.9   0.033       0  5000.9    0.05       0
Bank Sta=4996.9,5000.9
Exp/Cntr=0.3,0.1

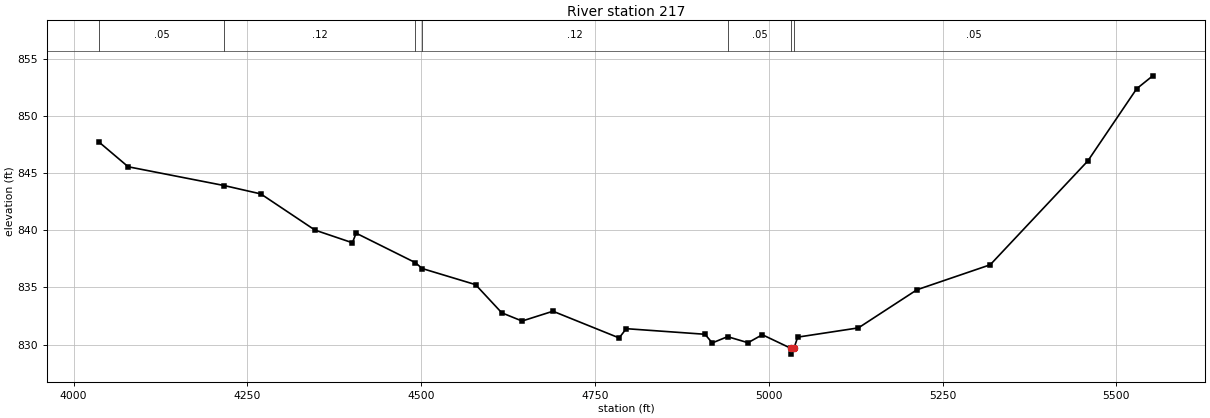
Type RM Length L Ch R = 1,217,0,0,0
BEGIN DESCRIPTION:
MDW T 081 0.7
END DESCRIPTION:
XS GIS Cut Line= 4
      2266787.90      7141537.95      2267015.75      7142104.32
      2267361.22      7142189.25      2267533.99      7141668.08
#Sta/Elev= 30
  4037.0  847.72  4078.5  845.58  4216.9  843.93  4269.3  843.20  4347.2  840.03
  4401.0  838.92  4406.4  839.76  4491.5  837.18  4501.5  836.66  4578.2  835.25
  4615.9  832.78  4645.1  832.06  4689.5  832.92  4784.7  830.58  4795.0  831.39
  4908.3  830.90  4918.6  830.14  4940.7  830.69  4970.1  830.16  4990.7  830.86
  5032.1  829.66  5032.3  829.16  5036.1  829.66  5041.6  830.65  5128.9  831.46
  5213.1  834.80  5318.5  836.99  5458.9  846.09  5529.2  852.42  5552.3  853.55
#Mann=7,-1,0
  4037.0    0.05       0  4216.9    0.12       0  4491.5    0.05       0
  4501.5    0.12       0  4940.7    0.05       0  5032.1   0.033       0
  5036.1    0.05       0
Bank Sta=5032.1,5036.1
Exp/Cntr=0.3,0.1

Chan Stop Cuts=-1