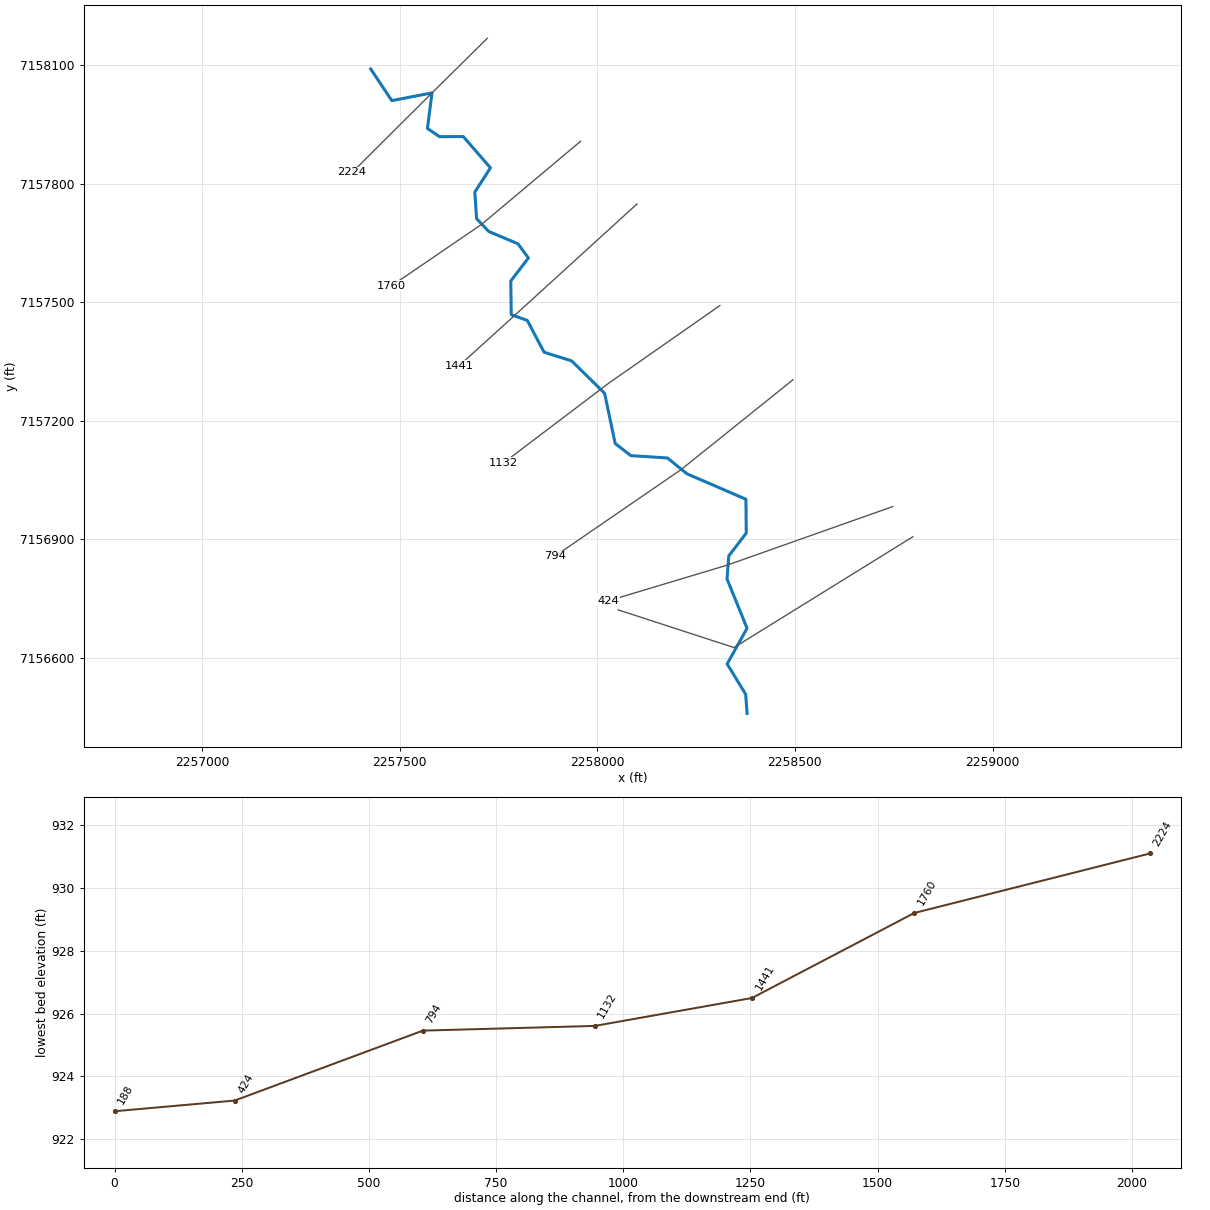
--- MDW T 083.prj (project) ---

Proj Title=MDW T 083 Base Level Engineering
Current Plan=p01
Default Exp/Contr=0.3,0.1
English Units
Geom File=g01
Flow File=f01
Plan File=p01
BEGIN DESCRIPTION:
MDW T 083
END DESCRIPTION:

--- MDW T 083.p01 (plan) ---

Plan Title=Multiple Run
Short Identifier=Multiple
Geom File=g01
Flow File=f01
Subcritical Flow
K Sum by GR= 0
Std Step Tol= 0.01
Critical Tol= 0.01
Num of Std Step Trials= 20
Max Error Tol= 0.3
Flow Tol Ratio= 0.001
Split Flow NTrial= 30
Split Flow Tol= 0.02
Split Flow Ratio= 0.02
Log Output Level= 0
Friction Slope Method= 1
Unsteady Friction Slope Method= 2
Unsteady Bridges Friction Slope Method= 1
Parabolic Critical Depth
Global Vel Dist=  1 , 1 , 1
Global Log Level= 0
CheckData=True
Encroach Param= -1, 0, 0, 0
BEGIN DESCRIPTION:
Multiple Run
END DESCRIPTION:

--- MDW T 083.f01 (steady flow) ---

Flow Title=Multiple
Number of Profiles=7
Profile Names=10-year,25-year,50-year,1pct_min,100-year,1pct_plu,500-year
River Rch & RM= MDW T 083,Reach-1,2224
     480     652     793     480     959    1913    1400
Boundary for River Rch & Prof#=MDW T 083,Reach-1,1
Up Type=0
Dn Type=3
Dn Slope=0.005
Boundary for River Rch & Prof#=MDW T 083,Reach-1,2
Up Type=0
Dn Type=3
Dn Slope=0.005
Boundary for River Rch & Prof#=MDW T 083,Reach-1,3
Up Type=0
Dn Type=3
Dn Slope=0.005
Boundary for River Rch & Prof#=MDW T 083,Reach-1,4
Up Type=0
Dn Type=3
Dn Slope=0.005
Boundary for River Rch & Prof#=MDW T 083,Reach-1,5
Up Type=0
Dn Type=3
Dn Slope=0.005
Boundary for River Rch & Prof#=MDW T 083,Reach-1,6
Up Type=0
Dn Type=3
Dn Slope=0.005
Boundary for River Rch & Prof#=MDW T 083,Reach-1,7
Up Type=0
Dn Type=3
Dn Slope=0.005

--- MDW T 083.g01 (geometry) ---

Geom Title=Existing Conditions

River Reach=MDW T 083,Reach-1
Reach XY= 30
      2257426.78      7158090.30      2257480.08      7158010.23
      2257581.81      7158029.68      2257570.36      7157939.75
      2257600.91      7157918.91      2257660.98      7157919.26
      2257729.73      7157840.10      2257690.15      7157778.64
      2257694.66      7157711.62      2257725.38      7157679.07
      2257799.18      7157648.08      2257825.80      7157612.11
      2257781.17      7157553.97      2257782.31      7157468.47
      2257822.92      7157454.17      2257865.46      7157373.55
      2257935.05      7157351.84      2258018.49      7157269.81
      2258045.27      7157142.79      2258084.69      7157112.07
      2258177.41      7157106.17      2258226.82      7157066.12
      2258376.03      7157001.68      2258376.87      7156916.06
      2258332.71      7156858.41      2258328.23      7156799.95
      2258378.89      7156675.39      2258328.54      7156585.01
      2258375.31      7156508.51      2258379.00      7156460.00

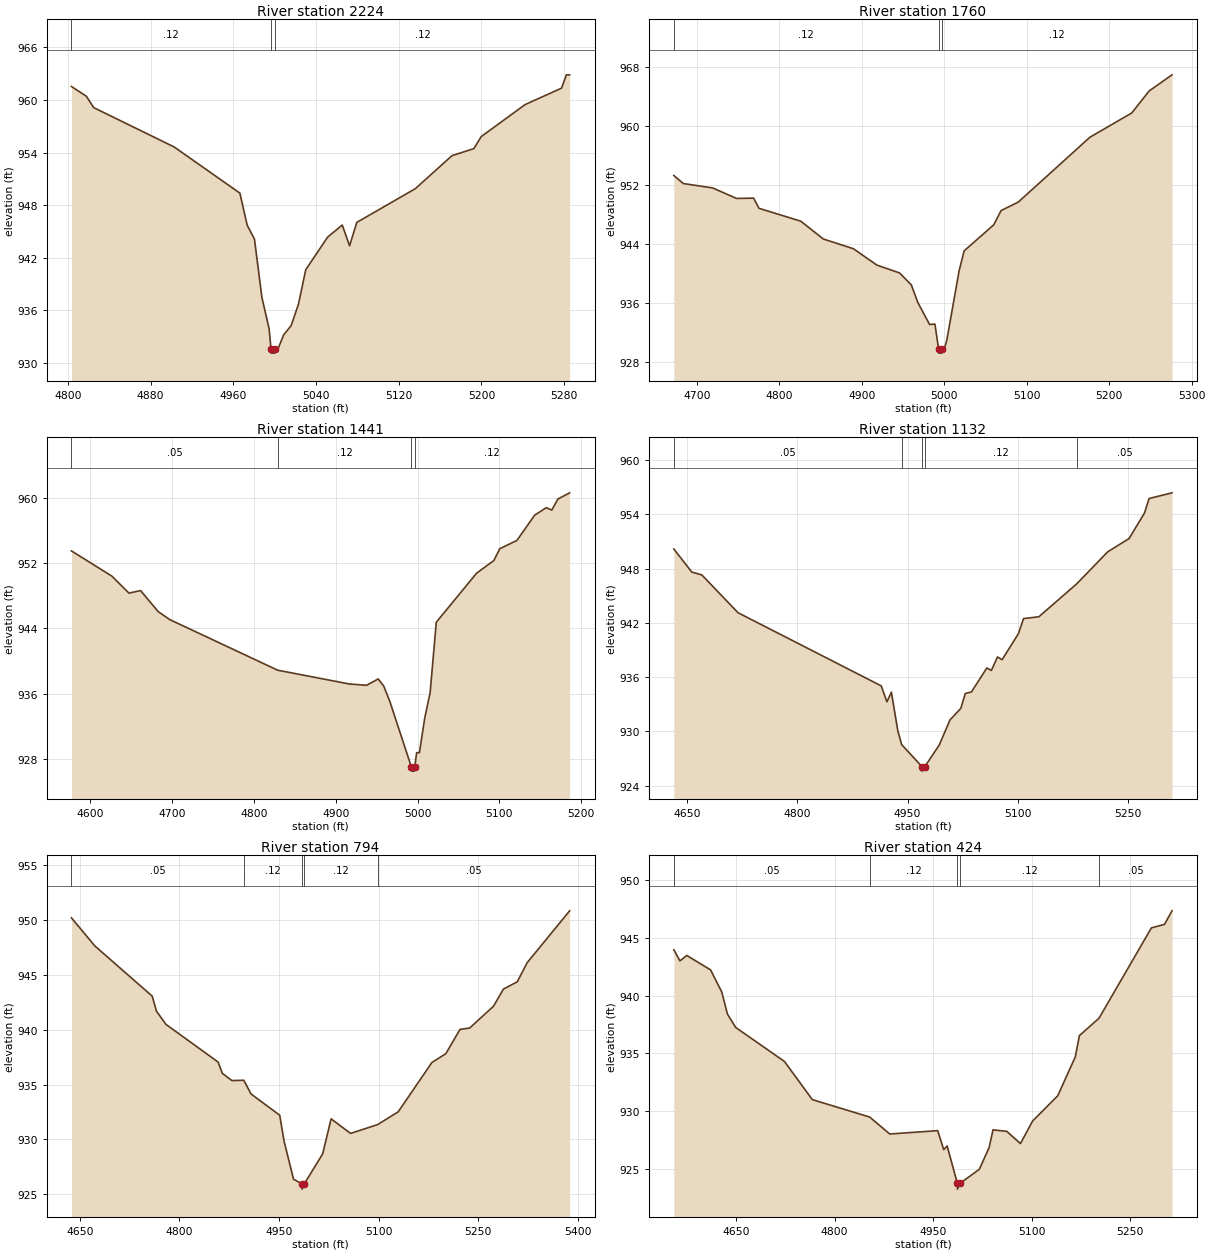
Type RM Length L Ch R = 1,2224,464,464,464
BEGIN DESCRIPTION:
MDW T 083 6.0
END DESCRIPTION:
XS GIS Cut Line= 3
      2257721.66      7158167.73      2257581.81      7158029.68
      2257379.67      7157828.35
#Sta/Elev= 30
  4803.5  961.54  4817.9  960.43  4825.0  959.13  4902.8  954.64  4966.4  949.37
  4973.5  945.70  4980.5  944.13  4987.7  937.47  4994.7  933.87  4996.5  931.61
  4996.7  931.11  5000.2  931.11  5000.5  931.61  5003.3  931.61  5008.8  933.21
  5015.9  934.23  5023.0  936.67  5030.1  940.63  5051.3  944.35  5065.4  945.73
  5072.5  943.36  5079.5  946.03  5136.1  949.88  5171.5  953.64  5192.7  954.45
  5199.8  955.82  5242.2  959.47  5277.5  961.35  5282.2  962.87  5285.3  962.87
#Mann=3,-1,0
  4803.5    0.12       0  4996.5    0.07       0  5000.5    0.12       0
Bank Sta=4996.5,5000.5
Exp/Cntr=0.3,0.1

Type RM Length L Ch R = 1,1760,319,319,319
BEGIN DESCRIPTION:
MDW T 083 5.0
END DESCRIPTION:
XS GIS Cut Line= 3
      2257957.82      7157907.36      2257706.81      7157696.69
      2257478.65      7157541.04
#Sta/Elev= 30
  4672.3  953.32  4683.8  952.23  4719.5  951.63  4748.2  950.21  4769.0  950.25
  4775.5  948.87  4826.2  947.12  4853.6  944.70  4890.0  943.38  4918.6  941.15
  4945.9  940.10  4960.2  938.47  4968.0  936.10  4982.3  933.10  4988.8  933.15
  4993.3  929.71  4993.6  929.21  4997.1  929.21  4997.3  929.71  5000.0  929.71
  5003.2  930.96  5018.1  940.38  5024.2  943.09  5060.1  946.63  5069.0  948.56
  5089.9  949.72  5176.7  958.52  5227.4  961.81  5248.5  964.80  5276.2  966.99
#Mann=3,-1,0
  4672.3    0.12       0  4993.3    0.07       0  4997.3    0.12       0
Bank Sta=4993.3,4997.3
Exp/Cntr=0.3,0.1

Type RM Length L Ch R = 1,1441,309,309,309
BEGIN DESCRIPTION:
MDW T 083 4.0
END DESCRIPTION:
XS GIS Cut Line= 3
      2258100.19      7157748.51      2257787.43      7157463.57
      2257649.64      7157338.77
#Sta/Elev= 30
  4576.9  953.47  4626.3  950.38  4647.2  948.30  4661.4  948.61  4683.0  946.03
  4697.2  945.05  4829.0  938.86  4916.7  937.17  4937.7  937.01  4951.9  937.79
  4958.7  936.91  4966.1  935.04  4992.5  927.00  4992.7  926.50  4996.2  926.50
  4996.5  927.00  4998.9  928.76  5002.3  928.76  5008.7  932.95  5015.4  936.12
  5022.9  944.73  5072.2  950.74  5093.2  952.28  5100.6  953.74  5121.5  954.75
  5143.2  957.85  5157.4  958.76  5164.1  958.47  5171.6  959.82  5185.9  960.58
#Mann=4,-1,0
  4576.9    0.05       0  4829.0    0.12       0  4992.5    0.07       0
  4996.5    0.12       0
Bank Sta=4992.5,4996.5
Exp/Cntr=0.3,0.1

Type RM Length L Ch R = 1,1132,338,338,338
BEGIN DESCRIPTION:
MDW T 083 3.0
END DESCRIPTION:
XS GIS Cut Line= 3
      2258310.12      7157491.69      2258030.12      7157296.14
      2257762.56      7157093.60
#Sta/Elev= 30
  4632.3  950.16  4656.7  947.61  4670.3  947.30  4719.5  943.12  4914.2  935.03
  4921.9  933.27  4928.0  934.33  4936.7  930.08  4941.9  928.55  4969.5  926.11
  4969.7  925.61  4973.5  926.11  4993.2  928.52  5007.7  931.28  5022.3  932.54
  5028.5  934.20  5036.8  934.36  5057.7  937.01  5063.9  936.74  5072.2  938.23
  5078.5  937.93  5100.6  940.80  5107.6  942.47  5128.4  942.67  5179.9  946.31
  5222.0  949.85  5251.1  951.32  5272.0  954.14  5278.2  955.74  5309.4  956.37
#Mann=5,-1,0
  4632.3    0.05       0  4941.9    0.12       0  4969.5    0.07       0
  4973.5    0.12       0  5179.9    0.05       0
Bank Sta=4969.5,4973.5
Exp/Cntr=0.3,0.1

Type RM Length L Ch R = 1,794,370,370,370
BEGIN DESCRIPTION:
MDW T 083 2.0
END DESCRIPTION:
XS GIS Cut Line= 3
      2258495.16      7157304.07      2258212.51      7157077.10
      2257892.94      7156857.76
#Sta/Elev= 30
  4637.5  950.20  4672.7  947.64  4759.1  943.06  4765.5  941.69  4779.9  940.48
  4858.3  937.05  4864.7  936.02  4879.1  935.36  4897.0  935.39  4907.9  934.14
  4951.1  932.20  4957.5  929.88  4971.9  926.36  4984.3  925.96  4984.6  925.46
  4988.3  925.96  5015.8  928.68  5028.5  931.87  5057.8  930.54  5098.7  931.35
  5129.5  932.51  5180.3  937.01  5201.2  937.81  5222.6  940.03  5237.1  940.15
  5273.0  942.14  5287.9  943.70  5308.8  944.37  5323.7  946.11  5387.6  950.84
#Mann=5,-1,0
  4637.5    0.05       0  4897.0    0.12       0  4984.3    0.07       0
  4988.3    0.12       0  5098.7    0.05       0
Bank Sta=4984.3,4988.3
Exp/Cntr=0.3,0.1

Type RM Length L Ch R = 1,424,236,236,236
BEGIN DESCRIPTION:
MDW T 083 1.0
END DESCRIPTION:
XS GIS Cut Line= 3
      2258747.74      7156983.30      2258328.60      7156835.00
      2258028.06      7156744.74
#Sta/Elev= 30
  4555.4  943.98  4564.7  943.02  4575.1  943.49  4611.3  942.24  4628.3  940.33
  4636.9  938.42  4649.5  937.25  4723.8  934.30  4766.2  930.99  4853.5  929.48
  4884.1  928.01  4957.1  928.30  4966.2  926.66  4971.5  926.97  4987.0  923.73
  4987.2  923.23  4991.0  923.73  5020.5  924.95  5035.4  926.84  5041.3  928.37
  5062.2  928.24  5083.1  927.18  5101.5  929.13  5139.8  931.32  5166.6  934.70
  5172.8  936.54  5202.7  938.05  5282.4  945.88  5302.4  946.19  5313.8  947.36
#Mann=5,-1,0
  4555.4    0.05       0  4853.5    0.12       0  4987.0    0.07       0
  4991.0    0.12       0  5202.7    0.05       0
Bank Sta=4987,4991
Exp/Cntr=0.3,0.1

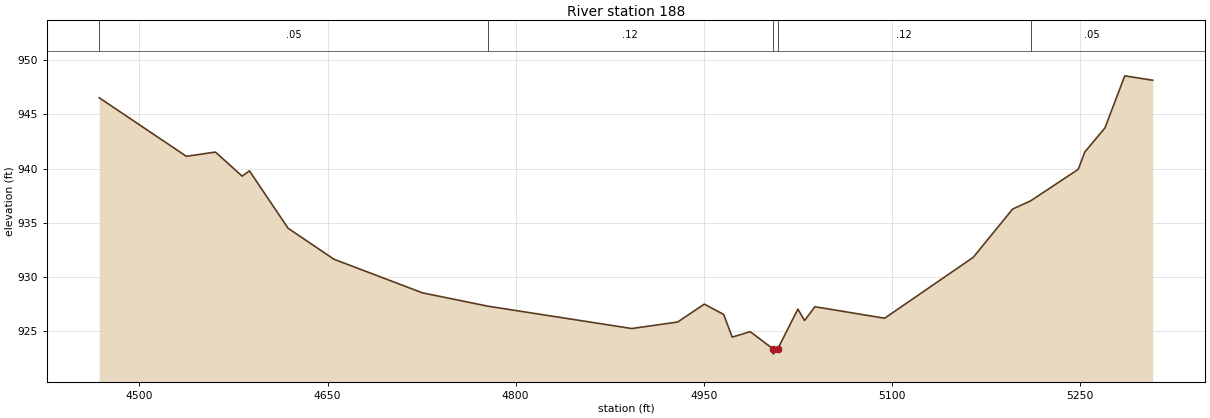
Type RM Length L Ch R = 1,188,0,0,0
BEGIN DESCRIPTION:
MDW T 083 0.5
END DESCRIPTION:
XS GIS Cut Line= 3
      2258798.13      7156906.71      2258345.77      7156626.52
      2258052.80      7156721.88
#Sta/Elev= 30
  4467.9  946.53  4537.4  941.13  4560.6  941.52  4581.9  939.30  4587.7  939.79
  4618.5  934.50  4655.1  931.64  4725.7  928.54  4777.9  927.31  4892.6  925.25
  4929.2  925.85  4950.5  927.50  4965.9  926.55  4972.7  924.46  4987.1  924.96
  5005.1  923.39  5005.4  922.89  5009.1  923.39  5025.1  927.04  5030.4  925.99
  5038.7  927.26  5094.3  926.20  5164.9  931.81  5196.4  936.27  5210.7  937.02
  5248.7  939.93  5253.9  941.52  5270.0  943.75  5285.8  948.55  5308.1  948.14
#Mann=5,-1,0
  4467.9    0.05       0  4777.9    0.12       0  5005.1    0.07       0
  5009.1    0.12       0  5210.7    0.05       0
Bank Sta=5005.1,5009.1
Exp/Cntr=0.3,0.1

Chan Stop Cuts=-1