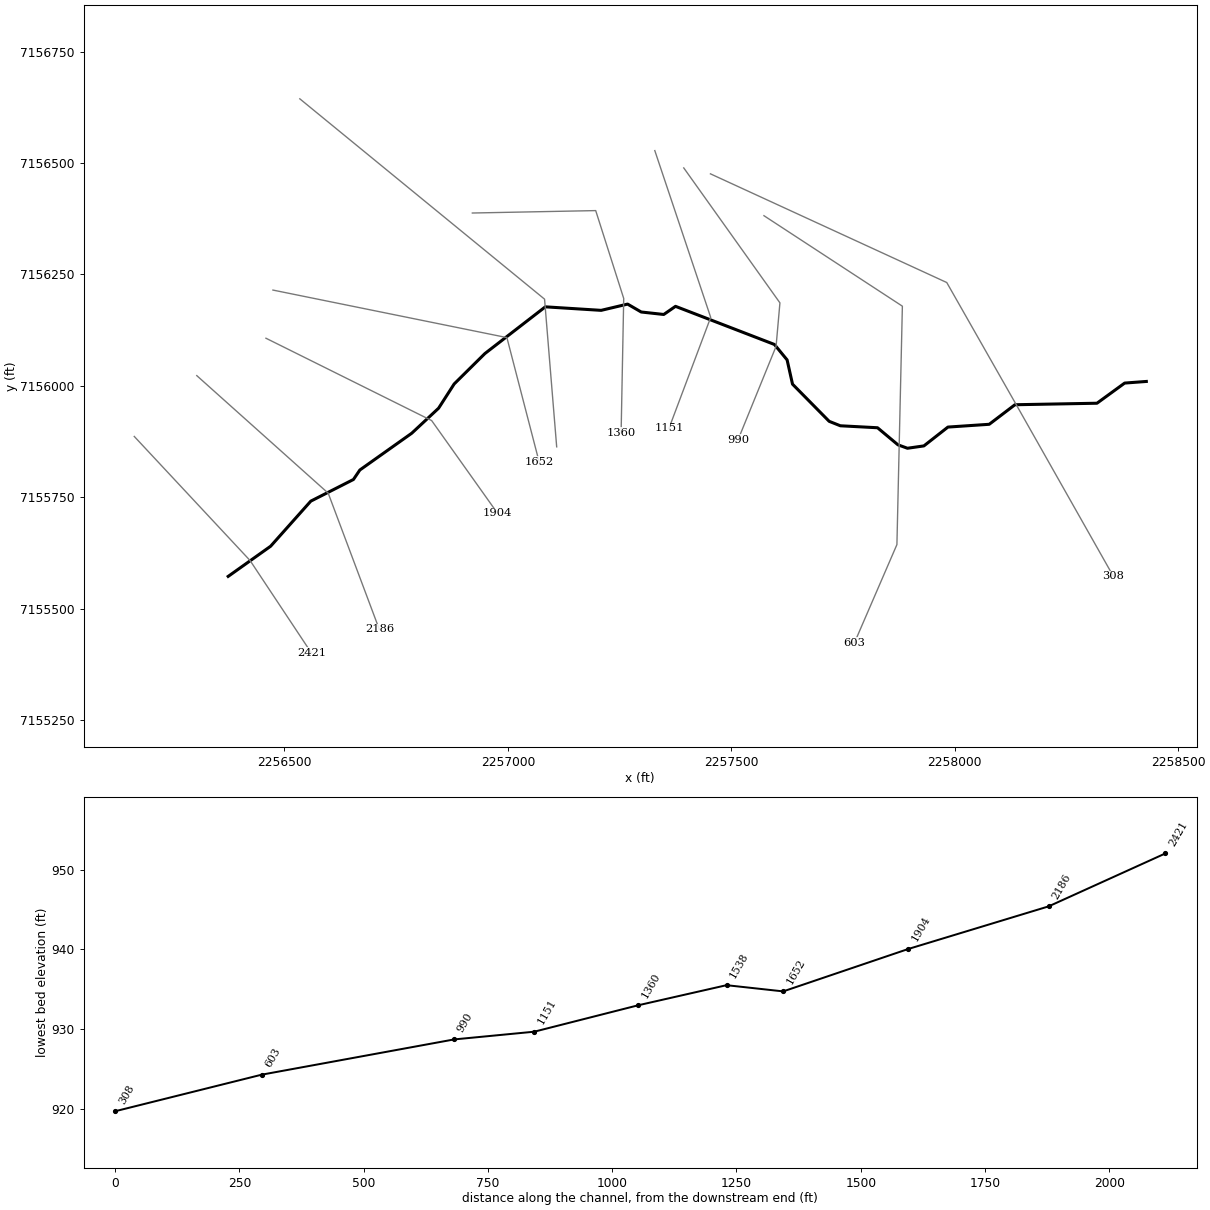
--- MDW T 084.prj (project) ---

Proj Title=MDW T 084 Base Level Engineering
Current Plan=p01
Default Exp/Contr=0.3,0.1
English Units
Geom File=g01
Flow File=f01
Plan File=p01
BEGIN DESCRIPTION:
MDW T 084
END DESCRIPTION:

--- MDW T 084.p01 (plan) ---

Plan Title=Multiple Run
Short Identifier=Multiple
Geom File=g01
Flow File=f01
Subcritical Flow
K Sum by GR= 0
Std Step Tol= 0.01
Critical Tol= 0.01
Num of Std Step Trials= 20
Max Error Tol= 0.3
Flow Tol Ratio= 0.001
Split Flow NTrial= 30
Split Flow Tol= 0.02
Split Flow Ratio= 0.02
Log Output Level= 0
Friction Slope Method= 1
Unsteady Friction Slope Method= 2
Unsteady Bridges Friction Slope Method= 1
Parabolic Critical Depth
Global Vel Dist=  1 , 1 , 1
Global Log Level= 0
CheckData=True
Encroach Param= -1, 0, 0, 0
BEGIN DESCRIPTION:
Multiple Run
END DESCRIPTION:

--- MDW T 084.f01 (steady flow) ---

Flow Title=Multiple
Number of Profiles=7
Profile Names=10-year,25-year,50-year,1pct_min,100-year,1pct_plu,500-year
River Rch & RM= MDW T 084,Reach-1,2421
     224     290     341     201     401     799     551
Boundary for River Rch & Prof#=MDW T 084,Reach-1,1
Up Type=0
Dn Type=3
Dn Slope=0.005
Boundary for River Rch & Prof#=MDW T 084,Reach-1,2
Up Type=0
Dn Type=3
Dn Slope=0.005
Boundary for River Rch & Prof#=MDW T 084,Reach-1,3
Up Type=0
Dn Type=3
Dn Slope=0.005
Boundary for River Rch & Prof#=MDW T 084,Reach-1,4
Up Type=0
Dn Type=3
Dn Slope=0.005
Boundary for River Rch & Prof#=MDW T 084,Reach-1,5
Up Type=0
Dn Type=3
Dn Slope=0.005
Boundary for River Rch & Prof#=MDW T 084,Reach-1,6
Up Type=0
Dn Type=3
Dn Slope=0.005
Boundary for River Rch & Prof#=MDW T 084,Reach-1,7
Up Type=0
Dn Type=3
Dn Slope=0.005

--- MDW T 084.g01 (geometry) ---

Geom Title=Existing Conditions

River Reach=MDW T 084,Reach-1
Reach XY= 30
      2256374.09      7155572.55      2256469.14      7155640.26
      2256558.98      7155741.39      2256654.47      7155790.00
      2256668.79      7155811.27      2256785.04      7155893.88
      2256845.08      7155949.99      2256879.91      7156004.38
      2256948.67      7156072.58      2257083.94      7156177.43
      2257208.88      7156169.54      2257268.03      7156183.59
      2257298.46      7156165.84      2257348.96      7156160.29
      2257375.28      7156178.55      2257596.65      7156093.00
      2257625.03      7156058.36      2257637.15      7156003.93
      2257719.19      7155920.51      2257744.21      7155910.52
      2257827.41      7155906.11      2257873.08      7155867.81
      2257894.39      7155860.09      2257931.18      7155865.37
      2257984.97      7155907.62      2258077.40      7155913.86
      2258134.94      7155957.74      2258318.54      7155961.12
      2258380.51      7156006.35      2258429.00      7156010.00

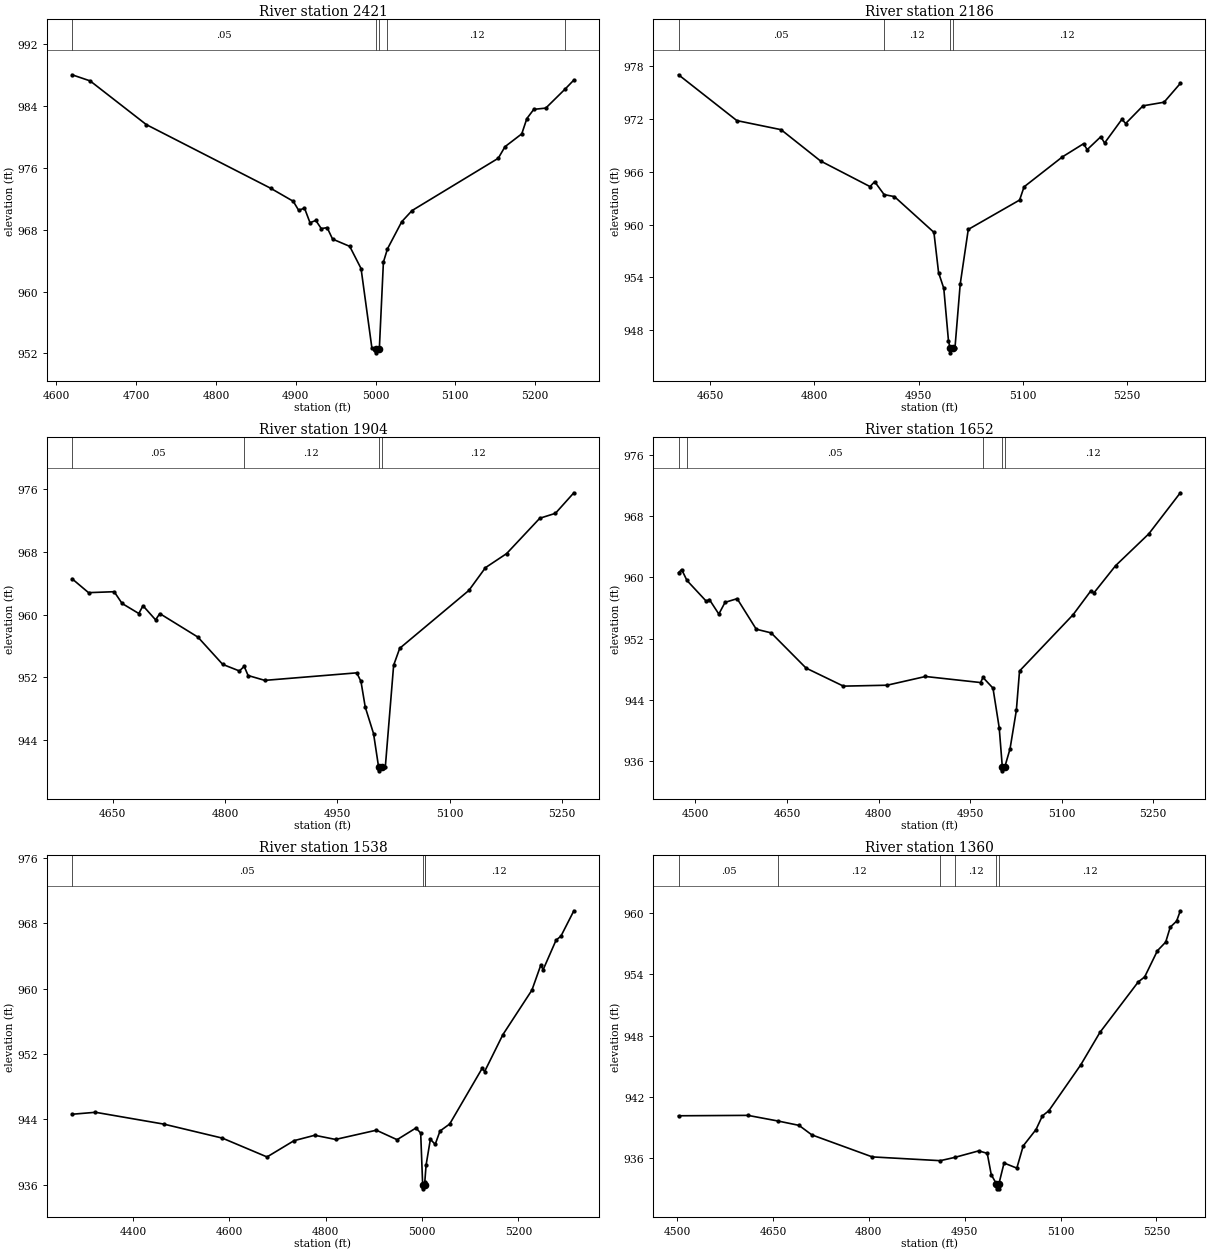
Type RM Length L Ch R = 1,2421,235,235,235
BEGIN DESCRIPTION:
MDW T 084 4.0
END DESCRIPTION:
XS GIS Cut Line= 3
      2256163.95      7155886.58      2256423.13      7155608.14
      2256560.26      7155400.90
#Sta/Elev= 30
  4619.6  988.04  4642.2  987.25  4712.6  981.60  4868.4  973.37  4896.8  971.68
  4903.6  970.51  4910.9  970.80  4917.8  968.91  4925.1  969.20  4931.9  968.15
  4939.3  968.27  4946.1  966.79  4967.6  965.85  4981.8  962.98  4995.3  952.76
  5000.7  952.58  5000.9  952.08  5004.7  952.58  5009.8  963.81  5014.9  965.53
  5032.8  969.04  5045.7  970.48  5153.7  977.24  5162.2  978.74  5183.2  980.40
  5189.6  982.38  5198.3  983.57  5213.3  983.73  5237.9  986.23  5248.5  987.36
#Mann=5,-1,0
  4619.6    0.05       0  5000.7   0.033       0  5004.7    0.05       0
  5014.9    0.12       0  5237.9    0.05       0
Bank Sta=5000.7,5004.7
Exp/Cntr=0.3,0.1

Type RM Length L Ch R = 1,2186,282,282,282
BEGIN DESCRIPTION:
MDW T 084 3.0
END DESCRIPTION:
XS GIS Cut Line= 3
      2256303.86      7156023.07      2256598.05      7155759.18
      2256712.39      7155453.57
#Sta/Elev= 30
  4604.8  977.03  4688.7  971.82  4752.2  970.79  4809.0  967.23  4880.1  964.32
  4886.8  964.88  4900.4  963.41  4915.2  963.18  4972.0  959.12  4978.7  954.54
  4986.2  952.75  4992.9  946.81  4995.3  945.92  4995.5  945.42  4999.3  945.92
  5002.2  945.92  5009.8  953.23  5021.4  959.45  5095.2  962.79  5101.6  964.29
  5156.8  967.70  5187.1  969.19  5192.4  968.52  5212.0  969.99  5217.4  969.27
  5242.3  971.97  5247.7  971.49  5272.6  973.50  5302.9  973.91  5326.3  976.05
#Mann=4,-1,0
  4604.8    0.05       0  4900.4    0.12       0  4995.3    0.07       0
  4999.3    0.12       0
Bank Sta=4995.3,4999.3
Exp/Cntr=0.3,0.1

Type RM Length L Ch R = 1,1904,252,252,252
BEGIN DESCRIPTION:
MDW T 084 2.0
END DESCRIPTION:
XS GIS Cut Line= 3
      2256458.67      7156106.98      2256829.51      7155922.21
      2256977.32      7155713.70
#Sta/Elev= 30
  4596.0  964.57  4618.0  962.80  4652.2  962.92  4662.8  961.42  4685.1  960.14
  4690.7  961.13  4707.5  959.33  4713.1  960.13  4764.0  957.13  4797.1  953.65
  4819.4  952.81  4825.8  953.40  4831.0  952.23  4853.3  951.61  4976.1  952.57
  4981.7  951.47  4987.4  948.20  4998.5  944.81  5005.2  940.57  5005.5  940.07
  5009.2  940.57  5014.2  940.57  5025.3  953.54  5033.4  955.70  5125.7  963.08
  5147.9  965.99  5176.1  967.78  5220.4  972.29  5241.3  972.92  5265.9  975.54
#Mann=4,-1,0
  4596.0    0.05       0  4825.8    0.12       0  5005.2    0.07       0
  5009.2    0.12       0
Bank Sta=5005.2,5009.2
Exp/Cntr=0.3,0.1

Type RM Length L Ch R = 1,1652,114,114,114
BEGIN DESCRIPTION:
MDW T 084 1.0
END DESCRIPTION:
XS GIS Cut Line= 3
      2256474.29      7156215.05      2256997.91      7156108.41
      2257069.95      7155829.94
#Sta/Elev= 30
  4472.3  960.64  4477.4  961.04  4486.1  959.61  4517.7  956.90  4522.8  957.12
  4538.3  955.22  4548.5  956.75  4568.3  957.23  4599.6  953.24  4624.0  952.76
  4681.2  948.16  4742.4  945.80  4813.9  945.92  4876.8  947.06  4967.0  946.27
  4971.1  946.93  4987.4  945.54  4997.6  940.37  5002.7  935.23  5002.9  934.73
  5006.7  935.23  5015.3  937.59  5025.7  942.64  5030.9  947.78  5118.6  955.13
  5147.6  958.24  5152.8  957.99  5188.2  961.54  5242.6  965.70  5294.3  971.07
#Mann=5,-1,0
  4472.3    0.12       0  4486.1    0.05       0  4971.1    0.12       0
  5002.7    0.07       0  5006.7    0.12       0
Bank Sta=5002.7,5006.7
Exp/Cntr=0.3,0.1

Type RM Length L Ch R = 1,1538,178,178,178
BEGIN DESCRIPTION:
Mapping XS 95cb81d7
END DESCRIPTION:
XS GIS Cut Line= 3
      2256534.46      7156644.20      2257082.21      7156194.65
      2257109.34      7155863.27
#Sta/Elev= 30
  4273.9  944.63  4322.5  944.87  4464.6  943.42  4585.8  941.71  4678.4  939.41
  4734.4  941.40  4777.4  942.06  4820.5  941.55  4905.2  942.68  4948.2  941.52
  4987.4  942.95  4997.2  942.33  5001.3  936.01  5001.6  935.51  5005.3  936.01
  5005.7  936.32  5008.4  938.41  5017.3  941.57  5027.3  940.95  5037.3  942.58
  5057.4  943.44  5124.8  950.25  5129.8  949.85  5167.8  954.37  5228.0  959.81
  5246.3  962.85  5251.3  962.31  5278.1  965.92  5288.2  966.41  5315.0  969.51
#Mann=4,-1,0
  4273.9    0.05       0  5001.3   0.033       0  5005.3    0.05       0
  5005.7    0.12       0
Bank Sta=5001.3,5005.3
Exp/Cntr=0.3,0.1

Type RM Length L Ch R = 1,1360,209,209,209
BEGIN DESCRIPTION:
Mapping XS e297aab1
END DESCRIPTION:
XS GIS Cut Line= 4
      2256920.57      7156387.96      2257196.67      7156393.38
      2257259.35      7156196.24      2257253.52      7155894.22
#Sta/Elev= 30
  4502.2  940.14  4610.7  940.18  4658.4  939.62  4690.7  939.20  4710.7  938.27
  4805.3  936.11  4911.7  935.74  4934.3  936.06  4971.8  936.70  4985.2  936.46
  4991.5  934.36  4999.5  933.48  4999.7  932.98  5003.2  932.98  5003.5  933.48
  5011.5  935.51  5031.5  935.01  5041.5  937.19  5061.5  938.79  5071.5  940.13
  5081.5  940.63  5131.5  945.13  5161.5  948.31  5221.5  953.26  5231.5  953.75
  5251.5  956.32  5264.4  957.16  5271.5  958.62  5281.5  959.22  5287.3  960.23
#Mann=6,-1,0
  4502.2    0.05       0  4658.4    0.12       0  4911.7    0.05       0
  4934.3    0.12       0  4999.5    0.07       0  5003.5    0.12       0
Bank Sta=4999.5,5003.5
Exp/Cntr=0.3,0.1

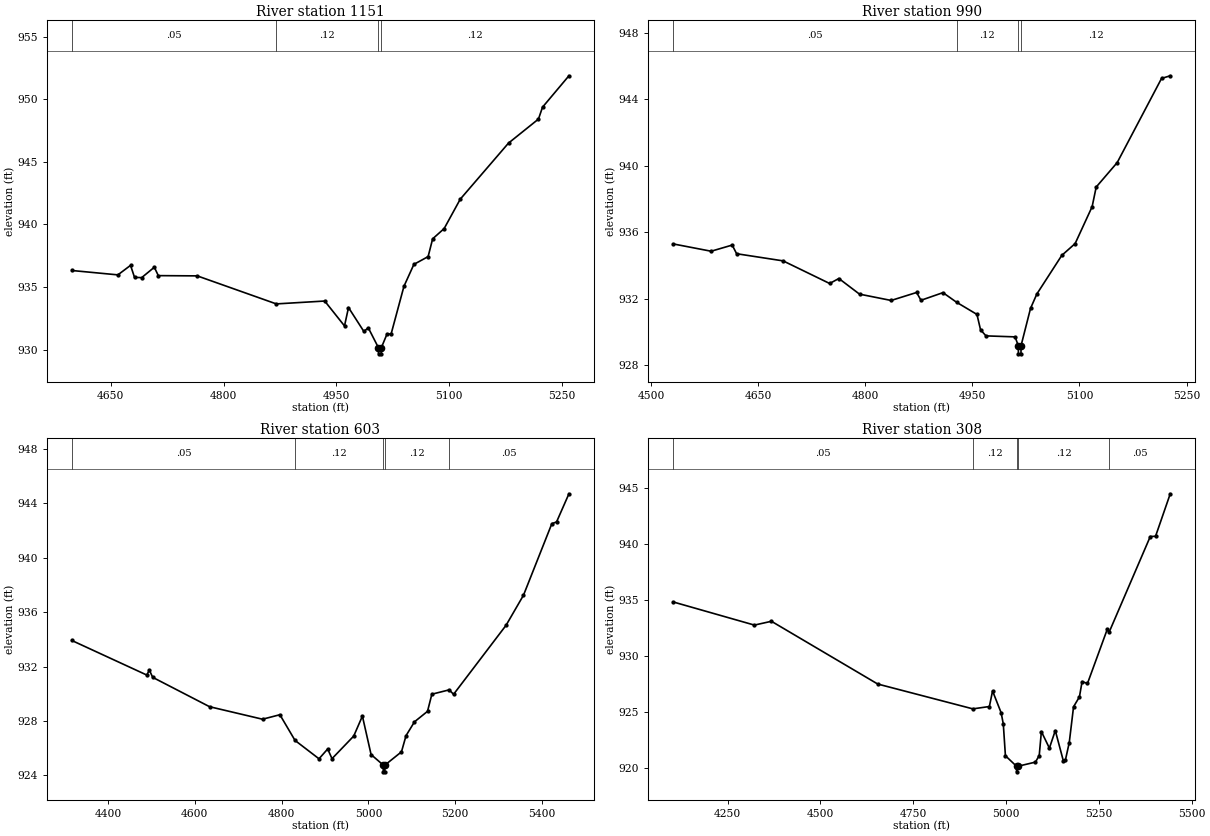
Type RM Length L Ch R = 1,1151,161,161,161
BEGIN DESCRIPTION:
Mapping XS d1676436
END DESCRIPTION:
XS GIS Cut Line= 3
      2257328.94      7156528.00      2257454.03      7156153.76
      2257360.65      7155904.79
#Sta/Elev= 30
  4598.4  936.32  4659.6  935.97  4676.4  936.73  4681.7  935.77  4691.2  935.75
  4708.0  936.58  4713.3  935.91  4765.0  935.89  4870.1  933.65  4934.4  933.88
  4960.7  931.89  4966.0  933.36  4986.4  931.45  4992.3  931.74  5005.7  930.16
  5005.9  929.66  5009.4  929.66  5009.7  930.16  5017.3  931.26  5022.6  931.24
  5039.7  935.06  5052.9  936.81  5071.8  937.43  5077.8  938.85  5093.1  939.67
  5114.5  942.02  5178.6  946.50  5218.4  948.42  5223.8  949.37  5258.9  951.88
#Mann=4,-1,0
  4598.4    0.05       0  4870.1    0.12       0  5005.7    0.07       0
  5009.7    0.12       0
Bank Sta=5005.7,5009.7
Exp/Cntr=0.3,0.1

Type RM Length L Ch R = 1,990,387,387,387
BEGIN DESCRIPTION:
Mapping XS bd27ee0f
END DESCRIPTION:
XS GIS Cut Line= 4
      2257393.74      7156489.14      2257608.97      7156186.34
      2257600.34      7156088.73      2257515.07      7155878.67
#Sta/Elev= 30
  4531.0  935.30  4584.2  934.86  4613.7  935.23  4619.9  934.71  4685.0  934.28
  4750.2  932.92  4763.1  933.22  4792.0  932.28  4836.3  931.90  4872.0  932.38
  4878.1  931.91  4908.9  932.37  4928.0  931.79  4956.5  931.06  4961.5  930.14
  4969.1  929.77  5009.9  929.71  5014.3  929.19  5014.6  928.69  5018.1  928.69
  5018.3  929.19  5031.5  931.42  5040.4  932.29  5075.3  934.61  5094.0  935.32
  5117.8  937.54  5123.5  938.72  5152.9  940.19  5215.0  945.25  5227.2  945.41
#Mann=4,-1,0
  4531.0    0.05       0  4928.0    0.12       0  5014.3    0.07       0
  5018.3    0.12       0
Bank Sta=5014.3,5018.3
Exp/Cntr=0.3,0.1

Type RM Length L Ch R = 1,603,295,295,295
BEGIN DESCRIPTION:
Mapping XS f254ca3b
END DESCRIPTION:
XS GIS Cut Line= 4
      2257573.22      7156381.94      2257883.02      7156178.90
      2257870.80      7155643.93      2257775.88      7155423.84
#Sta/Elev= 30
  4316.6  933.92  4489.2  931.38  4495.2  931.74  4502.9  931.21  4633.9  929.05
  4755.9  928.13  4795.9  928.46  4830.8  926.57  4886.0  925.22  4906.0  925.94
  4916.0  925.23  4966.0  926.89  4986.0  928.36  5006.0  925.53  5034.0  924.76
  5034.2  924.26  5037.7  924.26  5038.0  924.76  5076.0  925.73  5086.5  926.92
  5106.0  927.94  5136.0  928.71  5146.0  929.97  5186.0  930.29  5196.0  929.96
  5317.0  935.04  5357.1  937.25  5422.4  942.51  5433.3  942.64  5461.8  944.71
#Mann=5,-1,0
  4316.6    0.05       0  4830.8    0.12       0  5034.0    0.07       0
  5038.0    0.12       0  5186.0    0.05       0
Bank Sta=5034,5038
Exp/Cntr=0.3,0.1

Type RM Length L Ch R = 1,308,0,0,0
BEGIN DESCRIPTION:
MDW T 084 0.5
END DESCRIPTION:
XS GIS Cut Line= 4
      2257453.47      7156475.86      2257982.35      7156231.97
      2258139.44      7155955.09      2258354.98      7155573.15
#Sta/Elev= 30
  4103.0  934.85  4321.9  932.78  4367.8  933.12  4654.2  927.51  4910.5  925.29
  4955.0  925.50  4963.6  926.89  4986.6  924.95  4992.5  923.95  4998.2  921.10
  5028.1  920.16  5028.3  919.66  5032.1  920.16  5079.1  920.53  5089.3  921.12
  5095.1  923.26  5116.7  921.78  5132.6  923.35  5154.3  920.64  5160.0  920.74
  5170.2  922.27  5181.8  925.48  5197.6  926.36  5204.8  927.73  5219.3  927.56
  5272.7  932.41  5277.7  932.15  5388.5  940.70  5402.7  940.72  5442.3  944.52
#Mann=5,-1,0
  4103.0    0.05       0  4910.5    0.12       0  5028.1    0.07       0
  5032.1    0.12       0  5277.7    0.05       0
Bank Sta=5028.1,5032.1
Exp/Cntr=0.3,0.1

Chan Stop Cuts=-1