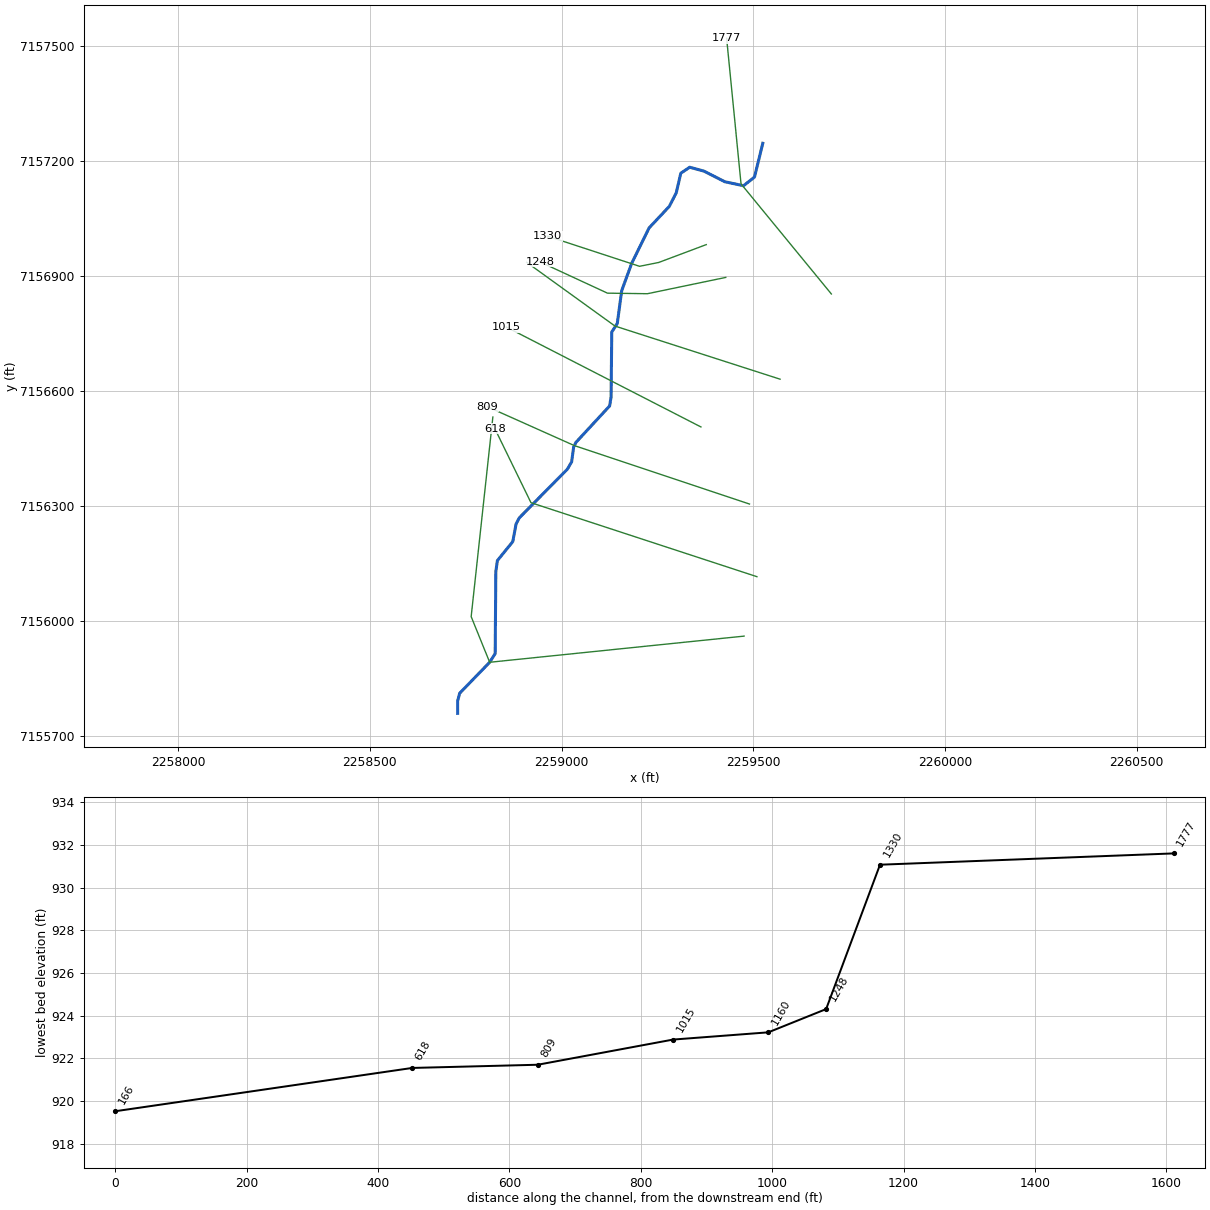
--- MDW T 085.prj (project) ---

Proj Title=MDW T 085 Base Level Engineering
Current Plan=p01
Default Exp/Contr=0.3,0.1
English Units
Geom File=g01
Flow File=f01
Plan File=p01
BEGIN DESCRIPTION:
MDW T 085
END DESCRIPTION:

--- MDW T 085.p01 (plan) ---

Plan Title=Multiple Run
Short Identifier=Multiple
Geom File=g01
Flow File=f01
Subcritical Flow
K Sum by GR= 0
Std Step Tol= 0.01
Critical Tol= 0.01
Num of Std Step Trials= 20
Max Error Tol= 0.3
Flow Tol Ratio= 0.001
Split Flow NTrial= 30
Split Flow Tol= 0.02
Split Flow Ratio= 0.02
Log Output Level= 0
Friction Slope Method= 1
Unsteady Friction Slope Method= 2
Unsteady Bridges Friction Slope Method= 1
Parabolic Critical Depth
Global Vel Dist=  1 , 1 , 1
Global Log Level= 0
CheckData=True
Encroach Param= -1, 0, 0, 0
BEGIN DESCRIPTION:
Multiple Run
END DESCRIPTION:

--- MDW T 085.f01 (steady flow) ---

Flow Title=Multiple
Number of Profiles=7
Profile Names=10-year,25-year,50-year,1pct_min,100-year,1pct_plu,500-year
River Rch & RM= MDW T 085,Reach-1,1777
     504     686     835     506    1010    2016    1478
Boundary for River Rch & Prof#=MDW T 085,Reach-1,1
Up Type=0
Dn Type=3
Dn Slope=0.005
Boundary for River Rch & Prof#=MDW T 085,Reach-1,2
Up Type=0
Dn Type=3
Dn Slope=0.005
Boundary for River Rch & Prof#=MDW T 085,Reach-1,3
Up Type=0
Dn Type=3
Dn Slope=0.005
Boundary for River Rch & Prof#=MDW T 085,Reach-1,4
Up Type=0
Dn Type=3
Dn Slope=0.005
Boundary for River Rch & Prof#=MDW T 085,Reach-1,5
Up Type=0
Dn Type=3
Dn Slope=0.005
Boundary for River Rch & Prof#=MDW T 085,Reach-1,6
Up Type=0
Dn Type=3
Dn Slope=0.005
Boundary for River Rch & Prof#=MDW T 085,Reach-1,7
Up Type=0
Dn Type=3
Dn Slope=0.005

--- MDW T 085.g01 (geometry) ---

Geom Title=Existing Conditions

River Reach=MDW T 085,Reach-1
Reach XY= 30
      2259525.07      7157246.32      2259503.37      7157158.21
      2259474.73      7157135.64      2259426.11      7157146.06
      2259371.43      7157173.83      2259334.36      7157183.89
      2259311.17      7157168.34      2259299.38      7157117.41
      2259281.15      7157081.82      2259228.37      7157025.56
      2259183.06      7156933.38      2259157.02      7156862.20
      2259145.47      7156776.75      2259131.07      7156754.14
      2259129.29      7156584.88      2259125.45      7156561.47
      2259037.18      7156466.04      2259031.54      7156453.95
      2259026.47      7156416.05      2259015.37      7156396.79
      2258889.76      7156269.68      2258881.50      7156253.97
      2258872.86      7156207.83      2258832.75      7156158.45
      2258828.64      7156130.15      2258826.94      7155915.85
      2258812.56      7155893.24      2258734.33      7155812.51
      2258728.93      7155791.88      2258729.00      7155760.00

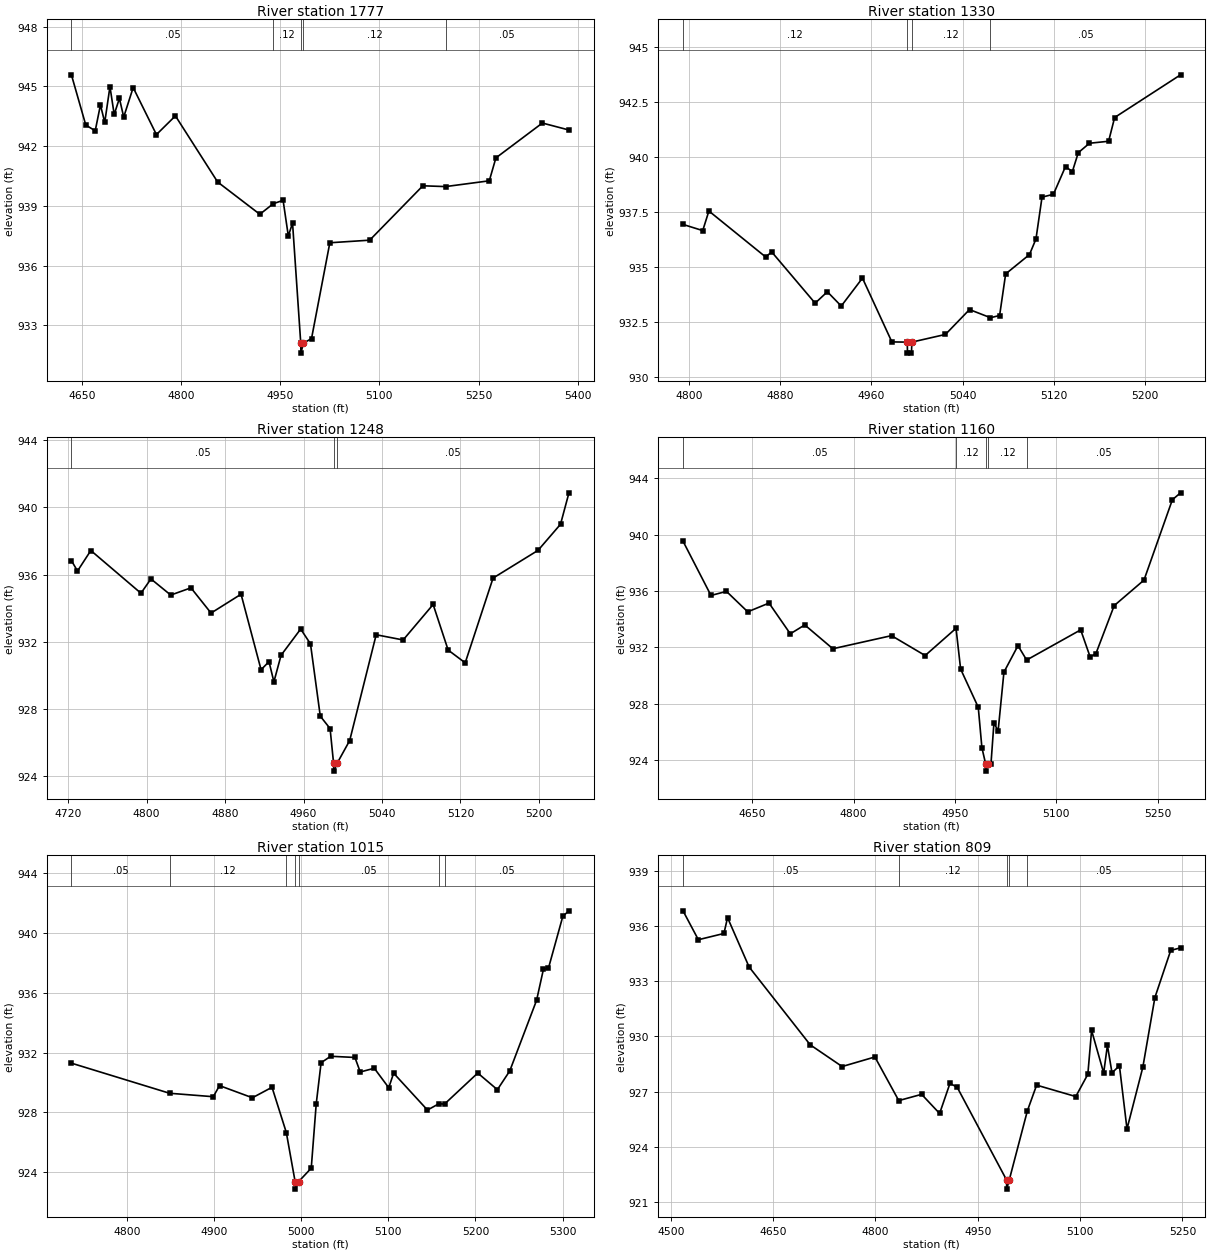
Type RM Length L Ch R = 1,1777,447,447,447
BEGIN DESCRIPTION:
MDW T 085 3.0
END DESCRIPTION:
XS GIS Cut Line= 3
      2259703.89      7156853.53      2259468.28      7157140.55
      2259430.74      7157519.96
#Sta/Elev= 30
  4634.2  945.58  4655.9  943.06  4670.2  942.77  4678.1  944.07  4684.6  943.19
  4692.5  944.99  4698.9  943.59  4706.8  944.40  4713.3  943.46  4727.6  944.94
  4762.8  942.58  4791.5  943.52  4855.4  940.20  4919.2  938.58  4939.5  939.11
  4954.4  939.28  4962.3  937.49  4968.7  938.14  4981.1  932.11  4981.3  931.61
  4985.1  932.11  4997.4  932.34  5025.1  937.15  5085.4  937.28  5165.8  940.01
  5200.2  939.97  5266.3  940.26  5276.3  941.41  5346.6  943.16  5386.8  942.81
#Mann=5,-1,0
  4634.2    0.05       0  4939.5    0.12       0  4981.1    0.07       0
  4985.1    0.12       0  5200.2    0.05       0
Bank Sta=4981.1,4985.1
Exp/Cntr=0.3,0.1

Type RM Length L Ch R = 1,1330,82,82,82
BEGIN DESCRIPTION:
Mapping XS 9a0f615c
END DESCRIPTION:
XS GIS Cut Line= 4
      2259377.49      7156982.12      2259253.55      7156935.61
      2259203.51      7156925.61      2258963.07      7157004.31
#Sta/Elev= 30
  4794.7  936.93  4812.0  936.65  4817.4  937.54  4867.2  935.45  4872.5  935.68
  4910.6  933.35  4921.3  933.87  4933.5  933.22  4952.1  934.49  4977.9  931.59
  4991.4  931.58  4991.6  931.08  4995.1  931.08  4995.4  931.58  5024.9  931.93
  5046.0  933.06  5064.4  932.69  5072.4  932.79  5077.7  934.68  5098.6  935.56
  5104.3  936.27  5109.6  938.17  5119.6  938.30  5130.2  939.56  5136.2  939.33
  5141.4  940.19  5151.2  940.62  5168.0  940.71  5173.3  941.79  5231.1  943.73
#Mann=4,-1,0
  4794.7    0.12       0  4991.4    0.07       0  4995.4    0.12       0
  5064.4    0.05       0
Bank Sta=4991.4,4995.4
Exp/Cntr=0.3,0.1

Type RM Length L Ch R = 1,1248,88,88,88
BEGIN DESCRIPTION:
Mapping XS a45186ae
END DESCRIPTION:
XS GIS Cut Line= 4
      2259428.38      7156896.60      2259224.21      7156854.15
      2259119.91      7156855.59      2258943.34      7156937.28
#Sta/Elev= 30
  4723.3  936.83  4729.5  936.21  4743.1  937.43  4794.2  934.89  4804.4  935.74
  4824.6  934.78  4845.2  935.21  4865.7  933.71  4896.3  934.83  4916.7  930.34
  4924.8  930.82  4929.8  929.62  4937.1  931.20  4957.1  932.76  4967.1  931.88
  4977.1  927.58  4987.1  926.84  4990.6  924.81  4990.9  924.31  4994.6  924.81
  5007.1  926.13  5034.1  932.42  5061.6  932.11  5092.2  934.22  5107.5  931.51
  5124.9  930.75  5153.3  935.79  5199.2  937.44  5222.1  938.99  5230.7  940.86
#Mann=3,-1,0
  4723.3    0.05       0  4990.6   0.033       0  4994.6    0.05       0
Bank Sta=4990.6,4994.6
Exp/Cntr=0.3,0.1

Type RM Length L Ch R = 1,1160,145,145,145
BEGIN DESCRIPTION:
MDW T 085 2.0
END DESCRIPTION:
XS GIS Cut Line= 3
      2259570.18      7156631.31      2259139.50      7156769.79
      2258909.16      7156935.93
#Sta/Elev= 30
  4547.6  939.53  4589.0  935.68  4611.9  935.97  4643.4  934.52  4674.9  935.14
  4706.4  932.96  4727.8  933.59  4769.4  931.90  4856.2  932.83  4906.0  931.42
  4951.7  933.35  4958.5  930.46  4984.6  927.75  4990.0  924.88  4995.6  923.72
  4995.9  923.22  4999.6  923.72  5003.4  923.72  5007.8  926.64  5014.0  926.07
  5022.6  930.24  5043.4  932.12  5056.2  931.10  5136.2  933.24  5150.2  931.32
  5158.7  931.55  5185.8  934.96  5229.9  936.77  5271.9  942.47  5284.0  942.96
#Mann=5,-1,0
  4547.6    0.05       0  4951.7    0.12       0  4995.6    0.07       0
  4999.6    0.12       0  5056.2    0.05       0
Bank Sta=4995.6,4999.6
Exp/Cntr=0.3,0.1

Type RM Length L Ch R = 1,1015,206,206,206
BEGIN DESCRIPTION:
Mapping XS 1d6c1d6f
END DESCRIPTION:
XS GIS Cut Line= 2
      2259363.73      7156506.75      2258855.95      7156767.25
#Sta/Elev= 30
  4736.5  931.29  4849.1  929.28  4899.2  929.05  4906.4  929.79  4944.1  928.98
  4966.6  929.68  4983.0  926.66  4993.1  923.38  4993.4  922.88  4997.1  923.38
  5011.6  924.28  5017.3  928.57  5022.9  931.32  5033.9  931.75  5061.7  931.67
  5067.8  930.70  5083.9  930.95  5100.5  929.65  5106.1  930.62  5144.9  928.16
  5158.0  928.58  5164.5  928.56  5202.6  930.63  5225.1  929.52  5239.3  930.77
  5270.1  935.49  5278.0  937.58  5283.6  937.61  5300.2  941.10  5307.2  941.46
#Mann=7,-1,0
  4736.5    0.05       0  4849.1    0.12       0  4983.0    0.05       0
  4993.1   0.033       0  4997.1    0.05       0  5158.0    0.12       0
  5164.5    0.05       0
Bank Sta=4993.1,4997.1
Exp/Cntr=0.3,0.1

Type RM Length L Ch R = 1,809,191,191,191
BEGIN DESCRIPTION:
MDW T 085 1.0
END DESCRIPTION:
XS GIS Cut Line= 3
      2259490.31      7156305.79      2259032.99      7156458.35
      2258807.21      7156559.24
#Sta/Elev= 30
  4517.9  936.82  4540.4  935.25  4577.9  935.59  4583.2  936.45  4614.8  933.77
  4704.4  929.54  4751.2  928.36  4799.2  928.88  4834.2  926.51  4867.7  926.85
  4894.1  925.81  4909.3  927.45  4919.9  927.23  4992.2  922.20  4992.4  921.70
  4996.2  922.20  5022.8  925.96  5036.3  927.35  5093.7  926.73  5111.4  927.94
  5116.9  930.32  5134.6  928.01  5140.1  929.51  5146.8  928.02  5157.7  928.40
  5168.8  924.97  5192.0  928.32  5209.7  932.11  5232.9  934.67  5247.3  934.81
#Mann=5,-1,0
  4517.9    0.05       0  4834.2    0.12       0  4992.2    0.07       0
  4996.2    0.12       0  5022.8    0.05       0
Bank Sta=4992.2,4996.2
Exp/Cntr=0.3,0.1

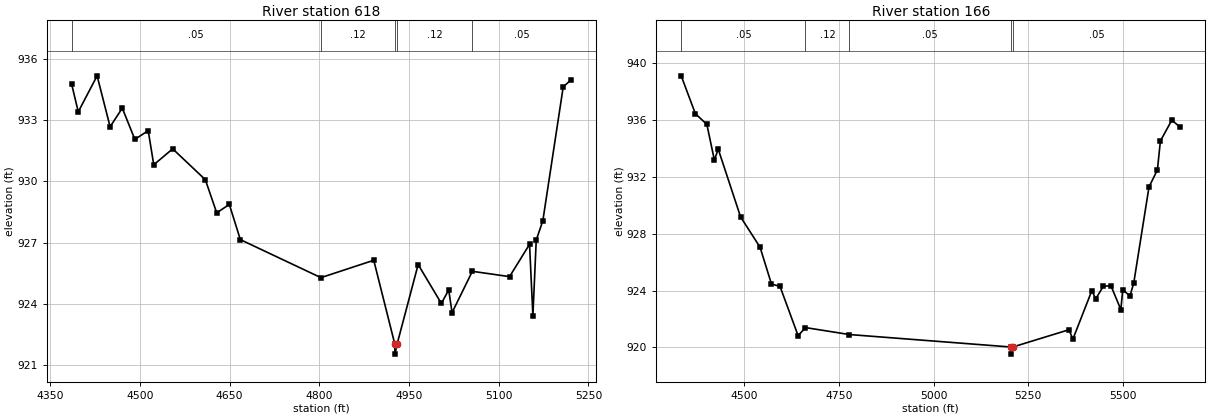
Type RM Length L Ch R = 1,618,452,452,452
BEGIN DESCRIPTION:
Mapping XS d10c20fe
END DESCRIPTION:
XS GIS Cut Line= 3
      2259509.69      7156116.41      2258920.30      7156309.30
      2258826.29      7156501.93
#Sta/Elev= 30
  4385.9  934.78  4397.2  933.40  4428.7  935.16  4450.4  932.67  4470.8  933.58
  4491.8  932.05  4514.1  932.48  4523.4  930.81  4555.0  931.59  4609.6  930.08
  4628.6  928.46  4649.7  928.87  4668.1  927.15  4802.8  925.29  4891.1  926.14
  4926.2  922.05  4926.5  921.55  4930.2  922.05  4965.3  925.93  5004.1  924.03
  5016.4  924.69  5022.0  923.58  5055.9  925.60  5118.1  925.34  5151.5  926.92
  5157.1  923.43  5162.7  927.13  5173.7  928.07  5207.8  934.62  5220.4  934.95
#Mann=5,-1,0
  4385.9    0.05       0  4802.8    0.12       0  4926.2    0.07       0
  4930.2    0.12       0  5055.9    0.05       0
Bank Sta=4926.2,4930.2
Exp/Cntr=0.3,0.1

Type RM Length L Ch R = 1,166,0,0,0
BEGIN DESCRIPTION:
MDW T 085 0.5
END DESCRIPTION:
XS GIS Cut Line= 4
      2259476.27      7155961.43      2258812.56      7155893.24
      2258764.30      7156012.22      2258820.91      7156532.65
#Sta/Elev= 30
  4332.8  939.13  4370.3  936.46  4400.6  935.71  4420.5  933.19  4430.6  933.97
  4489.7  929.19  4541.2  927.05  4571.3  924.46  4593.9  924.29  4641.7  920.82
  4661.2  921.39  4777.1  920.90  5204.6  920.02  5204.9  919.52  5208.6  920.02
  5357.5  921.24  5367.6  920.57  5417.9  924.00  5427.9  923.41  5448.1  924.30
  5468.2  924.34  5494.4  922.66  5499.5  924.05  5518.5  923.62  5528.5  924.53
  5568.8  931.30  5591.0  932.50  5598.9  934.54  5629.1  936.01  5651.9  935.49
#Mann=5,-1,0
  4332.8    0.05       0  4661.2    0.12       0  4777.1    0.05       0
  5204.6   0.033       0  5208.6    0.05       0
Bank Sta=5204.6,5208.6
Exp/Cntr=0.3,0.1

Chan Stop Cuts=-1