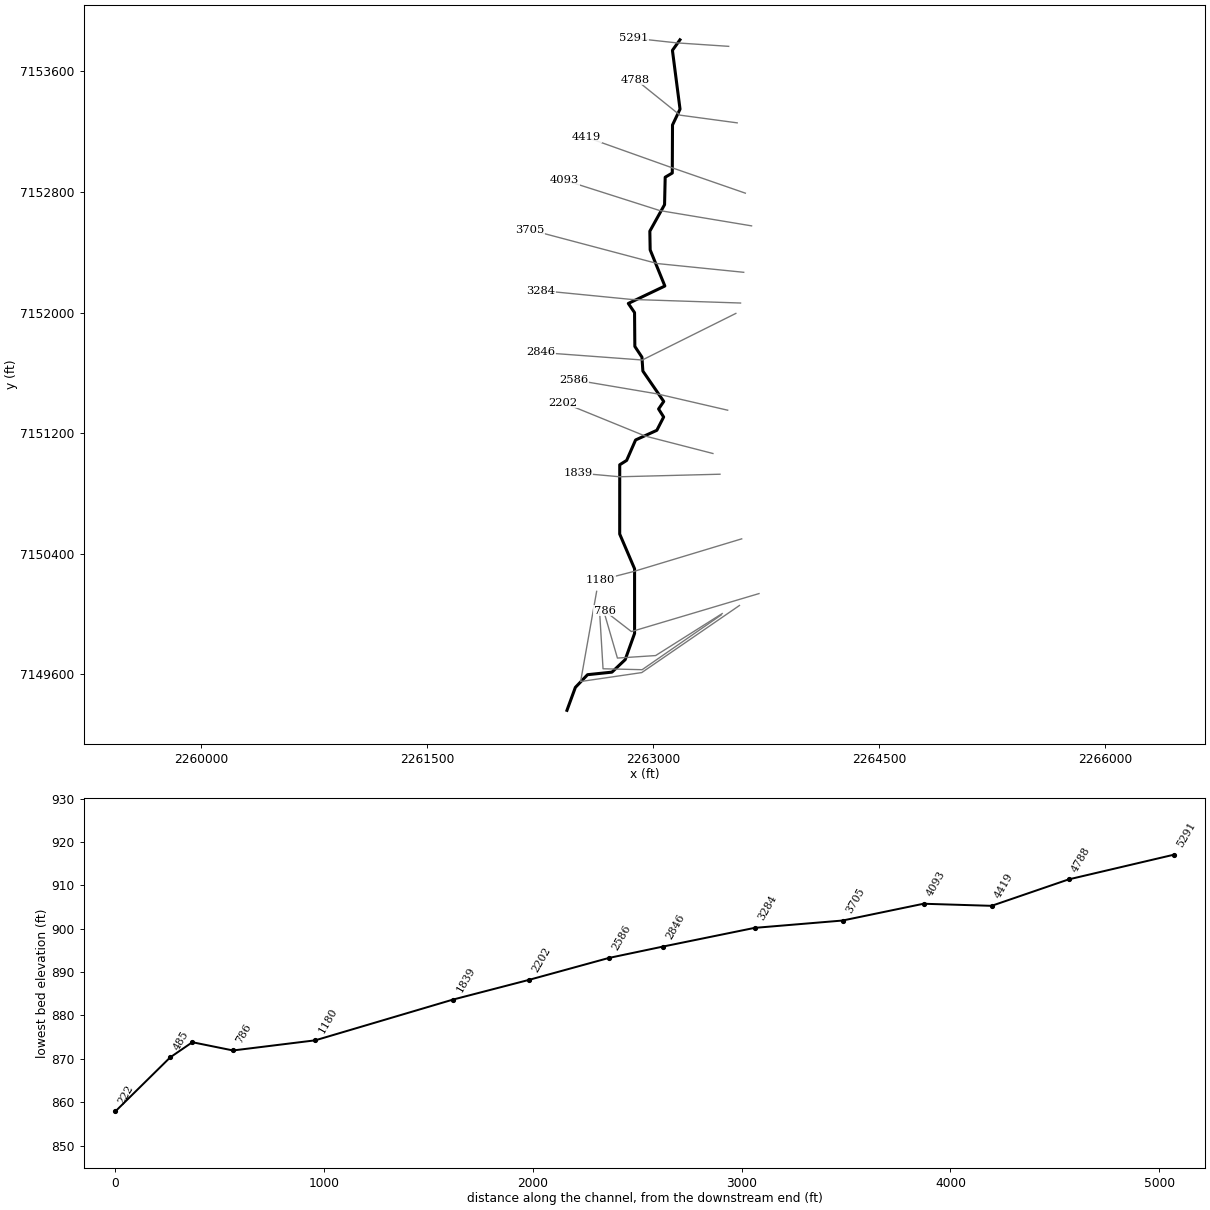
--- MDW T 086.prj (project) ---

Proj Title=MDW T 086 Base Level Engineering
Current Plan=p01
Default Exp/Contr=0.3,0.1
English Units
Geom File=g01
Flow File=f01
Plan File=p01
BEGIN DESCRIPTION:
MDW T 086
END DESCRIPTION:

--- MDW T 086.p01 (plan) ---

Plan Title=Multiple Run
Short Identifier=Multiple
Geom File=g01
Flow File=f01
Subcritical Flow
K Sum by GR= 0
Std Step Tol= 0.01
Critical Tol= 0.01
Num of Std Step Trials= 20
Max Error Tol= 0.3
Flow Tol Ratio= 0.001
Split Flow NTrial= 30
Split Flow Tol= 0.02
Split Flow Ratio= 0.02
Log Output Level= 0
Friction Slope Method= 1
Unsteady Friction Slope Method= 2
Unsteady Bridges Friction Slope Method= 1
Parabolic Critical Depth
Global Vel Dist=  1 , 1 , 1
Global Log Level= 0
CheckData=True
Encroach Param= -1, 0, 0, 0
BEGIN DESCRIPTION:
Multiple Run
END DESCRIPTION:

--- MDW T 086.f01 (steady flow) ---

Flow Title=Multiple
Number of Profiles=7
Profile Names=10-year,25-year,50-year,1pct_min,100-year,1pct_plu,500-year
River Rch & RM= MDW T 086,Reach-1,5291
     594     815     999     608    1214    2421    1794
Boundary for River Rch & Prof#=MDW T 086,Reach-1,1
Up Type=0
Dn Type=3
Dn Slope=0.005
Boundary for River Rch & Prof#=MDW T 086,Reach-1,2
Up Type=0
Dn Type=3
Dn Slope=0.005
Boundary for River Rch & Prof#=MDW T 086,Reach-1,3
Up Type=0
Dn Type=3
Dn Slope=0.005
Boundary for River Rch & Prof#=MDW T 086,Reach-1,4
Up Type=0
Dn Type=3
Dn Slope=0.005
Boundary for River Rch & Prof#=MDW T 086,Reach-1,5
Up Type=0
Dn Type=3
Dn Slope=0.005
Boundary for River Rch & Prof#=MDW T 086,Reach-1,6
Up Type=0
Dn Type=3
Dn Slope=0.005
Boundary for River Rch & Prof#=MDW T 086,Reach-1,7
Up Type=0
Dn Type=3
Dn Slope=0.005

--- MDW T 086.g01 (geometry) ---

Geom Title=Existing Conditions

River Reach=MDW T 086,Reach-1
Reach XY= 30
      2263179.00      7153810.00      2263128.98      7153740.01
      2263179.46      7153349.82      2263129.52      7153244.78
      2263128.04      7152925.96      2263080.97      7152898.03
      2263076.76      7152715.93      2262979.04      7152539.97
      2262981.25      7152415.94      2263078.78      7152176.00
      2262836.22      7152060.34      2262877.61      7151999.57
      2262879.52      7151775.22      2262926.64      7151704.02
      2262932.83      7151611.58      2263071.45      7151410.00
      2263037.04      7151360.00      2263070.78      7151306.73
      2263025.54      7151218.48      2262884.59      7151154.41
      2262825.09      7151018.65      2262779.26      7150989.72
      2262779.07      7150530.03      2262877.78      7150299.50
      2262877.78      7149870.50      2262815.61      7149696.67
      2262727.54      7149613.54      2262565.66      7149596.64
      2262484.81      7149512.32      2262429.00      7149360.00

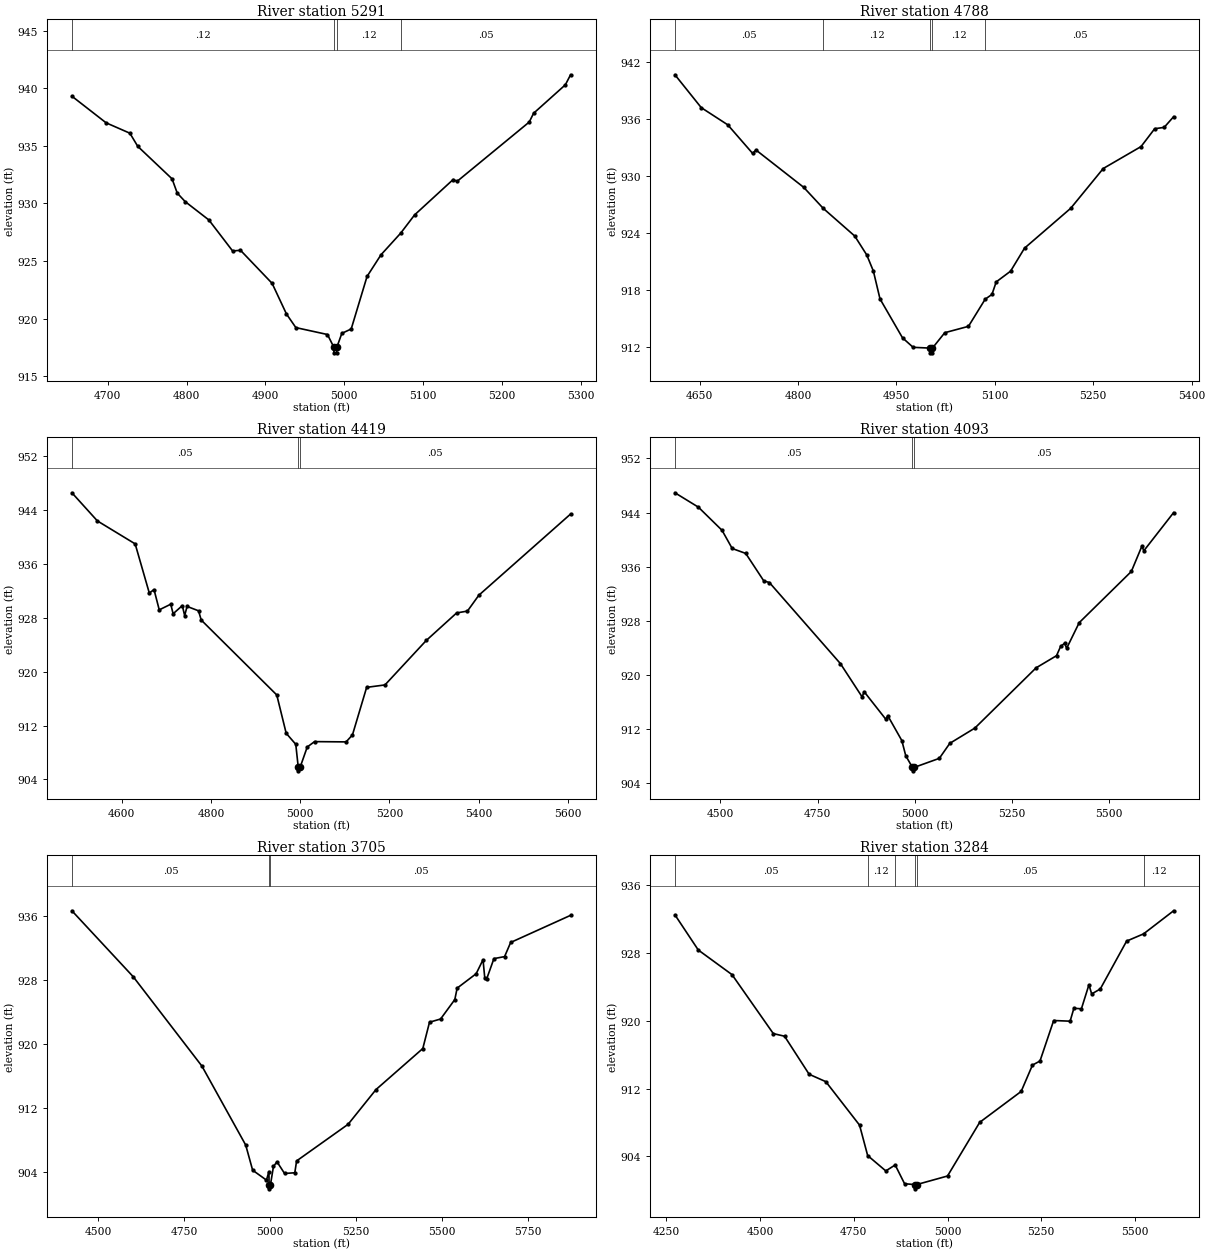
Type RM Length L Ch R = 1,5291,503,503,503
BEGIN DESCRIPTION:
MDW T 086 13.0
END DESCRIPTION:
XS GIS Cut Line= 3
      2263502.34      7153766.64      2263157.61      7153789.68
      2262872.39      7153820.73
#Sta/Elev= 30
  4654.5  939.31  4697.9  937.00  4728.0  936.10  4738.0  934.96  4781.5  932.14
  4788.1  930.90  4798.2  930.16  4828.2  928.57  4858.3  925.88  4868.3  925.94
  4908.4  923.07  4926.6  920.41  4938.5  919.23  4978.6  918.63  4986.6  917.54
  4986.8  917.04  4990.3  917.04  4990.6  917.54  4996.8  918.73  5008.7  919.11
  5028.8  923.67  5046.5  925.55  5071.5  927.43  5089.1  929.01  5138.0  932.08
  5143.0  931.92  5234.5  937.07  5240.0  937.83  5280.3  940.30  5286.9  941.17
#Mann=4,-1,0
  4654.5    0.12       0  4986.6    0.07       0  4990.6    0.12       0
  5071.5    0.05       0
Bank Sta=4986.6,4990.6
Exp/Cntr=0.3,0.1

Type RM Length L Ch R = 1,4788,369,369,369
BEGIN DESCRIPTION:
MDW T 086 12.0
END DESCRIPTION:
XS GIS Cut Line= 3
      2263558.73      7153258.83      2263179.00      7153310.00
      2262885.46      7153546.15
#Sta/Elev= 30
  4612.5  940.64  4652.6  937.18  4693.0  935.37  4730.9  932.36  4736.0  932.72
  4808.7  928.79  4838.4  926.58  4886.5  923.66  4904.8  921.67  4914.9  919.97
  4925.0  917.04  4959.3  912.94  4975.5  911.94  5000.9  911.86  5001.1  911.36
  5004.6  911.36  5004.9  911.86  5023.7  913.48  5059.8  914.15  5085.3  917.01
  5095.6  917.51  5102.1  918.83  5124.0  919.96  5145.2  922.38  5215.6  926.58
  5265.2  930.77  5322.8  933.08  5343.6  934.96  5358.0  935.10  5372.4  936.22
#Mann=5,-1,0
  4612.5    0.05       0  4838.4    0.12       0  5000.9    0.07       0
  5004.9    0.12       0  5085.3    0.05       0
Bank Sta=5000.9,5004.9
Exp/Cntr=0.3,0.1

Type RM Length L Ch R = 1,4419,326,326,326
BEGIN DESCRIPTION:
MDW T 086 11.0
END DESCRIPTION:
XS GIS Cut Line= 3
      2263612.95      7152792.27      2263129.00      7152960.00
      2262558.34      7153163.34
#Sta/Elev= 30
  4488.3  946.57  4545.4  942.39  4630.1  938.98  4661.8  931.68  4672.4  932.19
  4684.1  929.18  4709.9  930.02  4715.2  928.60  4735.8  929.81  4741.1  928.33
  4746.5  929.69  4772.2  929.04  4778.2  927.67  4947.6  916.54  4968.7  910.85
  4990.2  909.21  4995.8  905.77  4996.1  905.27  4999.8  905.77  5015.9  908.81
  5032.3  909.61  5103.1  909.57  5117.3  910.61  5149.1  917.67  5190.2  918.03
  5282.7  924.63  5350.8  928.72  5375.1  929.00  5400.6  931.35  5606.3  943.41
#Mann=3,-1,0
  4488.3    0.05       0  4995.8   0.033       0  4999.8    0.05       0
Bank Sta=4995.8,4999.8
Exp/Cntr=0.3,0.1

Type RM Length L Ch R = 1,4093,388,388,388
BEGIN DESCRIPTION:
MDW T 086 10.0
END DESCRIPTION:
XS GIS Cut Line= 3
      2263654.23      7152575.24      2263046.10      7152676.49
      2262412.34      7152878.55
#Sta/Elev= 30
  4383.5  946.92  4443.8  944.79  4504.6  941.36  4530.7  938.67  4565.5  937.94
  4611.8  933.88  4626.3  933.63  4808.9  921.62  4864.7  916.69  4869.8  917.47
  4925.5  913.39  4930.6  913.91  4966.7  910.23  4976.8  907.98  4994.0  906.25
  4994.2  905.75  4998.0  906.25  5063.1  907.60  5090.0  909.82  5154.4  912.08
  5311.8  921.00  5364.3  922.80  5374.8  924.17  5385.1  924.63  5390.4  923.90
  5422.6  927.69  5556.6  935.27  5583.6  939.00  5588.8  938.34  5665.2  943.98
#Mann=3,-1,0
  4383.5    0.05       0  4994.0   0.033       0  4998.0    0.05       0
Bank Sta=4994,4998
Exp/Cntr=0.3,0.1

Type RM Length L Ch R = 1,3705,421,421,421
BEGIN DESCRIPTION:
MDW T 086 9.0
END DESCRIPTION:
XS GIS Cut Line= 3
      2263602.13      7152267.08      2263029.15      7152325.06
      2262183.41      7152549.05
#Sta/Elev= 30
  4424.1  936.64  4602.6  928.39  4802.4  917.22  4929.8  907.35  4949.9  904.21
  4990.1  902.97  4997.3  904.04  4997.7  902.38  4998.0  901.88  5001.7  902.38
  5010.5  904.68  5020.8  905.26  5042.8  903.80  5072.6  903.89  5077.8  905.37
  5227.7  909.95  5308.8  914.29  5445.0  919.42  5464.5  922.71  5496.7  923.11
  5538.1  925.54  5544.9  926.97  5600.2  928.77  5620.2  930.52  5625.4  928.18
  5631.2  928.17  5651.9  930.66  5682.9  930.91  5700.6  932.68  5874.9  936.07
#Mann=3,-1,0
  4424.1    0.05       0  4997.7   0.033       0  5001.7    0.05       0
Bank Sta=4997.7,5001.7
Exp/Cntr=0.3,0.1

Type RM Length L Ch R = 1,3284,438,438,438
BEGIN DESCRIPTION:
MDW T 086 8.0
END DESCRIPTION:
XS GIS Cut Line= 3
      2263581.23      7152063.18      2262854.53      7152087.15
      2262254.33      7152146.17
#Sta/Elev= 30
  4272.9  932.45  4335.2  928.31  4425.2  925.41  4535.3  918.47  4565.3  918.16
  4630.9  913.68  4675.4  912.81  4765.4  907.69  4787.0  904.11  4835.4  902.30
  4860.4  903.00  4885.5  900.79  4913.5  900.69  4913.7  900.19  4917.5  900.69
  5000.0  901.70  5085.9  908.02  5196.5  911.66  5226.6  914.76  5246.7  915.24
  5283.2  920.01  5327.1  919.93  5337.1  921.45  5357.2  921.39  5377.3  924.22
  5384.6  923.14  5407.5  923.72  5477.8  929.36  5523.0  930.21  5603.1  932.93
#Mann=6,-1,0
  4272.9    0.05       0  4787.0    0.12       0  4860.4    0.05       0
  4913.5   0.033       0  4917.5    0.05       0  5523.0    0.12       0
Bank Sta=4913.5,4917.5
Exp/Cntr=0.3,0.1

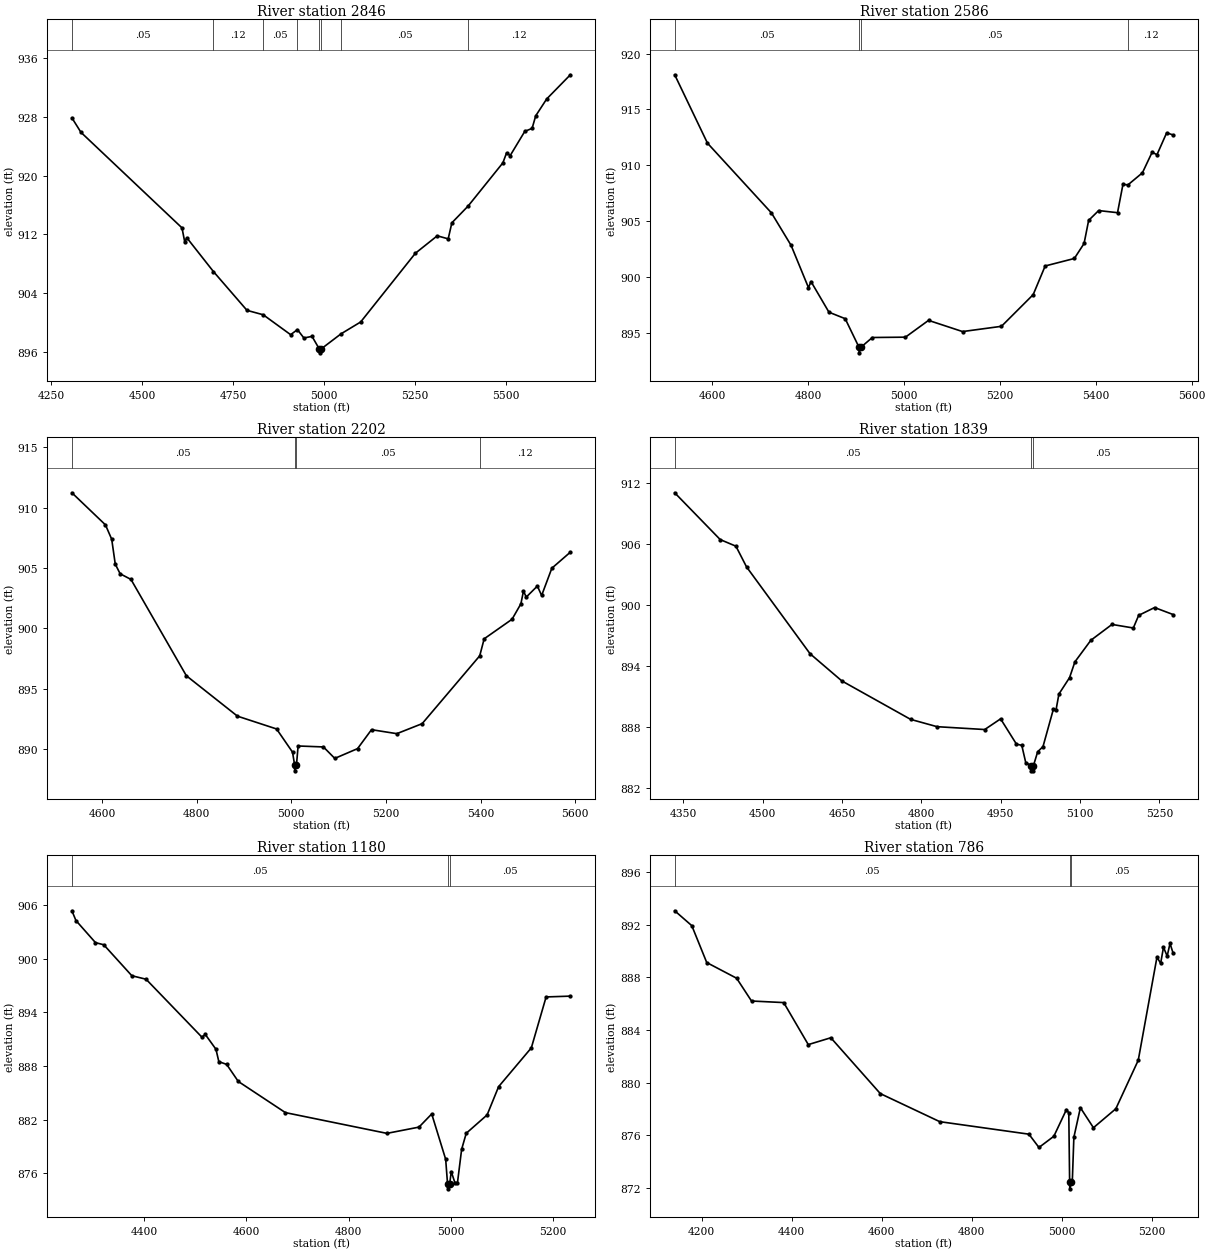
Type RM Length L Ch R = 1,2846,260,260,260
BEGIN DESCRIPTION:
MDW T 086 7.0
END DESCRIPTION:
XS GIS Cut Line= 3
      2263549.94      7151994.27      2262929.00      7151685.00
      2262254.05      7151735.00
#Sta/Elev= 30
  4306.3  927.86  4331.2  925.89  4609.0  912.89  4616.6  910.96  4622.2  911.55
  4695.4  906.95  4787.7  901.67  4832.3  901.07  4907.7  898.36  4926.4  899.05
  4944.1  897.91  4966.5  898.13  4986.8  896.39  4987.1  895.89  4990.8  896.39
  5046.4  898.48  5100.3  900.09  5250.7  909.44  5310.8  911.81  5340.9  911.40
  5351.0  913.58  5395.5  915.85  5491.3  921.74  5501.4  923.09  5511.4  922.73
  5551.5  926.02  5571.6  926.43  5581.6  928.14  5611.7  930.43  5676.8  933.72
#Mann=8,-1,0
  4306.3    0.05       0  4695.4    0.12       0  4832.3    0.05       0
  4926.4    0.12       0  4986.8    0.07       0  4990.8    0.12       0
  5046.4    0.05       0  5395.5    0.12       0
Bank Sta=4986.8,4990.8
Exp/Cntr=0.3,0.1

Type RM Length L Ch R = 1,2586,384,384,384
BEGIN DESCRIPTION:
MDW T 086 6.0
END DESCRIPTION:
XS GIS Cut Line= 3
      2263495.65      7151351.90      2263029.00      7151460.00
      2262475.69      7151553.73
#Sta/Elev= 30
  4521.2  918.10  4589.6  911.99  4723.1  905.76  4764.1  902.86  4800.4  899.08
  4805.6  899.63  4843.1  896.89  4877.0  896.31  4905.8  893.76  4906.1  893.26
  4909.8  893.76  4933.6  894.63  5002.7  894.66  5050.9  896.16  5121.9  895.16
  5203.1  895.63  5269.3  898.46  5294.3  901.02  5355.2  901.69  5375.5  903.03
  5385.0  905.09  5405.9  905.97  5445.3  905.78  5456.6  908.30  5467.2  908.27
  5497.2  909.34  5517.5  911.18  5527.6  910.96  5547.9  912.92  5561.4  912.72
#Mann=4,-1,0
  4521.2    0.05       0  4905.8   0.033       0  4909.8    0.05       0
  5467.2    0.12       0
Bank Sta=4905.8,4909.8
Exp/Cntr=0.3,0.1

Type RM Length L Ch R = 1,2202,363,363,363
BEGIN DESCRIPTION:
MDW T 086 5.0
END DESCRIPTION:
XS GIS Cut Line= 3
      2263397.71      7151064.58      2262948.86      7151180.20
      2262402.82      7151402.63
#Sta/Elev= 30
  4536.5  911.23  4607.4  908.57  4620.6  907.38  4628.1  905.32  4638.4  904.52
  4661.3  904.05  4778.3  896.07  4886.3  892.72  4968.9  891.66  5002.6  889.74
  5007.0  888.69  5007.2  888.19  5011.0  888.69  5014.4  890.25  5067.9  890.17
  5091.9  889.22  5140.0  890.03  5169.5  891.60  5223.0  891.27  5276.5  892.10
  5398.1  897.72  5407.5  899.13  5466.4  900.75  5485.1  902.03  5490.5  903.08
  5496.5  902.59  5519.9  903.50  5528.9  902.72  5550.5  904.98  5589.6  906.31
#Mann=4,-1,0
  4536.5    0.05       0  5007.0   0.033       0  5011.0    0.05       0
  5398.1    0.12       0
Bank Sta=5007,5011
Exp/Cntr=0.3,0.1

Type RM Length L Ch R = 1,1839,659,659,659
BEGIN DESCRIPTION:
MDW T 086 4.0
END DESCRIPTION:
XS GIS Cut Line= 3
      2263444.68      7150927.07      2262778.90      7150910.10
      2262504.02      7150935.00
#Sta/Elev= 30
  4334.0  910.99  4420.0  906.39  4449.7  905.74  4469.7  903.71  4589.8  895.17
  4649.8  892.50  4779.8  888.72  4829.8  888.00  4919.9  887.72  4949.9  888.77
  4979.9  886.28  4989.9  886.17  4997.4  884.47  5007.9  884.16  5008.2  883.66
  5011.7  883.66  5011.9  884.16  5020.0  885.54  5030.0  886.04  5049.7  889.73
  5054.7  889.66  5060.1  891.21  5080.2  892.82  5090.3  894.37  5120.4  896.49
  5160.4  898.05  5200.7  897.70  5210.8  898.94  5240.9  899.71  5276.0  899.02
#Mann=3,-1,0
  4334.0    0.05       0  5007.9   0.033       0  5011.9    0.05       0
Bank Sta=5007.9,5011.9
Exp/Cntr=0.3,0.1

Type RM Length L Ch R = 1,1180,394,394,394
BEGIN DESCRIPTION:
MDW T 086 2.0
END DESCRIPTION:
XS GIS Cut Line= 3
      2263588.67      7150498.17      2262869.80      7150280.99
      2262653.12      7150225.24
#Sta/Elev= 30
  4258.9  905.36  4266.8  904.27  4305.0  901.80  4321.2  901.56  4376.1  898.10
  4403.9  897.71  4513.2  891.23  4519.7  891.54  4540.6  889.88  4546.2  888.50
  4561.5  888.19  4584.3  886.28  4676.4  882.80  4874.9  880.48  4937.6  881.18
  4962.5  882.65  4989.8  877.58  4993.5  874.78  4993.8  874.28  4997.5  874.78
  5000.7  876.21  5007.7  874.98  5012.9  874.98  5021.0  878.70  5030.0  880.49
  5070.8  882.54  5093.3  885.70  5157.3  890.04  5186.2  895.73  5233.6  895.82
#Mann=3,-1,0
  4258.9    0.05       0  4993.5   0.033       0  4997.5    0.05       0
Bank Sta=4993.5,4997.5
Exp/Cntr=0.3,0.1

Type RM Length L Ch R = 1,786,195,195,195
BEGIN DESCRIPTION:
MDW T 086 1.0
END DESCRIPTION:
XS GIS Cut Line= 3
      2263703.59      7150134.93      2262856.67      7149882.77
      2262679.28      7150019.94
#Sta/Elev= 30
  4140.0  893.05  4178.0  891.92  4211.2  889.12  4277.6  887.93  4310.7  886.20
  4382.3  886.08  4436.9  882.89  4487.0  883.41  4597.0  879.17  4729.1  877.04
  4927.3  876.09  4949.6  875.08  4982.7  875.93  5010.7  877.96  5015.9  877.71
  5017.8  872.44  5018.1  871.94  5021.8  872.44  5023.7  872.44  5027.2  875.85
  5041.7  878.10  5070.7  876.58  5120.5  878.02  5170.3  881.70  5211.9  889.53
  5220.1  889.06  5226.4  890.28  5234.6  889.61  5240.9  890.57  5247.9  889.82
#Mann=3,-1,0
  4140.0    0.05       0  5017.8   0.033       0  5021.8    0.05       0
Bank Sta=5017.8,5021.8
Exp/Cntr=0.3,0.1

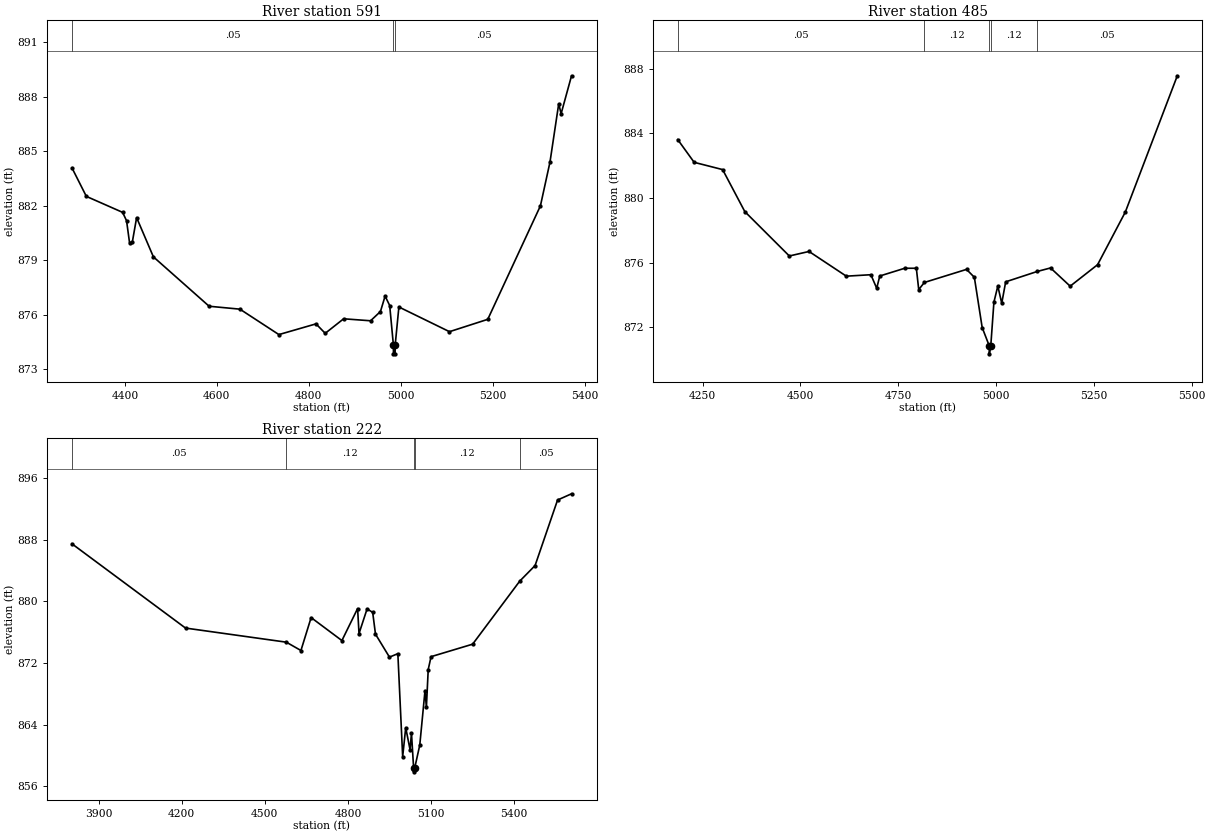
Type RM Length L Ch R = 1,591,106,106,106
BEGIN DESCRIPTION:
Mapping XS 62a73c51
END DESCRIPTION:
XS GIS Cut Line= 4
      2263459.46      7150002.32      2263017.37      7149723.55
      2262763.95      7149706.92      2262677.13      7150005.03
#Sta/Elev= 30
  4284.7  884.08  4316.0  882.51  4394.9  881.63  4403.5  881.17  4410.1  879.94
  4416.1  880.00  4425.4  881.34  4461.9  879.18  4583.2  876.46  4650.2  876.30
  4735.0  874.90  4815.7  875.49  4835.8  874.97  4875.9  875.77  4934.5  875.66
  4956.0  876.17  4966.1  877.02  4976.1  876.50  4984.1  874.34  4984.3  873.84
  4987.8  873.84  4988.1  874.34  4996.1  876.42  5106.2  875.06  5189.5  875.74
  5304.1  881.99  5324.9  884.40  5343.9  887.61  5349.1  887.06  5371.8  889.15
#Mann=3,-1,0
  4284.7    0.05       0  4984.1   0.033       0  4988.1    0.05       0
Bank Sta=4984.1,4988.1
Exp/Cntr=0.3,0.1

Type RM Length L Ch R = 1,485,263,263,263
BEGIN DESCRIPTION:
Mapping XS cc2215df
END DESCRIPTION:
XS GIS Cut Line= 4
      2263453.56      7149993.70      2262928.10      7149629.74
      2262668.46      7149635.94      2262645.78      7150013.46
#Sta/Elev= 30
  4186.3  883.62  4228.3  882.21  4301.1  881.76  4357.8  879.16  4471.6  876.41
  4522.0  876.69  4617.3  875.16  4680.1  875.25  4695.0  874.41  4702.8  875.17
  4766.6  875.65  4796.3  875.65  4802.4  874.33  4816.8  874.77  4924.6  875.58
  4944.6  875.09  4964.6  871.98  4982.6  870.85  4982.9  870.35  4986.6  870.85
  4994.6  873.55  5004.6  874.55  5014.6  873.48  5024.7  874.81  5105.2  875.45
  5139.4  875.67  5189.5  874.54  5259.6  875.87  5330.5  879.13  5463.4  887.57
#Mann=5,-1,0
  4186.3    0.05       0  4816.8    0.12       0  4982.6    0.07       0
  4986.6    0.12       0  5105.2    0.05       0
Bank Sta=4982.6,4986.6
Exp/Cntr=0.3,0.1

Type RM Length L Ch R = 1,222,0,0,0
BEGIN DESCRIPTION:
MDW T 086 0.5
END DESCRIPTION:
XS GIS Cut Line= 4
      2263573.93      7150055.96      2262925.50      7149610.65
      2262519.64      7149551.29      2262626.02      7150149.71
#Sta/Elev= 30
  3803.2  887.46  4213.4  876.53  4577.5  874.70  4630.3  873.62  4667.1  877.89
  4778.3  874.91  4835.0  879.06  4840.1  875.82  4869.3  879.02  4889.5  878.56
  4899.6  875.74  4950.1  872.76  4980.4  873.21  4997.8  859.85  5008.8  863.61
  5024.5  860.75  5029.6  862.92  5037.3  858.38  5037.6  857.88  5041.3  858.38
  5059.6  861.36  5078.5  868.42  5083.5  866.25  5090.1  871.15  5100.3  872.82
  5250.5  874.44  5420.7  882.62  5476.1  884.64  5557.3  893.14  5607.8  893.95
#Mann=5,-1,0
  3803.2    0.05       0  4577.5    0.12       0  5037.3    0.07       0
  5041.3    0.12       0  5420.7    0.05       0
Bank Sta=5037.3,5041.3
Exp/Cntr=0.3,0.1

Chan Stop Cuts=-1