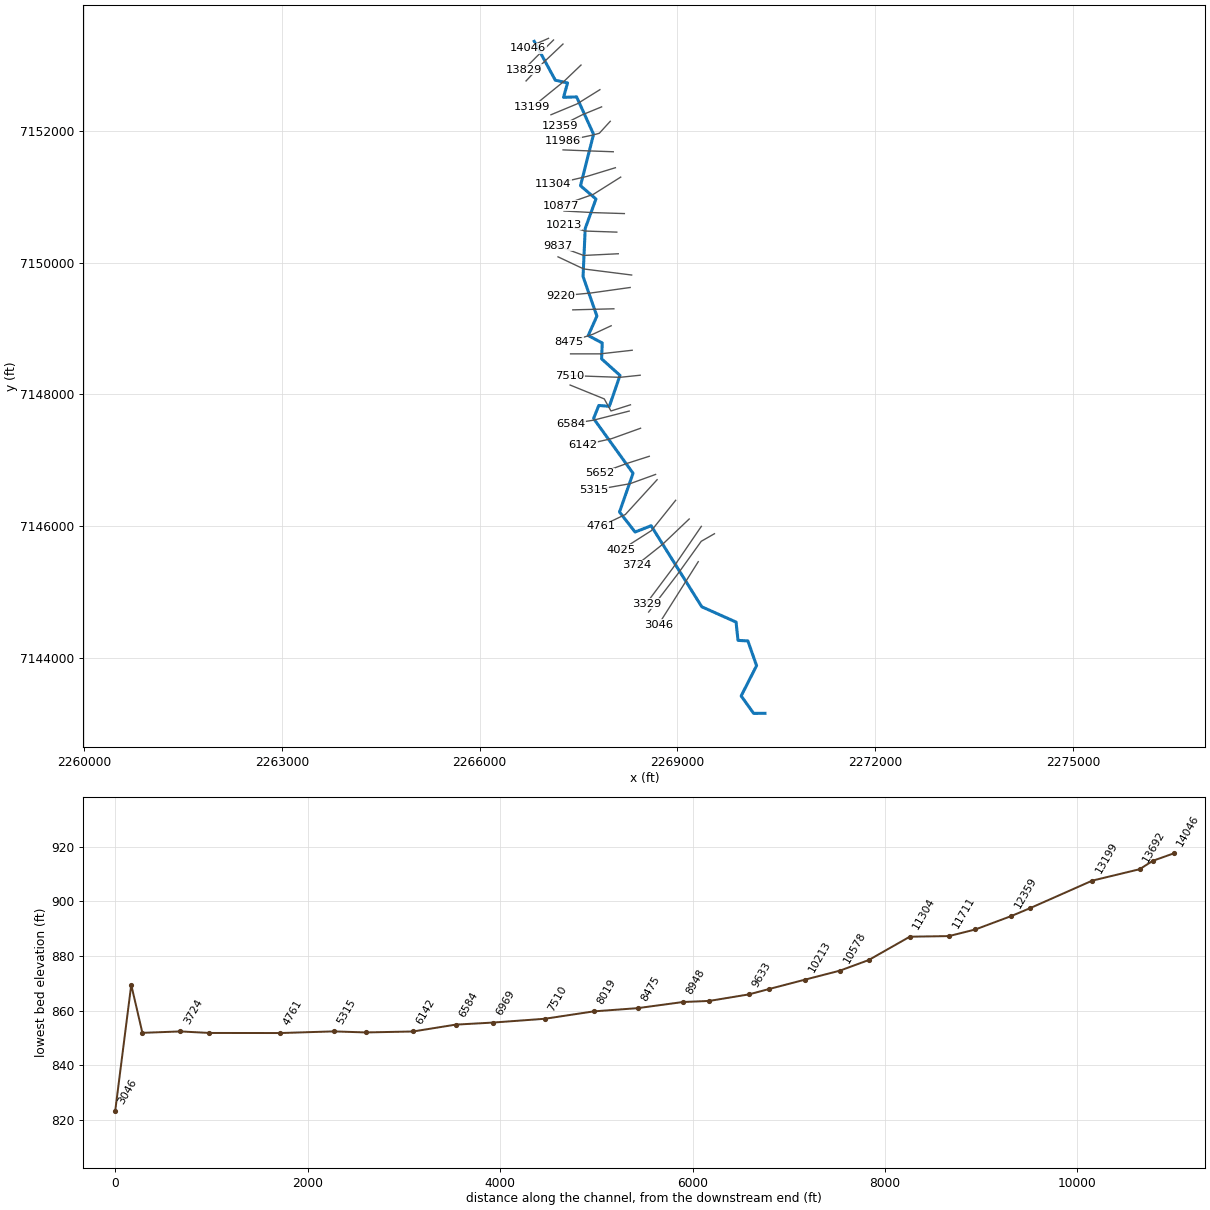
--- MDW T 087.prj (project) ---

Proj Title=MDW T 087 Base Level Engineering
Current Plan=p01
Default Exp/Contr=0.3,0.1
English Units
Geom File=g01
Flow File=f01
Plan File=p01
Y Axis Title=Elevation
X Axis Title(PF)=Main Channel Distance
X Axis Title(XS)=Station
BEGIN DESCRIPTION:
MDW T 087
END DESCRIPTION:
DSS Export Rating Curves= 0
DSS Export Rating Curve Sorted= 0
DSS Export Volume Flow Curves= 0
DXF OffsetX= 0
DXF OffsetY= 0
DXF ScaleX= 1
DXF ScaleY= 10

--- MDW T 087.p01 (plan) ---

Plan Title=Multiple Run
Short Identifier=Multiple
Geom File=g01
Flow File=f01
Subcritical Flow
K Sum by GR= 0
Std Step Tol= 0.01
Critical Tol= 0.01
Num of Std Step Trials= 20
Max Error Tol= 0.3
Flow Tol Ratio= 0.001
Split Flow NTrial= 30
Split Flow Tol= 0.02
Split Flow Ratio= 0.02
Log Output Level= 0
Friction Slope Method= 1
Unsteady Friction Slope Method= 2
Unsteady Bridges Friction Slope Method= 1
Parabolic Critical Depth
Global Vel Dist=  1 , 1 , 1
Global Log Level= 0
CheckData=True
Encroach Param= -1, 0, 0, 0
BEGIN DESCRIPTION:
Multiple Run
END DESCRIPTION:

--- MDW T 087.f01 (steady flow) ---

Flow Title=Multiple
Number of Profiles=7
Profile Names=10-year,25-year,50-year,1pct_min,100-year,1pct_plu,500-year
River Rch & RM= MDW T 087,Reach-1,14046
     795    1112    1380     850    1696    3384    2568
River Rch & RM= MDW T 087,Reach-1,9220
    1119    1590    1992    1237    2469    4926    3803
Boundary for River Rch & Prof#=MDW T 087,Reach-1,1
Up Type=0
Dn Type=3
Dn Slope=0.005
Boundary for River Rch & Prof#=MDW T 087,Reach-1,2
Up Type=0
Dn Type=3
Dn Slope=0.005
Boundary for River Rch & Prof#=MDW T 087,Reach-1,3
Up Type=0
Dn Type=3
Dn Slope=0.005
Boundary for River Rch & Prof#=MDW T 087,Reach-1,4
Up Type=0
Dn Type=3
Dn Slope=0.005
Boundary for River Rch & Prof#=MDW T 087,Reach-1,5
Up Type=0
Dn Type=3
Dn Slope=0.005
Boundary for River Rch & Prof#=MDW T 087,Reach-1,6
Up Type=0
Dn Type=3
Dn Slope=0.005
Boundary for River Rch & Prof#=MDW T 087,Reach-1,7
Up Type=0
Dn Type=3
Dn Slope=0.005

--- MDW T 087.g01 (geometry) ---

Geom Title=Existing Conditions

River Reach=MDW T 087,Reach-1
Reach XY= 30
      2266829.00      7153360.00      2267147.96      7152770.13
      2267333.93      7152728.78      2267272.94      7152510.03
      2267471.25      7152516.45      2267728.41      7151949.38
      2267530.07      7151168.30      2267764.71      7150966.45
      2267601.95      7150520.23      2267569.06      7149790.31
      2267778.95      7149189.96      2267647.44      7148894.67
      2267859.79      7148781.31      2267850.36      7148540.80
      2268129.40      7148289.42      2267967.97      7147820.63
      2267807.93      7147833.03      2267728.76      7147635.27
      2268327.20      7146803.89      2268121.86      7146215.55
      2268358.18      7145912.01      2268601.28      7146007.40
      2269369.30      7144777.73      2269889.84      7144544.97
      2269919.30      7144267.31      2270068.82      7144258.98
      2270200.77      7143883.61      2269966.91      7143424.19
      2270156.13      7143159.54      2270329.00      7143160.00

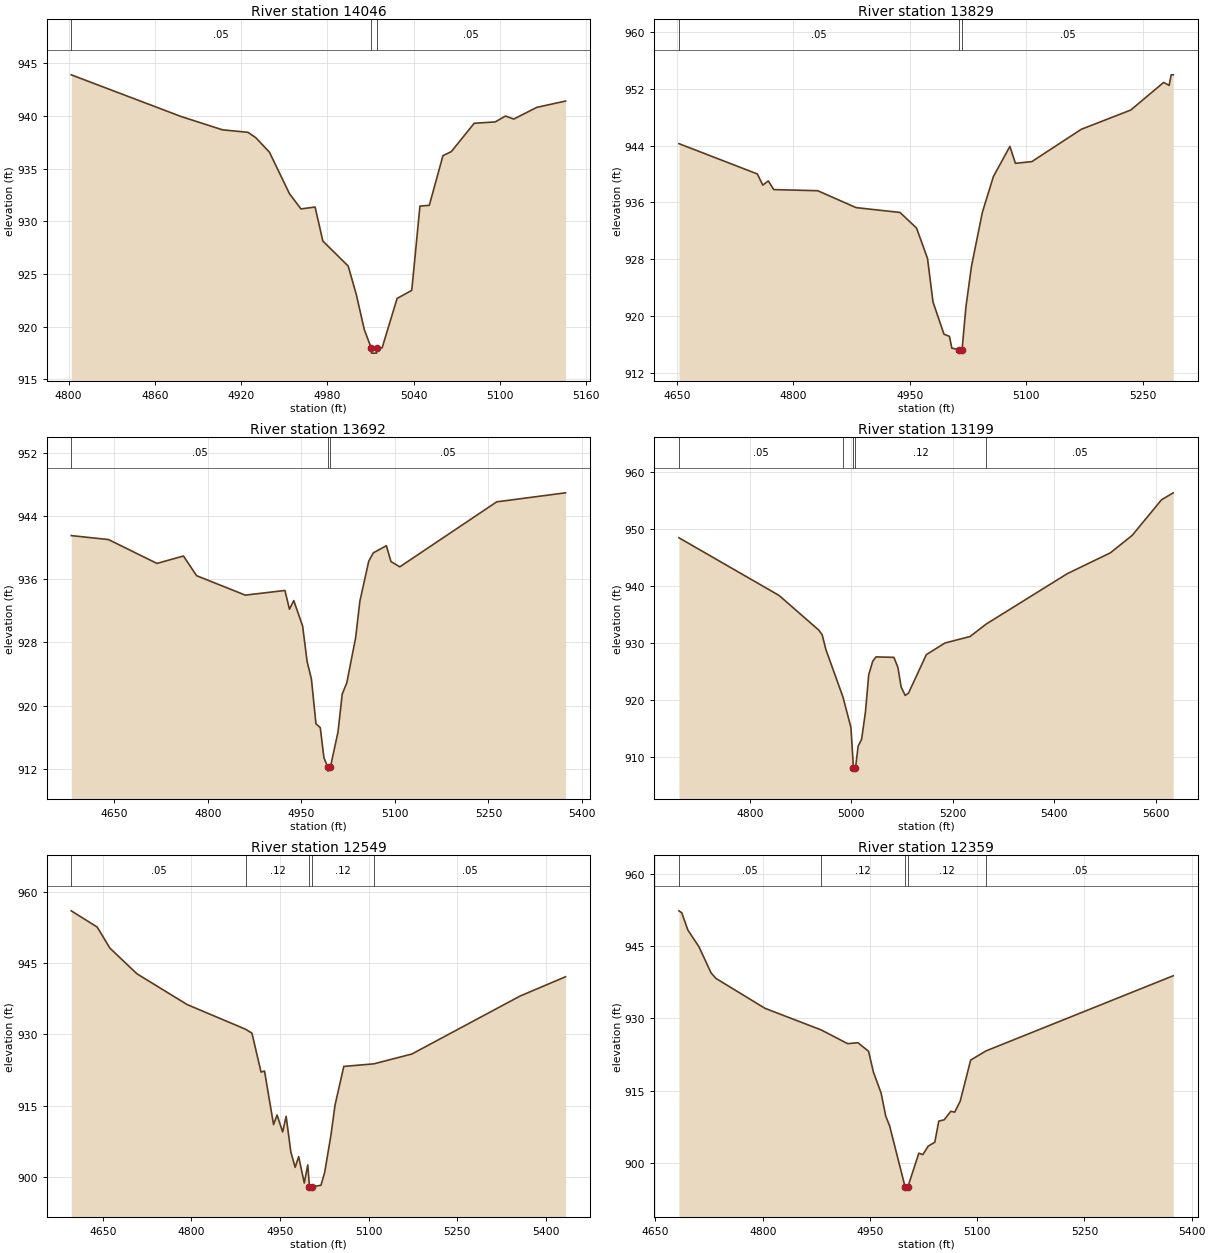
Type RM Length L Ch R = 1,14046,217,217,217
BEGIN DESCRIPTION:
MDW T 087 32.0
END DESCRIPTION:
XS GIS Cut Line= 3
      2267044.99      7153405.43      2266851.15      7153319.47
      2266736.27      7153255.37
#Sta/Elev= 30
  4801.9  943.90  4878.3  939.94  4907.0  938.68  4924.8  938.44  4930.3  937.92
  4939.7  936.55  4953.6  932.61  4961.6  931.17  4971.4  931.35  4976.8  928.12
  4994.4  925.75  5000.1  923.02  5005.6  919.72  5010.4  917.98  5010.6  917.48
  5014.1  917.48  5014.4  917.98  5018.0  917.98  5028.4  922.67  5038.6  923.44
  5044.3  931.44  5050.8  931.51  5060.3  936.23  5066.1  936.61  5082.0  939.30
  5096.6  939.43  5103.8  939.99  5109.5  939.70  5125.5  940.81  5145.5  941.41
#Mann=3,-1,0
  4801.9    0.05       0  5010.4   0.033       0  5014.4    0.05       0
Bank Sta=5010.4,5014.4
Exp/Cntr=0.3,0.1

Type RM Length L Ch R = 1,13829,137,137,137
BEGIN DESCRIPTION:
MDW T 087 31.5
END DESCRIPTION:
XS GIS Cut Line= 3
      2267121.28      7153380.44      2266869.82      7153132.17
      2266670.34      7152931.24
#Sta/Elev= 30
  4652.8  944.27  4753.8  940.00  4760.8  938.43  4767.9  939.02  4774.9  937.80
  4831.5  937.64  4881.0  935.26  4937.5  934.58  4958.8  932.38  4972.9  928.11
  4980.0  921.97  4994.1  917.44  5001.2  917.13  5004.2  915.47  5013.4  915.27
  5013.6  914.77  5017.4  915.27  5022.4  921.28  5029.5  926.99  5043.6  934.62
  5057.8  939.65  5079.0  943.88  5086.1  941.50  5107.3  941.74  5170.9  946.29
  5234.6  949.00  5277.0  952.89  5284.1  952.48  5286.7  953.96  5289.3  953.96
#Mann=3,-1,0
  4652.8    0.05       0  5013.4   0.033       0  5017.4    0.05       0
Bank Sta=5013.4,5017.4
Exp/Cntr=0.3,0.1

Type RM Length L Ch R = 1,13692,493,493,493
BEGIN DESCRIPTION:
MDW T 087 31.0
END DESCRIPTION:
XS GIS Cut Line= 3
      2267264.49      7153318.74      2266966.90      7153036.89
      2266704.54      7152758.79
#Sta/Elev= 30
  4581.3  941.49  4641.0  940.99  4718.7  937.97  4761.1  938.91  4782.2  936.42
  4860.2  933.96  4923.8  934.55  4931.0  932.18  4937.9  933.27  4952.1  930.06
  4959.3  925.57  4966.2  923.36  4973.5  917.69  4980.4  917.20  4986.3  913.38
  4992.6  912.20  4992.8  911.70  4996.6  912.20  5008.8  916.64  5015.6  921.45
  5022.9  922.86  5037.1  928.58  5043.9  933.20  5058.1  938.25  5065.4  939.31
  5086.4  940.21  5093.7  938.21  5107.9  937.54  5263.2  945.76  5373.5  946.90
#Mann=3,-1,0
  4581.3    0.05       0  4992.6   0.033       0  4996.6    0.05       0
Bank Sta=4992.6,4996.6
Exp/Cntr=0.3,0.1

Type RM Length L Ch R = 1,13199,650,650,650
BEGIN DESCRIPTION:
MDW T 087 30.0
END DESCRIPTION:
XS GIS Cut Line= 3
      2267538.10      7153000.11      2267281.71      7152754.59
      2266801.39      7152364.11
#Sta/Elev= 30
  4660.3  948.40  4857.7  938.29  4935.7  932.24  4942.6  931.41  4949.8  928.84
  4983.6  920.49  4999.3  915.14  5004.2  908.02  5004.4  907.52  5008.2  908.02
  5013.4  911.89  5020.3  913.10  5027.9  917.93  5034.3  924.40  5042.2  926.77
  5048.7  927.53  5083.9  927.45  5091.8  925.70  5098.2  922.26  5106.2  920.78
  5112.6  921.17  5147.8  927.92  5184.4  929.96  5234.0  931.10  5266.1  933.30
  5425.8  942.12  5510.5  945.76  5553.6  948.83  5611.1  955.04  5634.3  956.27
#Mann=5,-1,0
  4660.3    0.05       0  4983.6    0.12       0  5004.2    0.07       0
  5008.2    0.12       0  5266.1    0.05       0
Bank Sta=5004.2,5008.2
Exp/Cntr=0.3,0.1

Type RM Length L Ch R = 1,12549,190,190,190
BEGIN DESCRIPTION:
MDW T 087 29.0
END DESCRIPTION:
XS GIS Cut Line= 3
      2267824.64      7152626.08      2267477.01      7152409.74
      2267082.40      7152245.71
#Sta/Elev= 30
  4596.6  956.07  4640.5  952.65  4662.1  948.20  4707.8  942.80  4792.8  936.31
  4891.7  931.11  4902.5  930.28  4917.9  922.08  4923.8  922.29  4939.1  911.00
  4945.0  913.03  4954.5  909.46  4960.4  912.76  4968.4  905.18  4975.7  902.00
  4981.6  904.26  4991.1  898.69  4997.0  902.51  4999.9  897.90  5000.2  897.40
  5003.9  897.90  5019.3  898.21  5025.6  900.90  5036.4  908.89  5043.1  915.07
  5058.0  923.27  5108.7  923.81  5173.2  925.88  5356.5  938.11  5433.4  942.17
#Mann=5,-1,0
  4596.6    0.05       0  4891.7    0.12       0  4999.9    0.07       0
  5003.9    0.12       0  5108.7    0.05       0
Bank Sta=4999.9,5003.9
Exp/Cntr=0.3,0.1

Type RM Length L Ch R = 1,12359,373,373,373
BEGIN DESCRIPTION:
MDW T 087 28.0
END DESCRIPTION:
XS GIS Cut Line= 3
      2267850.58      7152365.35      2267554.69      7152243.81
      2267223.19      7152076.07
#Sta/Elev= 30
  4682.8  952.28  4686.8  951.86  4695.3  948.30  4710.8  944.84  4727.8  939.41
  4734.8  938.25  4803.4  932.06  4881.9  927.59  4918.8  924.75  4933.2  924.95
  4948.1  923.16  4954.8  918.88  4965.6  914.52  4972.1  909.73  4977.5  907.73
  4999.1  895.10  4999.4  894.60  5003.1  895.10  5018.4  902.04  5024.0  901.76
  5031.5  903.52  5040.7  904.31  5046.3  908.69  5053.9  908.97  5063.0  910.72
  5068.6  910.56  5076.3  912.85  5090.9  921.35  5112.4  923.25  5374.2  938.82
#Mann=5,-1,0
  4682.8    0.05       0  4881.9    0.12       0  4999.1    0.07       0
  5003.1    0.12       0  5112.4    0.05       0
Bank Sta=4999.1,5003.1
Exp/Cntr=0.3,0.1

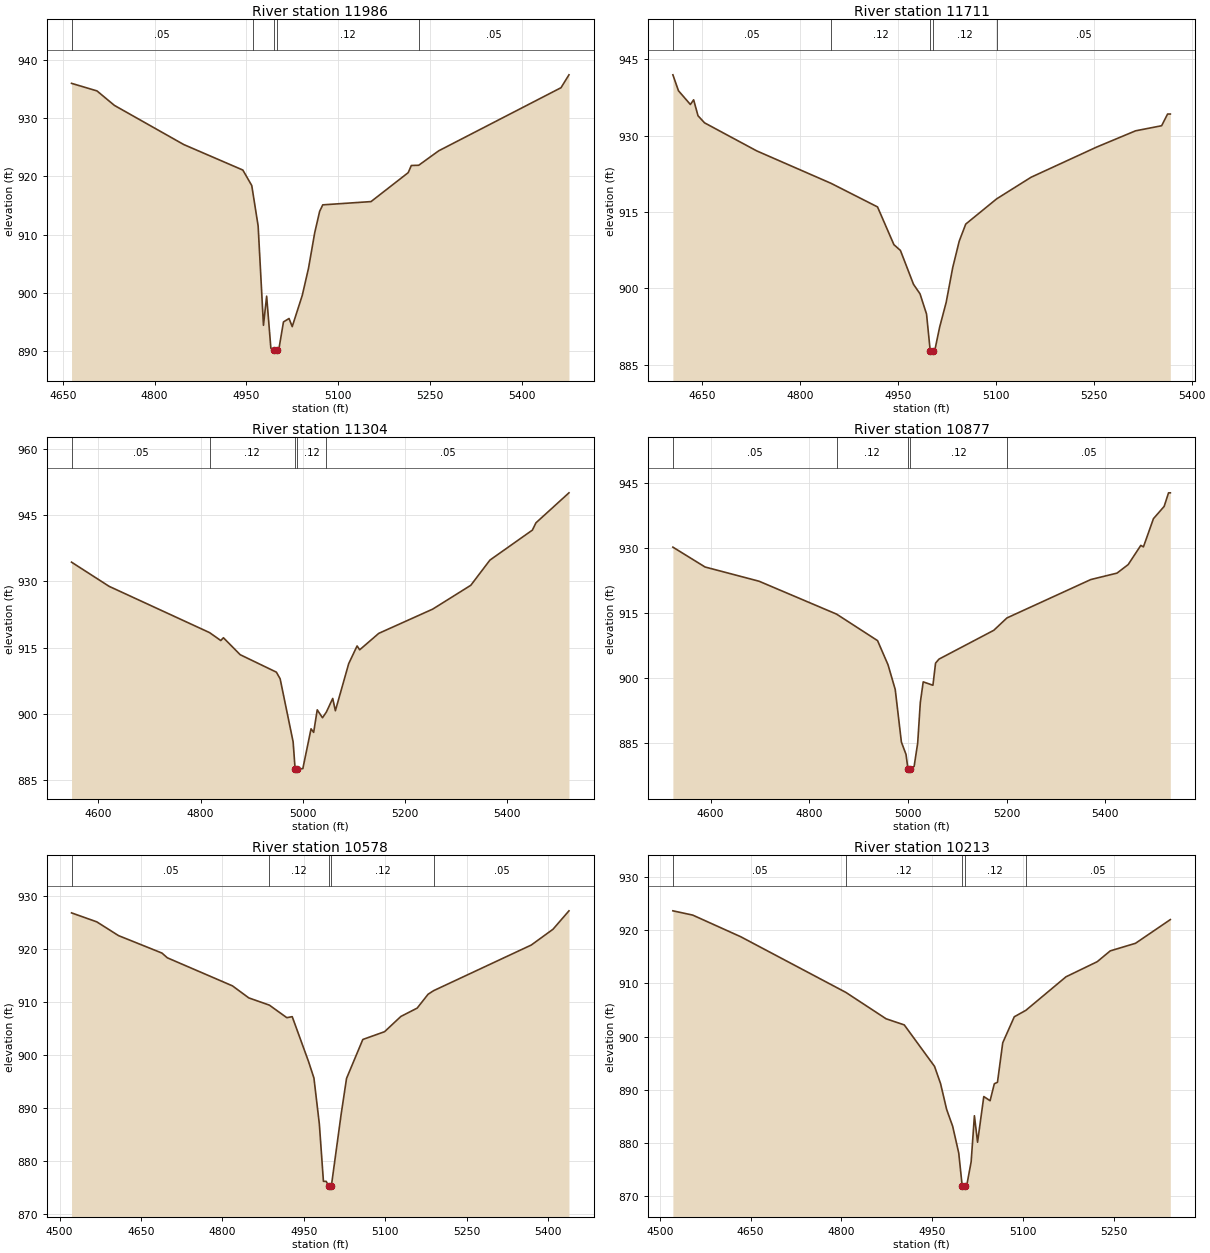
Type RM Length L Ch R = 1,11986,275,275,275
BEGIN DESCRIPTION:
MDW T 087 27.0
END DESCRIPTION:
XS GIS Cut Line= 4
      2267981.50      7152146.30      2267815.71      7151964.71
      2267729.41      7151939.87      2267262.43      7151842.08
#Sta/Elev= 30
  4664.3  935.97  4705.9  934.67  4734.3  932.19  4847.7  925.47  4944.2  921.10
  4958.8  918.44  4960.2  917.51  4969.2  911.51  4977.9  894.47  4983.1  899.47
  4990.0  890.55  4995.6  890.20  4995.9  889.70  4999.6  890.20  5002.8  890.20
  5010.6  895.05  5019.7  895.64  5024.9  894.25  5041.3  899.60  5051.5  904.25
  5061.7  910.37  5069.7  914.01  5074.8  915.13  5153.7  915.69  5214.4  920.65
  5219.5  921.88  5231.6  921.92  5264.3  924.40  5464.1  935.22  5477.1  937.43
#Mann=5,-1,0
  4664.3    0.05       0  4960.2    0.12       0  4995.6    0.07       0
  4999.6    0.12       0  5231.6    0.05       0
Bank Sta=4995.6,4999.6
Exp/Cntr=0.3,0.1

Type RM Length L Ch R = 1,11711,407,407,407
BEGIN DESCRIPTION:
MDW T 087 26.0
END DESCRIPTION:
XS GIS Cut Line= 3
      2268027.50      7151683.94      2267628.84      7151698.01
      2267265.72      7151712.15
#Sta/Elev= 30
  4605.0  941.94  4613.5  938.82  4631.8  936.11  4636.8  937.03  4643.5  933.90
  4653.5  932.51  4733.6  926.99  4847.3  920.63  4918.6  915.99  4943.7  908.58
  4953.7  907.44  4973.7  900.80  4983.7  898.92  4993.7  894.95  4999.3  887.77
  4999.6  887.27  5003.3  887.77  5006.3  887.77  5013.8  892.38  5023.8  897.24
  5033.8  904.06  5043.8  909.27  5053.8  912.62  5101.1  917.57  5153.9  921.82
  5253.9  927.72  5314.0  930.94  5354.0  931.94  5363.1  934.24  5367.3  934.24
#Mann=5,-1,0
  4605.0    0.05       0  4847.3    0.12       0  4999.3    0.07       0
  5003.3    0.12       0  5101.1    0.05       0
Bank Sta=4999.3,5003.3
Exp/Cntr=0.3,0.1

Type RM Length L Ch R = 1,11304,427,427,427
BEGIN DESCRIPTION:
MDW T 087 25.0
END DESCRIPTION:
XS GIS Cut Line= 3
      2268059.43      7151441.57      2267629.00      7151310.00
      2267119.27      7151190.69
#Sta/Elev= 30
  4547.3  934.36  4621.0  928.88  4817.5  918.41  4839.4  916.62  4844.6  917.25
  4877.4  913.41  4948.2  909.46  4955.6  907.95  4981.0  893.69  4984.9  887.55
  4985.2  887.05  4988.9  887.55  5000.0  887.61  5016.1  896.63  5021.2  895.82
  5028.2  900.93  5038.5  899.13  5046.1  900.43  5058.5  903.51  5063.7  900.72
  5089.8  911.39  5106.2  915.39  5111.3  914.52  5148.6  918.24  5254.2  923.73
  5328.8  929.13  5366.2  934.83  5449.3  941.62  5456.3  943.27  5520.9  950.06
#Mann=5,-1,0
  4547.3    0.05       0  4817.5    0.12       0  4984.9    0.07       0
  4988.9    0.12       0  5046.1    0.05       0
Bank Sta=4984.9,4988.9
Exp/Cntr=0.3,0.1

Type RM Length L Ch R = 1,10877,299,299,299
BEGIN DESCRIPTION:
MDW T 087 24.0
END DESCRIPTION:
XS GIS Cut Line= 3
      2268140.07      7151299.19      2267728.76      7151039.85
      2267237.24      7150865.13
#Sta/Elev= 30
  4523.6  930.18  4588.8  925.60  4698.2  922.32  4855.3  914.73  4938.3  908.62
  4959.5  903.05  4974.1  897.35  4986.6  885.22  4996.0  882.36  4999.9  879.02
  5000.2  878.52  5003.9  879.02  5012.4  879.61  5019.6  884.98  5024.9  894.32
  5030.8  899.11  5050.5  898.33  5055.8  903.42  5062.7  904.35  5173.8  911.00
  5200.4  913.85  5370.4  922.71  5423.5  924.19  5446.2  926.17  5471.7  930.59
  5477.0  930.24  5497.3  936.75  5519.0  939.58  5527.9  942.71  5531.5  942.71
#Mann=5,-1,0
  4523.6    0.05       0  4855.3    0.12       0  4999.9    0.07       0
  5003.9    0.12       0  5200.4    0.05       0
Bank Sta=4999.9,5003.9
Exp/Cntr=0.3,0.1

Type RM Length L Ch R = 1,10578,365,365,365
BEGIN DESCRIPTION:
MDW T 087 23.0
END DESCRIPTION:
XS GIS Cut Line= 3
      2268195.48      7150745.60      2267729.00      7150760.00
      2267279.68      7150784.67
#Sta/Elev= 30
  4522.0  926.85  4568.5  925.16  4608.5  922.56  4688.6  919.26  4698.6  918.36
  4818.6  913.06  4848.6  910.79  4886.6  909.42  4918.7  907.05  4928.7  907.24
  4958.7  898.78  4968.7  895.65  4978.7  886.94  4986.2  876.12  4991.2  876.12
  4996.7  875.15  4997.0  874.65  5000.5  874.65  5000.7  875.15  5018.7  888.69
  5028.8  895.57  5058.8  902.93  5098.9  904.40  5128.9  907.28  5159.0  908.86
  5179.0  911.47  5189.4  912.16  5369.3  920.78  5409.3  923.76  5438.7  927.24
#Mann=5,-1,0
  4522.0    0.05       0  4886.6    0.12       0  4996.7    0.07       0
  5000.7    0.12       0  5189.4    0.05       0
Bank Sta=4996.7,5000.7
Exp/Cntr=0.3,0.1

Type RM Length L Ch R = 1,10213,376,376,376
BEGIN DESCRIPTION:
MDW T 087 22.0
END DESCRIPTION:
XS GIS Cut Line= 3
      2268081.07      7150464.03      2267598.45      7150480.55
      2267273.94      7150578.58
#Sta/Elev= 30
  4521.6  923.64  4554.3  922.84  4633.7  918.77  4807.4  908.31  4873.9  903.35
  4903.9  902.20  4953.9  894.41  4963.9  891.16  4973.9  886.32  4983.9  883.14
  4993.9  878.13  4999.7  871.84  5000.0  871.34  5003.7  871.84  5006.8  871.84
  5014.4  876.47  5019.8  885.13  5025.0  880.15  5035.3  888.74  5045.7  887.95
  5052.7  891.14  5057.9  891.42  5066.6  898.84  5085.7  903.73  5104.8  904.94
  5171.1  911.24  5222.7  914.08  5244.2  916.11  5286.0  917.54  5343.5  921.99
#Mann=5,-1,0
  4521.6    0.05       0  4807.4    0.12       0  4999.7    0.07       0
  5003.7    0.12       0  5104.8    0.05       0
Bank Sta=4999.7,5003.7
Exp/Cntr=0.3,0.1

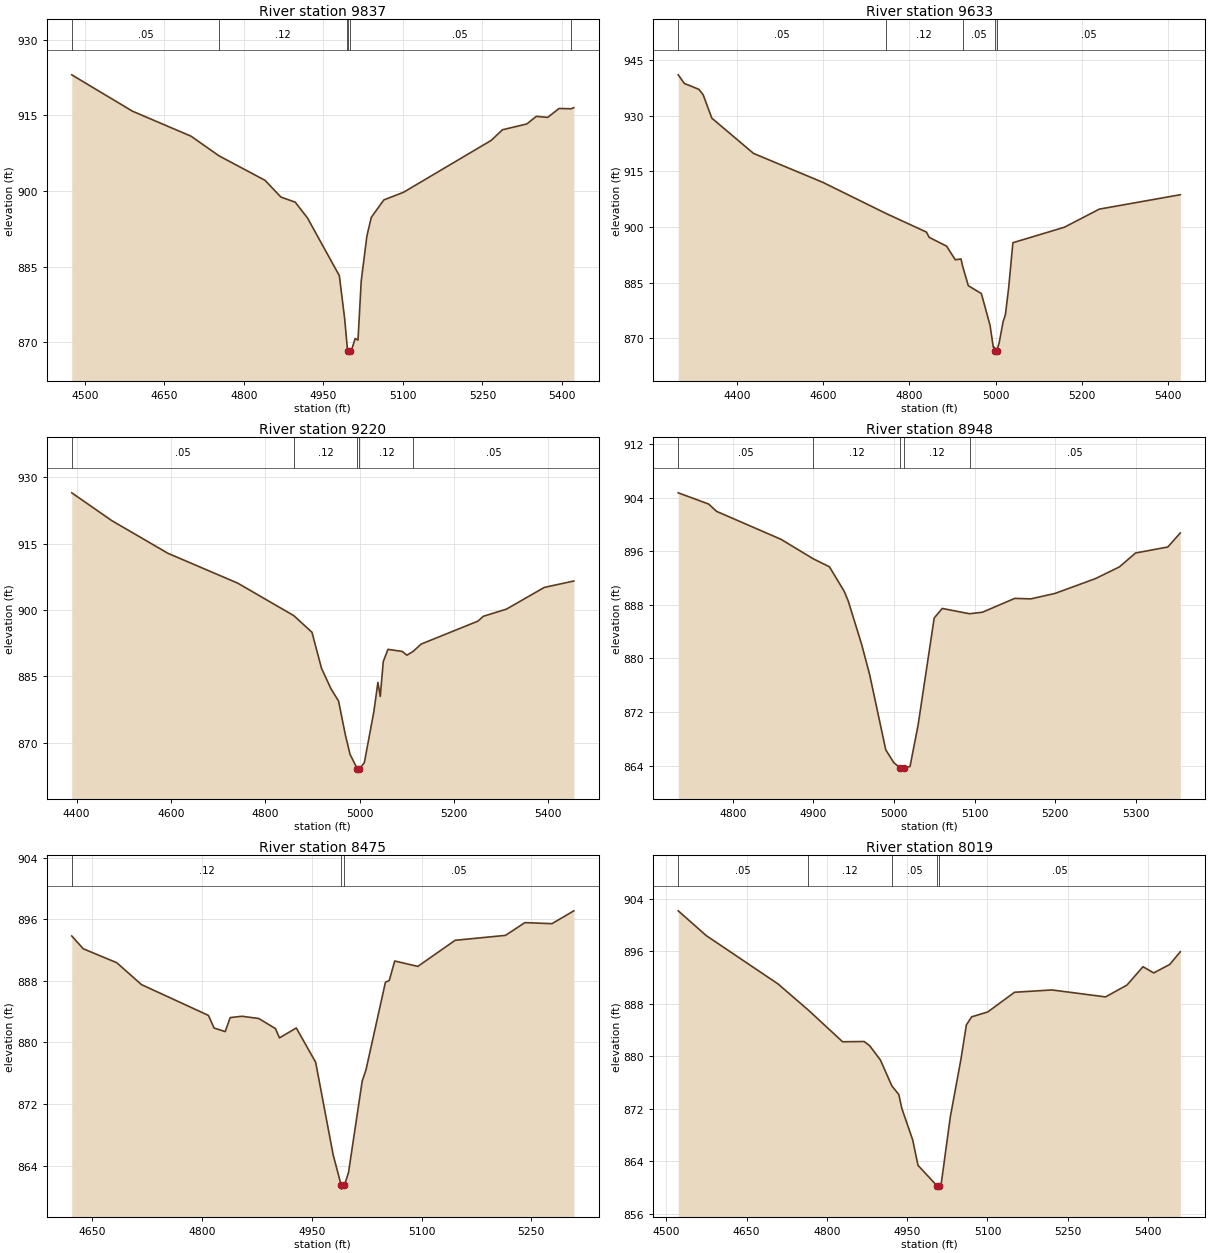
Type RM Length L Ch R = 1,9837,204,204,204
BEGIN DESCRIPTION:
MDW T 087 21.0
END DESCRIPTION:
XS GIS Cut Line= 3
      2268103.25      7150135.90      2267579.00      7150110.00
      2267182.70      7150256.50
#Sta/Elev= 30
  4475.1  923.05  4589.5  915.85  4700.3  910.88  4753.0  906.99  4839.8  902.14
  4869.8  898.82  4896.8  897.81  4919.9  894.68  4980.0  883.24  4990.0  874.77
  4994.8  869.20  4995.5  868.39  4995.7  867.89  4999.5  868.39  5002.7  868.39
  5009.9  870.79  5015.2  870.48  5021.3  882.20  5032.0  891.10  5040.3  894.80
  5064.0  898.26  5101.1  899.77  5266.5  910.05  5287.8  912.16  5333.7  913.31
  5351.8  914.82  5373.1  914.61  5394.6  916.38  5417.0  916.32  5422.5  916.54
#Mann=6,-1,0
  4475.1    0.05       0  4753.0    0.12       0  4994.8    0.05       0
  4995.5   0.033       0  4999.5    0.05       0  5417.0    0.12       0
Bank Sta=4995.5,4999.5
Exp/Cntr=0.3,0.1

Type RM Length L Ch R = 1,9633,413,413,413
BEGIN DESCRIPTION:
MDW T 087 20.0
END DESCRIPTION:
XS GIS Cut Line= 3
      2268306.33      7149812.99      2267578.91      7149904.96
      2267189.20      7150089.02
#Sta/Elev= 30
  4263.8  941.02  4278.0  938.69  4311.5  937.12  4321.6  935.65  4341.7  929.34
  4438.4  919.83  4598.7  912.05  4745.8  903.63  4839.3  898.62  4845.7  897.20
  4886.0  894.83  4906.2  891.16  4919.5  891.37  4923.1  889.49  4936.4  884.17
  4966.7  882.04  4986.8  873.50  4994.4  867.58  4997.0  867.58  4997.8  866.48
  4998.0  865.98  5001.8  866.48  5008.0  868.75  5017.0  874.42  5022.5  876.36
  5030.1  883.72  5039.8  895.75  5159.1  899.92  5240.2  904.81  5428.0  908.69
#Mann=5,-1,0
  4263.8    0.05       0  4745.8    0.12       0  4923.1    0.05       0
  4997.8   0.033       0  5001.8    0.05       0
Bank Sta=4997.8,5001.8
Exp/Cntr=0.3,0.1

Type RM Length L Ch R = 1,9220,272,272,272
BEGIN DESCRIPTION:
MDW T 087 19.0
END DESCRIPTION:
XS GIS Cut Line= 3
      2268283.44      7149623.74      2267679.06      7149538.95
      2267226.62      7149496.79
#Sta/Elev= 30
  4389.7  926.49  4475.0  920.18  4593.8  912.81  4741.5  906.08  4860.5  898.73
  4899.1  894.97  4919.3  886.82  4939.5  882.18  4955.5  879.41  4969.8  871.82
  4979.9  867.35  4995.4  864.08  4995.7  863.58  4999.3  863.58  4999.7  864.08
  5010.1  865.48  5030.2  876.96  5038.9  883.63  5043.9  880.47  5050.3  888.37
  5060.3  891.11  5090.5  890.64  5100.5  889.78  5114.2  890.70  5130.6  892.30
  5251.1  897.49  5262.2  898.57  5311.4  900.20  5391.8  905.11  5454.4  906.56
#Mann=5,-1,0
  4389.7    0.05       0  4860.5    0.12       0  4995.4    0.07       0
  4999.7    0.12       0  5114.2    0.05       0
Bank Sta=4995.4,4999.7
Exp/Cntr=0.3,0.1

Type RM Length L Ch R = 1,8948,473,473,473
BEGIN DESCRIPTION:
Mapping XS 443e9a98
END DESCRIPTION:
XS GIS Cut Line= 2
      2268036.65      7149300.43      2267413.47      7149284.25
#Sta/Elev= 30
  4732.1  904.71  4769.8  903.04  4779.8  901.94  4859.8  897.77  4900.0  894.85
  4919.8  893.68  4938.1  890.04  4943.1  888.60  4959.8  882.11  4969.8  877.57
  4989.8  866.36  4999.8  864.45  5007.7  863.69  5008.0  863.19  5011.6  863.19
  5012.0  863.69  5019.9  863.88  5029.9  870.04  5049.9  886.03  5059.9  887.46
  5093.8  886.67  5109.9  886.90  5149.9  888.96  5169.9  888.89  5199.9  889.70
  5249.9  891.90  5279.9  893.66  5299.9  895.73  5340.0  896.63  5355.5  898.73
#Mann=5,-1,0
  4732.1    0.05       0  4900.0    0.12       0  5007.7    0.07       0
  5012.0    0.12       0  5093.8    0.05       0
Bank Sta=5007.7,5012
Exp/Cntr=0.3,0.1

Type RM Length L Ch R = 1,8475,456,456,456
BEGIN DESCRIPTION:
Mapping XS 5ec2abd0
END DESCRIPTION:
XS GIS Cut Line= 3
      2267995.45      7149042.91      2267721.78      7148915.70
      2267356.36      7148795.41
#Sta/Elev= 30
  4621.7  893.83  4637.4  892.17  4683.2  890.36  4717.1  887.51  4808.6  883.51
  4816.3  881.87  4831.5  881.41  4838.3  883.23  4854.4  883.40  4877.3  883.11
  4900.2  881.80  4905.7  880.59  4928.7  881.88  4955.2  877.42  4979.1  865.40
  4990.1  861.44  4990.5  860.94  4994.5  861.44  5000.1  863.10  5018.8  874.97
  5024.0  876.44  5050.6  887.83  5055.8  888.04  5063.3  890.58  5094.9  889.88
  5145.9  893.27  5214.7  893.91  5241.3  895.57  5278.3  895.43  5308.2  897.10
#Mann=3,-1,0
  4621.7    0.12       0  4990.1    0.05       0  4994.5    0.05       0
Bank Sta=4990.1,4994.5
Exp/Cntr=0.3,0.1

Type RM Length L Ch R = 1,8019,509,509,509
BEGIN DESCRIPTION:
MDW T 087 17.0
END DESCRIPTION:
XS GIS Cut Line= 3
      2268314.22      7148671.06      2267828.94      7148616.39
      2267379.29      7148616.37
#Sta/Elev= 30
  4522.3  902.14  4574.6  898.37  4708.7  891.01  4765.3  887.03  4829.4  882.20
  4869.7  882.24  4879.8  881.61  4899.9  879.44  4921.3  875.50  4934.4  874.16
  4940.1  872.04  4960.3  867.26  4970.3  863.38  5005.8  860.26  5006.3  859.76
  5010.3  860.26  5013.1  860.26  5030.6  870.75  5050.6  879.60  5060.6  884.77
  5070.6  886.00  5100.6  886.74  5150.6  889.74  5220.6  890.09  5320.6  889.03
  5360.6  890.83  5390.6  893.63  5410.6  892.68  5440.6  893.98  5460.3  895.91
#Mann=5,-1,0
  4522.3    0.05       0  4765.3    0.12       0  4921.3    0.05       0
  5005.8    0.07       0  5010.3    0.05       0
Bank Sta=5005.8,5010.3
Exp/Cntr=0.3,0.1

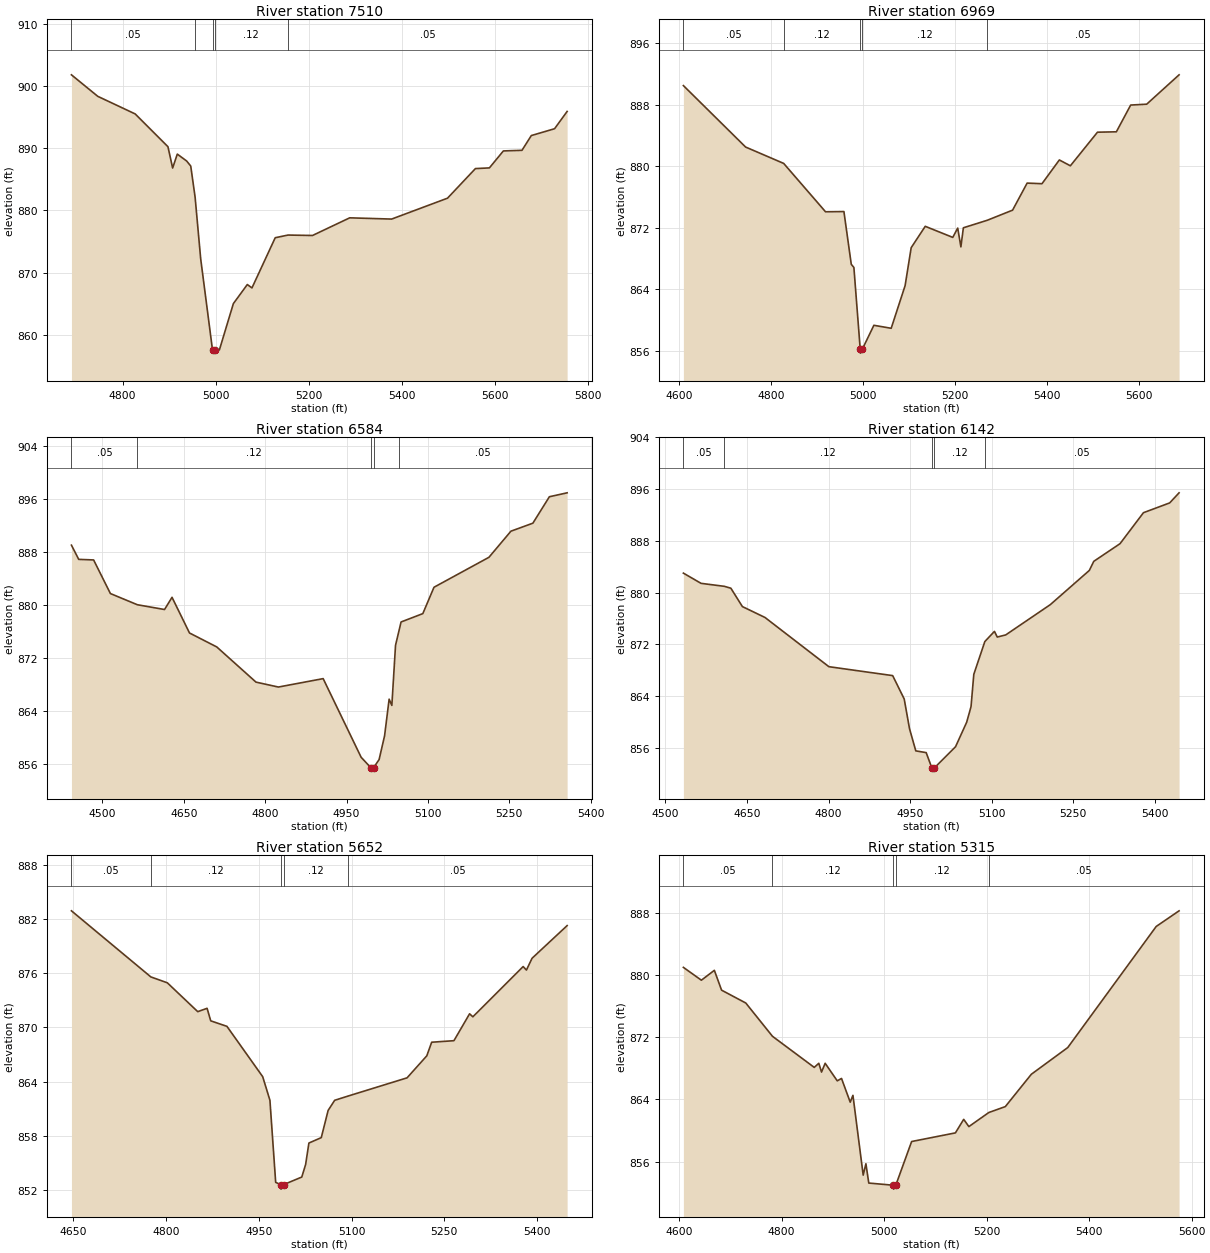
Type RM Length L Ch R = 1,7510,541,541,541
BEGIN DESCRIPTION:
MDW T 087 16.0
END DESCRIPTION:
XS GIS Cut Line= 3
      2268435.28      7148292.15      2268129.00      7148260.00
      2267372.04      7148286.88
#Sta/Elev= 30
  4690.0  901.82  4746.6  898.36  4827.0  895.53  4897.4  890.26  4907.5  886.83
  4917.5  889.07  4937.6  887.96  4946.4  887.15  4955.8  882.14  4967.8  872.22
  4993.2  857.56  4993.7  857.06  4997.7  857.56  5008.0  857.58  5038.0  865.02
  5068.0  868.09  5078.0  867.55  5128.0  875.62  5155.6  876.05  5208.1  875.98
  5288.1  878.82  5378.2  878.62  5498.3  881.98  5558.3  886.74  5588.3  886.85
  5618.4  889.58  5658.4  889.68  5678.4  892.05  5728.4  893.15  5755.4  895.93
#Mann=5,-1,0
  4690.0    0.05       0  4955.8    0.12       0  4993.2    0.07       0
  4997.7    0.12       0  5155.6    0.05       0
Bank Sta=4993.2,4997.7
Exp/Cntr=0.3,0.1

Type RM Length L Ch R = 1,6969,385,385,385
BEGIN DESCRIPTION:
Mapping XS ea167274
END DESCRIPTION:
XS GIS Cut Line= 4
      2268288.08      7147843.10      2267992.27      7147749.44
      2267890.20      7147932.90      2267372.56      7148143.07
#Sta/Elev= 30
  4609.0  890.46  4744.4  882.47  4827.3  880.34  4918.4  874.05  4958.4  874.08
  4974.4  867.22  4980.1  866.81  4993.9  856.17  4994.3  855.67  4998.4  856.17
  5023.6  859.29  5061.3  858.90  5091.6  864.45  5104.8  869.38  5135.4  872.16
  5195.3  870.72  5206.1  871.93  5213.0  869.49  5218.4  871.97  5270.1  872.94
  5325.5  874.26  5357.2  877.78  5389.5  877.70  5427.3  880.79  5451.3  880.03
  5510.3  884.40  5551.4  884.45  5582.6  887.93  5617.4  888.04  5687.9  891.86
#Mann=5,-1,0
  4609.0    0.05       0  4827.3    0.12       0  4993.9    0.07       0
  4998.4    0.12       0  5270.1    0.05       0
Bank Sta=4993.9,4998.4
Exp/Cntr=0.3,0.1

Type RM Length L Ch R = 1,6584,442,442,442
BEGIN DESCRIPTION:
MDW T 087 14.0
END DESCRIPTION:
XS GIS Cut Line= 3
      2268268.61      7147747.88      2267728.84      7147610.00
      2267376.69      7147553.87
#Sta/Elev= 30
  4442.9  889.02  4456.3  886.88  4483.8  886.79  4514.7  881.72  4564.4  880.03
  4614.5  879.31  4628.3  881.15  4660.5  875.77  4710.8  873.66  4783.1  868.35
  4824.4  867.61  4906.9  868.88  4976.9  857.01  4995.0  855.42  4995.5  854.92
  4999.7  855.42  5010.0  856.66  5020.1  860.25  5028.5  865.78  5033.5  864.84
  5040.3  873.91  5046.5  876.05  5050.5  877.43  5090.6  878.69  5111.2  882.67
  5212.5  887.19  5253.0  891.13  5293.5  892.34  5323.9  896.33  5356.6  896.92
#Mann=5,-1,0
  4442.9    0.05       0  4564.4    0.12       0  4995.0    0.07       0
  4999.7    0.12       0  5046.5    0.05       0
Bank Sta=4995,4999.7
Exp/Cntr=0.3,0.1

Type RM Length L Ch R = 1,6142,490,490,490
BEGIN DESCRIPTION:
MDW T 087 13.0
END DESCRIPTION:
XS GIS Cut Line= 3
      2268441.13      7147487.26      2268003.46      7147329.78
      2267568.08      7147230.95
#Sta/Elev= 30
  4533.1  883.02  4565.6  881.44  4608.4  880.98  4620.4  880.69  4641.6  877.85
  4683.1  876.17  4800.7  868.56  4918.0  867.18  4939.2  863.57  4948.9  859.00
  4960.5  855.55  4979.6  855.28  4990.0  852.92  4990.5  852.42  4994.7  852.92
  5033.6  856.19  5054.1  859.98  5062.1  862.39  5067.2  867.38  5087.5  872.45
  5105.2  874.02  5110.3  873.14  5125.9  873.47  5207.9  878.15  5279.7  883.44
  5287.8  884.84  5336.1  887.57  5379.2  892.36  5427.4  893.87  5444.7  895.43
#Mann=5,-1,0
  4533.1    0.05       0  4608.4    0.12       0  4990.0    0.07       0
  4994.7    0.12       0  5087.5    0.05       0
Bank Sta=4990,4994.7
Exp/Cntr=0.3,0.1

Type RM Length L Ch R = 1,5652,337,337,337
BEGIN DESCRIPTION:
MDW T 087 12.0
END DESCRIPTION:
XS GIS Cut Line= 3
      2268573.42      7147061.71      2268237.44      7146954.07
      2267815.65      7146801.31
#Sta/Elev= 30
  4647.2  882.93  4775.6  875.60  4802.2  874.95  4851.4  871.75  4866.5  872.12
  4872.4  870.73  4898.6  870.12  4956.4  864.54  4968.1  861.92  4977.4  852.82
  4985.5  852.57  4986.0  852.07  4990.2  852.57  5019.6  853.41  5025.8  854.80
  5031.1  857.18  5051.1  857.78  5062.2  860.80  5072.8  861.92  5094.9  862.40
  5189.8  864.41  5221.7  866.85  5229.6  868.36  5265.6  868.53  5290.9  871.51
  5296.2  871.18  5377.5  876.75  5382.8  876.36  5391.9  877.67  5448.6  881.29
#Mann=5,-1,0
  4647.2    0.05       0  4775.6    0.12       0  4985.5    0.07       0
  4990.2    0.12       0  5094.9    0.05       0
Bank Sta=4985.5,4990.2
Exp/Cntr=0.3,0.1

Type RM Length L Ch R = 1,5315,554,554,554
BEGIN DESCRIPTION:
MDW T 087 11.0
END DESCRIPTION:
XS GIS Cut Line= 3
      2268669.07      7146786.21      2268279.16      7146644.94
      2267735.12      7146549.26
#Sta/Elev= 30
  4608.4  880.96  4643.5  879.31  4668.8  880.58  4682.9  878.03  4730.1  876.38
  4782.2  872.10  4863.7  868.10  4872.6  868.63  4877.9  867.50  4885.0  868.63
  4908.6  866.37  4916.9  866.68  4933.9  863.63  4939.2  864.51  4959.2  854.25
  4964.5  855.71  4970.1  853.23  5018.0  852.95  5018.6  852.45  5022.8  852.95
  5053.7  858.57  5139.1  859.68  5155.3  861.42  5165.4  860.49  5204.3  862.30
  5236.5  863.06  5287.3  867.22  5358.3  870.65  5530.9  886.22  5575.5  888.23
#Mann=5,-1,0
  4608.4    0.05       0  4782.2    0.12       0  5018.0    0.07       0
  5022.8    0.12       0  5204.3    0.05       0
Bank Sta=5018,5022.8
Exp/Cntr=0.3,0.1

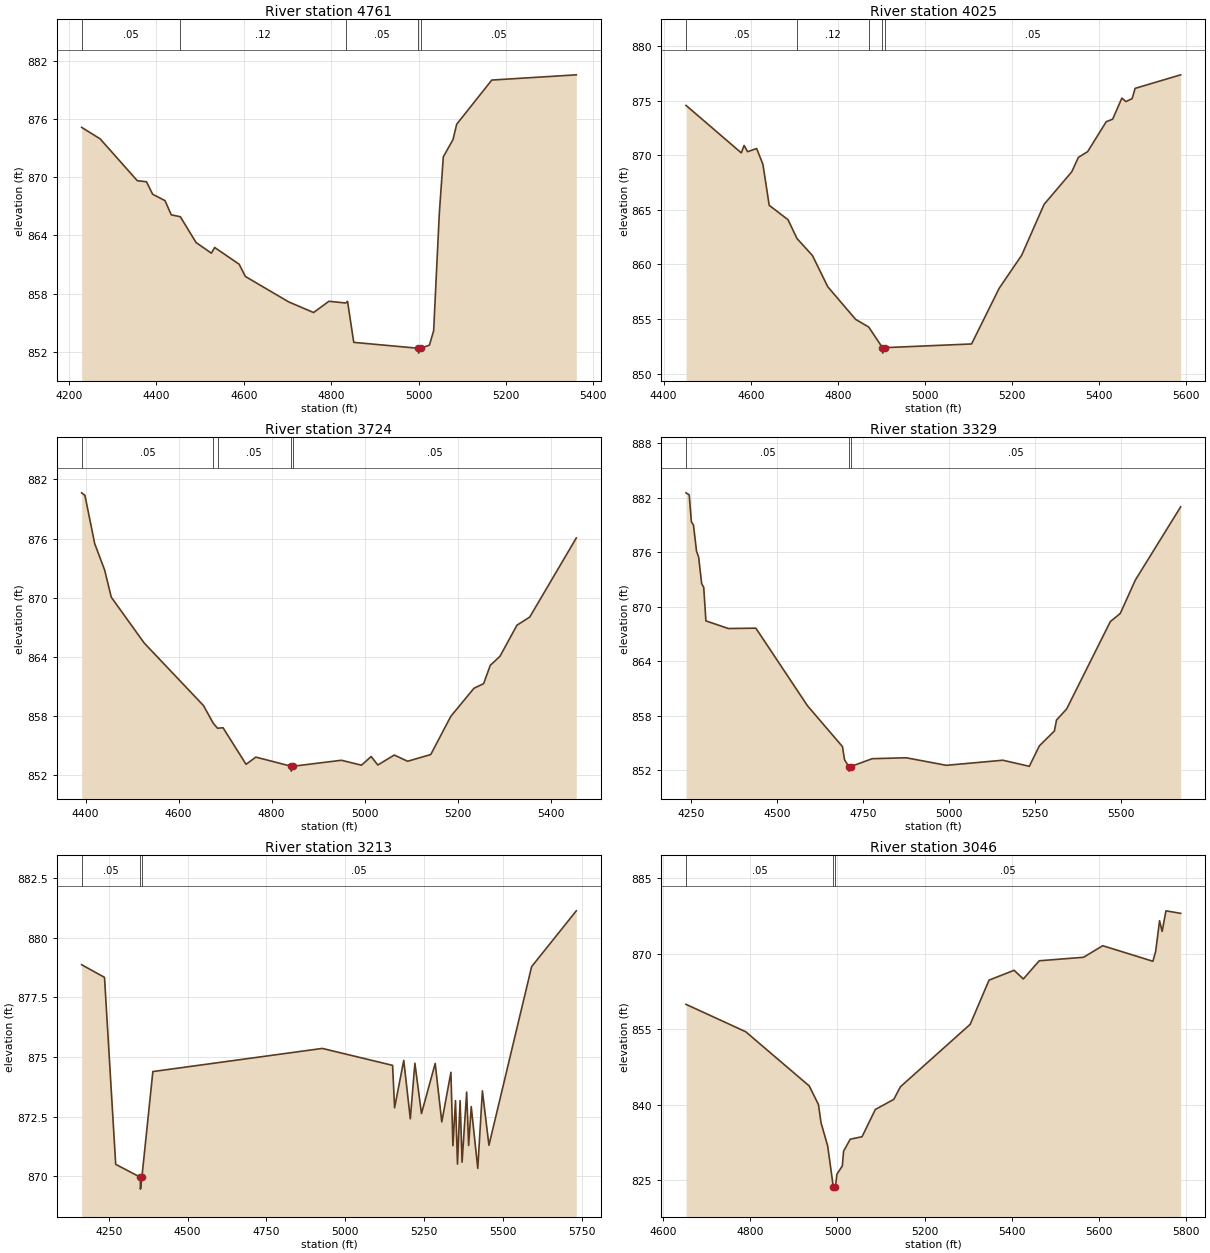
Type RM Length L Ch R = 1,4761,736,736,736
BEGIN DESCRIPTION:
MDW T 087 10.0
END DESCRIPTION:
XS GIS Cut Line= 3
      2268692.35      7146706.25      2268210.86      7146178.26
      2267834.64      7145997.87
#Sta/Elev= 30
  4229.2  875.14  4271.4  873.96  4356.5  869.64  4377.5  869.53  4391.7  868.24
  4420.0  867.58  4434.2  866.12  4455.0  865.92  4491.0  863.26  4526.1  862.16
  4533.5  862.75  4589.6  861.02  4603.8  859.76  4703.1  857.13  4759.9  856.04
  4795.0  857.20  4833.2  857.02  4837.6  857.19  4851.8  852.96  4999.8  852.35
  5000.4  851.85  5004.6  852.35  5024.9  852.67  5034.6  854.16  5047.5  866.22
  5056.7  872.10  5078.9  873.88  5087.3  875.46  5167.6  880.02  5361.0  880.56
#Mann=5,-1,0
  4229.2    0.05       0  4455.0    0.12       0  4833.2    0.05       0
  4999.8   0.033       0  5004.6    0.05       0
Bank Sta=4999.8,5004.6
Exp/Cntr=0.3,0.1

Type RM Length L Ch R = 1,4025,301,301,301
BEGIN DESCRIPTION:
MDW T 087 9.0
END DESCRIPTION:
XS GIS Cut Line= 3
      2268973.60      7146393.75      2268605.75      7145933.41
      2268144.98      7145639.29
#Sta/Elev= 30
  4451.4  874.57  4578.4  870.22  4584.8  870.90  4592.8  870.33  4613.6  870.62
  4628.0  869.17  4642.4  865.42  4685.6  864.10  4706.2  862.38  4741.7  860.82
  4776.9  857.96  4840.9  854.97  4870.9  854.27  4902.5  852.38  4903.1  851.88
  4907.5  852.38  5107.1  852.72  5170.5  857.82  5222.1  860.84  5273.7  865.51
  5337.2  868.49  5352.4  869.81  5373.6  870.33  5416.4  873.08  5431.1  873.31
  5452.3  875.24  5461.6  874.92  5475.8  875.19  5482.7  876.13  5587.3  877.37
#Mann=5,-1,0
  4451.4    0.05       0  4706.2    0.12       0  4870.9    0.05       0
  4902.5   0.033       0  4907.5    0.05       0
Bank Sta=4902.5,4907.5
Exp/Cntr=0.3,0.1

Type RM Length L Ch R = 1,3724,395,395,395
BEGIN DESCRIPTION:
MDW T 087 8.0
END DESCRIPTION:
XS GIS Cut Line= 3
      2269178.99      7146109.99      2268769.12      7145720.05
      2268379.03      7145410.03
#Sta/Elev= 30
  4391.4  880.63  4398.5  880.37  4419.5  875.48  4440.9  872.81  4455.1  870.06
  4525.9  865.42  4653.3  859.09  4674.4  857.30  4683.7  856.78  4695.4  856.84
  4745.1  853.13  4766.1  853.86  4841.7  852.94  4842.3  852.44  4846.7  852.94
  4950.2  853.54  4993.3  853.04  5014.1  853.92  5028.5  853.06  5063.8  854.07
  5092.6  853.44  5142.3  854.12  5185.5  857.99  5235.2  860.83  5256.0  861.30
  5270.4  863.16  5291.2  864.07  5327.7  867.22  5355.3  868.05  5455.4  876.06
#Mann=5,-1,0
  4391.4    0.05       0  4674.4    0.12       0  4683.7    0.05       0
  4841.7   0.033       0  4846.7    0.05       0
Bank Sta=4841.7,4846.7
Exp/Cntr=0.3,0.1

Type RM Length L Ch R = 1,3329,116,116,116
BEGIN DESCRIPTION:
MDW T 087 7.0
END DESCRIPTION:
XS GIS Cut Line= 3
      2269362.88      7145997.80      2268931.50      7145366.03
      2268527.38      7144826.00
#Sta/Elev= 30
  4235.0  882.56  4244.4  882.33  4250.6  879.37  4256.7  879.01  4265.6  876.12
  4271.6  875.51  4280.5  872.57  4286.5  872.16  4292.9  868.46  4358.3  867.62
  4438.2  867.66  4588.6  859.11  4690.3  854.62  4696.3  853.17  4708.7  852.42
  4709.3  851.92  4713.8  852.42  4777.0  853.29  4875.8  853.39  4992.4  852.56
  5157.0  853.12  5234.0  852.45  5263.2  854.70  5307.0  856.34  5313.2  857.55
  5342.4  858.75  5469.7  868.38  5498.7  869.28  5542.5  872.95  5674.5  881.02
#Mann=3,-1,0
  4235.0    0.05       0  4708.7   0.033       0  4713.8    0.05       0
Bank Sta=4708.7,4713.8
Exp/Cntr=0.3,0.1

Type RM Length L Ch R = 1,3213,167,167,167
BEGIN DESCRIPTION:
MDW T 087 6.8
END DESCRIPTION:
XS GIS Cut Line= 4
      2269561.87      7145886.32      2269361.18      7145771.14
      2269008.98      7145279.95      2268563.72      7144697.44
#Sta/Elev= 30
  4164.2  878.87  4236.7  878.34  4272.2  870.50  4350.2  869.96  4350.8  869.46
  4355.3  869.96  4390.1  874.39  4927.5  875.36  5150.5  874.65  5156.8  872.87
  5185.9  874.86  5206.7  872.41  5221.2  874.74  5242.1  872.63  5285.6  874.73
  5306.5  872.28  5335.5  874.36  5341.8  871.28  5350.0  873.17  5356.3  870.51
  5364.6  873.17  5370.9  870.59  5385.4  873.53  5391.7  871.29  5399.9  872.92
  5420.7  870.33  5435.3  873.58  5456.1  871.30  5591.5  878.79  5733.2  881.13
#Mann=3,-1,0
  4164.2    0.05       0  4350.2   0.033       0  4355.3    0.05       0
Bank Sta=4350.2,4355.3
Exp/Cntr=0.3,0.1

Type RM Length L Ch R = 1,3046,213,213,213
BEGIN DESCRIPTION:
MDW T 087 6.5
END DESCRIPTION:
XS GIS Cut Line= 3
      2269316.39      7145462.07      2269125.05      7145158.36
      2268709.71      7144501.40
#Sta/Elev= 30
  4652.2  859.99  4789.3  854.55  4935.2  843.78  4956.4  840.08  4962.3  836.47
  4977.6  831.85  4990.4  823.78  4991.0  823.28  4995.5  823.78  4998.8  826.24
  5011.2  827.89  5014.1  830.82  5029.4  833.20  5056.5  833.69  5087.0  839.10
  5129.4  841.11  5144.7  843.62  5305.0  856.03  5348.2  864.80  5405.8  866.76
  5427.0  865.03  5463.5  868.65  5565.3  869.34  5609.3  871.64  5724.6  868.55
  5730.9  870.50  5739.9  876.60  5745.8  874.48  5754.6  878.57  5788.4  878.07
#Mann=3,-1,0
  4652.2    0.05       0  4990.4   0.033       0  4995.5    0.05       0
Bank Sta=4990.4,4995.5
Exp/Cntr=0.3,0.1