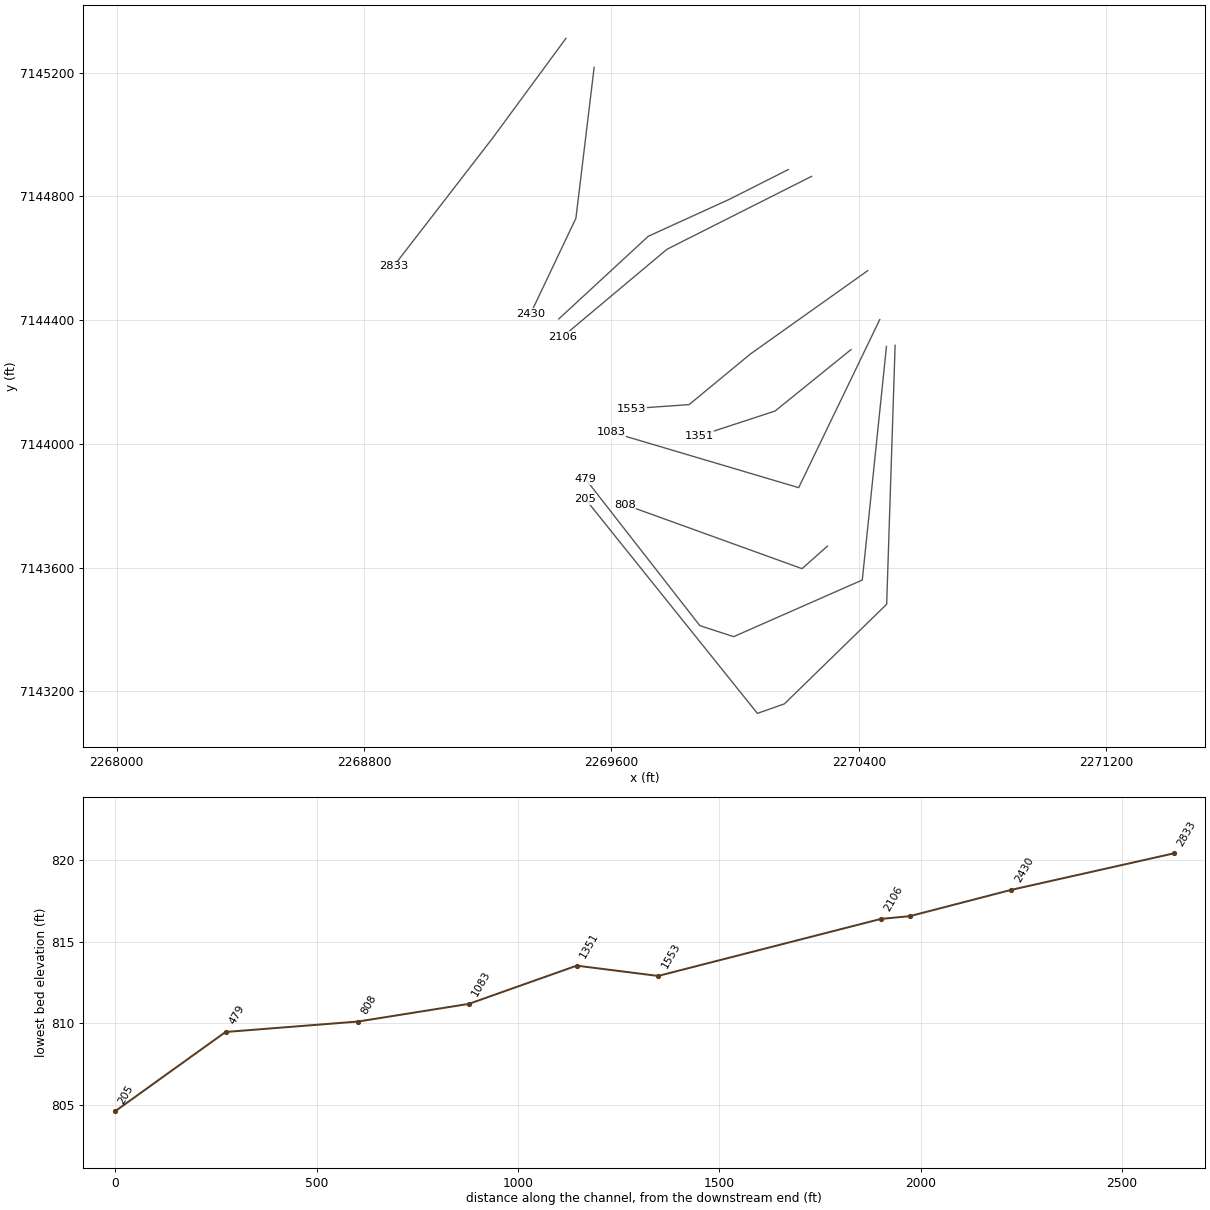
HEC-RAS study MDW T 087.prj: MDW T 087 Base Level Engineering

--- MDW T 087.g01 (geometry) --- (continued)

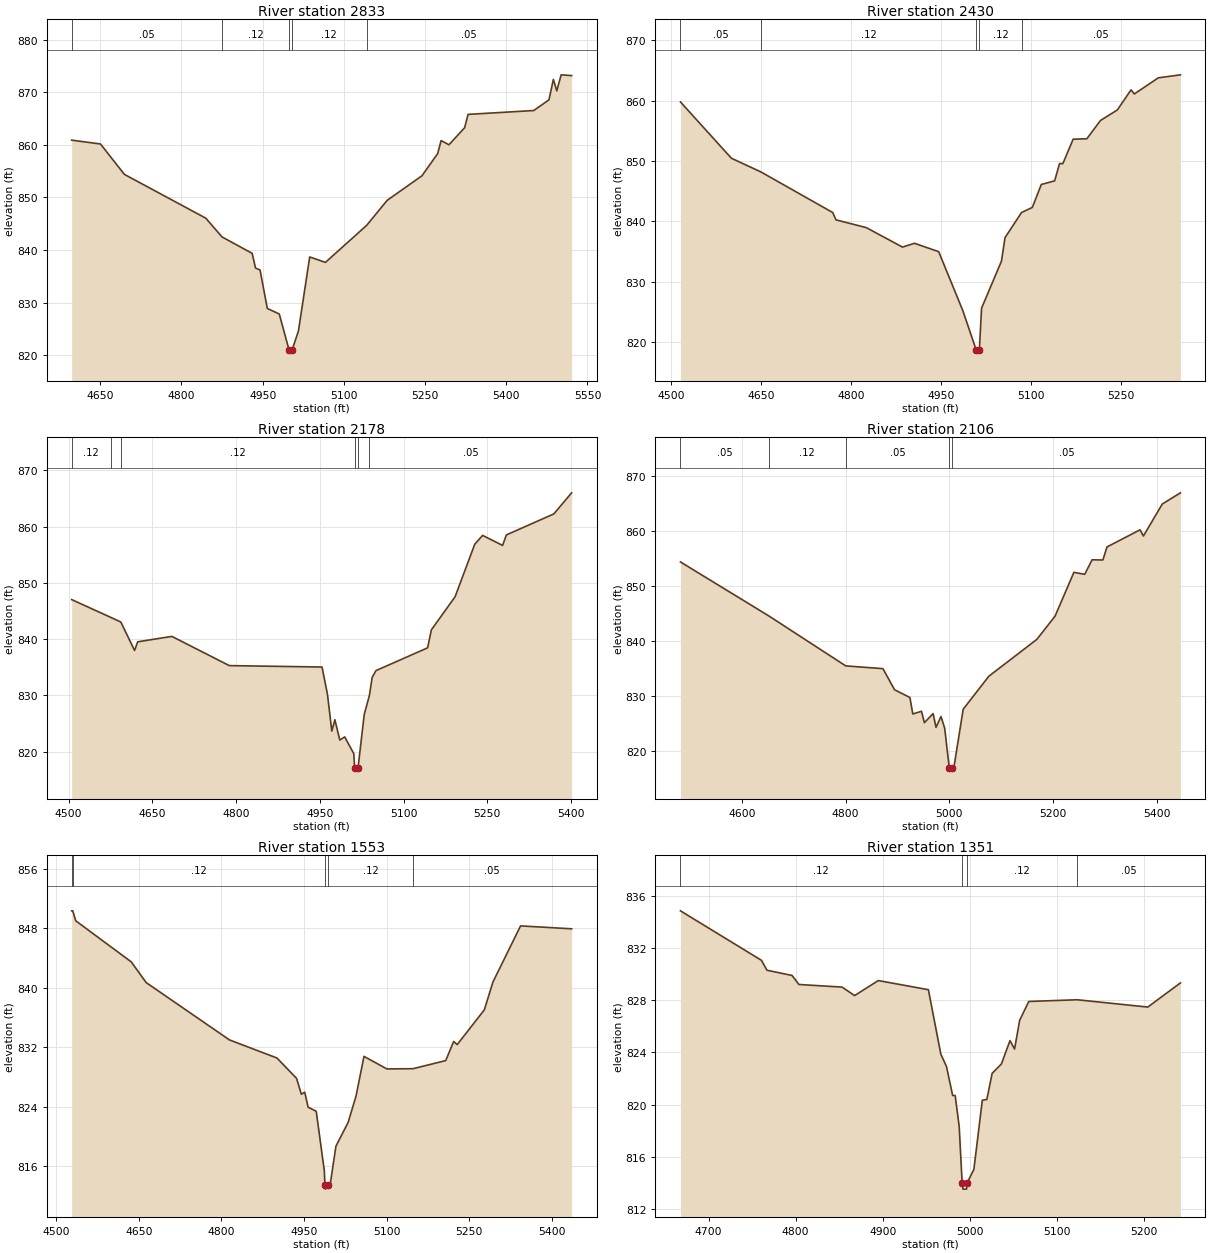
Type RM Length L Ch R = 1,2833,403,403,403
BEGIN DESCRIPTION:
MDW T 087 6.0
END DESCRIPTION:
XS GIS Cut Line= 3
      2269453.26      7145311.17      2269215.99      7144988.45
      2268896.29      7144574.61
#Sta/Elev= 30
  4597.2  860.89  4650.5  860.16  4694.5  854.39  4844.9  846.06  4875.1  842.48
  4930.6  839.37  4936.8  836.58  4945.2  836.20  4958.6  828.89  4980.7  827.84
  4999.0  820.90  4999.7  820.40  5004.1  820.90  5016.1  824.62  5036.9  838.69
  5065.9  837.65  5142.1  844.69  5180.0  849.45  5244.3  854.12  5273.3  858.34
  5279.6  860.81  5294.1  860.01  5323.1  863.26  5329.4  865.79  5450.7  866.52
  5478.8  868.55  5487.0  872.44  5493.3  870.26  5501.3  873.31  5520.7  873.16
#Mann=5,-1,0
  4597.2    0.05       0  4875.1    0.12       0  4999.0    0.07       0
  5004.1    0.12       0  5142.1    0.05       0
Bank Sta=4999,5004.1
Exp/Cntr=0.3,0.1

Type RM Length L Ch R = 1,2430,252,252,252
BEGIN DESCRIPTION:
MDW T 087 5.0
END DESCRIPTION:
XS GIS Cut Line= 3
      2269544.42      7145217.42      2269485.44      7144729.43
      2269338.69      7144420.56
#Sta/Elev= 30
  4515.0  859.77  4599.9  850.45  4649.5  848.16  4768.9  841.45  4774.3  840.24
  4824.7  838.96  4885.1  835.73  4905.2  836.36  4945.5  834.97  4985.8  825.20
  5008.1  818.67  5008.8  818.17  5013.3  818.67  5017.0  825.61  5050.2  833.41
  5056.1  837.30  5083.7  841.46  5101.6  842.30  5116.6  846.10  5138.8  846.70
  5147.0  849.56  5152.5  849.55  5169.7  853.60  5192.5  853.67  5215.2  856.69
  5243.4  858.45  5266.2  861.77  5271.7  861.09  5311.6  863.76  5348.5  864.26
#Mann=5,-1,0
  4515.0    0.05       0  4649.5    0.12       0  5008.1    0.07       0
  5013.3    0.12       0  5083.7    0.05       0
Bank Sta=5008.1,5013.3
Exp/Cntr=0.3,0.1

Type RM Length L Ch R = 1,2178,72,72,72
BEGIN DESCRIPTION:
MDW T 087 4.5
END DESCRIPTION:
XS GIS Cut Line= 4
      2270172.29      7144886.95      2269982.43      7144791.04
      2269719.48      7144671.15      2269430.11      7144403.91
#Sta/Elev= 30
  4505.4  847.03  4575.4  843.87  4593.5  843.04  4618.1  837.99  4623.7  839.53
  4684.9  840.49  4787.8  835.30  4953.9  835.05  4963.7  830.15  4971.4  823.67
  4976.9  825.69  4985.7  822.08  4994.5  822.64  5010.8  819.66  5012.4  817.06
  5013.4  816.56  5018.3  817.06  5029.5  826.63  5038.8  830.03  5043.7  833.21
  5050.5  834.41  5143.0  838.46  5149.8  841.66  5192.3  847.54  5227.4  856.85
  5241.6  858.43  5277.3  856.65  5284.1  858.51  5369.2  862.25  5401.0  865.99
#Mann=6,-1,0
  4505.4    0.12       0  4575.4    0.05       0  4593.5    0.12       0
  5012.4    0.07       0  5018.3    0.12       0  5038.8    0.05       0
Bank Sta=5012.4,5018.3
Exp/Cntr=0.3,0.1

Type RM Length L Ch R = 1,2106,553,553,553
BEGIN DESCRIPTION:
MDW T 087 4.0
END DESCRIPTION:
XS GIS Cut Line= 3
      2270247.47      7144864.90      2269780.03      7144629.23
      2269442.71      7144346.39
#Sta/Elev= 30
  4481.8  854.38  4652.4  844.56  4800.4  835.50  4872.1  835.00  4894.5  831.17
  4924.1  829.76  4929.7  826.77  4946.4  827.25  4952.0  825.19  4968.8  826.84
  4974.4  824.34  4984.0  826.30  4991.1  824.20  5000.1  816.89  5001.1  816.39
  5006.0  816.89  5008.6  816.89  5026.8  827.63  5076.3  833.63  5168.6  840.30
  5203.8  844.52  5240.2  852.49  5261.0  852.13  5275.3  854.77  5296.1  854.73
  5303.9  857.10  5367.7  860.21  5374.2  859.09  5410.6  864.90  5445.5  866.93
#Mann=5,-1,0
  4481.8    0.05       0  4652.4    0.12       0  4800.4    0.05       0
  5000.1   0.033       0  5006.0    0.05       0
Bank Sta=5000.1,5006
Exp/Cntr=0.3,0.1

Type RM Length L Ch R = 1,1553,202,202,202
BEGIN DESCRIPTION:
MDW T 087 3.0
END DESCRIPTION:
XS GIS Cut Line= 4
      2270428.99      7144559.99      2270049.56      7144290.40
      2269851.45      7144126.84      2269666.56      7144113.82
#Sta/Elev= 30
  4528.0  850.36  4530.0  850.36  4535.4  849.02  4636.2  843.49  4663.3  840.70
  4814.6  832.98  4900.7  830.55  4936.3  827.81  4945.0  825.67  4951.1  825.95
  4957.3  823.93  4972.0  823.38  4986.8  815.31  4987.8  813.40  4988.7  812.90
  4993.7  813.40  4997.1  813.40  5007.8  818.68  5030.0  821.89  5044.3  825.43
  5058.7  830.77  5100.3  829.08  5147.6  829.11  5207.1  830.20  5221.5  832.77
  5228.0  832.36  5277.2  837.03  5292.9  840.79  5343.0  848.33  5435.7  847.94
#Mann=5,-1,0
  4528.0    0.05       0  4530.0    0.12       0  4987.8    0.07       0
  4993.7    0.12       0  5147.6    0.05       0
Bank Sta=4987.8,4993.7
Exp/Cntr=0.3,0.1

Type RM Length L Ch R = 1,1351,268,268,268
BEGIN DESCRIPTION:
Mapping XS 403d64a8
END DESCRIPTION:
XS GIS Cut Line= 3
      2270374.93      7144304.72      2270129.39      7144106.07
      2269883.40      7144025.44
#Sta/Elev= 30
  4667.6  834.84  4760.7  831.05  4767.1  830.29  4795.9  829.89  4803.8  829.20
  4853.4  829.00  4867.8  828.35  4895.0  829.50  4952.6  828.80  4966.9  823.87
  4973.4  822.92  4980.5  820.70  4983.4  820.70  4988.0  818.34  4991.4  814.03
  4992.4  813.53  4996.4  813.53  4997.3  814.03  5004.9  815.04  5014.6  820.34
  5019.8  820.39  5025.9  822.40  5036.5  823.11  5046.4  824.90  5051.7  824.26
  5057.5  826.45  5068.0  827.90  5123.6  828.03  5204.8  827.47  5242.3  829.32
#Mann=4,-1,0
  4667.6    0.12       0  4991.4    0.07       0  4997.3    0.12       0
  5123.6    0.05       0
Bank Sta=4991.4,4997.3
Exp/Cntr=0.3,0.1

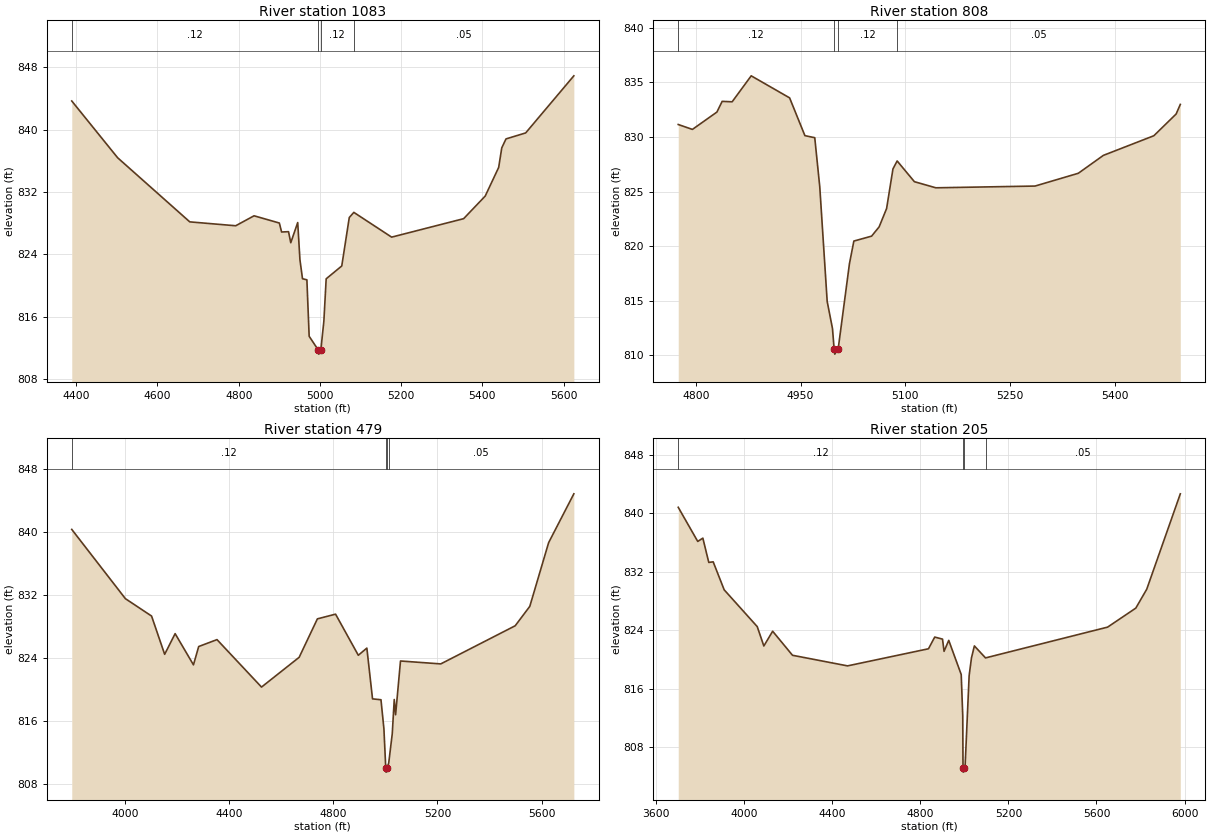
Type RM Length L Ch R = 1,1083,275,275,275
BEGIN DESCRIPTION:
MDW T 087 2.0
END DESCRIPTION:
XS GIS Cut Line= 3
      2270467.87      7144401.74      2270205.70      7143858.30
      2269598.81      7144038.31
#Sta/Elev= 30
  4388.9  843.69  4501.9  836.40  4679.5  828.17  4792.6  827.67  4837.8  828.95
  4900.1  828.02  4905.6  826.87  4922.7  826.91  4928.2  825.49  4945.3  828.08
  4950.8  823.30  4957.1  820.87  4967.9  820.73  4973.5  813.48  4996.3  811.69
  4997.3  811.19  5002.2  811.69  5009.7  815.42  5015.4  820.86  5053.8  822.51
  5072.3  828.73  5083.5  829.39  5176.6  826.21  5353.9  828.58  5407.0  831.48
  5440.2  835.16  5447.8  837.67  5458.2  838.82  5506.7  839.59  5625.3  846.92
#Mann=4,-1,0
  4388.9    0.12       0  4996.3    0.07       0  5002.2    0.12       0
  5083.5    0.05       0
Bank Sta=4996.3,5002.2
Exp/Cntr=0.3,0.1

Type RM Length L Ch R = 1,808,329,329,329
BEGIN DESCRIPTION:
Mapping XS 76550850
END DESCRIPTION:
XS GIS Cut Line= 3
      2270298.44      7143669.14      2270216.65      7143596.38
      2269643.39      7143803.52
#Sta/Elev= 30
  4774.9  831.15  4795.2  830.70  4830.3  832.29  4837.8  833.27  4852.1  833.23
  4879.4  835.61  4934.4  833.59  4956.3  830.13  4970.4  829.94  4977.6  825.43
  4988.2  814.94  4995.8  812.45  4998.1  810.61  4999.1  810.11  5004.0  810.61
  5020.1  818.40  5026.4  820.47  5051.8  820.92  5062.6  821.77  5073.3  823.45
  5082.4  827.08  5088.4  827.81  5113.1  825.91  5143.8  825.35  5285.9  825.51
  5347.8  826.68  5383.7  828.32  5456.0  830.12  5487.9  832.11  5493.9  832.99
#Mann=4,-1,0
  4774.9    0.12       0  4998.1    0.07       0  5004.0    0.12       0
  5088.4    0.05       0
Bank Sta=4998.1,5004
Exp/Cntr=0.3,0.1

Type RM Length L Ch R = 1,479,274,274,274
BEGIN DESCRIPTION:
MDW T 087 1.0
END DESCRIPTION:
XS GIS Cut Line= 5
      2270489.55      7144314.89      2270411.43      7143559.69
      2269995.58      7143376.58      2269886.25      7143412.12
      2269517.39      7143885.13
#Sta/Elev= 30
  3795.3  840.35  4001.3  831.54  4101.8  829.33  4152.1  824.46  4192.3  827.09
  4262.7  823.12  4282.8  825.45  4353.1  826.33  4524.1  820.29  4668.7  824.08
  4738.7  828.97  4808.5  829.57  4895.9  824.34  4928.7  825.25  4950.5  818.79
  4982.9  818.68  4994.2  814.99  5001.3  809.97  5002.3  809.47  5007.3  809.97
  5012.8  810.66  5026.3  814.37  5033.9  818.71  5039.1  816.77  5057.9  823.61
  5212.6  823.24  5498.4  828.09  5554.5  830.56  5626.9  838.67  5723.7  844.88
#Mann=4,-1,0
  3795.3    0.12       0  5001.3    0.07       0  5007.3    0.12       0
  5012.8    0.05       0
Bank Sta=5001.3,5007.3
Exp/Cntr=0.3,0.1

Type RM Length L Ch R = 1,205,0,0,0
BEGIN DESCRIPTION:
MDW T 087 0.5
END DESCRIPTION:
XS GIS Cut Line= 5
      2270517.59      7144318.58      2270490.25      7143481.35
      2270159.51      7143159.17      2270072.28      7143128.48
      2269516.30      7143821.18
#Sta/Elev= 30
  3700.6  840.84  3789.2  836.17  3812.4  836.62  3839.3  833.30  3859.3  833.38
  3909.3  829.55  4059.4  824.52  4089.4  821.87  4129.4  823.89  4219.5  820.60
  4469.6  819.15  4837.1  821.49  4865.4  823.09  4900.8  822.81  4907.8  821.14
  4929.1  822.64  4985.7  817.97  4992.7  812.30  4993.9  805.12  4994.9  804.62
  4999.9  805.12  5002.9  805.12  5021.7  817.81  5032.3  820.24  5045.5  821.88
  5096.0  820.24  5650.5  824.45  5778.6  827.05  5828.2  829.63  5980.7  842.68
#Mann=4,-1,0
  3700.6    0.12       0  4993.9    0.07       0  4999.9    0.12       0
  5096.0    0.05       0
Bank Sta=4993.9,4999.9
Exp/Cntr=0.3,0.1

Chan Stop Cuts=-1