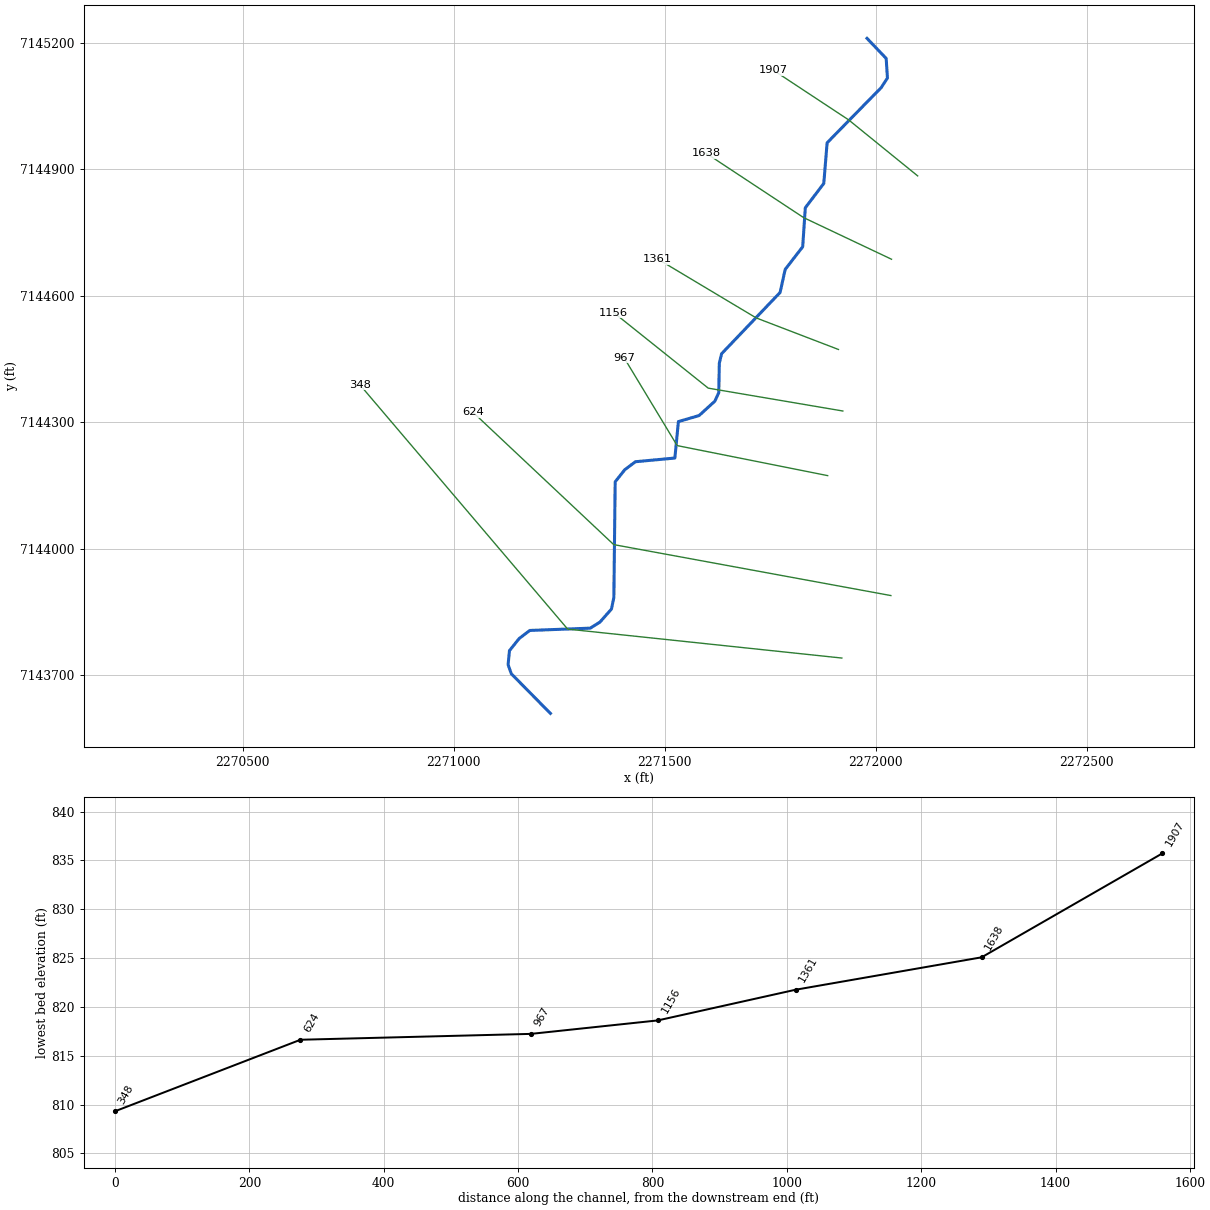
--- MDW T 088.prj (project) ---

Proj Title=MDW T 088 Base Level Engineering
Current Plan=p01
Default Exp/Contr=0.3,0.1
English Units
Geom File=g01
Flow File=f01
Plan File=p01
BEGIN DESCRIPTION:
MDW T 088
END DESCRIPTION:

--- MDW T 088.p01 (plan) ---

Plan Title=Multiple Run
Short Identifier=Multiple
Geom File=g01
Flow File=f01
Subcritical Flow
K Sum by GR= 0
Std Step Tol= 0.01
Critical Tol= 0.01
Num of Std Step Trials= 20
Max Error Tol= 0.3
Flow Tol Ratio= 0.001
Split Flow NTrial= 30
Split Flow Tol= 0.02
Split Flow Ratio= 0.02
Log Output Level= 0
Friction Slope Method= 1
Unsteady Friction Slope Method= 2
Unsteady Bridges Friction Slope Method= 1
Parabolic Critical Depth
Global Vel Dist=  1 , 1 , 1
Global Log Level= 0
CheckData=True
Encroach Param= -1, 0, 0, 0
BEGIN DESCRIPTION:
Multiple Run
END DESCRIPTION:

--- MDW T 088.f01 (steady flow) ---

Flow Title=Multiple
Number of Profiles=7
Profile Names=10-year,25-year,50-year,1pct_min,100-year,1pct_plu,500-year
River Rch & RM= MDW T 088,Reach-1,1907
     272     358     426     253     505    1008     709
Boundary for River Rch & Prof#=MDW T 088,Reach-1,1
Up Type=0
Dn Type=3
Dn Slope=0.005
Boundary for River Rch & Prof#=MDW T 088,Reach-1,2
Up Type=0
Dn Type=3
Dn Slope=0.005
Boundary for River Rch & Prof#=MDW T 088,Reach-1,3
Up Type=0
Dn Type=3
Dn Slope=0.005
Boundary for River Rch & Prof#=MDW T 088,Reach-1,4
Up Type=0
Dn Type=3
Dn Slope=0.005
Boundary for River Rch & Prof#=MDW T 088,Reach-1,5
Up Type=0
Dn Type=3
Dn Slope=0.005
Boundary for River Rch & Prof#=MDW T 088,Reach-1,6
Up Type=0
Dn Type=3
Dn Slope=0.005
Boundary for River Rch & Prof#=MDW T 088,Reach-1,7
Up Type=0
Dn Type=3
Dn Slope=0.005

--- MDW T 088.g01 (geometry) ---

Geom Title=Existing Conditions

River Reach=MDW T 088,Reach-1
Reach XY= 30
      2271979.00      7145210.00      2272024.43      7145162.35
      2272027.46      7145115.97      2272012.76      7145093.31
      2271884.52      7144962.43      2271876.64      7144865.98
      2271832.85      7144808.40      2271826.67      7144715.97
      2271785.14      7144662.17      2271773.17      7144607.70
      2271634.53      7144462.42      2271629.14      7144439.94
      2271627.88      7144370.34      2271618.55      7144349.92
      2271581.18      7144315.89      2271532.23      7144301.55
      2271523.86      7144215.18      2271430.33      7144206.46
      2271404.99      7144187.32      2271382.44      7144158.78
      2271379.33      7143884.78      2271373.66      7143857.26
      2271346.23      7143826.24      2271323.35      7143811.98
      2271180.19      7143806.55      2271154.84      7143787.30
      2271131.99      7143758.61      2271128.83      7143725.43
      2271136.35      7143703.95      2271229.00      7143610.00

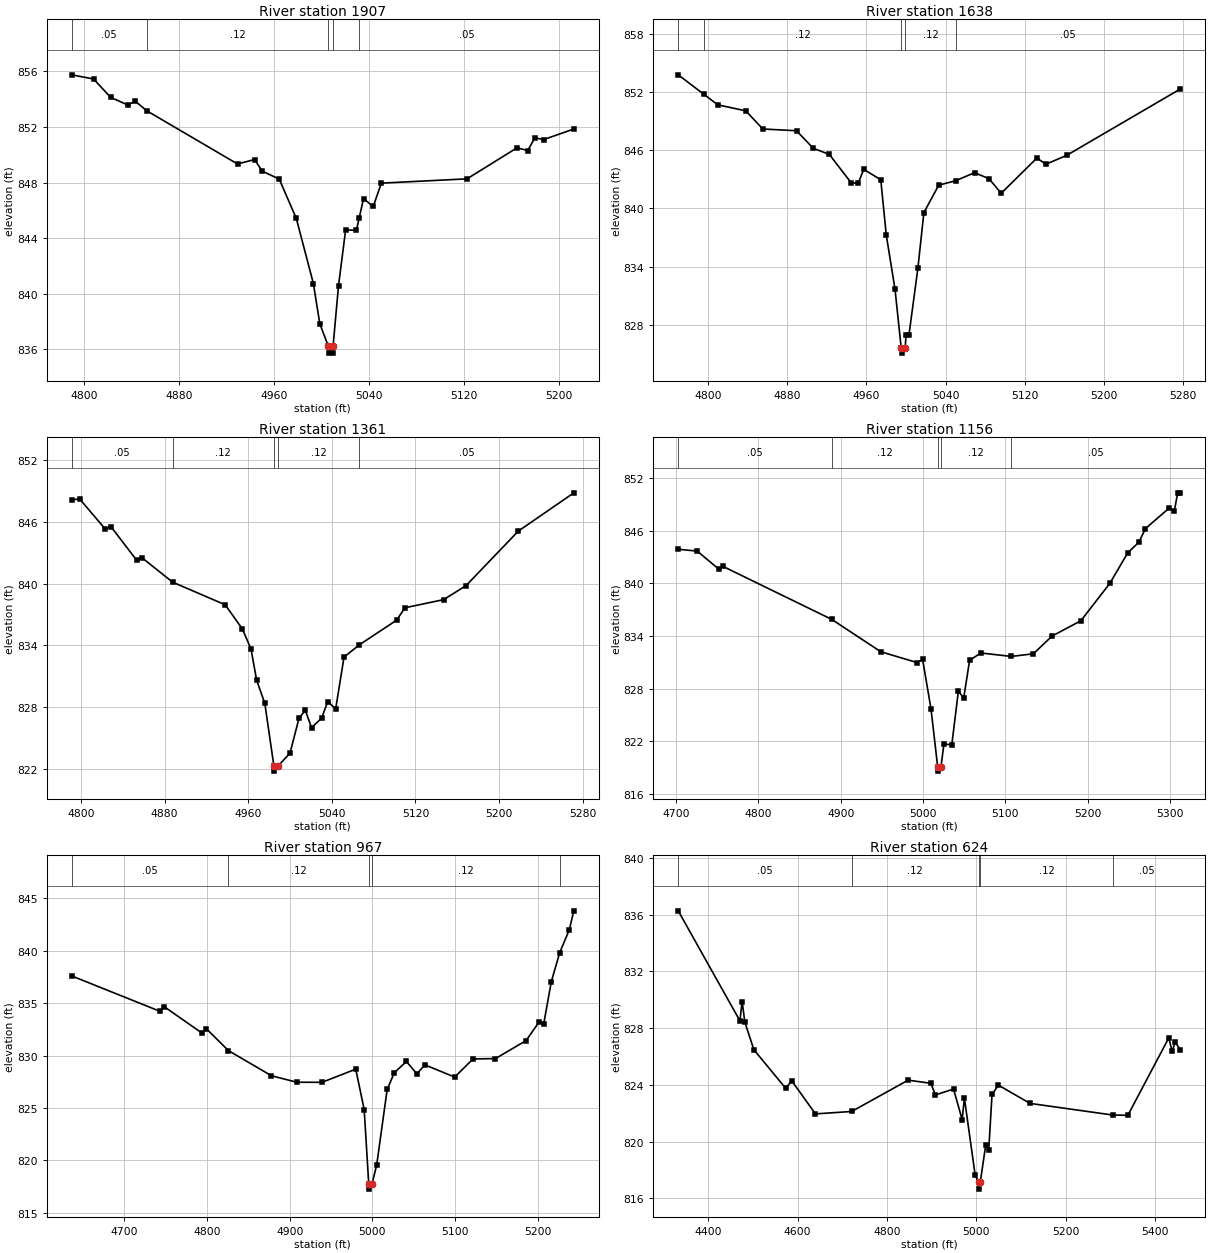
Type RM Length L Ch R = 1,1907,269,269,269
BEGIN DESCRIPTION:
MDW T 088 7.0
END DESCRIPTION:
XS GIS Cut Line= 3
      2272099.00      7144883.97      2271935.51      7145016.73
      2271757.82      7145134.00
#Sta/Elev= 30
  4789.4  855.76  4807.8  855.46  4822.2  854.14  4836.6  853.59  4843.0  853.86
  4852.5  853.18  4929.2  849.34  4943.6  849.66  4950.0  848.83  4964.4  848.25
  4978.8  845.42  4993.2  840.73  4998.6  837.84  5005.8  836.22  5006.1  835.72
  5009.6  835.72  5009.8  836.22  5014.4  840.58  5020.4  844.59  5029.5  844.57
  5031.9  845.48  5035.5  846.84  5043.7  846.28  5050.5  847.96  5122.8  848.27
  5164.9  850.50  5174.0  850.31  5180.0  851.22  5187.5  851.10  5212.9  851.86
#Mann=5,-1,0
  4789.4    0.05       0  4852.5    0.12       0  5005.8    0.07       0
  5009.8    0.12       0  5031.9    0.05       0
Bank Sta=5005.8,5009.8
Exp/Cntr=0.3,0.1

Type RM Length L Ch R = 1,1638,277,277,277
BEGIN DESCRIPTION:
MDW T 088 6.0
END DESCRIPTION:
XS GIS Cut Line= 3
      2272037.12      7144686.40      2271829.00      7144785.00
      2271597.49      7144937.82
#Sta/Elev= 30
  4769.7  853.75  4795.8  851.73  4809.7  850.66  4838.0  850.04  4855.2  848.17
  4889.3  847.99  4906.3  846.18  4922.5  845.55  4944.7  842.61  4951.7  842.59
  4957.3  844.01  4974.5  842.94  4980.0  837.30  4988.9  831.66  4995.2  825.58
  4995.5  825.08  4999.2  825.58  5000.0  826.94  5003.0  826.94  5012.0  833.80
  5018.1  839.56  5033.1  842.38  5050.5  842.85  5069.3  843.67  5083.9  843.05
  5096.3  841.55  5132.4  845.18  5141.5  844.54  5162.6  845.46  5277.4  852.29
#Mann=5,-1,0
  4769.7    0.05       0  4795.8    0.12       0  4995.2    0.07       0
  4999.2    0.12       0  5050.5    0.05       0
Bank Sta=4995.2,4999.2
Exp/Cntr=0.3,0.1

Type RM Length L Ch R = 1,1361,205,205,205
BEGIN DESCRIPTION:
MDW T 088 5.0
END DESCRIPTION:
XS GIS Cut Line= 3
      2271911.43      7144472.51      2271716.49      7144547.33
      2271483.44      7144686.80
#Sta/Elev= 30
  4791.2  848.13  4798.6  848.25  4823.3  845.30  4828.7  845.54  4853.3  842.27
  4858.7  842.49  4887.7  840.14  4938.0  837.94  4954.5  835.58  4962.7  833.63
  4968.1  830.60  4975.9  828.35  4984.6  822.26  4984.8  821.76  4988.6  822.26
  5000.0  823.51  5008.7  826.93  5014.7  827.67  5020.6  825.99  5030.3  826.91
  5036.1  828.53  5043.7  827.81  5051.7  832.85  5066.4  834.05  5102.0  836.44
  5110.0  837.65  5147.0  838.44  5168.4  839.80  5218.5  845.11  5271.6  848.83
#Mann=5,-1,0
  4791.2    0.05       0  4887.7    0.12       0  4984.6    0.07       0
  4988.6    0.12       0  5066.4    0.05       0
Bank Sta=4984.6,4988.6
Exp/Cntr=0.3,0.1

Type RM Length L Ch R = 1,1156,189,189,189
BEGIN DESCRIPTION:
MDW T 088 4.0
END DESCRIPTION:
XS GIS Cut Line= 3
      2271921.82      7144326.69      2271602.94      7144380.85
      2271379.02      7144559.98
#Sta/Elev= 30
  4702.6  843.90  4725.7  843.69  4751.7  841.65  4756.7  841.96  4889.1  835.91
  4948.9  832.22  4992.8  830.99  4999.6  831.35  5009.8  825.71  5017.9  819.12
  5018.2  818.62  5021.9  819.12  5025.5  821.69  5035.1  821.64  5043.1  827.77
  5049.5  826.92  5056.7  831.24  5070.3  832.08  5107.5  831.69  5134.3  831.99
  5156.8  834.00  5192.0  835.76  5227.2  840.02  5248.8  843.48  5262.4  844.70
  5270.4  846.25  5299.2  848.59  5305.6  848.28  5309.6  850.33  5312.8  850.33
#Mann=5,-1,0
  4702.6    0.05       0  4889.1    0.12       0  5017.9    0.07       0
  5021.9    0.12       0  5107.5    0.05       0
Bank Sta=5017.9,5021.9
Exp/Cntr=0.3,0.1

Type RM Length L Ch R = 1,967,343,343,343
BEGIN DESCRIPTION:
MDW T 088 3.0
END DESCRIPTION:
XS GIS Cut Line= 3
      2271885.86      7144173.54      2271529.29      7144244.70
      2271403.34      7144453.33
#Sta/Elev= 30
  4636.4  837.60  4743.2  834.22  4748.3  834.66  4794.2  832.13  4799.3  832.55
  4825.9  830.47  4877.9  828.07  4908.5  827.45  4939.1  827.44  4979.9  828.70
  4990.1  824.84  4995.6  817.74  4995.8  817.24  4999.6  817.74  5005.3  819.58
  5017.9  826.76  5026.6  828.37  5041.2  829.43  5053.8  828.25  5063.5  829.11
  5099.6  827.94  5121.7  829.67  5148.9  829.71  5185.8  831.42  5201.3  833.16
  5207.2  833.00  5216.4  837.04  5226.5  839.80  5238.2  842.02  5243.7  843.82
#Mann=5,-1,0
  4636.4    0.05       0  4825.9    0.12       0  4995.6    0.07       0
  4999.6    0.12       0  5226.5    0.05       0
Bank Sta=4995.6,4999.6
Exp/Cntr=0.3,0.1

Type RM Length L Ch R = 1,624,276,276,276
BEGIN DESCRIPTION:
MDW T 088 2.0
END DESCRIPTION:
XS GIS Cut Line= 3
      2272035.59      7143889.25      2271379.00      7144010.00
      2271046.02      7144323.29
#Sta/Elev= 30
  4332.4  836.28  4470.5  828.52  4475.6  829.88  4481.5  828.44  4501.8  826.48
  4573.0  823.76  4586.8  824.28  4639.8  821.95  4720.9  822.12  4847.5  824.33
  4898.3  824.11  4908.5  823.29  4949.2  823.70  4968.4  821.55  4973.5  823.06
  4997.5  817.65  5005.1  817.14  5005.3  816.64  5009.1  817.14  5021.2  819.74
  5028.1  819.43  5035.4  823.32  5049.6  823.98  5120.4  822.69  5305.7  821.87
  5339.7  821.85  5431.5  827.32  5438.8  826.36  5445.7  827.02  5457.2  826.46
#Mann=5,-1,0
  4332.4    0.05       0  4720.9    0.12       0  5005.1    0.07       0
  5009.1    0.12       0  5305.7    0.05       0
Bank Sta=5005.1,5009.1
Exp/Cntr=0.3,0.1

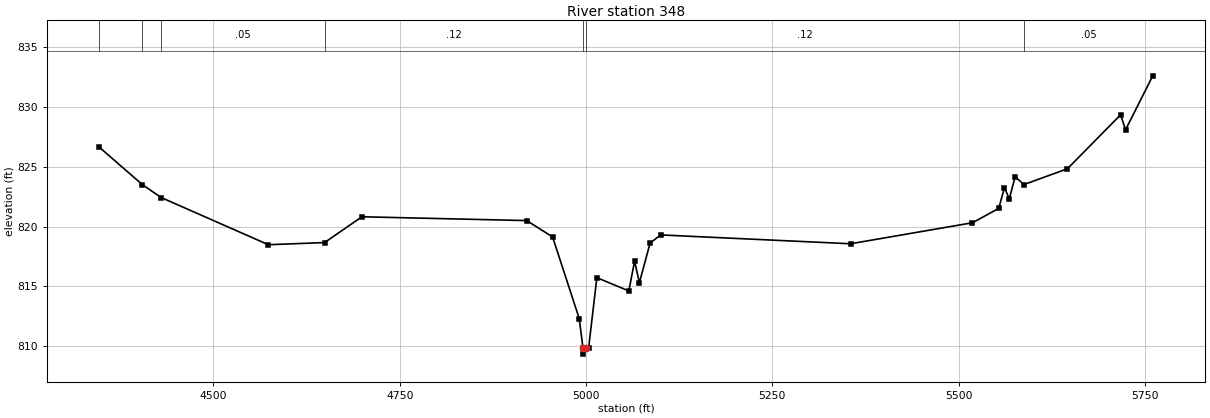
Type RM Length L Ch R = 1,348,0,0,0
BEGIN DESCRIPTION:
MDW T 088 1.0
END DESCRIPTION:
XS GIS Cut Line= 3
      2271919.43      7143741.14      2271269.84      7143809.77
      2270777.34      7144389.26
#Sta/Elev= 30
  4346.8  826.64  4404.6  823.51  4429.8  822.43  4573.7  818.48  4649.1  818.66
  4699.2  820.82  4920.4  820.50  4955.1  819.13  4990.8  812.30  4995.9  809.82
  4996.2  809.32  4999.9  809.82  5003.4  809.82  5014.5  815.72  5057.4  814.61
  5065.1  817.10  5071.6  815.30  5085.9  818.62  5100.2  819.30  5355.0  818.56
  5518.6  820.32  5553.8  821.52  5561.5  823.26  5568.0  822.32  5575.8  824.16
  5587.8  823.52  5646.0  824.84  5717.4  829.36  5724.0  828.10  5760.5  832.62
#Mann=7,-1,0
  4346.8    0.05       0  4404.6    0.12       0  4429.8    0.05       0
  4649.1    0.12       0  4995.9    0.07       0  4999.9    0.12       0
  5587.8    0.05       0
Bank Sta=4995.9,4999.9
Exp/Cntr=0.3,0.1

Chan Stop Cuts=-1