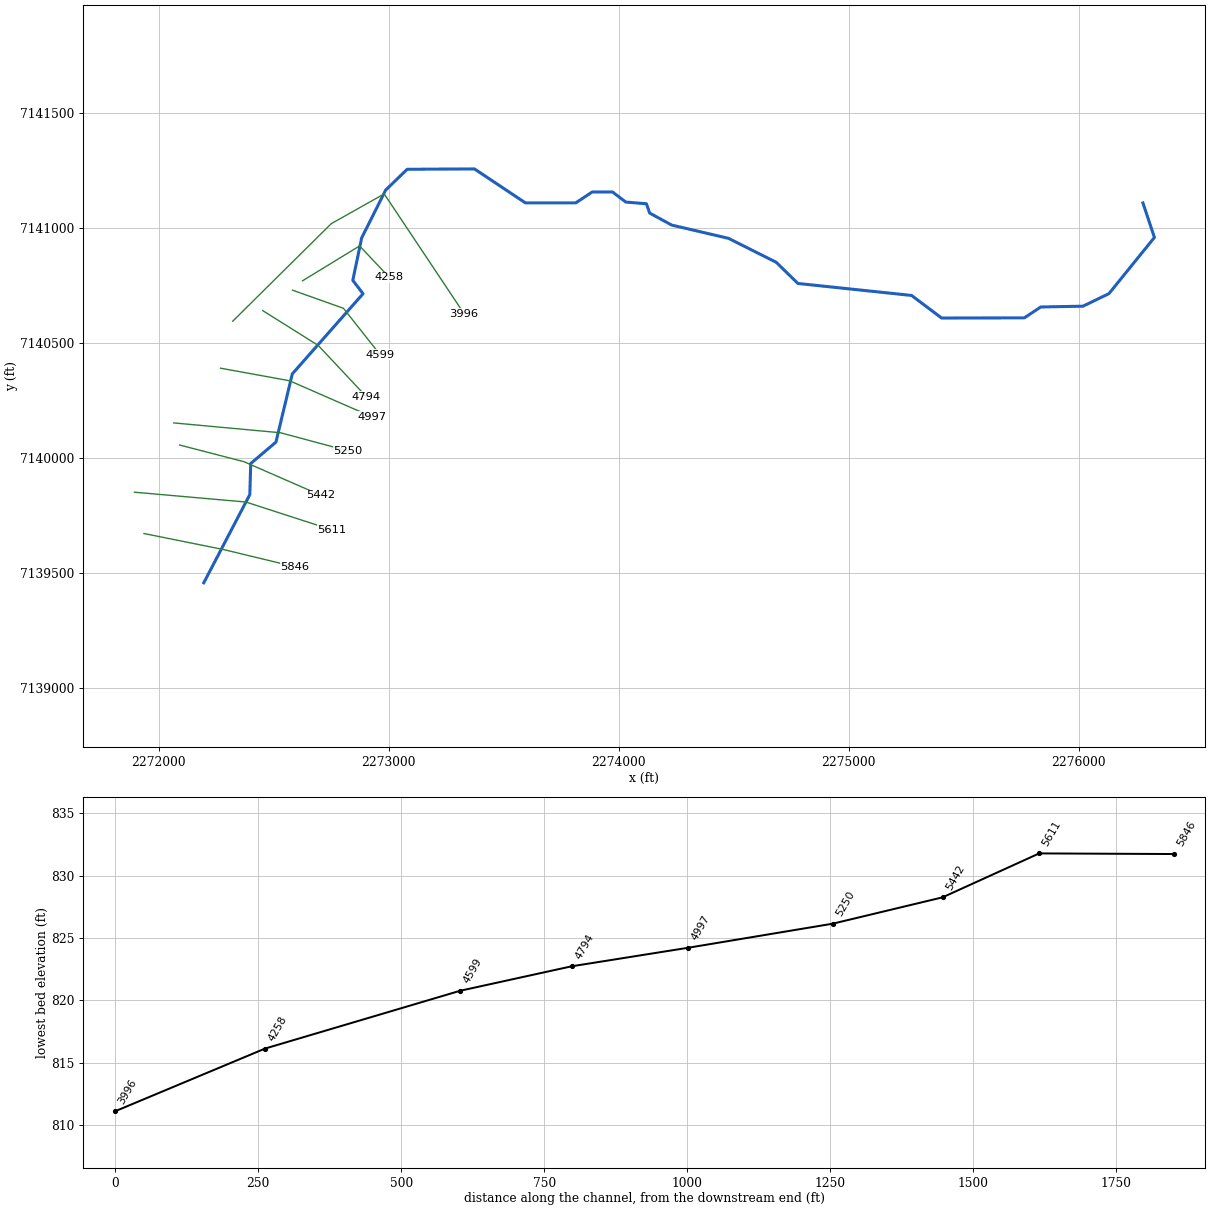
--- MDW T 089.prj (project) ---

Proj Title=MDW T 089 Base Level Engineering
Current Plan=p01
Default Exp/Contr=0.3,0.1
English Units
Geom File=g01
Flow File=f01
Plan File=p01
BEGIN DESCRIPTION:
MDW T 089
END DESCRIPTION:

--- MDW T 089.p01 (plan) ---

Plan Title=Multiple Run
Short Identifier=Multiple
Geom File=g01
Flow File=f01
Subcritical Flow
K Sum by GR= 0
Std Step Tol= 0.01
Critical Tol= 0.01
Num of Std Step Trials= 20
Max Error Tol= 0.3
Flow Tol Ratio= 0.001
Split Flow NTrial= 30
Split Flow Tol= 0.02
Split Flow Ratio= 0.02
Log Output Level= 0
Friction Slope Method= 1
Unsteady Friction Slope Method= 2
Unsteady Bridges Friction Slope Method= 1
Parabolic Critical Depth
Global Vel Dist=  1 , 1 , 1
Global Log Level= 0
CheckData=True
Encroach Param= -1, 0, 0, 0
BEGIN DESCRIPTION:
Multiple Run
END DESCRIPTION:

--- MDW T 089.f01 (steady flow) ---

Flow Title=Multiple
Number of Profiles=7
Profile Names=10-year,25-year,50-year,1pct_min,100-year,1pct_plu,500-year
River Rch & RM= MDW T 089,Reach-1,5846
     531     725     885     538    1073    2142    1579
Boundary for River Rch & Prof#=MDW T 089,Reach-1,1
Up Type=0
Dn Type=3
Dn Slope=0.005
Boundary for River Rch & Prof#=MDW T 089,Reach-1,2
Up Type=0
Dn Type=3
Dn Slope=0.005
Boundary for River Rch & Prof#=MDW T 089,Reach-1,3
Up Type=0
Dn Type=3
Dn Slope=0.005
Boundary for River Rch & Prof#=MDW T 089,Reach-1,4
Up Type=0
Dn Type=3
Dn Slope=0.005
Boundary for River Rch & Prof#=MDW T 089,Reach-1,5
Up Type=0
Dn Type=3
Dn Slope=0.005
Boundary for River Rch & Prof#=MDW T 089,Reach-1,6
Up Type=0
Dn Type=3
Dn Slope=0.005
Boundary for River Rch & Prof#=MDW T 089,Reach-1,7
Up Type=0
Dn Type=3
Dn Slope=0.005

--- MDW T 089.g01 (geometry) ---

Geom Title=Existing Conditions

River Reach=MDW T 089,Reach-1
Reach XY= 30
      2272196.28      7139458.74      2272396.29      7139842.04
      2272400.37      7139977.30      2272509.88      7140070.18
      2272581.03      7140366.79      2272888.53      7140715.39
      2272844.04      7140773.65      2272882.75      7140958.45
      2272987.13      7141166.07      2273080.45      7141256.47
      2273373.14      7141257.94      2273594.21      7141110.51
      2273813.78      7141110.52      2273884.98      7141157.83
      2273973.03      7141157.83      2274030.67      7141113.88
      2274120.52      7141106.50      2274134.79      7141066.02
      2274230.56      7141013.82      2274477.42      7140956.17
      2274685.08      7140851.91      2274779.00      7140760.00
      2275273.14      7140707.93      2275403.88      7140609.71
      2275763.78      7140610.52      2275834.94      7140657.74
      2276018.50      7140661.20      2276131.31      7140715.82
      2276329.00      7140960.00      2276279.00      7141110.00

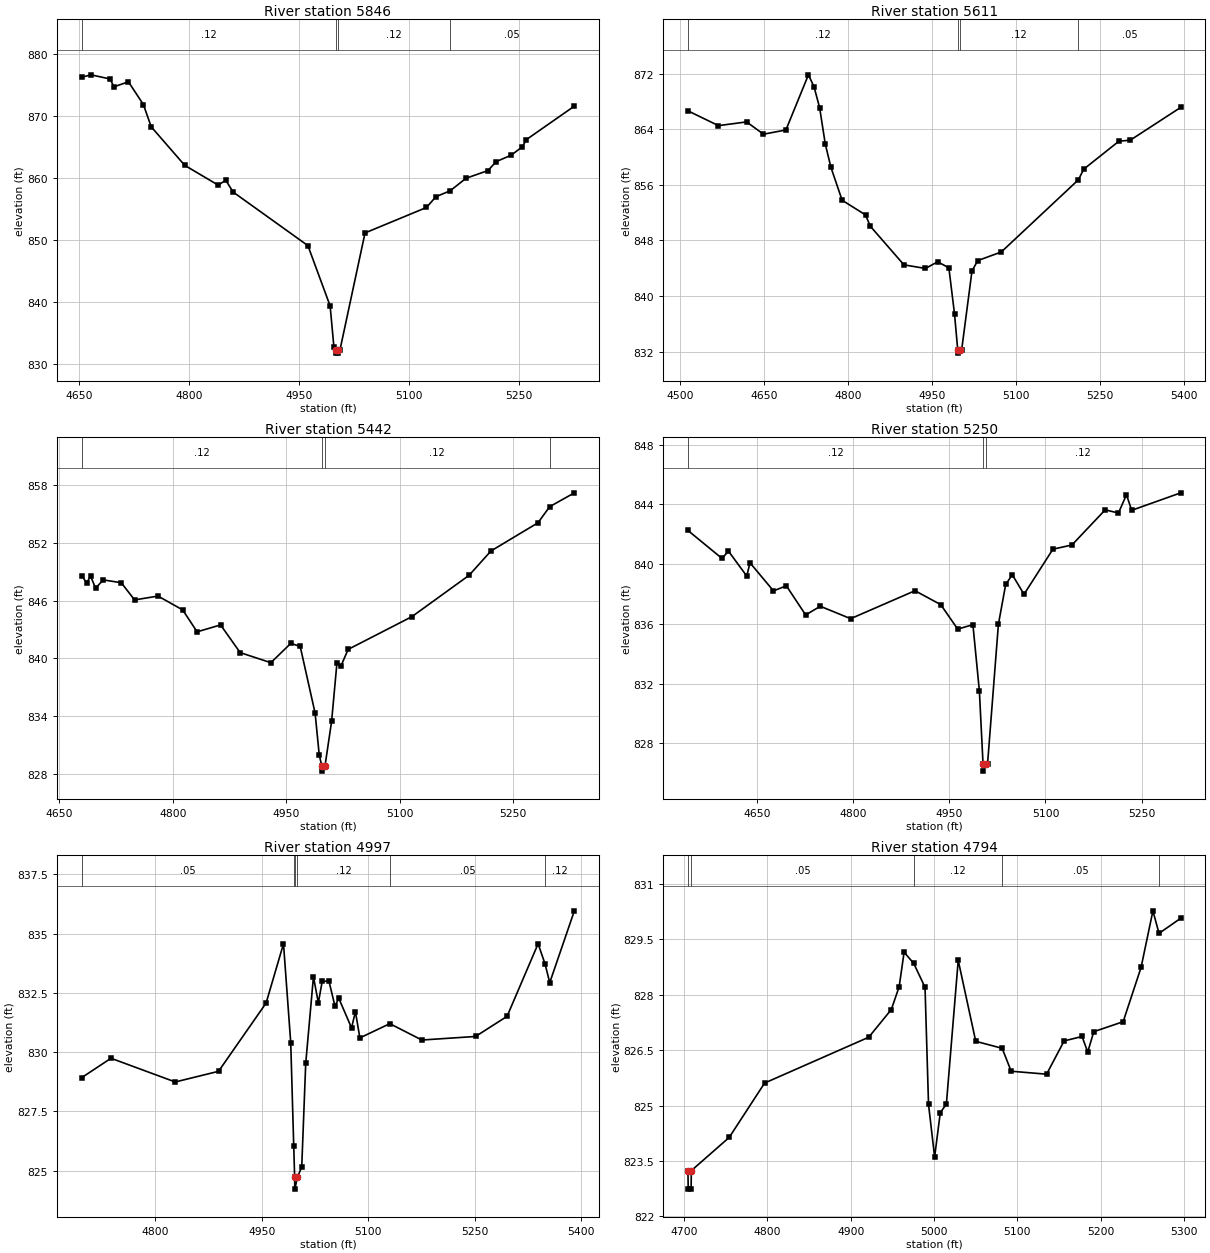
Type RM Length L Ch R = 1,5846,235,235,235
BEGIN DESCRIPTION:
MDW T 089 4.0
END DESCRIPTION:
XS GIS Cut Line= 3
      2271936.37      7139672.83      2272281.87      7139603.31
      2272592.62      7139528.30
#Sta/Elev= 30
  4653.3  876.25  4666.2  876.65  4692.3  875.98  4697.4  874.71  4717.2  875.53
  4737.6  871.86  4748.3  868.26  4794.0  862.04  4839.6  858.85  4850.0  859.63
  4860.0  857.73  4962.0  849.08  4992.3  839.35  4997.4  832.78  4999.7  832.23
  5000.0  831.73  5003.5  831.73  5003.7  832.23  5005.7  832.23  5039.9  851.13
  5123.7  855.24  5136.5  856.97  5156.1  857.94  5177.7  859.96  5207.5  861.19
  5218.8  862.64  5239.4  863.69  5254.5  865.04  5259.9  866.19  5325.4  871.60
#Mann=4,-1,0
  4653.3    0.12       0  4999.7    0.07       0  5003.7    0.12       0
  5156.1    0.05       0
Bank Sta=4999.7,5003.7
Exp/Cntr=0.3,0.1

Type RM Length L Ch R = 1,5611,169,169,169
BEGIN DESCRIPTION:
MDW T 089 3.0
END DESCRIPTION:
XS GIS Cut Line= 3
      2271894.67      7139852.53      2272379.40      7139809.83
      2272754.02      7139688.47
#Sta/Elev= 30
  4514.6  866.63  4569.1  864.50  4619.3  865.04  4649.5  863.27  4689.6  863.88
  4729.8  871.81  4739.8  870.09  4749.8  867.09  4759.9  861.87  4769.9  858.53
  4790.0  853.77  4831.8  851.66  4840.2  850.05  4900.4  844.48  4938.9  843.96
  4960.7  844.92  4980.7  844.05  4990.8  837.41  4996.5  832.28  4996.7  831.78
  5000.5  832.28  5003.6  832.28  5022.0  843.60  5032.3  845.09  5074.4  846.33
  5212.2  856.72  5221.5  858.23  5284.6  862.27  5304.6  862.40  5395.0  867.13
#Mann=4,-1,0
  4514.6    0.12       0  4996.5    0.07       0  5000.5    0.12       0
  5212.2    0.05       0
Bank Sta=4996.5,5000.5
Exp/Cntr=0.3,0.1

Type RM Length L Ch R = 1,5442,192,192,192
BEGIN DESCRIPTION:
Mapping XS e16442ca
END DESCRIPTION:
XS GIS Cut Line= 3
      2272091.12      7140057.65      2272371.01      7139985.13
      2272703.12      7139839.92
#Sta/Elev= 30
  4679.4  848.61  4686.2  847.84  4691.3  848.55  4697.9  847.30  4708.2  848.15
  4731.9  847.86  4749.5  846.07  4780.5  846.47  4813.1  845.03  4832.2  842.75
  4863.2  843.47  4889.1  840.59  4929.7  839.54  4956.1  841.55  4968.5  841.23
  4988.2  834.29  4993.7  829.91  4997.2  828.76  4997.4  828.26  5001.2  828.76
  5010.0  833.43  5017.1  839.54  5022.6  839.23  5031.8  840.92  5116.2  844.33
  5191.8  848.63  5220.7  851.16  5282.8  854.09  5298.4  855.77  5331.0  857.21
#Mann=4,-1,0
  4679.4    0.12       0  4997.2    0.07       0  5001.2    0.12       0
  5298.4    0.05       0
Bank Sta=4997.2,5001.2
Exp/Cntr=0.3,0.1

Type RM Length L Ch R = 1,5250,253,253,253
BEGIN DESCRIPTION:
MDW T 089 2.0
END DESCRIPTION:
XS GIS Cut Line= 3
      2272066.06      7140153.74      2272529.43      7140111.07
      2272822.99      7140032.22
#Sta/Elev= 30
  4541.9  842.25  4595.1  840.38  4605.1  840.87  4633.7  839.20  4638.7  840.09
  4675.4  838.21  4695.5  838.55  4725.6  836.60  4748.5  837.18  4795.9  836.35
  4896.3  838.22  4936.5  837.29  4963.0  835.65  4986.7  835.95  4996.8  831.52
  5002.5  826.65  5002.8  826.15  5006.5  826.65  5009.6  826.65  5026.5  835.97
  5037.9  838.64  5048.2  839.29  5066.5  837.98  5111.6  841.00  5141.3  841.28
  5193.2  843.63  5213.9  843.42  5226.4  844.64  5234.6  843.60  5311.2  844.77
#Mann=3,-1,0
  4541.9    0.12       0  5002.5    0.07       0  5006.5    0.12       0
Bank Sta=5002.5,5006.5
Exp/Cntr=0.3,0.1

Type RM Length L Ch R = 1,4997,203,203,203
BEGIN DESCRIPTION:
Mapping XS 14b9c32b
END DESCRIPTION:
XS GIS Cut Line= 3
      2272269.10      7140391.70      2272568.80      7140337.17
      2272925.86      7140181.11
#Sta/Elev= 30
  4696.0  828.92  4737.5  829.74  4828.0  828.74  4889.0  829.19  4956.0  832.07
  4980.5  834.57  4990.7  830.40  4994.9  826.06  4996.2  824.72  4996.4  824.22
  5000.2  824.72  5006.2  825.16  5011.8  829.52  5022.7  833.18  5029.6  832.08
  5035.0  832.98  5044.5  833.00  5053.0  831.94  5058.4  832.27  5076.4  831.02
  5081.8  831.71  5088.1  830.60  5130.3  831.20  5175.4  830.51  5251.1  830.66
  5295.5  831.51  5339.2  834.57  5349.0  833.72  5355.6  832.93  5390.3  835.96
#Mann=6,-1,0
  4696.0    0.05       0  4994.9    0.12       0  4996.2    0.07       0
  5000.2    0.12       0  5130.3    0.05       0  5349.0    0.12       0
Bank Sta=4996.2,5000.2
Exp/Cntr=0.3,0.1

Type RM Length L Ch R = 1,4794,195,195,195
BEGIN DESCRIPTION:
Mapping XS f3e16c65
END DESCRIPTION:
XS GIS Cut Line= 3
      2272452.86      7140641.82      2272693.68      7140490.68
      2272903.60      7140267.10
#Sta/Elev= 30
  4704.9  823.24  4705.2  822.74  4708.7  822.74  4708.9  823.24  4754.4  824.14
  4796.8  825.61  4921.7  826.85  4948.8  827.60  4958.2  828.22  4964.1  829.15
  4975.6  828.85  4989.2  828.20  4993.4  825.03  5000.7  823.61  5007.5  824.81
  5014.8  825.04  5029.0  828.93  5050.0  826.74  5081.7  826.55  5092.5  825.93
  5135.0  825.85  5156.0  826.75  5177.5  826.87  5184.3  826.45  5191.6  827.00
  5226.8  827.27  5248.3  828.74  5262.5  830.27  5269.8  829.66  5295.9  830.07
#Mann=5,-1,0
  4704.9    0.07       0  4708.9    0.05       0  4975.6    0.12       0
  5081.7    0.05       0  5269.8    0.12       0
Bank Sta=4704.9,4708.9
Exp/Cntr=0.3,0.1

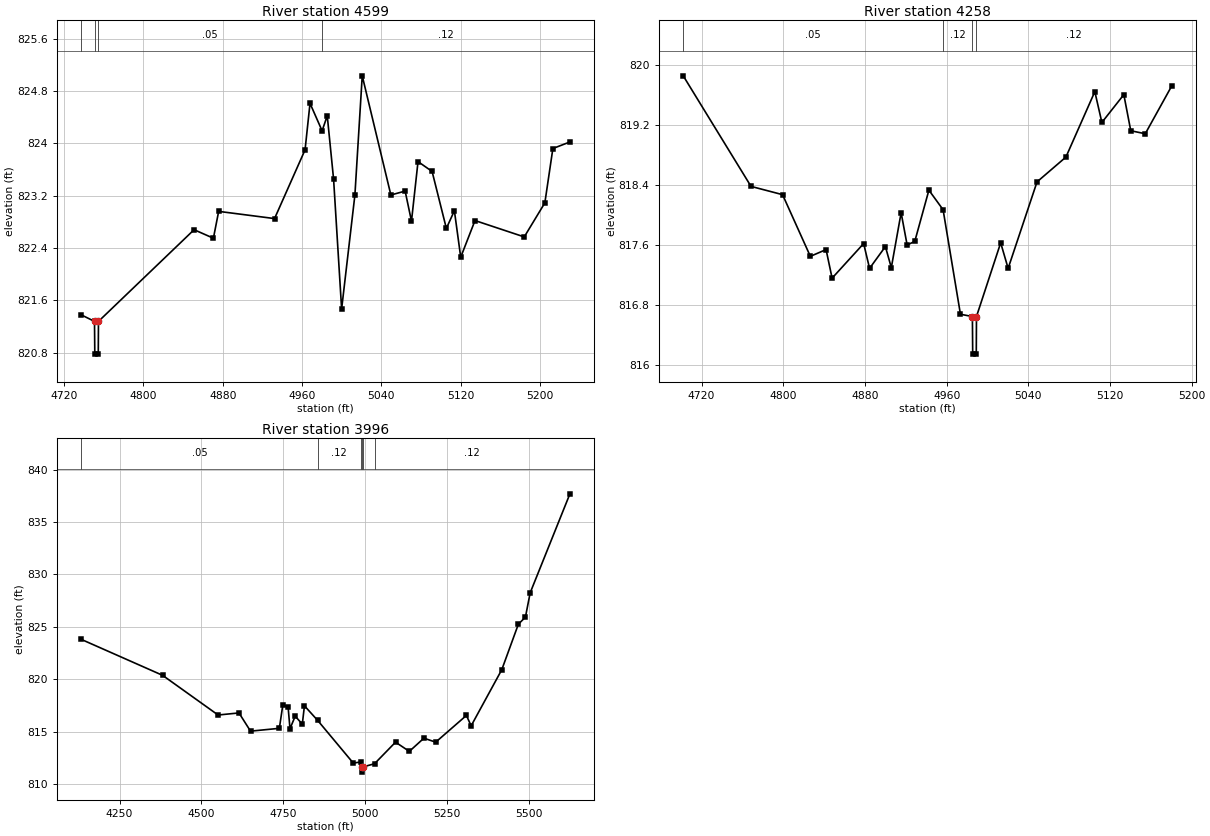
Type RM Length L Ch R = 1,4599,341,341,341
BEGIN DESCRIPTION:
Mapping XS 24aac438
END DESCRIPTION:
XS GIS Cut Line= 3
      2272581.71      7140730.97      2272803.51      7140651.96
      2272963.32      7140449.73
#Sta/Elev= 30
  4737.2  821.38  4750.6  821.28  4750.9  820.78  4754.4  820.78  4754.6  821.28
  4851.1  822.68  4870.6  822.55  4875.9  822.96  4932.3  822.85  4963.1  823.90
  4968.1  824.61  4980.3  824.19  4985.5  824.42  4991.9  823.45  5000.0  821.47
  5013.4  823.21  5020.8  825.03  5049.7  823.21  5064.1  823.27  5070.5  822.81
  5077.1  823.72  5091.3  823.57  5105.7  822.70  5113.8  822.97  5120.2  822.26
  5134.6  822.82  5184.3  822.57  5205.1  823.09  5213.2  823.92  5230.4  824.02
#Mann=4,-1,0
  4737.2    0.05       0  4750.6    0.07       0  4754.6    0.05       0
  4980.3    0.12       0
Bank Sta=4750.6,4754.6
Exp/Cntr=0.3,0.1

Type RM Length L Ch R = 1,4258,262,262,262
BEGIN DESCRIPTION:
Mapping XS 1f96d1db
END DESCRIPTION:
XS GIS Cut Line= 3
      2272625.42      7140771.58      2272873.70      7140923.18
      2273002.51      7140786.66
#Sta/Elev= 30
  4702.0  819.85  4768.4  818.38  4799.3  818.27  4826.5  817.45  4841.9  817.54
  4847.8  817.16  4878.7  817.62  4884.5  817.29  4900.0  817.58  4905.8  817.30
  4915.4  818.03  4921.3  817.60  4928.8  817.65  4942.6  818.33  4956.5  818.07
  4973.5  816.68  4985.2  816.65  4985.5  816.15  4989.0  816.15  4989.2  816.65
  5012.9  817.63  5020.2  817.29  5048.5  818.44  5076.8  818.77  5105.1  819.64
  5112.0  819.23  5133.5  819.60  5140.3  819.12  5154.5  819.08  5180.6  819.72
#Mann=4,-1,0
  4702.0    0.05       0  4956.5    0.12       0  4985.2    0.07       0
  4989.2    0.12       0
Bank Sta=4985.2,4989.2
Exp/Cntr=0.3,0.1

Type RM Length L Ch R = 1,3996,0,0,0
BEGIN DESCRIPTION:
MDW T 089 1.0
END DESCRIPTION:
XS GIS Cut Line= 4
      2272321.97      7140595.79      2272750.41      7141020.01
      2272980.50      7141149.38      2273327.42      7140629.03
#Sta/Elev= 30
  4133.1  823.80  4381.5  820.37  4551.1  816.58  4614.8  816.78  4650.1  815.04
  4738.1  815.31  4748.9  817.58  4764.9  817.32  4770.6  815.27  4786.5  816.47
  4808.2  815.71  4814.7  817.46  4854.7  816.08  4963.9  811.99  4986.3  812.10
  4989.8  811.63  4990.0  811.13  4993.8  811.63  5028.7  811.93  5092.9  813.99
  5135.0  813.11  5179.5  814.37  5215.6  813.99  5309.3  816.54  5323.8  815.55
  5417.4  820.91  5468.0  825.25  5489.5  825.92  5504.0  828.24  5625.4  837.69
#Mann=6,-1,0
  4133.1    0.05       0  4854.7    0.12       0  4986.3    0.05       0
  4989.8   0.033       0  4993.8    0.05       0  5028.7    0.12       0
Bank Sta=4989.8,4993.8
Exp/Cntr=0.3,0.1

Chan Stop Cuts=-1