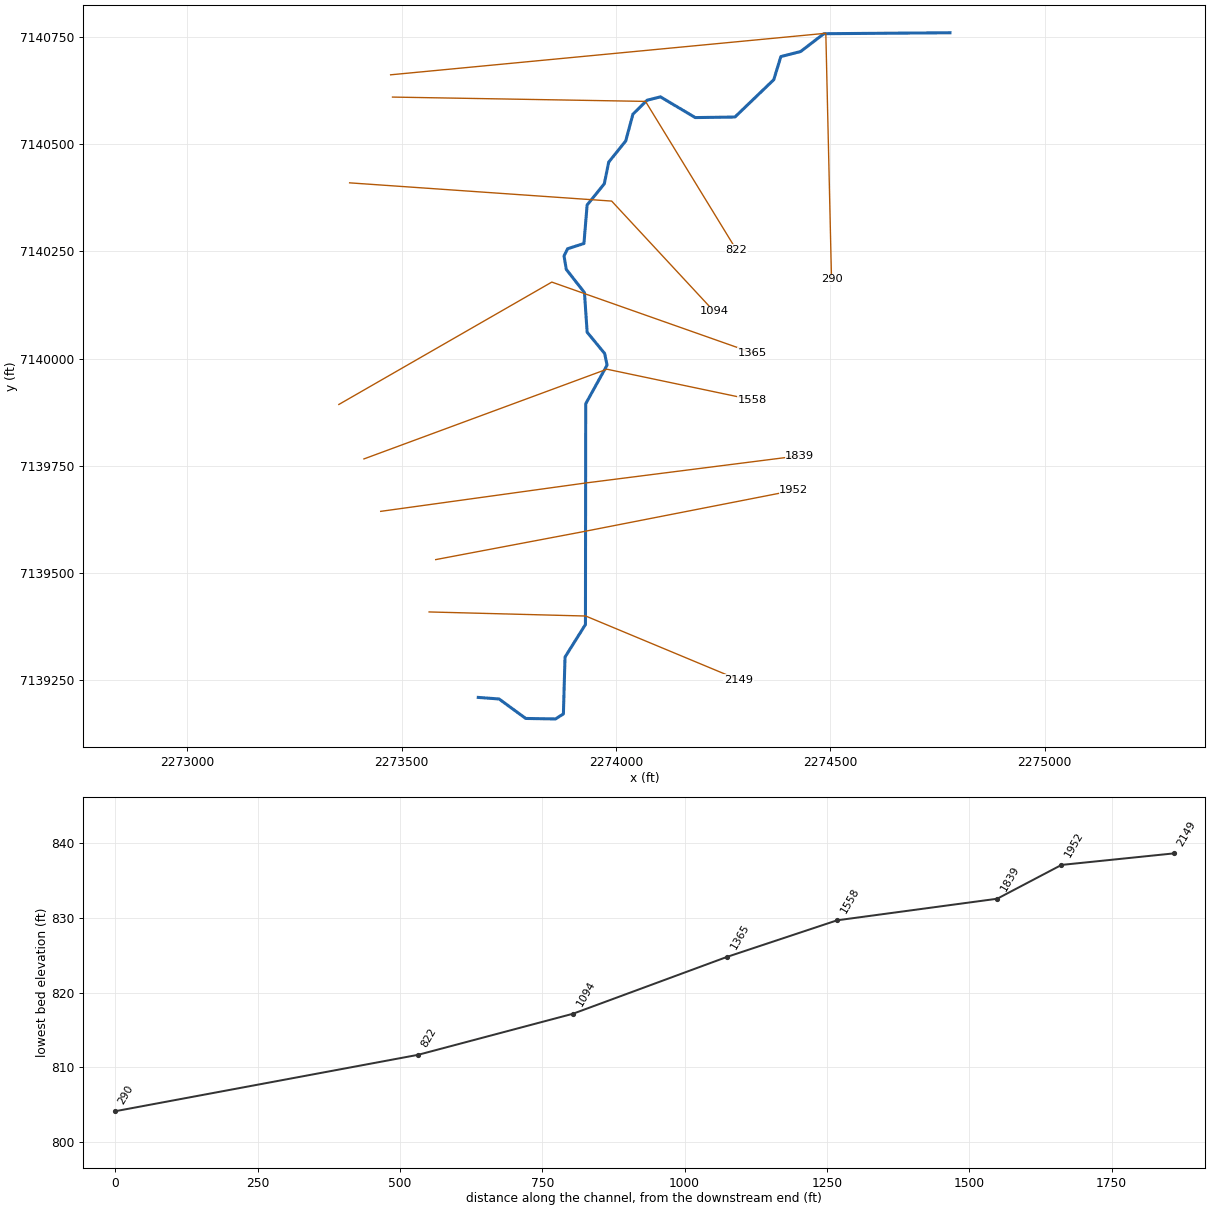
--- MDW T 090.prj (project) ---

Proj Title=MDW T 090 Base Level Engineering
Current Plan=p01
Default Exp/Contr=0.3,0.1
English Units
Geom File=g01
Flow File=f01
Plan File=p01
BEGIN DESCRIPTION:
MDW T 090
END DESCRIPTION:

--- MDW T 090.p01 (plan) ---

Plan Title=Multiple Run
Short Identifier=Multiple
Geom File=g01
Flow File=f01
Subcritical Flow
K Sum by GR= 0
Std Step Tol= 0.01
Critical Tol= 0.01
Num of Std Step Trials= 20
Max Error Tol= 0.3
Flow Tol Ratio= 0.001
Split Flow NTrial= 30
Split Flow Tol= 0.02
Split Flow Ratio= 0.02
Log Output Level= 0
Friction Slope Method= 1
Unsteady Friction Slope Method= 2
Unsteady Bridges Friction Slope Method= 1
Parabolic Critical Depth
Global Vel Dist=  1 , 1 , 1
Global Log Level= 0
CheckData=True
Encroach Param= -1, 0, 0, 0
BEGIN DESCRIPTION:
Multiple Run
END DESCRIPTION:

--- MDW T 090.f01 (steady flow) ---

Flow Title=Multiple
Number of Profiles=7
Profile Names=10-year,25-year,50-year,1pct_min,100-year,1pct_plu,500-year
River Rch & RM= MDW T 090,Reach-1,2149
     236     307     363     215     429     856     596
Boundary for River Rch & Prof#=MDW T 090,Reach-1,1
Up Type=0
Dn Type=3
Dn Slope=0.005
Boundary for River Rch & Prof#=MDW T 090,Reach-1,2
Up Type=0
Dn Type=3
Dn Slope=0.005
Boundary for River Rch & Prof#=MDW T 090,Reach-1,3
Up Type=0
Dn Type=3
Dn Slope=0.005
Boundary for River Rch & Prof#=MDW T 090,Reach-1,4
Up Type=0
Dn Type=3
Dn Slope=0.005
Boundary for River Rch & Prof#=MDW T 090,Reach-1,5
Up Type=0
Dn Type=3
Dn Slope=0.005
Boundary for River Rch & Prof#=MDW T 090,Reach-1,6
Up Type=0
Dn Type=3
Dn Slope=0.005
Boundary for River Rch & Prof#=MDW T 090,Reach-1,7
Up Type=0
Dn Type=3
Dn Slope=0.005

--- MDW T 090.g01 (geometry) ---

Geom Title=Existing Conditions

River Reach=MDW T 090,Reach-1
Reach XY= 30
      2273679.00      7139210.00      2273727.50      7139206.35
      2273789.64      7139160.94      2273859.00      7139159.77
      2273877.49      7139171.44      2273881.28      7139304.05
      2273928.93      7139380.03      2273929.54      7139894.79
      2273979.40      7139985.00      2273973.63      7140012.18
      2273932.89      7140061.59      2273926.61      7140154.06
      2273884.27      7140208.13      2273878.94      7140239.56
      2273887.21      7140256.27      2273925.38      7140268.48
      2273932.85      7140358.35      2273972.89      7140407.82
      2273983.16      7140458.28      2274022.89      7140507.84
      2274039.63      7140570.12      2274072.66      7140602.64
      2274103.88      7140610.53      2274184.97      7140562.19
      2274277.51      7140563.46      2274368.12      7140650.56
      2274384.61      7140704.41      2274430.84      7140716.28
      2274484.90      7140757.77      2274779.00      7140760.00

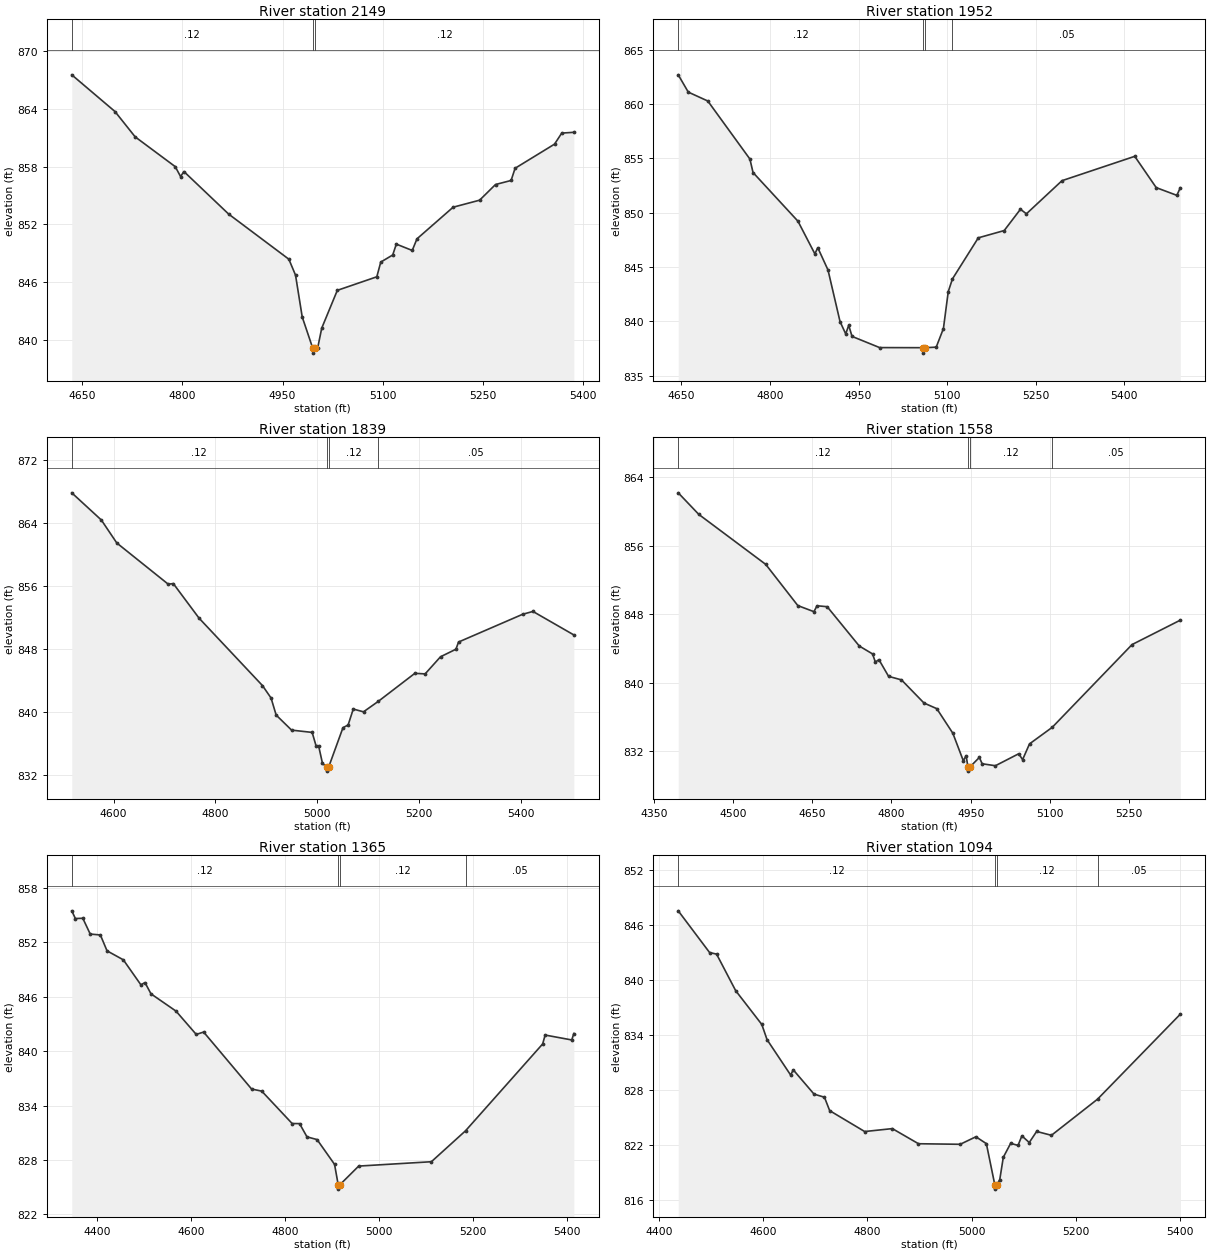
Type RM Length L Ch R = 1,2149,197,197,197
BEGIN DESCRIPTION:
MDW T 090 7.0
END DESCRIPTION:
XS GIS Cut Line= 3
      2273564.27      7139409.31      2273929.45      7139399.81
      2274285.67      7139251.41
#Sta/Elev= 30
  4634.7  867.56  4699.4  863.74  4729.5  861.11  4789.5  858.01  4797.5  856.98
  4802.5  857.50  4869.5  853.07  4959.5  848.38  4969.5  846.72  4979.5  842.37
  4995.3  839.11  4995.5  838.61  4999.3  839.11  5002.5  839.11  5008.7  841.21
  5032.0  845.14  5091.1  846.55  5097.0  848.08  5114.9  848.82  5120.3  849.95
  5144.1  849.29  5151.2  850.50  5205.3  853.79  5244.9  854.52  5268.7  856.15
  5292.0  856.57  5298.0  857.84  5357.0  860.35  5367.8  861.50  5385.9  861.58
#Mann=3,-1,0
  4634.7    0.12       0  4995.3    0.07       0  4999.3    0.12       0
Bank Sta=4995.3,4999.3
Exp/Cntr=0.3,0.1

Type RM Length L Ch R = 1,1952,113,113,113
BEGIN DESCRIPTION:
MDW T 090 6.5
END DESCRIPTION:
XS GIS Cut Line= 3
      2273579.73      7139531.38      2273917.92      7139595.42
      2274414.80      7139692.67
#Sta/Elev= 30
  4644.5  862.68  4661.5  861.09  4694.6  860.27  4765.9  854.93  4771.2  853.69
  4847.3  849.21  4875.9  846.21  4880.9  846.77  4898.2  844.72  4918.6  839.97
  4928.2  838.84  4933.3  839.63  4938.9  838.61  4985.6  837.58  5059.1  837.57
  5059.4  837.07  5063.1  837.57  5081.5  837.62  5093.7  839.33  5101.9  842.73
  5109.0  843.90  5152.8  847.68  5196.7  848.35  5224.2  850.31  5234.3  849.89
  5294.6  852.94  5417.8  855.18  5454.2  852.30  5489.1  851.59  5495.0  852.29
#Mann=4,-1,0
  4644.5    0.12       0  5059.1    0.07       0  5063.1    0.12       0
  5109.0    0.05       0
Bank Sta=5059.1,5063.1
Exp/Cntr=0.3,0.1

Type RM Length L Ch R = 1,1839,281,281,281
BEGIN DESCRIPTION:
MDW T 090 6.0
END DESCRIPTION:
XS GIS Cut Line= 3
      2273451.44      7139643.90      2273929.00      7139710.00
      2274428.66      7139773.57
#Sta/Elev= 30
  4517.9  867.84  4576.0  864.39  4606.3  861.48  4707.2  856.26  4717.3  856.33
  4767.8  851.95  4892.3  843.40  4909.2  841.82  4919.2  839.66  4949.5  837.75
  4989.9  837.46  4997.5  835.77  5002.5  835.77  5010.1  833.55  5018.2  833.05
  5018.4  832.55  5022.2  833.05  5050.4  838.06  5060.5  838.40  5070.6  840.42
  5090.7  840.07  5119.6  841.39  5191.5  844.95  5211.7  844.88  5241.9  847.05
  5272.2  848.01  5277.3  848.92  5403.2  852.44  5423.4  852.80  5503.7  849.82
#Mann=4,-1,0
  4517.9    0.12       0  5018.2    0.07       0  5022.2    0.12       0
  5119.6    0.05       0
Bank Sta=5018.2,5022.2
Exp/Cntr=0.3,0.1

Type RM Length L Ch R = 1,1558,193,193,193
BEGIN DESCRIPTION:
MDW T 090 5.0
END DESCRIPTION:
XS GIS Cut Line= 3
      2273412.40      7139766.19      2273978.91      7139975.39
      2274318.48      7139903.99
#Sta/Elev= 30
  4396.1  862.15  4435.1  859.63  4561.8  853.80  4622.6  848.99  4653.1  848.28
  4659.0  848.97  4678.2  848.86  4739.0  844.27  4764.1  843.35  4769.4  842.40
  4776.2  842.68  4794.5  840.73  4818.9  840.32  4861.5  837.62  4885.8  836.96
  4916.2  834.09  4936.0  830.88  4941.3  831.47  4944.8  830.17  4945.0  829.67
  4948.8  830.17  4966.4  831.27  4971.7  830.53  4996.8  830.30  5041.0  831.70
  5048.3  831.01  5061.4  832.85  5104.4  834.78  5255.6  844.44  5347.0  847.29
#Mann=4,-1,0
  4396.1    0.12       0  4944.8    0.07       0  4948.8    0.12       0
  5104.4    0.05       0
Bank Sta=4944.8,4948.8
Exp/Cntr=0.3,0.1

Type RM Length L Ch R = 1,1365,271,271,271
BEGIN DESCRIPTION:
MDW T 090 4.0
END DESCRIPTION:
XS GIS Cut Line= 3
      2273353.87      7139893.17      2273850.49      7140178.56
      2274318.48      7140013.58
#Sta/Elev= 30
  4345.9  855.46  4353.6  854.61  4369.4  854.64  4385.2  852.90  4406.8  852.80
  4421.0  851.05  4455.7  850.06  4493.0  847.31  4501.8  847.55  4514.6  846.31
  4567.8  844.41  4610.9  841.84  4626.7  842.10  4728.8  835.82  4750.4  835.59
  4815.1  832.02  4830.9  832.01  4846.7  830.55  4868.2  830.25  4905.4  827.52
  4913.1  825.29  4913.4  824.79  4917.1  825.29  4956.8  827.33  5111.6  827.81
  5184.3  831.22  5348.5  840.79  5353.8  841.77  5410.4  841.23  5414.9  841.94
#Mann=4,-1,0
  4345.9    0.12       0  4913.1    0.07       0  4917.1    0.12       0
  5184.3    0.05       0
Bank Sta=4913.1,4917.1
Exp/Cntr=0.3,0.1

Type RM Length L Ch R = 1,1094,272,272,272
BEGIN DESCRIPTION:
MDW T 090 3.0
END DESCRIPTION:
XS GIS Cut Line= 3
      2273378.96      7140410.00      2273990.08      7140367.45
      2274228.98      7140110.02
#Sta/Elev= 30
  4436.7  847.53  4496.9  842.98  4510.3  842.81  4547.0  838.82  4597.1  835.14
  4607.2  833.48  4652.5  829.62  4657.5  830.19  4697.4  827.54  4717.4  827.20
  4727.4  825.74  4794.6  823.46  4847.7  823.78  4897.9  822.13  4978.0  822.07
  5008.1  822.89  5028.2  822.14  5044.3  817.68  5044.5  817.18  5048.3  817.68
  5053.9  818.21  5060.7  820.65  5074.8  822.17  5089.0  821.95  5096.4  822.99
  5110.5  822.26  5124.7  823.47  5153.1  823.05  5241.6  826.99  5400.5  836.26
#Mann=4,-1,0
  4436.7    0.12       0  5044.3    0.07       0  5048.3    0.12       0
  5241.6    0.05       0
Bank Sta=5044.3,5048.3
Exp/Cntr=0.3,0.1

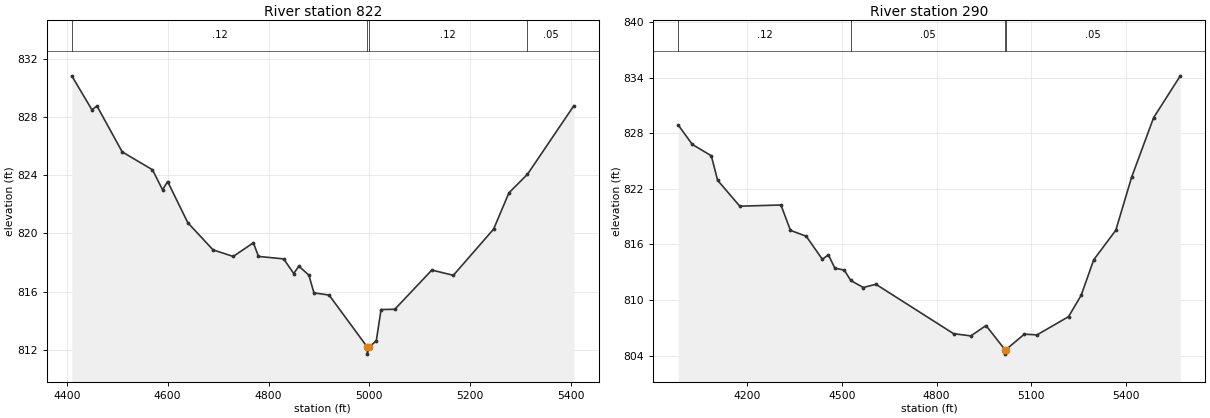
Type RM Length L Ch R = 1,822,532,532,532
BEGIN DESCRIPTION:
MDW T 090 2.0
END DESCRIPTION:
XS GIS Cut Line= 3
      2273478.98      7140610.00      2274069.00      7140599.94
      2274280.61      7140254.28
#Sta/Elev= 30
  4409.9  830.86  4449.9  828.52  4459.9  828.78  4509.9  825.62  4569.9  824.39
  4589.9  823.01  4599.9  823.58  4640.0  820.74  4690.0  818.87  4730.0  818.42
  4770.0  819.36  4780.0  818.42  4830.0  818.25  4850.0  817.24  4860.0  817.75
  4880.0  817.13  4890.0  815.91  4920.0  815.76  4995.5  812.19  4995.8  811.69
  4999.5  812.19  5013.6  812.60  5023.1  814.76  5050.3  814.78  5123.8  817.48
  5166.4  817.12  5246.2  820.30  5276.6  822.80  5313.4  824.08  5405.3  828.80
#Mann=4,-1,0
  4409.9    0.12       0  4995.5    0.07       0  4999.5    0.12       0
  5313.4    0.05       0
Bank Sta=4995.5,4999.5
Exp/Cntr=0.3,0.1

Type RM Length L Ch R = 1,290,0,0,0
BEGIN DESCRIPTION:
MDW T 090 1.0
END DESCRIPTION:
XS GIS Cut Line= 3
      2273474.59      7140661.94      2274489.48      7140758.81
      2274502.75      7140185.36
#Sta/Elev= 30
  3980.5  828.91  4025.1  826.82  4085.4  825.59  4105.5  822.94  4175.8  820.14
  4306.4  820.27  4336.5  817.53  4386.7  816.89  4437.8  814.40  4457.1  814.89
  4477.2  813.45  4507.3  813.23  4528.0  812.11  4567.6  811.35  4607.7  811.70
  4854.3  806.36  4909.1  806.12  4957.1  807.24  5016.8  804.65  5017.1  804.15
  5020.8  804.65  5078.8  806.31  5118.8  806.23  5218.9  808.20  5258.9  810.50
  5298.9  814.35  5368.9  817.54  5418.9  823.25  5488.9  829.71  5573.6  834.23
#Mann=4,-1,0
  3980.5    0.12       0  4528.0    0.05       0  5016.8   0.033       0
  5020.8    0.05       0
Bank Sta=5016.8,5020.8
Exp/Cntr=0.3,0.1

Chan Stop Cuts=-1