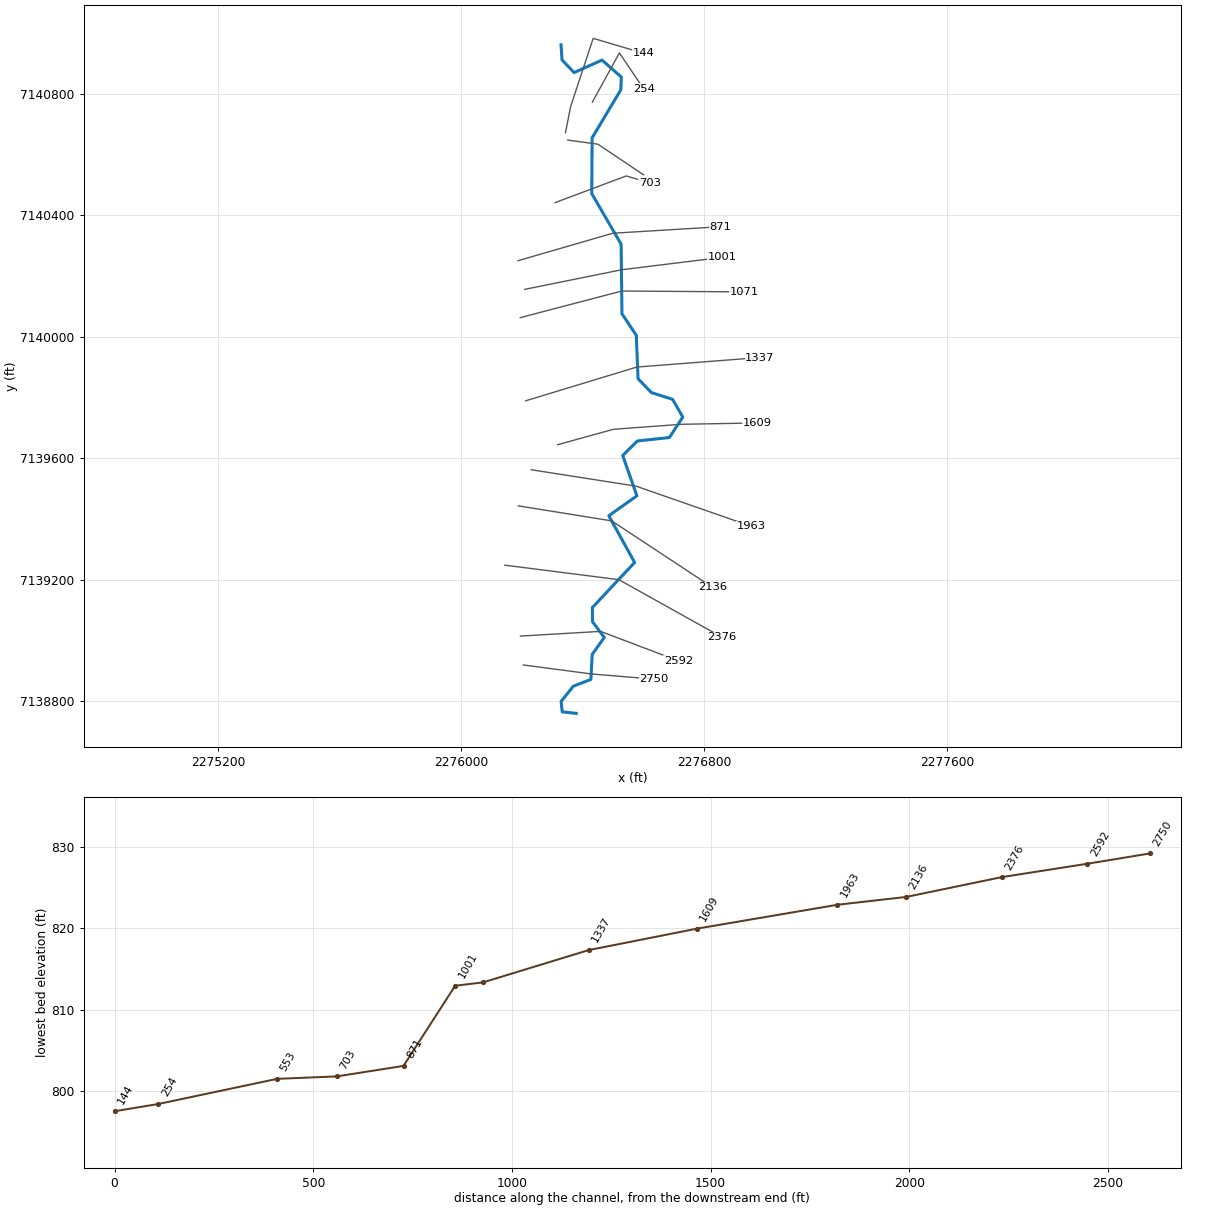
--- MDW T 091.prj (project) ---

Proj Title=MDW T 091 Base Level Engineering
Current Plan=p01
Default Exp/Contr=0.3,0.1
English Units
Geom File=g01
Flow File=f01
Plan File=p01
BEGIN DESCRIPTION:
MDW T 091
END DESCRIPTION:

--- MDW T 091.p01 (plan) ---

Plan Title=Multiple Run
Short Identifier=Multiple
Geom File=g01
Flow File=f01
Subcritical Flow
K Sum by GR= 0
Std Step Tol= 0.01
Critical Tol= 0.01
Num of Std Step Trials= 20
Max Error Tol= 0.3
Flow Tol Ratio= 0.001
Split Flow NTrial= 30
Split Flow Tol= 0.02
Split Flow Ratio= 0.02
Log Output Level= 0
Friction Slope Method= 1
Unsteady Friction Slope Method= 2
Unsteady Bridges Friction Slope Method= 1
Parabolic Critical Depth
Global Vel Dist=  1 , 1 , 1
Global Log Level= 0
CheckData=True
Encroach Param= -1, 0, 0, 0
BEGIN DESCRIPTION:
Multiple Run
END DESCRIPTION:

--- MDW T 091.f01 (steady flow) ---

Flow Title=Multiple
Number of Profiles=7
Profile Names=10-year,25-year,50-year,1pct_min,100-year,1pct_plu,500-year
River Rch & RM= MDW T 091,Reach-1,2750
     262     342     404     238     476     949     659
Boundary for River Rch & Prof#=MDW T 091,Reach-1,1
Up Type=0
Dn Type=3
Dn Slope=0.005
Boundary for River Rch & Prof#=MDW T 091,Reach-1,2
Up Type=0
Dn Type=3
Dn Slope=0.005
Boundary for River Rch & Prof#=MDW T 091,Reach-1,3
Up Type=0
Dn Type=3
Dn Slope=0.005
Boundary for River Rch & Prof#=MDW T 091,Reach-1,4
Up Type=0
Dn Type=3
Dn Slope=0.005
Boundary for River Rch & Prof#=MDW T 091,Reach-1,5
Up Type=0
Dn Type=3
Dn Slope=0.005
Boundary for River Rch & Prof#=MDW T 091,Reach-1,6
Up Type=0
Dn Type=3
Dn Slope=0.005
Boundary for River Rch & Prof#=MDW T 091,Reach-1,7
Up Type=0
Dn Type=3
Dn Slope=0.005

--- MDW T 091.g01 (geometry) ---

Geom Title=Existing Conditions

River Reach=MDW T 091,Reach-1
Reach XY= 30
      2276379.00      7138760.00      2276332.92      7138764.96
      2276329.31      7138799.38      2276369.21      7138849.21
      2276427.25      7138871.88      2276431.59      7138954.02
      2276471.41      7139010.01      2276432.57      7139061.65
      2276432.16      7139108.35      2276571.23      7139256.59
      2276486.23      7139410.29      2276578.73      7139476.02
      2276532.03      7139608.60      2276580.22      7139656.47
      2276685.55      7139667.75      2276729.67      7139734.99
      2276696.22      7139793.50      2276626.45      7139815.75
      2276582.46      7139861.25      2276576.73      7140004.06
      2276529.52      7140075.22      2276526.76      7140304.07
      2276430.20      7140470.50      2276431.24      7140654.07
      2276525.70      7140811.77      2276527.46      7140854.19
      2276463.79      7140910.04      2276372.04      7140868.81
      2276332.27      7140910.63      2276329.00      7140960.00

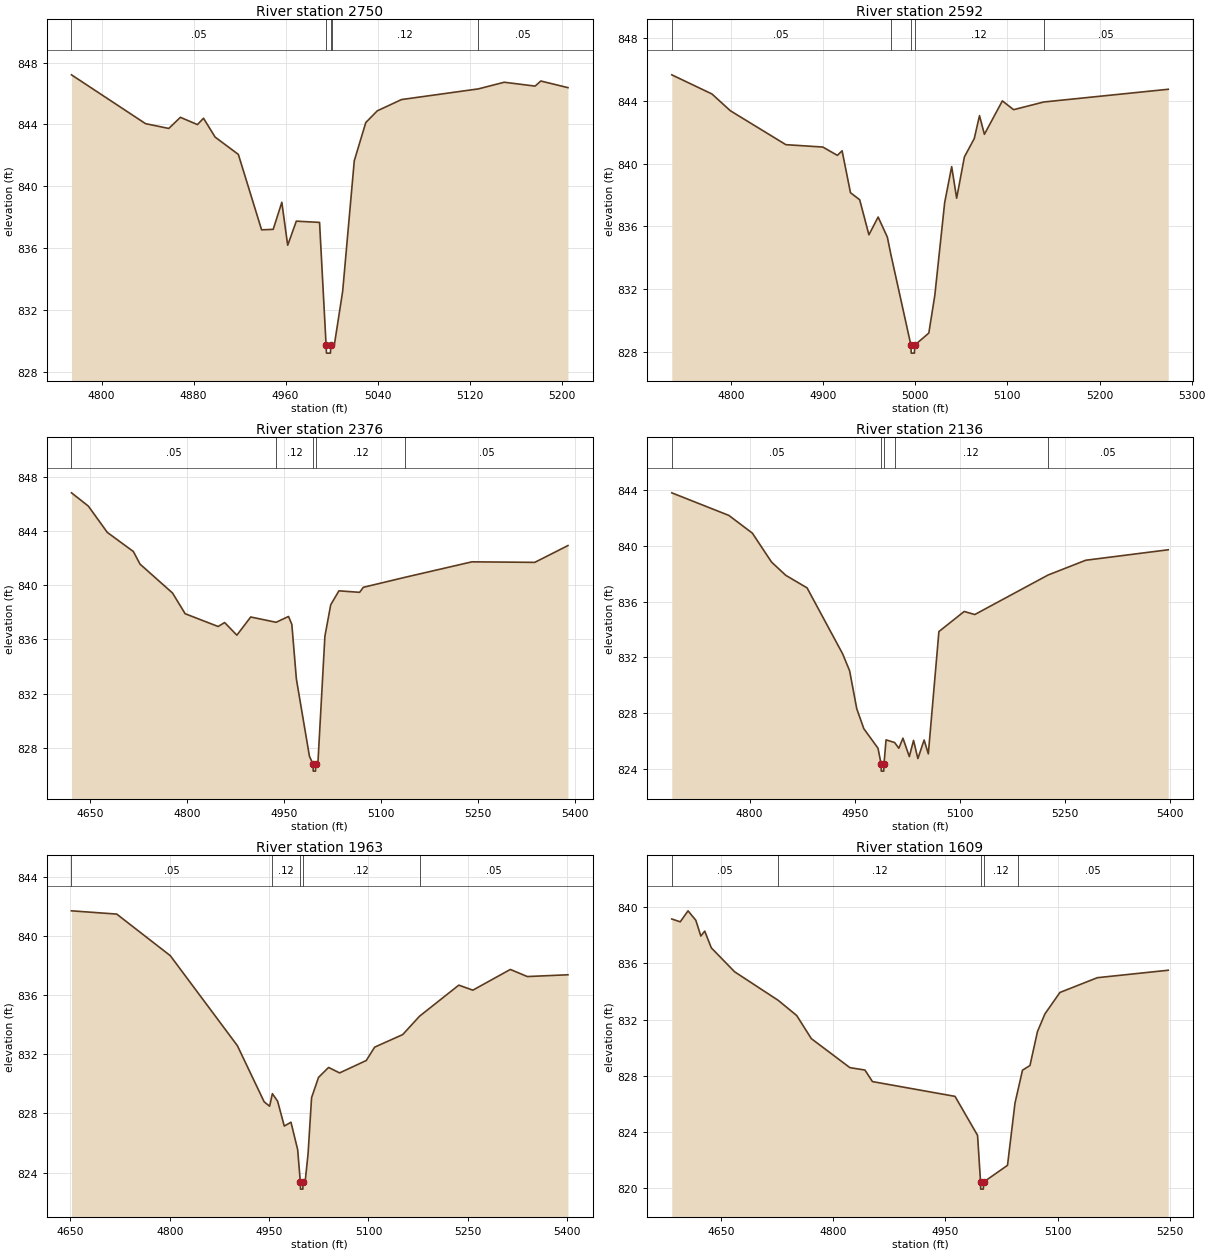
Type RM Length L Ch R = 1,2750,158,158,158
BEGIN DESCRIPTION:
MDW T 091 10.0
END DESCRIPTION:
XS GIS Cut Line= 3
      2276205.16      7138919.31      2276429.30      7138889.67
      2276634.21      7138872.79
#Sta/Elev= 30
  4773.9  847.21  4838.3  844.05  4858.5  843.74  4868.6  844.46  4883.4  843.99
  4888.7  844.40  4898.8  843.18  4919.0  842.06  4939.2  837.18  4949.3  837.21
  4956.8  838.96  4961.9  836.18  4969.4  837.74  4989.6  837.66  4995.3  829.70
  4995.6  829.20  4999.1  829.20  4999.3  829.70  5000.6  829.70  5002.4  829.70
  5009.7  833.20  5019.8  841.65  5029.8  844.12  5039.8  844.88  5060.9  845.61
  5127.7  846.30  5150.2  846.73  5177.0  846.48  5182.0  846.81  5205.6  846.38
#Mann=5,-1,0
  4773.9    0.05       0  4995.3   0.033       0  4999.3    0.05       0
  5000.6    0.12       0  5127.7    0.05       0
Bank Sta=4995.3,4999.3
Exp/Cntr=0.3,0.1

Type RM Length L Ch R = 1,2592,216,216,216
BEGIN DESCRIPTION:
MDW T 091 9.0
END DESCRIPTION:
XS GIS Cut Line= 3
      2276195.46      7139014.45      2276459.11      7139029.87
      2276715.87      7138932.50
#Sta/Elev= 30
  4735.9  845.66  4779.5  844.44  4799.5  843.37  4859.7  841.21  4899.7  841.06
  4915.6  840.53  4920.7  840.82  4929.8  838.15  4939.8  837.70  4949.8  835.47
  4959.8  836.60  4969.8  835.32  4973.5  834.25  4995.4  828.43  4995.7  827.93
  4999.2  827.93  4999.4  828.43  5014.8  829.21  5021.3  831.61  5032.0  837.52
  5039.6  839.81  5045.0  837.80  5053.4  840.43  5064.1  841.60  5069.8  843.06
  5075.1  841.87  5094.6  844.00  5106.8  843.44  5139.6  843.93  5274.6  844.74
#Mann=5,-1,0
  4735.9    0.05       0  4973.5    0.12       0  4995.4    0.07       0
  4999.4    0.12       0  5139.6    0.05       0
Bank Sta=4995.4,4999.4
Exp/Cntr=0.3,0.1

Type RM Length L Ch R = 1,2376,240,240,240
BEGIN DESCRIPTION:
MDW T 091 8.0
END DESCRIPTION:
XS GIS Cut Line= 3
      2276144.09      7139247.78      2276519.26      7139200.01
      2276859.33      7139010.30
#Sta/Elev= 30
  4621.8  846.81  4647.9  845.83  4677.2  843.89  4717.5  842.48  4727.8  841.55
  4778.0  839.42  4797.6  837.89  4848.5  836.95  4858.6  837.24  4877.5  836.31
  4898.9  837.65  4938.2  837.26  4957.4  837.69  4962.5  837.10  4969.5  833.08
  4989.7  827.38  4995.3  826.78  4995.6  826.28  4999.1  826.28  4999.3  826.78
  5002.7  826.78  5013.6  836.23  5022.6  838.55  5035.3  839.58  5067.3  839.47
  5073.0  839.84  5137.7  840.58  5241.0  841.72  5338.1  841.68  5389.4  842.92
#Mann=5,-1,0
  4621.8    0.05       0  4938.2    0.12       0  4995.3    0.07       0
  4999.3    0.12       0  5137.7    0.05       0
Bank Sta=4995.3,4999.3
Exp/Cntr=0.3,0.1

Type RM Length L Ch R = 1,2136,173,173,173
BEGIN DESCRIPTION:
MDW T 091 7.0
END DESCRIPTION:
XS GIS Cut Line= 3
      2276188.49      7139442.93      2276495.55      7139393.57
      2276827.29      7139174.95
#Sta/Elev= 30
  4689.0  843.79  4770.5  842.17  4804.0  840.90  4831.3  838.83  4851.6  837.88
  4882.0  836.98  4932.8  832.25  4942.7  831.04  4952.9  828.32  4963.0  826.89
  4983.2  825.49  4987.7  824.35  4987.9  823.85  4991.4  823.85  4991.7  824.35
  4994.7  826.09  5006.9  825.90  5012.9  825.49  5018.8  826.21  5027.9  824.89
  5033.9  826.05  5040.1  824.75  5049.0  826.08  5055.0  825.09  5070.1  833.85
  5106.2  835.29  5121.3  835.07  5225.8  837.90  5279.6  838.96  5397.3  839.71
#Mann=5,-1,0
  4689.0    0.05       0  4987.7   0.033       0  4991.7    0.05       0
  5006.9    0.12       0  5225.8    0.05       0
Bank Sta=4987.7,4991.7
Exp/Cntr=0.3,0.1

Type RM Length L Ch R = 1,1963,354,354,354
BEGIN DESCRIPTION:
MDW T 091 6.0
END DESCRIPTION:
XS GIS Cut Line= 3
      2276231.55      7139561.68      2276575.77      7139507.90
      2276954.59      7139375.77
#Sta/Elev= 30
  4651.6  841.69  4719.9  841.47  4800.8  838.66  4902.1  832.58  4942.5  828.79
  4950.8  828.49  4954.9  829.34  4962.8  828.83  4972.9  827.15  4983.0  827.41
  4993.1  825.56  4997.1  823.39  4997.4  822.89  5000.9  822.89  5001.1  823.39
  5004.4  823.39  5008.8  825.28  5014.1  829.07  5024.6  830.44  5039.8  831.11
  5056.4  830.74  5096.7  831.58  5109.3  832.48  5151.7  833.33  5177.1  834.57
  5236.4  836.67  5257.6  836.33  5314.2  837.73  5339.9  837.25  5401.2  837.37
#Mann=5,-1,0
  4651.6    0.05       0  4954.9    0.12       0  4997.1    0.07       0
  5001.1    0.12       0  5177.1    0.05       0
Bank Sta=4997.1,5001.1
Exp/Cntr=0.3,0.1

Type RM Length L Ch R = 1,1609,272,272,272
BEGIN DESCRIPTION:
MDW T 091 5.0
END DESCRIPTION:
XS GIS Cut Line= 4
      2276318.10      7139644.24      2276501.47      7139694.94
      2276726.02      7139711.43      2276973.68      7139715.77
#Sta/Elev= 30
  4584.6  839.14  4595.9  838.94  4606.3  839.72  4616.7  839.05  4623.4  837.93
  4628.6  838.28  4637.4  837.09  4668.5  835.39  4726.8  833.36  4751.5  832.28
  4771.0  830.64  4822.5  828.58  4842.6  828.41  4852.6  827.59  4962.9  826.54
  4993.0  823.77  4997.0  820.45  4997.2  819.95  5000.7  819.95  5001.0  820.45
  5033.0  821.64  5043.0  826.06  5047.5  827.11  5053.0  828.40  5063.0  828.73
  5073.0  831.14  5083.0  832.40  5103.0  833.92  5153.0  834.97  5247.7  835.50
#Mann=5,-1,0
  4584.6    0.05       0  4726.8    0.12       0  4997.0    0.07       0
  5001.0    0.12       0  5047.5    0.05       0
Bank Sta=4997,5001
Exp/Cntr=0.3,0.1

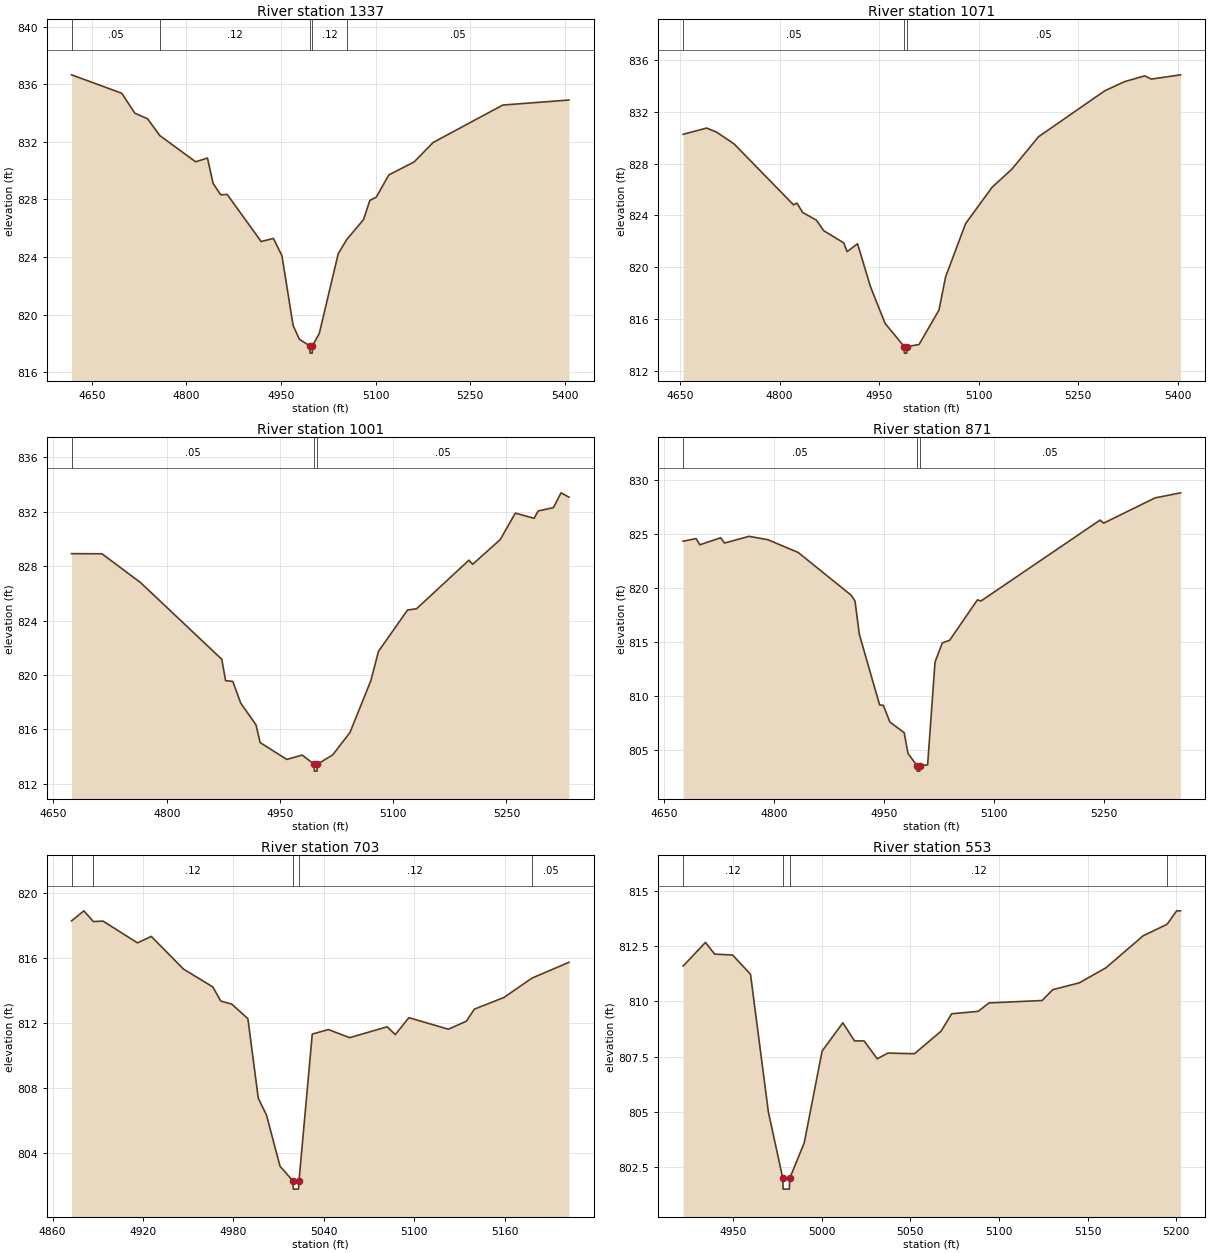
Type RM Length L Ch R = 1,1337,266,266,266
BEGIN DESCRIPTION:
MDW T 091 4.0
END DESCRIPTION:
XS GIS Cut Line= 3
      2276212.81      7139788.75      2276578.53      7139899.77
      2276983.62      7139931.11
#Sta/Elev= 30
  4617.8  836.65  4697.4  835.37  4718.3  833.98  4738.3  833.60  4757.8  832.43
  4814.5  830.61  4833.3  830.87  4842.2  829.11  4854.2  828.32  4864.6  828.34
  4918.4  825.07  4937.8  825.29  4951.3  824.09  4969.1  819.23  4979.0  818.28
  4995.6  817.82  4995.9  817.32  4999.4  817.32  4999.6  817.82  5010.5  818.68
  5040.6  824.23  5054.1  825.21  5080.7  826.60  5090.7  827.93  5100.8  828.15
  5120.8  829.70  5160.9  830.60  5191.0  831.95  5301.4  834.55  5406.3  834.90
#Mann=5,-1,0
  4617.8    0.05       0  4757.8    0.12       0  4995.6    0.07       0
  4999.6    0.12       0  5054.1    0.05       0
Bank Sta=4995.6,4999.6
Exp/Cntr=0.3,0.1

Type RM Length L Ch R = 1,1071,70,70,70
BEGIN DESCRIPTION:
MDW T 091 3.0
END DESCRIPTION:
XS GIS Cut Line= 3
      2276194.78      7140062.37      2276528.89      7140149.95
      2276932.98      7140147.09
#Sta/Elev= 30
  4654.6  830.28  4690.0  830.76  4704.9  830.45  4731.3  829.54  4821.0  824.82
  4826.1  824.96  4834.7  824.23  4855.4  823.64  4866.5  822.82  4896.6  821.88
  4901.7  821.20  4917.4  821.81  4937.0  818.48  4958.8  815.66  4987.8  813.85
  4988.0  813.35  4991.5  813.35  4991.8  813.85  5010.1  814.02  5040.1  816.68
  5050.1  819.25  5080.1  823.36  5120.1  826.18  5150.1  827.59  5190.1  830.09
  5290.1  833.65  5320.1  834.36  5350.1  834.80  5360.1  834.55  5404.1  834.88
#Mann=3,-1,0
  4654.6    0.05       0  4987.8   0.033       0  4991.8    0.05       0
Bank Sta=4987.8,4991.8
Exp/Cntr=0.3,0.1

Type RM Length L Ch R = 1,1001,130,130,130
BEGIN DESCRIPTION:
MDW T 091 2.5
END DESCRIPTION:
XS GIS Cut Line= 3
      2276209.49      7140155.45      2276529.12      7140220.07
      2276859.43      7140260.70
#Sta/Elev= 30
  4673.9  828.92  4714.2  828.91  4765.2  826.80  4872.9  821.16  4878.0  819.59
  4887.6  819.53  4897.9  817.95  4918.3  816.34  4923.7  815.04  4959.1  813.80
  4979.5  814.12  4995.4  813.44  4995.6  812.94  4999.1  812.94  4999.4  813.44
  5020.0  814.14  5042.8  815.79  5070.4  819.59  5080.5  821.74  5119.0  824.78
  5130.9  824.87  5200.3  828.44  5205.3  828.14  5241.7  829.95  5261.8  831.90
  5286.6  831.52  5292.1  832.06  5312.2  832.30  5322.3  833.39  5332.8  833.07
#Mann=3,-1,0
  4673.9    0.05       0  4995.4   0.033       0  4999.4    0.05       0
Bank Sta=4995.4,4999.4
Exp/Cntr=0.3,0.1

Type RM Length L Ch R = 1,871,168,168,168
BEGIN DESCRIPTION:
MDW T 091 2.0
END DESCRIPTION:
XS GIS Cut Line= 3
      2276187.79      7140249.85      2276499.28      7140340.11
      2276853.82      7140361.67
#Sta/Elev= 30
  4675.7  824.33  4693.4  824.57  4698.6  824.00  4727.0  824.65  4732.2  824.16
  4765.8  824.78  4791.5  824.47  4832.9  823.29  4905.3  819.34  4910.5  818.80
  4916.4  815.73  4944.1  809.21  4949.3  809.16  4958.1  807.63  4977.7  806.64
  4982.9  804.72  4995.3  803.59  4995.5  803.09  4999.0  803.09  4999.3  803.59
  5009.7  803.67  5019.8  813.16  5029.8  814.94  5039.8  815.18  5077.7  818.91
  5082.7  818.81  5245.2  826.28  5250.2  826.00  5320.3  828.33  5355.2  828.80
#Mann=3,-1,0
  4675.7    0.05       0  4995.3   0.033       0  4999.3    0.05       0
Bank Sta=4995.3,4999.3
Exp/Cntr=0.3,0.1

Type RM Length L Ch R = 1,703,150,150,150
BEGIN DESCRIPTION:
Mapping XS 06afb9b0
END DESCRIPTION:
XS GIS Cut Line= 3
      2276309.46      7140440.96      2276543.63      7140528.67
      2276620.32      7140506.09
#Sta/Elev= 30
  4872.6  818.27  4880.8  818.89  4887.1  818.23  4893.5  818.26  4916.4  816.92
  4925.5  817.32  4946.9  815.31  4966.3  814.22  4971.6  813.35  4978.9  813.16
  4989.6  812.27  4996.5  807.38  5001.9  806.36  5010.9  803.21  5019.5  802.30
  5019.7  801.80  5023.2  801.80  5023.5  802.30  5032.3  811.32  5043.0  811.60
  5057.1  811.10  5082.0  811.77  5087.4  811.29  5096.4  812.33  5122.6  811.62
  5134.5  812.11  5139.8  812.85  5159.5  813.57  5177.9  814.75  5202.6  815.73
#Mann=5,-1,0
  4872.6    0.05       0  4887.1    0.12       0  5019.5    0.07       0
  5023.5    0.12       0  5177.9    0.05       0
Bank Sta=5019.5,5023.5
Exp/Cntr=0.3,0.1

Type RM Length L Ch R = 1,553,299,299,299
BEGIN DESCRIPTION:
Mapping XS bdab0c1e
END DESCRIPTION:
XS GIS Cut Line= 3
      2276351.36      7140646.69      2276450.30      7140633.21
      2276600.43      7140532.57
#Sta/Elev= 30
  4921.8  811.60  4934.4  812.67  4939.6  812.14  4949.7  812.10  4959.8  811.23
  4969.9  804.99  4978.0  802.00  4978.2  801.50  4981.7  801.50  4982.0  802.00
  4990.1  803.59  5000.2  807.75  5011.9  809.03  5018.5  808.21  5023.9  808.21
  5031.3  807.40  5037.3  807.66  5052.3  807.63  5067.3  808.65  5073.3  809.44
  5088.3  809.55  5094.3  809.93  5124.3  810.04  5130.3  810.53  5145.3  810.84
  5160.3  811.52  5181.3  812.97  5194.8  813.49  5200.2  814.10  5202.4  814.10
#Mann=4,-1,0
  4921.8    0.12       0  4978.0    0.07       0  4982.0    0.12       0
  5194.8    0.05       0
Bank Sta=4978,4982
Exp/Cntr=0.3,0.1

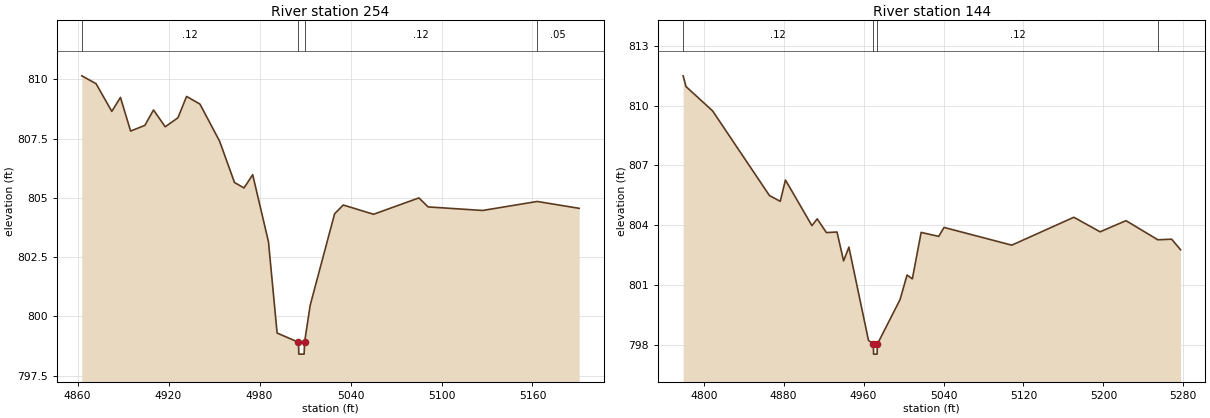
Type RM Length L Ch R = 1,254,110,110,110
BEGIN DESCRIPTION:
Mapping XS 499155ed
END DESCRIPTION:
XS GIS Cut Line= 3
      2276432.18      7140771.77      2276521.09      7140933.57
      2276601.32      7140814.73
#Sta/Elev= 30
  4862.8  810.15  4872.2  809.82  4882.6  808.65  4888.3  809.24  4895.0  807.82
  4904.4  808.06  4910.1  808.71  4917.8  808.00  4926.2  808.38  4931.9  809.28
  4940.7  808.96  4953.7  807.39  4963.5  805.65  4969.8  805.42  4975.5  805.98
  4985.9  803.15  4991.6  799.30  5005.7  798.91  5005.9  798.41  5009.4  798.41
  5009.7  798.91  5013.4  800.47  5029.5  804.33  5035.2  804.70  5055.2  804.31
  5085.1  805.00  5091.2  804.62  5127.1  804.47  5163.1  804.85  5190.8  804.56
#Mann=4,-1,0
  4862.8    0.12       0  5005.7    0.07       0  5009.7    0.12       0
  5163.1    0.05       0
Bank Sta=5005.7,5009.7
Exp/Cntr=0.3,0.1

Type RM Length L Ch R = 1,144,0,0,0
BEGIN DESCRIPTION:
MDW T 091 1.0
END DESCRIPTION:
XS GIS Cut Line= 4
      2276343.64      7140671.07      2276360.53      7140756.66
      2276434.84      7140981.57      2276601.33      7140932.11
#Sta/Elev= 30
  4779.4  811.49  4782.3  810.95  4808.9  809.73  4865.8  805.48  4876.6  805.19
  4881.8  806.26  4908.3  803.97  4913.6  804.31  4922.8  803.62  4933.4  803.65
  4940.0  802.20  4945.3  802.89  4964.9  798.21  4969.8  798.02  4970.0  797.52
  4973.5  797.52  4973.8  798.02  4996.5  800.26  5003.5  801.49  5008.8  801.30
  5017.6  803.63  5035.2  803.43  5040.5  803.88  5108.3  802.99  5170.4  804.39
  5196.7  803.66  5222.6  804.22  5254.5  803.26  5268.3  803.29  5277.2  802.76
#Mann=4,-1,0
  4779.4    0.12       0  4969.8    0.07       0  4973.8    0.12       0
  5254.5    0.05       0
Bank Sta=4969.8,4973.8
Exp/Cntr=0.3,0.1

Chan Stop Cuts=-1