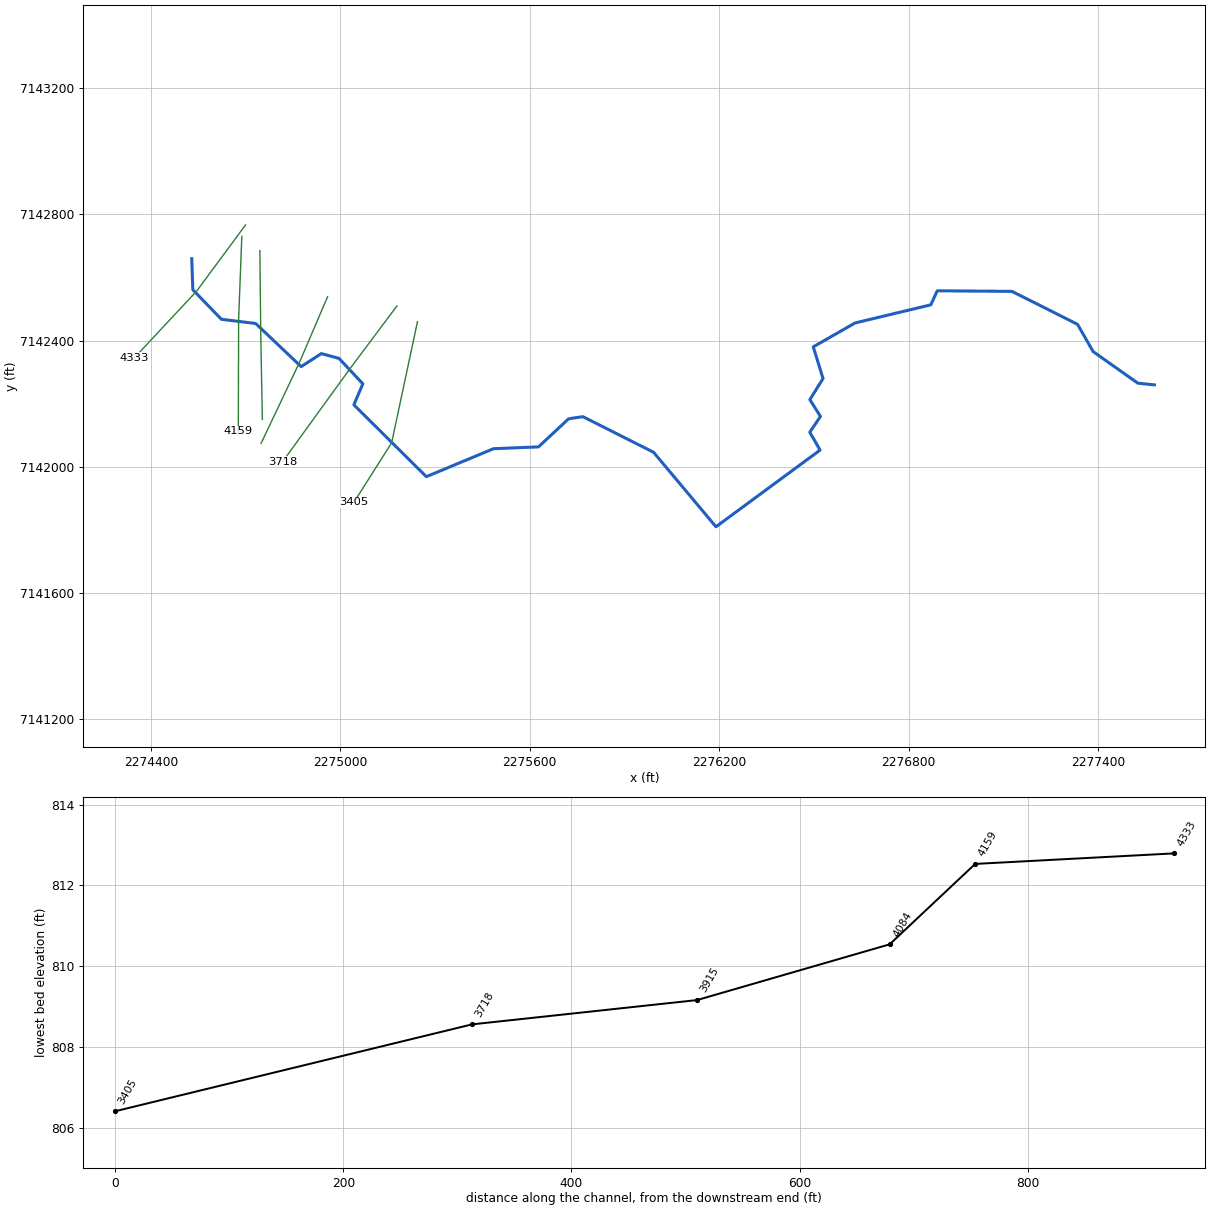
--- MDW T 092.prj (project) ---

Proj Title=MDW T 092 Base Level Engineering
Current Plan=p01
Default Exp/Contr=0.3,0.1
English Units
Geom File=g01
Flow File=f01
Plan File=p01
BEGIN DESCRIPTION:
MDW T 092
END DESCRIPTION:

--- MDW T 092.p01 (plan) ---

Plan Title=Multiple Run
Short Identifier=Multiple
Geom File=g01
Flow File=f01
Subcritical Flow
K Sum by GR= 0
Std Step Tol= 0.01
Critical Tol= 0.01
Num of Std Step Trials= 20
Max Error Tol= 0.3
Flow Tol Ratio= 0.001
Split Flow NTrial= 30
Split Flow Tol= 0.02
Split Flow Ratio= 0.02
Log Output Level= 0
Friction Slope Method= 1
Unsteady Friction Slope Method= 2
Unsteady Bridges Friction Slope Method= 1
Parabolic Critical Depth
Global Vel Dist=  1 , 1 , 1
Global Log Level= 0
CheckData=True
Encroach Param= -1, 0, 0, 0
BEGIN DESCRIPTION:
Multiple Run
END DESCRIPTION:

--- MDW T 092.f01 (steady flow) ---

Flow Title=Multiple
Number of Profiles=7
Profile Names=10-year,25-year,50-year,1pct_min,100-year,1pct_plu,500-year
River Rch & RM= MDW T 092,Reach-1,4333
     555     759     927     563    1122    2240    1649
Boundary for River Rch & Prof#=MDW T 092,Reach-1,1
Up Type=0
Dn Type=3
Dn Slope=0.005
Boundary for River Rch & Prof#=MDW T 092,Reach-1,2
Up Type=0
Dn Type=3
Dn Slope=0.005
Boundary for River Rch & Prof#=MDW T 092,Reach-1,3
Up Type=0
Dn Type=3
Dn Slope=0.005
Boundary for River Rch & Prof#=MDW T 092,Reach-1,4
Up Type=0
Dn Type=3
Dn Slope=0.005
Boundary for River Rch & Prof#=MDW T 092,Reach-1,5
Up Type=0
Dn Type=3
Dn Slope=0.005
Boundary for River Rch & Prof#=MDW T 092,Reach-1,6
Up Type=0
Dn Type=3
Dn Slope=0.005
Boundary for River Rch & Prof#=MDW T 092,Reach-1,7
Up Type=0
Dn Type=3
Dn Slope=0.005

--- MDW T 092.g01 (geometry) ---

Geom Title=Existing Conditions

River Reach=MDW T 092,Reach-1
Reach XY= 30
      2274529.00      7142660.00      2274532.37      7142561.39
      2274622.81      7142467.85      2274731.43      7142454.47
      2274875.59      7142317.82      2274939.64      7142359.11
      2274995.74      7142343.77      2275071.00      7142263.35
      2275042.65      7142196.67      2275272.26      7141969.13
      2275484.94      7142057.73      2275627.53      7142063.56
      2275722.95      7142152.50      2275768.30      7142159.30
      2275992.22      7142046.38      2276189.83      7141810.43
      2276519.72      7142053.32      2276487.03      7142110.00
      2276520.99      7142160.00      2276487.31      7142213.23
      2276529.10      7142280.16      2276498.14      7142380.42
      2276630.58      7142456.18      2276870.50      7142513.56
      2276890.97      7142558.04      2277127.45      7142556.25
      2277335.32      7142451.93      2277384.63      7142365.65
      2277526.49      7142265.33      2277579.00      7142260.00

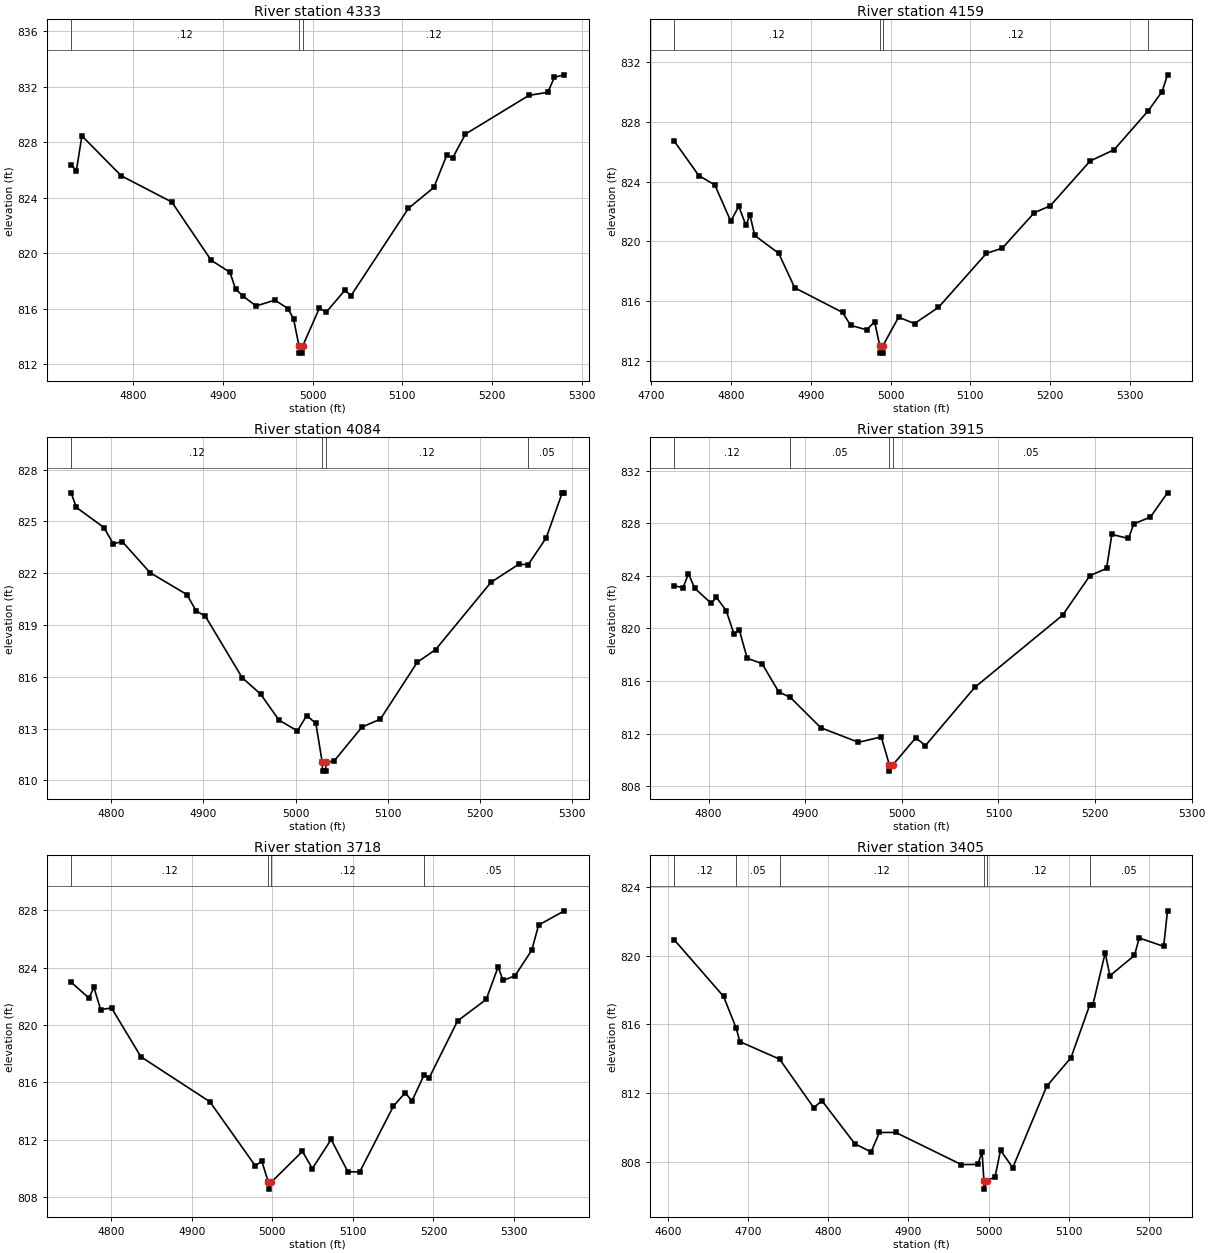
Type RM Length L Ch R = 1,4333,174,174,174
BEGIN DESCRIPTION:
MDW T 092 5.0
END DESCRIPTION:
XS GIS Cut Line= 3
      2274699.41      7142766.70      2274544.39      7142556.93
      2274347.32      7142345.86
#Sta/Elev= 30
  4731.0  826.37  4736.6  825.93  4742.8  828.45  4786.7  825.57  4843.0  823.68
  4886.9  819.48  4907.8  818.62  4914.0  817.42  4922.4  816.89  4937.0  816.19
  4957.9  816.61  4972.5  816.00  4978.7  815.26  4984.8  813.29  4985.1  812.79
  4988.6  812.79  4988.8  813.29  5007.6  816.05  5014.9  815.73  5035.9  817.32
  5042.8  816.94  5106.8  823.23  5135.1  824.73  5149.3  827.04  5156.1  826.87
  5170.3  828.58  5241.1  831.37  5262.1  831.59  5269.5  832.68  5280.6  832.85
#Mann=3,-1,0
  4731.0    0.12       0  4984.8    0.07       0  4988.8    0.12       0
Bank Sta=4984.8,4988.8
Exp/Cntr=0.3,0.1

Type RM Length L Ch R = 1,4159,75,75,75
BEGIN DESCRIPTION:
MDW T 092 4.0
END DESCRIPTION:
XS GIS Cut Line= 3
      2274687.61      7142730.57      2274677.48      7142468.15
      2274676.50      7142113.06
#Sta/Elev= 30
  4729.2  826.69  4759.8  824.40  4779.8  823.78  4799.8  821.35  4809.8  822.35
  4818.8  821.07  4823.8  821.78  4829.8  820.40  4859.9  819.20  4879.9  816.90
  4939.9  815.25  4949.9  814.39  4969.9  814.09  4980.0  814.62  4986.4  813.03
  4986.6  812.53  4990.1  812.53  4990.4  813.03  5010.0  814.93  5030.0  814.51
  5060.0  815.59  5120.0  819.20  5140.0  819.55  5180.0  821.92  5200.0  822.38
  5250.0  825.38  5280.0  826.13  5322.8  828.74  5340.0  830.01  5346.9  831.14
#Mann=4,-1,0
  4729.2    0.12       0  4986.4    0.07       0  4990.4    0.12       0
  5322.8    0.05       0
Bank Sta=4986.4,4990.4
Exp/Cntr=0.3,0.1

Type RM Length L Ch R = 1,4084,169,169,169
BEGIN DESCRIPTION:
MDW T 092 3.5
END DESCRIPTION:
XS GIS Cut Line= 3
      2274744.78      7142685.36      2274747.78      7142407.10
      2274752.70      7142150.32
#Sta/Elev= 30
  4756.6  826.62  4762.0  825.81  4792.0  824.64  4802.0  823.71  4812.0  823.82
  4842.0  822.03  4882.0  820.76  4892.0  819.82  4902.0  819.51  4942.0  815.95
  4962.0  815.00  4982.0  813.49  5002.0  812.87  5012.0  813.76  5022.0  813.30
  5028.9  811.04  5029.2  810.54  5032.7  810.54  5032.9  811.04  5042.0  811.14
  5072.0  813.09  5092.0  813.55  5132.0  816.84  5152.0  817.58  5212.0  821.47
  5242.0  822.51  5252.5  822.50  5272.0  824.05  5289.3  826.65  5291.7  826.65
#Mann=4,-1,0
  4756.6    0.12       0  5028.9    0.07       0  5032.9    0.12       0
  5252.5    0.05       0
Bank Sta=5028.9,5032.9
Exp/Cntr=0.3,0.1

Type RM Length L Ch R = 1,3915,197,197,197
BEGIN DESCRIPTION:
MDW T 092 3.0
END DESCRIPTION:
XS GIS Cut Line= 3
      2274959.30      7142539.26      2274870.18      7142330.93
      2274748.60      7142074.48
#Sta/Elev= 30
  4764.6  823.24  4773.6  823.11  4779.1  824.16  4785.6  823.06  4802.7  821.91
  4808.1  822.37  4818.2  821.35  4826.3  819.58  4831.7  819.90  4839.9  817.74
  4855.3  817.33  4872.6  815.18  4884.5  814.77  4916.1  812.46  4955.1  811.35
  4978.7  811.76  4987.0  809.66  4987.2  809.16  4991.0  809.66  5014.4  811.69
  5024.4  811.10  5075.4  815.52  5166.4  821.01  5194.7  824.02  5211.9  824.56
  5217.4  827.15  5234.6  826.84  5240.1  827.95  5257.3  828.47  5275.0  830.31
#Mann=4,-1,0
  4764.6    0.12       0  4884.5    0.05       0  4987.0   0.033       0
  4991.0    0.05       0
Bank Sta=4987,4991
Exp/Cntr=0.3,0.1

Type RM Length L Ch R = 1,3718,313,313,313
BEGIN DESCRIPTION:
MDW T 092 2.0
END DESCRIPTION:
XS GIS Cut Line= 3
      2275178.97      7142509.96      2275029.55      7142310.28
      2274816.93      7142016.68
#Sta/Elev= 30
  4750.6  822.97  4772.4  821.87  4778.7  822.61  4787.0  821.07  4800.5  821.18
  4837.0  817.78  4922.5  814.65  4978.7  810.20  4987.1  810.49  4995.0  809.06
  4995.3  808.56  4999.0  809.06  5037.4  811.19  5049.7  809.99  5073.0  812.02
  5093.8  809.77  5108.5  809.76  5150.3  814.34  5165.0  815.28  5173.2  814.69
  5188.4  816.52  5194.4  816.28  5229.9  820.28  5265.5  821.78  5280.2  824.04
  5286.4  823.10  5301.1  823.42  5321.9  825.20  5330.5  826.96  5362.5  827.95
#Mann=4,-1,0
  4750.6    0.12       0  4995.0    0.07       0  4999.0    0.12       0
  5188.4    0.05       0
Bank Sta=4995,4999
Exp/Cntr=0.3,0.1

Type RM Length L Ch R = 1,3405,0,0,0
BEGIN DESCRIPTION:
MDW T 092 1.0
END DESCRIPTION:
XS GIS Cut Line= 3
      2275244.02      7142459.85      2275162.33      7142076.66
      2275043.09      7141888.33
#Sta/Elev= 30
  4608.2  820.92  4669.4  817.64  4685.1  815.80  4689.8  815.00  4739.3  813.98
  4781.9  811.15  4792.1  811.56  4833.0  809.06  4853.4  808.57  4863.7  809.71
  4884.1  809.71  4965.9  807.84  4986.4  807.85  4991.7  808.59  4994.0  806.91
  4994.2  806.41  4998.0  806.91  5007.9  807.12  5014.7  808.67  5030.0  807.66
  5072.3  812.40  5102.6  814.07  5126.1  817.16  5129.9  817.15  5145.2  820.17
  5151.1  818.84  5181.7  820.02  5187.6  821.04  5218.1  820.55  5222.9  822.62
#Mann=6,-1,0
  4608.2    0.12       0  4685.1    0.05       0  4739.3    0.12       0
  4994.0    0.07       0  4998.0    0.12       0  5126.1    0.05       0
Bank Sta=4994,4998
Exp/Cntr=0.3,0.1

Chan Stop Cuts=-1