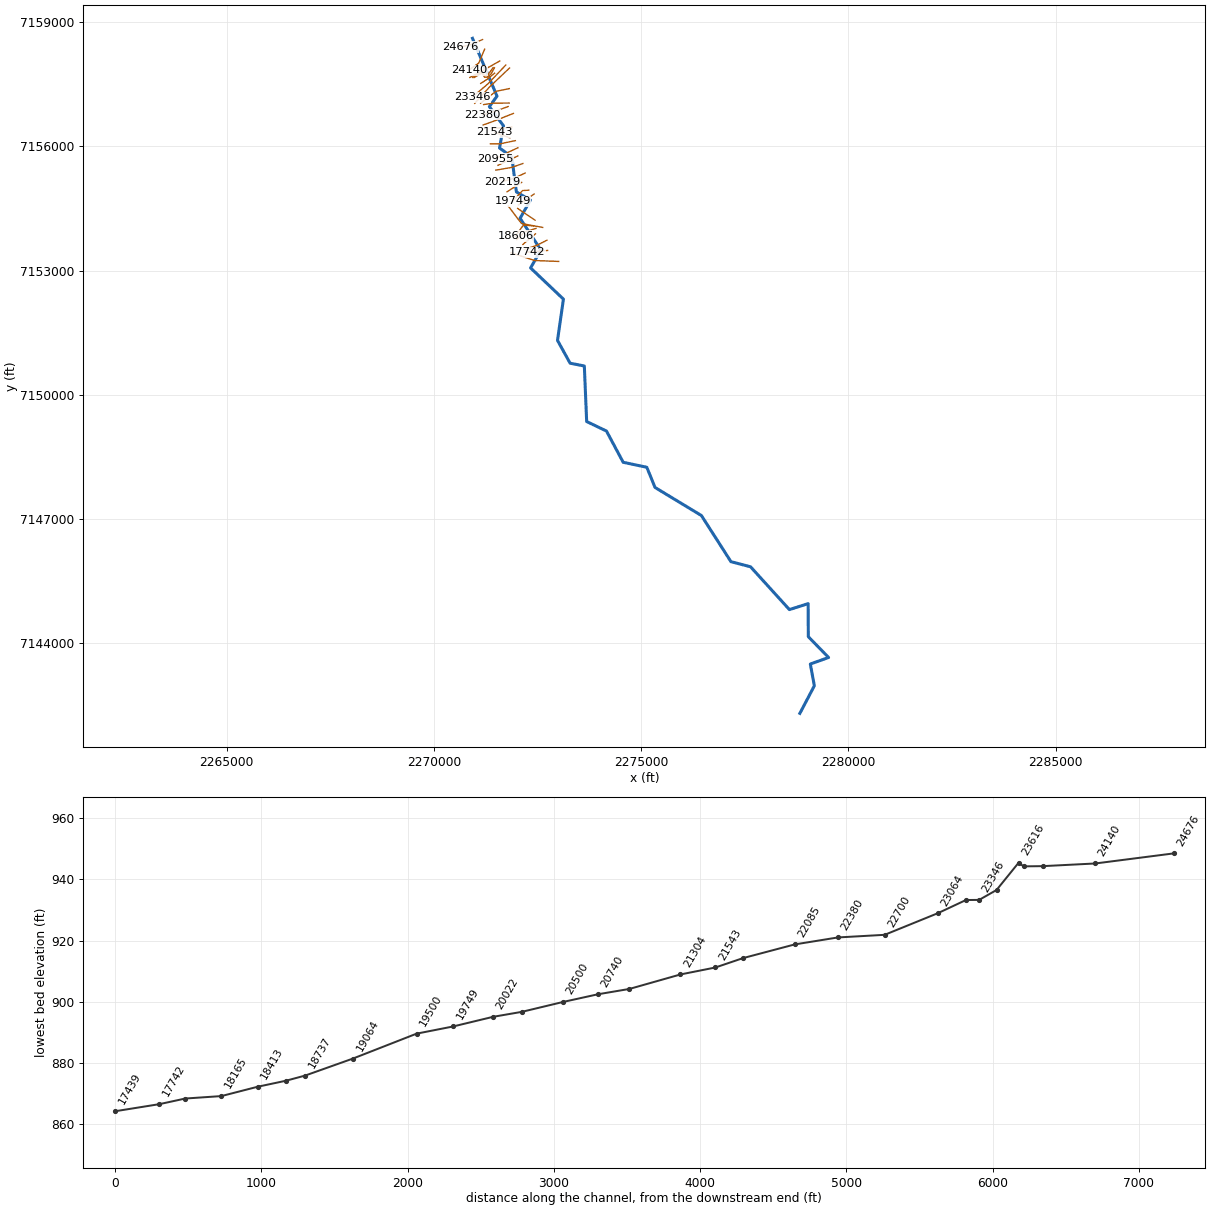
--- MDW T 093.prj (project) ---

Proj Title=MDW T 093 Base Level Engineering
Current Plan=p01
Default Exp/Contr=0.3,0.1
English Units
Geom File=g01
Flow File=f01
Plan File=p01
BEGIN DESCRIPTION:
MDW T 093
END DESCRIPTION:

--- MDW T 093.p01 (plan) ---

Plan Title=Multiple Run
Short Identifier=Multiple
Geom File=g01
Flow File=f01
Subcritical Flow
K Sum by GR= 0
Std Step Tol= 0.01
Critical Tol= 0.01
Num of Std Step Trials= 20
Max Error Tol= 0.3
Flow Tol Ratio= 0.001
Split Flow NTrial= 30
Split Flow Tol= 0.02
Split Flow Ratio= 0.02
Log Output Level= 0
Friction Slope Method= 1
Unsteady Friction Slope Method= 2
Unsteady Bridges Friction Slope Method= 1
Parabolic Critical Depth
Global Vel Dist=  1 , 1 , 1
Global Log Level= 0
CheckData=True
Encroach Param= -1, 0, 0, 0
BEGIN DESCRIPTION:
Multiple Run
END DESCRIPTION:

--- MDW T 093.f01 (steady flow) ---

Flow Title=Multiple
Number of Profiles=7
Profile Names=10-year,25-year,50-year,1pct_min,100-year,1pct_plu,500-year
River Rch & RM= MDW T 093,Reach-1,24676
     717     994    1226     750    1497    2987    2238
River Rch & RM= MDW T 093,Reach-1,18606
    1159    1649    2069    1287    2569    5125    3968
River Rch & RM= MDW T 093,Reach-1,15999
    1327    1900    2395    1496    2984    5954    4646
River Rch & RM= MDW T 093,Reach-1,14290
    1502    2162    2734    1712    3417    6817    5351
River Rch & RM= MDW T 093,Reach-1,11785
    1634    2348    2964    1852    3696    7374    5762
River Rch & RM= MDW T 093,Reach-1,3181
    2049    2982    3797    2391    4771    9519    7557
Boundary for River Rch & Prof#=MDW T 093,Reach-1,1
Up Type=0
Dn Type=3
Dn Slope=0.005
Boundary for River Rch & Prof#=MDW T 093,Reach-1,2
Up Type=0
Dn Type=3
Dn Slope=0.005
Boundary for River Rch & Prof#=MDW T 093,Reach-1,3
Up Type=0
Dn Type=3
Dn Slope=0.005
Boundary for River Rch & Prof#=MDW T 093,Reach-1,4
Up Type=0
Dn Type=3
Dn Slope=0.005
Boundary for River Rch & Prof#=MDW T 093,Reach-1,5
Up Type=0
Dn Type=3
Dn Slope=0.005
Boundary for River Rch & Prof#=MDW T 093,Reach-1,6
Up Type=0
Dn Type=3
Dn Slope=0.005
Boundary for River Rch & Prof#=MDW T 093,Reach-1,7
Up Type=0
Dn Type=3
Dn Slope=0.005

--- MDW T 093.g01 (geometry) ---

Geom Title=Existing Conditions

River Reach=MDW T 093,Reach-1
Reach XY= 30
      2270929.00      7158610.00      2271520.95      7157213.29
      2271336.17      7156959.70      2271677.39      7156498.19
      2271582.44      7155961.22      2271876.92      7155747.99
      2271989.98      7154899.63      2272327.39      7154703.97
      2272078.02      7154265.42      2272578.40      7153499.38
      2272330.93      7153065.98      2273123.64      7152312.70
      2272980.75      7151316.16      2273284.61      7150765.59
      2273627.97      7150698.33      2273684.36      7149357.22
      2274162.51      7149127.05      2274565.26      7148373.20
      2275135.51      7148252.37      2275334.63      7147764.77
      2276452.97      7147087.19      2277165.68      7145973.37
      2277638.80      7145849.52      2278576.70      7144815.83
      2279029.00      7144960.00      2279032.75      7144161.55
      2279521.94      7143660.00      2279081.62      7143501.54
      2279178.34      7142975.83      2278829.00      7142310.00

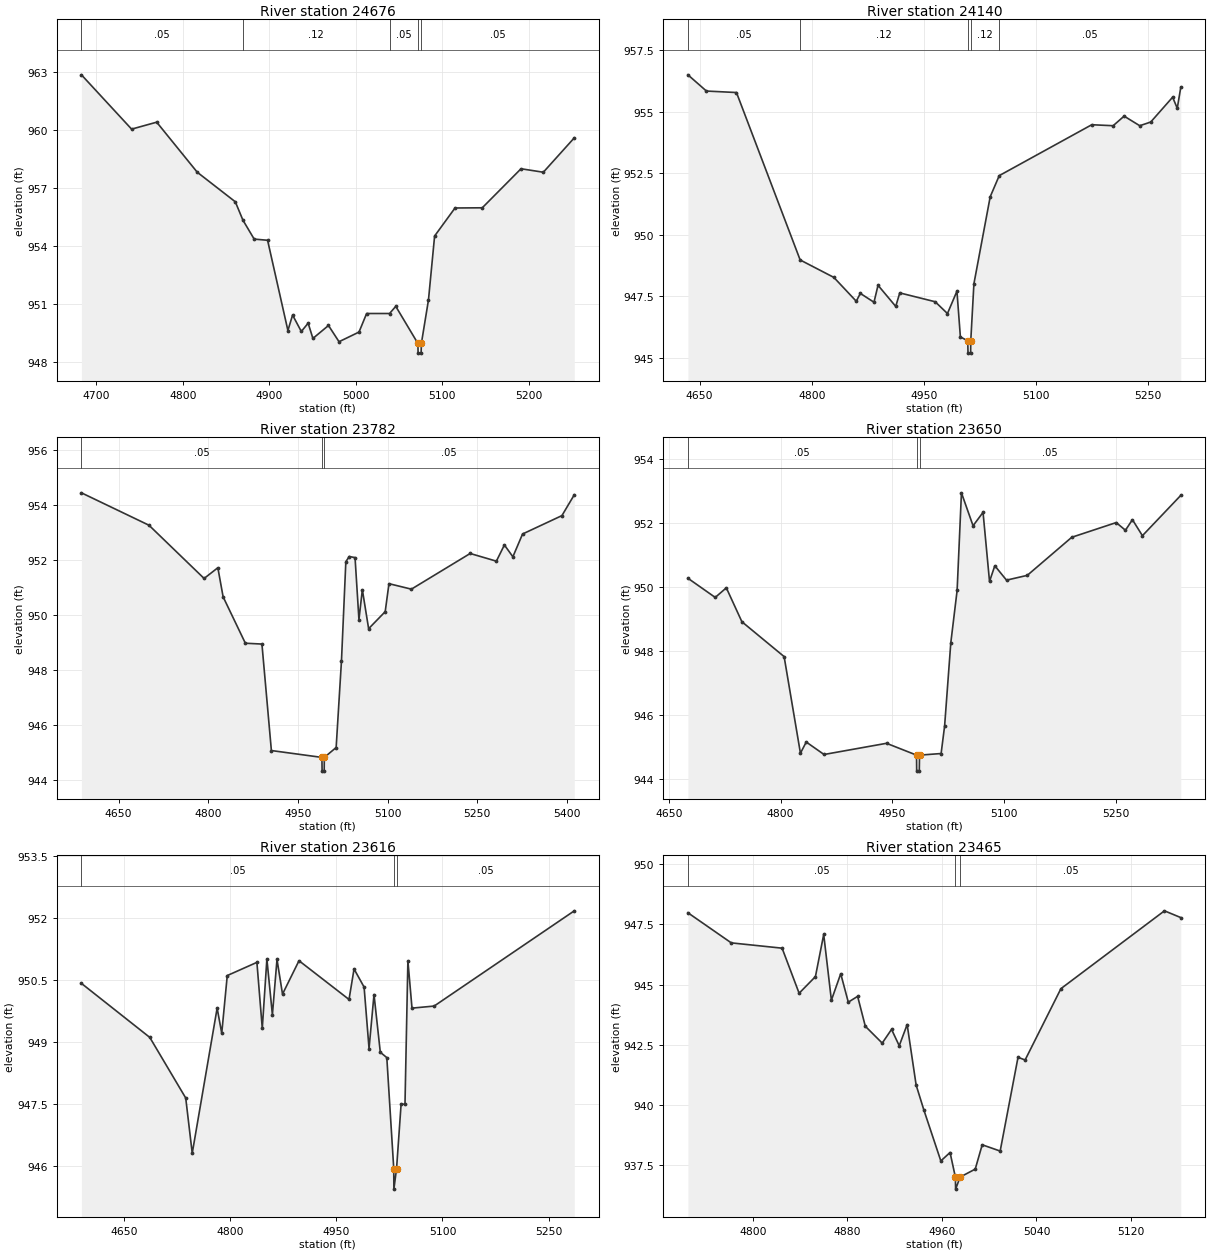
Type RM Length L Ch R = 1,24676,536,536,536
BEGIN DESCRIPTION:
MDW T 093 53.0
END DESCRIPTION:
XS GIS Cut Line= 3
      2271172.23      7158580.31      2270881.14      7158454.03
      2270633.98      7158402.34
#Sta/Elev= 30
  4682.7  962.87  4740.7  960.06  4769.7  960.42  4816.6  957.83  4860.6  956.30
  4869.4  955.35  4882.4  954.37  4897.9  954.31  4921.4  949.64  4926.8  950.44
  4936.9  949.59  4944.8  950.02  4950.3  949.23  4968.3  949.90  4980.5  949.06
  5003.6  949.56  5012.4  950.52  5038.9  950.52  5046.1  950.89  5071.7  948.97
  5071.9  948.47  5075.4  948.47  5075.7  948.97  5083.9  951.22  5091.0  954.53
  5114.6  955.98  5146.1  955.99  5190.9  958.01  5216.7  957.83  5252.5  959.61
#Mann=5,-1,0
  4682.7    0.05       0  4869.4    0.12       0  5038.9    0.05       0
  5071.7    0.07       0  5075.7    0.05       0
Bank Sta=5071.7,5075.7
Exp/Cntr=0.3,0.1

Type RM Length L Ch R = 1,24140,358,358,358
BEGIN DESCRIPTION:
MDW T 093 52.0
END DESCRIPTION:
XS GIS Cut Line= 3
      2271222.79      7158349.89      2271080.42      7158013.04
      2270842.63      7157840.49
#Sta/Elev= 30
  4634.3  956.50  4659.1  955.84  4699.3  955.78  4784.5  948.97  4829.6  948.26
  4859.6  947.29  4865.0  947.61  4883.3  947.25  4888.7  947.94  4912.4  947.08
  4917.8  947.63  4965.2  947.27  4981.6  946.79  4994.3  947.70  4998.9  945.84
  5008.8  945.68  5009.1  945.18  5012.6  945.18  5012.8  945.68  5017.0  948.00
  5038.8  951.54  5050.9  952.40  5174.7  954.47  5203.3  954.43  5218.0  954.82
  5238.9  954.43  5253.6  954.58  5282.9  955.59  5289.1  955.14  5293.8  955.99
#Mann=5,-1,0
  4634.3    0.05       0  4784.5    0.12       0  5008.8    0.07       0
  5012.8    0.12       0  5050.9    0.05       0
Bank Sta=5008.8,5012.8
Exp/Cntr=0.3,0.1

Type RM Length L Ch R = 1,23782,132,132,132
BEGIN DESCRIPTION:
MDW T 093 51.0
END DESCRIPTION:
XS GIS Cut Line= 3
      2271587.36      7158063.46      2271229.00      7157860.00
      2270866.03      7157665.04
#Sta/Elev= 30
  4588.0  954.45  4700.9  953.27  4793.1  951.33  4816.1  951.72  4824.9  950.66
  4862.1  948.97  4889.8  948.94  4905.6  945.06  4990.1  944.81  4990.4  944.31
  4993.9  944.31  4994.1  944.81  5013.9  945.17  5022.8  948.33  5030.1  951.94
  5035.8  952.13  5045.5  952.09  5052.0  949.83  5057.7  950.92  5068.2  949.50
  5095.9  950.12  5102.2  951.14  5139.7  950.94  5238.0  952.24  5281.8  951.96
  5295.2  952.55  5309.4  952.12  5325.6  952.95  5391.4  953.62  5412.1  954.38
#Mann=3,-1,0
  4588.0    0.05       0  4990.1   0.033       0  4994.1    0.05       0
Bank Sta=4990.1,4994.1
Exp/Cntr=0.3,0.1

Type RM Length L Ch R = 1,23650,34,34,34
BEGIN DESCRIPTION:
Mapping XS 6acb66af
END DESCRIPTION:
XS GIS Cut Line= 6
      2271425.87      7157903.90      2271320.56      7157753.03
      2271269.55      7157717.78      2271218.26      7157712.50
      2271169.16      7157794.76      2270933.88      7157665.50
#Sta/Elev= 30
  4675.6  950.27  4712.3  949.67  4727.2  949.97  4748.1  948.91  4804.8  947.82
  4826.7  944.80  4834.5  945.15  4858.4  944.76  4942.3  945.11  4982.6  944.74
  4982.8  944.24  4986.3  944.24  4986.6  944.74  5015.6  944.79  5020.3  945.65
  5028.6  948.25  5037.1  949.89  5042.9  952.94  5058.5  951.91  5071.9  952.33
  5080.6  950.17  5087.7  950.66  5103.4  950.21  5131.3  950.36  5191.0  951.55
  5250.7  952.01  5263.1  951.77  5272.5  952.10  5285.9  951.60  5337.4  952.86
#Mann=3,-1,0
  4675.6    0.05       0  4982.6   0.033       0  4986.6    0.05       0
Bank Sta=4982.6,4986.6
Exp/Cntr=0.3,0.1

Type RM Length L Ch R = 1,23616,151,151,151
BEGIN DESCRIPTION:
Mapping XS 1adfffe7
END DESCRIPTION:
XS GIS Cut Line= 6
      2271459.97      7157899.78      2271380.08      7157751.44
      2271287.52      7157674.39      2271223.61      7157669.03
      2271156.01      7157771.54      2270967.85      7157661.87
#Sta/Elev= 30
  4589.7  950.42  4686.3  949.11  4737.1  947.64  4746.3  946.30  4781.5  949.82
  4788.0  949.21  4795.8  950.61  4837.7  950.93  4845.3  949.33  4851.8  951.01
  4859.6  949.66  4866.1  951.00  4873.9  950.16  4897.2  950.97  4967.9  950.03
  4975.0  950.77  4989.2  950.33  4996.2  948.84  5003.2  950.15  5012.1  948.75
  5021.3  948.62  5031.1  945.93  5031.3  945.43  5035.1  945.93  5041.5  947.49
  5047.0  947.49  5051.1  950.97  5056.9  949.82  5088.2  949.87  5286.3  952.18
#Mann=3,-1,0
  4589.7    0.05       0  5031.1   0.033       0  5035.1    0.05       0
Bank Sta=5031.1,5035.1
Exp/Cntr=0.3,0.1

Type RM Length L Ch R = 1,23465,119,119,119
BEGIN DESCRIPTION:
Mapping XS 06c444ed
END DESCRIPTION:
XS GIS Cut Line= 3
      2271462.53      7157768.08      2271284.02      7157621.99
      2271127.73      7157520.54
#Sta/Elev= 30
  4745.1  947.98  4781.8  946.73  4824.8  946.51  4839.2  944.64  4853.0  945.33
  4860.0  947.08  4866.5  944.35  4874.4  945.45  4880.8  944.27  4888.7  944.51
  4895.2  943.27  4909.5  942.57  4917.4  943.14  4923.9  942.46  4930.6  943.34
  4938.2  940.83  4944.7  939.80  4959.1  937.68  4966.9  938.03  4971.4  937.01
  4971.6  936.51  4975.4  937.01  4988.2  937.34  4994.1  938.35  5009.3  938.09
  5024.4  941.98  5030.4  941.87  5060.7  944.83  5148.3  948.06  5162.1  947.78
#Mann=3,-1,0
  4745.1    0.05       0  4971.4   0.033       0  4975.4    0.05       0
Bank Sta=4971.4,4975.4
Exp/Cntr=0.3,0.1

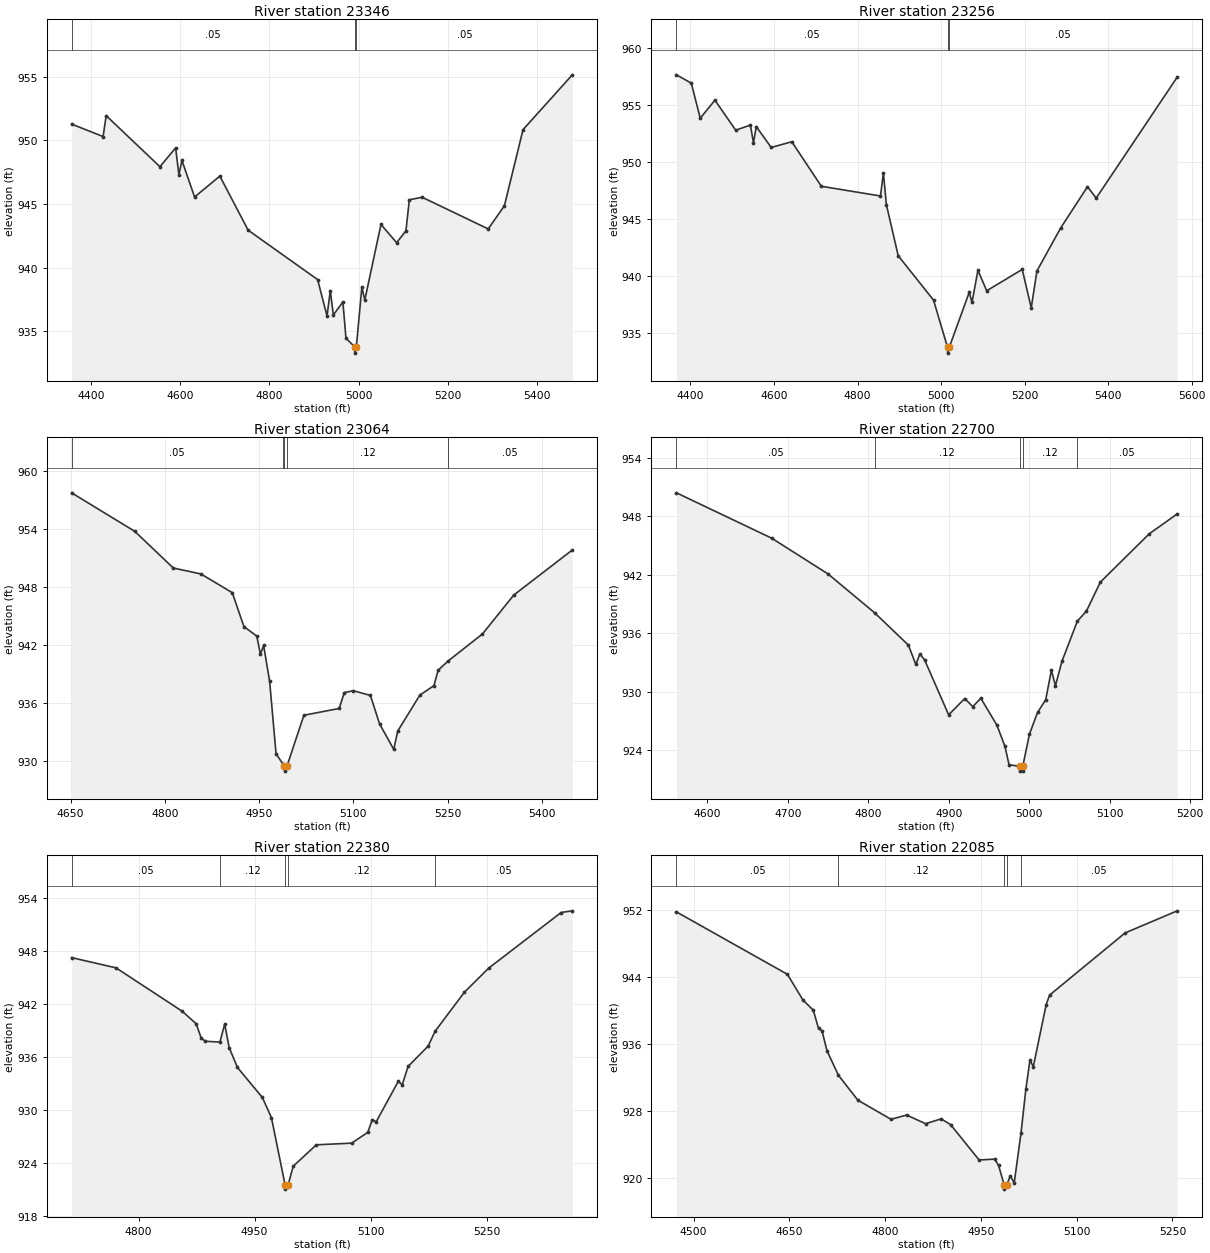
Type RM Length L Ch R = 1,23346,90,90,90
BEGIN DESCRIPTION:
MDW T 093 50.0
END DESCRIPTION:
XS GIS Cut Line= 3
      2271733.17      7157965.70      2271304.14      7157512.71
      2270924.12      7157189.64
#Sta/Elev= 30
  4356.6  951.28  4427.3  950.30  4434.2  951.94  4554.7  947.93  4589.9  949.41
  4597.2  947.30  4604.0  948.42  4632.4  945.55  4689.0  947.19  4752.5  942.94
  4908.2  939.06  4929.3  936.20  4936.6  938.18  4943.5  936.28  4964.9  937.30
  4971.8  934.45  4991.1  933.78  4991.4  933.28  4995.1  933.78  5007.4  938.47
  5014.0  937.45  5050.2  943.39  5085.4  941.96  5106.2  942.89  5113.9  945.33
  5142.5  945.53  5290.7  943.04  5327.0  944.86  5368.7  950.84  5479.3  955.15
#Mann=3,-1,0
  4356.6    0.05       0  4991.1   0.033       0  4995.1    0.05       0
Bank Sta=4991.1,4995.1
Exp/Cntr=0.3,0.1

Type RM Length L Ch R = 1,23256,192,192,192
BEGIN DESCRIPTION:
MDW T 093 49.5
END DESCRIPTION:
XS GIS Cut Line= 3
      2271824.37      7157894.98      2271350.16      7157445.00
      2270984.13      7157040.85
#Sta/Elev= 30
  4366.5  957.61  4402.0  956.88  4423.4  953.81  4458.6  955.39  4508.3  952.76
  4543.5  953.21  4550.8  951.66  4557.7  953.07  4593.3  951.25  4642.6  951.75
  4713.4  947.85  4855.0  947.00  4861.9  949.03  4869.1  946.24  4897.4  941.77
  4982.0  937.88  5015.6  933.74  5015.8  933.24  5019.6  933.74  5067.4  938.56
  5074.1  937.68  5088.3  940.49  5109.3  938.70  5194.4  940.57  5215.9  937.20
  5229.6  940.44  5286.4  944.20  5350.6  947.81  5371.5  946.82  5565.5  957.41
#Mann=3,-1,0
  4366.5    0.05       0  5015.6   0.033       0  5019.6    0.05       0
Bank Sta=5015.6,5019.6
Exp/Cntr=0.3,0.1

Type RM Length L Ch R = 1,23064,364,364,364
BEGIN DESCRIPTION:
MDW T 093 49.0
END DESCRIPTION:
XS GIS Cut Line= 3
      2271817.47      7157396.75      2271490.95      7157328.34
      2271125.05      7157044.16
#Sta/Elev= 30
  4651.5  957.77  4752.1  953.78  4813.4  949.98  4857.2  949.37  4907.2  947.43
  4925.8  943.91  4946.2  942.93  4952.0  941.05  4957.1  941.97  4966.7  938.23
  4976.9  930.74  4987.5  929.71  4990.2  929.44  4990.5  928.94  4994.2  929.44
  5021.2  934.73  5077.3  935.43  5085.5  937.07  5099.9  937.27  5127.1  936.78
  5141.6  933.84  5164.2  931.19  5170.5  933.09  5205.8  936.82  5228.1  937.79
  5234.8  939.39  5250.9  940.36  5305.4  943.15  5355.2  947.18  5448.4  951.85
#Mann=5,-1,0
  4651.5    0.05       0  4987.5    0.12       0  4990.2    0.07       0
  4994.2    0.12       0  5250.9    0.05       0
Bank Sta=4990.2,4994.2
Exp/Cntr=0.3,0.1

Type RM Length L Ch R = 1,22700,320,320,320
BEGIN DESCRIPTION:
MDW T 093 48.0
END DESCRIPTION:
XS GIS Cut Line= 3
      2271817.42      7157047.79      2271403.79      7157043.96
      2271197.69      7157009.60
#Sta/Elev= 30
  4561.6  950.39  4680.0  945.74  4750.0  942.08  4807.9  938.10  4850.0  934.78
  4859.2  932.80  4864.2  933.87  4870.0  933.29  4900.0  927.64  4920.0  929.31
  4930.0  928.48  4940.0  929.34  4960.0  926.58  4970.0  924.41  4975.1  922.52
  4988.2  922.37  4988.5  921.87  4992.0  921.87  4992.2  922.37  5000.4  925.64
  5010.5  927.88  5020.7  929.19  5027.7  932.20  5032.8  930.63  5040.9  933.13
  5060.0  937.24  5071.3  938.27  5088.6  941.24  5149.4  946.19  5184.2  948.23
#Mann=5,-1,0
  4561.6    0.05       0  4807.9    0.12       0  4988.2    0.07       0
  4992.2    0.12       0  5060.0    0.05       0
Bank Sta=4988.2,4992.2
Exp/Cntr=0.3,0.1

Type RM Length L Ch R = 1,22380,295,295,295
BEGIN DESCRIPTION:
MDW T 093 47.0
END DESCRIPTION:
XS GIS Cut Line= 3
      2271789.69      7156964.46      2271521.52      7156863.62
      2271175.12      7156763.07
#Sta/Elev= 30
  4713.5  947.24  4770.9  946.08  4856.2  941.18  4874.5  939.75  4881.1  938.11
  4886.5  937.76  4905.2  937.67  4911.4  939.71  4917.2  937.04  4927.9  934.79
  4960.0  931.40  4971.8  929.11  4989.4  921.51  4989.6  921.01  4993.4  921.51
  5000.0  923.61  5029.8  926.03  5075.5  926.22  5096.3  927.44  5102.1  928.87
  5107.3  928.66  5135.7  933.21  5140.9  932.85  5148.4  934.91  5174.4  937.22
  5183.4  938.91  5221.3  943.33  5252.5  946.04  5346.2  952.35  5360.7  952.54
#Mann=5,-1,0
  4713.5    0.05       0  4905.2    0.12       0  4989.4    0.07       0
  4993.4    0.12       0  5183.4    0.05       0
Bank Sta=4989.4,4993.4
Exp/Cntr=0.3,0.1

Type RM Length L Ch R = 1,22085,354,354,354
BEGIN DESCRIPTION:
MDW T 093 46.0
END DESCRIPTION:
XS GIS Cut Line= 3
      2271918.19      7156797.81      2271428.32      7156604.33
      2271185.51      7156518.28
#Sta/Elev= 30
  4473.3  951.73  4647.1  944.30  4671.4  941.24  4687.5  940.04  4695.8  937.86
  4701.2  937.59  4709.0  935.21  4726.9  932.29  4757.4  929.32  4809.4  927.04
  4833.7  927.55  4863.5  926.52  4887.8  927.09  4902.5  926.42  4947.3  922.20
  4971.7  922.30  4977.8  921.55  4986.5  919.23  4986.8  918.73  4990.5  919.23
  4996.0  920.29  5002.3  919.49  5012.9  925.38  5020.5  930.61  5026.9  934.08
  5032.2  933.32  5052.3  940.68  5057.7  941.83  5176.0  949.23  5257.6  951.86
#Mann=5,-1,0
  4473.3    0.05       0  4726.9    0.12       0  4986.5    0.07       0
  4990.5    0.12       0  5012.9    0.05       0
Bank Sta=4986.5,4990.5
Exp/Cntr=0.3,0.1

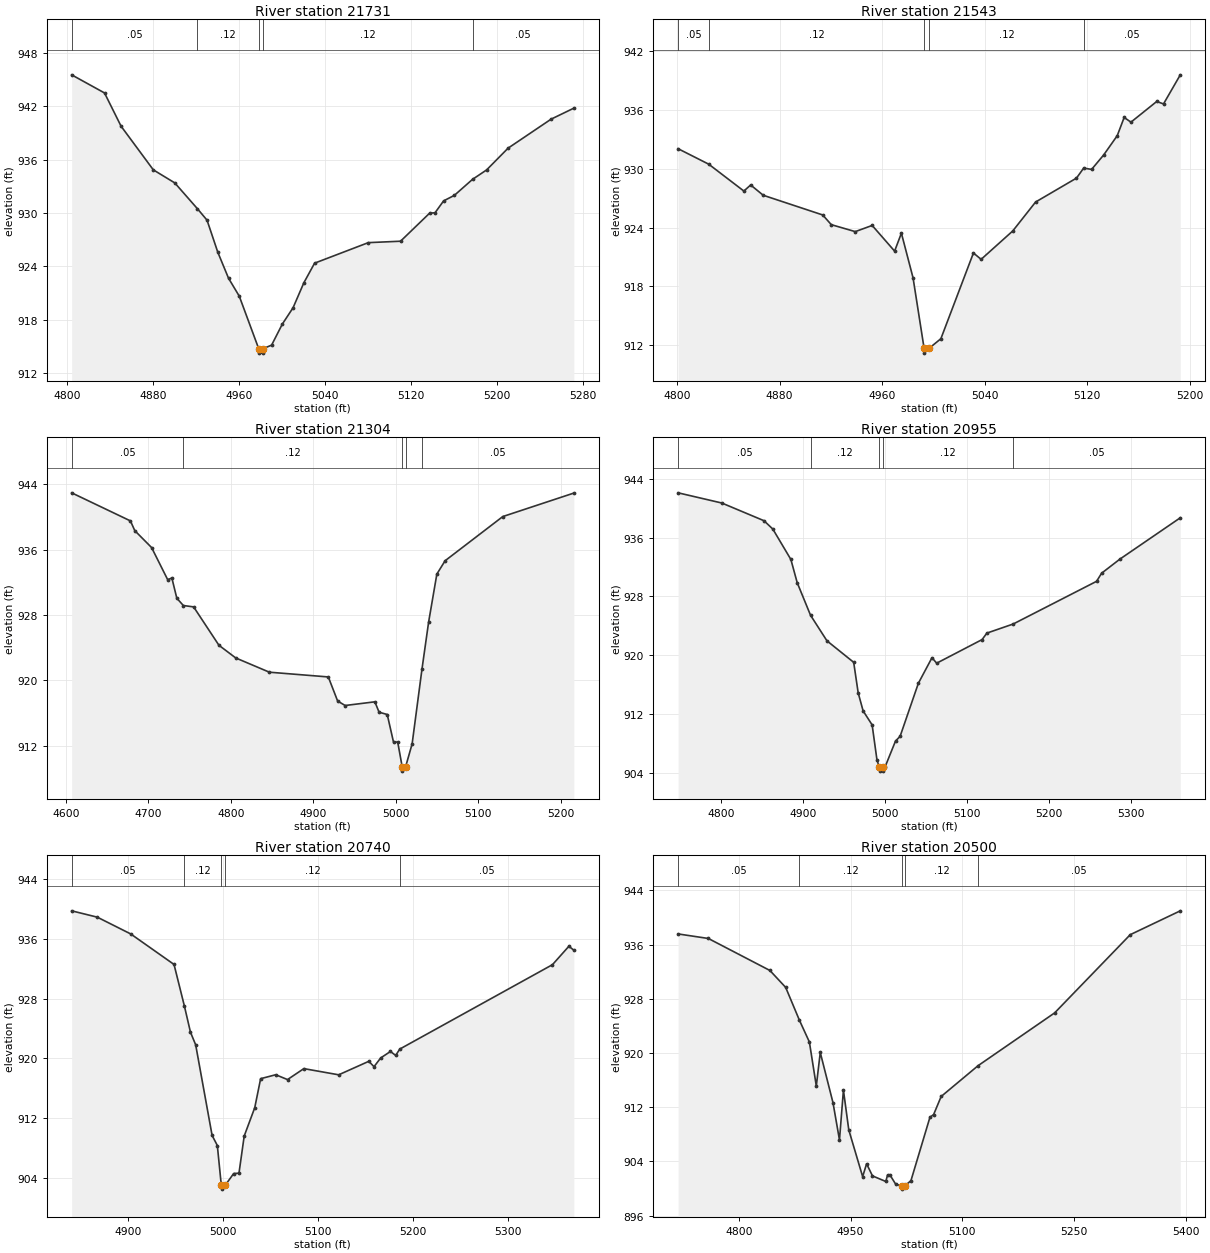
Type RM Length L Ch R = 1,21731,188,188,188
BEGIN DESCRIPTION:
Mapping XS 8e694273
END DESCRIPTION:
XS GIS Cut Line= 2
      2271874.97      7156455.99      2271407.82      7156440.67
#Sta/Elev= 30
  4804.4  945.56  4835.0  943.52  4850.4  939.78  4880.4  934.87  4900.4  933.40
  4921.5  930.49  4930.4  929.21  4940.4  925.61  4950.4  922.68  4960.4  920.66
  4978.5  914.75  4978.7  914.25  4982.2  914.25  4982.5  914.75  4990.5  915.15
  5000.5  917.52  5010.5  919.36  5020.5  922.16  5030.5  924.37  5080.5  926.68
  5110.5  926.84  5137.6  930.00  5142.6  930.04  5150.6  931.38  5160.6  932.00
  5177.5  933.80  5190.6  934.86  5210.6  937.31  5250.6  940.57  5271.8  941.81
#Mann=5,-1,0
  4804.4    0.05       0  4921.5    0.12       0  4978.5    0.07       0
  4982.5    0.12       0  5177.5    0.05       0
Bank Sta=4978.5,4982.5
Exp/Cntr=0.3,0.1

Type RM Length L Ch R = 1,21543,239,239,239
BEGIN DESCRIPTION:
Mapping XS 3d0736d9
END DESCRIPTION:
XS GIS Cut Line= 2
      2271831.48      7156207.38      2271462.73      7156339.80
#Sta/Elev= 30
  4800.9  932.06  4824.8  930.48  4852.2  927.74  4857.5  928.36  4867.3  927.31
  4913.7  925.30  4920.4  924.31  4939.1  923.60  4952.3  924.23  4969.8  921.61
  4975.1  923.44  4984.2  918.88  4992.8  911.70  4993.0  911.20  4996.8  911.70
  5005.9  912.67  5031.3  921.42  5037.3  920.77  5062.0  923.67  5079.8  926.62
  5111.7  929.06  5117.3  930.08  5123.5  929.95  5132.9  931.42  5143.5  933.39
  5148.9  935.25  5154.2  934.77  5174.3  936.88  5179.6  936.63  5192.7  939.60
#Mann=5,-1,0
  4800.9    0.05       0  4824.8    0.12       0  4992.8    0.07       0
  4996.8    0.12       0  5117.3    0.05       0
Bank Sta=4992.8,4996.8
Exp/Cntr=0.3,0.1

Type RM Length L Ch R = 1,21304,349,349,349
BEGIN DESCRIPTION:
MDW T 093 44.0
END DESCRIPTION:
XS GIS Cut Line= 3
      2271963.99      7156139.34      2271579.00      7156060.00
      2271362.82      7156063.80
#Sta/Elev= 30
  4606.8  942.93  4678.1  939.50  4683.4  938.31  4703.8  936.24  4723.3  932.32
  4728.4  932.52  4734.4  930.05  4742.3  929.16  4754.8  928.99  4785.5  924.30
  4805.9  922.75  4846.7  921.01  4918.2  920.43  4929.5  917.49  4938.6  916.94
  4974.7  917.39  4979.8  916.12  4989.7  915.84  4997.3  912.47  5002.4  912.47
  5007.9  909.42  5008.1  908.92  5011.9  909.42  5019.9  912.25  5031.8  921.35
  5039.9  927.13  5049.9  933.00  5059.9  934.63  5129.9  940.03  5216.1  942.90
#Mann=5,-1,0
  4606.8    0.05       0  4742.3    0.12       0  5007.9    0.07       0
  5011.9    0.12       0  5031.8    0.05       0
Bank Sta=5007.9,5011.9
Exp/Cntr=0.3,0.1

Type RM Length L Ch R = 1,20955,215,215,215
BEGIN DESCRIPTION:
MDW T 093 43.0
END DESCRIPTION:
XS GIS Cut Line= 3
      2272023.89      7155966.60      2271794.89      7155861.19
      2271473.31      7155698.70
#Sta/Elev= 30
  4747.9  942.12  4801.2  940.73  4852.6  938.32  4863.4  937.18  4885.4  933.04
  4893.1  929.88  4909.4  925.43  4929.4  921.95  4962.0  919.02  4967.5  914.85
  4973.5  912.40  4984.5  910.49  4990.4  905.71  4993.4  904.69  4993.7  904.19
  4997.2  904.19  4997.4  904.69  5000.0  904.69  5013.0  908.29  5018.6  908.93
  5040.9  916.17  5057.5  919.65  5063.2  918.90  5118.6  922.12  5124.4  923.00
  5156.5  924.24  5258.2  930.06  5264.3  931.16  5286.7  933.09  5360.3  938.72
#Mann=5,-1,0
  4747.9    0.05       0  4909.4    0.12       0  4993.4    0.07       0
  4997.4    0.12       0  5156.5    0.05       0
Bank Sta=4993.4,4997.4
Exp/Cntr=0.3,0.1

Type RM Length L Ch R = 1,20740,240,240,240
BEGIN DESCRIPTION:
Mapping XS 92370105
END DESCRIPTION:
XS GIS Cut Line= 2
      2272023.41      7155770.03      2271544.98      7155544.79
#Sta/Elev= 30
  4840.4  939.77  4867.4  938.92  4902.6  936.67  4948.2  932.58  4959.2  926.96
  4965.5  923.50  4971.0  921.80  4988.3  909.65  4993.8  908.30  4998.0  902.95
  4998.3  902.45  5002.0  902.95  5011.0  904.54  5016.6  904.59  5022.1  909.57
  5033.2  913.37  5039.4  917.26  5055.3  917.79  5067.7  917.14  5084.9  918.61
  5121.6  917.78  5153.3  919.59  5158.8  918.87  5165.8  920.04  5176.1  920.91
  5181.6  920.38  5185.9  921.23  5346.7  932.55  5364.0  935.02  5369.2  934.49
#Mann=5,-1,0
  4840.4    0.05       0  4959.2    0.12       0  4998.0    0.07       0
  5002.0    0.12       0  5185.9    0.05       0
Bank Sta=4998,5002
Exp/Cntr=0.3,0.1

Type RM Length L Ch R = 1,20500,281,281,281
BEGIN DESCRIPTION:
MDW T 093 42.0
END DESCRIPTION:
XS GIS Cut Line= 3
      2272145.40      7155587.25      2271879.52      7155494.78
      2271492.84      7155426.86
#Sta/Elev= 30
  4718.5  937.57  4759.1  936.90  4841.7  932.18  4862.9  929.68  4881.4  924.82
  4894.7  921.63  4904.0  915.13  4909.3  920.08  4926.4  912.67  4935.1  907.18
  4940.4  914.52  4947.6  908.65  4966.2  901.76  4971.5  903.66  4979.4  901.87
  4997.3  901.05  4999.7  902.02  5002.8  902.02  5010.7  900.62  5018.8  900.42
  5019.1  899.92  5022.8  900.42  5031.0  901.16  5056.5  910.51  5061.5  910.93
  5071.6  913.59  5121.1  918.13  5223.9  925.92  5325.4  937.46  5392.6  940.98
#Mann=5,-1,0
  4718.5    0.05       0  4881.4    0.12       0  5018.8    0.07       0
  5022.8    0.12       0  5121.1    0.05       0
Bank Sta=5018.8,5022.8
Exp/Cntr=0.3,0.1

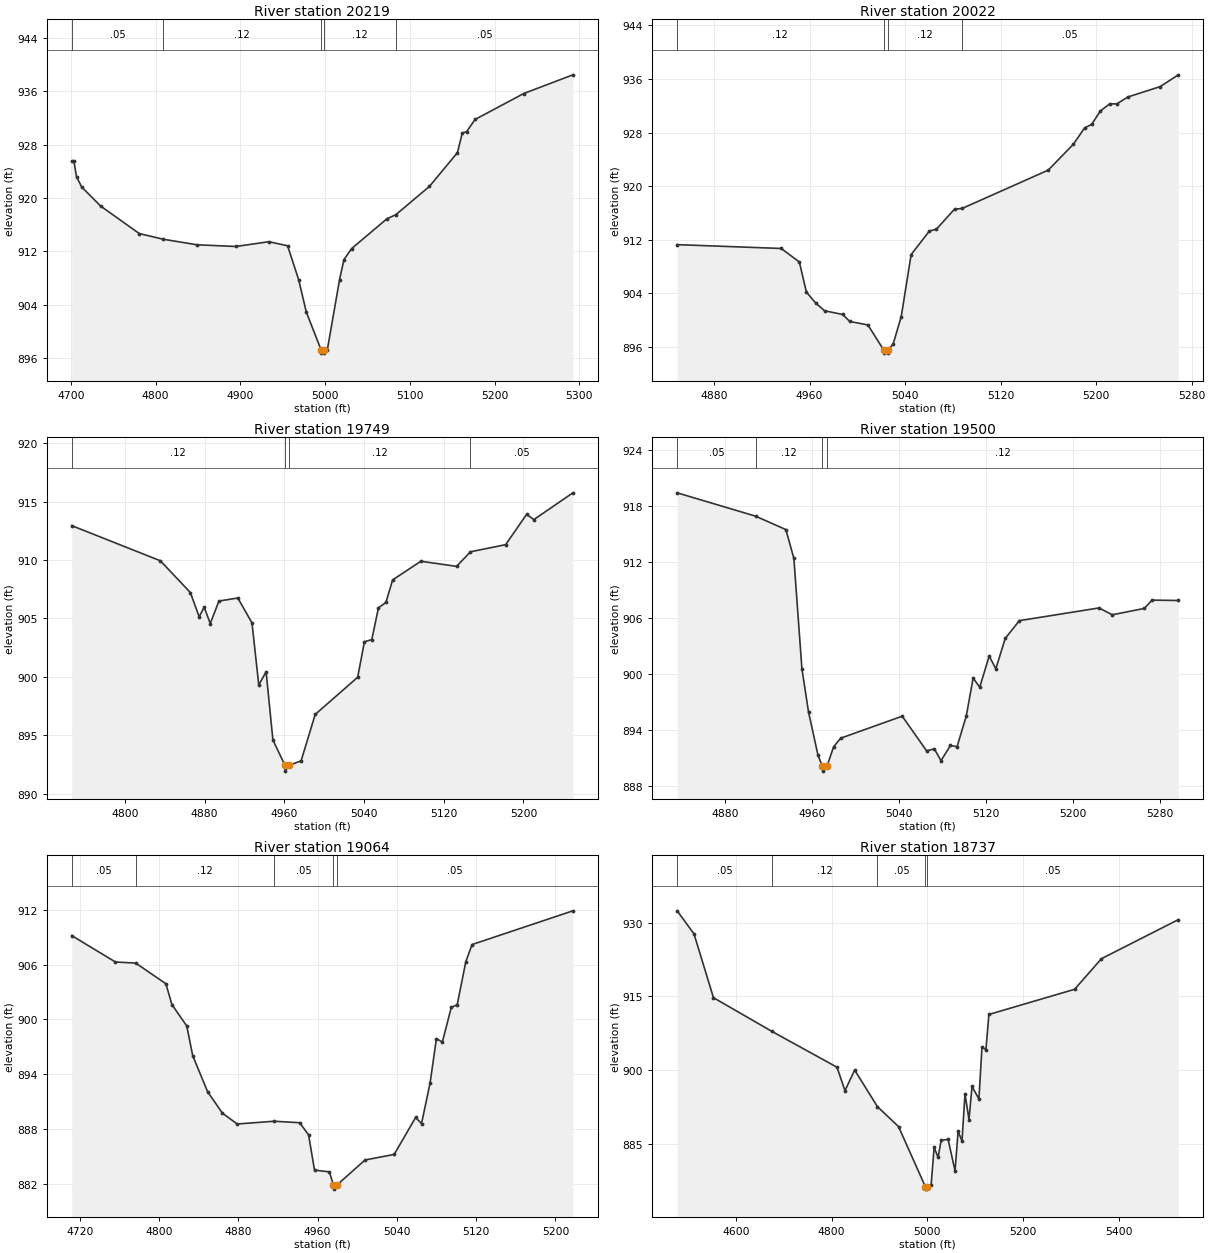
Type RM Length L Ch R = 1,20219,197,197,197
BEGIN DESCRIPTION:
MDW T 093 41.0
END DESCRIPTION:
XS GIS Cut Line= 3
      2272199.59      7155357.23      2271928.95      7155230.14
      2271648.17      7155148.88
#Sta/Elev= 30
  4701.0  925.49  4703.6  925.49  4706.7  923.18  4712.7  921.65  4735.0  918.79
  4780.7  914.65  4808.9  913.80  4849.1  912.96  4894.7  912.71  4933.7  913.43
  4955.7  912.81  4968.7  907.75  4977.8  902.86  4995.2  897.20  4995.5  896.70
  4999.0  896.70  4999.2  897.20  5002.6  897.20  5017.0  907.72  5022.2  910.74
  5031.2  912.39  5072.8  916.86  5083.5  917.49  5123.0  921.72  5156.1  926.80
  5161.8  929.74  5167.0  929.96  5176.9  931.78  5234.3  935.67  5292.3  938.48
#Mann=5,-1,0
  4701.0    0.05       0  4808.9    0.12       0  4995.2    0.07       0
  4999.2    0.12       0  5083.5    0.05       0
Bank Sta=4995.2,4999.2
Exp/Cntr=0.3,0.1

Type RM Length L Ch R = 1,20022,273,273,273
BEGIN DESCRIPTION:
Mapping XS c113fc46
END DESCRIPTION:
XS GIS Cut Line= 2
      2272116.55      7155132.70      2271764.24      7154904.80
#Sta/Elev= 30
  4849.2  911.27  4936.3  910.70  4951.5  908.68  4957.4  904.18  4965.4  902.51
  4972.6  901.40  4987.8  900.84  4993.7  899.80  5008.9  899.28  5022.0  895.57
  5022.3  895.07  5025.8  895.07  5026.0  895.57  5030.0  896.41  5036.8  900.52
  5045.1  909.79  5060.3  913.29  5066.3  913.59  5081.4  916.57  5087.7  916.67
  5159.9  922.40  5181.0  926.28  5190.3  928.70  5196.2  929.23  5203.6  931.24
  5211.4  932.30  5217.3  932.29  5226.5  933.32  5253.6  934.87  5268.8  936.63
#Mann=4,-1,0
  4849.2    0.12       0  5022.0    0.07       0  5026.0    0.12       0
  5087.7    0.05       0
Bank Sta=5022,5026
Exp/Cntr=0.3,0.1

Type RM Length L Ch R = 1,19749,249,249,249
BEGIN DESCRIPTION:
Mapping XS 190673f6
END DESCRIPTION:
XS GIS Cut Line= 3
      2272287.86      7154943.38      2272136.73      7154933.76
      2271899.87      7154673.70
#Sta/Elev= 30
  4746.5  912.95  4835.5  909.94  4865.6  907.22  4874.5  905.14  4879.5  905.97
  4885.6  904.56  4894.3  906.49  4913.3  906.75  4927.5  904.62  4934.3  899.31
  4941.7  900.42  4948.5  894.59  4960.6  892.42  4960.9  891.92  4964.7  892.42
  4976.8  892.80  4991.0  896.78  5033.6  899.96  5040.4  903.00  5047.8  903.19
  5054.5  905.91  5062.0  906.37  5068.7  908.30  5097.1  909.90  5132.9  909.46
  5146.9  910.71  5182.2  911.32  5203.2  913.91  5210.6  913.47  5249.7  915.76
#Mann=4,-1,0
  4746.5    0.12       0  4960.6    0.07       0  4964.7    0.12       0
  5146.9    0.05       0
Bank Sta=4960.6,4964.7
Exp/Cntr=0.3,0.1

Type RM Length L Ch R = 1,19500,436,436,436
BEGIN DESCRIPTION:
Mapping XS 03ef9151
END DESCRIPTION:
XS GIS Cut Line= 2
      2272416.92      7154851.84      2272039.24      7154586.45
#Sta/Elev= 30
  4835.6  919.41  4907.8  916.91  4935.7  915.47  4943.1  912.38  4950.5  900.55
  4956.6  895.91  4965.3  891.29  4969.4  890.08  4969.7  889.58  4973.5  890.08
  4979.7  892.19  4986.2  893.11  5042.9  895.47  5065.3  891.76  5072.5  891.96
  5078.6  890.70  5087.3  892.33  5093.4  892.20  5101.9  895.49  5108.2  899.55
  5114.3  898.58  5123.0  901.92  5129.1  900.55  5137.8  903.81  5150.8  905.71
  5224.1  907.07  5236.4  906.34  5265.9  907.02  5273.0  907.91  5297.2  907.87
#Mann=4,-1,0
  4835.6    0.05       0  4907.8    0.12       0  4969.4    0.07       0
  4973.5    0.12       0
Bank Sta=4969.4,4973.5
Exp/Cntr=0.3,0.1

Type RM Length L Ch R = 1,19064,327,327,327
BEGIN DESCRIPTION:
Mapping XS bb1fbd16
END DESCRIPTION:
XS GIS Cut Line= 2
      2272438.95      7154219.30      2272019.43      7154501.69
#Sta/Elev= 30
  4711.9  909.18  4756.0  906.29  4776.5  906.17  4806.9  903.91  4813.0  901.63
  4828.0  899.28  4834.0  896.03  4849.0  892.10  4863.9  889.75  4878.9  888.56
  4916.1  888.86  4941.9  888.70  4950.9  887.37  4956.9  883.51  4971.9  883.32
  4975.8  881.93  4976.2  881.43  4980.0  881.93  5007.9  884.62  5037.3  885.23
  5058.9  889.27  5064.9  888.61  5073.5  893.03  5079.9  897.90  5085.9  897.53
  5094.9  901.32  5100.9  901.62  5109.6  906.34  5115.9  908.20  5217.6  911.89
#Mann=5,-1,0
  4711.9    0.05       0  4776.5    0.12       0  4916.1    0.05       0
  4975.8   0.033       0  4980.0    0.05       0
Bank Sta=4975.8,4980
Exp/Cntr=0.3,0.1

Type RM Length L Ch R = 1,18737,131,131,131
BEGIN DESCRIPTION:
MDW T 093 38.0
END DESCRIPTION:
XS GIS Cut Line= 3
      2272623.47      7154043.60      2272109.75      7154140.09
      2271793.41      7154558.08
#Sta/Elev= 30
  4477.3  932.37  4512.4  927.70  4553.1  914.74  4674.7  907.92  4811.2  900.62
  4827.8  895.86  4848.1  900.04  4895.7  892.61  4939.7  888.57  4995.7  876.37
  4996.1  875.87  4999.9  876.37  5007.8  876.73  5014.1  884.34  5022.4  882.31
  5028.7  885.75  5043.2  885.99  5057.8  879.56  5064.1  887.60  5072.3  885.64
  5078.6  895.23  5086.9  889.96  5093.2  896.71  5107.7  894.17  5114.0  904.69
  5122.3  904.21  5128.5  911.33  5307.5  916.44  5363.7  922.66  5524.2  930.58
#Mann=5,-1,0
  4477.3    0.05       0  4674.7    0.12       0  4895.7    0.05       0
  4995.7   0.033       0  4999.9    0.05       0
Bank Sta=4995.7,4999.9
Exp/Cntr=0.3,0.1

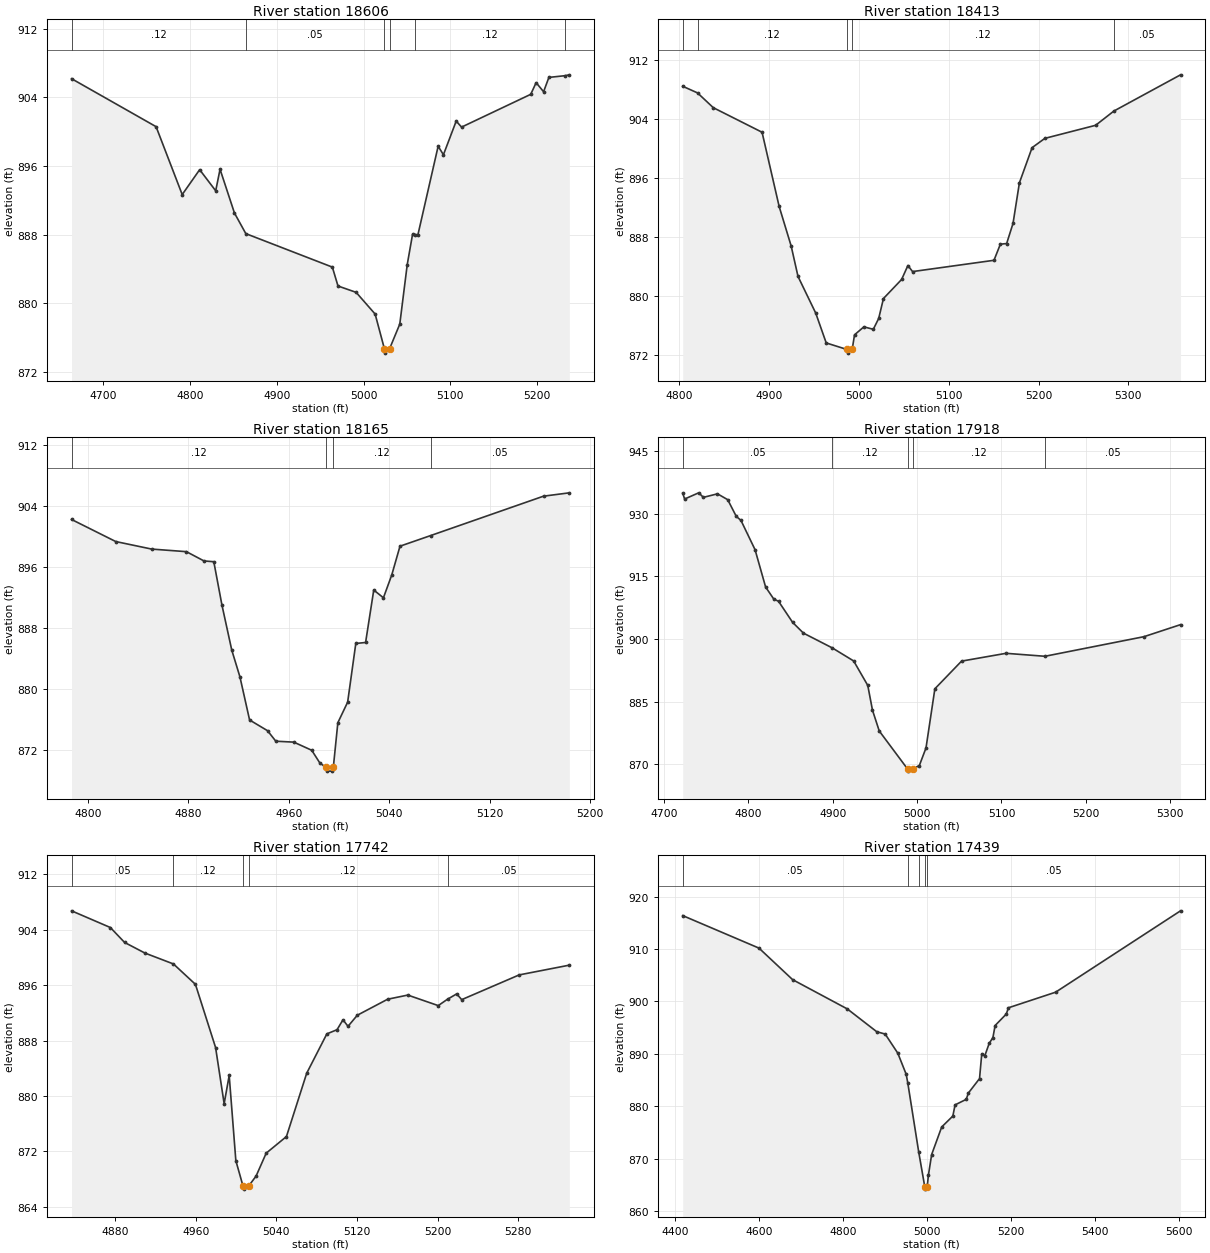
Type RM Length L Ch R = 1,18606,193,193,193
BEGIN DESCRIPTION:
Mapping XS 90224805
END DESCRIPTION:
XS GIS Cut Line= 3
      2272405.98      7154079.86      2272158.34      7154102.06
      2271968.39      7153838.40
#Sta/Elev= 30
  4663.6  906.16  4761.0  900.57  4791.1  892.66  4811.2  895.56  4829.7  893.10
  4834.7  895.61  4851.3  890.51  4864.4  888.11  4964.1  884.21  4970.6  882.01
  4991.5  881.27  5013.4  878.74  5024.1  874.69  5025.1  874.19  5030.0  874.69
  5041.8  877.57  5050.4  884.51  5056.5  888.02  5059.2  888.00  5062.7  887.98
  5086.0  898.29  5092.1  897.30  5106.8  901.22  5113.0  900.52  5192.7  904.34
  5198.9  905.70  5207.5  904.64  5213.6  906.31  5232.3  906.51  5237.2  906.61
#Mann=6,-1,0
  4663.6    0.12       0  4864.4    0.05       0  5024.1   0.033       0
  5030.0    0.05       0  5059.2    0.12       0  5232.3    0.05       0
Bank Sta=5024.1,5030
Exp/Cntr=0.3,0.1

Type RM Length L Ch R = 1,18413,248,248,248
BEGIN DESCRIPTION:
Mapping XS 28b470e7
END DESCRIPTION:
XS GIS Cut Line= 3
      2272461.45      7154020.37      2272182.84      7153933.19
      2271996.74      7153748.67
#Sta/Elev= 30
  4804.0  908.39  4820.5  907.49  4838.0  905.49  4892.3  902.16  4911.3  892.11
  4924.7  886.74  4932.3  882.62  4952.0  877.66  4963.7  873.61  4986.7  872.73
  4987.7  872.23  4992.6  872.73  4995.2  874.71  5005.6  875.79  5016.1  875.46
  5022.1  876.93  5027.4  879.63  5047.6  882.21  5054.6  884.10  5059.8  883.28
  5150.4  884.81  5157.5  886.99  5164.5  887.08  5171.6  889.81  5178.7  895.31
  5192.8  900.07  5207.0  901.33  5263.5  903.10  5283.8  905.03  5358.0  909.94
#Mann=5,-1,0
  4804.0    0.05       0  4820.5    0.12       0  4986.7    0.07       0
  4992.6    0.12       0  5283.8    0.05       0
Bank Sta=4986.7,4992.6
Exp/Cntr=0.3,0.1

Type RM Length L Ch R = 1,18165,247,247,247
BEGIN DESCRIPTION:
Mapping XS c3c129c2
END DESCRIPTION:
XS GIS Cut Line= 2
      2272448.98      7153889.34      2272145.75      7153633.88
#Sta/Elev= 30
  4787.1  902.24  4822.3  899.34  4850.9  898.35  4878.6  898.01  4892.6  896.79
  4900.4  896.69  4906.9  890.98  4914.7  885.08  4921.2  881.57  4928.9  875.90
  4943.2  874.49  4949.8  873.11  4964.1  872.99  4978.4  871.92  4984.9  870.24
  4989.7  869.68  4990.7  869.18  4994.7  869.18  4995.6  869.68  4999.2  875.54
  5007.0  878.24  5013.5  885.95  5021.3  886.08  5027.8  892.97  5035.5  891.95
  5042.1  894.93  5048.7  898.73  5073.2  900.13  5163.0  905.30  5183.6  905.74
#Mann=4,-1,0
  4787.1    0.12       0  4989.7    0.07       0  4995.6    0.12       0
  5073.2    0.05       0
Bank Sta=4989.7,4995.6
Exp/Cntr=0.3,0.1

Type RM Length L Ch R = 1,17918,176,176,176
BEGIN DESCRIPTION:
MDW T 093 36.0
END DESCRIPTION:
XS GIS Cut Line= 3
      2272726.51      7153735.77      2272479.00      7153610.00
      2272182.95      7153511.31
#Sta/Elev= 30
  4722.4  934.86  4724.7  933.49  4741.3  934.97  4746.9  933.89  4763.6  934.73
  4775.7  933.33  4785.8  929.35  4791.4  928.37  4808.1  921.36  4820.6  912.43
  4830.3  909.54  4835.9  909.02  4852.6  903.97  4865.4  901.40  4899.6  897.86
  4924.9  894.74  4941.6  888.89  4947.2  882.96  4955.2  877.99  4988.8  868.88
  4989.7  868.38  4994.7  868.88  5002.7  869.72  5010.6  873.93  5021.1  888.08
  5052.7  894.70  5105.4  896.57  5151.5  895.86  5268.8  900.55  5312.1  903.43
#Mann=5,-1,0
  4722.4    0.05       0  4899.6    0.12       0  4988.8    0.07       0
  4994.7    0.12       0  5151.5    0.05       0
Bank Sta=4988.8,4994.7
Exp/Cntr=0.3,0.1

Type RM Length L Ch R = 1,17742,303,303,303
BEGIN DESCRIPTION:
Mapping XS 0279711e
END DESCRIPTION:
XS GIS Cut Line= 2
      2272741.39      7153488.43      2272249.35      7153445.59
#Sta/Elev= 30
  4836.8  906.72  4875.3  904.31  4889.4  902.16  4909.5  900.63  4937.9  899.05
  4959.7  896.11  4979.7  886.99  4988.2  878.88  4993.2  882.96  4999.8  870.66
  5006.8  867.05  5007.8  866.55  5012.8  867.05  5019.9  868.44  5029.9  871.74
  5050.0  874.14  5070.1  883.28  5090.1  888.96  5100.2  889.56  5106.1  890.99
  5111.1  890.05  5120.3  891.65  5150.4  893.96  5170.4  894.56  5200.6  893.04
  5209.8  893.96  5218.9  894.73  5223.9  893.90  5280.9  897.47  5330.7  898.88
#Mann=5,-1,0
  4836.8    0.05       0  4937.9    0.12       0  5006.8    0.07       0
  5012.8    0.12       0  5209.8    0.05       0
Bank Sta=5006.8,5012.8
Exp/Cntr=0.3,0.1

Type RM Length L Ch R = 1,17439,192,192,192
BEGIN DESCRIPTION:
MDW T 093 35.0
END DESCRIPTION:
XS GIS Cut Line= 3
      2273010.34      7153222.74      2272429.85      7153244.70
      2271856.70      7153433.68
#Sta/Elev= 30
  4419.1  916.37  4600.6  910.17  4680.6  904.16  4810.7  898.58  4880.8  894.23
  4900.8  893.79  4930.8  890.15  4950.8  886.12  4954.6  884.46  4980.5  871.35
  4994.9  864.73  4995.9  864.23  5000.9  864.73  5003.6  866.85  5011.4  870.83
  5035.3  876.08  5061.8  878.16  5067.1  880.29  5093.6  881.34  5098.8  882.55
  5125.3  885.30  5130.6  890.04  5137.8  889.63  5148.3  892.02  5157.1  893.11
  5162.4  895.42  5188.9  897.60  5194.1  898.80  5306.3  901.77  5603.5  917.28
#Mann=5,-1,0
  4419.1    0.05       0  4954.6    0.12       0  4980.5    0.05       0
  4994.9   0.033       0  5000.9    0.05       0
Bank Sta=4994.9,5000.9
Exp/Cntr=0.3,0.1