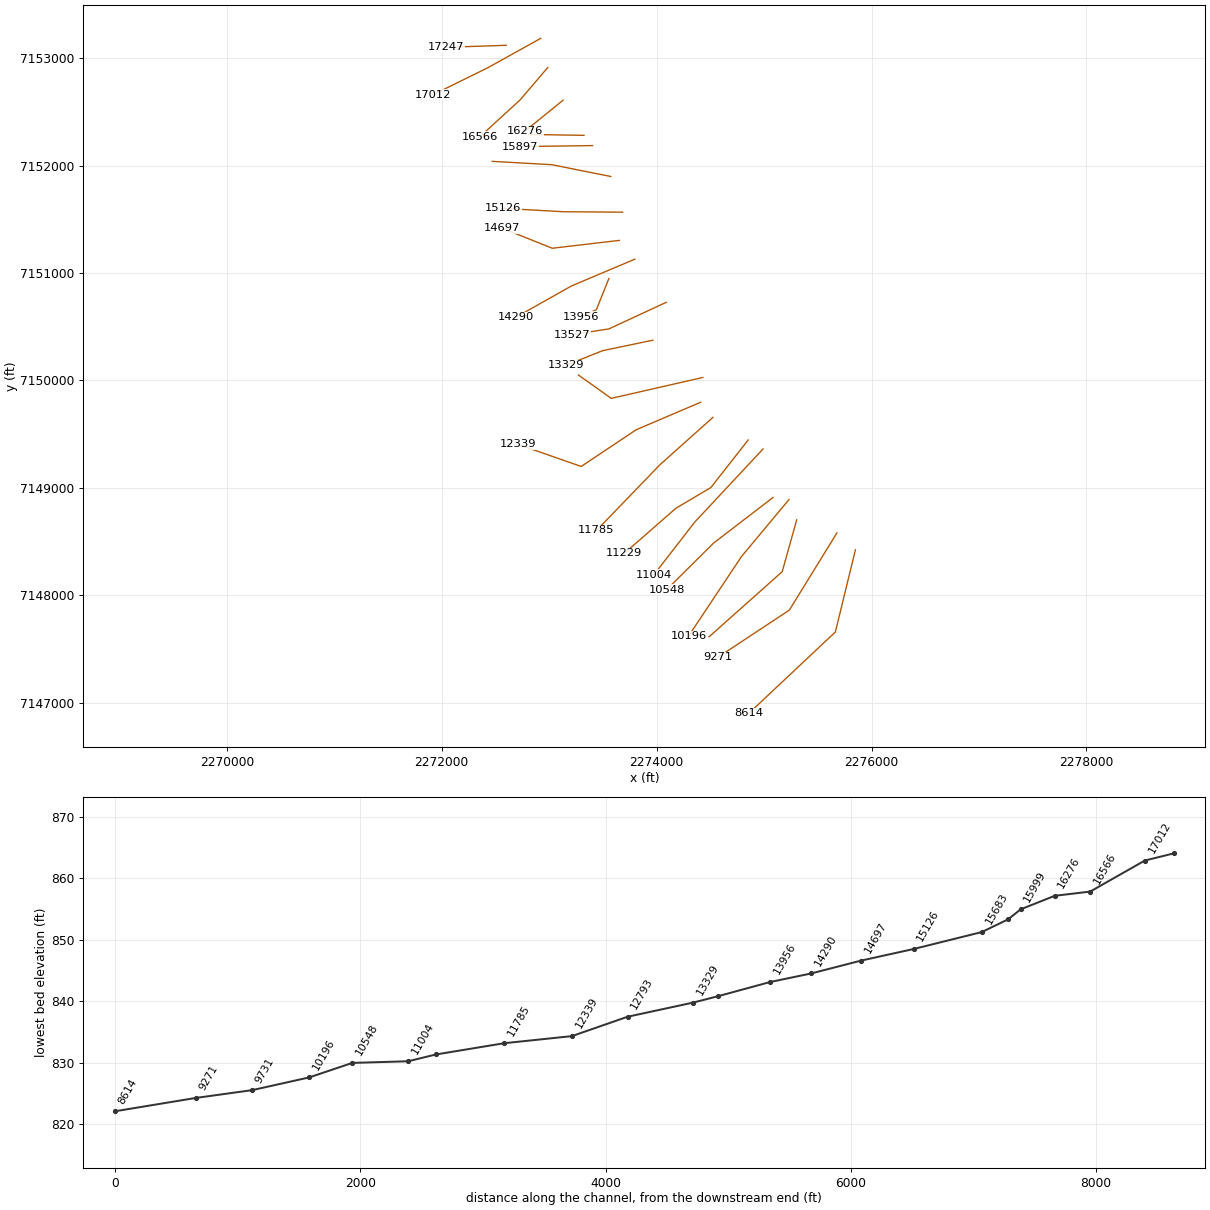
HEC-RAS study MDW T 093.prj: MDW T 093 Base Level Engineering

--- MDW T 093.g01 (geometry) --- (continued)

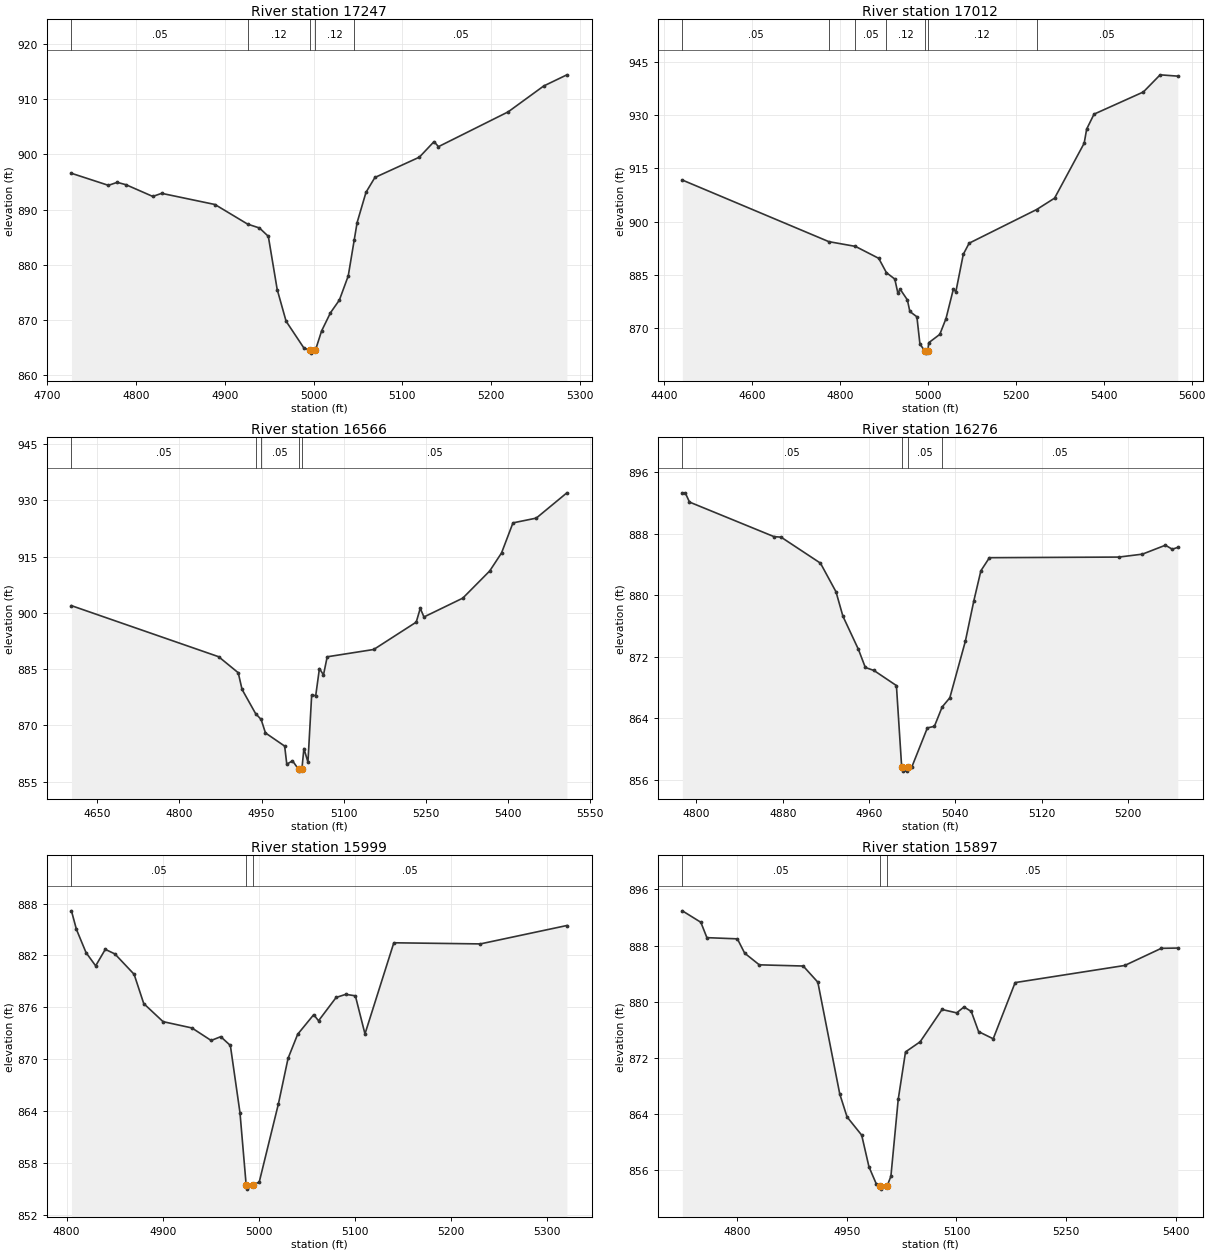
Type RM Length L Ch R = 1,17247,235,235,235
BEGIN DESCRIPTION:
Mapping XS d8fc7239
END DESCRIPTION:
XS GIS Cut Line= 2
      2272600.54      7153118.88      2272042.96      7153099.99
#Sta/Elev= 30
  4727.3  896.59  4768.9  894.41  4778.9  894.95  4788.9  894.51  4818.9  892.40
  4828.9  892.96  4888.9  890.94  4925.7  887.39  4939.0  886.69  4949.0  885.18
  4959.0  875.55  4969.0  869.82  4989.0  864.98  4995.9  864.54  4997.0  864.04
  5002.0  864.54  5009.0  868.06  5019.0  871.35  5029.0  873.64  5039.0  878.02
  5045.7  884.49  5049.0  887.68  5059.0  893.15  5069.0  895.83  5119.1  899.51
  5135.6  902.32  5140.6  901.41  5219.1  907.71  5259.1  912.39  5285.2  914.41
#Mann=5,-1,0
  4727.3    0.05       0  4925.7    0.12       0  4995.9    0.07       0
  5002.0    0.12       0  5045.7    0.05       0
Bank Sta=4995.9,5002
Exp/Cntr=0.3,0.1

Type RM Length L Ch R = 1,17012,446,446,446
BEGIN DESCRIPTION:
MDW T 093 34.0
END DESCRIPTION:
XS GIS Cut Line= 3
      2272921.78      7153183.66      2272429.00      7152910.00
      2271922.90      7152660.78
#Sta/Elev= 30
  4440.7  911.72  4774.1  894.34  4834.7  893.00  4887.7  889.63  4905.2  885.59
  4924.3  883.78  4931.1  879.92  4936.9  880.84  4952.9  877.91  4958.6  874.63
  4974.6  873.13  4981.5  865.45  4993.3  863.38  4994.3  862.88  4999.4  863.38
  5001.5  865.81  5026.7  868.17  5040.9  872.65  5057.7  880.98  5063.3  880.20
  5080.2  890.76  5093.5  893.90  5247.2  903.40  5288.0  906.61  5355.4  922.12
  5361.1  926.12  5377.8  930.31  5490.1  936.57  5528.3  941.41  5568.5  941.04
#Mann=7,-1,0
  4440.7    0.05       0  4774.1    0.12       0  4834.7    0.05       0
  4905.2    0.12       0  4993.3    0.07       0  4999.4    0.12       0
  5247.2    0.05       0
Bank Sta=4993.3,4999.4
Exp/Cntr=0.3,0.1

Type RM Length L Ch R = 1,16566,290,290,290
BEGIN DESCRIPTION:
MDW T 093 33.0
END DESCRIPTION:
XS GIS Cut Line= 3
      2272986.94      7152911.87      2272729.00      7152610.00
      2272353.61      7152266.34
#Sta/Elev= 30
  4602.4  901.93  4871.6  888.32  4907.4  884.05  4914.4  879.61  4939.1  873.18
  4949.3  871.59  4957.2  868.01  4992.3  864.50  4996.2  859.66  5006.6  860.59
  5017.7  858.33  5018.7  857.83  5023.8  858.33  5027.5  863.85  5034.9  860.23
  5041.7  878.13  5049.1  877.94  5055.9  885.17  5063.3  883.47  5070.1  888.30
  5155.2  890.25  5232.9  897.54  5240.3  901.23  5247.0  898.91  5318.0  903.93
  5367.3  911.18  5388.9  915.98  5409.8  923.99  5452.4  925.26  5508.4  932.00
#Mann=5,-1,0
  4602.4    0.05       0  4939.1    0.12       0  4949.3    0.05       0
  5017.7   0.033       0  5023.8    0.05       0
Bank Sta=5017.7,5023.8
Exp/Cntr=0.3,0.1

Type RM Length L Ch R = 1,16276,277,277,277
BEGIN DESCRIPTION:
Mapping XS 76e2deca
END DESCRIPTION:
XS GIS Cut Line= 2
      2273130.03      7152608.40      2272773.54      7152318.96
#Sta/Elev= 30
  4786.9  893.31  4789.6  893.31  4793.5  892.11  4871.8  887.62  4878.4  887.55
  4914.9  884.17  4929.3  880.45  4935.7  877.28  4950.1  872.96  4956.5  870.61
  4964.5  870.22  4985.3  868.26  4990.2  857.64  4991.2  857.14  4995.3  857.14
  4996.3  857.64  4999.7  857.72  5014.0  862.76  5020.5  862.96  5027.7  865.48
  5034.8  866.67  5049.2  874.02  5057.1  879.30  5063.6  883.18  5071.5  884.88
  5191.5  884.96  5213.3  885.34  5234.6  886.50  5241.0  885.98  5246.1  886.22
#Mann=4,-1,0
  4786.9    0.05       0  4990.2    0.07       0  4996.3    0.05       0
  5027.7    0.05       0
Bank Sta=4990.2,4996.3
Exp/Cntr=0.3,0.1

Type RM Length L Ch R = 1,15999,102,102,102
BEGIN DESCRIPTION:
Mapping XS 8e6b41c3
END DESCRIPTION:
XS GIS Cut Line= 2
      2273324.24      7152280.90      2272809.01      7152289.22
#Sta/Elev= 30
  4805.1  887.16  4810.3  885.01  4820.3  882.32  4830.3  880.79  4840.3  882.70
  4850.3  882.17  4870.3  879.81  4880.3  876.42  4900.4  874.33  4930.4  873.60
  4950.4  872.15  4960.4  872.59  4970.4  871.57  4980.4  863.78  4986.8  855.44
  4987.9  854.94  4993.9  855.44  5000.4  855.75  5020.4  864.83  5030.4  870.08
  5040.4  872.87  5057.1  875.14  5062.1  874.43  5080.4  877.13  5090.4  877.49
  5100.4  877.32  5110.4  872.91  5140.4  883.46  5230.4  883.33  5320.4  885.46
#Mann=3,-1,0
  4805.1    0.05       0  4986.8    0.07       0  4993.9    0.05       0
Bank Sta=4986.8,4993.9
Exp/Cntr=0.3,0.1

Type RM Length L Ch R = 1,15897,214,214,214
BEGIN DESCRIPTION:
Mapping XS 41c6692b
END DESCRIPTION:
XS GIS Cut Line= 2
      2273404.34      7152185.50      2272726.40      7152176.34
#Sta/Elev= 30
  4724.9  892.95  4750.2  891.32  4758.5  889.13  4800.2  888.96  4810.2  886.92
  4830.2  885.26  4890.3  885.09  4910.3  882.79  4940.3  866.87  4950.3  863.60
  4970.3  861.01  4980.3  856.49  4990.3  854.06  4995.4  853.82  4996.9  853.32
  5005.3  853.82  5010.3  855.15  5020.3  866.09  5030.3  872.86  5050.3  874.30
  5080.3  878.90  5100.3  878.42  5110.3  879.26  5120.3  878.62  5130.3  875.75
  5150.3  874.73  5180.3  882.73  5330.3  885.17  5380.3  887.61  5402.9  887.65
#Mann=3,-1,0
  4724.9    0.05       0  4995.4    0.05       0  5005.3    0.05       0
Bank Sta=4995.4,5005.3
Exp/Cntr=0.3,0.1

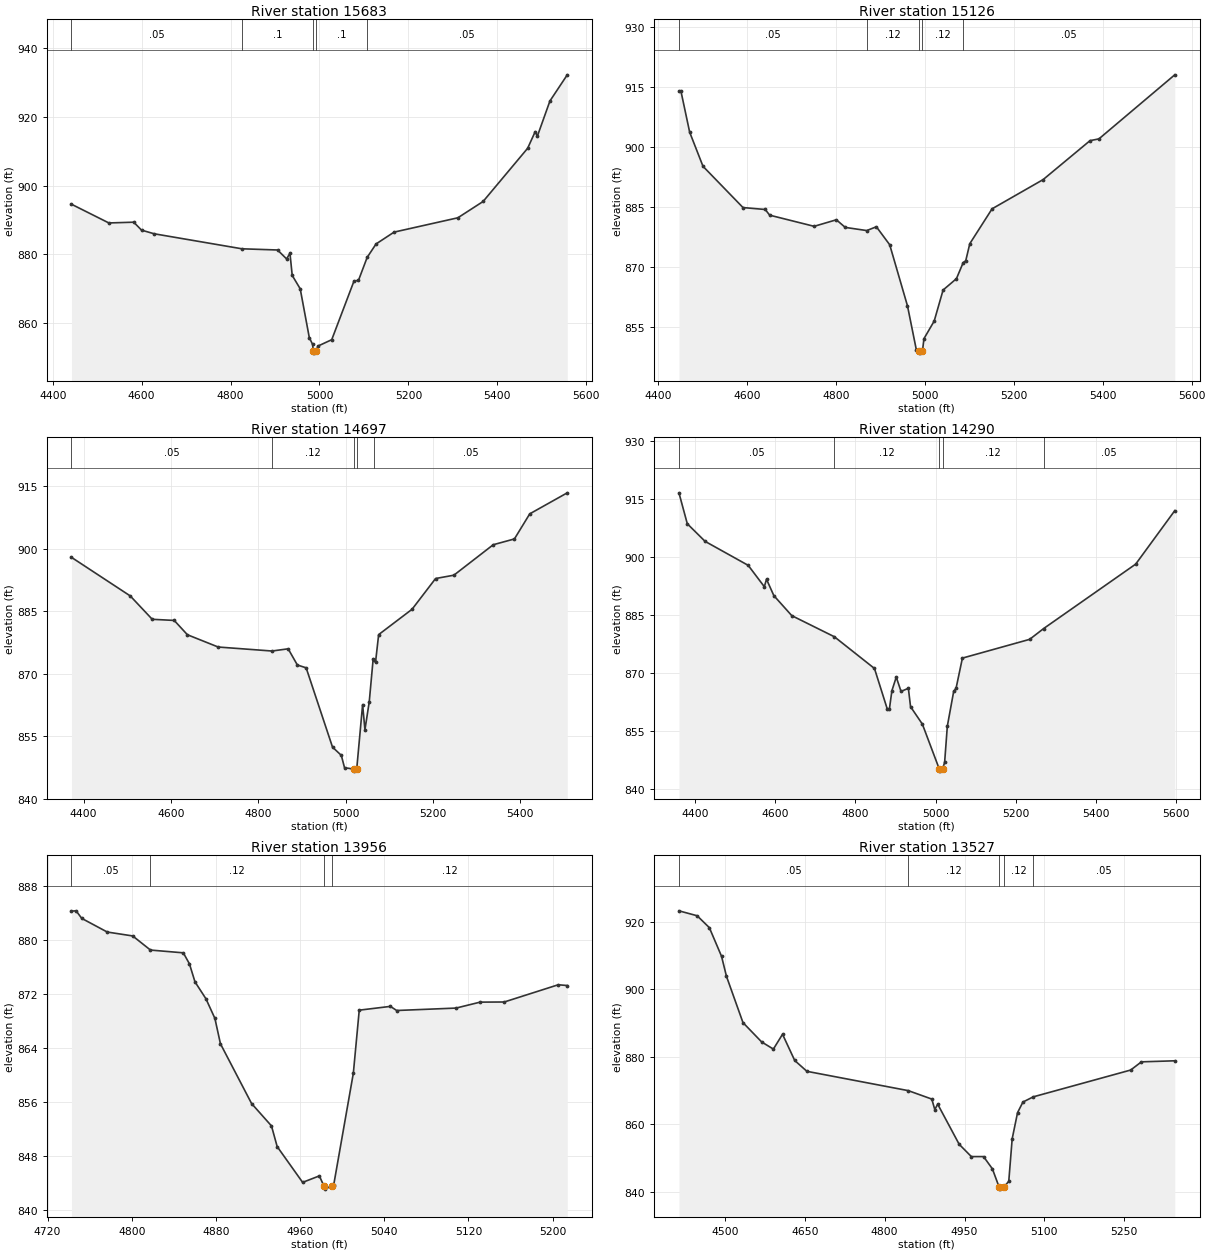
Type RM Length L Ch R = 1,15683,557,557,557
BEGIN DESCRIPTION:
MDW T 093 31.0
END DESCRIPTION:
XS GIS Cut Line= 3
      2273573.56      7151897.88      2273026.55      7152007.58
      2272470.03      7152038.95
#Sta/Elev= 30
  4442.1  894.58  4526.2  889.13  4582.2  889.35  4599.7  887.04  4628.1  885.98
  4825.5  881.61  4905.7  881.26  4926.1  878.66  4933.6  880.33  4938.7  873.86
  4956.7  869.96  4977.1  855.78  4984.5  853.80  4986.1  851.75  4987.2  851.25
  4993.2  851.75  4996.2  853.28  5027.6  855.16  5077.7  872.24  5087.7  872.40
  5107.3  879.11  5127.3  883.02  5167.8  886.46  5311.3  890.63  5368.1  895.38
  5468.3  910.86  5485.3  915.71  5490.3  914.43  5518.4  924.62  5557.4  932.23
#Mann=5,-1,0
  4442.1    0.05       0  4825.5     0.1       0  4986.1    0.05       0
  4993.2     0.1       0  5107.3    0.05       0
Bank Sta=4986.1,4993.2
Exp/Cntr=0.3,0.1

Type RM Length L Ch R = 1,15126,429,429,429
BEGIN DESCRIPTION:
MDW T 093 30.0
END DESCRIPTION:
XS GIS Cut Line= 3
      2273683.11      7151565.86      2273129.83      7151570.07
      2272568.71      7151601.67
#Sta/Elev= 30
  4446.7  913.82  4451.3  913.82  4470.8  903.64  4500.8  895.12  4590.8  884.82
  4640.8  884.34  4650.8  882.92  4750.8  880.14  4800.8  881.77  4820.8  879.87
  4869.2  879.08  4890.8  880.03  4920.8  875.54  4960.8  860.28  4980.8  849.27
  4987.2  848.99  4988.3  848.49  4994.4  848.99  4997.9  852.11  5020.9  856.50
  5040.9  864.24  5070.9  867.07  5086.1  871.08  5091.8  871.54  5101.0  875.81
  5151.1  884.51  5265.9  891.80  5371.4  901.52  5391.4  901.96  5562.0  917.95
#Mann=5,-1,0
  4446.7    0.05       0  4869.2    0.12       0  4987.2    0.07       0
  4994.4    0.12       0  5086.1    0.05       0
Bank Sta=4987.2,4994.4
Exp/Cntr=0.3,0.1

Type RM Length L Ch R = 1,14697,407,407,407
BEGIN DESCRIPTION:
MDW T 093 29.0
END DESCRIPTION:
XS GIS Cut Line= 3
      2273652.74      7151303.27      2273029.41      7151230.18
      2272557.85      7151418.31
#Sta/Elev= 30
  4372.4  897.97  4507.1  888.69  4557.4  883.08  4607.7  882.81  4637.9  879.37
  4708.4  876.42  4831.6  875.46  4868.6  875.99  4889.7  872.10  4909.8  871.42
  4970.2  852.36  4990.3  850.39  4997.7  847.42  5018.4  847.10  5019.5  846.60
  5025.6  847.10  5039.1  862.59  5044.4  856.53  5054.3  863.27  5063.3  873.61
  5064.9  873.37  5068.7  872.80  5075.8  879.40  5152.3  885.49  5206.2  892.88
  5248.1  893.68  5338.2  901.00  5386.7  902.39  5421.8  908.42  5507.7  913.47
#Mann=5,-1,0
  4372.4    0.05       0  4831.6    0.12       0  5018.4    0.07       0
  5025.6    0.12       0  5064.9    0.05       0
Bank Sta=5018.4,5025.6
Exp/Cntr=0.3,0.1

Type RM Length L Ch R = 1,14290,334,334,334
BEGIN DESCRIPTION:
MDW T 093 28.0
END DESCRIPTION:
XS GIS Cut Line= 3
      2273798.16      7151128.59      2273208.68      7150879.86
      2272689.18      7150587.12
#Sta/Elev= 30
  4360.2  916.53  4381.0  908.53  4425.4  903.97  4532.9  897.76  4573.1  892.23
  4578.5  894.17  4596.8  889.93  4641.5  884.75  4747.6  879.29  4847.7  871.07
  4879.4  860.64  4884.8  860.50  4891.1  865.31  4902.0  868.85  4913.9  865.14
  4932.2  865.94  4937.6  861.19  4967.1  856.67  5009.4  845.01  5010.6  844.51
  5017.3  845.01  5022.6  846.78  5029.3  856.14  5045.2  865.16  5051.0  865.90
  5066.9  873.76  5234.5  878.61  5269.5  881.41  5498.9  898.08  5596.3  911.91
#Mann=5,-1,0
  4360.2    0.05       0  4747.6    0.12       0  5009.4    0.07       0
  5017.3    0.12       0  5269.5    0.05       0
Bank Sta=5009.4,5017.3
Exp/Cntr=0.3,0.1

Type RM Length L Ch R = 1,13956,429,429,429
BEGIN DESCRIPTION:
Mapping XS 9cb75f34
END DESCRIPTION:
XS GIS Cut Line= 3
      2273555.84      7150948.64      2273439.47      7150658.40
      2273295.75      7150591.57
#Sta/Elev= 30
  4742.7  884.29  4747.1  884.33  4752.5  883.21  4776.7  881.19  4800.9  880.61
  4817.8  878.52  4849.0  878.11  4854.8  876.49  4860.1  873.81  4870.5  871.31
  4879.0  868.41  4884.3  864.64  4913.9  855.79  4932.8  852.48  4938.2  849.42
  4962.4  844.12  4978.3  845.08  4982.5  843.62  4983.7  843.12  4990.6  843.62
  4992.0  843.80  5010.6  860.29  5016.2  869.62  5045.8  870.18  5051.8  869.57
  5108.2  869.93  5131.1  870.81  5154.0  870.83  5205.3  873.38  5213.9  873.27
#Mann=4,-1,0
  4742.7    0.05       0  4817.8    0.12       0  4982.5    0.07       0
  4990.6    0.12       0
Bank Sta=4982.5,4990.6
Exp/Cntr=0.3,0.1

Type RM Length L Ch R = 1,13527,198,198,198
BEGIN DESCRIPTION:
MDW T 093 27.0
END DESCRIPTION:
XS GIS Cut Line= 3
      2274089.98      7150727.08      2273555.72      7150479.49
      2273217.18      7150427.18
#Sta/Elev= 30
  4413.5  923.24  4447.7  921.78  4470.6  918.26  4493.5  909.78  4502.8  903.83
  4533.8  890.12  4568.9  884.39  4590.9  882.28  4608.1  886.67  4631.0  878.90
  4653.9  875.69  4844.3  869.97  4888.5  867.47  4894.1  864.37  4899.6  865.95
  4939.9  854.08  4962.8  850.43  4985.7  850.43  5002.3  846.81  5015.2  841.29
  5016.4  840.79  5023.3  841.29  5033.1  843.11  5039.5  855.70  5049.6  863.45
  5059.7  866.59  5079.1  868.13  5262.1  876.07  5282.3  878.50  5344.9  878.81
#Mann=5,-1,0
  4413.5    0.05       0  4844.3    0.12       0  5015.2    0.07       0
  5023.3    0.12       0  5079.1    0.05       0
Bank Sta=5015.2,5023.3
Exp/Cntr=0.3,0.1

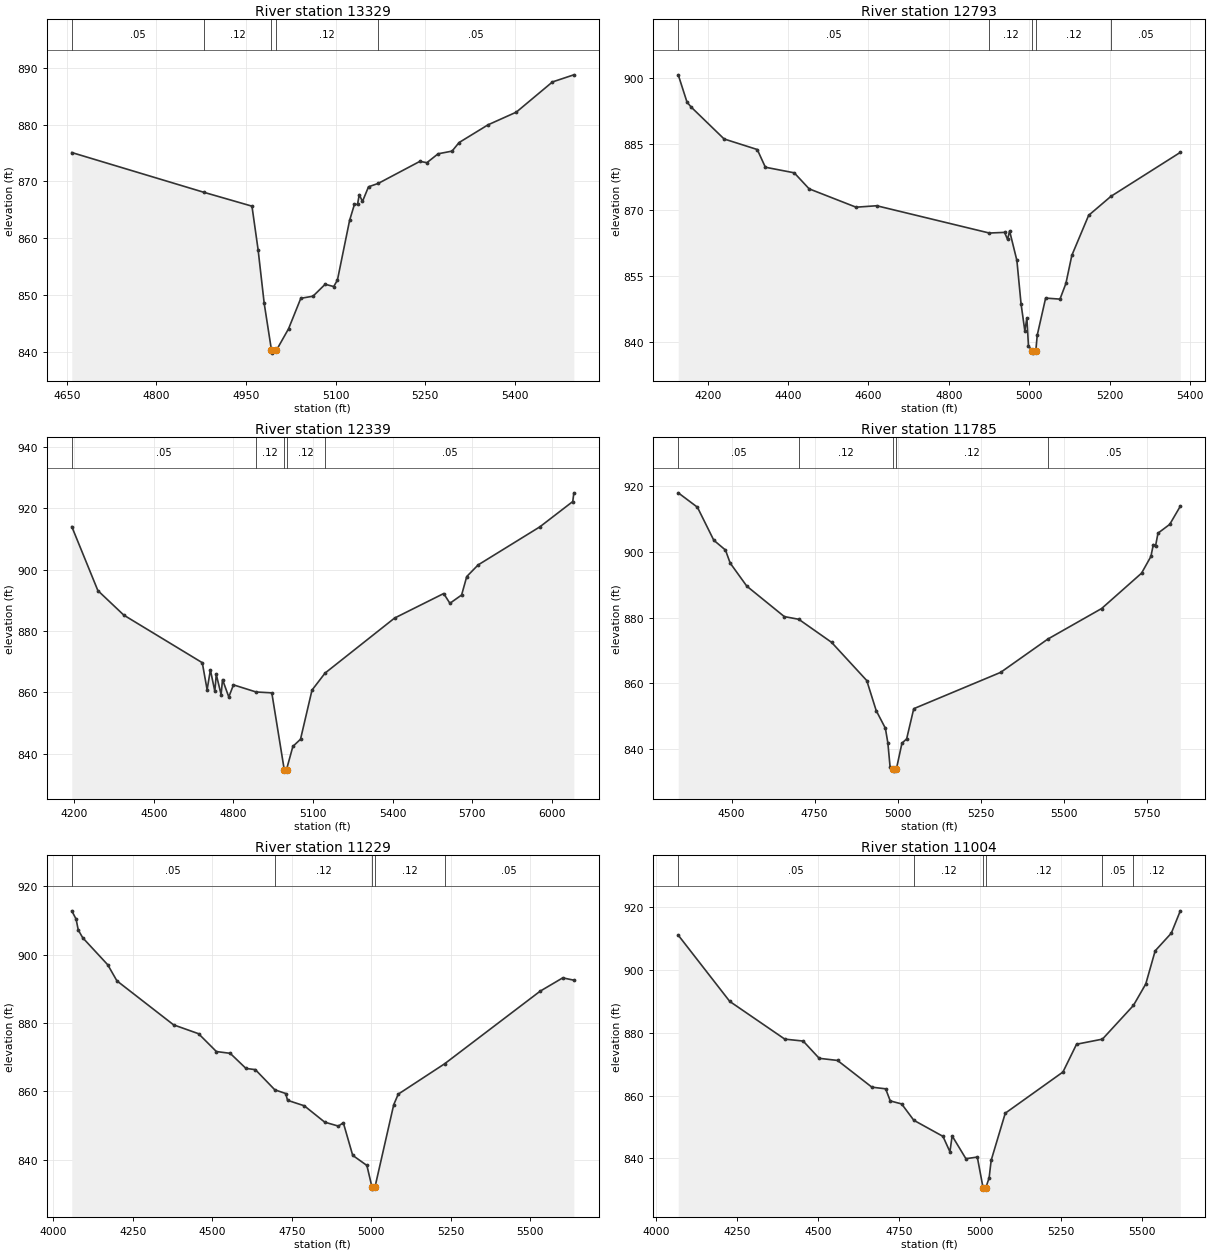
Type RM Length L Ch R = 1,13329,536,536,536
BEGIN DESCRIPTION:
MDW T 093 26.0
END DESCRIPTION:
XS GIS Cut Line= 3
      2273964.50      7150374.28      2273498.07      7150277.10
      2273159.48      7150142.26
#Sta/Elev= 30
  4658.1  875.09  4879.4  868.09  4959.9  865.65  4970.2  857.97  4980.4  848.53
  4992.6  840.28  4993.9  839.78  5000.8  840.28  5021.2  844.07  5041.7  849.43
  5062.1  849.80  5082.5  851.90  5096.8  851.50  5103.0  852.62  5123.4  863.14
  5131.5  865.96  5136.7  865.96  5139.6  867.68  5145.0  866.48  5155.1  869.06
  5171.5  869.66  5241.2  873.54  5252.8  873.30  5271.7  874.87  5295.0  875.34
  5306.8  876.85  5355.3  879.97  5402.6  882.20  5463.2  887.52  5499.0  888.77
#Mann=5,-1,0
  4658.1    0.05       0  4879.4    0.12       0  4992.6    0.07       0
  5000.8    0.12       0  5171.5    0.05       0
Bank Sta=4992.6,5000.8
Exp/Cntr=0.3,0.1

Type RM Length L Ch R = 1,12793,454,454,454
BEGIN DESCRIPTION:
MDW T 093 25.0
END DESCRIPTION:
XS GIS Cut Line= 3
      2274430.26      7150027.66      2273577.89      7149833.27
      2273272.59      7150050.25
#Sta/Elev= 30
  4126.8  900.69  4148.6  894.49  4158.9  893.37  4240.9  886.12  4323.4  883.72
  4343.5  879.70  4415.3  878.43  4452.4  874.79  4569.1  870.62  4620.4  870.95
  4900.6  864.75  4938.4  864.90  4945.9  863.32  4951.0  865.22  4969.1  858.53
  4979.4  848.73  4988.9  842.51  4994.0  845.50  4997.9  839.09  5007.7  837.97
  5009.0  837.47  5016.2  837.97  5019.7  841.54  5040.6  849.97  5076.3  849.74
  5091.0  853.29  5105.8  859.68  5147.6  868.77  5203.1  873.09  5375.6  883.07
#Mann=5,-1,0
  4126.8    0.05       0  4900.6    0.12       0  5007.7    0.07       0
  5016.2    0.12       0  5203.1    0.05       0
Bank Sta=5007.7,5016.2
Exp/Cntr=0.3,0.1

Type RM Length L Ch R = 1,12339,554,554,554
BEGIN DESCRIPTION:
MDW T 093 24.0
END DESCRIPTION:
XS GIS Cut Line= 4
      2274409.48      7149796.77      2273809.77      7149540.90
      2273298.34      7149199.54      2272707.96      7149405.57
#Sta/Elev= 30
  4190.7  914.04  4289.1  893.17  4386.9  885.17  4682.6  869.66  4700.8  860.85
  4713.1  867.30  4729.9  860.34  4735.3  865.85  4753.5  859.28  4758.9  864.16
  4782.5  858.48  4800.1  862.44  4885.3  860.12  4944.6  859.84  4991.4  834.82
  4992.6  834.32  5000.0  834.82  5024.0  842.38  5052.8  844.72  5096.1  860.73
  5145.3  866.28  5407.2  884.21  5592.4  892.21  5615.8  889.03  5659.9  891.73
  5679.3  897.75  5722.0  901.53  5954.6  913.94  6078.8  922.20  6082.9  925.04
#Mann=5,-1,0
  4190.7    0.05       0  4885.3    0.12       0  4991.4    0.07       0
  5000.0    0.12       0  5145.3    0.05       0
Bank Sta=4991.4,5000
Exp/Cntr=0.3,0.1

Type RM Length L Ch R = 1,11785,556,556,556
BEGIN DESCRIPTION:
MDW T 093 23.0
END DESCRIPTION:
XS GIS Cut Line= 3
      2274524.02      7149656.12      2274031.48      7149215.91
      2273440.27      7148603.66
#Sta/Elev= 30
  4339.4  918.02  4397.1  913.64  4446.4  903.57  4481.6  900.57  4495.8  896.60
  4545.9  889.56  4658.8  880.28  4702.3  879.46  4800.9  872.45  4907.0  860.78
  4935.4  851.63  4963.1  846.23  4970.6  841.73  4977.3  834.37  4987.1  833.66
  4988.3  833.16  4995.9  833.66  5013.0  841.68  5027.1  842.99  5048.5  852.20
  5310.1  863.27  5452.1  873.42  5614.2  882.74  5734.3  893.51  5762.6  898.62
  5769.8  902.24  5776.7  901.90  5783.9  905.72  5819.2  908.40  5851.1  913.94
#Mann=5,-1,0
  4339.4    0.05       0  4702.3    0.12       0  4987.1    0.07       0
  4995.9    0.12       0  5452.1    0.05       0
Bank Sta=4987.1,4995.9
Exp/Cntr=0.3,0.1

Type RM Length L Ch R = 1,11229,225,225,225
BEGIN DESCRIPTION:
MDW T 093 22.0
END DESCRIPTION:
XS GIS Cut Line= 4
      2274852.15      7149446.05      2274504.94      7149003.36
      2274178.42      7148809.79      2273699.39      7148390.51
#Sta/Elev= 30
  4057.8  912.79  4071.4  910.37  4078.2  907.18  4092.2  904.91  4170.9  897.00
  4199.8  892.29  4377.9  879.42  4456.5  876.82  4512.6  871.60  4556.0  871.08
  4605.7  866.65  4635.0  866.31  4696.4  860.39  4730.5  859.32  4736.3  857.33
  4789.0  855.72  4853.3  850.93  4896.1  849.78  4911.7  850.76  4941.2  841.22
  4985.8  838.26  5002.1  831.83  5003.4  831.33  5011.0  831.83  5070.2  856.04
  5084.4  859.13  5230.1  868.01  5530.8  889.28  5601.7  893.17  5636.6  892.49
#Mann=5,-1,0
  4057.8    0.05       0  4696.4    0.12       0  5002.1    0.07       0
  5011.0    0.12       0  5230.1    0.05       0
Bank Sta=5002.1,5011
Exp/Cntr=0.3,0.1

Type RM Length L Ch R = 1,11004,456,456,456
BEGIN DESCRIPTION:
MDW T 093 21.0
END DESCRIPTION:
XS GIS Cut Line= 3
      2274991.04      7149362.72      2274355.55      7148682.76
      2273976.34      7148193.77
#Sta/Elev= 30
  4069.3  911.03  4228.3  889.95  4398.2  877.95  4454.9  877.34  4504.3  871.85
  4560.9  871.17  4666.9  862.67  4709.4  862.14  4723.6  858.30  4758.8  857.33
  4796.3  852.14  4886.3  847.02  4907.8  842.11  4914.6  847.17  4957.1  839.91
  4992.3  840.43  5009.9  830.73  5011.2  830.23  5018.8  830.73  5028.8  833.85
  5035.1  839.40  5078.6  854.39  5256.6  867.49  5298.6  876.33  5378.5  877.95
  5474.1  888.67  5512.2  895.50  5541.2  906.04  5591.0  911.66  5618.8  918.77
#Mann=6,-1,0
  4069.3    0.05       0  4796.3    0.12       0  5009.9    0.07       0
  5018.8    0.12       0  5378.5    0.05       0  5474.1    0.12       0
Bank Sta=5009.9,5018.8
Exp/Cntr=0.3,0.1

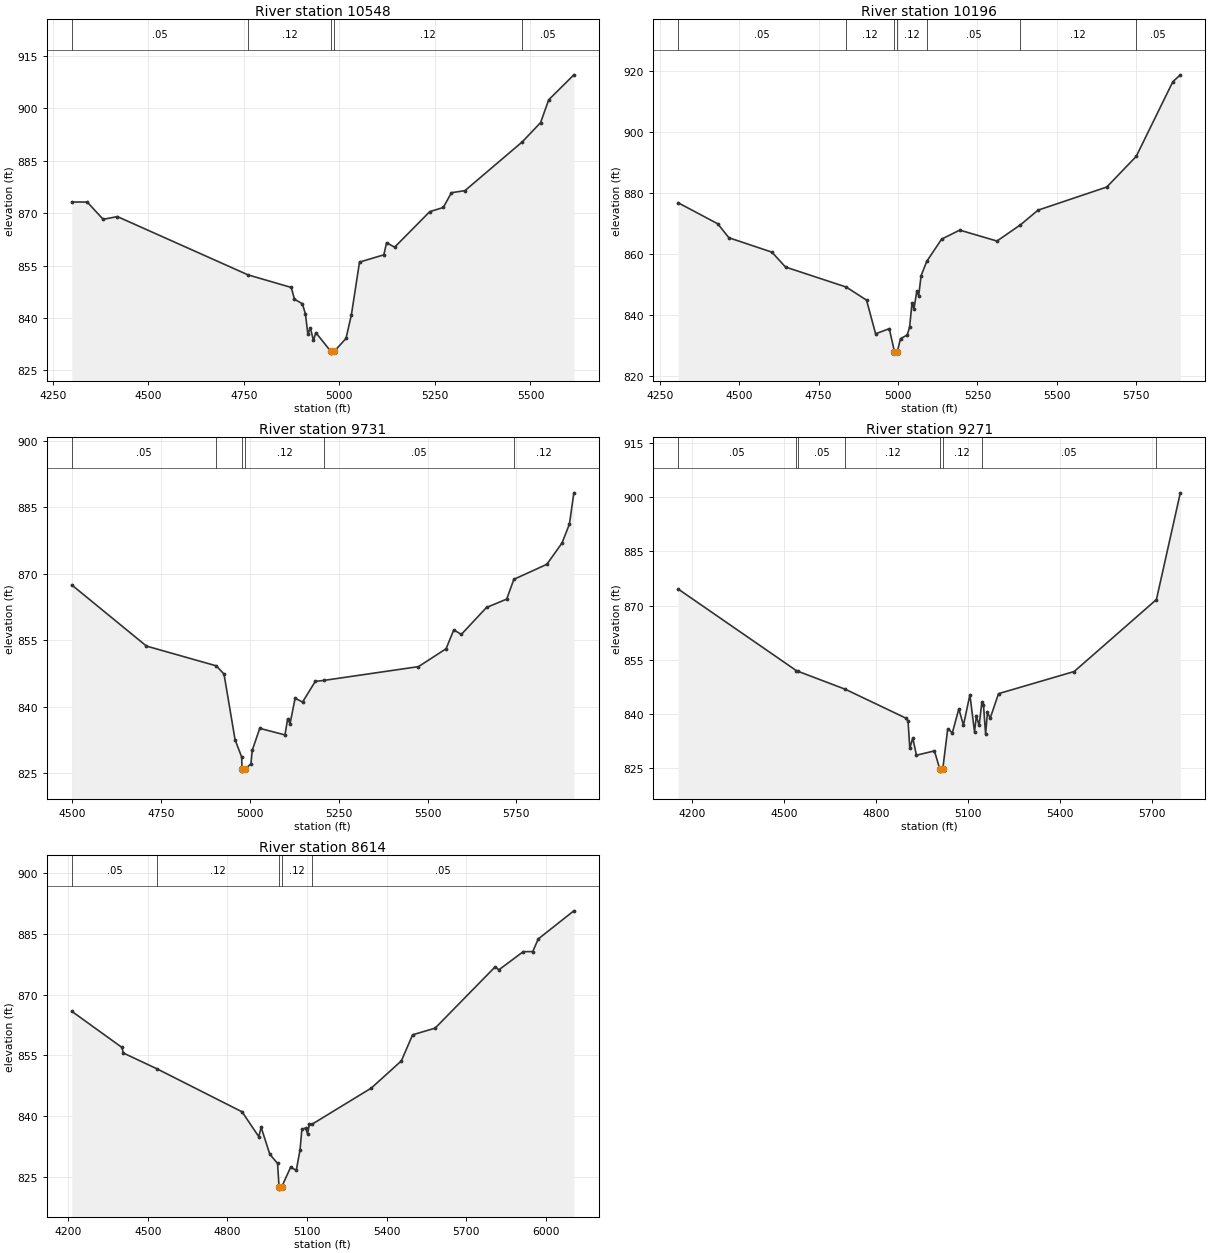
Type RM Length L Ch R = 1,10548,352,352,352
BEGIN DESCRIPTION:
MDW T 093 20.0
END DESCRIPTION:
XS GIS Cut Line= 3
      2275083.88      7148911.36      2274528.58      7148484.99
      2274093.27      7148052.69
#Sta/Elev= 30
  4299.9  873.20  4340.4  873.19  4382.0  868.24  4419.2  869.03  4761.1  852.35
  4874.2  848.75  4882.4  845.40  4903.2  844.09  4911.2  841.19  4917.7  835.33
  4924.0  837.24  4932.2  833.58  4938.5  835.83  4977.6  830.46  4978.9  829.96
  4986.6  830.46  5017.4  834.16  5031.5  840.92  5052.7  856.00  5116.4  858.09
  5123.5  861.56  5144.6  860.27  5236.6  870.45  5271.9  871.63  5293.2  875.86
  5328.5  876.45  5478.5  890.40  5526.5  895.92  5547.7  902.44  5613.5  909.59
#Mann=5,-1,0
  4299.9    0.05       0  4761.1    0.12       0  4977.6    0.07       0
  4986.6    0.12       0  5478.5    0.05       0
Bank Sta=4977.6,4986.6
Exp/Cntr=0.3,0.1

Type RM Length L Ch R = 1,10196,465,465,465
BEGIN DESCRIPTION:
MDW T 093 19.0
END DESCRIPTION:
XS GIS Cut Line= 3
      2275232.31      7148892.03      2274789.21      7148360.50
      2274296.98      7147620.33
#Sta/Elev= 30
  4308.0  876.80  4432.3  869.95  4467.5  865.37  4602.8  860.66  4645.8  855.78
  4837.0  849.23  4900.9  844.95  4929.5  833.92  4972.5  835.61  4988.8  828.10
  4990.1  827.60  4997.8  828.10  5008.0  832.37  5029.0  833.52  5036.6  836.16
  5044.1  844.08  5050.1  842.02  5059.1  847.87  5065.1  846.36  5072.7  852.95
  5090.5  857.64  5137.3  864.92  5194.4  867.87  5311.6  864.29  5385.6  869.60
  5440.9  874.40  5657.3  881.97  5750.1  892.01  5865.3  916.44  5888.9  918.70
#Mann=7,-1,0
  4308.0    0.05       0  4837.0    0.12       0  4988.8    0.07       0
  4997.8    0.12       0  5090.5    0.05       0  5385.6    0.12       0
  5750.1    0.05       0
Bank Sta=4988.8,4997.8
Exp/Cntr=0.3,0.1

Type RM Length L Ch R = 1,9731,460,460,460
BEGIN DESCRIPTION:
MDW T 093 18.0
END DESCRIPTION:
XS GIS Cut Line= 3
      2275303.65      7148702.45      2275168.72      7148220.17
      2274487.88      7147613.97
#Sta/Elev= 30
  4499.2  867.49  4709.4  853.71  4906.1  849.25  4927.5  847.39  4958.6  832.60
  4977.3  828.68  4978.0  826.03  4979.3  825.53  4987.1  826.03  5003.2  827.17
  5007.0  830.24  5028.0  835.17  5099.0  833.69  5106.5  837.31  5113.2  836.17
  5127.5  841.97  5148.4  841.09  5184.3  845.76  5207.9  845.97  5474.5  849.08
  5552.2  853.11  5573.9  857.38  5594.9  856.33  5665.9  862.41  5722.7  864.30
  5742.8  868.75  5835.7  872.14  5878.3  876.94  5899.2  881.21  5911.6  888.25
#Mann=6,-1,0
  4499.2    0.05       0  4906.1    0.12       0  4978.0    0.07       0
  4987.1    0.12       0  5207.9    0.05       0  5742.8    0.12       0
Bank Sta=4978,4987.1
Exp/Cntr=0.3,0.1

Type RM Length L Ch R = 1,9271,657,657,657
BEGIN DESCRIPTION:
MDW T 093 17.0
END DESCRIPTION:
XS GIS Cut Line= 3
      2275678.21      7148581.33      2275235.08      7147862.55
      2274573.39      7147425.50
#Sta/Elev= 30
  4155.6  874.55  4540.7  852.03  4545.8  851.85  4700.6  846.87  4897.3  838.93
  4905.0  838.15  4910.8  830.54  4920.4  833.42  4932.5  828.66  4991.2  829.85
  5008.8  824.76  5010.1  824.26  5018.2  824.76  5034.5  835.96  5049.6  834.84
  5070.7  841.46  5085.7  836.95  5106.8  845.33  5121.9  835.10  5127.8  839.45
  5136.9  836.89  5145.9  843.41  5151.1  842.50  5158.0  834.51  5164.0  840.50
  5173.0  838.88  5200.1  845.66  5446.9  851.78  5715.1  871.66  5793.0  901.14
#Mann=8,-1,0
  4155.6    0.05       0  4540.7    0.12       0  4545.8    0.05       0
  4700.6    0.12       0  5008.8    0.07       0  5018.2    0.12       0
  5145.9    0.05       0  5715.1    0.12       0
Bank Sta=5008.8,5018.2
Exp/Cntr=0.3,0.1

Type RM Length L Ch R = 1,8614,281,281,281
BEGIN DESCRIPTION:
MDW T 093 16.0
END DESCRIPTION:
XS GIS Cut Line= 3
      2275850.09      7148423.79      2275663.58      7147659.10
      2274857.92      7146901.66
#Sta/Elev= 30
  4212.9  865.88  4402.1  856.98  4407.3  855.61  4535.6  851.67  4855.0  841.13
  4917.8  835.04  4927.0  837.30  4959.5  830.69  4988.8  828.42  4994.4  822.60
  4995.7  822.10  5003.9  822.60  5037.9  827.47  5059.4  826.75  5073.5  831.75
  5080.4  836.78  5094.5  837.16  5101.8  835.71  5108.7  838.02  5119.9  838.12
  5342.2  846.98  5455.5  853.67  5497.9  860.09  5582.8  861.73  5809.1  876.82
  5823.2  876.09  5915.1  880.56  5950.7  880.57  5971.7  883.69  6105.8  890.61
#Mann=5,-1,0
  4212.9    0.05       0  4535.6    0.12       0  4994.4    0.07       0
  5003.9    0.12       0  5119.9    0.05       0
Bank Sta=4994.4,5003.9
Exp/Cntr=0.3,0.1