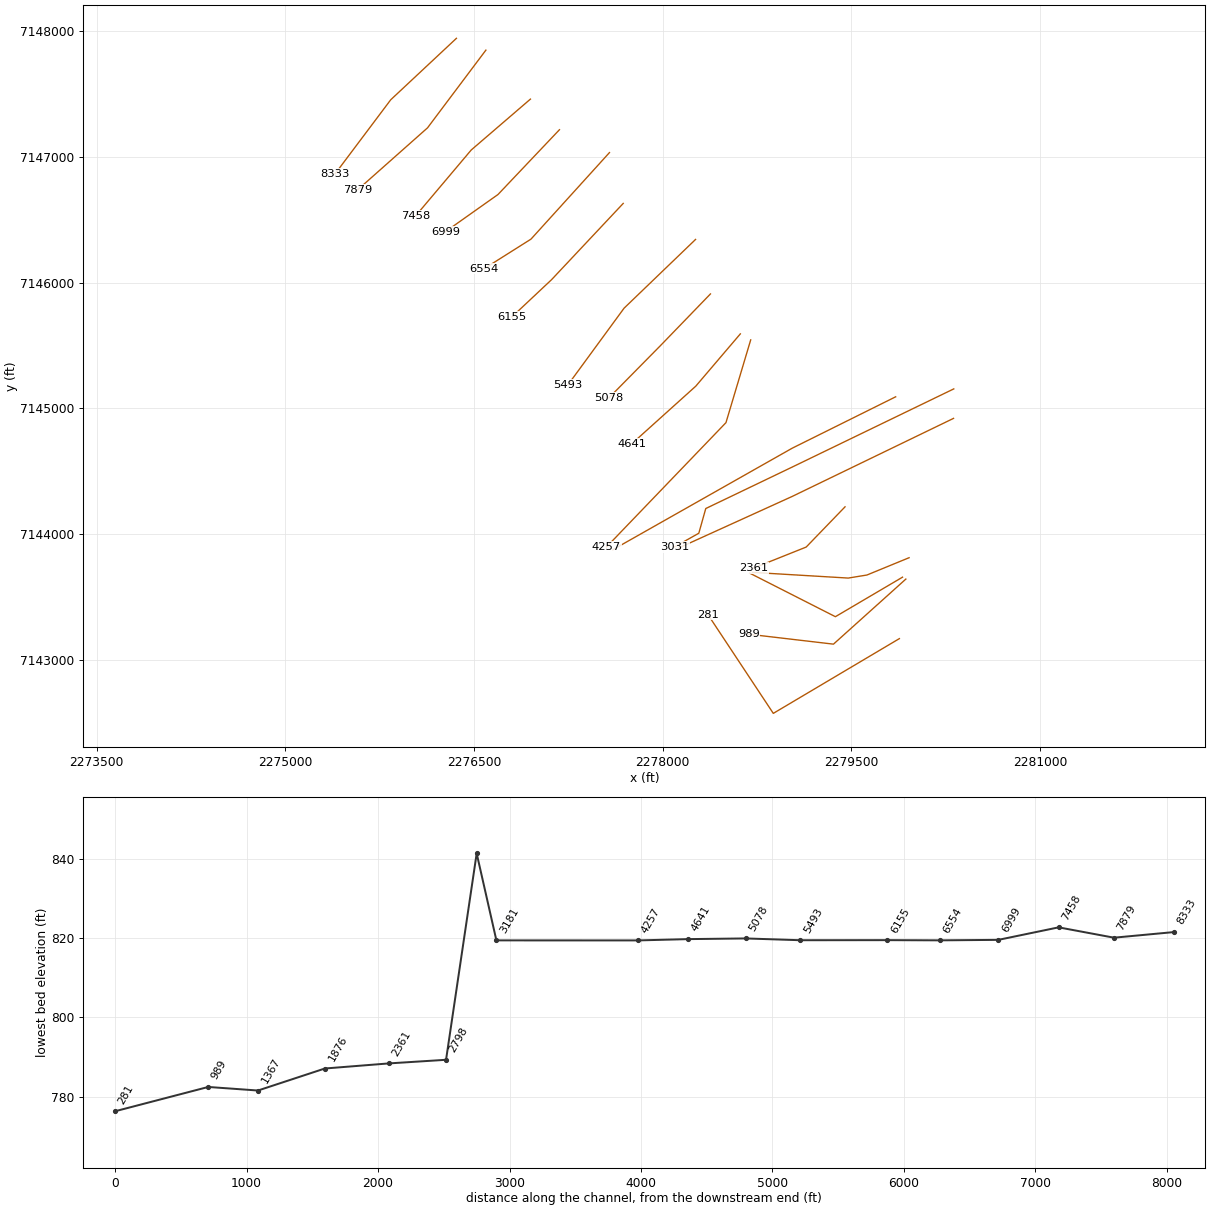
HEC-RAS study MDW T 093.prj: MDW T 093 Base Level Engineering

--- MDW T 093.g01 (geometry) --- (continued)

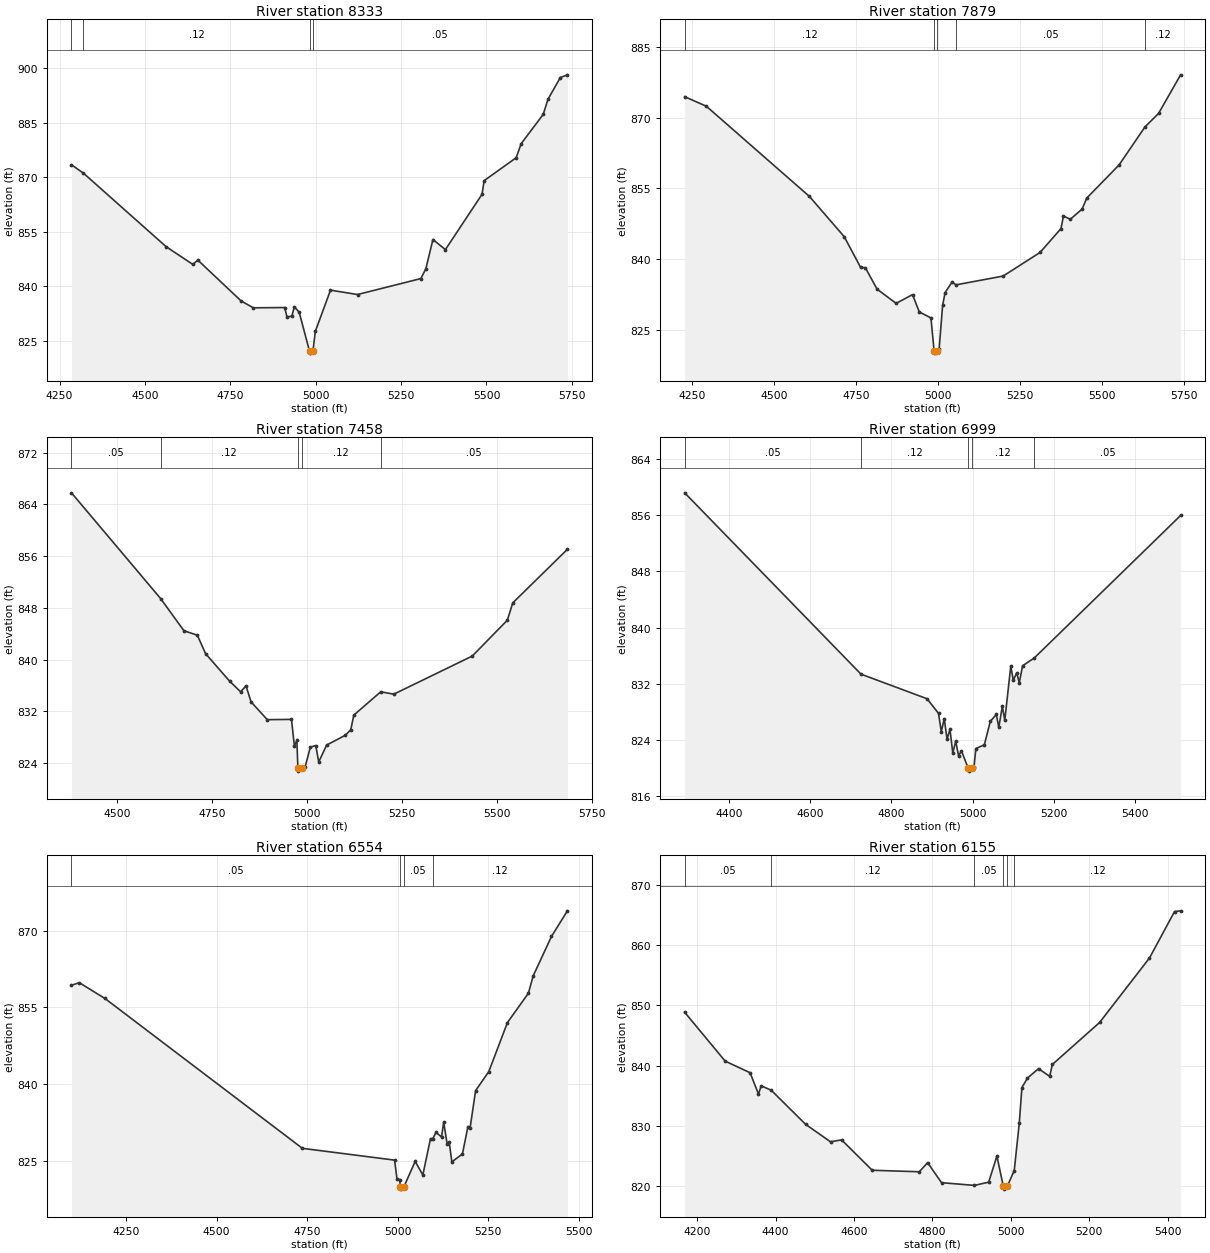
Type RM Length L Ch R = 1,8333,454,454,454
BEGIN DESCRIPTION:
MDW T 093 15.0
END DESCRIPTION:
XS GIS Cut Line= 3
      2276359.21      7147942.01      2275837.04      7147453.58
      2275394.43      7146864.41
#Sta/Elev= 30
  4285.0  873.38  4320.1  871.07  4562.4  850.82  4640.5  845.95  4654.7  847.17
  4781.7  835.90  4817.4  834.01  4909.2  834.09  4916.0  831.50  4930.2  831.73
  4937.5  834.29  4951.7  832.80  4982.0  822.04  4983.4  821.54  4991.8  822.04
  4999.0  827.54  5043.3  838.87  5122.5  837.67  5307.8  842.06  5322.4  844.73
  5343.2  852.81  5379.7  850.03  5486.9  865.25  5493.2  869.02  5586.9  875.32
  5601.5  879.19  5666.1  887.25  5679.9  891.39  5716.1  897.39  5736.9  898.14
#Mann=4,-1,0
  4285.0    0.05       0  4320.1    0.12       0  4982.0   0.033       0
  4991.8    0.05       0
Bank Sta=4982,4991.8
Exp/Cntr=0.3,0.1

Type RM Length L Ch R = 1,7879,421,421,421
BEGIN DESCRIPTION:
MDW T 093 14.0
END DESCRIPTION:
XS GIS Cut Line= 3
      2276593.56      7147848.23      2276129.37      7147230.12
      2275575.31      7146738.84
#Sta/Elev= 30
  4227.0  874.43  4293.2  872.41  4607.7  853.31  4714.0  844.78  4764.0  838.27
  4778.6  838.20  4814.0  833.69  4872.3  830.67  4922.3  832.52  4943.1  828.84
  4978.5  827.59  4988.2  820.63  4989.5  820.13  4998.0  820.63  5003.6  821.01
  5014.1  830.22  5021.7  832.93  5042.6  835.15  5055.2  834.59  5199.0  836.45
  5311.9  841.47  5375.4  846.51  5383.0  849.16  5403.9  848.48  5439.8  850.63
  5454.1  852.97  5552.7  859.98  5631.8  868.04  5673.2  870.89  5740.5  879.06
#Mann=5,-1,0
  4227.0    0.12       0  4988.2    0.07       0  4998.0    0.12       0
  5055.2    0.05       0  5631.8    0.12       0
Bank Sta=4988.2,4998
Exp/Cntr=0.3,0.1

Type RM Length L Ch R = 1,7458,459,459,459
BEGIN DESCRIPTION:
MDW T 093 13.0
END DESCRIPTION:
XS GIS Cut Line= 3
      2276947.73      7147458.92      2276477.01      7147054.32
      2276034.96      7146530.52
#Sta/Elev= 30
  4379.3  865.78  4614.1  849.43  4675.6  844.44  4710.7  843.77  4732.6  840.90
  4796.3  836.62  4824.8  835.01  4839.0  835.92  4852.3  833.45  4895.0  830.70
  4958.7  830.74  4966.3  826.66  4972.9  827.48  4975.6  823.24  4977.0  822.74
  4985.6  823.24  4994.9  823.44  5008.4  826.45  5022.7  826.70  5030.5  824.16
  5051.3  826.77  5100.7  828.29  5115.0  829.16  5122.8  831.40  5193.8  835.01
  5228.2  834.64  5434.9  840.54  5527.2  846.08  5541.5  848.76  5685.4  857.05
#Mann=5,-1,0
  4379.3    0.05       0  4614.1    0.12       0  4975.6    0.07       0
  4985.6    0.12       0  5193.8    0.05       0
Bank Sta=4975.6,4985.6
Exp/Cntr=0.3,0.1

Type RM Length L Ch R = 1,6999,445,445,445
BEGIN DESCRIPTION:
MDW T 093 12.0
END DESCRIPTION:
XS GIS Cut Line= 3
      2277178.43      7147215.55      2276689.78      7146700.32
      2276270.80      7146403.96
#Sta/Elev= 30
  4289.9  859.18  4724.8  833.38  4887.7  829.88  4916.0  827.80  4922.9  825.20
  4930.2  827.06  4937.1  824.11  4944.3  825.55  4951.2  822.14  4958.5  823.87
  4965.4  821.77  4972.7  822.46  4988.7  820.08  4990.1  819.58  4998.8  820.08
  5003.5  820.11  5008.1  822.79  5029.1  823.33  5043.8  826.66  5058.6  827.64
  5064.7  825.81  5073.4  828.79  5079.5  826.82  5094.3  834.54  5100.4  832.51
  5109.1  833.58  5115.2  832.12  5123.4  834.57  5152.2  835.68  5513.2  855.96
#Mann=5,-1,0
  4289.9    0.05       0  4724.8    0.12       0  4988.7    0.07       0
  4998.8    0.12       0  5152.2    0.05       0
Bank Sta=4988.7,4998.8
Exp/Cntr=0.3,0.1

Type RM Length L Ch R = 1,6554,399,399,399
BEGIN DESCRIPTION:
MDW T 093 11.0
END DESCRIPTION:
XS GIS Cut Line= 3
      2277576.04      7147033.67      2276952.20      7146345.70
      2276578.99      7146110.00
#Sta/Elev= 30
  4099.0  859.32  4120.6  859.83  4191.5  856.74  4736.9  827.44  4991.7  825.13
  4998.4  821.37  5005.9  821.34  5007.5  819.96  5008.9  819.46  5017.7  819.96
  5048.5  824.88  5069.7  822.23  5090.9  829.35  5096.4  829.23  5106.1  830.55
  5121.4  829.67  5127.3  832.55  5136.7  828.38  5142.6  828.67  5149.8  824.78
  5179.1  826.34  5194.3  831.69  5200.3  831.45  5215.5  838.73  5252.0  842.45
  5303.5  852.04  5361.4  857.77  5374.5  861.15  5425.0  868.86  5469.1  873.88
#Mann=4,-1,0
  4099.0    0.05       0  5007.5   0.033       0  5017.7    0.05       0
  5096.4    0.12       0
Bank Sta=5007.5,5017.7
Exp/Cntr=0.3,0.1

Type RM Length L Ch R = 1,6155,662,662,662
BEGIN DESCRIPTION:
MDW T 093 10.0
END DESCRIPTION:
XS GIS Cut Line= 3
      2277685.44      7146629.59      2277115.62      7146023.21
      2276800.06      7145726.85
#Sta/Elev= 30
  4167.9  848.85  4271.2  840.74  4334.7  838.82  4356.2  835.28  4363.1  836.64
  4388.5  835.92  4476.4  830.26  4539.9  827.36  4568.2  827.68  4646.3  822.64
  4766.5  822.39  4787.5  823.91  4823.1  820.58  4907.1  820.13  4943.3  820.67
  4964.3  825.00  4980.6  820.01  4982.1  819.51  4990.9  820.01  5008.5  822.59
  5021.3  830.40  5028.1  836.35  5042.3  837.94  5070.6  839.49  5098.9  838.22
  5105.8  840.19  5226.4  847.16  5353.4  857.84  5417.4  865.55  5432.9  865.67
#Mann=6,-1,0
  4167.9    0.05       0  4388.5    0.12       0  4907.1    0.05       0
  4980.6   0.033       0  4990.9    0.05       0  5008.5    0.12       0
Bank Sta=4980.6,4990.9
Exp/Cntr=0.3,0.1

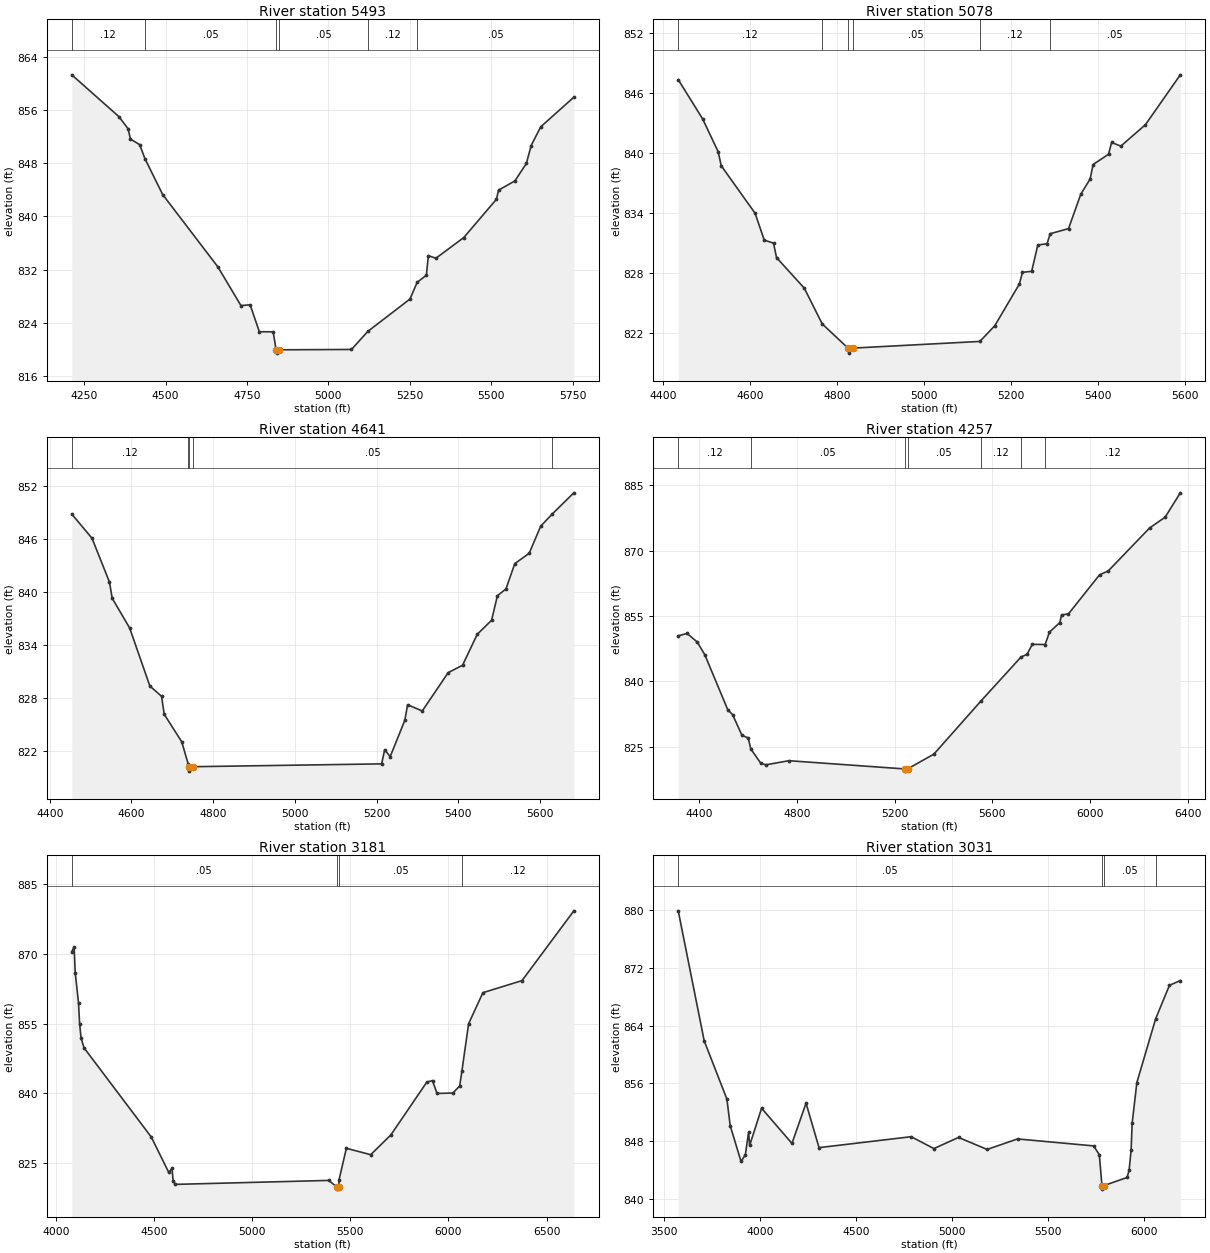
Type RM Length L Ch R = 1,5493,415,415,415
BEGIN DESCRIPTION:
MDW T 093 9.0
END DESCRIPTION:
XS GIS Cut Line= 3
      2278260.52      7146343.13      2277692.38      7145796.79
      2277247.06      7145188.59
#Sta/Elev= 30
  4211.8  861.26  4356.5  854.99  4384.8  853.16  4392.0  851.62  4420.3  850.78
  4436.5  848.68  4491.0  843.29  4660.6  832.43  4731.3  826.63  4759.6  826.74
  4787.9  822.70  4830.4  822.69  4839.3  819.99  4840.8  819.49  4849.7  819.99
  5070.8  820.04  5121.2  822.76  5250.6  827.61  5272.6  830.12  5300.8  831.18
  5307.0  834.12  5330.1  833.73  5415.8  836.84  5516.2  842.59  5522.4  843.95
  5572.6  845.33  5608.1  847.97  5622.7  850.65  5652.1  853.46  5753.8  857.90
#Mann=6,-1,0
  4211.8    0.12       0  4436.5    0.05       0  4839.3   0.033       0
  4849.7    0.05       0  5121.2    0.12       0  5272.6    0.05       0
Bank Sta=4839.3,4849.7
Exp/Cntr=0.3,0.1

Type RM Length L Ch R = 1,5078,437,437,437
BEGIN DESCRIPTION:
MDW T 093 8.0
END DESCRIPTION:
XS GIS Cut Line= 3
      2278378.97      7145909.97      2277985.68      7145503.34
      2277571.74      7145083.62
#Sta/Elev= 30
  4434.3  847.29  4490.7  843.34  4526.2  840.08  4533.2  838.68  4611.1  833.93
  4632.2  831.24  4653.5  830.94  4660.5  829.49  4724.3  826.44  4765.6  822.86
  4825.0  820.44  4826.5  819.94  4835.5  820.44  5128.3  821.11  5162.6  822.68
  5219.2  826.85  5226.3  828.02  5247.5  828.12  5261.6  830.75  5282.9  830.88
  5290.1  831.88  5332.3  832.39  5360.6  835.84  5381.9  837.34  5388.9  838.80
  5424.3  839.83  5431.4  841.01  5452.6  840.64  5509.2  842.78  5589.5  847.77
#Mann=6,-1,0
  4434.3    0.12       0  4765.6    0.05       0  4825.0   0.033       0
  4835.5    0.05       0  5128.3    0.12       0  5290.1    0.05       0
Bank Sta=4825,4835.5
Exp/Cntr=0.3,0.1

Type RM Length L Ch R = 1,4641,384,384,384
BEGIN DESCRIPTION:
MDW T 093 7.0
END DESCRIPTION:
XS GIS Cut Line= 3
      2278616.45      7145592.28      2278262.35      7145176.67
      2277754.87      7144719.86
#Sta/Elev= 30
  4454.0  848.82  4503.5  846.09  4546.3  841.13  4552.9  839.31  4595.7  835.94
  4645.1  829.39  4673.7  828.23  4680.3  826.19  4723.1  823.09  4738.8  820.60
  4739.8  820.27  4741.3  819.77  4750.4  820.27  5212.4  820.59  5219.8  822.19
  5233.3  821.41  5269.2  825.52  5275.9  827.27  5311.8  826.57  5375.3  830.90
  5410.5  831.74  5446.3  835.23  5481.5  836.82  5495.7  839.59  5516.6  840.36
  5538.3  843.22  5573.4  844.38  5601.8  847.46  5630.4  848.85  5682.8  851.22
#Mann=5,-1,0
  4454.0    0.12       0  4738.8    0.05       0  4739.8   0.033       0
  4750.4    0.05       0  5630.4    0.12       0
Bank Sta=4739.8,4750.4
Exp/Cntr=0.3,0.1

Type RM Length L Ch R = 1,4257,1076,1076,1076
BEGIN DESCRIPTION:
MDW T 093 6.0
END DESCRIPTION:
XS GIS Cut Line= 3
      2278698.92      7145544.57      2278502.31      7144886.62
      2277552.70      7143898.44
#Sta/Elev= 30
  4313.3  850.46  4349.4  851.01  4391.1  849.05  4422.4  846.10  4516.4  833.49
  4536.0  832.40  4574.4  827.65  4599.9  827.05  4610.8  824.51  4652.1  821.21
  4672.9  820.89  4766.9  821.83  5242.1  819.94  5243.5  819.44  5252.7  819.94
  5360.6  823.33  5554.3  835.56  5717.9  845.60  5742.7  846.23  5763.8  848.51
  5816.6  848.47  5834.5  851.32  5877.0  853.50  5883.9  855.25  5912.2  855.50
  6039.5  864.44  6075.1  865.33  6244.6  875.19  6308.4  877.67  6370.5  883.25
#Mann=7,-1,0
  4313.3    0.12       0  4610.8    0.05       0  5242.1   0.033       0
  5252.7    0.05       0  5554.3    0.12       0  5717.9    0.05       0
  5816.6    0.12       0
Bank Sta=5242.1,5252.7
Exp/Cntr=0.3,0.1

Type RM Length L Ch R = 1,3181,150,150,150
BEGIN DESCRIPTION:
MDW T 093 5.0
END DESCRIPTION:
XS GIS Cut Line= 3
      2279851.46      7145091.99      2279028.99      7144683.56
      2277602.48      7143875.87
#Sta/Elev= 30
  4081.7  870.47  4093.7  871.46  4099.3  865.96  4116.1  859.40  4121.7  854.98
  4129.1  851.88  4144.1  849.80  4486.4  830.66  4575.7  823.05  4592.3  823.90
  4598.0  821.23  4609.1  820.47  5390.7  821.32  5430.8  819.95  5432.4  819.45
  5442.5  819.95  5443.0  821.42  5480.5  828.22  5604.6  826.85  5707.1  831.09
  5890.4  842.44  5919.3  842.77  5942.3  840.00  6022.8  840.09  6057.7  841.60
  6069.2  844.85  6103.2  854.98  6176.1  861.65  6375.2  864.24  6639.3  879.23
#Mann=4,-1,0
  4081.7    0.05       0  5430.8   0.033       0  5442.5    0.05       0
  6069.2    0.12       0
Bank Sta=5430.8,5442.5
Exp/Cntr=0.3,0.1

Type RM Length L Ch R = 1,3031,233,233,233
BEGIN DESCRIPTION:
MDW T 093 4.5
END DESCRIPTION:
XS GIS Cut Line= 5
      2280313.44      7145154.91      2279030.94      7144534.37
      2278341.72      7144203.78      2278286.38      7144007.37
      2278092.50      7143898.41
#Sta/Elev= 30
  3573.1  879.84  3708.2  861.90  3826.7  853.84  3843.8  850.18  3900.2  845.23
  3922.6  846.12  3939.7  849.29  3945.2  847.45  4007.4  852.58  4165.6  847.72
  4238.9  853.28  4306.6  847.14  4786.6  848.65  4905.1  847.01  5033.3  848.55
  5182.2  846.89  5340.7  848.34  5736.9  847.38  5766.8  846.17  5780.4  841.91
  5782.0  841.41  5792.1  841.91  5911.6  843.02  5922.0  844.03  5932.4  846.79
  5937.9  850.52  5962.3  856.12  6060.5  864.95  6132.0  869.55  6188.7  870.21
#Mann=4,-1,0
  3573.1    0.05       0  5780.4   0.033       0  5792.1    0.05       0
  6060.5    0.12       0
Bank Sta=5780.4,5792.1
Exp/Cntr=0.3,0.1

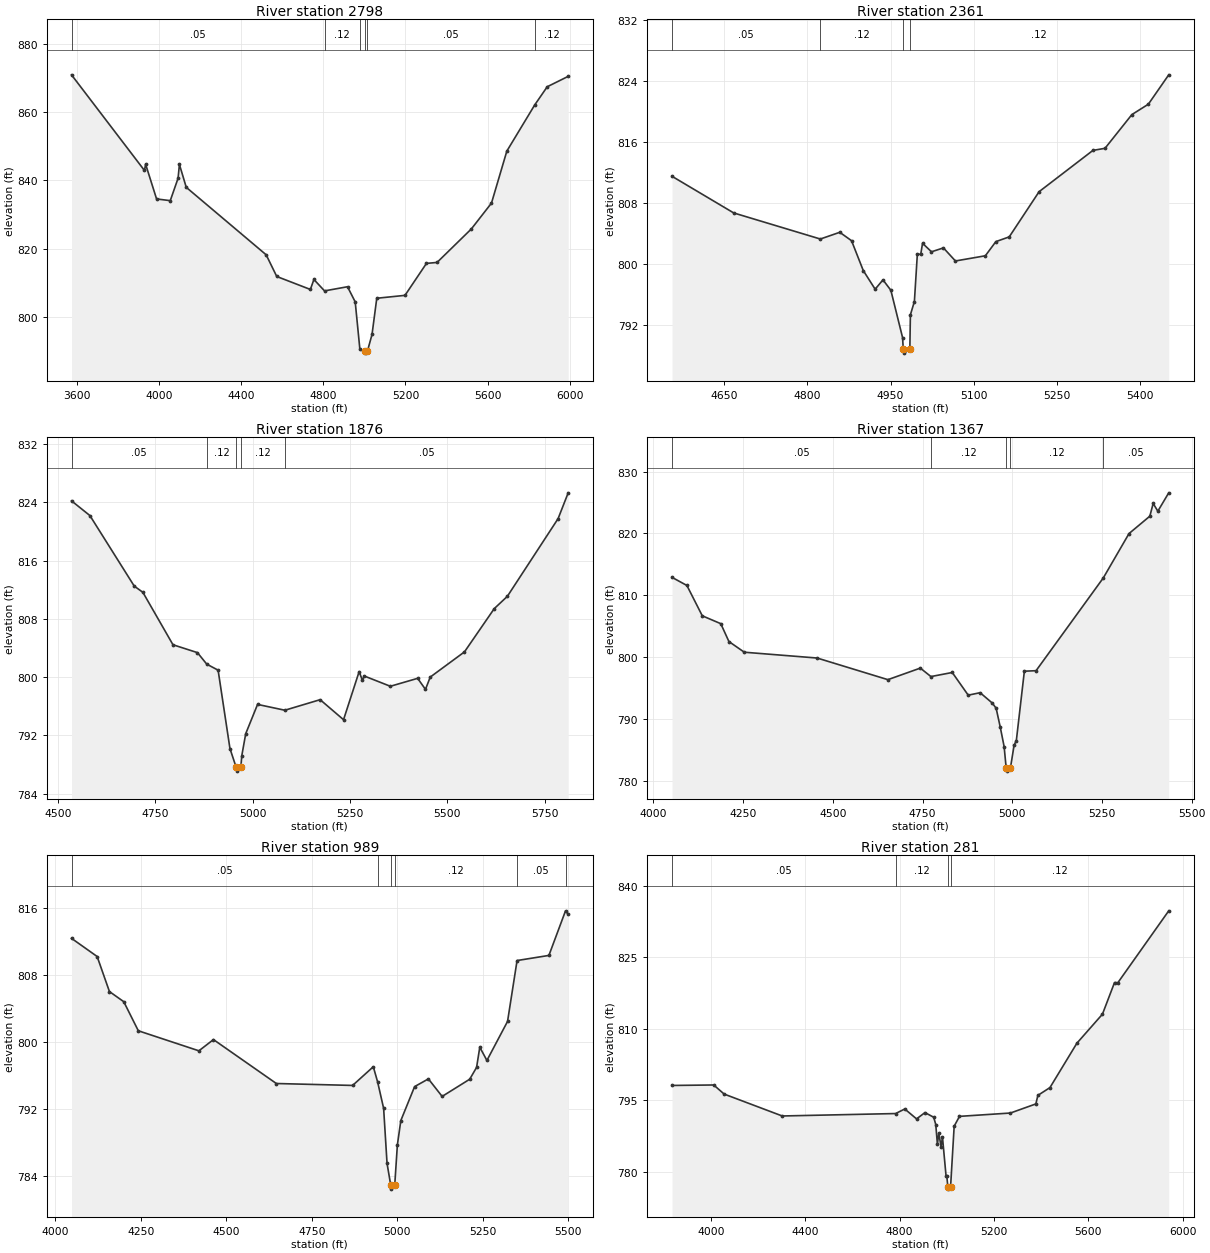
Type RM Length L Ch R = 1,2798,437,437,437
BEGIN DESCRIPTION:
MDW T 093 4.0
END DESCRIPTION:
XS GIS Cut Line= 3
      2280311.55      7144920.56      2279028.99      7144299.99
      2278126.14      7143889.71
#Sta/Elev= 30
  3575.2  870.96  3930.2  842.89  3935.7  844.74  3989.1  834.54  4055.7  834.04
  4093.8  840.63  4100.2  844.67  4133.5  837.95  4522.3  818.15  4573.8  811.79
  4737.4  807.98  4754.5  810.91  4806.3  807.56  4918.1  808.78  4955.5  804.33
  4978.0  790.56  5002.9  789.80  5004.5  789.30  5014.6  789.80  5037.3  794.77
  5060.4  805.40  5197.7  806.25  5302.1  815.63  5353.7  815.91  5520.7  825.75
  5618.5  833.32  5693.2  848.58  5828.9  862.13  5889.7  867.46  5991.7  870.51
#Mann=6,-1,0
  3575.2    0.05       0  4806.3    0.12       0  4978.0    0.05       0
  5002.9   0.033       0  5014.6    0.05       0  5828.9    0.12       0
Bank Sta=5002.9,5014.6
Exp/Cntr=0.3,0.1

Type RM Length L Ch R = 1,2361,485,485,485
BEGIN DESCRIPTION:
Mapping XS 620edf8e
END DESCRIPTION:
XS GIS Cut Line= 3
      2279448.93      7144217.27      2279140.03      7143897.44
      2278722.22      7143730.43
#Sta/Elev= 30
  4556.4  811.50  4667.5  806.71  4823.5  803.30  4858.5  804.18  4879.7  803.08
  4900.8  799.18  4922.2  796.74  4936.3  797.96  4950.5  796.60  4971.6  790.41
  4972.9  788.88  4974.5  788.38  4984.7  788.88  4985.7  793.39  4992.9  795.13
  4998.2  801.31  5004.3  801.31  5007.6  802.74  5023.7  801.63  5045.2  802.14
  5066.8  800.43  5120.7  801.11  5139.6  802.96  5163.7  803.58  5217.5  809.49
  5314.5  814.89  5336.2  815.16  5384.6  819.57  5414.3  820.93  5451.0  824.77
#Mann=4,-1,0
  4556.4    0.05       0  4823.5    0.12       0  4972.9    0.07       0
  4984.7    0.12       0
Bank Sta=4972.9,4984.7
Exp/Cntr=0.3,0.1

Type RM Length L Ch R = 1,1876,509,509,509
BEGIN DESCRIPTION:
Mapping XS6228
END DESCRIPTION:
XS GIS Cut Line= 4
      2279958.15      7143812.75      2279623.19      7143675.21
      2279474.31      7143650.93      2278713.10      7143696.19
#Sta/Elev= 30
  4535.1  824.21  4582.3  822.19  4696.3  812.50  4718.4  811.65  4795.7  804.45
  4858.5  803.37  4882.4  801.79  4911.6  800.96  4942.0  790.20  4958.1  787.60
  4959.7  787.10  4969.9  787.60  4972.4  789.22  4982.5  792.24  5012.9  796.26
  5083.0  795.46  5173.6  796.91  5233.7  794.16  5273.8  800.77  5281.9  799.59
  5286.9  800.16  5353.9  798.75  5424.0  799.84  5444.1  798.32  5456.3  800.01
  5544.2  803.47  5620.7  809.41  5654.4  811.10  5784.7  821.77  5810.6  825.31
#Mann=5,-1,0
  4535.1    0.05       0  4882.4    0.12       0  4958.1    0.07       0
  4969.9    0.12       0  5083.0    0.05       0
Bank Sta=4958.1,4969.9
Exp/Cntr=0.3,0.1

Type RM Length L Ch R = 1,1367,378,378,378
BEGIN DESCRIPTION:
Mapping XS 776943e9
END DESCRIPTION:
XS GIS Cut Line= 3
      2279906.04      7143658.11      2279372.32      7143343.87
      2278690.32      7143690.52
#Sta/Elev= 30
  4051.7  812.89  4093.1  811.58  4136.0  806.67  4187.5  805.40  4210.2  802.51
  4253.1  800.78  4456.1  799.84  4653.3  796.34  4743.7  798.21  4773.3  796.84
  4832.7  797.50  4877.2  793.83  4910.4  794.23  4944.0  792.57  4955.0  791.72
  4966.4  788.69  4977.3  785.51  4983.0  782.04  4984.6  781.54  4994.8  782.04
  5005.2  785.76  5011.3  786.47  5033.7  797.71  5066.3  797.79  5253.8  812.81
  5325.4  819.98  5383.4  822.79  5392.7  824.85  5405.7  823.60  5436.1  826.57
#Mann=5,-1,0
  4051.7    0.05       0  4773.3    0.12       0  4983.0    0.07       0
  4994.8    0.12       0  5253.8    0.05       0
Bank Sta=4983,4994.8
Exp/Cntr=0.3,0.1

Type RM Length L Ch R = 1,989,708,708,708
BEGIN DESCRIPTION:
Mapping XS 27dc0d2a
END DESCRIPTION:
XS GIS Cut Line= 3
      2279932.40      7143642.81      2279356.97      7143125.55
      2278682.94      7143204.62
#Sta/Elev= 30
  4047.1  812.36  4122.1  810.19  4158.0  806.01  4199.9  804.80  4242.5  801.33
  4419.6  798.94  4462.2  800.28  4646.1  795.04  4869.1  794.81  4929.6  797.04
  4942.1  795.25  4959.8  792.08  4969.8  785.51  4980.5  782.94  4982.1  782.44
  4992.3  782.94  5000.0  787.71  5010.1  790.62  5050.4  794.67  5090.7  795.59
  5130.9  793.50  5211.5  795.55  5231.6  796.96  5241.0  799.37  5261.8  797.79
  5322.2  802.45  5350.0  809.71  5443.1  810.32  5491.7  815.64  5499.5  815.24
#Mann=6,-1,0
  4047.1    0.05       0  4942.1    0.12       0  4980.5    0.07       0
  4992.3    0.12       0  5350.0    0.05       0  5491.7    0.12       0
Bank Sta=4980.5,4992.3
Exp/Cntr=0.3,0.1

Type RM Length L Ch R = 1,281,0,0,0
BEGIN DESCRIPTION:
MDW T 093 1.0
END DESCRIPTION:
XS GIS Cut Line= 3
      2279880.98      7143169.60      2278878.57      7142575.18
      2278359.25      7143360.02
#Sta/Elev= 30
  3834.6  798.08  4011.3  798.18  4055.6  796.27  4301.9  791.67  4782.8  792.18
  4821.6  793.14  4871.6  791.06  4907.3  792.38  4944.4  791.40  4953.0  789.88
  4960.0  785.75  4965.8  788.05  4975.6  785.24  4981.4  787.28  4996.8  779.02
  5000.0  779.02  5004.1  776.81  5005.8  776.31  5015.9  776.81  5031.1  789.53
  5053.7  791.59  5269.6  792.29  5377.5  794.20  5386.2  796.00  5437.3  797.63
  5551.7  806.96  5660.0  813.05  5711.1  819.68  5725.2  819.65  5941.1  834.75
#Mann=4,-1,0
  3834.6    0.05       0  4782.8    0.12       0  5004.1    0.07       0
  5015.9    0.12       0
Bank Sta=5004.1,5015.9
Exp/Cntr=0.3,0.1

Chan Stop Cuts=-1