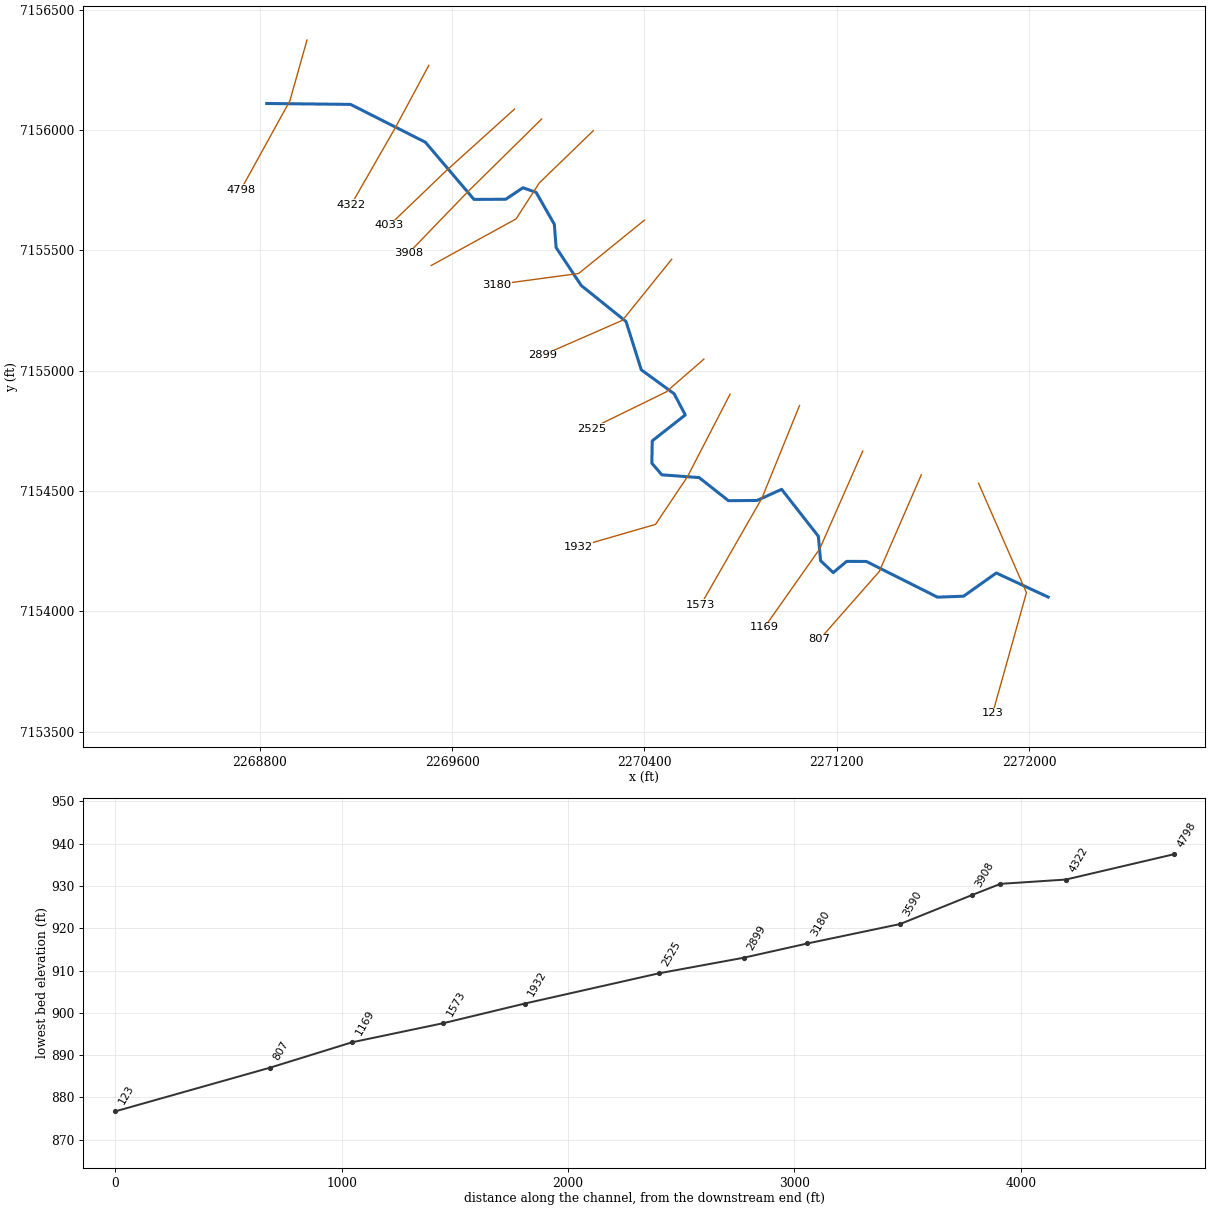
--- MDW T 094.prj (project) ---

Proj Title=MDW T 094 Base Level Engineering
Current Plan=p01
Default Exp/Contr=0.3,0.1
English Units
Geom File=g01
Flow File=f01
Plan File=p01
BEGIN DESCRIPTION:
MDW T 094
END DESCRIPTION:

--- MDW T 094.p01 (plan) ---

Plan Title=Multiple Run
Short Identifier=Multiple
Geom File=g01
Flow File=f01
Subcritical Flow
K Sum by GR= 0
Std Step Tol= 0.01
Critical Tol= 0.01
Num of Std Step Trials= 20
Max Error Tol= 0.3
Flow Tol Ratio= 0.001
Split Flow NTrial= 30
Split Flow Tol= 0.02
Split Flow Ratio= 0.02
Log Output Level= 0
Friction Slope Method= 1
Unsteady Friction Slope Method= 2
Unsteady Bridges Friction Slope Method= 1
Parabolic Critical Depth
Global Vel Dist=  1 , 1 , 1
Global Log Level= 0
CheckData=True
Encroach Param= -1, 0, 0, 0
BEGIN DESCRIPTION:
Multiple Run
END DESCRIPTION:

--- MDW T 094.f01 (steady flow) ---

Flow Title=Multiple
Number of Profiles=7
Profile Names=10-year,25-year,50-year,1pct_min,100-year,1pct_plu,500-year
River Rch & RM= MDW T 094,Reach-1,4798
     636     878    1079     659    1316    2625    1958
Boundary for River Rch & Prof#=MDW T 094,Reach-1,1
Up Type=0
Dn Type=3
Dn Slope=0.005
Boundary for River Rch & Prof#=MDW T 094,Reach-1,2
Up Type=0
Dn Type=3
Dn Slope=0.005
Boundary for River Rch & Prof#=MDW T 094,Reach-1,3
Up Type=0
Dn Type=3
Dn Slope=0.005
Boundary for River Rch & Prof#=MDW T 094,Reach-1,4
Up Type=0
Dn Type=3
Dn Slope=0.005
Boundary for River Rch & Prof#=MDW T 094,Reach-1,5
Up Type=0
Dn Type=3
Dn Slope=0.005
Boundary for River Rch & Prof#=MDW T 094,Reach-1,6
Up Type=0
Dn Type=3
Dn Slope=0.005
Boundary for River Rch & Prof#=MDW T 094,Reach-1,7
Up Type=0
Dn Type=3
Dn Slope=0.005

--- MDW T 094.g01 (geometry) ---

Geom Title=Existing Conditions

River Reach=MDW T 094,Reach-1
Reach XY= 30
      2268829.00      7156110.00      2269177.45      7156106.25
      2269488.68      7155949.24      2269690.83      7155711.61
      2269823.06      7155712.27      2269894.48      7155759.99
      2269949.48      7155740.74      2270025.17      7155608.42
      2270032.62      7155511.50      2270137.16      7155353.95
      2270323.41      7155204.39      2270386.86      7155003.81
      2270523.44      7154904.38      2270569.84      7154816.44
      2270432.37      7154708.71      2270430.87      7154615.69
      2270472.47      7154567.68      2270627.47      7154556.25
      2270749.29      7154460.24      2270868.50      7154461.23
      2270970.52      7154507.37      2271123.47      7154312.42
      2271132.55      7154211.21      2271185.19      7154161.43
      2271240.99      7154208.09      2271322.95      7154207.88
      2271618.83      7154059.49      2271727.53      7154063.54
      2271863.58      7154159.97      2272079.00      7154060.00

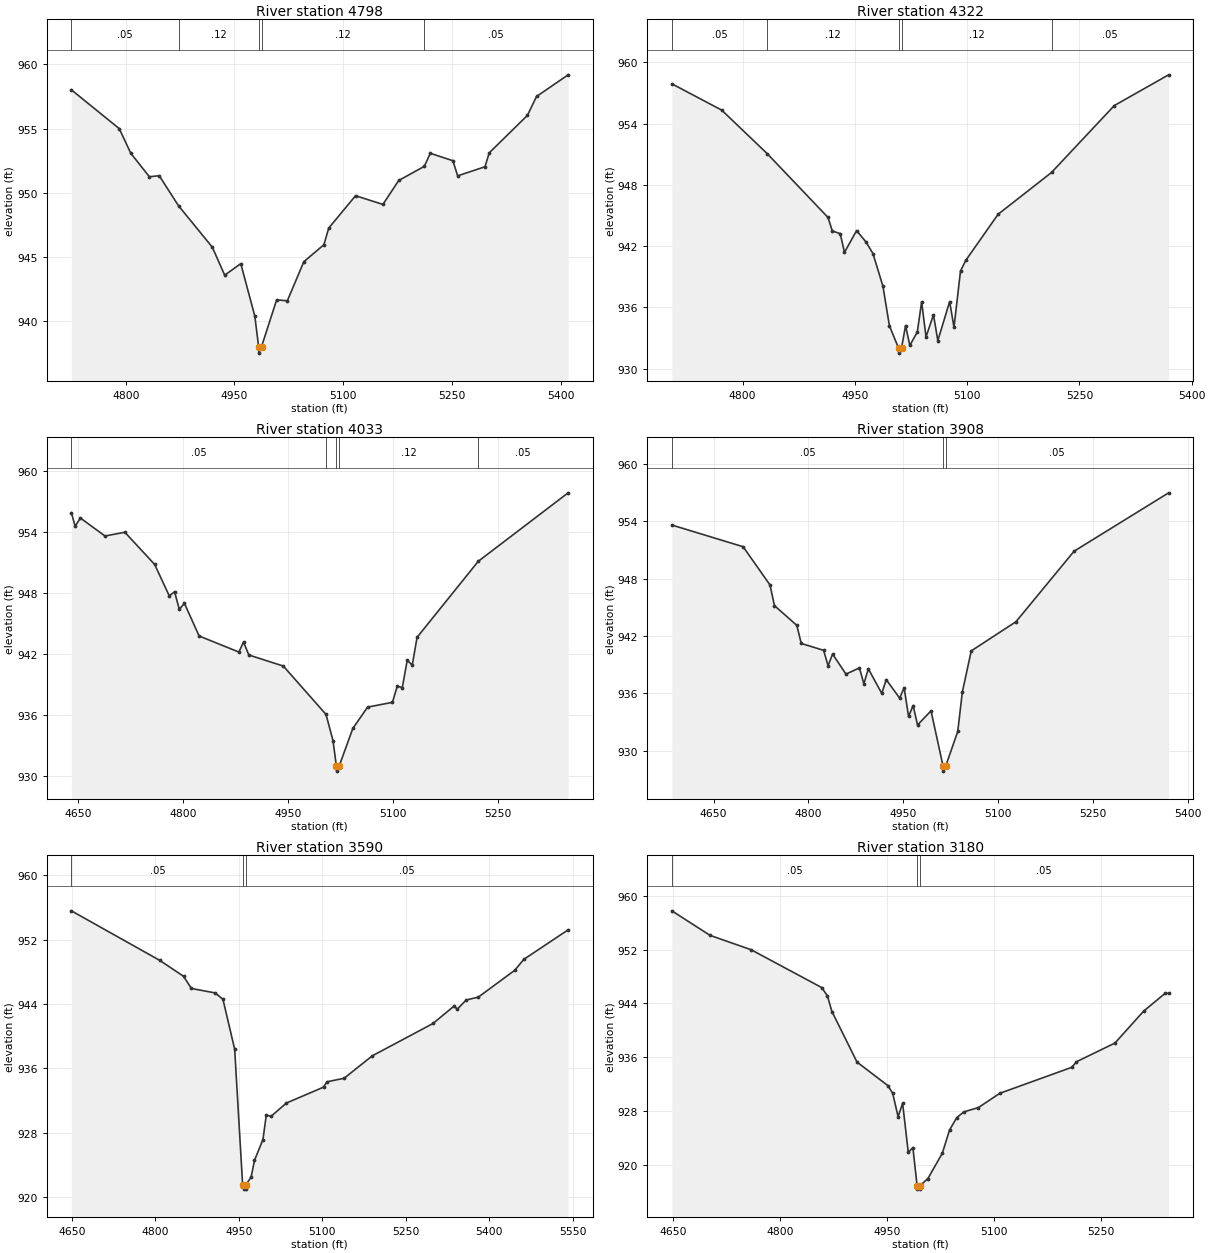
Type RM Length L Ch R = 1,4798,476,476,476
BEGIN DESCRIPTION:
MDW T 094 12.0
END DESCRIPTION:
XS GIS Cut Line= 3
      2268996.32      7156373.62      2268925.22      7156121.07
      2268720.74      7155750.86
#Sta/Elev= 30
  4725.0  958.02  4791.1  954.99  4807.0  953.07  4832.6  951.24  4846.2  951.32
  4872.9  948.97  4919.5  945.74  4936.5  943.56  4958.7  944.46  4978.1  940.36
  4983.3  937.98  4983.6  937.48  4987.3  937.98  5008.2  941.64  5022.9  941.56
  5045.7  944.61  5073.4  945.94  5080.0  947.23  5117.0  949.76  5154.8  949.08
  5176.6  950.95  5211.9  952.05  5220.1  953.07  5251.3  952.49  5257.9  951.31
  5295.7  952.02  5301.4  953.10  5354.2  956.03  5366.7  957.50  5410.3  959.19
#Mann=5,-1,0
  4725.0    0.05       0  4872.9    0.12       0  4983.3    0.07       0
  4987.3    0.12       0  5211.9    0.05       0
Bank Sta=4983.3,4987.3
Exp/Cntr=0.3,0.1

Type RM Length L Ch R = 1,4322,289,289,289
BEGIN DESCRIPTION:
MDW T 094 11.0
END DESCRIPTION:
XS GIS Cut Line= 3
      2269503.03      7156268.35      2269363.61      7156009.06
      2269179.68      7155688.94
#Sta/Elev= 30
  4705.6  957.91  4772.2  955.33  4832.9  951.07  4914.2  944.81  4919.9  943.49
  4930.5  943.22  4936.2  941.39  4952.4  943.52  4964.9  942.41  4974.3  941.26
  4987.6  938.06  4996.2  934.20  5008.4  932.01  5008.7  931.51  5012.4  932.01
  5017.8  934.21  5023.5  932.26  5033.5  933.59  5039.3  936.55  5045.1  933.10
  5055.1  935.27  5060.9  932.73  5076.7  936.56  5082.5  934.04  5091.2  939.56
  5098.3  940.61  5141.4  945.12  5212.8  949.22  5296.7  955.78  5369.2  958.79
#Mann=5,-1,0
  4705.6    0.05       0  4832.9    0.12       0  5008.4    0.07       0
  5012.4    0.12       0  5212.8    0.05       0
Bank Sta=5008.4,5012.4
Exp/Cntr=0.3,0.1

Type RM Length L Ch R = 1,4033,125,125,125
BEGIN DESCRIPTION:
MDW T 094 10.0
END DESCRIPTION:
XS GIS Cut Line= 3
      2269859.82      7156086.97      2269573.50      7155828.93
      2269339.43      7155604.53
#Sta/Elev= 30
  4640.5  955.92  4645.9  954.59  4653.4  955.40  4688.5  953.63  4716.9  954.00
  4759.5  950.83  4780.4  947.73  4787.9  948.15  4794.6  946.43  4802.1  946.99
  4823.0  943.79  4879.8  942.21  4886.5  943.19  4894.0  941.92  4943.3  940.83
  5004.3  936.07  5014.3  933.49  5019.1  930.99  5019.3  930.49  5023.1  930.99
  5042.6  934.69  5063.7  936.79  5099.2  937.26  5106.1  938.85  5113.3  938.71
  5120.3  941.41  5127.5  940.92  5134.4  943.66  5221.8  951.14  5350.2  957.88
#Mann=5,-1,0
  4640.5    0.05       0  5004.3    0.12       0  5019.1   0.033       0
  5023.1    0.12       0  5221.8    0.05       0
Bank Sta=5019.1,5023.1
Exp/Cntr=0.3,0.1

Type RM Length L Ch R = 1,3908,318,318,318
BEGIN DESCRIPTION:
MDW T 094 9.5
END DESCRIPTION:
XS GIS Cut Line= 3
      2269972.67      7156045.73      2269661.69      7155739.85
      2269418.95      7155488.68
#Sta/Elev= 30
  4584.0  953.61  4696.7  951.34  4739.2  947.34  4746.2  945.18  4781.6  943.11
  4788.6  941.22  4824.0  940.50  4831.0  938.89  4838.2  940.11  4859.3  938.01
  4880.6  938.66  4887.6  937.00  4894.7  938.56  4915.9  936.00  4923.0  937.43
  4944.2  935.50  4951.3  936.58  4958.3  933.58  4965.5  934.72  4972.5  932.69
  4993.8  934.17  5012.9  928.36  5013.2  927.86  5016.9  928.36  5036.1  932.02
  5043.3  936.12  5057.4  940.44  5128.1  943.49  5220.0  950.87  5369.5  956.98
#Mann=3,-1,0
  4584.0    0.05       0  5012.9   0.033       0  5016.9    0.05       0
Bank Sta=5012.9,5016.9
Exp/Cntr=0.3,0.1

Type RM Length L Ch R = 1,3590,410,410,410
BEGIN DESCRIPTION:
MDW T 094 9.0
END DESCRIPTION:
XS GIS Cut Line= 4
      2270187.11      7155996.87      2269962.56      7155780.00
      2269865.94      7155630.55      2269513.13      7155437.11
#Sta/Elev= 30
  4649.4  955.57  4808.5  949.40  4851.0  947.43  4865.1  945.92  4907.6  945.37
  4921.7  944.58  4942.8  938.37  4957.0  921.62  4958.6  921.49  4958.8  920.99
  4962.3  920.99  4962.6  921.49  4972.4  922.50  4978.4  924.57  4993.6  927.15
  4999.5  930.15  5008.7  930.07  5035.8  931.69  5102.4  933.66  5108.4  934.32
  5139.5  934.77  5190.0  937.55  5299.1  941.57  5337.0  943.74  5342.7  943.35
  5358.8  944.49  5380.6  944.85  5446.0  948.18  5462.1  949.53  5541.9  953.21
#Mann=3,-1,0
  4649.4    0.05       0  4958.6   0.033       0  4962.6    0.05       0
Bank Sta=4958.6,4962.6
Exp/Cntr=0.3,0.1

Type RM Length L Ch R = 1,3180,281,281,281
BEGIN DESCRIPTION:
MDW T 094 8.0
END DESCRIPTION:
XS GIS Cut Line= 3
      2270399.83      7155625.38      2270126.46      7155403.95
      2269784.33      7155357.98
#Sta/Elev= 30
  4648.2  957.77  4701.8  954.12  4759.3  951.99  4858.5  946.36  4866.4  945.14
  4872.8  942.80  4908.0  935.28  4951.2  931.79  4958.1  930.63  4965.6  927.17
  4972.0  929.15  4979.9  921.86  4986.4  922.57  4992.3  916.89  4992.6  916.39
  4996.1  916.39  4996.3  916.89  5007.5  917.97  5027.7  921.73  5037.8  925.17
  5047.9  927.02  5058.0  927.88  5078.2  928.51  5108.4  930.64  5209.3  934.50
  5215.9  935.33  5269.9  938.11  5310.2  942.86  5340.3  945.50  5345.2  945.50
#Mann=3,-1,0
  4648.2    0.05       0  4992.3   0.033       0  4996.3    0.05       0
Bank Sta=4992.3,4996.3
Exp/Cntr=0.3,0.1

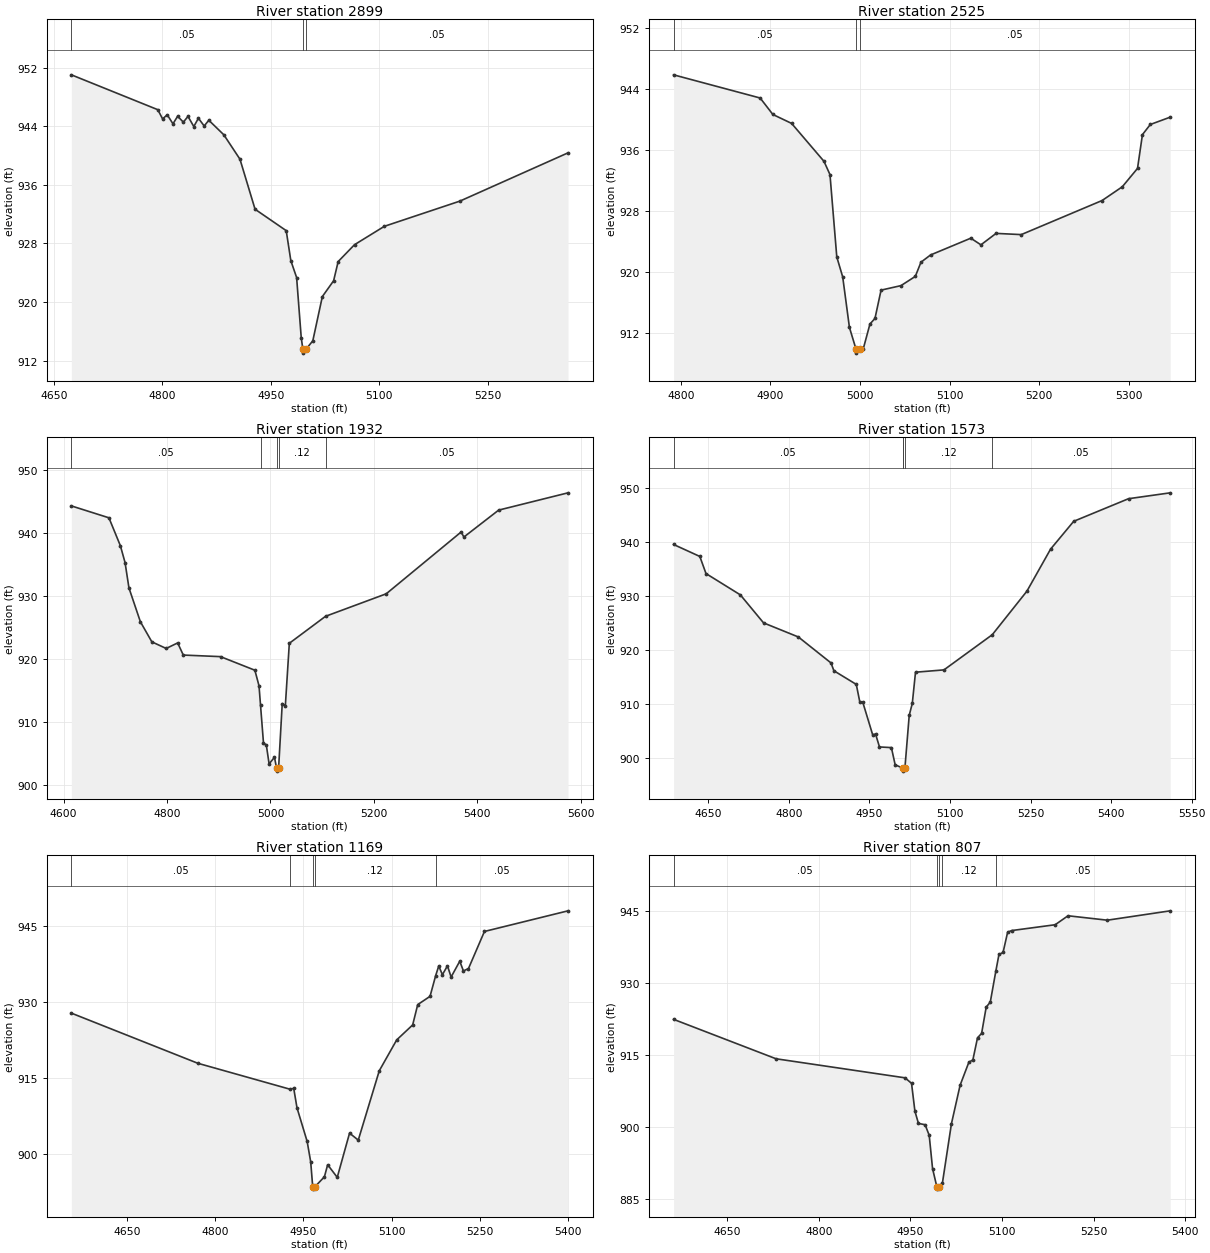
Type RM Length L Ch R = 1,2899,374,374,374
BEGIN DESCRIPTION:
MDW T 094 7.0
END DESCRIPTION:
XS GIS Cut Line= 3
      2270513.49      7155463.00      2270308.64      7155209.53
      2269977.50      7155064.78
#Sta/Elev= 30
  4674.1  951.01  4793.7  946.25  4800.3  945.00  4806.8  945.55  4814.7  944.32
  4821.1  945.35  4829.1  944.55  4835.5  945.34  4843.5  943.95  4849.9  945.08
  4857.9  944.03  4864.3  944.81  4885.1  942.82  4907.4  939.49  4928.3  932.66
  4971.4  929.74  4977.8  925.64  4985.8  923.34  4992.2  915.11  4994.5  913.52
  4994.7  913.02  4998.5  913.52  5008.2  914.70  5021.4  920.74  5037.0  922.90
  5043.3  925.52  5065.9  927.82  5107.2  930.33  5211.7  933.77  5361.4  940.36
#Mann=3,-1,0
  4674.1    0.05       0  4994.5   0.033       0  4998.5    0.05       0
Bank Sta=4994.5,4998.5
Exp/Cntr=0.3,0.1

Type RM Length L Ch R = 1,2525,593,593,593
BEGIN DESCRIPTION:
MDW T 094 6.0
END DESCRIPTION:
XS GIS Cut Line= 3
      2270647.19      7155048.10      2270490.02      7154911.70
      2270179.04      7154760.02
#Sta/Elev= 30
  4791.9  945.83  4888.5  942.79  4902.7  940.63  4923.6  939.46  4959.7  934.49
  4966.4  932.75  4974.0  921.95  4980.6  919.33  4988.1  912.71  4995.5  909.84
  4995.7  909.34  4999.5  909.84  5003.4  909.84  5011.0  913.16  5016.6  913.89
  5023.4  917.60  5045.6  918.19  5061.6  919.40  5067.9  921.26  5078.6  922.21
  5123.5  924.41  5134.8  923.54  5151.7  925.04  5179.8  924.88  5270.0  929.35
  5292.5  931.15  5309.5  933.56  5315.0  937.99  5323.8  939.32  5346.0  940.28
#Mann=3,-1,0
  4791.9    0.05       0  4995.5   0.033       0  4999.5    0.05       0
Bank Sta=4995.5,4999.5
Exp/Cntr=0.3,0.1

Type RM Length L Ch R = 1,1932,359,359,359
BEGIN DESCRIPTION:
MDW T 094 5.0
END DESCRIPTION:
XS GIS Cut Line= 4
      2270755.97      7154902.21      2270579.14      7154560.33
      2270446.06      7154361.80      2270122.90      7154268.36
#Sta/Elev= 30
  4615.1  944.34  4687.7  942.45  4709.9  938.00  4718.9  935.33  4726.4  931.31
  4748.5  925.93  4770.7  922.73  4798.4  921.68  4820.6  922.56  4831.5  920.63
  4903.5  920.38  4969.9  918.22  4977.9  915.74  4980.8  912.69  4986.5  906.70
  4992.1  906.30  4997.4  903.33  5007.8  904.38  5011.8  902.68  5012.1  902.18
  5015.8  902.68  5022.8  912.92  5028.8  912.56  5036.5  922.50  5106.5  926.79
  5223.9  930.37  5368.8  940.20  5374.0  939.39  5441.2  943.67  5575.4  946.42
#Mann=5,-1,0
  4615.1    0.05       0  4980.8    0.12       0  5011.8    0.07       0
  5015.8    0.12       0  5106.5    0.05       0
Bank Sta=5011.8,5015.8
Exp/Cntr=0.3,0.1

Type RM Length L Ch R = 1,1573,404,404,404
BEGIN DESCRIPTION:
MDW T 094 4.0
END DESCRIPTION:
XS GIS Cut Line= 3
      2271045.01      7154855.27      2270888.72      7154470.93
      2270634.87      7154028.48
#Sta/Elev= 30
  4585.1  939.55  4634.0  937.33  4645.5  934.16  4709.5  930.21  4752.7  925.02
  4817.5  922.41  4878.3  917.60  4883.7  916.15  4925.4  913.62  4931.9  910.40
  4937.3  910.38  4955.9  904.29  4961.3  904.42  4968.6  902.03  4990.8  901.91
  4997.8  898.73  5011.6  898.12  5011.9  898.05  5012.2  897.55  5015.9  898.05
  5024.0  907.89  5029.7  910.09  5035.7  915.88  5088.7  916.31  5178.7  922.83
  5243.2  930.90  5287.2  938.68  5330.3  943.84  5432.4  948.03  5510.1  949.12
#Mann=5,-1,0
  4585.1    0.05       0  5011.6    0.12       0  5011.9   0.033       0
  5015.9    0.12       0  5178.7    0.05       0
Bank Sta=5011.9,5015.9
Exp/Cntr=0.3,0.1

Type RM Length L Ch R = 1,1169,362,362,362
BEGIN DESCRIPTION:
MDW T 094 3.0
END DESCRIPTION:
XS GIS Cut Line= 3
      2271308.05      7154666.53      2271129.00      7154260.00
      2270898.90      7153933.56
#Sta/Elev= 30
  4555.8  927.82  4770.5  917.91  4926.7  912.79  4933.5  912.93  4939.0  909.11
  4956.3  902.44  4962.3  898.41  4965.7  893.52  4966.0  893.02  4969.7  893.52
  4985.6  895.46  4991.1  897.84  5007.4  895.35  5028.3  904.09  5043.1  902.71
  5078.8  916.43  5108.4  922.53  5135.5  925.49  5144.1  929.51  5165.0  931.14
  5174.6  935.25  5179.8  937.15  5186.0  935.42  5194.6  937.18  5200.8  934.96
  5215.5  938.09  5221.7  936.16  5230.3  936.64  5257.4  943.97  5399.4  948.05
#Mann=5,-1,0
  4555.8    0.05       0  4926.7    0.12       0  4965.7    0.07       0
  4969.7    0.12       0  5174.6    0.05       0
Bank Sta=4965.7,4969.7
Exp/Cntr=0.3,0.1

Type RM Length L Ch R = 1,807,684,684,684
BEGIN DESCRIPTION:
MDW T 094 2.0
END DESCRIPTION:
XS GIS Cut Line= 3
      2271551.53      7154567.55      2271376.82      7154166.12
      2271128.80      7153884.45
#Sta/Elev= 30
  4562.2  922.40  4730.0  914.18  4941.2  910.21  4951.8  909.06  4957.3  903.27
  4963.1  900.71  4974.0  900.44  4980.7  898.24  4986.2  891.30  4993.2  887.52
  4993.4  887.02  4997.2  887.52  5002.4  888.34  5017.1  900.64  5031.3  908.67
  5045.6  913.45  5052.2  913.95  5059.8  918.55  5066.5  919.47  5074.0  924.94
  5080.7  925.99  5089.9  932.52  5094.9  935.91  5101.6  936.33  5109.1  940.55
  5115.8  940.90  5186.9  942.11  5208.0  943.98  5272.3  943.06  5375.3  945.01
#Mann=5,-1,0
  4562.2    0.05       0  4993.2   0.033       0  4997.2    0.05       0
  5002.4    0.12       0  5089.9    0.05       0
Bank Sta=4993.2,4997.2
Exp/Cntr=0.3,0.1

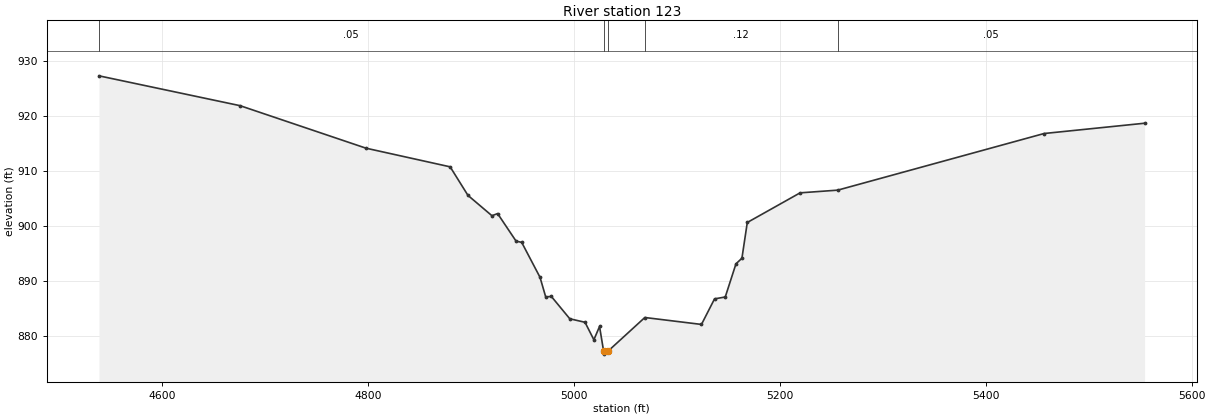
Type RM Length L Ch R = 1,123,0,0,0
BEGIN DESCRIPTION:
MDW T 094 1.0
END DESCRIPTION:
XS GIS Cut Line= 3
      2271789.79      7154532.41      2271988.88      7154078.14
      2271848.53      7153577.83
#Sta/Elev= 30
  4538.7  927.29  4675.8  921.86  4798.1  914.13  4879.8  910.74  4897.1  905.55
  4920.4  901.85  4925.9  902.24  4943.8  897.24  4949.3  897.00  4967.1  890.65
  4972.6  887.09  4978.1  887.17  4996.0  883.11  5010.8  882.47  5019.4  879.29
  5024.9  881.71  5028.9  877.18  5029.2  876.68  5032.9  877.18  5068.9  883.34
  5123.9  882.08  5136.6  886.73  5147.0  887.07  5157.4  893.10  5163.2  894.12
  5168.4  900.62  5219.7  906.01  5256.2  906.50  5456.7  916.80  5554.3  918.67
#Mann=5,-1,0
  4538.7    0.05       0  5028.9   0.033       0  5032.9    0.05       0
  5068.9    0.12       0  5256.2    0.05       0
Bank Sta=5028.9,5032.9
Exp/Cntr=0.3,0.1

Chan Stop Cuts=-1