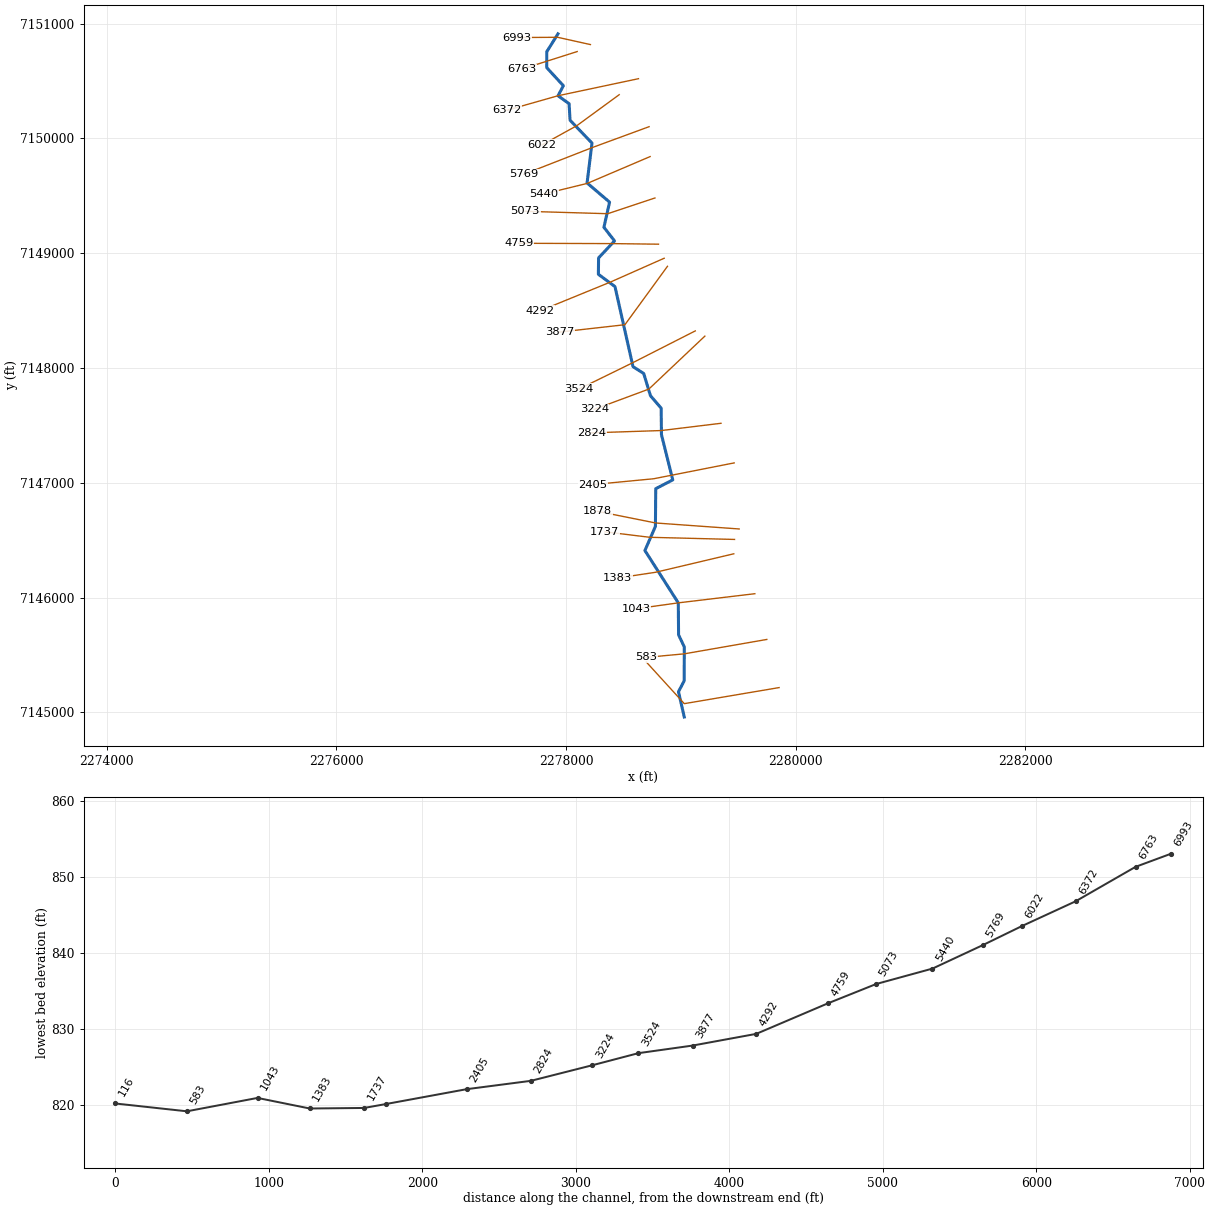
--- MDW T 095.prj (project) ---

Proj Title=MDW T 095 Base Level Engineering
Current Plan=p01
Default Exp/Contr=0.3,0.1
English Units
Geom File=g01
Flow File=f01
Plan File=p01
BEGIN DESCRIPTION:
MDW T 095
END DESCRIPTION:

--- MDW T 095.p01 (plan) ---

Plan Title=Multiple Run
Short Identifier=Multiple
Geom File=g01
Flow File=f01
Subcritical Flow
K Sum by GR= 0
Std Step Tol= 0.01
Critical Tol= 0.01
Num of Std Step Trials= 20
Max Error Tol= 0.3
Flow Tol Ratio= 0.001
Split Flow NTrial= 30
Split Flow Tol= 0.02
Split Flow Ratio= 0.02
Log Output Level= 0
Friction Slope Method= 1
Unsteady Friction Slope Method= 2
Unsteady Bridges Friction Slope Method= 1
Parabolic Critical Depth
Global Vel Dist=  1 , 1 , 1
Global Log Level= 0
CheckData=True
Encroach Param= -1, 0, 0, 0
BEGIN DESCRIPTION:
Multiple Run
END DESCRIPTION:

--- MDW T 095.f01 (steady flow) ---

Flow Title=Multiple
Number of Profiles=7
Profile Names=10-year,25-year,50-year,1pct_min,100-year,1pct_plu,500-year
River Rch & RM= MDW T 095,Reach-1,6993
     721    1002    1238     760    1516    3025    2277
River Rch & RM= MDW T 095,Reach-1,583
     728    1012    1250     767    1530    3054    2298
Boundary for River Rch & Prof#=MDW T 095,Reach-1,1
Up Type=0
Dn Type=3
Dn Slope=0.005
Boundary for River Rch & Prof#=MDW T 095,Reach-1,2
Up Type=0
Dn Type=3
Dn Slope=0.005
Boundary for River Rch & Prof#=MDW T 095,Reach-1,3
Up Type=0
Dn Type=3
Dn Slope=0.005
Boundary for River Rch & Prof#=MDW T 095,Reach-1,4
Up Type=0
Dn Type=3
Dn Slope=0.005
Boundary for River Rch & Prof#=MDW T 095,Reach-1,5
Up Type=0
Dn Type=3
Dn Slope=0.005
Boundary for River Rch & Prof#=MDW T 095,Reach-1,6
Up Type=0
Dn Type=3
Dn Slope=0.005
Boundary for River Rch & Prof#=MDW T 095,Reach-1,7
Up Type=0
Dn Type=3
Dn Slope=0.005

--- MDW T 095.g01 (geometry) ---

Geom Title=Existing Conditions

River Reach=MDW T 095,Reach-1
Reach XY= 30
      2277929.00      7150910.00      2277831.22      7150754.07
      2277831.05      7150615.86      2277975.97      7150458.02
      2277929.48      7150370.84      2278025.89      7150301.69
      2278034.40      7150157.32      2278225.46      7149958.53
      2278182.53      7149611.47      2278378.48      7149444.11
      2278329.25      7149225.22      2278421.47      7149106.43
      2278282.73      7148958.47      2278280.97      7148815.68
      2278425.48      7148708.72      2278582.55      7148011.30
      2278675.81      7147951.65      2278734.85      7147757.71
      2278827.95      7147649.56      2278830.22      7147420.50
      2278928.81      7147025.08      2278780.50      7146948.47
      2278777.78      7146620.50      2278686.33      7146409.90
      2278976.94      7145954.14      2278979.52      7145675.22
      2279029.45      7145570.19      2279028.46      7145275.21
      2278978.72      7145180.18      2279029.00      7144960.00

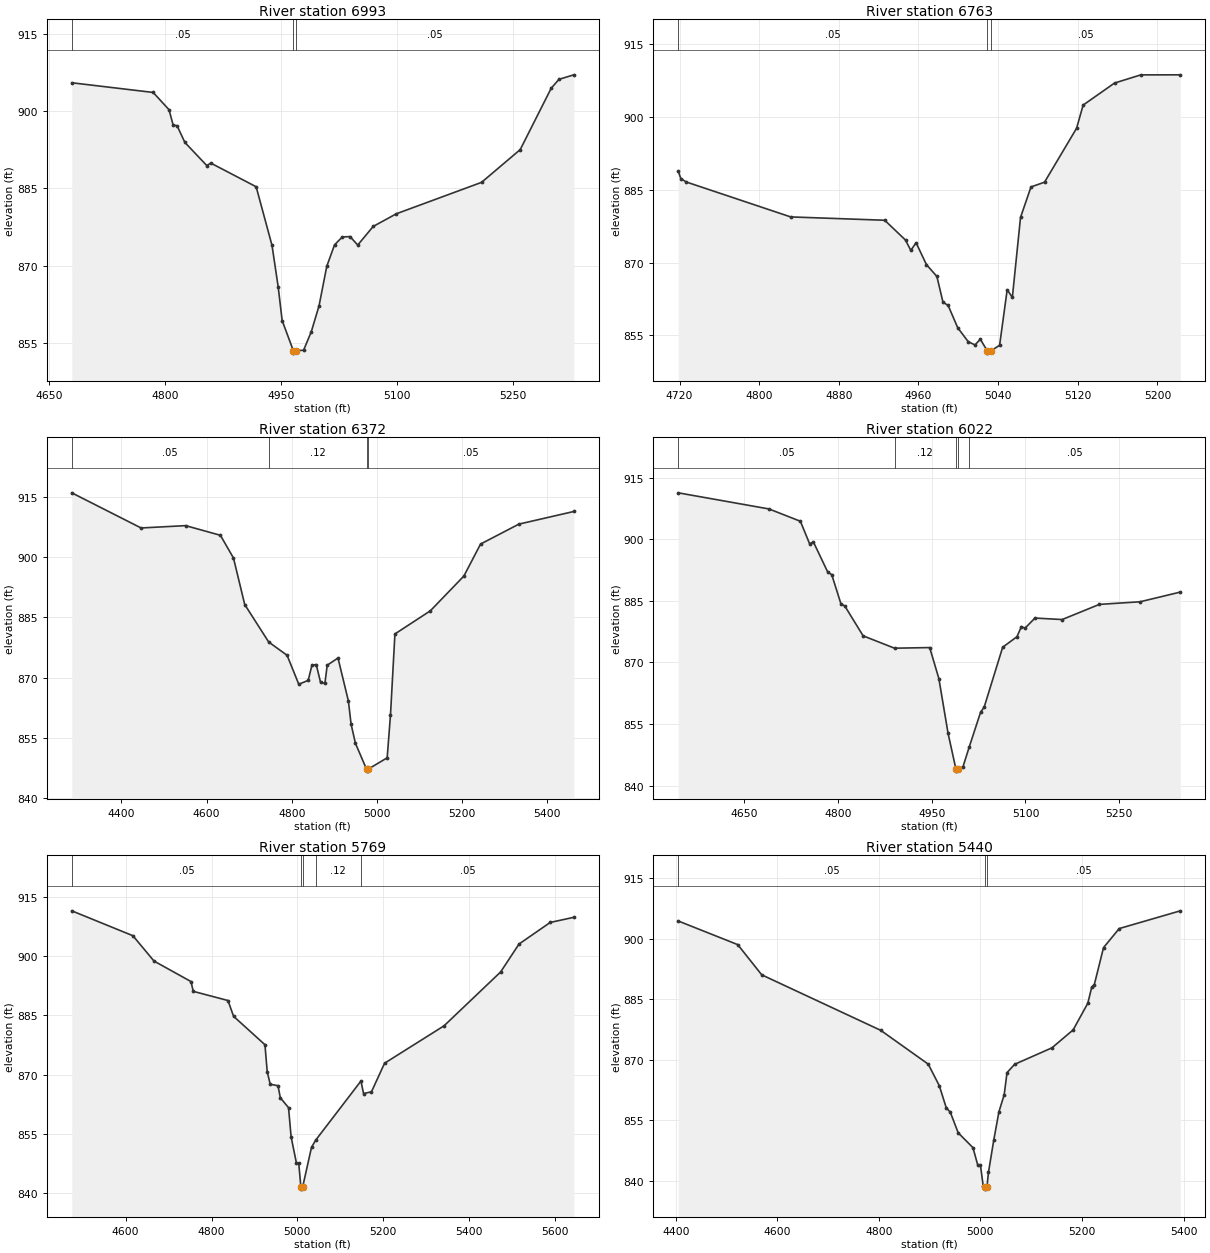
Type RM Length L Ch R = 1,6993,230,230,230
BEGIN DESCRIPTION:
MDW T 095 18.0
END DESCRIPTION:
XS GIS Cut Line= 3
      2278211.68      7150816.57      2277926.47      7150879.88
      2277569.73      7150877.92
#Sta/Elev= 30
  4679.4  905.50  4784.6  903.62  4805.1  900.27  4810.4  897.31  4815.5  897.16
  4825.6  893.92  4853.9  889.43  4859.1  889.91  4917.7  885.32  4938.2  873.94
  4946.2  865.87  4951.3  859.36  4965.7  853.53  4965.9  853.03  4969.7  853.53
  4979.0  853.59  4989.0  857.20  4999.0  862.22  5009.0  869.89  5019.0  874.04
  5029.0  875.57  5039.0  875.65  5049.0  874.01  5069.0  877.62  5099.0  880.08
  5209.0  886.17  5259.0  892.53  5299.0  904.43  5309.0  906.16  5328.3  907.04
#Mann=3,-1,0
  4679.4    0.05       0  4965.7   0.033       0  4969.7    0.05       0
Bank Sta=4965.7,4969.7
Exp/Cntr=0.3,0.1

Type RM Length L Ch R = 1,6763,391,391,391
BEGIN DESCRIPTION:
Mapping XS 4f317a14
END DESCRIPTION:
XS GIS Cut Line= 2
      2278096.63      7150755.73      2277616.00      7150603.06
#Sta/Elev= 30
  4718.7  888.84  4721.3  887.32  4726.7  886.62  4831.6  879.41  4926.1  878.72
  4947.0  874.63  4952.3  872.50  4957.6  874.08  4968.0  869.57  4978.5  867.13
  4984.6  861.83  4989.8  861.14  4999.5  856.52  5010.0  853.67  5016.8  853.00
  5022.1  854.19  5029.0  851.81  5029.2  851.31  5033.0  851.81  5041.5  852.93
  5049.1  864.39  5054.3  862.80  5062.5  879.30  5073.0  885.59  5086.6  886.57
  5118.8  897.69  5125.4  902.48  5156.9  907.02  5183.3  908.71  5223.0  908.72
#Mann=3,-1,0
  4718.7    0.05       0  5029.0   0.033       0  5033.0    0.05       0
Bank Sta=5029,5033
Exp/Cntr=0.3,0.1

Type RM Length L Ch R = 1,6372,350,350,350
BEGIN DESCRIPTION:
MDW T 095 17.0
END DESCRIPTION:
XS GIS Cut Line= 3
      2278630.21      7150519.37      2277929.48      7150370.84
      2277485.00      7150244.81
#Sta/Elev= 30
  4283.7  915.99  4446.4  907.25  4550.9  907.83  4632.5  905.43  4663.2  899.78
  4689.6  888.21  4745.8  878.89  4789.0  875.58  4816.5  868.37  4838.6  869.35
  4847.2  873.06  4857.4  873.28  4867.6  868.84  4877.8  868.60  4883.2  873.12
  4908.5  874.90  4932.9  864.22  4939.2  858.47  4949.4  853.69  4975.4  847.27
  4975.7  846.77  4979.4  847.27  5023.9  850.08  5031.7  860.75  5042.1  880.89
  5125.2  886.64  5203.9  895.29  5243.1  903.25  5333.1  908.21  5462.0  911.35
#Mann=4,-1,0
  4283.7    0.05       0  4745.8    0.12       0  4975.4   0.033       0
  4979.4    0.05       0
Bank Sta=4975.4,4979.4
Exp/Cntr=0.3,0.1

Type RM Length L Ch R = 1,6022,253,253,253
BEGIN DESCRIPTION:
MDW T 095 16.0
END DESCRIPTION:
XS GIS Cut Line= 3
      2278462.35      7150380.03      2278094.57      7150110.96
      2277790.33      7149942.43
#Sta/Elev= 30
  4544.3  911.31  4689.6  907.38  4739.8  904.38  4754.5  898.91  4760.7  899.31
  4783.8  891.93  4789.9  891.40  4804.7  884.26  4810.9  883.73  4840.2  876.47
  4890.4  873.46  4946.7  873.61  4961.4  866.06  4976.1  852.74  4988.7  844.01
  4989.0  843.51  4992.7  844.01  5000.0  844.58  5010.2  849.49  5028.2  857.87
  5033.9  859.10  5063.5  873.69  5086.4  876.26  5093.5  878.73  5099.2  878.33
  5115.2  880.80  5158.7  880.44  5218.3  884.13  5283.5  884.77  5347.8  887.13
#Mann=5,-1,0
  4544.3    0.05       0  4890.4    0.12       0  4988.7    0.07       0
  4992.7    0.12       0  5010.2    0.05       0
Bank Sta=4988.7,4992.7
Exp/Cntr=0.3,0.1

Type RM Length L Ch R = 1,5769,329,329,329
BEGIN DESCRIPTION:
MDW T 095 15.0
END DESCRIPTION:
XS GIS Cut Line= 3
      2278722.61      7150101.39      2278229.55      7149920.19
      2277630.16      7149686.02
#Sta/Elev= 30
  4474.7  911.46  4617.0  905.16  4666.1  898.75  4752.2  893.56  4757.5  891.08
  4838.3  888.76  4851.4  884.76  4924.4  877.57  4929.7  870.72  4936.7  867.56
  4954.8  867.20  4960.2  864.14  4979.3  861.64  4985.3  854.26  4997.6  847.66
  5003.0  847.66  5008.1  841.52  5008.4  841.02  5012.1  841.52  5032.8  851.60
  5042.6  853.43  5147.9  868.38  5154.0  865.20  5172.4  865.66  5202.9  872.89
  5341.4  882.36  5473.0  895.98  5515.9  903.06  5588.5  908.52  5643.5  909.82
#Mann=5,-1,0
  4474.7    0.05       0  5008.1   0.033       0  5012.1    0.05       0
  5042.6    0.12       0  5147.9    0.05       0
Bank Sta=5008.1,5012.1
Exp/Cntr=0.3,0.1

Type RM Length L Ch R = 1,5440,367,367,367
BEGIN DESCRIPTION:
MDW T 095 14.0
END DESCRIPTION:
XS GIS Cut Line= 3
      2278731.75      7149840.98      2278184.45      7149607.55
      2277802.09      7149514.17
#Sta/Elev= 30
  4405.0  904.45  4522.2  898.58  4569.4  891.09  4803.7  877.32  4897.2  868.94
  4919.0  863.59  4932.6  858.15  4940.7  857.00  4956.3  851.88  4985.3  848.21
  4994.8  843.88  5000.0  843.88  5005.6  838.63  5008.8  838.42  5009.0  837.92
  5012.8  838.42  5015.9  842.10  5026.2  850.03  5036.5  857.13  5046.8  861.34
  5052.4  866.82  5067.4  868.89  5140.9  872.98  5182.6  877.43  5211.5  884.06
  5219.1  888.00  5224.2  888.63  5242.4  897.84  5273.3  902.57  5393.6  906.97
#Mann=3,-1,0
  4405.0    0.05       0  5008.8   0.033       0  5012.8    0.05       0
Bank Sta=5008.8,5012.8
Exp/Cntr=0.3,0.1

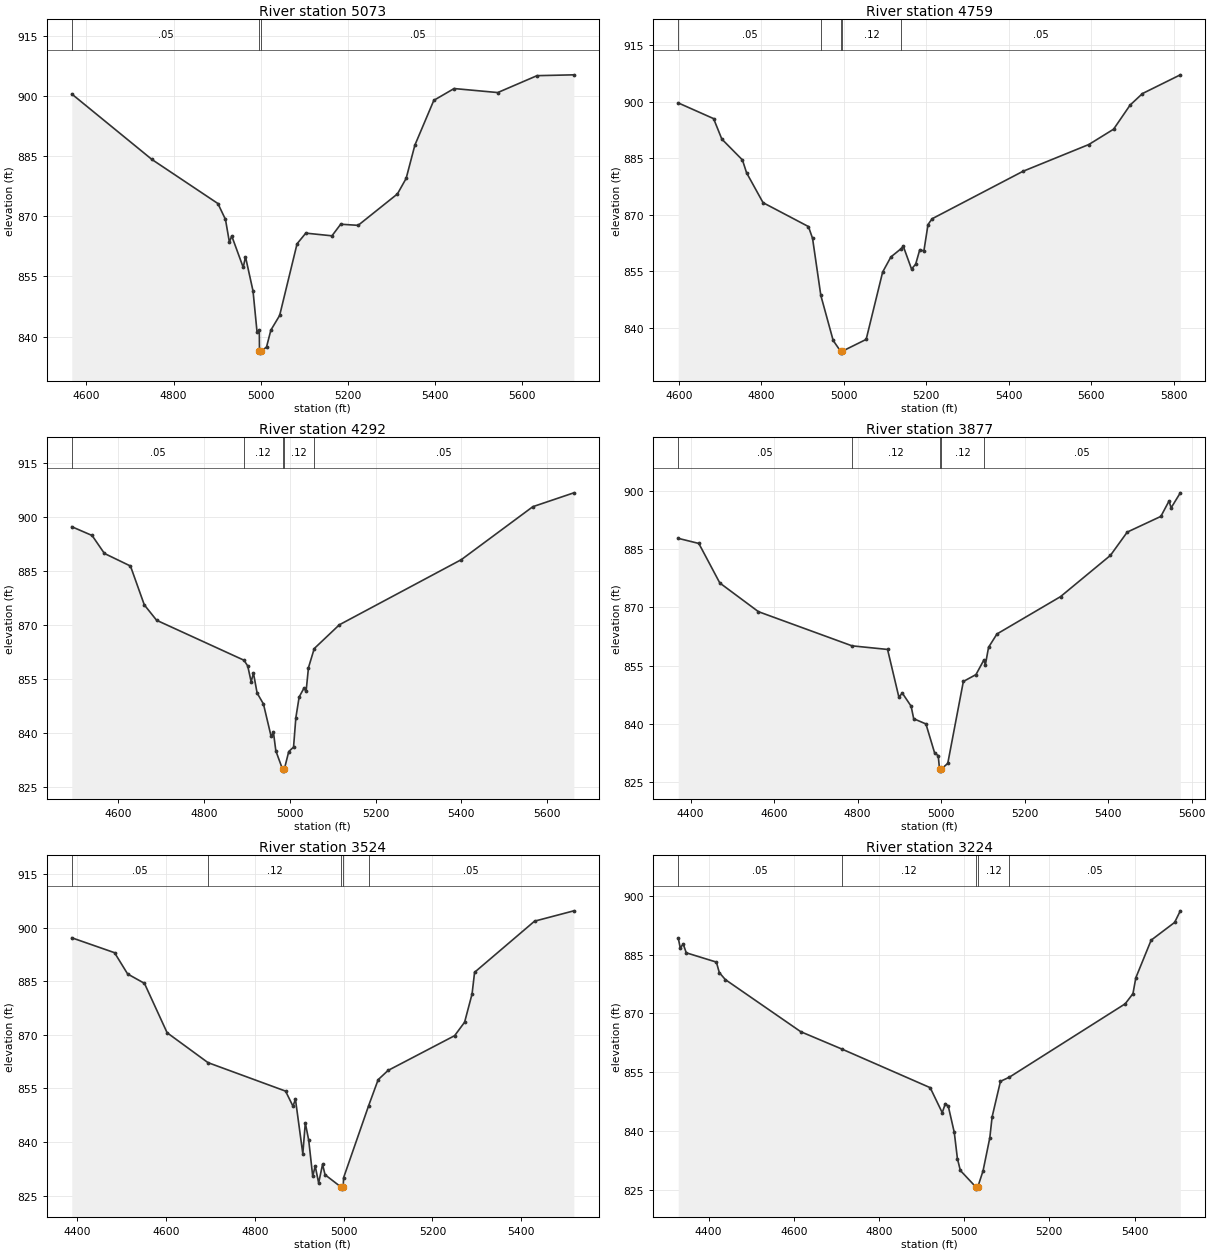
Type RM Length L Ch R = 1,5073,314,314,314
BEGIN DESCRIPTION:
MDW T 095 13.0
END DESCRIPTION:
XS GIS Cut Line= 3
      2278773.47      7149480.32      2278362.14      7149343.46
      2277644.54      7149364.42
#Sta/Elev= 30
  4566.5  900.50  4750.4  884.17  4901.6  873.19  4919.0  869.22  4928.0  863.54
  4933.3  865.12  4959.7  857.26  4964.9  859.91  4982.2  851.37  4991.3  841.24
  4996.6  841.57  4997.0  836.39  4997.3  835.89  5001.0  836.39  5013.1  837.40
  5023.1  841.63  5043.2  845.28  5083.2  863.16  5103.2  865.81  5163.2  865.14
  5183.2  868.03  5223.2  867.75  5313.3  875.58  5333.3  879.45  5353.3  887.74
  5396.8  898.92  5443.3  901.86  5543.4  900.86  5633.4  905.07  5717.9  905.28
#Mann=3,-1,0
  4566.5    0.05       0  4997.0   0.033       0  5001.0    0.05       0
Bank Sta=4997,5001
Exp/Cntr=0.3,0.1

Type RM Length L Ch R = 1,4759,467,467,467
BEGIN DESCRIPTION:
MDW T 095 12.0
END DESCRIPTION:
XS GIS Cut Line= 3
      2278804.69      7149077.96      2278403.33      7149083.07
      2277587.23      7149085.77
#Sta/Elev= 30
  4598.6  899.71  4684.3  895.55  4704.3  890.12  4754.3  884.58  4764.3  881.18
  4804.3  873.25  4914.3  866.92  4924.3  863.80  4944.4  848.64  4974.3  836.71
  4992.3  833.85  4992.6  833.35  4996.3  833.85  5054.3  836.99  5094.3  854.86
  5114.3  858.86  5139.0  861.05  5144.3  861.71  5164.3  855.66  5174.3  856.92
  5184.3  860.78  5194.3  860.44  5204.3  867.46  5214.3  868.99  5434.3  881.56
  5594.3  888.68  5654.3  892.74  5694.3  899.13  5724.3  902.19  5816.1  907.16
#Mann=5,-1,0
  4598.6    0.05       0  4944.4    0.12       0  4992.3    0.07       0
  4996.3    0.12       0  5139.0    0.05       0
Bank Sta=4992.3,4996.3
Exp/Cntr=0.3,0.1

Type RM Length L Ch R = 1,4292,415,415,415
BEGIN DESCRIPTION:
MDW T 095 11.0
END DESCRIPTION:
XS GIS Cut Line= 3
      2278854.17      7148955.58      2278389.03      7148749.37
      2277776.06      7148498.55
#Sta/Elev= 30
  4491.2  897.28  4538.6  894.84  4567.3  889.85  4628.1  886.35  4660.4  875.55
  4689.1  871.27  4892.9  860.16  4901.6  858.57  4909.6  854.19  4915.0  856.59
  4923.5  851.05  4938.3  847.99  4956.1  839.02  4961.6  840.14  4967.2  834.97
  4982.9  829.83  4983.1  829.33  4986.9  829.83  4997.3  834.77  5008.5  836.01
  5013.9  844.20  5021.6  849.96  5032.4  852.31  5037.9  851.67  5043.3  858.09
  5056.8  863.41  5115.3  870.01  5399.8  888.12  5566.7  902.85  5662.3  906.70
#Mann=5,-1,0
  4491.2    0.05       0  4892.9    0.12       0  4982.9    0.07       0
  4986.9    0.12       0  5056.8    0.05       0
Bank Sta=4982.9,4986.9
Exp/Cntr=0.3,0.1

Type RM Length L Ch R = 1,3877,353,353,353
BEGIN DESCRIPTION:
MDW T 095 10.0
END DESCRIPTION:
XS GIS Cut Line= 3
      2278882.79      7148885.24      2278512.11      7148376.57
      2277942.70      7148312.48
#Sta/Elev= 30
  4370.6  887.84  4419.9  886.52  4470.2  876.32  4562.7  868.92  4786.8  860.11
  4871.9  859.18  4898.9  846.93  4907.4  847.90  4928.3  844.54  4934.5  841.31
  4963.8  839.96  4984.7  832.45  4993.2  831.79  4996.4  828.29  4996.6  827.79
  5000.4  828.29  5016.1  829.80  5053.4  850.92  5083.6  852.69  5102.7  856.48
  5106.1  855.19  5113.8  859.74  5133.9  863.17  5286.1  872.80  5405.7  883.45
  5445.9  889.45  5526.4  893.50  5546.0  897.47  5551.0  895.71  5573.0  899.58
#Mann=5,-1,0
  4370.6    0.05       0  4786.8    0.12       0  4996.4    0.07       0
  5000.4    0.12       0  5102.7    0.05       0
Bank Sta=4996.4,5000.4
Exp/Cntr=0.3,0.1

Type RM Length L Ch R = 1,3524,300,300,300
BEGIN DESCRIPTION:
MDW T 095 9.0
END DESCRIPTION:
XS GIS Cut Line= 3
      2279124.95      7148322.74      2278578.77      7148044.86
      2278112.94      7147816.72
#Sta/Elev= 30
  4387.2  897.21  4483.6  893.03  4513.1  887.07  4551.0  884.44  4602.1  870.60
  4694.2  862.23  4869.0  854.25  4885.7  850.03  4891.3  851.98  4907.9  836.69
  4913.5  845.33  4921.2  840.49  4930.2  830.41  4935.8  833.23  4943.6  828.52
  4952.4  833.74  4958.0  830.82  4994.9  827.29  4995.2  826.79  4998.9  827.29
  4999.8  829.99  5056.2  850.16  5077.7  857.46  5100.0  860.04  5250.0  869.78
  5272.5  873.56  5289.3  881.46  5295.0  887.54  5430.1  901.86  5518.7  904.76
#Mann=5,-1,0
  4387.2    0.05       0  4694.2    0.12       0  4994.9    0.07       0
  4998.9    0.12       0  5056.2    0.05       0
Bank Sta=4994.9,4998.9
Exp/Cntr=0.3,0.1

Type RM Length L Ch R = 1,3224,400,400,400
BEGIN DESCRIPTION:
MDW T 095 8.0
END DESCRIPTION:
XS GIS Cut Line= 3
      2279208.35      7148277.21      2278720.52      7147815.92
      2278244.79      7147639.17
#Sta/Elev= 30
  4328.6  889.22  4333.2  886.76  4340.5  887.62  4347.4  885.44  4418.2  883.07
  4425.0  880.40  4439.2  878.61  4616.4  865.32  4713.8  860.86  4920.2  851.06
  4948.5  844.69  4955.8  847.00  4962.7  846.34  4976.8  839.64  4984.1  832.99
  4991.0  829.96  5027.8  825.70  5028.1  825.20  5031.8  825.70  5044.3  829.85
  5060.2  838.29  5065.6  843.61  5085.2  852.68  5106.2  853.74  5378.1  872.44
  5396.3  875.03  5403.1  879.09  5439.0  888.66  5494.2  893.19  5507.5  896.14
#Mann=5,-1,0
  4328.6    0.05       0  4713.8    0.12       0  5027.8    0.07       0
  5031.8    0.12       0  5106.2    0.05       0
Bank Sta=5027.8,5031.8
Exp/Cntr=0.3,0.1

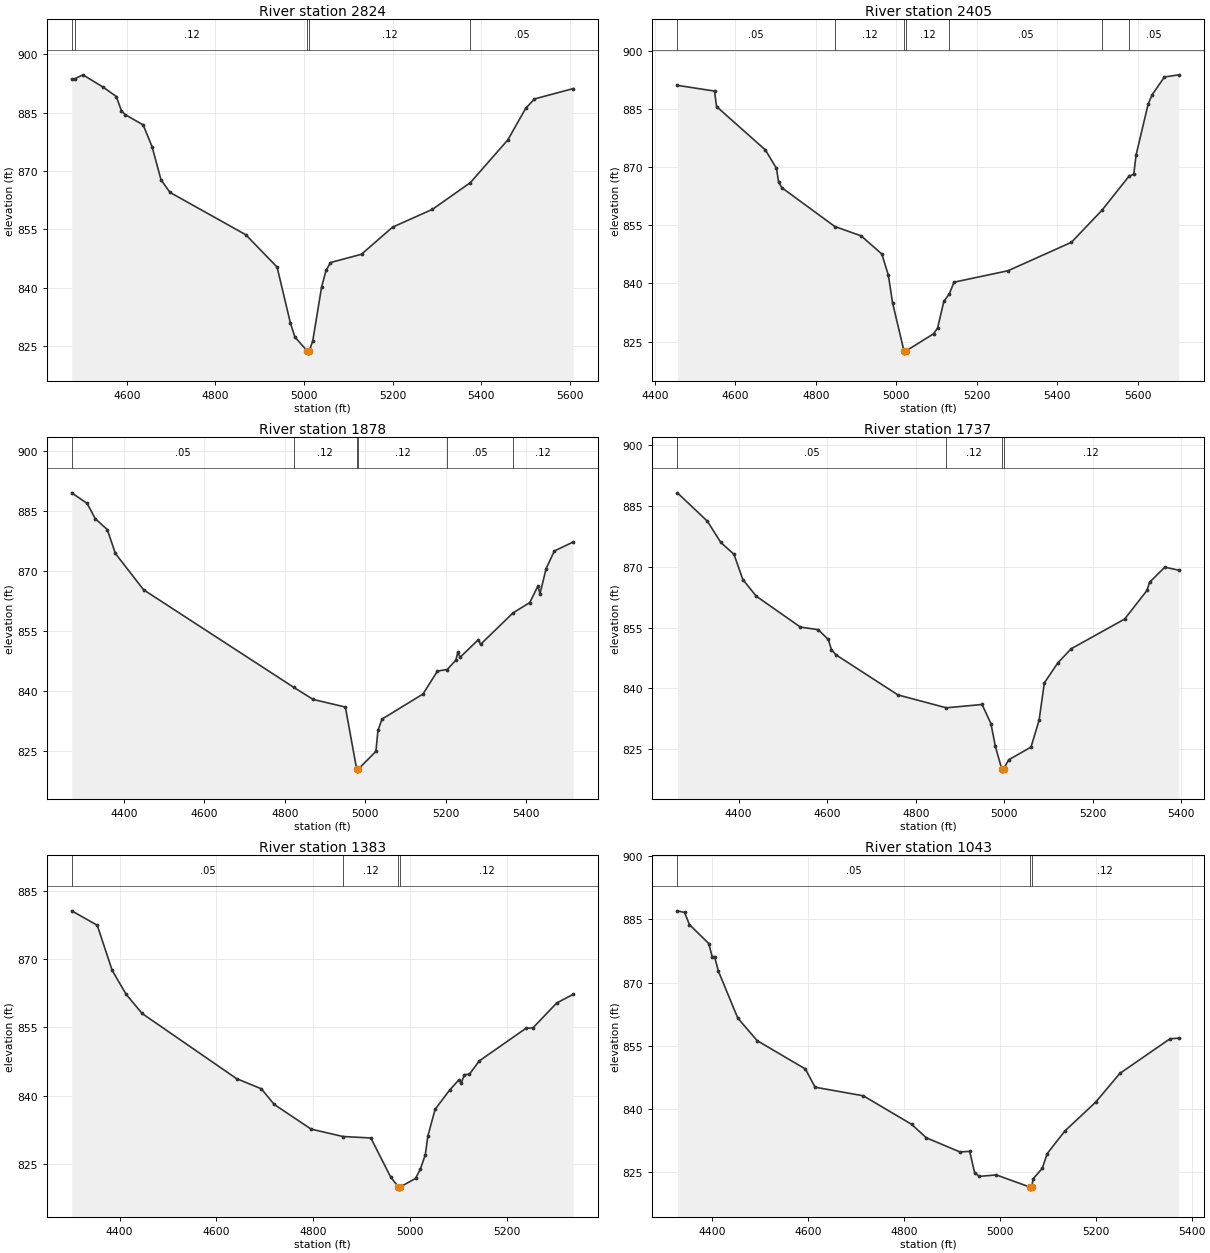
Type RM Length L Ch R = 1,2824,419,419,419
BEGIN DESCRIPTION:
MDW T 095 7.0
END DESCRIPTION:
XS GIS Cut Line= 3
      2279348.93      7147518.06      2278828.56      7147454.82
      2278221.99      7147434.80
#Sta/Elev= 30
  4475.8  893.54  4483.9  893.78  4501.1  894.74  4546.2  891.60  4576.5  889.16
  4587.8  885.52  4596.6  884.48  4636.9  881.87  4657.1  876.25  4677.2  867.75
  4697.4  864.50  4868.6  853.60  4939.1  845.29  4969.3  830.82  4979.4  827.27
  5007.6  823.65  5007.8  823.15  5011.6  823.65  5019.6  826.33  5039.6  840.20
  5049.6  844.41  5059.6  846.45  5129.6  848.59  5199.7  855.56  5289.7  860.14
  5375.2  867.01  5459.8  878.02  5499.8  886.08  5519.8  888.54  5606.9  891.19
#Mann=5,-1,0
  4475.8    0.05       0  4483.9    0.12       0  5007.6    0.07       0
  5011.6    0.12       0  5375.2    0.05       0
Bank Sta=5007.6,5011.6
Exp/Cntr=0.3,0.1

Type RM Length L Ch R = 1,2405,527,527,527
BEGIN DESCRIPTION:
MDW T 095 6.0
END DESCRIPTION:
XS GIS Cut Line= 3
      2279463.54      7147173.02      2278763.04      7147035.05
      2278233.53      7146984.26
#Sta/Elev= 30
  4456.0  891.08  4548.3  889.60  4553.3  885.62  4674.7  874.42  4702.3  869.67
  4707.4  866.22  4715.4  864.71  4847.2  854.69  4912.8  852.27  4964.2  847.59
  4980.4  842.08  4990.6  835.09  5019.2  822.55  5019.4  822.05  5023.2  822.55
  5092.5  827.03  5102.7  828.52  5118.3  835.45  5131.7  837.30  5143.5  840.34
  5277.4  843.28  5435.2  850.62  5510.9  858.86  5578.8  867.72  5590.2  868.14
  5595.9  873.12  5626.1  886.33  5636.1  888.69  5666.3  893.23  5701.9  893.79
#Mann=7,-1,0
  4456.0    0.05       0  4847.2    0.12       0  5019.2    0.07       0
  5023.2    0.12       0  5131.7    0.05       0  5510.9    0.12       0
  5578.8    0.05       0
Bank Sta=5019.2,5023.2
Exp/Cntr=0.3,0.1

Type RM Length L Ch R = 1,1878,141,141,141
BEGIN DESCRIPTION:
MDW T 095 5.0
END DESCRIPTION:
XS GIS Cut Line= 3
      2279507.18      7146597.62      2278779.45      7146649.81
      2278273.40      7146751.14
#Sta/Elev= 30
  4270.4  889.53  4308.7  886.88  4328.7  883.10  4358.8  880.35  4378.9  874.40
  4449.0  865.33  4822.2  840.99  4870.1  837.98  4950.3  836.08  4978.4  820.59
  4978.7  820.09  4982.4  820.59  5026.2  825.02  5031.3  830.23  5041.3  833.07
  5143.2  839.33  5179.1  845.06  5203.3  845.44  5224.8  847.78  5230.0  849.84
  5235.1  848.47  5281.0  852.91  5286.1  851.71  5367.0  859.58  5408.4  862.14
  5428.8  866.25  5433.9  864.35  5449.2  870.64  5469.6  875.02  5516.1  877.25
#Mann=6,-1,0
  4270.4    0.05       0  4822.2    0.12       0  4978.4    0.07       0
  4982.4    0.12       0  5203.3    0.05       0  5367.0    0.12       0
Bank Sta=4978.4,4982.4
Exp/Cntr=0.3,0.1

Type RM Length L Ch R = 1,1737,354,354,354
BEGIN DESCRIPTION:
MDW T 095 4.0
END DESCRIPTION:
XS GIS Cut Line= 3
      2279466.80      7146506.48      2278728.83      7146525.06
      2278337.85      7146572.89
#Sta/Elev= 30
  4261.8  888.31  4329.6  881.30  4359.6  876.08  4389.6  873.12  4409.6  866.90
  4439.7  862.80  4539.7  855.15  4579.7  854.52  4602.6  852.09  4609.7  849.57
  4619.7  848.32  4759.8  838.40  4869.1  835.22  4949.8  836.04  4969.8  831.33
  4979.8  825.72  4994.3  820.08  4994.6  819.58  4998.3  820.08  5009.9  822.38
  5060.3  825.51  5078.6  832.17  5090.5  841.38  5120.7  846.29  5151.0  849.80
  5271.8  857.14  5322.2  864.20  5328.1  866.23  5362.5  869.95  5393.9  869.21
#Mann=4,-1,0
  4261.8    0.05       0  4869.1    0.12       0  4994.3    0.07       0
  4998.3    0.12       0
Bank Sta=4994.3,4998.3
Exp/Cntr=0.3,0.1

Type RM Length L Ch R = 1,1383,340,340,340
BEGIN DESCRIPTION:
MDW T 095 3.0
END DESCRIPTION:
XS GIS Cut Line= 3
      2279460.28      7146381.48      2278780.17      7146220.49
      2278447.20      7146170.53
#Sta/Elev= 30
  4301.1  880.60  4353.8  877.43  4384.6  867.54  4413.2  862.32  4446.3  858.08
  4641.5  843.77  4692.9  841.53  4719.3  838.10  4795.7  832.68  4861.4  831.06
  4919.0  830.74  4960.1  822.12  4976.0  820.01  4976.2  819.51  4980.0  820.01
  5011.3  821.86  5021.4  823.94  5031.5  827.09  5036.8  831.20  5051.7  837.03
  5082.1  841.31  5100.8  843.50  5105.9  842.85  5112.4  844.65  5122.5  844.72
  5142.8  847.64  5239.0  854.79  5254.0  854.93  5303.0  860.38  5336.7  862.25
#Mann=4,-1,0
  4301.1    0.05       0  4861.4    0.12       0  4976.0    0.07       0
  4980.0    0.12       0
Bank Sta=4976,4980
Exp/Cntr=0.3,0.1

Type RM Length L Ch R = 1,1043,460,460,460
BEGIN DESCRIPTION:
MDW T 095 2.0
END DESCRIPTION:
XS GIS Cut Line= 3
      2279643.89      7146033.82      2278976.94      7145954.14
      2278607.45      7145902.32
#Sta/Elev= 30
  4328.3  887.05  4343.3  886.66  4353.4  883.78  4393.7  879.28  4400.7  876.19
  4405.7  876.18  4413.8  872.70  4454.1  861.57  4494.4  856.21  4595.1  849.45
  4615.2  845.13  4715.9  843.08  4816.6  836.29  4846.9  833.11  4917.4  829.73
  4937.5  829.88  4947.6  824.84  4957.6  823.93  4992.8  824.28  5062.7  821.40
  5062.9  820.90  5066.7  821.40  5069.7  823.36  5088.8  825.85  5098.9  829.33
  5136.0  834.74  5199.9  841.56  5250.4  848.41  5355.1  856.65  5373.1  856.78
#Mann=3,-1,0
  4328.3    0.05       0  5062.7   0.033       0  5066.7    0.12       0
Bank Sta=5062.7,5066.7
Exp/Cntr=0.3,0.1

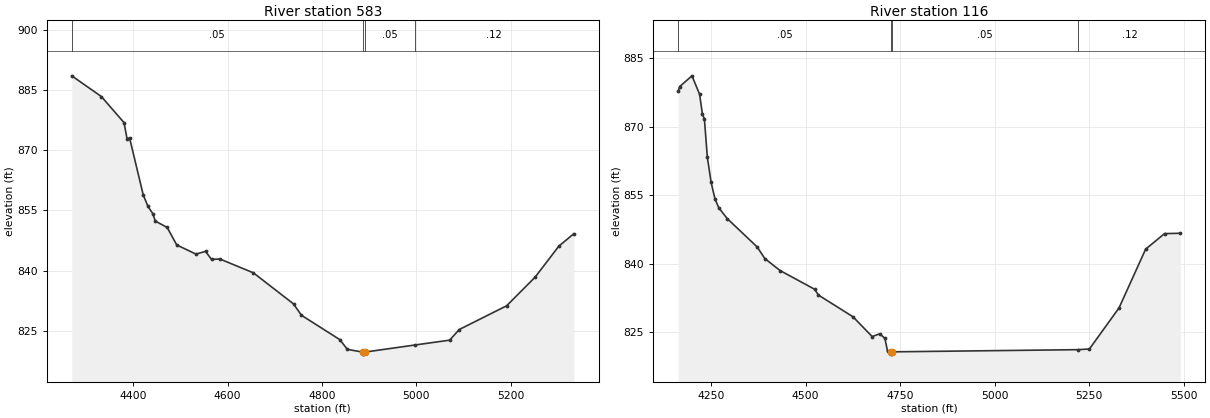
Type RM Length L Ch R = 1,583,467,467,467
BEGIN DESCRIPTION:
MDW T 095 1.0
END DESCRIPTION:
XS GIS Cut Line= 3
      2279748.03      7145635.38      2279029.08      7145510.03
      2278697.21      7145479.13
#Sta/Elev= 30
  4270.2  888.60  4332.9  883.43  4380.9  876.91  4387.4  872.80  4392.5  873.15
  4421.5  858.89  4431.6  856.00  4441.8  854.20  4447.0  852.36  4472.2  850.75
  4492.5  846.38  4533.1  844.11  4553.4  844.78  4566.1  842.79  4583.9  842.88
  4654.9  839.42  4739.7  831.68  4756.5  828.84  4837.7  822.76  4853.8  820.33
  4886.4  819.64  4886.7  819.14  4890.4  819.64  4996.4  821.41  5070.4  822.63
  5090.5  825.27  5190.9  831.20  5251.2  838.34  5301.4  846.07  5333.3  849.20
#Mann=4,-1,0
  4270.2    0.05       0  4886.4    0.07       0  4890.4    0.05       0
  4996.4    0.12       0
Bank Sta=4886.4,4890.4
Exp/Cntr=0.3,0.1

Type RM Length L Ch R = 1,116,0,0,0
BEGIN DESCRIPTION:
MDW T 095 0.5
END DESCRIPTION:
XS GIS Cut Line= 3
      2279854.80      7145216.11      2279029.30      7145076.16
      2278698.53      7145438.79
#Sta/Elev= 30
  4162.9  877.76  4166.6  878.77  4199.2  881.14  4219.5  877.07  4227.0  872.69
  4232.1  871.71  4239.8  863.39  4249.9  857.79  4260.1  854.17  4270.2  852.23
  4292.4  849.87  4371.6  843.66  4391.9  841.11  4432.5  838.47  4523.6  834.39
  4533.9  833.10  4625.2  828.35  4675.9  824.02  4696.2  824.63  4709.7  823.60
  4716.5  820.84  4724.6  820.67  4724.9  820.17  4728.7  820.67  5221.6  821.15
  5250.6  821.30  5329.0  830.31  5399.3  843.17  5449.2  846.57  5491.0  846.65
#Mann=4,-1,0
  4162.9    0.05       0  4724.6   0.033       0  4728.7    0.05       0
  5221.6    0.12       0
Bank Sta=4724.6,4728.7
Exp/Cntr=0.3,0.1

Chan Stop Cuts=-1