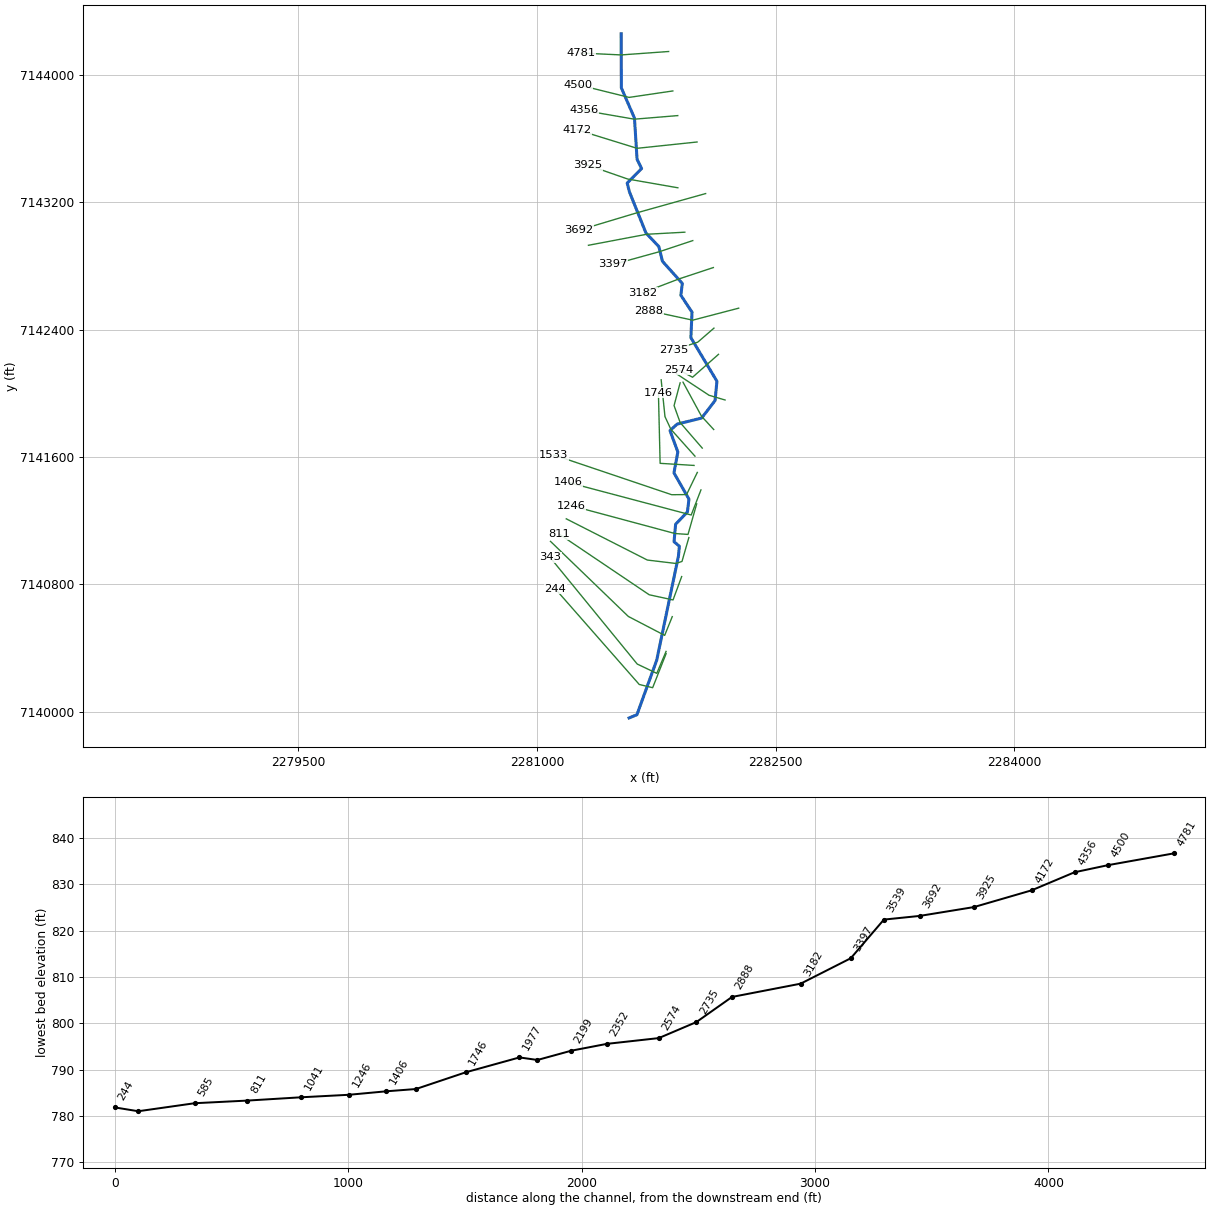
--- MDW T 096.prj (project) ---

Proj Title=MDW T 096 Base Level Engineering
Current Plan=p01
Default Exp/Contr=0.3,0.1
English Units
Geom File=g01
Flow File=f01
Plan File=p01
BEGIN DESCRIPTION:
MDW T 096
END DESCRIPTION:

--- MDW T 096.p01 (plan) ---

Plan Title=Multiple Run
Short Identifier=Multiple
Geom File=g01
Flow File=f01
Subcritical Flow
K Sum by GR= 0
Std Step Tol= 0.01
Critical Tol= 0.01
Num of Std Step Trials= 20
Max Error Tol= 0.3
Flow Tol Ratio= 0.001
Split Flow NTrial= 30
Split Flow Tol= 0.02
Split Flow Ratio= 0.02
Log Output Level= 0
Friction Slope Method= 1
Unsteady Friction Slope Method= 2
Unsteady Bridges Friction Slope Method= 1
Parabolic Critical Depth
Global Vel Dist=  1 , 1 , 1
Global Log Level= 0
CheckData=True
Encroach Param= -1, 0, 0, 0
BEGIN DESCRIPTION:
Multiple Run
END DESCRIPTION:

--- MDW T 096.f01 (steady flow) ---

Flow Title=Multiple
Number of Profiles=7
Profile Names=10-year,25-year,50-year,1pct_min,100-year,1pct_plu,500-year
River Rch & RM= MDW T 096,Reach-1,4781
     316     416     496     295     588    1173     826
Boundary for River Rch & Prof#=MDW T 096,Reach-1,1
Up Type=0
Dn Type=3
Dn Slope=0.005
Boundary for River Rch & Prof#=MDW T 096,Reach-1,2
Up Type=0
Dn Type=3
Dn Slope=0.005
Boundary for River Rch & Prof#=MDW T 096,Reach-1,3
Up Type=0
Dn Type=3
Dn Slope=0.005
Boundary for River Rch & Prof#=MDW T 096,Reach-1,4
Up Type=0
Dn Type=3
Dn Slope=0.005
Boundary for River Rch & Prof#=MDW T 096,Reach-1,5
Up Type=0
Dn Type=3
Dn Slope=0.005
Boundary for River Rch & Prof#=MDW T 096,Reach-1,6
Up Type=0
Dn Type=3
Dn Slope=0.005
Boundary for River Rch & Prof#=MDW T 096,Reach-1,7
Up Type=0
Dn Type=3
Dn Slope=0.005

--- MDW T 096.g01 (geometry) ---

Geom Title=Existing Conditions

River Reach=MDW T 096,Reach-1
Reach XY= 30
      2281529.00      7144260.00      2281530.06      7143920.44
      2281612.62      7143729.79      2281629.09      7143470.54
      2281657.48      7143412.96      2281566.86      7143321.43
      2281581.14      7143266.06      2281684.84      7143007.71
      2281765.88      7142922.56      2281788.45      7142830.16
      2281913.37      7142691.02      2281904.28      7142616.37
      2281974.44      7142509.90      2281967.06      7142350.16
      2282130.89      7142076.16      2282119.18      7141954.70
      2282034.88      7141844.95      2281880.22      7141806.48
      2281835.99      7141765.81      2281885.27      7141631.50
      2281860.75      7141500.40      2281955.10      7141335.38
      2281945.45      7141254.88      2281871.27      7141177.40
      2281861.29      7141067.65      2281894.73      7141039.46
      2281889.19      7140978.00      2281752.47      7140323.14
      2281628.18      7139980.54      2281579.00      7139960.00

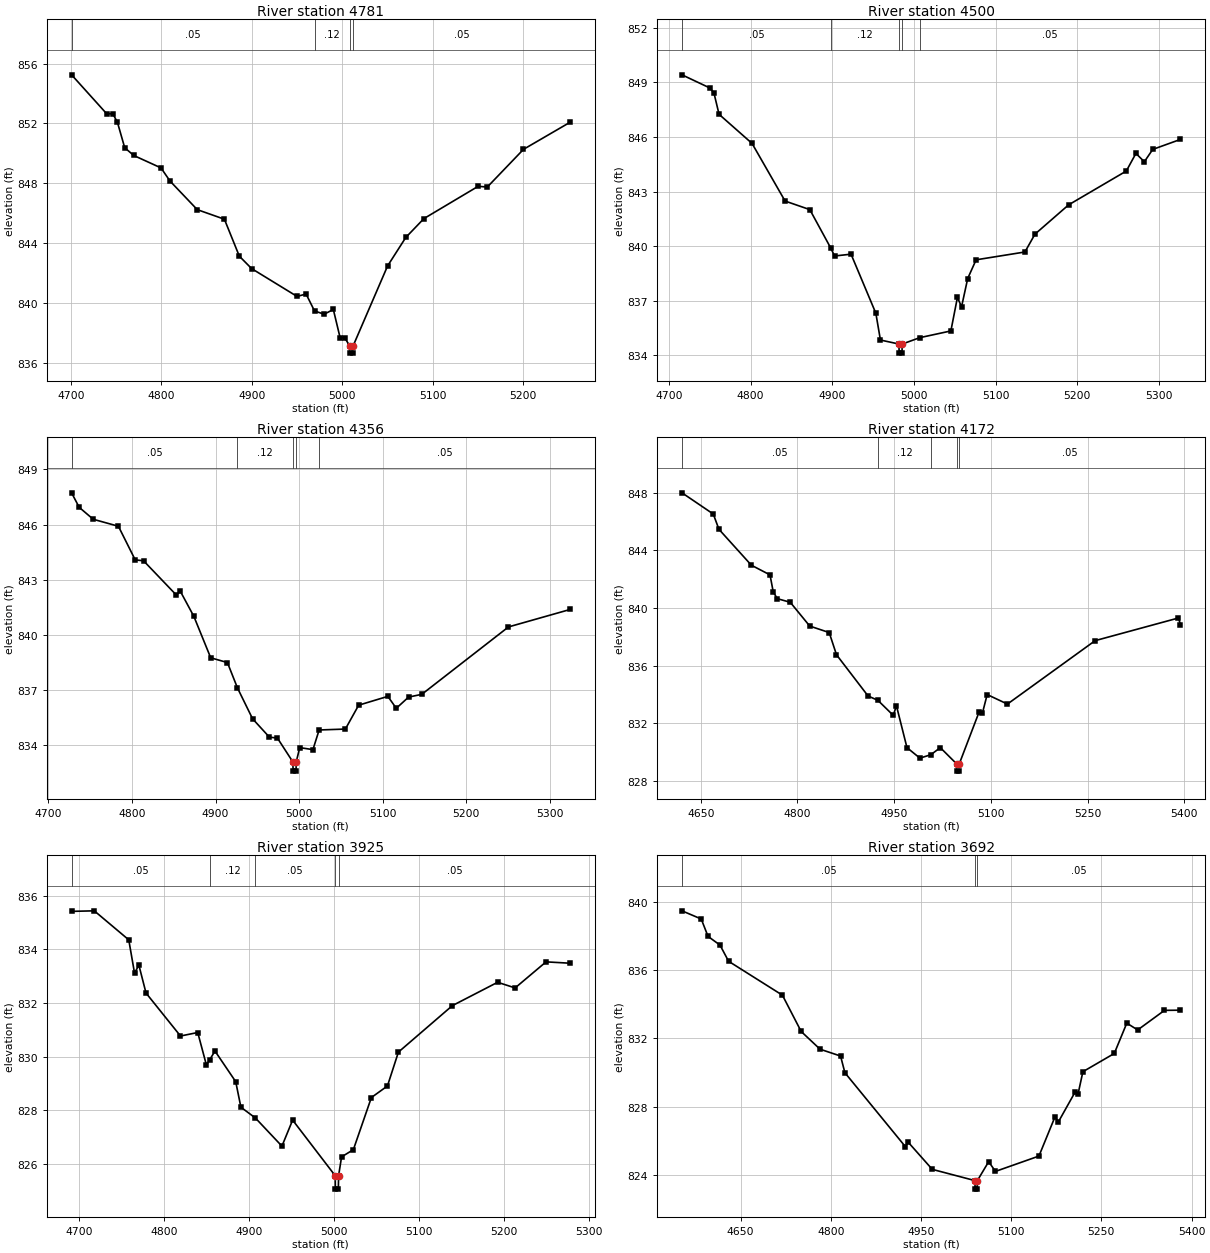
Type RM Length L Ch R = 1,4781,281,281,281
BEGIN DESCRIPTION:
MDW T 096 7.0
END DESCRIPTION:
XS GIS Cut Line= 3
      2281827.51      7144148.44      2281528.98      7144126.91
      2281277.56      7144138.71
#Sta/Elev= 30
  4700.7  855.25  4739.3  852.66  4746.4  852.64  4751.4  852.07  4759.4  850.38
  4769.4  849.86  4799.5  849.03  4809.5  848.15  4839.6  846.24  4869.6  845.60
  4886.1  843.13  4899.7  842.30  4949.9  840.44  4959.9  840.60  4969.2  839.47
  4979.9  839.25  4990.0  839.57  4997.5  837.68  5002.5  837.68  5008.0  837.15
  5008.2  836.65  5011.7  836.65  5012.0  837.15  5050.0  842.48  5070.1  844.38
  5090.1  845.64  5150.1  847.80  5160.2  847.75  5200.2  850.27  5251.7  852.08
#Mann=4,-1,0
  4700.7    0.05       0  4969.2    0.12       0  5008.0    0.07       0
  5012.0    0.05       0
Bank Sta=5008,5012
Exp/Cntr=0.3,0.1

Type RM Length L Ch R = 1,4500,144,144,144
BEGIN DESCRIPTION:
MDW T 096 6.0
END DESCRIPTION:
XS GIS Cut Line= 3
      2281853.92      7143900.52      2281579.00      7143860.00
      2281255.97      7143940.11
#Sta/Elev= 30
  4715.9  849.42  4749.9  848.70  4755.0  848.43  4761.3  847.25  4801.7  845.65
  4842.2  842.48  4872.5  842.01  4898.1  839.90  4902.8  839.46  4923.0  839.56
  4953.4  836.31  4959.0  834.84  4981.7  834.62  4981.9  834.12  4985.4  834.12
  4985.7  834.62  5007.2  834.97  5045.3  835.34  5053.3  837.18  5058.4  836.67
  5065.9  838.22  5076.2  839.25  5136.0  839.68  5148.3  840.66  5189.5  842.27
  5260.2  844.13  5272.0  845.10  5282.3  844.64  5292.6  845.32  5326.6  845.87
#Mann=5,-1,0
  4715.9    0.05       0  4898.1    0.12       0  4981.7    0.07       0
  4985.7    0.12       0  5007.2    0.05       0
Bank Sta=4981.7,4985.7
Exp/Cntr=0.3,0.1

Type RM Length L Ch R = 1,4356,184,184,184
BEGIN DESCRIPTION:
Mapping XS 6f28b83c
END DESCRIPTION:
XS GIS Cut Line= 3
      2281884.81      7143745.61      2281611.66      7143723.08
      2281294.16      7143778.03
#Sta/Elev= 30
  4727.8  847.73  4736.9  846.94  4753.7  846.29  4783.8  845.91  4803.9  844.08
  4813.9  844.03  4853.0  842.17  4858.0  842.36  4874.1  841.00  4894.2  838.75
  4914.2  838.49  4926.2  837.11  4944.3  835.43  4964.4  834.43  4974.0  834.38
  4992.5  833.08  4992.8  832.58  4996.3  832.58  4996.5  833.08  5000.7  833.86
  5016.5  833.75  5023.9  834.82  5055.3  834.87  5071.2  836.17  5106.1  836.65
  5116.2  836.00  5130.9  836.61  5146.7  836.76  5250.4  840.43  5324.1  841.38
#Mann=5,-1,0
  4727.8    0.05       0  4926.2    0.12       0  4992.5    0.07       0
  4996.5    0.12       0  5023.9    0.05       0
Bank Sta=4992.5,4996.5
Exp/Cntr=0.3,0.1

Type RM Length L Ch R = 1,4172,247,247,247
BEGIN DESCRIPTION:
MDW T 096 5.0
END DESCRIPTION:
XS GIS Cut Line= 3
      2282006.02      7143579.69      2281629.00      7143540.00
      2281252.62      7143656.49
#Sta/Elev= 30
  4620.9  847.98  4669.4  846.51  4678.2  845.45  4728.5  842.96  4757.4  842.29
  4762.4  841.11  4768.7  840.64  4788.8  840.39  4819.0  838.74  4849.2  838.29
  4860.5  836.75  4909.5  833.89  4924.7  833.59  4948.5  832.55  4953.5  833.21
  4969.8  830.31  4989.9  829.58  5006.9  829.82  5021.5  830.31  5046.9  829.18
  5047.2  828.68  5050.7  828.68  5050.9  829.18  5081.5  832.76  5086.8  832.70
  5094.2  833.99  5125.6  833.33  5261.7  837.73  5390.8  839.30  5394.0  838.84
#Mann=5,-1,0
  4620.9    0.05       0  4924.7    0.12       0  5006.9    0.05       0
  5046.9    0.07       0  5050.9    0.05       0
Bank Sta=5046.9,5050.9
Exp/Cntr=0.3,0.1

Type RM Length L Ch R = 1,3925,233,233,233
BEGIN DESCRIPTION:
Mapping XS 64ff7d38
END DESCRIPTION:
XS GIS Cut Line= 3
      2281885.32      7143291.96      2281570.41      7143346.92
      2281318.07      7143434.58
#Sta/Elev= 30
  4690.8  835.41  4717.5  835.43  4758.1  834.35  4764.9  833.11  4770.0  833.41
  4778.4  832.37  4819.0  830.77  4839.3  830.90  4849.5  829.69  4853.4  829.89
  4859.6  830.21  4884.0  829.07  4890.1  828.12  4907.1  827.72  4938.4  826.67
  4951.0  827.64  5001.1  825.57  5001.3  825.07  5004.8  825.07  5005.1  825.57
  5008.6  826.27  5022.5  826.54  5043.7  828.48  5062.6  828.91  5075.5  830.17
  5139.0  831.90  5192.3  832.77  5212.9  832.56  5249.3  833.53  5277.6  833.48
#Mann=5,-1,0
  4690.8    0.05       0  4853.4    0.12       0  4907.1    0.05       0
  5001.1   0.033       0  5005.1    0.05       0
Bank Sta=5001.1,5005.1
Exp/Cntr=0.3,0.1

Type RM Length L Ch R = 1,3692,153,153,153
BEGIN DESCRIPTION:
MDW T 096 4.0
END DESCRIPTION:
XS GIS Cut Line= 3
      2282059.85      7143255.53      2281628.99      7143135.00
      2281263.52      7143025.23
#Sta/Elev= 30
  4552.6  839.49  4584.6  839.01  4595.9  837.99  4615.8  837.48  4630.1  836.53
  4719.6  834.54  4750.8  832.41  4782.2  831.37  4816.3  830.97  4823.5  829.99
  4923.9  825.66  4929.1  825.90  4968.8  824.32  5039.8  823.66  5040.0  823.16
  5043.5  823.16  5043.8  823.66  5062.6  824.77  5073.9  824.20  5146.2  825.10
  5173.0  827.41  5178.3  827.09  5206.1  828.84  5211.3  828.75  5219.3  830.05
  5271.5  831.12  5292.3  832.90  5310.4  832.50  5355.0  833.65  5381.6  833.66
#Mann=3,-1,0
  4552.6    0.05       0  5039.8   0.033       0  5043.8    0.05       0
Bank Sta=5039.8,5043.8
Exp/Cntr=0.3,0.1

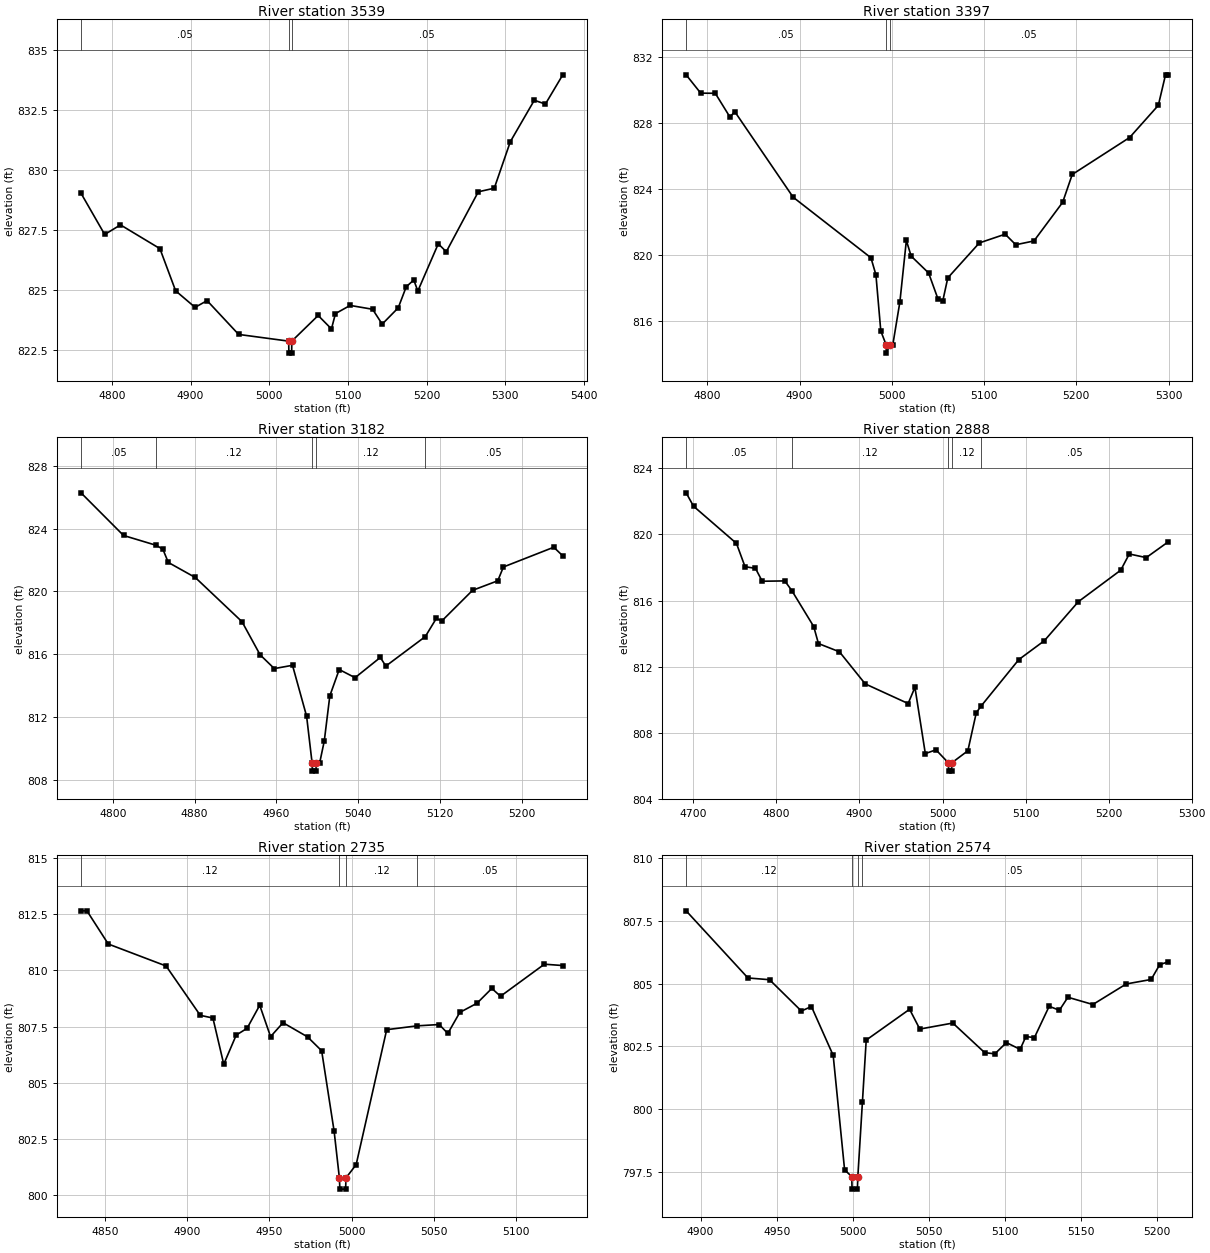
Type RM Length L Ch R = 1,3539,142,142,142
BEGIN DESCRIPTION:
Mapping XS 83e39b55
END DESCRIPTION:
XS GIS Cut Line= 3
      2281929.10      7143012.85      2281689.29      7142999.82
      2281323.44      7142930.66
#Sta/Elev= 30
  4760.7  829.04  4790.8  827.32  4810.9  827.72  4861.0  826.73  4881.0  824.97
  4905.7  824.28  4921.0  824.56  4961.1  823.15  5024.7  822.87  5025.0  822.37
  5028.5  822.37  5028.7  822.87  5062.2  823.94  5079.1  823.38  5084.2  824.02
  5102.9  824.36  5131.4  824.20  5143.6  823.58  5164.0  824.26  5174.2  825.14
  5183.8  825.42  5188.9  824.96  5214.9  826.93  5225.1  826.60  5265.8  829.10
  5286.1  829.25  5306.5  831.19  5337.0  832.92  5351.1  832.76  5373.2  833.98
#Mann=3,-1,0
  4760.7    0.05       0  5024.7    0.04       0  5028.7    0.05       0
Bank Sta=5024.7,5028.7
Exp/Cntr=0.3,0.1

Type RM Length L Ch R = 1,3397,215,215,215
BEGIN DESCRIPTION:
MDW T 096 3.0
END DESCRIPTION:
XS GIS Cut Line= 3
      2281979.02      7142960.01      2281768.91      7142890.08
      2281479.00      7142810.00
#Sta/Elev= 30
  4777.1  830.90  4792.9  829.79  4808.7  829.78  4824.6  828.34  4829.8  828.67
  4893.1  823.48  4977.4  819.81  4982.8  818.78  4988.1  815.37  4993.9  814.53
  4994.1  814.03  4997.9  814.53  5001.1  814.53  5008.8  817.14  5015.8  820.86
  5021.0  819.91  5039.9  818.89  5050.1  817.31  5055.3  817.20  5060.7  818.59
  5094.9  820.71  5122.9  821.24  5134.4  820.60  5154.1  820.83  5185.2  823.17
  5195.6  824.86  5257.8  827.10  5288.9  829.05  5296.7  830.90  5299.3  830.90
#Mann=3,-1,0
  4777.1    0.05       0  4993.9   0.033       0  4997.9    0.05       0
Bank Sta=4993.9,4997.9
Exp/Cntr=0.3,0.1

Type RM Length L Ch R = 1,3182,294,294,294
BEGIN DESCRIPTION:
MDW T 096 2.0
END DESCRIPTION:
XS GIS Cut Line= 3
      2282108.49      7142790.68      2281889.87      7142718.29
      2281664.74      7142632.28
#Sta/Elev= 30
  4768.8  826.29  4810.4  823.57  4842.5  822.94  4848.9  822.69  4854.2  821.85
  4880.6  820.89  4926.3  818.07  4944.0  815.96  4957.9  815.08  4975.7  815.29
  4989.5  812.04  4994.9  809.04  4995.2  808.54  4998.7  808.54  4998.9  809.04
  5002.2  809.04  5006.8  810.47  5012.2  813.34  5021.4  815.02  5036.9  814.50
  5061.6  815.79  5067.0  815.24  5105.6  817.12  5116.4  818.28  5121.8  818.12
  5151.8  820.07  5176.5  820.68  5182.0  821.56  5231.3  822.82  5240.1  822.27
#Mann=5,-1,0
  4768.8    0.05       0  4842.5    0.12       0  4994.9    0.07       0
  4998.9    0.12       0  5105.6    0.05       0
Bank Sta=4994.9,4998.9
Exp/Cntr=0.3,0.1

Type RM Length L Ch R = 1,2888,153,153,153
BEGIN DESCRIPTION:
MDW T 096 1.0
END DESCRIPTION:
XS GIS Cut Line= 3
      2282267.61      7142535.39      2281979.00      7142460.00
      2281703.51      7142519.33
#Sta/Elev= 30
  4691.3  822.52  4700.2  821.71  4751.9  819.46  4762.2  818.05  4774.8  817.95
  4782.9  817.17  4810.1  817.19  4818.6  816.60  4844.9  814.43  4850.6  813.40
  4875.9  812.90  4906.9  810.96  4958.6  809.77  4966.8  810.75  4979.3  806.74
  4992.1  806.97  5007.1  806.18  5007.4  805.68  5010.9  805.68  5011.1  806.18
  5030.5  806.91  5040.7  809.22  5046.5  809.62  5091.9  812.43  5122.6  813.57
  5163.5  815.93  5214.6  817.84  5224.9  818.82  5245.3  818.60  5271.4  819.54
#Mann=5,-1,0
  4691.3    0.05       0  4818.6    0.12       0  5007.1    0.07       0
  5011.1    0.12       0  5046.5    0.05       0
Bank Sta=5007.1,5011.1
Exp/Cntr=0.3,0.1

Type RM Length L Ch R = 1,2735,161,161,161
BEGIN DESCRIPTION:
Mapping XS 150498db
END DESCRIPTION:
XS GIS Cut Line= 3
      2282112.12      7142409.76      2282010.31      7142321.70
      2281859.32      7142272.86
#Sta/Elev= 30
  4835.3  812.66  4838.9  812.66  4851.9  811.18  4887.1  810.20  4907.9  808.00
  4915.6  807.88  4922.2  805.82  4929.8  807.12  4936.4  807.42  4944.1  808.45
  4950.7  807.05  4958.3  807.67  4973.2  807.04  4981.8  806.42  4989.4  802.83
  4992.6  800.75  4992.9  800.25  4996.4  800.25  4996.6  800.75  5002.8  801.34
  5021.4  807.36  5039.8  807.53  5053.4  807.59  5058.6  807.19  5065.9  808.13
  5076.4  808.54  5085.4  809.20  5090.7  808.85  5117.4  810.28  5128.6  810.22
#Mann=4,-1,0
  4835.3    0.12       0  4992.6    0.07       0  4996.6    0.12       0
  5039.8    0.05       0
Bank Sta=4992.6,4996.6
Exp/Cntr=0.3,0.1

Type RM Length L Ch R = 1,2574,222,222,222
BEGIN DESCRIPTION:
Mapping XS afe98a85
END DESCRIPTION:
XS GIS Cut Line= 3
      2282140.70      7142245.10      2281977.81      7142101.43
      2281890.07      7142147.94
#Sta/Elev= 30
  4890.5  807.91  4931.1  805.23  4945.3  805.16  4966.2  803.91  4972.8  804.09
  4987.1  802.14  4994.6  797.57  4999.3  797.30  4999.5  796.80  5003.0  796.80
  5003.3  797.30  5006.3  800.27  5008.8  802.75  5037.3  803.98  5044.0  803.19
  5065.7  803.43  5086.6  802.25  5093.3  802.20  5100.9  802.65  5109.9  802.38
  5113.7  802.89  5119.3  802.85  5129.0  804.10  5135.7  803.94  5141.3  804.46
  5157.7  804.17  5179.6  804.99  5196.0  805.17  5201.6  805.76  5207.0  805.87
#Mann=4,-1,0
  4890.5    0.12       0  4999.3    0.07       0  5003.3    0.12       0
  5006.3    0.05       0
Bank Sta=4999.3,5003.3
Exp/Cntr=0.3,0.1

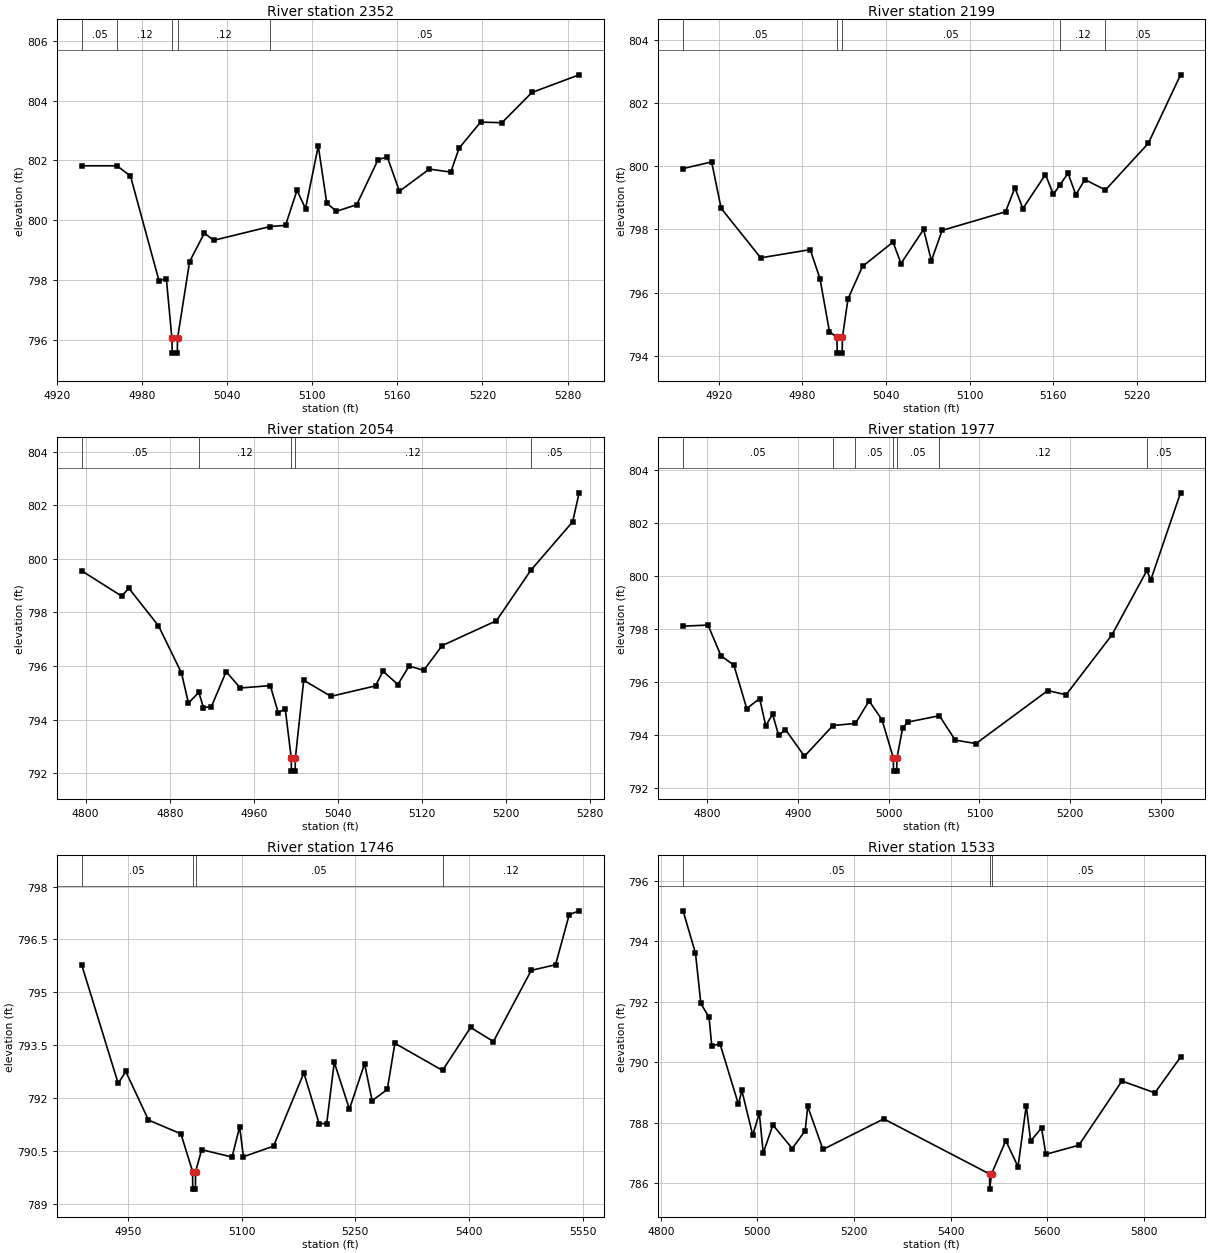
Type RM Length L Ch R = 1,2352,153,153,153
BEGIN DESCRIPTION:
Mapping XS 3866dc01
END DESCRIPTION:
XS GIS Cut Line= 3
      2282181.95      7141958.32      2282081.59      7141987.88
      2281876.18      7142123.37
#Sta/Elev= 30
  4937.5  801.82  4962.4  801.82  4971.9  801.48  4992.0  797.98  4997.2  798.05
  5001.1  796.06  5001.4  795.56  5004.9  795.56  5005.1  796.06  5013.6  798.62
  5024.0  799.57  5030.6  799.33  5070.3  799.79  5081.2  799.83  5089.3  801.00
  5095.3  800.39  5104.3  802.48  5110.3  800.57  5117.1  800.30  5131.4  800.52
  5146.5  802.03  5153.0  802.11  5161.5  800.97  5182.6  801.71  5197.7  801.61
  5203.6  802.41  5218.7  803.28  5233.8  803.26  5254.9  804.27  5288.2  804.86
#Mann=5,-1,0
  4937.5    0.05       0  4962.4    0.12       0  5001.1    0.07       0
  5005.1    0.12       0  5070.3    0.05       0
Bank Sta=5001.1,5005.1
Exp/Cntr=0.3,0.1

Type RM Length L Ch R = 1,2199,145,145,145
BEGIN DESCRIPTION:
Mapping XS cbdf5a2d
END DESCRIPTION:
XS GIS Cut Line= 3
      2282110.61      7141772.82      2282034.11      7141856.05
      2281917.81      7142070.27
#Sta/Elev= 30
  4894.4  799.93  4914.9  800.14  4921.7  798.67  4950.1  797.10  4985.6  797.36
  4992.6  796.44  4999.4  794.76  5004.7  794.58  5005.0  794.08  5008.5  794.08
  5008.7  794.58  5012.7  795.80  5023.1  796.83  5045.0  797.60  5050.7  796.92
  5066.9  798.00  5072.5  797.01  5080.2  797.97  5125.7  798.56  5132.4  799.32
  5138.1  798.66  5154.3  799.74  5160.0  799.11  5164.5  799.40  5170.5  799.78
  5176.1  799.10  5182.6  799.58  5197.3  799.25  5228.1  800.73  5251.2  802.90
#Mann=5,-1,0
  4894.4    0.05       0  5004.7   0.033       0  5008.7    0.05       0
  5164.5    0.12       0  5197.3    0.05       0
Bank Sta=5004.7,5008.7
Exp/Cntr=0.3,0.1

Type RM Length L Ch R = 1,2054,77,77,77
BEGIN DESCRIPTION:
Mapping XS f2cb5bf8
END DESCRIPTION:
XS GIS Cut Line= 4
      2282038.62      7141656.01      2281899.75      7141816.56
      2281861.49      7141923.11      2281899.59      7142066.03
#Sta/Elev= 30
  4796.2  799.55  4834.2  798.61  4841.1  798.90  4869.3  797.50  4891.2  795.74
  4897.8  794.62  4907.7  795.02  4912.1  794.45  4919.7  794.49  4933.7  795.79
  4947.2  795.18  4975.7  795.27  4983.3  794.25  4989.9  794.41  4995.6  792.58
  4995.8  792.08  4999.3  792.08  4999.6  792.58  5007.5  795.47  5033.4  794.87
  5075.9  795.26  5082.9  795.81  5097.1  795.31  5107.8  796.00  5121.7  795.84
  5139.2  796.76  5190.9  797.69  5223.6  799.57  5263.4  801.38  5269.6  802.46
#Mann=5,-1,0
  4796.2    0.05       0  4907.7    0.12       0  4995.6    0.07       0
  4999.6    0.12       0  5223.6    0.05       0
Bank Sta=4995.6,4999.6
Exp/Cntr=0.3,0.1

Type RM Length L Ch R = 1,1977,231,231,231
BEGIN DESCRIPTION:
Mapping XS 07235abd
END DESCRIPTION:
XS GIS Cut Line= 4
      2281992.90      7141605.18      2281841.12      7141774.74
      2281804.42      7141853.81      2281780.38      7142085.33
#Sta/Elev= 30
  4773.8  798.10  4801.3  798.14  4815.5  796.98  4829.7  796.63  4843.9  794.99
  4858.1  795.37  4864.8  794.34  4872.3  794.78  4879.0  793.98  4886.5  794.20
  4907.4  793.19  4938.7  794.35  4963.5  794.43  4978.5  795.28  4992.7  794.57
  5005.2  793.13  5005.4  792.63  5008.9  792.63  5009.2  793.13  5015.5  794.26
  5021.0  794.48  5055.9  794.72  5073.3  793.80  5096.2  793.67  5175.2  795.67
  5195.3  795.51  5245.6  797.76  5284.3  800.20  5288.5  799.84  5321.3  803.13
#Mann=7,-1,0
  4773.8    0.05       0  4938.7    0.12       0  4963.5    0.05       0
  5005.2   0.033       0  5009.2    0.05       0  5055.9    0.12       0
  5284.3    0.05       0
Bank Sta=5005.2,5009.2
Exp/Cntr=0.3,0.1

Type RM Length L Ch R = 1,1746,213,213,213
BEGIN DESCRIPTION:
Mapping XS 957a035f
END DESCRIPTION:
XS GIS Cut Line= 3
      2281987.07      7141547.05      2281773.92      7141560.24
      2281763.18      7142003.15
#Sta/Elev= 30
  4888.8  795.78  4937.0  792.41  4947.0  792.75  4977.0  791.37  5019.8  790.98
  5035.2  789.91  5035.4  789.41  5038.9  789.41  5039.2  789.91  5047.2  790.53
  5087.3  790.32  5097.3  791.18  5102.3  790.33  5142.1  790.63  5182.1  792.71
  5202.2  791.27  5212.2  791.27  5222.2  793.01  5242.2  791.68  5262.2  792.97
  5272.2  791.92  5292.2  792.24  5302.2  793.55  5365.1  792.78  5402.2  794.00
  5432.2  793.60  5482.2  795.62  5514.3  795.78  5532.3  797.20  5545.4  797.31
#Mann=4,-1,0
  4888.8    0.05       0  5035.2   0.035       0  5039.2    0.05       0
  5365.1    0.12       0
Bank Sta=5035.2,5039.2
Exp/Cntr=0.3,0.1

Type RM Length L Ch R = 1,1533,127,127,127
BEGIN DESCRIPTION:
Mapping XS 6ceda70a
END DESCRIPTION:
XS GIS Cut Line= 4
      2282007.62      7141503.13      2281940.19      7141363.91
      2281846.72      7141363.00      2281106.42      7141612.88
#Sta/Elev= 30
  4846.3  795.00  4872.0  793.60  4883.1  791.94  4900.1  791.48  4905.7  790.54
  4922.7  790.61  4960.9  788.61  4967.9  789.07  4990.5  787.59  5004.1  788.32
  5012.2  787.00  5032.2  787.93  5072.2  787.15  5099.0  787.74  5104.3  788.54
  5135.8  787.12  5261.6  788.13  5480.6  786.31  5480.8  785.81  5484.6  786.31
  5514.2  787.41  5539.5  786.55  5556.5  788.57  5565.7  787.40  5588.1  787.83
  5597.2  786.96  5665.4  787.26  5754.5  789.38  5822.7  788.99  5875.8  790.17
#Mann=3,-1,0
  4846.3    0.05       0  5480.6   0.035       0  5484.6    0.05       0
Bank Sta=5480.6,5484.6
Exp/Cntr=0.3,0.1

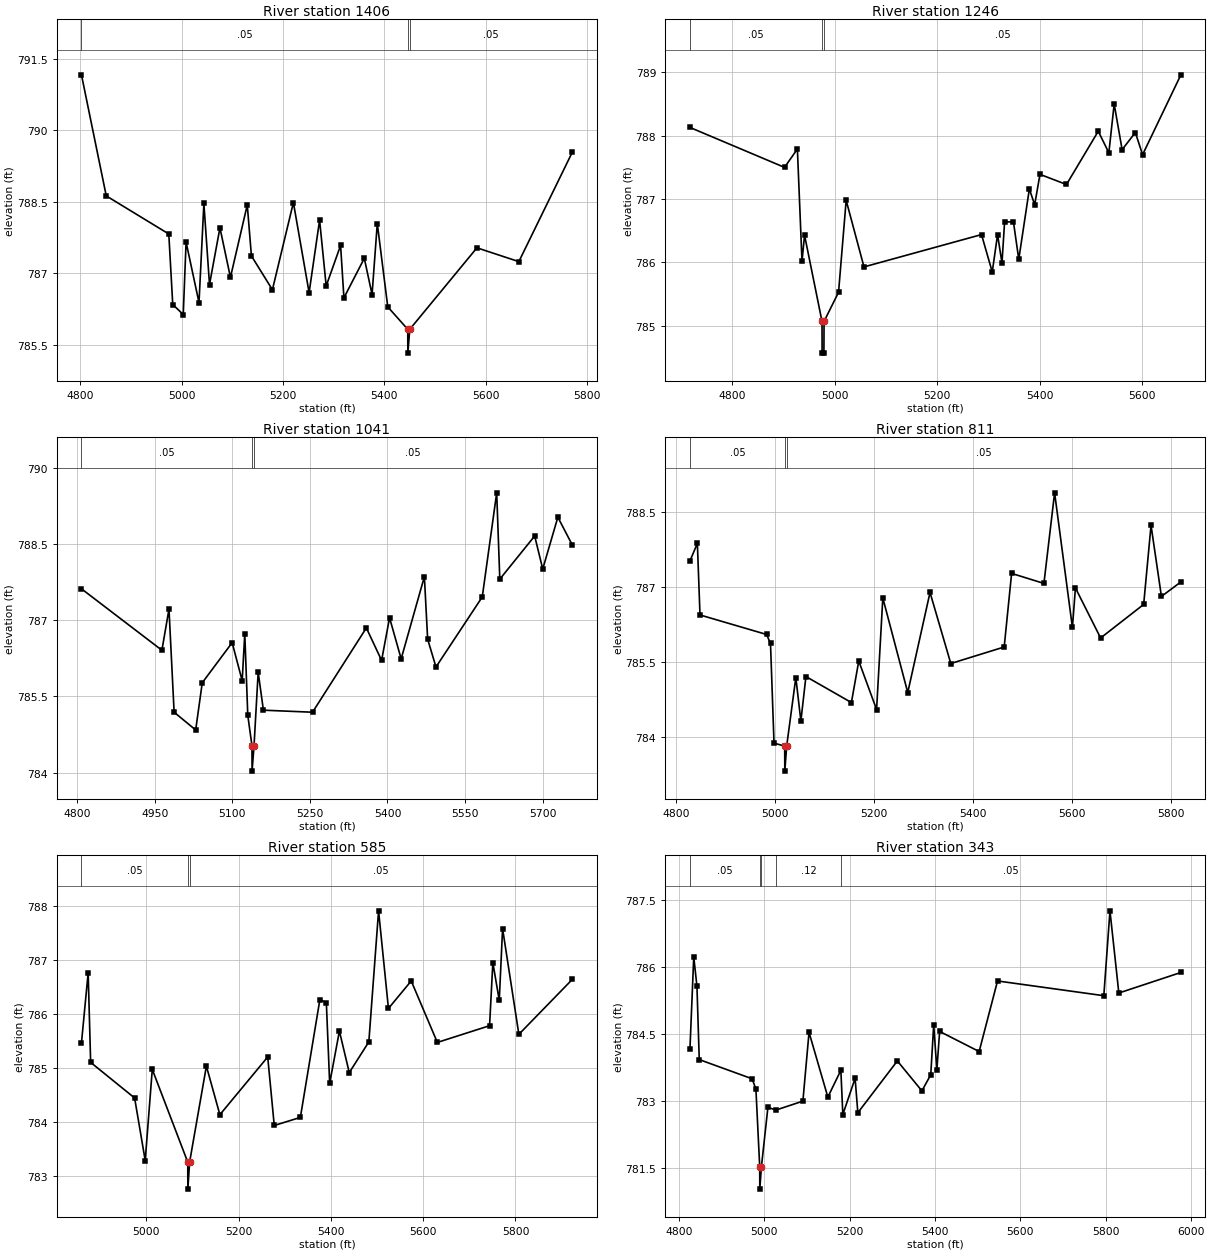
Type RM Length L Ch R = 1,1406,160,160,160
BEGIN DESCRIPTION:
Mapping XS b6ecfa0e
END DESCRIPTION:
XS GIS Cut Line= 3
      2282030.58      7141393.50      2281969.25      7141235.44
      2281196.93      7141440.04
#Sta/Elev= 30
  4802.3  791.16  4851.2  788.62  4974.6  787.82  4982.4  786.34  5003.1  786.13
  5008.7  787.65  5034.2  786.38  5043.8  788.46  5054.9  786.76  5075.5  787.95
  5096.2  786.91  5129.4  788.43  5137.6  787.36  5179.0  786.65  5220.4  788.48
  5251.4  786.59  5272.1  788.11  5285.1  786.73  5313.5  787.58  5320.1  786.48
  5360.3  787.31  5375.6  786.55  5385.9  788.04  5406.6  786.29  5446.0  785.82
  5446.2  785.32  5450.0  785.82  5582.5  787.53  5665.2  787.24  5770.8  789.54
#Mann=3,-1,0
  4802.3    0.05       0  5446.0   0.035       0  5450.0    0.05       0
Bank Sta=5446,5450
Exp/Cntr=0.3,0.1

Type RM Length L Ch R = 1,1246,205,205,205
BEGIN DESCRIPTION:
Mapping XS 53b21ef4
END DESCRIPTION:
XS GIS Cut Line= 4
      2282003.73      7141305.59      2281949.09      7141113.45
      2281868.05      7141118.88      2281213.14      7141294.79
#Sta/Elev= 30
  4716.9  788.13  4901.7  787.50  4926.8  787.79  4935.8  786.02  4940.8  786.43
  4974.9  785.07  4975.1  784.57  4978.6  784.57  4978.9  785.07  5007.2  785.53
  5022.1  786.98  5056.9  785.93  5286.5  786.44  5307.5  785.85  5317.9  786.44
  5326.5  785.99  5331.6  786.64  5348.9  786.64  5359.3  786.05  5380.0  787.16
  5390.4  786.91  5400.7  787.39  5452.5  787.23  5514.6  788.07  5535.3  787.73
  5545.7  788.50  5561.2  787.78  5587.1  788.05  5601.2  787.70  5676.0  788.96
#Mann=3,-1,0
  4716.9    0.05       0  4974.9   0.033       0  4978.9    0.05       0
Bank Sta=4974.9,4978.9
Exp/Cntr=0.3,0.1

Type RM Length L Ch R = 1,1041,230,230,230
BEGIN DESCRIPTION:
MDW T 096 0.1
END DESCRIPTION:
XS GIS Cut Line= 5
      2281954.50      7141093.80      2281911.32      7140943.67
      2281872.90      7140930.89      2281693.64      7140952.42
      2281183.97      7141211.52
#Sta/Elev= 30
  4808.4  787.62  4963.9  786.41  4977.6  787.22  4987.5  785.19  5029.2  784.84
  5041.9  785.77  5099.7  786.56  5119.1  785.81  5124.1  786.74  5129.9  785.13
  5138.0  784.53  5138.2  784.03  5142.0  784.53  5150.0  785.98  5160.1  785.23
  5255.1  785.19  5359.1  786.85  5388.6  786.21  5404.0  787.05  5426.4  786.24
  5471.3  787.86  5477.6  786.63  5493.7  786.08  5583.2  787.46  5611.1  789.51
  5617.1  787.81  5684.5  788.66  5700.1  788.01  5729.3  789.03  5757.4  788.48
#Mann=3,-1,0
  4808.4    0.05       0  5138.0   0.035       0  5142.0    0.05       0
Bank Sta=5138,5142
Exp/Cntr=0.3,0.1

Type RM Length L Ch R = 1,811,226,226,226
BEGIN DESCRIPTION:
Mapping XS a5760d76
END DESCRIPTION:
XS GIS Cut Line= 4
      2281909.33      7140848.62      2281855.06      7140701.74
      2281705.36      7140734.22      2281139.46      7141115.61
#Sta/Elev= 30
  4827.4  787.52  4842.4  787.87  4847.7  786.44  4982.3  786.05  4990.2  785.87
  4997.3  783.88  5018.9  783.82  5019.1  783.32  5022.9  783.82  5041.4  785.19
  5051.6  784.32  5061.8  785.21  5153.7  784.69  5168.6  785.52  5204.6  784.55
  5217.2  786.78  5267.6  784.89  5312.6  786.89  5354.6  785.47  5462.5  785.80
  5477.5  787.27  5542.8  787.07  5564.4  788.88  5600.4  786.19  5606.5  786.98
  5657.4  785.98  5744.4  786.65  5759.3  788.23  5780.3  786.81  5819.6  787.10
#Mann=3,-1,0
  4827.4    0.05       0  5018.9   0.035       0  5022.9    0.05       0
Bank Sta=5018.9,5022.9
Exp/Cntr=0.3,0.1

Type RM Length L Ch R = 1,585,242,242,242
BEGIN DESCRIPTION:
Mapping XS c7a91349
END DESCRIPTION:
XS GIS Cut Line= 4
      2281850.15      7140596.75      2281802.52      7140479.08
      2281574.14      7140597.97      2281084.93      7141069.80
#Sta/Elev= 30
  4859.2  785.46  4873.7  786.76  4879.1  785.10  4974.4  784.44  4997.4  783.28
  5012.7  784.97  5089.6  783.25  5089.8  782.75  5093.6  783.25  5130.0  785.03
  5159.2  784.13  5262.9  785.20  5277.1  783.93  5333.7  784.08  5375.9  786.26
  5390.0  786.21  5397.2  784.71  5418.3  785.68  5439.7  784.91  5482.1  785.48
  5503.2  787.91  5524.6  786.10  5574.0  786.61  5630.6  785.47  5743.8  785.78
  5750.9  786.95  5764.8  786.25  5772.0  787.58  5807.3  785.62  5923.3  786.64
#Mann=3,-1,0
  4859.2    0.05       0  5089.6   0.035       0  5093.6    0.05       0
Bank Sta=5089.6,5093.6
Exp/Cntr=0.3,0.1

Type RM Length L Ch R = 1,343,99,99,99
BEGIN DESCRIPTION:
Mapping XS 428c66ab
END DESCRIPTION:
XS GIS Cut Line= 4
      2281811.21      7140378.17      2281752.89      7140240.37
      2281630.08      7140298.77      2281082.76      7140968.57
#Sta/Elev= 30
  4826.0  784.16  4834.9  786.22  4842.4  785.56  4847.8  783.92  4971.7  783.49
  4980.6  783.26  4989.5  781.52  4989.7  781.02  4993.5  781.52  5008.7  782.85
  5027.5  782.79  5090.7  782.99  5105.1  784.53  5149.2  783.08  5179.7  783.68
  5184.3  782.69  5213.1  783.50  5219.5  782.73  5312.1  783.89  5369.6  783.22
  5390.4  783.58  5397.3  784.70  5404.7  783.69  5411.2  784.55  5503.8  784.10
  5546.9  785.68  5796.0  785.35  5810.4  787.25  5831.2  785.41  5976.6  785.87
#Mann=5,-1,0
  4826.0    0.05       0  4989.5    0.04       0  4993.5    0.05       0
  5027.5    0.12       0  5179.7    0.05       0
Bank Sta=4989.5,4993.5
Exp/Cntr=0.3,0.1

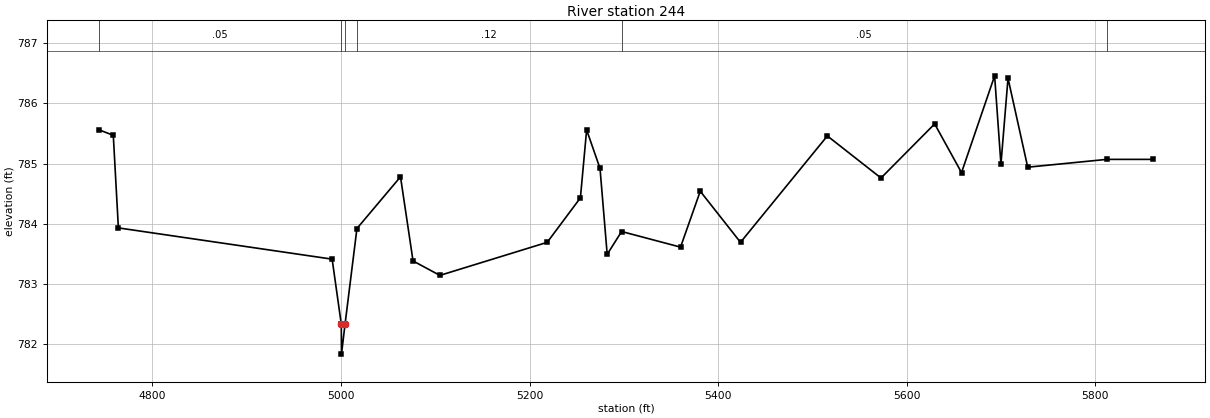
Type RM Length L Ch R = 1,244,0,0,0
BEGIN DESCRIPTION:
MDW T096 0.5
END DESCRIPTION:
XS GIS Cut Line= 4
      2281811.35      7140363.87      2281726.95      7140150.12
      2281642.75      7140170.50      2281114.44      7140772.25
#Sta/Elev= 30
  4743.7  785.56  4758.5  785.47  4763.9  783.93  4990.6  783.41  5000.3  782.33
  5000.5  781.83  5004.3  782.33  5016.9  783.92  5063.1  784.78  5076.4  783.38
  5104.9  783.14  5218.7  783.69  5253.9  784.43  5260.5  785.56  5274.7  784.92
  5282.3  783.49  5297.6  783.87  5360.1  783.61  5381.0  784.54  5423.7  783.69
  5515.8  785.46  5572.7  784.76  5629.6  785.66  5658.1  784.85  5693.2  786.46
  5699.9  784.99  5707.4  786.42  5728.3  784.94  5812.1  785.07  5860.9  785.07
#Mann=6,-1,0
  4743.7    0.05       0  5000.3    0.04       0  5004.3    0.05       0
  5016.9    0.12       0  5297.6    0.05       0  5812.1    0.12       0
Bank Sta=5000.3,5004.3
Exp/Cntr=0.3,0.1

Chan Stop Cuts=-1