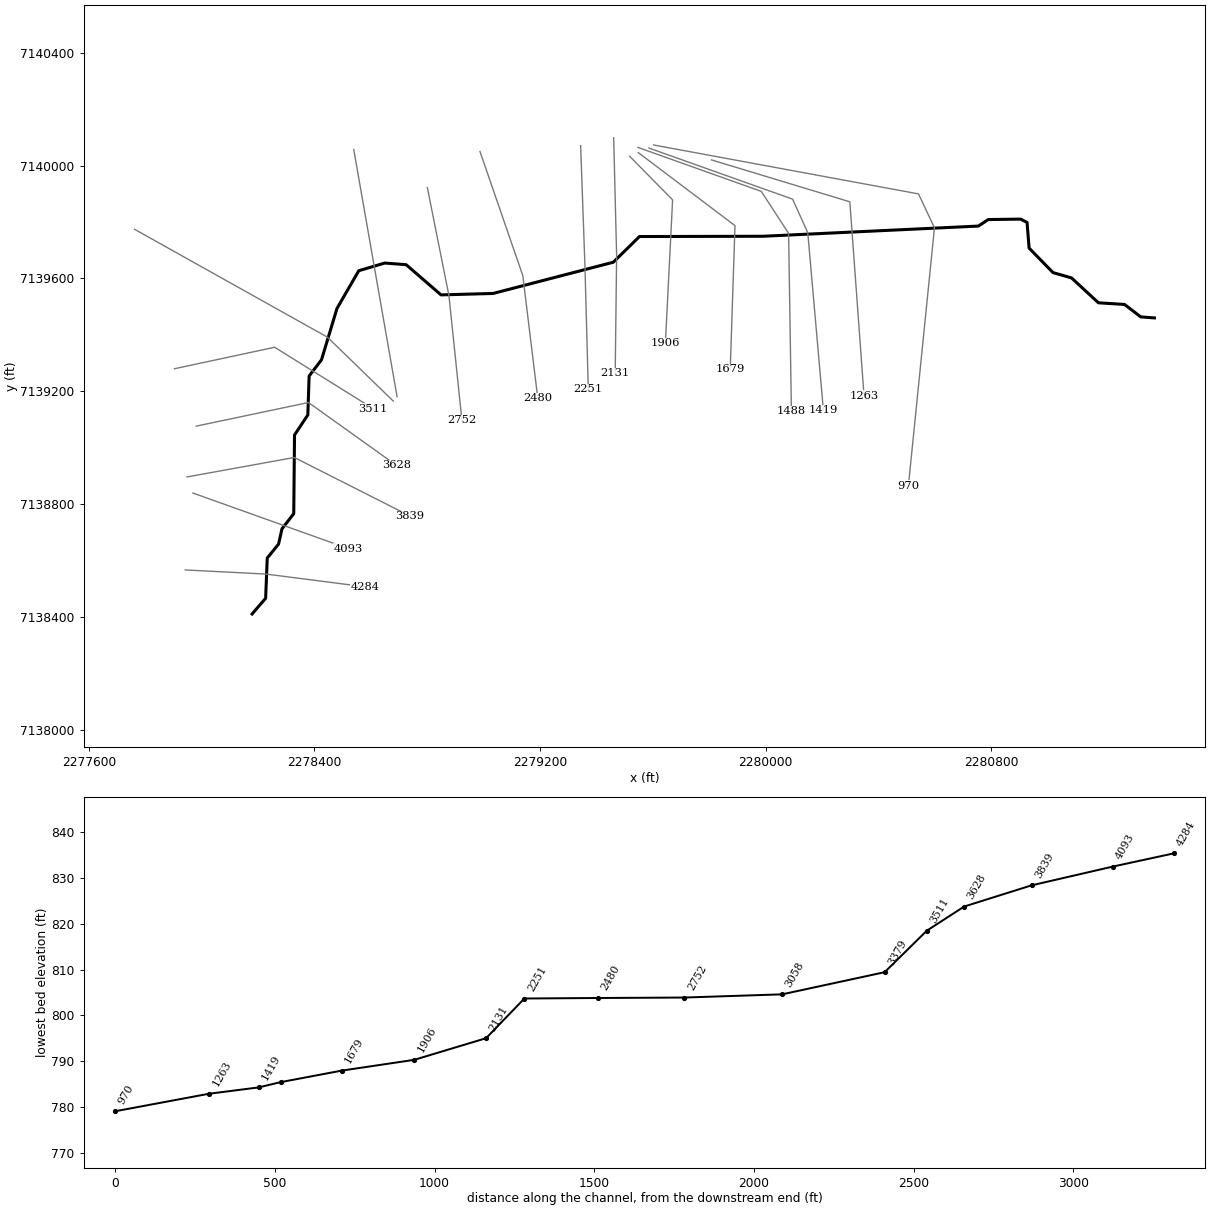
--- MDW T 097.prj (project) ---

Proj Title=MDW T 097 Base Level Engineering
Current Plan=p01
Default Exp/Contr=0.3,0.1
English Units
Geom File=g01
Flow File=f01
Plan File=p01
BEGIN DESCRIPTION:
MDW T 097
END DESCRIPTION:

--- MDW T 097.p01 (plan) ---

Plan Title=Multiple Run
Short Identifier=Multiple
Geom File=g01
Flow File=f01
Subcritical Flow
K Sum by GR= 0
Std Step Tol= 0.01
Critical Tol= 0.01
Num of Std Step Trials= 20
Max Error Tol= 0.3
Flow Tol Ratio= 0.001
Split Flow NTrial= 30
Split Flow Tol= 0.02
Split Flow Ratio= 0.02
Log Output Level= 0
Friction Slope Method= 1
Unsteady Friction Slope Method= 2
Unsteady Bridges Friction Slope Method= 1
Parabolic Critical Depth
Global Vel Dist=  1 , 1 , 1
Global Log Level= 0
CheckData=True
Encroach Param= -1, 0, 0, 0
BEGIN DESCRIPTION:
Multiple Run
END DESCRIPTION:

--- MDW T 097.f01 (steady flow) ---

Flow Title=Multiple
Number of Profiles=7
Profile Names=10-year,25-year,50-year,1pct_min,100-year,1pct_plu,500-year
River Rch & RM= MDW T 097,Reach-1,4284
     464     631     768     466     930    1855    1362
Boundary for River Rch & Prof#=MDW T 097,Reach-1,1
Up Type=0
Dn Type=3
Dn Slope=0.005
Boundary for River Rch & Prof#=MDW T 097,Reach-1,2
Up Type=0
Dn Type=3
Dn Slope=0.005
Boundary for River Rch & Prof#=MDW T 097,Reach-1,3
Up Type=0
Dn Type=3
Dn Slope=0.005
Boundary for River Rch & Prof#=MDW T 097,Reach-1,4
Up Type=0
Dn Type=3
Dn Slope=0.005
Boundary for River Rch & Prof#=MDW T 097,Reach-1,5
Up Type=0
Dn Type=3
Dn Slope=0.005
Boundary for River Rch & Prof#=MDW T 097,Reach-1,6
Up Type=0
Dn Type=3
Dn Slope=0.005
Boundary for River Rch & Prof#=MDW T 097,Reach-1,7
Up Type=0
Dn Type=3
Dn Slope=0.005

--- MDW T 097.g01 (geometry) ---

Geom Title=Existing Conditions

River Reach=MDW T 097,Reach-1
Reach XY= 30
      2278179.00      7138410.00      2278227.09      7138465.79
      2278232.75      7138608.44      2278272.88      7138657.82
      2278285.12      7138712.18      2278326.76      7138765.93
      2278329.52      7139044.78      2278376.73      7139115.94
      2278381.27      7139254.06      2278425.21      7139311.57
      2278480.17      7139493.83      2278557.45      7139627.44
      2278649.53      7139654.58      2278725.39      7139648.75
      2278849.09      7139541.68      2279033.73      7139546.75
      2279459.93      7139657.49      2279552.77      7139748.61
      2279991.74      7139749.59      2280754.76      7139785.73
      2280789.52      7139808.80      2280904.38      7139810.43
      2280927.40      7139798.47      2280934.55      7139707.62
      2281019.30      7139620.77      2281085.04      7139601.82
      2281180.50      7139513.62      2281273.08      7139507.77
      2281330.51      7139463.64      2281379.00      7139460.00

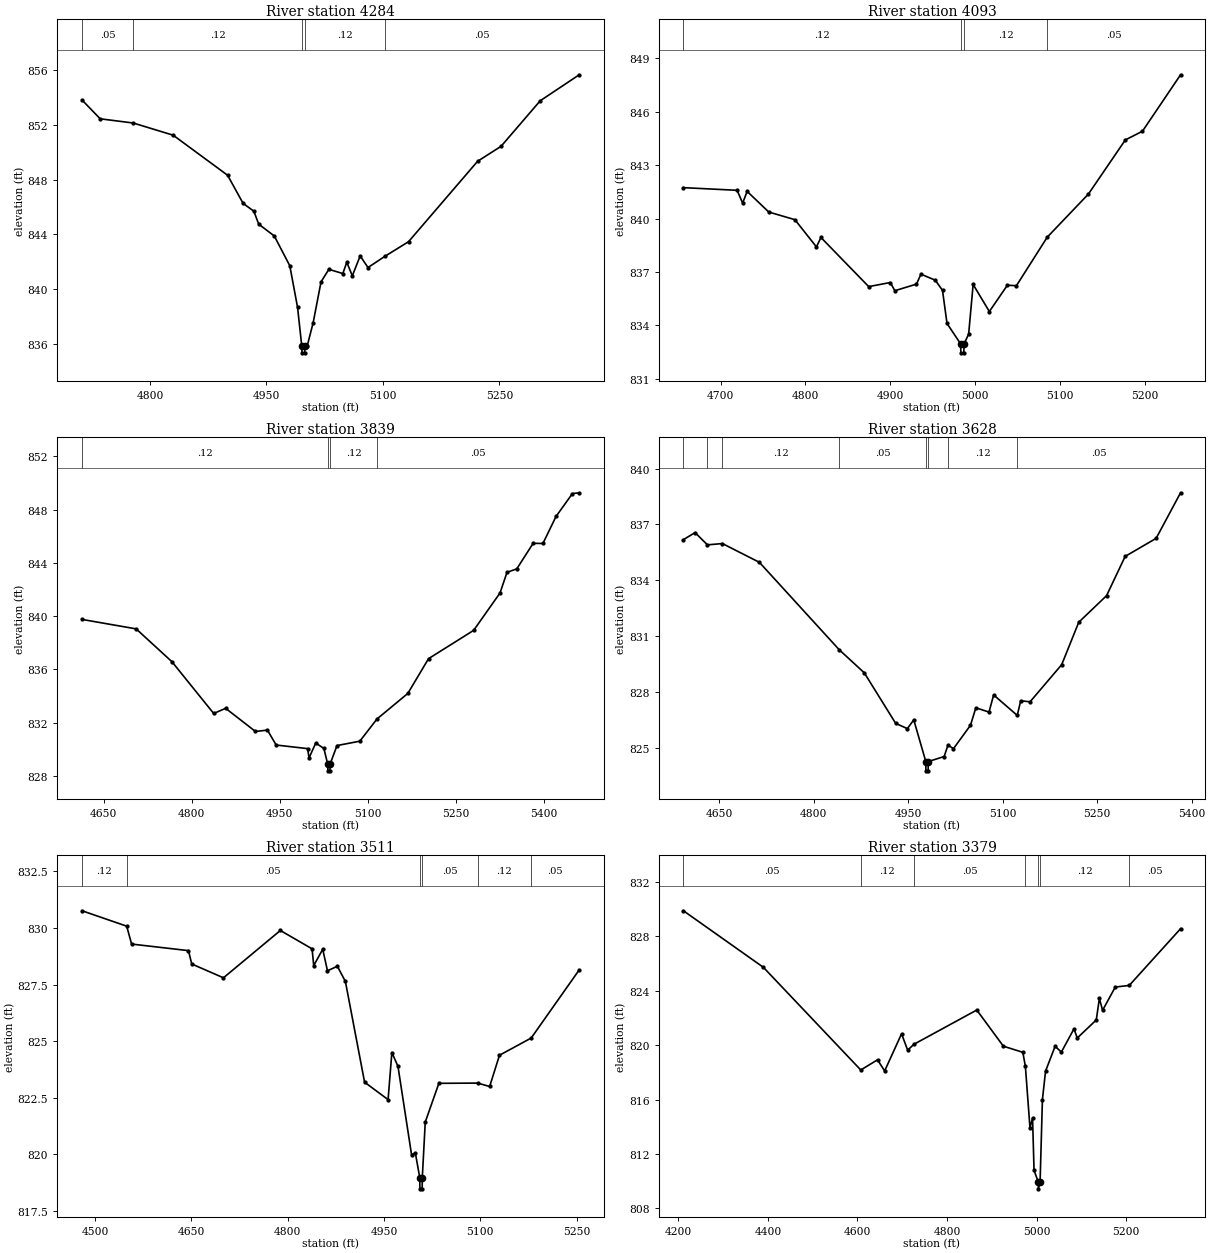
Type RM Length L Ch R = 1,4284,191,191,191
BEGIN DESCRIPTION:
MDW T 097 10.0
END DESCRIPTION:
XS GIS Cut Line= 3
      2277941.85      7138566.24      2278228.77      7138551.56
      2278578.79      7138506.57
#Sta/Elev= 30
  4712.7  853.83  4736.0  852.46  4778.7  852.15  4830.0  851.26  4900.1  848.33
  4920.1  846.27  4933.9  845.70  4940.2  844.75  4960.2  843.89  4980.2  841.71
  4990.2  838.66  4995.6  835.84  4995.9  835.34  4999.4  835.34  4999.6  835.84
  5002.6  835.84  5010.3  837.55  5020.4  840.53  5030.5  841.45  5048.5  841.14
  5053.6  841.97  5060.7  840.97  5070.8  842.43  5080.9  841.58  5103.2  842.42
  5133.1  843.47  5222.0  849.35  5252.3  850.45  5302.7  853.78  5352.9  855.68
#Mann=5,-1,0
  4712.7    0.05       0  4778.7    0.12       0  4995.6    0.07       0
  4999.6    0.12       0  5103.2    0.05       0
Bank Sta=4995.6,4999.6
Exp/Cntr=0.3,0.1

Type RM Length L Ch R = 1,4093,254,254,254
BEGIN DESCRIPTION:
Mapping XS 9f782ac4
END DESCRIPTION:
XS GIS Cut Line= 2
      2277969.42      7138838.90      2278521.23      7138641.65
#Sta/Elev= 30
  4656.2  841.74  4719.5  841.59  4726.0  840.87  4731.3  841.53  4756.8  840.37
  4787.6  839.94  4813.0  838.41  4818.3  838.94  4874.6  836.18  4900.0  836.41
  4905.4  835.95  4930.9  836.32  4936.2  836.88  4953.1  836.54  4961.6  835.97
  4966.9  834.11  4983.0  832.96  4983.2  832.46  4986.7  832.46  4987.0  832.96
  4992.4  833.51  4997.7  836.30  5016.8  834.78  5038.1  836.26  5048.7  836.23
  5085.1  838.96  5133.6  841.38  5177.1  844.42  5197.3  844.91  5242.2  848.08
#Mann=4,-1,0
  4656.2    0.12       0  4983.0    0.07       0  4987.0    0.12       0
  5085.1    0.05       0
Bank Sta=4983,4987
Exp/Cntr=0.3,0.1

Type RM Length L Ch R = 1,3839,211,211,211
BEGIN DESCRIPTION:
MDW T 097 9.0
END DESCRIPTION:
XS GIS Cut Line= 3
      2277948.40      7138896.11      2278328.91      7138965.04
      2278739.40      7138757.22
#Sta/Elev= 30
  4613.3  839.75  4705.4  839.04  4766.4  836.57  4837.5  832.68  4857.8  833.07
  4908.6  831.33  4929.0  831.43  4943.9  830.31  4997.4  830.04  4999.9  829.34
  5011.3  830.46  5025.2  830.05  5031.7  828.87  5032.0  828.37  5035.5  828.37
  5035.7  828.87  5047.5  830.27  5086.4  830.60  5115.7  832.27  5168.2  834.19
  5203.4  836.80  5280.3  838.93  5325.2  841.74  5337.1  843.29  5353.7  843.55
  5381.6  845.47  5398.3  845.46  5420.6  847.49  5448.5  849.21  5460.1  849.27
#Mann=4,-1,0
  4613.3    0.12       0  5031.7    0.07       0  5035.7    0.12       0
  5115.7    0.05       0
Bank Sta=5031.7,5035.7
Exp/Cntr=0.3,0.1

Type RM Length L Ch R = 1,3628,117,117,117
BEGIN DESCRIPTION:
MDW T 097 8.0
END DESCRIPTION:
XS GIS Cut Line= 3
      2277980.93      7139076.22      2278379.00      7139160.00
      2278690.53      7138937.36
#Sta/Elev= 30
  4592.8  836.18  4611.3  836.56  4630.9  835.90  4654.7  835.97  4713.5  834.96
  4840.3  830.26  4880.1  829.02  4930.0  826.30  4948.5  826.02  4958.7  826.49
  4977.8  824.25  4978.0  823.75  4981.5  823.75  4981.8  824.25  5007.0  824.52
  5013.1  825.14  5021.7  824.94  5048.8  826.20  5057.3  827.14  5078.2  826.91
  5085.6  827.83  5123.1  826.73  5128.6  827.52  5143.4  827.46  5193.7  829.46
  5220.8  831.74  5265.0  833.17  5294.5  835.28  5343.7  836.25  5382.5  838.70
#Mann=8,-1,0
  4592.8    0.12       0  4630.9    0.05       0  4654.7    0.12       0
  4840.3    0.05       0  4977.8   0.033       0  4981.8    0.05       0
  5013.1    0.12       0  5123.1    0.05       0
Bank Sta=4977.8,4981.8
Exp/Cntr=0.3,0.1

Type RM Length L Ch R = 1,3511,132,132,132
BEGIN DESCRIPTION:
Mapping XS a9f124fa
END DESCRIPTION:
XS GIS Cut Line= 3
      2277904.07      7139279.81      2278259.04      7139355.95
      2278608.13      7139138.55
#Sta/Elev= 30
  4479.7  830.76  4549.2  830.08  4556.8  829.29  4645.4  829.00  4650.5  828.41
  4699.9  827.80  4788.5  829.89  4837.9  829.08  4840.5  828.34  4854.5  829.06
  4861.9  828.11  4877.3  828.31  4889.8  827.64  4919.7  823.19  4956.3  822.42
  4962.2  824.50  4971.7  823.89  4992.9  819.98  4998.8  820.06  5005.6  818.98
  5005.9  818.48  5009.4  818.48  5009.6  818.98  5014.2  821.43  5035.4  823.14
  5095.8  823.15  5114.5  823.00  5129.8  824.38  5179.2  825.14  5254.0  828.15
#Mann=6,-1,0
  4479.7    0.12       0  4549.2    0.05       0  5005.6   0.033       0
  5009.6    0.05       0  5095.8    0.12       0  5179.2    0.05       0
Bank Sta=5005.6,5009.6
Exp/Cntr=0.3,0.1

Type RM Length L Ch R = 1,3379,321,321,321
BEGIN DESCRIPTION:
MDW T 097 7.0
END DESCRIPTION:
XS GIS Cut Line= 3
      2277762.15      7139774.33      2278446.15      7139391.77
      2278679.94      7139164.87
#Sta/Elev= 30
  4211.6  829.88  4390.1  825.72  4607.4  818.17  4644.8  818.92  4660.7  818.10
  4698.4  820.83  4712.1  819.63  4725.9  820.06  4866.3  822.58  4925.7  819.92
  4969.1  819.47  4974.8  818.43  4985.0  813.93  4990.8  814.63  4994.1  810.79
  5003.6  809.93  5003.9  809.43  5007.6  809.93  5012.8  815.99  5019.8  818.09
  5041.1  819.91  5055.1  819.49  5083.3  821.20  5090.5  820.52  5133.0  821.85
  5139.9  823.43  5147.1  822.56  5175.4  824.27  5206.6  824.39  5321.1  828.56
#Mann=7,-1,0
  4211.6    0.05       0  4607.4    0.12       0  4725.9    0.05       0
  4974.8    0.12       0  5003.6    0.07       0  5007.6    0.12       0
  5206.6    0.05       0
Bank Sta=5003.6,5007.6
Exp/Cntr=0.3,0.1

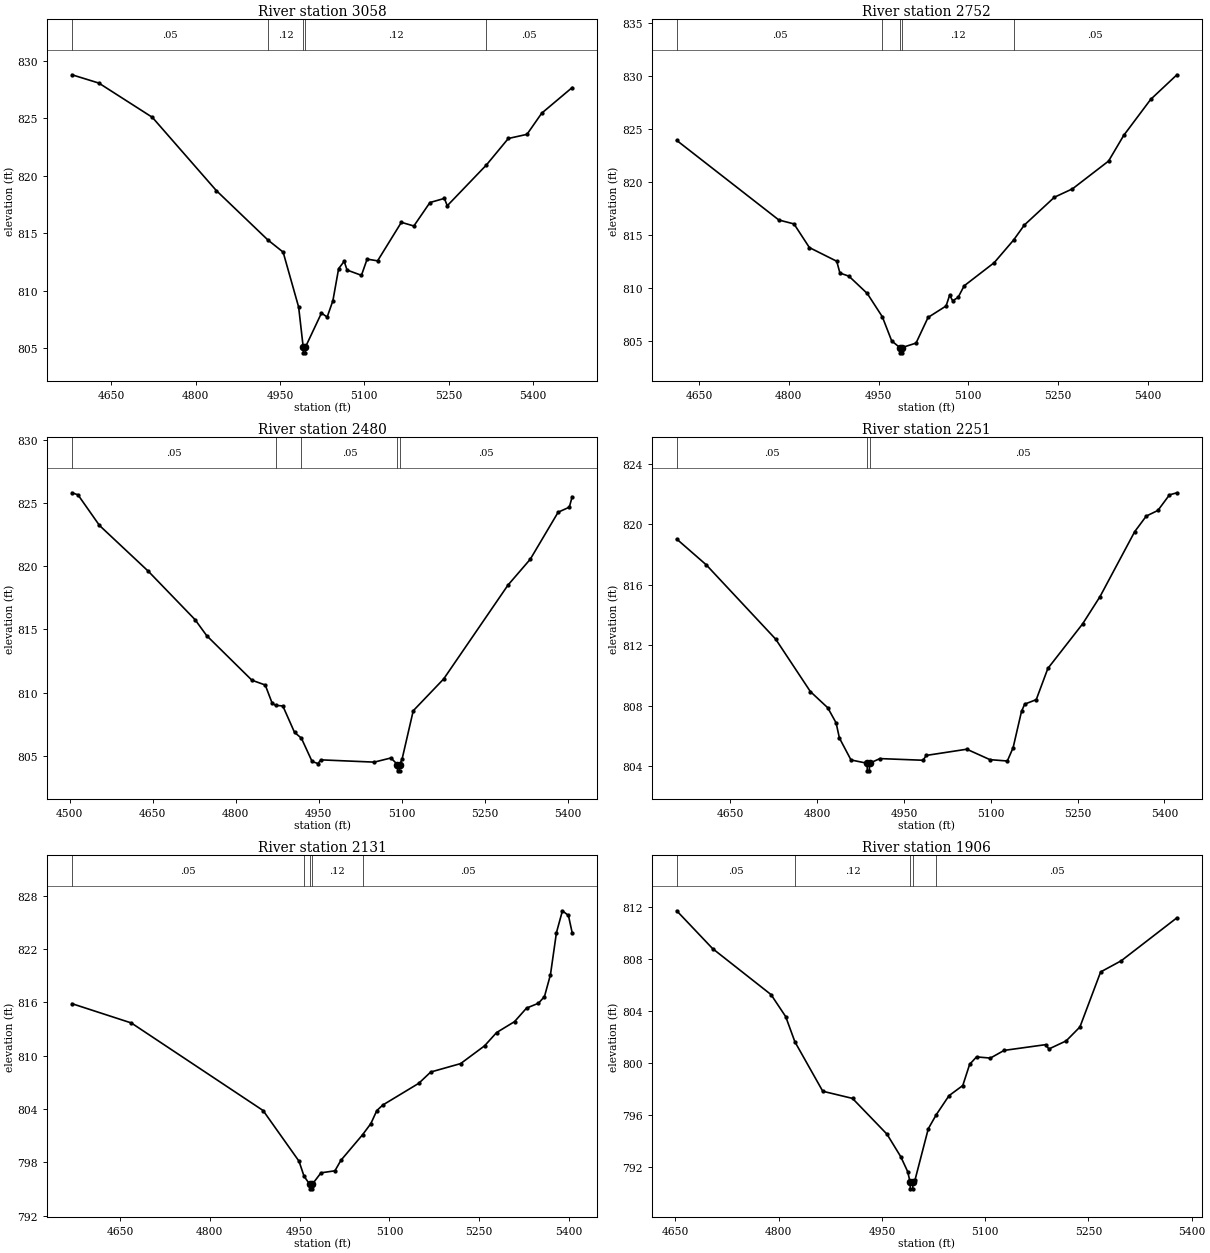
Type RM Length L Ch R = 1,3058,306,306,306
BEGIN DESCRIPTION:
MDW T 097 6.0
END DESCRIPTION:
XS GIS Cut Line= 2
      2278539.52      7140057.02      2278693.21      7139180.80
#Sta/Elev= 30
  4580.2  828.78  4627.9  828.06  4723.1  825.08  4836.9  818.71  4928.5  814.42
  4955.7  813.36  4983.3  808.58  4991.4  805.10  4991.7  804.60  4995.2  804.60
  4995.4  805.10  5023.9  808.06  5034.0  807.71  5044.2  809.13  5054.4  811.92
  5064.3  812.56  5069.4  811.80  5095.0  811.34  5105.1  812.75  5123.7  812.60
  5166.0  815.95  5188.2  815.63  5216.8  817.67  5242.5  818.03  5247.6  817.39
  5317.3  820.94  5356.2  823.24  5389.4  823.60  5415.6  825.44  5469.8  827.67
#Mann=5,-1,0
  4580.2    0.05       0  4928.5    0.12       0  4991.4    0.07       0
  4995.4    0.12       0  5317.3    0.05       0
Bank Sta=4991.4,4995.4
Exp/Cntr=0.3,0.1

Type RM Length L Ch R = 1,2752,272,272,272
BEGIN DESCRIPTION:
MDW T 097 5.0
END DESCRIPTION:
XS GIS Cut Line= 3
      2278800.54      7139922.23      2278877.20      7139538.47
      2278923.17      7139096.39
#Sta/Elev= 30
  4612.7  823.94  4783.4  816.43  4808.7  816.06  4834.4  813.83  4880.1  812.54
  4885.4  811.43  4900.5  811.13  4931.1  809.50  4956.3  807.30  4971.9  805.03
  4985.4  804.40  4985.7  803.90  4989.2  803.90  4989.4  804.40  5012.6  804.82
  5032.7  807.24  5062.8  808.32  5068.8  809.35  5073.8  808.81  5082.9  809.13
  5093.0  810.22  5143.3  812.41  5175.6  814.54  5193.5  815.95  5243.8  818.58
  5274.0  819.37  5334.3  821.99  5359.6  824.41  5404.7  827.81  5448.5  830.13
#Mann=5,-1,0
  4612.7    0.05       0  4956.3    0.12       0  4985.4    0.07       0
  4989.4    0.12       0  5175.6    0.05       0
Bank Sta=4985.4,4989.4
Exp/Cntr=0.3,0.1

Type RM Length L Ch R = 1,2480,229,229,229
BEGIN DESCRIPTION:
MDW T 097 4.0
END DESCRIPTION:
XS GIS Cut Line= 3
      2278987.18      7140050.23      2279139.05      7139610.12
      2279192.23      7139174.83
#Sta/Elev= 30
  4504.2  825.83  4515.0  825.67  4553.9  823.24  4642.0  819.62  4726.6  815.78
  4747.7  814.51  4829.4  810.98  4853.5  810.60  4865.9  809.17  4872.1  808.99
  4885.3  808.94  4906.4  806.85  4918.8  806.39  4938.2  804.54  4948.7  804.38
  4954.2  804.67  5050.5  804.49  5080.7  804.82  5092.4  804.30  5092.7  803.80
  5096.2  803.80  5096.4  804.30  5100.9  804.74  5121.0  808.56  5176.0  811.08
  5292.3  818.52  5332.6  820.57  5382.9  824.29  5403.1  824.69  5408.3  825.52
#Mann=5,-1,0
  4504.2    0.05       0  4872.1    0.12       0  4918.8    0.05       0
  5092.4   0.033       0  5096.4    0.05       0
Bank Sta=5092.4,5096.4
Exp/Cntr=0.3,0.1

Type RM Length L Ch R = 1,2251,120,120,120
BEGIN DESCRIPTION:
MDW T 097 3.0
END DESCRIPTION:
XS GIS Cut Line= 3
      2279344.17      7140070.88      2279359.40      7139645.51
      2279371.30      7139207.11
#Sta/Elev= 30
  4557.5  819.02  4608.4  817.32  4728.5  812.40  4788.5  808.93  4818.5  807.86
  4832.9  806.86  4838.6  805.86  4858.6  804.41  4886.6  804.19  4886.8  803.69
  4890.3  803.69  4890.6  804.19  4908.6  804.50  4983.1  804.39  4988.7  804.71
  5058.7  805.12  5098.7  804.43  5128.7  804.34  5138.7  805.22  5153.2  807.62
  5158.7  808.10  5178.7  808.40  5198.7  810.46  5258.8  813.41  5288.8  815.21
  5348.8  819.51  5368.8  820.54  5388.8  820.91  5408.8  821.94  5421.7  822.08
#Mann=3,-1,0
  4557.5    0.05       0  4886.6   0.033       0  4890.6    0.05       0
Bank Sta=4886.6,4890.6
Exp/Cntr=0.3,0.1

Type RM Length L Ch R = 1,2131,225,225,225
BEGIN DESCRIPTION:
MDW T 097 2.0
END DESCRIPTION:
XS GIS Cut Line= 3
      2279461.36      7140099.07      2279471.80      7139681.51
      2279466.80      7139263.73
#Sta/Elev= 30
  4569.8  815.86  4668.9  813.69  4889.0  803.84  4949.0  798.14  4957.4  796.45
  4967.0  795.53  4967.2  795.03  4970.7  795.03  4971.0  795.53  4985.7  796.83
  5009.0  797.06  5019.0  798.24  5055.2  801.12  5069.0  802.37  5079.0  803.84
  5089.0  804.46  5149.0  806.90  5169.0  808.17  5219.0  809.12  5259.0  811.12
  5279.0  812.61  5309.0  813.84  5329.0  815.36  5349.0  815.91  5359.0  816.66
  5369.0  819.12  5379.0  823.85  5389.0  826.31  5399.0  825.78  5405.3  823.84
#Mann=5,-1,0
  4569.8    0.05       0  4957.4    0.12       0  4967.0    0.07       0
  4971.0    0.12       0  5055.2    0.05       0
Bank Sta=4967,4971
Exp/Cntr=0.3,0.1

Type RM Length L Ch R = 1,1906,227,227,227
BEGIN DESCRIPTION:
Mapping XS 2d3fe779
END DESCRIPTION:
XS GIS Cut Line= 3
      2279518.21      7140033.03      2279670.29      7139878.66
      2279644.67      7139369.30
#Sta/Elev= 30
  4651.8  811.68  4704.0  808.77  4788.8  805.24  4810.1  803.55  4823.5  801.61
  4864.0  797.81  4907.2  797.26  4957.3  794.51  4977.3  792.78  4987.3  791.64
  4991.0  790.81  4991.2  790.31  4994.7  790.31  4995.0  790.81  4998.0  790.99
  5017.3  794.93  5028.8  796.00  5047.4  797.47  5067.4  798.25  5077.4  799.88
  5087.4  800.45  5107.5  800.36  5127.5  800.95  5187.6  801.39  5192.6  801.06
  5217.6  801.68  5237.6  802.75  5267.7  806.98  5297.7  807.84  5378.5  811.14
#Mann=5,-1,0
  4651.8    0.05       0  4823.5    0.12       0  4991.0    0.07       0
  4995.0    0.12       0  5028.8    0.05       0
Bank Sta=4991,4995
Exp/Cntr=0.3,0.1

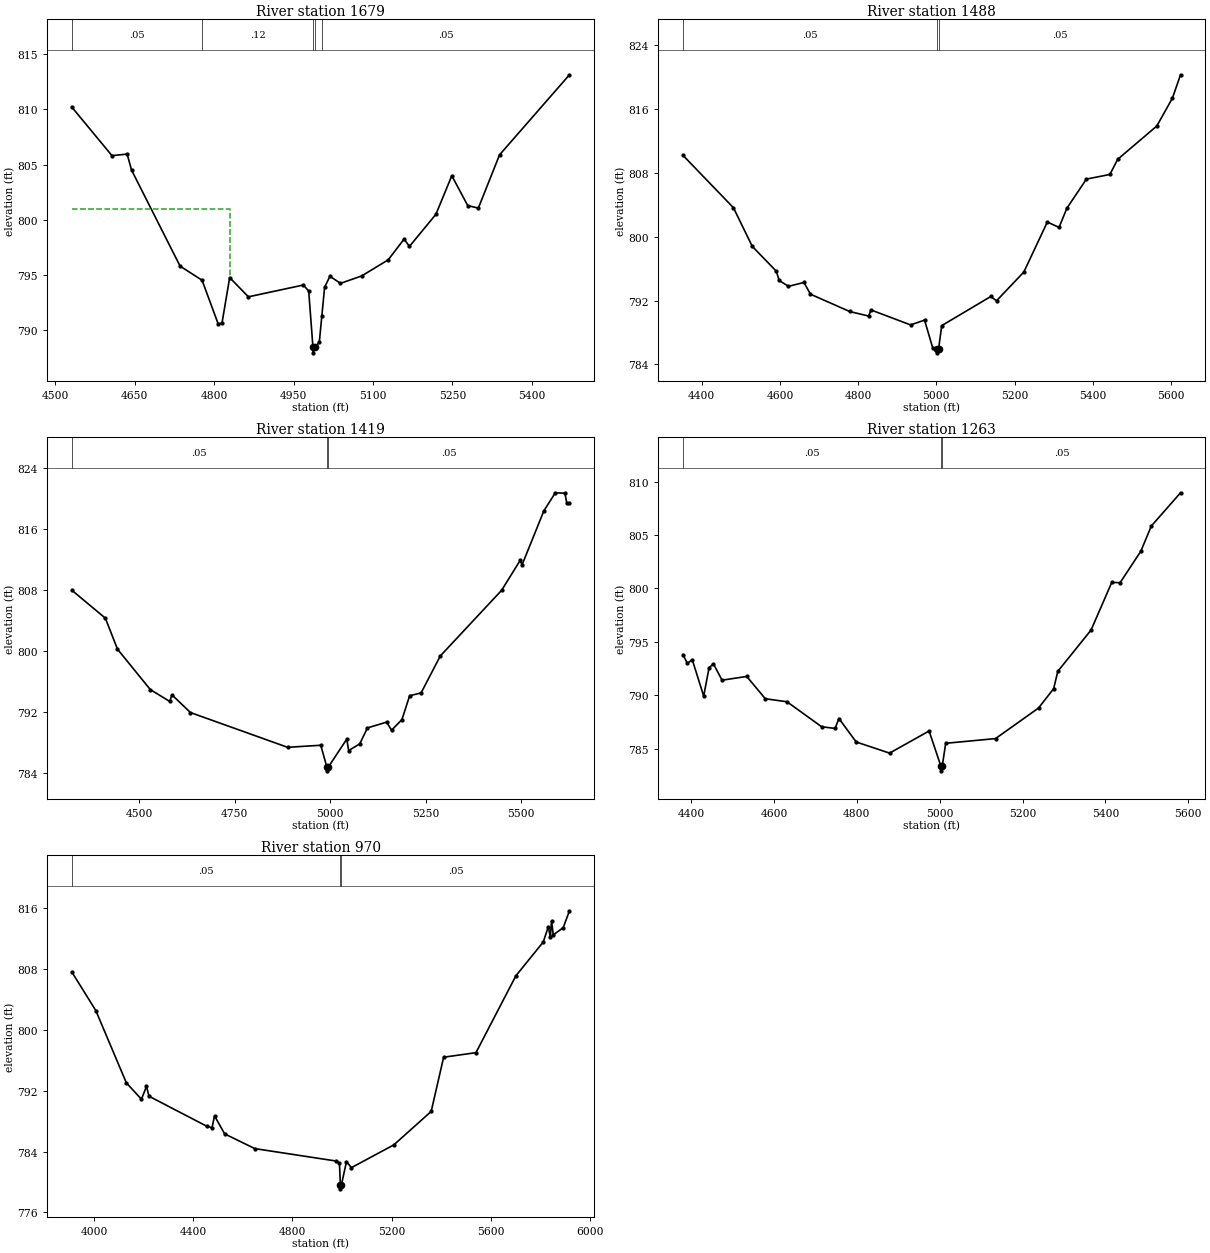
Type RM Length L Ch R = 1,1679,191,191,191
BEGIN DESCRIPTION:
Mapping XS 74b4fa69
END DESCRIPTION:
XS GIS Cut Line= 3
      2279548.62      7140046.32      2279891.58      7139787.30
      2279874.70      7139278.06
#Sta/Elev= 30
  4531.5  810.20  4607.2  805.81  4635.9  805.95  4644.2  804.50  4735.8  795.81
  4777.3  794.53  4807.7  790.58  4814.9  790.65  4829.4  794.77  4864.8  793.03
  4968.6  794.10  4978.6  793.55  4986.6  788.46  4986.8  787.96  4990.6  788.46
  4998.6  788.93  5003.4  791.31  5008.6  793.89  5018.6  794.89  5038.6  794.25
  5078.6  794.92  5128.7  796.38  5158.7  798.26  5168.7  797.59  5218.7  800.50
  5248.7  803.99  5278.8  801.29  5298.8  801.06  5338.8  805.88  5470.8  813.13
#Mann=5,-1,0
  4531.5    0.05       0  4777.3    0.12       0  4986.6    0.05       0
  4990.6    0.12       0  5003.4    0.05       0
#XS Ineff=2,0
    0.00 4830.00  801.02               0
Permanent Ineff=
       F       F
Bank Sta=4986.6,4990.6
Exp/Cntr=0.3,0.1

Type RM Length L Ch R = 1,1488,69,69,69
BEGIN DESCRIPTION:
MDW T 097 1.0
END DESCRIPTION:
XS GIS Cut Line= 4
      2279547.33      7140064.67      2279984.82      7139908.76
      2280081.71      7139759.76      2280091.61      7139129.31
#Sta/Elev= 30
  4351.9  810.20  4481.1  803.63  4529.2  798.79  4590.9  795.67  4597.8  794.53
  4621.7  793.78  4661.5  794.27  4678.0  792.80  4778.3  790.63  4826.8  790.06
  4833.0  790.82  4934.1  788.95  4969.9  789.55  4990.9  786.04  5001.8  785.95
  5002.1  785.45  5005.8  785.95  5013.8  788.86  5139.3  792.51  5153.9  791.97
  5223.9  795.58  5283.9  801.84  5313.9  801.16  5333.9  803.57  5383.9  807.22
  5443.9  807.80  5463.9  809.70  5563.9  813.87  5603.9  817.37  5624.6  820.29
#Mann=3,-1,0
  4351.9    0.05       0  5001.8   0.033       0  5005.8    0.05       0
Bank Sta=5001.8,5005.8
Exp/Cntr=0.3,0.1

Type RM Length L Ch R = 1,1419,156,156,156
BEGIN DESCRIPTION:
MDW T 097 0.9
END DESCRIPTION:
XS GIS Cut Line= 4
      2279586.38      7140062.42      2280095.82      7139881.18
      2280149.62      7139762.53      2280205.03      7139133.06
#Sta/Elev= 30
  4323.5  807.95  4411.2  804.29  4443.0  800.23  4528.9  794.94  4580.0  793.38
  4585.3  794.26  4634.1  791.93  4888.5  787.38  4975.3  787.65  4991.1  784.80
  4991.4  784.30  4995.1  784.80  5043.3  788.45  5048.3  786.96  5077.3  787.83
  5097.4  789.92  5147.6  790.68  5160.6  789.62  5187.8  791.01  5207.9  794.13
  5238.0  794.51  5288.2  799.34  5448.8  807.94  5497.3  811.85  5502.3  811.27
  5559.2  818.32  5589.3  820.71  5614.5  820.65  5619.5  819.34  5626.4  819.40
#Mann=3,-1,0
  4323.5    0.05       0  4991.1   0.033       0  4995.1    0.05       0
Bank Sta=4991.1,4995.1
Exp/Cntr=0.3,0.1

Type RM Length L Ch R = 1,1263,293,293,293
BEGIN DESCRIPTION:
Mapping XS 656171f8
END DESCRIPTION:
XS GIS Cut Line= 3
      2279808.57      7140020.26      2280298.84      7139871.77
      2280349.13      7139184.48
#Sta/Elev= 30
  4380.1  793.78  4391.0  792.97  4402.5  793.33  4430.2  789.91  4443.2  792.57
  4453.7  792.93  4474.6  791.40  4534.1  791.75  4579.1  789.66  4631.3  789.38
  4714.9  787.04  4747.4  786.88  4756.7  787.81  4798.5  785.61  4879.0  784.57
  4974.4  786.64  5002.4  783.41  5002.7  782.91  5006.4  783.41  5014.5  785.49
  5134.8  785.93  5238.6  788.79  5275.2  790.61  5285.2  792.23  5365.4  796.09
  5415.5  800.56  5435.6  800.53  5485.7  803.48  5511.0  805.84  5581.5  808.95
#Mann=3,-1,0
  4380.1    0.05       0  5002.4   0.033       0  5006.4    0.05       0
Bank Sta=5002.4,5006.4
Exp/Cntr=0.3,0.1

Type RM Length L Ch R = 1,970,0,0,0
BEGIN DESCRIPTION:
MDW T 097 0.5
END DESCRIPTION:
XS GIS Cut Line= 4
      2279602.94      7140073.28      2280542.38      7139899.80
      2280598.95      7139779.40      2280506.56      7138865.01
#Sta/Elev= 30
  3910.5  807.61  4007.1  802.55  4130.2  793.05  4191.2  790.88  4211.6  792.58
  4221.7  791.28  4456.2  787.31  4476.0  787.14  4486.1  788.70  4526.8  786.33
  4648.8  784.39  4976.1  782.76  4989.9  782.53  4993.8  779.60  4994.0  779.10
  4997.8  779.60  5018.3  782.67  5038.5  781.89  5209.3  784.88  5360.1  789.28
  5410.3  796.41  5540.7  797.01  5701.8  807.12  5812.4  811.57  5832.5  813.57
  5840.7  812.20  5845.7  814.32  5852.6  812.50  5892.8  813.45  5917.9  815.67
#Mann=3,-1,0
  3910.5    0.05       0  4993.8   0.033       0  4997.8    0.05       0
Bank Sta=4993.8,4997.8
Exp/Cntr=0.3,0.1

Chan Stop Cuts=-1