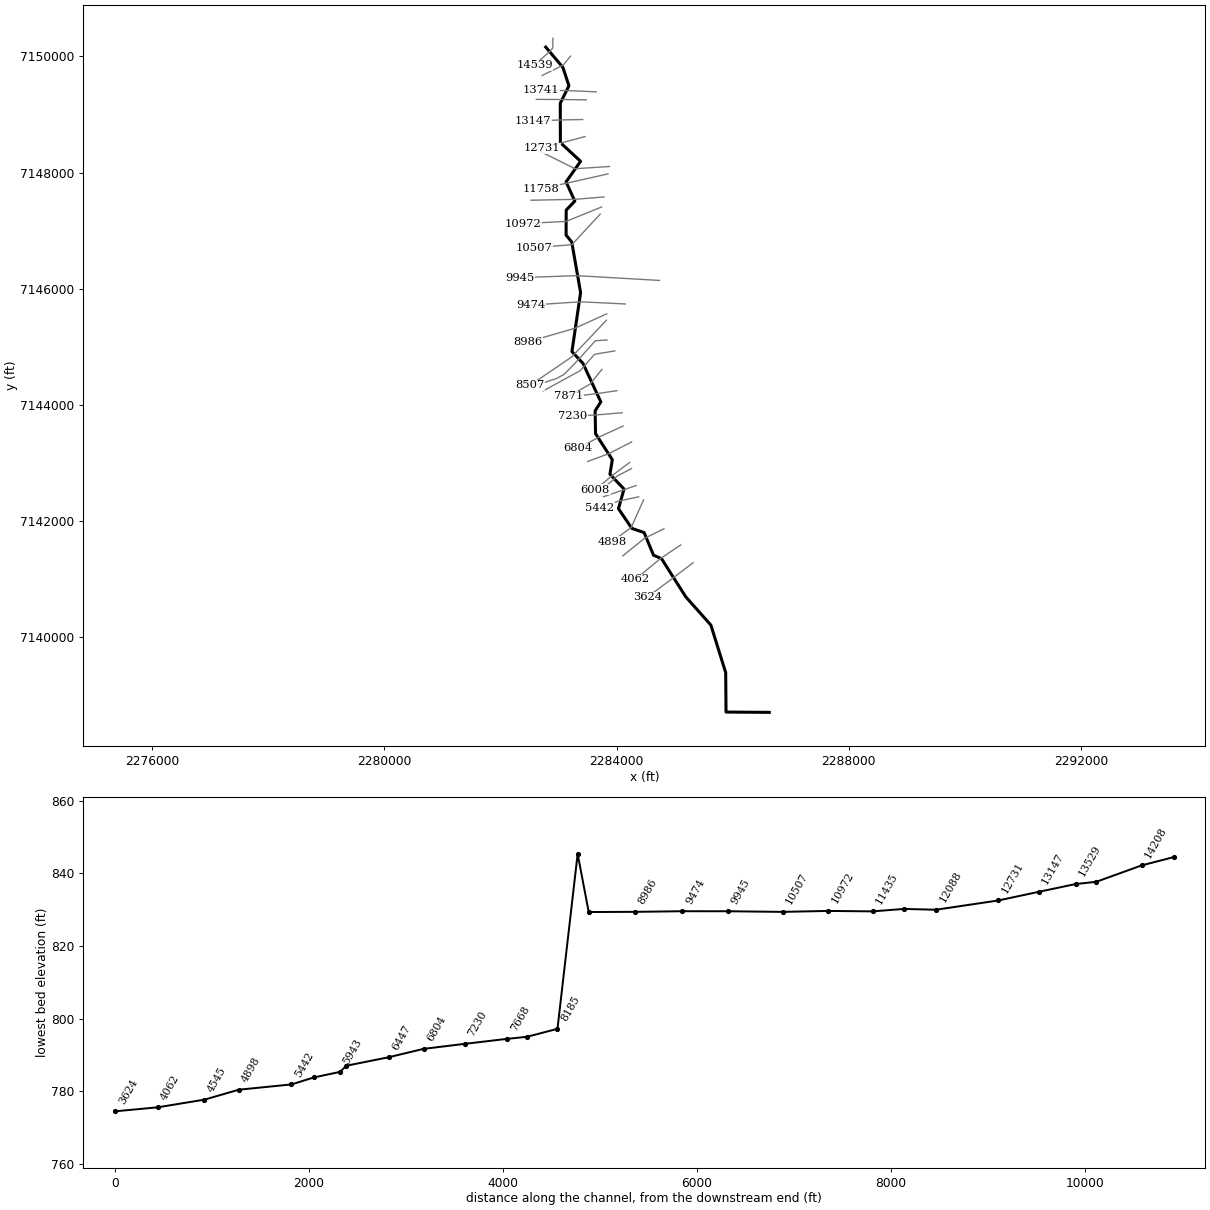
--- MDW T 098.prj (project) ---

Proj Title=MDW T 098 Base Level Engineering
Current Plan=p01
Default Exp/Contr=0.3,0.1
English Units
Geom File=g01
Flow File=f01
Plan File=p01
BEGIN DESCRIPTION:
MDW T 098
END DESCRIPTION:

--- MDW T 098.p01 (plan) ---

Plan Title=Multiple Run
Short Identifier=Multiple
Geom File=g01
Flow File=f01
Subcritical Flow
K Sum by GR= 0
Std Step Tol= 0.01
Critical Tol= 0.01
Num of Std Step Trials= 20
Max Error Tol= 0.3
Flow Tol Ratio= 0.001
Split Flow NTrial= 30
Split Flow Tol= 0.02
Split Flow Ratio= 0.02
Log Output Level= 0
Friction Slope Method= 1
Unsteady Friction Slope Method= 2
Unsteady Bridges Friction Slope Method= 1
Parabolic Critical Depth
Global Vel Dist=  1 , 1 , 1
Global Log Level= 0
CheckData=True
Encroach Param= -1, 0, 0, 0
BEGIN DESCRIPTION:
Multiple Run
END DESCRIPTION:

--- MDW T 098.f01 (steady flow) ---

Flow Title=Multiple
Number of Profiles=7
Profile Names=10-year,25-year,50-year,1pct_min,100-year,1pct_plu,500-year
River Rch & RM= MDW T 098,Reach-1,14539
     735    1024    1267     779    1555    3102    2344
River Rch & RM= MDW T 098,Reach-1,12088
    1137    1616    2027    1261    2515    5019    3883
River Rch & RM= MDW T 098,Reach-1,4545
    1307    1868    2351    1466    2925    5837    4542
Boundary for River Rch & Prof#=MDW T 098,Reach-1,1
Up Type=0
Dn Type=3
Dn Slope=0.005
Boundary for River Rch & Prof#=MDW T 098,Reach-1,2
Up Type=0
Dn Type=3
Dn Slope=0.005
Boundary for River Rch & Prof#=MDW T 098,Reach-1,3
Up Type=0
Dn Type=3
Dn Slope=0.005
Boundary for River Rch & Prof#=MDW T 098,Reach-1,4
Up Type=0
Dn Type=3
Dn Slope=0.005
Boundary for River Rch & Prof#=MDW T 098,Reach-1,5
Up Type=0
Dn Type=3
Dn Slope=0.005
Boundary for River Rch & Prof#=MDW T 098,Reach-1,6
Up Type=0
Dn Type=3
Dn Slope=0.005
Boundary for River Rch & Prof#=MDW T 098,Reach-1,7
Up Type=0
Dn Type=3
Dn Slope=0.005

--- MDW T 098.g01 (geometry) ---

Geom Title=Existing Conditions

River Reach=MDW T 098,Reach-1
Reach XY= 30
      2282779.00      7150160.00      2283073.46      7149812.42
      2283178.63      7149494.72      2283029.38      7149194.73
      2283031.06      7148515.85      2283379.11      7148194.64
      2283128.56      7147839.97      2283279.86      7147509.96
      2283130.98      7147354.33      2283129.25      7146925.22
      2283226.93      7146804.14      2283379.20      7145935.08
      2283230.05      7144920.43      2283419.70      7144716.67
      2283727.24      7144053.88      2283629.61      7143899.38
      2283636.81      7143506.59      2283925.67      7143058.31
      2283884.47      7142807.55      2284127.39      7142553.97
      2284031.23      7142215.93      2284262.21      7141876.45
      2284473.82      7141804.59      2284634.58      7141415.58
      2284773.75      7141354.55      2285189.62      7140699.95
      2285623.16      7140212.29      2285878.47      7139393.86
      2285884.17      7138715.41      2286629.00      7138710.00

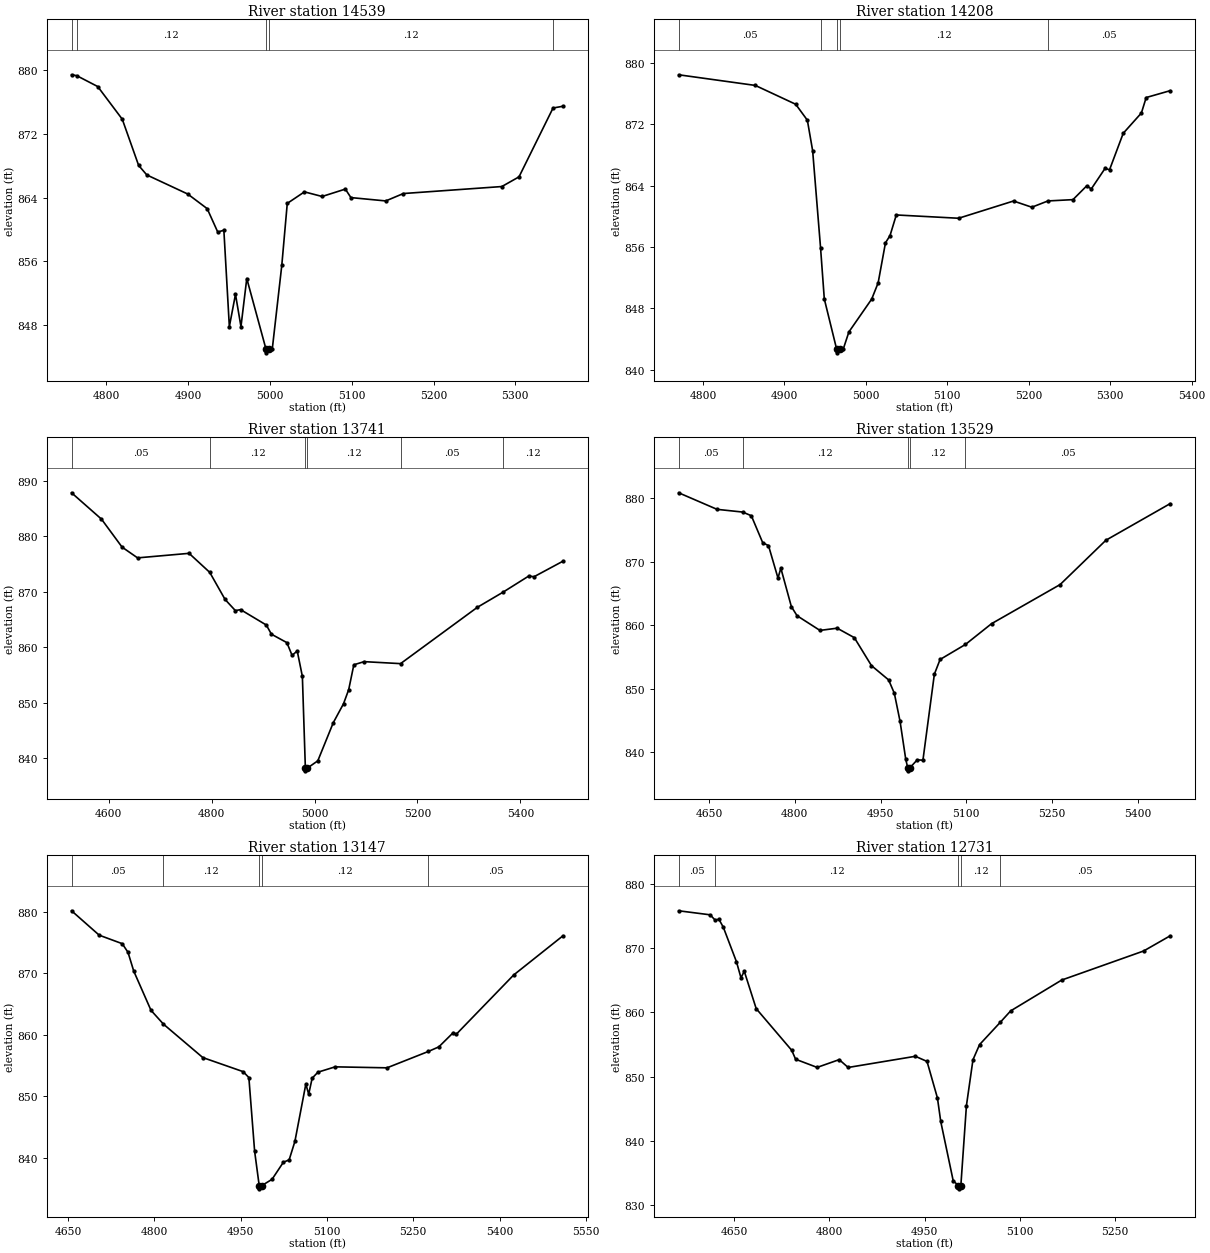
Type RM Length L Ch R = 1,14539,331,331,331
BEGIN DESCRIPTION:
MDW T 098 32.0
END DESCRIPTION:
XS GIS Cut Line= 4
      2282902.32      7150311.96      2282901.16      7150146.16
      2282850.14      7150088.89      2282584.17      7149848.96
#Sta/Elev= 30
  4757.5  879.44  4763.8  879.33  4789.5  877.96  4819.5  873.85  4839.5  868.04
  4849.5  866.84  4899.5  864.44  4923.3  862.60  4936.2  859.66  4943.7  859.88
  4950.4  847.76  4957.9  851.82  4964.6  847.76  4971.7  853.81  4995.1  844.96
  4995.3  844.46  4999.1  844.96  5002.9  844.96  5014.5  855.46  5021.2  863.26
  5042.2  864.71  5063.8  864.13  5092.2  865.06  5099.0  863.99  5141.6  863.57
  5163.1  864.50  5283.5  865.38  5304.5  866.60  5346.1  875.26  5358.2  875.48
#Mann=5,-1,0
  4757.5    0.05       0  4763.8    0.12       0  4995.1    0.07       0
  4999.1    0.12       0  5346.1    0.05       0
Bank Sta=4995.1,4999.1
Exp/Cntr=0.3,0.1

Type RM Length L Ch R = 1,14208,467,467,467
BEGIN DESCRIPTION:
MDW T 098 31.0
END DESCRIPTION:
XS GIS Cut Line= 3
      2283205.72      7150005.08      2283080.67      7149851.02
      2282717.44      7149672.16
#Sta/Elev= 30
  4770.1  878.48  4864.2  877.09  4913.8  874.63  4928.1  872.55  4934.6  868.57
  4944.3  855.90  4948.9  849.22  4964.0  842.68  4964.2  842.18  4968.0  842.68
  4972.2  842.68  4979.1  844.91  5007.1  849.20  5015.0  851.31  5024.0  856.54
  5029.6  857.49  5037.3  860.18  5113.8  859.75  5181.2  862.00  5203.7  861.19
  5223.5  862.01  5254.2  862.18  5271.1  863.98  5276.7  863.58  5293.6  866.26
  5299.1  866.08  5315.9  870.84  5338.2  873.49  5344.1  875.51  5373.4  876.40
#Mann=5,-1,0
  4770.1    0.05       0  4944.3    0.12       0  4964.0    0.07       0
  4968.0    0.12       0  5223.5    0.05       0
Bank Sta=4964,4968
Exp/Cntr=0.3,0.1

Type RM Length L Ch R = 1,13741,212,212,212
BEGIN DESCRIPTION:
MDW T 098 30.0
END DESCRIPTION:
XS GIS Cut Line= 3
      2283647.13      7149390.03      2283188.37      7149410.40
      2282692.69      7149420.39
#Sta/Elev= 30
  4527.7  887.86  4585.9  883.10  4625.9  878.05  4656.0  876.11  4756.1  876.93
  4796.3  873.49  4826.1  868.60  4846.1  866.59  4856.2  866.77  4906.2  863.99
  4916.2  862.33  4946.2  860.81  4956.3  858.51  4966.3  859.31  4976.3  854.71
  4982.1  838.17  4982.3  837.67  4986.1  838.17  5006.3  839.48  5036.3  846.35
  5056.3  849.79  5066.3  852.32  5076.3  856.81  5096.3  857.38  5167.1  857.02
  5316.4  867.19  5365.6  869.88  5416.4  872.84  5426.4  872.70  5482.7  875.51
#Mann=6,-1,0
  4527.7    0.05       0  4796.3    0.12       0  4982.1    0.07       0
  4986.1    0.12       0  5167.1    0.05       0  5365.6    0.12       0
Bank Sta=4982.1,4986.1
Exp/Cntr=0.3,0.1

Type RM Length L Ch R = 1,13529,382,382,382
BEGIN DESCRIPTION:
MDW T 098 29.0
END DESCRIPTION:
XS GIS Cut Line= 3
      2283476.13      7149252.88      2283073.16      7149257.75
      2282616.77      7149260.70
#Sta/Elev= 30
  4597.0  880.88  4664.1  878.27  4709.0  877.84  4724.1  877.26  4744.1  872.99
  4754.1  872.56  4770.7  867.44  4775.7  869.00  4794.1  862.94  4804.1  861.50
  4844.1  859.19  4874.2  859.54  4904.2  858.05  4934.2  853.64  4964.2  851.39
  4974.2  849.28  4984.2  844.86  4994.2  838.85  4997.6  837.56  4997.8  837.06
  5001.6  837.56  5014.2  838.79  5024.2  838.74  5044.2  852.29  5054.2  854.61
  5098.6  856.98  5144.2  860.25  5264.2  866.42  5344.2  873.40  5456.4  879.16
#Mann=5,-1,0
  4597.0    0.05       0  4709.0    0.12       0  4997.6    0.07       0
  5001.6    0.12       0  5098.6    0.05       0
Bank Sta=4997.6,5001.6
Exp/Cntr=0.3,0.1

Type RM Length L Ch R = 1,13147,416,416,416
BEGIN DESCRIPTION:
MDW T 098 28.0
END DESCRIPTION:
XS GIS Cut Line= 3
      2283417.11      7148913.47      2283073.26      7148907.67
      2282563.46      7148887.45
#Sta/Elev= 30
  4656.1  880.13  4704.2  876.16  4744.2  874.78  4754.2  873.38  4764.2  870.32
  4794.2  863.94  4815.9  861.69  4884.2  856.26  4954.3  853.97  4964.3  853.01
  4974.3  841.03  4982.3  835.41  4982.5  834.91  4986.3  835.41  5004.6  836.46
  5024.3  839.24  5034.3  839.62  5044.3  842.62  5063.3  851.94  5068.3  850.31
  5074.3  852.90  5084.3  853.88  5114.3  854.75  5204.4  854.59  5276.2  857.25
  5294.5  858.00  5319.6  860.32  5324.6  860.03  5424.6  869.69  5510.2  876.06
#Mann=5,-1,0
  4656.1    0.05       0  4815.9    0.12       0  4982.3    0.07       0
  4986.3    0.12       0  5276.2    0.05       0
Bank Sta=4982.3,4986.3
Exp/Cntr=0.3,0.1

Type RM Length L Ch R = 1,12731,643,643,643
BEGIN DESCRIPTION:
MDW T 098 27.0
END DESCRIPTION:
XS GIS Cut Line= 3
      2283457.01      7148620.94      2283034.46      7148507.55
      2282708.79      7148421.30
#Sta/Elev= 30
  4562.5  875.84  4612.2  875.21  4620.1  874.37  4625.9  874.53  4632.9  873.27
  4653.6  867.90  4660.7  865.40  4665.9  866.42  4684.7  860.60  4740.7  854.11
  4746.8  852.72  4780.7  851.45  4815.5  852.66  4829.6  851.44  4935.5  853.18
  4953.9  852.38  4970.3  846.69  4975.5  843.03  4995.1  833.82  5003.2  833.04
  5003.5  832.54  5007.2  833.04  5016.0  845.50  5026.3  852.64  5036.7  855.00
  5069.5  858.49  5085.7  860.25  5166.1  865.05  5295.3  869.58  5336.9  871.93
#Mann=5,-1,0
  4562.5    0.05       0  4620.1    0.12       0  5003.2    0.07       0
  5007.2    0.12       0  5069.5    0.05       0
Bank Sta=5003.2,5007.2
Exp/Cntr=0.3,0.1

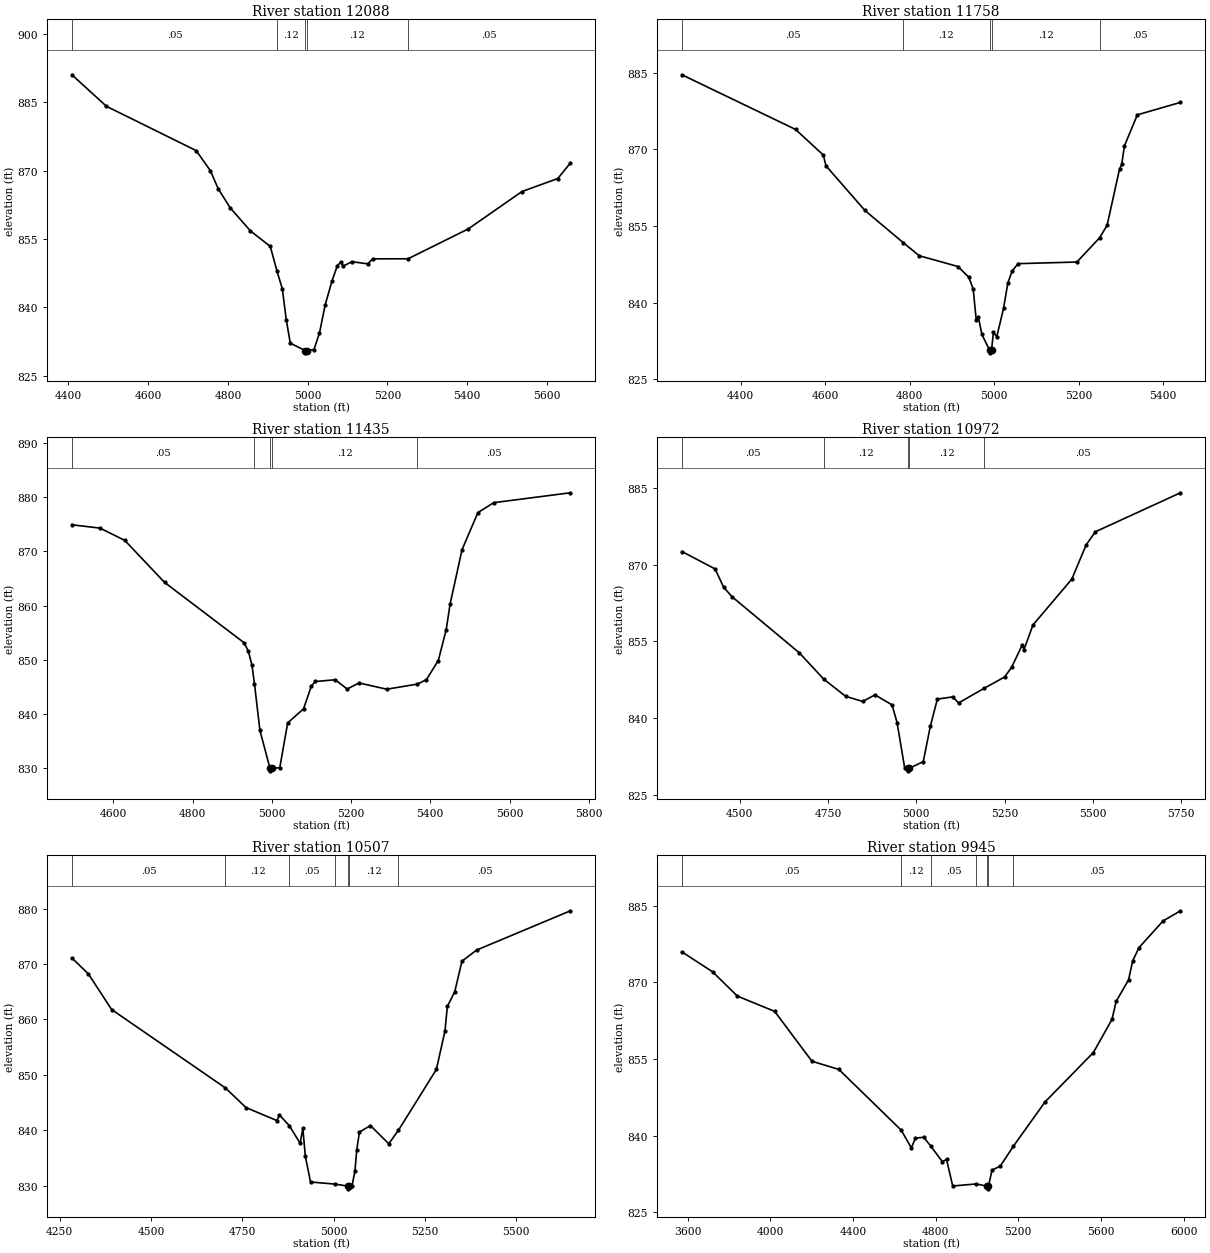
Type RM Length L Ch R = 1,12088,330,330,330
BEGIN DESCRIPTION:
MDW T 098 26.0
END DESCRIPTION:
XS GIS Cut Line= 3
      2283875.45      7148105.32      2283285.51      7148066.73
      2282694.87      7148358.78
#Sta/Elev= 30
  4408.8  891.04  4495.4  884.12  4720.5  874.39  4756.0  869.98  4776.0  865.94
  4806.1  861.79  4856.2  856.79  4906.3  853.34  4923.3  847.86  4936.4  844.04
  4946.4  837.21  4956.4  832.11  4993.7  830.49  4994.0  829.99  4997.8  830.49
  5015.8  830.71  5029.6  834.35  5043.8  840.49  5060.6  845.66  5074.2  849.10
  5083.1  849.92  5088.6  849.03  5111.1  850.00  5150.4  849.53  5163.4  850.63
  5251.7  850.64  5402.7  857.20  5537.4  865.41  5627.1  868.26  5658.9  871.69
#Mann=5,-1,0
  4408.8    0.05       0  4923.3    0.12       0  4993.7    0.07       0
  4997.8    0.12       0  5251.7    0.05       0
Bank Sta=4993.7,4997.8
Exp/Cntr=0.3,0.1

Type RM Length L Ch R = 1,11758,323,323,323
BEGIN DESCRIPTION:
MDW T 098 25.0
END DESCRIPTION:
XS GIS Cut Line= 3
      2283851.37      7147978.14      2283130.75      7147816.16
      2282699.08      7147726.41
#Sta/Elev= 30
  4261.4  884.62  4530.3  873.92  4595.9  868.91  4602.1  866.81  4694.3  858.07
  4785.0  851.77  4822.7  849.22  4914.4  847.10  4940.3  844.98  4950.5  842.67
  4957.7  836.59  4962.8  837.18  4971.0  833.82  4989.3  830.71  4989.7  830.21
  4993.8  830.71  4998.3  834.21  5006.3  833.38  5022.2  838.89  5032.4  843.86
  5042.6  846.20  5056.4  847.66  5195.8  847.98  5249.5  852.72  5267.3  855.17
  5296.7  866.18  5301.8  867.09  5308.2  870.69  5338.8  876.78  5440.9  879.22
#Mann=5,-1,0
  4261.4    0.05       0  4785.0    0.12       0  4989.3    0.07       0
  4993.8    0.12       0  5249.5    0.05       0
Bank Sta=4989.3,4993.8
Exp/Cntr=0.3,0.1

Type RM Length L Ch R = 1,11435,463,463,463
BEGIN DESCRIPTION:
MDW T 098 24.0
END DESCRIPTION:
XS GIS Cut Line= 3
      2283781.94      7147581.01      2283279.12      7147539.89
      2282525.47      7147524.59
#Sta/Elev= 30
  4495.5  874.87  4566.4  874.26  4628.9  872.00  4729.2  864.27  4929.9  853.15
  4941.1  851.53  4950.0  848.96  4956.3  845.56  4970.0  837.00  4995.3  830.04
  4995.8  829.54  4999.8  830.04  5020.1  830.10  5040.1  838.37  5080.1  840.96
  5100.1  845.22  5110.1  846.00  5160.2  846.32  5190.2  844.61  5220.2  845.73
  5290.2  844.58  5367.6  845.52  5390.2  846.34  5420.2  849.86  5440.2  855.56
  5450.2  860.33  5480.2  870.29  5520.2  877.12  5560.2  878.95  5753.8  880.77
#Mann=5,-1,0
  4495.5    0.05       0  4956.3    0.12       0  4995.3    0.07       0
  4999.8    0.12       0  5367.6    0.05       0
Bank Sta=4995.3,4999.8
Exp/Cntr=0.3,0.1

Type RM Length L Ch R = 1,10972,465,465,465
BEGIN DESCRIPTION:
MDW T 098 23.0
END DESCRIPTION:
XS GIS Cut Line= 3
      2283742.87      7147409.56      2283129.00      7147160.00
      2282382.06      7147123.21
#Sta/Elev= 30
  4337.0  872.60  4430.8  869.20  4454.9  865.61  4479.0  863.74  4669.1  852.77
  4738.0  847.63  4800.2  844.25  4848.4  843.25  4883.2  844.54  4931.4  842.57
  4945.7  839.10  4967.3  830.17  4975.8  830.16  4976.3  829.66  4980.3  830.16
  5019.7  831.46  5039.7  838.38  5059.7  843.71  5103.0  844.14  5119.8  842.96
  5192.7  845.85  5250.0  848.04  5270.0  849.97  5299.8  854.32  5304.8  853.39
  5330.1  858.23  5440.2  867.21  5480.2  873.85  5506.5  876.47  5747.5  884.11
#Mann=5,-1,0
  4337.0    0.05       0  4738.0    0.12       0  4975.8    0.07       0
  4980.3    0.12       0  5192.7    0.05       0
Bank Sta=4975.8,4980.3
Exp/Cntr=0.3,0.1

Type RM Length L Ch R = 1,10507,562,562,562
BEGIN DESCRIPTION:
MDW T 098 22.0
END DESCRIPTION:
XS GIS Cut Line= 3
      2283716.87      7147285.90      2283229.00      7146760.00
      2282582.96      7146706.53
#Sta/Elev= 30
  4283.3  871.09  4328.5  868.20  4392.1  861.78  4704.0  847.61  4760.0  844.08
  4845.0  841.72  4851.8  842.74  4879.0  840.79  4908.5  837.62  4915.9  840.31
  4922.7  835.30  4936.9  830.64  5004.6  830.25  5038.5  829.90  5039.0  829.40
  5043.1  829.90  5050.8  829.98  5058.6  832.65  5063.6  836.48  5070.9  839.64
  5101.0  840.83  5151.2  837.54  5177.7  839.97  5281.6  850.95  5305.2  857.91
  5311.7  862.35  5331.8  864.96  5351.8  870.52  5392.0  872.52  5648.9  879.61
#Mann=7,-1,0
  4283.3    0.05       0  4704.0    0.12       0  4879.0    0.05       0
  5004.6    0.12       0  5038.5   0.033       0  5043.1    0.12       0
  5177.7    0.05       0
Bank Sta=5038.5,5043.1
Exp/Cntr=0.3,0.1

Type RM Length L Ch R = 1,9945,471,471,471
BEGIN DESCRIPTION:
MDW T 098 21.0
END DESCRIPTION:
XS GIS Cut Line= 3
      2284736.84      7146144.37      2283312.11      7146226.57
      2282327.91      7146192.12
#Sta/Elev= 30
  3572.9  875.94  3721.0  872.05  3841.2  867.29  4021.5  864.30  4201.8  854.54
  4332.0  852.94  4633.5  841.06  4682.6  837.59  4702.6  839.48  4742.7  839.67
  4775.4  837.99  4832.8  834.89  4852.9  835.32  4882.9  830.13  4997.3  830.53
  5050.6  830.07  5051.2  829.57  5055.7  830.07  5073.2  833.23  5113.2  834.03
  5175.8  837.88  5329.5  846.58  5563.5  856.25  5653.5  862.74  5673.5  866.25
  5733.6  870.48  5753.6  874.18  5783.6  876.75  5900.5  882.00  5984.8  883.99
#Mann=7,-1,0
  3572.9    0.05       0  4633.5    0.12       0  4775.4    0.05       0
  4997.3    0.12       0  5050.6    0.07       0  5055.7    0.12       0
  5175.8    0.05       0
Bank Sta=5050.6,5055.7
Exp/Cntr=0.3,0.1

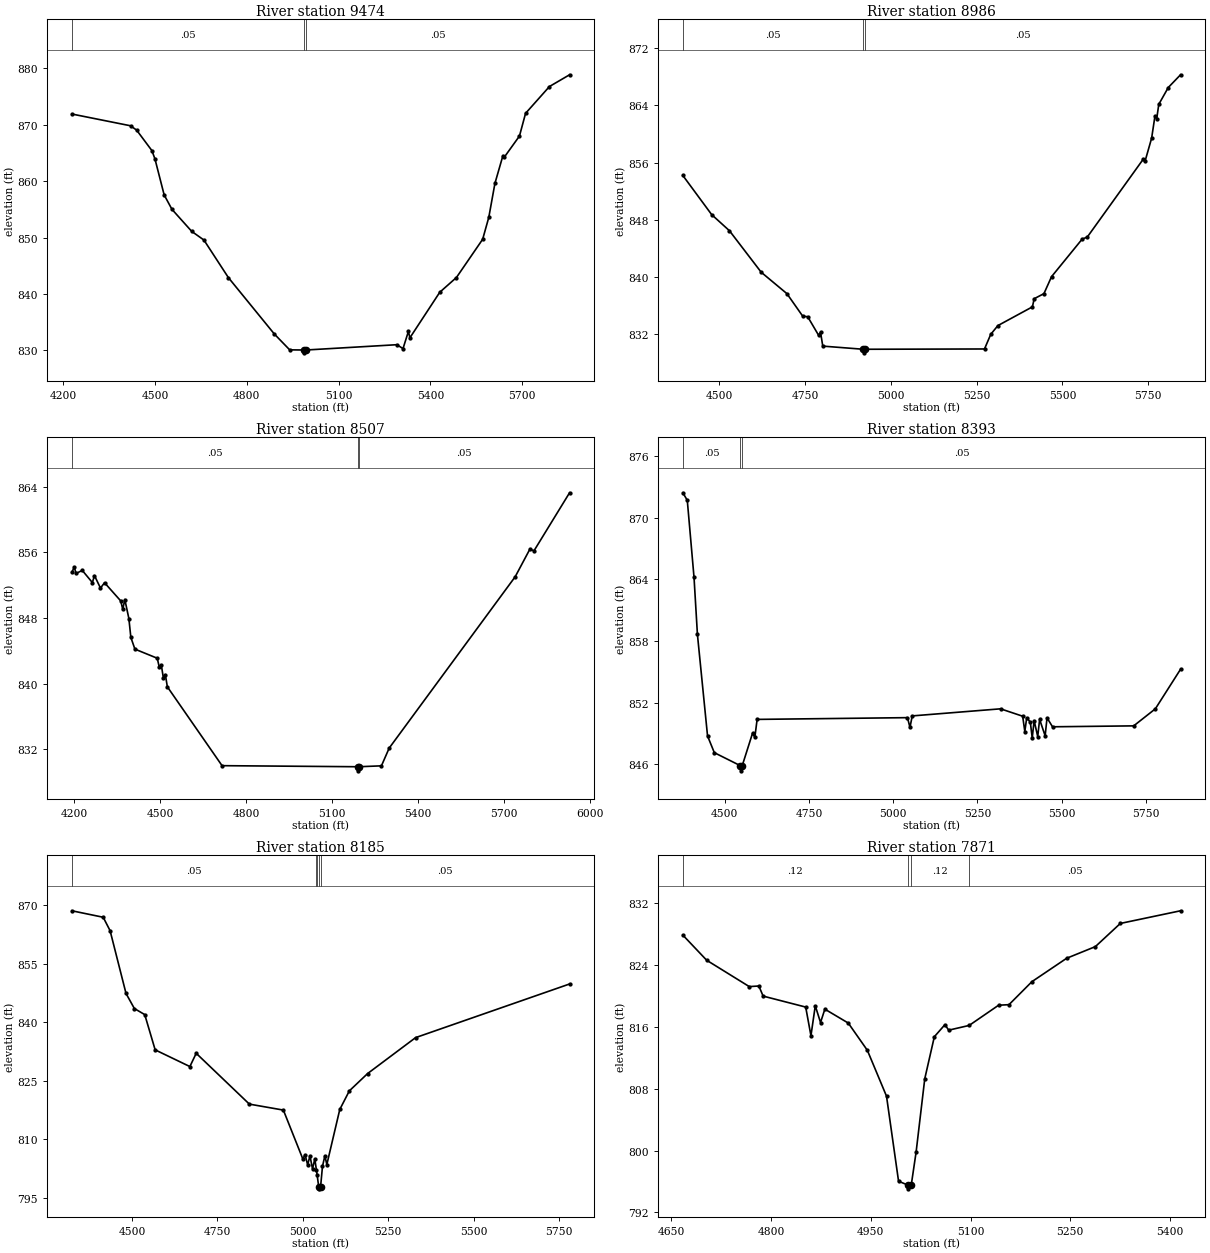
Type RM Length L Ch R = 1,9474,488,488,488
BEGIN DESCRIPTION:
MDW T 098 20.0
END DESCRIPTION:
XS GIS Cut Line= 3
      2284150.53      7145739.15      2283379.03      7145776.48
      2282525.44      7145720.92
#Sta/Elev= 30
  4227.6  871.87  4419.4  869.79  4439.4  869.02  4489.4  865.39  4499.4  863.91
  4529.5  857.54  4555.0  854.99  4619.6  851.09  4659.6  849.55  4739.7  842.89
  4889.9  832.91  4940.0  830.11  4987.4  830.08  4988.1  829.58  4992.7  830.08
  5290.6  831.02  5310.7  830.33  5328.2  833.36  5333.2  832.24  5430.9  840.31
  5485.4  842.92  5571.2  849.69  5591.3  853.59  5611.3  859.59  5637.5  864.51
  5642.5  864.27  5691.5  867.97  5711.5  871.99  5789.6  876.74  5855.4  878.82
#Mann=3,-1,0
  4227.6    0.05       0  4987.4   0.033       0  4992.7    0.05       0
Bank Sta=4987.4,4992.7
Exp/Cntr=0.3,0.1

Type RM Length L Ch R = 1,8986,479,479,479
BEGIN DESCRIPTION:
MDW T 098 19.0
END DESCRIPTION:
XS GIS Cut Line= 3
      2283830.20      7145569.90      2283278.60      7145320.17
      2282468.19      7145085.51
#Sta/Elev= 30
  4394.5  854.21  4478.6  848.73  4530.3  846.48  4622.7  840.68  4697.5  837.69
  4743.7  834.53  4758.1  834.46  4789.9  831.86  4795.4  832.31  4802.0  830.35
  4920.0  829.91  4920.8  829.41  4925.4  829.91  5272.9  829.95  5291.1  832.00
  5311.9  833.22  5412.4  835.84  5417.6  836.98  5446.0  837.69  5468.1  840.06
  5557.2  845.31  5572.2  845.60  5735.6  856.52  5740.8  856.27  5759.6  859.44
  5769.2  862.51  5774.4  862.17  5780.4  864.16  5808.0  866.51  5843.7  868.29
#Mann=3,-1,0
  4394.5    0.05       0  4920.0   0.033       0  4925.4    0.05       0
Bank Sta=4920,4925.4
Exp/Cntr=0.3,0.1

Type RM Length L Ch R = 1,8507,114,114,114
BEGIN DESCRIPTION:
MDW T 098 18.0
END DESCRIPTION:
XS GIS Cut Line= 3
      2283822.35      7145457.90      2283227.39      7144828.30
      2282507.23      7144338.10
#Sta/Elev= 30
  4192.3  853.53  4200.4  854.19  4207.2  853.42  4228.7  853.78  4263.9  852.30
  4271.2  853.15  4292.2  851.63  4306.4  852.28  4363.0  850.06  4369.9  849.04
  4377.2  850.23  4391.3  847.92  4398.2  845.62  4412.4  844.19  4490.4  843.08
  4497.3  842.01  4504.6  842.25  4511.5  840.73  4518.7  841.08  4525.6  839.60
  4716.6  829.99  5189.6  829.86  5190.3  829.36  5195.0  829.86  5273.0  829.97
  5300.0  832.13  5739.9  853.01  5790.7  856.34  5805.7  856.18  5929.7  863.24
#Mann=3,-1,0
  4192.3    0.05       0  5189.6   0.033       0  5195.0    0.05       0
Bank Sta=5189.6,5195
Exp/Cntr=0.3,0.1

Type RM Length L Ch R = 1,8393,208,208,208
BEGIN DESCRIPTION:
MDW T 098 17.5
END DESCRIPTION:
XS GIS Cut Line= 6
      2283832.19      7145118.95      2283634.69      7145106.63
      2283289.62      7144726.31      2283096.41      7144527.53
      2282955.78      7144452.88      2282642.72      7144352.15
#Sta/Elev= 30
  4375.8  872.44  4389.0  871.71  4409.0  864.20  4419.1  858.64  4449.1  848.76
  4469.2  847.13  4546.6  845.86  4547.4  845.36  4552.0  845.86  4582.6  849.02
  4589.5  848.63  4596.2  850.37  5042.3  850.54  5049.7  849.59  5056.5  850.71
  5318.5  851.40  5384.1  850.68  5390.5  849.19  5396.1  850.53  5406.8  850.10
  5412.5  848.56  5418.1  850.25  5428.8  848.70  5434.4  850.37  5450.8  848.77
  5456.4  850.52  5472.7  849.65  5713.6  849.74  5777.8  851.40  5852.5  855.25
#Mann=3,-1,0
  4375.8    0.05       0  4546.6   0.033       0  4552.0    0.05       0
Bank Sta=4546.6,4552
Exp/Cntr=0.3,0.1

Type RM Length L Ch R = 1,8185,314,314,314
BEGIN DESCRIPTION:
MDW T 098 17.0
END DESCRIPTION:
XS GIS Cut Line= 4
      2283969.39      7144931.42      2283620.57      7144872.84
      2283371.71      7144591.76      2282733.92      7144241.82
#Sta/Elev= 30
  4324.0  868.52  4415.7  866.86  4435.9  863.41  4482.5  847.32  4506.9  843.46
  4537.3  841.90  4567.8  832.86  4669.4  828.58  4687.9  831.98  4843.5  818.95
  4943.0  817.42  4999.9  804.90  5006.6  805.97  5014.1  803.35  5020.8  805.72
  5028.3  802.34  5035.0  804.89  5039.9  801.95  5041.8  800.81  5046.5  797.73
  5047.3  797.23  5051.9  797.73  5057.5  803.01  5064.5  805.71  5070.2  803.46
  5108.1  817.58  5136.1  822.35  5189.6  826.79  5330.0  836.00  5780.6  849.75
#Mann=5,-1,0
  4324.0    0.05       0  5039.9    0.12       0  5041.8    0.05       0
  5046.5   0.033       0  5051.9    0.05       0
Bank Sta=5046.5,5051.9
Exp/Cntr=0.3,0.1

Type RM Length L Ch R = 1,7871,203,203,203
BEGIN DESCRIPTION:
Mapping XS 7c48f0a0
END DESCRIPTION:
XS GIS Cut Line= 3
      2283746.38      7144613.17      2283541.61      7144359.26
      2283174.87      7144150.46
#Sta/Elev= 30
  4667.5  827.90  4703.4  824.64  4767.4  821.23  4781.8  821.31  4788.2  820.00
  4852.2  818.58  4860.1  814.87  4866.6  818.75  4874.5  816.58  4881.0  818.31
  4916.2  816.51  4944.9  812.98  4973.7  807.04  4991.8  796.03  5005.4  795.54
  5006.2  795.04  5010.9  795.54  5018.2  799.81  5031.2  809.30  5045.6  814.74
  5061.5  816.30  5067.2  815.59  5097.9  816.20  5142.2  818.82  5157.8  818.89
  5192.3  821.87  5244.5  824.90  5287.7  826.41  5325.2  829.41  5415.7  831.05
#Mann=4,-1,0
  4667.5    0.12       0  5005.4    0.07       0  5010.9    0.12       0
  5097.9    0.05       0
Bank Sta=5005.4,5010.9
Exp/Cntr=0.3,0.1

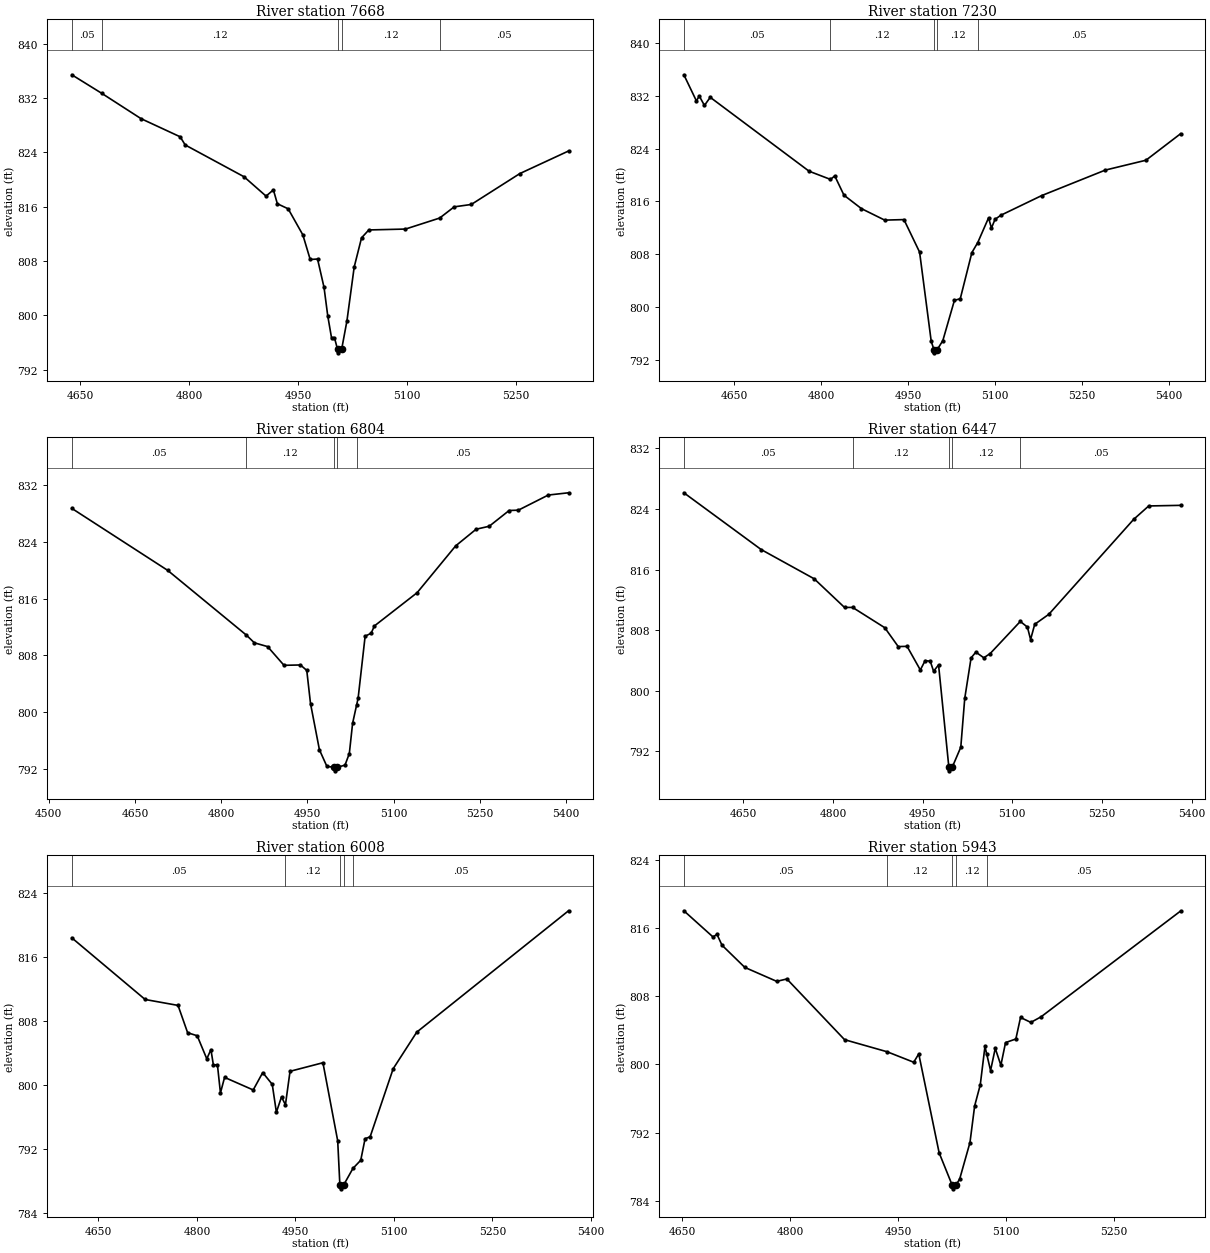
Type RM Length L Ch R = 1,7668,438,438,438
BEGIN DESCRIPTION:
MDW T 098 16.0
END DESCRIPTION:
XS GIS Cut Line= 3
      2284003.21      7144246.70      2283645.96      7144193.45
      2283326.14      7144157.73
#Sta/Elev= 30
  4638.8  835.41  4679.8  832.69  4734.0  828.95  4787.8  826.28  4794.7  825.08
  4875.6  820.40  4905.9  817.55  4916.0  818.47  4921.4  816.43  4936.3  815.68
  4956.5  811.84  4966.6  808.22  4976.7  808.29  4985.6  804.12  4990.7  799.94
  4995.9  796.70  5000.0  796.70  5004.2  794.98  5005.0  794.48  5009.8  794.98
  5017.1  799.18  5027.1  807.12  5037.2  811.41  5047.2  812.57  5097.6  812.70
  5144.6  814.32  5164.6  815.97  5188.1  816.32  5254.9  820.87  5321.8  824.19
#Mann=5,-1,0
  4638.8    0.05       0  4679.8    0.12       0  5004.2    0.07       0
  5009.8    0.12       0  5144.6    0.05       0
Bank Sta=5004.2,5009.8
Exp/Cntr=0.3,0.1

Type RM Length L Ch R = 1,7230,426,426,426
BEGIN DESCRIPTION:
MDW T 098 15.0
END DESCRIPTION:
XS GIS Cut Line= 3
      2284094.33      7143866.93      2283658.80      7143830.00
      2283239.31      7143807.25
#Sta/Elev= 30
  4562.9  835.17  4584.5  831.22  4589.5  831.95  4598.4  830.53  4608.4  831.76
  4779.0  820.58  4815.9  819.34  4823.3  819.87  4839.2  816.95  4869.3  814.92
  4909.5  813.18  4942.7  813.26  4969.7  808.34  4989.8  794.82  4994.5  793.60
  4995.4  793.10  5000.2  793.60  5009.8  794.95  5029.8  801.04  5039.9  801.29
  5059.9  808.26  5070.1  809.79  5088.7  813.52  5093.7  811.98  5099.9  813.30
  5110.0  813.92  5180.1  816.88  5290.2  820.75  5360.3  822.24  5420.1  826.25
#Mann=5,-1,0
  4562.9    0.05       0  4815.9    0.12       0  4994.5    0.07       0
  5000.2    0.12       0  5070.1    0.05       0
Bank Sta=4994.5,5000.2
Exp/Cntr=0.3,0.1

Type RM Length L Ch R = 1,6804,357,357,357
BEGIN DESCRIPTION:
MDW T 098 14.0
END DESCRIPTION:
XS GIS Cut Line= 3
      2284110.62      7143637.97      2283692.45      7143446.81
      2283338.08      7143252.79
#Sta/Elev= 30
  4540.2  828.73  4706.9  819.99  4843.9  810.85  4857.7  809.77  4880.7  809.24
  4909.2  806.60  4937.8  806.65  4948.8  805.88  4955.3  801.21  4970.8  794.69
  4983.8  792.35  4996.3  792.22  4997.2  791.72  5002.0  792.22  5015.3  792.53
  5022.8  794.16  5028.5  798.42  5035.5  801.01  5038.1  801.97  5050.3  810.71
  5060.7  811.12  5066.4  812.15  5140.7  816.84  5207.7  823.44  5243.3  825.79
  5266.1  826.21  5300.7  828.43  5316.8  828.48  5368.8  830.61  5404.0  830.93
#Mann=5,-1,0
  4540.2    0.05       0  4843.9    0.12       0  4996.3    0.07       0
  5002.0    0.12       0  5035.5    0.05       0
Bank Sta=4996.3,5002
Exp/Cntr=0.3,0.1

Type RM Length L Ch R = 1,6447,439,439,439
BEGIN DESCRIPTION:
MDW T 098 13.0
END DESCRIPTION:
XS GIS Cut Line= 3
      2284258.18      7143364.53      2283858.23      7143159.36
      2283499.78      7143028.19
#Sta/Elev= 30
  4550.5  826.15  4679.9  818.65  4768.6  814.79  4819.3  811.01  4832.9  811.01
  4886.7  808.33  4909.2  805.84  4924.0  805.87  4946.2  802.75  4954.2  803.98
  4962.8  803.91  4968.4  802.58  4976.7  803.42  4993.9  789.93  4994.8  789.43
  4999.7  789.93  5013.9  792.55  5020.5  798.99  5031.1  804.34  5039.1  805.11
  5052.4  804.36  5063.1  804.92  5113.5  809.16  5125.4  808.41  5130.7  806.77
  5137.6  808.78  5161.2  810.10  5303.2  822.64  5328.4  824.41  5381.7  824.49
#Mann=5,-1,0
  4550.5    0.05       0  4832.9    0.12       0  4993.9    0.07       0
  4999.7    0.12       0  5113.5    0.05       0
Bank Sta=4993.9,4999.7
Exp/Cntr=0.3,0.1

Type RM Length L Ch R = 1,6008,65,65,65
BEGIN DESCRIPTION:
MDW T 098 12.5
END DESCRIPTION:
XS GIS Cut Line= 4
      2284224.61      7143010.84      2284048.79      7142880.60
      2283884.94      7142754.73      2283633.49      7142539.19
#Sta/Elev= 30
  4609.4  818.43  4721.1  810.73  4771.2  809.99  4785.8  806.58  4800.4  806.20
  4815.0  803.32  4821.3  804.47  4825.0  802.57  4831.2  802.57  4835.8  799.06
  4842.1  801.00  4885.7  799.43  4900.2  801.60  4914.7  800.13  4921.0  796.65
  4928.8  798.56  4934.8  797.58  4941.8  801.76  4991.9  802.83  5014.4  793.08
  5017.7  787.58  5018.7  787.08  5023.6  787.58  5037.6  789.63  5049.5  790.65
  5056.1  793.34  5063.8  793.58  5098.9  802.08  5134.8  806.65  5366.0  821.81
#Mann=5,-1,0
  4609.4    0.05       0  4934.8    0.12       0  5017.7    0.07       0
  5023.6    0.12       0  5037.6    0.05       0
Bank Sta=5017.7,5023.6
Exp/Cntr=0.3,0.1

Type RM Length L Ch R = 1,5943,271,271,271
BEGIN DESCRIPTION:
MDW T 098 12.0
END DESCRIPTION:
XS GIS Cut Line= 4
      2284256.00      7142905.54      2284006.47      7142776.44
      2283944.98      7142715.73      2283698.28      7142508.40
#Sta/Elev= 30
  4652.6  818.05  4693.0  814.98  4698.6  815.28  4705.5  814.01  4737.2  811.40
  4781.5  809.76  4795.6  810.04  4875.7  802.91  4934.8  801.49  4971.7  800.26
  4978.7  801.24  5007.0  789.62  5024.8  785.89  5025.8  785.39  5030.7  785.89
  5035.5  786.54  5049.8  790.83  5056.3  795.13  5064.1  797.61  5070.6  802.11
  5073.2  801.17  5078.4  799.28  5084.9  801.89  5092.7  799.91  5099.2  802.57
  5113.5  802.99  5120.0  805.52  5134.3  804.94  5148.6  805.60  5342.2  818.02
#Mann=5,-1,0
  4652.6    0.05       0  4934.8    0.12       0  5024.8    0.07       0
  5030.7    0.12       0  5073.2    0.05       0
Bank Sta=5024.8,5030.7
Exp/Cntr=0.3,0.1

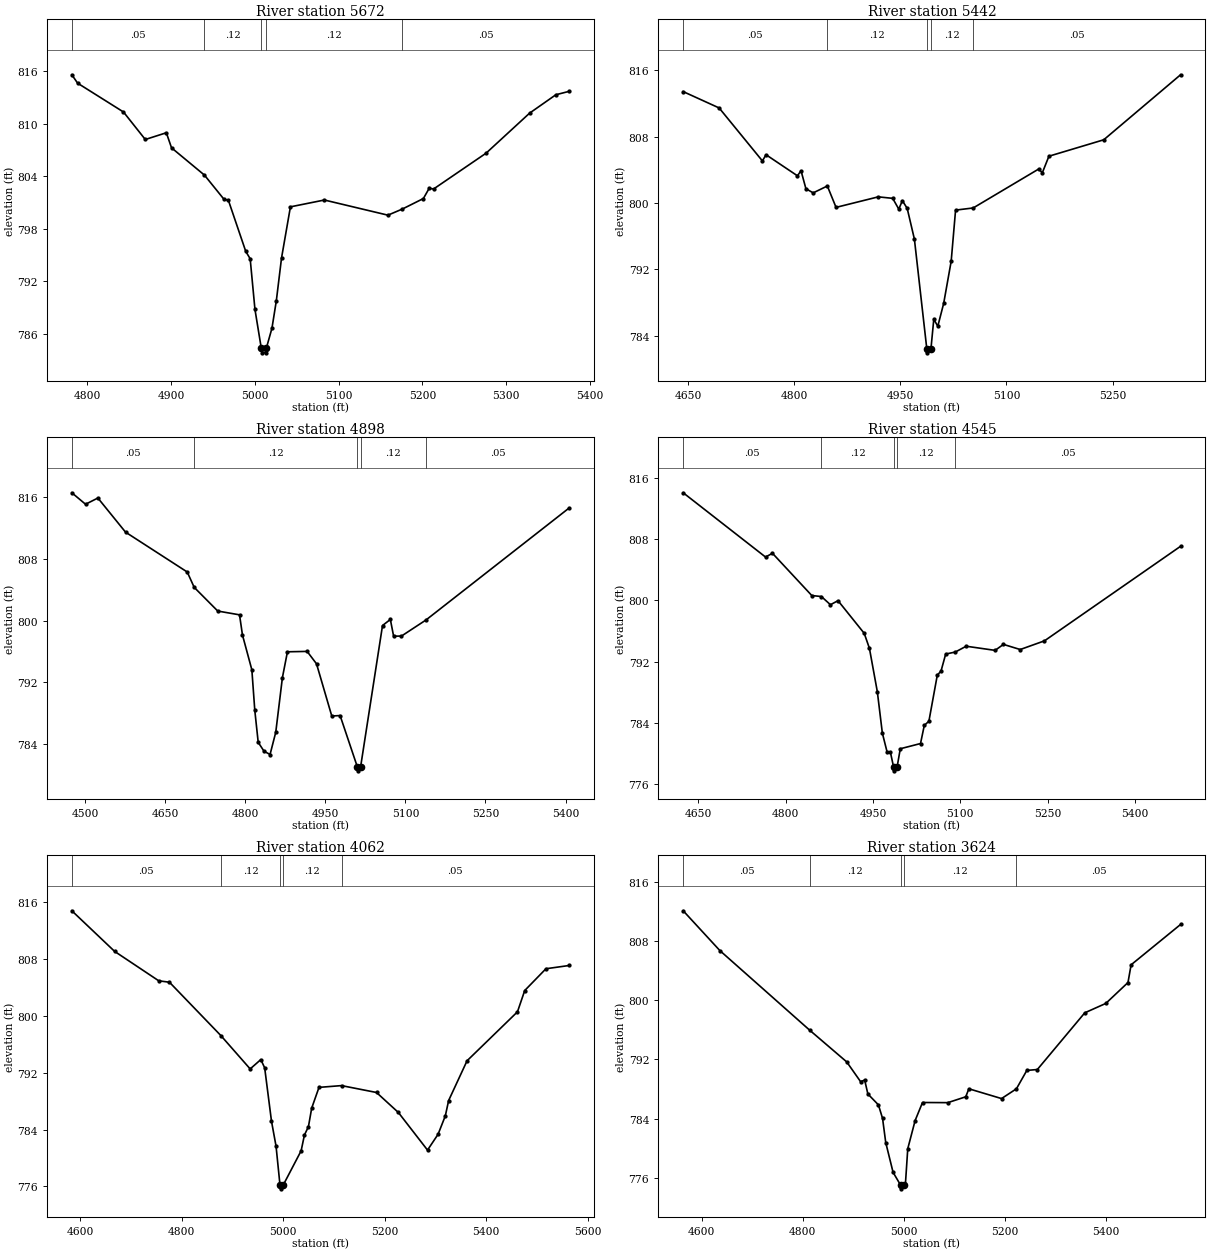
Type RM Length L Ch R = 1,5672,230,230,230
BEGIN DESCRIPTION:
Mapping XS 04d52d0f
END DESCRIPTION:
XS GIS Cut Line= 2
      2284335.56      7142613.89      2283774.47      7142421.37
#Sta/Elev= 30
  4781.8  815.60  4788.7  814.64  4843.4  811.35  4869.4  808.21  4894.5  808.98
  4900.7  807.26  4940.0  804.14  4963.2  801.39  4968.5  801.27  4989.2  795.44
  4994.5  794.59  5000.2  788.81  5007.8  784.35  5008.8  783.85  5012.8  783.85
  5013.7  784.35  5020.5  786.67  5025.7  789.80  5031.9  794.68  5042.5  800.52
  5083.0  801.30  5158.8  799.57  5176.0  800.27  5201.1  801.47  5208.0  802.64
  5213.3  802.56  5275.9  806.65  5327.8  811.22  5359.1  813.32  5375.0  813.71
#Mann=5,-1,0
  4781.8    0.05       0  4940.0    0.12       0  5007.8    0.07       0
  5013.7    0.12       0  5176.0    0.05       0
Bank Sta=5007.8,5013.7
Exp/Cntr=0.3,0.1

Type RM Length L Ch R = 1,5442,544,544,544
BEGIN DESCRIPTION:
MDW T 098 11.0
END DESCRIPTION:
XS GIS Cut Line= 3
      2284378.70      7142419.46      2284029.49      7142344.78
      2283703.89      7142227.45
#Sta/Elev= 30
  4642.9  813.44  4693.7  811.47  4754.9  805.08  4760.0  805.83  4804.4  803.29
  4809.5  803.90  4816.4  801.73  4826.7  801.23  4846.7  802.06  4859.0  799.48
  4918.7  800.75  4939.1  800.57  4947.7  799.27  4952.8  800.29  4959.6  799.36
  4969.8  795.65  4987.3  782.44  4988.3  781.94  4993.2  782.44  4997.2  785.99
  5002.9  785.15  5011.2  787.91  5021.8  792.99  5028.0  799.15  5052.9  799.41
  5145.4  804.10  5150.7  803.66  5160.0  805.65  5237.5  807.63  5346.1  815.47
#Mann=5,-1,0
  4642.9    0.05       0  4846.7    0.12       0  4987.3    0.07       0
  4993.2    0.12       0  5052.9    0.05       0
Bank Sta=4987.3,4993.2
Exp/Cntr=0.3,0.1

Type RM Length L Ch R = 1,4898,353,353,353
BEGIN DESCRIPTION:
MDW T 098 10.0
END DESCRIPTION:
XS GIS Cut Line= 3
      2284464.54      7142368.42      2284248.73      7141889.50
      2283919.67      7141650.14
#Sta/Elev= 30
  4474.7  816.59  4500.4  815.10  4523.5  815.91  4575.3  811.48  4691.0  806.30
  4704.0  804.31  4748.2  801.23  4789.0  800.74  4794.5  798.12  4812.1  793.60
  4817.6  788.34  4824.0  784.18  4834.9  783.03  4846.2  782.60  4856.9  785.49
  4869.4  792.60  4878.8  795.94  4915.7  795.99  4933.3  794.38  4961.9  787.60
  4977.5  787.66  5009.9  780.98  5010.9  780.48  5015.9  780.98  5057.0  799.35
  5071.7  800.14  5077.8  797.97  5092.5  797.98  5138.5  800.07  5406.9  814.62
#Mann=5,-1,0
  4474.7    0.05       0  4704.0    0.12       0  5009.9    0.07       0
  5015.9    0.12       0  5138.5    0.05       0
Bank Sta=5009.9,5015.9
Exp/Cntr=0.3,0.1

Type RM Length L Ch R = 1,4545,483,483,483
BEGIN DESCRIPTION:
MDW T 098 9.0
END DESCRIPTION:
XS GIS Cut Line= 3
      2284815.89      7141870.38      2284478.61      7141704.89
      2284107.00      7141404.39
#Sta/Elev= 30
  4624.3  814.01  4765.6  805.63  4777.5  806.12  4845.0  800.61  4861.5  800.48
  4877.0  799.41  4890.0  799.94  4935.0  795.68  4943.9  793.73  4957.5  788.06
  4966.1  782.67  4974.4  780.16  4979.9  780.18  4985.4  778.25  4986.4  777.75
  4991.4  778.25  4996.9  780.63  5031.6  781.31  5038.1  783.68  5046.0  784.22
  5060.4  790.23  5066.8  790.76  5074.8  792.98  5091.2  793.24  5110.0  794.00
  5159.6  793.46  5173.9  794.24  5202.7  793.57  5244.3  794.70  5477.9  807.03
#Mann=5,-1,0
  4624.3    0.05       0  4861.5    0.12       0  4985.4    0.07       0
  4991.4    0.12       0  5091.2    0.05       0
Bank Sta=4985.4,4991.4
Exp/Cntr=0.3,0.1

Type RM Length L Ch R = 1,4062,438,438,438
BEGIN DESCRIPTION:
MDW T 098 8.0
END DESCRIPTION:
XS GIS Cut Line= 3
      2285104.52      7141591.51      2284758.87      7141359.68
      2284323.67      7141001.56
#Sta/Elev= 30
  4583.8  814.83  4668.0  809.11  4755.0  804.96  4776.1  804.76  4877.4  797.24
  4935.1  792.54  4956.1  793.86  4963.7  792.69  4977.1  785.18  4986.1  781.65
  4993.9  776.14  4994.9  775.64  5000.0  776.14  5035.5  781.00  5042.0  783.22
  5049.9  784.41  5056.3  787.01  5070.7  789.94  5115.1  790.19  5184.0  789.22
  5227.1  786.40  5284.5  781.10  5305.3  783.33  5319.6  785.93  5326.1  788.09
  5362.4  793.69  5461.7  800.59  5476.0  803.59  5517.8  806.66  5563.6  807.12
#Mann=5,-1,0
  4583.8    0.05       0  4877.4    0.12       0  4993.9    0.07       0
  5000.0    0.12       0  5115.1    0.05       0
Bank Sta=4993.9,5000
Exp/Cntr=0.3,0.1

Type RM Length L Ch R = 1,3624,390,390,390
BEGIN DESCRIPTION:
MDW T 098 7.0
END DESCRIPTION:
XS GIS Cut Line= 3
      2285316.51      7141285.41      2284969.26      7141020.76
      2284529.00      7140693.95
#Sta/Elev= 30
  4563.4  812.06  4636.0  806.69  4814.0  795.94  4887.2  791.67  4914.6  789.01
  4922.8  789.21  4929.1  787.34  4950.0  785.87  4958.2  784.04  4964.5  780.78
  4979.0  776.77  4993.9  775.04  4995.0  774.54  5000.1  775.04  5003.3  775.04
  5008.1  779.96  5022.7  783.76  5037.3  786.19  5087.4  786.17  5122.9  786.96
  5129.1  788.04  5193.8  786.72  5223.3  788.04  5243.9  790.52  5264.7  790.64
  5358.6  798.29  5400.3  799.56  5444.2  802.38  5450.4  804.77  5548.3  810.21
#Mann=5,-1,0
  4563.4    0.05       0  4814.0    0.12       0  4993.9    0.07       0
  5000.1    0.12       0  5223.3    0.05       0
Bank Sta=4993.9,5000.1
Exp/Cntr=0.3,0.1