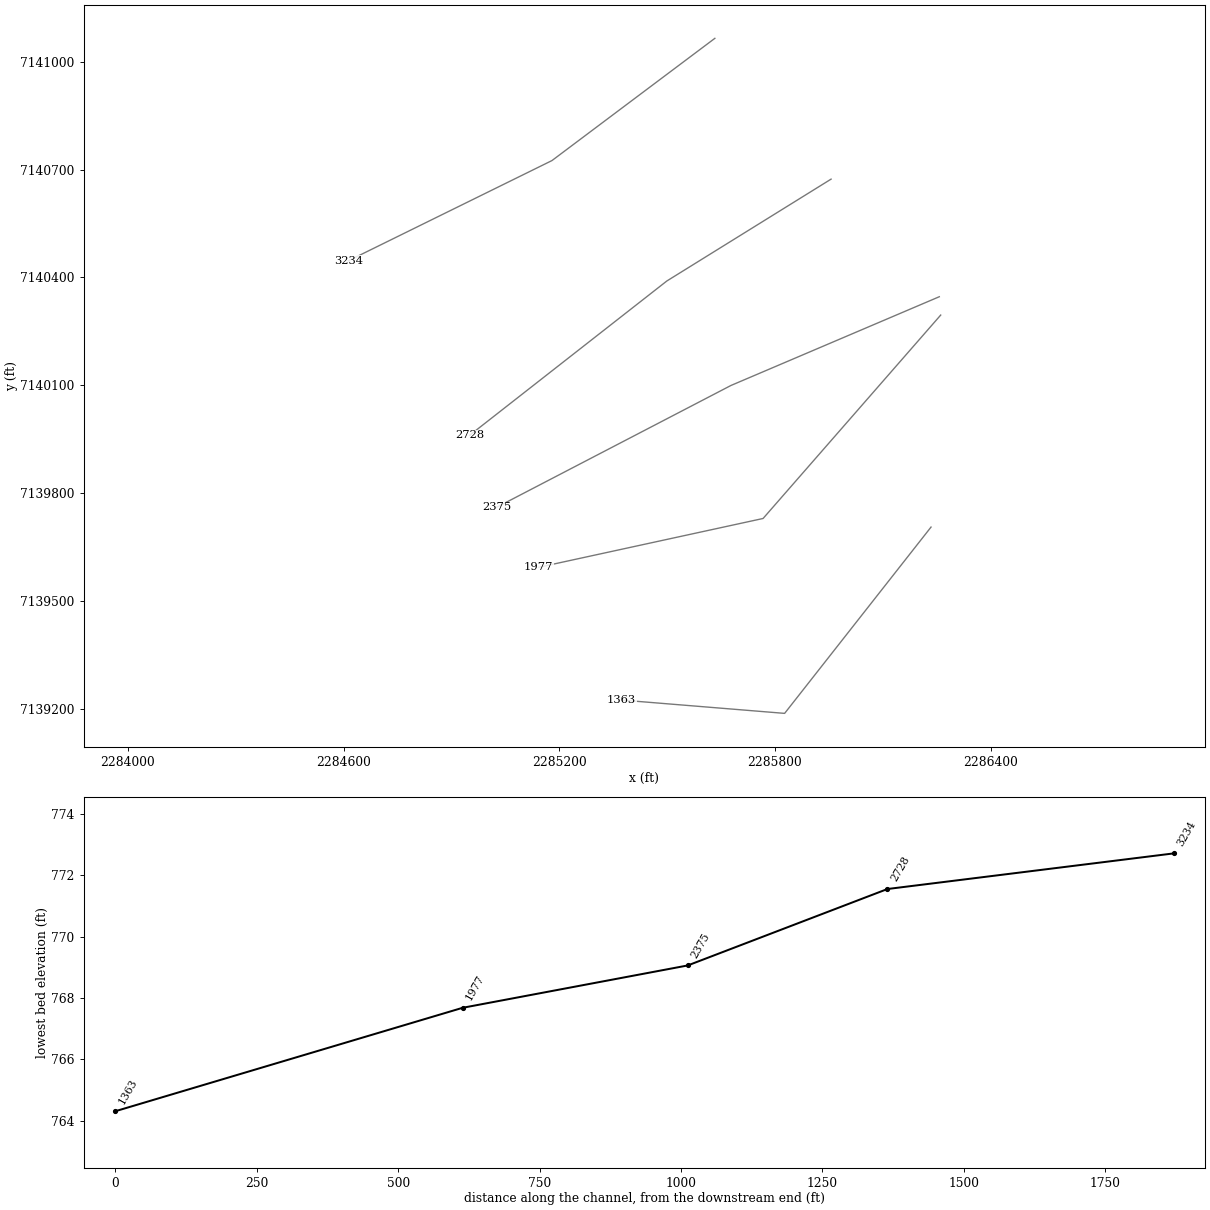
HEC-RAS study MDW T 098.prj: MDW T 098 Base Level Engineering

--- MDW T 098.g01 (geometry) --- (continued)

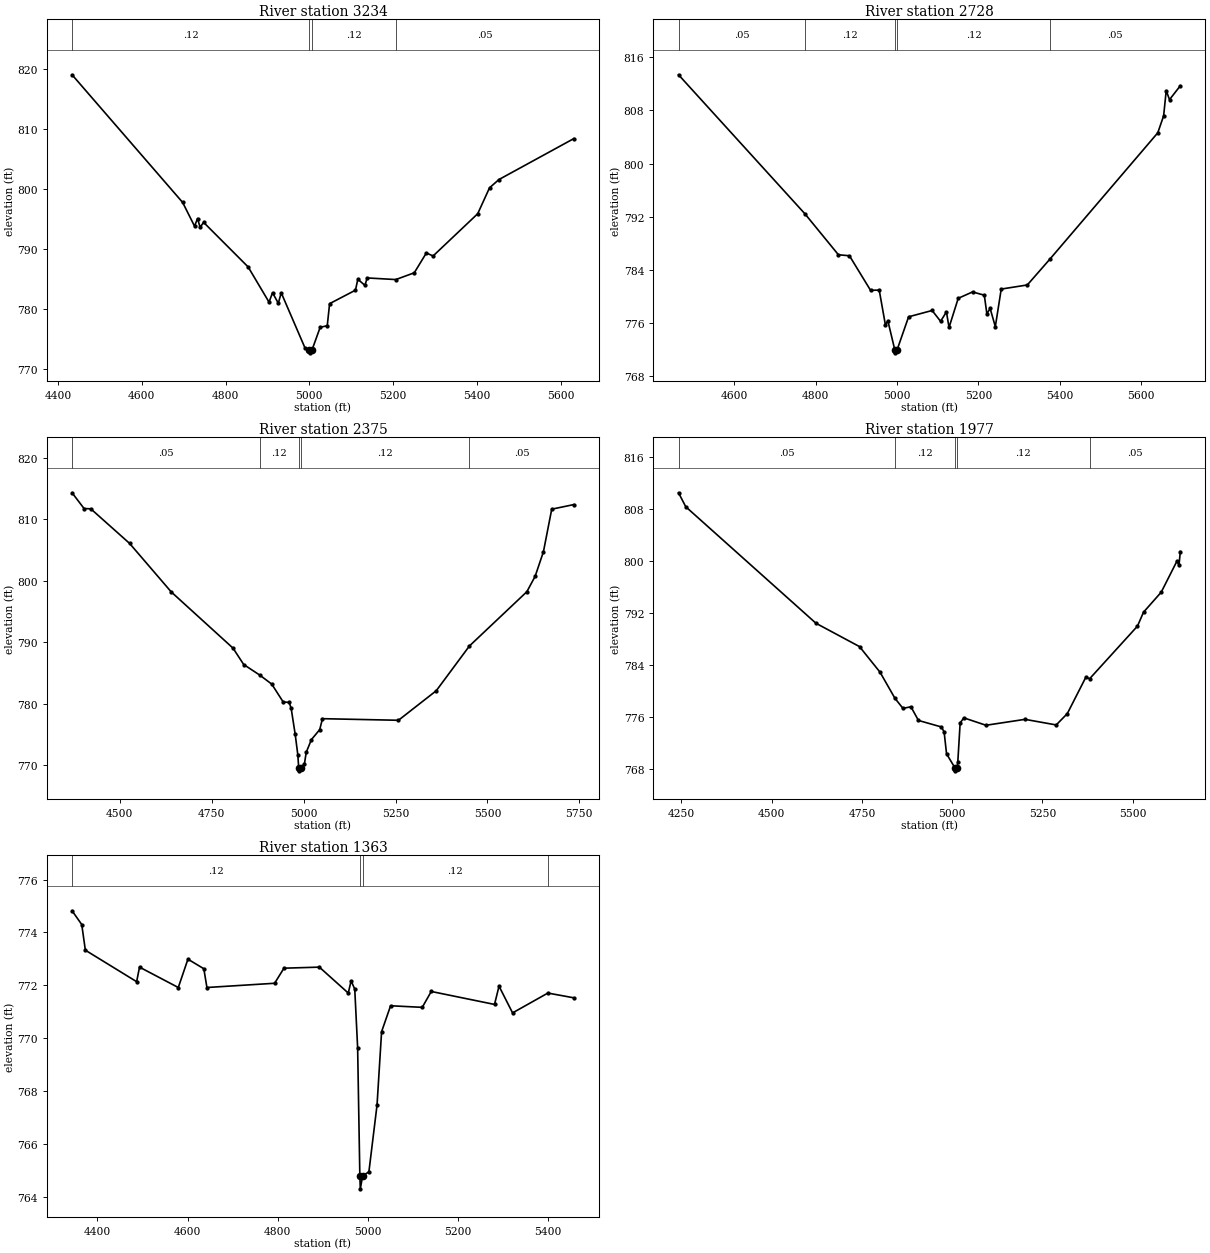
Type RM Length L Ch R = 1,3234,506,506,506
BEGIN DESCRIPTION:
MDW T 098 6.0
END DESCRIPTION:
XS GIS Cut Line= 3
      2285632.96      7141065.26      2285179.76      7140725.20
      2284613.00      7140446.23
#Sta/Elev= 30
  4433.4  819.08  4697.5  797.79  4725.9  793.83  4733.0  795.11  4739.2  793.64
  4747.5  794.47  4853.8  787.04  4903.8  781.16  4912.1  782.74  4925.9  780.98
  4932.9  782.72  4989.2  773.60  5000.3  773.21  5001.3  772.71  5006.5  773.21
  5025.9  776.97  5042.8  777.23  5048.4  780.91  5110.2  783.16  5115.8  784.99
  5132.7  783.96  5138.2  785.20  5206.5  784.93  5250.6  786.06  5279.5  789.37
  5295.5  788.86  5402.1  795.91  5430.3  800.23  5452.8  801.61  5631.7  808.44
#Mann=4,-1,0
  4433.4    0.12       0  5000.3    0.07       0  5006.5    0.12       0
  5206.5    0.05       0
Bank Sta=5000.3,5006.5
Exp/Cntr=0.3,0.1

Type RM Length L Ch R = 1,2728,353,353,353
BEGIN DESCRIPTION:
MDW T 098 5.0
END DESCRIPTION:
XS GIS Cut Line= 3
      2285956.33      7140673.57      2285499.38      7140390.16
      2284950.44      7139960.65
#Sta/Elev= 30
  4462.3  813.37  4773.3  792.46  4855.7  786.30  4882.8  786.15  4934.8  780.95
  4956.1  780.99  4971.4  775.72  4977.3  776.39  4994.2  772.05  4995.2  771.55
  5000.4  772.05  5028.4  776.97  5086.3  777.92  5107.1  776.29  5121.5  777.71
  5127.9  775.37  5150.5  779.75  5185.7  780.71  5214.7  780.22  5221.0  777.41
  5229.0  778.23  5241.8  775.49  5256.3  781.14  5320.5  781.76  5376.3  785.66
  5641.5  804.64  5655.9  807.19  5662.3  810.99  5670.4  809.63  5697.0  811.72
#Mann=5,-1,0
  4462.3    0.05       0  4773.3    0.12       0  4994.2    0.07       0
  5000.4    0.12       0  5376.3    0.05       0
Bank Sta=4994.2,5000.4
Exp/Cntr=0.3,0.1

Type RM Length L Ch R = 1,2375,398,398,398
BEGIN DESCRIPTION:
MDW T 098 4.0
END DESCRIPTION:
XS GIS Cut Line= 3
      2286257.41      7140346.39      2285677.80      7140099.50
      2285025.58      7139760.42
#Sta/Elev= 30
  4370.0  814.32  4402.7  811.75  4420.9  811.71  4526.3  806.09  4640.0  798.17
  4807.9  789.03  4837.0  786.36  4880.7  784.64  4913.3  783.17  4944.3  780.27
  4960.6  780.20  4966.1  779.21  4977.0  775.00  4984.2  771.64  4986.5  769.56
  4987.5  769.06  4992.8  769.56  5002.1  770.18  5007.0  772.07  5021.2  774.15
  5043.7  775.77  5051.2  777.55  5257.9  777.29  5360.8  782.10  5451.1  789.39
  5607.3  798.22  5629.8  800.73  5652.3  804.72  5674.9  811.65  5735.1  812.40
#Mann=5,-1,0
  4370.0    0.05       0  4880.7    0.12       0  4986.5    0.07       0
  4992.8    0.12       0  5451.1    0.05       0
Bank Sta=4986.5,4992.8
Exp/Cntr=0.3,0.1

Type RM Length L Ch R = 1,1977,614,614,614
BEGIN DESCRIPTION:
Mapping XS 5715897e
END DESCRIPTION:
XS GIS Cut Line= 3
      2286261.29      7140295.35      2285767.13      7139729.43
      2285143.05      7139593.59
#Sta/Elev= 30
  4241.9  810.45  4261.9  808.30  4622.6  790.38  4743.2  786.79  4800.1  782.85
  4841.3  778.84  4863.7  777.28  4885.6  777.54  4906.5  775.43  4970.0  774.43
  4977.6  773.67  4984.3  770.30  5007.1  768.18  5008.2  767.68  5013.5  768.18
  5015.5  769.05  5022.0  775.05  5032.2  775.83  5093.6  774.69  5201.6  775.60
  5288.1  774.74  5318.8  776.48  5370.0  782.06  5380.9  781.86  5513.2  789.94
  5529.9  792.08  5579.0  795.16  5623.0  799.99  5628.1  799.27  5631.9  801.41
#Mann=5,-1,0
  4241.9    0.05       0  4841.3    0.12       0  5007.1    0.07       0
  5013.5    0.12       0  5380.9    0.05       0
Bank Sta=5007.1,5013.5
Exp/Cntr=0.3,0.1

Type RM Length L Ch R = 1,1363,0,0,0
BEGIN DESCRIPTION:
MDW T 098 3.0
END DESCRIPTION:
XS GIS Cut Line= 3
      2286234.40      7139705.51      2285827.05      7139187.19
      2285373.39      7139224.21
#Sta/Elev= 30
  4343.6  774.82  4365.1  774.30  4373.1  773.33  4487.0  772.14  4493.4  772.69
  4579.5  771.92  4600.9  772.99  4636.2  772.63  4643.1  771.92  4793.4  772.08
  4814.2  772.65  4892.8  772.69  4957.0  771.71  4963.3  772.17  4971.4  771.86
  4977.8  769.64  4982.7  764.81  4983.7  764.31  4989.1  764.81  5002.8  764.95
  5020.9  767.48  5031.0  770.25  5051.0  771.23  5121.3  771.17  5141.3  771.77
  5281.8  771.28  5291.8  771.97  5321.9  770.96  5400.3  771.71  5458.0  771.53
#Mann=4,-1,0
  4343.6    0.12       0  4982.7    0.07       0  4989.1    0.12       0
  5400.3    0.05       0
Bank Sta=4982.7,4989.1
Exp/Cntr=0.3,0.1

Chan Stop Cuts=-1