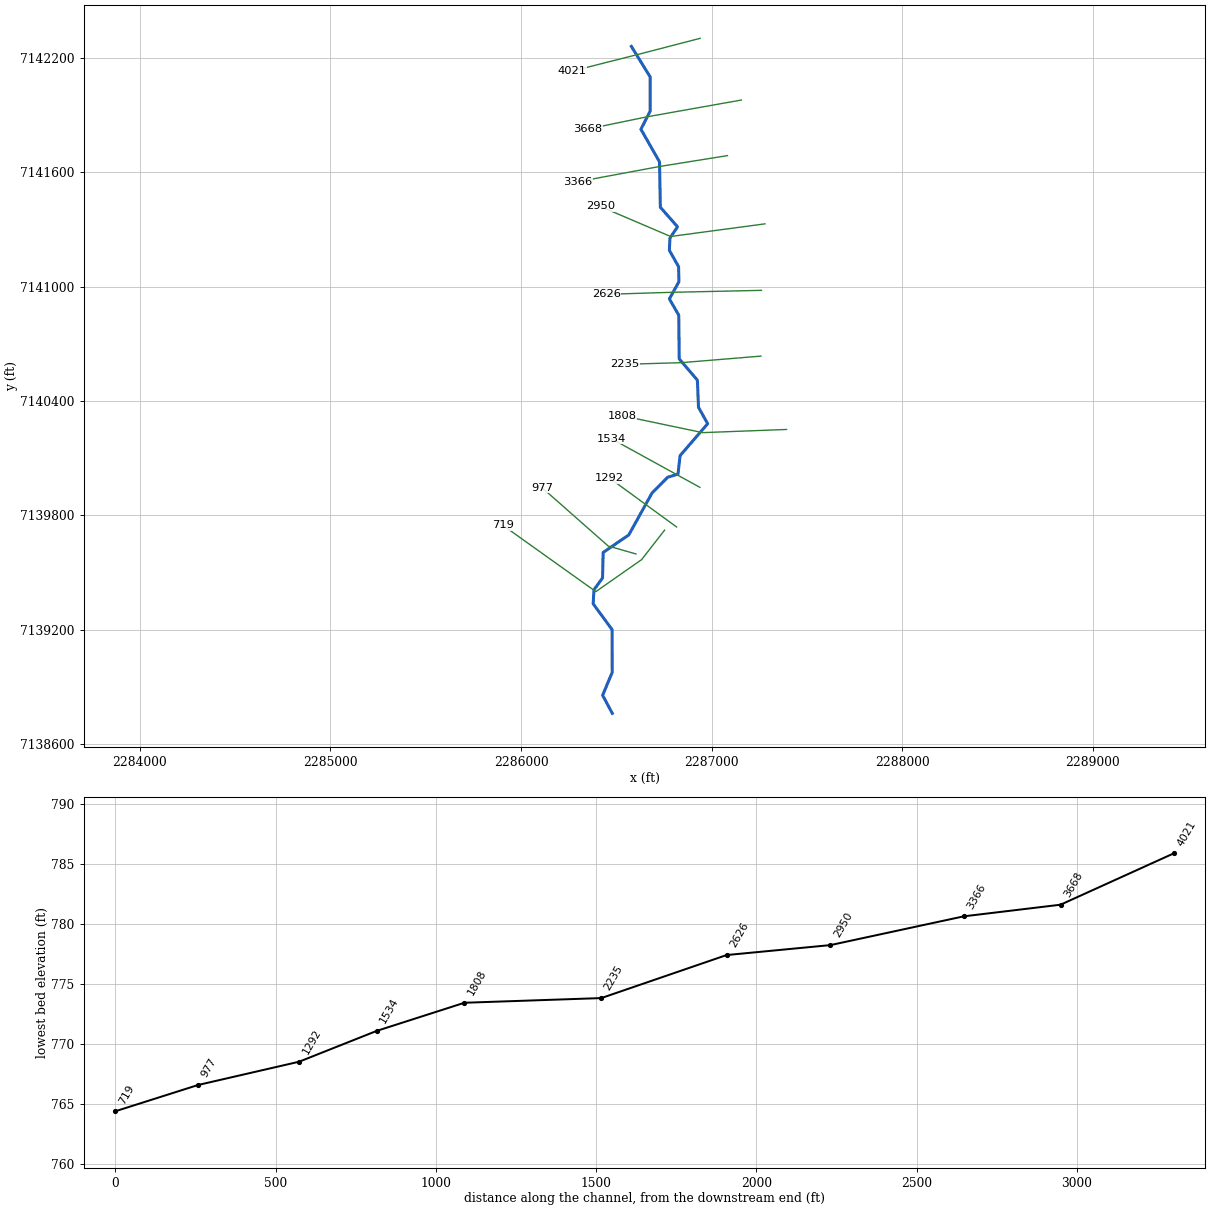
--- MDW T 099.prj (project) ---

Proj Title=MDW T 099 Base Level Engineering
Current Plan=p01
Default Exp/Contr=0.3,0.1
English Units
Geom File=g01
Flow File=f01
Plan File=p01
BEGIN DESCRIPTION:
MDW T 099
END DESCRIPTION:

--- MDW T 099.p01 (plan) ---

Plan Title=Multiple Run
Short Identifier=Multiple
Geom File=g01
Flow File=f01
Subcritical Flow
K Sum by GR= 0
Std Step Tol= 0.01
Critical Tol= 0.01
Num of Std Step Trials= 20
Max Error Tol= 0.3
Flow Tol Ratio= 0.001
Split Flow NTrial= 30
Split Flow Tol= 0.02
Split Flow Ratio= 0.02
Log Output Level= 0
Friction Slope Method= 1
Unsteady Friction Slope Method= 2
Unsteady Bridges Friction Slope Method= 1
Parabolic Critical Depth
Global Vel Dist=  1 , 1 , 1
Global Log Level= 0
CheckData=True
Encroach Param= -1, 0, 0, 0
BEGIN DESCRIPTION:
Multiple Run
END DESCRIPTION:

--- MDW T 099.f01 (steady flow) ---

Flow Title=Multiple
Number of Profiles=7
Profile Names=10-year,25-year,50-year,1pct_min,100-year,1pct_plu,500-year
River Rch & RM= MDW T 099,Reach-1,4021
     548     749     915     556    1110    2215    1635
Boundary for River Rch & Prof#=MDW T 099,Reach-1,1
Up Type=0
Dn Type=3
Dn Slope=0.005
Boundary for River Rch & Prof#=MDW T 099,Reach-1,2
Up Type=0
Dn Type=3
Dn Slope=0.005
Boundary for River Rch & Prof#=MDW T 099,Reach-1,3
Up Type=0
Dn Type=3
Dn Slope=0.005
Boundary for River Rch & Prof#=MDW T 099,Reach-1,4
Up Type=0
Dn Type=3
Dn Slope=0.005
Boundary for River Rch & Prof#=MDW T 099,Reach-1,5
Up Type=0
Dn Type=3
Dn Slope=0.005
Boundary for River Rch & Prof#=MDW T 099,Reach-1,6
Up Type=0
Dn Type=3
Dn Slope=0.005
Boundary for River Rch & Prof#=MDW T 099,Reach-1,7
Up Type=0
Dn Type=3
Dn Slope=0.005

--- MDW T 099.g01 (geometry) ---

Geom Title=Existing Conditions

River Reach=MDW T 099,Reach-1
Reach XY= 30
      2286579.00      7142260.00      2286677.81      7142099.51
      2286677.76      7141920.50      2286629.08      7141825.39
      2286726.76      7141654.07      2286731.08      7141415.85
      2286821.19      7141313.41      2286781.37      7141254.11
      2286778.42      7141189.96      2286826.83      7141104.03
      2286828.60      7141025.27      2286778.60      7140935.00
      2286827.76      7140849.50      2286830.06      7140620.44
      2286925.44      7140508.53      2286931.30      7140365.93
      2286979.40      7140280.13      2286834.55      7140112.37
      2286823.74      7140015.47      2286769.60      7139999.11
      2286687.15      7139916.06      2286565.51      7139696.44
      2286430.99      7139604.32      2286427.77      7139470.51
      2286382.70      7139408.40      2286378.51      7139334.96
      2286477.94      7139199.56      2286478.48      7138975.22
      2286428.19      7138855.01      2286479.00      7138760.00

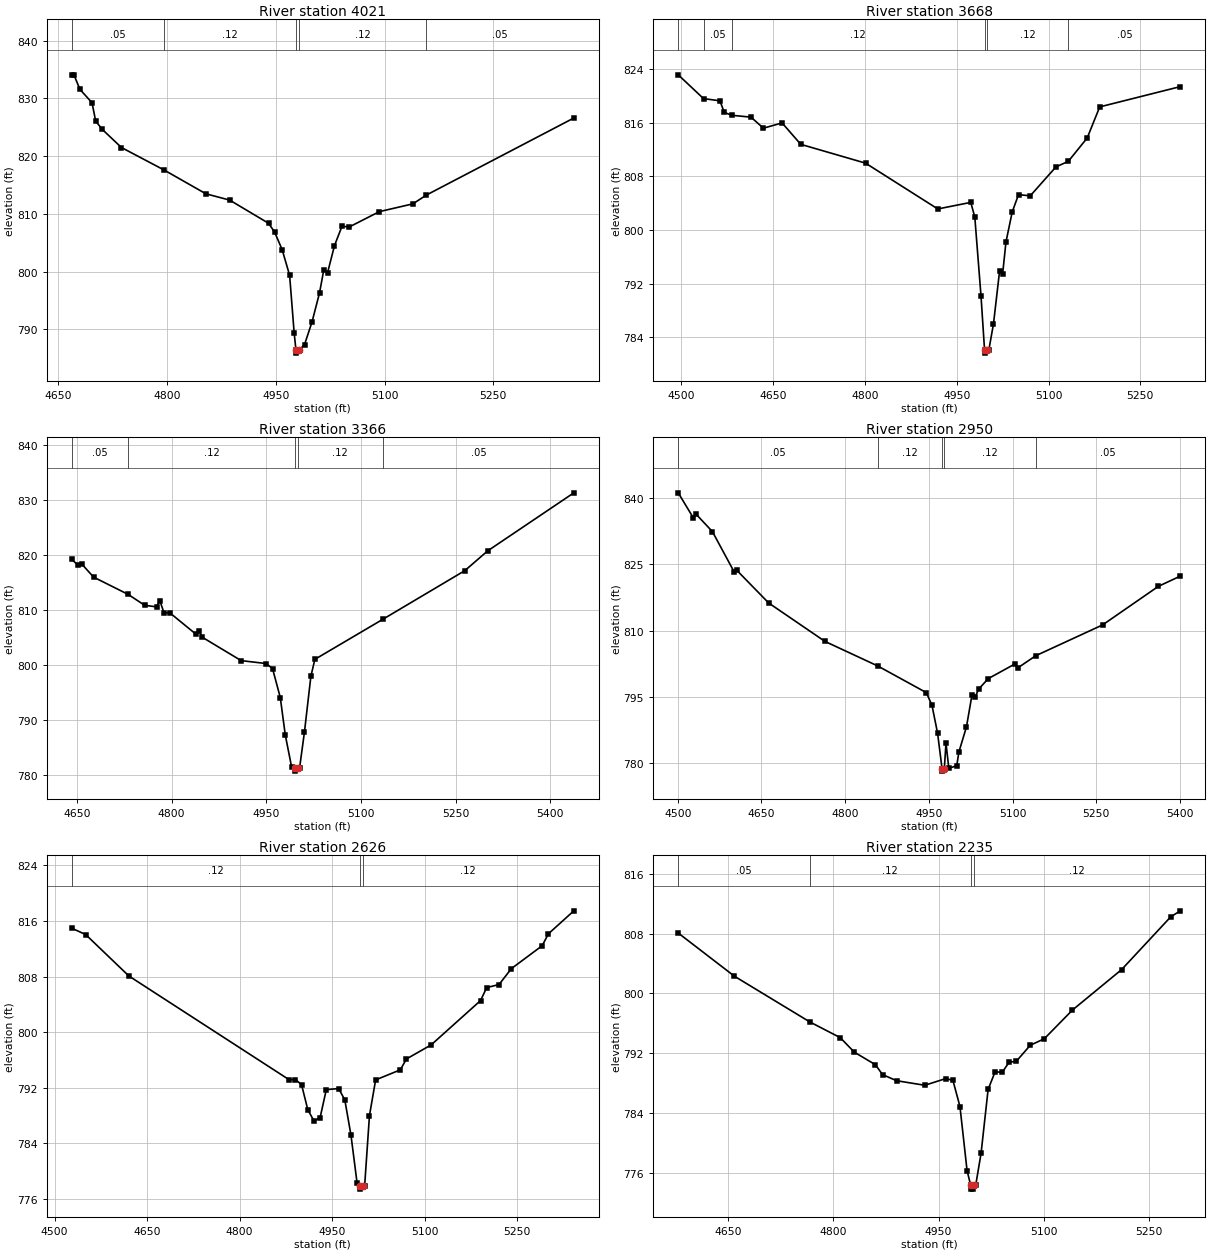
Type RM Length L Ch R = 1,4021,353,353,353
BEGIN DESCRIPTION:
MDW T 099 6.0
END DESCRIPTION:
XS GIS Cut Line= 3
      2286939.88      7142302.28      2286635.22      7142223.30
      2286268.94      7142130.42
#Sta/Elev= 30
  4668.5  834.10  4671.5  834.10  4679.7  831.59  4696.4  829.27  4701.5  826.08
  4710.7  824.63  4737.0  821.51  4795.6  817.63  4853.5  813.49  4886.3  812.40
  4939.9  808.39  4948.3  806.86  4958.7  803.82  4969.0  799.38  4975.3  789.37
  4977.8  786.39  4978.1  785.89  4981.8  786.39  4989.6  787.37  5000.0  791.33
  5010.3  796.34  5016.2  800.35  5021.4  799.83  5030.9  804.51  5041.2  807.85
  5051.5  807.76  5092.8  810.40  5139.1  811.75  5157.8  813.28  5361.1  826.62
#Mann=5,-1,0
  4668.5    0.05       0  4795.6    0.12       0  4977.8    0.07       0
  4981.8    0.12       0  5157.8    0.05       0
Bank Sta=4977.8,4981.8
Exp/Cntr=0.3,0.1

Type RM Length L Ch R = 1,3668,302,302,302
BEGIN DESCRIPTION:
MDW T 099 5.0
END DESCRIPTION:
XS GIS Cut Line= 3
      2287156.08      7141978.51      2286658.80      7141890.00
      2286350.03      7141826.15
#Sta/Elev= 30
  4494.9  823.17  4536.2  819.62  4563.0  819.29  4570.1  817.57  4582.1  817.13
  4613.8  816.85  4634.1  815.20  4664.6  815.99  4695.1  812.79  4801.0  809.98
  4919.0  803.14  4972.9  804.12  4979.5  801.92  4989.6  790.19  4995.4  782.11
  4995.6  781.61  4999.4  782.11  5002.5  782.11  5010.0  785.97  5019.9  793.80
  5025.0  793.48  5030.4  798.20  5040.6  802.68  5050.9  805.28  5070.1  805.10
  5112.1  809.42  5132.3  810.25  5163.2  813.75  5183.6  818.38  5315.3  821.41
#Mann=6,-1,0
  4494.9    0.12       0  4536.2    0.05       0  4582.1    0.12       0
  4995.4    0.07       0  4999.4    0.12       0  5132.3    0.05       0
Bank Sta=4995.4,4999.4
Exp/Cntr=0.3,0.1

Type RM Length L Ch R = 1,3366,416,416,416
BEGIN DESCRIPTION:
MDW T 099 4.0
END DESCRIPTION:
XS GIS Cut Line= 3
      2287083.15      7141686.84      2286729.36      7141630.15
      2286299.25      7141550.11
#Sta/Elev= 30
  4641.7  819.20  4652.1  818.08  4657.2  818.39  4676.3  815.96  4731.0  812.82
  4757.3  810.83  4776.1  810.55  4781.2  811.70  4787.7  809.52  4797.8  809.40
  4838.1  805.61  4843.2  806.24  4848.5  805.02  4910.2  800.76  4949.7  800.23
  4959.9  799.32  4972.2  794.04  4980.1  787.23  4990.2  781.37  4995.7  781.14
  4995.9  780.64  4999.7  781.14  5002.7  781.14  5010.5  787.76  5020.7  797.91
  5027.0  800.99  5134.7  808.28  5264.8  817.15  5300.9  820.74  5437.5  831.31
#Mann=5,-1,0
  4641.7    0.05       0  4731.0    0.12       0  4995.7    0.07       0
  4999.7    0.12       0  5134.7    0.05       0
Bank Sta=4995.7,4999.7
Exp/Cntr=0.3,0.1

Type RM Length L Ch R = 1,2950,324,324,324
BEGIN DESCRIPTION:
MDW T 099 3.0
END DESCRIPTION:
XS GIS Cut Line= 3
      2287279.74      7141328.76      2286784.97      7141262.43
      2286416.51      7141419.89
#Sta/Elev= 30
  4500.8  841.10  4527.9  835.44  4533.0  836.25  4562.1  832.33  4600.9  823.27
  4605.9  823.58  4663.0  816.21  4763.9  807.53  4858.3  802.00  4945.5  795.97
  4955.6  793.10  4965.7  786.76  4973.7  778.74  4973.9  778.24  4977.7  778.74
  4980.7  784.57  4985.8  778.87  5000.0  779.47  5003.8  782.54  5017.4  788.24
  5027.4  795.51  5032.8  794.88  5039.1  796.74  5056.4  799.13  5103.6  802.40
  5109.1  801.53  5141.5  804.30  5261.5  811.27  5361.4  819.98  5400.7  822.29
#Mann=5,-1,0
  4500.8    0.05       0  4858.3    0.12       0  4973.7    0.07       0
  4977.7    0.12       0  5141.5    0.05       0
Bank Sta=4973.7,4977.7
Exp/Cntr=0.3,0.1

Type RM Length L Ch R = 1,2626,391,391,391
BEGIN DESCRIPTION:
MDW T 099 2.0
END DESCRIPTION:
XS GIS Cut Line= 3
      2287261.56      7140979.81      2286789.57      7140969.53
      2286447.73      7140958.97
#Sta/Elev= 30
  4527.9  814.97  4550.5  814.05  4620.5  808.09  4880.5  793.15  4890.5  793.19
  4900.5  792.44  4910.6  788.85  4920.6  787.22  4930.6  787.71  4940.6  791.73
  4960.6  791.89  4970.6  790.27  4980.6  785.19  4990.6  778.23  4995.8  777.91
  4996.0  777.41  4999.8  777.91  5002.8  777.91  5010.6  788.00  5020.6  793.13
  5060.6  794.58  5070.6  796.15  5110.6  798.17  5190.7  804.55  5200.7  806.42
  5220.7  806.86  5240.7  809.15  5290.7  812.45  5300.7  814.16  5342.0  817.47
#Mann=3,-1,0
  4527.9    0.12       0  4995.8    0.07       0  4999.8    0.12       0
Bank Sta=4995.8,4999.8
Exp/Cntr=0.3,0.1

Type RM Length L Ch R = 1,2235,427,427,427
BEGIN DESCRIPTION:
MDW T 099 1.0
END DESCRIPTION:
XS GIS Cut Line= 3
      2287258.88      7140634.75      2286839.50      7140600.21
      2286545.42      7140591.79
#Sta/Elev= 30
  4579.2  808.07  4659.3  802.29  4766.6  796.18  4809.9  794.08  4829.9  792.14
  4860.0  790.46  4870.1  789.14  4890.1  788.32  4930.3  787.71  4960.4  788.61
  4970.4  788.36  4980.4  784.86  4990.5  776.31  4995.7  774.32  4996.0  773.82
  4999.5  773.82  4999.7  774.32  5002.8  774.32  5010.5  778.64  5020.5  787.16
  5030.5  789.52  5040.5  789.43  5050.5  790.81  5060.5  790.90  5080.5  793.06
  5100.5  793.93  5140.6  797.77  5210.6  803.18  5280.6  810.24  5294.2  811.04
#Mann=4,-1,0
  4579.2    0.05       0  4766.6    0.12       0  4995.7    0.07       0
  4999.7    0.12       0
Bank Sta=4995.7,4999.7
Exp/Cntr=0.3,0.1

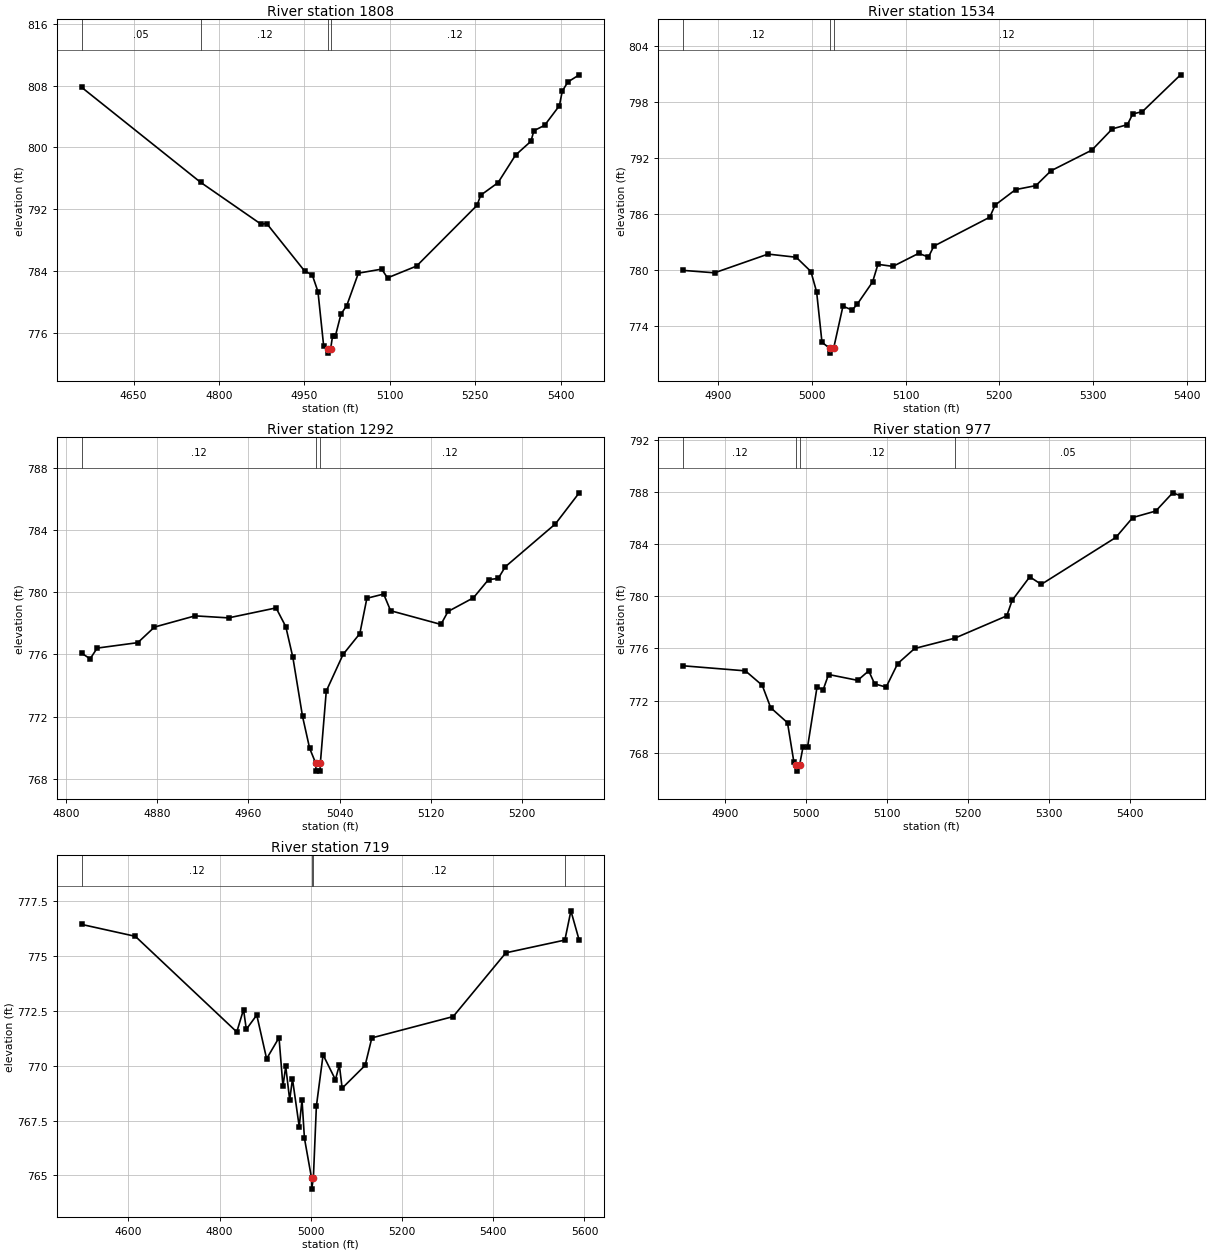
Type RM Length L Ch R = 1,1808,274,274,274
BEGIN DESCRIPTION:
MDW T 099 0.9
END DESCRIPTION:
XS GIS Cut Line= 3
      2287393.44      7140249.86      2286952.96      7140233.18
      2286529.59      7140322.08
#Sta/Elev= 30
  4559.2  807.75  4767.9  795.49  4873.9  790.09  4883.9  790.17  4950.4  784.04
  4963.9  783.53  4973.9  781.37  4983.9  774.36  4992.0  773.93  4992.2  773.43
  4996.0  773.93  4999.5  775.62  5004.4  775.62  5014.3  778.47  5024.5  779.58
  5044.9  783.76  5085.8  784.28  5096.0  783.15  5147.1  784.68  5253.3  792.53
  5259.5  793.82  5290.1  795.45  5320.8  799.01  5347.9  800.80  5353.0  802.16
  5371.9  802.86  5397.8  805.39  5402.9  807.28  5412.8  808.46  5432.6  809.38
#Mann=4,-1,0
  4559.2    0.05       0  4767.9    0.12       0  4992.0    0.07       0
  4996.0    0.12       0
Bank Sta=4992,4996
Exp/Cntr=0.3,0.1

Type RM Length L Ch R = 1,1534,242,242,242
BEGIN DESCRIPTION:
Mapping XS e771aee8
END DESCRIPTION:
XS GIS Cut Line= 2
      2286938.40      7139946.16      2286473.52      7140201.93
#Sta/Elev= 30
  4862.7  779.96  4896.2  779.70  4953.3  781.71  4983.3  781.37  4999.0  779.84
  5005.1  777.65  5010.8  772.25  5019.2  771.58  5019.4  771.08  5023.2  771.58
  5033.2  776.12  5043.0  775.70  5048.7  776.37  5064.8  778.72  5070.5  780.61
  5086.5  780.39  5114.0  781.79  5124.4  781.39  5130.1  782.56  5189.8  785.67
  5195.5  786.97  5217.3  788.63  5239.0  789.06  5255.1  790.65  5298.7  792.87
  5320.5  795.15  5336.6  795.60  5342.3  796.75  5352.6  797.00  5393.3  800.95
#Mann=3,-1,0
  4862.7    0.12       0  5019.2    0.07       0  5023.2    0.12       0
Bank Sta=5019.2,5023.2
Exp/Cntr=0.3,0.1

Type RM Length L Ch R = 1,1292,315,315,315
BEGIN DESCRIPTION:
Mapping XS 905a6858
END DESCRIPTION:
XS GIS Cut Line= 2
      2286816.31      7139738.05      2286464.08      7139995.01
#Sta/Elev= 30
  4814.0  776.08  4821.3  775.72  4827.5  776.41  4863.1  776.76  4877.7  777.76
  4913.3  778.48  4942.6  778.35  4984.3  778.99  4992.8  777.79  4999.0  775.82
  5007.5  772.02  5013.7  769.98  5019.1  769.01  5019.3  768.51  5022.8  768.51
  5023.1  769.01  5028.3  773.65  5043.0  776.00  5057.7  777.34  5063.9  779.61
  5078.6  779.88  5084.7  778.81  5128.8  777.93  5135.0  778.76  5157.3  779.64
  5170.5  780.81  5179.0  780.88  5185.2  781.63  5229.2  784.39  5250.0  786.38
#Mann=3,-1,0
  4814.0    0.12       0  5019.1    0.07       0  5023.1    0.12       0
Bank Sta=5019.1,5023.1
Exp/Cntr=0.3,0.1

Type RM Length L Ch R = 1,977,258,258,258
BEGIN DESCRIPTION:
Mapping XS 1044a61f
END DESCRIPTION:
XS GIS Cut Line= 3
      2286602.93      7139596.63      2286457.21      7139638.42
      2286110.11      7139944.39
#Sta/Elev= 30
  4847.8  774.67  4924.7  774.28  4945.5  773.17  4955.9  771.45  4976.7  770.29
  4984.5  767.30  4987.7  767.07  4987.9  766.57  4991.7  767.07  4995.9  768.43
  5001.5  768.43  5013.2  773.05  5020.7  772.82  5027.4  774.00  5063.4  773.55
  5077.0  774.28  5084.3  773.28  5098.5  773.03  5112.8  774.84  5133.7  776.00
  5183.1  776.79  5247.5  778.51  5254.1  779.70  5275.9  781.51  5290.1  780.93
  5382.2  784.54  5403.1  786.07  5431.5  786.57  5452.4  787.97  5462.1  787.75
#Mann=4,-1,0
  4847.8    0.12       0  4987.7    0.07       0  4991.7    0.12       0
  5183.1    0.05       0
Bank Sta=4987.7,4991.7
Exp/Cntr=0.3,0.1

Type RM Length L Ch R = 1,719,0,0,0
BEGIN DESCRIPTION:
MDW T 099 0.7
END DESCRIPTION:
XS GIS Cut Line= 4
      2286753.31      7139721.30      2286632.91      7139566.93
      2286392.68      7139398.91      2285902.88      7139748.18
#Sta/Elev= 30
  4498.0  776.42  4615.4  775.88  4837.8  771.53  4852.6  772.55  4858.7  771.65
  4881.6  772.30  4903.2  770.31  4930.4  771.27  4939.0  769.06  4945.1  769.96
  4953.8  768.44  4959.9  769.39  4974.7  767.22  4980.8  768.44  4986.1  766.70
  5001.7  764.88  5002.0  764.38  5005.7  764.88  5012.3  768.15  5027.0  770.49
  5054.0  769.36  5062.7  770.02  5068.8  768.97  5119.2  770.01  5133.9  771.26
  5312.2  772.23  5427.7  775.13  5557.1  775.71  5570.3  777.04  5588.5  775.70
#Mann=4,-1,0
  4498.0    0.12       0  5001.7    0.07       0  5005.7    0.12       0
  5557.1    0.05       0
Bank Sta=5001.7,5005.7
Exp/Cntr=0.3,0.1

Chan Stop Cuts=-1