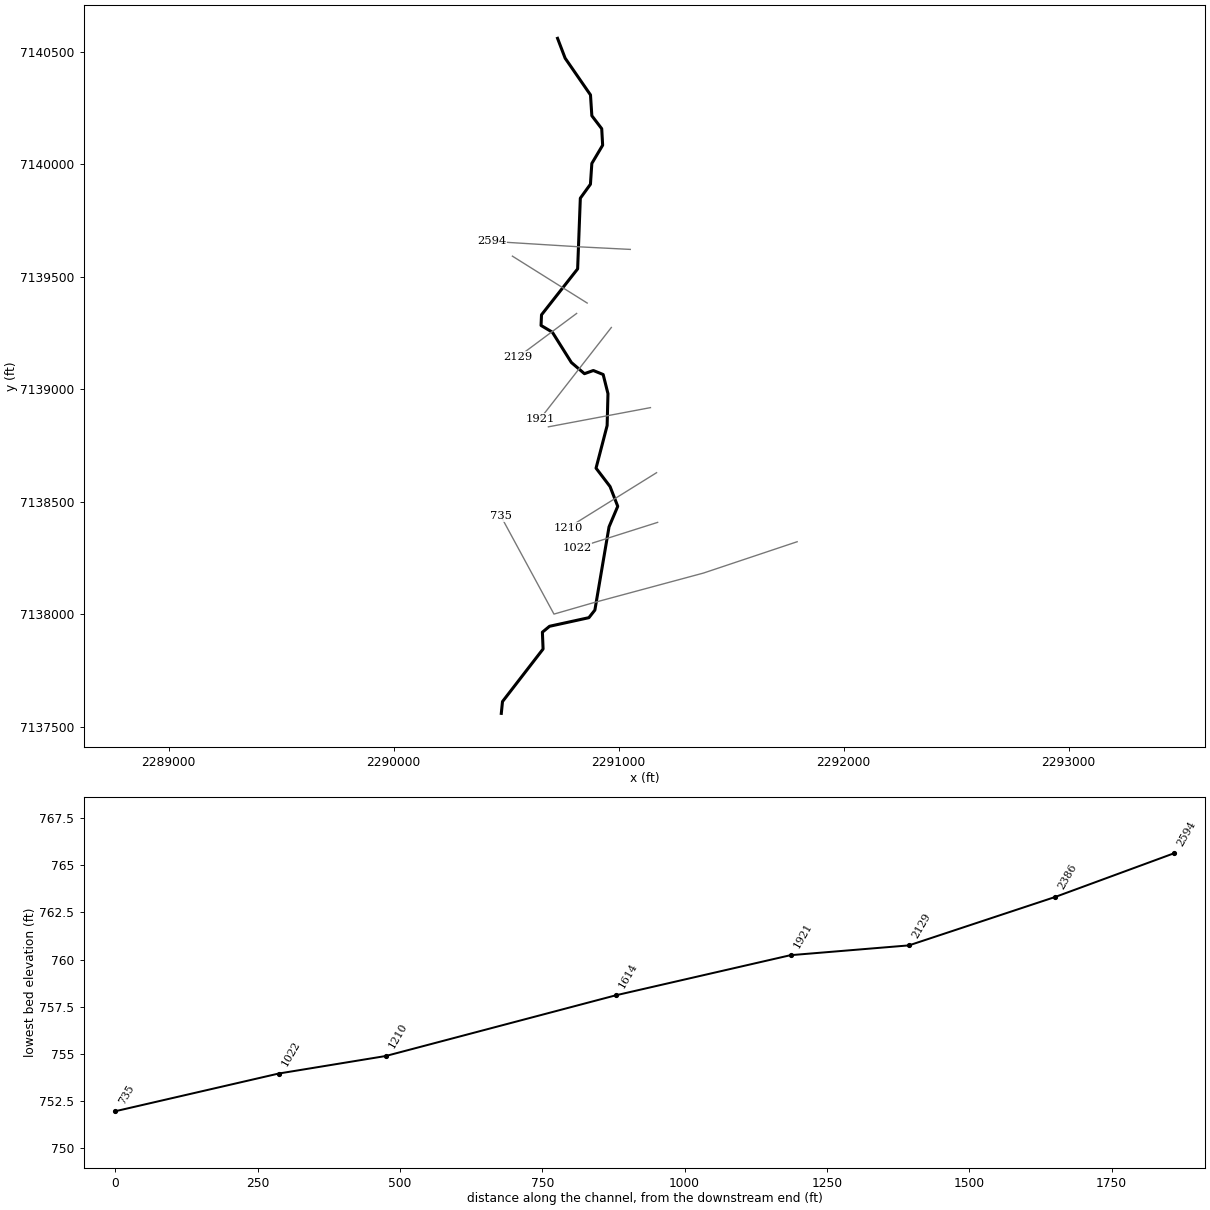
--- MDW T 100.prj (project) ---

Proj Title=MDW T 100 Base Level Engineering
Current Plan=p01
Default Exp/Contr=0.3,0.1
English Units
Geom File=g01
Flow File=f01
Plan File=p01
BEGIN DESCRIPTION:
MDW T 100
END DESCRIPTION:

--- MDW T 100.p01 (plan) ---

Plan Title=Multiple Run
Short Identifier=Multiple
Geom File=g01
Flow File=f01
Subcritical Flow
K Sum by GR= 0
Std Step Tol= 0.01
Critical Tol= 0.01
Num of Std Step Trials= 20
Max Error Tol= 0.3
Flow Tol Ratio= 0.001
Split Flow NTrial= 30
Split Flow Tol= 0.02
Split Flow Ratio= 0.02
Log Output Level= 0
Friction Slope Method= 1
Unsteady Friction Slope Method= 2
Unsteady Bridges Friction Slope Method= 1
Parabolic Critical Depth
Global Vel Dist=  1 , 1 , 1
Global Log Level= 0
CheckData=True
Encroach Param= -1, 0, 0, 0
BEGIN DESCRIPTION:
Multiple Run
END DESCRIPTION:

--- MDW T 100.f01 (steady flow) ---

Flow Title=Multiple
Number of Profiles=7
Profile Names=10-year,25-year,50-year,1pct_min,100-year,1pct_plu,500-year
River Rch & RM= MDW T 100,Reach-1,2594
     594     818    1005     614    1224    2443    1821
Boundary for River Rch & Prof#=MDW T 100,Reach-1,1
Up Type=0
Dn Type=3
Dn Slope=0.005
Boundary for River Rch & Prof#=MDW T 100,Reach-1,2
Up Type=0
Dn Type=3
Dn Slope=0.005
Boundary for River Rch & Prof#=MDW T 100,Reach-1,3
Up Type=0
Dn Type=3
Dn Slope=0.005
Boundary for River Rch & Prof#=MDW T 100,Reach-1,4
Up Type=0
Dn Type=3
Dn Slope=0.005
Boundary for River Rch & Prof#=MDW T 100,Reach-1,5
Up Type=0
Dn Type=3
Dn Slope=0.005
Boundary for River Rch & Prof#=MDW T 100,Reach-1,6
Up Type=0
Dn Type=3
Dn Slope=0.005
Boundary for River Rch & Prof#=MDW T 100,Reach-1,7
Up Type=0
Dn Type=3
Dn Slope=0.005

--- MDW T 100.g01 (geometry) ---

Geom Title=Existing Conditions

River Reach=MDW T 100,Reach-1
Reach XY= 30
      2290729.00      7140560.00      2290762.76      7140471.69
      2290875.39      7140308.50      2290881.36      7140215.98
      2290925.30      7140158.40      2290929.40      7140085.00
      2290881.36      7140004.03      2290875.14      7139911.60
      2290830.22      7139849.50      2290818.23      7139535.47
      2290657.73      7139331.27      2290655.65      7139284.03
      2290705.86      7139254.07      2290790.41      7139119.36
      2290848.50      7139069.67      2290888.03      7139083.78
      2290931.73      7139065.94      2290953.06      7138980.85
      2290949.36      7138839.16      2290900.07      7138649.78
      2290962.32      7138568.15      2290996.48      7138480.15
      2290957.78      7138388.88      2290894.88      7138019.12
      2290868.34      7137985.34      2290693.38      7137947.03
      2290661.64      7137920.82      2290664.67      7137846.05
      2290484.33      7137612.51      2290479.00      7137560.00

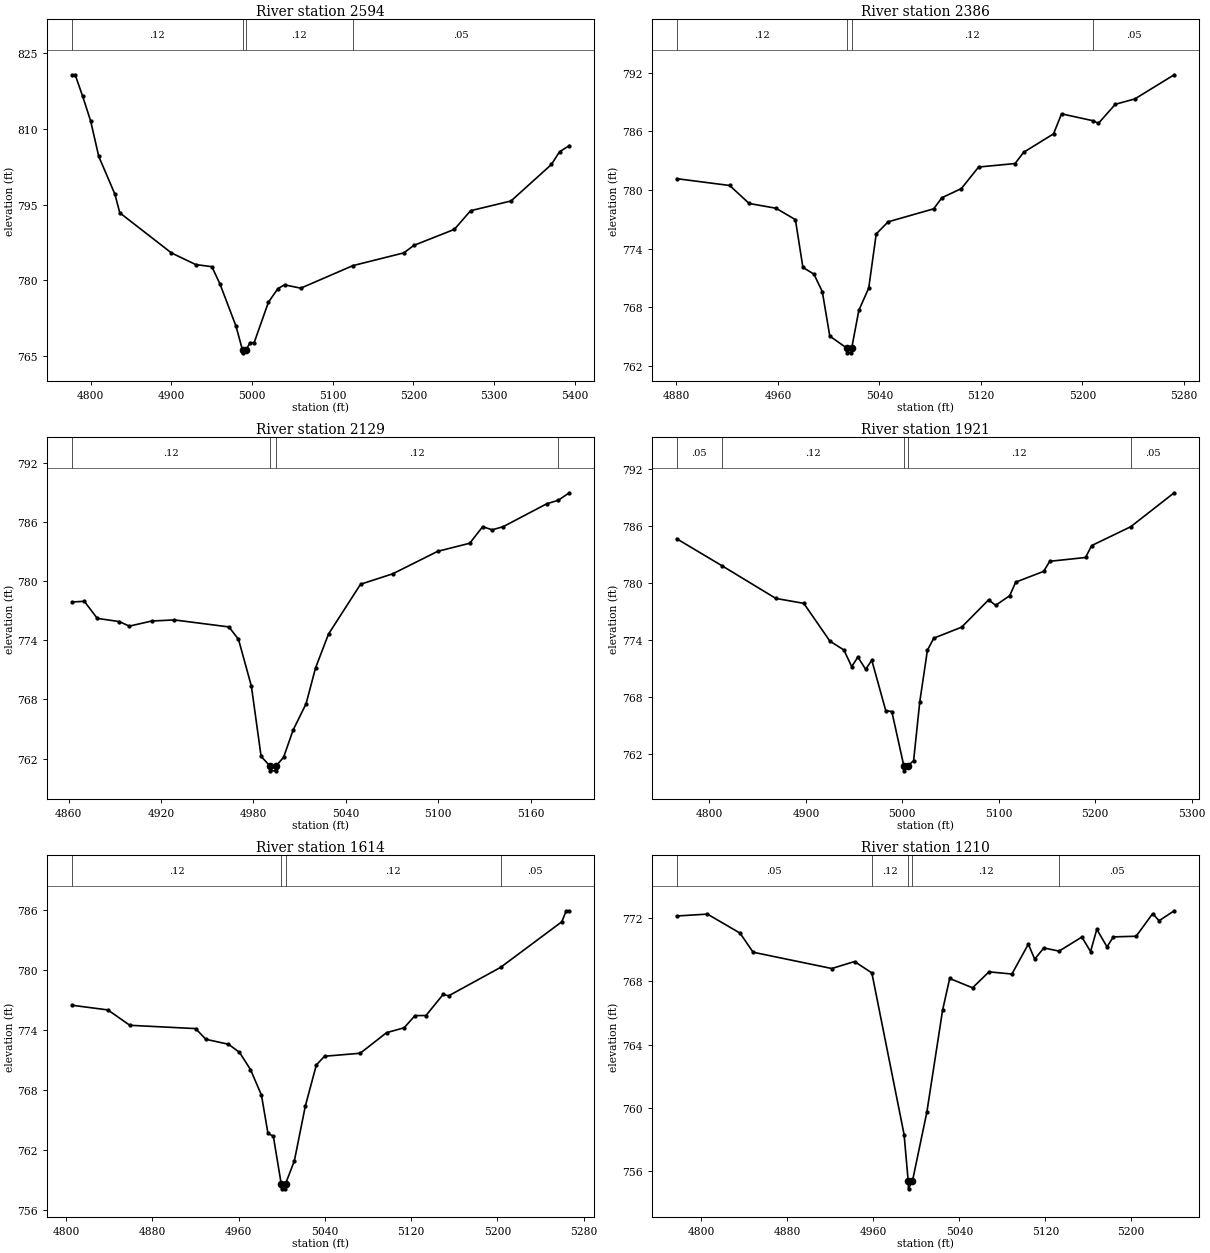
Type RM Length L Ch R = 1,2594,208,208,208
BEGIN DESCRIPTION:
MDW T 100 6.0
END DESCRIPTION:
XS GIS Cut Line= 3
      2291052.27      7139621.95      2290829.25      7139633.22
      2290436.81      7139657.54
#Sta/Elev= 30
  4776.7  820.76  4780.8  820.76  4790.0  816.54  4800.0  811.59  4810.0  804.59
  4830.0  797.10  4836.1  793.39  4900.1  785.44  4930.2  783.13  4950.2  782.71
  4960.2  779.30  4980.2  770.88  4988.2  766.13  4988.5  765.63  4992.2  766.13
  4997.6  767.65  5002.6  767.65  5020.3  775.67  5032.1  778.38  5040.3  779.11
  5060.4  778.45  5124.9  782.92  5188.1  785.45  5200.6  786.94  5250.7  790.11
  5270.8  793.81  5320.9  795.74  5371.0  802.98  5381.0  805.49  5393.2  806.72
#Mann=4,-1,0
  4776.7    0.12       0  4988.2    0.07       0  4992.2    0.12       0
  5124.9    0.05       0
Bank Sta=4988.2,4992.2
Exp/Cntr=0.3,0.1

Type RM Length L Ch R = 1,2386,257,257,257
BEGIN DESCRIPTION:
Mapping XS 9d5ca9a4
END DESCRIPTION:
XS GIS Cut Line= 2
      2290860.66      7139383.60      2290528.40      7139591.98
#Sta/Elev= 30
  4880.2  781.16  4922.0  780.46  4937.3  778.62  4958.5  778.13  4973.8  776.96
  4979.7  772.07  4988.4  771.38  4995.0  769.59  5000.9  765.03  5014.2  763.82
  5014.5  763.32  5018.0  763.32  5018.2  763.82  5023.8  767.67  5031.6  769.96
  5037.5  775.50  5046.9  776.74  5082.8  778.07  5089.3  779.21  5104.6  780.14
  5118.2  782.35  5147.0  782.71  5153.7  783.86  5177.3  785.75  5183.6  787.80
  5208.5  787.09  5212.7  786.83  5226.0  788.78  5241.3  789.32  5272.4  791.80
#Mann=4,-1,0
  4880.2    0.12       0  5014.2    0.07       0  5018.2    0.12       0
  5208.5    0.05       0
Bank Sta=5014.2,5018.2
Exp/Cntr=0.3,0.1

Type RM Length L Ch R = 1,2129,208,208,208
BEGIN DESCRIPTION:
Mapping XS 0d130ba0
END DESCRIPTION:
XS GIS Cut Line= 2
      2290813.80      7139337.40      2290554.50      7139144.63
#Sta/Elev= 30
  4862.1  777.88  4870.2  777.95  4878.6  776.22  4893.0  775.89  4899.4  775.43
  4914.0  775.95  4928.7  776.06  4964.1  775.35  4970.3  774.10  4978.7  769.34
  4985.0  762.22  4990.7  761.25  4990.9  760.75  4994.4  760.75  4994.7  761.25
  4999.6  762.12  5005.8  764.89  5014.2  767.55  5020.4  771.21  5028.8  774.63
  5049.6  779.68  5070.5  780.74  5099.7  783.02  5120.5  783.84  5128.9  785.52
  5135.1  785.20  5142.2  785.52  5170.6  787.85  5178.0  788.20  5185.2  788.96
#Mann=4,-1,0
  4862.1    0.12       0  4990.7    0.07       0  4994.7    0.12       0
  5178.0    0.05       0
Bank Sta=4990.7,4994.7
Exp/Cntr=0.3,0.1

Type RM Length L Ch R = 1,1921,307,307,307
BEGIN DESCRIPTION:
Mapping XS 4e0ed3ab
END DESCRIPTION:
XS GIS Cut Line= 2
      2290968.05      7139275.02      2290650.86      7138868.15
#Sta/Elev= 30
  4766.0  784.62  4813.0  781.78  4868.8  778.35  4897.8  777.83  4924.9  773.86
  4939.4  772.93  4947.5  771.18  4953.9  772.19  4962.0  770.89  4968.3  771.86
  4982.8  766.56  4989.1  766.46  5001.6  760.73  5001.9  760.23  5005.6  760.73
  5011.7  761.31  5018.1  767.50  5026.0  772.90  5032.6  774.17  5061.5  775.33
  5089.4  778.19  5096.8  777.63  5111.3  778.63  5117.6  780.06  5146.5  781.19
  5152.9  782.25  5190.0  782.65  5196.3  783.90  5236.8  785.88  5281.9  789.45
#Mann=5,-1,0
  4766.0    0.05       0  4813.0    0.12       0  5001.6    0.07       0
  5005.6    0.12       0  5236.8    0.05       0
Bank Sta=5001.6,5005.6
Exp/Cntr=0.3,0.1

Type RM Length L Ch R = 1,1614,404,404,404
BEGIN DESCRIPTION:
Mapping XS 33ad4d14
END DESCRIPTION:
XS GIS Cut Line= 2
      2291141.85      7138918.78      2290688.30      7138833.48
#Sta/Elev= 30
  4805.3  776.49  4838.7  776.02  4859.1  774.48  4920.1  774.15  4929.6  773.08
  4950.6  772.58  4960.8  771.77  4971.0  770.05  4981.2  767.48  4987.2  763.66
  4992.2  763.37  4999.5  758.60  4999.8  758.10  5003.3  758.10  5003.5  758.60
  5011.7  760.90  5021.9  766.40  5032.1  770.51  5039.7  771.38  5072.8  771.68
  5097.2  773.74  5113.5  774.23  5123.6  775.45  5133.8  775.46  5149.7  777.57
  5154.8  777.43  5203.0  780.28  5259.8  784.85  5263.9  785.95  5266.8  785.95
#Mann=4,-1,0
  4805.3    0.12       0  4999.5    0.07       0  5003.5    0.12       0
  5203.0    0.05       0
Bank Sta=4999.5,5003.5
Exp/Cntr=0.3,0.1

Type RM Length L Ch R = 1,1210,188,188,188
BEGIN DESCRIPTION:
Mapping XS 4335b26d
END DESCRIPTION:
XS GIS Cut Line= 2
      2291169.04      7138629.63      2290776.04      7138385.03
#Sta/Elev= 30
  4777.0  772.13  4805.6  772.25  4835.9  771.05  4848.1  769.84  4921.3  768.81
  4942.5  769.25  4958.6  768.53  4988.6  758.31  4992.4  755.38  4992.7  754.88
  4996.4  755.38  5009.8  759.74  5024.4  766.17  5031.0  768.18  5052.3  767.59
  5067.6  768.60  5088.9  768.46  5104.2  770.35  5110.1  769.40  5118.6  770.11
  5132.8  769.91  5154.0  770.80  5162.1  769.88  5167.9  771.29  5177.4  770.18
  5183.3  770.81  5204.5  770.85  5219.9  772.28  5225.8  771.83  5239.9  772.46
#Mann=5,-1,0
  4777.0    0.05       0  4958.6    0.12       0  4992.4    0.07       0
  4996.4    0.12       0  5132.8    0.05       0
Bank Sta=4992.4,4996.4
Exp/Cntr=0.3,0.1

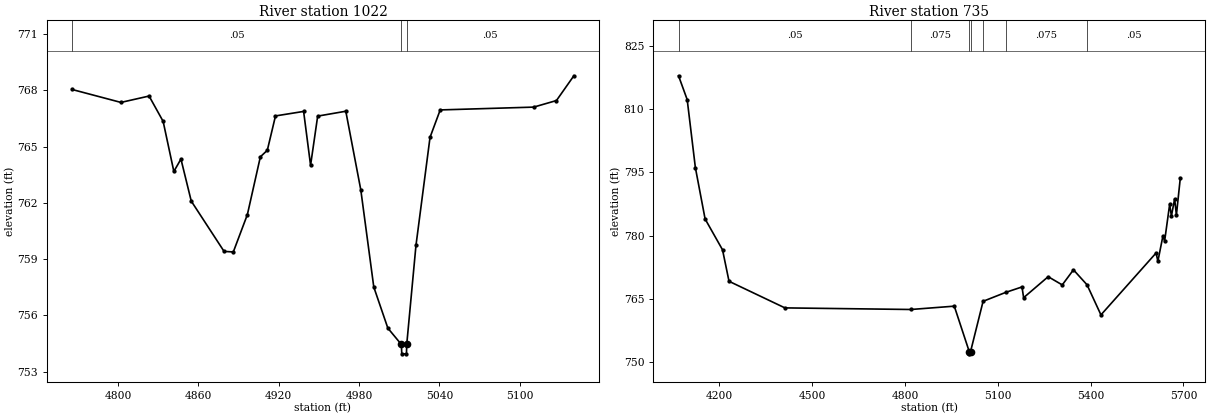
Type RM Length L Ch R = 1,1022,287,287,287
BEGIN DESCRIPTION:
Mapping XS c77364a6
END DESCRIPTION:
XS GIS Cut Line= 2
      2291173.81      7138408.81      2290816.63      7138295.57
#Sta/Elev= 30
  4765.7  768.04  4802.2  767.35  4823.2  767.69  4833.7  766.34  4841.7  763.67
  4847.0  764.33  4854.7  762.09  4879.2  759.41  4886.1  759.38  4896.6  761.37
  4906.3  764.45  4911.5  764.80  4917.6  766.63  4938.6  766.87  4943.8  764.00
  4949.1  766.62  4970.1  766.88  4981.3  762.69  4991.0  757.51  5001.5  755.32
  5011.6  754.45  5011.9  753.95  5015.4  753.95  5015.6  754.45  5022.5  759.73
  5033.0  765.49  5040.6  766.95  5110.4  767.10  5127.4  767.45  5140.4  768.77
#Mann=3,-1,0
  4765.7    0.05       0  5011.6   0.033       0  5015.6    0.05       0
Bank Sta=5011.6,5015.6
Exp/Cntr=0.3,0.1

Type RM Length L Ch R = 1,735,0,0,0
BEGIN DESCRIPTION:
MDW T 100 1.0
END DESCRIPTION:
XS GIS Cut Line= 5
      2291793.82      7138322.81      2291377.12      7138183.48
      2290889.83      7138052.18      2290713.06      7138001.19
      2290477.66      7138435.57
#Sta/Elev= 30
  4067.8  817.91  4095.8  812.25  4122.2  796.14  4153.7  783.94  4210.0  776.63
  4231.0  769.16  4411.7  762.85  4818.9  762.47  4959.2  763.26  5007.7  752.45
  5007.9  751.95  5011.7  752.45  5052.3  764.41  5125.2  766.52  5178.1  767.82
  5183.3  765.27  5262.7  770.25  5308.2  768.30  5344.4  771.88  5388.3  768.33
  5433.3  761.19  5611.6  775.88  5617.3  773.89  5633.5  779.86  5639.2  778.74
  5655.4  787.41  5661.1  784.65  5671.5  788.71  5677.2  784.88  5689.9  793.71
#Mann=7,-1,0
  4067.8    0.05       0  4818.9   0.075       0  5007.7    0.07       0
  5011.7   0.075       0  5052.3    0.12       0  5125.2   0.075       0
  5388.3    0.05       0
Bank Sta=5007.7,5011.7
Exp/Cntr=0.3,0.1

Chan Stop Cuts=-1