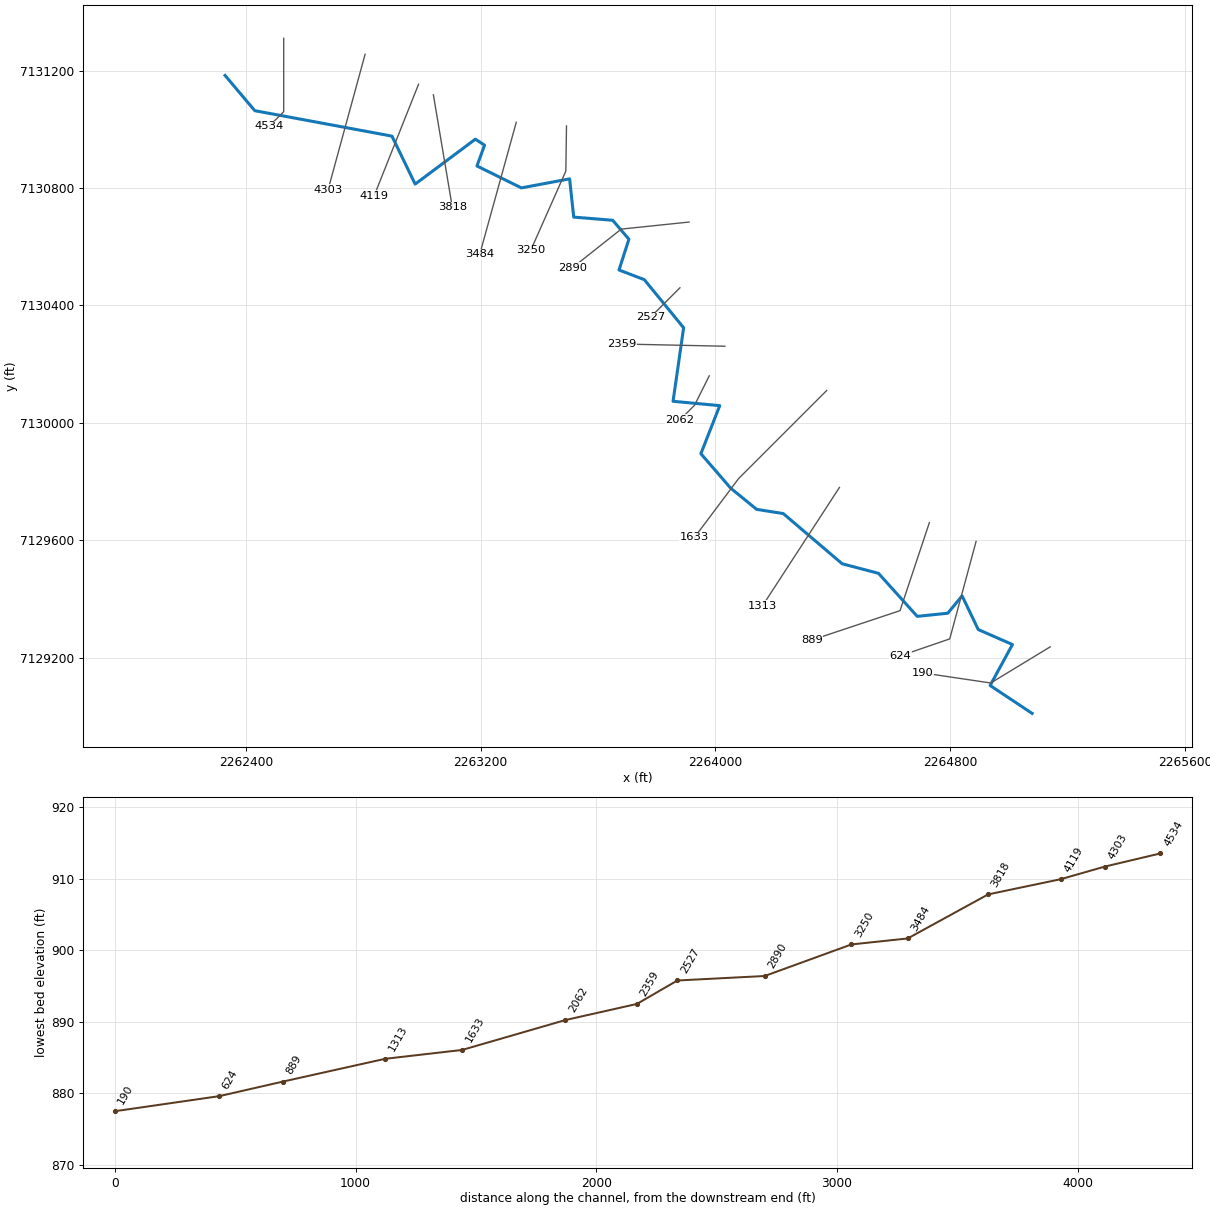
--- MDW T 102.prj (project) ---

Proj Title=MDW T 102 Base Level Engineering
Current Plan=p01
Default Exp/Contr=0.3,0.1
English Units
Geom File=g01
Flow File=f01
Plan File=p01
BEGIN DESCRIPTION:
MDW T 102
END DESCRIPTION:

--- MDW T 102.p01 (plan) ---

Plan Title=Multiple Run
Short Identifier=Multiple
Geom File=g01
Flow File=f01
Subcritical Flow
K Sum by GR= 0
Std Step Tol= 0.01
Critical Tol= 0.01
Num of Std Step Trials= 20
Max Error Tol= 0.3
Flow Tol Ratio= 0.001
Split Flow NTrial= 30
Split Flow Tol= 0.02
Split Flow Ratio= 0.02
Log Output Level= 0
Friction Slope Method= 1
Unsteady Friction Slope Method= 2
Unsteady Bridges Friction Slope Method= 1
Parabolic Critical Depth
Global Vel Dist=  1 , 1 , 1
Global Log Level= 0
CheckData=True
Encroach Param= -1, 0, 0, 0
BEGIN DESCRIPTION:
Multiple Run
END DESCRIPTION:

--- MDW T 102.f01 (steady flow) ---

Flow Title=Multiple
Number of Profiles=7
Profile Names=10-year,25-year,50-year,1pct_min,100-year,1pct_plu,500-year
River Rch & RM= MDW T 102,Reach-1,4534
     387     519     627     377     753    1502    1085
River Rch & RM= MDW T 102,Reach-1,2890
     691     961    1188     731    1458    2908    2196
Boundary for River Rch & Prof#=MDW T 102,Reach-1,1
Up Type=0
Dn Type=3
Dn Slope=0.005
Boundary for River Rch & Prof#=MDW T 102,Reach-1,2
Up Type=0
Dn Type=3
Dn Slope=0.005
Boundary for River Rch & Prof#=MDW T 102,Reach-1,3
Up Type=0
Dn Type=3
Dn Slope=0.005
Boundary for River Rch & Prof#=MDW T 102,Reach-1,4
Up Type=0
Dn Type=3
Dn Slope=0.005
Boundary for River Rch & Prof#=MDW T 102,Reach-1,5
Up Type=0
Dn Type=3
Dn Slope=0.005
Boundary for River Rch & Prof#=MDW T 102,Reach-1,6
Up Type=0
Dn Type=3
Dn Slope=0.005
Boundary for River Rch & Prof#=MDW T 102,Reach-1,7
Up Type=0
Dn Type=3
Dn Slope=0.005

--- MDW T 102.g01 (geometry) ---

Geom Title=Existing Conditions

River Reach=MDW T 102,Reach-1
Reach XY= 30
      2262329.28      7131183.55      2262430.45      7131063.53
      2262897.80      7130976.85      2262976.98      7130813.38
      2263182.11      7130966.41      2263213.37      7130946.03
      2263187.51      7130875.12      2263338.99      7130800.39
      2263503.20      7130831.26      2263517.19      7130700.90
      2263650.01      7130690.10      2263705.23      7130625.43
      2263671.47      7130520.73      2263757.68      7130487.81
      2263891.70      7130323.77      2263855.62      7130073.34
      2264014.77      7130058.49      2263950.48      7129894.80
      2264052.09      7129777.21      2264140.48      7129705.17
      2264231.09      7129690.78      2264431.90      7129519.74
      2264555.58      7129487.17      2264687.62      7129340.51
      2264791.71      7129351.25      2264840.51      7129410.42
      2264895.49      7129295.67      2265012.03      7129244.55
      2264936.02      7129105.03      2265079.00      7129010.00

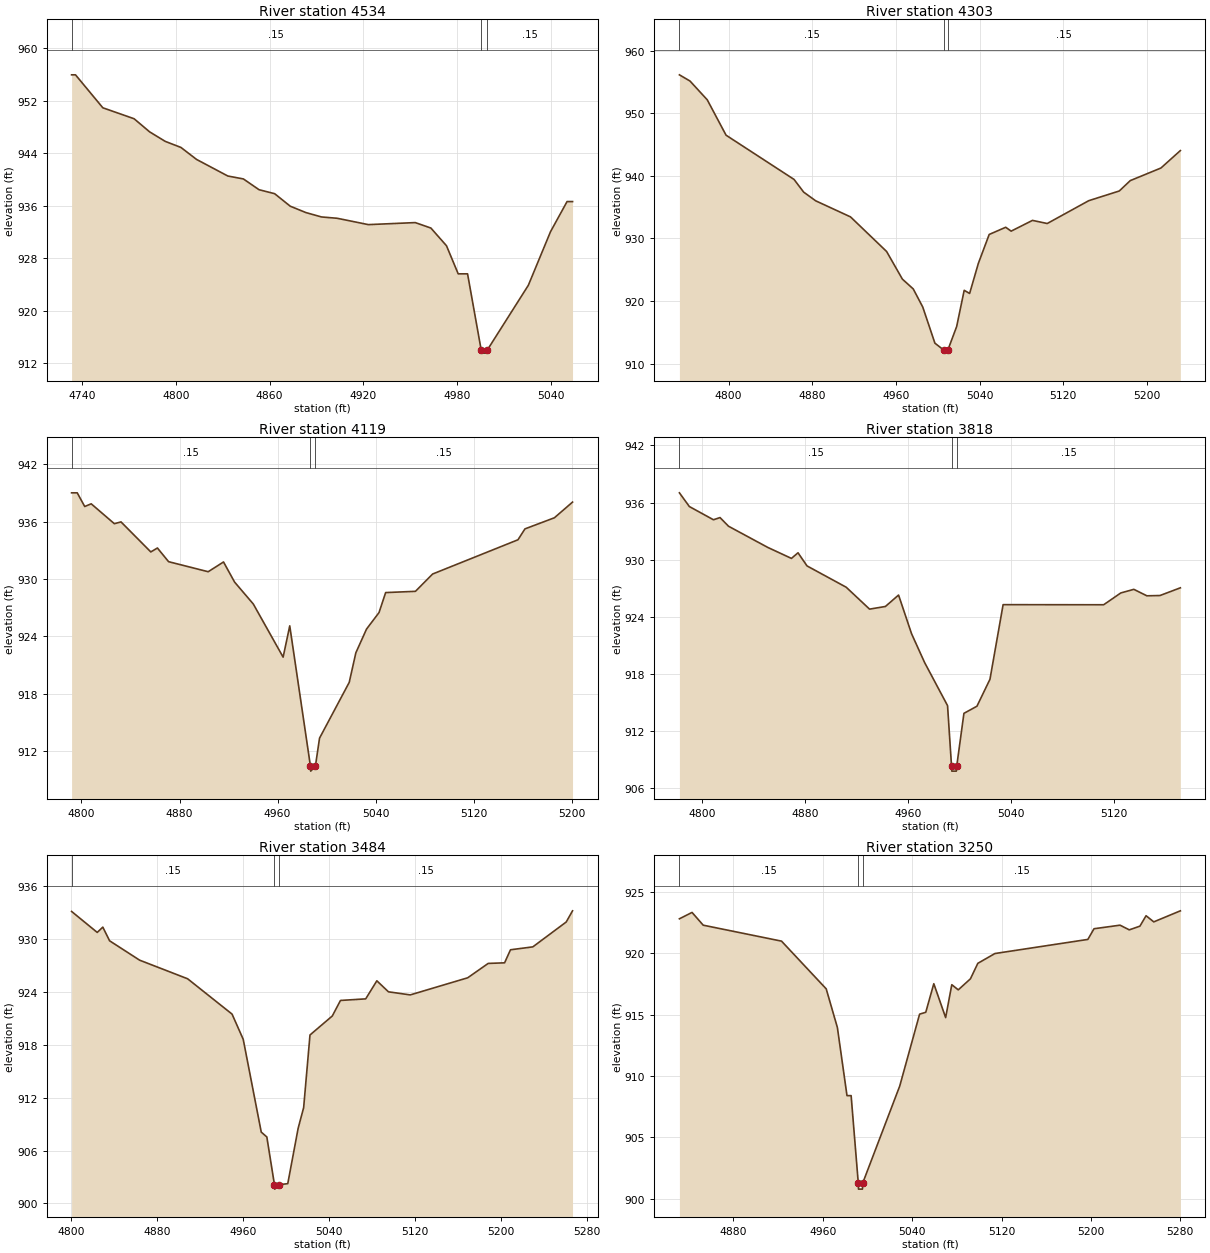
Type RM Length L Ch R = 1,4534,231,231,231
BEGIN DESCRIPTION:
MDW T 102 12.0
END DESCRIPTION:
XS GIS Cut Line= 3
      2262529.00      7131310.01      2262529.00      7131060.00
      2262479.02      7131010.02
#Sta/Elev= 30
  4733.2  955.98  4735.7  955.98  4753.2  950.95  4773.2  949.28  4783.2  947.27
  4793.2  945.82  4803.2  944.90  4813.2  943.07  4833.2  940.54  4843.2  940.09
  4853.2  938.45  4863.2  937.84  4873.2  935.93  4883.2  934.96  4893.2  934.29
  4903.2  934.09  4923.2  933.12  4953.2  933.43  4963.2  932.60  4973.2  929.90
  4980.7  925.61  4986.7  925.61  4995.4  914.01  4995.6  913.51  4999.1  913.51
  4999.4  914.01  5025.6  923.86  5039.8  932.04  5050.4  936.64  5053.9  936.64
#Mann=3,-1,0
  4733.2    0.15       0  4995.4    0.05       0  4999.4    0.15       0
Bank Sta=4995.4,4999.4
Exp/Cntr=0.3,0.1

Type RM Length L Ch R = 1,4303,184,184,184
BEGIN DESCRIPTION:
Mapping XS 4fb03035
END DESCRIPTION:
XS GIS Cut Line= 2
      2262806.38      7131255.68      2262680.05      7130793.64
#Sta/Elev= 30
  4752.9  956.16  4763.0  955.17  4779.5  952.17  4797.5  946.51  4862.5  939.44
  4871.7  937.41  4883.2  936.02  4916.5  933.45  4951.0  927.92  4966.1  923.50
  4976.5  921.93  4985.6  919.03  4997.2  913.26  5005.6  912.17  5005.8  911.67
  5009.6  912.17  5018.0  915.92  5025.2  921.71  5030.4  921.21  5038.7  926.00
  5049.1  930.64  5064.9  931.79  5070.1  931.17  5090.5  932.89  5104.6  932.39
  5144.3  936.04  5173.5  937.59  5184.0  939.25  5213.3  941.26  5231.9  944.05
#Mann=3,-1,0
  4752.9    0.15       0  5005.6    0.05       0  5009.6    0.15       0
Bank Sta=5005.6,5009.6
Exp/Cntr=0.3,0.1

Type RM Length L Ch R = 1,4119,301,301,301
BEGIN DESCRIPTION:
Mapping XS e7ab9f70
END DESCRIPTION:
XS GIS Cut Line= 2
      2262988.50      7131153.49      2262837.43      7130773.95
#Sta/Elev= 30
  4792.0  939.00  4796.6  939.00  4802.7  937.57  4808.0  937.85  4826.9  935.77
  4832.3  935.96  4856.6  932.82  4862.0  933.23  4871.1  931.80  4903.4  930.75
  4915.9  931.77  4924.9  929.67  4940.2  927.37  4964.5  921.82  4969.9  925.09
  4986.8  910.40  4987.0  909.90  4990.8  910.40  4994.2  913.35  5018.4  919.18
  5023.8  922.27  5032.5  924.75  5042.7  926.48  5048.1  928.57  5072.4  928.70
  5086.4  930.51  5156.0  934.09  5161.7  935.23  5185.7  936.39  5200.5  938.03
#Mann=3,-1,0
  4792.0    0.15       0  4986.8    0.05       0  4990.8    0.15       0
Bank Sta=4986.8,4990.8
Exp/Cntr=0.3,0.1

Type RM Length L Ch R = 1,3818,334,334,334
BEGIN DESCRIPTION:
Mapping XS 001016b9
END DESCRIPTION:
XS GIS Cut Line= 2
      2263039.03      7131117.60      2263103.57      7130734.40
#Sta/Elev= 30
  4782.6  937.02  4790.3  935.58  4809.0  934.19  4814.1  934.42  4820.7  933.51
  4851.2  931.28  4869.5  930.13  4874.6  930.72  4881.6  929.34  4912.0  927.10
  4930.1  924.80  4942.4  925.08  4952.6  926.28  4962.7  922.21  4972.8  919.19
  4990.6  914.66  4993.7  908.28  4993.9  907.78  4997.4  907.78  4997.7  908.28
  5003.3  913.85  5013.4  914.60  5023.5  917.43  5033.7  925.27  5111.7  925.26
  5125.0  926.50  5135.1  926.88  5145.2  926.20  5155.4  926.23  5171.2  927.04
#Mann=3,-1,0
  4782.6    0.15       0  4993.7    0.05       0  4997.7    0.15       0
Bank Sta=4993.7,4997.7
Exp/Cntr=0.3,0.1

Type RM Length L Ch R = 1,3484,234,234,234
BEGIN DESCRIPTION:
Mapping XS 3561589a
END DESCRIPTION:
XS GIS Cut Line= 2
      2263321.48      7131024.09      2263197.01      7130574.29
#Sta/Elev= 30
  4800.2  933.13  4824.1  930.75  4829.3  931.35  4835.6  929.80  4863.6  927.60
  4908.3  925.49  4949.7  921.48  4960.1  918.62  4976.9  908.09  4982.1  907.54
  4989.2  902.12  4989.5  901.62  4993.2  902.12  5001.6  902.24  5011.3  908.54
  5016.4  910.87  5022.3  919.11  5043.1  921.27  5050.7  923.03  5074.2  923.21
  5084.6  925.26  5095.4  924.01  5115.7  923.66  5169.2  925.60  5188.3  927.23
  5203.6  927.30  5209.1  928.78  5229.9  929.11  5261.0  931.93  5266.9  933.20
#Mann=3,-1,0
  4800.2    0.15       0  4989.2    0.05       0  4993.2    0.15       0
Bank Sta=4989.2,4993.2
Exp/Cntr=0.3,0.1

Type RM Length L Ch R = 1,3250,360,360,360
BEGIN DESCRIPTION:
Mapping XS d7cb9e5d
END DESCRIPTION:
XS GIS Cut Line= 3
      2263492.58      7131011.35      2263490.36      7130857.67
      2263370.97      7130588.23
#Sta/Elev= 30
  4831.6  922.81  4842.9  923.33  4852.9  922.29  4923.0  920.99  4963.0  917.10
  4973.0  913.95  4981.6  908.40  4985.3  908.40  4991.7  901.28  4991.9  900.78
  4995.4  900.78  4995.7  901.28  5028.8  909.18  5046.6  915.04  5052.1  915.19
  5059.3  917.52  5069.9  914.76  5075.4  917.44  5081.2  917.02  5092.1  917.92
  5098.7  919.18  5114.0  919.98  5197.2  921.13  5202.7  922.00  5226.0  922.29
  5234.3  921.91  5243.8  922.21  5249.3  923.06  5256.2  922.56  5280.0  923.46
#Mann=3,-1,0
  4831.6    0.15       0  4991.7    0.05       0  4995.7    0.15       0
Bank Sta=4991.7,4995.7
Exp/Cntr=0.3,0.1

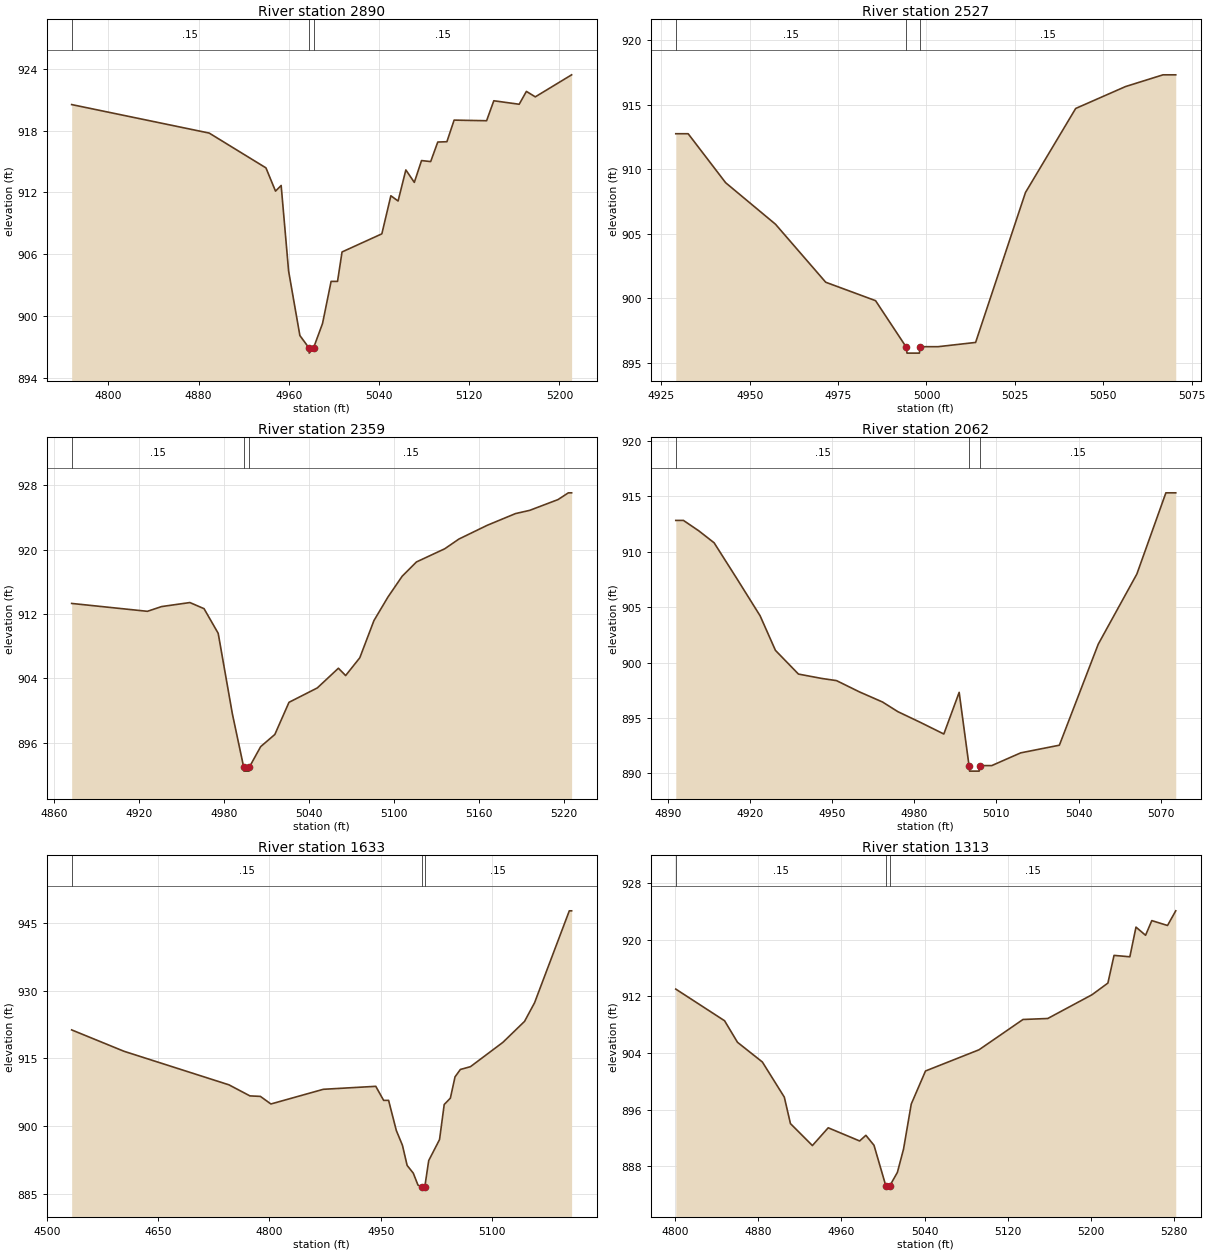
Type RM Length L Ch R = 1,2890,363,363,363
BEGIN DESCRIPTION:
MDW T 102 7.0
END DESCRIPTION:
XS GIS Cut Line= 3
      2263910.35      7130684.05      2263679.00      7130660.00
      2263513.72      7130529.16
#Sta/Elev= 30
  4767.4  920.52  4889.4  917.75  4939.7  914.37  4948.2  912.11  4953.2  912.66
  4959.8  904.35  4969.8  898.08  4977.9  896.87  4978.1  896.37  4981.9  896.87
  4989.9  899.25  4997.5  903.34  5003.2  903.34  5007.2  906.20  5042.5  907.96
  5050.5  911.66  5056.9  911.15  5063.8  914.17  5071.3  912.96  5077.7  915.08
  5085.8  914.98  5092.1  916.88  5100.2  916.91  5106.6  919.01  5135.4  918.95
  5141.8  920.89  5164.3  920.55  5170.7  921.80  5178.6  921.27  5210.8  923.41
#Mann=3,-1,0
  4767.4    0.15       0  4977.9    0.05       0  4981.9    0.15       0
Bank Sta=4977.9,4981.9
Exp/Cntr=0.3,0.1

Type RM Length L Ch R = 1,2527,168,168,168
BEGIN DESCRIPTION:
MDW T 102 6.0
END DESCRIPTION:
XS GIS Cut Line= 3
      2263878.96      7130459.96      2263829.00      7130410.00
      2263778.98      7130359.98
#Sta/Elev= 18
  4929.1  912.76  4932.6  912.76  4943.2  908.96  4957.3  905.74  4971.5  901.24
  4985.6  899.81  4994.2  896.24  4994.5  895.74  4998.0  895.74  4998.2  896.24
  4999.8  896.24  5003.3  896.24  5013.9  896.57  5028.0  908.20  5042.2  914.72
  5056.3  916.42  5066.9  917.33  5070.5  917.33
#Mann=3,-1,0
  4929.1    0.15       0  4994.2    0.05       0  4998.2    0.15       0
Bank Sta=4994.2,4998.2
Exp/Cntr=0.3,0.1

Type RM Length L Ch R = 1,2359,297,297,297
BEGIN DESCRIPTION:
Mapping XS f3218d4f
END DESCRIPTION:
XS GIS Cut Line= 2
      2264032.47      7130260.96      2263679.45      7130268.54
#Sta/Elev= 30
  4872.4  913.32  4925.9  912.34  4935.9  912.93  4955.9  913.43  4965.9  912.67
  4975.9  909.60  4985.9  899.59  4993.9  892.96  4994.1  892.46  4997.6  892.46
  4997.9  892.96  5005.9  895.51  5015.9  897.02  5025.9  901.02  5045.9  902.81
  5060.8  905.26  5065.9  904.35  5075.9  906.56  5085.9  911.19  5095.9  914.15
  5105.9  916.72  5115.9  918.48  5135.9  920.12  5145.9  921.33  5165.9  923.04
  5185.9  924.50  5195.9  924.90  5215.9  926.24  5223.2  927.08  5225.5  927.08
#Mann=3,-1,0
  4872.4    0.15       0  4993.9    0.05       0  4997.9    0.15       0
Bank Sta=4993.9,4997.9
Exp/Cntr=0.3,0.1

Type RM Length L Ch R = 1,2062,429,429,429
BEGIN DESCRIPTION:
MDW T 102 5.0
END DESCRIPTION:
XS GIS Cut Line= 3
      2263979.02      7130160.04      2263929.00      7130060.00
      2263878.97      7130009.97
#Sta/Elev= 28
  4892.9  912.84  4895.7  912.84  4901.3  911.90  4906.9  910.82  4915.3  907.55
  4923.7  904.23  4929.3  901.11  4937.7  898.97  4946.1  898.58  4951.6  898.38
  4960.0  897.36  4968.4  896.45  4974.0  895.58  4982.4  894.59  4990.8  893.56
  4996.4  897.32  5000.0  890.71  5000.2  890.21  5003.7  890.21  5004.0  890.71
  5004.7  890.71  5008.3  890.71  5018.9  891.86  5033.0  892.55  5047.2  901.67
  5061.3  908.00  5071.9  915.33  5075.5  915.33
#Mann=3,-1,0
  4892.9    0.15       0  5000.0    0.05       0  5004.0    0.15       0
Bank Sta=5000,5004
Exp/Cntr=0.3,0.1

Type RM Length L Ch R = 1,1633,320,320,320
BEGIN DESCRIPTION:
MDW T 102 4.0
END DESCRIPTION:
XS GIS Cut Line= 3
      2264378.99      7130109.99      2264079.00      7129810.00
      2263929.03      7129610.04
#Sta/Elev= 30
  4533.3  921.28  4604.0  916.54  4745.4  909.12  4773.7  906.67  4787.8  906.56
  4802.0  904.88  4872.7  908.13  4943.4  908.79  4954.0  905.68  4960.7  905.68
  4971.1  899.02  4979.4  895.72  4985.7  891.28  4994.0  889.57  5000.3  886.93
  5005.5  886.53  5005.8  886.03  5009.5  886.53  5014.8  892.35  5029.4  897.00
  5035.7  904.76  5044.0  906.17  5050.3  910.89  5057.5  912.52  5071.1  913.14
  5114.8  918.52  5144.0  923.16  5157.5  927.27  5204.4  947.64  5207.5  947.64
#Mann=3,-1,0
  4533.3    0.15       0  5005.5    0.05       0  5009.5    0.15       0
Bank Sta=5005.5,5009.5
Exp/Cntr=0.3,0.1

Type RM Length L Ch R = 1,1313,424,424,424
BEGIN DESCRIPTION:
Mapping XS 21311f6b
END DESCRIPTION:
XS GIS Cut Line= 2
      2264422.56      7129779.75      2264160.66      7129376.90
#Sta/Elev= 30
  4800.9  913.03  4847.8  908.56  4860.2  905.52  4884.1  902.74  4905.2  897.78
  4911.1  894.04  4932.2  890.94  4947.4  893.45  4977.6  891.59  4983.6  892.39
  4991.4  890.98  5002.7  885.29  5002.9  884.79  5006.7  885.29  5013.9  887.16
  5019.8  890.45  5027.2  896.80  5040.9  901.47  5092.3  904.46  5134.6  908.74
  5158.4  908.88  5201.0  912.24  5216.2  913.88  5222.1  917.79  5237.3  917.59
  5243.2  921.78  5252.4  920.63  5258.4  922.70  5273.5  922.01  5281.4  924.08
#Mann=3,-1,0
  4800.9    0.15       0  5002.7    0.05       0  5006.7    0.15       0
Bank Sta=5002.7,5006.7
Exp/Cntr=0.3,0.1

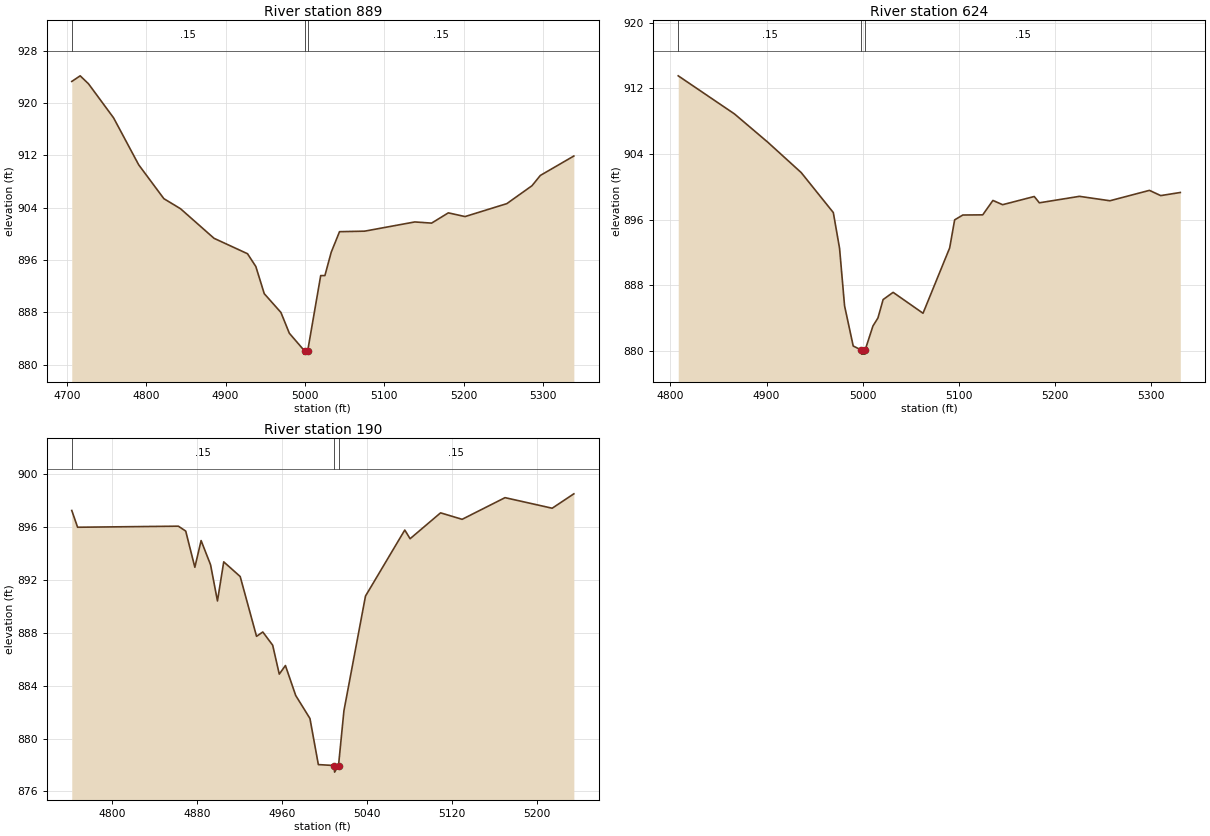
Type RM Length L Ch R = 1,889,265,265,265
BEGIN DESCRIPTION:
MDW T 102 2.0
END DESCRIPTION:
XS GIS Cut Line= 3
      2264729.00      7129660.01      2264629.00      7129360.00
      2264328.97      7129259.99
#Sta/Elev= 30
  4706.2  923.30  4716.8  924.16  4727.3  922.94  4758.9  917.73  4790.5  910.56
  4822.2  905.38  4843.2  903.84  4885.4  899.32  4927.6  896.96  4938.1  895.00
  4948.7  890.85  4969.7  887.98  4980.3  884.80  4999.4  882.11  4999.6  881.61
  5003.1  881.61  5003.4  882.11  5019.8  893.62  5025.1  893.62  5033.0  897.17
  5043.5  900.33  5075.1  900.41  5138.4  901.82  5159.5  901.64  5180.6  903.21
  5201.6  902.64  5254.3  904.62  5286.0  907.36  5296.5  908.93  5338.7  911.90
#Mann=3,-1,0
  4706.2    0.15       0  4999.4    0.05       0  5003.4    0.15       0
Bank Sta=4999.4,5003.4
Exp/Cntr=0.3,0.1

Type RM Length L Ch R = 1,624,434,434,434
BEGIN DESCRIPTION:
Mapping XS e475872b
END DESCRIPTION:
XS GIS Cut Line= 3
      2264888.12      7129595.74      2264798.40      7129263.74
      2264629.74      7129205.91
#Sta/Elev= 30
  4808.1  913.54  4866.6  908.89  4901.3  905.43  4936.0  901.73  4969.4  896.85
  4975.9  892.48  4981.1  885.46  4990.1  880.56  4998.5  880.07  4998.8  879.57
  5002.3  879.57  5002.5  880.07  5010.6  883.00  5015.8  883.98  5021.2  886.23
  5031.6  887.11  5062.7  884.56  5090.4  892.53  5095.6  895.96  5104.1  896.55
  5124.8  896.57  5135.4  898.33  5145.5  897.81  5178.4  898.81  5183.7  898.04
  5225.4  898.83  5257.1  898.29  5298.2  899.56  5309.9  898.92  5330.3  899.30
#Mann=3,-1,0
  4808.1    0.15       0  4998.5    0.05       0  5002.5    0.15       0
Bank Sta=4998.5,5002.5
Exp/Cntr=0.3,0.1

Type RM Length L Ch R = 1,190,0,0,0
BEGIN DESCRIPTION:
MDW T 102 1.0
END DESCRIPTION:
XS GIS Cut Line= 3
      2265140.68      7129236.62      2264938.04      7129113.53
      2264704.90      7129148.17
#Sta/Elev= 30
  4761.7  897.27  4767.2  896.00  4862.1  896.08  4869.0  895.71  4877.6  892.97
  4883.5  894.99  4892.4  893.16  4898.9  890.42  4904.8  893.38  4920.3  892.27
  4935.7  887.74  4941.6  888.07  4950.9  887.07  4957.1  884.88  4962.9  885.53
  4972.6  883.26  4986.0  881.52  4993.9  878.03  5008.9  877.96  5009.2  877.46
  5012.9  877.96  5018.0  882.11  5038.3  890.79  5075.3  895.79  5080.3  895.13
  5109.0  897.09  5129.3  896.60  5169.7  898.24  5214.1  897.44  5234.5  898.53
#Mann=3,-1,0
  4761.7    0.15       0  5008.9    0.05       0  5012.9    0.15       0
Bank Sta=5008.9,5012.9
Exp/Cntr=0.3,0.1

Chan Stop Cuts=-1