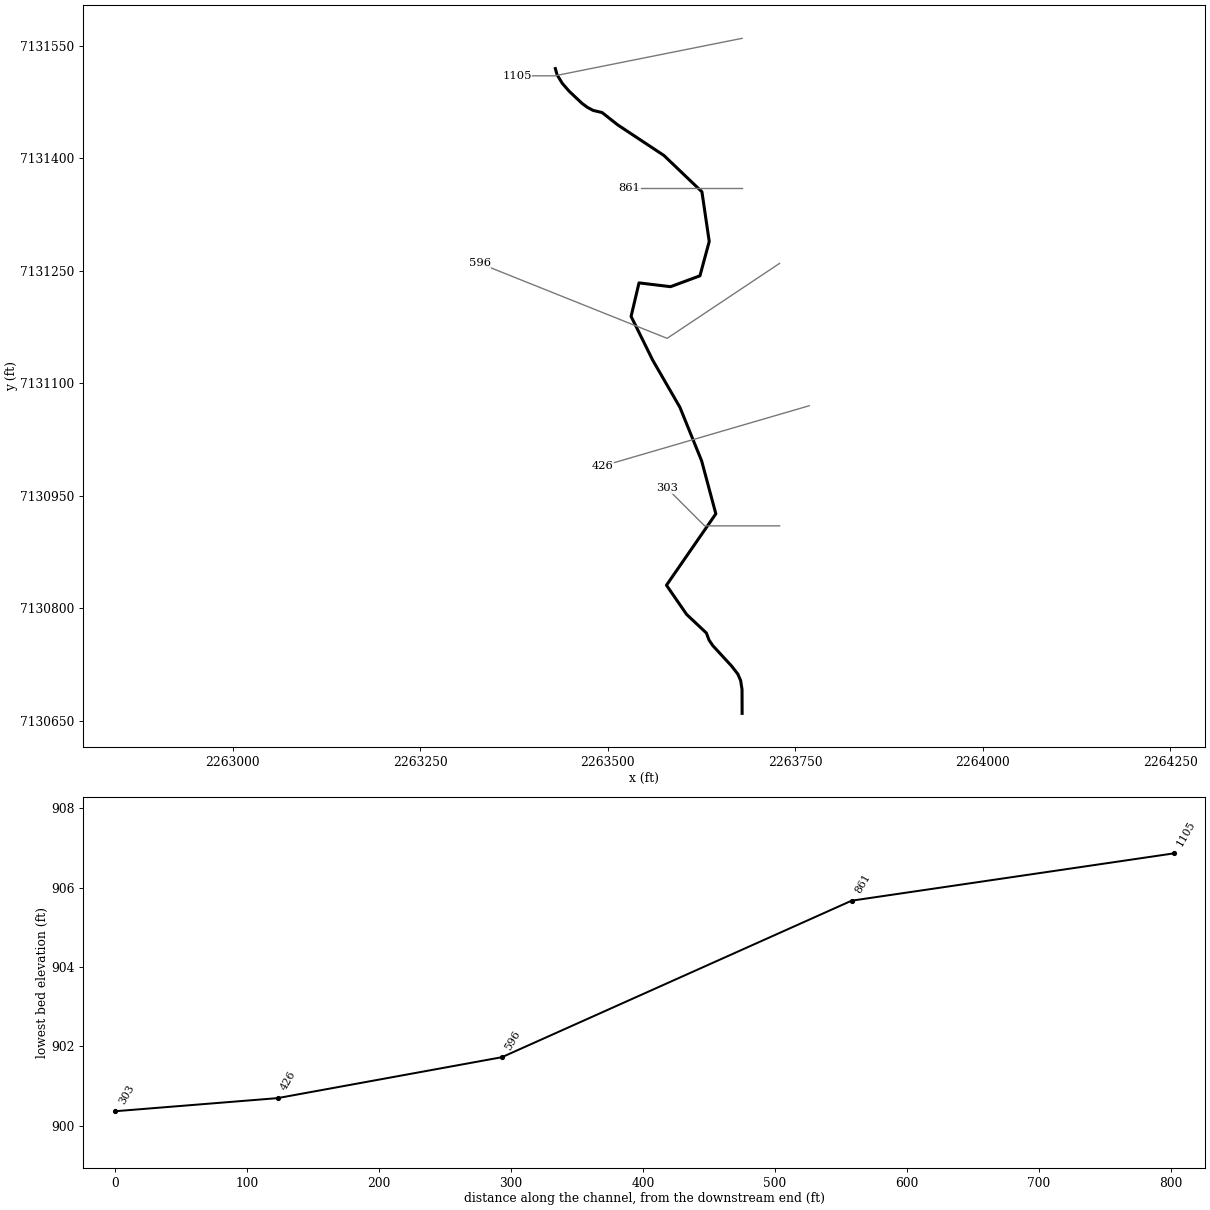
--- MDW T 103.prj (project) ---

Proj Title=MDW T 103 Base Level Engineering
Current Plan=p01
Default Exp/Contr=0.3,0.1
English Units
Geom File=g01
Flow File=f01
Plan File=p01
BEGIN DESCRIPTION:
MDW T 103
END DESCRIPTION:

--- MDW T 103.p01 (plan) ---

Plan Title=Multiple Run
Short Identifier=Multiple
Geom File=g01
Flow File=f01
Subcritical Flow
K Sum by GR= 0
Std Step Tol= 0.01
Critical Tol= 0.01
Num of Std Step Trials= 20
Max Error Tol= 0.3
Flow Tol Ratio= 0.001
Split Flow NTrial= 30
Split Flow Tol= 0.02
Split Flow Ratio= 0.02
Log Output Level= 0
Friction Slope Method= 1
Unsteady Friction Slope Method= 2
Unsteady Bridges Friction Slope Method= 1
Parabolic Critical Depth
Global Vel Dist=  1 , 1 , 1
Global Log Level= 0
CheckData=True
Encroach Param= -1, 0, 0, 0
BEGIN DESCRIPTION:
Multiple Run
END DESCRIPTION:

--- MDW T 103.f01 (steady flow) ---

Flow Title=Multiple
Number of Profiles=7
Profile Names=10-year,25-year,50-year,1pct_min,100-year,1pct_plu,500-year
River Rch & RM= MDW T 103,Reach-1,1105
     364     487     586     352     702    1400    1006
Boundary for River Rch & Prof#=MDW T 103,Reach-1,1
Up Type=0
Dn Type=3
Dn Slope=0.005
Boundary for River Rch & Prof#=MDW T 103,Reach-1,2
Up Type=0
Dn Type=3
Dn Slope=0.005
Boundary for River Rch & Prof#=MDW T 103,Reach-1,3
Up Type=0
Dn Type=3
Dn Slope=0.005
Boundary for River Rch & Prof#=MDW T 103,Reach-1,4
Up Type=0
Dn Type=3
Dn Slope=0.005
Boundary for River Rch & Prof#=MDW T 103,Reach-1,5
Up Type=0
Dn Type=3
Dn Slope=0.005
Boundary for River Rch & Prof#=MDW T 103,Reach-1,6
Up Type=0
Dn Type=3
Dn Slope=0.005
Boundary for River Rch & Prof#=MDW T 103,Reach-1,7
Up Type=0
Dn Type=3
Dn Slope=0.005

--- MDW T 103.g01 (geometry) ---

Geom Title=Existing Conditions

River Reach=MDW T 103,Reach-1
Reach XY= 30
      2263430.02      7131519.66      2263432.37      7131511.29
      2263439.30      7131499.90      2263448.42      7131489.46
      2263465.36      7131473.46      2263472.62      7131468.03
      2263480.40      7131463.88      2263492.30      7131461.08
      2263513.11      7131444.62      2263574.71      7131403.87
      2263625.42      7131355.40      2263635.16      7131289.16
      2263622.79      7131243.38      2263583.63      7131228.89
      2263541.54      7131233.94      2263530.99      7131189.26
      2263559.85      7131130.80      2263596.07      7131068.07
      2263625.06      7130996.57      2263643.98      7130926.06
      2263578.14      7130830.86      2263605.00      7130791.96
      2263631.34      7130767.16      2263634.92      7130757.76
      2263639.88      7130750.38      2263665.02      7130723.07
      2263673.32      7130712.36      2263677.05      7130703.74
      2263678.90      7130691.81      2263679.00      7130660.00

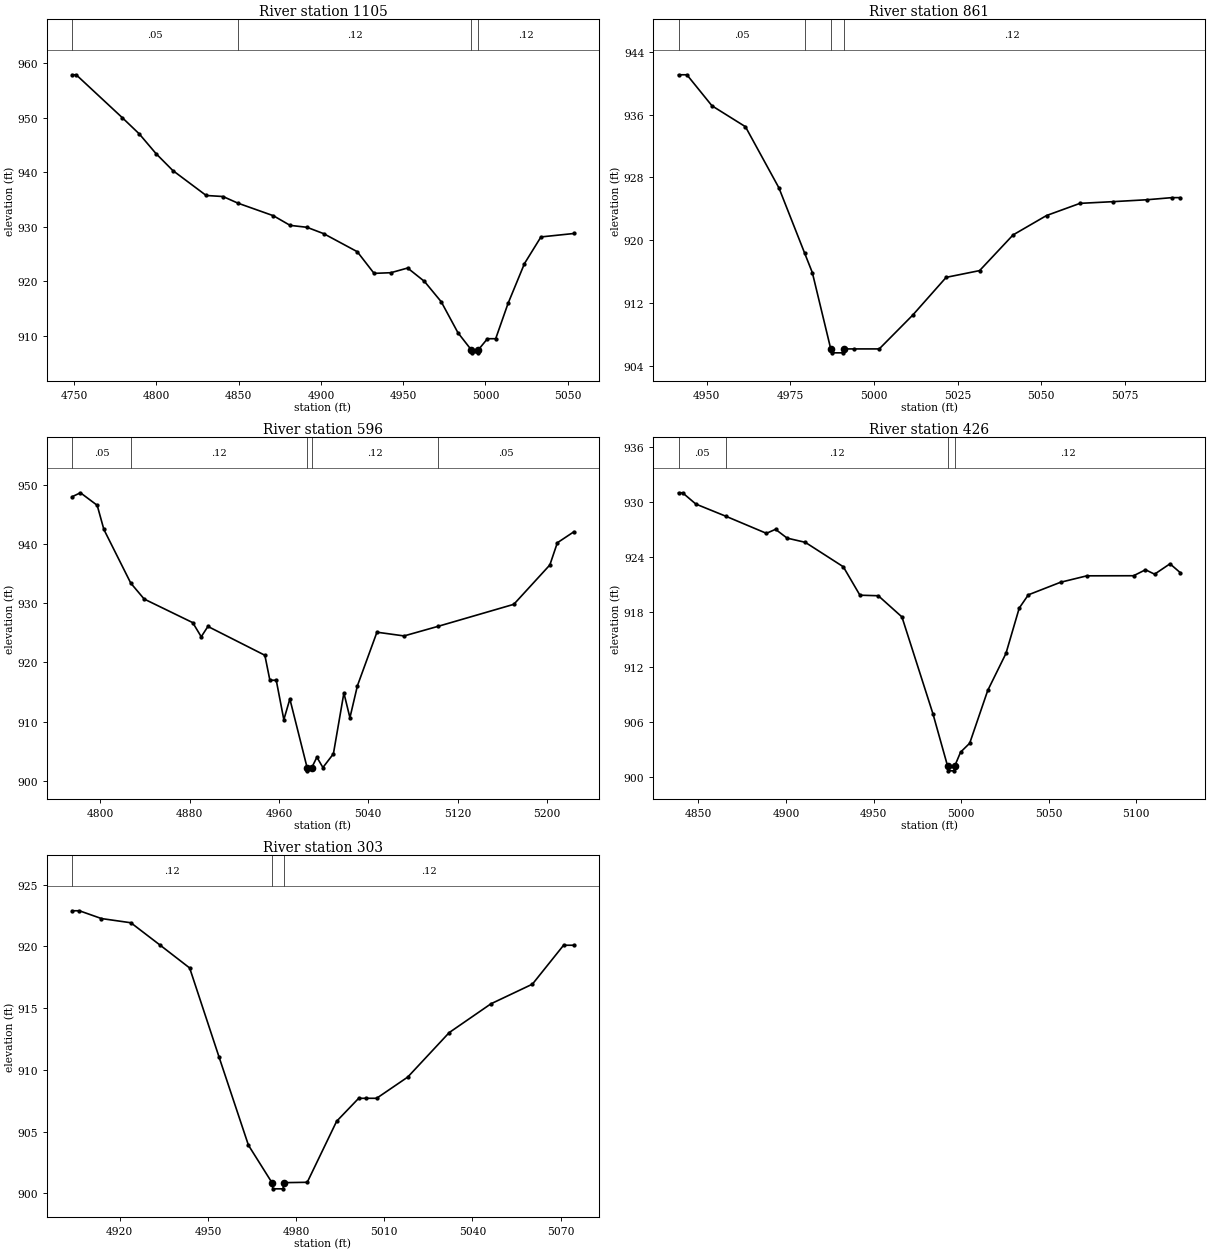
Type RM Length L Ch R = 1,1105,244,244,244
BEGIN DESCRIPTION:
MDW T 103 4.0
END DESCRIPTION:
XS GIS Cut Line= 3
      2263678.96      7131559.99      2263429.00      7131510.00
      2263379.01      7131510.00
#Sta/Elev= 30
  4748.8  957.84  4751.3  957.84  4779.4  949.95  4789.6  947.01  4799.8  943.39
  4810.0  940.29  4830.3  935.71  4840.5  935.52  4849.6  934.30  4871.1  932.00
  4881.3  930.23  4891.5  929.88  4901.7  928.71  4922.1  925.40  4932.3  921.43
  4942.5  921.55  4952.7  922.41  4962.9  919.96  4973.1  916.23  4983.3  910.53
  4991.5  907.36  4991.8  906.86  4995.3  906.86  4995.5  907.36  5001.2  909.45
  5006.2  909.45  5013.7  915.91  5023.7  923.23  5033.7  928.11  5053.7  928.74
#Mann=4,-1,0
  4748.8    0.05       0  4849.6    0.12       0  4991.5    0.07       0
  4995.5    0.12       0
Bank Sta=4991.5,4995.5
Exp/Cntr=0.3,0.1

Type RM Length L Ch R = 1,861,265,265,265
BEGIN DESCRIPTION:
MDW T 103 3.0
END DESCRIPTION:
XS GIS Cut Line= 3
      2263679.01      7131360.00      2263629.00      7131360.00
      2263529.01      7131360.00
#Sta/Elev= 23
  4941.6  941.07  4944.1  941.07  4951.6  937.12  4961.6  934.46  4971.6  926.68
  4979.3  918.36  4981.6  915.88  4987.1  906.17  4987.4  905.67  4990.9  905.67
  4991.1  906.17  4994.1  906.17  5001.6  906.17  5011.6  910.47  5021.6  915.28
  5031.6  916.14  5041.6  920.68  5051.6  923.15  5061.6  924.70  5071.6  924.92
  5081.6  925.16  5089.1  925.43  5091.6  925.43
#Mann=4,-1,0
  4941.6    0.05       0  4979.3    0.12       0  4987.1    0.07       0
  4991.1    0.12       0
Bank Sta=4987.1,4991.1
Exp/Cntr=0.3,0.1

Type RM Length L Ch R = 1,596,170,170,170
BEGIN DESCRIPTION:
MDW T 103 2.0
END DESCRIPTION:
XS GIS Cut Line= 3
      2263728.98      7131259.98      2263579.00      7131160.00
      2263329.01      7131260.00
#Sta/Elev= 30
  4774.7  947.95  4782.2  948.62  4797.2  946.51  4803.2  942.43  4827.3  933.38
  4839.3  930.70  4882.8  926.72  4890.4  924.34  4896.4  926.08  4947.4  921.22
  4951.9  917.01  4957.6  917.01  4964.4  910.36  4969.8  913.85  4985.3  902.23
  4985.5  901.73  4989.3  902.23  4994.0  904.03  4999.4  902.29  5008.8  904.60
  5018.2  914.86  5023.6  910.69  5030.3  916.07  5047.8  925.11  5072.1  924.48
  5102.6  926.10  5170.4  929.81  5202.7  936.45  5209.4  940.19  5224.2  942.04
#Mann=5,-1,0
  4774.7    0.05       0  4827.3    0.12       0  4985.3    0.07       0
  4989.3    0.12       0  5102.6    0.05       0
Bank Sta=4985.3,4989.3
Exp/Cntr=0.3,0.1

Type RM Length L Ch R = 1,426,123,123,123
BEGIN DESCRIPTION:
Mapping XS ae7f4d66
END DESCRIPTION:
XS GIS Cut Line= 2
      2263768.49      7131070.16      2263493.36      7130989.89
#Sta/Elev= 30
  4838.6  931.00  4840.9  931.00  4848.5  929.77  4865.8  928.43  4888.8  926.58
  4894.0  927.02  4900.6  926.06  4911.0  925.60  4932.7  922.94  4942.2  919.84
  4952.7  919.78  4966.2  917.47  4983.9  906.92  4992.3  901.20  4992.6  900.70
  4996.1  900.70  4996.3  901.20  4999.7  902.74  5004.9  903.71  5015.2  909.46
  5025.6  913.49  5033.2  918.44  5038.4  919.88  5056.8  921.25  5071.8  921.95
  5098.5  921.96  5105.3  922.61  5110.5  922.13  5119.3  923.26  5125.2  922.29
#Mann=4,-1,0
  4838.6    0.05       0  4865.8    0.12       0  4992.3    0.07       0
  4996.3    0.12       0
Bank Sta=4992.3,4996.3
Exp/Cntr=0.3,0.1

Type RM Length L Ch R = 1,303,0,0,0
BEGIN DESCRIPTION:
MDW T 103 1.0
END DESCRIPTION:
XS GIS Cut Line= 3
      2263729.03      7130910.00      2263629.00      7130910.00
      2263579.03      7130959.97
#Sta/Elev= 23
  4903.8  922.88  4906.3  922.88  4913.8  922.25  4923.8  921.91  4933.8  920.09
  4943.8  918.25  4953.8  911.04  4963.8  903.90  4971.8  900.87  4972.1  900.37
  4975.6  900.37  4975.8  900.87  4983.8  900.90  4993.8  905.84  5001.3  907.70
  5003.8  907.70  5007.4  907.70  5018.0  909.42  5032.1  913.02  5046.3  915.35
  5060.4  916.94  5071.0  920.09  5074.5  920.09
#Mann=3,-1,0
  4903.8    0.12       0  4971.8    0.07       0  4975.8    0.12       0
Bank Sta=4971.8,4975.8
Exp/Cntr=0.3,0.1

Chan Stop Cuts=-1