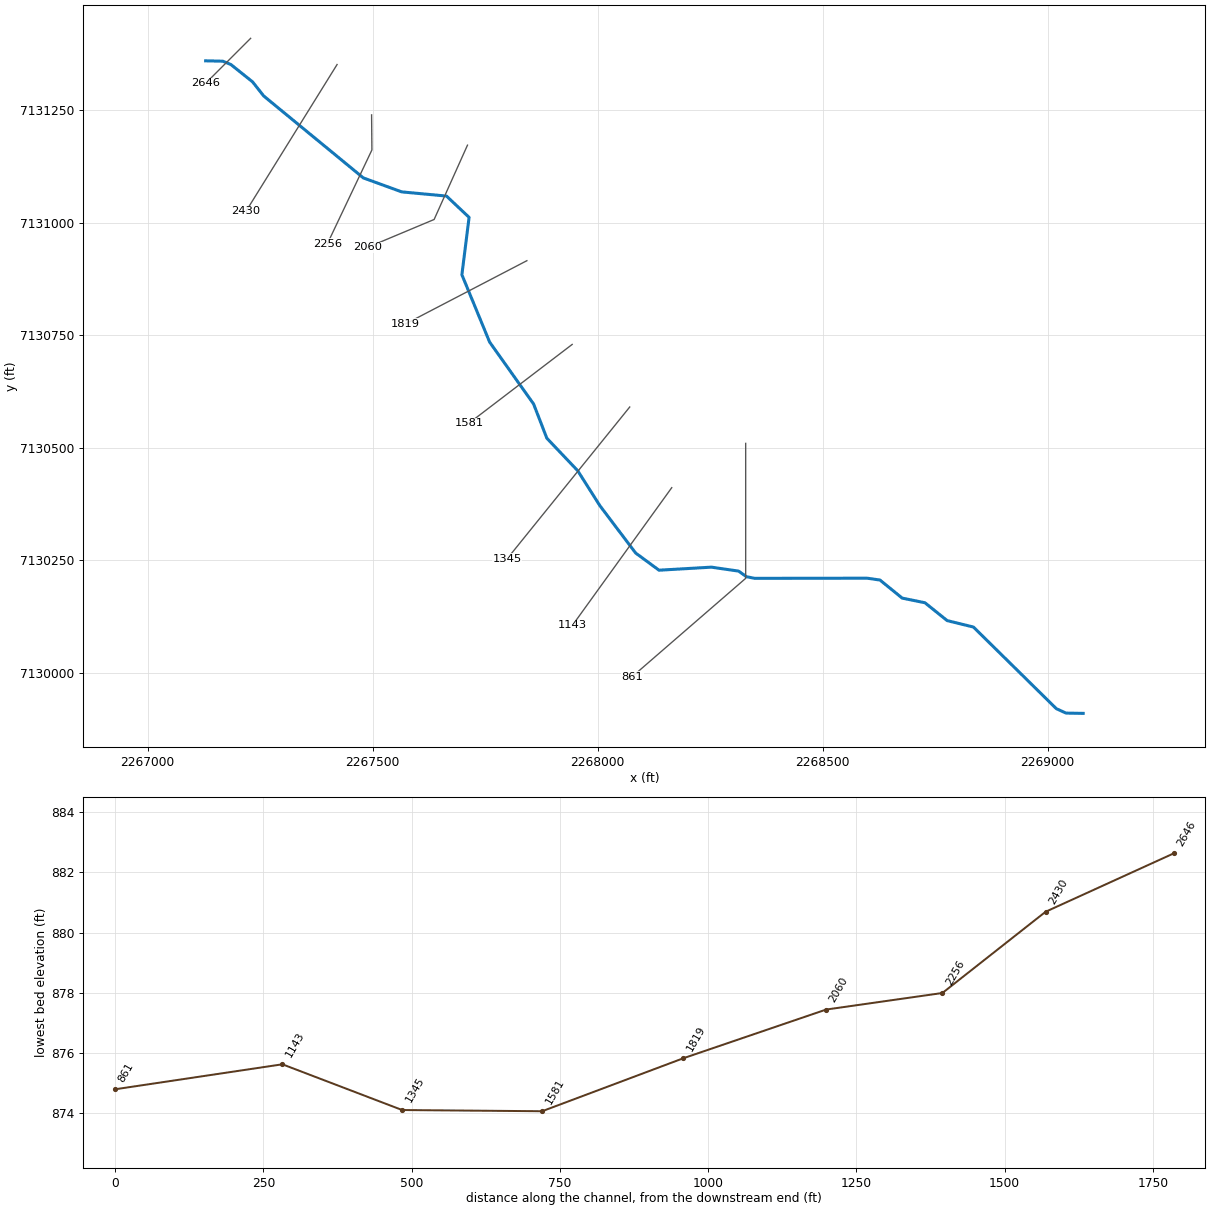
--- MDW T 104.prj (project) ---

Proj Title=MDW T 104 Base Level Engineering
Current Plan=p01
Default Exp/Contr=0.3,0.1
English Units
Geom File=g01
Flow File=f01
Plan File=p01
BEGIN DESCRIPTION:
MDW T 104
END DESCRIPTION:

--- MDW T 104.p01 (plan) ---

Plan Title=Multiple Run
Short Identifier=Multiple
Geom File=g01
Flow File=f01
Subcritical Flow
K Sum by GR= 0
Std Step Tol= 0.01
Critical Tol= 0.01
Num of Std Step Trials= 20
Max Error Tol= 0.3
Flow Tol Ratio= 0.001
Split Flow NTrial= 30
Split Flow Tol= 0.02
Split Flow Ratio= 0.02
Log Output Level= 0
Friction Slope Method= 1
Unsteady Friction Slope Method= 2
Unsteady Bridges Friction Slope Method= 1
Parabolic Critical Depth
Global Vel Dist=  1 , 1 , 1
Global Log Level= 0
CheckData=True
Encroach Param= -1, 0, 0, 0
BEGIN DESCRIPTION:
Multiple Run
END DESCRIPTION:

--- MDW T 104.f01 (steady flow) ---

Flow Title=Multiple
Number of Profiles=7
Profile Names=10-year,25-year,50-year,1pct_min,100-year,1pct_plu,500-year
River Rch & RM= MDW T 104,Reach-1,2646
     406     544     657     395     788    1572    1133
Boundary for River Rch & Prof#=MDW T 104,Reach-1,1
Up Type=0
Dn Type=3
Dn Slope=0.005
Boundary for River Rch & Prof#=MDW T 104,Reach-1,2
Up Type=0
Dn Type=3
Dn Slope=0.005
Boundary for River Rch & Prof#=MDW T 104,Reach-1,3
Up Type=0
Dn Type=3
Dn Slope=0.005
Boundary for River Rch & Prof#=MDW T 104,Reach-1,4
Up Type=0
Dn Type=3
Dn Slope=0.005
Boundary for River Rch & Prof#=MDW T 104,Reach-1,5
Up Type=0
Dn Type=3
Dn Slope=0.005
Boundary for River Rch & Prof#=MDW T 104,Reach-1,6
Up Type=0
Dn Type=3
Dn Slope=0.005
Boundary for River Rch & Prof#=MDW T 104,Reach-1,7
Up Type=0
Dn Type=3
Dn Slope=0.005

--- MDW T 104.g01 (geometry) ---

Geom Title=Existing Conditions

River Reach=MDW T 104,Reach-1
Reach XY= 30
      2267129.00      7131360.00      2267167.06      7131359.19
      2267185.04      7131351.82      2267233.28      7131313.25
      2267257.96      7131281.97      2267479.45      7131099.83
      2267564.79      7131068.78      2267664.26      7131059.47
      2267714.40      7131012.18      2267698.38      7130884.68
      2267759.98      7130735.16      2267857.79      7130597.35
      2267887.17      7130521.44      2267955.69      7130449.31
      2268005.16      7130371.31      2268084.50      7130266.30
      2268136.46      7130228.13      2268252.99      7130234.90
      2268313.30      7130226.09      2268330.56      7130213.78
      2268349.03      7130210.07      2268599.15      7130210.36
      2268627.45      7130206.25      2268676.82      7130166.12
      2268727.28      7130155.84      2268776.81      7130116.10
      2268835.06      7130101.86      2269019.21      7129920.52
      2269040.84      7129910.59      2269079.00      7129910.00

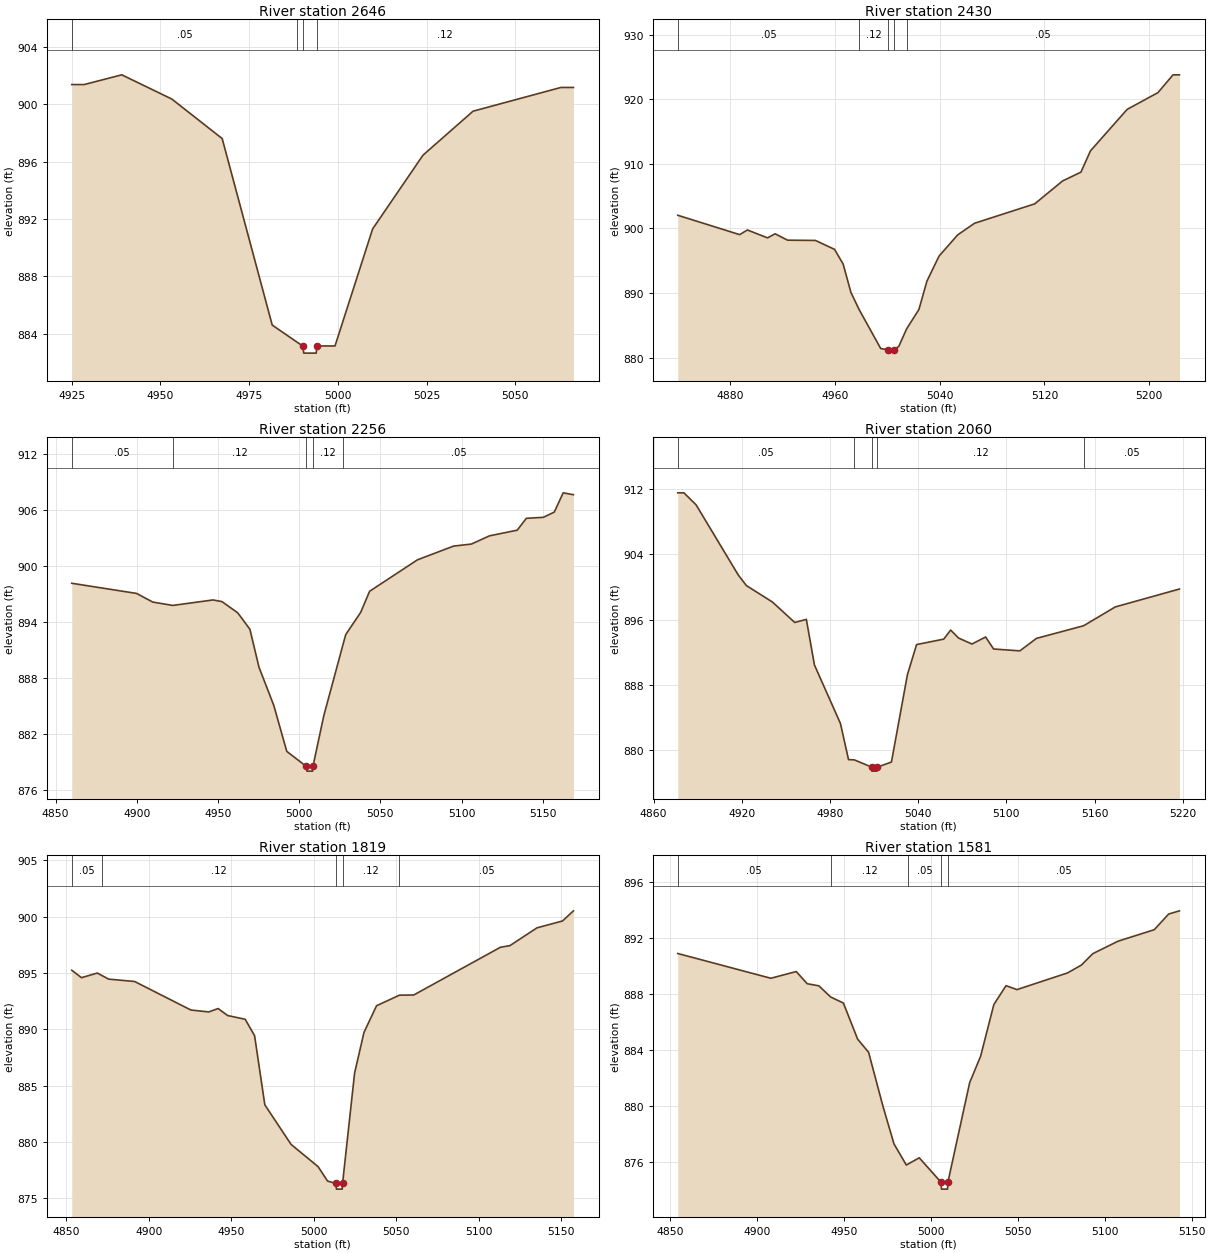
Type RM Length L Ch R = 1,2646,216,216,216
BEGIN DESCRIPTION:
MDW T 104 8.0
END DESCRIPTION:
XS GIS Cut Line= 3
      2267228.98      7131409.98      2267179.00      7131360.00
      2267128.99      7131309.99
#Sta/Elev= 17
  4925.0  901.38  4928.5  901.38  4939.1  902.06  4953.2  900.37  4967.4  897.61
  4981.5  884.59  4988.6  883.38  4990.1  883.13  4990.4  882.63  4993.9  882.63
  4994.1  883.13  4999.2  883.13  5009.8  891.30  5024.0  896.45  5038.1  899.52
  5062.9  901.18  5066.4  901.18
#Mann=4,-1,0
  4925.0    0.05       0  4988.6    0.12       0  4990.1    0.07       0
  4994.1    0.12       0
Bank Sta=4990.1,4994.1
Exp/Cntr=0.3,0.1

Type RM Length L Ch R = 1,2430,174,174,174
BEGIN DESCRIPTION:
Mapping XS abcb6f50
END DESCRIPTION:
XS GIS Cut Line= 2
      2267421.07      7131351.78      2267218.87      7131026.03
#Sta/Elev= 30
  4839.8  902.05  4887.1  899.05  4893.0  899.77  4908.4  898.55  4914.2  899.18
  4923.7  898.19  4945.0  898.15  4959.6  896.77  4966.2  894.48  4972.1  890.11
  4978.4  887.44  4994.9  881.40  5000.8  881.19  5001.1  880.69  5004.8  881.19
  5008.7  881.73  5014.7  884.45  5024.1  887.46  5030.2  891.84  5039.5  895.73
  5053.7  899.01  5066.6  900.81  5112.6  903.82  5133.9  907.37  5147.9  908.73
  5155.2  912.03  5183.2  918.45  5206.8  921.06  5218.3  923.81  5223.2  923.81
#Mann=5,-1,0
  4839.8    0.05       0  4978.4    0.12       0  5000.8    0.07       0
  5004.8    0.12       0  5014.7    0.05       0
Bank Sta=5000.8,5004.8
Exp/Cntr=0.3,0.1

Type RM Length L Ch R = 1,2256,196,196,196
BEGIN DESCRIPTION:
Mapping XS 6cb66810
END DESCRIPTION:
XS GIS Cut Line= 3
      2267497.76      7131239.88      2267498.48      7131161.99
      2267399.41      7130953.31
#Sta/Elev= 30
  4860.0  898.16  4899.9  897.07  4909.9  896.14  4922.2  895.78  4947.0  896.37
  4952.5  896.19  4962.2  894.99  4969.7  893.22  4975.3  889.14  4984.4  885.05
  4992.4  880.11  5004.5  878.49  5004.8  877.99  5008.3  877.99  5008.5  878.49
  5015.2  883.94  5027.3  891.76  5028.7  892.65  5037.9  895.03  5043.4  897.30
  5072.9  900.68  5095.1  902.15  5106.1  902.37  5117.2  903.25  5134.3  903.86
  5139.9  905.13  5150.4  905.24  5157.1  905.80  5162.6  907.87  5168.9  907.67
#Mann=5,-1,0
  4860.0    0.05       0  4922.2    0.12       0  5004.5    0.07       0
  5008.5    0.12       0  5027.3    0.05       0
Bank Sta=5004.5,5008.5
Exp/Cntr=0.3,0.1

Type RM Length L Ch R = 1,2060,241,241,241
BEGIN DESCRIPTION:
Mapping XS 7c8996e7
END DESCRIPTION:
XS GIS Cut Line= 3
      2267710.84      7131172.62      2267636.72      7131007.45
      2267488.82      7130945.45
#Sta/Elev= 30
  4876.4  911.55  4880.6  911.55  4888.9  910.07  4917.6  901.47  4923.1  900.18
  4940.8  898.17  4956.0  895.66  4963.9  896.04  4969.4  890.45  4987.1  883.28
  4992.6  878.85  4996.5  878.82  5008.3  877.94  5008.5  877.44  5012.0  877.44
  5012.3  877.94  5021.8  878.55  5032.7  889.28  5038.9  892.95  5057.4  893.62
  5062.1  894.73  5067.5  893.75  5076.6  893.02  5085.9  893.88  5091.3  892.41
  5109.2  892.18  5120.5  893.71  5152.6  895.26  5174.2  897.57  5217.8  899.76
#Mann=5,-1,0
  4876.4    0.05       0  4996.5    0.12       0  5008.3    0.07       0
  5012.3    0.12       0  5152.6    0.05       0
Bank Sta=5008.3,5012.3
Exp/Cntr=0.3,0.1

Type RM Length L Ch R = 1,1819,238,238,238
BEGIN DESCRIPTION:
Mapping XS 3d741bde
END DESCRIPTION:
XS GIS Cut Line= 2
      2267842.78      7130915.88      2267573.16      7130775.46
#Sta/Elev= 30
  4853.3  895.24  4859.2  894.58  4868.8  894.99  4871.7  894.76  4875.7  894.45
  4891.4  894.24  4925.5  891.71  4936.3  891.54  4942.0  891.84  4947.8  891.22
  4958.4  890.89  4964.1  889.43  4970.3  883.30  4986.2  879.79  5002.6  877.81
  5008.3  876.54  5013.4  876.32  5013.7  875.82  5017.2  875.82  5017.4  876.32
  5024.7  886.12  5030.4  889.73  5038.0  892.09  5051.9  893.03  5060.5  893.04
  5113.1  897.28  5118.8  897.42  5135.2  899.00  5150.7  899.61  5157.3  900.51
#Mann=5,-1,0
  4853.3    0.05       0  4871.7    0.12       0  5013.4    0.07       0
  5017.4    0.12       0  5051.9    0.05       0
Bank Sta=5013.4,5017.4
Exp/Cntr=0.3,0.1

Type RM Length L Ch R = 1,1581,236,236,236
BEGIN DESCRIPTION:
Mapping XS d87d8090
END DESCRIPTION:
XS GIS Cut Line= 2
      2267943.49      7130729.83      2267714.20      7130554.89
#Sta/Elev= 30
  4854.6  890.90  4908.1  889.13  4922.7  889.61  4929.0  888.74  4935.7  888.59
  4942.5  887.79  4949.8  887.36  4958.0  884.78  4964.3  883.84  4972.6  879.96
  4978.9  877.29  4986.0  875.78  4987.1  875.86  4993.4  876.30  5005.9  874.56
  5006.2  874.06  5009.7  874.06  5009.9  874.56  5022.4  881.67  5028.7  883.56
  5036.3  887.25  5043.3  888.60  5049.6  888.32  5078.6  889.51  5086.6  890.07
  5093.2  890.89  5107.7  891.78  5128.5  892.60  5136.8  893.72  5143.0  893.95
#Mann=5,-1,0
  4854.6    0.05       0  4942.5    0.12       0  4987.1    0.05       0
  5005.9   0.033       0  5009.9    0.05       0
Bank Sta=5005.9,5009.9
Exp/Cntr=0.3,0.1

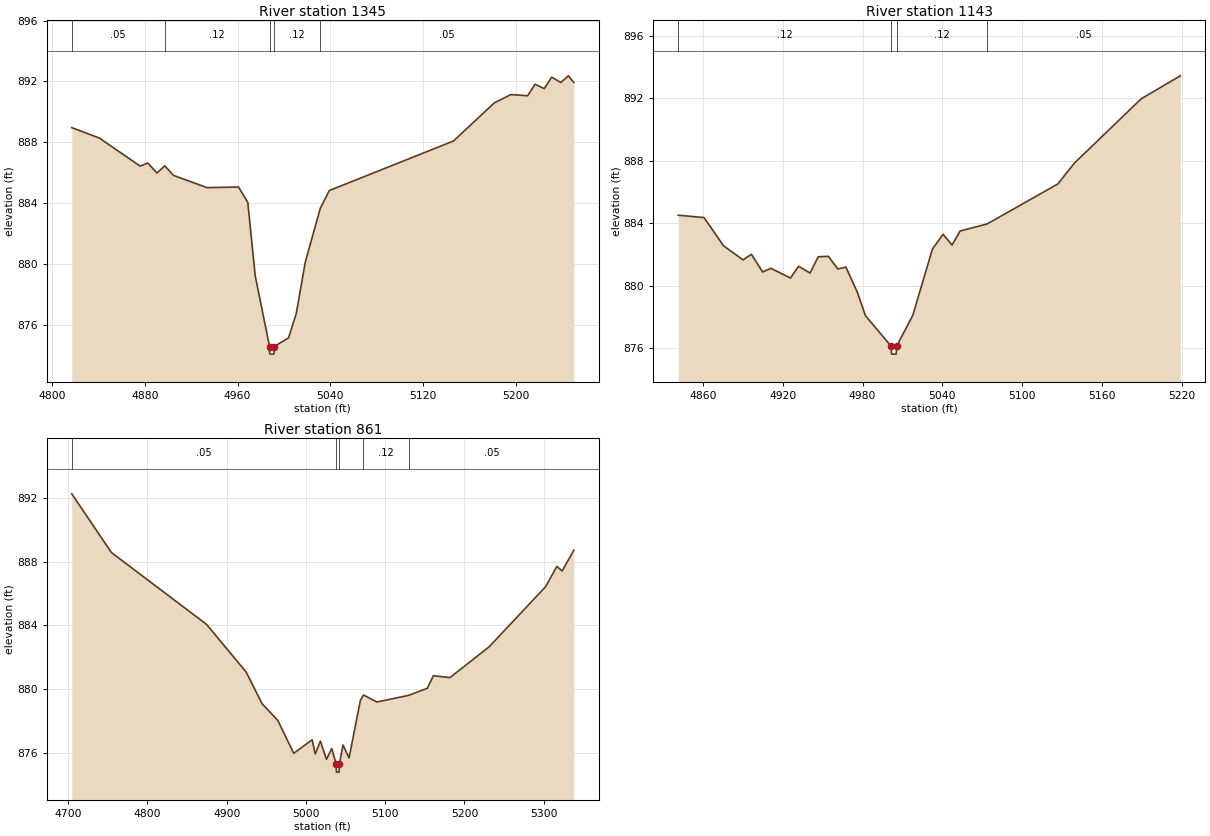
Type RM Length L Ch R = 1,1345,202,202,202
BEGIN DESCRIPTION:
Mapping XS be6a3a0a
END DESCRIPTION:
XS GIS Cut Line= 2
      2268071.36      7130590.76      2267799.12      7130253.66
#Sta/Elev= 30
  4816.9  888.97  4840.8  888.28  4876.0  886.44  4882.5  886.65  4890.4  885.99
  4897.2  886.46  4904.8  885.83  4933.6  885.03  4960.8  885.07  4968.8  884.07
  4975.2  879.25  4987.6  874.60  4987.8  874.10  4991.3  874.10  4991.6  874.60
  5004.0  875.17  5010.7  876.79  5018.4  880.13  5031.4  883.68  5039.2  884.84
  5146.3  888.09  5181.5  890.59  5195.9  891.14  5210.3  891.06  5216.7  891.82
  5224.6  891.53  5231.1  892.28  5239.0  891.93  5245.5  892.37  5250.2  891.93
#Mann=5,-1,0
  4816.9    0.05       0  4897.2    0.12       0  4987.6    0.07       0
  4991.6    0.12       0  5031.4    0.05       0
Bank Sta=4987.6,4991.6
Exp/Cntr=0.3,0.1

Type RM Length L Ch R = 1,1143,282,282,282
BEGIN DESCRIPTION:
Mapping XS fc7ee7e2
END DESCRIPTION:
XS GIS Cut Line= 2
      2268164.72      7130411.55      2267943.85      7130105.28
#Sta/Elev= 30
  4841.4  884.51  4860.8  884.36  4875.5  882.55  4890.2  881.65  4896.4  882.01
  4904.9  880.88  4911.1  881.11  4925.8  880.49  4931.9  881.24  4940.5  880.81
  4946.7  881.85  4954.3  881.88  4961.4  881.07  4967.5  881.19  4976.1  879.58
  4982.2  878.08  5001.6  876.12  5001.8  875.62  5005.3  875.62  5005.6  876.12
  5017.8  878.10  5032.6  882.35  5040.6  883.29  5047.3  882.60  5053.4  883.50
  5073.7  883.95  5126.9  886.51  5139.3  887.84  5189.6  891.96  5219.0  893.43
#Mann=4,-1,0
  4841.4    0.12       0  5001.6    0.07       0  5005.6    0.12       0
  5073.7    0.05       0
Bank Sta=5001.6,5005.6
Exp/Cntr=0.3,0.1

Type RM Length L Ch R = 1,861,0,0,0
BEGIN DESCRIPTION:
MDW T 104 1.0
END DESCRIPTION:
XS GIS Cut Line= 3
      2268329.00      7130509.97      2268329.00      7130210.00
      2268076.95      7129991.71
#Sta/Elev= 30
  4704.6  892.25  4754.6  888.57  4874.6  884.06  4924.6  881.07  4944.6  879.09
  4964.6  878.03  4984.6  875.97  5007.9  876.82  5011.7  875.93  5018.3  876.73
  5025.9  875.59  5032.6  876.27  5038.2  875.29  5038.4  874.79  5041.9  874.79
  5042.2  875.29  5046.8  876.49  5054.4  875.68  5068.7  879.29  5072.6  879.63
  5089.6  879.19  5129.8  879.61  5153.2  880.05  5160.8  880.84  5181.7  880.72
  5231.1  882.65  5302.3  886.42  5316.6  887.70  5323.2  887.41  5338.0  888.71
#Mann=5,-1,0
  4704.6    0.05       0  5038.2   0.033       0  5042.2    0.05       0
  5072.6    0.12       0  5129.8    0.05       0
Bank Sta=5038.2,5042.2
Exp/Cntr=0.3,0.1

Chan Stop Cuts=-1