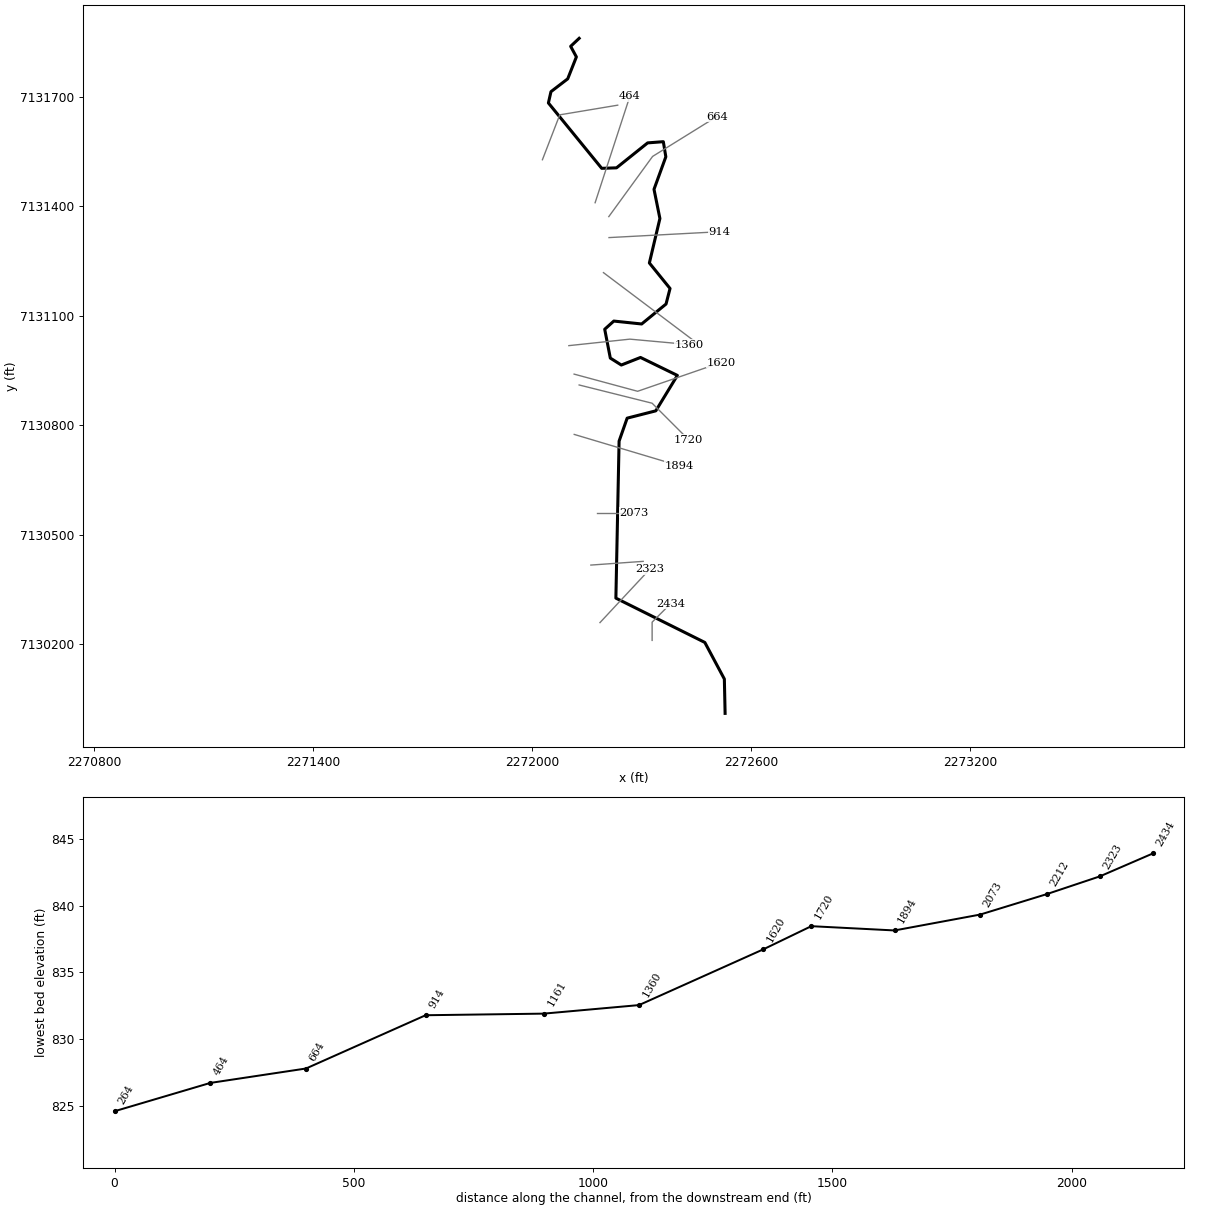
--- MDW T 105.prj (project) ---

Proj Title=MDW T 105 Base Level Engineering
Current Plan=p01
Default Exp/Contr=0.3,0.1
English Units
Geom File=g01
Flow File=f01
Plan File=p01
BEGIN DESCRIPTION:
MDW T 105
END DESCRIPTION:

--- MDW T 105.p01 (plan) ---

Plan Title=Multiple Run
Short Identifier=Multiple
Geom File=g01
Flow File=f01
Subcritical Flow
K Sum by GR= 0
Std Step Tol= 0.01
Critical Tol= 0.01
Num of Std Step Trials= 20
Max Error Tol= 0.3
Flow Tol Ratio= 0.001
Split Flow NTrial= 30
Split Flow Tol= 0.02
Split Flow Ratio= 0.02
Log Output Level= 0
Friction Slope Method= 1
Unsteady Friction Slope Method= 2
Unsteady Bridges Friction Slope Method= 1
Parabolic Critical Depth
Global Vel Dist=  1 , 1 , 1
Global Log Level= 0
CheckData=True
Encroach Param= -1, 0, 0, 0
BEGIN DESCRIPTION:
Multiple Run
END DESCRIPTION:

--- MDW T 105.f01 (steady flow) ---

Flow Title=Multiple
Number of Profiles=7
Profile Names=10-year,25-year,50-year,1pct_min,100-year,1pct_plu,500-year
River Rch & RM= MDW T 105,Reach-1,2434
     537     736     901     549    1095    2185    1620
Boundary for River Rch & Prof#=MDW T 105,Reach-1,1
Up Type=0
Dn Type=3
Dn Slope=0.005
Boundary for River Rch & Prof#=MDW T 105,Reach-1,2
Up Type=0
Dn Type=3
Dn Slope=0.005
Boundary for River Rch & Prof#=MDW T 105,Reach-1,3
Up Type=0
Dn Type=3
Dn Slope=0.005
Boundary for River Rch & Prof#=MDW T 105,Reach-1,4
Up Type=0
Dn Type=3
Dn Slope=0.005
Boundary for River Rch & Prof#=MDW T 105,Reach-1,5
Up Type=0
Dn Type=3
Dn Slope=0.005
Boundary for River Rch & Prof#=MDW T 105,Reach-1,6
Up Type=0
Dn Type=3
Dn Slope=0.005
Boundary for River Rch & Prof#=MDW T 105,Reach-1,7
Up Type=0
Dn Type=3
Dn Slope=0.005

--- MDW T 105.g01 (geometry) ---

Geom Title=Existing Conditions

River Reach=MDW T 105,Reach-1
Reach XY= 30
      2272529.00      7130010.00      2272526.94      7130104.17
      2272473.42      7130204.42      2272229.66      7130325.82
      2272238.45      7130756.12      2272260.57      7130819.07
      2272339.07      7130839.12      2272398.19      7130936.20
      2272297.13      7130985.44      2272244.59      7130964.67
      2272214.40      7130983.69      2272199.05      7131062.70
      2272223.98      7131085.14      2272300.31      7131077.17
      2272367.13      7131131.86      2272378.08      7131174.43
      2272321.45      7131244.36      2272350.31      7131366.25
      2272334.14      7131446.22      2272366.56      7131535.33
      2272359.68      7131576.77      2272316.71      7131573.47
      2272231.37      7131505.09      2272190.82      7131503.74
      2272044.73      7131682.86      2272051.74      7131713.82
      2272097.64      7131749.00      2272121.41      7131809.07
      2272105.72      7131838.11      2272129.00      7131860.00

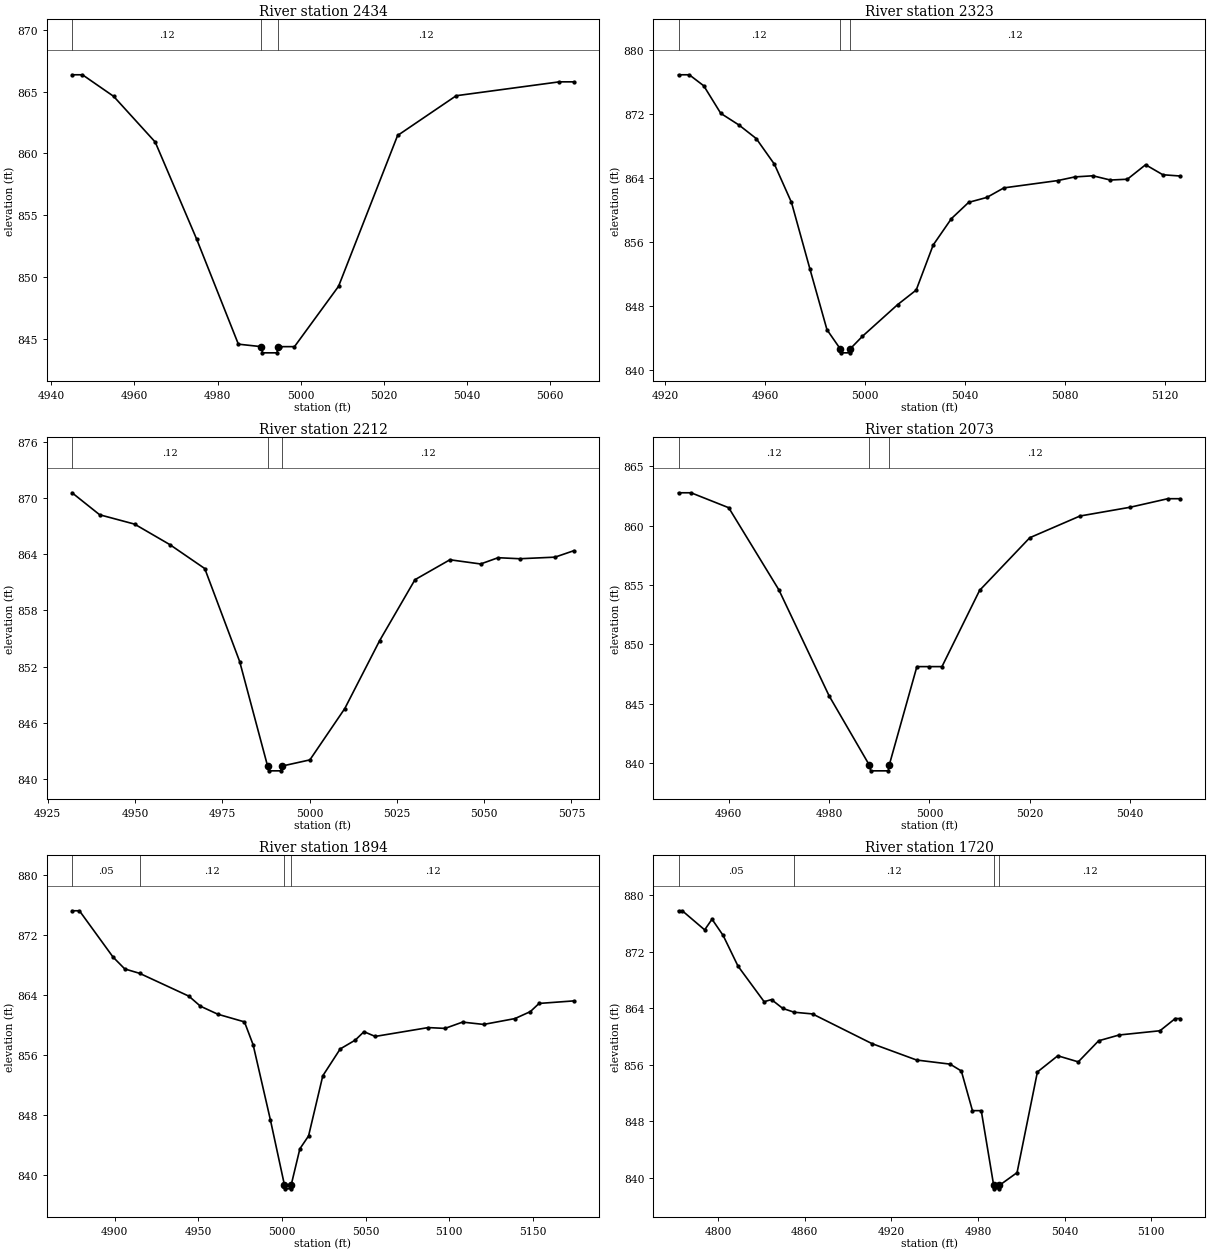
Type RM Length L Ch R = 1,2434,111,111,111
BEGIN DESCRIPTION:
MDW T 105 5.0
END DESCRIPTION:
XS GIS Cut Line= 3
      2272329.00      7130209.99      2272329.00      7130260.00
      2272378.99      7130309.99
#Sta/Elev= 17
  4945.0  866.35  4947.5  866.35  4955.0  864.61  4965.0  860.92  4975.0  853.06
  4985.0  844.61  4990.5  844.41  4990.8  843.91  4994.3  843.91  4994.5  844.41
  4995.0  844.41  4998.5  844.41  5009.1  849.28  5023.3  861.45  5037.4  864.66
  5062.2  865.78  5065.7  865.78
#Mann=3,-1,0
  4945.0    0.12       0  4990.5    0.07       0  4994.5    0.12       0
Bank Sta=4990.5,4994.5
Exp/Cntr=0.3,0.1

Type RM Length L Ch R = 1,2323,111,111,111
BEGIN DESCRIPTION:
Mapping XS 2514ade8
END DESCRIPTION:
XS GIS Cut Line= 2
      2272186.07      7130258.77      2272323.06      7130405.59
#Sta/Elev= 30
  4925.3  876.93  4929.6  876.93  4935.4  875.55  4942.2  872.11  4949.5  870.65
  4956.4  868.96  4963.7  865.74  4970.5  860.98  4977.9  852.64  4984.7  845.08
  4990.0  842.69  4990.3  842.19  4993.8  842.19  4994.0  842.69  4998.9  844.26
  5013.0  848.22  5020.4  850.03  5027.2  855.66  5034.5  858.96  5041.4  860.99
  5048.7  861.61  5055.5  862.80  5077.0  863.71  5083.9  864.17  5091.1  864.31
  5098.1  863.78  5104.9  863.88  5112.2  865.69  5119.1  864.44  5126.1  864.28
#Mann=3,-1,0
  4925.3    0.12       0  4990.0    0.07       0  4994.0    0.12       0
Bank Sta=4990,4994
Exp/Cntr=0.3,0.1

Type RM Length L Ch R = 1,2212,139,139,139
BEGIN DESCRIPTION:
Mapping XS c137d0ae
END DESCRIPTION:
XS GIS Cut Line= 2
      2272161.10      7130416.43      2272304.44      7130426.62
#Sta/Elev= 20
  4932.0  870.58  4939.9  868.23  4949.9  867.23  4960.0  865.04  4970.0  862.48
  4980.0  852.54  4988.0  841.36  4988.3  840.86  4991.8  840.86  4992.0  841.36
  5000.1  842.03  5010.1  847.52  5020.1  854.79  5030.2  861.29  5040.2  863.42
  5049.0  862.97  5054.0  863.64  5060.2  863.53  5070.3  863.70  5075.7  864.39
#Mann=3,-1,0
  4932.0    0.12       0  4988.0    0.07       0  4992.0    0.12       0
Bank Sta=4988,4992
Exp/Cntr=0.3,0.1

Type RM Length L Ch R = 1,2073,179,179,179
BEGIN DESCRIPTION:
MDW T 105 4.0
END DESCRIPTION:
XS GIS Cut Line= 3
      2272178.98      7130560.00      2272229.00      7130560.00
      2272278.98      7130560.00
#Sta/Elev= 18
  4950.0  862.78  4952.5  862.78  4960.0  861.52  4970.0  854.59  4980.0  845.66
  4988.0  839.83  4988.3  839.33  4991.8  839.33  4992.0  839.83  4997.5  848.12
  5000.0  848.12  5002.5  848.12  5010.0  854.55  5020.0  858.99  5030.0  860.82
  5040.0  861.56  5047.5  862.28  5050.0  862.28
#Mann=3,-1,0
  4950.0    0.12       0  4988.0    0.07       0  4992.0    0.12       0
Bank Sta=4988,4992
Exp/Cntr=0.3,0.1

Type RM Length L Ch R = 1,1894,174,174,174
BEGIN DESCRIPTION:
Mapping XS 5d90ae09
END DESCRIPTION:
XS GIS Cut Line= 2
      2272115.50      7130774.52      2272402.76      7130688.71
#Sta/Elev= 30
  4874.6  875.23  4879.0  875.23  4899.1  869.05  4906.1  867.47  4914.9  866.89
  4944.4  863.84  4951.3  862.50  4961.7  861.43  4977.6  860.41  4982.8  857.34
  4993.1  847.33  5001.5  838.64  5001.7  838.14  5005.2  838.14  5005.5  838.64
  5010.7  843.48  5015.9  845.20  5024.4  853.22  5034.8  856.80  5043.8  857.98
  5049.0  859.10  5055.7  858.47  5087.4  859.65  5097.4  859.54  5107.9  860.38
  5120.5  860.07  5139.2  860.85  5148.4  861.78  5153.6  862.87  5174.4  863.21
#Mann=4,-1,0
  4874.6    0.05       0  4914.9    0.12       0  5001.5    0.07       0
  5005.5    0.12       0
Bank Sta=5001.5,5005.5
Exp/Cntr=0.3,0.1

Type RM Length L Ch R = 1,1720,100,100,100
BEGIN DESCRIPTION:
MDW T 105 3.0
END DESCRIPTION:
XS GIS Cut Line= 3
      2272128.98      7130910.00      2272329.00      7130860.00
      2272429.01      7130759.99
#Sta/Elev= 30
  4772.6  877.79  4775.2  877.79  4790.7  875.09  4795.8  876.60  4803.5  874.30
  4813.8  869.96  4831.9  864.93  4837.0  865.23  4844.8  863.98  4852.7  863.44
  4865.4  863.20  4906.6  859.00  4937.5  856.68  4960.7  856.10  4968.5  855.13
  4976.2  849.52  4982.3  849.52  4990.9  838.96  4991.2  838.46  4994.7  838.46
  4994.9  838.96  5007.1  840.75  5021.2  854.99  5035.3  857.28  5049.5  856.42
  5063.6  859.40  5077.8  860.22  5106.1  860.82  5116.7  862.55  5120.2  862.55
#Mann=4,-1,0
  4772.6    0.05       0  4852.7    0.12       0  4990.9    0.07       0
  4994.9    0.12       0
Bank Sta=4990.9,4994.9
Exp/Cntr=0.3,0.1

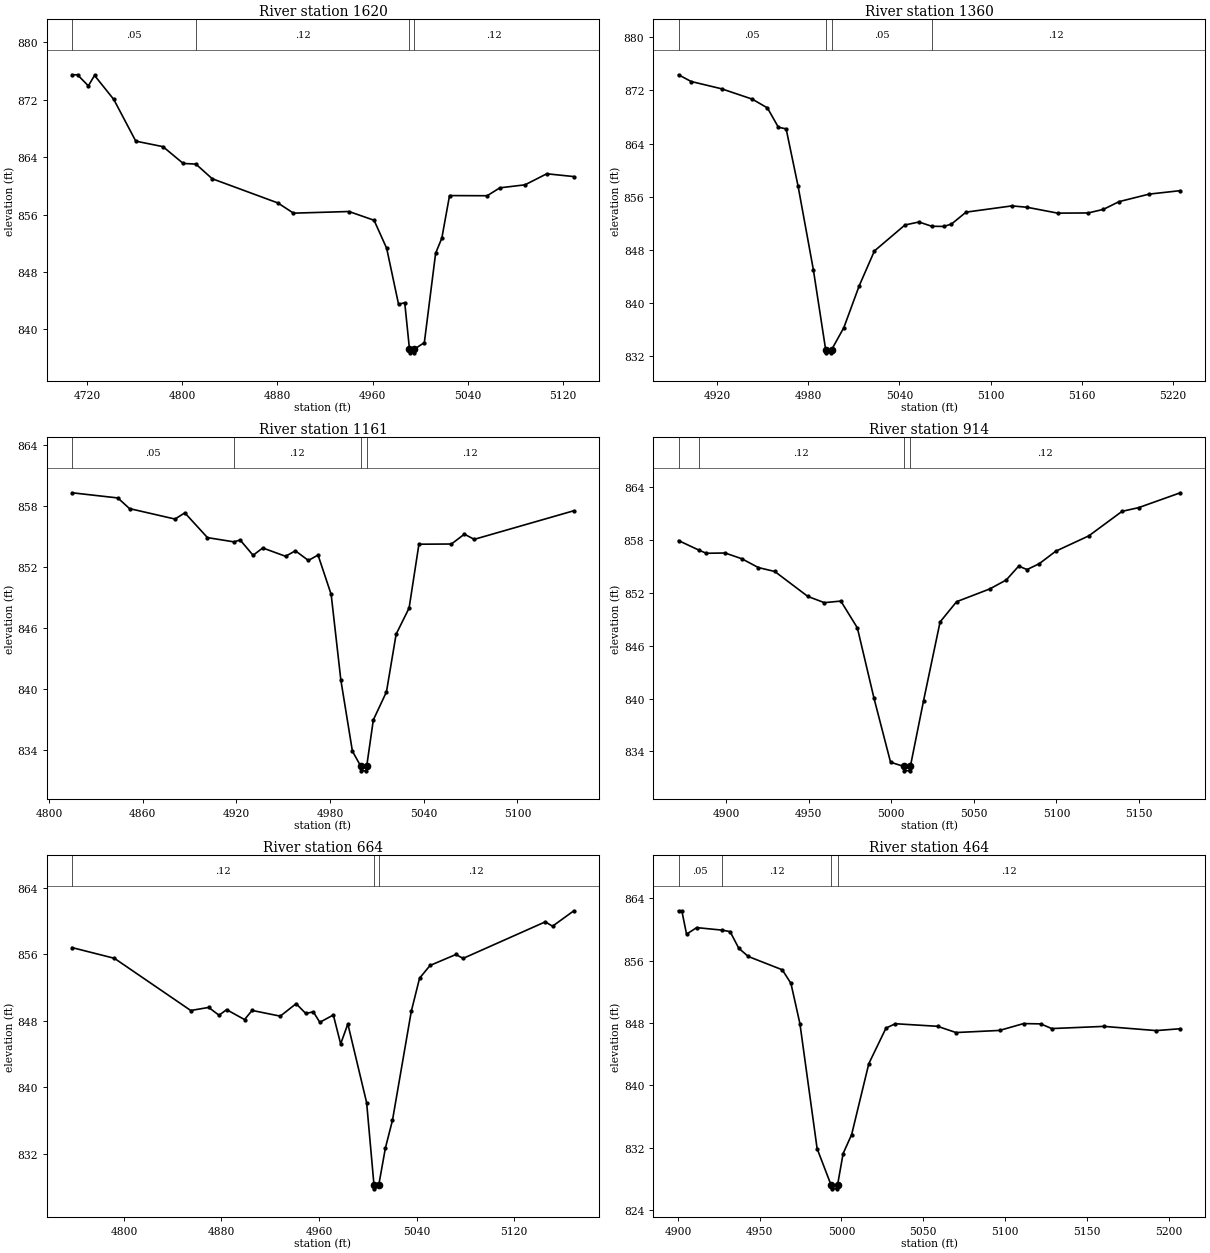
Type RM Length L Ch R = 1,1620,260,260,260
BEGIN DESCRIPTION:
Mapping XS f591f1b3
END DESCRIPTION:
XS GIS Cut Line= 3
      2272115.16      7130939.76      2272289.23      7130892.71
      2272517.89      7130971.60
#Sta/Elev= 30
  4707.2  875.49  4711.8  875.49  4720.9  873.94  4726.1  875.40  4742.3  872.05
  4760.8  866.24  4783.7  865.47  4800.7  863.13  4811.4  863.04  4825.1  861.00
  4880.4  857.62  4893.5  856.20  4940.2  856.43  4961.3  855.21  4971.9  851.30
  4981.9  843.50  4987.1  843.72  4991.1  837.23  4991.3  836.73  4994.8  836.73
  4995.1  837.23  5003.6  838.16  5013.1  850.62  5018.3  852.71  5024.8  858.65
  5056.5  858.63  5067.1  859.73  5088.3  860.15  5106.6  861.69  5129.4  861.30
#Mann=4,-1,0
  4707.2    0.05       0  4811.4    0.12       0  4991.1    0.07       0
  4995.1    0.12       0
Bank Sta=4991.1,4995.1
Exp/Cntr=0.3,0.1

Type RM Length L Ch R = 1,1360,199,199,199
BEGIN DESCRIPTION:
Mapping XS 2249f8ad
END DESCRIPTION:
XS GIS Cut Line= 3
      2272100.79      7131017.81      2272268.04      7131035.62
      2272429.38      7131020.92
#Sta/Elev= 30
  4894.6  874.33  4902.9  873.32  4923.0  872.22  4943.1  870.67  4953.1  869.35
  4960.3  866.44  4965.4  866.21  4973.3  857.55  4983.3  845.07  4991.4  833.05
  4991.6  832.55  4995.1  832.55  4995.4  833.05  5003.4  836.35  5013.5  842.63
  5023.5  847.86  5043.6  851.76  5052.8  852.21  5061.2  851.57  5069.2  851.54
  5074.2  851.90  5083.8  853.69  5114.0  854.63  5124.0  854.42  5144.1  853.54
  5164.2  853.57  5174.2  854.11  5184.5  855.27  5204.3  856.40  5224.8  856.92
#Mann=4,-1,0
  4894.6    0.05       0  4991.4   0.033       0  4995.4    0.05       0
  5061.2    0.12       0
Bank Sta=4991.4,4995.4
Exp/Cntr=0.3,0.1

Type RM Length L Ch R = 1,1161,247,247,247
BEGIN DESCRIPTION:
Mapping XS 0642000c
END DESCRIPTION:
XS GIS Cut Line= 2
      2272195.63      7131217.88      2272452.27      7131024.56
#Sta/Elev= 30
  4814.8  859.32  4844.1  858.81  4851.6  857.76  4880.7  856.73  4887.0  857.34
  4901.5  854.90  4918.5  854.48  4922.4  854.67  4930.7  853.16  4936.9  853.88
  4951.5  853.06  4957.8  853.60  4966.1  852.65  4972.3  853.18  4980.7  849.30
  4986.9  840.86  4994.3  833.85  4999.5  832.41  4999.7  831.91  5003.2  831.91
  5003.5  832.41  5007.7  836.93  5016.1  839.69  5022.3  845.38  5030.6  847.96
  5036.9  854.25  5057.7  854.27  5066.0  855.24  5072.3  854.73  5136.1  857.55
#Mann=4,-1,0
  4814.8    0.05       0  4918.5    0.12       0  4999.5    0.07       0
  5003.5    0.12       0
Bank Sta=4999.5,5003.5
Exp/Cntr=0.3,0.1

Type RM Length L Ch R = 1,914,250,250,250
BEGIN DESCRIPTION:
Mapping XS 61bf007b
END DESCRIPTION:
XS GIS Cut Line= 2
      2272210.80      7131313.92      2272514.27      7131330.06
#Sta/Elev= 30
  4871.1  857.94  4883.3  856.87  4887.9  856.50  4899.3  856.53  4909.4  855.88
  4919.4  854.88  4929.4  854.43  4949.4  851.60  4959.4  850.89  4969.4  851.07
  4979.4  848.03  4989.5  840.02  4999.5  832.77  5007.5  832.29  5007.7  831.79
  5011.2  831.79  5011.5  832.29  5019.5  839.76  5029.5  848.70  5039.5  851.00
  5059.6  852.45  5069.6  853.47  5077.1  855.04  5082.2  854.65  5089.6  855.32
  5099.6  856.74  5119.6  858.48  5139.7  861.26  5149.7  861.68  5175.0  863.37
#Mann=4,-1,0
  4871.1    0.05       0  4883.3    0.12       0  5007.5    0.07       0
  5011.5    0.12       0
Bank Sta=5007.5,5011.5
Exp/Cntr=0.3,0.1

Type RM Length L Ch R = 1,664,200,200,200
BEGIN DESCRIPTION:
Mapping XS 0fce1c87
END DESCRIPTION:
XS GIS Cut Line= 3
      2272210.28      7131371.42      2272330.26      7131536.36
      2272506.53      7131645.72
#Sta/Elev= 30
  4757.5  856.83  4792.2  855.54  4854.8  849.26  4869.5  849.63  4878.0  848.69
  4884.2  849.36  4898.9  848.17  4905.1  849.27  4928.2  848.58  4941.2  850.08
  4949.1  848.90  4955.3  849.10  4960.6  847.84  4971.7  848.72  4977.7  845.24
  4983.6  847.64  4999.0  838.17  5005.0  828.30  5005.3  827.80  5009.0  828.30
  5014.4  832.72  5020.2  836.06  5035.6  849.15  5042.4  853.15  5051.0  854.68
  5072.2  856.00  5078.1  855.53  5145.5  859.93  5151.4  859.40  5168.9  861.26
#Mann=3,-1,0
  4757.5    0.12       0  5005.0    0.07       0  5009.0    0.12       0
Bank Sta=5005,5009
Exp/Cntr=0.3,0.1

Type RM Length L Ch R = 1,464,200,200,200
BEGIN DESCRIPTION:
Mapping XS a2381dc6
END DESCRIPTION:
XS GIS Cut Line= 2
      2272172.76      7131409.49      2272267.96      7131701.04
#Sta/Elev= 30
  4900.4  862.39  4902.4  862.39  4905.3  859.39  4911.5  860.23  4926.9  859.91
  4931.9  859.72  4937.2  857.59  4943.0  856.53  4963.8  854.82  4969.1  853.08
  4974.6  847.90  4985.1  831.88  4993.6  827.22  4993.9  826.72  4997.4  826.72
  4997.6  827.22  5001.0  831.25  5006.2  833.68  5016.7  842.78  5027.2  847.34
  5032.9  847.90  5058.7  847.57  5070.0  846.77  5096.6  847.04  5111.3  847.92
  5121.8  847.88  5128.5  847.28  5160.4  847.56  5192.3  847.02  5207.1  847.26
#Mann=4,-1,0
  4900.4    0.05       0  4926.9    0.12       0  4993.6    0.07       0
  4997.6    0.12       0
Bank Sta=4993.6,4997.6
Exp/Cntr=0.3,0.1

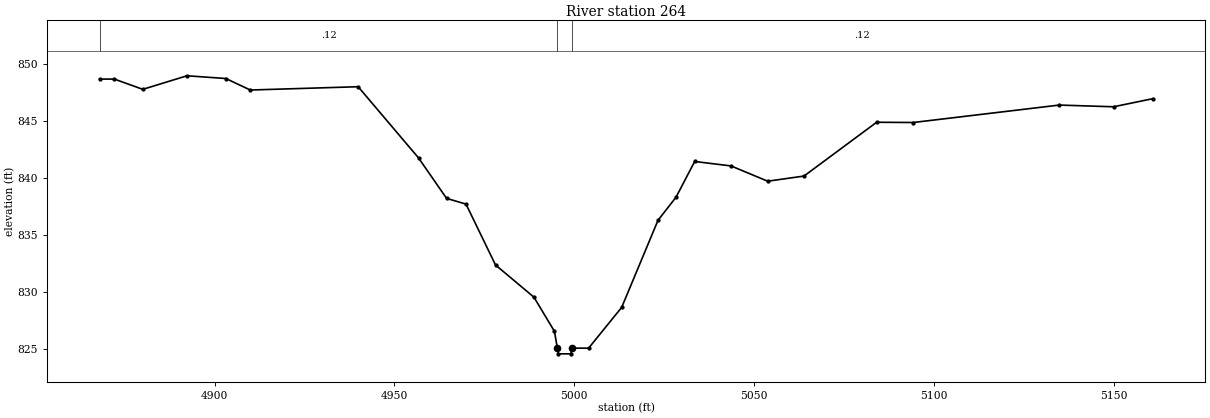
Type RM Length L Ch R = 1,264,0,0,0
BEGIN DESCRIPTION:
MDW T 105 1.0
END DESCRIPTION:
XS GIS Cut Line= 3
      2272028.35      7131527.29      2272075.86      7131650.34
      2272234.67      7131676.82
#Sta/Elev= 30
  4868.0  848.71  4872.1  848.71  4880.0  847.81  4892.3  849.00  4903.1  848.76
  4909.9  847.75  4939.9  848.04  4956.7  841.79  4964.5  838.24  4969.9  837.74
  4978.1  832.40  4988.8  829.57  4994.5  826.57  4995.3  825.10  4995.6  824.60
  4999.1  824.60  4999.3  825.10  5004.0  825.10  5013.2  828.68  5023.3  836.32
  5028.3  838.34  5033.5  841.48  5043.6  841.09  5053.8  839.75  5063.9  840.20
  5084.1  844.92  5094.3  844.90  5134.9  846.43  5150.0  846.28  5160.9  846.99
#Mann=3,-1,0
  4868.0    0.12       0  4995.3    0.07       0  4999.3    0.12       0
Bank Sta=4995.3,4999.3
Exp/Cntr=0.3,0.1

Chan Stop Cuts=-1