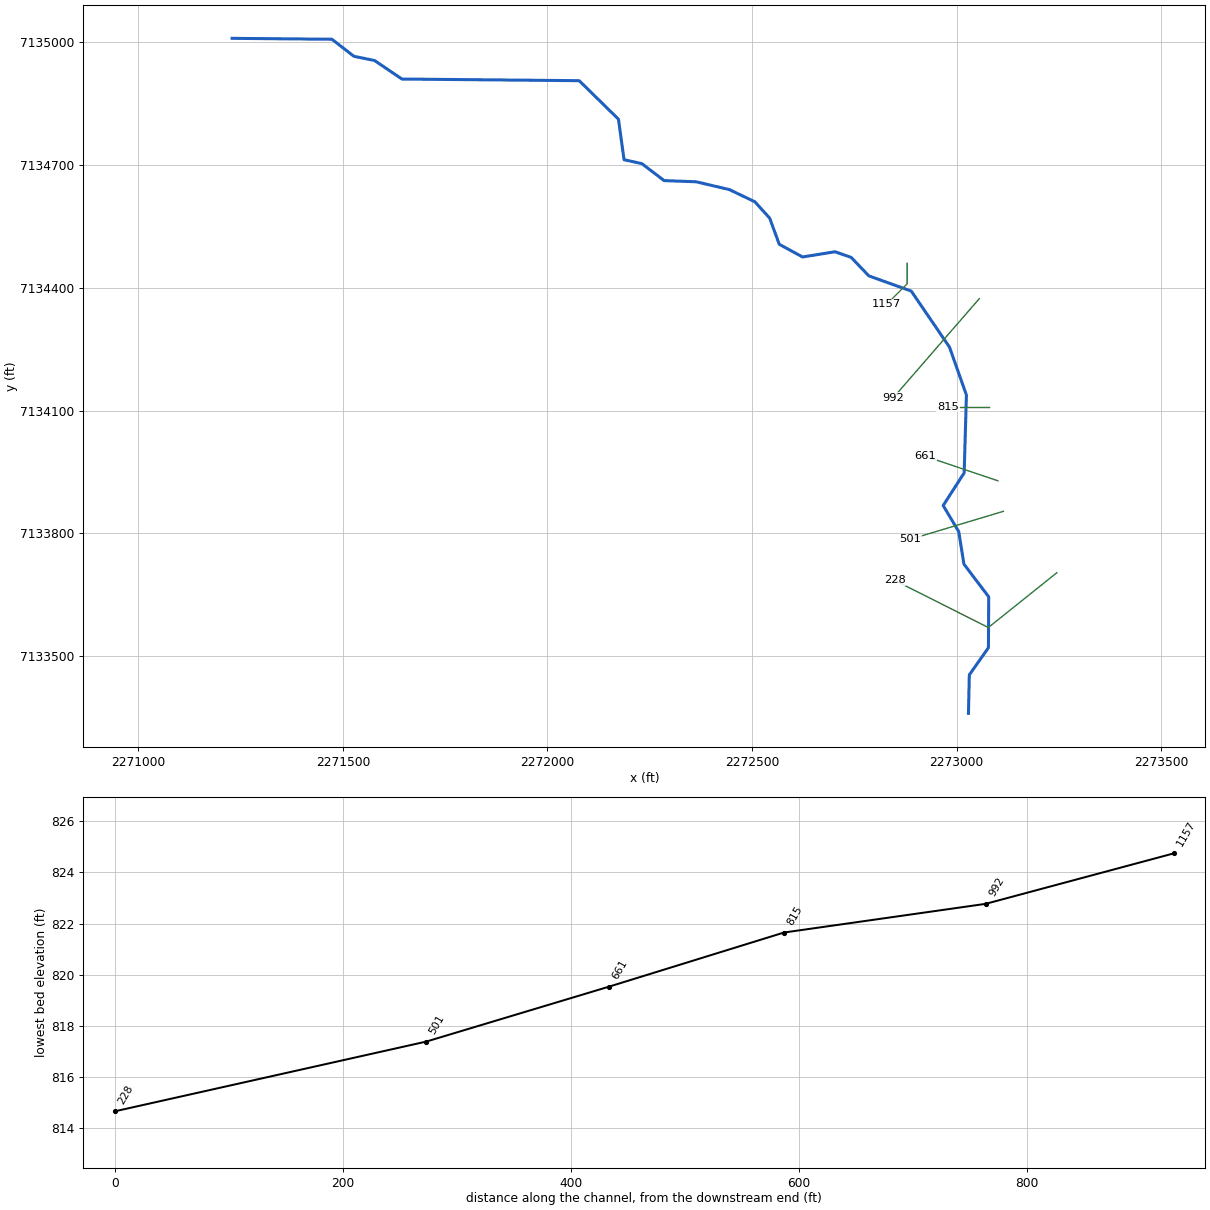
--- MDW T 106.prj (project) ---

Proj Title=MDW T 106 Base Level Engineering
Current Plan=p01
Default Exp/Contr=0.3,0.1
English Units
Geom File=g01
Flow File=f01
Plan File=p01
BEGIN DESCRIPTION:
MDW T 106
END DESCRIPTION:

--- MDW T 106.p01 (plan) ---

Plan Title=Multiple Run
Short Identifier=Multiple
Geom File=g01
Flow File=f01
Subcritical Flow
K Sum by GR= 0
Std Step Tol= 0.01
Critical Tol= 0.01
Num of Std Step Trials= 20
Max Error Tol= 0.3
Flow Tol Ratio= 0.001
Split Flow NTrial= 30
Split Flow Tol= 0.02
Split Flow Ratio= 0.02
Log Output Level= 0
Friction Slope Method= 1
Unsteady Friction Slope Method= 2
Unsteady Bridges Friction Slope Method= 1
Parabolic Critical Depth
Global Vel Dist=  1 , 1 , 1
Global Log Level= 0
CheckData=True
Encroach Param= -1, 0, 0, 0
BEGIN DESCRIPTION:
Multiple Run
END DESCRIPTION:

--- MDW T 106.f01 (steady flow) ---

Flow Title=Multiple
Number of Profiles=7
Profile Names=10-year,25-year,50-year,1pct_min,100-year,1pct_plu,500-year
River Rch & RM= MDW T 106,Reach-1,1157
     592     815    1001     611    1220    2433    1813
Boundary for River Rch & Prof#=MDW T 106,Reach-1,1
Up Type=0
Dn Type=3
Dn Slope=0.005
Boundary for River Rch & Prof#=MDW T 106,Reach-1,2
Up Type=0
Dn Type=3
Dn Slope=0.005
Boundary for River Rch & Prof#=MDW T 106,Reach-1,3
Up Type=0
Dn Type=3
Dn Slope=0.005
Boundary for River Rch & Prof#=MDW T 106,Reach-1,4
Up Type=0
Dn Type=3
Dn Slope=0.005
Boundary for River Rch & Prof#=MDW T 106,Reach-1,5
Up Type=0
Dn Type=3
Dn Slope=0.005
Boundary for River Rch & Prof#=MDW T 106,Reach-1,6
Up Type=0
Dn Type=3
Dn Slope=0.005
Boundary for River Rch & Prof#=MDW T 106,Reach-1,7
Up Type=0
Dn Type=3
Dn Slope=0.005

--- MDW T 106.g01 (geometry) ---

Geom Title=Existing Conditions

River Reach=MDW T 106,Reach-1
Reach XY= 30
      2271229.00      7135010.00      2271473.07      7135007.76
      2271526.82      7134966.12      2271577.26      7134955.81
      2271644.21      7134910.51      2272077.55      7134906.47
      2272173.46      7134812.38      2272187.15      7134713.37
      2272230.78      7134703.70      2272284.94      7134662.32
      2272363.73      7134659.35      2272444.69      7134640.23
      2272507.09      7134610.39      2272543.09      7134570.51
      2272566.54      7134506.60      2272623.46      7134475.62
      2272702.81      7134488.33      2272742.22      7134474.57
      2272785.58      7134429.33      2272889.15      7134392.26
      2272982.71      7134255.10      2273024.02      7134138.10
      2273018.51      7133947.82      2272967.20      7133867.99
      2273005.26      7133804.21      2273017.88      7133724.98
      2273078.51      7133644.78      2273077.81      7133520.50
      2273031.10      7133454.13      2273029.00      7133360.00

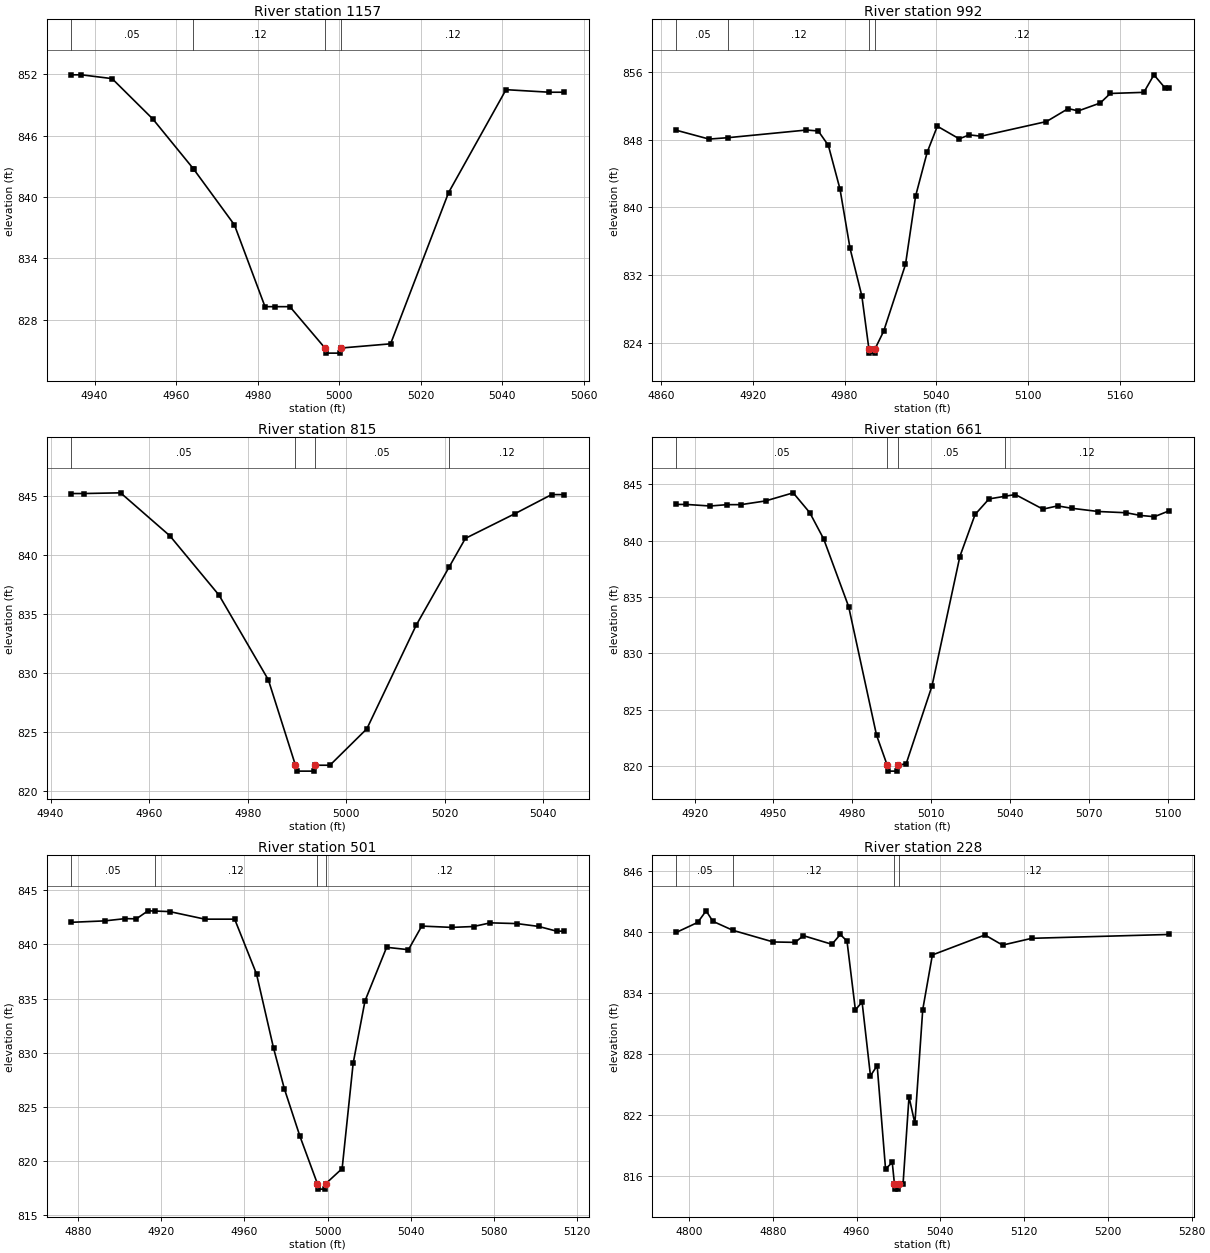
Type RM Length L Ch R = 1,1157,165,165,165
BEGIN DESCRIPTION:
MDW T 106 3.0
END DESCRIPTION:
XS GIS Cut Line= 3
      2272879.00      7134460.04      2272879.00      7134410.00
      2272828.97      7134359.97
#Sta/Elev= 19
  4934.3  851.93  4936.8  851.93  4944.3  851.56  4954.3  847.61  4964.2  842.77
  4964.3  842.72  4974.3  837.27  4981.8  829.28  4984.3  829.28  4987.9  829.28
  4996.5  825.24  4996.7  824.74  5000.2  824.74  5000.5  825.24  5012.6  825.65
  5026.8  840.41  5040.9  850.48  5051.5  850.23  5055.1  850.23
#Mann=4,-1,0
  4934.3    0.05       0  4964.2    0.12       0  4996.5    0.07       0
  5000.5    0.12       0
Bank Sta=4996.5,5000.5
Exp/Cntr=0.3,0.1

Type RM Length L Ch R = 1,992,177,177,177
BEGIN DESCRIPTION:
Mapping XS 078963af
END DESCRIPTION:
XS GIS Cut Line= 2
      2273055.63      7134373.81      2272844.65      7134130.81
#Sta/Elev= 30
  4870.2  849.09  4891.5  848.05  4904.1  848.22  4955.1  849.12  4962.8  849.01
  4969.4  847.31  4977.0  842.16  4983.6  835.13  4991.3  829.51  4995.9  823.27
  4996.1  822.77  4999.6  822.77  4999.9  823.27  5005.5  825.34  5019.8  833.24
  5026.4  841.32  5034.0  846.51  5040.6  849.57  5054.9  848.08  5061.5  848.55
  5069.1  848.39  5111.9  850.12  5126.1  851.65  5132.7  851.38  5147.0  852.31
  5153.6  853.44  5175.5  853.57  5182.1  855.64  5189.2  854.12  5192.0  854.12
#Mann=4,-1,0
  4870.2    0.05       0  4904.1    0.12       0  4995.9    0.07       0
  4999.9    0.12       0
Bank Sta=4995.9,4999.9
Exp/Cntr=0.3,0.1

Type RM Length L Ch R = 1,815,154,154,154
BEGIN DESCRIPTION:
MDW T 106 2.0
END DESCRIPTION:
XS GIS Cut Line= 3
      2273079.00      7134110.00      2273029.00      7134110.00
      2272979.00      7134110.00
#Sta/Elev= 18
  4944.2  845.18  4946.7  845.18  4954.2  845.24  4964.2  841.60  4974.2  836.56
  4984.2  829.39  4989.7  822.15  4990.0  821.65  4993.5  821.65  4993.7  822.15
  4996.7  822.15  5004.2  825.24  5014.2  834.01  5020.9  838.95  5024.2  841.38
  5034.2  843.46  5041.7  845.09  5044.2  845.09
#Mann=4,-1,0
  4944.2    0.05       0  4989.7   0.033       0  4993.7    0.05       0
  5020.9    0.12       0
Bank Sta=4989.7,4993.7
Exp/Cntr=0.3,0.1

Type RM Length L Ch R = 1,661,160,160,160
BEGIN DESCRIPTION:
Mapping XS e0f9a423
END DESCRIPTION:
XS GIS Cut Line= 2
      2273101.08      7133928.45      2272923.55      7133988.45
#Sta/Elev= 30
  4913.1  843.22  4916.8  843.22  4925.9  843.08  4932.4  843.20  4937.6  843.20
  4947.0  843.53  4957.5  844.25  4963.8  842.49  4969.1  840.15  4978.6  834.14
  4989.2  822.73  4993.3  820.03  4993.5  819.53  4997.0  819.53  4997.3  820.03
  5000.5  820.20  5010.3  827.09  5020.9  838.59  5026.7  842.33  5032.0  843.71
  5038.0  843.94  5042.0  844.10  5052.5  842.80  5058.1  843.09  5063.4  842.88
  5073.6  842.59  5084.2  842.48  5089.6  842.24  5094.9  842.13  5100.5  842.65
#Mann=4,-1,0
  4913.1    0.05       0  4993.3   0.033       0  4997.3    0.05       0
  5038.0    0.12       0
Bank Sta=4993.3,4997.3
Exp/Cntr=0.3,0.1

Type RM Length L Ch R = 1,501,273,273,273
BEGIN DESCRIPTION:
Mapping XS b352dc70
END DESCRIPTION:
XS GIS Cut Line= 2
      2273114.32      7133853.89      2272887.36      7133785.63
#Sta/Elev= 30
  4876.7  842.04  4892.7  842.17  4902.7  842.38  4908.0  842.36  4913.6  843.10
  4916.9  843.08  4924.0  843.03  4941.0  842.33  4955.3  842.33  4965.8  837.27
  4974.0  830.42  4979.2  826.66  4986.7  822.27  4995.1  817.89  4995.4  817.39
  4998.9  817.39  4999.1  817.89  5007.0  819.29  5012.3  829.02  5018.0  834.78
  5028.4  839.73  5038.9  839.51  5045.3  841.69  5059.8  841.57  5070.2  841.65
  5078.3  841.99  5091.1  841.92  5101.5  841.66  5110.2  841.22  5113.7  841.22
#Mann=4,-1,0
  4876.7    0.05       0  4916.9    0.12       0  4995.1    0.07       0
  4999.1    0.12       0
Bank Sta=4995.1,4999.1
Exp/Cntr=0.3,0.1

Type RM Length L Ch R = 1,228,0,0,0
BEGIN DESCRIPTION:
MDW T 106 1.0
END DESCRIPTION:
XS GIS Cut Line= 3
      2273244.88      7133703.71      2273077.62      7133569.84
      2272848.90      7133684.98
#Sta/Elev= 30
  4788.1  839.99  4808.4  840.97  4816.4  842.11  4822.8  841.08  4841.9  840.19
  4880.5  839.04  4901.3  839.00  4909.3  839.66  4936.5  838.81  4944.5  839.78
  4950.9  839.12  4958.9  832.34  4965.3  833.12  4973.3  825.84  4979.7  826.85
  4987.7  816.66  4994.1  817.30  4996.2  815.17  4996.5  814.67  5000.0  814.67
  5000.2  815.17  5004.4  815.17  5010.1  823.77  5015.7  821.15  5023.2  832.37
  5032.4  837.76  5082.6  839.73  5099.4  838.73  5127.3  839.40  5258.4  839.78
#Mann=4,-1,0
  4788.1    0.05       0  4841.9    0.12       0  4996.2    0.07       0
  5000.2    0.12       0
Bank Sta=4996.2,5000.2
Exp/Cntr=0.3,0.1

Chan Stop Cuts=-1