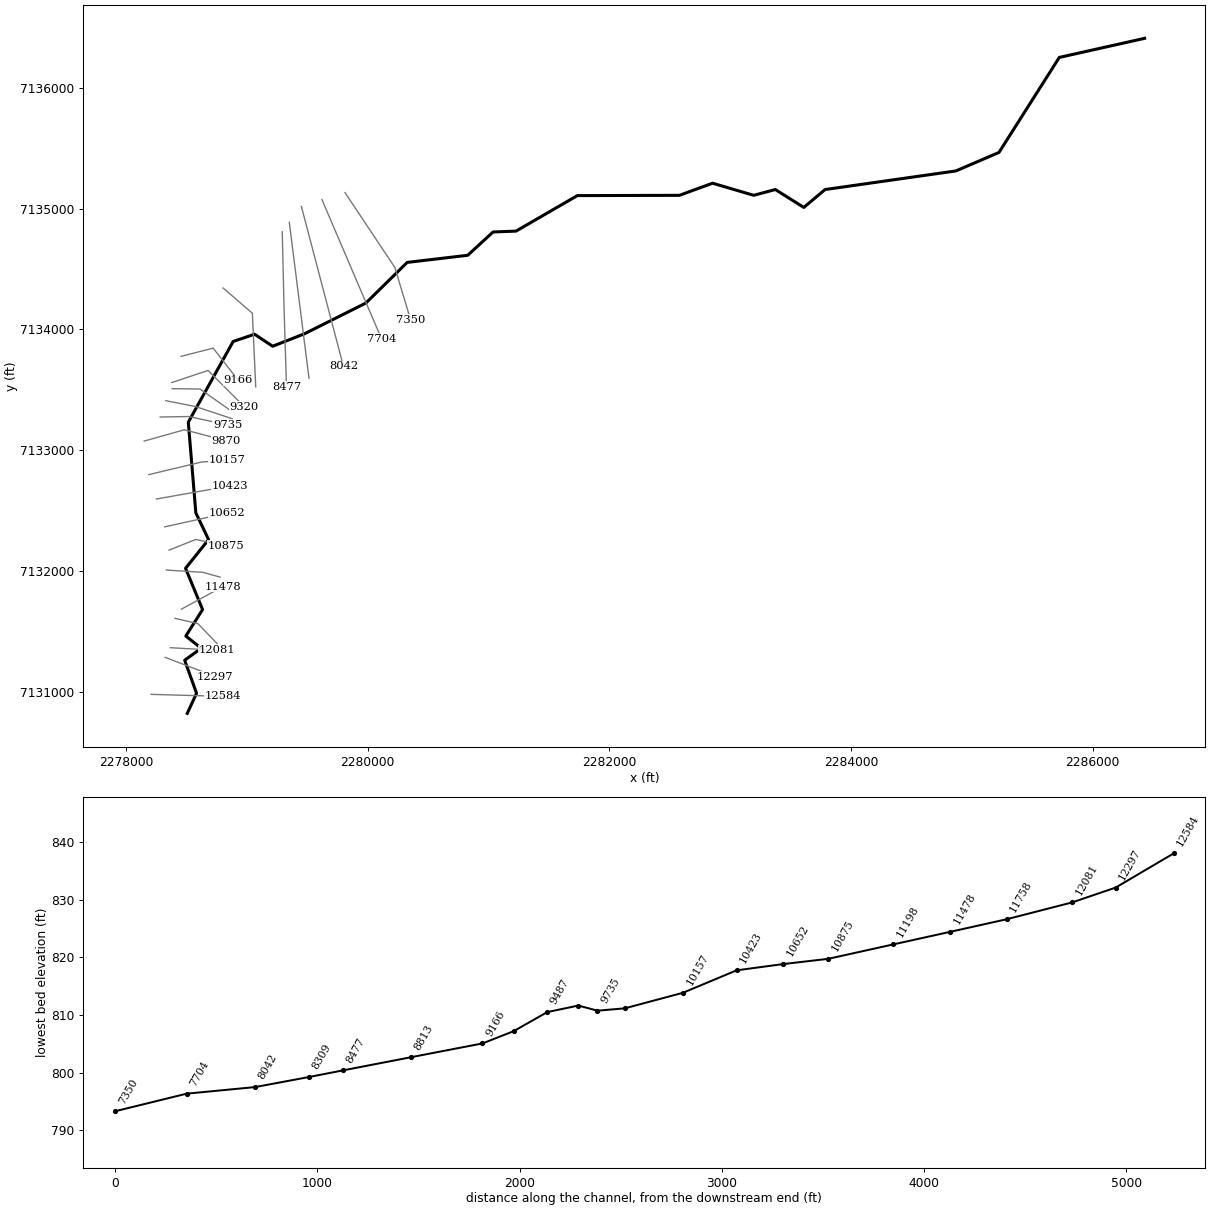
--- MDW T 107.prj (project) ---

Proj Title=MDW T 107 Base Level Engineering
Current Plan=p01
Default Exp/Contr=0.3,0.1
English Units
Geom File=g01
Flow File=f01
Plan File=p01
BEGIN DESCRIPTION:
MDW T 107
END DESCRIPTION:

--- MDW T 107.p01 (plan) ---

Plan Title=Multiple Run
Short Identifier=Multiple
Geom File=g01
Flow File=f01
Subcritical Flow
K Sum by GR= 0
Std Step Tol= 0.01
Critical Tol= 0.01
Num of Std Step Trials= 20
Max Error Tol= 0.3
Flow Tol Ratio= 0.001
Split Flow NTrial= 30
Split Flow Tol= 0.02
Split Flow Ratio= 0.02
Log Output Level= 0
Friction Slope Method= 1
Unsteady Friction Slope Method= 2
Unsteady Bridges Friction Slope Method= 1
Parabolic Critical Depth
Global Vel Dist=  1 , 1 , 1
Global Log Level= 0
CheckData=True
Encroach Param= -1, 0, 0, 0
BEGIN DESCRIPTION:
Multiple Run
END DESCRIPTION:

--- MDW T 107.f01 (steady flow) ---

Flow Title=Multiple
Number of Profiles=7
Profile Names=10-year,25-year,50-year,1pct_min,100-year,1pct_plu,500-year
River Rch & RM= MDW T 107,Reach-1,12584
     944    1368    1741    1103    2201    4392    3524
River Rch & RM= MDW T 107,Reach-1,9320
     775    1085    1347     831    1659    3309    2519
River Rch & RM= MDW T 107,Reach-1,7350
     811    1137    1412     871    1738    3468    2640
Boundary for River Rch & Prof#=MDW T 107,Reach-1,1
Up Type=0
Dn Type=3
Dn Slope=0.005
Boundary for River Rch & Prof#=MDW T 107,Reach-1,2
Up Type=0
Dn Type=3
Dn Slope=0.005
Boundary for River Rch & Prof#=MDW T 107,Reach-1,3
Up Type=0
Dn Type=3
Dn Slope=0.005
Boundary for River Rch & Prof#=MDW T 107,Reach-1,4
Up Type=0
Dn Type=3
Dn Slope=0.005
Boundary for River Rch & Prof#=MDW T 107,Reach-1,5
Up Type=0
Dn Type=3
Dn Slope=0.005
Boundary for River Rch & Prof#=MDW T 107,Reach-1,6
Up Type=0
Dn Type=3
Dn Slope=0.005
Boundary for River Rch & Prof#=MDW T 107,Reach-1,7
Up Type=0
Dn Type=3
Dn Slope=0.005

--- MDW T 107.g01 (geometry) ---

Geom Title=Existing Conditions

River Reach=MDW T 107,Reach-1
Reach XY= 30
      2278506.96      7130820.42      2278583.61      7130986.92
      2278485.52      7131260.19      2278622.15      7131359.73
      2278494.76      7131460.82      2278633.68      7131680.11
      2278492.79      7132021.52      2278683.11      7132259.72
      2278577.79      7132480.74      2278515.51      7133231.17
      2278886.54      7133899.83      2279063.90      7133959.80
      2279213.60      7133860.31      2279477.42      7133963.83
      2279985.05      7134218.16      2280326.55      7134554.53
      2280827.54      7134613.54      2281037.44      7134806.60
      2281227.45      7134813.75      2281734.93      7135107.76
      2282579.00      7135110.00      2282854.00      7135210.40
      2283194.39      7135110.09      2283373.11      7135158.04
      2283608.94      7135009.78      2283784.85      7135157.94
      2284867.03      7135311.96      2285223.92      7135465.04
      2285722.94      7136251.86      2286429.00      7136410.00

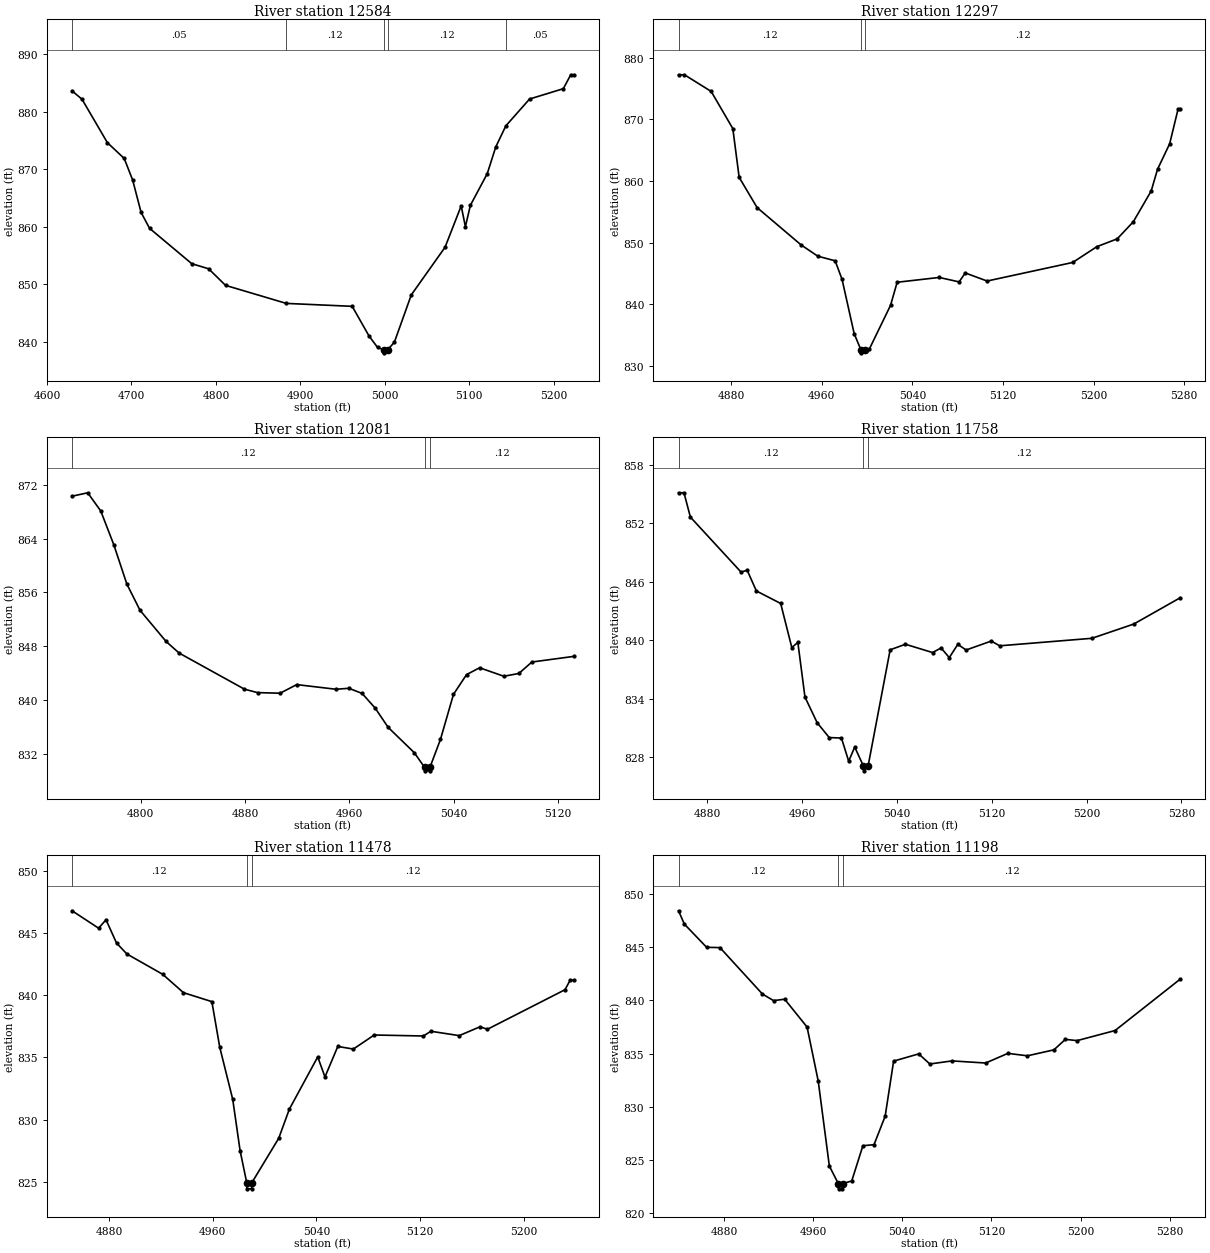
Type RM Length L Ch R = 1,12584,287,287,287
BEGIN DESCRIPTION:
MDW T 107 16.0
END DESCRIPTION:
XS GIS Cut Line= 3
      2278207.24      7130977.98      2278583.79      7130967.09
      2278801.53      7130961.93
#Sta/Elev= 30
  4629.6  883.61  4641.4  882.15  4671.4  874.61  4691.4  871.85  4701.4  868.09
  4711.4  862.46  4721.4  859.70  4771.4  853.55  4791.4  852.66  4811.4  849.78
  4883.4  846.64  4961.5  846.13  4981.5  840.95  4991.5  838.99  4999.4  838.54
  4999.7  838.04  5003.4  838.54  5011.5  839.91  5031.5  848.12  5071.5  856.41
  5090.6  863.60  5095.6  859.99  5101.5  863.70  5121.5  869.21  5131.5  873.83
  5143.5  877.52  5171.6  882.19  5211.6  883.99  5220.4  886.41  5224.1  886.41
#Mann=5,-1,0
  4629.6    0.05       0  4883.4    0.12       0  4999.4    0.07       0
  5003.4    0.12       0  5143.5    0.05       0
Bank Sta=4999.4,5003.4
Exp/Cntr=0.3,0.1

Type RM Length L Ch R = 1,12297,216,216,216
BEGIN DESCRIPTION:
Mapping XS 8b2034b6
END DESCRIPTION:
XS GIS Cut Line= 2
      2278324.29      7131284.23      2278737.73      7131125.69
#Sta/Elev= 30
  4833.7  877.22  4838.9  877.22  4862.5  874.52  4881.6  868.49  4887.2  860.58
  4903.0  855.68  4941.9  849.61  4956.6  847.79  4971.9  847.04  4978.0  844.03
  4988.7  835.22  4994.6  832.61  4994.8  832.11  4998.6  832.61  5001.9  832.66
  5020.8  839.82  5026.6  843.56  5063.7  844.34  5081.3  843.62  5086.7  845.07
  5106.0  843.76  5181.5  846.77  5202.9  849.34  5220.8  850.60  5235.0  853.37
  5250.8  858.37  5256.4  861.90  5267.1  866.03  5274.5  871.64  5276.5  871.64
#Mann=3,-1,0
  4833.7    0.12       0  4994.6    0.07       0  4998.6    0.12       0
Bank Sta=4994.6,4998.6
Exp/Cntr=0.3,0.1

Type RM Length L Ch R = 1,12081,323,323,323
BEGIN DESCRIPTION:
Mapping XS b7b5b52c
END DESCRIPTION:
XS GIS Cut Line= 2
      2278367.02      7131364.36      2278751.18      7131342.09
#Sta/Elev= 30
  4747.3  870.29  4759.3  870.80  4769.3  868.10  4779.3  863.09  4789.3  857.26
  4799.4  853.36  4819.4  848.73  4829.4  847.01  4879.5  841.65  4889.5  841.14
  4906.8  841.05  4919.6  842.33  4949.6  841.64  4959.6  841.78  4969.7  841.02
  4979.7  838.85  4989.7  835.98  5009.7  832.23  5017.7  830.03  5018.0  829.53
  5021.5  829.53  5021.7  830.03  5029.8  834.19  5039.8  840.89  5049.8  843.81
  5059.8  844.83  5078.4  843.57  5089.9  843.98  5099.9  845.68  5132.1  846.52
#Mann=3,-1,0
  4747.3    0.12       0  5017.7    0.07       0  5021.7    0.12       0
Bank Sta=5017.7,5021.7
Exp/Cntr=0.3,0.1

Type RM Length L Ch R = 1,11758,280,280,280
BEGIN DESCRIPTION:
Mapping XS 747a7f21
END DESCRIPTION:
XS GIS Cut Line= 3
      2278404.99      7131607.39      2278594.64      7131563.76
      2278753.20      7131398.67
#Sta/Elev= 30
  4855.6  855.11  4860.2  855.11  4865.6  852.62  4908.4  846.98  4913.5  847.18
  4921.3  845.05  4941.8  843.77  4951.2  839.25  4956.3  839.78  4962.3  834.18
  4972.6  831.55  4982.8  830.03  4993.1  829.98  4999.2  827.61  5004.3  829.06
  5011.6  827.12  5011.9  826.62  5015.6  827.12  5034.2  839.02  5047.1  839.59
  5070.0  838.74  5077.2  839.21  5084.1  838.22  5091.3  839.58  5098.3  839.00
  5119.6  839.92  5126.6  839.43  5204.5  840.20  5239.8  841.66  5279.1  844.36
#Mann=3,-1,0
  4855.6    0.12       0  5011.6    0.07       0  5015.6    0.12       0
Bank Sta=5011.6,5015.6
Exp/Cntr=0.3,0.1

Type RM Length L Ch R = 1,11478,280,280,280
BEGIN DESCRIPTION:
Mapping XS f106e92f
END DESCRIPTION:
XS GIS Cut Line= 2
      2278458.88      7131683.66      2278799.08      7131868.76
#Sta/Elev= 30
  4851.4  846.77  4871.9  845.37  4877.6  846.05  4885.7  844.18  4893.7  843.30
  4921.3  841.67  4937.4  840.19  4959.3  839.47  4965.4  835.80  4975.4  831.62
  4981.1  827.49  4986.2  824.93  4986.4  824.43  4989.9  824.43  4990.2  824.93
  5010.9  828.49  5019.1  830.83  5041.0  835.03  5046.6  833.42  5056.5  835.87
  5068.5  835.66  5084.6  836.79  5122.6  836.71  5128.3  837.09  5150.2  836.74
  5166.3  837.45  5172.0  837.25  5231.9  840.43  5235.8  841.19  5238.7  841.19
#Mann=3,-1,0
  4851.4    0.12       0  4986.2    0.07       0  4990.2    0.12       0
Bank Sta=4986.2,4990.2
Exp/Cntr=0.3,0.1

Type RM Length L Ch R = 1,11198,323,323,323
BEGIN DESCRIPTION:
Mapping XS e61b646f
END DESCRIPTION:
XS GIS Cut Line= 3
      2278333.83      7132007.11      2278636.01      7131988.38
      2278778.30      7131948.62
#Sta/Elev= 30
  4839.1  848.45  4844.3  847.20  4864.3  845.01  4876.3  844.98  4914.4  840.61
  4924.4  839.99  4934.4  840.12  4954.5  837.50  4964.5  832.42  4974.5  824.41
  4982.5  822.76  4982.8  822.26  4986.3  822.26  4986.5  822.76  4994.6  823.00
  5004.6  826.32  5014.6  826.42  5024.6  829.10  5032.2  834.29  5054.7  834.97
  5064.7  834.02  5084.7  834.31  5114.8  834.11  5134.8  835.02  5152.3  834.79
  5176.1  835.35  5186.4  836.34  5196.9  836.22  5231.0  837.17  5289.6  842.02
#Mann=3,-1,0
  4839.1    0.12       0  4982.5    0.07       0  4986.5    0.12       0
Bank Sta=4982.5,4986.5
Exp/Cntr=0.3,0.1

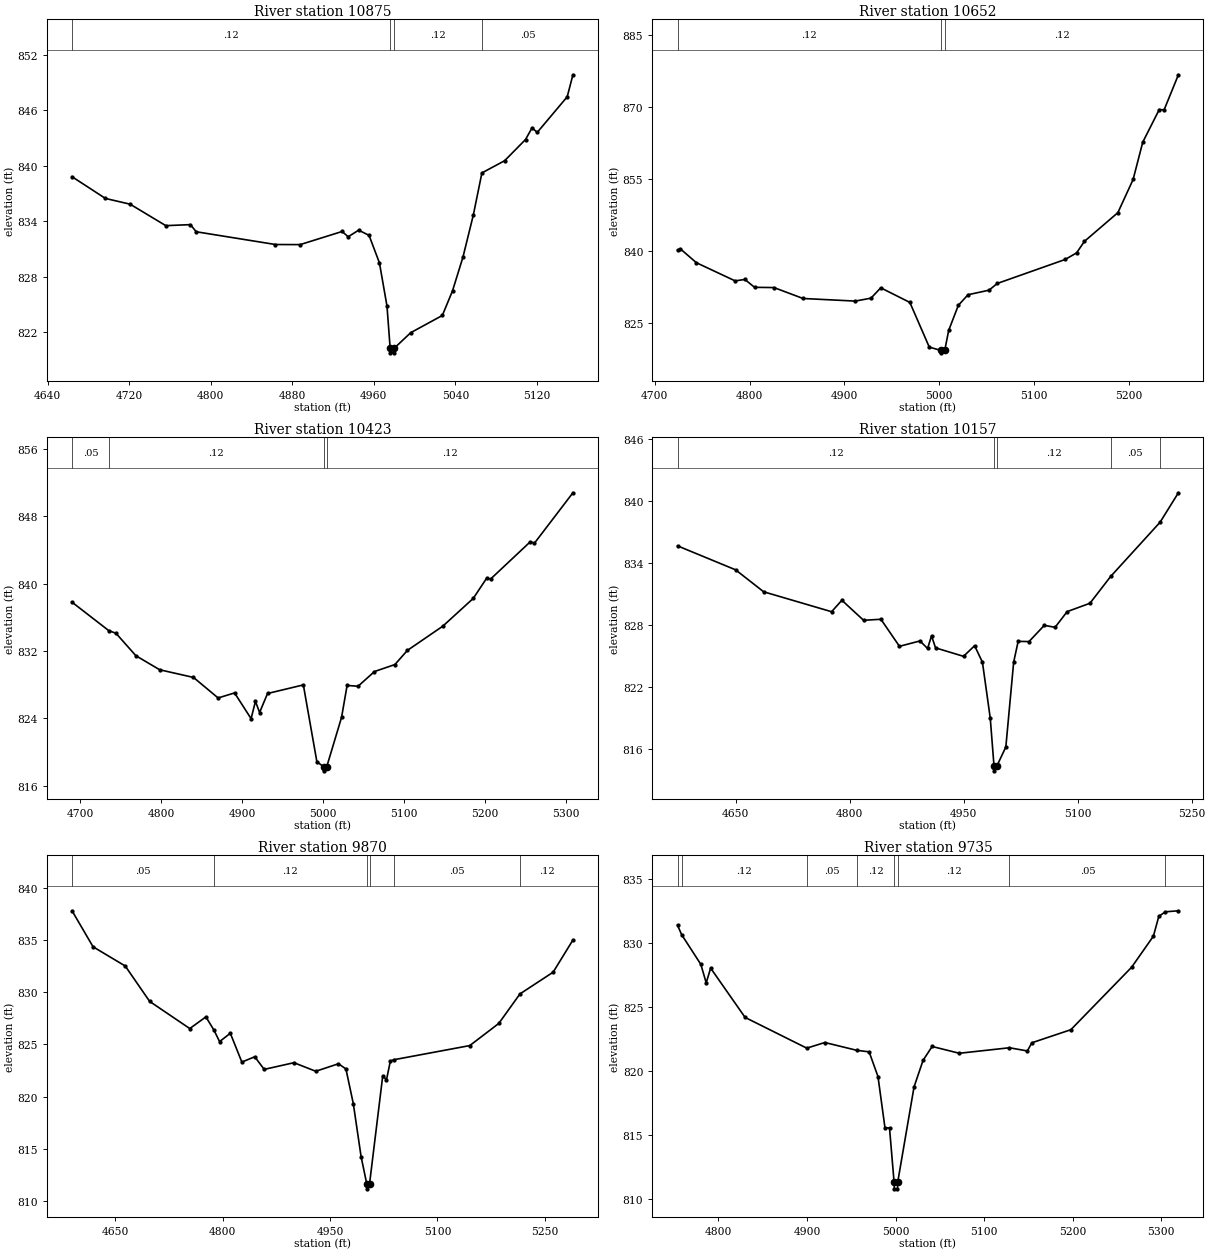
Type RM Length L Ch R = 1,10875,223,223,223
BEGIN DESCRIPTION:
Mapping XS 25ffd394
END DESCRIPTION:
XS GIS Cut Line= 3
      2278355.94      7132171.81      2278577.00      7132260.52
      2278824.43      7132206.74
#Sta/Elev= 30
  4663.9  838.79  4696.7  836.44  4720.9  835.82  4755.9  833.50  4780.1  833.61
  4785.7  832.84  4863.5  831.46  4887.7  831.45  4928.9  832.87  4934.8  832.30
  4945.1  833.01  4955.3  832.45  4965.5  829.47  4972.9  824.80  4976.0  820.25
  4976.3  819.75  4979.8  819.75  4980.0  820.25  4996.2  821.93  5027.2  823.79
  5037.2  826.46  5047.4  830.09  5057.6  834.65  5066.0  839.20  5088.3  840.52
  5108.8  842.81  5115.2  844.07  5120.3  843.58  5149.7  847.43  5155.3  849.81
#Mann=4,-1,0
  4663.9    0.12       0  4976.0    0.07       0  4980.0    0.12       0
  5066.0    0.05       0
Bank Sta=4976,4980
Exp/Cntr=0.3,0.1

Type RM Length L Ch R = 1,10652,229,229,229
BEGIN DESCRIPTION:
Mapping XS 540563d3
END DESCRIPTION:
XS GIS Cut Line= 2
      2278319.60      7132364.71      2278835.71      7132478.94
#Sta/Elev= 30
  4724.0  840.19  4726.9  840.48  4743.9  837.58  4784.8  833.80  4795.1  834.10
  4805.3  832.46  4825.8  832.41  4856.5  830.14  4911.6  829.60  4928.2  830.21
  4938.5  832.36  4969.2  829.32  4989.7  820.03  5002.0  819.34  5002.3  818.84
  5006.0  819.34  5010.2  823.52  5020.4  828.73  5030.6  830.92  5052.8  831.87
  5061.4  833.26  5133.1  838.25  5145.1  839.61  5153.5  842.03  5188.7  847.98
  5204.8  854.88  5215.0  862.65  5232.4  869.42  5237.5  869.35  5252.6  876.65
#Mann=3,-1,0
  4724.0    0.12       0  5002.0    0.07       0  5006.0    0.12       0
Bank Sta=5002,5006
Exp/Cntr=0.3,0.1

Type RM Length L Ch R = 1,10423,266,266,266
BEGIN DESCRIPTION:
Mapping XS f7e006f2
END DESCRIPTION:
XS GIS Cut Line= 2
      2278251.44      7132595.38      2278860.13      7132703.41
#Sta/Elev= 30
  4690.0  837.80  4735.5  834.41  4744.2  834.11  4768.8  831.44  4798.2  829.77
  4839.9  828.86  4870.3  826.42  4890.6  827.02  4911.0  823.96  4916.4  826.02
  4921.5  824.69  4931.3  826.95  4975.5  827.97  4992.2  818.84  5000.4  818.26
  5000.6  817.76  5004.4  818.26  5022.7  824.13  5029.5  827.91  5043.0  827.81
  5063.3  829.56  5088.5  830.39  5103.9  832.07  5147.6  834.95  5185.2  838.25
  5201.6  840.63  5206.7  840.56  5255.6  844.98  5260.7  844.81  5308.2  850.80
#Mann=4,-1,0
  4690.0    0.05       0  4735.5    0.12       0  5000.4    0.07       0
  5004.4    0.12       0
Bank Sta=5000.4,5004.4
Exp/Cntr=0.3,0.1

Type RM Length L Ch R = 1,10157,287,287,287
BEGIN DESCRIPTION:
Mapping XS 8697d265
END DESCRIPTION:
XS GIS Cut Line= 4
      2278188.64      7132797.54      2278360.42      7132838.49
      2278625.38      7132901.65      2278835.07      7132916.59
#Sta/Elev= 30
  4573.3  835.65  4649.7  833.33  4686.7  831.20  4776.1  829.27  4789.6  830.38
  4818.2  828.44  4841.0  828.54  4865.4  825.92  4892.4  826.44  4902.4  825.71
  4907.6  826.93  4912.9  825.77  4949.7  824.95  4964.3  825.98  4974.6  824.38
  4984.9  818.96  4989.8  814.36  4990.1  813.86  4993.8  814.36  5005.4  816.17
  5015.7  824.39  5021.6  826.40  5035.9  826.38  5056.0  827.95  5070.2  827.76
  5086.1  829.28  5116.1  830.09  5143.4  832.69  5208.3  837.93  5232.5  840.79
#Mann=5,-1,0
  4573.3    0.12       0  4989.8    0.07       0  4993.8    0.12       0
  5143.4    0.05       0  5208.3    0.12       0
Bank Sta=4989.8,4993.8
Exp/Cntr=0.3,0.1

Type RM Length L Ch R = 1,9870,135,135,135
BEGIN DESCRIPTION:
Mapping XS 4a9f6ee1
END DESCRIPTION:
XS GIS Cut Line= 4
      2278150.70      7133075.41      2278283.20      7133112.62
      2278482.74      7133168.65      2278825.72      7133079.35
#Sta/Elev= 30
  4589.9  837.80  4619.3  834.35  4664.2  832.51  4698.3  829.12  4754.3  826.52
  4776.8  827.64  4788.2  826.35  4795.9  825.27  4810.9  826.07  4827.0  823.31
  4845.0  823.82  4858.2  822.61  4899.7  823.25  4930.2  822.43  4961.9  823.15
  4972.3  822.65  4982.6  819.33  4993.5  814.24  5001.3  811.67  5001.5  811.17
  5005.3  811.67  5023.7  822.00  5028.9  821.60  5034.3  823.40  5038.9  823.53
  5145.2  824.89  5185.7  827.01  5215.3  829.84  5261.6  831.92  5289.2  835.00
#Mann=6,-1,0
  4589.9    0.05       0  4788.2    0.12       0  5001.3    0.07       0
  5005.3    0.12       0  5038.9    0.05       0  5215.3    0.12       0
Bank Sta=5001.3,5005.3
Exp/Cntr=0.3,0.1

Type RM Length L Ch R = 1,9735,95,95,95
BEGIN DESCRIPTION:
Mapping XS 5e1308b4
END DESCRIPTION:
XS GIS Cut Line= 3
      2278282.75      7133274.43      2278519.88      7133278.45
      2278840.64      7133208.83
#Sta/Elev= 30
  4753.9  831.35  4758.6  830.61  4780.2  828.30  4786.3  826.85  4791.3  828.00
  4830.2  824.15  4899.8  821.75  4920.2  822.19  4956.3  821.58  4970.2  821.46
  4980.2  819.53  4988.1  815.52  4993.2  815.52  4998.4  811.26  4998.7  810.76
  5002.2  810.76  5002.4  811.26  5020.9  818.72  5031.1  820.80  5041.3  821.88
  5072.0  821.35  5128.6  821.78  5148.8  821.53  5153.9  822.17  5197.9  823.19
  5266.5  828.07  5291.1  830.50  5297.2  832.05  5304.7  832.40  5319.3  832.48
#Mann=8,-1,0
  4753.9    0.05       0  4758.6    0.12       0  4899.8    0.05       0
  4956.3    0.12       0  4998.4    0.07       0  5002.4    0.12       0
  5128.6    0.05       0  5304.7    0.12       0
Bank Sta=4998.4,5002.4
Exp/Cntr=0.3,0.1

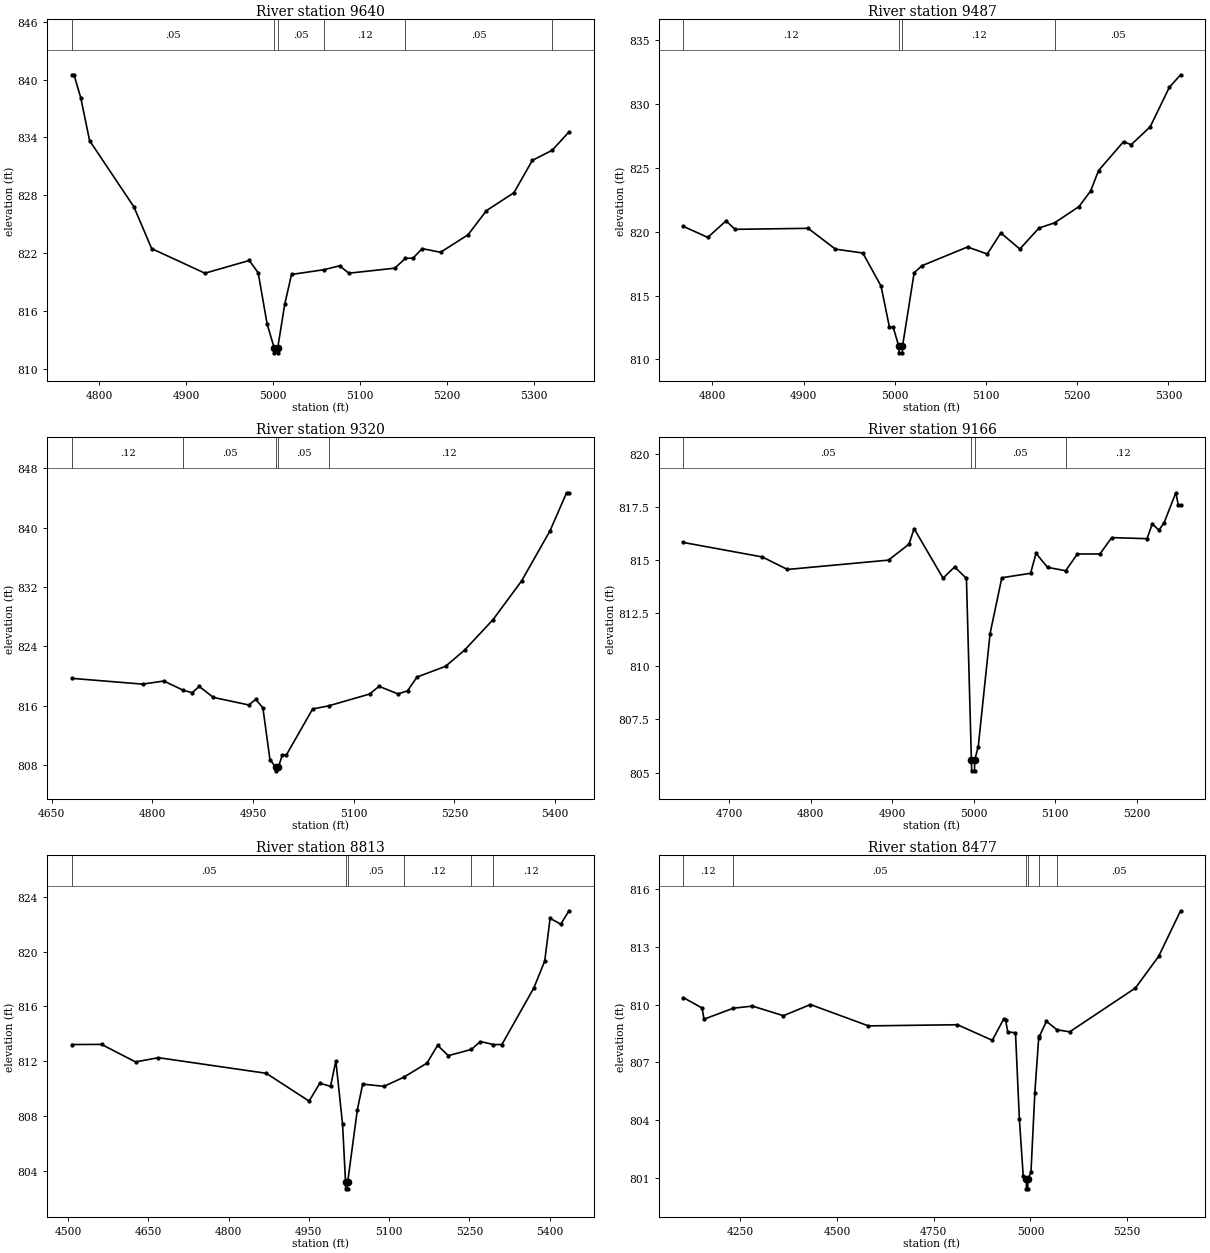
Type RM Length L Ch R = 1,9640,153,153,153
BEGIN DESCRIPTION:
MDW T 107 10.0
END DESCRIPTION:
XS GIS Cut Line= 3
      2278329.04      7133409.99      2278579.00      7133360.00
      2278878.97      7133260.01
#Sta/Elev= 30
  4768.8  840.49  4771.3  840.49  4779.0  838.12  4789.2  833.66  4840.1  826.79
  4860.5  822.46  4921.7  819.91  4972.7  821.23  4982.9  819.95  4993.1  814.66
  5001.3  812.15  5001.6  811.65  5005.1  811.65  5005.3  812.15  5013.5  816.75
  5021.2  819.78  5058.3  820.27  5076.4  820.68  5087.0  819.91  5139.7  820.43
  5152.0  821.45  5160.7  821.47  5171.3  822.46  5192.4  822.08  5224.0  823.90
  5245.1  826.40  5276.7  828.26  5297.8  831.61  5320.6  832.66  5339.9  834.56
#Mann=6,-1,0
  4768.8    0.05       0  5001.3   0.033       0  5005.3    0.05       0
  5058.3    0.12       0  5152.0    0.05       0  5320.6    0.12       0
Bank Sta=5001.3,5005.3
Exp/Cntr=0.3,0.1

Type RM Length L Ch R = 1,9487,167,167,167
BEGIN DESCRIPTION:
Mapping XS 2cd79249
END DESCRIPTION:
XS GIS Cut Line= 3
      2278382.28      7133509.15      2278612.27      7133506.17
      2278870.14      7133325.11
#Sta/Elev= 30
  4768.2  820.41  4794.9  819.55  4814.9  820.84  4824.9  820.18  4904.9  820.26
  4934.9  818.63  4964.9  818.33  4984.9  815.74  4994.1  812.52  4998.2  812.52
  5004.4  811.02  5004.7  810.52  5008.2  810.52  5008.4  811.02  5021.2  816.79
  5029.9  817.34  5079.7  818.80  5101.4  818.25  5116.2  819.90  5137.1  818.64
  5158.0  820.28  5175.2  820.69  5201.9  821.96  5214.7  823.18  5223.4  824.78
  5250.8  827.04  5259.1  826.80  5280.0  828.20  5300.9  831.28  5313.3  832.27
#Mann=4,-1,0
  4768.2    0.12       0  5004.4    0.07       0  5008.4    0.12       0
  5175.2    0.05       0
Bank Sta=5004.4,5008.4
Exp/Cntr=0.3,0.1

Type RM Length L Ch R = 1,9320,154,154,154
BEGIN DESCRIPTION:
MDW T 107 9.0
END DESCRIPTION:
XS GIS Cut Line= 3
      2278379.03      7133560.01      2278679.00      7133660.00
      2278979.03      7133359.97
#Sta/Elev= 30
  4680.2  819.68  4785.6  818.90  4817.2  819.32  4846.2  818.07  4859.4  817.74
  4869.9  818.59  4891.0  817.11  4943.7  816.09  4954.2  816.85  4964.8  815.69
  4975.3  808.71  4983.9  807.70  4984.1  807.20  4987.9  807.70  4993.8  809.36
  4999.9  809.36  5038.8  815.54  5062.7  815.97  5123.7  817.56  5137.8  818.60
  5166.1  817.58  5180.2  818.00  5194.4  819.86  5236.8  821.30  5265.1  823.48
  5307.5  827.59  5350.0  832.81  5392.4  839.57  5417.1  844.72  5420.7  844.72
#Mann=5,-1,0
  4680.2    0.12       0  4846.2    0.05       0  4983.9   0.033       0
  4987.9    0.05       0  5062.7    0.12       0
Bank Sta=4983.9,4987.9
Exp/Cntr=0.3,0.1

Type RM Length L Ch R = 1,9166,353,353,353
BEGIN DESCRIPTION:
Mapping XS 5a35b6c1
END DESCRIPTION:
XS GIS Cut Line= 3
      2278455.38      7133776.50      2278721.04      7133844.87
      2278927.34      7133580.18
#Sta/Elev= 30
  4643.8  815.83  4740.5  815.15  4771.4  814.56  4895.4  815.00  4920.5  815.75
  4926.8  816.48  4962.3  814.15  4976.5  814.68  4991.0  814.14  4997.1  805.58
  4997.4  805.08  5000.9  805.08  5001.1  805.58  5005.5  806.22  5020.0  811.54
  5034.4  814.17  5069.7  814.38  5076.4  815.32  5090.5  814.66  5112.7  814.50
  5127.1  815.29  5154.8  815.29  5169.2  816.06  5212.6  816.01  5219.0  816.71
  5227.1  816.41  5233.5  816.76  5247.9  818.17  5251.0  817.58  5253.7  817.58
#Mann=4,-1,0
  4643.8    0.05       0  4997.1   0.033       0  5001.1    0.05       0
  5112.7    0.12       0
Bank Sta=4997.1,5001.1
Exp/Cntr=0.3,0.1

Type RM Length L Ch R = 1,8813,336,336,336
BEGIN DESCRIPTION:
Mapping XS dd23b994
END DESCRIPTION:
XS GIS Cut Line= 3
      2278803.55      7134342.60      2279045.65      7134133.70
      2279073.36      7133524.70
#Sta/Elev= 30
  4506.9  813.22  4562.4  813.23  4626.0  811.95  4668.8  812.26  4870.4  811.12
  4950.5  809.09  4970.5  810.40  4990.5  810.17  5000.5  812.03  5013.0  807.42
  5018.6  803.19  5018.8  802.69  5022.3  802.69  5022.6  803.19  5040.6  808.44
  5050.6  810.33  5090.6  810.17  5127.2  810.83  5170.7  811.86  5190.7  813.16
  5210.8  812.41  5253.7  812.86  5270.8  813.44  5294.9  813.22  5310.9  813.22
  5370.9  817.37  5391.0  819.32  5401.0  822.43  5421.0  822.00  5436.3  822.98
#Mann=6,-1,0
  4506.9    0.05       0  5018.6   0.033       0  5022.6    0.05       0
  5127.2    0.12       0  5253.7    0.05       0  5294.9    0.12       0
Bank Sta=5018.6,5022.6
Exp/Cntr=0.3,0.1

Type RM Length L Ch R = 1,8477,168,168,168
BEGIN DESCRIPTION:
Mapping XS c3ee666e
END DESCRIPTION:
XS GIS Cut Line= 4
      2279292.72      7134808.31      2279298.42      7134571.62
      2279308.37      7134158.28      2279327.99      7133523.40
#Sta/Elev= 30
  4102.7  810.36  4150.9  809.82  4155.9  809.24  4231.8  809.81  4281.1  809.92
  4361.1  809.42  4431.1  810.00  4581.1  808.89  4811.2  808.95  4901.3  808.14
  4930.8  809.25  4935.8  809.18  4941.3  808.58  4961.3  808.53  4971.3  804.06
  4981.3  801.07  4989.3  800.91  4989.6  800.41  4993.1  800.41  4993.3  800.91
  5001.3  801.27  5011.3  805.40  5021.3  808.27  5023.3  808.35  5041.3  809.13
  5068.3  808.69  5101.4  808.58  5271.4  810.86  5331.5  812.51  5388.1  814.88
#Mann=6,-1,0
  4102.7    0.12       0  4231.8    0.05       0  4989.3   0.033       0
  4993.3    0.05       0  5023.3    0.12       0  5068.3    0.05       0
Bank Sta=4989.3,4993.3
Exp/Cntr=0.3,0.1

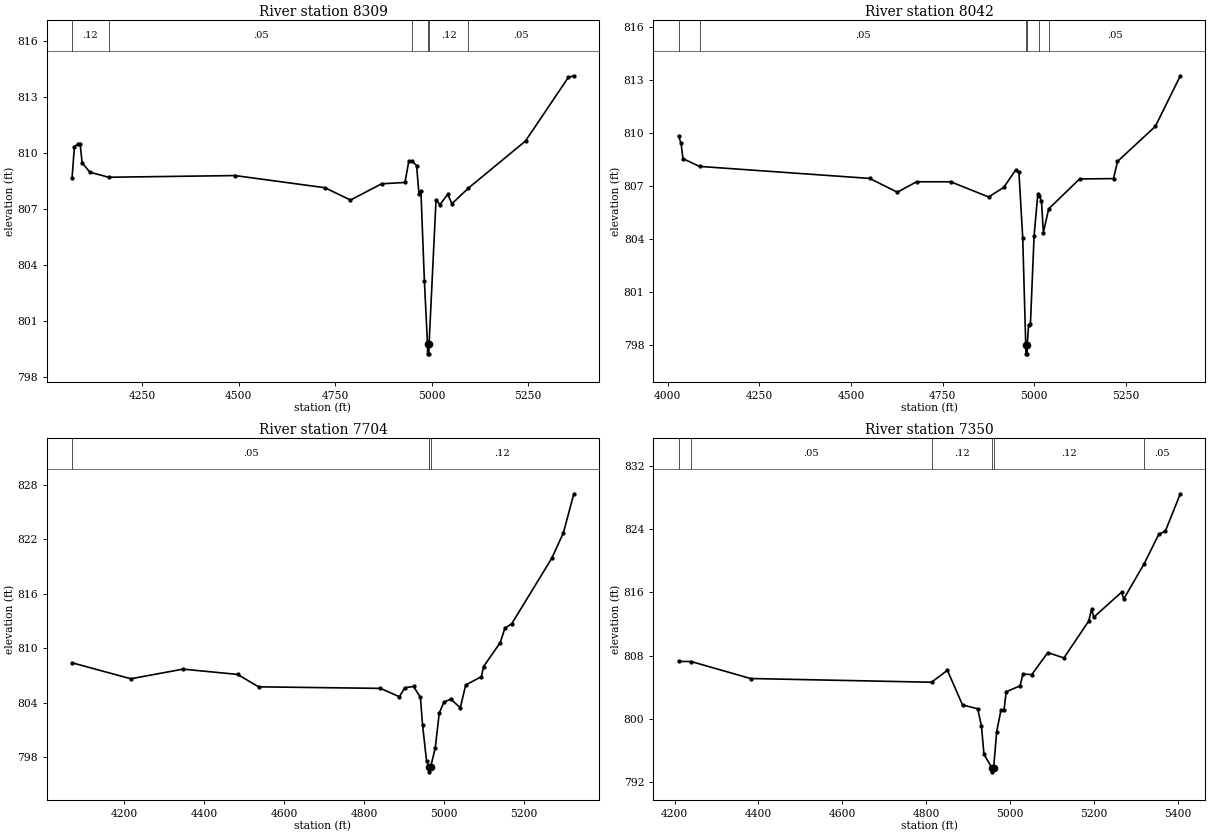
Type RM Length L Ch R = 1,8309,267,267,267
BEGIN DESCRIPTION:
Mapping XS d3a8f770
END DESCRIPTION:
XS GIS Cut Line= 4
      2279351.40      7134885.93      2279373.75      7134708.66
      2279433.35      7134235.90      2279514.08      7133595.64
#Sta/Elev= 30
  4068.0  808.68  4074.0  810.34  4083.9  810.51  4088.9  810.48  4094.1  809.48
  4114.3  808.98  4162.9  808.71  4490.4  808.80  4723.2  808.15  4789.6  807.49
  4870.2  808.36  4930.7  808.43  4940.8  809.58  4949.5  809.57  4960.9  809.33
  4967.1  807.81  4972.1  807.97  4981.1  803.17  4989.2  799.76  4989.4  799.26
  4992.9  799.26  4993.2  799.76  5011.3  807.51  5021.4  807.24  5041.6  807.80
  5052.4  807.29  5094.7  808.12  5243.2  810.65  5354.0  814.05  5368.5  814.14
#Mann=6,-1,0
  4068.0    0.12       0  4162.9    0.05       0  4949.5    0.12       0
  4989.2    0.07       0  4993.2    0.12       0  5094.7    0.05       0
Bank Sta=4989.2,4993.2
Exp/Cntr=0.3,0.1

Type RM Length L Ch R = 1,8042,338,338,338
BEGIN DESCRIPTION:
Mapping XS 2d38b62d
END DESCRIPTION:
XS GIS Cut Line= 4
      2279451.23      7135017.96      2279466.24      7134960.82
      2279637.53      7134308.99      2279799.09      7133694.20
#Sta/Elev= 30
  4029.5  809.84  4036.5  809.42  4041.6  808.56  4086.7  808.12  4550.7  807.44
  4626.3  806.66  4678.8  807.25  4771.8  807.25  4875.2  806.39  4916.6  806.93
  4949.1  807.92  4957.9  807.80  4968.3  804.08  4976.6  798.01  4976.9  797.51
  4980.4  797.51  4980.6  798.01  4984.3  799.13  4989.4  799.22  4999.3  804.19
  5009.6  806.58  5012.6  806.46  5019.4  806.18  5024.6  804.37  5039.2  805.72
  5123.4  807.41  5216.0  807.43  5226.8  808.40  5330.2  810.39  5398.2  813.25
#Mann=6,-1,0
  4029.5    0.12       0  4086.7    0.05       0  4976.6   0.033       0
  4980.6    0.05       0  5012.6    0.12       0  5039.2    0.05       0
Bank Sta=4976.6,4980.6
Exp/Cntr=0.3,0.1

Type RM Length L Ch R = 1,7704,354,354,354
BEGIN DESCRIPTION:
Mapping XS 5650ef2a
END DESCRIPTION:
XS GIS Cut Line= 3
      2279621.09      7135075.10      2279883.63      7134461.21
      2280114.54      7133921.29
#Sta/Elev= 30
  4069.5  808.39  4216.4  806.63  4346.9  807.69  4483.3  807.11  4536.0  805.74
  4840.8  805.57  4888.0  804.65  4901.6  805.64  4923.4  805.78  4940.6  804.60
  4946.1  801.50  4956.0  797.56  4961.9  796.90  4962.2  796.87  4962.5  796.37
  4966.2  796.87  4977.8  799.03  4987.8  802.85  4999.5  804.06  5016.8  804.38
  5040.4  803.43  5053.9  805.94  5093.1  806.86  5098.5  807.97  5140.2  810.61
  5151.8  812.19  5169.3  812.71  5269.1  819.91  5298.1  822.70  5324.4  827.02
#Mann=4,-1,0
  4069.5    0.05       0  4961.9    0.12       0  4962.2    0.07       0
  4966.2    0.12       0
Bank Sta=4962.2,4966.2
Exp/Cntr=0.3,0.1

Type RM Length L Ch R = 1,7350,0,0,0
BEGIN DESCRIPTION:
Mapping XS d61019cc
END DESCRIPTION:
XS GIS Cut Line= 4
      2279812.06      7135132.58      2280060.01      7134760.06
      2280224.61      7134512.77      2280354.36      7134080.99
#Sta/Elev= 30
  4209.6  807.28  4239.3  807.27  4381.2  805.12  4812.3  804.65  4850.1  806.16
  4886.1  801.78  4922.2  801.29  4931.2  799.13  4937.2  795.54  4956.2  793.82
  4956.5  793.32  4960.2  793.82  4967.5  798.40  4977.9  801.17  4985.0  801.15
  4990.2  803.45  5023.2  804.19  5030.1  805.69  5051.0  805.61  5089.3  808.40
  5127.6  807.72  5186.8  812.39  5193.6  813.91  5198.8  812.88  5264.9  816.03
  5270.3  815.19  5318.6  819.61  5353.8  823.37  5369.3  823.75  5405.0  828.48
#Mann=6,-1,0
  4209.6    0.12       0  4239.3    0.05       0  4812.3    0.12       0
  4956.2    0.07       0  4960.2    0.12       0  5318.6    0.05       0
Bank Sta=4956.2,4960.2
Exp/Cntr=0.3,0.1

Chan Stop Cuts=-1