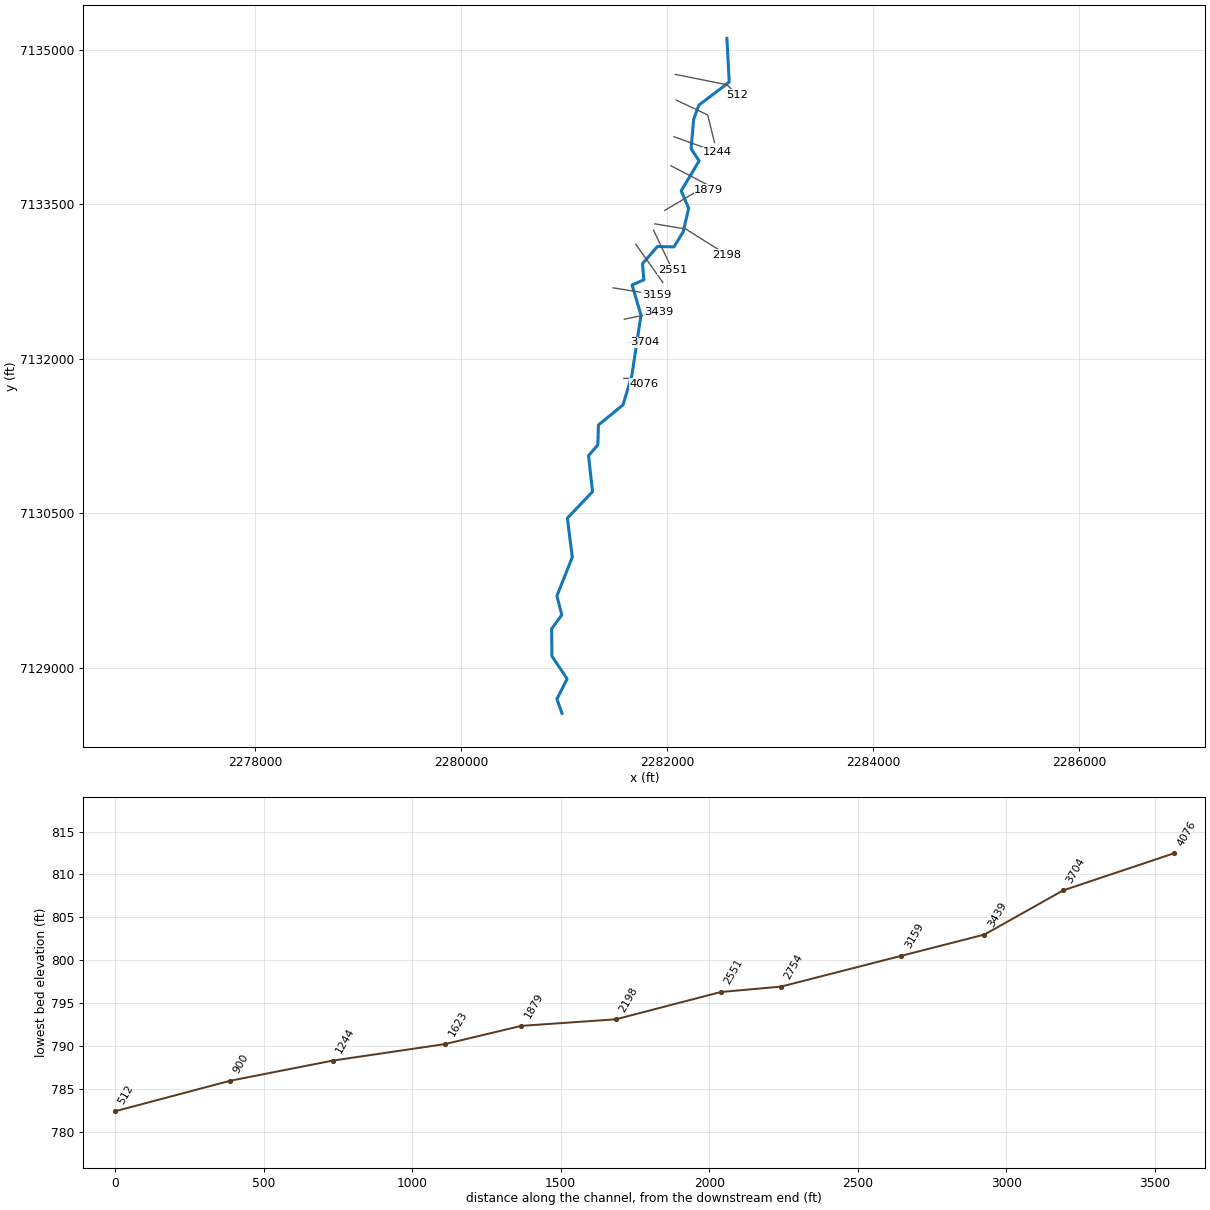
--- MDW T 108.prj (project) ---

Proj Title=MDW T 108 Base Level Engineering
Current Plan=p01
Default Exp/Contr=0.3,0.1
English Units
Geom File=g01
Flow File=f01
Plan File=p01
BEGIN DESCRIPTION:
MDW T 108
END DESCRIPTION:

--- MDW T 108.p01 (plan) ---

Plan Title=Multiple Run
Short Identifier=Multiple
Geom File=g01
Flow File=f01
Subcritical Flow
K Sum by GR= 0
Std Step Tol= 0.01
Critical Tol= 0.01
Num of Std Step Trials= 20
Max Error Tol= 0.3
Flow Tol Ratio= 0.001
Split Flow NTrial= 30
Split Flow Tol= 0.02
Split Flow Ratio= 0.02
Log Output Level= 0
Friction Slope Method= 1
Unsteady Friction Slope Method= 2
Unsteady Bridges Friction Slope Method= 1
Parabolic Critical Depth
Global Vel Dist=  1 , 1 , 1
Global Log Level= 0
CheckData=True
Encroach Param= -1, 0, 0, 0
BEGIN DESCRIPTION:
Multiple Run
END DESCRIPTION:

--- MDW T 108.f01 (steady flow) ---

Flow Title=Multiple
Number of Profiles=7
Profile Names=10-year,25-year,50-year,1pct_min,100-year,1pct_plu,500-year
River Rch & RM= MDW T 108,Reach-1,4076
     764    1069    1327     818    1632    3257    2476
River Rch & RM= MDW T 108,Reach-1,2198
     808    1132    1406     867    1730    3453    2626
Boundary for River Rch & Prof#=MDW T 108,Reach-1,1
Up Type=0
Dn Type=3
Dn Slope=0.005
Boundary for River Rch & Prof#=MDW T 108,Reach-1,2
Up Type=0
Dn Type=3
Dn Slope=0.005
Boundary for River Rch & Prof#=MDW T 108,Reach-1,3
Up Type=0
Dn Type=3
Dn Slope=0.005
Boundary for River Rch & Prof#=MDW T 108,Reach-1,4
Up Type=0
Dn Type=3
Dn Slope=0.005
Boundary for River Rch & Prof#=MDW T 108,Reach-1,5
Up Type=0
Dn Type=3
Dn Slope=0.005
Boundary for River Rch & Prof#=MDW T 108,Reach-1,6
Up Type=0
Dn Type=3
Dn Slope=0.005
Boundary for River Rch & Prof#=MDW T 108,Reach-1,7
Up Type=0
Dn Type=3
Dn Slope=0.005

--- MDW T 108.g01 (geometry) ---

Geom Title=Existing Conditions

River Reach=MDW T 108,Reach-1
Reach XY= 30
      2280979.00      7128560.00      2280929.57      7128699.39
      2281028.76      7128894.78      2280881.24      7129115.93
      2280878.57      7129380.18      2280977.03      7129515.89
      2280929.61      7129699.38      2281078.91      7130075.39
      2281031.23      7130454.10      2281275.46      7130711.46
      2281236.33      7131060.10      2281326.92      7131165.85
      2281332.54      7131358.54      2281571.30      7131553.53
      2281656.47      7131837.41      2281745.72      7132424.12
      2281658.89      7132716.54      2281772.99      7132767.15
      2281760.47      7132923.94      2281904.85      7133089.72
      2282065.78      7133086.62      2282154.62      7133232.26
      2282208.12      7133460.67      2282135.83      7133629.94
      2282309.58      7133921.17      2282231.51      7134039.02
      2282256.96      7134326.00      2282307.53      7134462.28
      2282601.74      7134685.18      2282579.00      7135110.00

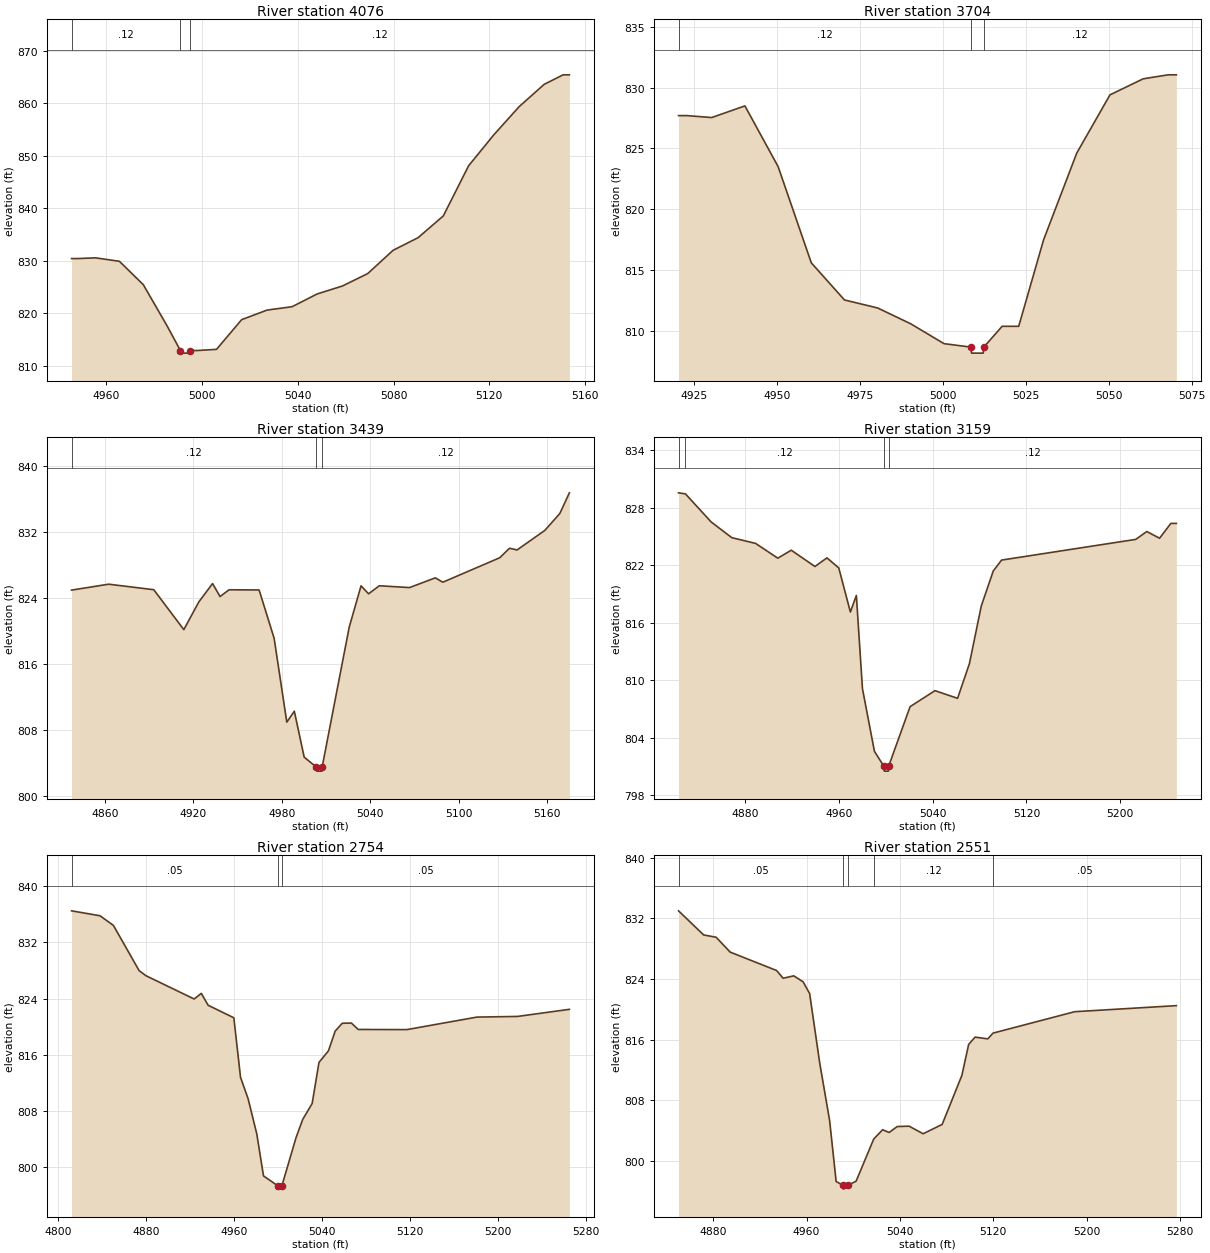
Type RM Length L Ch R = 1,4076,372,372,372
BEGIN DESCRIPTION:
MDW T 108 10.0
END DESCRIPTION:
XS GIS Cut Line= 3
      2281578.97      7131810.00      2281629.00      7131810.00
      2281778.96      7131760.01
#Sta/Elev= 28
  4945.4  830.45  4947.9  830.45  4955.4  830.59  4965.4  829.93  4975.4  825.48
  4985.4  817.58  4990.9  812.95  4991.2  812.45  4994.7  812.45  4994.9  812.95
  4995.4  812.95  4998.1  812.95  5006.0  813.17  5016.5  818.82  5027.1  820.64
  5037.6  821.29  5048.1  823.72  5058.7  825.24  5069.2  827.59  5079.8  832.02
  5090.3  834.44  5100.8  838.57  5111.4  848.13  5121.9  854.00  5132.5  859.37
  5143.0  863.63  5150.9  865.43  5153.5  865.43
#Mann=3,-1,0
  4945.4    0.12       0  4990.9    0.07       0  4994.9    0.12       0
Bank Sta=4990.9,4994.9
Exp/Cntr=0.3,0.1

Type RM Length L Ch R = 1,3704,265,265,265
BEGIN DESCRIPTION:
MDW T 108 9.0
END DESCRIPTION:
XS GIS Cut Line= 3
      2281628.95      7132160.00      2281729.00      7132160.00
      2281778.95      7132160.00
#Sta/Elev= 22
  4920.4  827.71  4922.9  827.71  4930.4  827.55  4940.4  828.51  4950.4  823.51
  4960.4  815.58  4970.4  812.52  4980.4  811.86  4990.4  810.55  5000.4  808.92
  5008.4  808.64  5008.7  808.14  5012.2  808.14  5012.4  808.64  5017.9  810.35
  5022.9  810.35  5030.4  817.48  5040.4  824.63  5050.4  829.42  5060.4  830.74
  5067.9  831.07  5070.4  831.07
#Mann=3,-1,0
  4920.4    0.12       0  5008.4    0.07       0  5012.4    0.12       0
Bank Sta=5008.4,5012.4
Exp/Cntr=0.3,0.1

Type RM Length L Ch R = 1,3439,280,280,280
BEGIN DESCRIPTION:
Mapping XS ca153b11
END DESCRIPTION:
XS GIS Cut Line= 2
      2281584.33      7132384.92      2281915.33      7132452.84
#Sta/Elev= 30
  4837.3  824.98  4862.5  825.70  4893.1  825.03  4913.5  820.18  4923.7  823.55
  4933.0  825.78  4938.1  824.20  4944.2  825.02  4964.6  825.00  4974.8  819.13
  4983.4  808.94  4988.5  810.27  4995.2  804.69  5003.4  803.49  5003.7  802.99
  5007.2  802.99  5007.4  803.49  5025.8  820.51  5033.8  825.50  5038.9  824.53
  5046.2  825.51  5066.7  825.29  5084.2  826.47  5089.3  825.94  5127.9  828.91
  5134.6  830.07  5139.7  829.86  5158.5  832.23  5168.7  834.28  5175.2  836.80
#Mann=3,-1,0
  4837.3    0.12       0  5003.4    0.07       0  5007.4    0.12       0
Bank Sta=5003.4,5007.4
Exp/Cntr=0.3,0.1

Type RM Length L Ch R = 1,3159,405,405,405
BEGIN DESCRIPTION:
Mapping XS 8af04661
END DESCRIPTION:
XS GIS Cut Line= 2
      2281474.14      7132689.02      2281893.16      7132621.68
#Sta/Elev= 30
  4823.4  829.56  4829.3  829.45  4851.2  826.52  4868.8  824.88  4889.1  824.28
  4908.0  822.74  4919.5  823.57  4939.7  821.87  4949.9  822.77  4960.0  821.72
  4969.9  817.12  4975.0  818.85  4980.2  809.11  4990.4  802.58  4998.5  801.01
  4998.8  800.51  5002.3  800.51  5002.5  801.01  5020.8  807.24  5042.0  808.91
  5061.3  808.11  5071.4  811.74  5081.5  817.75  5091.7  821.40  5098.8  822.54
  5213.2  824.70  5222.6  825.52  5233.5  824.82  5243.1  826.37  5247.8  826.37
#Mann=4,-1,0
  4823.4    0.05       0  4829.3    0.12       0  4998.5    0.07       0
  5002.5    0.12       0
Bank Sta=4998.5,5002.5
Exp/Cntr=0.3,0.1

Type RM Length L Ch R = 1,2754,203,203,203
BEGIN DESCRIPTION:
Mapping XS b9377d24
END DESCRIPTION:
XS GIS Cut Line= 2
      2281695.51      7133111.11      2281957.42      7132741.37
#Sta/Elev= 30
  4812.0  836.47  4837.9  835.77  4850.1  834.40  4873.5  827.97  4879.7  827.25
  4923.6  823.94  4930.1  824.74  4936.3  823.05  4959.7  821.27  4965.8  812.81
  4972.7  809.76  4980.6  804.76  4986.7  798.80  4999.5  797.42  4999.7  796.92
  5003.2  796.92  5003.5  797.42  5016.3  804.23  5022.4  806.83  5031.0  809.09
  5037.2  814.93  5045.8  816.57  5052.0  819.39  5058.4  820.49  5066.7  820.52
  5072.9  819.61  5117.2  819.59  5181.0  821.37  5217.8  821.46  5265.1  822.47
#Mann=3,-1,0
  4812.0    0.05       0  4999.5   0.033       0  5003.5    0.05       0
Bank Sta=4999.5,5003.5
Exp/Cntr=0.3,0.1

Type RM Length L Ch R = 1,2551,353,353,353
BEGIN DESCRIPTION:
Mapping XS 603a09ae
END DESCRIPTION:
XS GIS Cut Line= 2
      2281866.99      7133249.10      2282050.48      7132864.19
#Sta/Elev= 30
  4850.4  832.98  4871.9  829.80  4882.6  829.50  4894.6  827.54  4934.4  825.11
  4940.0  824.09  4949.1  824.41  4957.1  823.62  4962.7  822.07  4971.3  812.94
  4979.8  805.34  4985.4  797.29  4991.4  796.79  4991.7  796.29  4995.4  796.79
  5002.5  797.34  5017.6  802.90  5025.2  804.12  5030.8  803.76  5037.7  804.54
  5047.9  804.59  5059.9  803.59  5076.2  804.82  5093.1  811.29  5098.9  815.37
  5104.4  816.33  5115.3  816.10  5119.8  816.86  5189.7  819.68  5276.8  820.48
#Mann=5,-1,0
  4850.4    0.05       0  4991.4   0.033       0  4995.4    0.05       0
  5017.6    0.12       0  5119.8    0.05       0
Bank Sta=4991.4,4995.4
Exp/Cntr=0.3,0.1

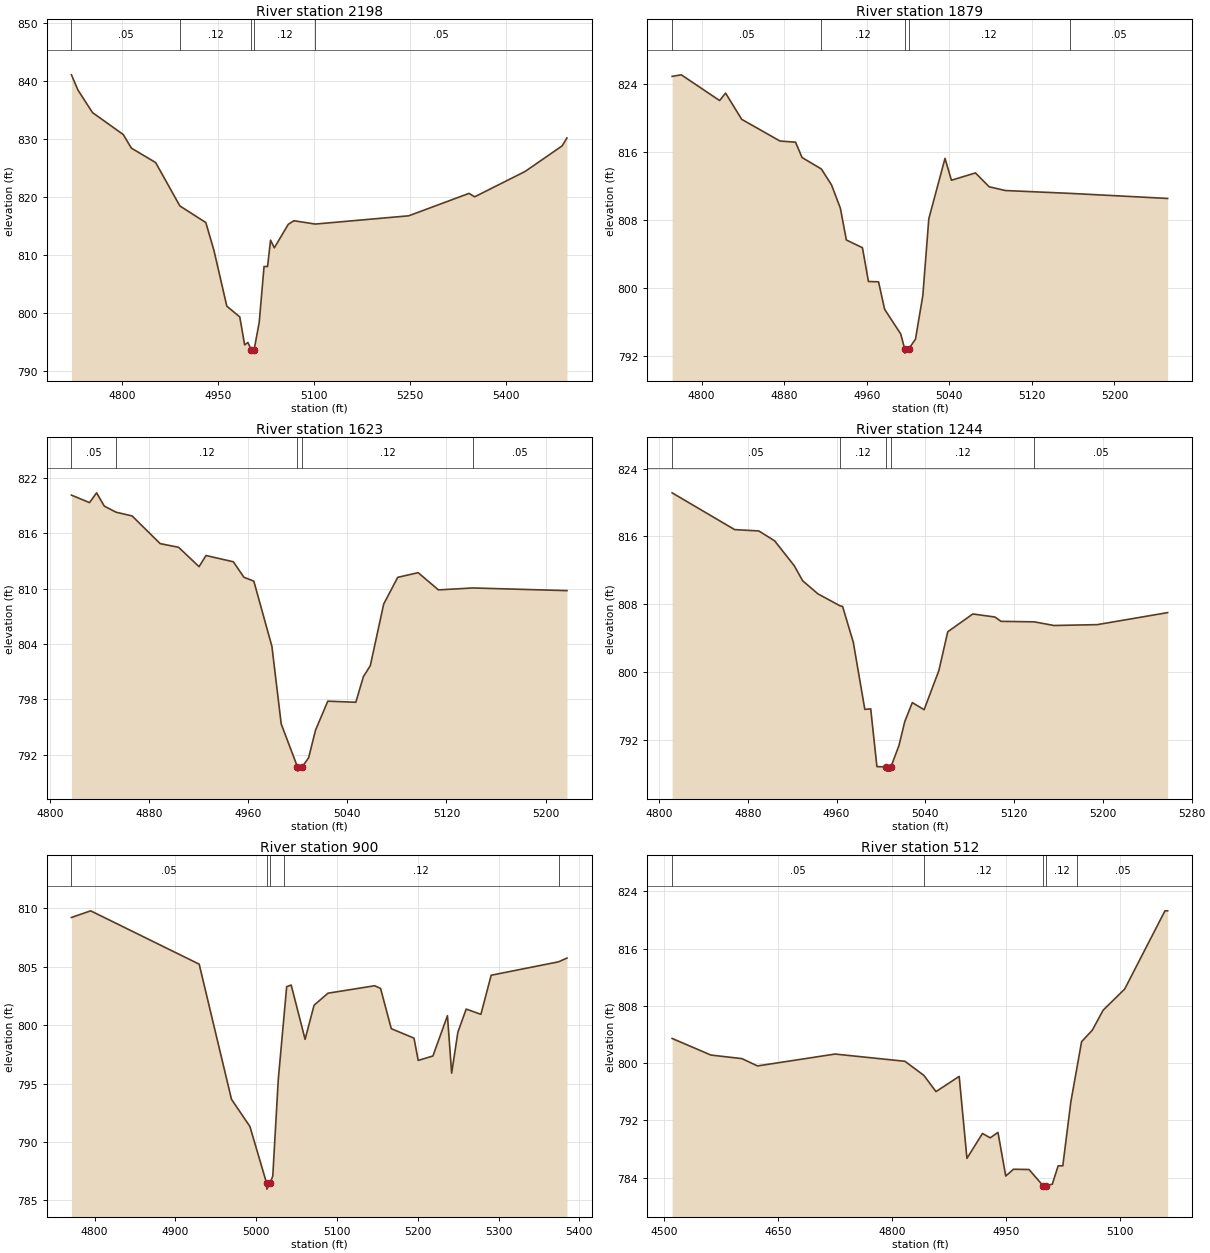
Type RM Length L Ch R = 1,2198,319,319,319
BEGIN DESCRIPTION:
MDW T 108 5.0
END DESCRIPTION:
XS GIS Cut Line= 3
      2281878.98      7133310.00      2282179.00      7133260.00
      2282579.04      7133009.98
#Sta/Elev= 30
  4720.3  841.00  4730.5  838.38  4753.3  834.50  4801.4  830.73  4814.1  828.39
  4852.1  825.91  4890.1  818.44  4930.7  815.58  4943.4  810.81  4963.6  801.19
  4983.9  799.34  4991.5  794.53  4996.6  794.94  5002.2  793.61  5002.4  793.11
  5006.2  793.61  5014.3  798.39  5021.9  808.02  5027.4  808.02  5032.1  812.55
  5038.0  811.23  5059.8  815.27  5068.7  815.89  5102.1  815.32  5248.5  816.74
  5342.9  820.60  5351.7  820.01  5430.7  824.37  5488.5  828.76  5496.2  830.13
#Mann=5,-1,0
  4720.3    0.05       0  4890.1    0.12       0  5002.2    0.07       0
  5006.2    0.12       0  5102.1    0.05       0
Bank Sta=5002.2,5006.2
Exp/Cntr=0.3,0.1

Type RM Length L Ch R = 1,1879,256,256,256
BEGIN DESCRIPTION:
Mapping XS 4d83d7e8
END DESCRIPTION:
XS GIS Cut Line= 3
      2281976.07      7133440.64      2282299.78      7133632.10
      2282403.34      7133641.77
#Sta/Elev= 30
  4771.5  824.87  4780.4  825.05  4817.5  822.03  4823.3  822.90  4838.9  819.82
  4876.0  817.27  4891.1  817.13  4897.4  815.33  4916.1  813.98  4925.9  812.12
  4934.5  809.38  4940.3  805.64  4955.9  804.73  4961.7  800.76  4971.5  800.72
  4977.4  797.49  4993.0  794.59  4996.8  792.84  4997.0  792.34  5000.8  792.84
  5007.3  793.99  5014.4  799.10  5020.2  808.13  5035.9  815.23  5042.1  812.66
  5065.4  813.52  5078.7  811.89  5094.4  811.45  5156.6  811.12  5251.6  810.52
#Mann=5,-1,0
  4771.5    0.05       0  4916.1    0.12       0  4996.8    0.07       0
  5000.8    0.12       0  5156.6    0.05       0
Bank Sta=4996.8,5000.8
Exp/Cntr=0.3,0.1

Type RM Length L Ch R = 1,1623,379,379,379
BEGIN DESCRIPTION:
Mapping XS fc1798fa
END DESCRIPTION:
XS GIS Cut Line= 2
      2282035.52      7133874.09      2282390.15      7133689.27
#Sta/Elev= 30
  4817.4  820.16  4832.0  819.35  4837.7  820.41  4843.9  818.97  4853.4  818.31
  4866.4  817.90  4889.0  814.90  4903.9  814.50  4920.4  812.40  4926.0  813.61
  4948.1  812.93  4956.6  811.25  4964.6  810.83  4979.2  803.75  4986.7  795.34
  4999.7  790.72  5000.0  790.22  5003.8  790.72  5008.8  791.66  5014.4  794.67
  5024.3  797.81  5046.9  797.69  5053.0  800.46  5058.6  801.66  5069.4  808.34
  5080.7  811.24  5097.2  811.75  5113.6  809.88  5141.4  810.09  5217.3  809.80
#Mann=5,-1,0
  4817.4    0.05       0  4853.4    0.12       0  4999.7    0.07       0
  5003.8    0.12       0  5141.4    0.05       0
Bank Sta=4999.7,5003.8
Exp/Cntr=0.3,0.1

Type RM Length L Ch R = 1,1244,344,344,344
BEGIN DESCRIPTION:
Mapping XS 2b0a2a1e
END DESCRIPTION:
XS GIS Cut Line= 2
      2282065.52      7134155.75      2282485.34      7134004.02
#Sta/Elev= 30
  4811.9  821.14  4868.2  816.80  4890.0  816.64  4904.2  815.48  4921.9  812.54
  4929.5  810.76  4943.2  809.22  4963.2  807.80  4965.5  807.72  4975.1  803.51
  4985.5  795.58  4990.8  795.64  4996.4  788.82  5004.9  788.79  5005.2  788.29
  5008.7  788.29  5009.0  788.79  5016.2  791.29  5021.5  794.15  5028.3  796.38
  5038.9  795.54  5052.2  800.16  5060.2  804.74  5082.8  806.84  5102.7  806.48
  5108.2  805.97  5138.2  805.91  5155.9  805.48  5194.8  805.58  5258.3  807.00
#Mann=5,-1,0
  4811.9    0.05       0  4963.2    0.12       0  5004.9    0.07       0
  5009.0    0.12       0  5138.2    0.05       0
Bank Sta=5004.9,5009
Exp/Cntr=0.3,0.1

Type RM Length L Ch R = 1,900,388,388,388
BEGIN DESCRIPTION:
Mapping XS dcfc47c1
END DESCRIPTION:
XS GIS Cut Line= 3
      2282087.53      7134510.92      2282392.64      7134366.74
      2282458.92      7134098.99
#Sta/Elev= 30
  4771.3  809.23  4795.1  809.80  4929.4  805.23  4969.4  793.65  4992.2  791.32
  5012.9  786.45  5013.2  785.95  5017.0  786.45  5020.5  787.07  5027.3  795.34
  5034.2  800.62  5037.7  803.30  5043.3  803.44  5060.5  798.79  5071.6  801.71
  5088.8  802.74  5146.6  803.38  5153.9  803.15  5167.2  799.70  5195.3  798.89
  5200.5  796.98  5218.7  797.36  5236.7  800.81  5241.9  795.89  5249.6  799.40
  5259.9  801.38  5278.1  800.93  5290.8  804.28  5374.2  805.43  5384.6  805.75
#Mann=5,-1,0
  4771.3    0.05       0  5012.9   0.033       0  5017.0    0.05       0
  5034.2    0.12       0  5374.2    0.05       0
Bank Sta=5012.9,5017
Exp/Cntr=0.3,0.1

Type RM Length L Ch R = 1,512,0,0,0
BEGIN DESCRIPTION:
MDW T 108 1.0
END DESCRIPTION:
XS GIS Cut Line= 3
      2282078.98      7134760.00      2282579.00      7134660.00
      2282678.97      7134560.03
#Sta/Elev= 30
  4511.0  803.45  4562.0  801.13  4602.8  800.63  4623.2  799.61  4725.2  801.27
  4817.0  800.26  4841.9  798.29  4857.8  796.02  4888.3  798.15  4898.5  786.69
  4918.9  790.17  4929.1  789.56  4939.3  790.32  4949.5  784.22  4959.7  785.17
  4980.1  785.13  4998.4  782.89  4998.7  782.39  5002.7  782.89  5010.7  783.08
  5018.4  785.65  5024.5  785.65  5035.1  794.60  5043.5  799.60  5049.2  803.00
  5063.3  804.61  5077.5  807.40  5105.8  810.35  5158.8  821.29  5162.3  821.29
#Mann=5,-1,0
  4511.0    0.05       0  4841.9    0.12       0  4998.4    0.07       0
  5002.7    0.12       0  5043.5    0.05       0
Bank Sta=4998.4,5002.7
Exp/Cntr=0.3,0.1

Chan Stop Cuts=-1