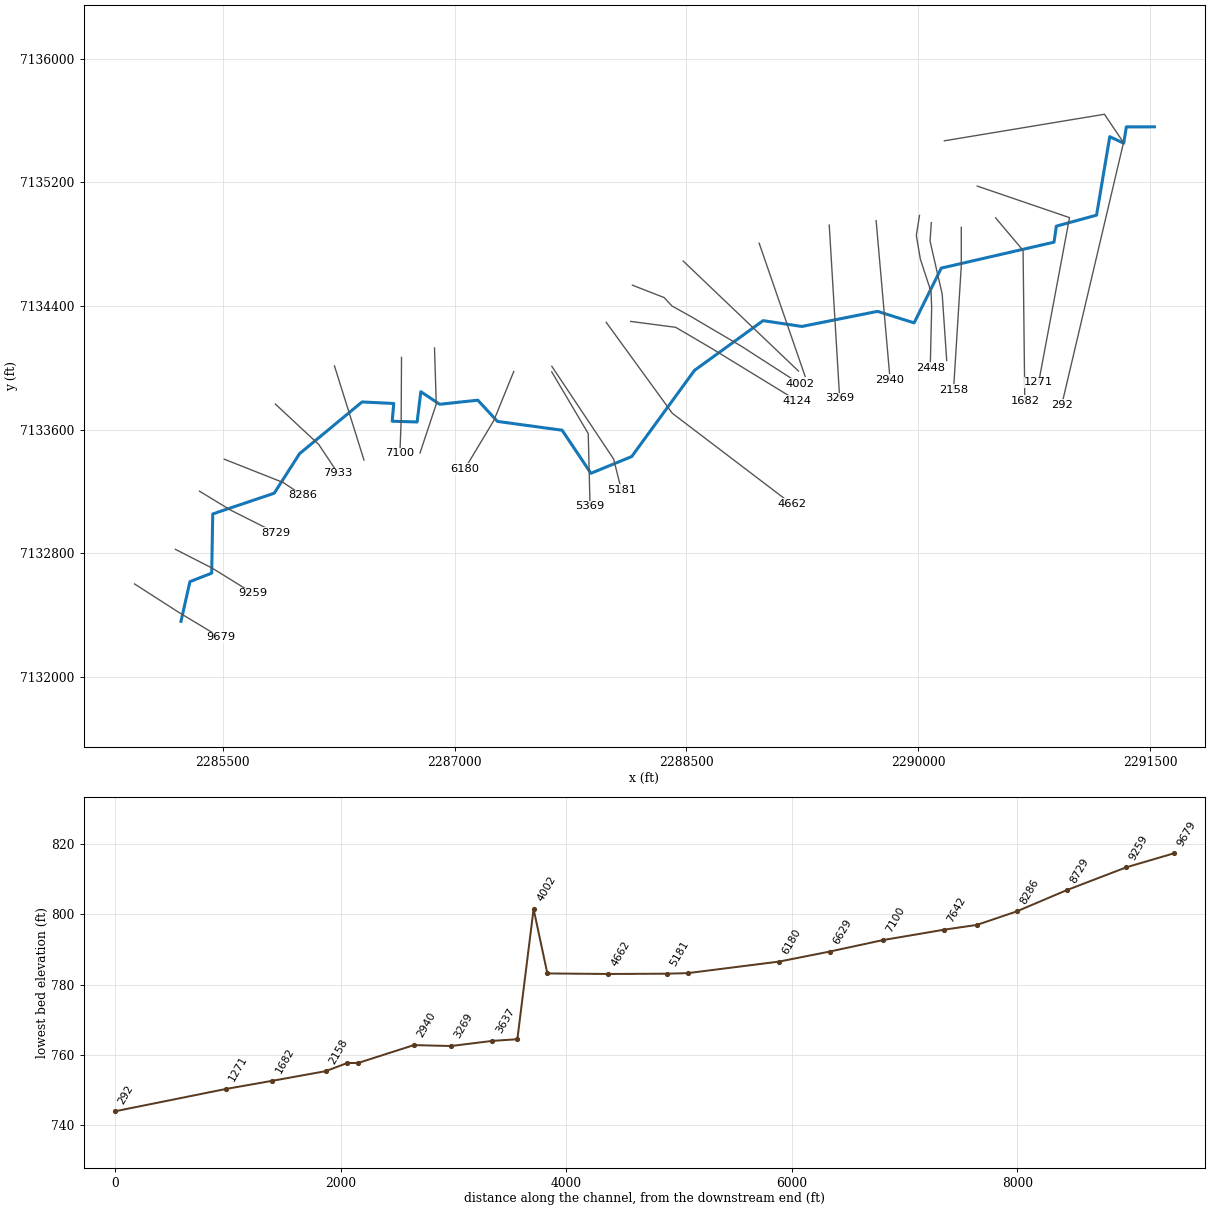
--- MDW T 109.prj (project) ---

Proj Title=MDW T 109 Base Level Engineering
Current Plan=p01
Default Exp/Contr=0.3,0.1
English Units
Geom File=g01
Flow File=f01
Plan File=p01
BEGIN DESCRIPTION:
MDW T 109
END DESCRIPTION:

--- MDW T 109.p01 (plan) ---

Plan Title=Multiple Run
Short Identifier=Multiple
Geom File=g01
Flow File=f01
Subcritical Flow
K Sum by GR= 0
Std Step Tol= 0.01
Critical Tol= 0.01
Num of Std Step Trials= 20
Max Error Tol= 0.3
Flow Tol Ratio= 0.001
Split Flow NTrial= 30
Split Flow Tol= 0.02
Split Flow Ratio= 0.02
Log Output Level= 0
Friction Slope Method= 1
Unsteady Friction Slope Method= 2
Unsteady Bridges Friction Slope Method= 1
Parabolic Critical Depth
Global Vel Dist=  1 , 1 , 1
Global Log Level= 0
CheckData=True
Encroach Param= -1, 0, 0, 0
BEGIN DESCRIPTION:
Multiple Run
END DESCRIPTION:

--- MDW T 109.f01 (steady flow) ---

Flow Title=Multiple
Number of Profiles=7
Profile Names=10-year,25-year,50-year,1pct_min,100-year,1pct_plu,500-year
River Rch & RM= MDW T 109,Reach-1,9679
     587     808     993     607    1212    2417    1804
River Rch & RM= MDW T 109,Reach-1,5369
     695     967    1195     734    1464    2921    2202
River Rch & RM= MDW T 109,Reach-1,4124
    1113    1589    1998    1246    2487    4962    3863
River Rch & RM= MDW T 109,Reach-1,1271
    1172    1678    2114    1321    2636    5259    4109
Boundary for River Rch & Prof#=MDW T 109,Reach-1,1
Up Type=0
Dn Type=3
Dn Slope=0.005
Boundary for River Rch & Prof#=MDW T 109,Reach-1,2
Up Type=0
Dn Type=3
Dn Slope=0.005
Boundary for River Rch & Prof#=MDW T 109,Reach-1,3
Up Type=0
Dn Type=3
Dn Slope=0.005
Boundary for River Rch & Prof#=MDW T 109,Reach-1,4
Up Type=0
Dn Type=3
Dn Slope=0.005
Boundary for River Rch & Prof#=MDW T 109,Reach-1,5
Up Type=0
Dn Type=3
Dn Slope=0.005
Boundary for River Rch & Prof#=MDW T 109,Reach-1,6
Up Type=0
Dn Type=3
Dn Slope=0.005
Boundary for River Rch & Prof#=MDW T 109,Reach-1,7
Up Type=0
Dn Type=3
Dn Slope=0.005

--- MDW T 109.g01 (geometry) ---

Geom Title=Existing Conditions

River Reach=MDW T 109,Reach-1
Reach XY= 30
      2285229.00      7132360.00      2285286.73      7132616.50
      2285427.60      7132671.58      2285434.41      7133054.74
      2285832.22      7133188.86      2285996.57      7133445.03
      2286400.93      7133779.54      2286605.98      7133769.57
      2286595.92      7133654.86      2286757.25      7133649.80
      2286781.06      7133845.94      2286902.83      7133764.52
      2287150.08      7133790.96      2287276.88      7133653.62
      2287695.61      7133596.54      2287882.06      7133317.79
      2288146.13      7133426.30      2288552.01      7133983.52
      2288996.28      7134305.72      2289246.99      7134268.08
      2289736.89      7134365.93      2289973.77      7134291.19
      2290149.53      7134645.76      2290879.28      7134813.63
      2290894.22      7134917.30      2291154.48      7134988.58
      2291239.92      7135496.46      2291329.99      7135454.06
      2291347.33      7135559.71      2291529.00      7135560.00

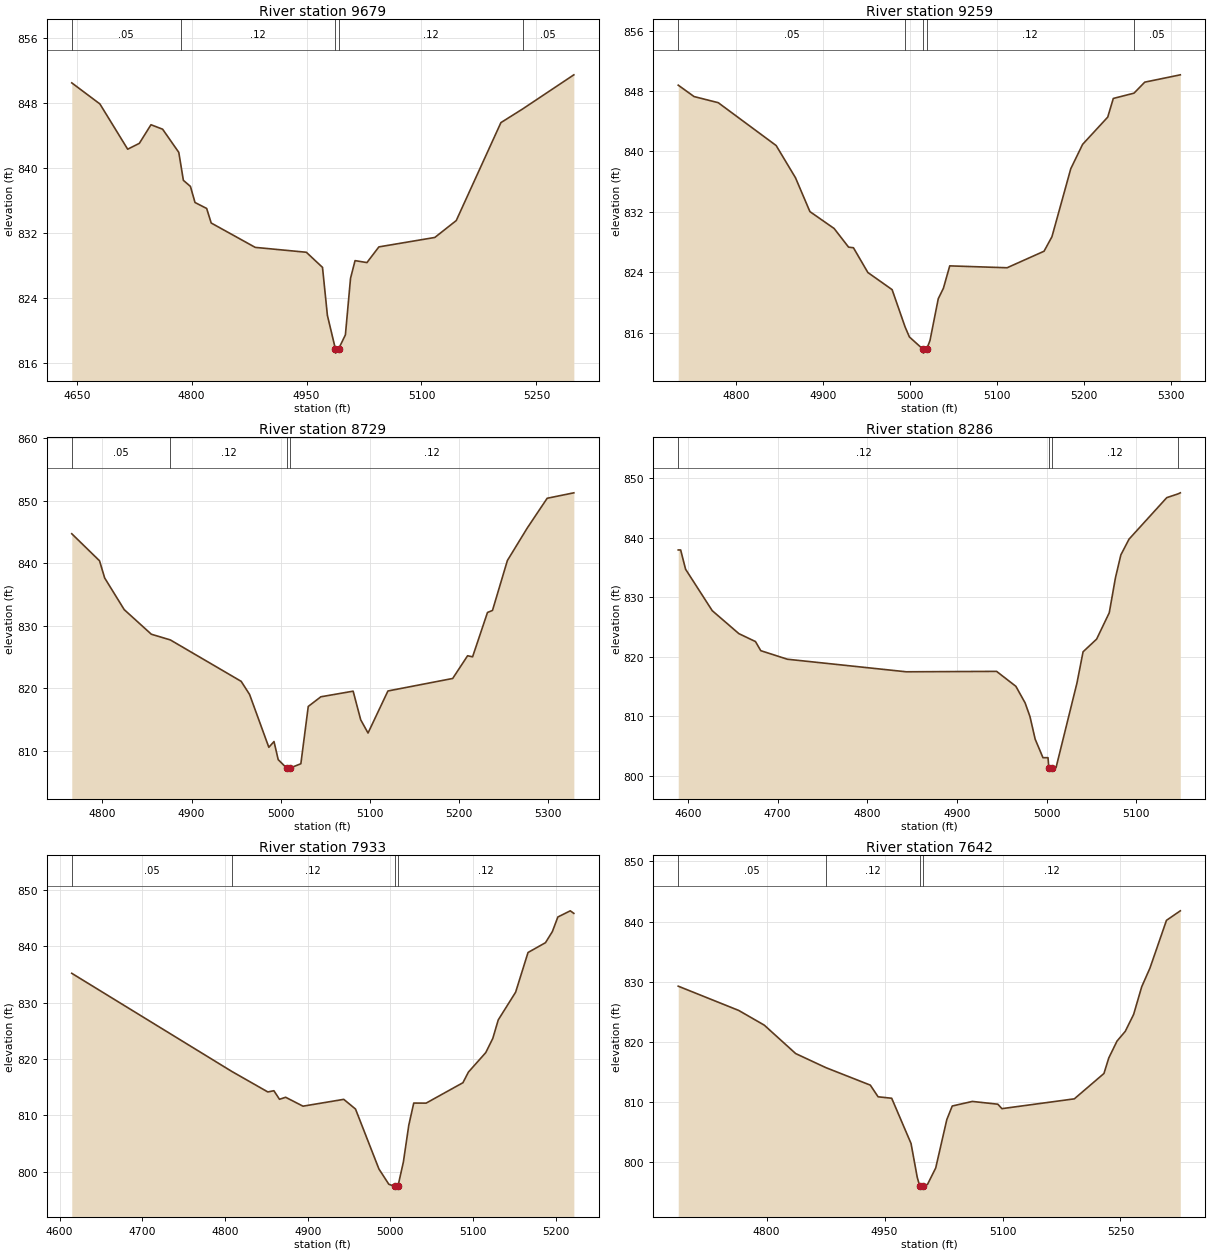
Type RM Length L Ch R = 1,9679,420,420,420
BEGIN DESCRIPTION:
MDW T 109 22.0
END DESCRIPTION:
XS GIS Cut Line= 3
      2284928.27      7132601.70      2285220.13      7132414.21
      2285484.61      7132255.39
#Sta/Elev= 30
  4643.5  850.48  4680.2  847.89  4716.5  842.32  4731.7  843.04  4746.9  845.33
  4762.1  844.78  4783.2  841.93  4785.7  840.50  4789.2  838.49  4798.4  837.74
  4804.4  835.76  4819.6  835.03  4825.5  833.24  4883.0  830.24  4949.7  829.64
  4970.8  827.78  4977.2  821.87  4987.7  817.73  4987.9  817.23  4991.7  817.73
  5000.7  819.48  5007.4  826.44  5013.3  828.61  5028.8  828.37  5044.4  830.30
  5117.4  831.46  5145.4  833.54  5203.7  845.59  5231.9  847.26  5298.9  851.47
#Mann=5,-1,0
  4643.5    0.05       0  4785.7    0.12       0  4987.7    0.07       0
  4991.7    0.12       0  5231.9    0.05       0
Bank Sta=4987.7,4991.7
Exp/Cntr=0.3,0.1

Type RM Length L Ch R = 1,9259,530,530,530
BEGIN DESCRIPTION:
MDW T 109 21.0
END DESCRIPTION:
XS GIS Cut Line= 3
      2285192.55      7132825.68      2285430.02      7132704.50
      2285694.61      7132540.86
#Sta/Elev= 30
  4733.4  848.78  4751.6  847.27  4779.4  846.46  4846.1  840.78  4868.3  836.52
  4884.9  832.03  4912.8  829.79  4929.4  827.32  4935.0  827.24  4951.6  823.96
  4979.5  821.69  4994.4  816.76  4999.4  815.42  5015.2  813.78  5015.5  813.28
  5019.2  813.78  5023.1  814.96  5032.6  820.49  5038.5  821.87  5045.8  824.84
  5111.8  824.59  5154.3  826.78  5163.4  828.70  5185.1  837.72  5198.7  840.94
  5227.6  844.55  5234.0  847.02  5257.8  847.72  5270.2  849.18  5311.1  850.15
#Mann=5,-1,0
  4733.4    0.05       0  4994.4    0.12       0  5015.2    0.07       0
  5019.2    0.12       0  5257.8    0.05       0
Bank Sta=5015.2,5019.2
Exp/Cntr=0.3,0.1

Type RM Length L Ch R = 1,8729,443,443,443
BEGIN DESCRIPTION:
MDW T 109 20.0
END DESCRIPTION:
XS GIS Cut Line= 3
      2285348.82      7133201.97      2285548.93      7133080.12
      2285842.36      7132932.42
#Sta/Elev= 30
  4765.7  844.72  4796.8  840.40  4802.6  837.65  4824.5  832.59  4854.9  828.66
  4876.2  827.75  4955.6  821.13  4965.0  819.04  4986.6  810.59  4992.4  811.51
  4997.1  808.62  5006.5  807.28  5006.8  806.78  5010.5  807.28  5022.5  807.96
  5030.8  817.12  5044.9  818.66  5081.1  819.56  5089.6  814.98  5097.8  812.87
  5120.1  819.59  5192.7  821.59  5209.4  825.22  5215.0  825.05  5231.7  832.14
  5237.3  832.46  5254.0  840.44  5276.3  845.64  5298.6  850.39  5328.5  851.26
#Mann=4,-1,0
  4765.7    0.05       0  4876.2    0.12       0  5006.5    0.07       0
  5010.5    0.12       0
Bank Sta=5006.5,5010.5
Exp/Cntr=0.3,0.1

Type RM Length L Ch R = 1,8286,353,353,353
BEGIN DESCRIPTION:
MDW T 109 19.0
END DESCRIPTION:
XS GIS Cut Line= 3
      2285508.95      7133409.01      2285890.03      7133258.29
      2286015.14      7133175.72
#Sta/Elev= 30
  4589.3  837.91  4592.0  837.91  4597.5  834.67  4627.2  827.71  4656.9  823.85
  4675.4  822.52  4681.3  820.99  4711.0  819.55  4843.5  817.44  4944.2  817.51
  4965.7  815.00  4976.0  812.21  4981.4  809.92  4987.2  806.12  4995.9  803.01
  5001.5  803.01  5002.5  801.25  5002.7  800.75  5006.5  801.25  5010.5  801.36
  5033.8  815.56  5040.6  820.80  5055.7  822.93  5069.8  827.36  5076.7  833.24
  5082.7  837.07  5091.8  839.72  5133.9  846.70  5146.4  847.33  5149.0  847.51
#Mann=4,-1,0
  4589.3    0.12       0  5002.5    0.07       0  5006.5    0.12       0
  5146.4    0.05       0
Bank Sta=5002.5,5006.5
Exp/Cntr=0.3,0.1

Type RM Length L Ch R = 1,7933,291,291,291
BEGIN DESCRIPTION:
MDW T 109 18.0
END DESCRIPTION:
XS GIS Cut Line= 3
      2285839.68      7133765.79      2286120.83      7133503.97
      2286244.31      7133318.38
#Sta/Elev= 30
  4614.7  835.19  4808.1  817.80  4851.8  814.15  4859.1  814.37  4865.9  812.85
  4873.3  813.21  4894.3  811.63  4943.6  812.84  4957.8  811.12  4986.1  800.50
  4998.1  797.78  5005.1  797.42  5005.4  796.92  5009.1  797.42  5015.7  801.75
  5022.2  808.24  5028.2  812.18  5043.2  812.17  5087.7  815.79  5094.3  817.67
  5115.3  821.13  5123.8  823.65  5130.4  826.93  5151.4  831.84  5166.4  838.88
  5187.5  840.62  5195.8  842.58  5202.5  845.18  5217.5  846.27  5221.8  845.82
#Mann=4,-1,0
  4614.7    0.05       0  4808.1    0.12       0  5005.1    0.07       0
  5009.1    0.12       0
Bank Sta=5005.1,5009.1
Exp/Cntr=0.3,0.1

Type RM Length L Ch R = 1,7642,542,542,542
BEGIN DESCRIPTION:
Mapping XS 9d5aae93
END DESCRIPTION:
XS GIS Cut Line= 2
      2286222.28      7134012.54      2286413.32      7133403.18
#Sta/Elev= 30
  4687.5  829.28  4764.4  825.25  4796.9  822.81  4836.9  818.08  4875.4  815.74
  4931.8  812.84  4941.7  810.90  4959.0  810.66  4983.6  803.15  4991.5  797.52
  4994.7  796.06  4995.0  795.56  4998.7  796.06  5004.6  796.36  5015.0  799.08
  5029.1  807.11  5036.0  809.37  5061.6  810.13  5094.0  809.67  5099.2  808.93
  5191.3  810.56  5229.0  814.78  5235.1  817.35  5245.6  820.16  5256.1  821.78
  5266.7  824.58  5277.0  829.18  5287.5  832.29  5308.5  840.22  5326.1  841.80
#Mann=4,-1,0
  4687.5    0.05       0  4875.4    0.12       0  4994.7    0.07       0
  4998.7    0.12       0
Bank Sta=4994.7,4998.7
Exp/Cntr=0.3,0.1

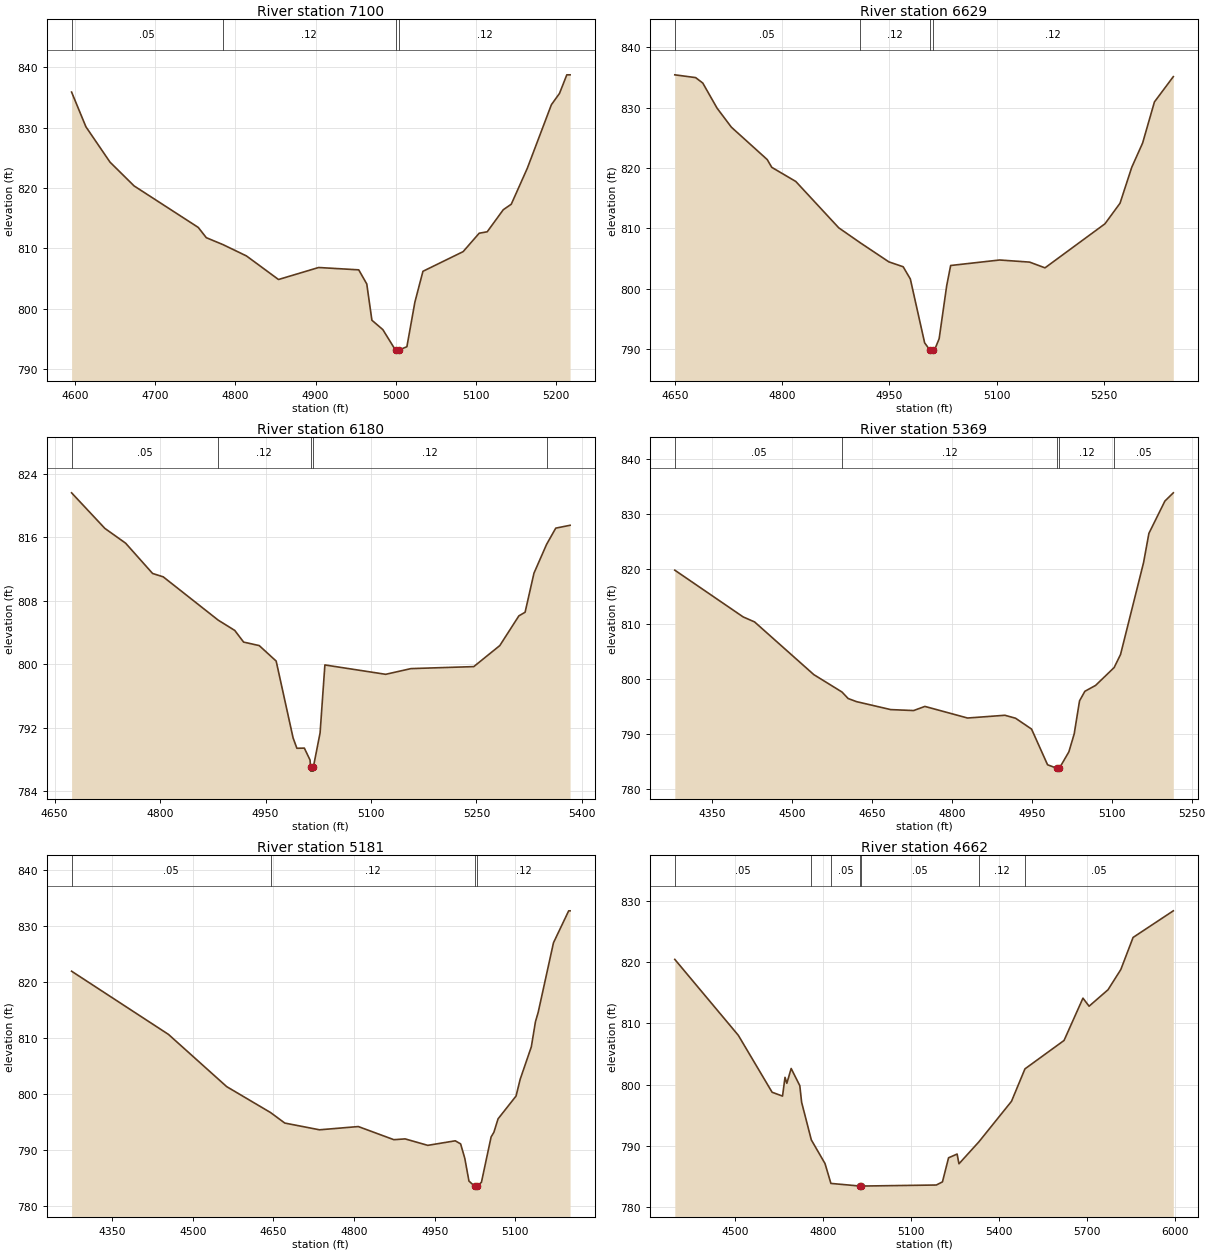
Type RM Length L Ch R = 1,7100,471,471,471
BEGIN DESCRIPTION:
MDW T 109 16.0
END DESCRIPTION:
XS GIS Cut Line= 3
      2286656.12      7134067.90      2286653.82      7133659.50
      2286645.70      7133446.76
#Sta/Elev= 30
  4595.9  835.87  4613.8  830.11  4643.8  824.26  4673.8  820.32  4753.8  813.44
  4763.8  811.74  4784.5  810.60  4813.8  808.72  4853.8  804.81  4903.8  806.80
  4953.8  806.41  4963.8  804.07  4970.2  798.06  4983.8  796.51  4999.6  793.11
  4999.8  792.61  5003.6  793.11  5013.8  793.67  5023.8  801.08  5033.8  806.17
  5083.9  809.43  5103.9  812.48  5113.9  812.72  5133.9  816.37  5143.9  817.29
  5163.9  823.25  5193.9  833.78  5204.0  835.65  5213.1  838.73  5217.2  838.73
#Mann=4,-1,0
  4595.9    0.05       0  4784.5    0.12       0  4999.6    0.07       0
  5003.6    0.12       0
Bank Sta=4999.6,5003.6
Exp/Cntr=0.3,0.1

Type RM Length L Ch R = 1,6629,449,449,449
BEGIN DESCRIPTION:
MDW T 109 15.0
END DESCRIPTION:
XS GIS Cut Line= 3
      2286869.66      7134129.10      2286881.17      7133766.14
      2286775.89      7133449.32
#Sta/Elev= 30
  4650.0  835.44  4679.1  834.98  4689.1  834.08  4709.1  829.92  4729.1  826.77
  4779.2  821.41  4785.6  820.12  4819.2  817.78  4879.2  810.11  4908.6  807.69
  4949.3  804.47  4969.3  803.66  4979.3  801.64  4999.3  791.07  5006.7  789.86
  5007.0  789.36  5010.7  789.86  5013.1  789.86  5019.6  791.75  5030.2  800.56
  5035.7  803.87  5104.2  804.78  5146.1  804.43  5167.6  803.48  5251.4  810.77
  5272.5  814.18  5288.9  820.13  5304.1  824.15  5320.6  830.95  5347.0  835.14
#Mann=4,-1,0
  4650.0    0.05       0  4908.6    0.12       0  5006.7    0.07       0
  5010.7    0.12       0
Bank Sta=5006.7,5010.7
Exp/Cntr=0.3,0.1

Type RM Length L Ch R = 1,6180,811,811,811
BEGIN DESCRIPTION:
MDW T 109 14.0
END DESCRIPTION:
XS GIS Cut Line= 3
      2287382.68      7133976.72      2287253.96      7133659.91
      2287064.95      7133345.17
#Sta/Elev= 30
  4674.1  821.58  4721.4  817.10  4750.9  815.24  4789.3  811.42  4804.5  810.99
  4882.6  805.54  4906.2  804.24  4918.8  802.77  4941.0  802.33  4965.1  800.38
  4989.2  790.69  4994.6  789.39  5005.2  789.41  5013.3  787.91  5014.0  787.01
  5014.3  786.51  5017.8  786.51  5018.0  787.01  5027.6  791.34  5034.4  799.89
  5120.9  798.71  5156.9  799.43  5246.2  799.68  5283.2  802.33  5310.4  806.08
  5319.2  806.53  5331.8  811.45  5349.8  815.09  5362.8  817.13  5383.2  817.49
#Mann=5,-1,0
  4674.1    0.05       0  4882.6    0.12       0  5014.0    0.07       0
  5018.0    0.12       0  5349.8    0.05       0
Bank Sta=5014,5018
Exp/Cntr=0.3,0.1

Type RM Length L Ch R = 1,5369,188,188,188
BEGIN DESCRIPTION:
Mapping XS 79e09c9a
END DESCRIPTION:
XS GIS Cut Line= 3
      2287628.30      7133974.52      2287864.52      7133575.12
      2287876.47      7133104.20
#Sta/Elev= 30
  4280.4  819.78  4408.6  811.28  4430.0  810.37  4541.2  800.78  4594.0  797.62
  4605.5  796.44  4621.2  795.87  4685.5  794.42  4728.4  794.25  4749.5  795.00
  4829.6  792.89  4899.6  793.39  4919.6  792.85  4949.6  790.88  4979.6  784.39
  4997.6  783.73  4997.9  783.23  5001.4  783.23  5001.6  783.73  5019.6  786.74
  5029.6  790.01  5039.6  796.01  5049.6  797.75  5069.7  798.82  5104.5  802.07
  5116.5  804.44  5159.7  821.15  5169.7  826.47  5199.7  832.35  5215.5  833.85
#Mann=5,-1,0
  4280.4    0.05       0  4594.0    0.12       0  4997.6    0.07       0
  5001.6    0.12       0  5104.5    0.05       0
Bank Sta=4997.6,5001.6
Exp/Cntr=0.3,0.1

Type RM Length L Ch R = 1,5181,519,519,519
BEGIN DESCRIPTION:
MDW T 109 11.0
END DESCRIPTION:
XS GIS Cut Line= 3
      2287629.03      7134009.96      2288029.00      7133410.00
      2288079.00      7133210.02
#Sta/Elev= 30
  4274.7  821.90  4454.9  810.64  4563.1  801.34  4644.7  796.72  4671.3  794.84
  4735.9  793.64  4808.0  794.22  4874.1  791.88  4895.1  792.02  4937.2  790.87
  4988.3  791.68  4998.3  791.13  5006.1  788.54  5013.8  784.50  5024.7  783.57
  5024.9  783.07  5028.4  783.07  5028.7  783.57  5037.0  784.29  5055.0  792.37
  5060.2  793.21  5067.9  795.59  5101.4  799.66  5109.1  802.65  5129.8  808.43
  5137.5  812.91  5142.6  814.59  5171.0  826.97  5199.3  832.66  5201.9  832.66
#Mann=4,-1,0
  4274.7    0.05       0  4644.7    0.12       0  5024.7    0.07       0
  5028.7    0.12       0
Bank Sta=5024.7,5028.7
Exp/Cntr=0.3,0.1

Type RM Length L Ch R = 1,4662,538,538,538
BEGIN DESCRIPTION:
Mapping XS d0538981
END DESCRIPTION:
XS GIS Cut Line= 3
      2287980.87      7134294.91      2288408.89      7133706.07
      2289180.00      7133119.86
#Sta/Elev= 30
  4296.2  820.45  4512.4  808.07  4627.3  798.79  4662.8  798.16  4671.3  801.22
  4677.5  800.25  4692.2  802.66  4721.6  799.86  4727.8  797.15  4760.8  791.02
  4807.4  787.16  4827.5  783.92  4926.7  783.49  4926.9  782.99  4930.7  783.49
  5186.2  783.66  5207.1  784.17  5227.9  788.10  5257.0  788.71  5263.3  787.12
  5331.1  790.70  5442.1  797.31  5487.9  802.60  5620.9  807.23  5685.3  814.13
  5706.2  812.82  5770.6  815.50  5814.2  818.80  5855.9  824.03  5992.8  828.37
#Mann=7,-1,0
  4296.2    0.05       0  4760.8    0.12       0  4827.5    0.05       0
  4926.7   0.033       0  4930.7    0.05       0  5331.1    0.12       0
  5487.9    0.05       0
Bank Sta=4926.7,4930.7
Exp/Cntr=0.3,0.1

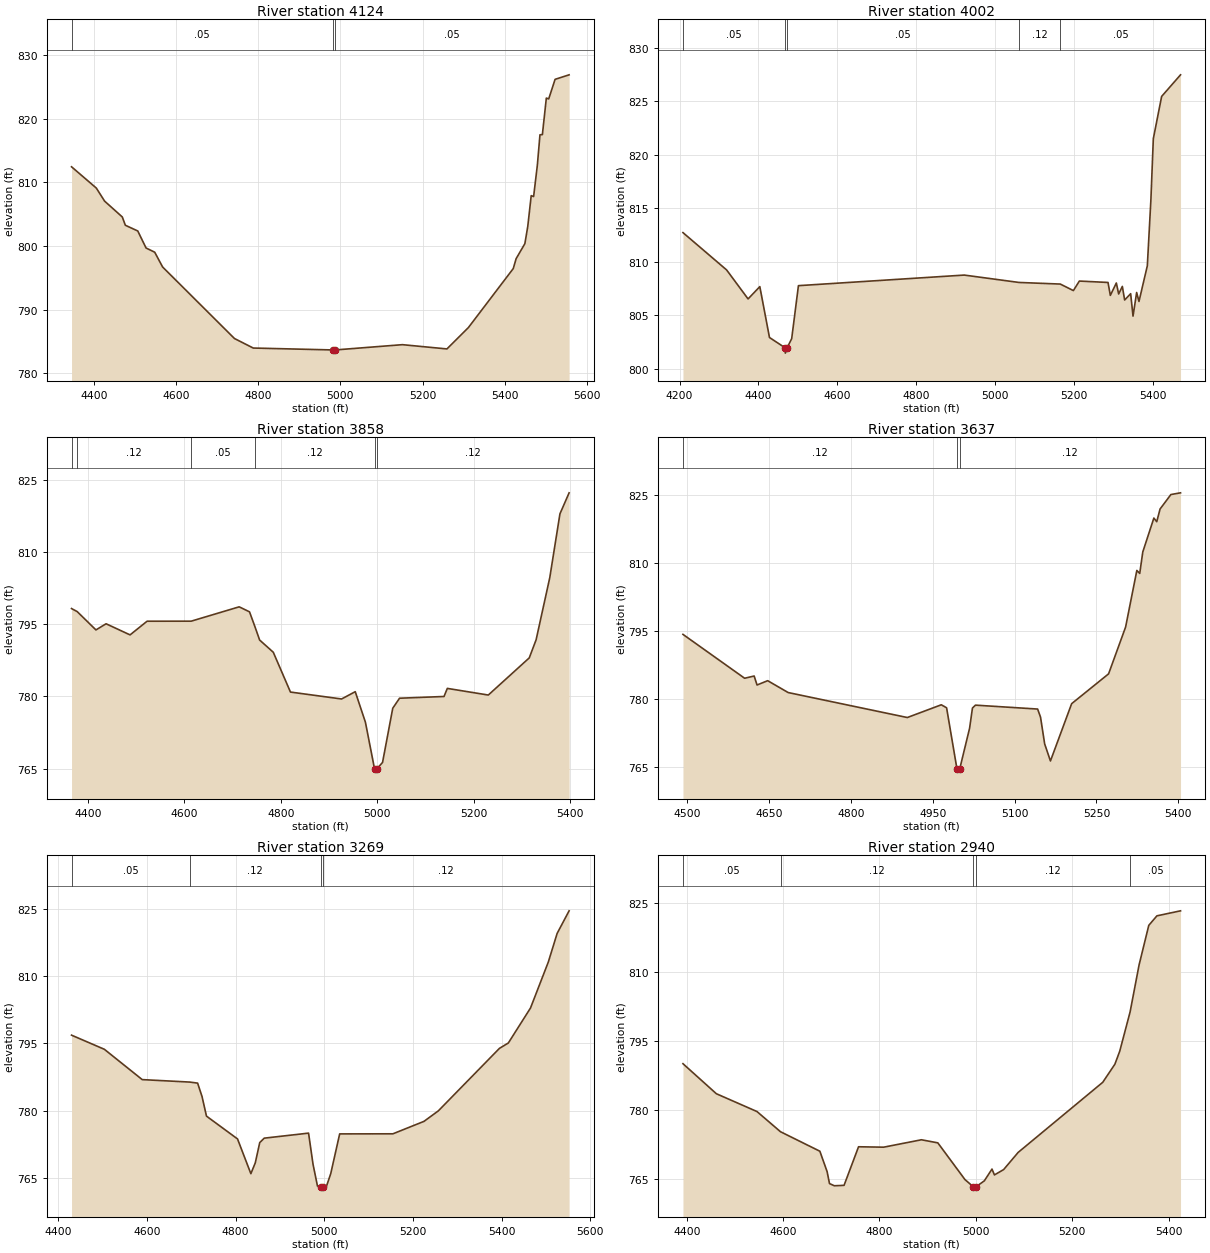
Type RM Length L Ch R = 1,4124,122,122,122
BEGIN DESCRIPTION:
Mapping XS e6cbfd35
END DESCRIPTION:
XS GIS Cut Line= 4
      2288139.24      7134300.76      2288430.63      7134262.54
      2288655.67      7134130.59      2289214.83      7133788.22
#Sta/Elev= 30
  4346.1  812.46  4406.4  809.11  4426.5  807.06  4469.6  804.56  4477.0  803.26
  4507.2  802.36  4527.4  799.68  4548.4  799.02  4567.7  796.69  4742.4  785.44
  4788.1  783.94  4982.0  783.64  4982.7  783.14  4987.1  783.64  5151.0  784.47
  5259.3  783.80  5311.5  787.16  5420.7  796.45  5427.6  798.00  5448.9  800.37
  5455.9  803.06  5464.3  807.92  5470.2  807.78  5479.3  812.74  5485.6  817.49
  5491.5  817.53  5501.1  823.27  5506.9  823.14  5522.4  826.22  5556.5  826.93
#Mann=3,-1,0
  4346.1    0.05       0  4982.0   0.033       0  4987.1    0.05       0
Bank Sta=4982,4987.1
Exp/Cntr=0.3,0.1

Type RM Length L Ch R = 1,4002,144,144,144
BEGIN DESCRIPTION:
Mapping XS 43e57055
END DESCRIPTION:
XS GIS Cut Line= 6
      2288150.59      7134535.14      2288355.95      7134455.03
      2288406.36      7134400.76      2288527.22      7134333.49
      2288855.20      7134140.48      2289232.26      7133897.76
#Sta/Elev= 30
  4208.5  812.71  4319.2  809.22  4373.6  806.51  4403.4  807.66  4427.9  802.90
  4467.5  801.94  4468.1  801.44  4472.6  801.94  4484.2  802.79  4501.3  807.75
  4921.9  808.74  5060.6  808.05  5165.3  807.90  5198.6  807.29  5213.7  808.18
  5286.4  808.05  5292.3  806.84  5307.5  808.00  5313.4  806.97  5322.7  807.68
  5328.6  806.41  5343.8  807.00  5349.8  804.90  5359.0  807.11  5364.9  806.27
  5386.1  809.61  5395.1  815.75  5401.3  821.50  5422.4  825.45  5470.3  827.47
#Mann=5,-1,0
  4208.5    0.05       0  4467.5   0.033       0  4472.6    0.05       0
  5060.6    0.12       0  5165.3    0.05       0
Bank Sta=4467.5,4472.6
Exp/Cntr=0.3,0.1

Type RM Length L Ch R = 1,3858,221,221,221
BEGIN DESCRIPTION:
Mapping XS 7eed30f8
END DESCRIPTION:
XS GIS Cut Line= 2
      2288479.12      7134691.55      2289225.26      7133979.47
#Sta/Elev= 30
  4366.0  798.24  4377.7  797.61  4416.6  793.80  4437.6  795.08  4487.3  792.77
  4522.6  795.61  4614.0  795.62  4713.5  798.60  4734.9  797.56  4745.6  794.63
  4755.9  791.70  4784.2  789.16  4819.8  780.89  4925.8  779.45  4954.1  780.97
  4975.2  774.61  4994.0  764.96  4994.6  764.46  4999.1  764.96  5010.7  766.27
  5031.8  777.52  5045.9  779.61  5138.1  779.97  5145.0  781.65  5229.9  780.27
  5314.8  787.99  5329.0  791.75  5357.3  804.65  5378.4  817.92  5397.4  822.29
#Mann=6,-1,0
  4366.0    0.05       0  4377.7    0.12       0  4614.0    0.05       0
  4745.6    0.12       0  4994.0    0.07       0  4999.1    0.12       0
Bank Sta=4994,4999.1
Exp/Cntr=0.3,0.1

Type RM Length L Ch R = 1,3637,368,368,368
BEGIN DESCRIPTION:
Mapping XS 6c33f815
END DESCRIPTION:
XS GIS Cut Line= 2
      2288970.87      7134806.83      2289268.51      7133944.56
#Sta/Elev= 30
  4492.0  794.17  4605.0  784.49  4622.5  784.98  4627.8  783.00  4647.3  783.95
  4684.9  781.33  4903.3  775.82  4965.6  778.63  4975.3  777.97  4994.3  764.49
  4994.9  763.99  4999.4  764.49  5017.5  773.47  5022.7  777.91  5028.2  778.55
  5142.2  777.69  5147.5  775.92  5155.1  770.00  5165.7  766.23  5204.6  778.88
  5272.3  785.46  5303.5  795.79  5324.1  808.28  5329.4  807.62  5335.0  812.36
  5355.3  819.84  5360.6  819.04  5366.7  821.84  5386.5  825.03  5404.2  825.41
#Mann=3,-1,0
  4492.0    0.12       0  4994.3    0.07       0  4999.4    0.12       0
Bank Sta=4994.3,4999.4
Exp/Cntr=0.3,0.1

Type RM Length L Ch R = 1,3269,329,329,329
BEGIN DESCRIPTION:
Mapping XS 1c6c87ce
END DESCRIPTION:
XS GIS Cut Line= 2
      2289424.40      7134923.97      2289491.90      7133803.10
#Sta/Elev= 30
  4429.6  796.82  4503.7  793.67  4589.1  786.92  4696.6  786.37  4714.1  786.14
  4724.1  783.15  4734.1  778.79  4804.2  773.71  4834.3  765.97  4844.3  768.39
  4854.3  772.89  4864.4  773.88  4964.5  775.00  4974.6  768.06  4984.6  763.22
  4992.0  763.03  4992.7  762.53  4997.2  763.03  5004.6  763.08  5014.6  765.99
  5034.7  774.83  5154.9  774.85  5225.0  777.62  5257.4  779.96  5395.3  793.88
  5415.4  795.08  5465.4  802.87  5505.5  813.09  5525.5  819.48  5552.5  824.51
#Mann=4,-1,0
  4429.6    0.05       0  4696.6    0.12       0  4992.0    0.07       0
  4997.2    0.12       0
Bank Sta=4992,4997.2
Exp/Cntr=0.3,0.1

Type RM Length L Ch R = 1,2940,492,492,492
BEGIN DESCRIPTION:
Mapping XS 5cf10200
END DESCRIPTION:
XS GIS Cut Line= 2
      2289727.86      7134952.98      2289818.12      7133924.33
#Sta/Elev= 30
  4392.2  790.06  4461.5  783.53  4545.8  779.66  4594.6  775.27  4676.3  771.03
  4691.3  766.61  4696.3  764.00  4706.4  763.52  4726.5  763.61  4756.6  772.00
  4808.7  771.91  4887.1  773.52  4921.1  772.85  4977.4  764.87  4994.9  763.29
  4995.6  762.79  5000.1  763.29  5017.6  764.59  5033.5  767.15  5038.6  765.88
  5057.7  767.04  5087.8  770.77  5263.4  786.02  5288.6  789.96  5298.6  792.77
  5320.1  801.30  5338.8  811.55  5358.9  820.14  5375.8  822.21  5424.8  823.30
#Mann=5,-1,0
  4392.2    0.05       0  4594.6    0.12       0  4994.9    0.07       0
  5000.1    0.12       0  5320.1    0.05       0
Bank Sta=4994.9,5000.1
Exp/Cntr=0.3,0.1

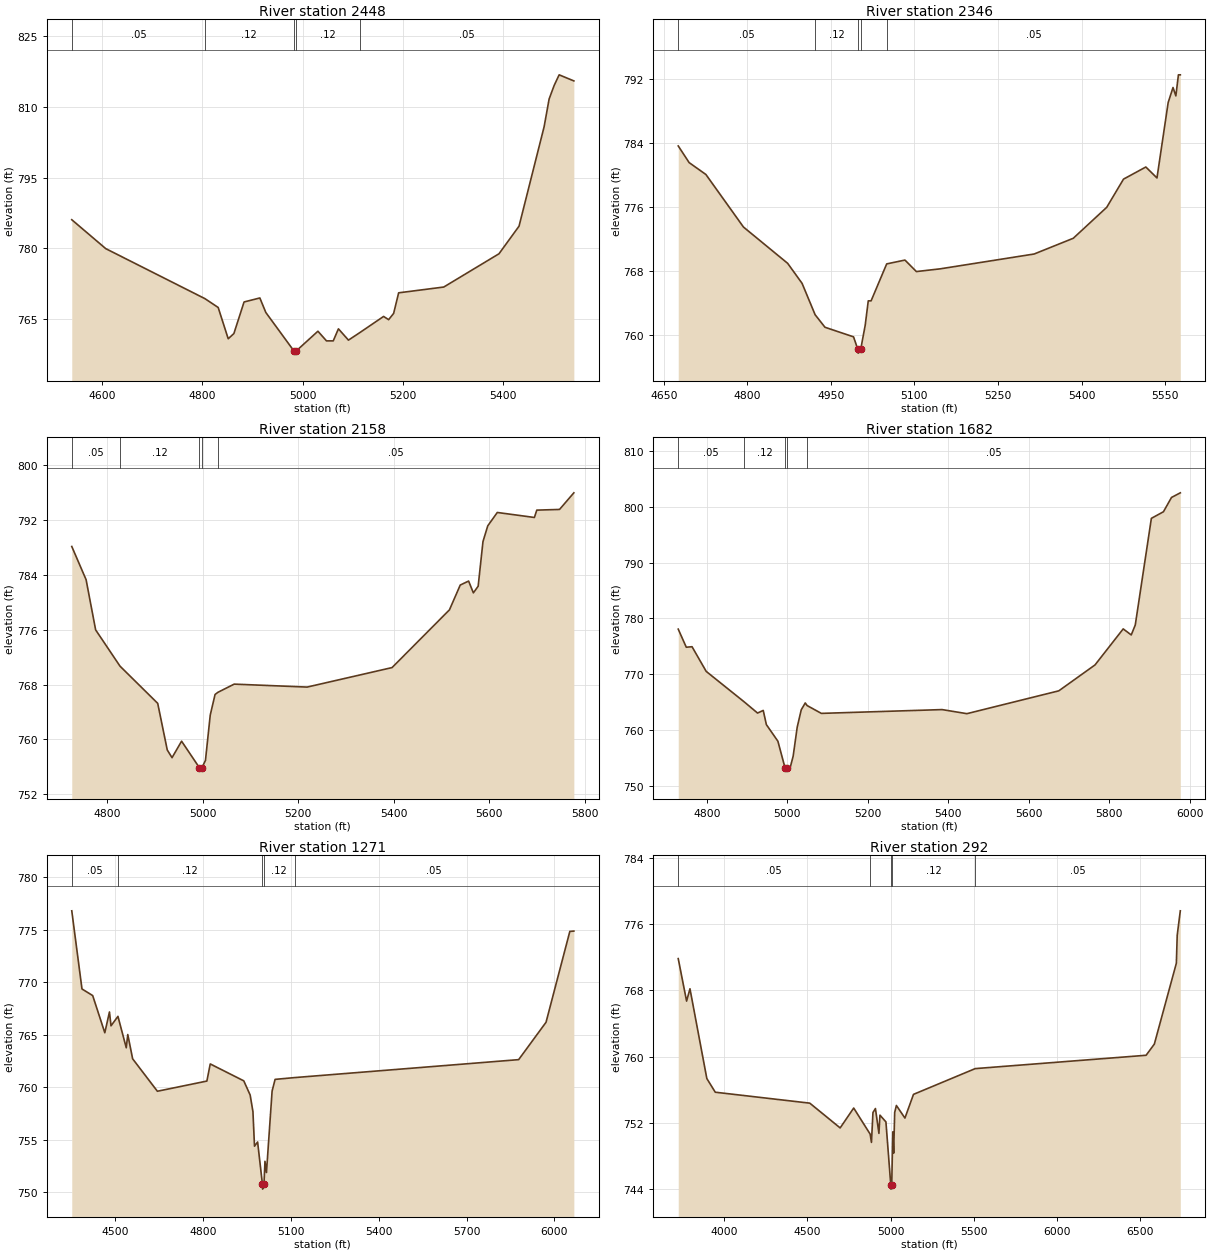
Type RM Length L Ch R = 1,2448,102,102,102
BEGIN DESCRIPTION:
Mapping XS 91d7a479
END DESCRIPTION:
XS GIS Cut Line= 6
      2290008.56      7134986.94      2289988.04      7134856.87
      2290014.31      7134703.03      2290083.36      7134492.48
      2290087.31      7134388.63      2290078.10      7134000.70
#Sta/Elev= 30
  4539.3  786.06  4607.1  779.92  4804.8  769.31  4831.3  767.43  4851.3  760.79
  4862.6  761.89  4882.9  768.60  4914.4  769.45  4926.3  766.37  4982.1  758.24
  4982.8  757.74  4987.3  758.24  5030.2  762.39  5047.3  760.34  5060.8  760.34
  5071.1  762.90  5091.1  760.50  5114.1  762.12  5161.2  765.53  5171.2  764.84
  5181.2  766.17  5191.2  770.54  5281.2  771.77  5391.3  778.83  5431.3  784.69
  5481.3  805.79  5491.3  811.69  5501.3  814.55  5511.3  816.82  5540.6  815.53
#Mann=5,-1,0
  4539.3    0.05       0  4804.8    0.12       0  4982.1    0.07       0
  4987.3    0.12       0  5114.1    0.05       0
Bank Sta=4982.1,4987.3
Exp/Cntr=0.3,0.1

Type RM Length L Ch R = 1,2346,188,188,188
BEGIN DESCRIPTION:
Mapping XS d1c948e2
END DESCRIPTION:
XS GIS Cut Line= 5
      2290084.93      7134939.59      2290076.91      7134820.54
      2290126.45      7134603.42      2290155.33      7134478.47
      2290184.63      7134048.23
#Sta/Elev= 30
  4675.9  783.63  4695.5  781.54  4725.6  780.05  4793.0  773.47  4872.4  768.92
  4898.3  766.41  4921.7  762.48  4939.4  760.91  4990.7  759.71  4998.2  758.17
  4999.0  757.67  5003.6  758.17  5011.6  761.16  5017.1  764.22  5022.2  764.22
  5050.2  768.85  5083.0  769.33  5103.5  767.89  5146.2  768.23  5315.0  770.09
  5385.2  772.06  5445.3  775.94  5475.4  779.47  5515.5  780.99  5535.5  779.62
  5555.6  789.07  5564.3  790.95  5569.4  789.90  5574.0  792.54  5577.4  792.54
#Mann=5,-1,0
  4675.9    0.05       0  4921.7    0.12       0  4998.2    0.07       0
  5003.6    0.12       0  5050.2    0.05       0
Bank Sta=4998.2,5003.6
Exp/Cntr=0.3,0.1

Type RM Length L Ch R = 1,2158,476,476,476
BEGIN DESCRIPTION:
MDW T 109 4.0
END DESCRIPTION:
XS GIS Cut Line= 3
      2290279.00      7134909.96      2290279.00      7134660.00
      2290229.00      7133860.02
#Sta/Elev= 30
  4725.8  788.11  4755.8  783.27  4775.8  775.96  4826.8  770.68  4905.8  765.26
  4925.8  758.47  4935.8  757.35  4955.8  759.75  4993.1  755.89  4993.9  755.39
  4998.5  755.89  5005.8  756.96  5015.8  763.55  5025.9  766.55  5031.7  766.86
  5065.9  768.06  5218.7  767.63  5396.6  770.47  5516.8  778.88  5539.4  782.49
  5556.9  783.07  5566.9  781.35  5576.9  782.32  5587.0  788.82  5597.0  791.11
  5617.0  793.06  5694.7  792.33  5699.7  793.40  5747.3  793.50  5777.3  795.92
#Mann=5,-1,0
  4725.8    0.05       0  4826.8    0.12       0  4993.1    0.07       0
  4998.5    0.12       0  5031.7    0.05       0
Bank Sta=4993.1,4998.5
Exp/Cntr=0.3,0.1

Type RM Length L Ch R = 1,1682,411,411,411
BEGIN DESCRIPTION:
MDW T 109 3.0
END DESCRIPTION:
XS GIS Cut Line= 3
      2290501.44      7134970.74      2290679.00      7134760.00
      2290690.09      7133788.13
#Sta/Elev= 30
  4729.2  778.07  4749.2  774.83  4763.5  774.92  4798.7  770.50  4892.3  765.09
  4926.3  763.04  4940.4  763.51  4948.2  760.97  4976.8  758.00  4994.9  753.14
  4995.7  752.64  5000.4  753.14  5007.3  753.25  5014.8  755.34  5024.8  760.51
  5034.8  763.61  5044.8  764.85  5049.3  764.39  5084.8  762.98  5384.8  763.66
  5446.4  762.93  5674.8  767.02  5764.8  771.66  5834.8  778.11  5854.8  777.03
  5864.8  778.81  5904.8  797.91  5934.8  799.09  5954.8  801.65  5976.7  802.48
#Mann=5,-1,0
  4729.2    0.05       0  4892.3    0.12       0  4994.9    0.07       0
  5000.4    0.12       0  5049.3    0.05       0
Bank Sta=4994.9,5000.4
Exp/Cntr=0.3,0.1

Type RM Length L Ch R = 1,1271,979,979,979
BEGIN DESCRIPTION:
Mapping XS 50745a5e
END DESCRIPTION:
XS GIS Cut Line= 3
      2290382.17      7135176.71      2290979.51      7134972.43
      2290779.86      7133906.58
#Sta/Elev= 30
  4350.8  776.82  4385.7  769.38  4422.3  768.75  4463.7  765.21  4479.6  767.19
  4484.9  765.87  4508.6  766.77  4537.0  763.78  4542.2  765.04  4558.8  762.73
  4643.4  759.64  4812.5  760.61  4824.0  762.24  4938.6  760.63  4960.4  759.28
  4969.9  757.70  4975.2  754.41  4985.9  754.81  5002.2  750.82  5003.0  750.32
  5007.7  750.82  5011.0  752.97  5016.1  751.90  5035.4  759.66  5045.6  760.77
  5112.0  760.94  5877.9  762.65  5971.5  766.21  6052.8  774.86  6066.5  774.89
#Mann=5,-1,0
  4350.8    0.05       0  4508.6    0.12       0  5002.2    0.07       0
  5007.7    0.12       0  5112.0    0.05       0
Bank Sta=5002.2,5007.7
Exp/Cntr=0.3,0.1

Type RM Length L Ch R = 1,292,0,0,0
BEGIN DESCRIPTION:
MDW T 109 2.0
END DESCRIPTION:
XS GIS Cut Line= 4
      2290169.48      7135469.69      2291205.43      7135641.44
      2291329.02      7135458.28      2290929.00      7133760.00
#Sta/Elev= 30
  3724.6  771.84  3774.8  766.71  3795.1  768.20  3896.4  757.36  3947.1  755.71
  4514.8  754.39  4697.2  751.40  4778.6  753.80  4877.4  750.65  4885.2  749.65
  4894.2  753.25  4909.1  753.74  4930.1  750.74  4936.2  752.94  4972.1  752.13
  5001.3  744.51  5002.2  744.01  5007.0  744.51  5013.4  750.92  5018.5  748.35
  5024.7  753.26  5035.0  754.11  5086.3  752.59  5137.7  755.45  5508.4  758.56
  6534.9  760.17  6584.4  761.52  6716.7  771.29  6721.8  774.67  6740.4  777.61
#Mann=5,-1,0
  3724.6    0.05       0  4877.4    0.12       0  5001.3    0.07       0
  5007.0    0.12       0  5508.4    0.05       0
Bank Sta=5001.3,5007
Exp/Cntr=0.3,0.1

Chan Stop Cuts=-1