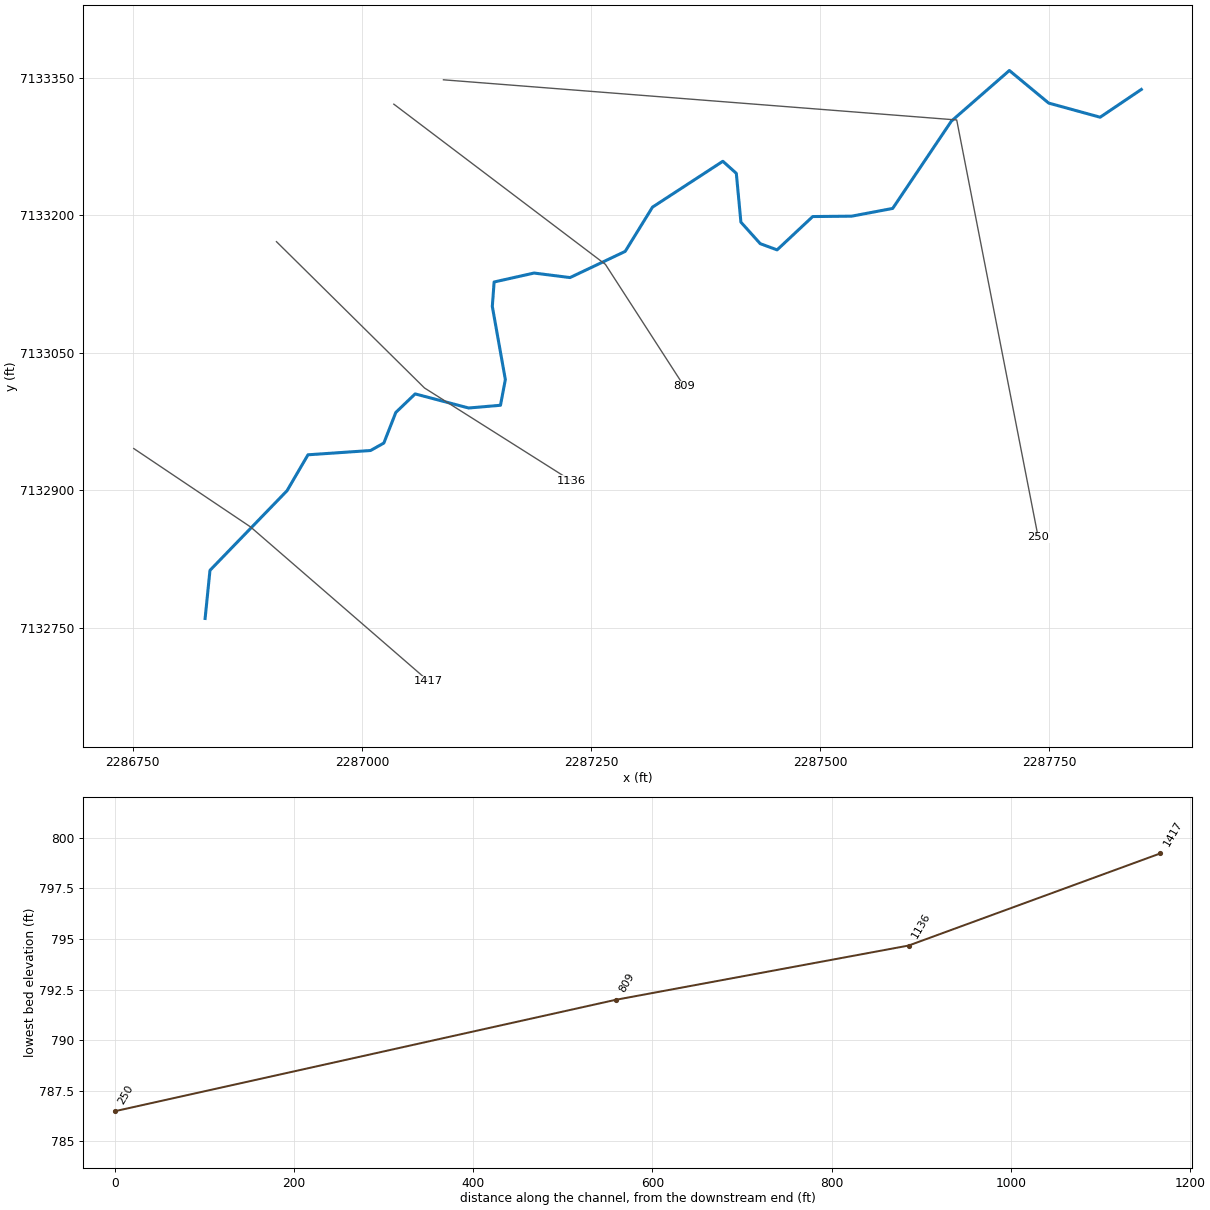
--- MDW T 110.prj (project) ---

Proj Title=MDW T 110 Base Level Engineering
Current Plan=p01
Default Exp/Contr=0.3,0.1
English Units
Geom File=g01
Flow File=f01
Plan File=p01
BEGIN DESCRIPTION:
MDW T 110
END DESCRIPTION:

--- MDW T 110.p01 (plan) ---

Plan Title=Multiple Run
Short Identifier=Multiple
Geom File=g01
Flow File=f01
Subcritical Flow
K Sum by GR= 0
Std Step Tol= 0.01
Critical Tol= 0.01
Num of Std Step Trials= 20
Max Error Tol= 0.3
Flow Tol Ratio= 0.001
Split Flow NTrial= 30
Split Flow Tol= 0.02
Split Flow Ratio= 0.02
Log Output Level= 0
Friction Slope Method= 1
Unsteady Friction Slope Method= 2
Unsteady Bridges Friction Slope Method= 1
Parabolic Critical Depth
Global Vel Dist=  1 , 1 , 1
Global Log Level= 0
CheckData=True
Encroach Param= -1, 0, 0, 0
BEGIN DESCRIPTION:
Multiple Run
END DESCRIPTION:

--- MDW T 110.f01 (steady flow) ---

Flow Title=Multiple
Number of Profiles=7
Profile Names=10-year,25-year,50-year,1pct_min,100-year,1pct_plu,500-year
River Rch & RM= MDW T 110,Reach-1,1417
     252     330     393     234     466     930     654
Boundary for River Rch & Prof#=MDW T 110,Reach-1,1
Up Type=0
Dn Type=3
Dn Slope=0.005
Boundary for River Rch & Prof#=MDW T 110,Reach-1,2
Up Type=0
Dn Type=3
Dn Slope=0.005
Boundary for River Rch & Prof#=MDW T 110,Reach-1,3
Up Type=0
Dn Type=3
Dn Slope=0.005
Boundary for River Rch & Prof#=MDW T 110,Reach-1,4
Up Type=0
Dn Type=3
Dn Slope=0.005
Boundary for River Rch & Prof#=MDW T 110,Reach-1,5
Up Type=0
Dn Type=3
Dn Slope=0.005
Boundary for River Rch & Prof#=MDW T 110,Reach-1,6
Up Type=0
Dn Type=3
Dn Slope=0.005
Boundary for River Rch & Prof#=MDW T 110,Reach-1,7
Up Type=0
Dn Type=3
Dn Slope=0.005

--- MDW T 110.g01 (geometry) ---

Geom Title=Existing Conditions

River Reach=MDW T 110,Reach-1
Reach XY= 30
      2286829.00      7132760.00      2286834.31      7132812.52
      2286918.41      7132899.46      2286941.25      7132938.63
      2287009.53      7132943.30      2287024.01      7132951.44
      2287037.11      7132984.89      2287058.19      7133005.09
      2287116.59      7132989.68      2287151.28      7132992.68
      2287156.60      7133020.72      2287142.37      7133100.54
      2287144.34      7133127.22      2287187.92      7133136.98
      2287227.17      7133132.04      2287287.37      7133160.62
      2287317.13      7133208.90      2287393.91      7133258.97
      2287408.60      7133245.79      2287413.61      7133192.53
      2287434.69      7133169.05      2287453.11      7133162.27
      2287491.95      7133198.64      2287534.50      7133199.06
      2287579.22      7133207.50      2287643.23      7133302.76
      2287706.52      7133358.03      2287749.44      7133322.47
      2287805.59      7133307.04      2287850.52      7133337.37

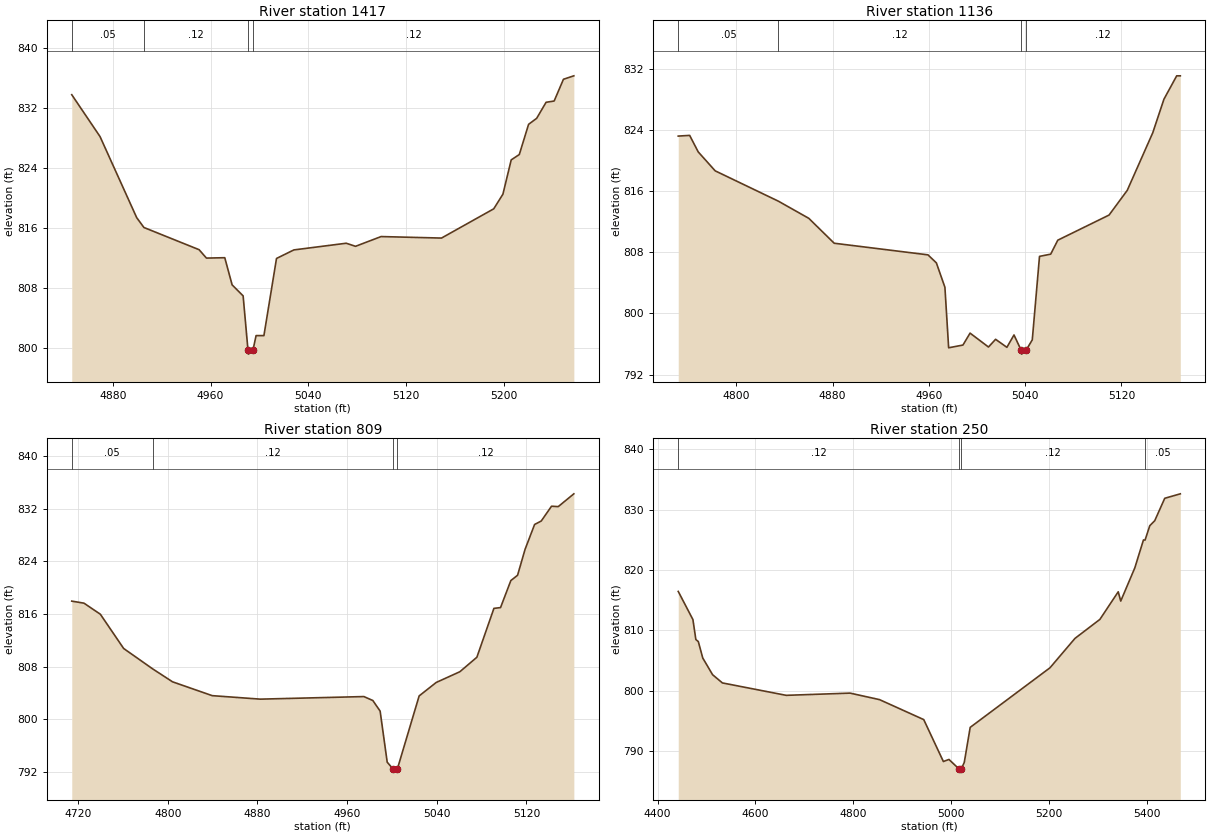
Type RM Length L Ch R = 1,1417,281,281,281
BEGIN DESCRIPTION:
MDW T 110 3.0
END DESCRIPTION:
XS GIS Cut Line= 3
      2286751.19      7132945.44      2286878.62      7132859.87
      2287072.81      7132691.53
#Sta/Elev= 30
  4846.5  833.82  4869.6  828.24  4899.6  817.42  4905.5  816.11  4950.6  813.15
  4956.6  812.03  4971.6  812.08  4977.6  808.46  4986.6  806.99  4990.6  799.72
  4990.9  799.22  4994.6  799.72  4997.2  801.69  5003.6  801.69  5013.9  811.98
  5028.1  813.12  5070.9  814.01  5078.5  813.60  5099.4  814.90  5148.8  814.70
  5191.5  818.60  5199.0  820.55  5205.8  825.13  5212.4  825.84  5220.0  829.87
  5226.6  830.67  5234.3  832.81  5240.9  832.98  5248.5  835.88  5257.0  836.34
#Mann=4,-1,0
  4846.5    0.05       0  4905.5    0.12       0  4990.6    0.07       0
  4994.6    0.12       0
Bank Sta=4990.6,4994.6
Exp/Cntr=0.3,0.1

Type RM Length L Ch R = 1,1136,327,327,327
BEGIN DESCRIPTION:
MDW T 110 2.0
END DESCRIPTION:
XS GIS Cut Line= 3
      2286906.85      7133171.24      2287068.36      7133011.56
      2287229.02      7132909.99
#Sta/Elev= 30
  4751.7  823.22  4761.2  823.31  4768.3  821.15  4782.4  818.67  4835.0  814.69
  4860.2  812.45  4881.3  809.19  4959.2  807.67  4966.2  806.62  4973.3  803.42
  4976.4  795.50  4988.3  795.86  4994.2  797.42  5009.5  795.60  5015.4  796.61
  5024.8  795.56  5030.7  797.18  5036.7  795.17  5037.0  794.67  5040.7  795.17
  5045.9  796.54  5051.9  807.47  5061.2  807.76  5067.1  809.59  5109.7  812.88
  5124.8  816.11  5146.0  823.65  5155.3  828.05  5165.9  831.11  5168.9  831.11
#Mann=4,-1,0
  4751.7    0.05       0  4835.0    0.12       0  5036.7    0.07       0
  5040.7    0.12       0
Bank Sta=5036.7,5040.7
Exp/Cntr=0.3,0.1

Type RM Length L Ch R = 1,809,559,559,559
BEGIN DESCRIPTION:
MDW T 110 1.0
END DESCRIPTION:
XS GIS Cut Line= 3
      2287034.92      7133321.29      2287265.77      7133146.45
      2287351.64      7133013.45
#Sta/Elev= 30
  4714.4  817.95  4725.3  817.64  4739.9  815.96  4760.7  810.76  4786.6  807.66
  4804.3  805.70  4839.7  803.60  4882.6  803.07  4975.0  803.46  4983.0  802.86
  4989.5  801.25  4995.8  793.50  5000.9  792.49  5001.1  791.99  5004.6  791.99
  5004.9  792.49  5024.3  803.56  5039.5  805.60  5060.6  807.23  5075.8  809.43
  5091.0  816.85  5096.9  816.97  5106.1  821.07  5112.1  821.88  5118.8  825.82
  5127.3  829.59  5133.2  830.11  5142.4  832.36  5148.4  832.30  5162.3  834.24
#Mann=4,-1,0
  4714.4    0.05       0  4786.6    0.12       0  5000.9    0.07       0
  5004.9    0.12       0
Bank Sta=5000.9,5004.9
Exp/Cntr=0.3,0.1

Type RM Length L Ch R = 1,250,0,0,0
BEGIN DESCRIPTION:
MDW T 110 0.5
END DESCRIPTION:
XS GIS Cut Line= 3
      2287089.06      7133347.88      2287649.08      7133304.04
      2287737.96      7132848.77
#Sta/Elev= 30
  4442.3  816.45  4472.3  811.78  4478.3  808.47  4483.3  808.14  4492.4  805.41
  4512.5  802.64  4532.5  801.28  4662.9  799.22  4793.3  799.59  4853.5  798.51
  4943.8  795.20  4983.9  788.25  4995.3  788.59  5016.3  786.99  5016.6  786.49
  5020.3  786.99  5026.6  788.10  5038.7  793.91  5201.7  803.79  5252.7  808.66
  5303.6  811.81  5341.1  816.39  5346.2  814.85  5374.9  820.34  5392.6  824.98
  5395.9  824.96  5405.5  827.34  5415.7  828.18  5436.1  831.89  5467.9  832.63
#Mann=4,-1,0
  4442.3    0.12       0  5016.3    0.07       0  5020.3    0.12       0
  5395.9    0.05       0
Bank Sta=5016.3,5020.3
Exp/Cntr=0.3,0.1

Chan Stop Cuts=-1