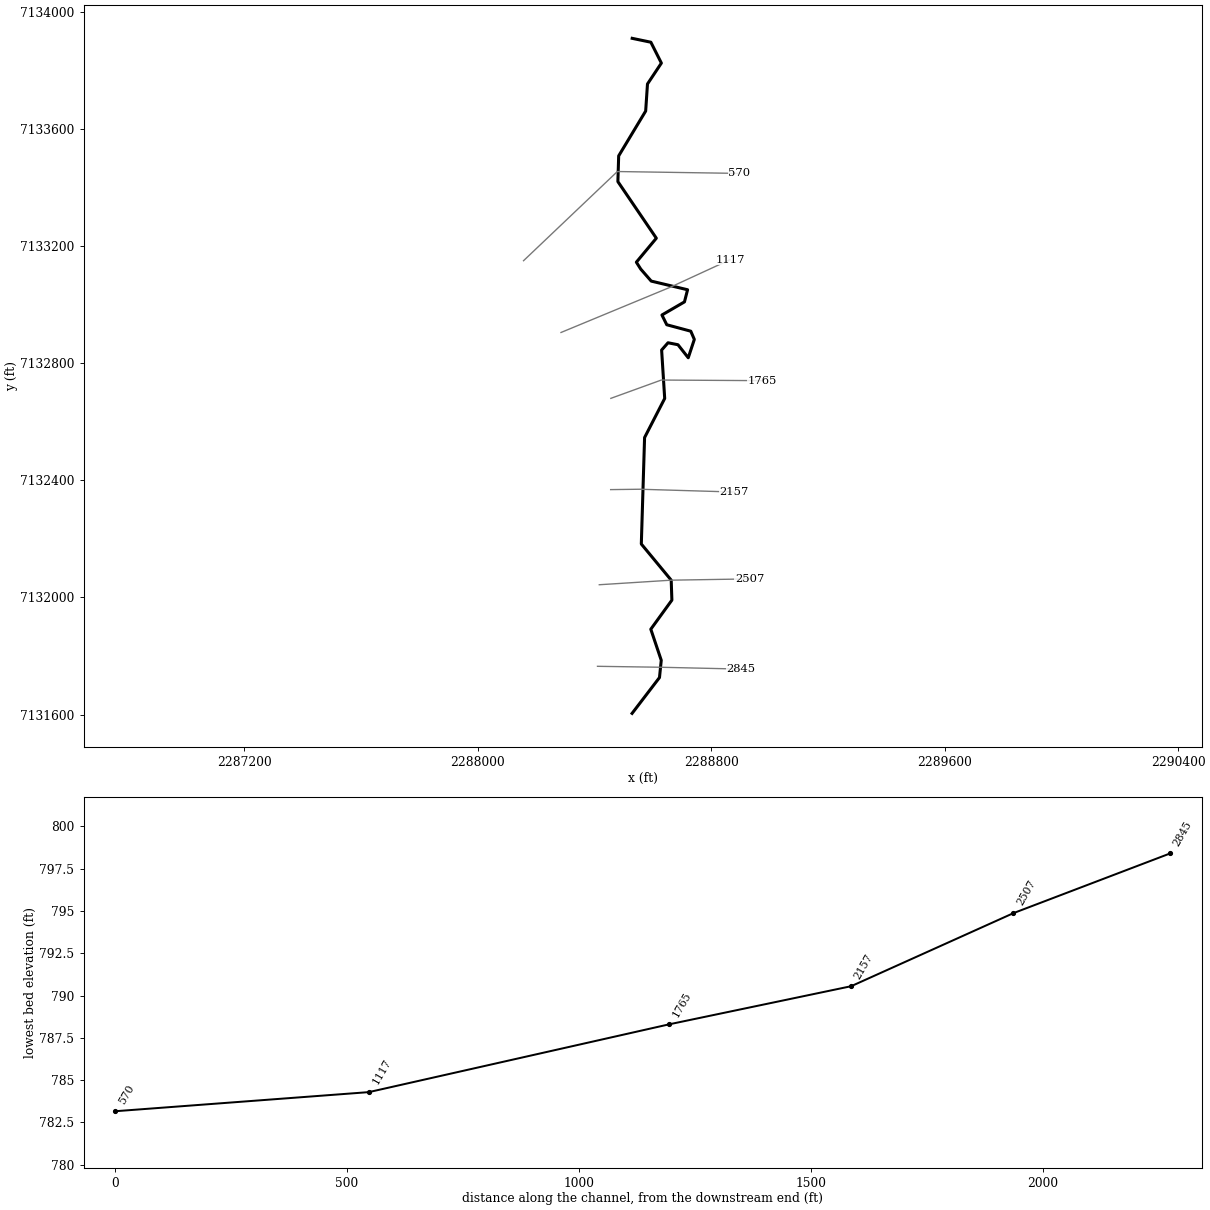
--- MDW T 111.prj (project) ---

Proj Title=MDW T 111 Base Level Engineering
Current Plan=p01
Default Exp/Contr=0.3,0.1
English Units
Geom File=g01
Flow File=f01
Plan File=p01
BEGIN DESCRIPTION:
MDW T 111
END DESCRIPTION:

--- MDW T 111.p01 (plan) ---

Plan Title=Multiple Run
Short Identifier=Multiple
Geom File=g01
Flow File=f01
Subcritical Flow
K Sum by GR= 0
Std Step Tol= 0.01
Critical Tol= 0.01
Num of Std Step Trials= 20
Max Error Tol= 0.3
Flow Tol Ratio= 0.001
Split Flow NTrial= 30
Split Flow Tol= 0.02
Split Flow Ratio= 0.02
Log Output Level= 0
Friction Slope Method= 1
Unsteady Friction Slope Method= 2
Unsteady Bridges Friction Slope Method= 1
Parabolic Critical Depth
Global Vel Dist=  1 , 1 , 1
Global Log Level= 0
CheckData=True
Encroach Param= -1, 0, 0, 0
BEGIN DESCRIPTION:
Multiple Run
END DESCRIPTION:

--- MDW T 111.f01 (steady flow) ---

Flow Title=Multiple
Number of Profiles=7
Profile Names=10-year,25-year,50-year,1pct_min,100-year,1pct_plu,500-year
River Rch & RM= MDW T 111,Reach-1,2845
     548     752     921     561    1119    2234    1656
Boundary for River Rch & Prof#=MDW T 111,Reach-1,1
Up Type=0
Dn Type=3
Dn Slope=0.005
Boundary for River Rch & Prof#=MDW T 111,Reach-1,2
Up Type=0
Dn Type=3
Dn Slope=0.005
Boundary for River Rch & Prof#=MDW T 111,Reach-1,3
Up Type=0
Dn Type=3
Dn Slope=0.005
Boundary for River Rch & Prof#=MDW T 111,Reach-1,4
Up Type=0
Dn Type=3
Dn Slope=0.005
Boundary for River Rch & Prof#=MDW T 111,Reach-1,5
Up Type=0
Dn Type=3
Dn Slope=0.005
Boundary for River Rch & Prof#=MDW T 111,Reach-1,6
Up Type=0
Dn Type=3
Dn Slope=0.005
Boundary for River Rch & Prof#=MDW T 111,Reach-1,7
Up Type=0
Dn Type=3
Dn Slope=0.005

--- MDW T 111.g01 (geometry) ---

Geom Title=Existing Conditions

River Reach=MDW T 111,Reach-1
Reach XY= 30
      2288528.61      7131603.86      2288622.51      7131726.22
      2288628.58      7131785.26      2288592.76      7131891.41
      2288665.01      7131990.72      2288662.67      7132059.01
      2288560.26      7132182.46      2288571.44      7132546.11
      2288640.38      7132679.72      2288629.86      7132845.10
      2288651.80      7132869.97      2288685.90      7132863.27
      2288721.11      7132818.72      2288741.94      7132881.43
      2288729.82      7132909.48      2288647.49      7132931.54
      2288630.88      7132964.83      2288708.11      7133009.61
      2288718.80      7133051.09      2288594.22      7133080.65
      2288558.30      7133121.67      2288543.27      7133145.29
      2288611.72      7133227.21      2288479.94      7133420.48
      2288482.67      7133508.41      2288575.17      7133661.58
      2288581.38      7133754.04      2288629.01      7133825.45
      2288592.97      7133896.73      2288529.00      7133910.00

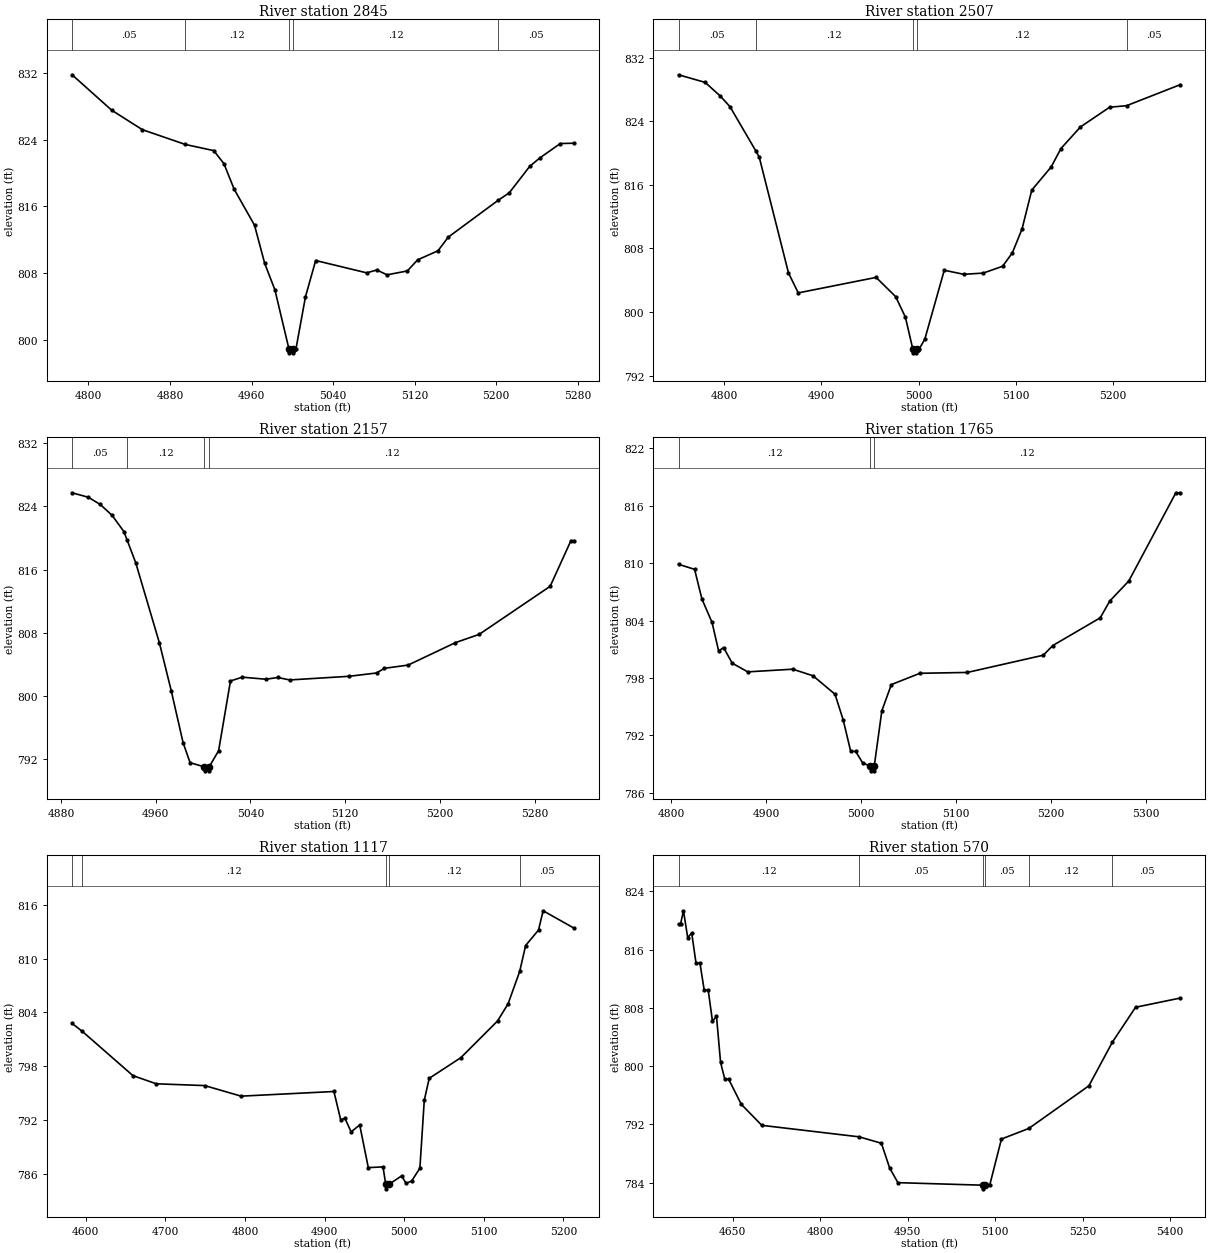
Type RM Length L Ch R = 1,2845,338,338,338
BEGIN DESCRIPTION:
MDW T 111 5.0
END DESCRIPTION:
XS GIS Cut Line= 3
      2288410.06      7131764.66      2288625.44      7131761.47
      2288902.26      7131755.11
#Sta/Elev= 30
  4783.9  831.80  4822.8  827.54  4852.8  825.21  4895.0  823.43  4922.9  822.69
  4932.9  821.12  4942.9  818.06  4962.9  813.73  4972.9  809.14  4982.9  805.97
  4996.6  798.90  4996.8  798.40  5000.3  798.40  5000.6  798.90  5003.6  798.90
  5012.9  805.14  5022.9  809.49  5072.9  808.01  5082.9  808.35  5092.9  807.77
  5112.9  808.24  5122.9  809.57  5142.9  810.66  5152.9  812.29  5201.9  816.72
  5212.9  817.63  5232.9  820.80  5242.9  821.82  5262.9  823.54  5276.2  823.58
#Mann=5,-1,0
  4783.9    0.05       0  4895.0    0.12       0  4996.6    0.07       0
  5000.6    0.12       0  5201.9    0.05       0
Bank Sta=4996.6,5000.6
Exp/Cntr=0.3,0.1

Type RM Length L Ch R = 1,2507,350,350,350
BEGIN DESCRIPTION:
MDW T 111 4.0
END DESCRIPTION:
XS GIS Cut Line= 3
      2288416.16      7132043.31      2288663.24      7132058.93
      2288931.74      7132063.27
#Sta/Elev= 30
  4753.0  829.85  4780.4  828.89  4795.9  827.18  4805.9  825.84  4832.3  820.31
  4836.0  819.49  4866.1  804.92  4876.1  802.41  4956.2  804.36  4976.3  801.94
  4986.3  799.37  4993.9  795.37  4994.2  794.87  4997.7  794.87  4997.9  795.37
  5000.6  795.37  5006.3  796.59  5026.3  805.26  5046.3  804.75  5066.3  804.90
  5086.3  805.76  5096.3  807.44  5106.3  810.45  5116.3  815.34  5136.3  818.26
  5146.3  820.57  5166.3  823.28  5196.4  825.77  5213.8  825.96  5269.1  828.61
#Mann=5,-1,0
  4753.0    0.05       0  4832.3    0.12       0  4993.9    0.07       0
  4997.9    0.12       0  5213.8    0.05       0
Bank Sta=4993.9,4997.9
Exp/Cntr=0.3,0.1

Type RM Length L Ch R = 1,2157,392,392,392
BEGIN DESCRIPTION:
MDW T 111 3.0
END DESCRIPTION:
XS GIS Cut Line= 3
      2288455.21      7132368.30      2288555.86      7132369.60
      2288878.96      7132360.00
#Sta/Elev= 30
  4889.3  825.70  4903.1  825.13  4913.1  824.22  4923.1  822.85  4933.1  820.79
  4935.9  819.68  4943.1  816.84  4963.1  806.71  4973.1  800.66  4983.1  794.10
  4989.0  791.58  5001.1  791.05  5001.4  790.55  5004.9  790.55  5005.1  791.05
  5013.1  793.09  5023.1  801.91  5033.1  802.39  5053.1  802.13  5063.1  802.35
  5073.1  802.04  5123.2  802.50  5146.5  802.92  5153.2  803.51  5173.2  803.92
  5213.2  806.76  5233.2  807.80  5293.2  813.88  5310.7  819.64  5313.2  819.64
#Mann=4,-1,0
  4889.3    0.05       0  4935.9    0.12       0  5001.1    0.07       0
  5005.1    0.12       0
Bank Sta=5001.1,5005.1
Exp/Cntr=0.3,0.1

Type RM Length L Ch R = 1,1765,648,648,648
BEGIN DESCRIPTION:
MDW T 111 2.0
END DESCRIPTION:
XS GIS Cut Line= 3
      2288455.84      7132680.09      2288628.75      7132742.62
      2288973.27      7132740.53
#Sta/Elev= 30
  4807.7  809.88  4824.6  809.35  4832.3  806.26  4843.0  803.80  4849.9  800.83
  4855.2  801.17  4864.2  799.55  4880.6  798.64  4928.0  798.92  4949.3  798.23
  4972.5  796.30  4981.2  793.58  4989.0  790.33  4994.2  790.33  5001.8  789.10
  5009.8  788.80  5010.1  788.30  5013.6  788.30  5013.8  788.80  5021.8  794.58
  5031.8  797.31  5061.8  798.49  5111.8  798.58  5191.8  800.38  5201.8  801.39
  5251.8  804.29  5261.8  806.04  5281.8  808.13  5331.4  817.35  5336.1  817.35
#Mann=3,-1,0
  4807.7    0.12       0  5009.8    0.07       0  5013.8    0.12       0
Bank Sta=5009.8,5013.8
Exp/Cntr=0.3,0.1

Type RM Length L Ch R = 1,1117,547,547,547
BEGIN DESCRIPTION:
MDW T 111 1.0
END DESCRIPTION:
XS GIS Cut Line= 3
      2288285.01      7132905.10      2288659.02      7133059.50
      2288864.11      7133153.67
#Sta/Elev= 30
  4582.9  802.76  4595.8  801.87  4659.4  796.93  4688.7  796.02  4749.5  795.82
  4795.2  794.64  4911.8  795.16  4920.3  792.01  4925.7  792.16  4933.4  790.65
  4944.2  791.42  4955.0  786.66  4973.5  786.74  4976.9  784.79  4977.2  784.29
  4980.9  784.79  4996.9  785.74  5002.4  784.90  5009.5  785.17  5019.8  786.60
  5025.3  794.17  5031.5  796.63  5071.3  798.94  5117.3  803.03  5130.6  804.95
  5145.2  808.58  5152.6  811.46  5168.8  813.19  5174.6  815.34  5213.2  813.41
#Mann=5,-1,0
  4582.9    0.05       0  4595.8    0.12       0  4976.9    0.07       0
  4980.9    0.12       0  5145.2    0.05       0
Bank Sta=4976.9,4980.9
Exp/Cntr=0.3,0.1

Type RM Length L Ch R = 1,570,0,0,0
BEGIN DESCRIPTION:
MDW T 111 0.5
END DESCRIPTION:
XS GIS Cut Line= 3
      2288156.65      7133150.33      2288478.15      7133454.96
      2288895.80      7133448.54
#Sta/Elev= 30
  4557.1  819.50  4560.5  819.50  4565.6  821.34  4572.8  817.66  4579.7  818.27
  4587.0  814.20  4593.9  814.13  4601.1  810.46  4608.0  810.43  4615.3  806.18
  4622.2  806.85  4629.2  800.52  4636.3  798.26  4643.2  798.19  4664.7  794.77
  4699.9  791.88  4866.9  790.30  4905.0  789.42  4919.1  786.04  4933.3  784.01
  5078.9  783.66  5079.1  783.16  5082.9  783.66  5090.9  783.70  5110.9  790.00
  5157.8  791.45  5260.9  797.31  5301.3  803.32  5340.9  808.09  5417.7  809.36
#Mann=6,-1,0
  4557.1    0.12       0  4866.9    0.05       0  5078.9   0.033       0
  5082.9    0.05       0  5157.8    0.12       0  5301.3    0.05       0
Bank Sta=5078.9,5082.9
Exp/Cntr=0.3,0.1

Chan Stop Cuts=-1