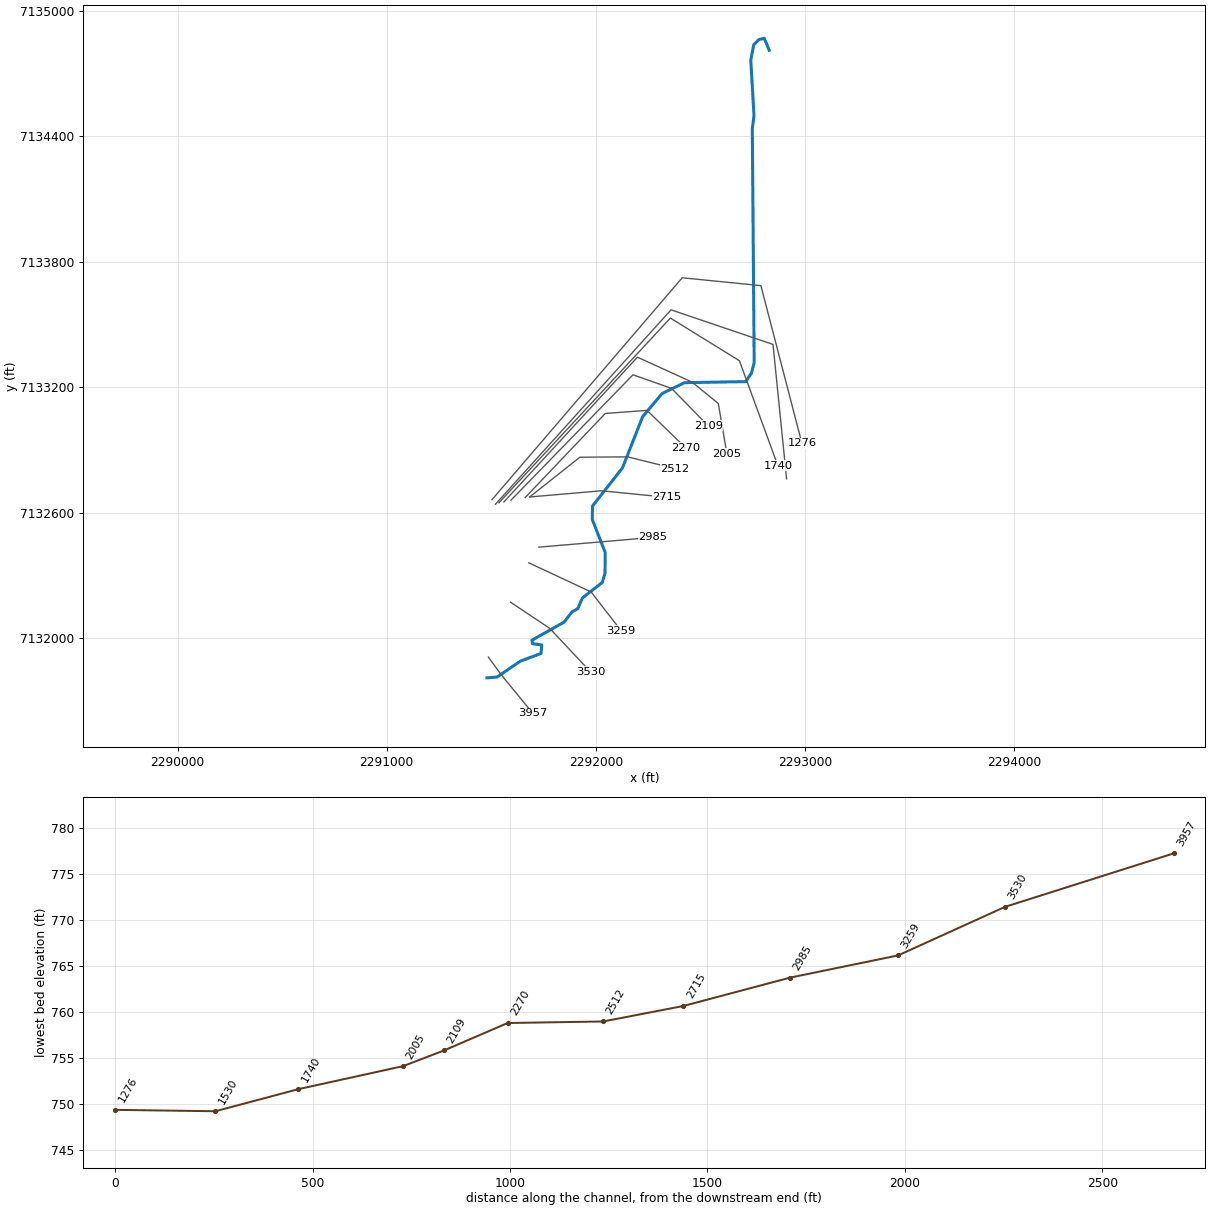
--- MDW T 112.prj (project) ---

Proj Title=MDW T 112 Base Level Engineering
Current Plan=p01
Default Exp/Contr=0.3,0.1
English Units
Geom File=g01
Flow File=f01
Plan File=p01
Y Axis Title=Elevation
X Axis Title(PF)=Main Channel Distance
X Axis Title(XS)=Station
BEGIN DESCRIPTION:
MDW T 112
END DESCRIPTION:
DSS Export Rating Curves= 0
DSS Export Rating Curve Sorted= 0
DSS Export Volume Flow Curves= 0
DXF OffsetX= 0
DXF OffsetY= 0
DXF ScaleX= 1
DXF ScaleY= 10

--- MDW T 112.p01 (plan) ---

Plan Title=Multiple Run
Short Identifier=Multiple
Geom File=g01
Flow File=f01
Subcritical Flow
K Sum by GR= 0
Std Step Tol= 0.01
Critical Tol= 0.01
Num of Std Step Trials= 20
Max Error Tol= 0.3
Flow Tol Ratio= 0.001
Split Flow NTrial= 30
Split Flow Tol= 0.02
Split Flow Ratio= 0.02
Log Output Level= 0
Friction Slope Method= 1
Unsteady Friction Slope Method= 2
Unsteady Bridges Friction Slope Method= 1
Parabolic Critical Depth
Global Vel Dist=  1 , 1 , 1
Global Log Level= 0
CheckData=True
Encroach Param= -1, 0, 0, 0
BEGIN DESCRIPTION:
Multiple Run
END DESCRIPTION:

--- MDW T 112.f01 (steady flow) ---

Flow Title=Multiple
Number of Profiles=7
Profile Names=10-year,25-year,50-year,1pct_min,100-year,1pct_plu,500-year
River Rch & RM= MDW T 112,Reach-1,3957
     404     545     661     400     798    1592    1162
Boundary for River Rch & Prof#=MDW T 112,Reach-1,1
Up Type=0
Dn Type=3
Dn Slope=0.005
Boundary for River Rch & Prof#=MDW T 112,Reach-1,2
Up Type=0
Dn Type=3
Dn Slope=0.005
Boundary for River Rch & Prof#=MDW T 112,Reach-1,3
Up Type=0
Dn Type=3
Dn Slope=0.005
Boundary for River Rch & Prof#=MDW T 112,Reach-1,4
Up Type=0
Dn Type=3
Dn Slope=0.005
Boundary for River Rch & Prof#=MDW T 112,Reach-1,5
Up Type=0
Dn Type=3
Dn Slope=0.005
Boundary for River Rch & Prof#=MDW T 112,Reach-1,6
Up Type=0
Dn Type=3
Dn Slope=0.005
Boundary for River Rch & Prof#=MDW T 112,Reach-1,7
Up Type=0
Dn Type=3
Dn Slope=0.005

--- MDW T 112.g01 (geometry) ---

Geom Title=Existing Conditions

River Reach=MDW T 112,Reach-1
Reach XY= 30
      2291479.00      7131810.00      2291527.51      7131813.60
      2291637.66      7131888.99      2291737.76      7131926.46
      2291741.37      7131967.14      2291696.59      7131973.27
      2291694.42      7131989.98      2291848.28      7132076.41
      2291885.47      7132124.61      2291913.94      7132141.03
      2291936.03      7132192.07      2292030.74      7132265.95
      2292043.86      7132310.31      2292044.87      7132408.96
      2291983.00      7132566.74      2291984.35      7132631.91
      2292127.21      7132813.28      2292223.76      7133058.26
      2292316.94      7133169.32      2292424.68      7133220.97
      2292716.83      7133225.99      2292744.35      7133267.14
      2292757.23      7133317.13      2292748.26      7134436.30
      2292756.38      7134496.64      2292740.89      7134762.44
      2292755.28      7134836.70      2292779.48      7134861.18
      2292805.61      7134866.99      2292829.00      7134810.00

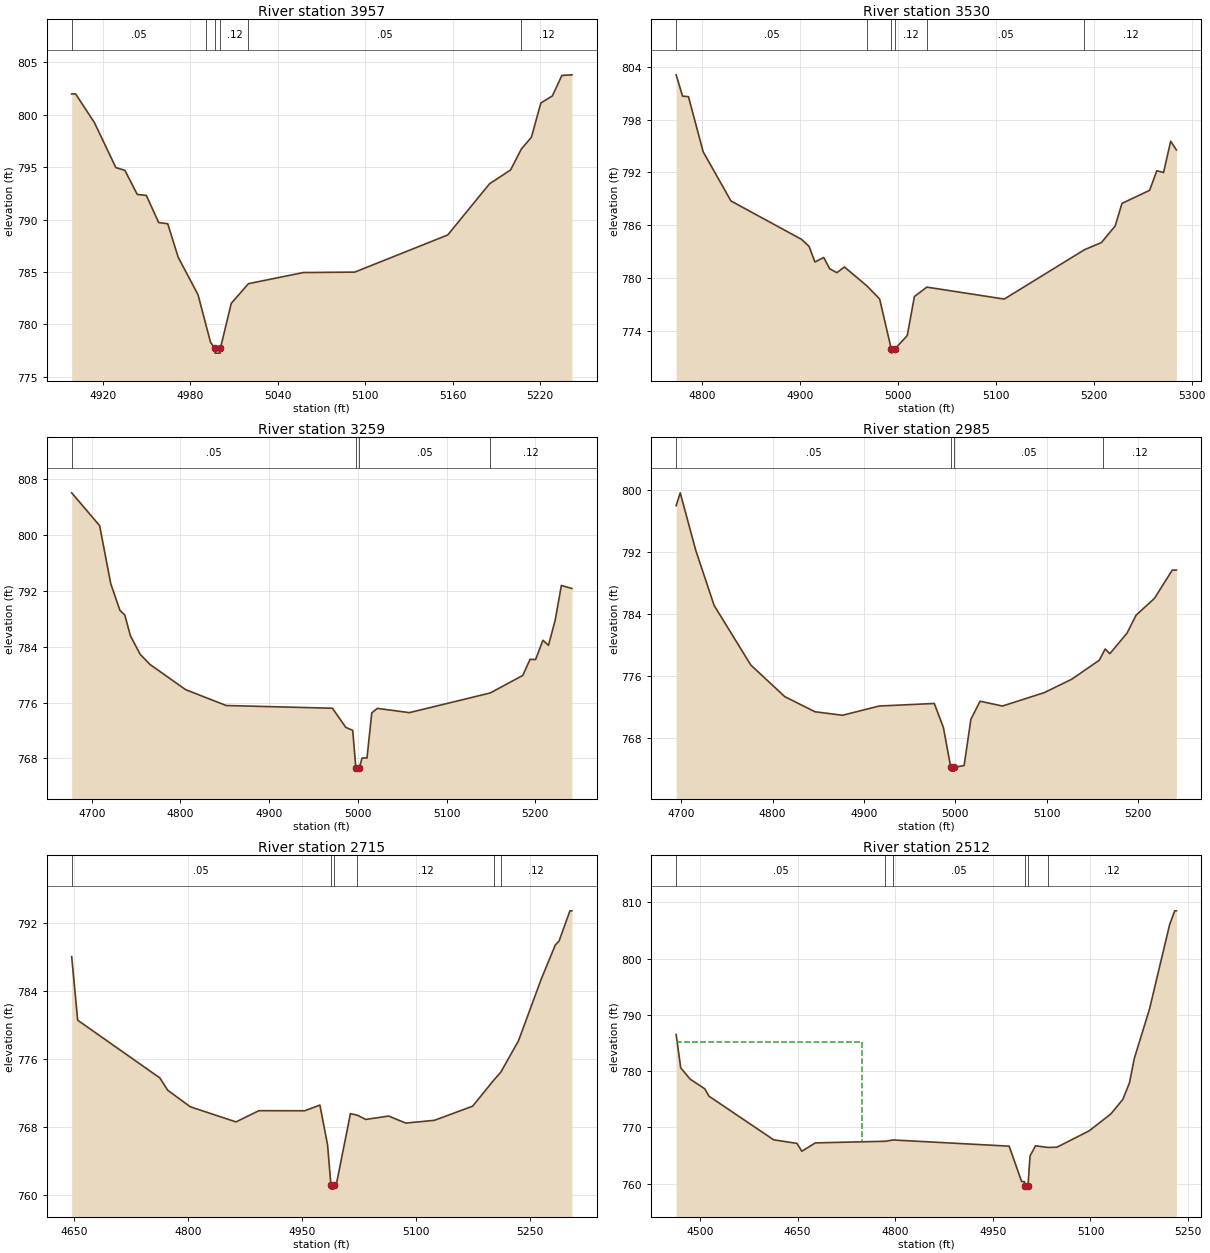
Type RM Length L Ch R = 1,3957,427,427,427
BEGIN DESCRIPTION:
MDW T 112 8.0
END DESCRIPTION:
XS GIS Cut Line= 3
      2291486.06      7131909.27      2291545.49      7131827.11
      2291698.78      7131640.11
#Sta/Elev= 30
  4898.6  801.97  4901.3  801.97  4914.2  799.24  4928.9  794.95  4935.1  794.69
  4943.6  792.39  4949.8  792.30  4958.3  789.71  4964.5  789.60  4971.7  786.40
  4985.3  782.83  4991.0  779.82  4993.9  778.29  4996.7  777.77  4997.0  777.27
  5000.5  777.27  5000.7  777.77  5008.1  782.02  5019.9  783.89  5057.6  784.95
  5092.8  784.99  5156.6  788.53  5185.3  793.41  5199.7  794.72  5207.1  796.72
  5214.0  797.84  5220.5  801.11  5228.4  801.78  5234.9  803.73  5241.8  803.79
#Mann=6,-1,0
  4898.6    0.05       0  4991.0    0.12       0  4996.7    0.07       0
  5000.7    0.12       0  5019.9    0.05       0  5207.1    0.12       0
Bank Sta=4996.7,5000.7
Exp/Cntr=0.3,0.1

Type RM Length L Ch R = 1,3530,271,271,271
BEGIN DESCRIPTION:
MDW T 112 7.0
END DESCRIPTION:
XS GIS Cut Line= 3
      2291592.40      7132171.28      2291779.61      7132046.38
      2291975.24      7131837.82
#Sta/Elev= 30
  4773.4  803.08  4780.0  800.66  4786.0  800.60  4801.0  794.34  4829.4  788.75
  4901.6  784.38  4909.2  783.59  4915.2  781.81  4924.2  782.33  4930.2  781.05
  4937.6  780.60  4945.3  781.25  4968.3  779.10  4981.3  777.61  4993.1  771.96
  4993.3  771.46  4997.1  771.96  5009.5  773.46  5016.8  777.89  5029.5  778.96
  5108.6  777.60  5190.5  783.21  5207.8  784.02  5221.9  785.91  5228.8  788.47
  5257.1  789.96  5264.4  792.18  5271.3  791.98  5278.6  795.54  5284.4  794.55
#Mann=6,-1,0
  4773.4    0.05       0  4968.3    0.12       0  4993.1    0.07       0
  4997.1    0.12       0  5029.5    0.05       0  5190.5    0.12       0
Bank Sta=4993.1,4997.1
Exp/Cntr=0.3,0.1

Type RM Length L Ch R = 1,3259,274,274,274
BEGIN DESCRIPTION:
MDW T 112 6.0
END DESCRIPTION:
XS GIS Cut Line= 3
      2291679.00      7132360.00      2291977.36      7132220.66
      2292120.92      7132035.11
#Sta/Elev= 30
  4677.4  806.05  4708.9  801.35  4721.5  793.01  4731.8  789.21  4737.3  788.55
  4743.6  785.57  4754.6  782.92  4765.7  781.46  4805.9  777.85  4851.6  775.58
  4971.3  775.19  4986.4  772.45  4994.2  772.02  4997.7  766.68  4998.0  766.18
  5001.7  766.68  5004.8  768.06  5010.3  768.06  5015.7  774.53  5022.0  775.17
  5058.1  774.56  5149.3  777.38  5185.9  779.89  5194.1  782.19  5200.4  782.18
  5208.6  784.93  5214.9  784.20  5222.5  787.84  5229.4  792.78  5241.3  792.35
#Mann=4,-1,0
  4677.4    0.05       0  4997.7   0.033       0  5001.7    0.05       0
  5149.3    0.12       0
Bank Sta=4997.7,5001.7
Exp/Cntr=0.3,0.1

Type RM Length L Ch R = 1,2985,270,270,270
BEGIN DESCRIPTION:
MDW T 112 5.0
END DESCRIPTION:
XS GIS Cut Line= 3
      2291727.54      7132434.79      2292039.13      7132461.19
      2292272.93      7132481.68
#Sta/Elev= 30
  4694.4  797.97  4698.9  799.63  4715.9  792.21  4736.0  785.11  4776.1  777.44
  4813.3  773.36  4846.4  771.41  4876.5  770.96  4916.6  772.15  4976.9  772.48
  4986.9  769.37  4994.9  764.26  4995.2  763.76  4998.7  763.76  4998.9  764.26
  5009.5  764.47  5017.0  770.46  5027.0  772.77  5051.5  772.15  5097.3  773.88
  5127.4  775.61  5157.5  778.06  5161.7  779.01  5163.9  779.50  5169.0  778.90
  5187.7  781.53  5197.7  783.86  5217.8  786.02  5237.3  789.67  5241.8  789.67
#Mann=4,-1,0
  4694.4    0.05       0  4994.9   0.033       0  4998.9    0.05       0
  5161.7    0.12       0
Bank Sta=4994.9,4998.9
Exp/Cntr=0.3,0.1

Type RM Length L Ch R = 1,2715,203,203,203
BEGIN DESCRIPTION:
MDW T 112 4.0
END DESCRIPTION:
XS GIS Cut Line= 3
      2291683.47      7132674.55      2292026.76      7132704.12
      2292339.07      7132673.16
#Sta/Elev= 30
  4647.2  788.04  4655.1  780.56  4763.2  773.77  4773.6  772.32  4803.3  770.37
  4863.5  768.59  4893.6  769.91  4953.9  769.90  4973.9  770.57  4984.0  765.89
  4988.4  761.18  4988.6  760.68  4992.1  760.68  4992.4  761.18  4995.4  761.18
  5014.1  769.56  5023.2  769.38  5034.2  768.88  5064.4  769.28  5086.9  768.45
  5124.7  768.78  5174.9  770.44  5202.7  773.50  5211.9  774.43  5235.2  778.12
  5265.3  785.41  5283.7  789.41  5288.7  789.88  5303.0  793.43  5305.6  793.43
#Mann=6,-1,0
  4647.2    0.05       0  4988.4   0.033       0  4992.4    0.05       0
  5023.2    0.12       0  5202.7    0.05       0  5211.9    0.12       0
Bank Sta=4988.4,4992.4
Exp/Cntr=0.3,0.1

Type RM Length L Ch R = 1,2512,242,242,242
BEGIN DESCRIPTION:
MDW T 112 3.0
END DESCRIPTION:
XS GIS Cut Line= 4
      2291683.45      7132674.53      2291923.57      7132864.55
      2292152.32      7132866.31      2292378.96      7132810.01
#Sta/Elev= 30
  4463.5  786.49  4470.6  780.56  4485.0  778.56  4507.5  776.84  4513.9  775.53
  4613.3  767.77  4649.1  767.13  4656.6  765.74  4677.4  767.22  4785.0  767.51
  4796.8  767.74  4975.1  766.64  4994.3  760.34  4998.5  760.34  5000.0  759.50
  5000.3  759.00  5004.0  759.50  5007.2  764.92  5015.7  766.70  5034.7  766.41
  5048.5  766.45  5098.1  769.37  5131.2  772.35  5149.6  774.93  5159.9  777.88
  5167.4  782.24  5190.8  791.05  5221.7  806.05  5229.5  808.48  5232.0  808.48
#Mann=6,-1,0
  4463.5    0.05       0  4785.0    0.12       0  4796.8    0.05       0
  5000.0   0.033       0  5004.0    0.05       0  5034.7    0.12       0
#XS Ineff=2,0
    0.00 4749.30  785.22               0
Permanent Ineff=
       F       F
Bank Sta=5000,5004
Exp/Cntr=0.3,0.1

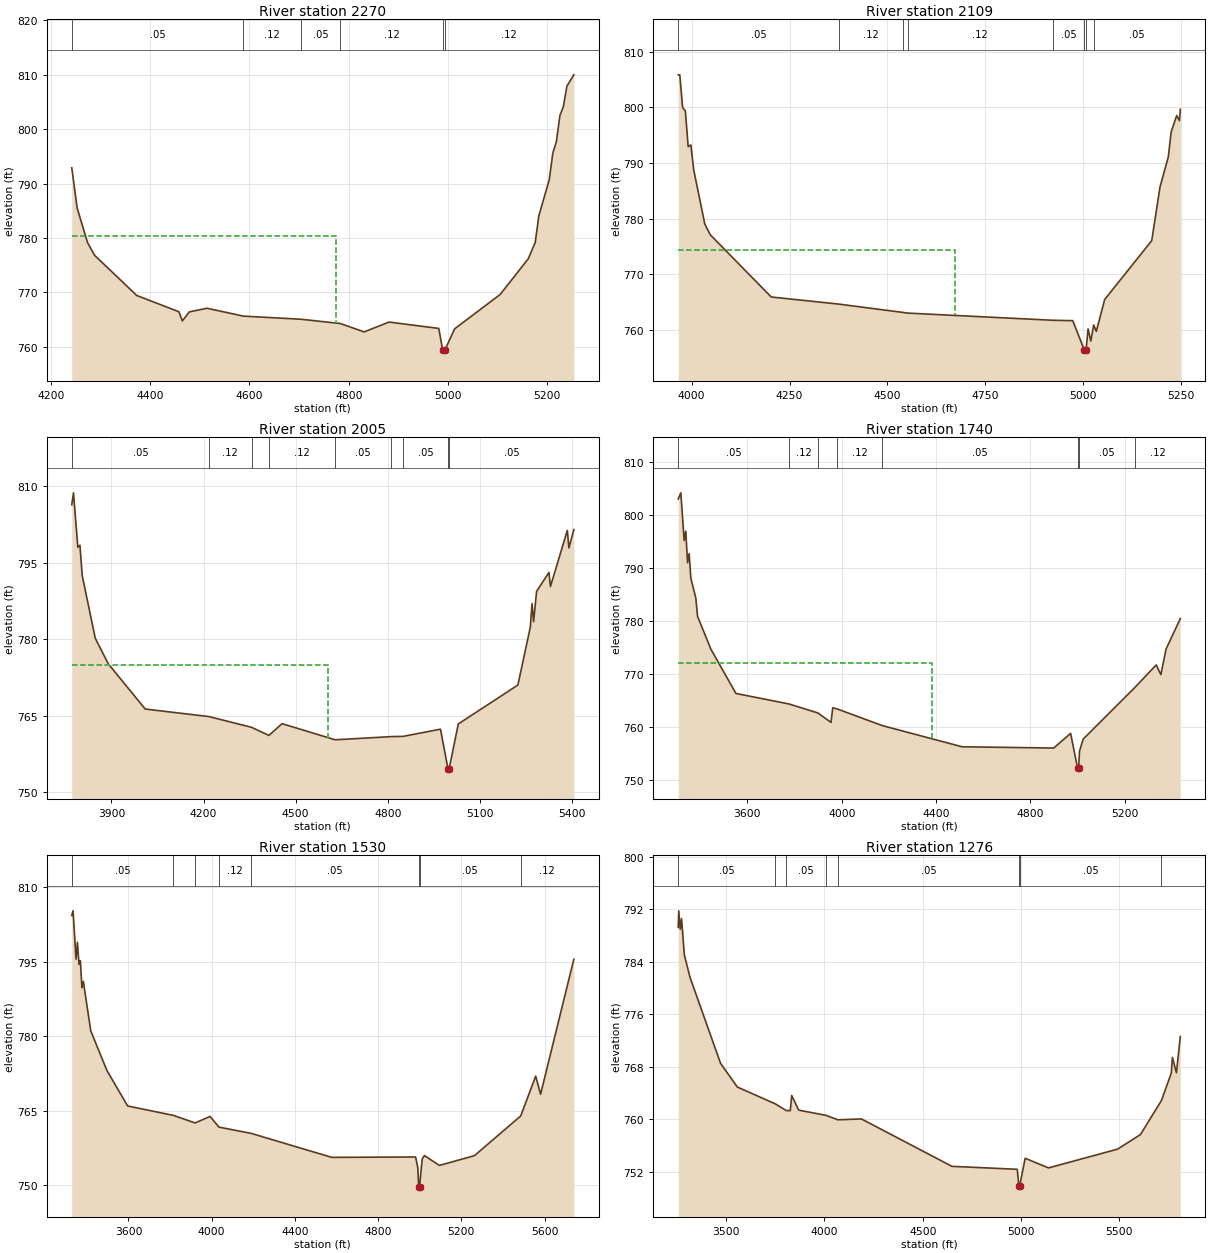
Type RM Length L Ch R = 1,2270,161,161,161
BEGIN DESCRIPTION:
MDW T 112 2.0
END DESCRIPTION:
XS GIS Cut Line= 4
      2291662.14      7132671.84      2292045.01      7133073.74
      2292244.73      7133088.44      2292428.97      7132910.03
#Sta/Elev= 30
  4241.9  792.91  4252.7  785.53  4273.7  779.14  4287.9  776.81  4372.8  769.43
  4457.8  766.44  4464.7  764.75  4478.8  766.41  4514.4  767.08  4587.9  765.63
  4703.6  765.06  4783.3  764.27  4831.1  762.73  4881.2  764.54  4981.5  763.37
  4989.5  759.33  4989.7  758.83  4993.5  759.33  5013.4  763.29  5105.2  769.61
  5161.8  776.17  5175.9  779.18  5183.1  784.04  5204.2  790.74  5211.4  795.63
  5218.4  797.66  5225.6  802.50  5232.5  804.11  5239.7  807.90  5253.7  809.99
#Mann=6,-1,0
  4241.9    0.05       0  4587.9    0.12       0  4703.6    0.05       0
  4783.3    0.12       0  4989.5    0.07       0  4993.5    0.12       0
#XS Ineff=2,0
    0.00 4774.10  780.39               0
Permanent Ineff=
       F       F
Bank Sta=4989.5,4993.5
Exp/Cntr=0.3,0.1

Type RM Length L Ch R = 1,2109,104,104,104
BEGIN DESCRIPTION:
MDW T 112 1.5
END DESCRIPTION:
XS GIS Cut Line= 4
      2291593.99      7132659.21      2292177.56      7133258.61
      2292362.23      7133193.57      2292537.11      7133014.86
#Sta/Elev= 30
  3965.8  805.83  3969.8  805.83  3977.0  799.96  3984.0  799.34  3991.2  792.94
  3998.1  793.23  4005.3  788.78  4033.6  779.05  4047.7  777.10  4203.4  765.93
  4376.3  764.65  4539.6  763.16  4551.9  763.04  4922.1  761.75  4973.5  761.68
  5003.4  756.35  5003.7  755.85  5007.4  756.35  5012.6  760.21  5019.6  758.03
  5027.0  760.90  5033.7  759.76  5055.0  765.48  5175.2  776.05  5196.4  785.71
  5217.6  791.10  5224.7  795.54  5238.9  798.51  5245.9  797.60  5248.2  799.65
#Mann=8,-1,0
  3965.8    0.05       0  4376.3    0.12       0  4539.6    0.05       0
  4551.9    0.12       0  4922.1    0.05       0  5003.4   0.033       0
  5007.4    0.05       0  5027.0    0.05       0
#XS Ineff=2,0
    0.00 4673.30  774.30               0
Permanent Ineff=
       F       F
Bank Sta=5003.4,5007.4
Exp/Cntr=0.3,0.1

Type RM Length L Ch R = 1,2005,265,265,265
BEGIN DESCRIPTION:
MDW T 112 1.0
END DESCRIPTION:
XS GIS Cut Line= 5
      2291560.24      7132650.82      2292198.85      7133342.82
      2292459.80      7133224.06      2292585.60      7133121.34
      2292626.94      7132880.32
#Sta/Elev= 30
  3770.9  806.33  3776.5  808.68  3790.7  798.01  3797.5  798.41  3804.9  792.47
  3847.4  780.18  3889.9  775.16  4010.1  766.31  4217.7  764.83  4356.3  762.73
  4413.0  761.14  4455.8  763.44  4628.8  760.28  4810.9  760.90  4850.2  760.95
  4971.9  762.36  4996.1  754.64  4996.4  754.14  5000.1  754.64  5029.9  763.39
  5223.9  771.01  5264.5  782.37  5270.0  786.98  5275.1  783.42  5284.8  789.35
  5325.0  793.08  5330.0  790.32  5385.0  801.32  5390.1  797.88  5406.2  801.48
#Mann=9,-1,0
  3770.9    0.05       0  4217.7    0.12       0  4356.3    0.05       0
  4413.0    0.12       0  4628.8    0.05       0  4810.9    0.12       0
  4850.2    0.05       0  4996.1   0.033       0  5000.1    0.05       0
#XS Ineff=2,0
    0.00 4605.30  774.88               0
Permanent Ineff=
       F       F
Bank Sta=4996.1,5000.1
Exp/Cntr=0.3,0.1

Type RM Length L Ch R = 1,1740,210,210,210
BEGIN DESCRIPTION:
Mapping XS 56aad007
END DESCRIPTION:
XS GIS Cut Line= 4
      2291536.59      7132646.81      2292356.38      7133529.86
      2292686.62      7133325.94      2292870.76      7132823.37
#Sta/Elev= 30
  3307.1  803.05  3318.1  804.21  3332.3  795.19  3339.1  796.97  3346.5  791.01
  3353.3  792.73  3360.6  788.06  3381.6  784.34  3389.0  780.87  3445.7  774.66
  3551.7  766.31  3776.2  764.33  3899.0  762.63  3954.8  760.84  3962.1  763.61
  3981.2  763.38  4172.2  760.24  4510.3  756.24  4898.6  756.00  4970.4  758.77
  5000.3  752.14  5000.6  751.64  5004.3  752.14  5008.2  755.45  5023.6  757.69
  5241.3  767.38  5333.2  771.70  5353.0  769.87  5375.1  774.71  5435.4  780.45
#Mann=8,-1,0
  3307.1    0.05       0  3776.2    0.12       0  3899.0    0.05       0
  3981.2    0.12       0  4172.2    0.05       0  5000.3   0.033       0
  5004.3    0.05       0  5241.3    0.12       0
#XS Ineff=2,0
    0.00 4382.20  772.02               0
Permanent Ineff=
       F       F
Bank Sta=5000.3,5004.3
Exp/Cntr=0.3,0.1

Type RM Length L Ch R = 1,1530,254,254,254
BEGIN DESCRIPTION:
Mapping XS b4f6e751
END DESCRIPTION:
XS GIS Cut Line= 4
      2291520.12      7132640.06      2292359.65      7133569.17
      2292847.17      7133403.92      2292912.33      7132761.00
#Sta/Elev= 30
  3327.5  804.28  3333.7  805.22  3347.9  795.51  3354.7  798.90  3362.1  794.46
  3368.9  795.19  3376.3  789.75  3383.1  791.01  3418.9  781.06  3496.6  773.09
  3596.0  765.97  3816.2  764.07  3920.5  762.55  3992.1  763.86  4035.2  761.71
  4190.2  760.45  4576.9  755.63  4980.3  755.70  4990.8  753.51  4994.9  749.74
  4995.1  749.24  4998.9  749.74  5011.9  755.29  5022.5  755.99  5094.5  754.01
  5262.8  755.97  5485.3  763.95  5557.3  771.97  5580.9  768.33  5740.7  795.49
#Mann=8,-1,0
  3327.5    0.05       0  3816.2    0.12       0  3920.5    0.05       0
  4035.2    0.12       0  4190.2    0.05       0  4994.9    0.04       0
  4998.9    0.05       0  5485.3    0.12       0
Bank Sta=4994.9,4998.9
Exp/Cntr=0.3,0.1

Type RM Length L Ch R = 1,1276,0,0,0
BEGIN DESCRIPTION:
MDW T 112 0.5
END DESCRIPTION:
XS GIS Cut Line= 4
      2291503.40      7132661.70      2292413.11      7133722.42
      2292789.33      7133684.76      2292985.54      7132930.97
#Sta/Elev= 30
  3255.9  789.26  3258.5  791.78  3266.2  788.99  3272.8  790.59  3287.1  785.05
  3315.6  781.67  3471.4  768.54  3556.7  764.94  3750.2  762.37  3805.1  761.36
  3825.9  761.34  3833.3  763.65  3868.8  761.42  4007.8  760.63  4068.5  759.95
  4188.1  760.08  4648.4  752.86  4980.8  752.41  4988.9  749.89  4989.1  749.39
  4992.9  749.89  5021.0  754.09  5139.6  752.62  5491.4  755.48  5607.7  757.71
  5714.4  762.89  5764.6  767.08  5770.0  769.45  5790.6  767.12  5810.3  772.62
#Mann=8,-1,0
  3255.9    0.05       0  3750.2    0.12       0  3805.1    0.05       0
  4007.8    0.12       0  4068.5    0.05       0  4988.9    0.04       0
  4992.9    0.05       0  5714.4    0.12       0
Bank Sta=4988.9,4992.9
Exp/Cntr=0.3,0.1

Chan Stop Cuts=-1