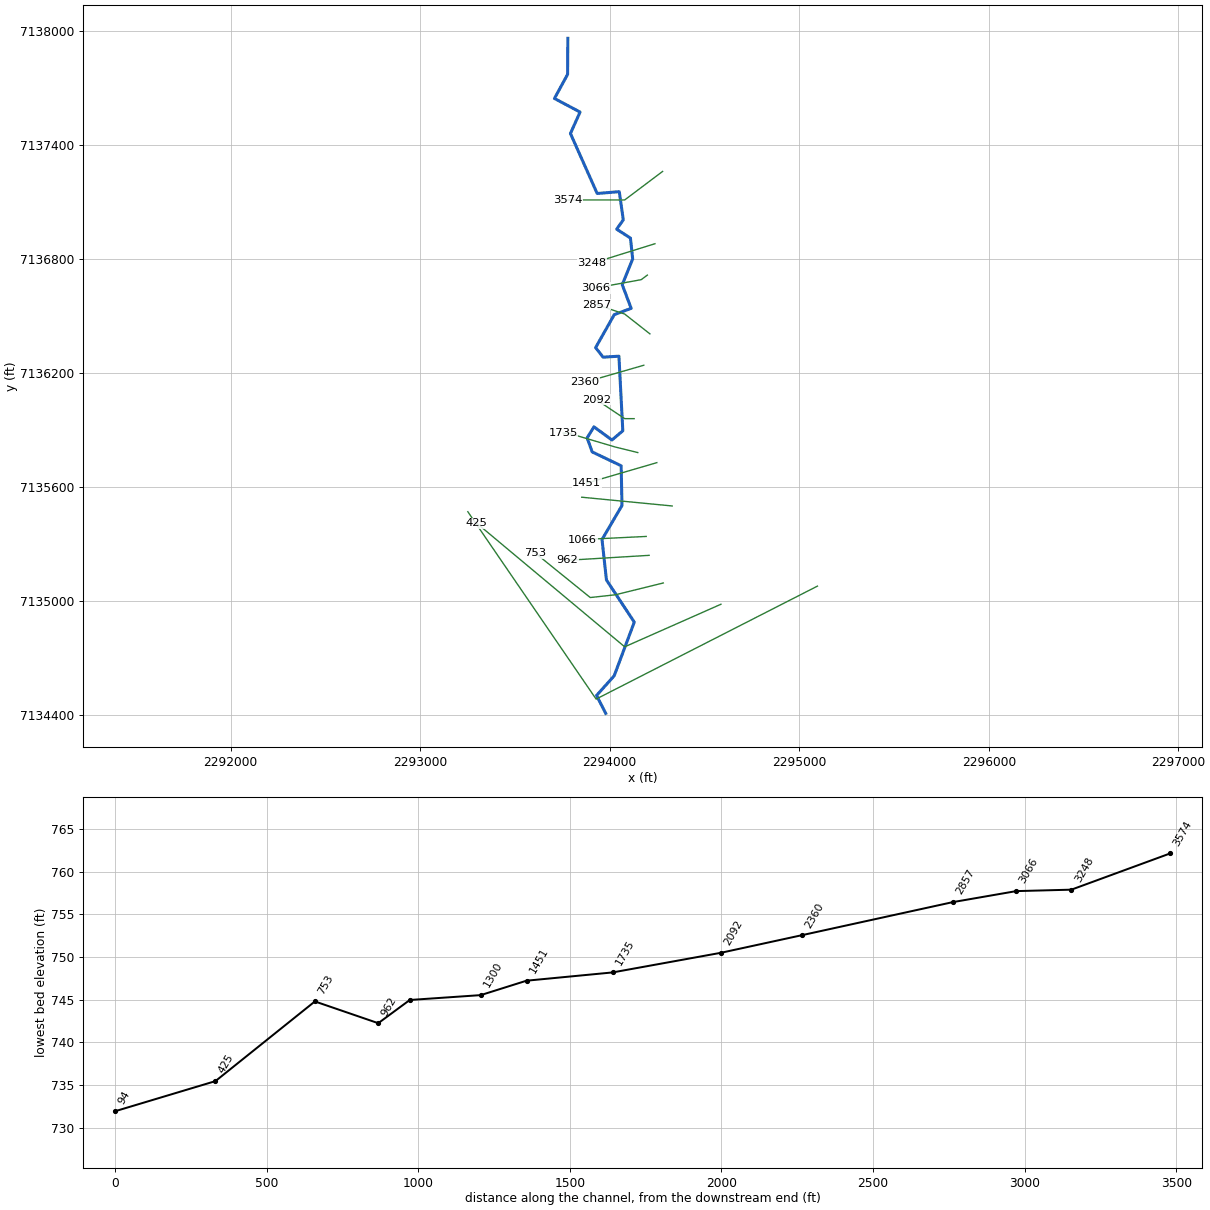
--- MDW T 113.prj (project) ---

Proj Title=MDW T 113 Base Level Engineering
Current Plan=p01
Default Exp/Contr=0.3,0.1
English Units
Geom File=g01
Flow File=f01
Plan File=p01
BEGIN DESCRIPTION:
MDW T 113
END DESCRIPTION:

--- MDW T 113.p01 (plan) ---

Plan Title=Multiple Run
Short Identifier=Multiple
Geom File=g01
Flow File=f01
Subcritical Flow
K Sum by GR= 0
Std Step Tol= 0.01
Critical Tol= 0.01
Num of Std Step Trials= 20
Max Error Tol= 0.3
Flow Tol Ratio= 0.001
Split Flow NTrial= 30
Split Flow Tol= 0.02
Split Flow Ratio= 0.02
Log Output Level= 0
Friction Slope Method= 1
Unsteady Friction Slope Method= 2
Unsteady Bridges Friction Slope Method= 1
Parabolic Critical Depth
Global Vel Dist=  1 , 1 , 1
Global Log Level= 0
CheckData=True
Encroach Param= -1, 0, 0, 0
BEGIN DESCRIPTION:
Multiple Run
END DESCRIPTION:

--- MDW T 113.f01 (steady flow) ---

Flow Title=Multiple
Number of Profiles=7
Profile Names=10-year,25-year,50-year,1pct_min,100-year,1pct_plu,500-year
River Rch & RM= MDW T 113,Reach-1,3574
     542     742     908     553    1104    2203    1632
River Rch & RM= MDW T 113,Reach-1,425
     670     930    1149     706    1408    2809    2117
Boundary for River Rch & Prof#=MDW T 113,Reach-1,1
Up Type=0
Dn Type=3
Dn Slope=0.005
Boundary for River Rch & Prof#=MDW T 113,Reach-1,2
Up Type=0
Dn Type=3
Dn Slope=0.005
Boundary for River Rch & Prof#=MDW T 113,Reach-1,3
Up Type=0
Dn Type=3
Dn Slope=0.005
Boundary for River Rch & Prof#=MDW T 113,Reach-1,4
Up Type=0
Dn Type=3
Dn Slope=0.005
Boundary for River Rch & Prof#=MDW T 113,Reach-1,5
Up Type=0
Dn Type=3
Dn Slope=0.005
Boundary for River Rch & Prof#=MDW T 113,Reach-1,6
Up Type=0
Dn Type=3
Dn Slope=0.005
Boundary for River Rch & Prof#=MDW T 113,Reach-1,7
Up Type=0
Dn Type=3
Dn Slope=0.005

--- MDW T 113.g01 (geometry) ---

Geom Title=Existing Conditions

River Reach=MDW T 113,Reach-1
Reach XY= 30
      2293779.00      7137960.00      2293777.77      7137770.49
      2293708.45      7137643.77      2293843.50      7137572.22
      2293792.80      7137459.52      2293933.86      7137144.03
      2294050.42      7137153.63      2294071.59      7137005.37
      2294036.73      7136956.35      2294109.35      7136909.53
      2294121.18      7136799.56      2294065.98      7136664.38
      2294113.20      7136540.05      2294023.98      7136506.89
      2293925.58      7136333.41      2293964.97      7136283.33
      2294048.59      7136288.38      2294069.06      7135895.94
      2294011.81      7135847.68      2293916.84      7135916.84
      2293880.89      7135858.98      2293907.57      7135784.93
      2294060.32      7135712.15      2294064.79      7135503.25
      2293959.37      7135324.09      2293982.75      7135111.55
      2294129.57      7134889.94      2294023.47      7134607.58
      2293930.55      7134504.03      2293979.00      7134410.00

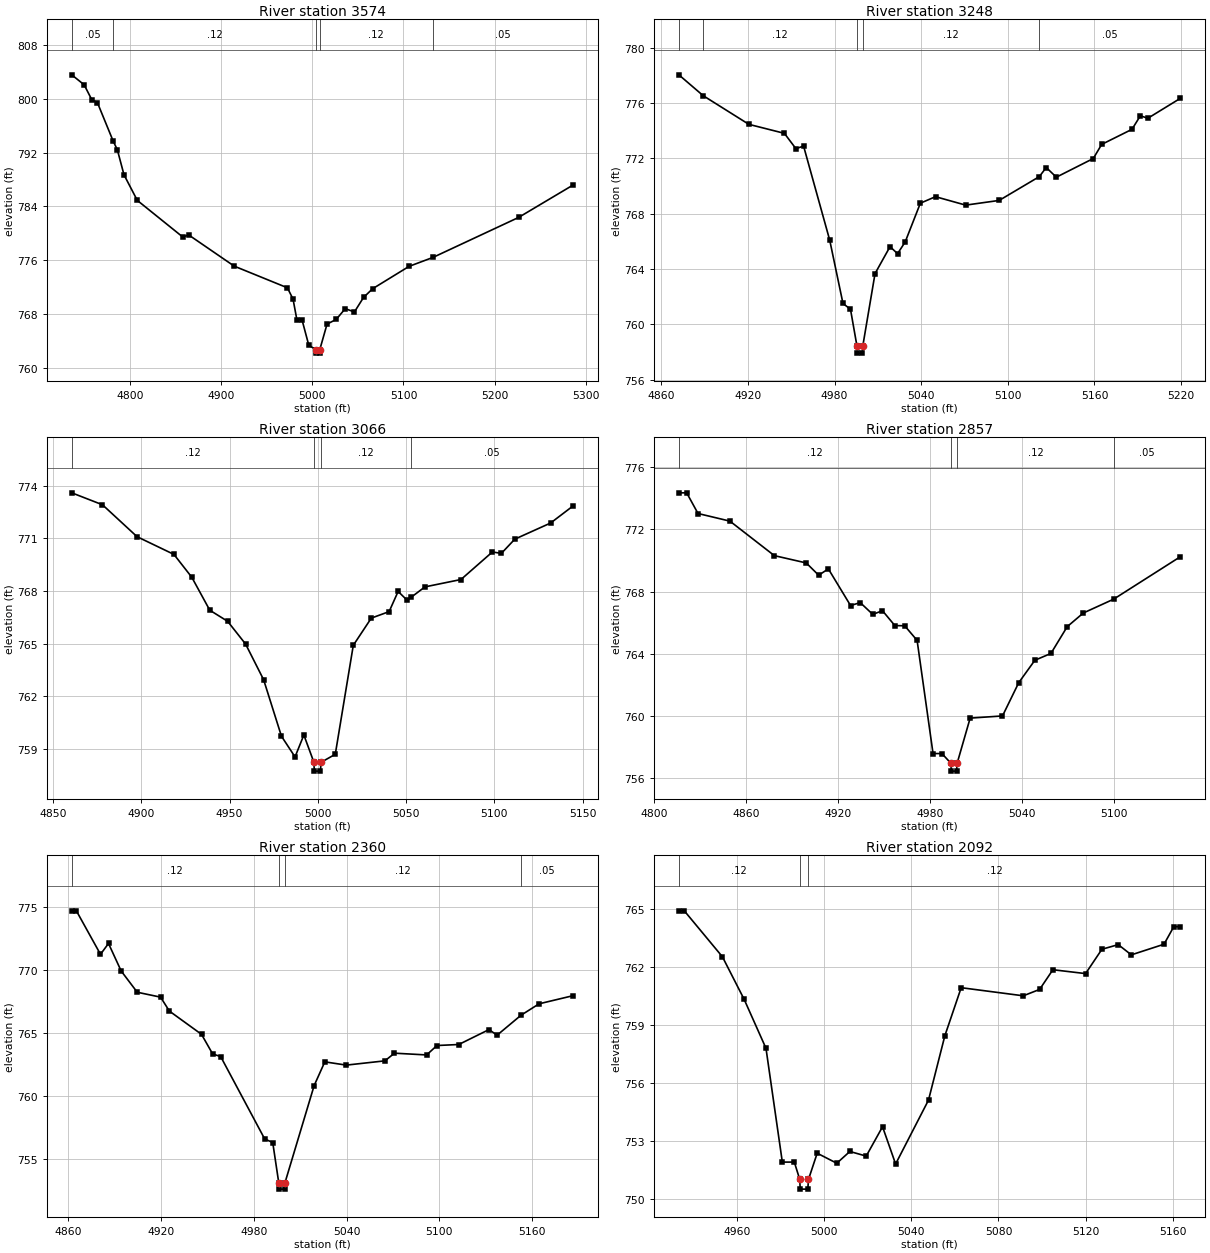
Type RM Length L Ch R = 1,3574,326,326,326
BEGIN DESCRIPTION:
MDW T 113 8.0
END DESCRIPTION:
XS GIS Cut Line= 3
      2294279.02      7137260.02      2294079.00      7137110.00
      2293779.03      7137110.00
#Sta/Elev= 30
  4736.2  803.56  4749.8  802.08  4758.1  799.88  4764.4  799.41  4781.7  793.68
  4786.2  792.42  4793.5  788.69  4808.1  784.88  4858.1  779.42  4864.4  779.75
  4914.4  775.10  4972.7  771.88  4978.9  770.20  4983.1  767.14  4988.7  767.14
  4996.2  763.32  5004.2  762.66  5004.5  762.16  5008.0  762.16  5008.2  762.66
  5016.2  766.48  5026.2  767.17  5036.2  768.78  5046.2  768.28  5056.2  770.44
  5066.2  771.74  5106.2  775.07  5132.4  776.40  5226.2  782.34  5286.2  787.18
#Mann=5,-1,0
  4736.2    0.05       0  4781.7    0.12       0  5004.2    0.07       0
  5008.2    0.12       0  5132.4    0.05       0
Bank Sta=5004.2,5008.2
Exp/Cntr=0.3,0.1

Type RM Length L Ch R = 1,3248,182,182,182
BEGIN DESCRIPTION:
Mapping XS 56fcfb4f
END DESCRIPTION:
XS GIS Cut Line= 2
      2294238.77      7136879.88      2293906.97      7136776.95
#Sta/Elev= 30
  4872.1  778.03  4889.0  776.52  4920.6  774.45  4945.2  773.80  4953.2  772.69
  4958.5  772.88  4976.6  766.08  4985.8  761.50  4991.0  761.08  4995.5  758.41
  4995.8  757.91  4999.3  757.91  4999.5  758.41  5008.0  763.66  5018.4  765.61
  5023.6  765.10  5028.9  765.95  5039.4  768.75  5049.9  769.22  5070.8  768.61
  5094.0  768.95  5121.8  770.67  5126.6  771.33  5133.6  770.63  5159.2  771.98
  5165.0  773.00  5186.0  774.09  5191.8  775.07  5197.0  774.89  5219.5  776.33
#Mann=5,-1,0
  4872.1    0.05       0  4889.0    0.12       0  4995.5    0.07       0
  4999.5    0.12       0  5121.8    0.05       0
Bank Sta=4995.5,4999.5
Exp/Cntr=0.3,0.1

Type RM Length L Ch R = 1,3066,209,209,209
BEGIN DESCRIPTION:
Mapping XS a291088b
END DESCRIPTION:
XS GIS Cut Line= 3
      2294198.59      7136714.98      2294166.08      7136690.83
      2293926.40      7136647.27
#Sta/Elev= 30
  4860.6  773.60  4878.0  772.92  4897.6  771.10  4918.5  770.09  4928.6  768.79
  4938.8  766.91  4948.9  766.28  4959.1  764.98  4969.3  762.95  4979.4  759.73
  4987.1  758.55  4992.1  759.80  4997.8  758.24  4998.0  757.74  5001.5  757.74
  5001.8  758.24  5009.9  758.70  5020.1  764.91  5030.3  766.46  5040.4  766.83
  5045.5  767.98  5050.6  767.48  5052.9  767.65  5060.7  768.24  5081.1  768.66
  5098.9  770.23  5104.0  770.15  5111.6  770.96  5131.9  771.88  5144.7  772.86
#Mann=4,-1,0
  4860.6    0.12       0  4997.8    0.07       0  5001.8    0.12       0
  5052.9    0.05       0
Bank Sta=4997.8,5001.8
Exp/Cntr=0.3,0.1

Type RM Length L Ch R = 1,2857,497,497,497
BEGIN DESCRIPTION:
MDW T 113 6.0
END DESCRIPTION:
XS GIS Cut Line= 3
      2294212.00      7136405.81      2294079.00      7136510.00
      2293928.97      7136560.01
#Sta/Elev= 30
  4816.3  774.35  4821.4  774.35  4828.8  773.02  4849.6  772.53  4878.6  770.31
  4899.4  769.84  4907.5  769.05  4913.8  769.46  4928.3  767.10  4934.6  767.29
  4942.8  766.53  4949.1  766.77  4957.2  765.81  4963.6  765.80  4971.7  764.86
  4982.1  757.58  4987.9  757.58  4993.8  756.95  4994.0  756.45  4997.5  756.45
  4997.8  756.95  5006.3  759.86  5027.4  760.00  5038.0  762.14  5048.5  763.58
  5059.0  764.02  5069.6  765.74  5080.1  766.62  5099.9  767.51  5143.4  770.24
#Mann=4,-1,0
  4816.3    0.12       0  4993.8    0.07       0  4997.8    0.12       0
  5099.9    0.05       0
Bank Sta=4993.8,4997.8
Exp/Cntr=0.3,0.1

Type RM Length L Ch R = 1,2360,268,268,268
BEGIN DESCRIPTION:
Mapping XS 31696876
END DESCRIPTION:
XS GIS Cut Line= 2
      2294179.74      7136240.77      2293867.79      7136151.03
#Sta/Elev= 30
  4862.1  774.73  4865.1  774.73  4880.7  771.27  4885.9  772.13  4894.1  769.94
  4904.5  768.25  4919.6  767.86  4925.3  766.75  4946.1  764.90  4953.3  763.34
  4958.5  763.13  4987.0  756.57  4992.2  756.29  4996.1  753.08  4996.4  752.58
  4999.9  752.58  5000.1  753.08  5019.0  760.82  5025.9  762.71  5039.8  762.45
  5064.8  762.79  5071.0  763.40  5091.8  763.26  5098.5  764.01  5112.6  764.09
  5132.2  765.28  5137.4  764.83  5152.9  766.42  5164.6  767.33  5186.7  767.98
#Mann=4,-1,0
  4862.1    0.12       0  4996.1    0.07       0  5000.1    0.12       0
  5152.9    0.05       0
Bank Sta=4996.1,5000.1
Exp/Cntr=0.3,0.1

Type RM Length L Ch R = 1,2092,357,357,357
BEGIN DESCRIPTION:
MDW T 113 4.0
END DESCRIPTION:
XS GIS Cut Line= 3
      2294128.96      7135960.00      2294079.00      7135960.00
      2293929.04      7136059.98
#Sta/Elev= 30
  4933.3  764.92  4935.8  764.92  4953.3  762.54  4963.3  760.33  4973.3  757.80
  4980.8  751.91  4986.3  751.91  4988.8  751.01  4989.0  750.51  4992.5  750.51
  4992.8  751.01  4996.8  752.37  5005.8  751.85  5011.8  752.46  5019.3  752.22
  5026.8  753.74  5032.8  751.81  5047.9  755.12  5055.4  758.45  5062.9  760.94
  5091.4  760.52  5098.9  760.85  5105.0  761.87  5120.0  761.67  5127.5  762.93
  5135.0  763.17  5141.0  762.64  5156.0  763.19  5160.5  764.10  5163.5  764.10
#Mann=3,-1,0
  4933.3    0.12       0  4988.8    0.07       0  4992.8    0.12       0
Bank Sta=4988.8,4992.8
Exp/Cntr=0.3,0.1

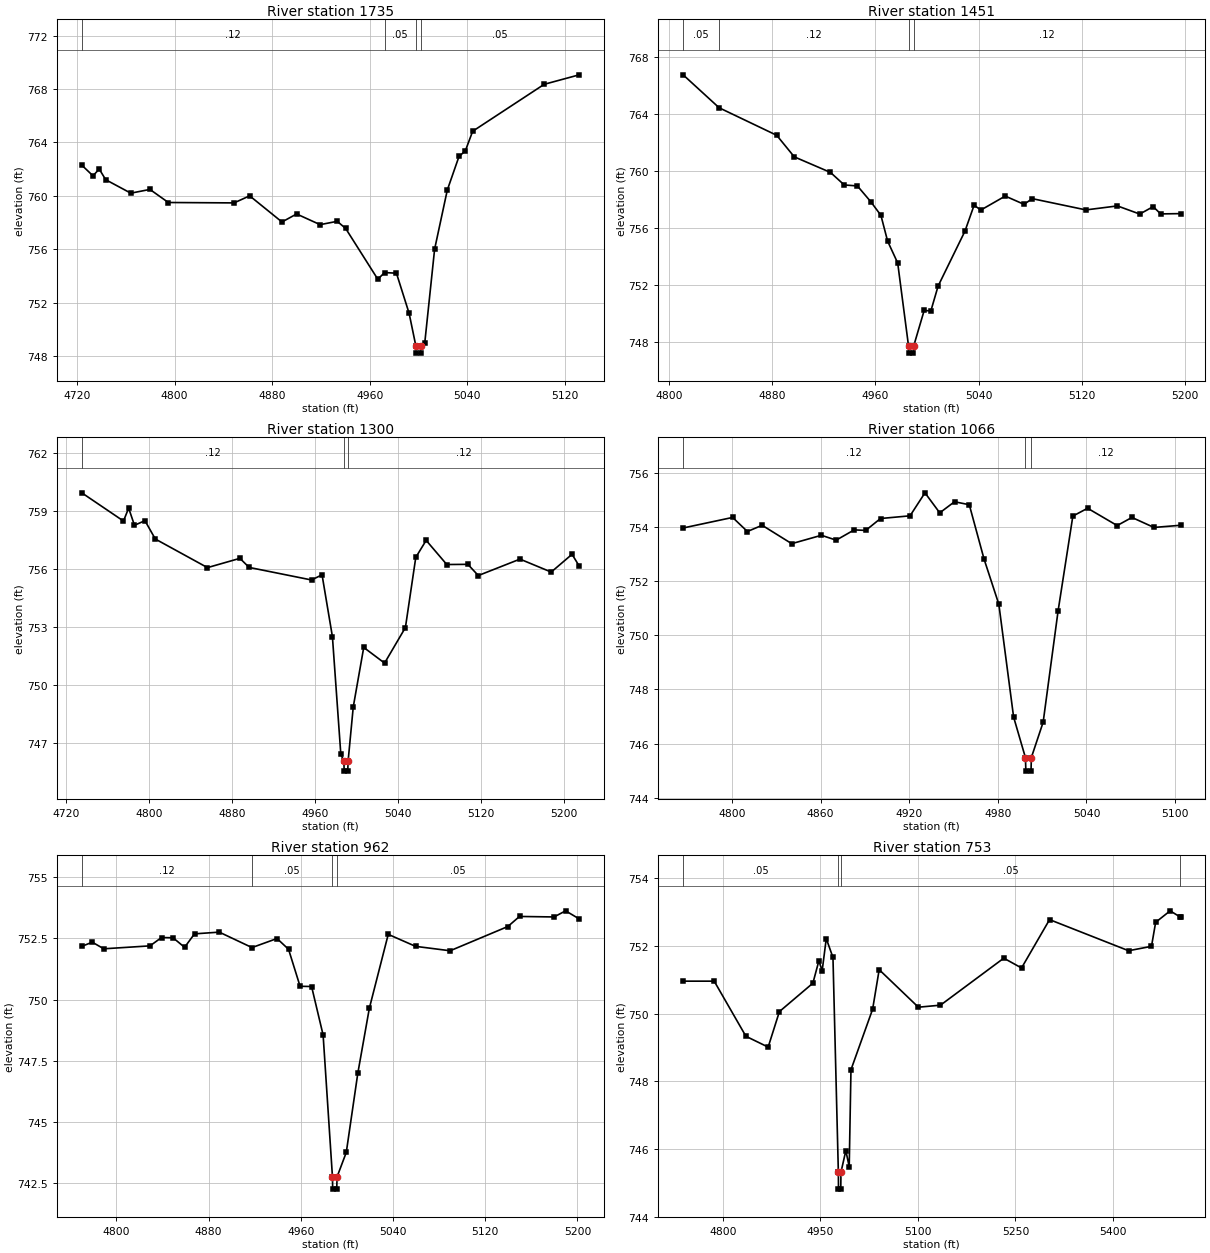
Type RM Length L Ch R = 1,1735,284,284,284
BEGIN DESCRIPTION:
Mapping XS 66b5a196
END DESCRIPTION:
XS GIS Cut Line= 4
      2294148.00      7135781.60      2294029.50      7135810.70
      2293781.40      7135883.94      2293754.11      7135883.66
#Sta/Elev= 30
  4723.9  762.30  4733.1  761.50  4738.2  762.01  4743.5  761.21  4764.1  760.20
  4779.8  760.48  4794.9  759.50  4848.8  759.47  4861.6  760.00  4888.1  758.04
  4900.1  758.64  4919.4  757.84  4933.4  758.09  4940.3  757.56  4966.7  753.75
  4972.3  754.25  4982.0  754.20  4992.4  751.19  4998.0  748.71  4998.3  748.21
  5001.8  748.21  5002.0  748.71  5005.2  748.96  5013.3  756.00  5023.7  760.43
  5033.3  762.95  5038.5  763.37  5044.5  764.84  5103.2  768.36  5131.9  769.07
#Mann=4,-1,0
  4723.9    0.12       0  4972.3    0.05       0  4998.0   0.033       0
  5002.0    0.05       0
Bank Sta=4998,5002
Exp/Cntr=0.3,0.1

Type RM Length L Ch R = 1,1451,151,151,151
BEGIN DESCRIPTION:
Mapping XS 65144609
END DESCRIPTION:
XS GIS Cut Line= 2
      2294248.59      7135728.51      2293878.63      7135620.86
#Sta/Elev= 30
  4811.1  766.75  4839.0  764.44  4883.6  762.51  4897.2  761.00  4925.2  759.91
  4935.9  759.03  4946.1  758.96  4956.5  757.85  4964.3  756.90  4969.5  755.09
  4977.3  753.56  4985.7  747.74  4986.0  747.24  4989.5  747.24  4989.7  747.74
  4997.8  750.23  5003.0  750.20  5008.6  751.94  5029.4  755.79  5036.5  757.61
  5041.7  757.27  5060.6  758.25  5075.2  757.67  5081.5  758.07  5123.1  757.28
  5147.5  757.56  5164.8  756.99  5175.2  757.51  5181.0  757.00  5196.4  757.02
#Mann=4,-1,0
  4811.1    0.05       0  4839.0    0.12       0  4985.7    0.07       0
  4989.7    0.12       0
Bank Sta=4985.7,4989.7
Exp/Cntr=0.3,0.1

Type RM Length L Ch R = 1,1300,234,234,234
BEGIN DESCRIPTION:
Mapping XS d1bc7d25
END DESCRIPTION:
XS GIS Cut Line= 2
      2294329.61      7135500.71      2293852.13      7135546.81
#Sta/Elev= 30
  4735.1  759.95  4775.3  758.49  4780.3  759.16  4785.9  758.27  4796.0  758.51
  4806.0  757.56  4856.3  756.08  4887.6  756.56  4896.5  756.09  4956.7  755.44
  4966.8  755.71  4976.8  752.51  4984.9  746.43  4987.9  746.05  4988.1  745.55
  4991.6  745.55  4991.9  746.05  4996.9  748.87  5007.0  751.95  5027.1  751.14
  5047.2  752.98  5057.2  756.61  5067.2  757.49  5087.1  756.24  5107.4  756.25
  5117.5  755.67  5157.7  756.52  5187.8  755.85  5207.9  756.77  5214.8  756.16
#Mann=3,-1,0
  4735.1    0.12       0  4987.9    0.07       0  4991.9    0.12       0
Bank Sta=4987.9,4991.9
Exp/Cntr=0.3,0.1

Type RM Length L Ch R = 1,1066,104,104,104
BEGIN DESCRIPTION:
Mapping XS 436108db
END DESCRIPTION:
XS GIS Cut Line= 2
      2294192.46      7135340.51      2293856.16      7135324.11
#Sta/Elev= 30
  4767.0  753.97  4800.5  754.36  4810.5  753.84  4820.5  754.07  4840.5  753.39
  4860.6  753.70  4870.6  753.52  4882.8  753.90  4890.6  753.88  4900.6  754.32
  4920.6  754.42  4930.7  755.27  4940.7  754.53  4950.7  754.94  4960.7  754.83
  4970.7  752.82  4980.7  751.15  4990.7  746.98  4998.7  745.48  4999.0  744.98
  5002.5  744.98  5002.7  745.48  5010.7  746.79  5020.8  750.90  5030.8  754.41
  5040.8  754.70  5060.8  754.06  5070.8  754.36  5085.7  753.99  5103.7  754.07
#Mann=3,-1,0
  4767.0    0.12       0  4998.7    0.07       0  5002.7    0.12       0
Bank Sta=4998.7,5002.7
Exp/Cntr=0.3,0.1

Type RM Length L Ch R = 1,962,209,209,209
BEGIN DESCRIPTION:
Mapping XS bba3acb2
END DESCRIPTION:
XS GIS Cut Line= 2
      2294208.06      7135241.10      2293777.25      7135215.09
#Sta/Elev= 30
  4769.9  752.17  4779.0  752.34  4789.0  752.07  4829.1  752.19  4839.1  752.53
  4849.1  752.52  4859.1  752.13  4867.7  752.68  4889.2  752.75  4917.6  752.12
  4939.3  752.49  4949.3  752.05  4959.3  750.54  4969.3  750.53  4979.3  748.55
  4987.4  742.76  4987.6  742.26  4991.1  742.26  4991.4  742.76  4999.4  743.76
  5009.4  746.99  5019.4  749.64  5035.8  752.66  5059.5  752.17  5089.5  751.99
  5139.6  752.98  5149.7  753.39  5179.7  753.37  5189.7  753.62  5201.5  753.29
#Mann=4,-1,0
  4769.9    0.12       0  4917.6    0.05       0  4987.4   0.033       0
  4991.4    0.05       0
Bank Sta=4987.4,4991.4
Exp/Cntr=0.3,0.1

Type RM Length L Ch R = 1,753,328,328,328
BEGIN DESCRIPTION:
Mapping XS ccb30759
END DESCRIPTION:
XS GIS Cut Line= 4
      2294282.80      7135095.80      2294030.10      7135033.68
      2293897.36      7135019.16      2293608.19      7135252.30
#Sta/Elev= 30
  4738.7  750.96  4786.5  750.96  4835.3  749.33  4869.5  749.01  4886.8  750.06
  4938.3  750.90  4947.5  751.56  4952.6  751.27  4958.9  752.22  4969.2  751.66
  4977.5  745.31  4977.7  744.81  4981.2  744.81  4981.5  745.31  4989.0  745.95
  4994.2  745.47  4996.9  748.34  5030.2  750.13  5040.3  751.30  5100.6  750.19
  5134.6  750.25  5232.0  751.64  5259.3  751.35  5302.4  752.78  5424.0  751.86
  5459.2  751.99  5465.6  752.70  5487.9  753.04  5503.1  752.86  5503.9  752.86
#Mann=4,-1,0
  4738.7    0.05       0  4977.5   0.033       0  4981.5    0.05       0
  5503.1    0.12       0
Bank Sta=4977.5,4981.5
Exp/Cntr=0.3,0.1

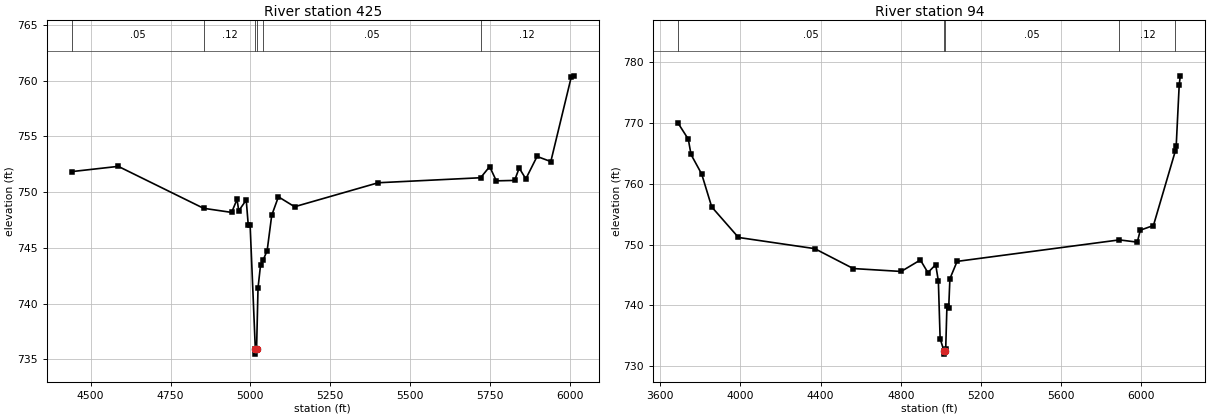
Type RM Length L Ch R = 1,425,331,331,331
BEGIN DESCRIPTION:
MDW T 113 1.0
END DESCRIPTION:
XS GIS Cut Line= 3
      2294586.82      7134983.91      2294079.00      7134760.00
      2293297.77      7135410.51
#Sta/Elev= 30
  4440.8  751.84  4586.4  752.31  4853.3  748.55  4941.2  748.18  4958.1  749.35
  4963.5  748.33  4986.9  749.29  4993.1  747.09  4999.0  747.09  5015.3  735.97
  5015.5  735.47  5019.3  735.97  5023.8  741.40  5031.6  743.44  5039.8  743.90
  5052.4  744.76  5066.7  747.92  5087.6  749.58  5138.3  748.69  5400.0  750.84
  5720.5  751.29  5748.9  752.29  5769.7  751.01  5827.0  751.05  5841.3  752.16
  5862.1  751.19  5897.3  753.20  5940.3  752.74  6004.0  760.29  6012.4  760.43
#Mann=6,-1,0
  4440.8    0.05       0  4853.3    0.12       0  5015.3    0.07       0
  5019.3    0.12       0  5039.8    0.05       0  5720.5    0.12       0
Bank Sta=5015.3,5019.3
Exp/Cntr=0.3,0.1

Type RM Length L Ch R = 1,94,0,0,0
BEGIN DESCRIPTION:
MDW T 113 0.5
END DESCRIPTION:
XS GIS Cut Line= 3
      2295095.89      7135079.28      2293928.28      7134485.10
      2293251.48      7135470.45
#Sta/Elev= 30
  3689.9  769.95  3740.2  767.35  3753.7  764.83  3806.9  761.61  3857.0  756.19
  3990.5  751.16  4370.9  749.32  4563.2  746.04  4802.3  745.56  4898.2  747.45
  4935.8  745.37  4974.7  746.68  4988.0  743.98  4996.8  734.51  5016.1  732.44
  5016.3  731.94  5020.1  732.44  5024.7  732.85  5030.8  739.87  5039.6  739.53
  5045.6  744.36  5081.5  747.22  5891.2  750.76  5980.8  750.39  5995.7  752.36
  6061.3  753.13  6171.2  765.48  6175.0  766.30  6189.9  776.31  6195.4  777.79
#Mann=5,-1,0
  3689.9    0.05       0  5016.1   0.033       0  5020.1    0.05       0
  5891.2    0.12       0  6171.2    0.05       0
Bank Sta=5016.1,5020.1
Exp/Cntr=0.3,0.1

Chan Stop Cuts=-1