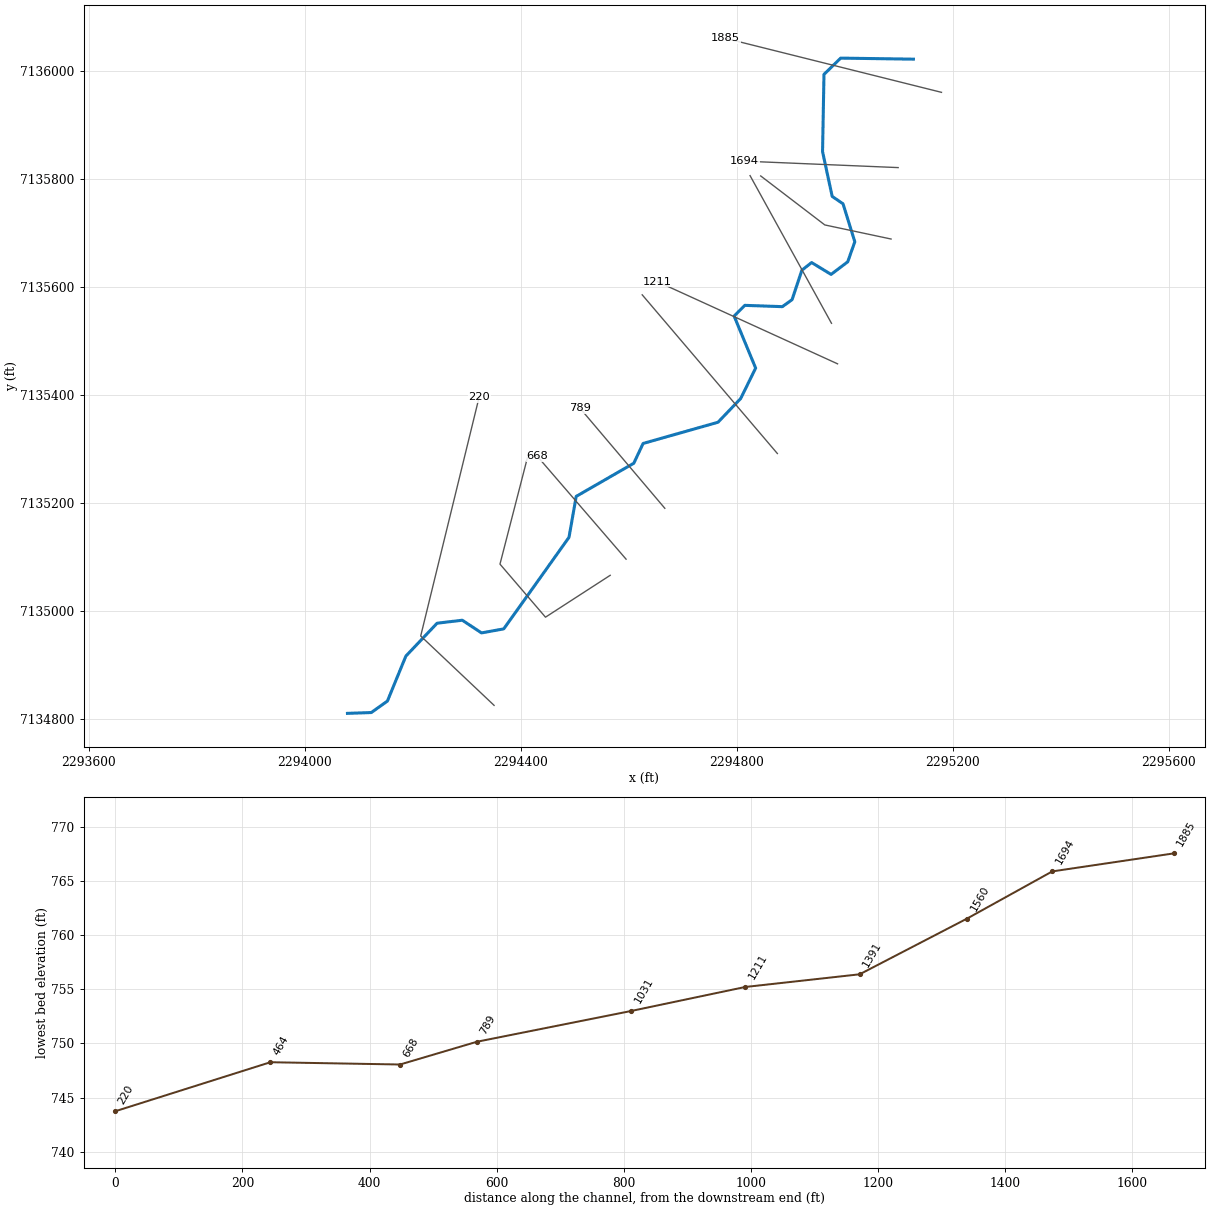
--- MDW T 114.prj (project) ---

Proj Title=MDW T 114 Base Level Engineering
Current Plan=p01
Default Exp/Contr=0.3,0.1
English Units
Geom File=g01
Flow File=f01
Plan File=p01
BEGIN DESCRIPTION:
MDW T 114
END DESCRIPTION:

--- MDW T 114.p01 (plan) ---

Plan Title=Multiple Run
Short Identifier=Multiple
Geom File=g01
Flow File=f01
Subcritical Flow
K Sum by GR= 0
Std Step Tol= 0.01
Critical Tol= 0.01
Num of Std Step Trials= 20
Max Error Tol= 0.3
Flow Tol Ratio= 0.001
Split Flow NTrial= 30
Split Flow Tol= 0.02
Split Flow Ratio= 0.02
Log Output Level= 0
Friction Slope Method= 1
Unsteady Friction Slope Method= 2
Unsteady Bridges Friction Slope Method= 1
Parabolic Critical Depth
Global Vel Dist=  1 , 1 , 1
Global Log Level= 0
CheckData=True
Encroach Param= -1, 0, 0, 0
BEGIN DESCRIPTION:
Multiple Run
END DESCRIPTION:

--- MDW T 114.f01 (steady flow) ---

Flow Title=Multiple
Number of Profiles=7
Profile Names=10-year,25-year,50-year,1pct_min,100-year,1pct_plu,500-year
River Rch & RM= MDW T 114,Reach-1,1885
     179     227     264     153     306     610     410
Boundary for River Rch & Prof#=MDW T 114,Reach-1,1
Up Type=0
Dn Type=3
Dn Slope=0.005
Boundary for River Rch & Prof#=MDW T 114,Reach-1,2
Up Type=0
Dn Type=3
Dn Slope=0.005
Boundary for River Rch & Prof#=MDW T 114,Reach-1,3
Up Type=0
Dn Type=3
Dn Slope=0.005
Boundary for River Rch & Prof#=MDW T 114,Reach-1,4
Up Type=0
Dn Type=3
Dn Slope=0.005
Boundary for River Rch & Prof#=MDW T 114,Reach-1,5
Up Type=0
Dn Type=3
Dn Slope=0.005
Boundary for River Rch & Prof#=MDW T 114,Reach-1,6
Up Type=0
Dn Type=3
Dn Slope=0.005
Boundary for River Rch & Prof#=MDW T 114,Reach-1,7
Up Type=0
Dn Type=3
Dn Slope=0.005

--- MDW T 114.g01 (geometry) ---

Geom Title=Existing Conditions

River Reach=MDW T 114,Reach-1
Reach XY= 30
      2295127.04      7136021.45      2294992.28      7136023.36
      2294961.38      7135993.25      2294958.73      7135850.18
      2294976.58      7135767.32      2294996.65      7135753.57
      2295018.48      7135683.31      2295005.37      7135646.19
      2294974.53      7135622.85      2294938.53      7135644.82
      2294920.50      7135630.68      2294902.29      7135576.06
      2294884.33      7135563.14      2294814.80      7135565.55
      2294794.97      7135545.72      2294834.84      7135449.37
      2294807.13      7135392.99      2294765.15      7135349.09
      2294626.50      7135309.82      2294609.19      7135273.19
      2294502.58      7135211.81      2294489.21      7135135.95
      2294368.38      7134966.44      2294327.21      7134959.01
      2294291.62      7134982.49      2294245.00      7134976.97
      2294187.15      7134916.08      2294152.98      7134832.82
      2294123.13      7134811.56      2294079.00      7134810.00

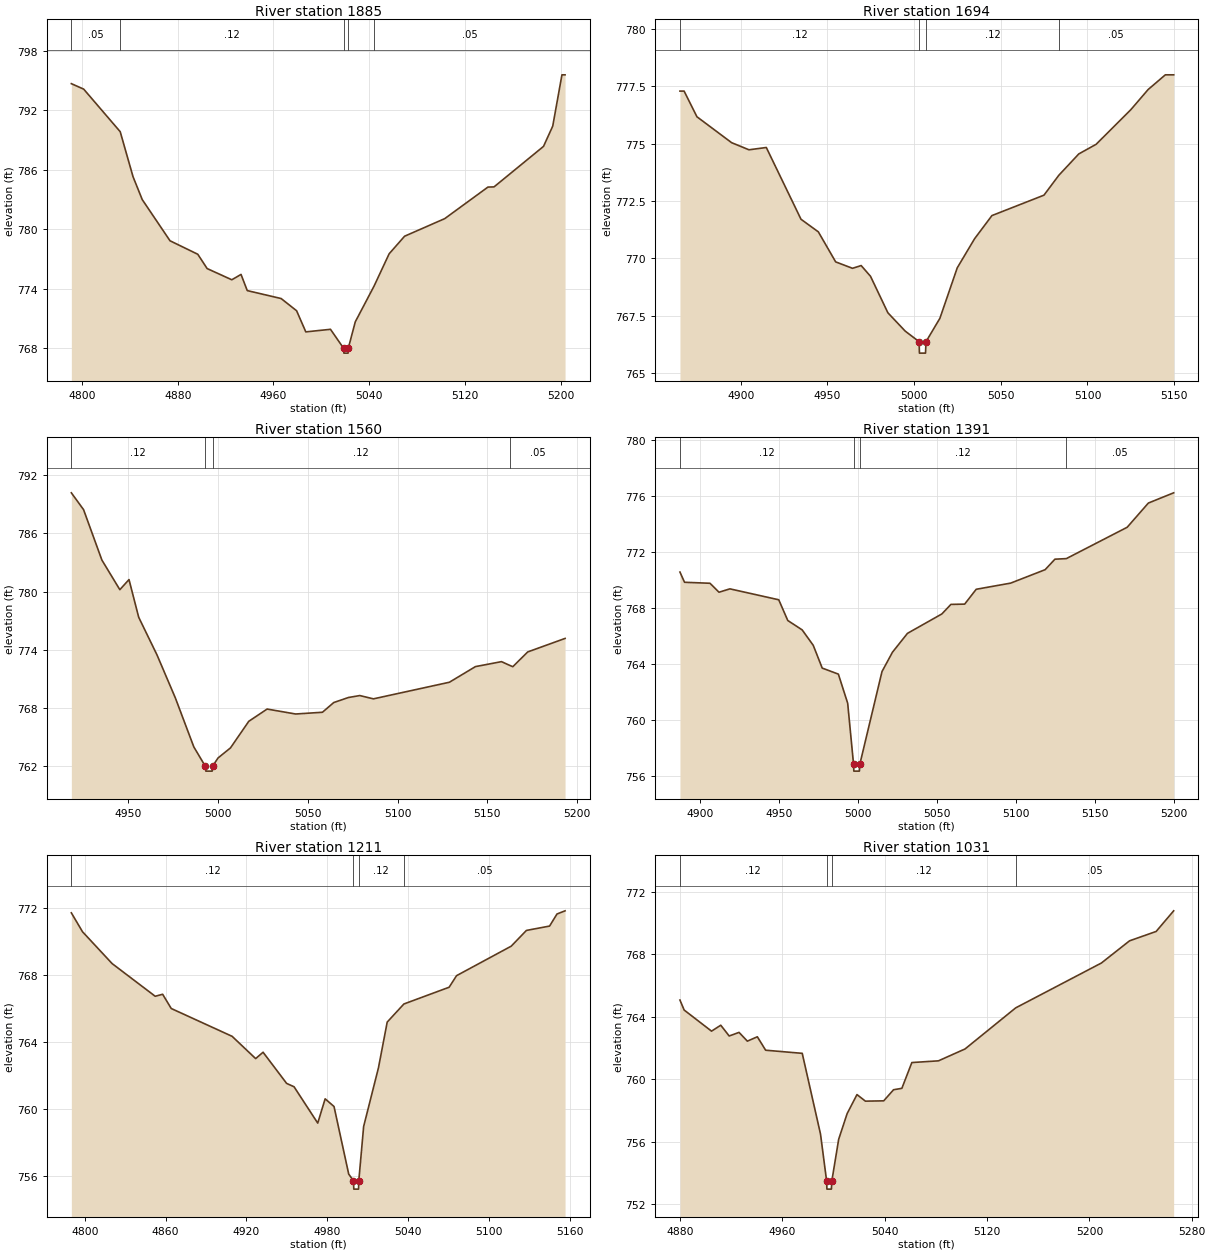
Type RM Length L Ch R = 1,1885,191,191,191
BEGIN DESCRIPTION:
MDW T 114 4.0
END DESCRIPTION:
XS GIS Cut Line= 3
      2295178.98      7135960.00      2294979.00      7136010.00
      2294778.99      7136060.00
#Sta/Elev= 30
  4791.2  794.67  4801.5  794.12  4832.0  789.83  4842.7  785.30  4850.4  782.99
  4873.6  778.84  4896.8  777.48  4904.6  776.04  4925.2  774.91  4932.9  775.45
  4938.1  773.82  4966.4  773.02  4979.3  771.79  4987.0  769.66  5007.6  769.92
  5018.5  768.02  5018.8  767.52  5022.3  767.52  5022.5  768.02  5028.3  770.67
  5044.1  774.30  5056.6  777.53  5069.5  779.30  5103.0  781.07  5139.1  784.25
  5144.2  784.27  5185.5  788.35  5193.2  790.39  5200.9  795.56  5203.5  795.56
#Mann=5,-1,0
  4791.2    0.05       0  4832.0    0.12       0  5018.5    0.07       0
  5022.5    0.12       0  5044.1    0.05       0
Bank Sta=5018.5,5022.5
Exp/Cntr=0.3,0.1

Type RM Length L Ch R = 1,1694,134,134,134
BEGIN DESCRIPTION:
Mapping XS aef8a284
END DESCRIPTION:
XS GIS Cut Line= 2
      2295098.76      7135820.64      2294814.30      7135832.56
#Sta/Elev= 30
  4865.0  777.29  4867.4  777.29  4874.8  776.17  4894.8  775.04  4904.8  774.73
  4914.8  774.83  4934.8  771.70  4944.8  771.15  4954.8  769.84  4964.5  769.56
  4969.5  769.68  4974.9  769.21  4984.9  767.62  4994.9  766.82  5002.9  766.36
  5003.1  765.86  5006.6  765.86  5006.9  766.36  5014.9  767.38  5024.9  769.58
  5034.9  770.85  5044.9  771.86  5074.9  772.75  5083.5  773.62  5095.0  774.55
  5105.0  774.97  5125.0  776.48  5135.0  777.36  5144.9  778.00  5149.7  778.00
#Mann=4,-1,0
  4865.0    0.12       0  5002.9    0.07       0  5006.9    0.12       0
  5083.5    0.05       0
Bank Sta=5002.9,5006.9
Exp/Cntr=0.3,0.1

Type RM Length L Ch R = 1,1560,169,169,169
BEGIN DESCRIPTION:
Mapping XS 82722e72
END DESCRIPTION:
XS GIS Cut Line= 3
      2295085.66      7135688.37      2294962.90      7135714.46
      2294844.21      7135805.19
#Sta/Elev= 30
  4918.4  790.16  4925.2  788.43  4935.4  783.24  4945.4  780.19  4950.5  781.23
  4955.9  777.35  4966.1  773.47  4976.3  769.05  4986.6  764.00  4993.0  762.01
  4993.3  761.51  4996.8  761.51  4997.0  762.01  5000.1  762.87  5007.0  763.90
  5017.2  766.64  5027.4  767.90  5043.3  767.39  5058.2  767.57  5064.5  768.57
  5072.7  769.09  5079.0  769.29  5086.6  768.95  5128.9  770.66  5143.4  772.27
  5157.9  772.78  5162.7  772.38  5164.2  772.26  5172.5  773.78  5193.3  775.17
#Mann=4,-1,0
  4918.4    0.12       0  4993.0    0.07       0  4997.0    0.12       0
  5162.7    0.05       0
Bank Sta=4993,4997
Exp/Cntr=0.3,0.1

Type RM Length L Ch R = 1,1391,180,180,180
BEGIN DESCRIPTION:
Mapping XS fe0748b7
END DESCRIPTION:
XS GIS Cut Line= 2
      2294975.30      7135532.29      2294824.50      7135805.77
#Sta/Elev= 30
  4887.3  770.59  4890.2  769.86  4906.3  769.79  4912.0  769.15  4918.9  769.39
  4949.8  768.61  4955.5  767.13  4964.6  766.46  4971.6  765.36  4977.3  763.73
  4987.5  763.30  4993.4  761.22  4997.1  756.87  4997.3  756.37  5000.8  756.37
  5001.1  756.87  5015.1  763.48  5021.7  764.86  5031.2  766.21  5053.0  767.60
  5058.7  768.28  5067.4  768.30  5074.7  769.36  5096.5  769.80  5118.3  770.76
  5124.5  771.51  5131.7  771.55  5170.2  773.79  5183.6  775.52  5199.6  776.25
#Mann=4,-1,0
  4887.3    0.12       0  4997.1    0.07       0  5001.1    0.12       0
  5131.7    0.05       0
Bank Sta=4997.1,5001.1
Exp/Cntr=0.3,0.1

Type RM Length L Ch R = 1,1211,180,180,180
BEGIN DESCRIPTION:
Mapping XS 2171330c
END DESCRIPTION:
XS GIS Cut Line= 2
      2294986.54      7135457.26      2294652.91      7135609.45
#Sta/Elev= 30
  4790.0  771.69  4798.3  770.56  4820.3  768.66  4852.3  766.71  4857.8  766.83
  4864.2  765.98  4909.4  764.32  4926.9  762.99  4932.4  763.37  4949.9  761.51
  4955.4  761.31  4973.0  759.14  4978.5  760.59  4985.1  760.13  4996.0  756.10
  4999.5  755.70  4999.8  755.20  5003.3  755.20  5003.5  755.70  5007.1  758.94
  5018.1  762.44  5024.6  765.17  5037.0  766.25  5070.6  767.25  5076.1  767.94
  5116.7  769.70  5128.0  770.64  5145.2  770.90  5150.7  771.62  5156.7  771.81
#Mann=4,-1,0
  4790.0    0.12       0  4999.5    0.07       0  5003.5    0.12       0
  5037.0    0.05       0
Bank Sta=4999.5,5003.5
Exp/Cntr=0.3,0.1

Type RM Length L Ch R = 1,1031,242,242,242
BEGIN DESCRIPTION:
Mapping XS b5d8ab9d
END DESCRIPTION:
XS GIS Cut Line= 2
      2294875.06      7135291.17      2294624.80      7135585.05
#Sta/Elev= 30
  4879.9  765.08  4883.2  764.44  4904.6  763.09  4911.8  763.47  4918.4  762.78
  4926.1  763.01  4932.6  762.45  4940.4  762.73  4946.9  761.87  4975.5  761.67
  4989.8  756.50  4994.6  753.48  4994.8  752.98  4998.3  752.98  4998.6  753.48
  5004.0  756.17  5010.6  757.81  5018.3  759.03  5024.9  758.61  5039.2  758.63
  5046.9  759.34  5053.4  759.43  5061.2  761.08  5082.0  761.19  5102.8  761.95
  5142.4  764.58  5209.4  767.45  5231.4  768.87  5252.2  769.47  5265.9  770.79
#Mann=4,-1,0
  4879.9    0.12       0  4994.6    0.07       0  4998.6    0.12       0
  5142.4    0.05       0
Bank Sta=4994.6,4998.6
Exp/Cntr=0.3,0.1

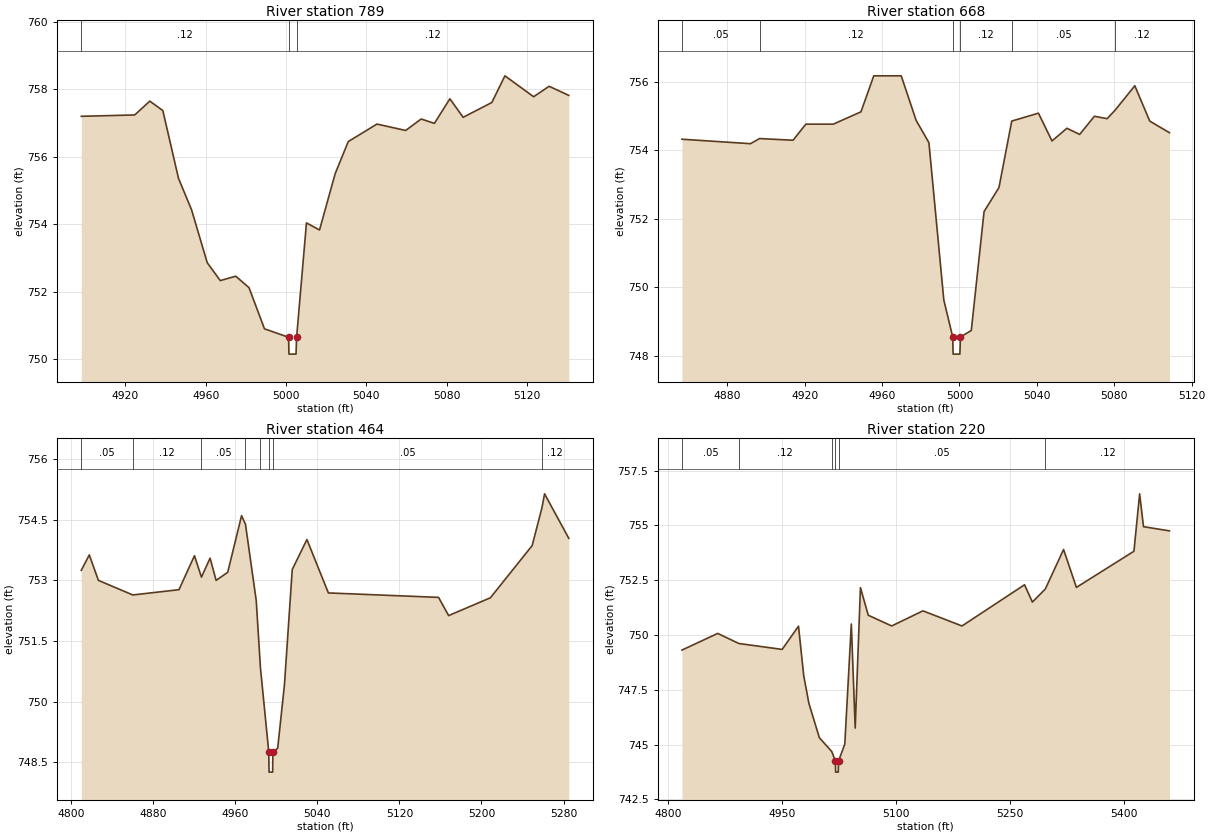
Type RM Length L Ch R = 1,789,121,121,121
BEGIN DESCRIPTION:
Mapping XS 5f8dad47
END DESCRIPTION:
XS GIS Cut Line= 2
      2294666.67      7135189.74      2294509.76      7135374.90
#Sta/Elev= 30
  4898.1  757.20  4924.7  757.24  4932.2  757.65  4938.7  757.37  4946.5  755.36
  4953.0  754.43  4960.8  752.86  4967.3  752.33  4975.0  752.46  4981.6  752.12
  4989.3  750.90  5001.3  750.65  5001.5  750.15  5005.0  750.15  5005.3  750.65
  5010.2  754.04  5016.7  753.83  5024.5  755.50  5031.0  756.45  5045.3  756.97
  5059.6  756.78  5067.3  757.12  5073.9  756.99  5081.6  757.72  5088.2  757.17
  5102.5  757.61  5109.0  758.40  5123.3  757.78  5131.0  758.09  5140.8  757.82
#Mann=3,-1,0
  4898.1    0.12       0  5001.3    0.07       0  5005.3    0.12       0
Bank Sta=5001.3,5005.3
Exp/Cntr=0.3,0.1

Type RM Length L Ch R = 1,668,204,204,204
BEGIN DESCRIPTION:
Mapping XS 7397236e
END DESCRIPTION:
XS GIS Cut Line= 2
      2294594.91      7135095.56      2294430.35      7135286.27
#Sta/Elev= 30
  4856.6  754.32  4892.0  754.19  4896.7  754.34  4914.0  754.29  4920.6  754.76
  4934.8  754.76  4949.1  755.12  4955.7  756.17  4969.9  756.17  4977.6  754.87
  4984.2  754.22  4991.9  749.63  4996.5  748.55  4996.7  748.05  5000.2  748.05
  5000.5  748.55  5006.1  748.74  5012.7  752.21  5020.4  752.91  5027.0  754.85
  5040.8  755.08  5047.8  754.27  5055.5  754.64  5062.1  754.46  5069.7  754.99
  5076.3  754.92  5080.3  755.16  5090.6  755.88  5098.3  754.85  5108.5  754.51
#Mann=6,-1,0
  4856.6    0.05       0  4896.7    0.12       0  4996.5    0.07       0
  5000.5    0.12       0  5027.0    0.05       0  5080.3    0.12       0
Bank Sta=4996.5,5000.5
Exp/Cntr=0.3,0.1

Type RM Length L Ch R = 1,464,244,244,244
BEGIN DESCRIPTION:
Mapping XS f9bc7a43
END DESCRIPTION:
XS GIS Cut Line= 4
      2294565.52      7135065.66      2294445.69      7134988.12
      2294361.41      7135086.37      2294412.08      7135282.86
#Sta/Elev= 30
  4810.0  753.25  4817.8  753.63  4826.7  753.00  4860.2  752.64  4905.2  752.77
  4920.3  753.61  4927.1  753.08  4935.5  753.55  4941.4  753.00  4952.7  753.20
  4966.2  754.60  4970.0  754.39  4980.5  752.50  4984.6  750.84  4992.7  748.76
  4993.0  748.26  4996.5  748.26  4996.7  748.76  5001.4  748.85  5008.0  750.42
  5015.6  753.27  5029.9  754.01  5050.8  752.69  5158.2  752.58  5168.0  752.13
  5208.7  752.57  5249.4  753.86  5258.9  754.79  5261.5  755.14  5285.1  754.04
#Mann=8,-1,0
  4810.0    0.05       0  4860.2    0.12       0  4927.1    0.05       0
  4970.0    0.12       0  4984.6    0.05       0  4992.7   0.033       0
  4996.7    0.05       0  5258.9    0.12       0
Bank Sta=4992.7,4996.7
Exp/Cntr=0.3,0.1

Type RM Length L Ch R = 1,220,0,0,0
BEGIN DESCRIPTION:
MDW T 114 1.0
END DESCRIPTION:
XS GIS Cut Line= 3
      2294350.51      7134824.83      2294214.62      7134953.31
      2294322.78      7135395.46
#Sta/Elev= 30
  4817.9  749.31  4865.0  750.07  4892.8  749.61  4949.9  749.34  4971.4  750.40
  4978.3  748.14  4985.1  746.88  4998.9  745.31  5015.2  744.68  5020.1  744.24
  5020.3  743.74  5023.8  743.74  5024.1  744.24  5032.4  745.02  5041.0  750.50
  5046.1  745.75  5053.0  752.16  5063.3  750.90  5094.2  750.41  5135.3  751.10
  5186.8  750.41  5269.2  752.29  5279.5  751.50  5296.6  752.10  5320.6  753.90
  5337.5  752.17  5413.3  753.82  5420.8  756.44  5425.9  754.94  5460.1  754.75
#Mann=6,-1,0
  4817.9    0.05       0  4892.8    0.12       0  5015.2    0.05       0
  5020.1    0.07       0  5024.1    0.05       0  5296.6    0.12       0
Bank Sta=5020.1,5024.1
Exp/Cntr=0.3,0.1

Chan Stop Cuts=-1