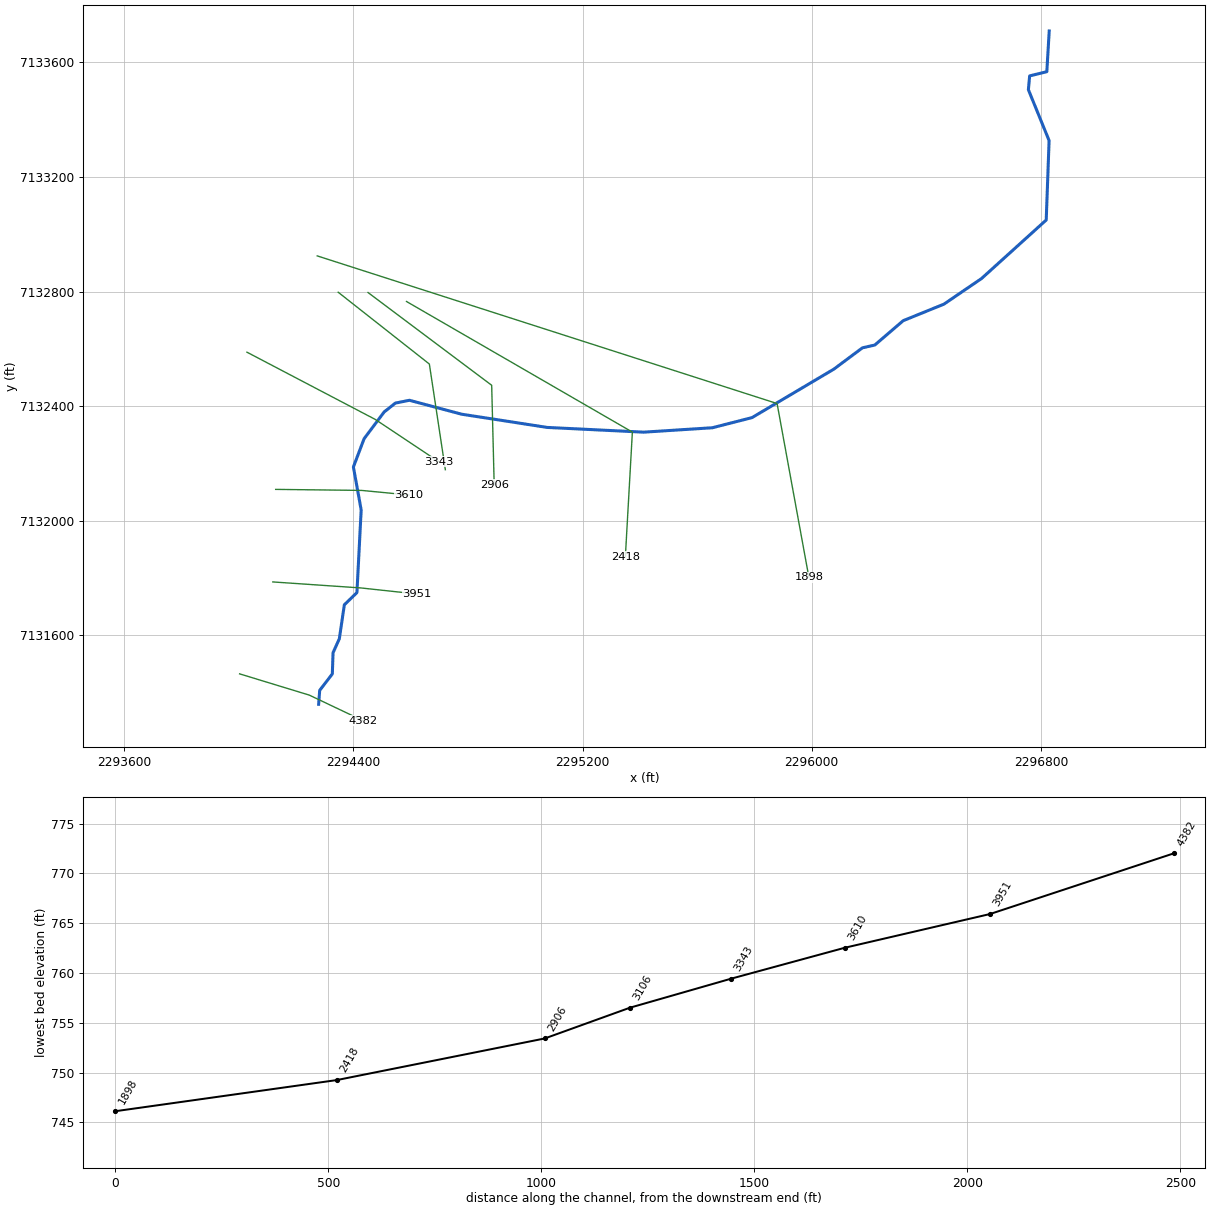
--- MDW T 115.prj (project) ---

Proj Title=MDW T 115 Base Level Engineering
Current Plan=p01
Default Exp/Contr=0.3,0.1
English Units
Geom File=g01
Flow File=f01
Plan File=p01
BEGIN DESCRIPTION:
MDW T 115
END DESCRIPTION:

--- MDW T 115.p01 (plan) ---

Plan Title=Multiple Run
Short Identifier=Multiple
Geom File=g01
Flow File=f01
Subcritical Flow
K Sum by GR= 0
Std Step Tol= 0.01
Critical Tol= 0.01
Num of Std Step Trials= 20
Max Error Tol= 0.3
Flow Tol Ratio= 0.001
Split Flow NTrial= 30
Split Flow Tol= 0.02
Split Flow Ratio= 0.02
Log Output Level= 0
Friction Slope Method= 1
Unsteady Friction Slope Method= 2
Unsteady Bridges Friction Slope Method= 1
Parabolic Critical Depth
Global Vel Dist=  1 , 1 , 1
Global Log Level= 0
CheckData=True
Encroach Param= -1, 0, 0, 0
BEGIN DESCRIPTION:
Multiple Run
END DESCRIPTION:

--- MDW T 115.f01 (steady flow) ---

Flow Title=Multiple
Number of Profiles=7
Profile Names=10-year,25-year,50-year,1pct_min,100-year,1pct_plu,500-year
River Rch & RM= MDW T 115,Reach-1,4382
     390     525     635     383     764    1525    1106
Boundary for River Rch & Prof#=MDW T 115,Reach-1,1
Up Type=0
Dn Type=3
Dn Slope=0.005
Boundary for River Rch & Prof#=MDW T 115,Reach-1,2
Up Type=0
Dn Type=3
Dn Slope=0.005
Boundary for River Rch & Prof#=MDW T 115,Reach-1,3
Up Type=0
Dn Type=3
Dn Slope=0.005
Boundary for River Rch & Prof#=MDW T 115,Reach-1,4
Up Type=0
Dn Type=3
Dn Slope=0.005
Boundary for River Rch & Prof#=MDW T 115,Reach-1,5
Up Type=0
Dn Type=3
Dn Slope=0.005
Boundary for River Rch & Prof#=MDW T 115,Reach-1,6
Up Type=0
Dn Type=3
Dn Slope=0.005
Boundary for River Rch & Prof#=MDW T 115,Reach-1,7
Up Type=0
Dn Type=3
Dn Slope=0.005

--- MDW T 115.g01 (geometry) ---

Geom Title=Existing Conditions

River Reach=MDW T 115,Reach-1
Reach XY= 30
      2294279.00      7131360.00      2294282.64      7131408.49
      2294326.77      7131465.92      2294329.23      7131539.79
      2294351.18      7131588.54      2294368.70      7131707.12
      2294412.60      7131749.77      2294427.41      7132038.30
      2294400.27      7132188.08      2294437.69      7132286.94
      2294507.68      7132380.26      2294546.78      7132411.13
      2294595.94      7132421.01      2294777.71      7132372.45
      2295076.70      7132326.25      2295413.81      7132309.75
      2295653.06      7132325.08      2295791.62      7132360.49
      2296077.57      7132529.87      2296177.02      7132604.06
      2296220.36      7132613.88      2296319.20      7132698.80
      2296461.46      7132756.52      2296592.57      7132845.79
      2296818.53      7133050.17      2296828.56      7133327.53
      2296756.27      7133505.12      2296760.70      7133553.23
      2296820.65      7133567.91      2296829.00      7133710.00

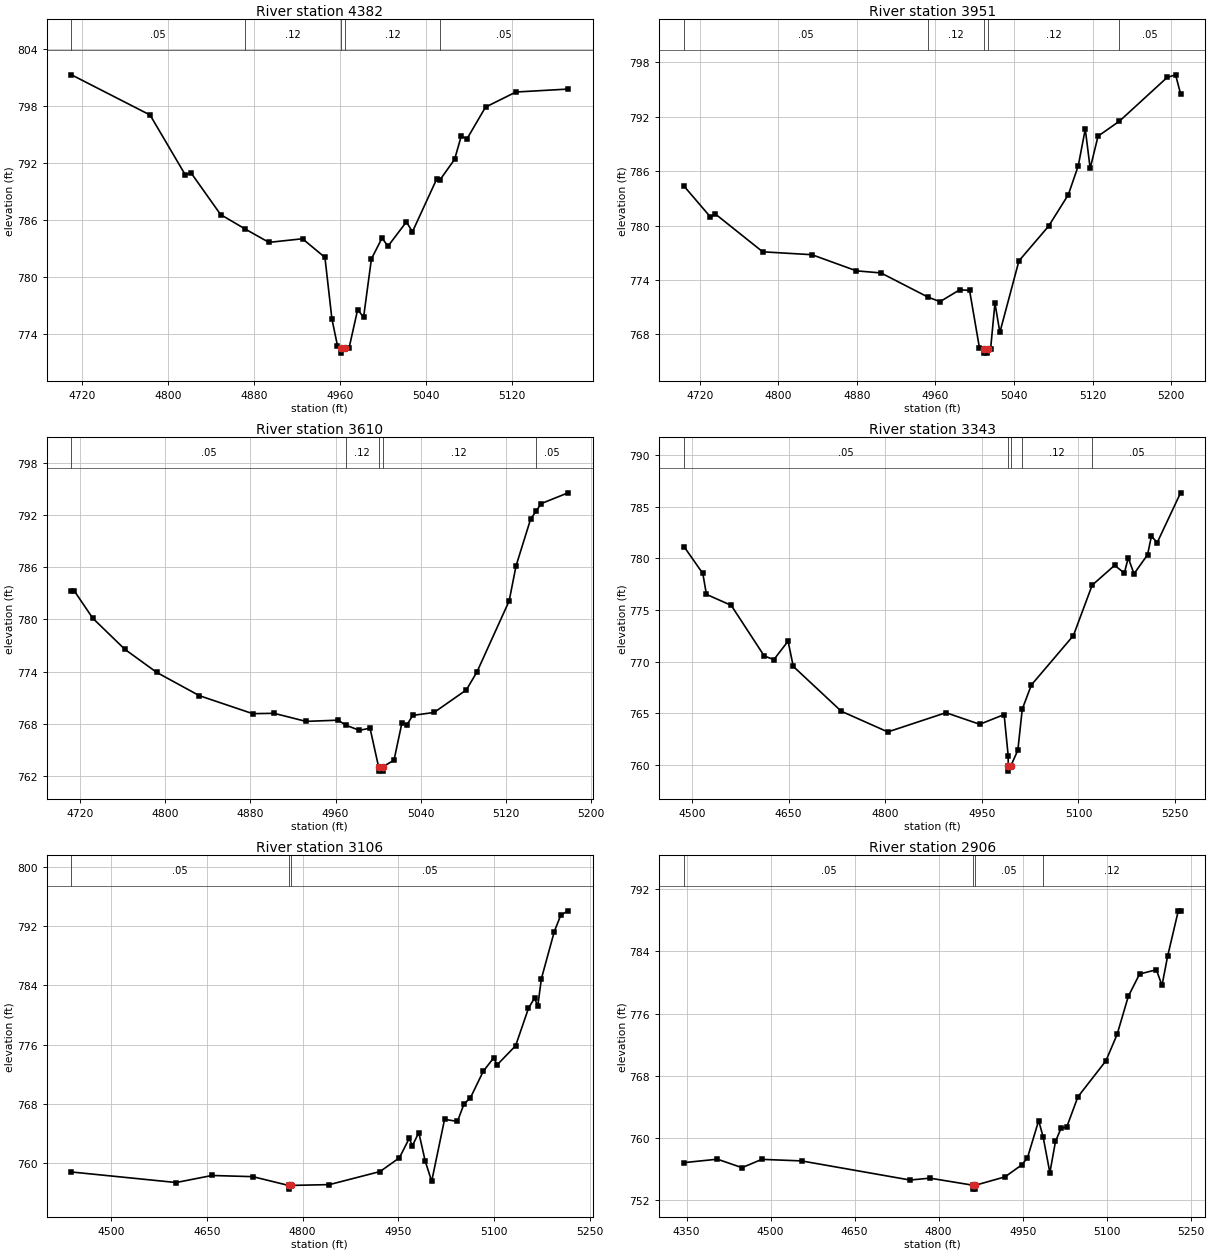
Type RM Length L Ch R = 1,4382,431,431,431
BEGIN DESCRIPTION:
MDW T 115 5.0
END DESCRIPTION:
XS GIS Cut Line= 3
      2294003.13      7131466.13      2294246.27      7131391.95
      2294434.50      7131302.51
#Sta/Elev= 30
  4710.0  801.31  4783.2  797.08  4816.1  790.76  4821.3  791.00  4848.9  786.60
  4871.6  785.09  4893.9  783.67  4925.2  784.05  4946.1  782.09  4952.6  775.61
  4957.8  772.78  4961.0  772.51  4961.3  772.01  4965.0  772.51  4968.5  772.51
  4976.6  776.60  4982.1  775.78  4989.4  781.93  4999.3  784.13  5004.8  783.26
  5022.0  785.83  5027.6  784.78  5050.3  790.36  5053.0  790.21  5066.9  792.41
  5073.0  794.83  5078.5  794.58  5095.7  797.91  5124.0  799.50  5172.6  799.81
#Mann=5,-1,0
  4710.0    0.05       0  4871.6    0.12       0  4961.0    0.07       0
  4965.0    0.12       0  5053.0    0.05       0
Bank Sta=4961,4965
Exp/Cntr=0.3,0.1

Type RM Length L Ch R = 1,3951,341,341,341
BEGIN DESCRIPTION:
MDW T 115 4.0
END DESCRIPTION:
XS GIS Cut Line= 3
      2294119.08      7131786.97      2294426.74      7131765.94
      2294622.53      7131744.83
#Sta/Elev= 30
  4704.1  784.35  4731.0  780.94  4736.0  781.27  4784.2  777.10  4834.3  776.78
  4879.5  775.00  4904.5  774.77  4952.4  772.10  4964.6  771.60  4984.7  772.91
  4994.7  772.84  5004.7  766.51  5009.1  766.42  5009.4  765.92  5012.9  765.92
  5013.1  766.42  5016.1  766.42  5020.5  771.44  5025.5  768.21  5044.9  776.10
  5075.1  779.93  5095.2  783.41  5105.3  786.60  5112.4  790.64  5117.4  786.31
  5125.4  789.86  5147.2  791.52  5195.8  796.35  5204.3  796.63  5209.4  794.53
#Mann=5,-1,0
  4704.1    0.05       0  4952.4    0.12       0  5009.1    0.07       0
  5013.1    0.12       0  5147.2    0.05       0
Bank Sta=5009.1,5013.1
Exp/Cntr=0.3,0.1

Type RM Length L Ch R = 1,3610,267,267,267
BEGIN DESCRIPTION:
MDW T 115 3.0
END DESCRIPTION:
XS GIS Cut Line= 3
      2294128.97      7132110.00      2294428.98      7132106.41
      2294594.08      7132090.44
#Sta/Elev= 30
  4712.3  783.31  4714.8  783.31  4732.3  780.14  4762.3  776.57  4792.3  773.90
  4832.3  771.22  4882.3  769.15  4902.3  769.19  4932.3  768.26  4962.3  768.40
  4970.0  767.81  4982.4  767.23  4992.4  767.48  5000.4  763.03  5000.6  762.53
  5004.1  762.53  5004.4  763.03  5014.9  763.79  5022.2  768.02  5027.2  767.89
  5032.4  768.95  5052.5  769.29  5082.7  771.88  5092.7  773.95  5122.9  782.13
  5129.4  786.18  5143.0  791.54  5148.0  792.45  5153.0  793.35  5178.2  794.59
#Mann=5,-1,0
  4712.3    0.05       0  4970.0    0.12       0  5000.4    0.07       0
  5004.4    0.12       0  5148.0    0.05       0
Bank Sta=5000.4,5004.4
Exp/Cntr=0.3,0.1

Type RM Length L Ch R = 1,3343,237,237,237
BEGIN DESCRIPTION:
MDW T 115 2.0
END DESCRIPTION:
XS GIS Cut Line= 3
      2294028.75      7132588.88      2294476.41      7132354.29
      2294697.51      7132207.13
#Sta/Elev= 30
  4487.6  781.13  4516.8  778.53  4522.4  776.51  4560.9  775.45  4612.1  770.56
  4627.1  770.20  4649.2  771.99  4657.2  769.55  4731.8  765.21  4804.0  763.21
  4894.3  765.07  4946.8  763.95  4984.6  764.89  4990.9  760.92  4991.0  759.92
  4991.3  759.42  4995.0  759.92  5005.9  761.44  5012.8  765.42  5027.0  767.76
  5092.2  772.53  5121.3  777.40  5156.2  779.32  5171.3  778.57  5177.3  780.05
  5186.3  778.50  5207.3  780.34  5213.3  782.14  5222.3  781.52  5258.6  786.33
#Mann=5,-1,0
  4487.6    0.05       0  4991.0    0.04       0  4995.0    0.05       0
  5012.8    0.12       0  5121.3    0.05       0
Bank Sta=4991,4995
Exp/Cntr=0.3,0.1

Type RM Length L Ch R = 1,3106,200,200,200
BEGIN DESCRIPTION:
Mapping XS a5cdbca7
END DESCRIPTION:
XS GIS Cut Line= 3
      2294347.26      7132798.09      2294665.42      7132547.51
      2294721.20      7132178.69
#Sta/Elev= 30
  4437.8  758.82  4601.8  757.40  4657.8  758.35  4722.0  758.19  4777.8  757.01
  4778.0  756.51  4781.8  757.01  4841.9  757.12  4921.2  758.88  4951.5  760.73
  4966.9  763.34  4971.9  762.35  4981.9  764.14  4992.0  760.29  5002.1  757.56
  5022.3  765.92  5042.5  765.64  5052.7  767.98  5062.8  768.82  5083.0  772.41
  5099.5  774.23  5104.5  773.25  5133.6  775.84  5153.8  780.90  5163.3  782.28
  5168.3  781.17  5174.0  784.88  5194.2  791.23  5204.4  793.45  5215.8  794.03
#Mann=3,-1,0
  4437.8    0.05       0  4777.8   0.033       0  4781.8    0.05       0
Bank Sta=4777.8,4781.8
Exp/Cntr=0.3,0.1

Type RM Length L Ch R = 1,2906,488,488,488
BEGIN DESCRIPTION:
Mapping XS 1c23ff9a
END DESCRIPTION:
XS GIS Cut Line= 3
      2294451.29      7132797.12      2294882.97      7132473.36
      2294891.70      7132126.77
#Sta/Elev= 30
  4345.5  756.83  4405.2  757.27  4449.0  756.18  4484.4  757.25  4555.2  757.05
  4749.0  754.59  4784.4  754.83  4861.5  753.92  4861.8  753.42  4865.3  753.42
  4865.5  753.92  4918.5  755.00  4948.5  756.55  4958.5  757.45  4978.5  762.23
  4986.5  760.12  4998.5  755.54  5008.5  759.55  5018.5  761.25  5028.5  761.39
  5048.5  765.29  5098.5  769.92  5118.5  773.32  5138.5  778.22  5158.6  781.09
  5188.6  781.64  5198.6  779.62  5208.6  783.36  5227.7  789.22  5231.8  789.22
#Mann=4,-1,0
  4345.5    0.05       0  4861.5    0.07       0  4865.5    0.05       0
  4986.5    0.12       0
Bank Sta=4861.5,4865.5
Exp/Cntr=0.3,0.1

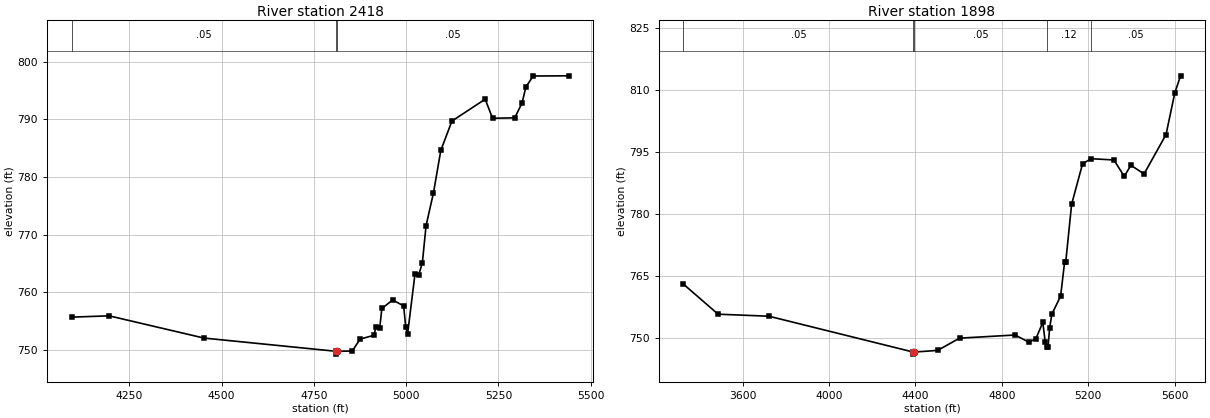
Type RM Length L Ch R = 1,2418,520,520,520
BEGIN DESCRIPTION:
MDW T 115 1.0
END DESCRIPTION:
XS GIS Cut Line= 3
      2294585.60      7132765.83      2295374.03      7132309.94
      2295349.51      7131874.27
#Sta/Elev= 30
  4093.1  755.66  4194.9  755.89  4451.8  752.03  4808.7  749.74  4808.9  749.24
  4812.7  749.74  4853.8  749.78  4875.3  751.85  4912.6  752.51  4918.4  754.03
  4928.4  753.83  4934.1  757.17  4963.4  758.64  4993.0  757.62  4998.8  754.01
  5003.8  752.72  5023.8  763.11  5033.8  762.97  5043.8  765.07  5053.9  771.54
  5073.9  777.22  5093.9  784.62  5124.0  789.71  5214.1  793.50  5234.1  790.19
  5294.2  790.27  5314.3  792.88  5324.3  795.62  5344.3  797.53  5440.2  797.56
#Mann=3,-1,0
  4093.1    0.05       0  4808.7   0.033       0  4812.7    0.05       0
Bank Sta=4808.7,4812.7
Exp/Cntr=0.3,0.1

Type RM Length L Ch R = 1,1898,0,0,0
BEGIN DESCRIPTION:
MDW T 115 0.5
END DESCRIPTION:
XS GIS Cut Line= 3
      2294274.14      7132924.95      2295879.17      7132409.60
      2295990.02      7131803.78
#Sta/Elev= 30
  3325.8  763.01  3486.2  755.76  3721.5  755.27  4389.7  746.61  4389.9  746.11
  4393.7  746.61  4502.6  747.01  4604.2  749.97  4861.0  750.73  4925.3  748.99
  4957.4  749.83  4989.5  753.76  5000.9  749.01  5010.8  747.92  5013.9  747.92
  5021.3  752.44  5031.5  755.79  5072.1  760.11  5090.7  768.46  5095.7  768.31
  5122.9  782.30  5173.8  792.13  5213.5  793.33  5318.7  793.03  5366.8  789.07
  5397.4  791.74  5458.4  789.66  5560.1  799.16  5600.7  809.24  5627.4  813.36
#Mann=5,-1,0
  3325.8    0.05       0  4389.7   0.033       0  4393.7    0.05       0
  5010.8    0.12       0  5213.5    0.05       0
Bank Sta=4389.7,4393.7
Exp/Cntr=0.3,0.1

Chan Stop Cuts=-1