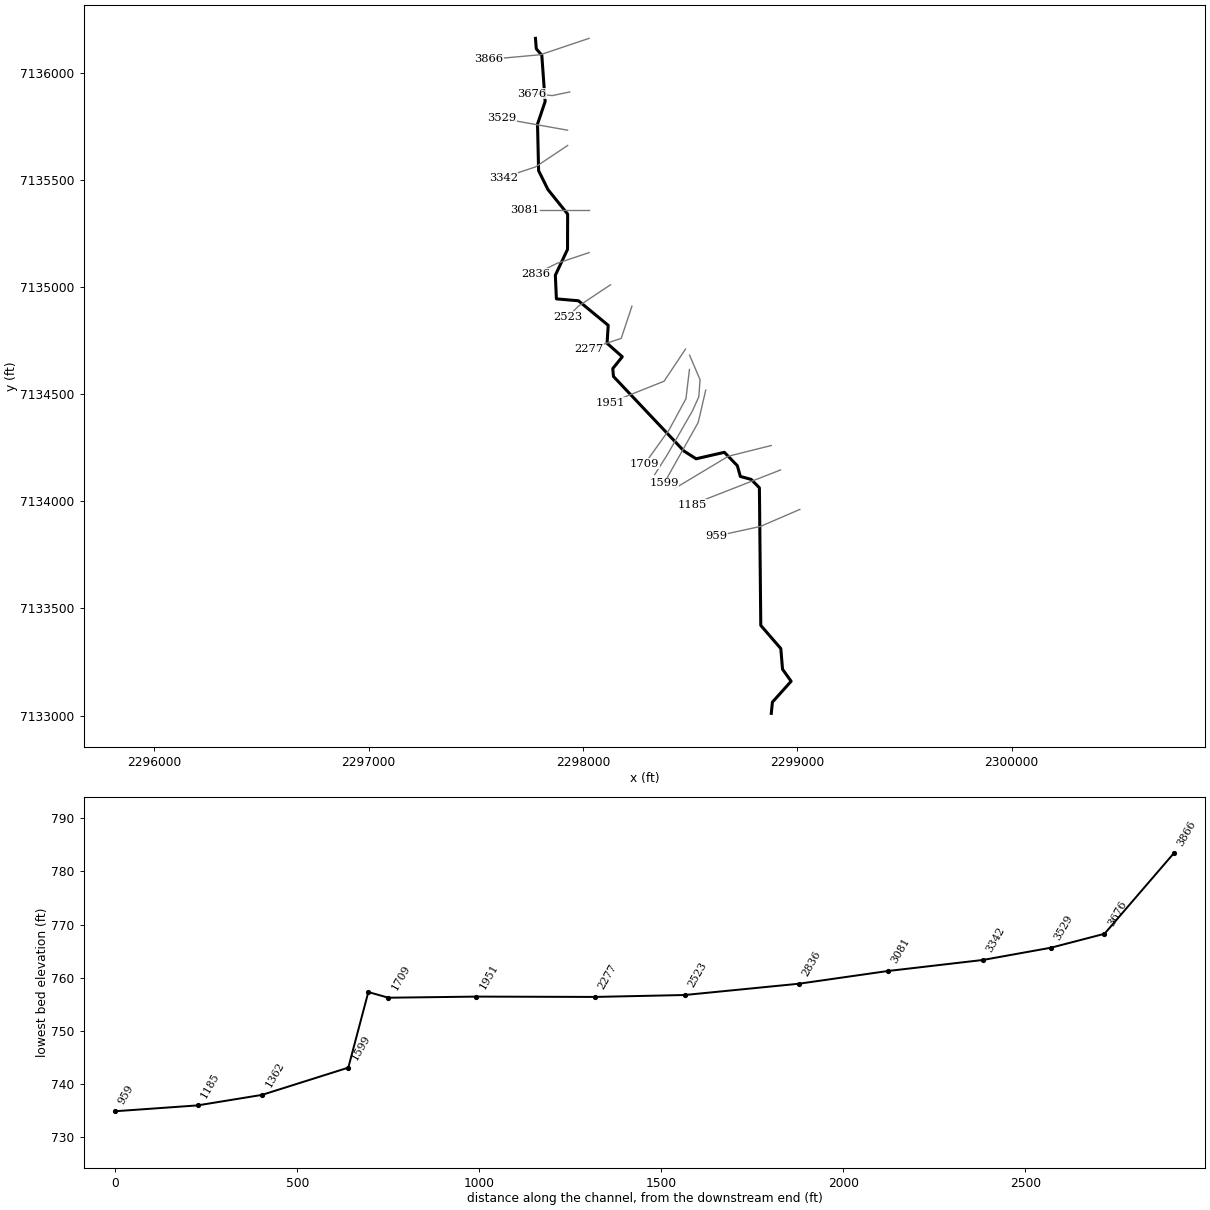
--- MDW T 116.prj (project) ---

Proj Title=MDW T 116 Base Level Engineering
Current Plan=p01
Default Exp/Contr=0.3,0.1
English Units
Geom File=g01
Flow File=f01
Plan File=p01
BEGIN DESCRIPTION:
MDW T 116
END DESCRIPTION:

--- MDW T 116.p01 (plan) ---

Plan Title=Multiple Run
Short Identifier=Multiple
Geom File=g01
Flow File=f01
Subcritical Flow
K Sum by GR= 0
Std Step Tol= 0.01
Critical Tol= 0.01
Num of Std Step Trials= 20
Max Error Tol= 0.3
Flow Tol Ratio= 0.001
Split Flow NTrial= 30
Split Flow Tol= 0.02
Split Flow Ratio= 0.02
Log Output Level= 0
Friction Slope Method= 1
Unsteady Friction Slope Method= 2
Unsteady Bridges Friction Slope Method= 1
Parabolic Critical Depth
Global Vel Dist=  1 , 1 , 1
Global Log Level= 0
CheckData=True
Encroach Param= -1, 0, 0, 0
BEGIN DESCRIPTION:
Multiple Run
END DESCRIPTION:

--- MDW T 116.f01 (steady flow) ---

Flow Title=Multiple
Number of Profiles=7
Profile Names=10-year,25-year,50-year,1pct_min,100-year,1pct_plu,500-year
River Rch & RM= MDW T 116,Reach-1,3866
     416     560     678     408     814    1624    1175
Boundary for River Rch & Prof#=MDW T 116,Reach-1,1
Up Type=0
Dn Type=3
Dn Slope=0.005
Boundary for River Rch & Prof#=MDW T 116,Reach-1,2
Up Type=0
Dn Type=3
Dn Slope=0.005
Boundary for River Rch & Prof#=MDW T 116,Reach-1,3
Up Type=0
Dn Type=3
Dn Slope=0.005
Boundary for River Rch & Prof#=MDW T 116,Reach-1,4
Up Type=0
Dn Type=3
Dn Slope=0.005
Boundary for River Rch & Prof#=MDW T 116,Reach-1,5
Up Type=0
Dn Type=3
Dn Slope=0.005
Boundary for River Rch & Prof#=MDW T 116,Reach-1,6
Up Type=0
Dn Type=3
Dn Slope=0.005
Boundary for River Rch & Prof#=MDW T 116,Reach-1,7
Up Type=0
Dn Type=3
Dn Slope=0.005

--- MDW T 116.g01 (geometry) ---

Geom Title=Existing Conditions

River Reach=MDW T 116,Reach-1
Reach XY= 30
      2297779.00      7136160.00      2297782.65      7136111.51
      2297808.51      7136080.90      2297823.99      7135865.07
      2297788.51      7135759.85      2297793.55      7135542.39
      2297837.25      7135454.23      2297929.04      7135340.02
      2297928.48      7135175.22      2297871.67      7135054.63
      2297876.55      7134944.25      2297979.75      7134935.27
      2298118.20      7134820.84      2298113.02      7134736.98
      2298183.96      7134674.13      2298139.54      7134619.01
      2298142.73      7134582.24      2298471.57      7134234.25
      2298528.18      7134198.02      2298660.23      7134228.22
      2298720.70      7134165.74      2298734.65      7134115.64
      2298785.08      7134101.85      2298823.61      7134062.69
      2298830.06      7133420.44      2298923.47      7133312.42
      2298931.56      7133215.89      2298971.69      7133159.90
      2298884.35      7133062.52      2298879.00      7133010.00

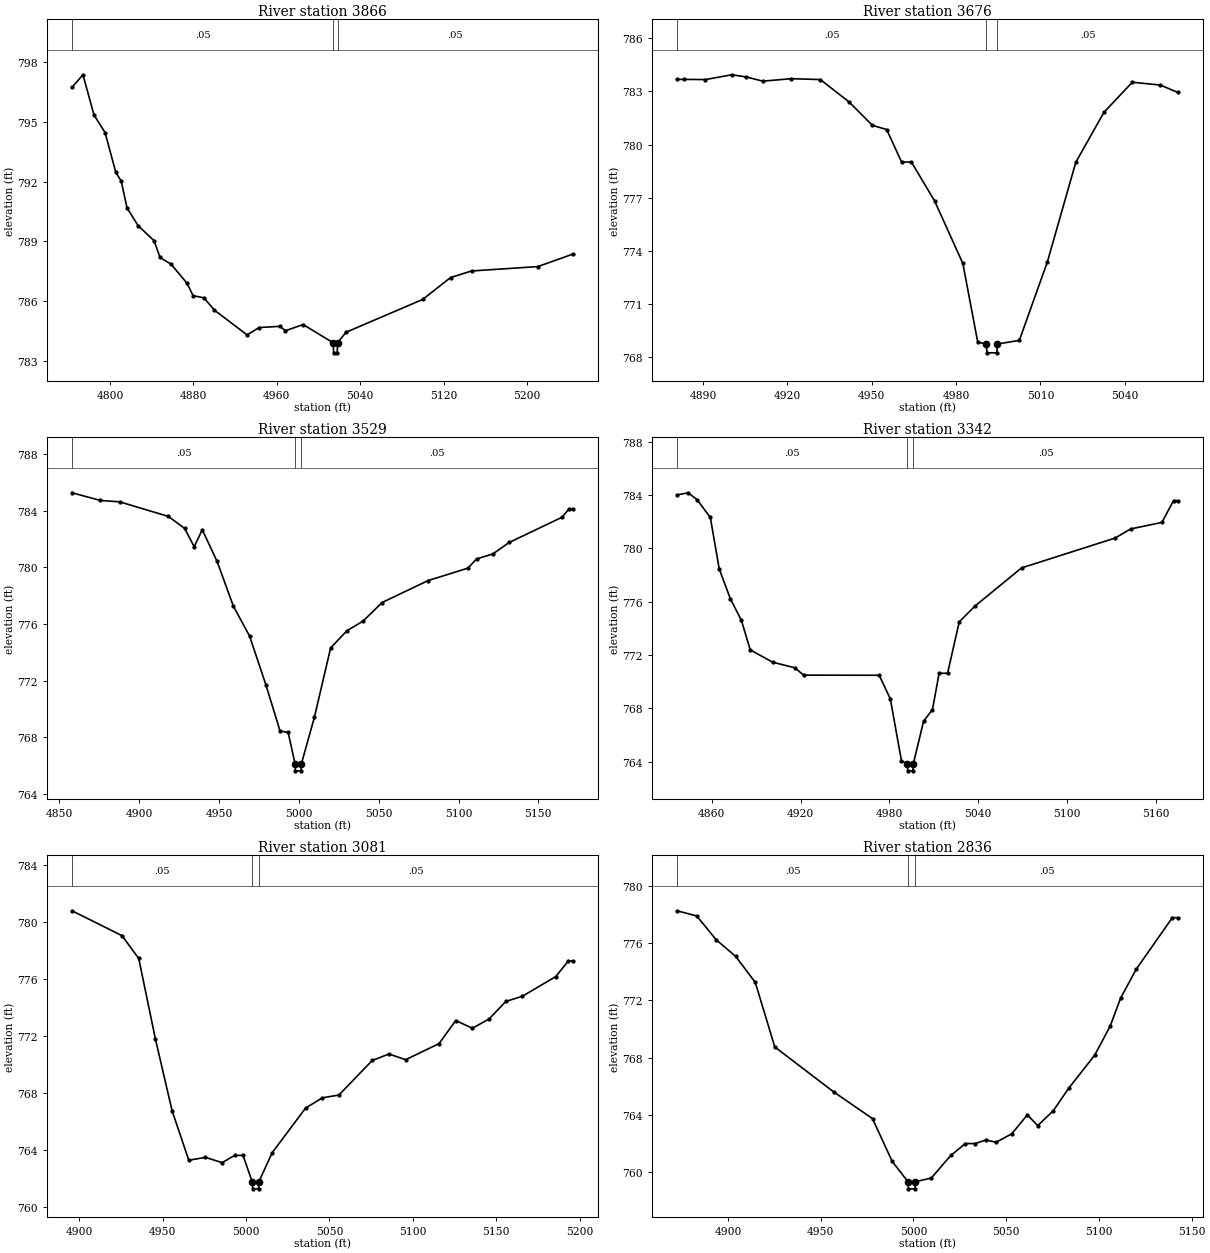
Type RM Length L Ch R = 1,3866,190,190,190
BEGIN DESCRIPTION:
MDW T 116 11.0
END DESCRIPTION:
XS GIS Cut Line= 3
      2298029.00      7136160.00      2297802.18      7136083.62
      2297562.61      7136061.82
#Sta/Elev= 30
  4763.6  796.73  4774.1  797.36  4784.7  795.34  4795.3  794.46  4805.6  792.46
  4810.8  792.02  4816.4  790.67  4826.9  789.79  4842.3  789.03  4848.0  788.19
  4858.6  787.85  4873.8  786.90  4879.7  786.27  4890.2  786.16  4900.0  785.55
  4931.5  784.30  4943.0  784.67  4963.0  784.73  4968.3  784.51  4985.2  784.82
  5014.2  783.90  5014.4  783.40  5017.9  783.40  5018.2  783.90  5026.2  784.43
  5099.8  786.08  5126.6  787.18  5146.7  787.51  5210.2  787.73  5243.5  788.35
#Mann=3,-1,0
  4763.6    0.05       0  5014.2   0.033       0  5018.2    0.05       0
Bank Sta=5014.2,5018.2
Exp/Cntr=0.3,0.1

Type RM Length L Ch R = 1,3676,147,147,147
BEGIN DESCRIPTION:
Mapping XS 6d76a0bb
END DESCRIPTION:
XS GIS Cut Line= 3
      2297938.88      7135909.87      2297857.29      7135892.82
      2297762.94      7135901.46
#Sta/Elev= 27
  4880.7  783.68  4883.2  783.68  4890.8  783.67  4900.2  783.94  4905.3  783.82
  4911.2  783.58  4921.4  783.72  4931.7  783.67  4941.9  782.41  4950.2  781.09
  4955.3  780.85  4960.6  779.02  4964.1  779.02  4972.4  776.81  4982.4  773.30
  4987.7  768.86  4990.7  768.76  4991.0  768.26  4994.5  768.26  4994.7  768.76
  5002.5  768.96  5012.5  773.40  5022.6  779.01  5032.6  781.82  5042.7  783.52
  5052.7  783.36  5058.8  782.95
#Mann=3,-1,0
  4880.7    0.05       0  4990.7   0.033       0  4994.7    0.05       0
Bank Sta=4990.7,4994.7
Exp/Cntr=0.3,0.1

Type RM Length L Ch R = 1,3529,187,187,187
BEGIN DESCRIPTION:
Mapping XS 426f7a89
END DESCRIPTION:
XS GIS Cut Line= 2
      2297928.47      7135731.37      2297619.87      7135786.59
#Sta/Elev= 30
  4857.9  785.27  4875.6  784.73  4887.8  784.63  4918.3  783.60  4928.5  782.75
  4934.4  781.46  4939.5  782.66  4948.8  780.42  4959.0  777.26  4969.1  775.16
  4979.3  771.73  4988.2  768.46  4993.3  768.35  4997.6  766.14  4997.8  765.64
  5001.3  765.64  5001.6  766.14  5009.7  769.41  5019.9  774.32  5030.1  775.53
  5040.2  776.21  5052.1  777.52  5080.9  779.07  5105.9  779.95  5111.3  780.60
  5121.5  780.95  5131.7  781.76  5164.8  783.54  5169.3  784.14  5171.4  784.14
#Mann=3,-1,0
  4857.9    0.05       0  4997.6   0.033       0  5001.6    0.05       0
Bank Sta=4997.6,5001.6
Exp/Cntr=0.3,0.1

Type RM Length L Ch R = 1,3342,261,261,261
BEGIN DESCRIPTION:
MDW T 116 9.0
END DESCRIPTION:
XS GIS Cut Line= 3
      2297928.97      7135659.98      2297779.00      7135560.00
      2297628.96      7135509.99
#Sta/Elev= 30
  4836.5  784.00  4844.0  784.16  4850.0  783.65  4859.0  782.31  4865.0  778.46
  4872.5  776.23  4880.0  774.60  4886.0  772.39  4901.1  771.47  4916.1  771.05
  4922.1  770.50  4973.2  770.49  4980.7  768.72  4988.2  764.10  4992.2  763.83
  4992.5  763.33  4996.0  763.33  4996.2  763.83  5003.2  767.05  5009.2  767.92
  5013.7  770.64  5019.4  770.64  5027.3  774.49  5037.8  775.66  5069.4  778.53
  5132.7  780.77  5143.2  781.45  5164.3  781.94  5172.2  783.57  5174.9  783.57
#Mann=3,-1,0
  4836.5    0.05       0  4992.2   0.033       0  4996.2    0.05       0
Bank Sta=4992.2,4996.2
Exp/Cntr=0.3,0.1

Type RM Length L Ch R = 1,3081,245,245,245
BEGIN DESCRIPTION:
MDW T 116 8.0
END DESCRIPTION:
XS GIS Cut Line= 3
      2298029.03      7135360.00      2297929.00      7135360.00
      2297729.03      7135360.00
#Sta/Elev= 30
  4895.7  780.78  4925.7  779.03  4935.7  777.43  4945.7  771.77  4955.7  766.73
  4965.7  763.26  4975.7  763.46  4985.7  763.09  4993.2  763.60  4998.2  763.60
  5003.7  761.75  5004.0  761.25  5007.5  761.25  5007.7  761.75  5015.7  763.79
  5035.7  766.92  5045.7  767.64  5055.7  767.84  5075.7  770.27  5085.7  770.72
  5095.7  770.32  5115.7  771.45  5125.7  773.07  5135.7  772.53  5145.7  773.18
  5155.7  774.41  5165.7  774.78  5185.7  776.16  5193.2  777.26  5195.7  777.26
#Mann=3,-1,0
  4895.7    0.05       0  5003.7   0.033       0  5007.7    0.05       0
Bank Sta=5003.7,5007.7
Exp/Cntr=0.3,0.1

Type RM Length L Ch R = 1,2836,313,313,313
BEGIN DESCRIPTION:
MDW T 116 7.0
END DESCRIPTION:
XS GIS Cut Line= 3
      2298029.02      7135160.01      2297879.00      7135110.00
      2297779.04      7135060.02
#Sta/Elev= 30
  4872.5  778.25  4883.1  777.89  4893.6  776.23  4904.1  775.07  4914.7  773.25
  4925.2  768.75  4956.9  765.62  4977.9  763.75  4988.5  760.77  4997.0  759.35
  4997.3  758.85  5000.8  758.85  5001.0  759.35  5009.6  759.60  5020.1  761.18
  5028.0  762.01  5033.4  762.01  5039.0  762.26  5044.6  762.10  5053.0  762.69
  5061.4  764.01  5067.0  763.26  5075.4  764.30  5083.7  765.87  5097.7  768.17
  5106.1  770.21  5111.7  772.16  5120.1  774.17  5139.6  777.77  5142.4  777.77
#Mann=3,-1,0
  4872.5    0.05       0  4997.0   0.033       0  5001.0    0.05       0
Bank Sta=4997,5001
Exp/Cntr=0.3,0.1

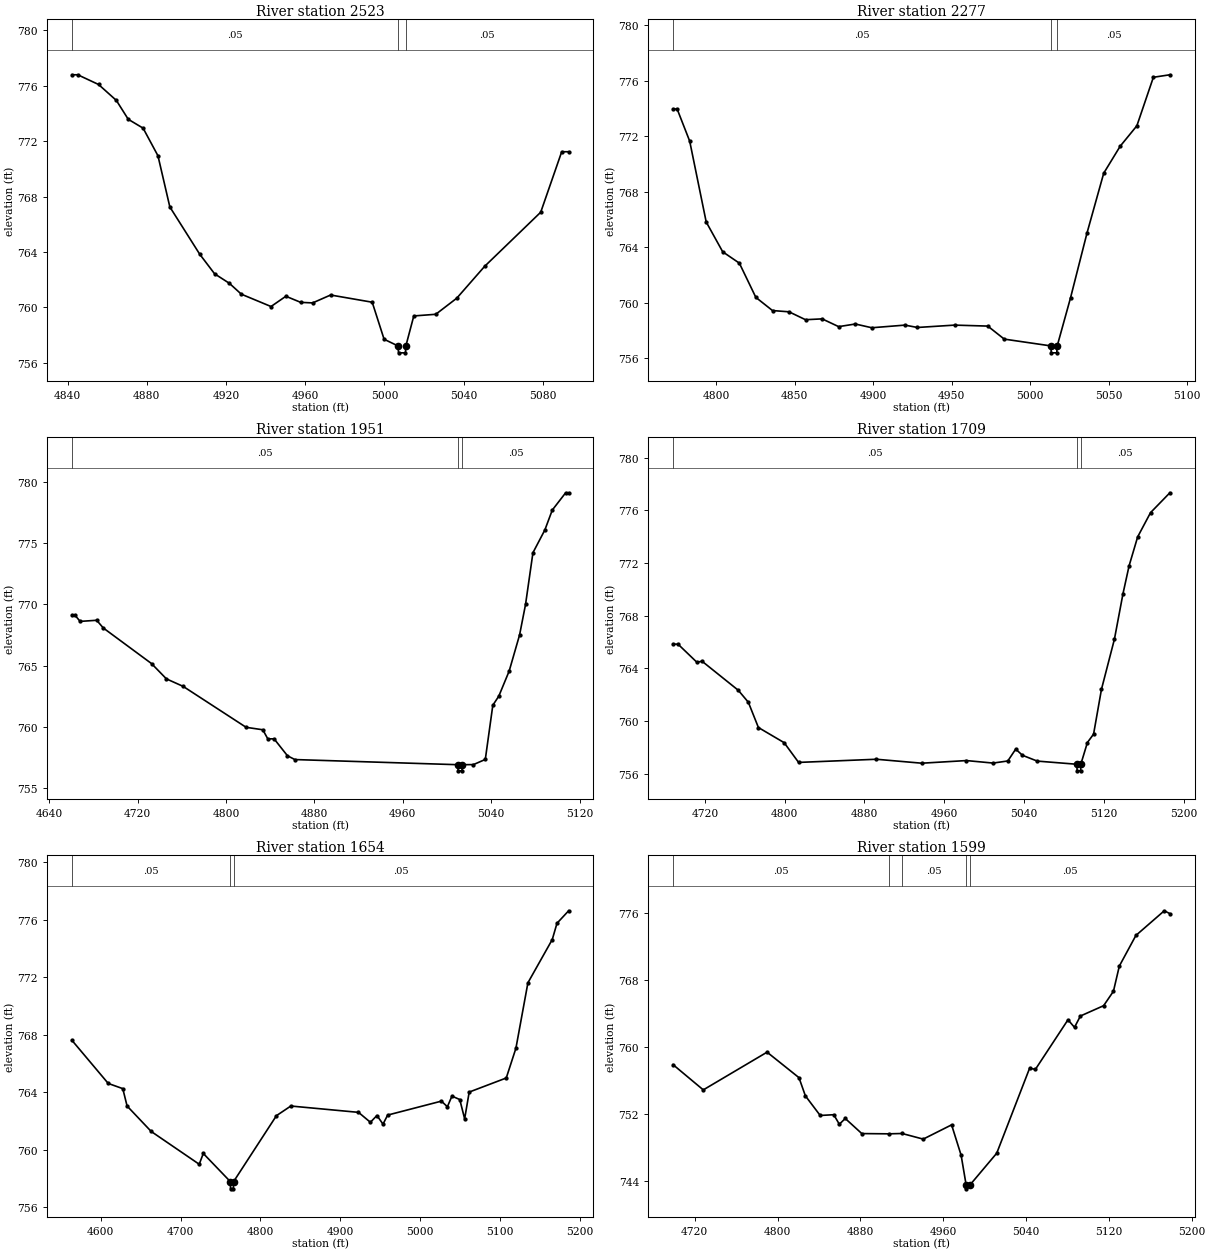
Type RM Length L Ch R = 1,2523,246,246,246
BEGIN DESCRIPTION:
MDW T 116 6.0
END DESCRIPTION:
XS GIS Cut Line= 3
      2298128.96      7135009.97      2297979.00      7134910.00
      2297929.03      7134860.03
#Sta/Elev= 30
  4842.1  776.78  4845.1  776.78  4855.6  776.08  4864.6  774.93  4870.6  773.57
  4878.1  772.93  4885.6  770.94  4891.6  767.25  4906.7  763.84  4914.2  762.43
  4921.7  761.74  4927.7  760.96  4942.7  760.07  4950.2  760.81  4957.7  760.37
  4963.7  760.33  4972.8  760.90  4993.8  760.38  4999.8  757.71  5006.8  757.23
  5007.1  756.73  5010.6  756.73  5010.8  757.23  5014.8  759.39  5025.9  759.51
  5036.5  760.67  5050.6  762.97  5078.9  766.87  5089.5  771.23  5093.0  771.23
#Mann=3,-1,0
  4842.1    0.05       0  5006.8   0.033       0  5010.8    0.05       0
Bank Sta=5006.8,5010.8
Exp/Cntr=0.3,0.1

Type RM Length L Ch R = 1,2277,326,326,326
BEGIN DESCRIPTION:
MDW T 116 5.0
END DESCRIPTION:
XS GIS Cut Line= 3
      2298229.00      7134910.01      2298179.00      7134760.00
      2298029.04      7134710.01
#Sta/Elev= 30
  4772.7  773.96  4775.3  773.96  4783.3  771.64  4793.8  765.81  4804.3  763.66
  4814.9  762.84  4825.4  760.37  4836.0  759.42  4846.5  759.33  4857.0  758.76
  4867.6  758.82  4878.1  758.26  4888.7  758.45  4899.2  758.18  4920.3  758.37
  4928.2  758.20  4951.9  758.37  4973.0  758.30  4983.5  757.36  5013.2  756.87
  5013.4  756.37  5016.9  756.37  5017.2  756.87  5025.7  760.35  5036.2  765.03
  5046.8  769.33  5057.3  771.28  5067.9  772.75  5078.4  776.25  5088.9  776.43
#Mann=3,-1,0
  4772.7    0.05       0  5013.2   0.033       0  5017.2    0.05       0
Bank Sta=5013.2,5017.2
Exp/Cntr=0.3,0.1

Type RM Length L Ch R = 1,1951,242,242,242
BEGIN DESCRIPTION:
MDW T 116 4.0
END DESCRIPTION:
XS GIS Cut Line= 3
      2298479.00      7134710.00      2298379.00      7134560.00
      2298129.04      7134460.02
#Sta/Elev= 30
  4660.5  769.11  4663.5  769.11  4668.0  768.62  4683.0  768.71  4689.0  768.08
  4732.6  765.18  4746.1  763.93  4761.2  763.32  4818.2  759.98  4833.3  759.78
  4837.8  759.04  4843.5  759.04  4855.6  757.66  4862.3  757.35  5009.8  756.93
  5010.0  756.43  5013.5  756.43  5013.8  756.93  5023.9  756.94  5034.6  757.36
  5041.4  761.78  5046.8  762.52  5056.2  764.57  5065.6  767.51  5071.0  770.00
  5077.7  774.22  5088.5  776.08  5095.2  777.70  5107.3  779.11  5110.0  779.11
#Mann=3,-1,0
  4660.5    0.05       0  5009.8   0.033       0  5013.8    0.05       0
Bank Sta=5009.8,5013.8
Exp/Cntr=0.3,0.1

Type RM Length L Ch R = 1,1709,55,55,55
BEGIN DESCRIPTION:
Mapping XS 9e2e03a5
END DESCRIPTION:
XS GIS Cut Line= 4
      2298497.30      7134614.96      2298480.99      7134478.57
      2298403.42      7134335.06      2298288.50      7134174.19
#Sta/Elev= 30
  4688.1  765.84  4693.1  765.84  4712.1  764.46  4717.1  764.55  4753.5  762.34
  4763.6  761.43  4773.7  759.51  4799.5  758.36  4814.0  756.86  4892.0  757.10
  4937.5  756.80  4982.3  757.00  5009.0  756.81  5023.8  756.97  5031.7  757.87
  5038.5  757.40  5053.3  756.96  5093.0  756.72  5093.3  756.22  5096.8  756.22
  5097.0  756.72  5103.6  758.37  5109.8  759.01  5117.7  762.41  5130.7  766.22
  5139.3  769.68  5145.4  771.79  5154.0  773.99  5166.9  775.83  5186.3  777.34
#Mann=3,-1,0
  4688.1    0.05       0  5093.0   0.033       0  5097.0    0.05       0
Bank Sta=5093,5097
Exp/Cntr=0.3,0.1

Type RM Length L Ch R = 1,1654,55,55,55
BEGIN DESCRIPTION:
Mapping XS e89d238c
END DESCRIPTION:
XS GIS Cut Line= 6
      2298498.00      7134681.41      2298546.86      7134566.82
      2298540.86      7134487.29      2298511.55      7134422.12
      2298393.73      7134216.57      2298335.20      7134124.28
#Sta/Elev= 30
  4563.8  767.63  4609.4  764.62  4627.6  764.26  4633.0  763.05  4663.2  761.28
  4723.3  759.00  4728.4  759.75  4762.3  757.79  4762.5  757.29  4766.0  757.29
  4766.3  757.79  4820.0  762.38  4838.0  763.05  4922.7  762.61  4937.6  761.92
  4945.8  762.39  4953.4  761.79  4959.2  762.42  5026.5  763.39  5034.0  763.00
  5039.7  763.74  5049.5  763.50  5055.6  762.16  5061.3  764.02  5107.7  765.00
  5119.8  767.07  5134.8  771.62  5165.3  774.63  5171.2  775.76  5185.8  776.63
#Mann=3,-1,0
  4563.8    0.05       0  4762.3   0.033       0  4766.3    0.05       0
Bank Sta=4762.3,4766.3
Exp/Cntr=0.3,0.1

Type RM Length L Ch R = 1,1599,237,237,237
BEGIN DESCRIPTION:
Mapping XS b34dc12b
END DESCRIPTION:
XS GIS Cut Line= 3
      2298573.24      7134518.40      2298538.01      7134367.25
      2298379.16      7134084.18
#Sta/Elev= 30
  4699.1  757.86  4728.3  754.85  4789.9  759.35  4820.7  756.31  4826.9  754.14
  4841.2  751.80  4854.3  751.89  4859.7  750.75  4865.4  751.44  4881.4  749.64
  4907.4  749.61  4920.3  749.65  4940.7  748.98  4968.1  750.68  4977.3  747.06
  4982.1  743.55  4982.3  743.05  4986.1  743.55  5011.7  747.30  5043.4  757.42
  5049.1  757.31  5080.5  763.21  5086.8  762.31  5092.5  763.66  5114.9  764.89
  5124.4  766.61  5130.1  769.62  5146.1  773.27  5173.5  776.21  5178.9  775.87
#Mann=5,-1,0
  4699.1    0.05       0  4907.4    0.12       0  4920.3    0.05       0
  4982.1   0.033       0  4986.1    0.05       0
Bank Sta=4982.1,4986.1
Exp/Cntr=0.3,0.1

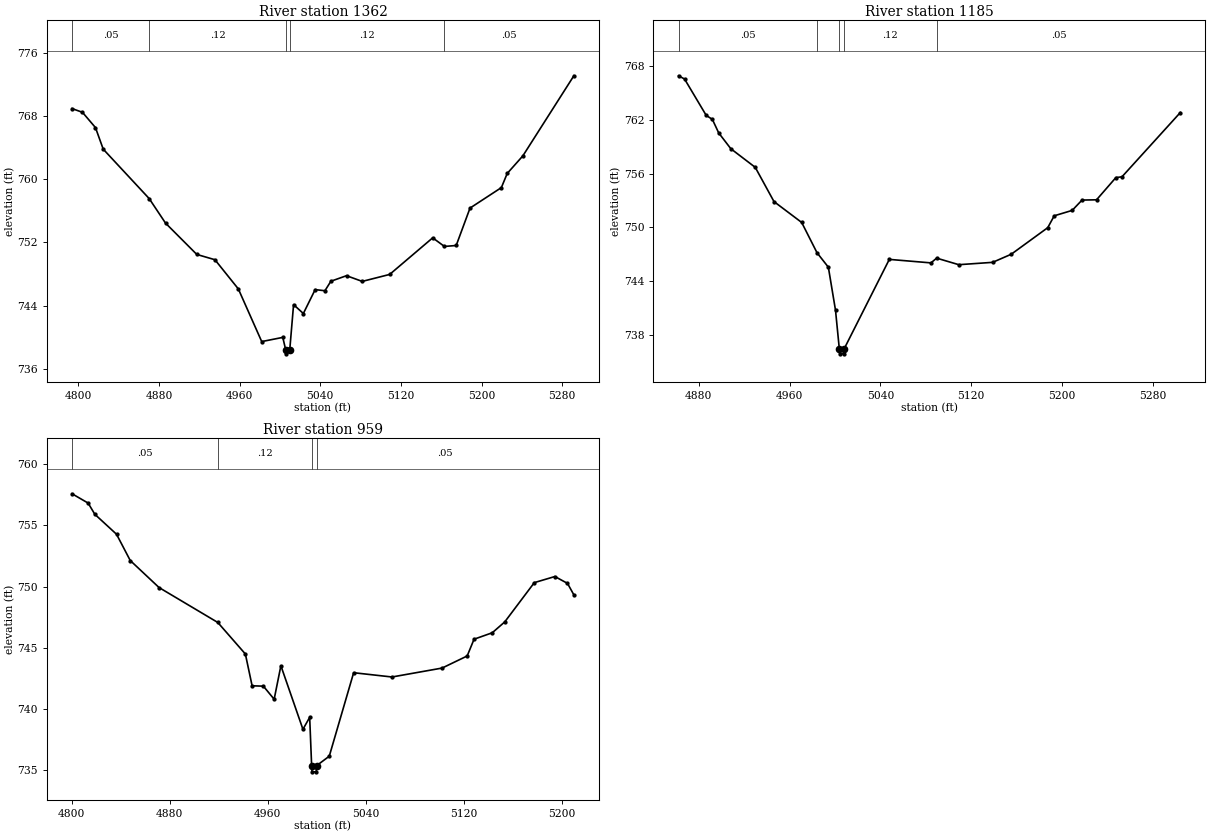
Type RM Length L Ch R = 1,1362,177,177,177
BEGIN DESCRIPTION:
MDW T 116 2.0
END DESCRIPTION:
XS GIS Cut Line= 3
      2298878.96      7134259.99      2298679.00      7134210.00
      2298428.97      7134059.98
#Sta/Elev= 30
  4793.8  768.93  4804.1  768.46  4817.0  766.53  4824.7  763.80  4870.3  757.55
  4886.5  754.45  4917.5  750.49  4935.5  749.82  4958.7  746.13  4981.9  739.47
  5002.8  740.00  5005.7  738.42  5005.9  737.92  5009.7  738.42  5013.5  744.14
  5023.2  743.02  5034.9  746.04  5044.6  745.90  5050.5  747.10  5066.0  747.80
  5081.6  747.08  5108.8  747.96  5151.5  752.59  5163.1  751.50  5174.8  751.62
  5188.5  756.35  5219.6  758.94  5225.4  760.73  5240.9  762.95  5291.5  773.08
#Mann=5,-1,0
  4793.8    0.05       0  4870.3    0.12       0  5005.7    0.07       0
  5009.7    0.12       0  5163.1    0.05       0
Bank Sta=5005.7,5009.7
Exp/Cntr=0.3,0.1

Type RM Length L Ch R = 1,1185,226,226,226
BEGIN DESCRIPTION:
Mapping XS bcbc1005
END DESCRIPTION:
XS GIS Cut Line= 2
      2298921.92      7134145.79      2298510.25      7133984.62
#Sta/Elev= 30
  4862.1  766.88  4867.4  766.52  4886.5  762.47  4891.9  762.03  4897.5  760.52
  4908.2  758.76  4929.7  756.69  4946.2  752.88  4970.6  750.56  4984.1  747.19
  4994.1  745.58  5000.4  740.79  5003.8  736.44  5004.1  735.94  5007.6  735.94
  5007.8  736.44  5047.8  746.45  5084.5  746.06  5089.5  746.59  5109.0  745.86
  5138.8  746.12  5155.2  747.02  5187.4  749.98  5193.1  751.30  5208.9  751.90
  5217.6  753.05  5230.4  753.08  5247.4  755.55  5252.8  755.64  5304.2  762.79
#Mann=5,-1,0
  4862.1    0.05       0  4984.1    0.12       0  5003.8    0.07       0
  5007.8    0.12       0  5089.5    0.05       0
Bank Sta=5003.8,5007.8
Exp/Cntr=0.3,0.1

Type RM Length L Ch R = 1,959,0,0,0
BEGIN DESCRIPTION:
MDW T 116 1.0
END DESCRIPTION:
XS GIS Cut Line= 3
      2299012.35      7133961.82      2298827.83      7133882.08
      2298623.88      7133837.83
#Sta/Elev= 30
  4800.3  757.59  4813.4  756.83  4818.9  755.91  4836.6  754.28  4847.8  752.13
  4871.3  749.92  4919.3  747.06  4941.8  744.48  4947.3  741.88  4956.5  741.85
  4965.3  740.78  4970.8  743.52  4988.8  738.32  4994.3  739.30  4995.9  735.34
  4996.2  734.84  4999.7  734.84  4999.9  735.34  5010.3  736.12  5030.2  742.95
  5061.5  742.60  5102.4  743.33  5122.9  744.32  5128.5  745.69  5143.4  746.22
  5153.6  747.11  5177.7  750.32  5194.5  750.82  5204.8  750.26  5210.0  749.32
#Mann=4,-1,0
  4800.3    0.05       0  4919.3    0.12       0  4995.9   0.033       0
  4999.9    0.05       0
Bank Sta=4995.9,4999.9
Exp/Cntr=0.3,0.1

Chan Stop Cuts=-1