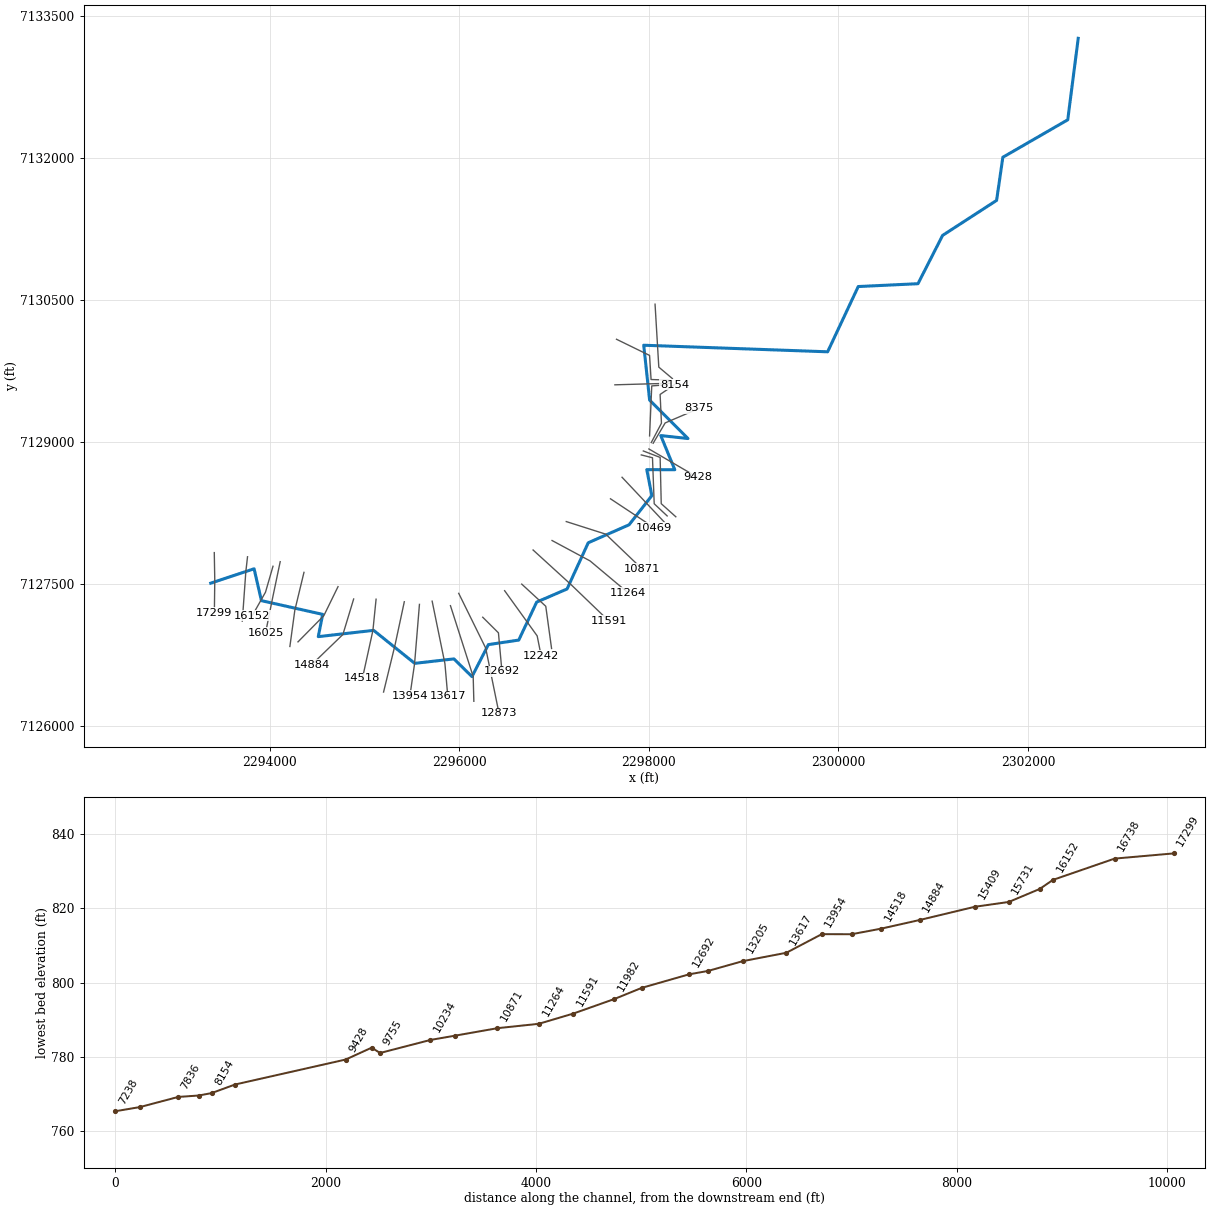
--- MDW T 117.prj (project) ---

Proj Title=MDW T 117 Base Level Engineering
Current Plan=p01
Default Exp/Contr=0.3,0.1
English Units
Geom File=g01
Flow File=f01
Plan File=p01
BEGIN DESCRIPTION:
MDW T 117
END DESCRIPTION:

--- MDW T 117.p01 (plan) ---

Plan Title=Multiple Run
Short Identifier=Multiple
Geom File=g01
Flow File=f01
Subcritical Flow
K Sum by GR= 0
Std Step Tol= 0.01
Critical Tol= 0.01
Num of Std Step Trials= 20
Max Error Tol= 0.3
Flow Tol Ratio= 0.001
Split Flow NTrial= 30
Split Flow Tol= 0.02
Split Flow Ratio= 0.02
Log Output Level= 0
Friction Slope Method= 1
Unsteady Friction Slope Method= 2
Unsteady Bridges Friction Slope Method= 1
Parabolic Critical Depth
Global Vel Dist=  1 , 1 , 1
Global Log Level= 0
CheckData=True
Encroach Param= -1, 0, 0, 0
BEGIN DESCRIPTION:
Multiple Run
END DESCRIPTION:

--- MDW T 117.f01 (steady flow) ---

Flow Title=Multiple
Number of Profiles=7
Profile Names=10-year,25-year,50-year,1pct_min,100-year,1pct_plu,500-year
River Rch & RM= MDW T 117,Reach-1,17299
     681     946    1167     716    1428    2850    2143
River Rch & RM= MDW T 117,Reach-1,11982
    1094    1549    1937    1201    2397    4782    3677
River Rch & RM= MDW T 117,Reach-1,4596
    1154    1637    2050    1273    2539    5066    3905
Boundary for River Rch & Prof#=MDW T 117,Reach-1,1
Up Type=0
Dn Type=3
Dn Slope=0.005
Boundary for River Rch & Prof#=MDW T 117,Reach-1,2
Up Type=0
Dn Type=3
Dn Slope=0.005
Boundary for River Rch & Prof#=MDW T 117,Reach-1,3
Up Type=0
Dn Type=3
Dn Slope=0.005
Boundary for River Rch & Prof#=MDW T 117,Reach-1,4
Up Type=0
Dn Type=3
Dn Slope=0.005
Boundary for River Rch & Prof#=MDW T 117,Reach-1,5
Up Type=0
Dn Type=3
Dn Slope=0.005
Boundary for River Rch & Prof#=MDW T 117,Reach-1,6
Up Type=0
Dn Type=3
Dn Slope=0.005
Boundary for River Rch & Prof#=MDW T 117,Reach-1,7
Up Type=0
Dn Type=3
Dn Slope=0.005

--- MDW T 117.g01 (geometry) ---

Geom Title=Existing Conditions

River Reach=MDW T 117,Reach-1
Reach XY= 30
      2293379.00      7127510.00      2293836.30      7127661.70
      2293913.61      7127325.23      2294559.79      7127180.58
      2294513.09      7126945.51      2295097.02      7127011.80
      2295530.50      7126663.61      2295943.90      7126710.73
      2296134.43      7126523.71      2296307.47      7126861.41
      2296627.96      7126909.30      2296816.90      7127310.16
      2297137.56      7127448.60      2297360.89      7127936.42
      2297791.32      7128125.85      2298031.92      7128434.08
      2297978.37      7128707.79      2298273.65      7128707.23
      2298125.79      7129067.55      2298412.88      7129036.37
      2298008.35      7129441.65      2297946.15      7130021.02
      2299885.81      7129951.74      2300208.83      7130640.40
      2300838.82      7130670.47      2301098.61      7131180.16
      2301668.06      7131549.56      2301734.03      7132004.93
      2302418.53      7132400.18      2302529.00      7133260.00

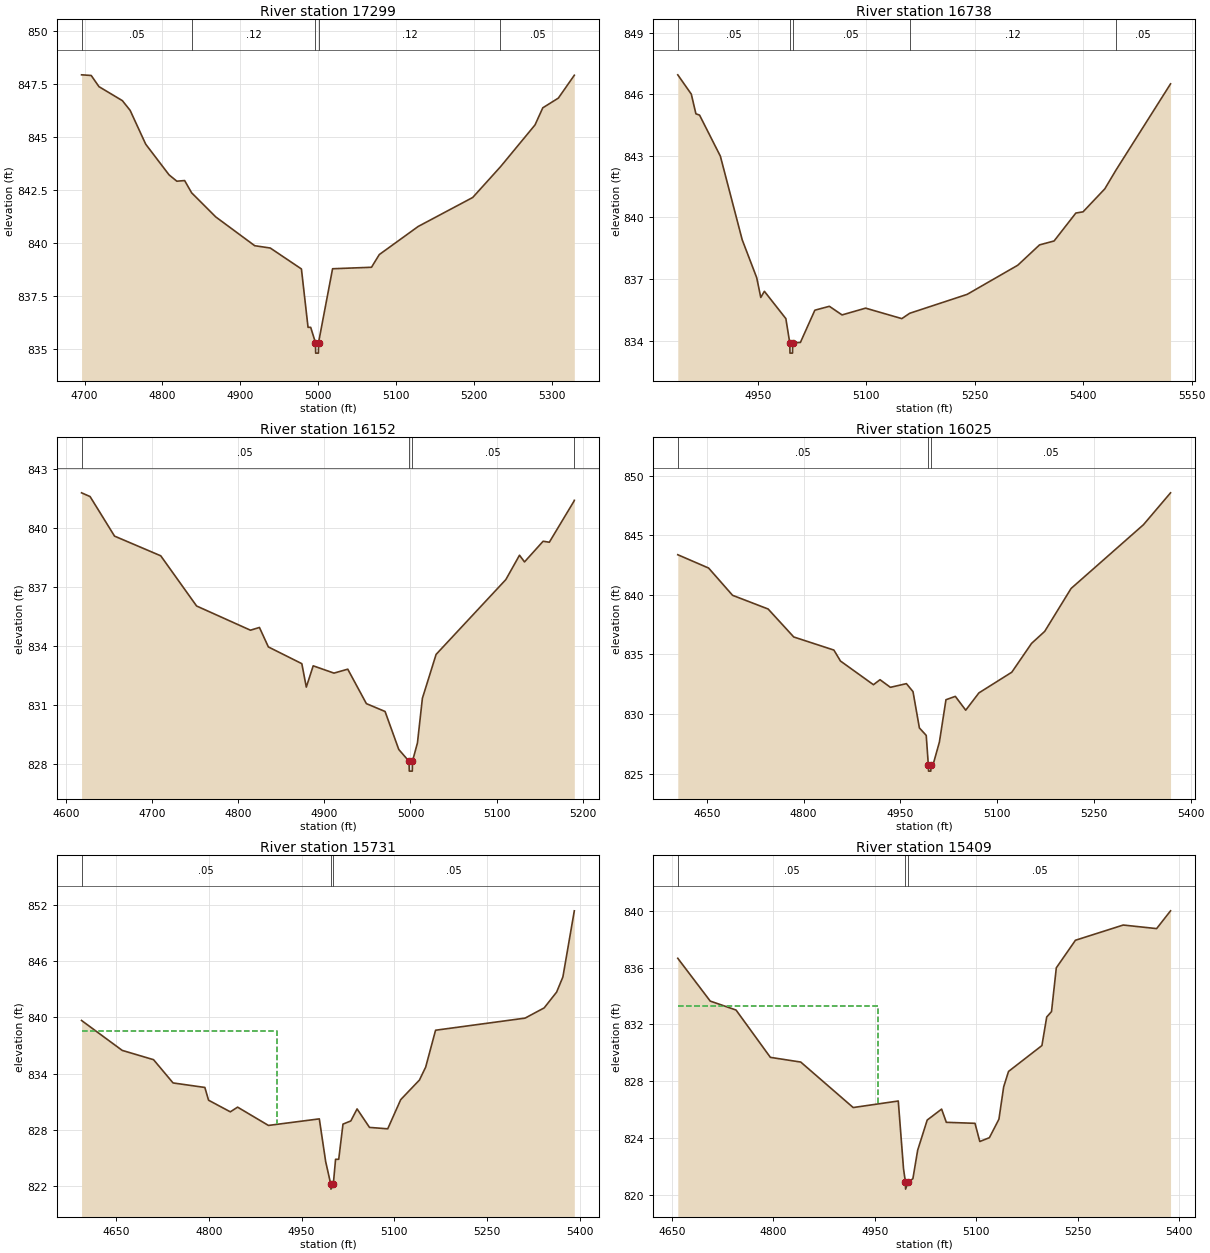
Type RM Length L Ch R = 1,17299,561,561,561
BEGIN DESCRIPTION:
MDW T 117 35.0
END DESCRIPTION:
XS GIS Cut Line= 3
      2293416.37      7127832.36      2293421.57      7127538.08
      2293417.23      7127199.54
#Sta/Elev= 30
  4696.1  847.95  4708.5  847.92  4718.5  847.39  4748.5  846.73  4758.5  846.27
  4778.5  844.67  4808.5  843.22  4818.5  842.92  4828.5  842.95  4837.5  842.37
  4868.5  841.23  4918.5  839.87  4938.5  839.76  4978.5  838.77  4987.0  836.01
  4990.4  836.01  4996.5  835.29  4996.8  834.79  5000.3  834.79  5000.5  835.29
  5018.5  838.78  5068.5  838.85  5078.5  839.45  5128.5  840.78  5198.5  842.15
  5234.1  843.60  5278.5  845.58  5288.5  846.39  5308.5  846.85  5329.0  847.93
#Mann=5,-1,0
  4696.1    0.05       0  4837.5    0.12       0  4996.5    0.07       0
  5000.5    0.12       0  5234.1    0.05       0
Bank Sta=4996.5,5000.5
Exp/Cntr=0.3,0.1

Type RM Length L Ch R = 1,16738,586,586,586
BEGIN DESCRIPTION:
MDW T 117 34.0
END DESCRIPTION:
XS GIS Cut Line= 3
      2293766.99      7127788.54      2293749.04      7127630.22
      2293711.65      7127109.29
#Sta/Elev= 30
  4839.2  846.94  4857.9  846.00  4864.3  845.04  4869.3  844.98  4898.1  842.98
  4928.3  838.91  4948.4  837.06  4954.0  836.10  4959.0  836.40  4988.7  835.07
  4994.1  833.89  4994.4  833.39  4997.9  833.39  4998.1  833.89  5008.8  833.91
  5028.8  835.48  5048.9  835.67  5066.4  835.25  5099.0  835.58  5149.1  835.07
  5160.0  835.33  5239.4  836.25  5309.5  837.67  5339.6  838.66  5359.7  838.85
  5389.8  840.21  5399.8  840.27  5429.9  841.39  5445.3  842.30  5520.8  846.50
#Mann=5,-1,0
  4839.2    0.05       0  4994.1   0.033       0  4998.1    0.05       0
  5160.0    0.12       0  5445.3    0.05       0
Bank Sta=4994.1,4998.1
Exp/Cntr=0.3,0.1

Type RM Length L Ch R = 1,16152,127,127,127
BEGIN DESCRIPTION:
Mapping XS 24a0d72b
END DESCRIPTION:
XS GIS Cut Line= 3
      2294035.68      7127688.27      2293956.60      7127414.80
      2293815.55      7127164.71
#Sta/Elev= 30
  4618.3  841.80  4628.2  841.61  4656.6  839.60  4710.2  838.60  4751.8  836.05
  4814.3  834.82  4824.7  834.96  4835.1  833.97  4873.9  833.12  4879.1  831.93
  4887.1  833.01  4911.2  832.64  4927.2  832.84  4948.8  831.09  4970.5  830.69
  4986.4  828.76  4998.3  828.16  4998.6  827.66  5002.1  827.66  5002.3  828.16
  5008.1  829.10  5013.8  831.36  5029.7  833.59  5110.6  837.39  5126.5  838.63
  5132.3  838.29  5153.9  839.34  5161.1  839.29  5189.5  841.36  5190.1  841.42
#Mann=4,-1,0
  4618.3    0.05       0  4998.3   0.033       0  5002.3    0.05       0
  5189.5    0.12       0
Bank Sta=4998.3,5002.3
Exp/Cntr=0.3,0.1

Type RM Length L Ch R = 1,16025,294,294,294
BEGIN DESCRIPTION:
MDW T 117 33.0
END DESCRIPTION:
XS GIS Cut Line= 3
      2294111.69      7127736.79      2294031.65      7127354.54
      2293957.96      7126988.83
#Sta/Elev= 30
  4605.1  843.38  4652.9  842.26  4690.0  839.97  4745.1  838.82  4784.8  836.47
  4847.0  835.37  4857.2  834.45  4908.3  832.46  4918.5  832.88  4934.6  832.24
  4959.4  832.55  4969.6  831.88  4979.5  828.83  4990.1  828.20  4993.4  825.70
  4993.7  825.20  4997.2  825.20  4997.4  825.70  5000.5  825.70  5010.5  827.64
  5020.7  831.20  5035.2  831.48  5051.3  830.32  5071.7  831.77  5122.7  833.51
  5153.3  835.93  5173.7  836.94  5214.5  840.54  5326.7  845.90  5368.7  848.58
#Mann=3,-1,0
  4605.1    0.05       0  4993.4   0.033       0  4997.4    0.05       0
Bank Sta=4993.4,4997.4
Exp/Cntr=0.3,0.1

Type RM Length L Ch R = 1,15731,322,322,322
BEGIN DESCRIPTION:
MDW T 117 32.0
END DESCRIPTION:
XS GIS Cut Line= 3
      2294362.35      7127623.97      2294265.86      7127223.79
      2294213.84      7126841.67
#Sta/Elev= 30
  4594.0  839.68  4659.8  836.49  4710.5  835.50  4742.1  833.02  4793.5  832.54
  4799.5  831.18  4834.7  829.94  4846.5  830.44  4896.4  828.49  4978.7  829.19
  4989.0  824.63  4997.3  822.20  4997.5  821.70  5001.3  822.20  5005.0  824.88
  5010.1  824.88  5017.0  828.63  5029.7  828.97  5039.8  830.25  5059.9  828.28
  5089.4  828.13  5110.4  831.24  5140.7  833.33  5150.8  834.71  5166.8  838.64
  5311.6  839.93  5342.5  841.02  5362.7  842.71  5372.8  844.32  5391.3  851.37
#Mann=3,-1,0
  4594.0    0.05       0  4997.3   0.033       0  5001.3    0.05       0
#XS Ineff=2,0
    0.00 4909.60  838.53               0
Permanent Ineff=
       F       F
Bank Sta=4997.3,5001.3
Exp/Cntr=0.3,0.1

Type RM Length L Ch R = 1,15409,525,525,525
BEGIN DESCRIPTION:
MDW T 117 31.0
END DESCRIPTION:
XS GIS Cut Line= 3
      2294721.50      7127473.14      2294571.68      7127166.38
      2294299.44      7126890.48
#Sta/Elev= 30
  4658.6  836.65  4706.6  833.64  4744.8  833.01  4795.6  829.68  4840.5  829.35
  4918.1  826.15  4984.8  826.61  4992.6  821.82  4995.4  820.91  4995.6  820.41
  4999.4  820.91  5006.4  821.14  5013.5  823.15  5027.6  825.27  5048.9  826.04
  5055.9  825.11  5098.3  825.04  5105.4  823.76  5119.6  824.03  5133.7  825.33
  5140.7  827.60  5147.9  828.69  5197.3  830.51  5204.4  832.52  5211.5  832.90
  5218.6  835.98  5246.9  837.92  5317.6  838.99  5367.0  838.74  5387.6  839.99
#Mann=3,-1,0
  4658.6    0.05       0  4995.4   0.033       0  4999.4    0.05       0
#XS Ineff=2,0
    0.00 4954.60  833.28               0
Permanent Ineff=
       F       F
Bank Sta=4995.4,4999.4
Exp/Cntr=0.3,0.1

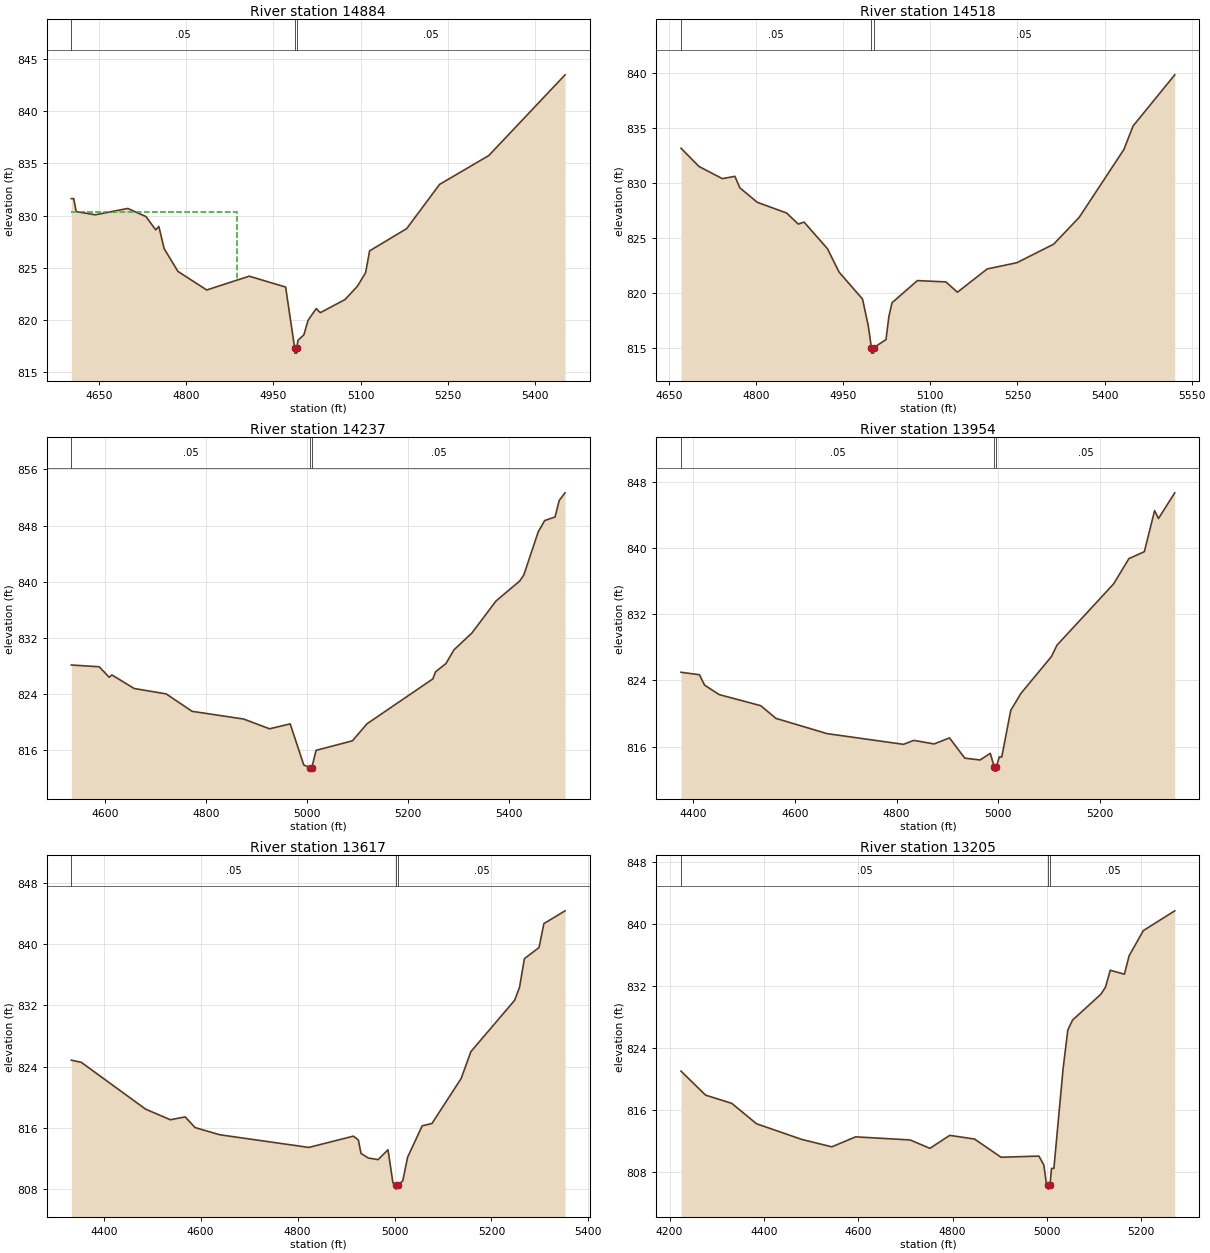
Type RM Length L Ch R = 1,14884,366,366,366
BEGIN DESCRIPTION:
MDW T 117 30.0
END DESCRIPTION:
XS GIS Cut Line= 3
      2294886.42      7127342.90      2294772.96      7126968.10
      2294443.87      7126649.71
#Sta/Elev= 30
  4602.3  831.62  4606.4  831.62  4610.6  830.38  4643.5  830.07  4699.4  830.68
  4730.7  829.90  4747.5  828.63  4752.8  828.96  4762.0  826.83  4785.7  824.66
  4835.2  822.88  4908.3  824.20  4971.0  823.16  4986.5  817.34  4986.8  816.84
  4990.3  816.84  4990.5  817.34  4992.1  818.06  5002.4  818.59  5009.6  819.98
  5023.7  821.10  5030.7  820.71  5073.1  821.96  5094.4  823.23  5108.6  824.53
  5115.5  826.62  5179.3  828.75  5235.9  832.98  5320.6  835.74  5451.8  843.46
#Mann=3,-1,0
  4602.3    0.05       0  4986.5   0.033       0  4990.5    0.05       0
#XS Ineff=2,0
    0.00 4887.80  830.35               0
Permanent Ineff=
       F       F
Bank Sta=4986.5,4990.5
Exp/Cntr=0.3,0.1

Type RM Length L Ch R = 1,14518,281,281,281
BEGIN DESCRIPTION:
MDW T 117 29.0
END DESCRIPTION:
XS GIS Cut Line= 3
      2295122.98      7127340.76      2295089.54      7127010.56
      2294978.74      7126504.54
#Sta/Elev= 30
  4671.0  833.18  4701.9  831.52  4742.1  830.41  4763.7  830.62  4772.3  829.57
  4802.4  828.25  4852.7  827.28  4872.8  826.27  4882.8  826.45  4923.0  824.03
  4943.1  821.89  4983.4  819.44  4993.4  816.98  4998.7  815.01  4998.9  814.51
  5002.4  814.51  5002.7  815.01  5023.8  815.74  5028.9  817.87  5034.2  819.10
  5077.9  821.12  5126.9  821.00  5146.8  820.06  5198.0  822.18  5249.2  822.75
  5312.5  824.44  5356.4  826.88  5433.4  833.07  5449.2  835.21  5520.9  839.87
#Mann=3,-1,0
  4671.0    0.05       0  4998.7   0.033       0  5002.7    0.05       0
Bank Sta=4998.7,5002.7
Exp/Cntr=0.3,0.1

Type RM Length L Ch R = 1,14237,283,283,283
BEGIN DESCRIPTION:
MDW T 117 28.0
END DESCRIPTION:
XS GIS Cut Line= 3
      2295420.72      7127313.85      2295322.95      7126857.47
      2295201.97      7126360.73
#Sta/Elev= 30
  4533.1  828.13  4588.2  827.88  4608.2  826.38  4613.3  826.72  4657.7  824.78
  4721.1  824.01  4772.3  821.53  4874.5  820.43  4925.7  819.04  4966.6  819.74
  4993.5  813.89  5005.5  813.51  5005.8  813.01  5009.5  813.51  5017.8  815.97
  5089.9  817.33  5118.9  819.76  5249.2  826.15  5254.5  827.16  5275.1  828.33
  5290.9  830.28  5326.6  832.69  5374.3  837.25  5421.2  840.09  5429.5  840.97
  5457.8  847.07  5470.7  848.71  5491.3  849.22  5499.5  851.57  5511.1  852.66
#Mann=3,-1,0
  4533.1    0.05       0  5005.5   0.033       0  5009.5    0.05       0
Bank Sta=5005.5,5009.5
Exp/Cntr=0.3,0.1

Type RM Length L Ch R = 1,13954,337,337,337
BEGIN DESCRIPTION:
MDW T 117 27.0
END DESCRIPTION:
XS GIS Cut Line= 3
      2295580.44      7127286.08      2295529.00      7126660.00
      2295479.76      7126320.84
#Sta/Elev= 30
  4376.0  824.99  4412.2  824.69  4422.2  823.44  4451.0  822.29  4532.6  820.95
  4562.7  819.41  4663.0  817.57  4813.5  816.27  4833.6  816.75  4873.7  816.32
  4903.9  817.05  4934.0  814.60  4964.1  814.38  4984.1  815.18  4992.2  813.53
  4992.4  813.03  4995.9  813.03  4996.2  813.53  5001.7  814.74  5006.7  814.74
  5024.4  820.38  5044.6  822.45  5104.4  826.89  5115.3  828.27  5226.5  835.67
  5256.8  838.74  5287.1  839.58  5307.3  844.55  5314.9  843.59  5346.9  846.70
#Mann=3,-1,0
  4376.0    0.05       0  4992.2   0.033       0  4996.2    0.05       0
Bank Sta=4992.2,4996.2
Exp/Cntr=0.3,0.1

Type RM Length L Ch R = 1,13617,412,412,412
BEGIN DESCRIPTION:
MDW T 117 26.0
END DESCRIPTION:
XS GIS Cut Line= 3
      2295714.34      7127320.12      2295849.21      7126659.65
      2295879.27      7126316.47
#Sta/Elev= 30
  4333.2  824.83  4353.7  824.55  4486.5  818.44  4537.5  817.06  4568.1  817.43
  4588.5  816.04  4639.5  815.10  4823.2  813.45  4915.1  814.92  4925.3  814.43
  4930.8  812.67  4945.7  812.07  4966.1  811.86  4986.5  813.14  4996.7  808.83
  5002.6  808.51  5002.8  808.01  5006.6  808.51  5017.0  809.10  5027.0  812.18
  5057.1  816.27  5077.2  816.57  5137.4  822.44  5157.5  825.94  5247.9  832.65
  5257.9  834.34  5267.9  838.07  5298.1  839.52  5308.1  842.64  5351.8  844.31
#Mann=3,-1,0
  4333.2    0.05       0  5002.6   0.033       0  5006.6    0.05       0
Bank Sta=5002.6,5006.6
Exp/Cntr=0.3,0.1

Type RM Length L Ch R = 1,13205,332,332,332
BEGIN DESCRIPTION:
MDW T 117 25.0
END DESCRIPTION:
XS GIS Cut Line= 3
      2295907.48      7127272.41      2296147.28      7126523.92
      2296154.18      7126263.38
#Sta/Elev= 30
  4224.4  820.98  4276.4  817.89  4331.9  816.83  4384.4  814.20  4479.7  812.19
  4544.0  811.22  4594.5  812.51  4710.0  812.11  4752.0  811.03  4794.0  812.70
  4846.5  812.23  4902.8  809.88  4983.0  810.03  4993.5  808.88  4999.2  806.32
  5002.4  806.27  5002.7  805.77  5006.4  806.27  5009.8  808.44  5014.8  808.44
  5034.3  821.28  5044.3  826.28  5054.3  827.56  5114.3  830.89  5124.3  831.82
  5134.3  833.99  5164.3  833.48  5174.3  835.86  5204.4  839.10  5271.0  841.65
#Mann=3,-1,0
  4224.4    0.05       0  5002.4   0.033       0  5006.4    0.05       0
Bank Sta=5002.4,5006.4
Exp/Cntr=0.3,0.1

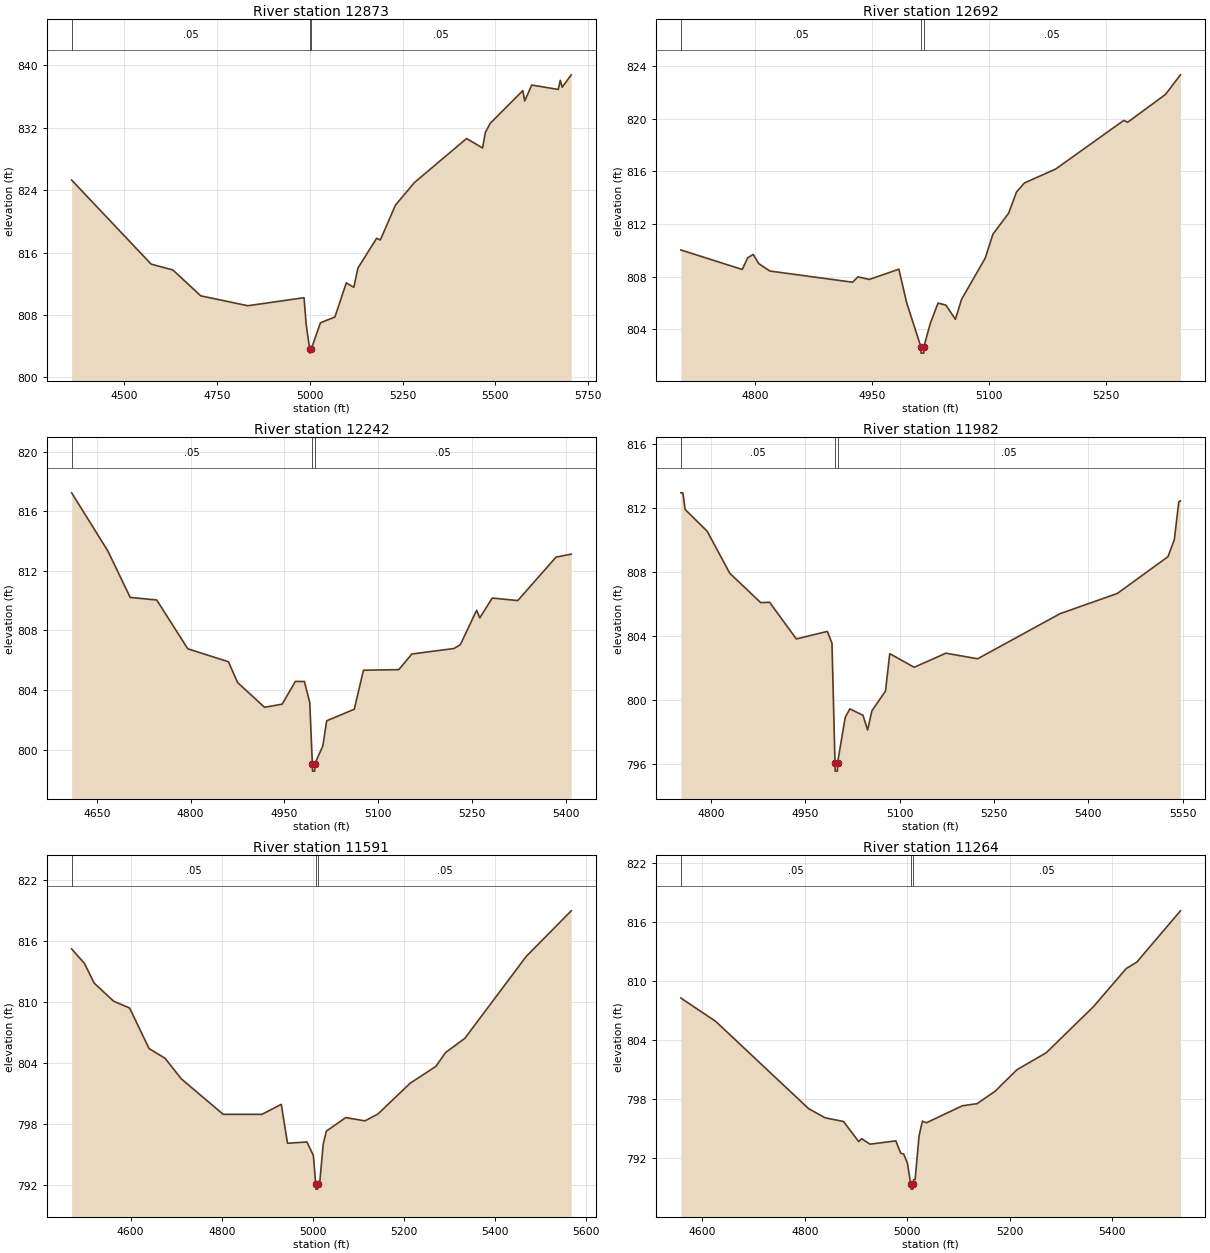
Type RM Length L Ch R = 1,12873,181,181,181
BEGIN DESCRIPTION:
MDW T 117 24.0
END DESCRIPTION:
XS GIS Cut Line= 3
      2295994.79      7127402.34      2296279.40      7126824.33
      2296419.78      7126135.68
#Sta/Elev= 30
  4357.8  825.29  4572.2  814.52  4630.6  813.78  4706.0  810.46  4832.8  809.19
  4984.5  810.22  4990.0  806.90  4999.7  803.62  5000.0  803.12  5003.7  803.62
  5028.6  807.00  5067.7  807.75  5098.4  812.12  5118.8  811.55  5129.7  814.01
  5180.2  817.83  5190.2  817.61  5231.0  822.08  5282.1  824.97  5422.7  830.61
  5465.8  829.40  5473.3  831.37  5486.2  832.54  5574.4  836.75  5579.5  835.42
  5598.4  837.46  5669.9  836.90  5675.5  838.07  5680.6  837.18  5704.9  838.77
#Mann=3,-1,0
  4357.8    0.05       0  4999.7   0.033       0  5003.7    0.05       0
Bank Sta=4999.7,5003.7
Exp/Cntr=0.3,0.1

Type RM Length L Ch R = 1,12692,450,450,450
BEGIN DESCRIPTION:
Mapping XS 5f7a5eac
END DESCRIPTION:
XS GIS Cut Line= 3
      2296248.12      7127150.24      2296413.54      7126985.69
      2296450.42      7126580.90
#Sta/Elev= 30
  4705.2  810.03  4783.8  808.55  4790.9  809.44  4797.9  809.69  4805.0  808.99
  4819.2  808.43  4925.2  807.58  4931.9  807.99  4946.4  807.79  4984.4  808.57
  4994.5  806.00  5012.5  802.70  5012.8  802.20  5016.3  802.20  5016.5  802.70
  5024.6  804.45  5034.6  806.00  5044.7  805.84  5056.8  804.77  5064.7  806.28
  5094.9  809.40  5104.9  811.23  5125.0  812.82  5135.0  814.42  5145.1  815.11
  5185.2  816.17  5272.4  819.86  5277.4  819.72  5325.8  821.83  5345.0  823.32
#Mann=3,-1,0
  4705.2    0.05       0  5012.5   0.033       0  5016.5    0.05       0
Bank Sta=5012.5,5016.5
Exp/Cntr=0.3,0.1

Type RM Length L Ch R = 1,12242,260,260,260
BEGIN DESCRIPTION:
Mapping XS 84aabd69
END DESCRIPTION:
XS GIS Cut Line= 3
      2296478.88      7127430.47      2296822.12      7126953.51
      2296863.54      7126746.13
#Sta/Elev= 30
  4609.7  817.25  4667.8  813.33  4703.4  810.22  4745.8  810.05  4795.5  806.77
  4860.5  805.90  4875.2  804.50  4918.3  802.84  4946.4  803.05  4967.6  804.58
  4982.0  804.57  4990.6  803.16  4994.7  799.05  4995.0  798.55  4998.5  798.55
  4998.7  799.05  5011.5  800.24  5017.6  801.93  5061.8  802.71  5076.5  805.33
  5133.0  805.37  5153.9  806.42  5221.3  806.79  5231.5  807.05  5257.5  809.36
  5262.6  808.85  5282.5  810.18  5323.3  810.01  5384.5  812.93  5408.8  813.13
#Mann=3,-1,0
  4609.7    0.05       0  4994.7   0.033       0  4998.7    0.05       0
Bank Sta=4994.7,4998.7
Exp/Cntr=0.3,0.1

Type RM Length L Ch R = 1,11982,391,391,391
BEGIN DESCRIPTION:
Mapping XS 0aeae713
END DESCRIPTION:
XS GIS Cut Line= 3
      2296659.33      7127499.89      2296912.80      7127266.10
      2296974.07      7126820.42
#Sta/Elev= 30
  4751.9  812.94  4755.1  812.94  4758.7  811.90  4793.8  810.54  4829.6  807.92
  4878.9  806.08  4893.1  806.10  4935.6  803.81  4984.9  804.28  4992.3  803.54
  4997.1  796.05  4997.4  795.55  5000.9  795.55  5001.1  796.05  5013.3  798.90
  5020.7  799.44  5041.6  799.04  5049.0  798.12  5055.8  799.32  5077.4  800.55
  5084.2  802.89  5123.1  802.04  5173.5  802.92  5224.0  802.57  5355.2  805.39
  5446.1  806.65  5526.8  808.95  5536.9  810.02  5544.0  812.38  5546.6  812.44
#Mann=3,-1,0
  4751.9    0.05       0  4997.1   0.033       0  5001.1    0.05       0
Bank Sta=4997.1,5001.1
Exp/Cntr=0.3,0.1

Type RM Length L Ch R = 1,11591,327,327,327
BEGIN DESCRIPTION:
MDW T 117 21.0
END DESCRIPTION:
XS GIS Cut Line= 3
      2296779.01      7127860.00      2297179.24      7127494.82
      2297579.02      7127109.98
#Sta/Elev= 30
  4470.5  815.19  4498.5  813.78  4520.1  811.83  4562.7  810.06  4597.8  809.39
  4640.4  805.42  4675.6  804.46  4711.3  802.44  4803.2  798.96  4888.4  798.96
  4930.7  799.94  4944.4  796.12  4987.0  796.25  5001.2  794.92  5006.3  792.12
  5006.8  791.62  5010.5  791.62  5010.9  792.12  5015.6  792.49  5022.7  796.01
  5029.6  797.31  5072.1  798.64  5114.5  798.32  5142.8  798.99  5213.6  802.01
  5270.2  803.67  5291.3  805.02  5333.7  806.42  5468.3  814.45  5567.2  818.93
#Mann=3,-1,0
  4470.5    0.05       0  5006.3   0.033       0  5010.9    0.05       0
Bank Sta=5006.3,5010.9
Exp/Cntr=0.3,0.1

Type RM Length L Ch R = 1,11264,393,393,393
BEGIN DESCRIPTION:
MDW T 117 20.0
END DESCRIPTION:
XS GIS Cut Line= 3
      2296979.00      7127960.00      2297379.77      7127744.91
      2297778.97      7127410.03
#Sta/Elev= 30
  4557.8  808.26  4625.9  805.89  4807.5  797.03  4839.6  796.11  4875.6  795.73
  4905.3  793.69  4911.0  793.99  4927.3  793.43  4977.7  793.77  4987.3  792.51
  4993.0  792.44  5000.4  791.50  5006.9  789.37  5007.4  788.87  5011.1  788.87
  5011.6  789.37  5012.5  789.84  5015.4  789.84  5023.1  794.27  5029.6  795.77
  5037.4  795.60  5107.7  797.33  5136.3  797.54  5171.4  798.79  5214.4  800.99
  5271.6  802.71  5363.9  807.39  5427.7  811.25  5448.5  811.91  5533.7  817.11
#Mann=3,-1,0
  4557.8    0.05       0  5006.9   0.033       0  5011.6    0.05       0
Bank Sta=5006.9,5011.6
Exp/Cntr=0.3,0.1

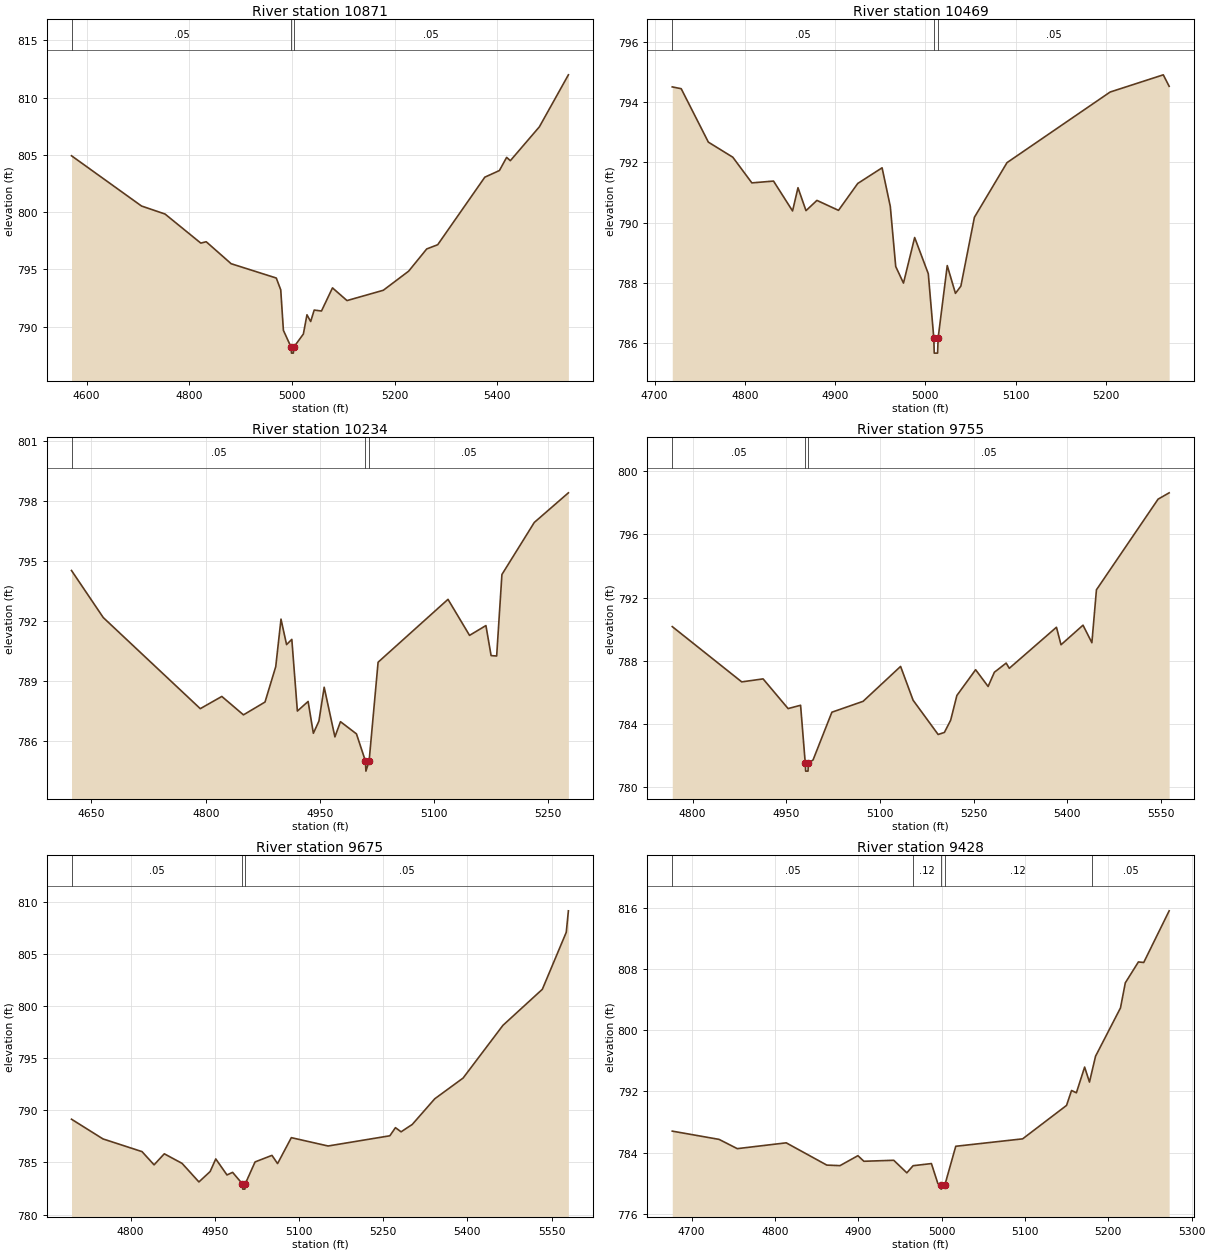
Type RM Length L Ch R = 1,10871,402,402,402
BEGIN DESCRIPTION:
MDW T 117 19.0
END DESCRIPTION:
XS GIS Cut Line= 3
      2297129.02      7128159.99      2297545.33      7128027.08
      2297929.00      7127660.00
#Sta/Elev= 30
  4570.6  804.93  4707.0  800.54  4752.8  799.84  4822.5  797.30  4833.0  797.42
  4881.6  795.50  4969.5  794.25  4978.2  793.22  4983.4  789.68  4998.6  788.19
  4999.1  787.69  5002.8  787.69  5003.3  788.19  5022.3  789.36  5029.3  791.04
  5036.5  790.45  5043.4  791.45  5057.6  791.37  5079.0  793.39  5107.3  792.28
  5178.0  793.18  5227.4  794.85  5262.6  796.79  5284.0  797.16  5375.8  803.06
  5404.2  803.64  5418.3  804.79  5425.5  804.50  5482.1  807.46  5538.6  812.00
#Mann=3,-1,0
  4570.6    0.05       0  4998.6   0.033       0  5003.3    0.05       0
Bank Sta=4998.6,5003.3
Exp/Cntr=0.3,0.1

Type RM Length L Ch R = 1,10469,235,235,235
BEGIN DESCRIPTION:
Mapping XS 9b7f3da0
END DESCRIPTION:
XS GIS Cut Line= 2
      2297595.43      7128400.30      2298054.43      7128096.19
#Sta/Elev= 30
  4719.6  794.50  4729.5  794.44  4759.6  792.67  4786.7  792.17  4807.8  791.32
  4831.8  791.38  4852.9  790.39  4858.9  791.16  4867.8  790.40  4879.9  790.74
  4903.8  790.41  4925.1  791.30  4952.1  791.82  4961.2  790.54  4967.2  788.55
  4975.8  788.00  4988.2  789.51  5003.3  788.31  5009.4  786.18  5009.9  785.68
  5013.6  785.68  5014.2  786.18  5024.3  788.58  5033.4  787.66  5039.4  787.90
  5054.4  790.18  5090.5  791.99  5204.8  794.33  5263.7  794.90  5270.2  794.52
#Mann=3,-1,0
  4719.6    0.05       0  5009.4   0.033       0  5014.2    0.05       0
Bank Sta=5009.4,5014.2
Exp/Cntr=0.3,0.1

Type RM Length L Ch R = 1,10234,479,479,479
BEGIN DESCRIPTION:
Mapping XS 0f5a0bea
END DESCRIPTION:
XS GIS Cut Line= 2
      2297717.51      7128627.54      2298164.78      7128152.45
#Sta/Elev= 30
  4623.8  794.54  4665.5  792.19  4792.9  787.64  4821.2  788.25  4849.6  787.33
  4877.9  787.97  4892.0  789.74  4898.9  792.11  4906.2  790.84  4913.1  791.10
  4920.4  787.52  4934.5  788.00  4941.4  786.41  4948.7  787.02  4955.6  788.71
  4969.7  786.23  4977.0  786.99  4998.0  786.38  5009.8  785.02  5010.4  784.52
  5014.6  785.02  5026.4  789.96  5118.2  793.10  5146.5  791.30  5168.0  791.79
  5174.8  790.29  5182.1  790.27  5189.0  794.34  5231.5  796.94  5276.3  798.42
#Mann=3,-1,0
  4623.8    0.05       0  5009.8   0.033       0  5014.6    0.05       0
Bank Sta=5009.8,5014.6
Exp/Cntr=0.3,0.1

Type RM Length L Ch R = 1,9755,80,80,80
BEGIN DESCRIPTION:
Mapping XS 31422a5f
END DESCRIPTION:
XS GIS Cut Line= 4
      2297920.27      7128863.36      2298038.50      7128833.40
      2298056.58      7128347.89      2298193.27      7128219.42
#Sta/Elev= 30
  4767.5  790.16  4878.7  786.66  4912.9  786.85  4952.9  784.97  4972.9  785.18
  4980.4  781.51  4981.0  781.01  4984.8  781.01  4985.4  781.51  4992.9  781.72
  5023.0  784.74  5073.0  785.43  5133.0  787.64  5153.0  785.50  5193.1  783.33
  5203.1  783.46  5213.1  784.23  5223.1  785.80  5253.1  787.43  5273.1  786.37
  5283.1  787.27  5302.0  787.85  5307.0  787.52  5382.5  790.12  5389.8  789.01
  5425.0  790.25  5439.2  789.14  5446.5  792.49  5545.2  798.23  5562.9  798.63
#Mann=3,-1,0
  4767.5    0.05       0  4980.4   0.033       0  4985.4    0.05       0
Bank Sta=4980.4,4985.4
Exp/Cntr=0.3,0.1

Type RM Length L Ch R = 1,9675,247,247,247
BEGIN DESCRIPTION:
Mapping XS e550715f
END DESCRIPTION:
XS GIS Cut Line= 4
      2297941.75      7128905.12      2298119.24      7128836.82
      2298130.80      7128348.66      2298284.52      7128210.45
#Sta/Elev= 30
  4694.8  789.15  4750.8  787.26  4820.4  786.04  4841.9  784.77  4860.1  785.83
  4891.8  784.91  4921.8  783.13  4941.8  784.13  4951.8  785.34  4971.8  783.80
  4981.8  784.05  4999.3  782.94  4999.9  782.44  5003.7  782.44  5004.3  782.94
  5021.8  785.05  5051.9  785.68  5061.9  784.89  5086.4  787.38  5151.9  786.58
  5261.9  787.56  5271.9  788.34  5281.9  787.94  5301.9  788.65  5341.9  791.11
  5392.4  793.10  5463.4  798.16  5533.6  801.62  5576.2  807.09  5580.0  809.15
#Mann=3,-1,0
  4694.8    0.05       0  4999.3   0.033       0  5004.3    0.05       0
Bank Sta=4999.3,5004.3
Exp/Cntr=0.3,0.1

Type RM Length L Ch R = 1,9428,1053,1053,1053
BEGIN DESCRIPTION:
Mapping XS d9e82df7
END DESCRIPTION:
XS GIS Cut Line= 2
      2298000.46      7128926.50      2298515.30      7128626.05
#Sta/Elev= 30
  4676.9  786.82  4733.1  785.74  4754.9  784.53  4813.6  785.29  4862.3  782.38
  4878.1  782.31  4899.6  783.61  4906.8  782.88  4942.6  783.01  4958.3  781.37
  4965.8  782.30  4987.8  782.58  4995.5  779.98  4998.8  779.74  4999.4  779.24
  5003.8  779.74  5017.0  784.84  5097.2  785.81  5149.9  790.18  5155.9  792.13
  5161.7  791.83  5171.6  795.19  5177.4  793.23  5180.4  794.62  5184.7  796.61
  5214.6  802.92  5220.4  806.20  5236.1  808.93  5242.5  808.86  5273.0  815.61
#Mann=5,-1,0
  4676.9    0.05       0  4965.8    0.12       0  4998.8    0.07       0
  5003.8    0.12       0  5180.4    0.05       0
Bank Sta=4998.8,5003.8
Exp/Cntr=0.3,0.1

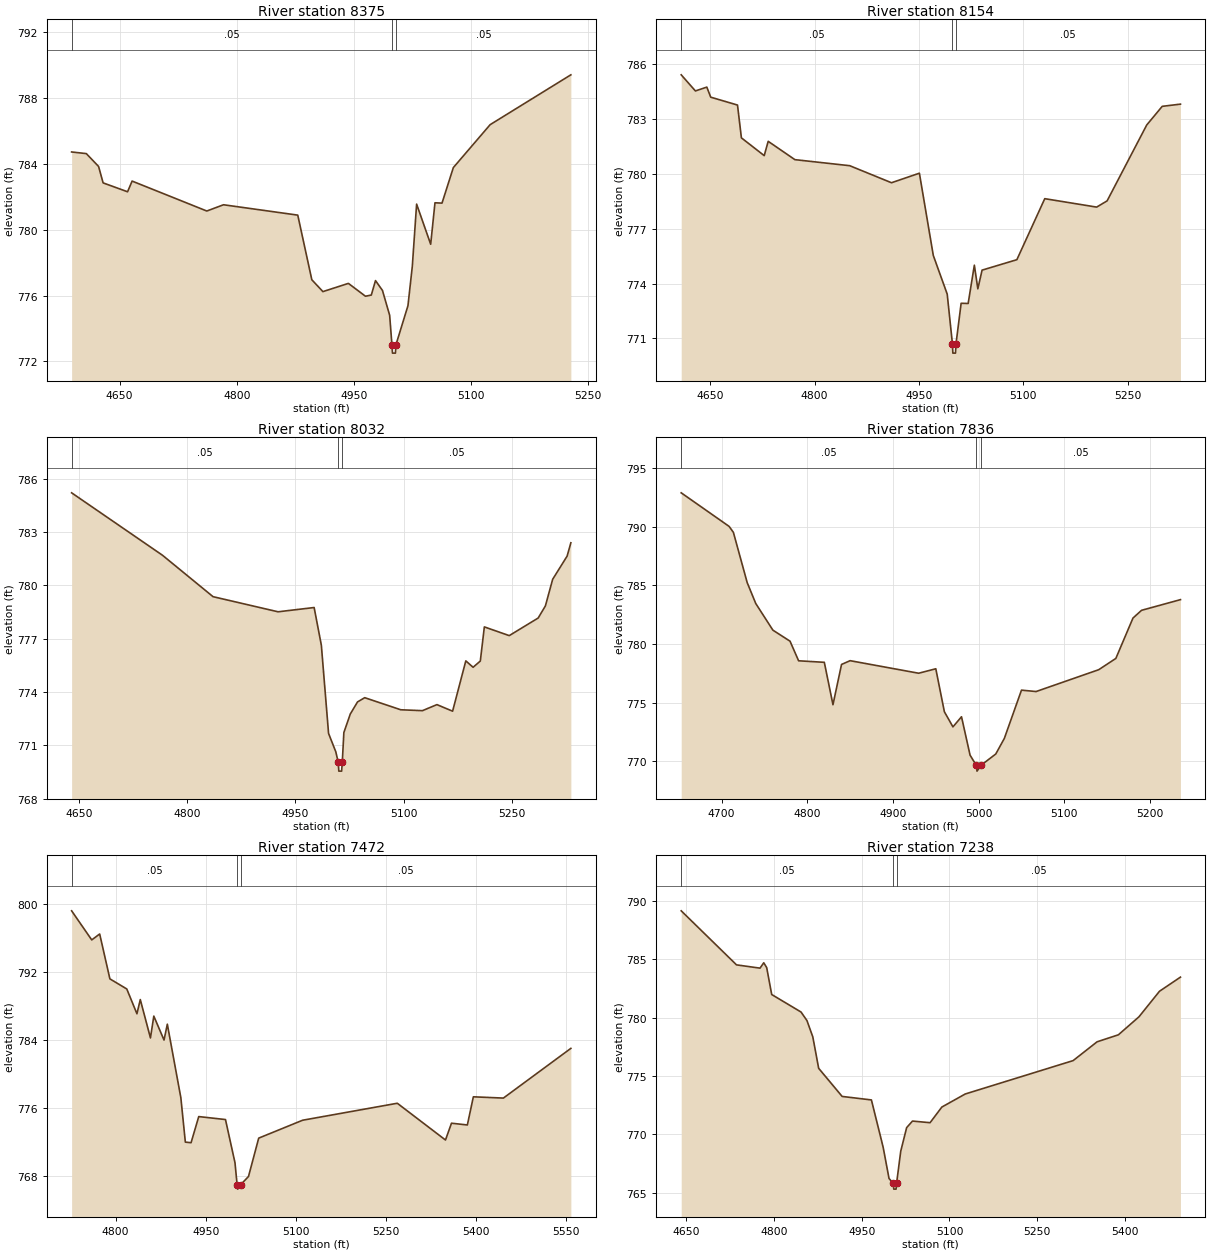
Type RM Length L Ch R = 1,8375,221,221,221
BEGIN DESCRIPTION:
Mapping XS 549f2899
END DESCRIPTION:
XS GIS Cut Line= 3
      2298045.65      7128986.68      2298172.26      7129200.99
      2298530.49      7129355.15
#Sta/Elev= 30
  4588.7  784.73  4607.5  784.63  4623.2  783.85  4629.0  782.85  4660.3  782.31
  4666.1  782.96  4761.7  781.14  4783.1  781.52  4878.1  780.89  4896.1  776.96
  4910.3  776.24  4942.9  776.74  4964.7  775.96  4972.2  776.03  4977.6  776.91
  4986.5  776.31  4995.7  774.80  4998.6  773.00  4999.3  772.50  5003.1  772.50
  5003.7  773.00  5019.1  775.38  5024.7  777.78  5030.2  781.56  5048.2  779.12
  5053.7  781.64  5062.7  781.62  5077.2  783.78  5124.3  786.39  5227.6  789.42
#Mann=3,-1,0
  4588.7    0.05       0  4998.6   0.033       0  5003.7    0.05       0
Bank Sta=4998.6,5003.7
Exp/Cntr=0.3,0.1

Type RM Length L Ch R = 1,8154,122,122,122
BEGIN DESCRIPTION:
Mapping XS 4079dce0
END DESCRIPTION:
XS GIS Cut Line= 4
      2298025.92      7128994.26      2298133.00      7129197.99
      2298118.97      7129501.72      2298270.69      7129604.56
#Sta/Elev= 30
  4608.3  785.39  4628.7  784.51  4645.1  784.72  4650.7  784.17  4689.2  783.74
  4694.8  781.95  4727.6  780.98  4733.3  781.76  4771.7  780.76  4850.5  780.43
  4910.5  779.50  4950.6  780.02  4970.6  775.53  4990.6  773.42  4998.1  770.70
  4998.7  770.20  5002.5  770.20  5003.2  770.70  5010.6  772.92  5020.7  772.91
  5029.6  775.00  5034.6  773.71  5040.7  774.73  5090.7  775.30  5130.8  778.63
  5205.4  778.17  5220.4  778.51  5277.3  782.65  5299.6  783.67  5325.8  783.79
#Mann=3,-1,0
  4608.3    0.05       0  4998.1   0.033       0  5003.2    0.05       0
Bank Sta=4998.1,5003.2
Exp/Cntr=0.3,0.1

Type RM Length L Ch R = 1,8032,196,196,196
BEGIN DESCRIPTION:
Mapping XS bc5df3fe
END DESCRIPTION:
XS GIS Cut Line= 3
      2298007.76      7129064.21      2298030.73      7129591.72
      2298194.17      7129603.78
#Sta/Elev= 30
  4639.8  785.20  4765.7  781.69  4835.8  779.36  4925.9  778.51  4975.9  778.75
  4985.9  776.63  4995.9  771.67  5005.9  770.64  5009.3  770.05  5010.1  769.55
  5014.0  769.55  5014.9  770.05  5017.1  771.72  5026.0  772.76  5036.0  773.44
  5046.0  773.68  5096.0  773.00  5126.0  772.95  5146.1  773.29  5167.8  772.92
  5186.1  775.75  5196.2  775.39  5206.2  775.74  5211.8  777.66  5246.3  777.17
  5286.4  778.16  5296.4  778.84  5306.5  780.34  5326.5  781.64  5331.7  782.39
#Mann=3,-1,0
  4639.8    0.05       0  5009.3   0.033       0  5014.9    0.05       0
Bank Sta=5009.3,5014.9
Exp/Cntr=0.3,0.1

Type RM Length L Ch R = 1,7836,364,364,364
BEGIN DESCRIPTION:
Mapping XS 5084ce0b
END DESCRIPTION:
XS GIS Cut Line= 2
      2297642.02      7129603.32      2298224.39      7129619.68
#Sta/Elev= 30
  4652.9  792.87  4708.8  790.01  4713.8  789.50  4729.9  785.22  4739.9  783.44
  4759.9  781.17  4779.9  780.23  4789.9  778.56  4819.9  778.43  4830.0  774.82
  4840.0  778.25  4850.0  778.57  4930.0  777.50  4950.0  777.88  4960.0  774.22
  4970.0  772.93  4980.0  773.79  4990.0  770.52  4997.2  769.66  4998.1  769.16
  5002.8  769.66  5020.0  770.62  5030.0  771.95  5050.0  776.06  5067.0  775.94
  5140.1  777.80  5160.1  778.76  5180.1  782.20  5190.1  782.86  5235.5  783.77
#Mann=3,-1,0
  4652.9    0.05       0  4997.2   0.033       0  5002.8    0.05       0
Bank Sta=4997.2,5002.8
Exp/Cntr=0.3,0.1

Type RM Length L Ch R = 1,7472,234,234,234
BEGIN DESCRIPTION:
Mapping XS 773d62d4
END DESCRIPTION:
XS GIS Cut Line= 4
      2297658.92      7130084.00      2298007.78      7129913.55
      2298023.48      7129659.18      2298211.26      7129653.31
#Sta/Elev= 30
  4726.7  799.23  4760.2  795.80  4773.4  796.50  4790.4  791.21  4818.5  790.02
  4835.4  787.10  4841.0  788.77  4857.9  784.25  4863.5  786.82  4880.5  784.00
  4886.0  785.87  4908.5  777.21  4916.0  771.97  4925.5  771.90  4938.3  774.98
  4982.8  774.63  4998.6  769.55  5002.2  766.93  5003.1  766.43  5007.8  766.93
  5021.1  767.92  5038.1  772.44  5111.2  774.55  5268.8  776.55  5349.0  772.22
  5359.0  774.20  5385.4  773.99  5395.4  777.31  5445.4  777.16  5557.7  783.02
#Mann=3,-1,0
  4726.7    0.05       0  5002.2   0.033       0  5007.8    0.05       0
Bank Sta=5002.2,5007.8
Exp/Cntr=0.3,0.1

Type RM Length L Ch R = 1,7238,357,357,357
BEGIN DESCRIPTION:
Mapping XS 3860acb7
END DESCRIPTION:
XS GIS Cut Line= 3
      2298065.54      7130454.37      2298105.10      7129789.88
      2298248.20      7129669.30
#Sta/Elev= 30
  4641.8  789.15  4736.3  784.52  4776.4  784.24  4782.8  784.70  4787.8  784.29
  4796.4  781.98  4846.5  780.48  4856.6  779.75  4866.6  778.35  4876.6  775.66
  4916.7  773.25  4966.7  772.95  4986.8  768.89  4996.8  766.22  5004.0  765.81
  5004.9  765.31  5008.8  765.31  5009.7  765.81  5016.8  768.56  5026.9  770.58
  5036.9  771.14  5066.9  771.00  5087.0  772.34  5127.0  773.46  5311.3  776.32
  5352.2  777.93  5388.6  778.53  5423.7  780.07  5458.8  782.26  5494.6  783.47
#Mann=3,-1,0
  4641.8    0.05       0  5004.0   0.033       0  5009.7    0.05       0
Bank Sta=5004,5009.7
Exp/Cntr=0.3,0.1