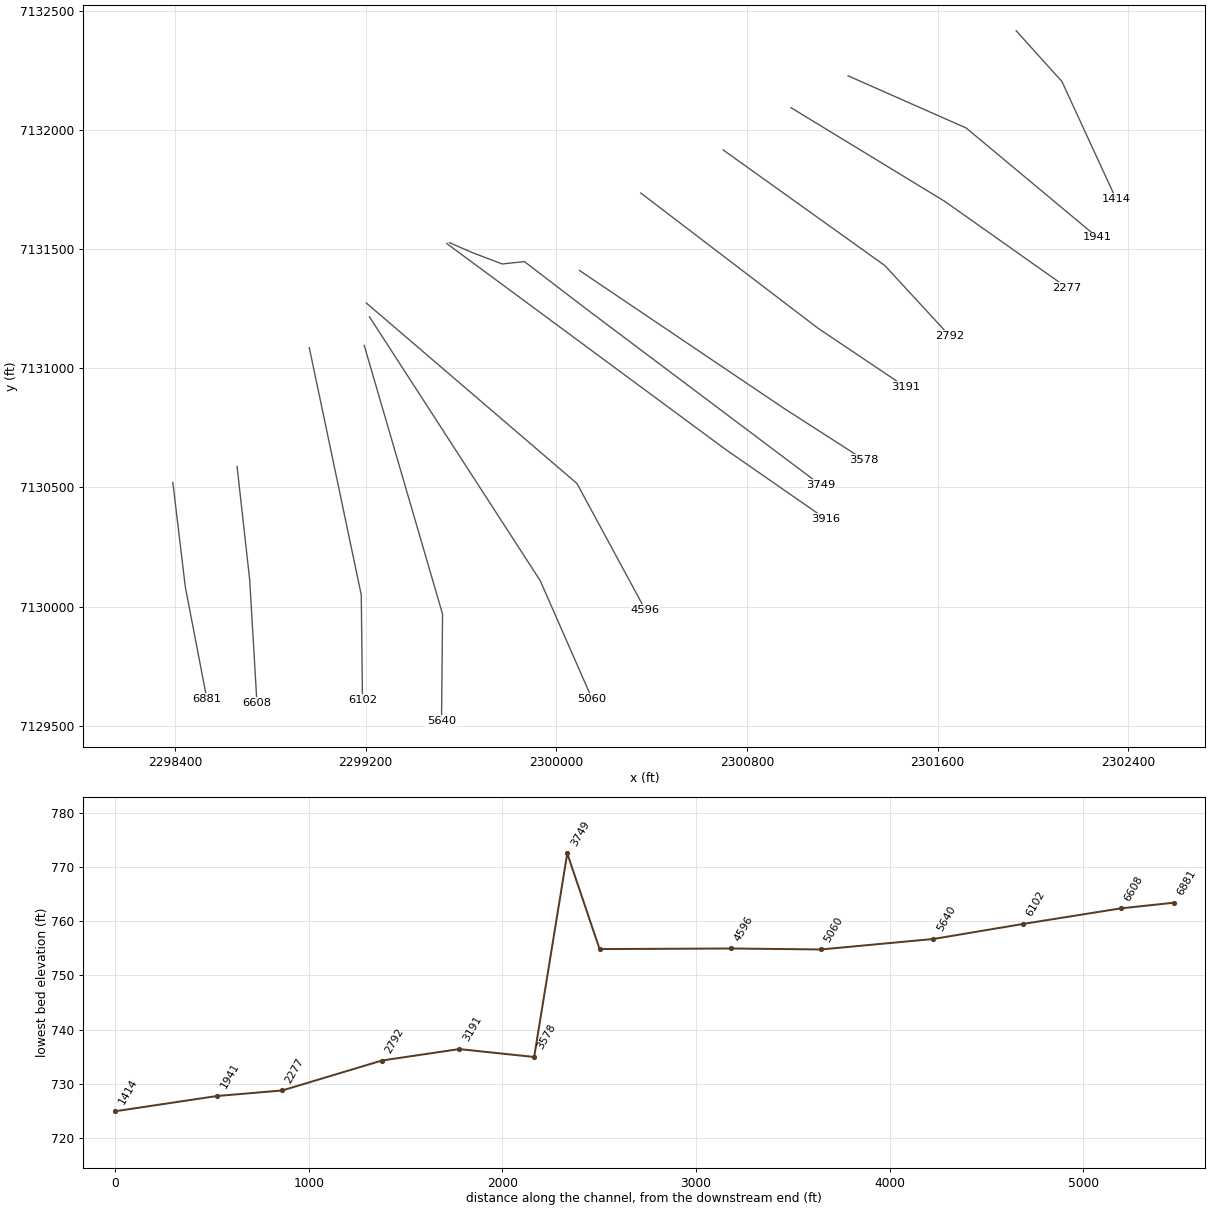
HEC-RAS study MDW T 117.prj: MDW T 117 Base Level Engineering

--- MDW T 117.g01 (geometry) --- (continued)

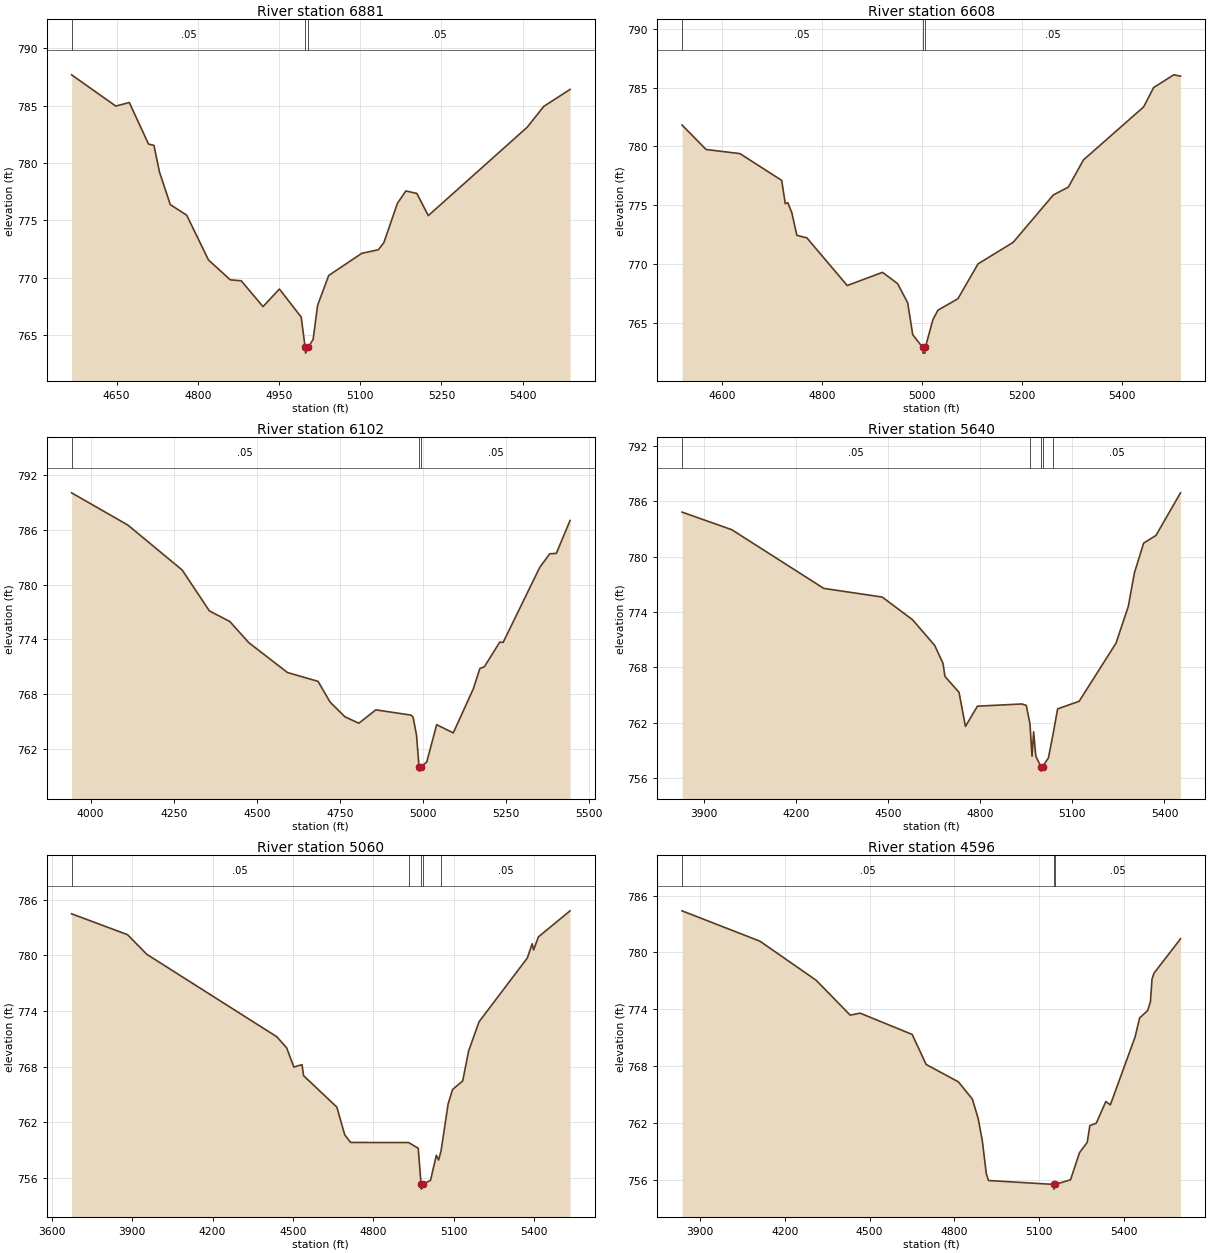
Type RM Length L Ch R = 1,6881,273,273,273
BEGIN DESCRIPTION:
MDW T 117 13.0
END DESCRIPTION:
XS GIS Cut Line= 3
      2298391.39      7130521.05      2298443.70      7130083.13
      2298534.31      7129612.30
#Sta/Elev= 30
  4566.9  787.68  4648.5  784.96  4673.5  785.27  4709.0  781.65  4719.0  781.54
  4729.1  779.24  4749.2  776.38  4779.5  775.46  4819.7  771.56  4860.0  769.83
  4880.2  769.75  4920.4  767.50  4950.7  769.03  4990.9  766.59  4998.2  763.95
  4999.1  763.45  5003.9  763.95  5012.9  764.64  5021.3  767.62  5041.7  770.21
  5102.8  772.14  5133.3  772.45  5143.5  773.06  5168.6  776.49  5184.2  777.57
  5204.6  777.35  5225.6  775.42  5408.3  783.12  5438.8  784.93  5487.4  786.41
#Mann=3,-1,0
  4566.9    0.05       0  4998.2   0.033       0  5003.9    0.05       0
Bank Sta=4998.2,5003.9
Exp/Cntr=0.3,0.1

Type RM Length L Ch R = 1,6608,506,506,506
BEGIN DESCRIPTION:
MDW T 117 12.0
END DESCRIPTION:
XS GIS Cut Line= 3
      2298660.98      7130587.78      2298713.91      7130112.06
      2298744.30      7129596.51
#Sta/Elev= 30
  4520.8  781.81  4568.9  779.73  4636.4  779.38  4719.8  777.10  4726.9  775.12
  4731.9  775.21  4739.9  774.37  4750.0  772.43  4770.1  772.21  4850.6  768.16
  4921.0  769.28  4951.2  768.32  4971.3  766.69  4981.4  763.98  5000.9  762.91
  5001.8  762.41  5005.7  762.41  5006.6  762.91  5021.6  765.25  5031.6  766.06
  5071.6  767.04  5111.7  770.00  5181.8  771.83  5262.0  775.86  5292.0  776.53
  5322.1  778.84  5442.3  783.35  5462.3  785.00  5502.4  786.08  5515.9  785.97
#Mann=3,-1,0
  4520.8    0.05       0  5000.9   0.033       0  5006.6    0.05       0
Bank Sta=5000.9,5006.6
Exp/Cntr=0.3,0.1

Type RM Length L Ch R = 1,6102,462,462,462
BEGIN DESCRIPTION:
MDW T 117 11.0
END DESCRIPTION:
XS GIS Cut Line= 3
      2298963.94      7131085.70      2299181.89      7130049.10
      2299187.01      7129608.69
#Sta/Elev= 30
  3942.8  790.09  4112.1  786.55  4275.6  781.61  4357.4  777.12  4418.7  775.96
  4476.3  773.62  4592.4  770.35  4684.4  769.38  4720.4  767.11  4765.2  765.49
  4807.0  764.78  4858.1  766.25  4964.5  765.67  4970.5  765.43  4980.7  763.45
  4988.0  760.02  4989.0  759.52  4993.8  760.02  5011.2  760.51  5041.2  764.62
  5091.2  763.72  5151.2  768.54  5171.2  770.79  5184.8  770.99  5231.2  773.70
  5241.2  773.66  5351.2  781.89  5381.2  783.39  5401.2  783.44  5442.5  787.05
#Mann=3,-1,0
  3942.8    0.05       0  4988.0   0.033       0  4993.8    0.05       0
Bank Sta=4988,4993.8
Exp/Cntr=0.3,0.1

Type RM Length L Ch R = 1,5640,580,580,580
BEGIN DESCRIPTION:
MDW T 117 10.0
END DESCRIPTION:
XS GIS Cut Line= 3
      2299194.26      7131095.61      2299522.94      7129968.14
      2299518.61      7129520.16
#Sta/Elev= 30
  3829.8  784.83  3991.9  782.92  4291.1  776.56  4481.4  775.62  4579.8  773.17
  4652.0  770.39  4679.4  768.42  4685.5  767.02  4731.4  765.29  4752.3  761.59
  4791.2  763.79  4935.5  764.03  4950.2  763.88  4962.3  761.87  4969.0  758.36
  4974.2  761.01  4981.4  758.36  4997.7  757.25  4998.7  756.75  5003.5  757.25
  5022.3  758.18  5036.5  760.60  5052.3  763.50  5122.3  764.32  5242.3  770.62
  5282.4  774.62  5302.4  778.27  5332.4  781.47  5372.4  782.30  5452.2  786.92
#Mann=5,-1,0
  3829.8    0.05       0  4962.3    0.12       0  4997.7    0.07       0
  5003.5    0.12       0  5036.5    0.05       0
Bank Sta=4997.7,5003.5
Exp/Cntr=0.3,0.1

Type RM Length L Ch R = 1,5060,464,464,464
BEGIN DESCRIPTION:
MDW T 117 9.0
END DESCRIPTION:
XS GIS Cut Line= 3
      2299216.48      7131215.18      2299932.63      7130108.49
      2300149.92      7129613.58
#Sta/Elev= 30
  3674.4  784.49  3883.1  782.24  3954.5  780.13  4439.9  771.23  4476.2  770.05
  4503.3  767.97  4533.6  768.23  4539.5  767.04  4663.5  763.65  4693.0  760.66
  4714.9  759.84  4931.5  759.83  4967.0  759.21  4977.8  755.31  4978.8  754.81
  4983.8  755.31  5012.8  755.76  5034.6  758.46  5042.9  757.95  5052.1  758.93
  5078.3  763.97  5095.1  765.55  5132.9  766.48  5154.8  769.70  5194.0  772.86
  5373.9  779.73  5391.8  781.27  5397.2  780.59  5415.1  782.00  5533.1  784.81
#Mann=5,-1,0
  3674.4    0.05       0  4931.5    0.12       0  4977.8    0.07       0
  4983.8    0.12       0  5052.1    0.05       0
Bank Sta=4977.8,4983.8
Exp/Cntr=0.3,0.1

Type RM Length L Ch R = 1,4596,680,680,680
BEGIN DESCRIPTION:
MDW T 117 8.0
END DESCRIPTION:
XS GIS Cut Line= 3
      2299203.07      7131273.44      2300086.82      7130516.19
      2300372.66      7129987.63
#Sta/Elev= 30
  3836.2  784.39  4112.2  781.18  4310.9  777.06  4431.6  773.37  4466.7  773.58
  4651.1  771.33  4700.5  768.16  4814.7  766.32  4864.1  764.50  4884.9  762.42
  4899.2  760.13  4913.4  756.64  4921.1  755.90  5151.8  755.49  5152.8  754.99
  5157.8  755.49  5211.7  755.98  5243.2  758.83  5270.8  759.94  5279.9  761.70
  5302.6  761.95  5336.7  764.25  5352.6  763.89  5440.1  771.06  5456.3  773.08
  5484.5  773.85  5494.4  774.77  5500.1  777.18  5507.3  777.81  5600.9  781.43
#Mann=3,-1,0
  3836.2    0.05       0  5151.8   0.033       0  5157.8    0.05       0
Bank Sta=5151.8,5157.8
Exp/Cntr=0.3,0.1

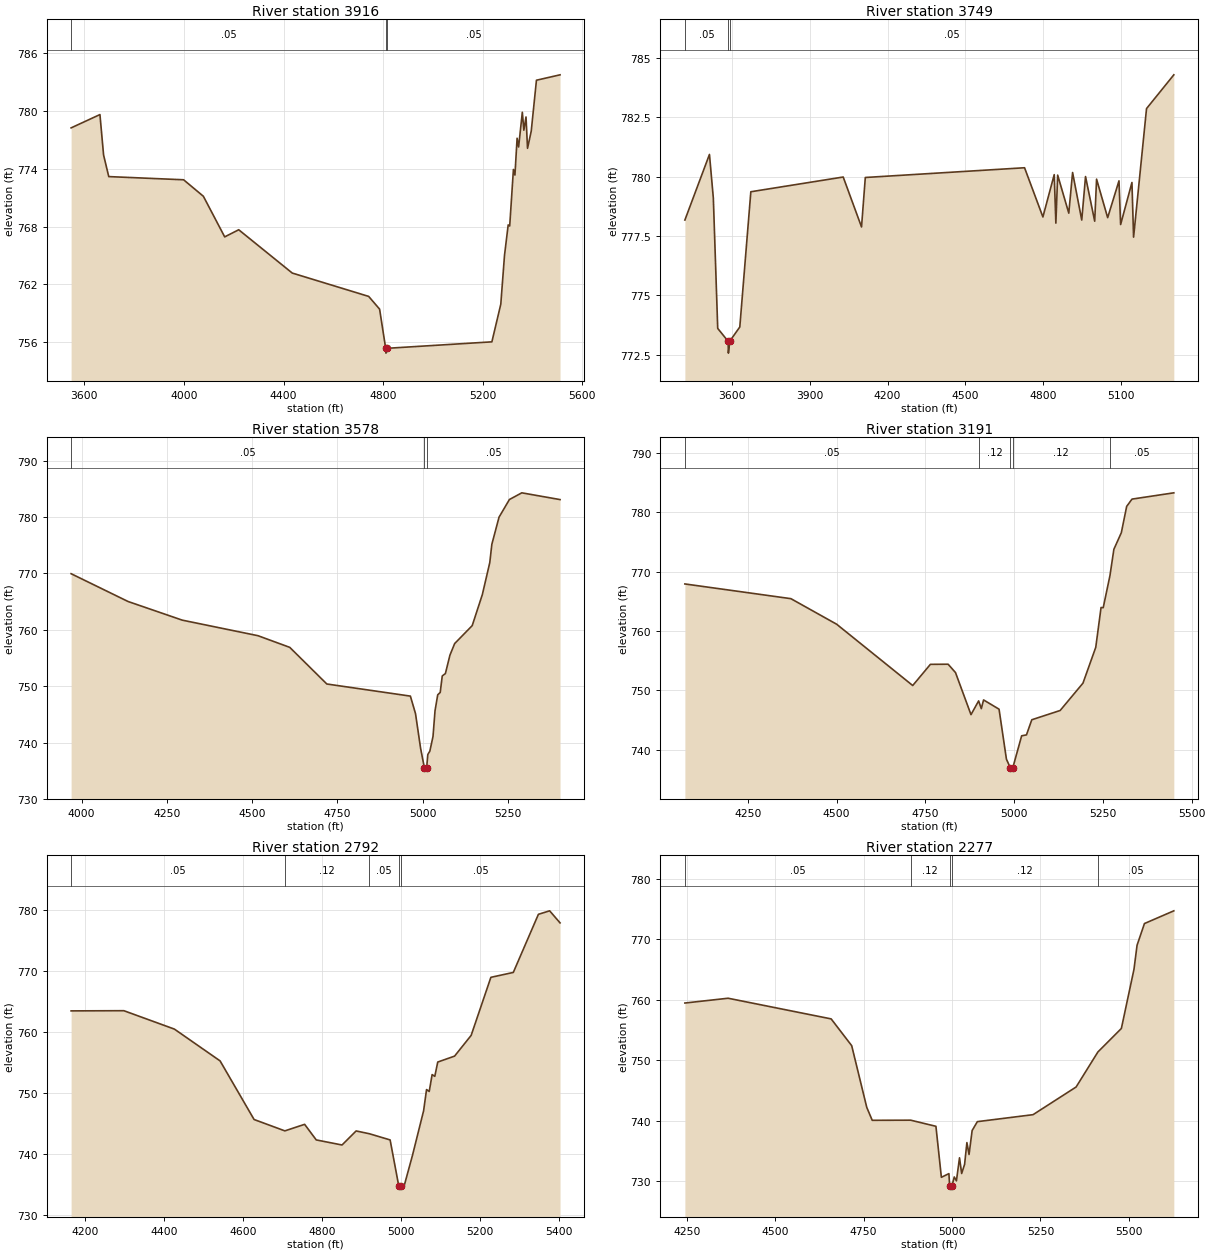
Type RM Length L Ch R = 1,3916,167,167,167
BEGIN DESCRIPTION:
MDW T 117 7.0
END DESCRIPTION:
XS GIS Cut Line= 3
      2299540.12      7131523.21      2300709.01      7130659.97
      2301128.64      7130368.71
#Sta/Elev= 30
  3546.9  778.23  3662.7  779.61  3677.3  775.42  3698.1  773.18  3998.8  772.85
  4078.2  771.14  4163.8  766.93  4220.1  767.67  4435.2  763.18  4742.1  760.76
  4786.0  759.44  4810.4  755.38  4811.5  754.88  4816.6  755.38  5237.0  756.05
  5272.8  759.95  5287.7  765.01  5302.5  768.17  5308.6  768.06  5323.5  773.92
  5329.6  773.34  5338.3  777.16  5344.4  776.25  5359.3  779.85  5365.4  777.99
  5374.1  779.36  5380.2  776.11  5395.1  777.90  5416.0  783.17  5510.8  783.73
#Mann=3,-1,0
  3546.9    0.05       0  4810.4   0.033       0  4816.6    0.05       0
Bank Sta=4810.4,4816.6
Exp/Cntr=0.3,0.1

Type RM Length L Ch R = 1,3749,171,171,171
BEGIN DESCRIPTION:
MDW T 117 6.5
END DESCRIPTION:
XS GIS Cut Line= 6
      2299552.05      7131526.46      2299652.76      7131482.77
      2299773.20      7131437.13      2299866.24      7131447.17
      2300122.79      7131250.80      2301107.34      7130511.08
#Sta/Elev= 30
  3417.9  778.17  3512.7  780.93  3527.7  779.09  3544.6  773.61  3584.7  773.07
  3585.8  772.57  3590.9  773.07  3629.8  773.67  3672.4  779.36  4028.8  779.98
  4099.5  777.88  4114.1  779.96  4728.6  780.37  4799.4  778.30  4843.1  780.08
  4849.4  778.04  4856.4  780.06  4899.3  778.46  4913.9  780.17  4949.3  778.17
  4963.9  780.00  4999.3  778.12  5006.5  779.89  5049.3  778.27  5093.0  779.82
  5099.3  777.98  5143.0  779.75  5149.3  777.45  5199.3  782.86  5304.6  784.28
#Mann=3,-1,0
  3417.9    0.05       0  3584.7   0.033       0  3590.9    0.05       0
Bank Sta=3584.7,3590.9
Exp/Cntr=0.3,0.1

Type RM Length L Ch R = 1,3578,387,387,387
BEGIN DESCRIPTION:
MDW T 117 6.0
END DESCRIPTION:
XS GIS Cut Line= 3
      2300097.66      7131409.58      2300952.06      7130833.44
      2301290.52      7130615.79
#Sta/Elev= 30
  3969.5  769.96  4136.3  765.03  4295.2  761.72  4517.1  758.96  4610.3  756.89
  4718.9  750.39  4963.8  748.24  4978.8  745.14  4993.7  738.99  5005.1  735.43
  5006.2  734.93  5011.3  735.43  5014.9  737.88  5020.8  738.47  5030.1  741.09
  5036.0  745.64  5043.9  748.47  5051.2  748.89  5057.2  751.82  5066.4  752.24
  5079.6  755.49  5093.5  757.56  5145.0  760.75  5174.7  766.26  5196.5  771.94
  5202.5  775.17  5223.6  779.99  5254.0  783.12  5290.3  784.31  5402.4  783.11
#Mann=3,-1,0
  3969.5    0.05       0  5005.1   0.033       0  5011.3    0.05       0
Bank Sta=5005.1,5011.3
Exp/Cntr=0.3,0.1

Type RM Length L Ch R = 1,3191,399,399,399
BEGIN DESCRIPTION:
MDW T 117 5.0
END DESCRIPTION:
XS GIS Cut Line= 3
      2300354.64      7131734.55      2301096.47      7131168.58
      2301464.75      7130921.26
#Sta/Elev= 30
  4073.1  767.94  4371.6  765.46  4500.5  761.15  4714.6  750.82  4764.4  754.39
  4814.3  754.41  4835.1  753.00  4878.7  745.91  4900.2  748.23  4907.8  746.92
  4914.1  748.39  4957.7  746.83  4978.5  738.40  4989.9  736.89  4990.9  736.39
  4996.1  736.89  5021.3  742.34  5034.9  742.50  5049.9  745.05  5129.7  746.61
  5194.0  751.22  5230.0  757.26  5244.9  763.97  5251.0  763.94  5270.0  769.36
  5281.0  773.78  5302.0  776.58  5317.0  781.01  5332.0  782.24  5449.8  783.30
#Mann=5,-1,0
  4073.1    0.05       0  4900.2    0.12       0  4989.9    0.07       0
  4996.1    0.12       0  5270.0    0.05       0
Bank Sta=4989.9,4996.1
Exp/Cntr=0.3,0.1

Type RM Length L Ch R = 1,2792,515,515,515
BEGIN DESCRIPTION:
MDW T 117 4.0
END DESCRIPTION:
XS GIS Cut Line= 3
      2300699.77      7131915.62      2301378.58      7131430.23
      2301650.90      7131134.66
#Sta/Elev= 30
  4165.5  763.44  4298.9  763.47  4426.7  760.46  4542.2  755.26  4628.2  745.67
  4706.0  743.81  4756.0  744.88  4785.4  742.33  4850.6  741.50  4886.2  743.80
  4919.8  743.34  4972.2  742.33  4994.1  734.78  4995.1  734.28  5000.3  734.78
  5007.6  734.79  5028.5  739.75  5056.9  747.11  5064.3  750.57  5071.1  750.26
  5078.4  753.02  5085.2  752.73  5092.6  755.07  5135.2  756.04  5177.1  759.43
  5227.0  768.93  5283.7  769.73  5347.2  779.24  5375.6  779.81  5401.9  777.84
#Mann=5,-1,0
  4165.5    0.05       0  4706.0    0.12       0  4919.8    0.05       0
  4994.1   0.033       0  5000.3    0.05       0
Bank Sta=4994.1,5000.3
Exp/Cntr=0.3,0.1

Type RM Length L Ch R = 1,2277,336,336,336
BEGIN DESCRIPTION:
MDW T 117 3.0
END DESCRIPTION:
XS GIS Cut Line= 3
      2300984.56      7132092.66      2301629.95      7131699.51
      2302142.48      7131337.49
#Sta/Elev= 30
  4244.3  759.46  4366.6  760.25  4658.1  756.84  4716.2  752.42  4758.8  742.24
  4774.3  740.10  4883.2  740.12  4954.5  739.11  4969.9  730.69  4991.2  731.30
  4993.4  729.24  4994.4  728.74  4999.7  729.24  5006.4  730.75  5012.5  730.11
  5021.2  733.91  5027.3  731.32  5035.6  732.83  5042.1  736.42  5048.2  734.46
  5056.9  738.41  5071.7  739.88  5229.2  741.03  5351.1  745.60  5412.7  751.38
  5479.1  755.26  5514.8  765.03  5523.5  769.00  5544.4  772.58  5627.5  774.68
#Mann=5,-1,0
  4244.3    0.05       0  4883.2    0.12       0  4993.4    0.07       0
  4999.7    0.12       0  5412.7    0.05       0
Bank Sta=4993.4,4999.7
Exp/Cntr=0.3,0.1

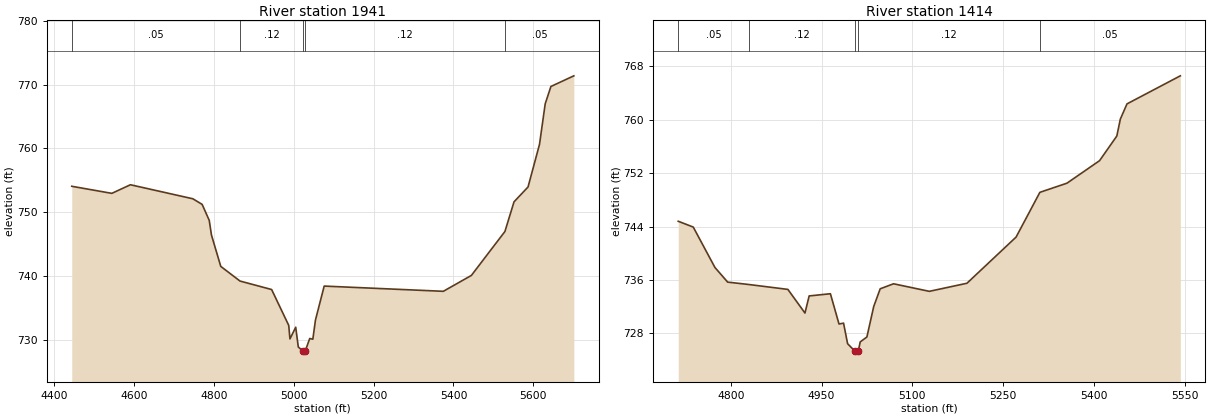
Type RM Length L Ch R = 1,1941,527,527,527
BEGIN DESCRIPTION:
MDW T 117 2.0
END DESCRIPTION:
XS GIS Cut Line= 3
      2301224.11      7132226.36      2301719.24      7132007.62
      2302269.29      7131549.24
#Sta/Elev= 30
  4444.1  754.04  4544.4  752.93  4591.0  754.28  4747.3  752.08  4770.6  751.20
  4788.4  748.69  4793.9  746.41  4817.2  741.48  4865.4  739.18  4944.6  737.85
  4987.4  732.23  4990.5  730.11  5004.9  731.94  5011.4  728.84  5022.5  728.22
  5023.5  727.72  5028.9  728.22  5040.0  730.17  5047.8  730.06  5054.3  733.05
  5076.2  738.39  5374.5  737.57  5444.8  740.06  5528.8  746.95  5551.6  751.60
  5586.7  753.93  5615.4  760.61  5629.7  766.98  5644.0  769.69  5701.4  771.36
#Mann=5,-1,0
  4444.1    0.05       0  4865.4    0.12       0  5022.5    0.07       0
  5028.9    0.12       0  5528.8    0.05       0
Bank Sta=5022.5,5028.9
Exp/Cntr=0.3,0.1

Type RM Length L Ch R = 1,1414,0,0,0
BEGIN DESCRIPTION:
MDW T 117 1.0
END DESCRIPTION:
XS GIS Cut Line= 3
      2301929.19      7132415.37      2302121.12      7132202.53
      2302348.02      7131710.09
#Sta/Elev= 30
  4713.4  744.79  4738.2  743.92  4774.0  737.87  4795.0  735.68  4831.0  735.31
  4894.4  734.59  4922.6  731.05  4929.5  733.61  4964.6  733.94  4978.8  729.41
  4986.3  729.54  4993.0  726.46  5004.4  725.40  5005.4  724.90  5010.8  725.40
  5013.8  726.73  5024.8  727.46  5036.1  732.03  5046.8  734.68  5068.8  735.43
  5127.9  734.30  5190.0  735.51  5271.1  742.42  5310.4  749.12  5355.1  750.49
  5408.9  753.86  5437.4  757.55  5443.2  760.08  5454.2  762.36  5542.2  766.56
#Mann=5,-1,0
  4713.4    0.05       0  4831.0    0.12       0  5004.4    0.07       0
  5010.8    0.12       0  5310.4    0.05       0
Bank Sta=5004.4,5010.8
Exp/Cntr=0.3,0.1

Chan Stop Cuts=-1