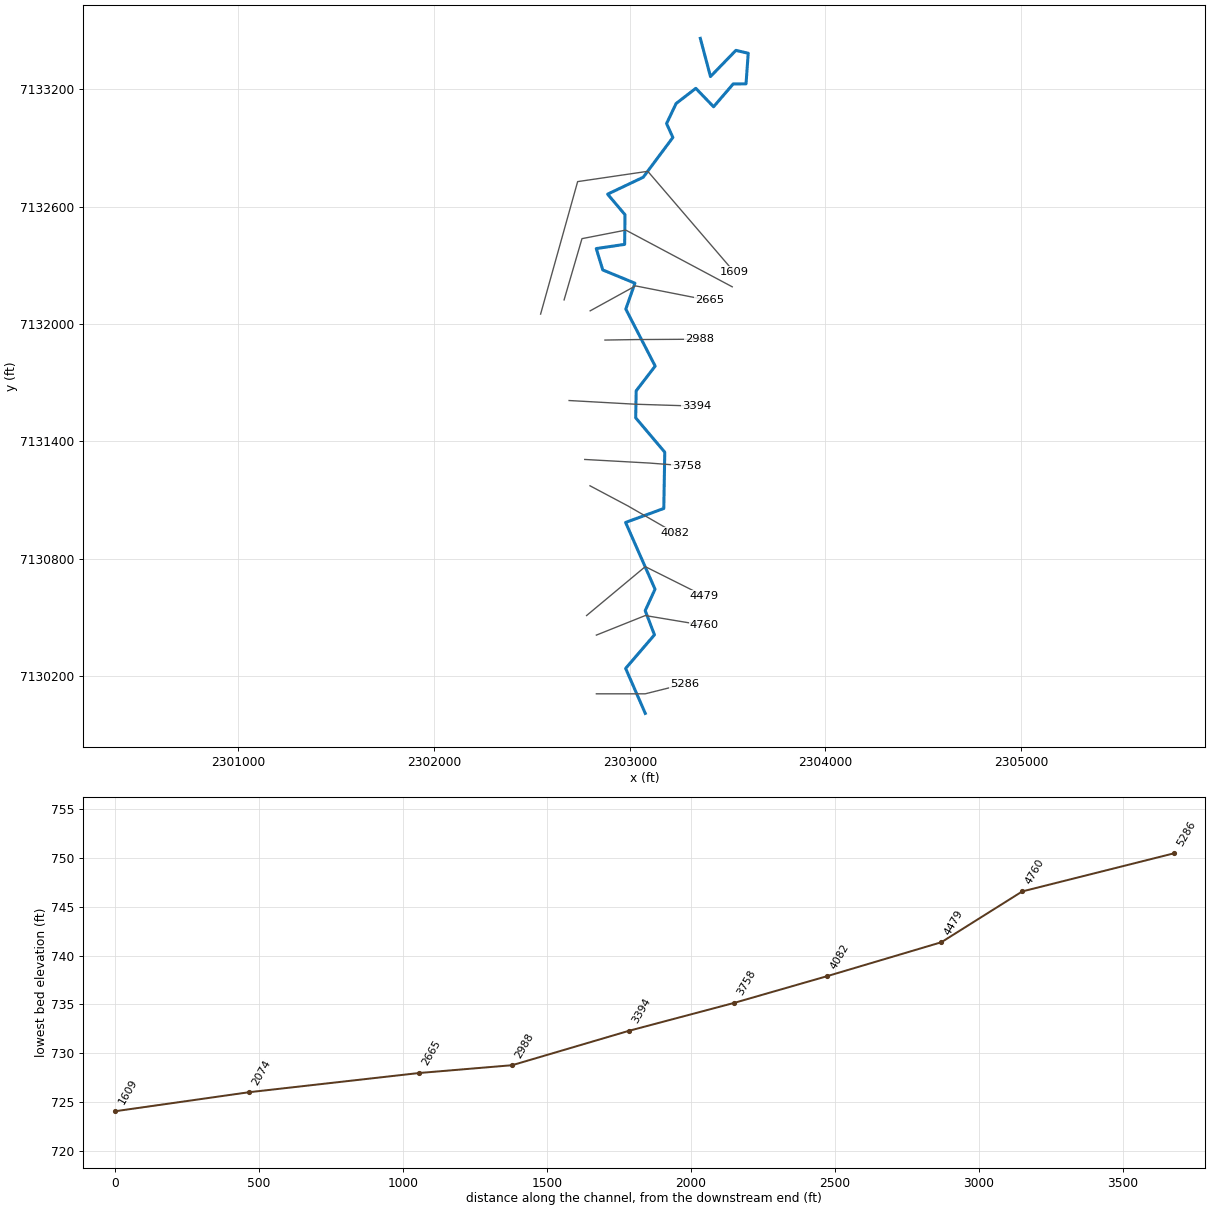
--- MDW T 118.prj (project) ---

Proj Title=MDW T 118 Base Level Engineering
Current Plan=p01
Default Exp/Contr=0.3,0.1
English Units
Geom File=g01
Flow File=f01
Plan File=p01
BEGIN DESCRIPTION:
MDW T 118
END DESCRIPTION:

--- MDW T 118.p01 (plan) ---

Plan Title=Multiple Run
Short Identifier=Multiple
Geom File=g01
Flow File=f01
Subcritical Flow
K Sum by GR= 0
Std Step Tol= 0.01
Critical Tol= 0.01
Num of Std Step Trials= 20
Max Error Tol= 0.3
Flow Tol Ratio= 0.001
Split Flow NTrial= 30
Split Flow Tol= 0.02
Split Flow Ratio= 0.02
Log Output Level= 0
Friction Slope Method= 1
Unsteady Friction Slope Method= 2
Unsteady Bridges Friction Slope Method= 1
Parabolic Critical Depth
Global Vel Dist=  1 , 1 , 1
Global Log Level= 0
CheckData=True
Encroach Param= -1, 0, 0, 0
BEGIN DESCRIPTION:
Multiple Run
END DESCRIPTION:

--- MDW T 118.f01 (steady flow) ---

Flow Title=Multiple
Number of Profiles=7
Profile Names=10-year,25-year,50-year,1pct_min,100-year,1pct_plu,500-year
River Rch & RM= MDW T 118,Reach-1,5286
     357     475     570     340     679    1355     965
River Rch & RM= MDW T 118,Reach-1,4082
     570     779     951     577    1152    2299    1693
Boundary for River Rch & Prof#=MDW T 118,Reach-1,1
Up Type=0
Dn Type=3
Dn Slope=0.005
Boundary for River Rch & Prof#=MDW T 118,Reach-1,2
Up Type=0
Dn Type=3
Dn Slope=0.005
Boundary for River Rch & Prof#=MDW T 118,Reach-1,3
Up Type=0
Dn Type=3
Dn Slope=0.005
Boundary for River Rch & Prof#=MDW T 118,Reach-1,4
Up Type=0
Dn Type=3
Dn Slope=0.005
Boundary for River Rch & Prof#=MDW T 118,Reach-1,5
Up Type=0
Dn Type=3
Dn Slope=0.005
Boundary for River Rch & Prof#=MDW T 118,Reach-1,6
Up Type=0
Dn Type=3
Dn Slope=0.005
Boundary for River Rch & Prof#=MDW T 118,Reach-1,7
Up Type=0
Dn Type=3
Dn Slope=0.005

--- MDW T 118.g01 (geometry) ---

Geom Title=Existing Conditions

River Reach=MDW T 118,Reach-1
Reach XY= 30
      2303079.00      7130010.00      2302978.63      7130239.81
      2303125.93      7130411.43      2303078.62      7130535.00
      2303128.92      7130644.61      2302978.42      7130985.77
      2303173.66      7131057.26      2303178.62      7131344.84
      2303030.04      7131520.44      2303032.54      7131658.53
      2303129.58      7131785.00      2302979.53      7132076.14
      2303025.97      7132208.60      2302861.77      7132276.28
      2302828.45      7132385.51      2302973.55      7132406.99
      2302975.45      7132558.53      2302886.48      7132663.62
      2303068.37      7132749.95      2303220.05      7132953.35
      2303187.82      7133024.55      2303236.71      7133126.96
      2303337.24      7133204.44      2303428.14      7133110.28
      2303528.27      7133226.81      2303593.92      7133227.49
      2303605.13      7133383.86      2303542.18      7133398.49
      2303412.26      7133264.66      2303360.33      7133460.02

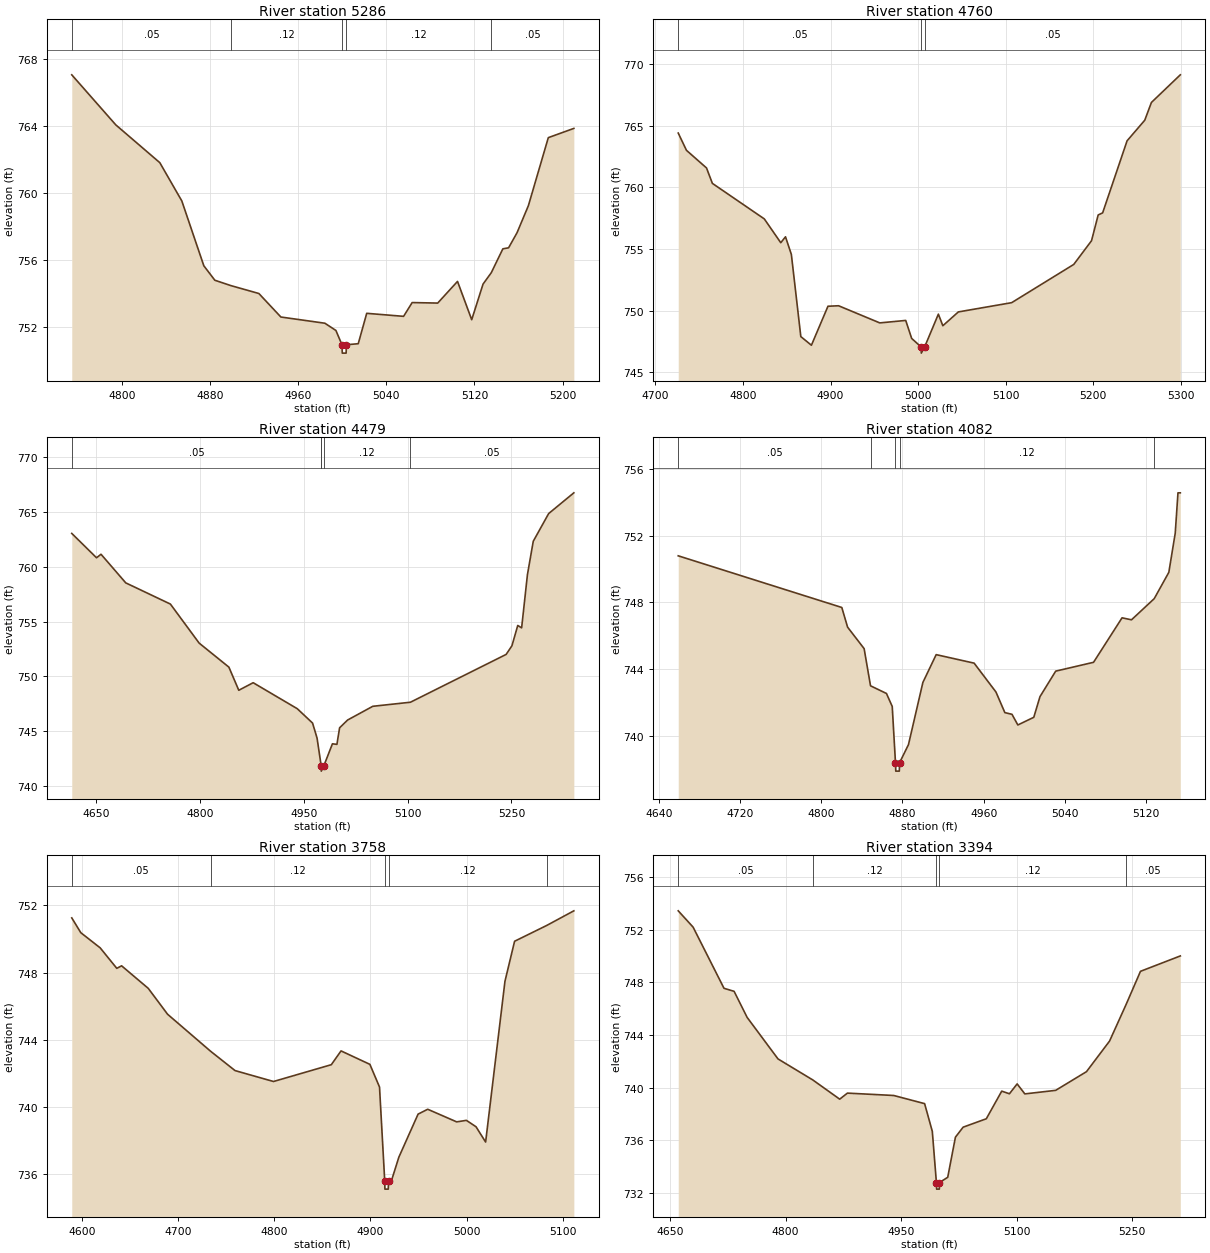
Type RM Length L Ch R = 1,5286,526,526,526
BEGIN DESCRIPTION:
MDW T 118 9.0
END DESCRIPTION:
XS GIS Cut Line= 3
      2302828.99      7130110.00      2303079.00      7130110.00
      2303279.04      7130160.01
#Sta/Elev= 30
  4754.1  767.04  4794.1  764.06  4834.1  761.81  4854.1  759.53  4874.1  755.67
  4884.1  754.81  4898.7  754.49  4924.1  754.02  4944.1  752.62  4984.1  752.25
  4994.1  751.82  4999.6  750.97  4999.9  750.47  5003.4  750.47  5003.6  750.97
  5014.4  751.03  5022.1  752.84  5055.6  752.66  5063.4  753.48  5086.6  753.45
  5104.6  754.74  5117.5  752.46  5127.8  754.58  5135.3  755.26  5145.8  756.68
  5151.0  756.74  5158.7  757.64  5169.0  759.25  5187.1  763.30  5210.3  763.85
#Mann=5,-1,0
  4754.1    0.05       0  4898.7    0.12       0  4999.6    0.07       0
  5003.6    0.12       0  5135.3    0.05       0
Bank Sta=4999.6,5003.6
Exp/Cntr=0.3,0.1

Type RM Length L Ch R = 1,4760,281,281,281
BEGIN DESCRIPTION:
MDW T 118 7.0
END DESCRIPTION:
XS GIS Cut Line= 3
      2302829.01      7130410.01      2303079.00      7130510.00
      2303379.02      7130460.00
#Sta/Elev= 30
  4726.0  764.41  4735.4  763.01  4758.3  761.58  4765.0  760.33  4824.3  757.45
  4843.1  755.52  4848.5  756.00  4855.2  754.57  4866.0  747.91  4878.1  747.21
  4897.0  750.37  4909.1  750.41  4956.2  749.02  4985.8  749.22  4992.6  747.76
  5003.4  747.07  5003.6  746.57  5007.4  747.07  5023.1  749.73  5028.2  748.79
  5045.9  749.91  5106.8  750.66  5177.7  753.76  5198.0  755.68  5205.6  757.77
  5210.7  757.94  5238.6  763.78  5258.8  765.45  5266.4  766.89  5299.4  769.13
#Mann=3,-1,0
  4726.0    0.05       0  5003.4   0.033       0  5007.4    0.05       0
Bank Sta=5003.4,5007.4
Exp/Cntr=0.3,0.1

Type RM Length L Ch R = 1,4479,397,397,397
BEGIN DESCRIPTION:
MDW T 118 6.0
END DESCRIPTION:
XS GIS Cut Line= 3
      2302778.98      7130509.98      2303079.00      7130760.00
      2303379.04      7130609.98
#Sta/Elev= 30
  4614.3  763.03  4650.1  760.81  4656.6  761.13  4692.4  758.52  4756.9  756.59
  4798.5  753.03  4841.5  750.84  4855.8  748.73  4876.6  749.42  4940.4  747.05
  4962.5  745.74  4969.0  744.37  4974.7  741.95  4974.9  741.86  4975.1  741.36
  4978.9  741.86  4991.2  743.85  4997.7  743.80  5001.6  745.31  5013.2  746.02
  5049.6  747.27  5104.0  747.64  5242.4  752.00  5250.8  752.79  5259.2  754.64
  5264.8  754.42  5273.2  759.27  5281.6  762.31  5303.9  764.84  5340.3  766.73
#Mann=5,-1,0
  4614.3    0.05       0  4974.7    0.12       0  4974.9    0.07       0
  4978.9    0.12       0  5104.0    0.05       0
Bank Sta=4974.9,4978.9
Exp/Cntr=0.3,0.1

Type RM Length L Ch R = 1,4082,324,324,324
BEGIN DESCRIPTION:
MDW T 118 5.0
END DESCRIPTION:
XS GIS Cut Line= 3
      2302796.42      7131173.19      2302990.62      7131070.06
      2303228.76      7130932.71
#Sta/Elev= 30
  4659.0  750.80  4820.2  747.70  4825.9  746.52  4842.2  745.23  4848.5  743.00
  4864.2  742.54  4869.9  741.76  4873.1  738.38  4873.4  737.88  4876.9  737.88
  4877.1  738.38  4885.9  739.47  4900.1  743.20  4913.2  744.87  4950.6  744.36
  4972.1  742.63  4980.9  741.39  4987.9  741.29  4993.7  740.65  5009.4  741.11
  5015.5  742.35  5031.0  743.88  5068.3  744.41  5096.4  747.08  5105.7  746.96
  5128.1  748.23  5142.5  749.81  5148.8  752.16  5151.5  754.58  5153.8  754.58
#Mann=5,-1,0
  4659.0    0.05       0  4848.5    0.12       0  4873.1    0.07       0
  4877.1    0.12       0  5128.1    0.05       0
Bank Sta=4873.1,4877.1
Exp/Cntr=0.3,0.1

Type RM Length L Ch R = 1,3758,364,364,364
BEGIN DESCRIPTION:
MDW T 118 4.0
END DESCRIPTION:
XS GIS Cut Line= 3
      2302769.58      7131307.72      2303098.69      7131289.46
      2303290.41      7131274.86
#Sta/Elev= 30
  4589.6  751.26  4599.0  750.38  4619.1  749.48  4636.4  748.26  4641.4  748.41
  4669.1  747.07  4689.2  745.53  4733.9  743.33  4759.3  742.18  4799.3  741.53
  4859.4  742.53  4869.5  743.35  4899.5  742.55  4909.5  741.20  4914.9  735.63
  4915.1  735.13  4918.6  735.13  4918.9  735.63  4921.9  735.63  4929.6  737.03
  4949.6  739.59  4959.6  739.88  4989.7  739.13  4999.8  739.22  5009.8  738.84
  5019.8  737.93  5039.9  747.49  5049.9  749.87  5083.3  750.81  5111.5  751.68
#Mann=5,-1,0
  4589.6    0.05       0  4733.9    0.12       0  4914.9    0.07       0
  4918.9    0.12       0  5083.3    0.05       0
Bank Sta=4914.9,4918.9
Exp/Cntr=0.3,0.1

Type RM Length L Ch R = 1,3394,406,406,406
BEGIN DESCRIPTION:
MDW T 118 3.0
END DESCRIPTION:
XS GIS Cut Line= 3
      2302689.70      7131608.93      2303028.57      7131590.03
      2303340.72      7131580.29
#Sta/Elev= 30
  4660.6  753.44  4679.9  752.20  4720.0  747.55  4733.1  747.32  4750.0  745.34
  4790.1  742.18  4835.3  740.58  4870.2  739.12  4880.2  739.58  4940.3  739.40
  4980.4  738.78  4990.4  736.67  4995.7  732.78  4996.0  732.28  4999.5  732.28
  4999.7  732.78  5010.4  733.18  5020.4  736.23  5030.4  736.99  5060.5  737.63
  5080.5  739.73  5090.5  739.53  5100.5  740.28  5110.5  739.52  5150.5  739.79
  5190.5  741.21  5220.5  743.54  5242.1  746.34  5260.6  748.84  5312.3  750.01
#Mann=5,-1,0
  4660.6    0.05       0  4835.3    0.12       0  4995.7    0.07       0
  4999.7    0.12       0  5242.1    0.05       0
Bank Sta=4995.7,4999.7
Exp/Cntr=0.3,0.1

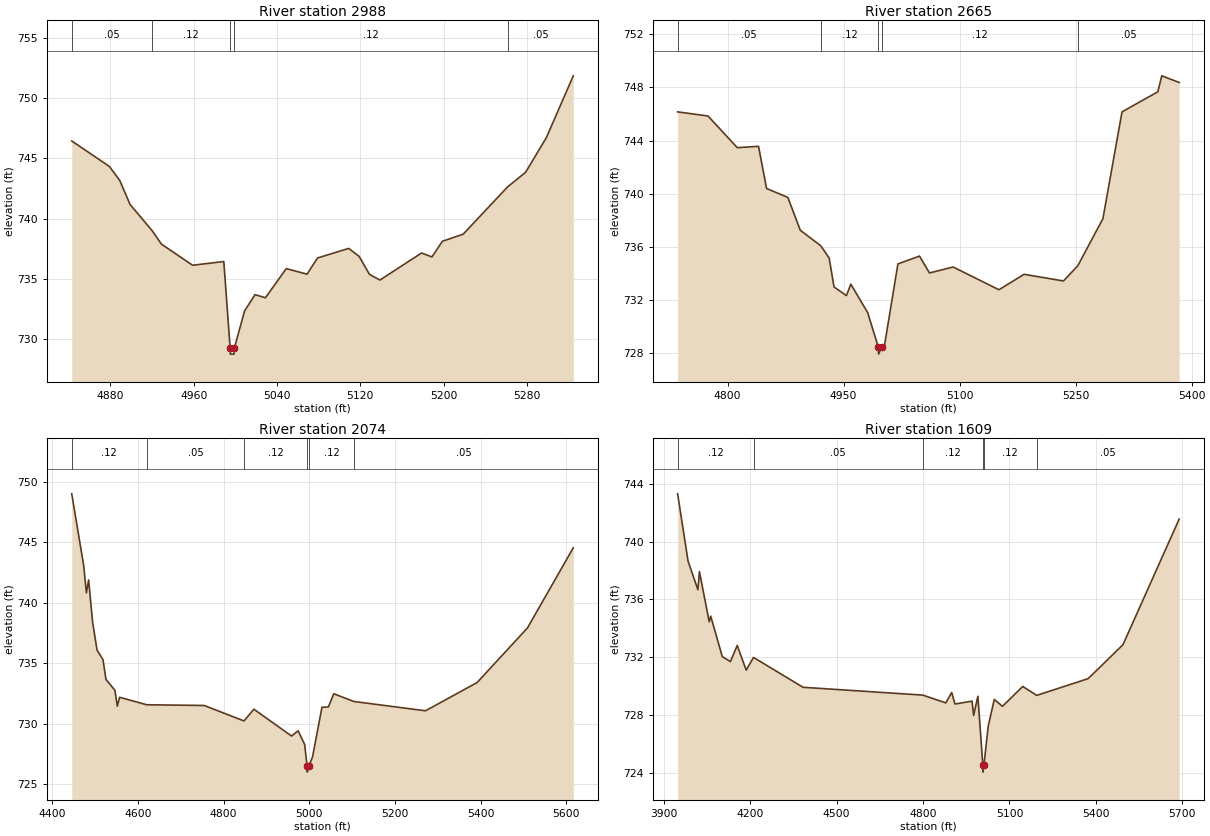
Type RM Length L Ch R = 1,2988,323,323,323
BEGIN DESCRIPTION:
MDW T 118 2.0
END DESCRIPTION:
XS GIS Cut Line= 3
      2302872.89      7131917.96      2303030.07      7131920.45
      2303354.77      7131922.30
#Sta/Elev= 30
  4842.8  746.45  4878.9  744.34  4888.9  743.18  4898.9  741.17  4919.9  739.02
  4928.9  737.89  4958.9  736.13  4988.9  736.44  4995.0  729.25  4995.2  728.75
  4998.7  728.75  4999.0  729.25  5008.9  732.34  5018.9  733.69  5028.9  733.43
  5048.9  735.85  5068.9  735.39  5078.9  736.73  5108.9  737.53  5118.9  736.87
  5128.9  735.37  5138.9  734.90  5178.9  737.15  5188.9  736.82  5198.9  738.12
  5218.9  738.71  5261.6  742.64  5278.9  743.85  5298.9  746.74  5324.7  751.86
#Mann=5,-1,0
  4842.8    0.05       0  4919.9    0.12       0  4995.0    0.07       0
  4999.0    0.12       0  5261.6    0.05       0
Bank Sta=4995,4999
Exp/Cntr=0.3,0.1

Type RM Length L Ch R = 1,2665,591,591,591
BEGIN DESCRIPTION:
MDW T 118 1.0
END DESCRIPTION:
XS GIS Cut Line= 3
      2302797.36      7132067.29      2303029.10      7132194.80
      2303405.76      7132120.58
#Sta/Elev= 30
  4735.5  746.16  4774.8  745.85  4812.6  743.47  4840.1  743.57  4850.5  740.40
  4878.0  739.73  4894.1  737.26  4920.5  736.10  4931.4  735.17  4937.7  733.00
  4953.7  732.35  4959.4  733.21  4981.2  731.07  4995.1  728.45  4995.3  727.95
  4999.1  728.45  5002.5  728.45  5020.3  734.73  5048.2  735.32  5061.1  734.05
  5091.6  734.50  5150.9  732.79  5183.4  733.95  5234.3  733.45  5252.8  734.59
  5285.3  738.13  5310.0  746.16  5356.3  747.67  5361.4  748.87  5383.9  748.37
#Mann=5,-1,0
  4735.5    0.05       0  4920.5    0.12       0  4995.1    0.07       0
  4999.1    0.12       0  5252.8    0.05       0
Bank Sta=4995.1,4999.1
Exp/Cntr=0.3,0.1

Type RM Length L Ch R = 1,2074,465,465,465
BEGIN DESCRIPTION:
MDW T 118 0.5
END DESCRIPTION:
XS GIS Cut Line= 4
      2302664.09      7132123.27      2302755.45      7132436.19
      2302979.43      7132479.94      2303523.44      7132190.11
#Sta/Elev= 30
  4445.8  749.03  4473.6  743.11  4480.0  740.83  4485.2  741.90  4494.5  738.40
  4504.9  736.08  4518.7  735.30  4525.7  733.66  4546.6  732.76  4552.2  731.44
  4557.4  732.18  4620.8  731.56  4754.9  731.50  4847.8  730.22  4871.0  731.19
  4958.8  728.97  4974.2  729.40  4989.4  728.27  4995.2  726.48  4995.5  725.98
  4999.2  726.48  5007.8  727.24  5029.8  731.35  5044.8  731.38  5057.4  732.47
  5104.4  731.83  5271.5  731.06  5391.9  733.40  5509.4  737.92  5616.4  744.56
#Mann=6,-1,0
  4445.8    0.12       0  4620.8    0.05       0  4847.8    0.12       0
  4995.2    0.07       0  4999.2    0.12       0  5104.4    0.05       0
Bank Sta=4995.2,4999.2
Exp/Cntr=0.3,0.1

Type RM Length L Ch R = 1,1609,0,0,0
BEGIN DESCRIPTION:
MDW T 118 0.3
END DESCRIPTION:
XS GIS Cut Line= 4
      2302544.08      7132050.69      2302733.31      7132727.74
      2303091.89      7132780.47      2303531.89      7132267.70
#Sta/Elev= 30
  3948.1  743.32  3984.3  738.66  4018.5  736.67  4023.7  737.93  4057.8  734.45
  4063.0  734.84  4103.1  732.04  4131.3  731.69  4155.0  732.81  4186.2  731.10
  4211.6  731.98  4383.5  729.91  4798.8  729.37  4879.2  728.83  4899.4  729.55
  4910.9  728.75  4970.2  728.95  4975.6  727.96  4990.4  729.29  5007.5  724.53
  5007.8  724.03  5011.5  724.53  5026.4  727.23  5047.3  729.07  5075.8  728.59
  5146.1  729.97  5194.6  729.35  5373.2  730.51  5494.0  732.86  5689.2  741.57
#Mann=6,-1,0
  3948.1    0.12       0  4211.6    0.05       0  4798.8    0.12       0
  5007.5    0.07       0  5011.5    0.12       0  5194.6    0.05       0
Bank Sta=5007.5,5011.5
Exp/Cntr=0.3,0.1

Chan Stop Cuts=-1