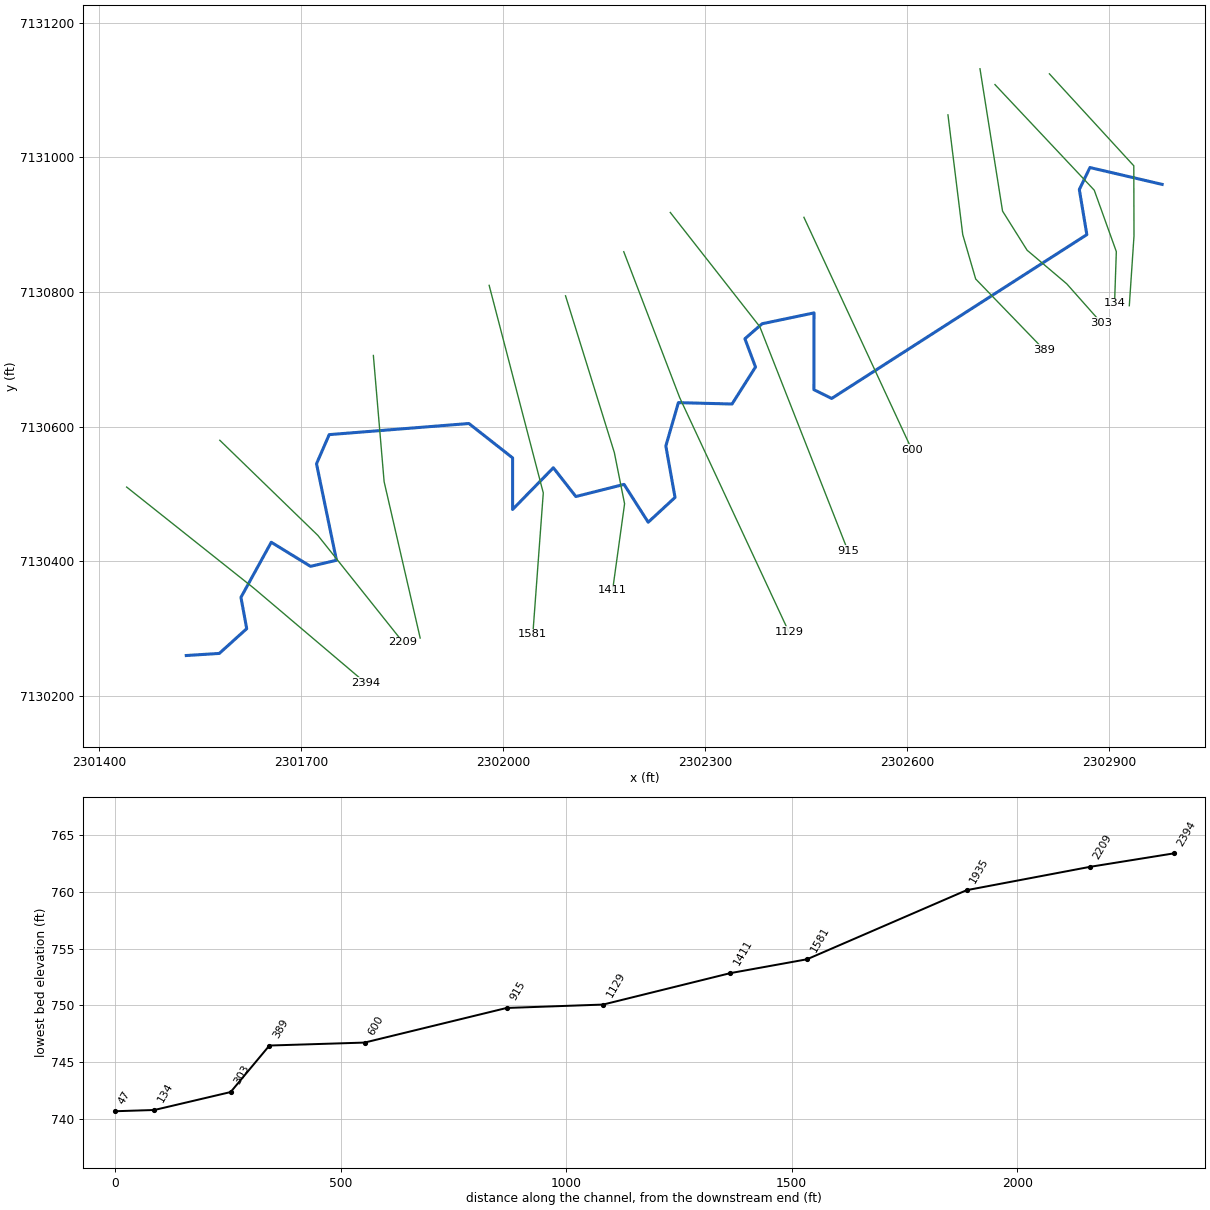
--- MDW T 119.prj (project) ---

Proj Title=MDW T 119 Base Level Engineering
Current Plan=p01
Default Exp/Contr=0.3,0.1
English Units
Geom File=g01
Flow File=f01
Plan File=p01
BEGIN DESCRIPTION:
MDW T 119
END DESCRIPTION:

--- MDW T 119.p01 (plan) ---

Plan Title=Multiple Run
Short Identifier=Multiple
Geom File=g01
Flow File=f01
Subcritical Flow
K Sum by GR= 0
Std Step Tol= 0.01
Critical Tol= 0.01
Num of Std Step Trials= 20
Max Error Tol= 0.3
Flow Tol Ratio= 0.001
Split Flow NTrial= 30
Split Flow Tol= 0.02
Split Flow Ratio= 0.02
Log Output Level= 0
Friction Slope Method= 1
Unsteady Friction Slope Method= 2
Unsteady Bridges Friction Slope Method= 1
Parabolic Critical Depth
Global Vel Dist=  1 , 1 , 1
Global Log Level= 0
CheckData=True
Encroach Param= -1, 0, 0, 0
BEGIN DESCRIPTION:
Multiple Run
END DESCRIPTION:

--- MDW T 119.f01 (steady flow) ---

Flow Title=Multiple
Number of Profiles=7
Profile Names=10-year,25-year,50-year,1pct_min,100-year,1pct_plu,500-year
River Rch & RM= MDW T 119,Reach-1,2394
     288     377     448     266     530    1058     741
Boundary for River Rch & Prof#=MDW T 119,Reach-1,1
Up Type=0
Dn Type=3
Dn Slope=0.005
Boundary for River Rch & Prof#=MDW T 119,Reach-1,2
Up Type=0
Dn Type=3
Dn Slope=0.005
Boundary for River Rch & Prof#=MDW T 119,Reach-1,3
Up Type=0
Dn Type=3
Dn Slope=0.005
Boundary for River Rch & Prof#=MDW T 119,Reach-1,4
Up Type=0
Dn Type=3
Dn Slope=0.005
Boundary for River Rch & Prof#=MDW T 119,Reach-1,5
Up Type=0
Dn Type=3
Dn Slope=0.005
Boundary for River Rch & Prof#=MDW T 119,Reach-1,6
Up Type=0
Dn Type=3
Dn Slope=0.005
Boundary for River Rch & Prof#=MDW T 119,Reach-1,7
Up Type=0
Dn Type=3
Dn Slope=0.005

--- MDW T 119.g01 (geometry) ---

Geom Title=Existing Conditions

River Reach=MDW T 119,Reach-1
Reach XY= 30
      2301529.00      7130260.00      2301578.02      7130263.12
      2301618.78      7130299.89      2301610.22      7130346.41
      2301655.26      7130428.30      2301713.60      7130392.50
      2301752.15      7130401.52      2301722.48      7130544.91
      2301741.36      7130588.21      2301948.91      7130604.73
      2302013.85      7130553.68      2302013.84      7130477.04
      2302074.38      7130538.98      2302107.84      7130496.22
      2302179.43      7130514.27      2302215.31      7130458.06
      2302255.19      7130494.88      2302241.51      7130571.37
      2302260.16      7130635.74      2302339.89      7130633.70
      2302374.75      7130688.66      2302359.01      7130730.65
      2302384.54      7130752.95      2302461.67      7130769.08
      2302461.51      7130654.99      2302487.95      7130641.94
      2302867.04      7130885.37      2302855.88      7130952.31
      2302871.64      7130985.05      2302979.00      7130960.00

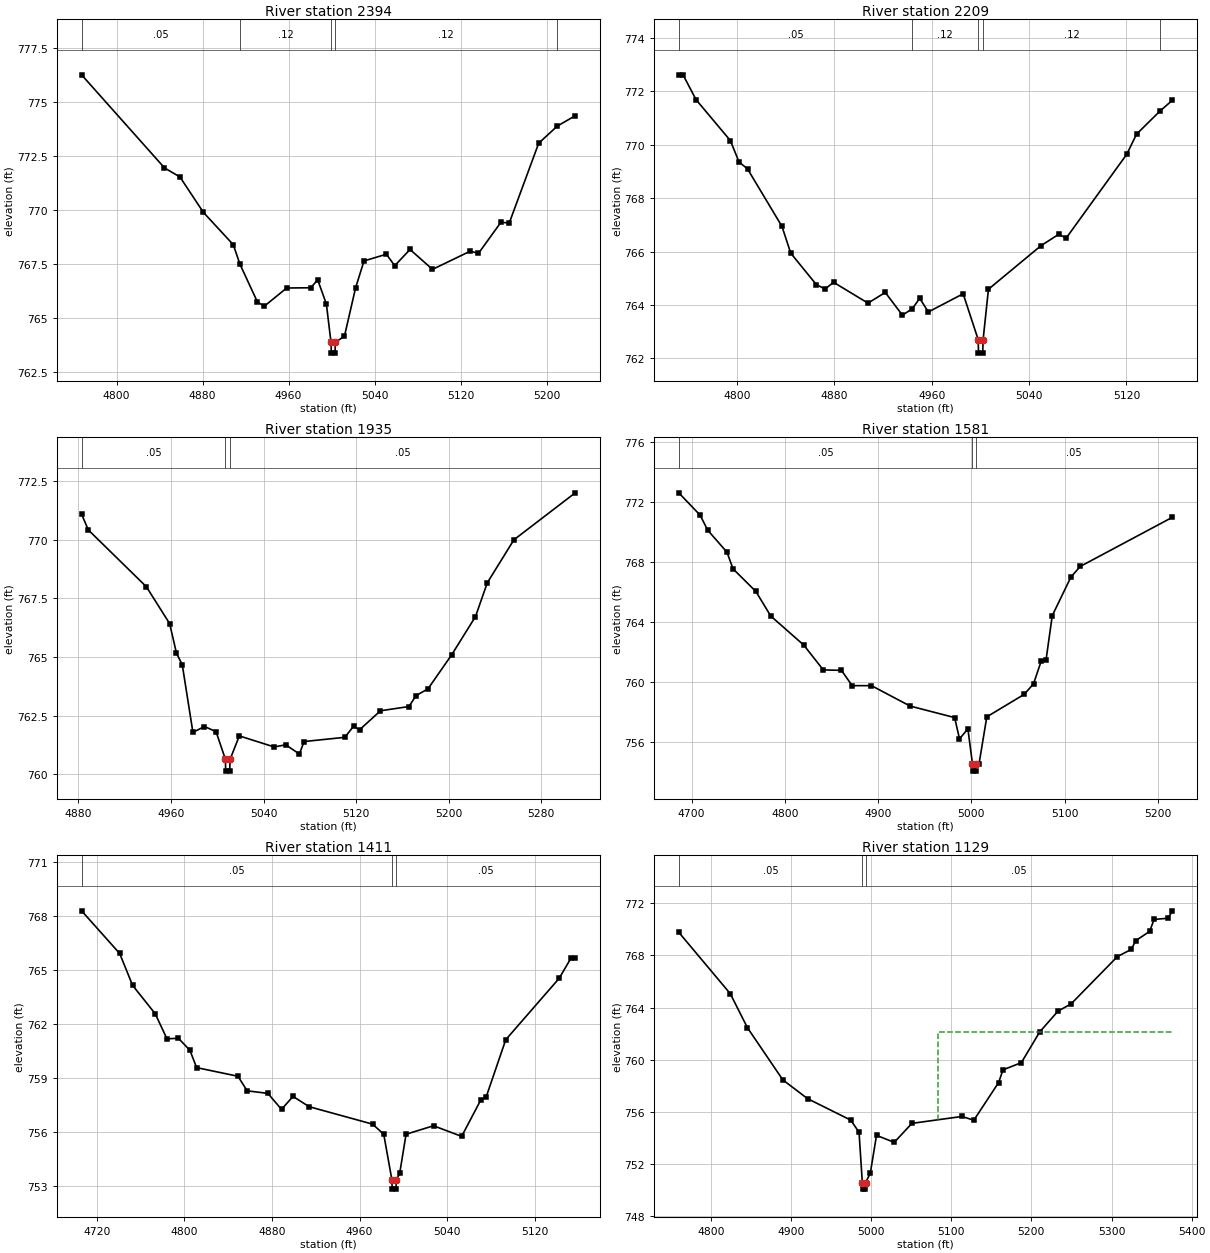
Type RM Length L Ch R = 1,2394,185,185,185
BEGIN DESCRIPTION:
MDW T 119 6.0
END DESCRIPTION:
XS GIS Cut Line= 3
      2301440.38      7130510.32      2301629.32      7130360.09
      2301795.47      7130219.25
#Sta/Elev= 30
  4767.5  776.24  4844.6  771.94  4859.0  771.52  4880.7  769.89  4908.6  768.39
  4914.8  767.49  4931.1  765.74  4937.5  765.55  4958.3  766.39  4980.7  766.40
  4987.1  766.77  4995.2  765.65  4999.5  763.88  4999.8  763.38  5003.3  763.38
  5003.5  763.88  5012.0  764.16  5022.4  766.40  5030.2  767.64  5051.0  767.95
  5058.8  767.42  5073.0  768.17  5093.9  767.25  5129.0  768.09  5136.7  767.99
  5157.6  769.43  5165.3  769.39  5192.7  773.08  5210.0  773.87  5226.7  774.35
#Mann=5,-1,0
  4767.5    0.05       0  4914.8    0.12       0  4999.5    0.07       0
  5003.5    0.12       0  5210.0    0.05       0
Bank Sta=4999.5,5003.5
Exp/Cntr=0.3,0.1

Type RM Length L Ch R = 1,2209,274,274,274
BEGIN DESCRIPTION:
Mapping XS f2ce0bc3
END DESCRIPTION:
XS GIS Cut Line= 3
      2301578.80      7130579.83      2301724.39      7130438.59
      2301850.82      7130279.95
#Sta/Elev= 30
  4752.1  772.61  4755.6  772.61  4766.3  771.68  4794.5  770.15  4801.6  769.35
  4808.6  769.09  4836.9  766.94  4844.1  765.94  4865.2  764.76  4872.4  764.60
  4879.3  764.85  4907.6  764.07  4921.8  764.47  4935.9  763.62  4944.0  763.86
  4950.1  764.25  4957.2  763.74  4985.8  764.42  4998.2  762.70  4998.4  762.20
  5001.9  762.20  5002.2  762.70  5006.6  764.59  5049.8  766.22  5064.2  766.64
  5070.6  766.51  5120.3  769.64  5128.3  770.39  5147.7  771.26  5157.8  771.66
#Mann=5,-1,0
  4752.1    0.05       0  4944.0    0.12       0  4998.2    0.07       0
  5002.2    0.12       0  5147.7    0.05       0
Bank Sta=4998.2,5002.2
Exp/Cntr=0.3,0.1

Type RM Length L Ch R = 1,1935,354,354,354
BEGIN DESCRIPTION:
MDW T 119 5.0
END DESCRIPTION:
XS GIS Cut Line= 3
      2301806.96      7130705.81      2301822.95      7130518.24
      2301876.52      7130285.99
#Sta/Elev= 30
  4882.7  771.08  4888.5  770.41  4938.7  767.99  4958.8  766.42  4964.7  765.16
  4969.7  764.67  4978.9  761.79  4988.9  762.04  4998.9  761.82  5007.0  760.64
  5007.2  760.14  5010.7  760.14  5011.0  760.64  5019.0  761.64  5049.1  761.17
  5059.1  761.26  5070.9  760.87  5075.0  761.40  5110.2  761.58  5117.7  762.05
  5122.9  761.90  5141.0  762.71  5165.6  762.89  5171.8  763.36  5182.0  763.64
  5202.6  765.10  5223.1  766.72  5233.3  768.16  5256.3  769.99  5309.3  771.99
#Mann=3,-1,0
  4882.7    0.05       0  5007.0   0.033       0  5011.0    0.05       0
Bank Sta=5007,5011
Exp/Cntr=0.3,0.1

Type RM Length L Ch R = 1,1581,170,170,170
BEGIN DESCRIPTION:
MDW T 119 4.0
END DESCRIPTION:
XS GIS Cut Line= 3
      2301978.99      7130810.03      2302059.42      7130501.60
      2302043.88      7130291.42
#Sta/Elev= 30
  4686.2  772.61  4709.1  771.12  4717.2  770.12  4737.9  768.65  4744.4  767.54
  4768.9  766.03  4784.9  764.39  4820.2  762.46  4841.2  760.80  4860.7  760.77
  4872.2  759.75  4892.9  759.75  4934.3  758.39  4982.1  757.62  4987.3  756.20
  4996.3  756.87  5001.2  754.55  5001.4  754.05  5004.9  754.05  5005.2  754.55
  5008.3  754.55  5016.6  757.67  5056.7  759.17  5066.7  759.87  5075.1  761.42
  5080.1  761.45  5086.8  764.42  5106.8  766.99  5116.8  767.70  5215.7  770.98
#Mann=3,-1,0
  4686.2    0.05       0  5001.2   0.033       0  5005.2    0.05       0
Bank Sta=5001.2,5005.2
Exp/Cntr=0.3,0.1

Type RM Length L Ch R = 1,1411,282,282,282
BEGIN DESCRIPTION:
Mapping XS ca25bffd
END DESCRIPTION:
XS GIS Cut Line= 4
      2302092.49      7130794.49      2302164.95      7130561.75
      2302180.22      7130485.46      2302162.44      7130357.14
#Sta/Elev= 30
  4706.0  768.29  4740.8  765.92  4752.6  764.15  4773.3  762.57  4784.0  761.18
  4794.5  761.21  4805.0  760.54  4811.1  759.58  4848.9  759.10  4857.3  758.29
  4876.2  758.15  4888.7  757.26  4899.2  757.98  4913.9  757.41  4971.9  756.44
  4982.1  755.88  4989.6  753.33  4989.8  752.83  4993.3  752.83  4993.6  753.33
  4996.7  753.71  5002.5  755.88  5027.6  756.35  5053.3  755.76  5070.6  757.76
  5075.7  757.95  5093.6  761.13  5142.4  764.54  5153.1  765.65  5157.1  765.65
#Mann=3,-1,0
  4706.0    0.05       0  4989.6   0.033       0  4993.6    0.05       0
Bank Sta=4989.6,4993.6
Exp/Cntr=0.3,0.1

Type RM Length L Ch R = 1,1129,214,214,214
BEGIN DESCRIPTION:
MDW T 119 3.0
END DESCRIPTION:
XS GIS Cut Line= 3
      2302179.01      7130859.98      2302261.96      7130643.50
      2302424.18      7130295.37
#Sta/Elev= 30
  4760.1  769.78  4824.3  765.07  4845.8  762.45  4889.9  758.45  4920.7  757.01
  4974.6  755.36  4985.0  754.43  4989.1  750.56  4989.4  750.06  4992.9  750.06
  4993.1  750.56  4999.0  751.27  5006.8  754.19  5028.9  753.65  5051.0  755.11
  5113.4  755.64  5128.2  755.35  5159.1  758.24  5164.6  759.22  5187.5  759.77
  5210.4  762.13  5233.3  763.73  5249.5  764.28  5307.4  767.92  5324.7  768.47
  5330.2  769.14  5347.6  769.85  5353.1  770.77  5370.5  770.86  5376.0  771.43
#Mann=3,-1,0
  4760.1    0.05       0  4989.1   0.033       0  4993.1    0.05       0
#XS Ineff=2,0
       0                 5082.90    0.00  762.10
Permanent Ineff=
       F       F
Bank Sta=4989.1,4993.1
Exp/Cntr=0.3,0.1

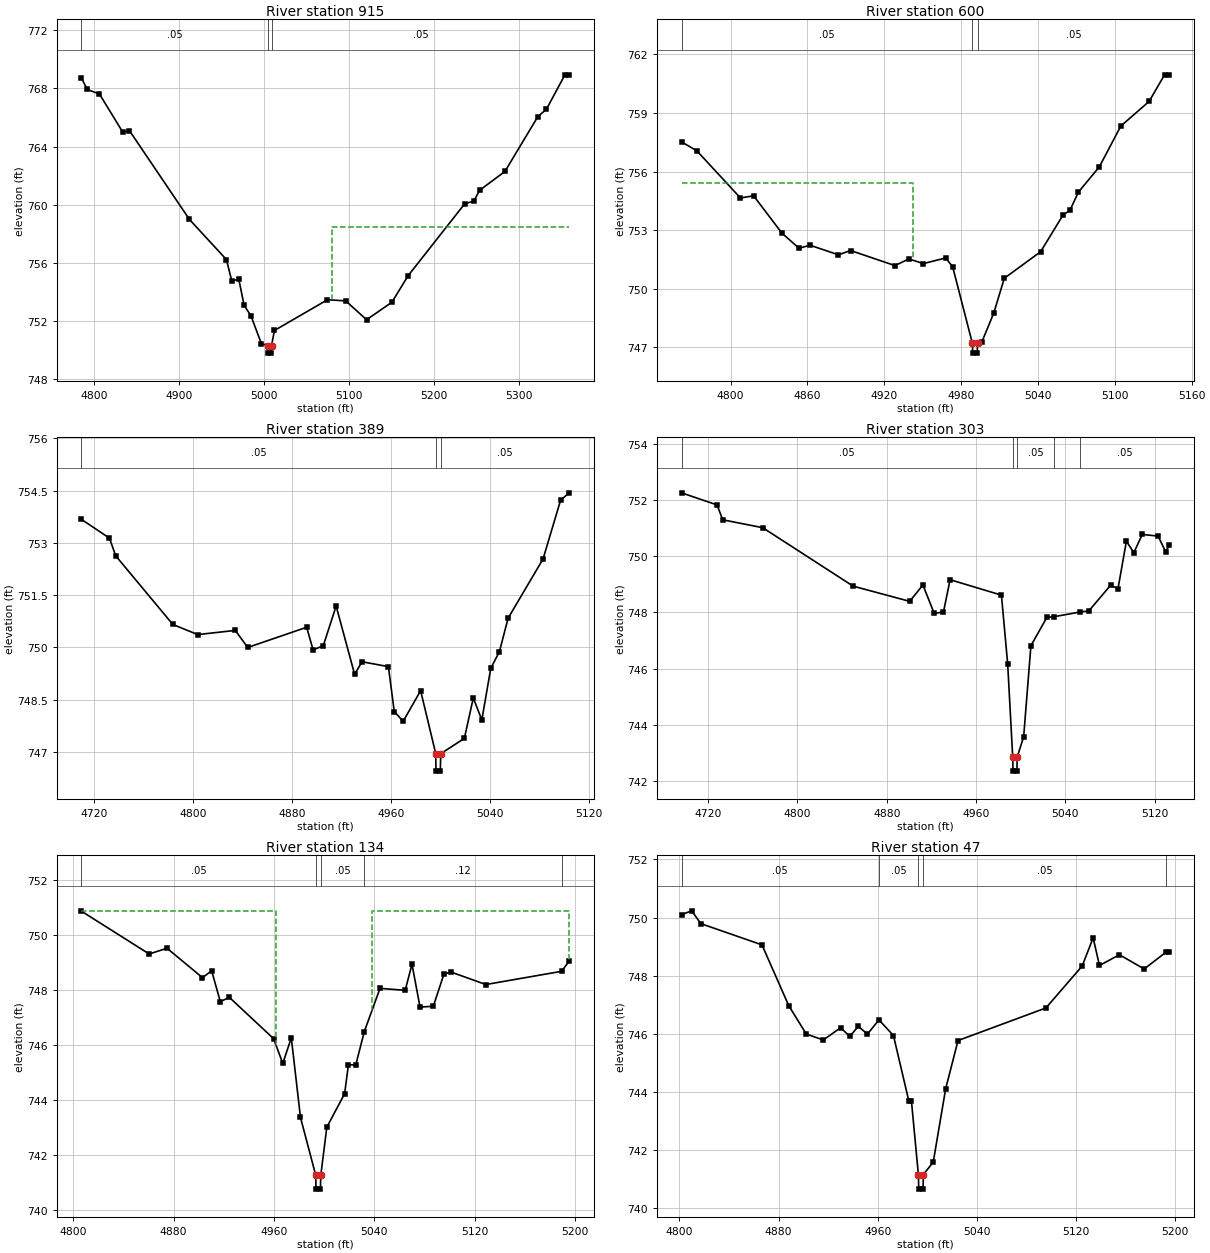
Type RM Length L Ch R = 1,915,315,315,315
BEGIN DESCRIPTION:
MDW T 119 2.0
END DESCRIPTION:
XS GIS Cut Line= 3
      2302248.11      7130918.31      2302381.13      7130748.59
      2302512.00      7130415.73
#Sta/Elev= 30
  4785.4  768.75  4792.3  767.93  4806.7  767.62  4834.1  764.99  4842.0  765.09
  4912.5  758.97  4955.9  756.21  4962.3  754.72  4970.4  754.87  4976.7  753.06
  4984.8  752.32  4997.0  750.42  5004.9  750.26  5005.1  749.76  5008.6  749.76
  5008.9  750.26  5012.3  751.32  5074.7  753.44  5096.2  753.36  5120.6  752.06
  5150.4  753.27  5169.5  755.10  5235.9  760.05  5246.7  760.24  5253.4  760.98
  5283.2  762.28  5321.9  766.06  5332.0  766.57  5353.7  768.94  5358.7  768.94
#Mann=3,-1,0
  4785.4    0.05       0  5004.9   0.033       0  5008.9    0.05       0
#XS Ineff=2,0
    0.00 4920.10  758.42 5079.90    0.00  758.42
Permanent Ineff=
       F       F
Bank Sta=5004.9,5008.9
Exp/Cntr=0.3,0.1

Type RM Length L Ch R = 1,600,211,211,211
BEGIN DESCRIPTION:
Mapping XS ebab7582
END DESCRIPTION:
XS GIS Cut Line= 2
      2302446.69      7130911.09      2302607.15      7130565.63
#Sta/Elev= 30
  4761.7  757.52  4773.7  757.06  4807.7  754.65  4818.0  754.76  4840.1  752.85
  4853.4  752.08  4862.1  752.23  4884.2  751.74  4893.7  751.96  4928.3  751.19
  4939.3  751.53  4950.5  751.29  4967.9  751.58  4973.4  751.13  4988.8  747.21
  4989.1  746.71  4992.6  746.71  4992.8  747.21  4996.3  747.30  5005.5  748.76
  5013.7  750.54  5042.1  751.90  5059.5  753.77  5065.0  754.02  5071.6  754.95
  5087.9  756.24  5104.7  758.33  5126.8  759.59  5138.8  760.95  5142.6  760.95
#Mann=3,-1,0
  4761.7    0.05       0  4988.8   0.033       0  4992.8    0.05       0
#XS Ineff=2,0
    0.00 4942.40  755.43               0
Permanent Ineff=
       F       F
Bank Sta=4988.8,4992.8
Exp/Cntr=0.3,0.1

Type RM Length L Ch R = 1,389,86,86,86
BEGIN DESCRIPTION:
Mapping XS 5fe25b1f
END DESCRIPTION:
XS GIS Cut Line= 4
      2302660.69      7131063.32      2302682.67      7130885.37
      2302701.87      7130819.47      2302803.23      7130714.58
#Sta/Elev= 30
  4710.0  753.68  4732.7  753.14  4737.8  752.63  4783.9  750.66  4804.0  750.37
  4834.3  750.49  4844.3  750.00  4891.9  750.58  4897.1  749.93  4905.3  750.05
  4915.7  751.19  4930.6  749.23  4936.6  749.59  4957.9  749.45  4962.6  748.16
  4969.8  747.88  4983.9  748.76  4996.1  746.95  4996.3  746.45  4999.8  746.45
  5000.1  746.95  5019.2  747.39  5026.4  748.55  5033.3  747.92  5040.5  749.40
  5047.5  749.88  5054.5  750.84  5082.7  752.54  5096.9  754.23  5103.8  754.44
#Mann=3,-1,0
  4710.0    0.05       0  4996.1   0.033       0  5000.1    0.05       0
Bank Sta=4996.1,5000.1
Exp/Cntr=0.3,0.1

Type RM Length L Ch R = 1,303,169,169,169
BEGIN DESCRIPTION:
Mapping XS 70d8e8d8
END DESCRIPTION:
XS GIS Cut Line= 5
      2302708.28      7131131.82      2302741.79      7130920.37
      2302778.28      7130862.21      2302837.21      7130812.26
      2302888.22      7130754.71
#Sta/Elev= 30
  4696.2  752.25  4728.0  751.82  4733.1  751.29  4768.9  751.01  4849.9  748.93
  4900.5  748.39  4912.4  748.97  4922.5  747.96  4930.8  748.01  4936.7  749.16
  4982.7  748.61  4988.3  746.16  4992.8  742.85  4993.1  742.35  4996.6  742.35
  4996.8  742.85  5002.6  743.57  5009.1  746.81  5023.4  747.82  5029.4  747.84
  5053.1  748.01  5061.0  748.05  5080.4  748.96  5087.1  748.84  5094.6  750.53
  5101.3  750.12  5108.8  750.77  5123.0  750.71  5129.7  750.16  5133.1  750.38
#Mann=5,-1,0
  4696.2    0.05       0  4992.8   0.033       0  4996.8    0.05       0
  5029.4    0.12       0  5053.1    0.05       0
Bank Sta=4992.8,4996.8
Exp/Cntr=0.3,0.1

Type RM Length L Ch R = 1,134,87,87,87
BEGIN DESCRIPTION:
Mapping XS 77886f93
END DESCRIPTION:
XS GIS Cut Line= 4
      2302730.55      7131108.29      2302878.07      7130951.40
      2302910.86      7130860.14      2302908.24      7130783.61
#Sta/Elev= 30
  4806.5  750.88  4860.6  749.32  4874.8  749.53  4903.1  748.46  4910.4  748.71
  4917.3  747.59  4924.6  747.74  4959.8  746.24  4967.1  745.34  4973.9  746.27
  4981.2  743.38  4993.4  741.27  4993.6  740.77  4997.1  740.77  4997.4  741.27
  5002.2  743.02  5016.4  744.24  5019.4  745.29  5025.3  745.29  5032.1  746.50
  5044.6  748.07  5064.7  748.00  5070.1  748.95  5076.5  747.39  5087.1  747.42
  5095.5  748.58  5100.8  748.67  5129.0  748.21  5189.3  748.69  5195.4  749.06
#Mann=5,-1,0
  4806.5    0.05       0  4993.4   0.033       0  4997.4    0.05       0
  5032.1    0.12       0  5189.3    0.05       0
#XS Ineff=2,0
    0.00 4961.90  750.89 5038.10    0.00  750.89
Permanent Ineff=
       F       F
Bank Sta=4993.4,4997.4
Exp/Cntr=0.3,0.1

Type RM Length L Ch R = 1,47,0,0,0
BEGIN DESCRIPTION:
MDW T 119 1.0
END DESCRIPTION:
XS GIS Cut Line= 4
      2302811.41      7131124.28      2302936.82      7130987.64
      2302937.11      7130883.23      2302930.14      7130779.74
#Sta/Elev= 30
  4801.7  750.10  4809.9  750.23  4817.3  749.79  4866.6  749.06  4888.2  746.97
  4902.4  745.99  4916.1  745.79  4930.1  746.21  4937.5  745.91  4944.3  746.26
  4951.7  745.99  4961.0  746.48  4972.7  745.94  4985.1  743.69  4987.2  743.69
  4992.8  741.16  4993.1  740.66  4996.6  740.66  4996.8  741.16  5004.8  741.59
  5014.8  744.11  5024.8  745.77  5095.7  746.89  5124.9  748.33  5133.8  749.30
  5138.9  748.35  5155.0  748.72  5175.0  748.23  5192.6  748.81  5195.3  748.81
#Mann=5,-1,0
  4801.7    0.05       0  4961.0    0.05       0  4992.8   0.033       0
  4996.8    0.05       0  5192.6    0.05       0
Bank Sta=4992.8,4996.8
Exp/Cntr=0.3,0.1

Chan Stop Cuts=-1