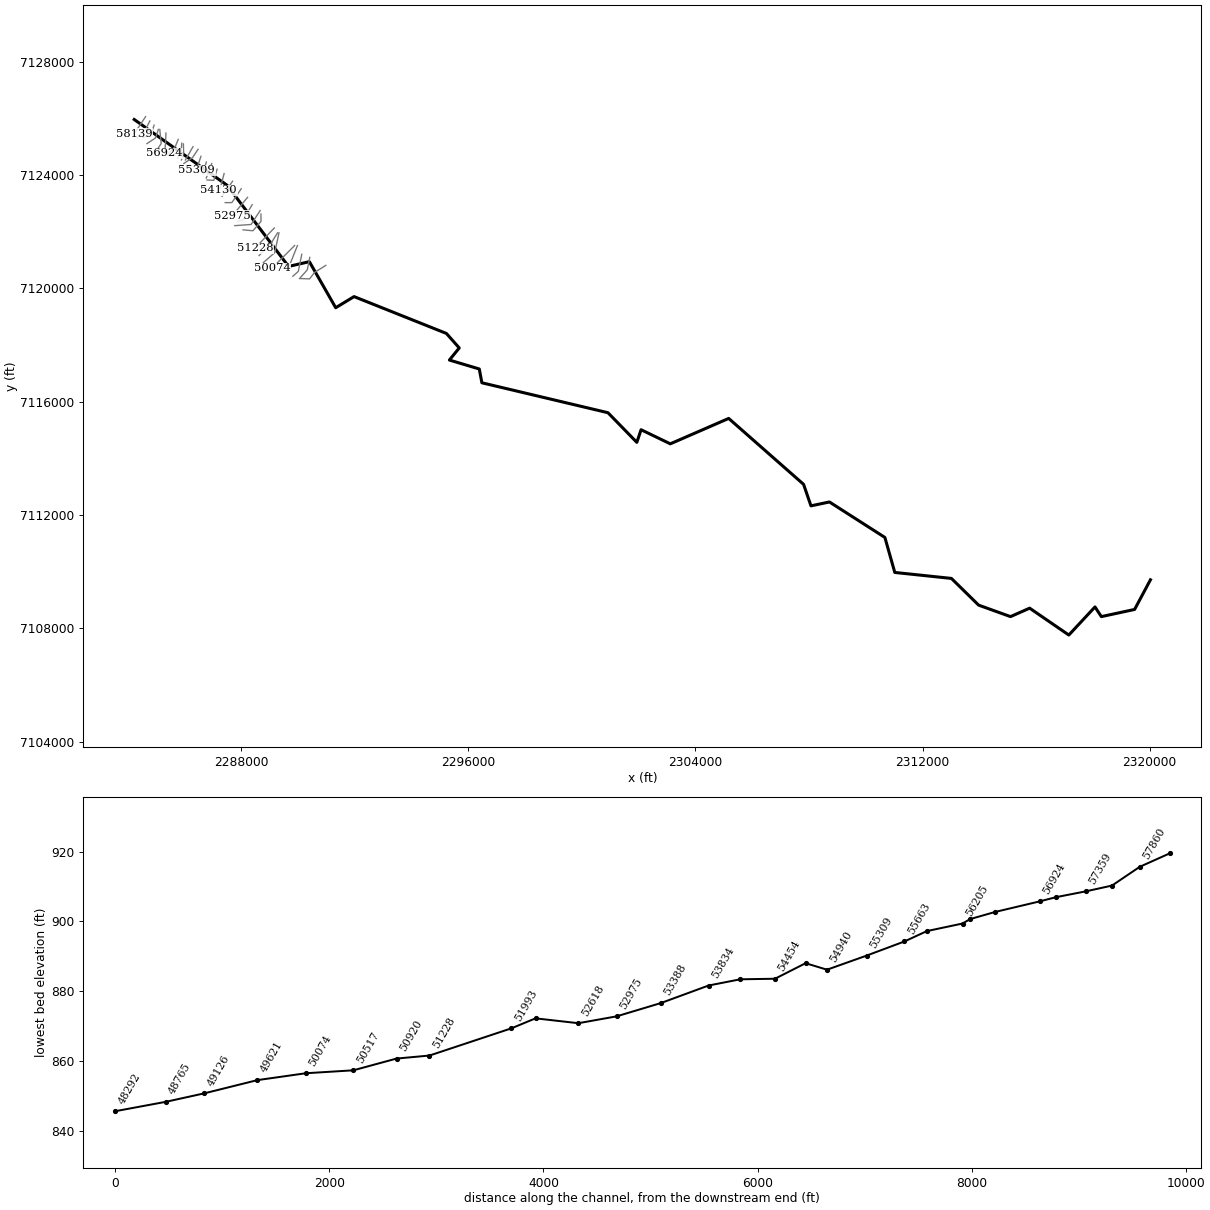
--- Morris Branch.prj (project) ---

Proj Title=Morris Branch Base Level Engineering
Current Plan=p01
Default Exp/Contr=0.3,0.1
English Units
Geom File=g01
Flow File=f01
Plan File=p01
BEGIN DESCRIPTION:
Morris Branch
END DESCRIPTION:

--- Morris Branch.p01 (plan) ---

Plan Title=Multiple Run
Short Identifier=Multiple
Geom File=g01
Flow File=f01
Subcritical Flow
K Sum by GR= 0
Std Step Tol= 0.01
Critical Tol= 0.01
Num of Std Step Trials= 20
Max Error Tol= 0.3
Flow Tol Ratio= 0.001
Split Flow NTrial= 30
Split Flow Tol= 0.02
Split Flow Ratio= 0.02
Log Output Level= 0
Friction Slope Method= 1
Unsteady Friction Slope Method= 2
Unsteady Bridges Friction Slope Method= 1
Parabolic Critical Depth
Global Vel Dist=  1 , 1 , 1
Global Log Level= 0
CheckData=True
Encroach Param= -1, 0, 0, 0
BEGIN DESCRIPTION:
Multiple Run
END DESCRIPTION:

--- Morris Branch.f01 (steady flow) ---

Flow Title=Multiple
Number of Profiles=7
Profile Names=10-year,25-year,50-year,1pct_min,100-year,1pct_plu,500-year
River Rch & RM= Morris Branch,Reach-1,58139
     470     638     776     469     937    1869    1366
River Rch & RM= Morris Branch,Reach-1,54130
     673     933    1151     705    1407    2807    2108
River Rch & RM= Morris Branch,Reach-1,53388
     686     954    1177     722    1441    2875    2163
River Rch & RM= Morris Branch,Reach-1,52975
     749    1045    1293     795    1586    3164    2390
River Rch & RM= Morris Branch,Reach-1,51228
    1042    1477    1847    1145    2284    4558    3507
River Rch & RM= Morris Branch,Reach-1,47402
    1199    1707    2141    1331    2655    5298    4098
River Rch & RM= Morris Branch,Reach-1,43192
    1332    1906    2398    1495    2983    5952    4630
River Rch & RM= Morris Branch,Reach-1,41841
    1541    2217    2800    1750    3492    6968    5453
River Rch & RM= Morris Branch,Reach-1,37012
    1727    2494    3158    1978    3947    7875    6187
River Rch & RM= Morris Branch,Reach-1,35228
    1824    2643    3353    2105    4200    8380    6612
River Rch & RM= Morris Branch,Reach-1,33091
    1987    2887    3672    2309    4608    9193    7281
River Rch & RM= Morris Branch,Reach-1,30839
    2045    2972    3779    2376    4740    9458    7486
River Rch & RM= Morris Branch,Reach-1,24526
    2695    3959    5070    3208    6400   12771   10238
River Rch & RM= Morris Branch,Reach-1,17904
    3155    4658    5987    3800    7581   15127   12201
River Rch & RM= Morris Branch,Reach-1,13442
    3401    5034    6481    4119    8219   16399   13267
River Rch & RM= Morris Branch,Reach-1,10973
    3424    5053    6493    4118    8217   16395   13207
Boundary for River Rch & Prof#=Morris Branch,Reach-1,1
Up Type=0
Dn Type=3
Dn Slope=0.005
Boundary for River Rch & Prof#=Morris Branch,Reach-1,2
Up Type=0
Dn Type=3
Dn Slope=0.005
Boundary for River Rch & Prof#=Morris Branch,Reach-1,3
Up Type=0
Dn Type=3
Dn Slope=0.005
Boundary for River Rch & Prof#=Morris Branch,Reach-1,4
Up Type=0
Dn Type=3
Dn Slope=0.005
Boundary for River Rch & Prof#=Morris Branch,Reach-1,5
Up Type=0
Dn Type=3
Dn Slope=0.005
Boundary for River Rch & Prof#=Morris Branch,Reach-1,6
Up Type=0
Dn Type=3
Dn Slope=0.005
Boundary for River Rch & Prof#=Morris Branch,Reach-1,7
Up Type=0
Dn Type=3
Dn Slope=0.005

--- Morris Branch.g01 (geometry) ---

Geom Title=Existing Conditions

River Reach=Morris Branch,Reach-1
Reach XY= 30
      2284229.00      7125960.00      2287499.16      7123640.37
      2289665.37      7120772.93      2290399.48      7120940.74
      2291326.62      7119315.37      2291973.33      7119708.02
      2295227.32      7118406.91      2295679.19      7117894.71
      2295331.90      7117467.91      2296385.09      7117152.52
      2296476.29      7116665.28      2300917.51      7115608.53
      2301934.97      7114562.14      2302084.85      7115007.94
      2303113.81      7114509.89      2305170.86      7115407.05
      2307809.21      7113080.09      2308069.32      7112320.19
      2308720.53      7112457.42      2310673.82      7111204.59
      2311022.33      7109968.96      2313017.17      7109758.38
      2313976.45      7108815.05      2315099.19      7108409.62
      2315773.33      7108708.02      2317153.88      7107759.71
      2318075.72      7108752.00      2318298.91      7108409.89
      2319470.69      7108662.97      2320029.00      7109710.00

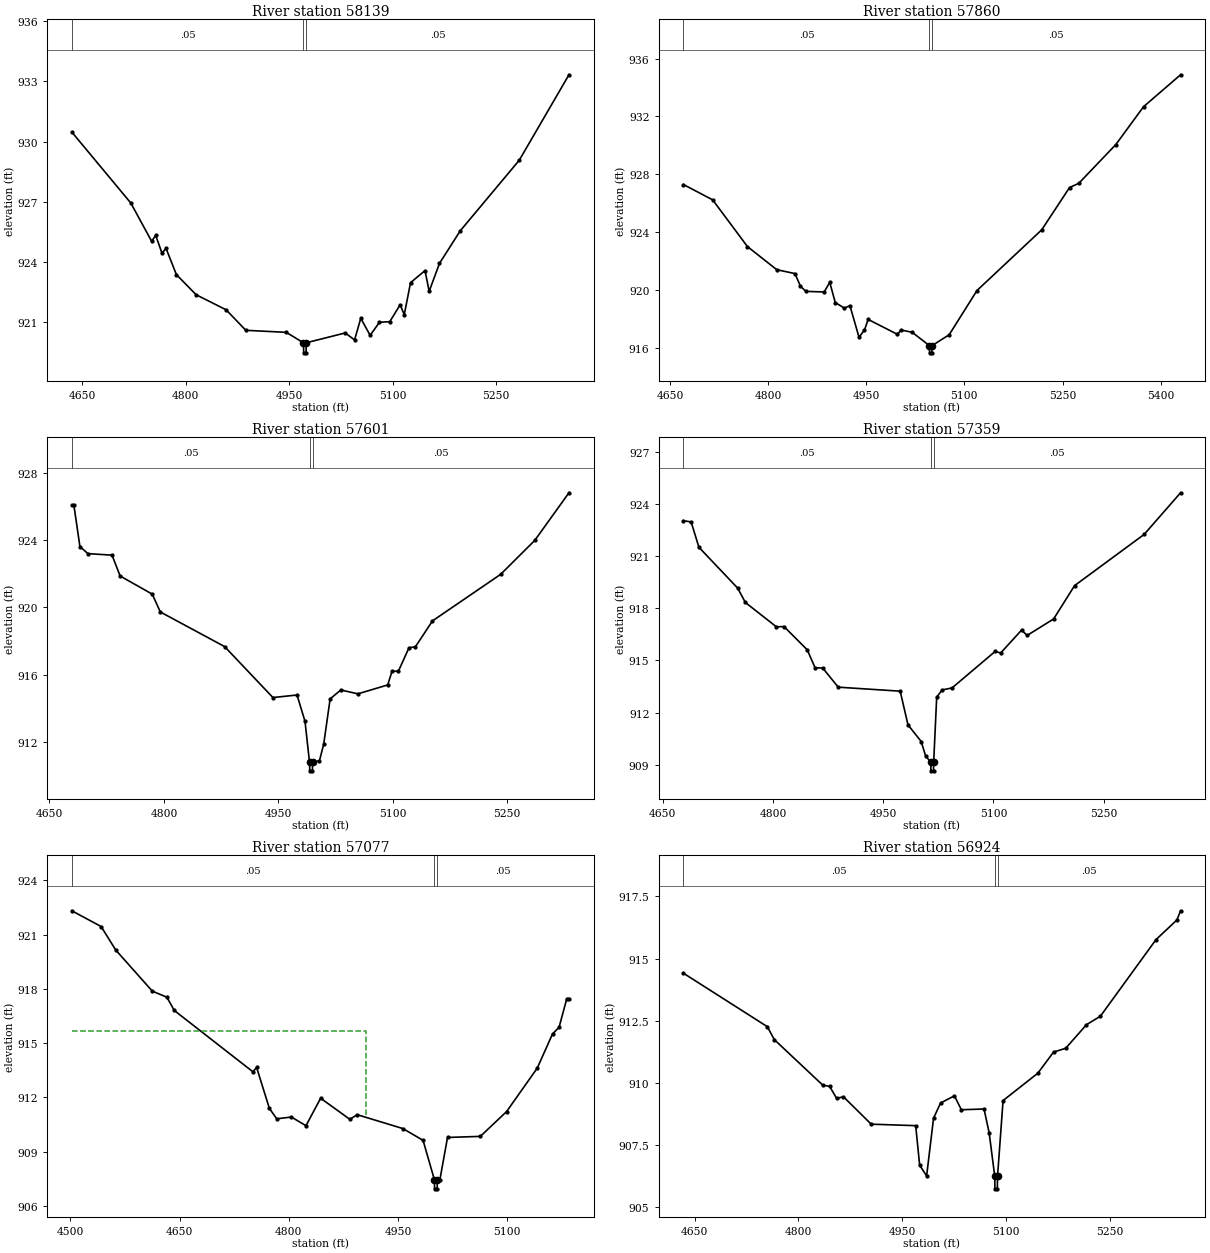
Type RM Length L Ch R = 1,58139,279,279,279
BEGIN DESCRIPTION:
Morris Branch 109.0
END DESCRIPTION:
XS GIS Cut Line= 3
      2284629.00      7126060.00      2284429.00      7125760.00
      2284229.01      7125460.01
#Sta/Elev= 30
  4634.7  930.47  4720.3  926.94  4750.4  925.04  4756.4  925.33  4765.4  924.45
  4771.4  924.68  4786.4  923.38  4815.0  922.38  4858.5  921.63  4887.1  920.61
  4945.7  920.51  4970.7  919.99  4971.0  919.49  4974.5  919.49  4974.7  919.99
  5031.3  920.48  5044.8  920.13  5053.8  921.21  5067.4  920.36  5080.9  921.01
  5095.9  921.04  5110.9  921.88  5116.9  921.39  5126.0  922.98  5147.0  923.58
  5153.0  922.55  5168.0  923.94  5198.1  925.56  5283.7  929.07  5355.8  933.32
#Mann=3,-1,0
  4634.7    0.05       0  4970.7    0.04       0  4974.7    0.05       0
Bank Sta=4970.7,4974.7
Exp/Cntr=0.3,0.1

Type RM Length L Ch R = 1,57860,259,259,259
BEGIN DESCRIPTION:
Morris Branch 108.0
END DESCRIPTION:
XS GIS Cut Line= 3
      2284779.01      7125910.02      2284629.00      7125610.00
      2284329.00      7125310.00
#Sta/Elev= 30
  4670.7  927.29  4715.4  926.23  4768.5  923.00  4813.3  921.40  4841.2  921.13
  4849.6  920.25  4858.0  919.90  4885.9  919.86  4894.3  920.53  4902.7  919.13
  4916.7  918.74  4925.1  918.92  4939.0  916.73  4947.4  917.23  4953.0  917.96
  4997.7  916.93  5003.3  917.23  5020.3  917.07  5046.6  916.15  5046.8  915.65
  5050.3  915.65  5050.6  916.15  5076.8  916.90  5119.3  919.96  5218.3  924.16
  5260.7  927.08  5274.8  927.37  5331.4  930.05  5373.8  932.67  5430.4  934.88
#Mann=3,-1,0
  4670.7    0.05       0  5046.6   0.033       0  5050.6    0.05       0
Bank Sta=5046.6,5050.6
Exp/Cntr=0.3,0.1

Type RM Length L Ch R = 1,57601,242,242,242
BEGIN DESCRIPTION:
Morris Branch 107.0
END DESCRIPTION:
XS GIS Cut Line= 3
      2284929.01      7125760.03      2284829.00      7125460.00
      2284528.97      7125309.99
#Sta/Elev= 30
  4679.3  926.08  4682.0  926.08  4689.9  923.62  4700.4  923.20  4732.0  923.11
  4742.6  921.87  4784.7  920.79  4795.3  919.73  4879.6  917.67  4942.9  914.64
  4974.5  914.79  4985.0  913.22  4990.9  910.78  4991.2  910.28  4994.7  910.28
  4994.9  910.78  5003.9  910.88  5009.5  911.87  5017.9  914.56  5031.9  915.09
  5054.3  914.86  5093.4  915.39  5099.0  916.20  5107.4  916.21  5121.3  917.60
  5129.7  917.66  5152.1  919.20  5241.5  921.97  5286.2  923.99  5331.0  926.82
#Mann=3,-1,0
  4679.3    0.05       0  4990.9   0.033       0  4994.9    0.05       0
Bank Sta=4990.9,4994.9
Exp/Cntr=0.3,0.1

Type RM Length L Ch R = 1,57359,282,282,282
BEGIN DESCRIPTION:
Morris Branch 106.0
END DESCRIPTION:
XS GIS Cut Line= 3
      2285078.99      7125609.98      2284979.00      7125310.00
      2284678.97      7125109.98
#Sta/Elev= 30
  4678.0  923.05  4688.5  922.98  4699.1  921.52  4751.8  919.17  4762.3  918.34
  4804.5  916.94  4815.0  916.95  4846.6  915.61  4857.2  914.58  4867.7  914.56
  4888.8  913.46  4973.1  913.23  4983.7  911.29  5001.7  910.33  5007.7  909.50
  5014.7  909.14  5015.0  908.64  5018.5  908.64  5018.7  909.14  5022.8  912.89
  5030.3  913.30  5043.8  913.42  5102.4  915.52  5109.9  915.43  5138.4  916.75
  5145.9  916.44  5182.0  917.39  5210.5  919.31  5305.2  922.26  5354.8  924.66
#Mann=3,-1,0
  4678.0    0.05       0  5014.7   0.033       0  5018.7    0.05       0
Bank Sta=5014.7,5018.7
Exp/Cntr=0.3,0.1

Type RM Length L Ch R = 1,57077,153,153,153
BEGIN DESCRIPTION:
Morris Branch 105.0
END DESCRIPTION:
XS GIS Cut Line= 3
      2285129.00      7125610.00      2285179.00      7125110.00
      2285078.98      7124959.97
#Sta/Elev= 30
  4502.0  922.32  4542.2  921.45  4562.3  920.15  4612.5  917.88  4632.6  917.54
  4642.7  916.81  4750.7  913.42  4755.8  913.66  4773.3  911.40  4783.4  910.82
  4803.5  910.92  4823.6  910.44  4843.7  911.96  4883.9  910.79  4893.9  911.05
  4956.8  910.28  4984.4  909.63  5000.0  907.45  5000.2  906.95  5003.7  906.95
  5004.0  907.45  5007.5  907.45  5018.0  909.79  5063.1  909.85  5099.1  911.22
  5141.2  913.62  5162.2  915.51  5171.2  915.88  5181.8  917.46  5184.8  917.46
#Mann=3,-1,0
  4502.0    0.05       0  5000.0   0.033       0  5004.0    0.05       0
#XS Ineff=2,0
    0.00 4906.40  915.67               0
Permanent Ineff=
       F       F
Bank Sta=5000,5004
Exp/Cntr=0.3,0.1

Type RM Length L Ch R = 1,56924,415,415,415
BEGIN DESCRIPTION:
Mapping XS b6281dbc
END DESCRIPTION:
XS GIS Cut Line= 3
      2285346.63      7125481.26      2285333.57      7125145.67
      2285295.52      7124764.71
#Sta/Elev= 30
  4633.9  914.41  4755.2  912.26  4765.3  911.74  4835.3  909.91  4845.3  909.86
  4855.3  909.38  4865.3  909.44  4905.4  908.34  4969.7  908.28  4975.4  906.69
  4985.5  906.26  4995.5  908.58  5005.6  909.19  5025.7  909.48  5035.7  908.92
  5068.5  908.95  5075.9  907.99  5084.0  906.24  5084.2  905.74  5087.7  905.74
  5088.0  906.24  5096.0  909.29  5146.3  910.39  5169.0  911.24  5186.5  911.39
  5216.6  912.34  5236.7  912.68  5317.1  915.76  5347.3  916.55  5352.6  916.92
#Mann=3,-1,0
  4633.9    0.05       0  5084.0   0.033       0  5088.0    0.05       0
Bank Sta=5084,5088
Exp/Cntr=0.3,0.1

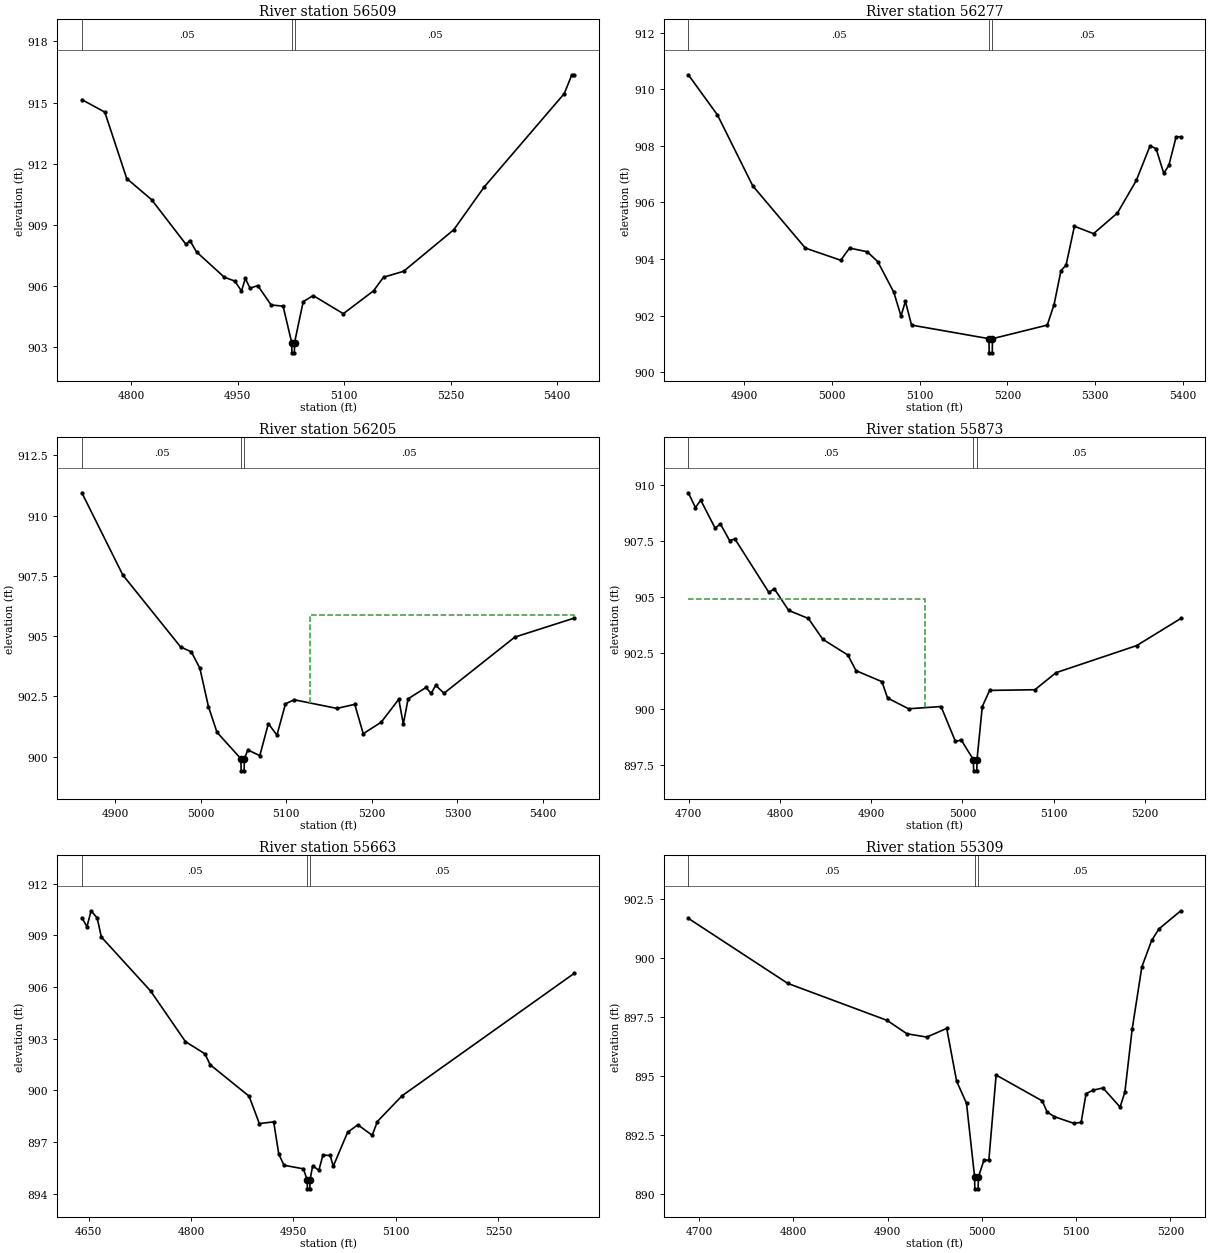
Type RM Length L Ch R = 1,56509,232,232,232
BEGIN DESCRIPTION:
Morris Branch 103.0
END DESCRIPTION:
XS GIS Cut Line= 3
      2285778.99      7125259.97      2285679.00      7125010.00
      2285379.00      7124710.00
#Sta/Elev= 30
  4730.5  915.14  4762.8  914.53  4793.7  911.27  4828.8  910.23  4877.2  908.04
  4882.6  908.23  4892.0  907.67  4931.1  906.43  4945.9  906.24  4955.3  905.75
  4960.7  906.37  4967.4  905.89  4978.2  906.02  4997.0  905.07  5013.9  905.01
  5026.0  903.22  5026.3  902.72  5029.8  902.72  5030.0  903.22  5042.2  905.23
  5056.3  905.53  5098.7  904.64  5141.2  905.76  5155.3  906.43  5183.6  906.72
  5254.3  908.76  5296.7  910.84  5409.9  915.44  5420.5  916.36  5424.0  916.36
#Mann=3,-1,0
  4730.5    0.05       0  5026.0   0.033       0  5030.0    0.05       0
Bank Sta=5026,5030
Exp/Cntr=0.3,0.1

Type RM Length L Ch R = 1,56277,72,72,72
BEGIN DESCRIPTION:
Mapping XS c3412025
END DESCRIPTION:
XS GIS Cut Line= 4
      2285903.26      7125123.13      2285888.98      7124910.90
      2285870.17      7124789.51      2285755.65      7124595.77
#Sta/Elev= 30
  4836.7  910.51  4869.9  909.09  4910.0  906.59  4969.9  904.39  5010.2  903.96
  5020.2  904.39  5040.3  904.26  5052.4  903.91  5070.6  902.83  5078.8  901.99
  5083.8  902.51  5090.8  901.67  5178.9  901.19  5179.2  900.69  5182.7  900.69
  5182.9  901.19  5245.3  901.67  5253.0  902.39  5260.9  903.59  5266.7  903.79
  5276.2  905.16  5298.0  904.90  5325.2  905.63  5346.7  906.78  5362.3  908.00
  5369.2  907.90  5377.9  907.03  5383.7  907.31  5392.0  908.32  5397.3  908.32
#Mann=3,-1,0
  4836.7    0.05       0  5178.9   0.033       0  5182.9    0.05       0
Bank Sta=5178.9,5182.9
Exp/Cntr=0.3,0.1

Type RM Length L Ch R = 1,56205,332,332,332
BEGIN DESCRIPTION:
Mapping XS 0a1d675c
END DESCRIPTION:
XS GIS Cut Line= 4
      2285961.73      7125097.75      2285965.48      7124903.00
      2285972.11      7124784.02      2285894.61      7124534.63
#Sta/Elev= 30
  4861.4  910.95  4909.2  907.54  4976.8  904.55  4989.2  904.35  4999.2  903.67
  5009.2  902.08  5019.2  901.01  5047.2  899.91  5047.4  899.41  5050.9  899.41
  5051.2  899.91  5055.2  900.28  5069.2  900.04  5079.2  901.37  5089.2  900.89
  5099.2  902.19  5109.3  902.36  5159.3  902.00  5180.1  902.17  5190.0  900.95
  5211.0  901.43  5231.5  902.38  5236.8  901.35  5242.4  902.40  5263.3  902.87
  5269.3  902.62  5274.6  902.96  5284.3  902.63  5367.0  904.96  5436.5  905.75
#Mann=3,-1,0
  4861.4    0.05       0  5047.2   0.033       0  5051.2    0.05       0
#XS Ineff=2,0
       0                 5127.30    0.00  905.87
Permanent Ineff=
       F       F
Bank Sta=5047.2,5051.2
Exp/Cntr=0.3,0.1

Type RM Length L Ch R = 1,55873,210,210,210
BEGIN DESCRIPTION:
Mapping XS 6236102f
END DESCRIPTION:
XS GIS Cut Line= 2
      2286299.27      7124999.33      2286031.00      7124531.37
#Sta/Elev= 30
  4699.7  909.66  4707.5  909.00  4713.3  909.33  4729.1  908.08  4734.8  908.27
  4744.9  907.53  4750.7  907.60  4788.0  905.21  4793.8  905.38  4809.6  904.41
  4831.2  904.05  4847.0  903.12  4874.4  902.42  4883.4  901.72  4911.8  901.23
  4917.9  900.50  4941.0  900.02  4976.5  900.12  4992.3  898.56  4998.6  898.63
  5011.9  897.75  5012.2  897.25  5015.7  897.25  5015.9  897.75  5021.7  900.12
  5029.7  900.84  5079.3  900.87  5102.4  901.63  5190.8  902.84  5239.1  904.05
#Mann=3,-1,0
  4699.7    0.05       0  5011.9   0.033       0  5015.9    0.05       0
#XS Ineff=2,0
    0.00 4959.30  904.94               0
Permanent Ineff=
       F       F
Bank Sta=5011.9,5015.9
Exp/Cntr=0.3,0.1

Type RM Length L Ch R = 1,55663,354,354,354
BEGIN DESCRIPTION:
Morris Branch 100.0
END DESCRIPTION:
XS GIS Cut Line= 3
      2286479.00      7124910.00      2286279.00      7124610.00
      2285979.01      7124410.00
#Sta/Elev= 30
  4640.2  910.03  4647.7  909.50  4653.7  910.43  4662.7  910.01  4668.7  908.91
  4740.9  905.77  4791.9  902.83  4820.5  902.12  4828.0  901.49  4885.1  899.66
  4900.1  898.07  4921.1  898.17  4928.6  896.29  4936.2  895.65  4964.7  895.44
  4970.2  894.78  4970.5  894.28  4974.0  894.28  4974.2  894.78  4978.2  895.63
  4987.2  895.35  4993.2  896.24  5003.8  896.22  5008.3  895.59  5029.3  897.56
  5044.3  898.00  5065.4  897.39  5072.9  898.19  5108.9  899.68  5361.3  906.80
#Mann=3,-1,0
  4640.2    0.05       0  4970.2   0.033       0  4974.2    0.05       0
Bank Sta=4970.2,4974.2
Exp/Cntr=0.3,0.1

Type RM Length L Ch R = 1,55309,369,369,369
BEGIN DESCRIPTION:
Morris Branch 99.0
END DESCRIPTION:
XS GIS Cut Line= 3
      2286579.00      7124659.99      2286479.00      7124360.00
      2286428.99      7124159.98
#Sta/Elev= 30
  4688.7  901.70  4794.1  898.94  4899.5  897.37  4920.6  896.80  4941.7  896.66
  4962.8  897.03  4973.3  894.79  4983.8  893.85  4992.4  890.72  4992.6  890.22
  4996.1  890.22  4996.4  890.72  5002.3  891.44  5007.5  891.44  5015.2  895.05
  5064.2  893.95  5069.3  893.48  5077.1  893.28  5097.7  893.00  5105.4  893.04
  5110.6  894.26  5118.3  894.41  5128.6  894.50  5146.7  893.69  5151.8  894.33
  5159.5  896.99  5169.8  899.64  5180.2  900.76  5187.9  901.25  5211.1  902.02
#Mann=3,-1,0
  4688.7    0.05       0  4992.4   0.033       0  4996.4    0.05       0
Bank Sta=4992.4,4996.4
Exp/Cntr=0.3,0.1

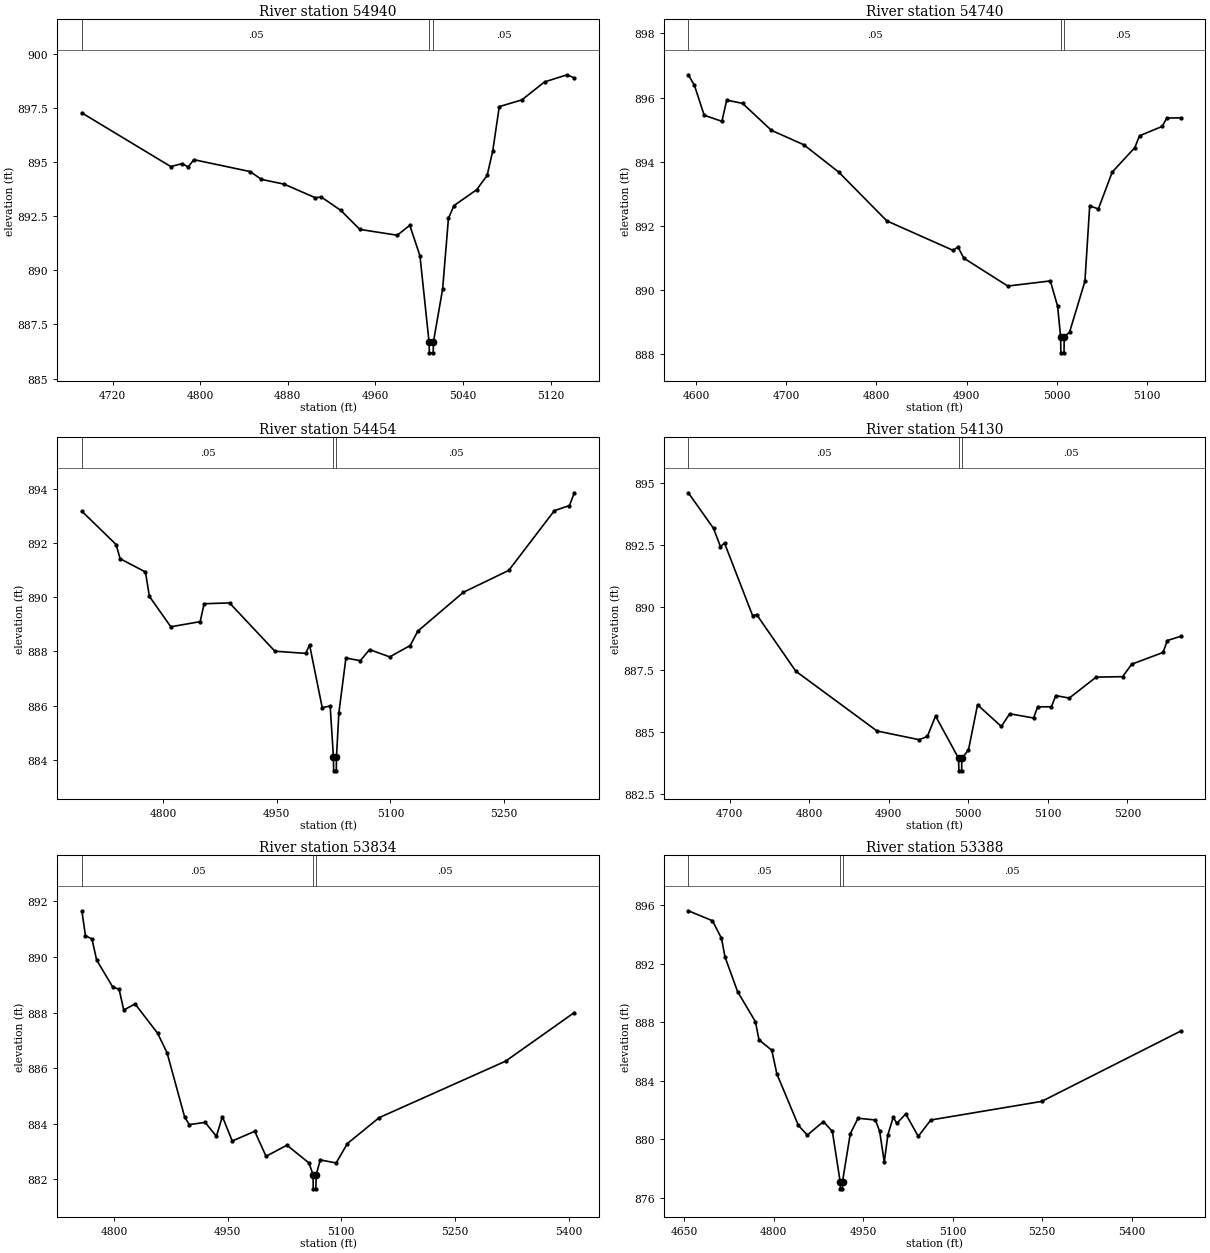
Type RM Length L Ch R = 1,54940,200,200,200
BEGIN DESCRIPTION:
Mapping XS 86284ec3
END DESCRIPTION:
XS GIS Cut Line= 2
      2286768.60      7124458.58      2286654.98      7124023.68
#Sta/Elev= 30
  4692.0  897.27  4773.2  894.79  4783.6  894.93  4789.0  894.77  4794.2  895.11
  4845.6  894.56  4855.9  894.20  4876.6  893.98  4905.2  893.35  4910.4  893.39
  4928.3  892.77  4945.7  891.89  4979.9  891.62  4991.3  892.08  5000.6  890.67
  5008.9  886.69  5009.2  886.19  5012.7  886.19  5012.9  886.69  5021.3  889.14
  5026.6  892.40  5031.7  892.99  5052.3  893.72  5061.9  894.38  5067.0  895.50
  5073.0  897.56  5093.6  897.87  5114.3  898.70  5135.0  899.03  5141.5  898.88
#Mann=3,-1,0
  4692.0    0.05       0  5008.9   0.033       0  5012.9    0.05       0
Bank Sta=5008.9,5012.9
Exp/Cntr=0.3,0.1

Type RM Length L Ch R = 1,54740,286,286,286
BEGIN DESCRIPTION:
Mapping XS 270ef40c
END DESCRIPTION:
XS GIS Cut Line= 2
      2286958.34      7124406.38      2286767.15      7123894.31
#Sta/Elev= 30
  4591.2  896.71  4598.0  896.38  4608.8  895.45  4628.5  895.26  4633.8  895.92
  4651.4  895.82  4683.4  894.98  4719.4  894.53  4758.1  893.68  4811.5  892.16
  4885.2  891.24  4890.5  891.35  4896.9  891.00  4945.8  890.13  4993.0  890.29
  5001.1  889.50  5004.4  888.55  5004.7  888.05  5008.2  888.05  5008.4  888.55
  5014.3  888.69  5031.4  890.28  5036.7  892.63  5046.3  892.53  5061.7  893.68
  5086.7  894.44  5092.0  894.81  5117.0  895.10  5122.3  895.36  5137.8  895.37
#Mann=3,-1,0
  4591.2    0.05       0  5004.4   0.033       0  5008.4    0.05       0
Bank Sta=5004.4,5008.4
Exp/Cntr=0.3,0.1

Type RM Length L Ch R = 1,54454,324,324,324
BEGIN DESCRIPTION:
Mapping XS 2be9a3f9
END DESCRIPTION:
XS GIS Cut Line= 3
      2287147.74      7124204.79      2287033.37      7123811.90
      2286792.60      7123824.58
#Sta/Elev= 30
  4692.6  893.17  4737.9  891.94  4743.1  891.42  4776.6  890.93  4781.8  890.03
  4810.1  888.91  4848.8  889.10  4854.1  889.76  4887.6  889.79  4947.5  888.01
  4988.1  887.93  4993.3  888.24  5010.0  885.93  5020.5  885.99  5024.8  884.10
  5025.1  883.60  5028.6  883.60  5028.8  884.10  5032.0  885.74  5041.3  887.76
  5060.3  887.66  5072.5  888.07  5099.1  887.80  5126.2  888.22  5136.2  888.75
  5196.3  890.18  5256.4  890.99  5316.5  893.19  5336.5  893.38  5342.9  893.85
#Mann=3,-1,0
  4692.6    0.05       0  5024.8   0.033       0  5028.8    0.05       0
Bank Sta=5024.8,5028.8
Exp/Cntr=0.3,0.1

Type RM Length L Ch R = 1,54130,296,296,296
BEGIN DESCRIPTION:
Mapping XS 85c1d1dc
END DESCRIPTION:
XS GIS Cut Line= 3
      2287395.11      7124050.69      2287283.69      7123625.28
      2287204.26      7123464.49
#Sta/Elev= 30
  4648.0  894.60  4679.7  893.17  4688.4  892.44  4693.5  892.58  4728.8  889.67
  4733.9  889.71  4783.1  887.44  4885.2  885.04  4938.2  884.69  4948.5  884.82
  4958.8  885.64  4987.8  883.94  4988.1  883.44  4991.6  883.44  4991.8  883.94
  5000.2  884.28  5011.6  886.09  5041.5  885.22  5052.0  885.73  5082.1  885.56
  5087.1  886.01  5104.4  886.01  5110.0  886.46  5126.9  886.36  5160.6  887.20
  5194.0  887.22  5205.4  887.72  5244.7  888.19  5250.2  888.67  5267.1  888.84
#Mann=3,-1,0
  4648.0    0.05       0  4987.8   0.033       0  4991.8    0.05       0
Bank Sta=4987.8,4991.8
Exp/Cntr=0.3,0.1

Type RM Length L Ch R = 1,53834,446,446,446
BEGIN DESCRIPTION:
Mapping XS dcabce46
END DESCRIPTION:
XS GIS Cut Line= 2
      2287694.20      7123782.39      2287323.64      7123248.36
#Sta/Elev= 30
  4757.5  891.66  4762.2  890.77  4770.9  890.64  4777.0  889.89  4798.0  888.93
  4806.7  888.83  4812.8  888.09  4827.7  888.31  4857.4  887.26  4870.0  886.55
  4893.2  884.24  4899.3  883.97  4920.2  884.05  4935.1  883.55  4943.0  884.26
  4956.0  883.38  4985.7  883.73  5000.6  882.83  5028.2  883.23  5057.3  882.59
  5062.7  882.16  5062.9  881.66  5066.4  881.66  5066.7  882.16  5072.2  882.70
  5093.1  882.59  5108.0  883.29  5149.9  884.22  5316.7  886.25  5407.5  888.00
#Mann=3,-1,0
  4757.5    0.05       0  5062.7   0.033       0  5066.7    0.05       0
Bank Sta=5062.7,5066.7
Exp/Cntr=0.3,0.1

Type RM Length L Ch R = 1,53388,413,413,413
BEGIN DESCRIPTION:
Mapping XS 104d0155
END DESCRIPTION:
XS GIS Cut Line= 3
      2287998.24      7123516.15      2287669.16      7123026.50
      2287433.53      7123026.09
#Sta/Elev= 30
  4657.0  895.61  4697.5  894.93  4712.5  893.74  4718.5  892.46  4739.5  890.10
  4769.5  888.04  4775.5  886.80  4796.9  886.09  4805.5  884.47  4841.5  880.96
  4856.5  880.30  4883.5  881.22  4898.5  880.55  4911.5  877.13  4911.8  876.63
  4915.3  876.63  4915.5  877.13  4928.5  880.39  4941.5  881.45  4970.5  881.33
  4977.7  880.57  4985.5  878.46  4991.5  880.31  5000.5  881.52  5006.5  881.10
  5021.5  881.74  5042.5  880.21  5063.5  881.33  5249.5  882.60  5482.6  887.40
#Mann=3,-1,0
  4657.0    0.05       0  4911.5   0.033       0  4915.5    0.05       0
Bank Sta=4911.5,4915.5
Exp/Cntr=0.3,0.1

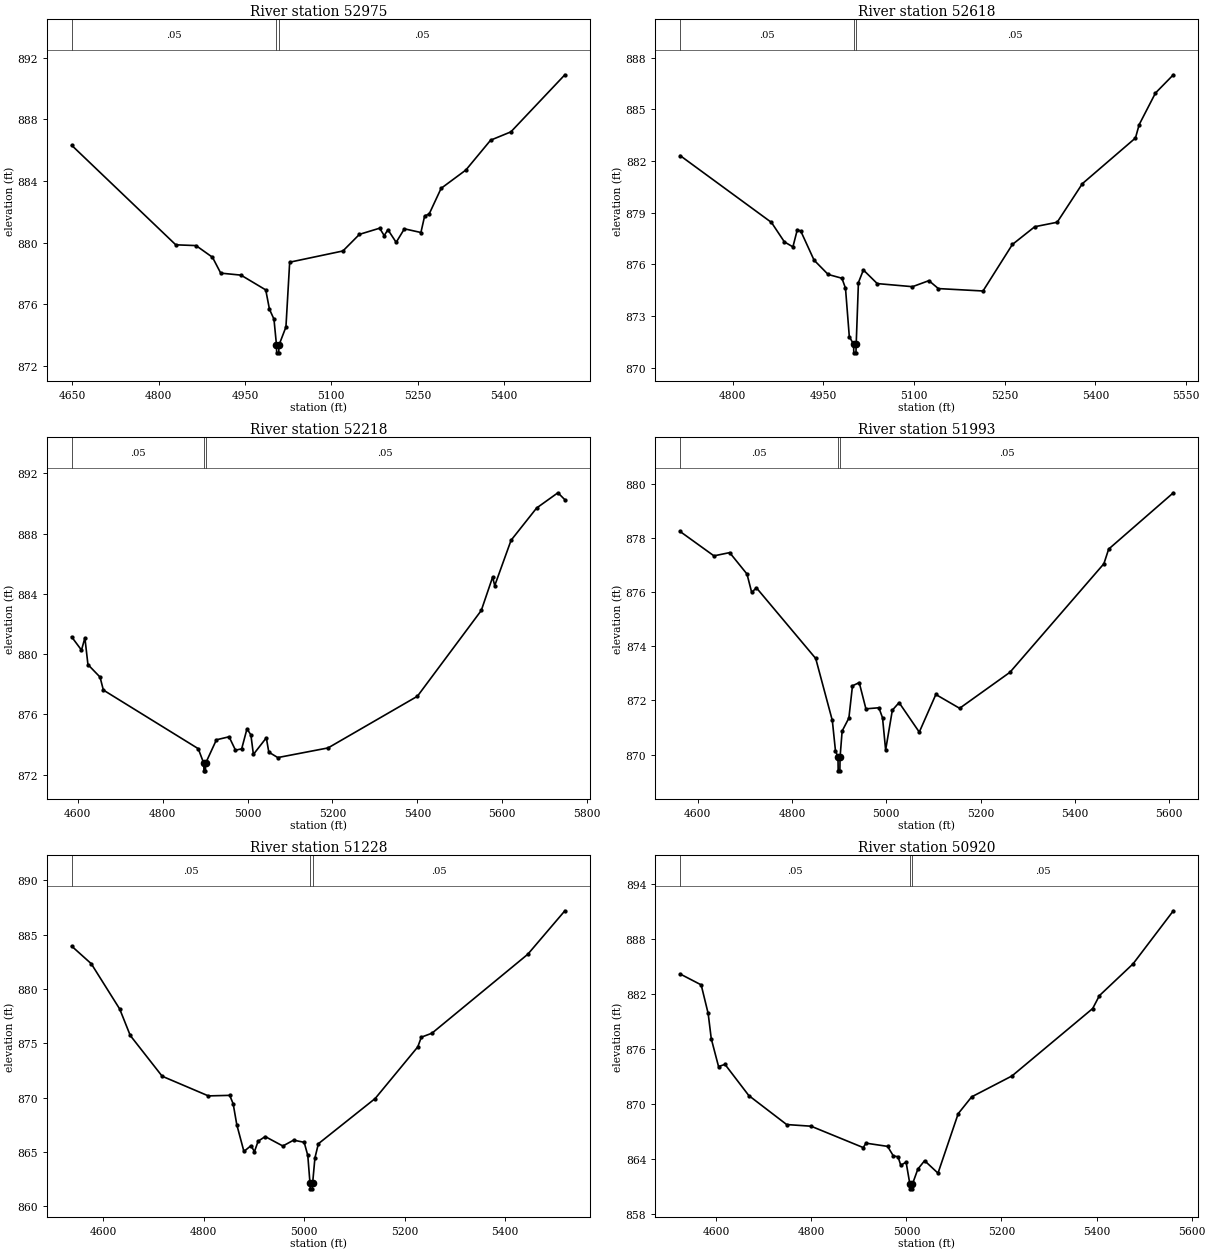
Type RM Length L Ch R = 1,52975,357,357,357
BEGIN DESCRIPTION:
Mapping XS 85784e65
END DESCRIPTION:
XS GIS Cut Line= 2
      2288221.58      7123211.67      2287675.01      7122551.72
#Sta/Elev= 30
  4648.9  886.32  4829.8  879.85  4865.0  879.80  4893.6  879.04  4907.9  878.01
  4943.1  877.88  4986.1  876.92  4992.6  875.66  5000.4  875.02  5004.8  873.33
  5005.1  872.83  5008.7  872.83  5009.1  873.33  5021.2  874.51  5027.7  878.72
  5120.2  879.45  5148.9  880.53  5184.0  880.93  5191.9  880.45  5198.4  880.83
  5212.7  880.01  5227.0  880.89  5255.7  880.65  5262.2  881.73  5270.0  881.85
  5290.8  883.52  5333.8  884.71  5376.8  886.65  5412.0  887.19  5505.8  890.90
#Mann=3,-1,0
  4648.9    0.05       0  5004.8   0.033       0  5009.1    0.05       0
Bank Sta=5004.8,5009.1
Exp/Cntr=0.3,0.1

Type RM Length L Ch R = 1,52618,400,400,400
BEGIN DESCRIPTION:
Mapping XS 287a74bc
END DESCRIPTION:
XS GIS Cut Line= 4
      2288384.31      7122950.11      2288069.31      7122424.06
      2288066.39      7122424.03      2287874.85      7122366.73
#Sta/Elev= 30
  4713.1  882.32  4864.2  878.44  4885.6  877.31  4899.7  877.02  4907.0  878.02
  4912.8  877.93  4934.7  876.25  4958.0  875.42  4980.8  875.20  4986.7  874.62
  4993.0  871.81  5000.1  871.37  5000.4  870.87  5004.0  870.87  5004.4  871.37
  5008.1  874.95  5016.3  875.68  5039.2  874.89  5097.5  874.71  5124.7  875.06
  5140.3  874.60  5214.2  874.46  5262.8  877.16  5299.8  878.19  5336.9  878.45
  5378.6  880.69  5466.4  883.34  5472.6  884.12  5499.5  885.95  5529.1  887.01
#Mann=3,-1,0
  4713.1    0.05       0  5000.1   0.033       0  5004.4    0.05       0
Bank Sta=5000.1,5004.4
Exp/Cntr=0.3,0.1

Type RM Length L Ch R = 1,52218,225,225,225
BEGIN DESCRIPTION:
Mapping XS b8865ab3
END DESCRIPTION:
XS GIS Cut Line= 3
      2288665.55      7122746.19      2288347.27      7122254.71
      2287772.64      7122212.72
#Sta/Elev= 30
  4585.7  881.15  4608.9  880.27  4616.9  881.08  4624.1  879.31  4652.6  878.48
  4660.4  877.62  4883.9  873.73  4896.9  872.76  4897.3  872.26  4900.9  872.26
  4901.2  872.76  4926.7  874.32  4956.5  874.52  4971.6  873.63  4986.2  873.72
  4998.7  875.05  5007.9  874.64  5013.8  873.35  5044.2  874.45  5050.1  873.50
  5071.2  873.14  5189.6  873.78  5400.1  877.21  5550.5  882.90  5577.2  885.11
  5582.2  884.55  5620.7  887.56  5680.9  889.70  5731.0  890.71  5747.4  890.25
#Mann=3,-1,0
  4585.7    0.05       0  4896.9   0.033       0  4901.2    0.05       0
Bank Sta=4896.9,4901.2
Exp/Cntr=0.3,0.1

Type RM Length L Ch R = 1,51993,765,765,765
BEGIN DESCRIPTION:
Mapping XS 24bc437b
END DESCRIPTION:
XS GIS Cut Line= 4
      2288692.97      7122621.72      2288695.56      7122362.07
      2288410.63      7122031.97      2288062.49      7122064.71
#Sta/Elev= 30
  4563.1  878.24  4634.8  877.34  4668.1  877.46  4704.8  876.67  4714.8  875.99
  4724.8  876.16  4850.5  873.55  4885.7  871.26  4892.3  870.15  4897.7  869.90
  4898.1  869.40  4901.7  869.40  4902.1  869.90  4906.5  870.87  4920.8  871.35
  4928.4  872.54  4942.7  872.66  4956.9  871.69  4984.4  871.73  4992.1  871.36
  4998.7  870.17  5012.9  871.64  5027.2  871.92  5070.0  870.83  5105.1  872.22
  5155.5  871.71  5262.2  873.04  5461.3  877.05  5471.4  877.59  5608.5  879.67
#Mann=3,-1,0
  4563.1    0.05       0  4897.7   0.033       0  4902.1    0.05       0
Bank Sta=4897.7,4902.1
Exp/Cntr=0.3,0.1

Type RM Length L Ch R = 1,51228,308,308,308
BEGIN DESCRIPTION:
Mapping XS 7fbf783b
END DESCRIPTION:
XS GIS Cut Line= 2
      2289163.98      7122130.24      2288484.01      7121420.50
#Sta/Elev= 30
  4536.6  883.94  4575.7  882.32  4632.4  878.15  4653.4  875.72  4717.0  871.97
  4809.1  870.16  4851.6  870.21  4858.5  869.43  4865.7  867.51  4879.9  865.05
  4894.0  865.58  4900.9  865.03  4908.2  865.99  4922.3  866.42  4957.5  865.55
  4978.9  866.09  5000.0  865.89  5007.2  864.68  5011.6  862.11  5012.3  861.61
  5016.1  861.61  5016.8  862.11  5021.4  864.45  5028.3  865.76  5141.5  869.92
  5226.4  874.67  5233.4  875.56  5254.7  875.93  5445.6  883.19  5519.5  887.19
#Mann=3,-1,0
  4536.6    0.05       0  5011.6   0.033       0  5016.8    0.05       0
Bank Sta=5011.6,5016.8
Exp/Cntr=0.3,0.1

Type RM Length L Ch R = 1,50920,403,403,403
BEGIN DESCRIPTION:
Morris Branch 88.0
END DESCRIPTION:
XS GIS Cut Line= 3
      2289279.02      7121960.03      2289029.00      7121560.00
      2288629.01      7121160.01
#Sta/Elev= 30
  4524.1  884.17  4568.4  882.98  4583.1  879.86  4589.6  877.11  4604.9  874.08
  4618.5  874.31  4668.6  870.91  4748.2  867.75  4799.5  867.57  4909.2  865.24
  4915.1  865.72  4960.5  865.37  4972.8  864.31  4982.3  864.25  4988.2  863.31
  4999.4  863.65  5007.4  861.24  5008.1  860.74  5011.9  860.74  5012.6  861.24
  5024.1  862.89  5038.3  863.81  5066.5  862.45  5109.0  868.94  5137.3  870.77
  5222.1  873.05  5391.8  880.40  5406.0  881.81  5476.7  885.27  5561.5  891.06
#Mann=3,-1,0
  4524.1    0.05       0  5007.4   0.033       0  5012.6    0.05       0
Bank Sta=5007.4,5012.6
Exp/Cntr=0.3,0.1

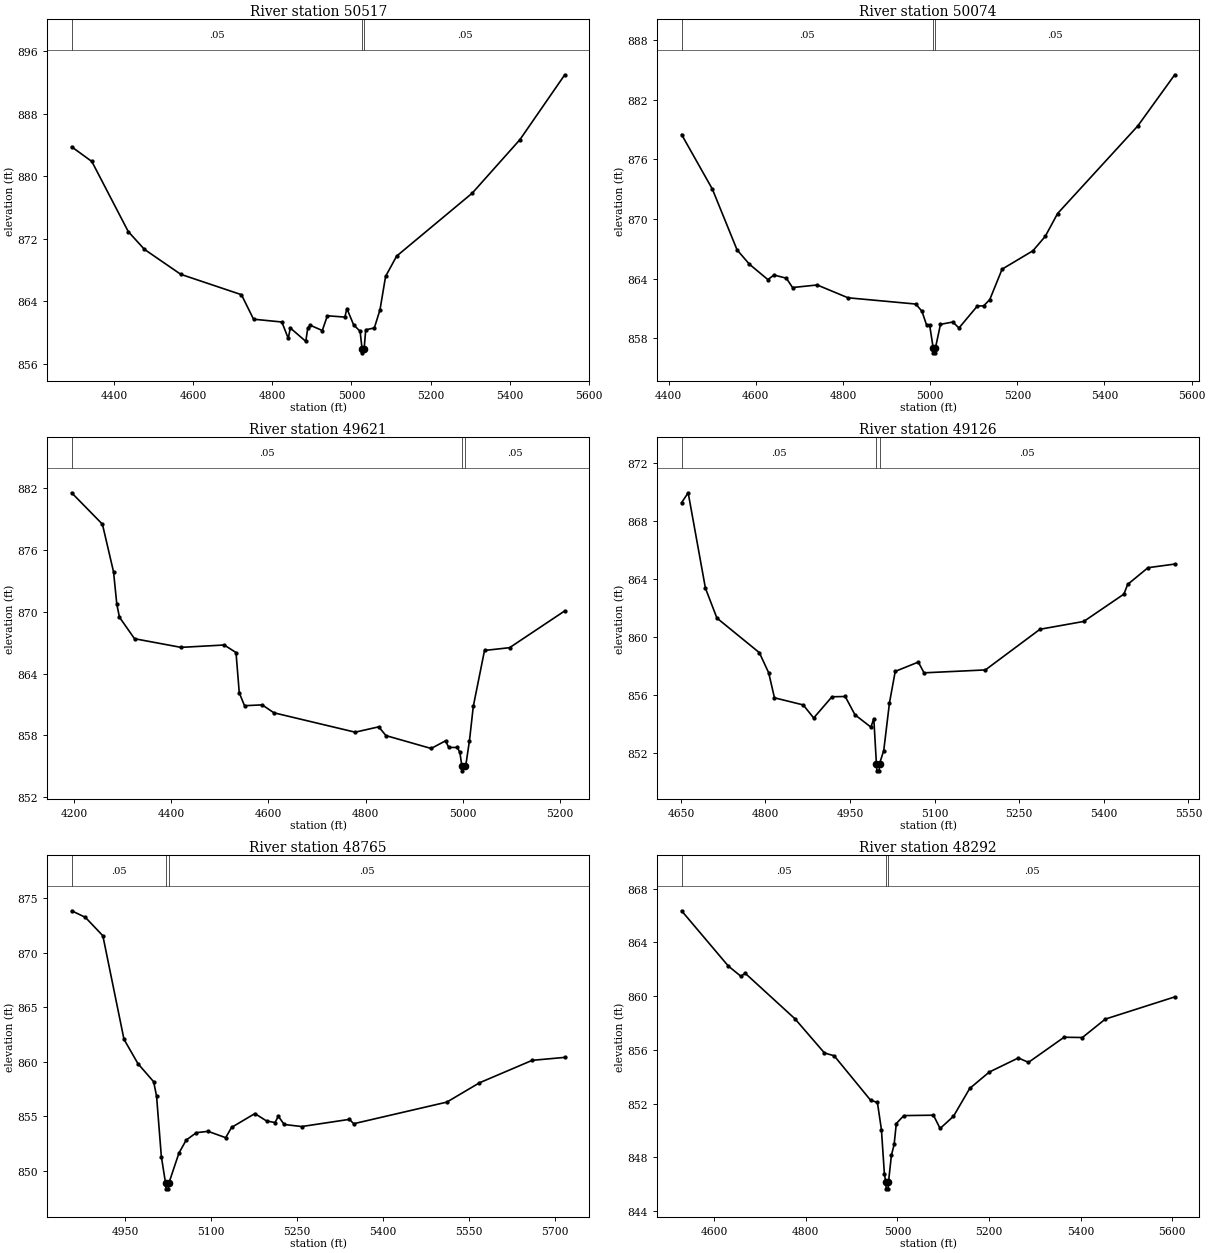
Type RM Length L Ch R = 1,50517,443,443,443
BEGIN DESCRIPTION:
Morris Branch 87.0
END DESCRIPTION:
XS GIS Cut Line= 3
      2289329.00      7121960.01      2289179.00      7121260.00
      2288779.01      7120910.01
#Sta/Elev= 30
  4292.1  883.78  4343.2  881.90  4435.3  872.92  4476.2  870.64  4568.2  867.44
  4721.6  864.83  4752.3  861.69  4823.9  861.33  4840.1  859.22  4845.2  860.57
  4884.4  858.85  4889.5  860.57  4895.5  860.92  4926.2  860.24  4939.0  862.13
  4983.3  861.96  4988.4  863.05  5005.4  860.97  5021.8  860.14  5026.8  857.88
  5027.5  857.38  5032.0  857.88  5036.0  860.33  5057.8  860.57  5072.1  862.89
  5086.3  867.18  5114.3  869.78  5305.6  877.85  5426.1  884.70  5539.5  893.01
#Mann=3,-1,0
  4292.1    0.05       0  5026.8   0.033       0  5032.0    0.05       0
Bank Sta=5026.8,5032
Exp/Cntr=0.3,0.1

Type RM Length L Ch R = 1,50074,453,453,453
BEGIN DESCRIPTION:
Morris Branch 86.0
END DESCRIPTION:
XS GIS Cut Line= 3
      2289879.00      7121510.00      2289479.00      7121110.00
      2289078.98      7120709.98
#Sta/Elev= 30
  4429.7  878.51  4500.4  873.01  4557.0  866.90  4585.3  865.46  4627.7  863.91
  4641.8  864.37  4670.1  864.05  4684.3  863.11  4740.8  863.37  4811.5  862.08
  4967.1  861.45  4981.2  860.72  4991.9  859.33  4998.9  859.33  5006.9  857.04
  5007.6  856.54  5011.4  856.54  5012.2  857.04  5023.7  859.41  5052.0  859.64
  5066.1  859.04  5108.5  861.26  5122.7  861.26  5136.8  861.90  5165.1  864.96
  5235.8  866.81  5264.1  868.26  5292.4  870.56  5476.2  879.36  5561.1  884.52
#Mann=3,-1,0
  4429.7    0.05       0  5006.9   0.033       0  5012.2    0.05       0
Bank Sta=5006.9,5012.2
Exp/Cntr=0.3,0.1

Type RM Length L Ch R = 1,49621,495,495,495
BEGIN DESCRIPTION:
Morris Branch 85.0
END DESCRIPTION:
XS GIS Cut Line= 3
      2289979.01      7121510.04      2289679.00      7120760.00
      2289478.97      7120709.99
#Sta/Elev= 30
  4195.5  881.55  4258.8  878.50  4281.7  873.87  4288.4  870.74  4293.8  869.48
  4324.8  867.39  4420.4  866.55  4509.2  866.78  4533.5  866.05  4540.2  862.14
  4551.0  860.89  4587.3  860.97  4611.5  860.20  4778.5  858.32  4827.0  858.84
  4841.8  857.99  4934.7  856.74  4964.3  857.48  4971.0  856.84  4988.5  856.84
  4993.9  856.35  4997.8  855.07  4998.7  854.57  5003.4  855.07  5005.9  855.07
  5013.6  857.51  5021.4  860.82  5044.5  866.25  5096.1  866.52  5209.5  870.09
#Mann=3,-1,0
  4195.5    0.05       0  4997.8   0.033       0  5003.4    0.05       0
Bank Sta=4997.8,5003.4
Exp/Cntr=0.3,0.1

Type RM Length L Ch R = 1,49126,361,361,361
BEGIN DESCRIPTION:
Mapping XS e75557ba
END DESCRIPTION:
XS GIS Cut Line= 3
      2290131.09      7121201.43      2290009.02      7120597.63
      2289815.71      7120426.04
#Sta/Elev= 30
  4651.2  869.26  4662.9  869.94  4693.5  863.37  4713.9  861.31  4789.1  858.93
  4805.7  857.54  4815.9  855.82  4866.9  855.33  4885.5  854.43  4917.9  855.89
  4941.4  855.91  4958.7  854.65  4987.0  853.80  4992.1  854.39  4996.7  851.29
  4997.6  850.79  5001.5  850.79  5002.3  851.29  5009.7  852.18  5019.9  855.48
  5030.1  857.64  5071.0  858.28  5081.2  857.54  5190.0  857.74  5286.8  860.54
  5364.5  861.08  5435.6  862.96  5442.3  863.63  5478.3  864.78  5525.7  865.03
#Mann=3,-1,0
  4651.2    0.05       0  4996.7   0.033       0  5002.3    0.05       0
Bank Sta=4996.7,5002.3
Exp/Cntr=0.3,0.1

Type RM Length L Ch R = 1,48765,473,473,473
BEGIN DESCRIPTION:
Mapping XS 53d91fe5
END DESCRIPTION:
XS GIS Cut Line= 3
      2290411.66      7121093.43      2290325.82      7120652.74
      2290053.17      7120346.23
#Sta/Elev= 30
  4857.2  873.84  4881.1  873.24  4911.6  871.55  4948.4  862.06  4972.8  859.82
  5000.1  858.17  5005.2  856.84  5013.5  851.31  5020.9  848.85  5021.8  848.35
  5025.7  848.35  5026.5  848.85  5044.1  851.62  5056.8  852.82  5074.6  853.50
  5095.0  853.62  5125.6  853.04  5135.8  853.98  5176.5  855.25  5196.9  854.57
  5211.6  854.43  5217.3  855.01  5227.5  854.25  5258.0  854.06  5341.2  854.72
  5348.7  854.32  5510.9  856.30  5567.8  858.07  5659.7  860.13  5716.4  860.40
#Mann=3,-1,0
  4857.2    0.05       0  5020.9   0.033       0  5026.5    0.05       0
Bank Sta=5020.9,5026.5
Exp/Cntr=0.3,0.1

Type RM Length L Ch R = 1,48292,469,469,469
BEGIN DESCRIPTION:
Morris Branch 82.0
END DESCRIPTION:
XS GIS Cut Line= 4
      2290979.00      7120810.00      2290579.00      7120560.00
      2290409.17      7120333.56      2290087.63      7120345.05
#Sta/Elev= 30
  4528.9  866.35  4630.9  862.24  4658.6  861.47  4667.5  861.71  4776.5  858.31
  4840.8  855.77  4862.0  855.56  4941.6  852.25  4956.4  852.09  4965.2  850.06
  4971.7  846.75  4974.7  846.16  4975.6  845.66  4979.6  845.66  4980.6  846.16
  4987.0  848.16  4992.9  848.96  4997.7  850.52  5014.1  851.11  5078.7  851.14
  5093.3  850.15  5122.5  851.06  5157.9  853.13  5200.6  854.35  5264.1  855.40
  5286.2  855.07  5363.9  856.94  5403.9  856.92  5453.9  858.29  5605.4  859.94
#Mann=3,-1,0
  4528.9    0.05       0  4974.7   0.033       0  4980.6    0.05       0
Bank Sta=4974.7,4980.6
Exp/Cntr=0.3,0.1