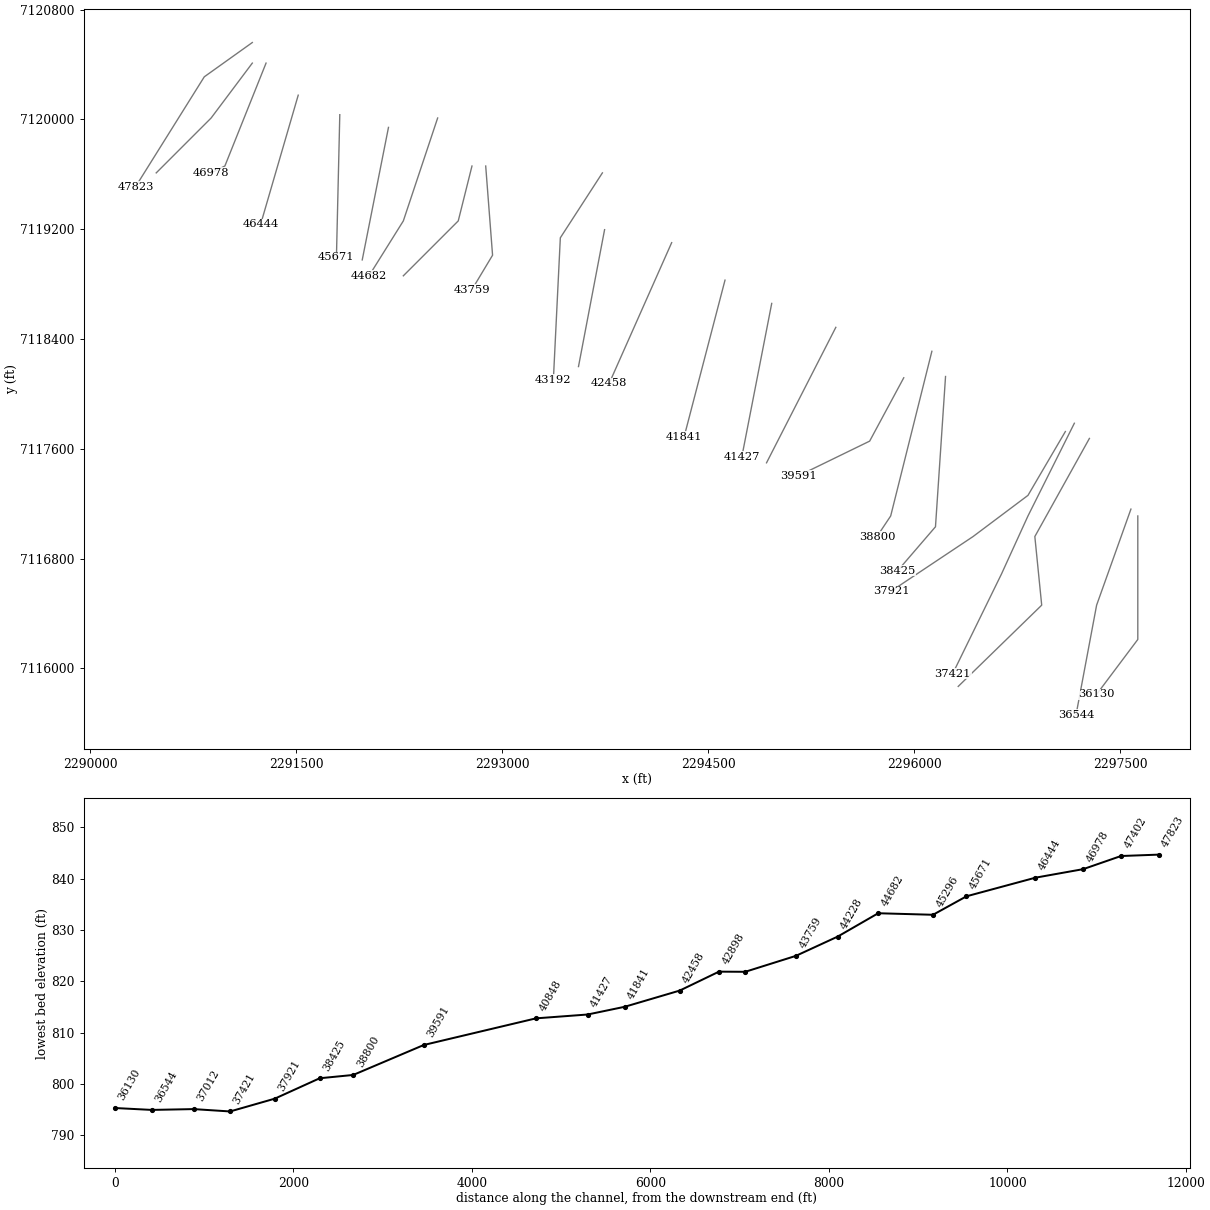
HEC-RAS study Morris Branch.prj: Morris Branch Base Level Engineering

--- Morris Branch.g01 (geometry) --- (continued)

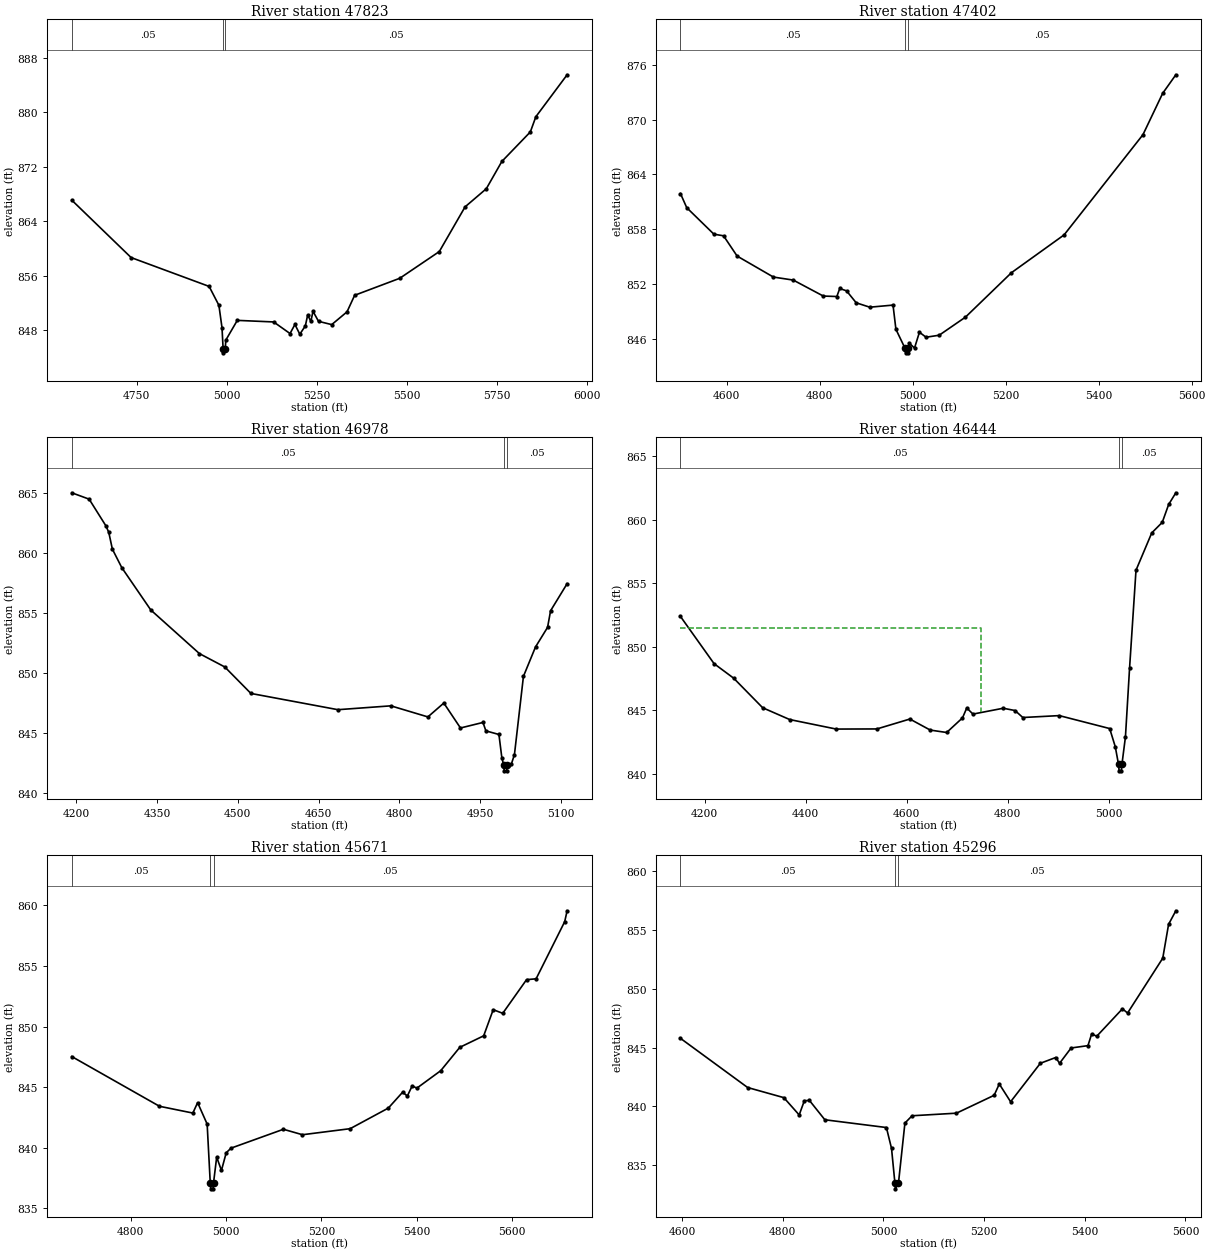
Type RM Length L Ch R = 1,47823,421,421,421
BEGIN DESCRIPTION:
Morris Branch 81.0
END DESCRIPTION:
XS GIS Cut Line= 3
      2291178.97      7120559.98      2290829.00      7120310.00
      2290328.99      7119509.98
#Sta/Elev= 30
  4570.2  867.10  4734.8  858.68  4951.1  854.45  4978.2  851.68  4986.8  848.40
  4990.0  845.21  4990.9  844.71  4995.9  845.21  4997.2  846.56  5029.2  849.47
  5130.0  849.24  5175.4  847.54  5189.0  848.87  5202.5  847.44  5217.9  848.66
  5224.3  850.26  5233.2  849.32  5239.1  850.80  5254.4  849.33  5291.0  848.85
  5333.4  850.72  5354.6  853.15  5479.6  855.64  5589.3  859.56  5660.7  866.11
  5719.6  868.77  5762.7  872.77  5841.7  877.10  5857.0  879.33  5943.7  885.48
#Mann=3,-1,0
  4570.2    0.05       0  4990.0    0.04       0  4995.9    0.05       0
Bank Sta=4990,4995.9
Exp/Cntr=0.3,0.1

Type RM Length L Ch R = 1,47402,424,424,424
BEGIN DESCRIPTION:
Morris Branch 80.0
END DESCRIPTION:
XS GIS Cut Line= 3
      2291178.99      7120409.99      2290879.00      7120010.00
      2290478.98      7119609.98
#Sta/Elev= 30
  4500.3  861.89  4513.8  860.34  4572.2  857.44  4593.0  857.26  4622.2  855.04
  4700.3  852.74  4743.0  852.41  4807.6  850.66  4836.7  850.61  4843.0  851.49
  4857.6  851.23  4878.4  849.92  4907.6  849.44  4957.6  849.67  4963.8  847.02
  4983.4  844.94  4984.5  844.44  4989.0  844.44  4990.0  844.94  4993.0  845.49
  5003.8  844.96  5014.4  846.70  5028.6  846.15  5056.9  846.37  5113.4  848.35
  5212.4  853.22  5325.6  857.36  5495.3  868.34  5537.7  872.87  5566.0  874.90
#Mann=3,-1,0
  4500.3    0.05       0  4983.4    0.04       0  4990.0    0.05       0
Bank Sta=4983.4,4990
Exp/Cntr=0.3,0.1

Type RM Length L Ch R = 1,46978,534,534,534
BEGIN DESCRIPTION:
Morris Branch 79.0
END DESCRIPTION:
XS GIS Cut Line= 3
      2291279.01      7120410.03      2290979.00      7119660.00
      2290879.00      7119610.00
#Sta/Elev= 30
  4191.9  864.98  4224.2  864.45  4255.2  862.24  4260.6  861.70  4267.3  860.30
  4284.8  858.76  4338.7  855.24  4428.9  851.62  4476.0  850.51  4524.5  848.31
  4686.0  846.96  4784.3  847.28  4853.0  846.36  4882.6  847.51  4913.5  845.44
  4955.3  845.90  4960.7  845.20  4984.9  844.90  4990.3  842.97  4993.7  842.38
  4994.8  841.88  4999.3  841.88  5000.3  842.38  5008.1  842.46  5013.7  843.23
  5030.4  849.73  5052.8  852.17  5075.2  853.80  5080.8  855.18  5111.5  857.43
#Mann=3,-1,0
  4191.9    0.05       0  4993.7   0.033       0  5000.3    0.05       0
Bank Sta=4993.7,5000.3
Exp/Cntr=0.3,0.1

Type RM Length L Ch R = 1,46444,773,773,773
BEGIN DESCRIPTION:
Mapping XS cb2ee72a
END DESCRIPTION:
XS GIS Cut Line= 2
      2291513.37      7120176.34      2291239.21      7119234.21
#Sta/Elev= 30
  4151.8  852.38  4218.4  848.66  4257.1  847.52  4314.6  845.19  4368.1  844.26
  4460.4  843.51  4540.9  843.52  4606.2  844.30  4646.6  843.43  4679.1  843.24
  4710.4  844.39  4718.9  845.17  4731.2  844.69  4791.1  845.15  4814.5  844.97
  4829.9  844.42  4902.1  844.57  5002.0  843.55  5013.1  842.11  5019.5  840.72
  5020.6  840.22  5025.1  840.22  5026.2  840.72  5033.2  842.90  5041.4  848.34
  5054.1  856.02  5085.3  858.96  5106.1  859.79  5118.8  861.20  5133.0  862.12
#Mann=3,-1,0
  4151.8    0.05       0  5019.5    0.04       0  5026.2    0.05       0
#XS Ineff=2,0
    0.00 4748.00  851.50               0
Permanent Ineff=
       F       F
Bank Sta=5019.5,5026.2
Exp/Cntr=0.3,0.1

Type RM Length L Ch R = 1,45671,375,375,375
BEGIN DESCRIPTION:
Mapping XS 04ceeaa8
END DESCRIPTION:
XS GIS Cut Line= 2
      2291816.15      7120034.01      2291791.67      7118994.90
#Sta/Elev= 30
  4676.1  847.52  4860.2  843.41  4930.2  842.85  4940.2  843.71  4960.2  841.94
  4966.7  837.09  4967.8  836.59  4972.5  836.59  4973.6  837.09  4980.2  839.21
  4990.2  838.11  5000.2  839.57  5010.2  839.95  5120.2  841.51  5160.2  841.06
  5260.3  841.56  5340.3  843.26  5370.3  844.57  5380.3  844.26  5390.3  845.09
  5400.3  844.91  5450.3  846.35  5490.3  848.28  5540.4  849.23  5560.4  851.39
  5580.4  851.09  5630.4  853.87  5650.4  853.94  5710.4  858.66  5715.5  859.56
#Mann=3,-1,0
  4676.1    0.05       0  4966.7   0.033       0  4973.6    0.05       0
Bank Sta=4966.7,4973.6
Exp/Cntr=0.3,0.1

Type RM Length L Ch R = 1,45296,614,614,614
BEGIN DESCRIPTION:
Mapping XS 8bea98e1
END DESCRIPTION:
XS GIS Cut Line= 2
      2292170.83      7119941.45      2291979.65      7118975.89
#Sta/Elev= 30
  4596.6  845.78  4730.1  841.60  4802.0  840.74  4832.5  839.27  4842.8  840.48
  4852.9  840.50  4883.5  838.86  5005.8  838.20  5016.0  836.42  5022.7  833.49
  5023.8  832.99  5029.8  833.49  5042.6  838.58  5056.8  839.20  5145.0  839.42
  5219.9  840.94  5230.1  841.90  5252.6  840.39  5311.7  843.66  5342.2  844.15
  5349.9  843.66  5372.8  844.96  5406.3  845.16  5413.6  846.15  5423.8  845.96
  5474.8  848.29  5485.0  847.93  5554.9  852.59  5566.5  855.47  5580.9  856.62
#Mann=3,-1,0
  4596.6    0.05       0  5022.7    0.04       0  5029.8    0.05       0
Bank Sta=5022.7,5029.8
Exp/Cntr=0.3,0.1

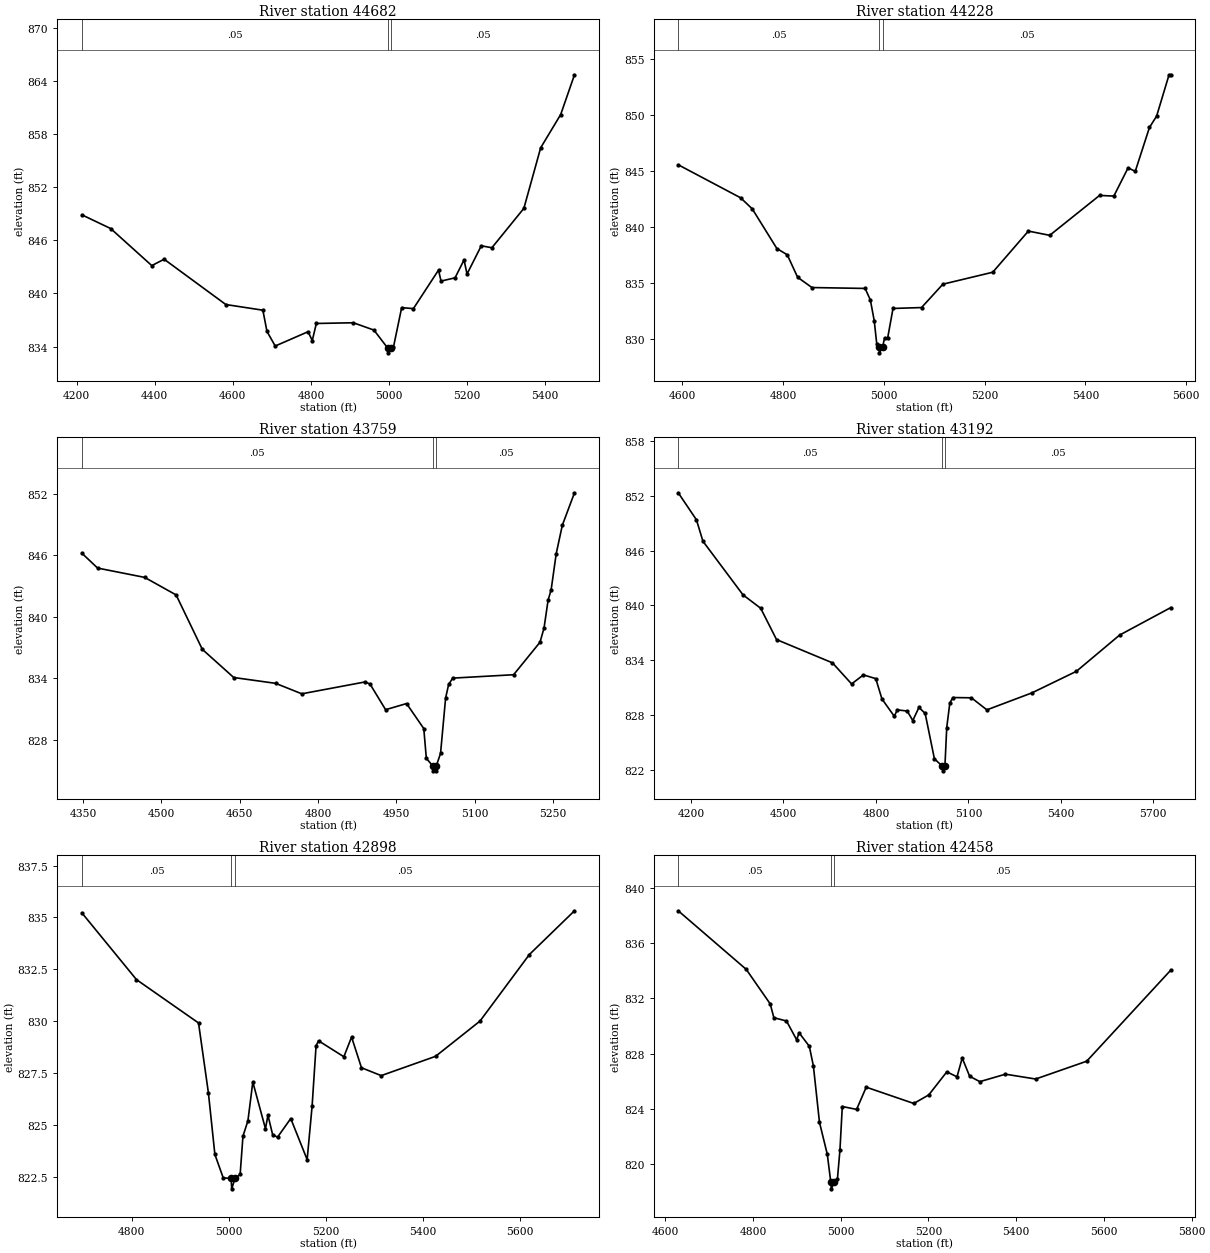
Type RM Length L Ch R = 1,44682,454,454,454
BEGIN DESCRIPTION:
Morris Branch 74.0
END DESCRIPTION:
XS GIS Cut Line= 3
      2292528.99      7120009.98      2292279.00      7119260.00
      2292029.02      7118860.04
#Sta/Elev= 30
  4213.1  848.89  4286.9  847.34  4392.3  843.15  4423.9  843.87  4582.0  838.75
  4676.9  838.11  4687.4  835.71  4708.5  834.06  4792.8  835.68  4803.4  834.67
  4813.9  836.61  4908.8  836.69  4961.5  835.86  4997.4  833.79  4998.6  833.29
  5004.6  833.79  5011.3  833.90  5032.5  838.40  5062.6  838.29  5126.9  842.64
  5133.4  841.40  5169.3  841.77  5192.3  843.79  5200.0  842.20  5236.5  845.39
  5263.7  845.17  5345.6  849.62  5388.7  856.47  5440.0  860.23  5475.3  864.72
#Mann=3,-1,0
  4213.1    0.05       0  4997.4   0.033       0  5004.6    0.05       0
Bank Sta=4997.4,5004.6
Exp/Cntr=0.3,0.1

Type RM Length L Ch R = 1,44228,469,469,469
BEGIN DESCRIPTION:
Morris Branch 73.0
END DESCRIPTION:
XS GIS Cut Line= 3
      2292778.99      7119659.97      2292679.00      7119260.00
      2292278.98      7118859.98
#Sta/Elev= 30
  4591.8  845.56  4715.5  842.61  4738.7  841.62  4787.6  838.07  4808.2  837.51
  4828.8  835.50  4857.2  834.58  4962.8  834.50  4973.2  833.47  4980.9  831.61
  4986.0  829.50  4990.2  829.24  4991.3  828.74  4997.4  829.24  5001.5  830.08
  5007.6  830.08  5018.2  832.71  5074.8  832.79  5117.2  834.88  5216.2  835.95
  5286.9  839.63  5329.3  839.25  5428.3  842.82  5456.6  842.76  5484.9  845.29
  5499.1  844.97  5527.3  848.90  5541.5  849.91  5566.2  853.61  5569.8  853.61
#Mann=3,-1,0
  4591.8    0.05       0  4990.2   0.033       0  4997.4    0.05       0
Bank Sta=4990.2,4997.4
Exp/Cntr=0.3,0.1

Type RM Length L Ch R = 1,43759,567,567,567
BEGIN DESCRIPTION:
Morris Branch 72.0
END DESCRIPTION:
XS GIS Cut Line= 3
      2292879.00      7119659.97      2292929.00      7119010.00
      2292779.02      7118760.03
#Sta/Elev= 30
  4348.0  846.20  4378.1  844.75  4468.3  843.84  4528.5  842.13  4578.6  836.83
  4638.8  834.08  4719.1  833.51  4769.2  832.49  4889.6  833.64  4899.6  833.46
  4929.7  830.94  4969.8  831.54  5002.8  829.10  5007.7  826.20  5019.6  825.48
  5020.7  824.98  5025.7  824.98  5026.9  825.48  5034.9  826.68  5044.6  832.08
  5050.4  833.40  5058.2  834.02  5174.8  834.35  5225.4  837.52  5233.1  838.91
  5240.9  841.63  5246.7  842.63  5256.4  846.15  5268.1  848.92  5291.4  852.09
#Mann=3,-1,0
  4348.0    0.05       0  5019.6    0.04       0  5026.9    0.05       0
Bank Sta=5019.6,5026.9
Exp/Cntr=0.3,0.1

Type RM Length L Ch R = 1,43192,294,294,294
BEGIN DESCRIPTION:
Morris Branch 71.0
END DESCRIPTION:
XS GIS Cut Line= 3
      2293729.01      7119610.01      2293422.62      7119136.98
      2293371.99      7118103.91
#Sta/Elev= 30
  4158.9  852.34  4217.9  849.38  4239.0  847.03  4368.9  841.16  4426.3  839.69
  4477.7  836.26  4659.1  833.71  4721.2  831.40  4759.5  832.39  4799.6  831.98
  4819.6  829.76  4859.6  827.86  4869.6  828.56  4901.6  828.43  4919.7  827.39
  4939.7  828.83  4959.8  828.17  4989.8  823.20  5015.8  822.38  5017.0  821.88
  5023.9  822.38  5029.8  826.62  5039.8  829.31  5049.9  829.91  5109.9  829.88
  5160.0  828.56  5306.1  830.42  5450.3  832.78  5590.5  836.75  5756.8  839.77
#Mann=3,-1,0
  4158.9    0.05       0  5015.8    0.04       0  5023.9    0.05       0
Bank Sta=5015.8,5023.9
Exp/Cntr=0.3,0.1

Type RM Length L Ch R = 1,42898,440,440,440
BEGIN DESCRIPTION:
Mapping XS 1ef5bedd
END DESCRIPTION:
XS GIS Cut Line= 2
      2293744.96      7119196.20      2293554.88      7118198.65
#Sta/Elev= 30
  4697.4  835.22  4810.0  832.00  4937.9  829.91  4958.2  826.55  4971.6  823.57
  4988.8  822.44  5005.1  822.41  5006.3  821.91  5013.2  822.41  5023.7  822.61
  5029.5  824.45  5039.7  825.19  5049.8  827.06  5075.9  824.81  5081.0  825.46
  5090.6  824.53  5100.7  824.40  5128.0  825.30  5161.8  823.32  5172.0  825.89
  5180.2  828.81  5185.3  829.05  5237.5  828.28  5253.4  829.23  5273.8  827.75
  5314.5  827.37  5426.5  828.30  5518.1  830.00  5619.9  833.21  5712.9  835.32
#Mann=3,-1,0
  4697.4    0.05       0  5005.1   0.033       0  5013.2    0.05       0
Bank Sta=5005.1,5013.2
Exp/Cntr=0.3,0.1

Type RM Length L Ch R = 1,42458,617,617,617
BEGIN DESCRIPTION:
Mapping XS 1281f5b5
END DESCRIPTION:
XS GIS Cut Line= 2
      2294233.59      7119101.55      2293778.14      7118075.38
#Sta/Elev= 30
  4629.9  838.35  4784.8  834.11  4839.5  831.61  4847.8  830.61  4876.6  830.37
  4899.8  829.01  4905.3  829.52  4928.6  828.54  4937.9  827.12  4951.8  823.03
  4969.6  820.72  4977.5  818.72  4978.8  818.22  4985.8  818.72  4992.6  818.90
  4998.4  821.02  5003.8  824.18  5036.4  823.97  5058.3  825.58  5166.7  824.40
  5200.9  825.02  5242.0  826.69  5265.2  826.33  5277.1  827.69  5294.0  826.37
  5317.2  825.98  5375.6  826.52  5444.5  826.17  5560.8  827.46  5752.6  834.06
#Mann=3,-1,0
  4629.9    0.05       0  4977.5   0.033       0  4985.8    0.05       0
Bank Sta=4977.5,4985.8
Exp/Cntr=0.3,0.1

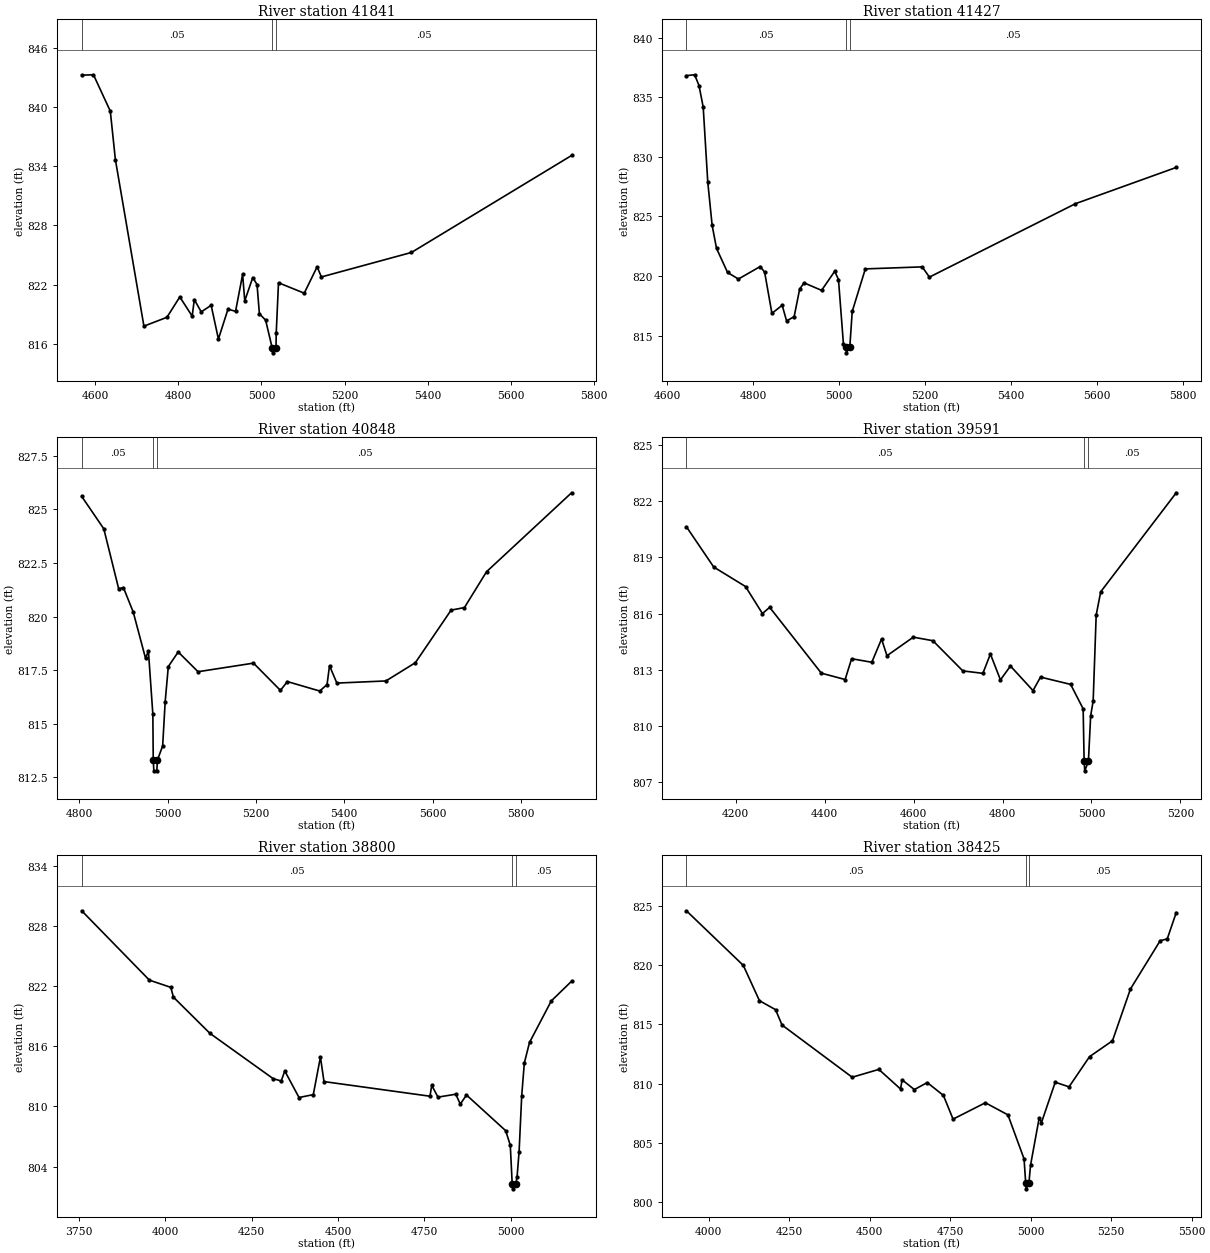
Type RM Length L Ch R = 1,41841,414,414,414
BEGIN DESCRIPTION:
Mapping XS f6f89829
END DESCRIPTION:
XS GIS Cut Line= 2
      2294622.17      7118828.52      2294324.38      7117687.02
#Sta/Elev= 30
  4567.1  843.27  4595.4  843.31  4635.9  839.62  4648.2  834.68  4716.9  817.77
  4772.3  818.67  4803.3  820.74  4833.1  818.79  4838.3  820.47  4854.9  819.22
  4878.8  819.89  4896.3  816.46  4919.3  819.49  4937.6  819.28  4954.6  823.03
  4959.7  820.34  4979.0  822.71  4989.3  822.00  4995.0  819.03  5010.0  818.38
  5025.8  815.56  5027.1  815.06  5035.0  815.56  5035.5  817.04  5041.0  822.18
  5103.0  821.12  5134.0  823.80  5144.3  822.77  5361.3  825.26  5746.8  835.11
#Mann=3,-1,0
  4567.1    0.05       0  5025.8   0.033       0  5035.0    0.05       0
Bank Sta=5025.8,5035
Exp/Cntr=0.3,0.1

Type RM Length L Ch R = 1,41427,579,579,579
BEGIN DESCRIPTION:
Mapping XS 2652aa69
END DESCRIPTION:
XS GIS Cut Line= 2
      2294962.36      7118658.77      2294744.44      7117539.79
#Sta/Elev= 30
  4644.7  836.81  4663.8  836.88  4674.0  835.98  4683.8  834.17  4694.4  827.89
  4704.6  824.25  4714.8  822.32  4740.5  820.30  4765.7  819.75  4816.6  820.80
  4826.8  820.32  4843.7  816.87  4867.6  817.55  4877.8  816.24  4895.4  816.59
  4908.3  818.91  4918.5  819.43  4959.3  818.80  4989.8  820.40  4998.6  819.71
  5010.2  814.28  5015.8  814.06  5017.1  813.56  5025.0  814.06  5030.6  817.03
  5061.1  820.60  5193.6  820.77  5210.2  819.91  5550.2  826.07  5784.7  829.11
#Mann=3,-1,0
  4644.7    0.05       0  5015.8    0.04       0  5025.0    0.05       0
Bank Sta=5015.8,5025
Exp/Cntr=0.3,0.1

Type RM Length L Ch R = 1,40848,1257,1257,1257
BEGIN DESCRIPTION:
Mapping XS 81c959e4
END DESCRIPTION:
XS GIS Cut Line= 2
      2295429.30      7118484.48      2294924.57      7117497.22
#Sta/Elev= 30
  4805.7  825.60  4855.7  824.09  4889.3  821.30  4900.1  821.35  4922.3  820.21
  4950.1  818.06  4956.7  818.39  4966.7  815.45  4967.6  813.31  4969.0  812.81
  4975.7  812.81  4977.0  813.31  4988.9  813.97  4994.6  816.03  5001.7  817.67
  5024.1  818.35  5069.0  817.43  5194.5  817.83  5255.5  816.56  5271.2  816.97
  5344.4  816.53  5361.0  816.83  5366.6  817.71  5383.2  816.90  5494.3  817.00
  5560.9  817.85  5641.8  820.30  5672.0  820.42  5722.0  822.09  5914.5  825.77
#Mann=3,-1,0
  4805.7    0.05       0  4967.6    0.04       0  4977.0    0.05       0
Bank Sta=4967.6,4977
Exp/Cntr=0.3,0.1

Type RM Length L Ch R = 1,39591,791,791,791
BEGIN DESCRIPTION:
Mapping XS 37ab876a
END DESCRIPTION:
XS GIS Cut Line= 3
      2295924.17      7118117.06      2295675.79      7117655.37
      2295157.15      7117402.64
#Sta/Elev= 30
  4089.4  820.64  4150.8  818.49  4222.3  817.45  4260.3  816.01  4276.6  816.34
  4392.7  812.83  4446.2  812.49  4460.8  813.60  4506.2  813.41  4528.1  814.65
  4540.3  813.76  4599.5  814.75  4643.5  814.56  4710.8  812.95  4755.9  812.82
  4772.8  813.85  4795.4  812.47  4817.9  813.21  4868.6  811.90  4885.5  812.62
  4953.2  812.23  4981.3  810.93  4983.5  808.12  4984.9  807.62  4993.1  808.12
  4998.2  810.56  5003.8  811.34  5010.6  815.93  5020.8  817.17  5190.6  822.45
#Mann=3,-1,0
  4089.4    0.05       0  4983.5   0.035       0  4993.1    0.05       0
Bank Sta=4983.5,4993.1
Exp/Cntr=0.3,0.1

Type RM Length L Ch R = 1,38800,375,375,375
BEGIN DESCRIPTION:
Morris Branch 63.0
END DESCRIPTION:
XS GIS Cut Line= 3
      2296128.99      7118309.97      2295829.00      7117110.00
      2295728.99      7116959.98
#Sta/Elev= 30
  3758.6  829.52  3954.4  822.60  4016.3  821.88  4024.0  820.90  4129.6  817.29
  4312.6  812.77  4335.8  812.54  4346.1  813.54  4387.3  810.89  4428.6  811.18
  4449.2  814.93  4459.5  812.48  4766.1  811.02  4771.3  812.10  4789.3  810.93
  4840.9  811.22  4853.8  810.23  4871.8  811.14  4985.2  807.58  4998.5  806.13
  5004.0  802.28  5005.4  801.78  5014.1  802.28  5018.0  802.92  5024.0  805.50
  5031.6  811.09  5039.1  814.33  5054.1  816.38  5117.2  820.53  5175.8  822.49
#Mann=3,-1,0
  3758.6    0.05       0  5004.0   0.033       0  5014.1    0.05       0
Bank Sta=5004,5014.1
Exp/Cntr=0.3,0.1

Type RM Length L Ch R = 1,38425,504,504,504
BEGIN DESCRIPTION:
Morris Branch 62.0
END DESCRIPTION:
XS GIS Cut Line= 3
      2296228.53      7118126.28      2296155.26      7117031.20
      2295878.99      7116709.99
#Sta/Elev= 30
  3931.0  824.56  4107.7  819.96  4157.8  816.99  4207.9  816.23  4227.9  814.94
  4445.8  810.54  4528.6  811.20  4595.9  809.55  4600.9  810.32  4638.9  809.50
  4678.9  810.09  4729.1  809.01  4759.1  807.01  4859.4  808.39  4929.5  807.37
  4979.6  803.66  4984.6  801.64  4986.0  801.14  4994.7  801.64  4999.7  803.13
  5026.6  807.12  5033.6  806.72  5076.4  810.12  5119.2  809.73  5182.8  812.27
  5254.1  813.61  5310.1  817.98  5402.3  822.04  5424.2  822.19  5452.2  824.41
#Mann=3,-1,0
  3931.0    0.05       0  4984.6   0.033       0  4994.7    0.05       0
Bank Sta=4984.6,4994.7
Exp/Cntr=0.3,0.1

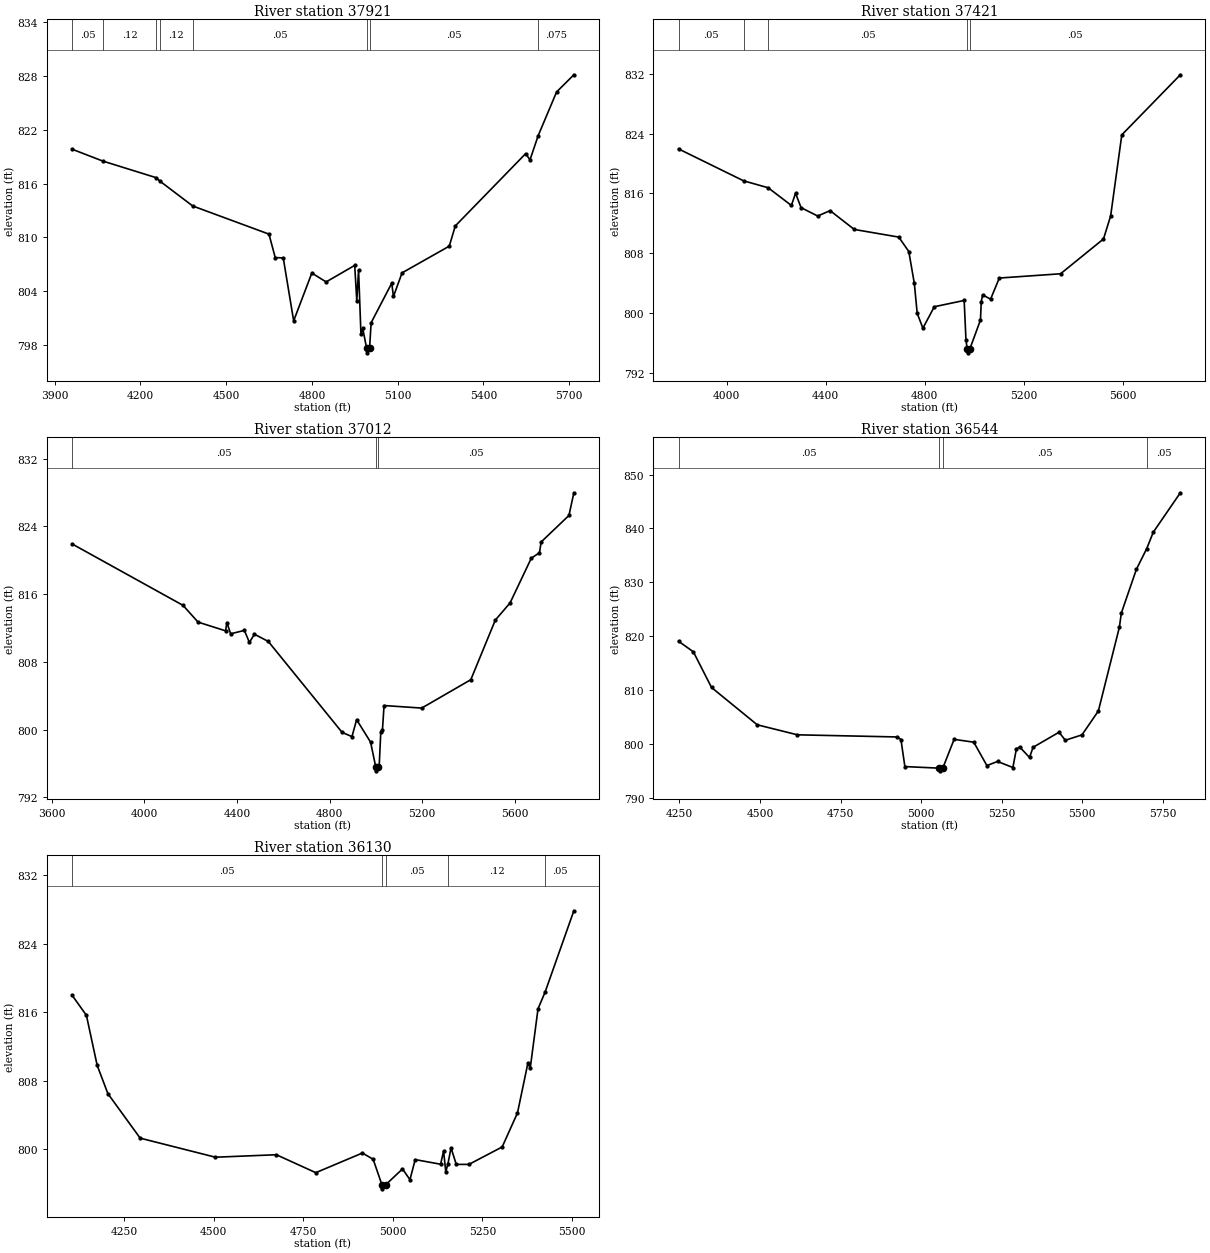
Type RM Length L Ch R = 1,37921,500,500,500
BEGIN DESCRIPTION:
Morris Branch 61.0
END DESCRIPTION:
XS GIS Cut Line= 5
      2297101.30      7117725.15      2296829.00      7117260.00
      2296429.00      7116960.00      2296129.00      7116760.00
      2295832.49      7116562.33
#Sta/Elev= 30
  3960.6  819.82  4067.9  818.50  4255.9  816.64  4267.8  816.27  4382.8  813.50
  4649.6  810.37  4671.5  807.76  4699.6  807.72  4736.0  800.72  4799.6  806.04
  4849.6  805.05  4949.6  806.89  4956.9  802.96  4963.1  806.38  4971.5  799.23
  4977.7  799.87  4991.4  797.66  4992.8  797.16  5001.6  797.66  5007.1  800.51
  5079.2  804.91  5085.2  803.43  5115.3  806.06  5280.5  809.03  5301.6  811.28
  5547.9  819.33  5563.0  818.63  5591.7  821.33  5656.1  826.19  5716.5  828.10
#Mann=8,-1,0
  3960.6    0.05       0  4067.9    0.12       0  4255.9    0.05       0
  4267.8    0.12       0  4382.8    0.05       0  4991.4   0.033       0
  5001.6    0.05       0  5591.7   0.075       0
Bank Sta=4991.4,5001.6
Exp/Cntr=0.3,0.1

Type RM Length L Ch R = 1,37421,409,409,409
BEGIN DESCRIPTION:
Morris Branch 60.0
END DESCRIPTION:
XS GIS Cut Line= 4
      2297166.79      7117785.61      2296829.00      7117110.00
      2296635.82      7116686.65      2296280.70      7115960.98
#Sta/Elev= 30
  3804.9  821.96  4067.9  817.69  4167.3  816.76  4261.2  814.39  4277.9  816.03
  4300.3  814.10  4367.4  812.98  4417.7  813.70  4515.5  811.18  4695.2  810.16
  4735.8  808.23  4758.1  803.97  4769.8  799.95  4792.8  797.97  4838.9  800.84
  4959.6  801.68  4967.0  796.36  4972.0  795.17  4973.4  794.67  4982.3  795.17
  5025.6  799.07  5028.6  801.49  5034.2  802.43  5066.4  801.85  5101.7  804.68
  5349.3  805.25  5522.9  809.91  5551.8  812.99  5596.9  823.84  5833.5  831.88
#Mann=5,-1,0
  3804.9    0.05       0  4067.9    0.12       0  4167.3    0.05       0
  4972.0   0.033       0  4982.3    0.05       0
Bank Sta=4972,4982.3
Exp/Cntr=0.3,0.1

Type RM Length L Ch R = 1,37012,468,468,468
BEGIN DESCRIPTION:
Morris Branch 59.0
END DESCRIPTION:
XS GIS Cut Line= 4
      2297276.51      7117674.98      2296879.00      7116960.00
      2296929.00      7116460.00      2296321.00      7115867.93
#Sta/Elev= 30
  3686.9  821.92  4166.4  814.67  4231.6  812.69  4350.5  811.66  4356.3  812.64
  4372.3  811.31  4431.8  811.71  4453.5  810.29  4475.2  811.26  4535.1  810.41
  4854.2  799.67  4896.9  799.17  4917.0  801.17  4977.3  798.52  4999.4  795.63
  5000.9  795.13  5010.5  795.63  5014.5  795.65  5021.5  799.71  5028.7  799.99
  5035.6  802.84  5198.4  802.54  5410.6  805.89  5516.6  812.93  5580.2  814.95
  5672.2  820.24  5707.5  820.88  5714.6  822.15  5834.8  825.28  5856.1  827.96
#Mann=3,-1,0
  3686.9    0.05       0  4999.4   0.033       0  5010.5    0.05       0
Bank Sta=4999.4,5010.5
Exp/Cntr=0.3,0.1

Type RM Length L Ch R = 1,36544,414,414,414
BEGIN DESCRIPTION:
Morris Branch 58.0
END DESCRIPTION:
XS GIS Cut Line= 3
      2297578.98      7117159.96      2297329.00      7116460.00
      2297179.00      7115660.00
#Sta/Elev= 30
  4247.3  819.04  4293.4  817.07  4349.7  810.45  4491.5  803.52  4616.3  801.66
  4926.8  801.26  4937.5  800.78  4949.7  795.76  5056.2  795.47  5057.7  794.97
  5067.3  795.47  5102.5  800.82  5163.5  800.29  5204.2  795.95  5237.3  796.71
  5284.8  795.59  5295.8  799.05  5306.0  799.40  5336.5  797.45  5347.5  799.34
  5428.1  802.14  5447.6  800.65  5499.3  801.65  5550.1  806.08  5615.4  821.65
  5621.4  824.26  5668.0  832.37  5700.2  836.24  5720.6  839.29  5804.5  846.61
#Mann=4,-1,0
  4247.3    0.05       0  5056.2   0.033       0  5067.3    0.05       0
  5700.2    0.05       0
Bank Sta=5056.2,5067.3
Exp/Cntr=0.3,0.1

Type RM Length L Ch R = 1,36130,431,431,431
BEGIN DESCRIPTION:
Morris Branch 57.0
END DESCRIPTION:
XS GIS Cut Line= 3
      2297629.00      7117110.04      2297629.00      7116210.00
      2297329.02      7115810.03
#Sta/Elev= 30
  4105.0  817.99  4145.0  815.64  4175.0  809.79  4205.0  806.47  4295.0  801.27
  4505.0  799.04  4675.0  799.33  4785.0  797.23  4915.0  799.53  4945.0  798.80
  4969.3  795.84  4970.9  795.34  4980.7  795.84  5026.9  797.67  5047.7  796.41
  5062.3  798.76  5133.2  798.22  5141.5  799.75  5147.7  797.33  5153.7  798.27
  5162.3  800.14  5176.9  798.20  5212.3  798.20  5305.0  800.24  5347.7  804.22
  5376.9  810.08  5383.2  809.43  5405.0  816.40  5424.5  818.33  5505.0  827.87
#Mann=5,-1,0
  4105.0    0.05       0  4969.3   0.033       0  4980.7    0.05       0
  5153.7    0.12       0  5424.5    0.05       0
Bank Sta=4969.3,4980.7
Exp/Cntr=0.3,0.1