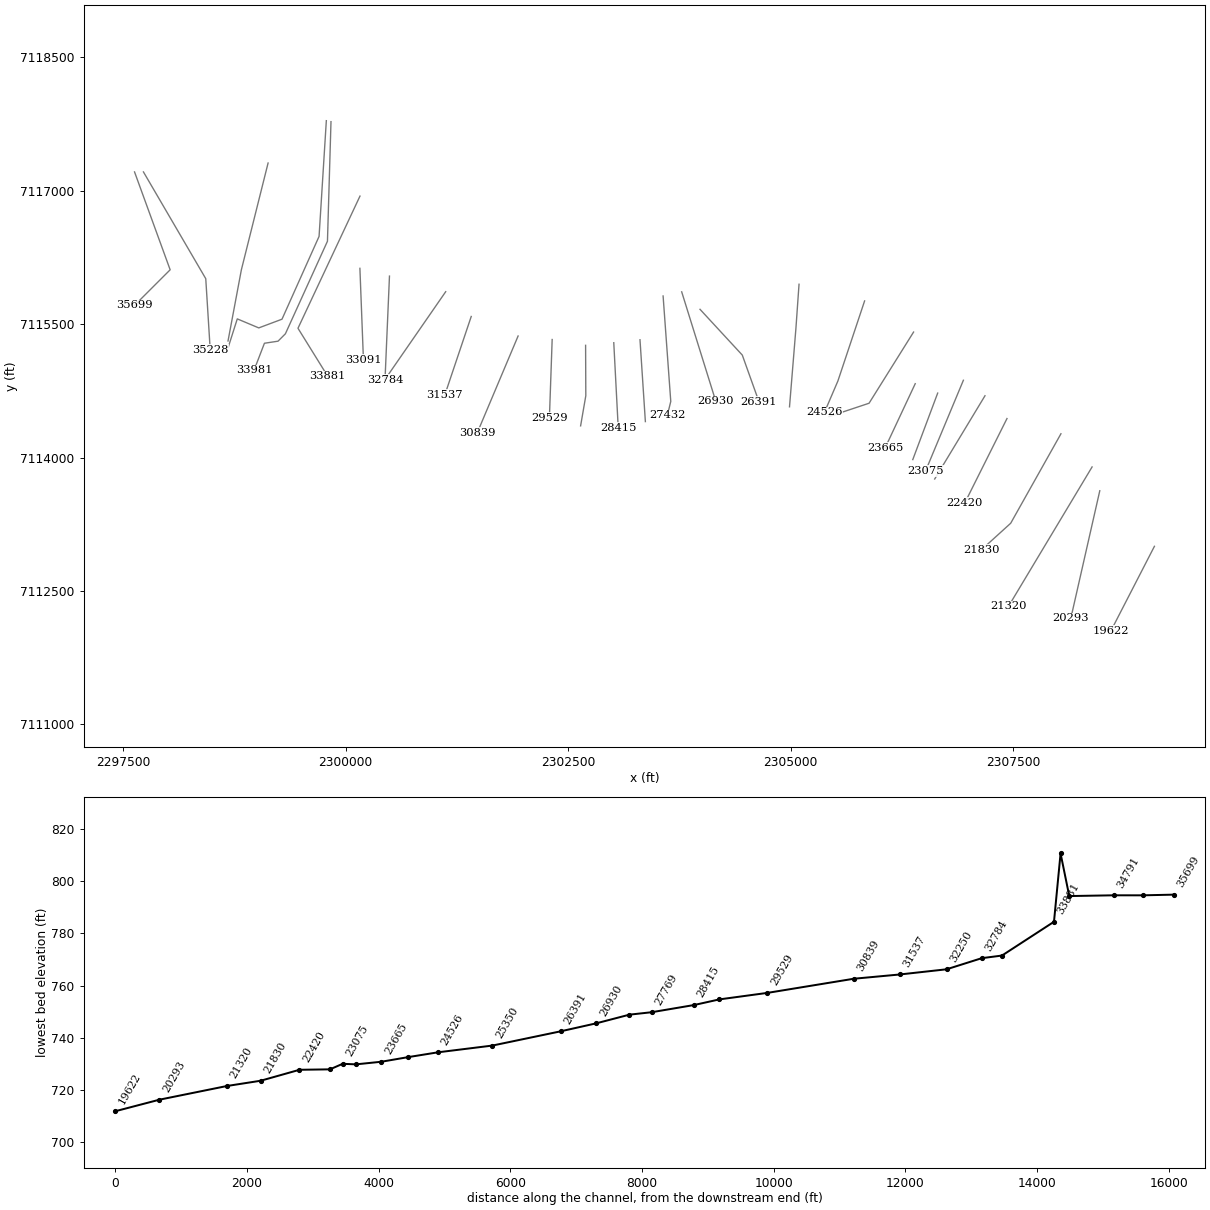
HEC-RAS study Morris Branch.prj: Morris Branch Base Level Engineering

--- Morris Branch.g01 (geometry) --- (continued)

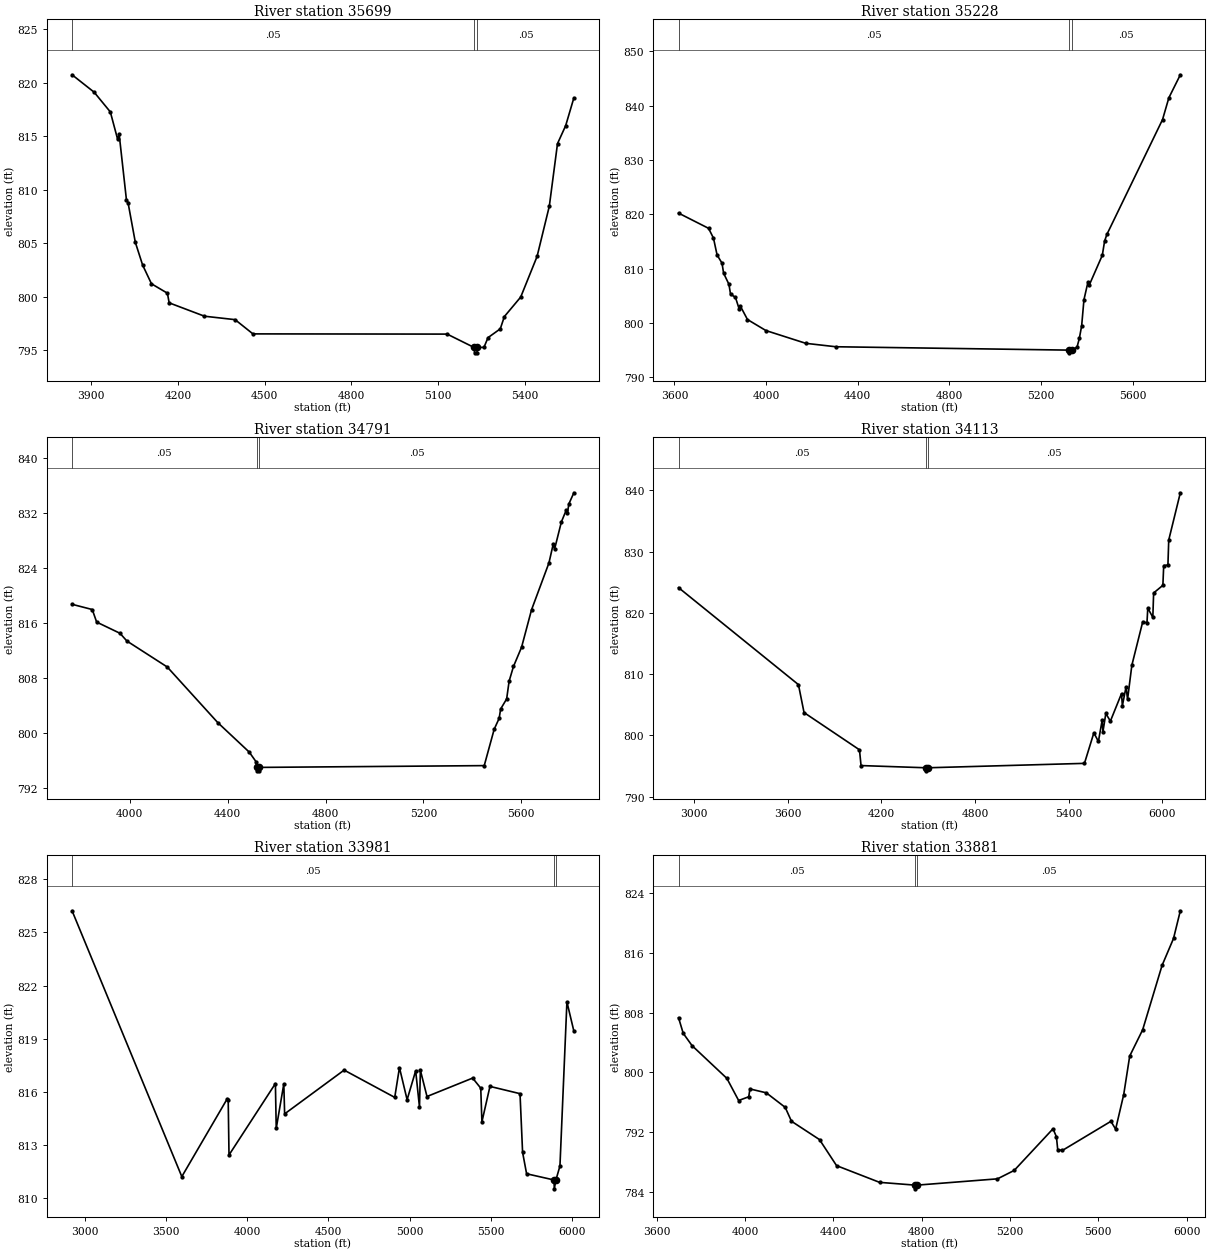
Type RM Length L Ch R = 1,35699,471,471,471
BEGIN DESCRIPTION:
Morris Branch 56.0
END DESCRIPTION:
XS GIS Cut Line= 3
      2297628.99      7117210.03      2298029.00      7116110.00
      2297628.99      7115709.99
#Sta/Elev= 30
  3833.6  820.73  3910.1  819.10  3966.0  817.26  3991.2  814.71  3996.6  815.16
  4021.8  809.03  4027.2  808.80  4052.4  805.09  4077.7  802.96  4108.3  801.21
  4163.5  800.33  4169.5  799.43  4291.8  798.18  4397.6  797.86  4459.4  796.53
  5131.4  796.51  5224.7  795.26  5226.2  794.76  5234.5  794.76  5236.1  795.26
  5258.7  795.27  5272.8  796.18  5315.2  797.00  5329.4  798.15  5385.9  799.97
  5442.5  803.76  5484.9  808.46  5513.2  814.30  5541.5  815.98  5569.8  818.57
#Mann=3,-1,0
  3833.6    0.05       0  5224.7   0.033       0  5236.1    0.05       0
Bank Sta=5224.7,5236.1
Exp/Cntr=0.3,0.1

Type RM Length L Ch R = 1,35228,437,437,437
BEGIN DESCRIPTION:
Morris Branch 55.0
END DESCRIPTION:
XS GIS Cut Line= 3
      2297728.99      7117210.01      2298429.00      7116010.00
      2298479.00      7115210.02
#Sta/Elev= 30
  3617.9  820.22  3749.0  817.42  3770.5  815.61  3786.2  812.51  3807.7  811.01
  3814.7  809.16  3837.9  807.12  3844.9  805.31  3866.4  804.71  3882.1  802.64
  3887.9  803.09  3918.9  800.63  3999.5  798.60  4173.6  796.25  4304.7  795.62
  5322.0  795.00  5323.6  794.50  5333.6  795.00  5357.8  795.55  5367.9  797.19
  5377.9  799.47  5387.9  804.27  5405.4  807.52  5410.4  806.91  5468.1  812.46
  5478.1  815.07  5488.1  816.30  5731.1  837.44  5758.6  841.44  5808.7  845.68
#Mann=3,-1,0
  3617.9    0.05       0  5322.0   0.033       0  5333.6    0.05       0
Bank Sta=5322,5333.6
Exp/Cntr=0.3,0.1

Type RM Length L Ch R = 1,34791,678,678,678
BEGIN DESCRIPTION:
Morris Branch 54.0
END DESCRIPTION:
XS GIS Cut Line= 3
      2299129.00      7117309.99      2298829.00      7116110.00
      2298678.99      7115309.97
#Sta/Elev= 30
  3763.9  818.76  3846.4  818.00  3864.4  816.17  3959.7  814.54  3988.1  813.41
  4153.0  809.63  4359.2  801.54  4488.0  797.24  4516.4  795.81  4518.3  795.01
  4519.9  794.51  4528.3  794.51  4529.9  795.01  5448.5  795.27  5489.2  800.57
  5509.5  802.16  5515.5  803.51  5540.1  804.98  5550.2  807.57  5568.0  809.71
  5601.1  812.51  5641.8  817.96  5713.0  824.79  5730.8  827.58  5735.9  826.78
  5763.9  830.77  5783.4  832.45  5788.5  832.04  5794.4  833.38  5814.8  835.00
#Mann=3,-1,0
  3763.9    0.05       0  4518.3   0.033       0  4529.9    0.05       0
Bank Sta=4518.3,4529.9
Exp/Cntr=0.3,0.1

Type RM Length L Ch R = 1,34113,132,132,132
BEGIN DESCRIPTION:
Mapping XS 6bba3084
END DESCRIPTION:
XS GIS Cut Line= 6
      2299783.25      7117786.22      2299701.61      7116485.34
      2299285.33      7115554.70      2299024.27      7115456.78
      2298782.99      7115558.19      2298680.73      7115236.79
#Sta/Elev= 30
  2901.5  824.12  3669.2  808.29  3705.1  803.73  4060.0  797.65  4070.0  795.08
  4485.8  794.72  4487.4  794.22  4497.4  794.72  5500.5  795.44  5560.7  800.42
  5589.8  799.01  5613.6  802.44  5619.0  800.64  5637.3  803.58  5666.5  802.33
  5737.8  806.83  5743.2  804.84  5766.9  807.93  5776.5  805.90  5804.0  811.46
  5873.7  818.56  5900.7  818.37  5906.0  820.79  5938.2  819.27  5943.4  823.25
  6002.6  824.50  6007.9  827.72  6034.9  827.81  6040.1  831.89  6114.3  839.60
#Mann=3,-1,0
  2901.5    0.05       0  4485.8   0.033       0  4497.4    0.05       0
Bank Sta=4485.8,4497.4
Exp/Cntr=0.3,0.1

Type RM Length L Ch R = 1,33981,100,100,100
BEGIN DESCRIPTION:
Mapping XS 1035d466
END DESCRIPTION:
XS GIS Cut Line= 6
      2299835.54      7117775.21      2299795.80      7116430.87
      2299323.42      7115390.60      2299240.56      7115307.50
      2299087.92      7115284.28      2298970.95      7114980.11
#Sta/Elev= 30
  2923.4  826.22  3598.7  811.22  3878.7  815.62  3884.1  815.57  3889.1  812.44
  4174.6  816.47  4179.7  813.94  4226.3  816.45  4231.4  814.76  4597.5  817.23
  4908.9  815.69  4937.9  817.37  4985.0  815.56  5037.7  817.19  5061.2  815.14
  5066.7  817.22  5107.4  815.74  5388.3  816.78  5438.2  816.21  5445.3  814.31
  5494.8  816.31  5679.8  815.90  5695.6  812.59  5720.3  811.38  5889.1  811.03
  5890.7  810.53  5900.7  811.03  5925.5  811.82  5968.4  821.08  6011.1  819.43
#Mann=3,-1,0
  2923.4    0.05       0  5889.1   0.033       0  5900.7    0.05       0
Bank Sta=5889.1,5900.7
Exp/Cntr=0.3,0.1

Type RM Length L Ch R = 1,33881,790,790,790
BEGIN DESCRIPTION:
Mapping XS f28ee07c
END DESCRIPTION:
XS GIS Cut Line= 4
      2300161.17      7116938.25      2299984.72      7116561.85
      2299464.74      7115452.65      2299797.85      7114915.02
#Sta/Elev= 30
  3698.7  807.33  3720.0  805.23  3760.1  803.58  3917.6  799.20  3971.0  796.23
  4016.7  796.73  4022.2  797.78  4096.2  797.26  4182.0  795.31  4210.3  793.45
  4337.3  790.99  4414.6  787.50  4609.4  785.26  4768.9  784.89  4770.5  784.39
  4780.5  784.89  5143.6  785.73  5219.4  786.86  5395.2  792.44  5410.6  791.36
  5416.5  789.64  5437.8  789.54  5657.5  793.44  5678.8  792.39  5715.4  797.02
  5742.6  802.19  5801.3  805.71  5889.1  814.33  5941.1  817.95  5971.9  821.66
#Mann=3,-1,0
  3698.7    0.05       0  4768.9   0.033       0  4780.5    0.05       0
Bank Sta=4768.9,4780.5
Exp/Cntr=0.3,0.1

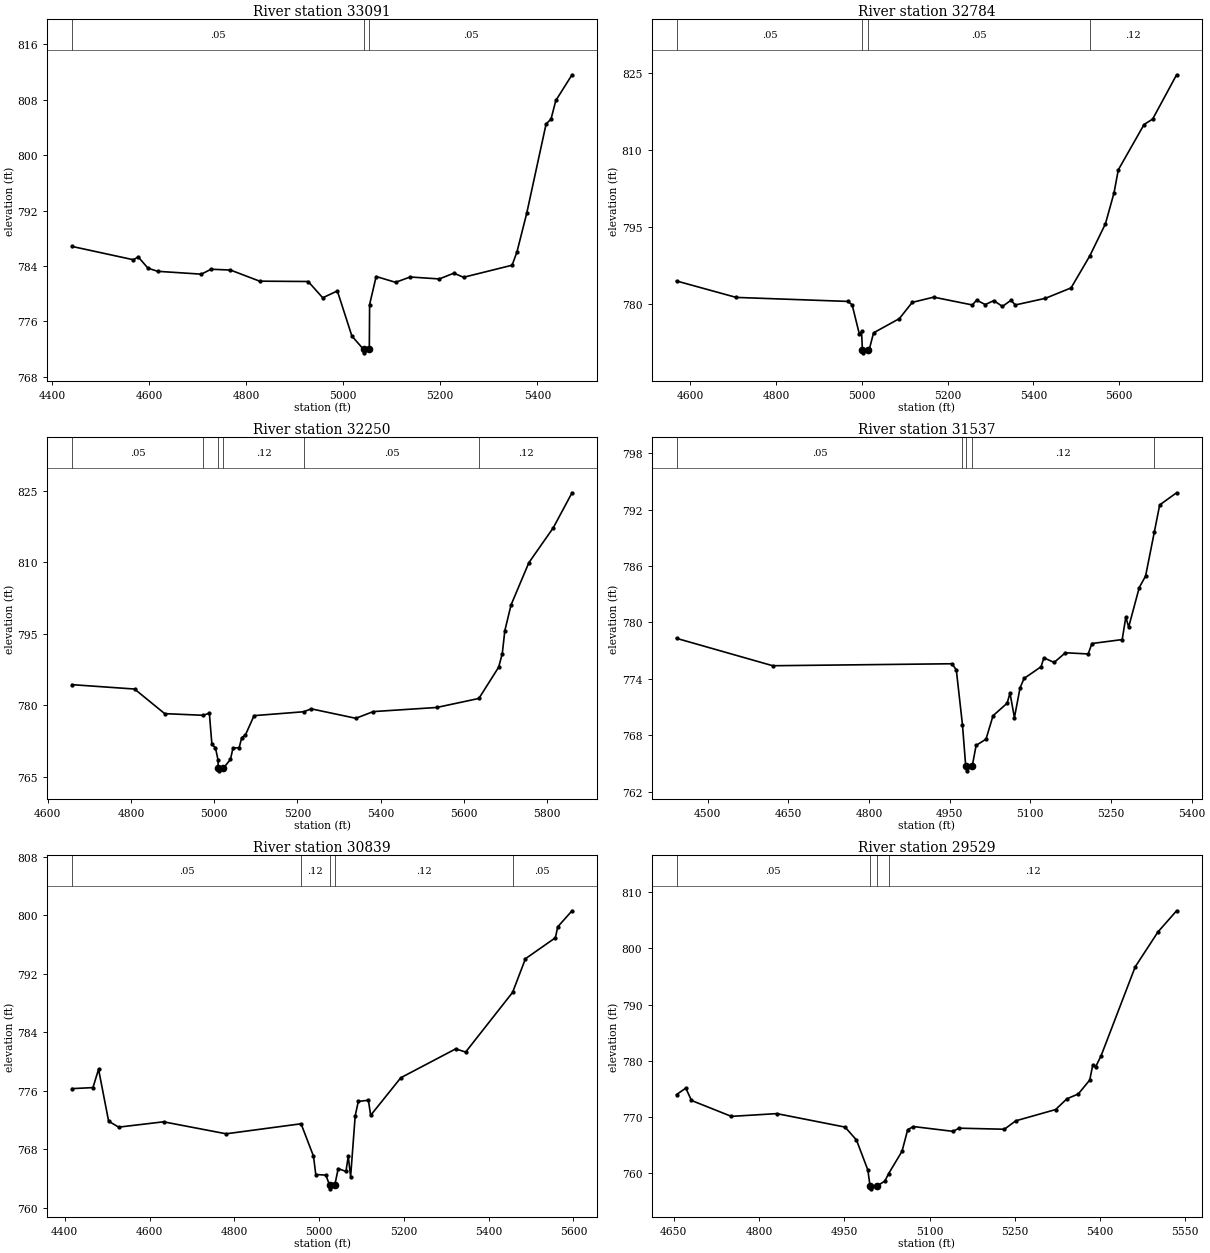
Type RM Length L Ch R = 1,33091,307,307,307
BEGIN DESCRIPTION:
Mapping XS abfa5532
END DESCRIPTION:
XS GIS Cut Line= 2
      2300160.29      7116126.44      2300200.03      7115096.61
#Sta/Elev= 30
  4440.9  786.82  4567.4  784.90  4577.4  785.31  4597.5  783.68  4617.5  783.23
  4707.5  782.82  4727.6  783.53  4767.6  783.41  4827.6  781.81  4927.7  781.76
  4957.7  779.41  4987.8  780.40  5017.8  773.89  5041.8  771.97  5043.5  771.47
  5053.7  771.97  5054.3  778.44  5067.8  782.48  5107.8  781.64  5137.9  782.41
  5197.9  782.13  5227.9  782.96  5247.9  782.37  5348.0  784.11  5358.0  786.03
  5378.0  791.57  5418.1  804.50  5428.1  805.17  5438.1  807.87  5471.5  811.58
#Mann=3,-1,0
  4440.9    0.05       0  5041.8   0.033       0  5053.7    0.05       0
Bank Sta=5041.8,5053.7
Exp/Cntr=0.3,0.1

Type RM Length L Ch R = 1,32784,534,534,534
BEGIN DESCRIPTION:
Mapping XS 1bf8d6a4
END DESCRIPTION:
XS GIS Cut Line= 3
      2300492.41      7116039.00      2300457.19      7115220.48
      2300442.29      7114874.27
#Sta/Elev= 30
  4568.1  784.47  4707.2  781.27  4967.5  780.49  4977.5  779.83  4994.4  774.09
  4999.4  774.63  5001.5  770.97  5003.2  770.47  5013.5  770.97  5017.5  771.17
  5027.5  774.37  5087.6  777.14  5117.6  780.30  5167.6  781.32  5257.7  779.80
  5267.7  780.74  5287.8  779.88  5307.8  780.64  5327.8  779.51  5347.8  780.71
  5357.8  779.80  5427.9  781.09  5487.9  783.12  5531.5  789.35  5568.0  795.61
  5588.0  801.63  5598.0  806.13  5658.1  814.96  5678.1  816.02  5733.9  824.65
#Mann=4,-1,0
  4568.1    0.05       0  5001.5   0.035       0  5013.5    0.05       0
  5531.5    0.12       0
Bank Sta=5001.5,5013.5
Exp/Cntr=0.3,0.1

Type RM Length L Ch R = 1,32250,713,713,713
BEGIN DESCRIPTION:
Mapping XS ac4c092d
END DESCRIPTION:
XS GIS Cut Line= 3
      2301123.92      7115863.71      2300614.67      7115126.87
      2300440.34      7114874.64
#Sta/Elev= 30
  4658.1  784.33  4808.5  783.41  4881.0  778.24  4973.8  777.89  4988.4  778.34
  4994.5  771.77  5003.0  771.08  5009.4  768.45  5009.5  766.72  5011.1  766.22
  5021.5  766.72  5039.1  768.61  5045.2  771.01  5060.1  771.09  5066.2  773.19
  5075.0  773.74  5095.9  777.82  5215.7  778.64  5233.1  779.25  5340.6  777.26
  5382.5  778.67  5534.6  779.53  5636.4  781.43  5683.9  787.99  5692.7  790.86
  5698.8  795.67  5713.7  801.07  5756.6  809.96  5815.1  817.27  5860.4  824.65
#Mann=6,-1,0
  4658.1    0.05       0  4973.8    0.12       0  5009.5    0.07       0
  5021.5    0.12       0  5215.7    0.05       0  5636.4    0.12       0
Bank Sta=5009.5,5021.5
Exp/Cntr=0.3,0.1

Type RM Length L Ch R = 1,31537,698,698,698
BEGIN DESCRIPTION:
Mapping XS 3cb856cd
END DESCRIPTION:
XS GIS Cut Line= 2
      2301410.71      7115585.30      2301114.33      7114704.21
#Sta/Elev= 30
  4442.3  778.31  4621.1  775.40  4954.3  775.61  4962.4  774.96  4973.8  769.14
  4979.9  764.73  4981.6  764.23  4992.0  764.73  4999.2  766.93  5017.6  767.60
  5030.7  770.09  5056.9  771.42  5062.2  772.50  5070.4  769.88  5080.9  773.05
  5088.4  774.05  5119.9  775.29  5125.2  776.24  5144.2  775.75  5165.3  776.78
  5207.5  776.65  5214.5  777.76  5270.8  778.18  5277.5  780.57  5282.8  779.51
  5302.5  783.71  5314.3  784.94  5330.4  789.58  5340.5  792.49  5371.9  793.78
#Mann=5,-1,0
  4442.3    0.05       0  4973.8    0.12       0  4979.9    0.07       0
  4992.0    0.12       0  5330.4    0.05       0
Bank Sta=4979.9,4992
Exp/Cntr=0.3,0.1

Type RM Length L Ch R = 1,30839,1310,1310,1310
BEGIN DESCRIPTION:
Mapping XS 5e4065bc
END DESCRIPTION:
XS GIS Cut Line= 2
      2301937.14      7115365.66      2301478.85      7114278.72
#Sta/Elev= 30
  4417.0  776.31  4466.5  776.45  4479.7  778.96  4503.4  771.86  4527.1  771.04
  4632.9  771.77  4780.6  770.13  4957.4  771.50  4986.7  767.07  4992.1  764.56
  5015.8  764.48  5024.8  763.10  5026.5  762.60  5036.9  763.10  5045.0  765.37
  5063.3  764.98  5068.7  767.07  5074.3  764.27  5085.1  772.59  5092.4  774.56
  5116.2  774.72  5121.6  772.66  5192.7  777.80  5322.2  781.75  5345.6  781.31
  5456.4  789.48  5486.7  794.08  5557.4  796.95  5562.8  798.44  5596.6  800.64
#Mann=5,-1,0
  4417.0    0.05       0  4957.4    0.12       0  5024.8    0.07       0
  5036.9    0.12       0  5456.4    0.05       0
Bank Sta=5024.8,5036.9
Exp/Cntr=0.3,0.1

Type RM Length L Ch R = 1,29529,730,730,730
BEGIN DESCRIPTION:
Mapping XS b86a04c7
END DESCRIPTION:
XS GIS Cut Line= 2
      2302319.74      7115326.31      2302288.83      7114447.26
#Sta/Elev= 30
  4655.0  773.98  4671.3  775.13  4681.3  772.93  4751.4  770.10  4831.4  770.59
  4951.5  768.19  4971.5  765.89  4991.5  760.56  4995.4  757.70  4997.1  757.20
  5007.6  757.70  5021.5  758.59  5028.1  759.92  5051.6  763.88  5061.6  767.72
  5071.6  768.29  5141.6  767.43  5151.6  768.00  5231.7  767.81  5251.7  769.31
  5321.7  771.31  5341.7  773.23  5361.7  774.09  5381.8  776.57  5387.1  779.22
  5392.1  778.90  5401.8  780.89  5461.8  796.72  5501.8  802.93  5534.6  806.70
#Mann=4,-1,0
  4655.0    0.05       0  4995.4   0.035       0  5007.6    0.05       0
  5028.1    0.12       0
Bank Sta=4995.4,5007.6
Exp/Cntr=0.3,0.1

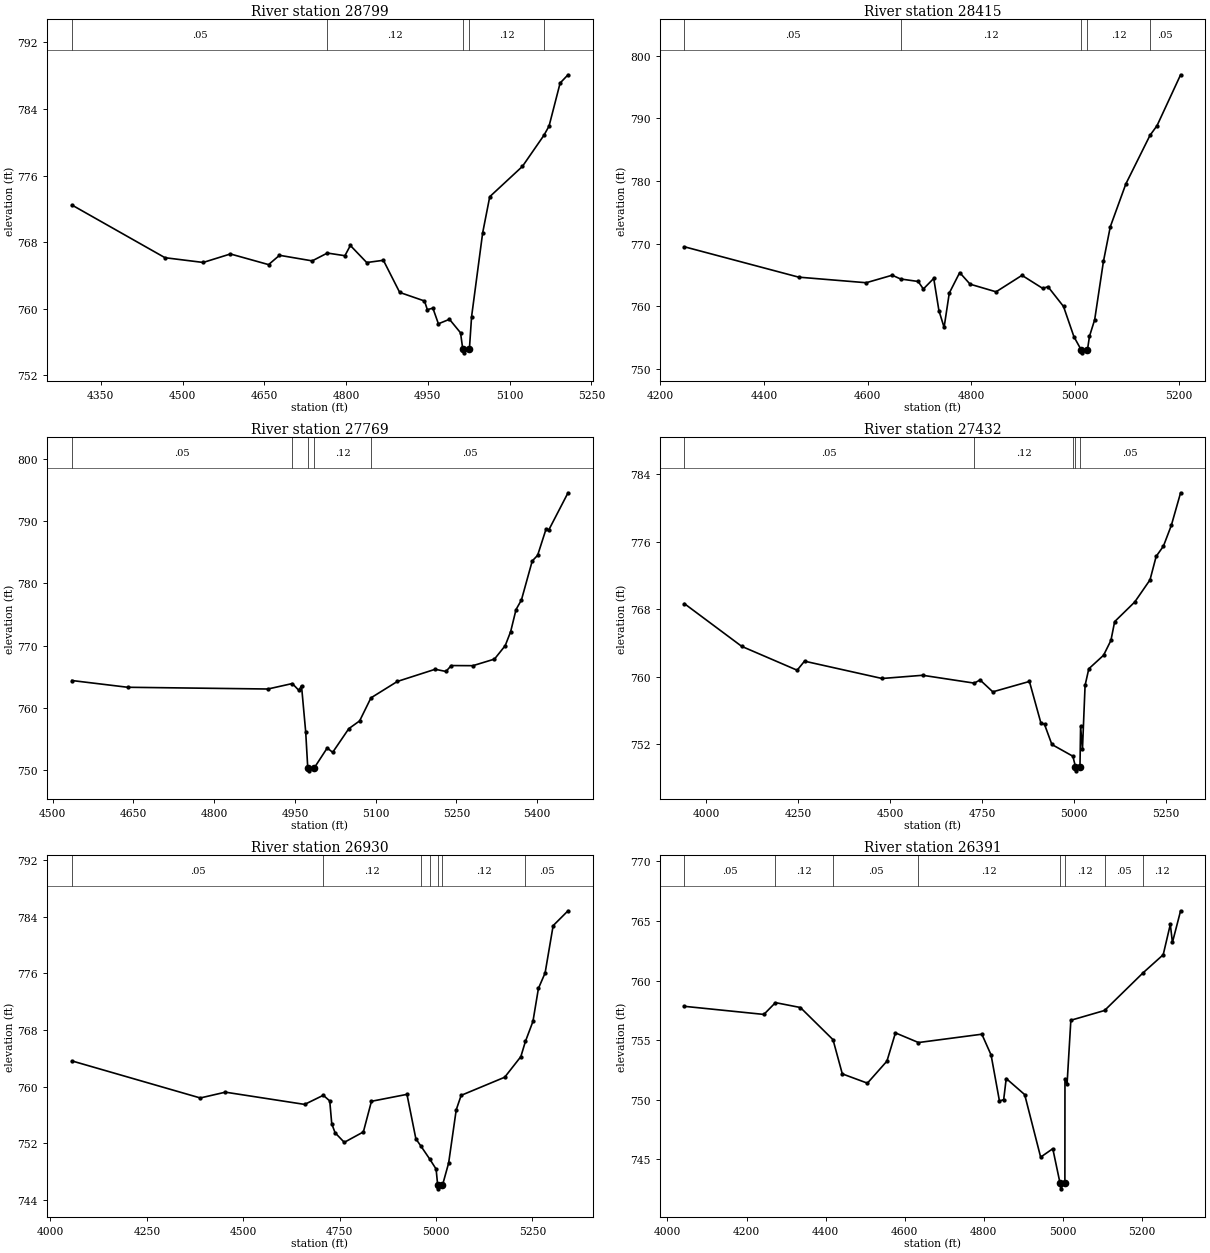
Type RM Length L Ch R = 1,28799,384,384,384
BEGIN DESCRIPTION:
Mapping XS cc78b42d
END DESCRIPTION:
XS GIS Cut Line= 3
      2302695.33      7115260.96      2302697.59      7114693.95
      2302639.22      7114355.67
#Sta/Elev= 30
  4296.9  772.48  4467.9  766.14  4537.9  765.57  4587.9  766.59  4657.9  765.31
  4677.9  766.43  4737.9  765.76  4765.7  766.70  4797.9  766.38  4807.9  767.61
  4837.9  765.56  4868.5  765.83  4898.4  761.97  4943.9  760.94  4949.1  759.90
  4959.3  760.08  4969.4  758.20  4989.7  758.74  5010.0  757.12  5014.0  755.21
  5015.7  754.71  5026.3  755.21  5030.3  759.07  5050.6  769.13  5063.6  773.47
  5123.5  777.11  5163.0  780.85  5172.4  781.96  5192.7  787.13  5207.2  788.12
#Mann=5,-1,0
  4296.9    0.05       0  4765.7    0.12       0  5014.0    0.07       0
  5026.3    0.12       0  5163.0    0.05       0
Bank Sta=5014,5026.3
Exp/Cntr=0.3,0.1

Type RM Length L Ch R = 1,28415,646,646,646
BEGIN DESCRIPTION:
Mapping XS faf1ad4d
END DESCRIPTION:
XS GIS Cut Line= 2
      2303011.70      7115290.24      2303061.67      7114334.54
#Sta/Elev= 30
  4246.5  769.49  4467.0  764.64  4597.2  763.75  4647.3  764.95  4663.4  764.35
  4697.4  763.95  4707.4  762.75  4727.4  764.44  4737.4  759.31  4747.4  756.62
  4757.4  762.10  4777.5  765.37  4797.5  763.52  4847.6  762.30  4897.6  764.93
  4937.7  762.84  4947.7  763.12  4977.7  759.96  4997.8  755.13  5011.6  753.06
  5013.3  752.56  5023.9  753.06  5027.8  755.21  5037.8  757.85  5054.7  767.16
  5067.9  772.68  5097.9  779.52  5144.5  787.28  5158.0  788.81  5203.5  796.94
#Mann=5,-1,0
  4246.5    0.05       0  4663.4    0.12       0  5011.6    0.07       0
  5023.9    0.12       0  5144.5    0.05       0
Bank Sta=5011.6,5023.9
Exp/Cntr=0.3,0.1

Type RM Length L Ch R = 1,27769,337,337,337
BEGIN DESCRIPTION:
Mapping XS 253fc59c
END DESCRIPTION:
XS GIS Cut Line= 2
      2303306.19      7115323.62      2303366.66      7114403.60
#Sta/Elev= 30
  4535.5  764.36  4639.3  763.27  4899.9  762.99  4945.2  763.87  4957.3  762.78
  4962.3  763.52  4970.1  756.06  4973.9  750.30  4975.6  749.80  4986.2  750.30
  5010.1  753.49  5020.2  752.78  5050.2  756.60  5070.3  757.85  5091.3  761.56
  5140.4  764.21  5210.6  766.17  5230.6  765.82  5240.6  766.77  5280.7  766.75
  5320.8  767.81  5340.8  769.98  5350.9  772.24  5360.9  775.80  5370.9  777.34
  5391.0  783.63  5401.0  784.54  5416.5  788.73  5421.5  788.59  5457.5  794.62
#Mann=5,-1,0
  4535.5    0.05       0  4945.2    0.12       0  4973.9    0.07       0
  4986.2    0.12       0  5091.3    0.05       0
Bank Sta=4973.9,4986.2
Exp/Cntr=0.3,0.1

Type RM Length L Ch R = 1,27432,502,502,502
BEGIN DESCRIPTION:
Mapping XS cb957590
END DESCRIPTION:
XS GIS Cut Line= 4
      2303565.70      7115815.47      2303592.45      7115447.81
      2303651.93      7114630.30      2303613.88      7114475.51
#Sta/Elev= 30
  3941.3  768.66  4097.2  763.60  4247.6  760.78  4267.6  761.85  4478.2  759.80
  4588.5  760.18  4728.7  759.25  4744.3  759.63  4779.0  758.22  4878.4  759.45
  4909.3  754.58  4919.4  754.37  4939.4  751.99  4996.4  750.60  5003.4  749.37
  5005.1  748.87  5015.7  749.37  5017.4  754.12  5022.5  751.46  5029.6  758.99
  5039.7  760.95  5079.8  762.55  5099.8  764.31  5109.9  766.53  5164.4  768.85
  5205.9  771.47  5222.6  774.25  5242.3  775.46  5263.8  777.92  5289.0  781.78
#Mann=5,-1,0
  3941.3    0.05       0  4728.7    0.12       0  4996.4    0.05       0
  5003.4   0.033       0  5015.7    0.05       0
Bank Sta=5003.4,5015.7
Exp/Cntr=0.3,0.1

Type RM Length L Ch R = 1,26930,539,539,539
BEGIN DESCRIPTION:
Mapping XS 2a7f42ed
END DESCRIPTION:
XS GIS Cut Line= 3
      2303774.54      7115862.12      2303871.65      7115550.29
      2304157.29      7114633.15
#Sta/Elev= 30
  4055.4  763.65  4388.7  758.41  4453.8  759.23  4659.4  757.50  4707.8  758.79
  4724.5  757.99  4729.7  754.77  4738.4  753.49  4762.2  752.14  4811.7  753.61
  4832.7  757.94  4924.8  758.92  4947.9  752.64  4961.6  751.56  4984.4  749.73
  5000.4  748.36  5004.5  746.07  5006.3  745.57  5016.9  746.07  5032.9  749.22
  5052.6  756.74  5065.4  758.78  5178.3  761.34  5220.2  764.25  5232.0  766.39
  5251.6  769.23  5265.8  773.89  5283.1  776.07  5304.0  782.76  5342.6  784.86
#Mann=7,-1,0
  4055.4    0.05       0  4707.8    0.12       0  4961.6    0.05       0
  4984.4    0.12       0  5004.5    0.07       0  5016.9    0.12       0
  5232.0    0.05       0
Bank Sta=5004.5,5016.9
Exp/Cntr=0.3,0.1

Type RM Length L Ch R = 1,26391,1041,1041,1041
BEGIN DESCRIPTION:
Mapping XS d54dee83
END DESCRIPTION:
XS GIS Cut Line= 3
      2303980.37      7115665.70      2304455.30      7115151.21
      2304642.02      7114628.55
#Sta/Elev= 30
  4042.8  757.84  4243.9  757.16  4273.2  758.15  4336.3  757.74  4418.8  755.04
  4442.3  752.17  4505.8  751.39  4555.2  753.24  4576.7  755.61  4635.0  754.80
  4795.3  755.50  4818.6  753.76  4839.8  749.89  4850.5  750.01  4856.9  751.78
  4903.6  750.43  4944.0  745.18  4974.7  745.89  4992.9  743.02  4994.7  742.52
  5005.3  743.02  5005.5  751.74  5010.8  751.31  5020.4  756.67  5105.6  757.49
  5203.3  760.66  5254.0  762.17  5272.0  764.72  5277.3  763.20  5298.0  765.86
#Mann=8,-1,0
  4042.8    0.05       0  4273.2    0.12       0  4418.8    0.05       0
  4635.0    0.12       0  4992.9    0.07       0  5005.3    0.12       0
  5105.6    0.05       0  5203.3    0.12       0
Bank Sta=4992.9,5005.3
Exp/Cntr=0.3,0.1

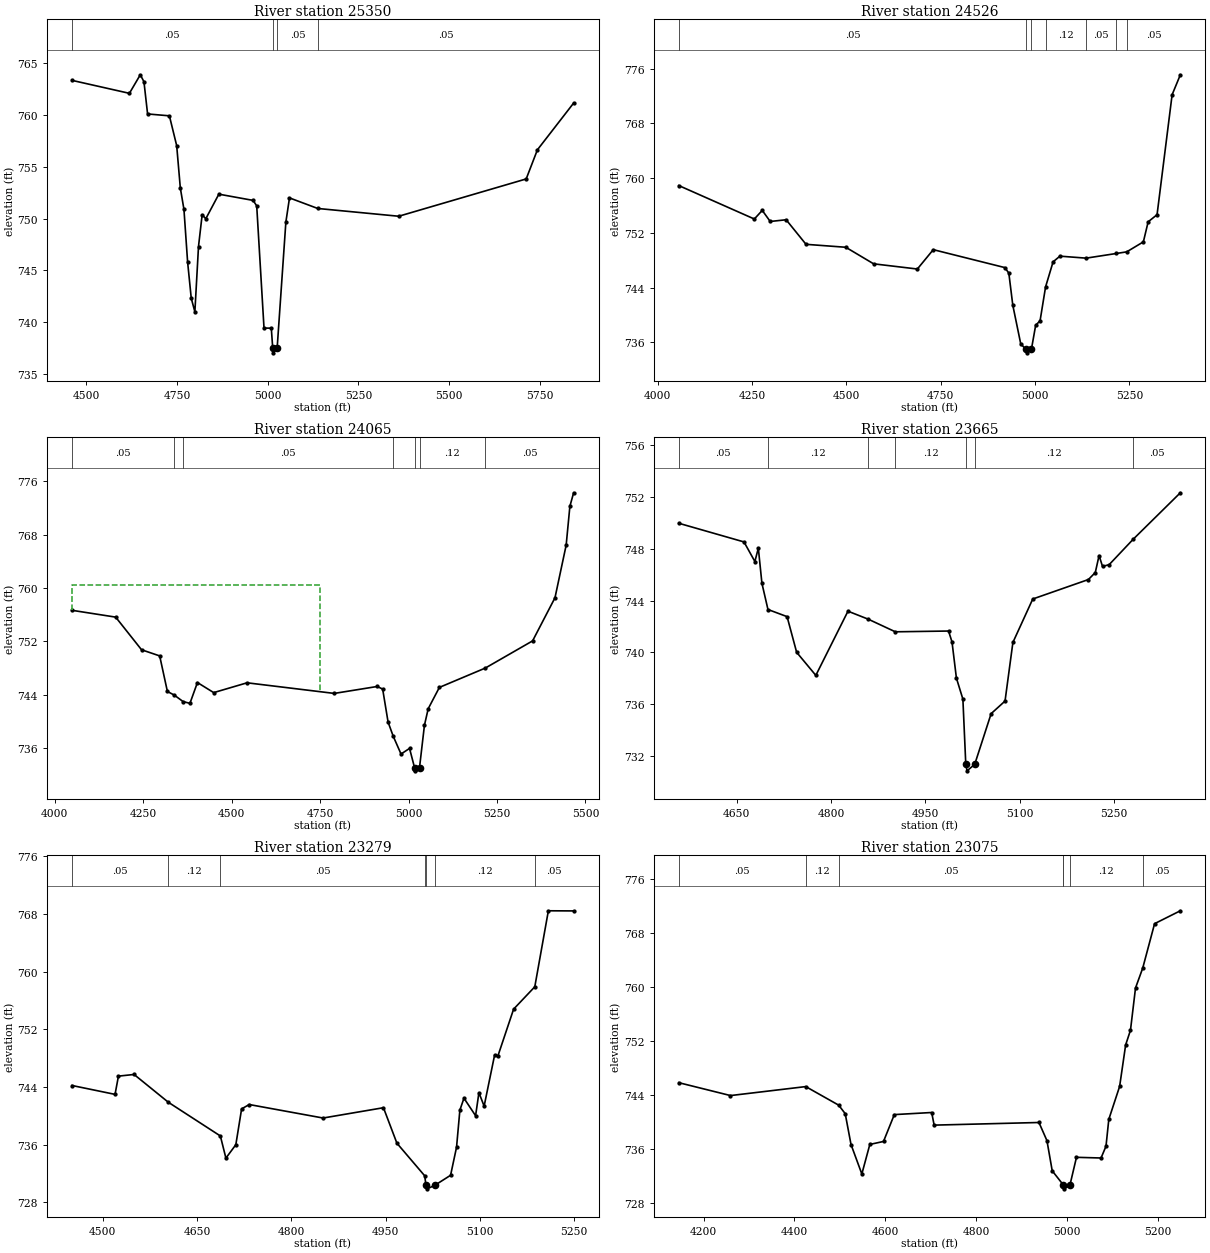
Type RM Length L Ch R = 1,25350,824,824,824
BEGIN DESCRIPTION:
Mapping XS e24f6305
END DESCRIPTION:
XS GIS Cut Line= 3
      2305092.44      7115947.57      2305057.82      7115455.17
      2304985.54      7114569.73
#Sta/Elev= 30
  4460.9  763.34  4618.9  762.09  4648.9  763.88  4659.0  763.21  4669.0  760.10
  4729.1  759.92  4749.2  757.04  4759.2  752.96  4769.2  750.89  4779.3  745.81
  4789.3  742.32  4799.3  741.01  4809.3  747.31  4819.4  750.38  4829.4  749.99
  4865.4  752.36  4959.7  751.76  4969.7  751.23  4989.8  739.44  5009.9  739.43
  5013.7  737.55  5015.5  737.05  5026.1  737.55  5050.0  749.66  5060.0  752.00
  5137.8  750.98  5361.0  750.23  5712.2  753.83  5743.1  756.64  5842.9  761.15
#Mann=4,-1,0
  4460.9    0.05       0  5013.7   0.033       0  5026.1    0.05       0
  5137.8    0.05       0
Bank Sta=5013.7,5026.1
Exp/Cntr=0.3,0.1

Type RM Length L Ch R = 1,24526,461,461,461
BEGIN DESCRIPTION:
Morris Branch 38.0
END DESCRIPTION:
XS GIS Cut Line= 3
      2305828.99      7115759.98      2305529.00      7114860.00
      2305378.98      7114509.96
#Sta/Elev= 30
  4055.7  758.93  4256.0  754.04  4277.0  755.30  4298.1  753.68  4340.3  753.93
  4393.0  750.34  4498.4  749.91  4572.2  747.49  4688.1  746.73  4730.3  749.56
  4920.0  746.94  4930.6  746.13  4941.1  741.44  4962.2  735.78  4976.2  734.98
  4978.2  734.48  4990.4  734.98  5001.7  738.50  5013.4  739.17  5028.0  744.12
  5047.9  747.78  5066.0  748.61  5135.6  748.32  5215.4  749.00  5243.1  749.24
  5287.2  750.70  5299.9  753.63  5323.5  754.67  5363.4  772.20  5385.2  775.12
#Mann=7,-1,0
  4055.7    0.05       0  4976.2   0.033       0  4990.4    0.05       0
  5028.0    0.12       0  5135.6    0.05       0  5215.4    0.12       0
  5243.1    0.05       0
Bank Sta=4976.2,4990.4
Exp/Cntr=0.3,0.1

Type RM Length L Ch R = 1,24065,400,400,400
BEGIN DESCRIPTION:
Morris Branch 37.0
END DESCRIPTION:
XS GIS Cut Line= 3
      2306379.02      7115410.04      2305879.00      7114610.00
      2305428.99      7114460.00
#Sta/Elev= 30
  4048.9  756.66  4172.2  755.64  4245.3  750.75  4296.6  749.83  4318.4  744.50
  4337.8  743.96  4362.7  742.99  4382.1  742.72  4403.3  745.84  4449.3  744.33
  4543.6  745.80  4790.1  744.21  4911.6  745.25  4926.9  744.86  4942.2  739.92
  4956.7  737.80  4978.8  735.13  5002.9  735.97  5016.9  733.11  5018.9  732.61
  5031.1  733.11  5045.0  739.44  5055.6  741.91  5087.2  745.11  5217.1  748.01
  5350.7  752.08  5414.0  758.54  5445.6  766.42  5456.1  772.24  5466.7  774.27
#Mann=7,-1,0
  4048.9    0.05       0  4337.8    0.12       0  4362.7    0.05       0
  4956.7    0.12       0  5016.9    0.07       0  5031.1    0.12       0
  5217.1    0.05       0
#XS Ineff=2,0
    0.00 4750.00  760.45               0
Permanent Ineff=
       F       F
Bank Sta=5016.9,5031.1
Exp/Cntr=0.3,0.1

Type RM Length L Ch R = 1,23665,386,386,386
BEGIN DESCRIPTION:
Mapping XS b9833af2
END DESCRIPTION:
XS GIS Cut Line= 2
      2306397.62      7114829.69      2306059.40      7114107.57
#Sta/Elev= 30
  4557.8  749.96  4661.5  748.52  4678.8  747.01  4684.3  748.04  4690.0  745.33
  4699.6  743.31  4730.0  742.76  4745.2  740.01  4775.7  738.23  4826.8  743.18
  4859.2  742.56  4902.1  741.59  4986.7  741.65  4992.2  740.81  4999.2  738.02
  5009.5  736.40  5014.1  731.37  5016.1  730.87  5028.3  731.37  5054.4  735.28
  5076.5  736.25  5089.0  740.77  5120.6  744.12  5209.0  745.62  5220.0  746.16
  5226.0  747.47  5231.5  746.63  5242.1  746.77  5280.1  748.72  5355.2  752.31
#Mann=7,-1,0
  4557.8    0.05       0  4699.6    0.12       0  4859.2    0.05       0
  4902.1    0.12       0  5014.1    0.07       0  5028.3    0.12       0
  5280.1    0.05       0
Bank Sta=5014.1,5028.3
Exp/Cntr=0.3,0.1

Type RM Length L Ch R = 1,23279,204,204,204
BEGIN DESCRIPTION:
Mapping XS 000cd0bb
END DESCRIPTION:
XS GIS Cut Line= 2
      2306649.87      7114724.09      2306370.17      7113976.61
#Sta/Elev= 30
  4451.2  744.20  4519.6  742.97  4525.0  745.50  4549.9  745.73  4604.5  741.87
  4687.2  737.20  4696.0  734.13  4711.8  735.99  4721.0  740.96  4733.2  741.56
  4850.6  739.69  4946.7  741.12  4968.1  736.20  5012.4  731.67  5014.3  730.37
  5016.3  729.87  5028.6  730.37  5053.5  731.75  5063.0  735.64  5068.3  740.79
  5074.8  742.44  5093.3  740.01  5098.6  743.20  5106.9  741.34  5123.6  748.44
  5128.9  748.32  5153.8  754.79  5187.5  757.89  5209.1  768.43  5249.3  768.41
#Mann=7,-1,0
  4451.2    0.05       0  4604.5    0.12       0  4687.2    0.05       0
  5012.4    0.12       0  5014.3   0.033       0  5028.6    0.12       0
  5187.5    0.05       0
Bank Sta=5014.3,5028.6
Exp/Cntr=0.3,0.1

Type RM Length L Ch R = 1,23075,192,192,192
BEGIN DESCRIPTION:
Mapping XS 98db263d
END DESCRIPTION:
XS GIS Cut Line= 3
      2306938.55      7114868.29      2306864.98      7114691.74
      2306513.74      7113848.86
#Sta/Elev= 30
  4145.2  745.80  4259.1  743.89  4424.8  745.22  4497.3  742.47  4511.7  741.21
  4524.5  736.63  4548.3  732.27  4565.9  736.65  4596.0  737.09  4619.8  741.07
  4702.1  741.38  4707.5  739.51  4938.3  739.90  4955.9  737.21  4967.5  732.74
  4991.8  730.66  4992.0  730.57  4994.0  730.07  5006.3  730.57  5020.9  734.74
  5075.0  734.64  5085.9  736.38  5092.1  740.37  5115.9  745.24  5129.2  751.40
  5139.8  753.57  5150.9  759.83  5166.8  762.78  5192.9  769.36  5249.6  771.27
#Mann=7,-1,0
  4145.2    0.05       0  4424.8    0.12       0  4497.3    0.05       0
  4991.8    0.12       0  4992.0    0.07       0  5006.3    0.12       0
  5166.8    0.05       0
Bank Sta=4992,5006.3
Exp/Cntr=0.3,0.1

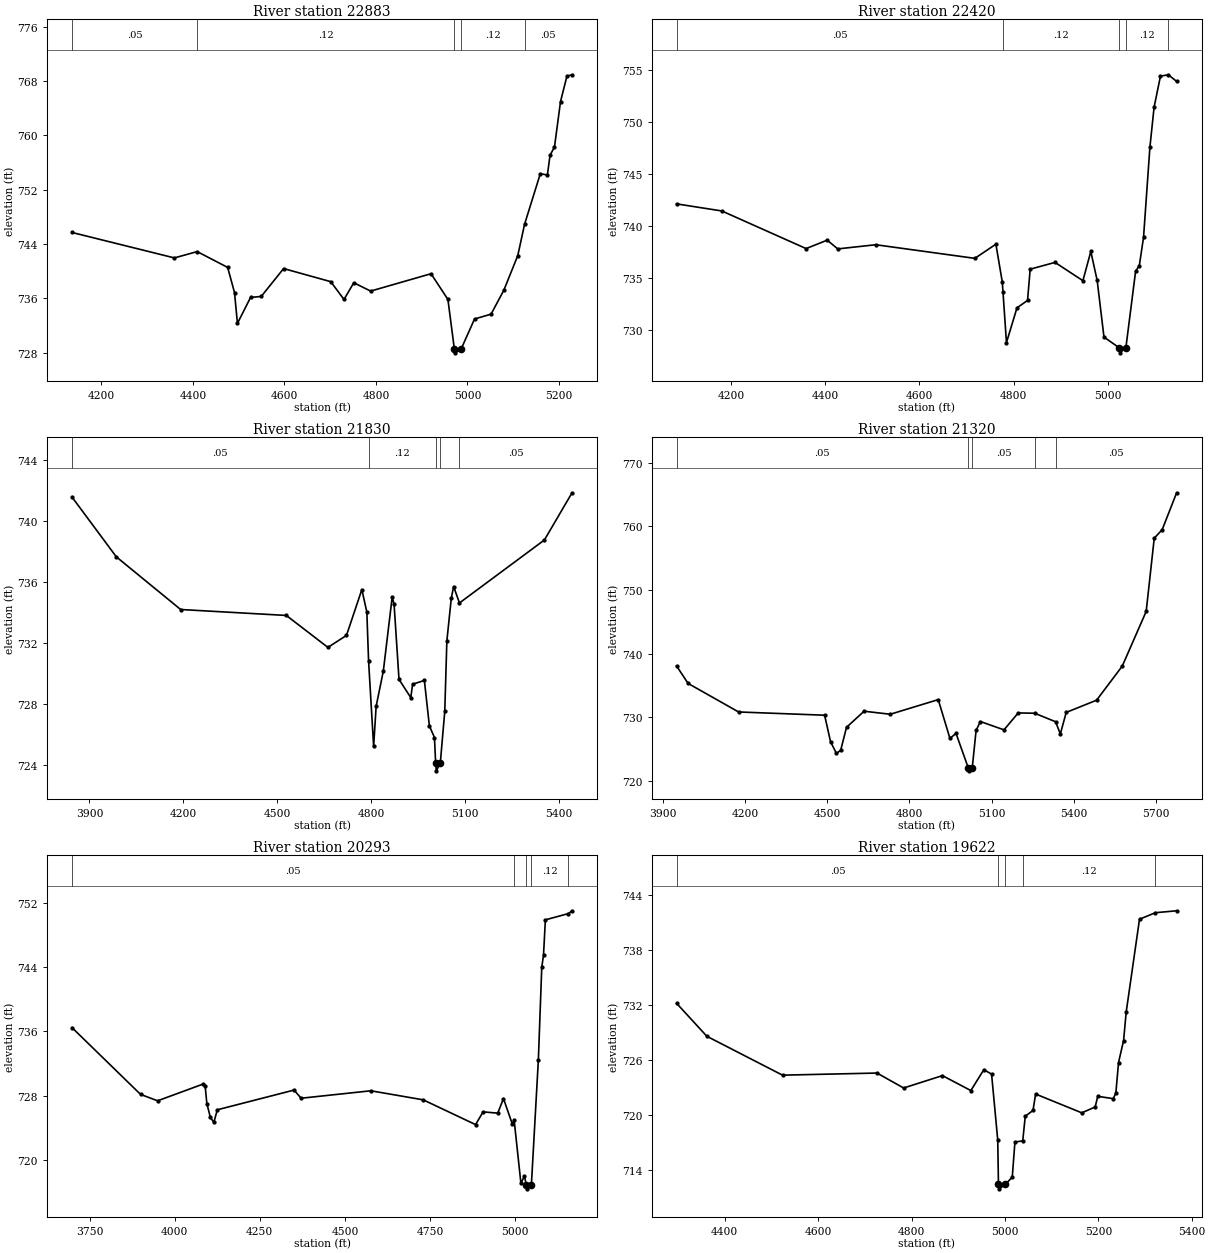
Type RM Length L Ch R = 1,22883,463,463,463
BEGIN DESCRIPTION:
Mapping XS 61771269
END DESCRIPTION:
XS GIS Cut Line= 3
      2307181.10      7114694.13      2307052.83      7114481.61
      2306616.36      7113758.45
#Sta/Elev= 30
  4135.8  745.70  4359.6  741.95  4409.4  742.88  4476.0  740.55  4491.0  736.85
  4497.4  732.30  4526.1  736.13  4549.4  736.27  4598.3  740.38  4701.3  738.45
  4730.3  735.83  4751.7  738.29  4788.5  737.06  4920.5  739.62  4957.4  735.83
  4971.6  728.46  4973.6  727.96  4985.9  728.46  5015.6  732.95  5051.7  733.66
  5079.7  737.20  5110.1  742.30  5124.9  746.90  5159.3  754.36  5174.8  754.17
  5180.6  757.08  5190.3  758.30  5203.5  765.00  5217.5  768.73  5228.7  768.94
#Mann=5,-1,0
  4135.8    0.05       0  4409.4    0.12       0  4971.6    0.07       0
  4985.9    0.12       0  5124.9    0.05       0
Bank Sta=4971.6,4985.9
Exp/Cntr=0.3,0.1

Type RM Length L Ch R = 1,22420,590,590,590
BEGIN DESCRIPTION:
Mapping XS 5fb468cd
END DESCRIPTION:
XS GIS Cut Line= 2
      2307428.24      7114437.99      2306954.08      7113489.28
#Sta/Elev= 30
  4084.9  742.12  4180.8  741.44  4359.7  737.82  4404.4  738.63  4426.8  737.79
  4507.5  738.19  4717.5  736.88  4762.2  738.24  4775.8  734.59  4777.3  733.60
  4784.6  728.78  4806.9  732.12  4829.3  732.83  4834.9  735.84  4887.6  736.49
  4946.7  734.73  4963.5  737.54  4977.0  734.75  4991.4  729.31  5023.2  728.29
  5025.2  727.79  5037.9  728.29  5058.5  735.64  5066.4  736.19  5075.3  738.89
  5088.8  747.56  5097.7  751.42  5111.2  754.41  5128.0  754.54  5145.5  753.90
#Mann=5,-1,0
  4084.9    0.05       0  4777.3    0.12       0  5023.2    0.07       0
  5037.9    0.12       0  5128.0    0.05       0
Bank Sta=5023.2,5037.9
Exp/Cntr=0.3,0.1

Type RM Length L Ch R = 1,21830,510,510,510
BEGIN DESCRIPTION:
Mapping XS 2b013c8b
END DESCRIPTION:
XS GIS Cut Line= 3
      2308034.26      7114266.84      2307469.75      7113260.96
      2307141.61      7112963.13
#Sta/Elev= 30
  3844.4  741.59  3986.0  737.66  4191.4  734.20  4528.8  733.81  4661.5  731.71
  4720.8  732.50  4769.9  735.51  4785.8  734.03  4791.4  730.80  4807.5  725.20
  4815.5  727.84  4838.4  730.15  4866.8  735.03  4872.8  734.54  4888.5  729.61
  4926.1  728.41  4931.9  729.29  4969.5  729.54  4985.5  726.55  5001.7  725.79
  5005.5  724.10  5007.5  723.60  5020.3  724.10  5034.6  727.51  5041.3  732.14
  5055.5  734.95  5062.9  735.71  5081.5  734.63  5352.8  738.77  5441.0  741.87
#Mann=5,-1,0
  3844.4    0.05       0  4791.4    0.12       0  5005.5    0.07       0
  5020.3    0.12       0  5081.5    0.05       0
Bank Sta=5005.5,5020.3
Exp/Cntr=0.3,0.1

Type RM Length L Ch R = 1,21320,1027,1027,1027
BEGIN DESCRIPTION:
Mapping XS 53707c23
END DESCRIPTION:
XS GIS Cut Line= 2
      2308384.04      7113893.99      2307446.80      7112330.02
#Sta/Elev= 30
  3951.1  738.08  3993.3  735.33  4177.3  730.85  4491.0  730.34  4512.4  726.20
  4533.8  724.35  4549.4  724.81  4570.8  728.44  4634.9  730.97  4730.2  730.49
  4905.2  732.79  4947.9  726.69  4970.0  727.49  5014.4  722.10  5016.4  721.60
  5029.3  722.10  5043.2  727.94  5058.8  729.35  5144.9  728.04  5196.8  730.70
  5256.9  730.65  5333.2  729.31  5350.4  727.39  5371.8  730.78  5482.6  732.70
  5576.2  738.06  5663.4  746.65  5692.8  758.16  5721.7  759.49  5774.4  765.29
#Mann=5,-1,0
  3951.1    0.05       0  5014.4   0.033       0  5029.3    0.05       0
  5256.9    0.12       0  5333.2    0.05       0
Bank Sta=5014.4,5029.3
Exp/Cntr=0.3,0.1

Type RM Length L Ch R = 1,20293,671,671,671
BEGIN DESCRIPTION:
Mapping XS 51259c8d
END DESCRIPTION:
XS GIS Cut Line= 2
      2308470.57      7113626.46      2308145.37      7112193.50
#Sta/Elev= 30
  3698.1  736.47  3899.6  728.14  3949.7  727.34  4084.1  729.44  4089.3  729.24
  4094.4  726.99  4104.6  725.30  4114.9  724.64  4125.2  726.22  4350.7  728.68
  4371.3  727.66  4576.3  728.59  4730.2  727.46  4884.0  724.37  4906.1  725.96
  4949.2  725.80  4966.0  727.62  4992.3  724.40  4997.2  724.98  5017.3  717.03
  5027.5  717.96  5033.1  716.86  5035.1  716.36  5048.0  716.86  5068.5  732.44
  5078.5  744.01  5083.6  745.48  5089.1  749.91  5156.8  750.69  5167.5  751.04
#Mann=5,-1,0
  3698.1    0.05       0  4997.2    0.12       0  5033.1    0.07       0
  5048.0    0.12       0  5156.8    0.05       0
Bank Sta=5033.1,5048
Exp/Cntr=0.3,0.1

Type RM Length L Ch R = 1,19622,611,611,611
BEGIN DESCRIPTION:
Mapping XS 4f5512ef
END DESCRIPTION:
XS GIS Cut Line= 2
      2309084.18      7113001.79      2308594.40      7112049.34
#Sta/Elev= 30
  4296.7  732.18  4361.6  728.58  4523.6  724.34  4726.0  724.57  4783.0  722.94
  4866.1  724.29  4927.0  722.66  4954.8  724.94  4971.4  724.45  4984.6  717.25
  4986.1  712.44  4988.1  711.94  5001.1  712.44  5015.7  713.22  5021.4  717.05
  5038.1  717.17  5043.5  719.86  5060.1  720.49  5065.7  722.28  5164.6  720.23
  5193.2  720.87  5198.8  722.03  5231.9  721.78  5237.5  722.37  5243.3  725.72
  5254.1  728.12  5259.7  731.23  5288.2  741.35  5322.3  742.06  5367.7  742.27
#Mann=5,-1,0
  4296.7    0.05       0  4986.1   0.033       0  5001.1    0.05       0
  5038.1    0.12       0  5322.3    0.05       0
Bank Sta=4986.1,5001.1
Exp/Cntr=0.3,0.1