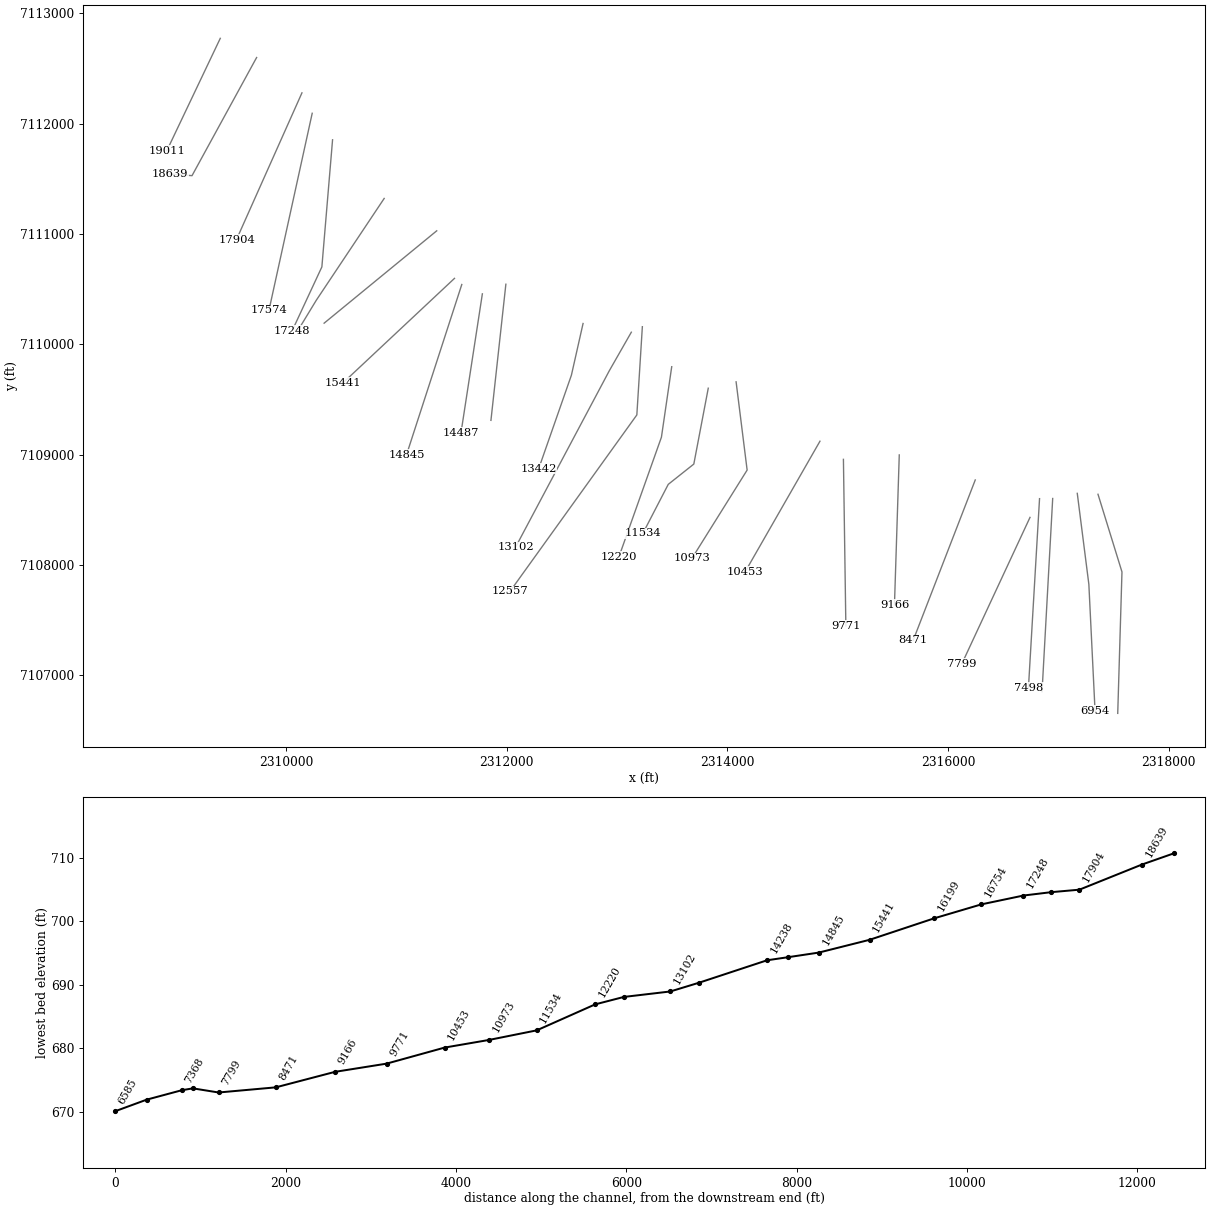
HEC-RAS study Morris Branch.prj: Morris Branch Base Level Engineering

--- Morris Branch.g01 (geometry) --- (continued)

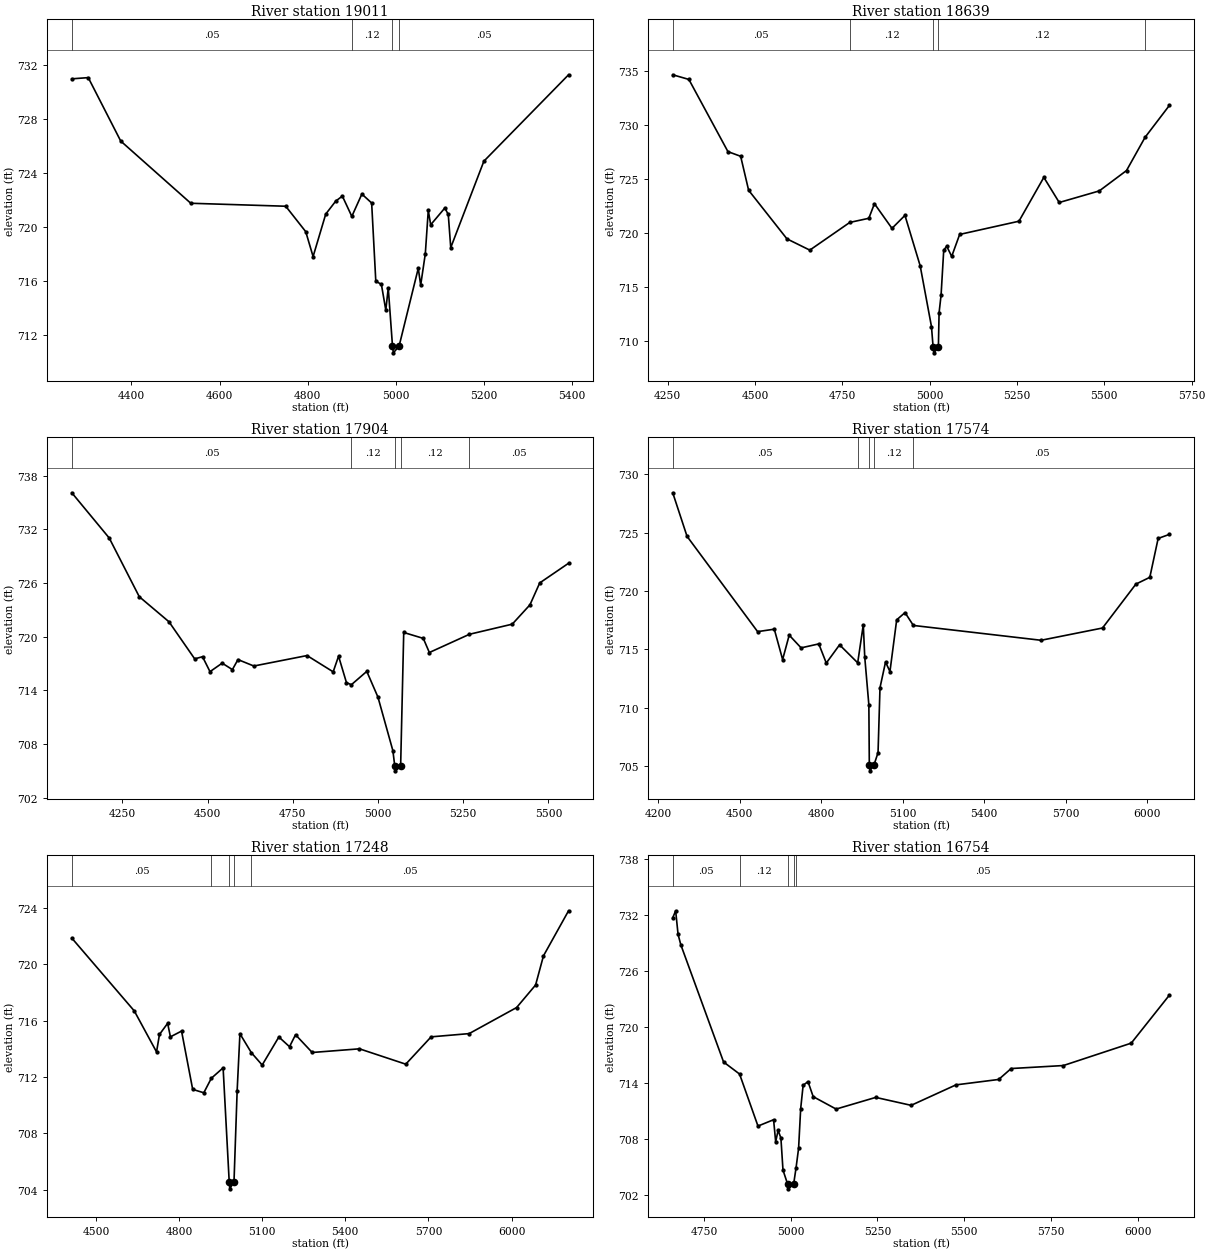
Type RM Length L Ch R = 1,19011,372,372,372
BEGIN DESCRIPTION:
Mapping XS 16bad518
END DESCRIPTION:
XS GIS Cut Line= 2
      2309402.02      7112774.51      2308917.73      7111756.43
#Sta/Elev= 30
  4264.7  730.96  4302.0  731.05  4375.7  726.36  4534.7  721.76  4750.2  721.54
  4795.6  719.66  4812.3  717.82  4841.0  720.96  4863.7  721.92  4878.7  722.29
  4900.2  720.79  4923.0  722.44  4945.2  721.78  4954.6  716.00  4967.3  715.76
  4977.3  713.86  4982.9  715.50  4992.5  711.20  4994.5  710.70  5007.5  711.20
  5051.0  716.95  5056.5  715.71  5067.0  718.03  5073.7  721.23  5079.2  720.17
  5111.3  721.41  5119.1  720.93  5124.7  718.48  5199.9  724.87  5392.1  731.26
#Mann=4,-1,0
  4264.7    0.05       0  4900.2    0.12       0  4992.5   0.033       0
  5007.5    0.05       0
Bank Sta=4992.5,5007.5
Exp/Cntr=0.3,0.1

Type RM Length L Ch R = 1,18639,735,735,735
BEGIN DESCRIPTION:
Mapping XS 073ddbb1
END DESCRIPTION:
XS GIS Cut Line= 3
      2309731.51      7112600.55      2309145.84      7111529.43
      2308945.50      7111544.62
#Sta/Elev= 30
  4264.8  734.64  4311.0  734.21  4422.8  727.54  4459.2  727.11  4482.0  723.97
  4591.7  719.48  4657.1  718.44  4771.6  721.00  4826.0  721.38  4842.1  722.73
  4892.3  720.45  4929.4  721.65  4973.0  716.99  5005.3  711.38  5010.1  709.45
  5012.1  708.95  5025.1  709.45  5027.1  712.65  5032.8  714.28  5040.4  718.44
  5048.9  718.80  5063.2  717.86  5086.0  719.89  5255.7  721.11  5326.9  725.16
  5371.0  722.84  5485.6  723.91  5563.5  725.79  5616.6  728.86  5686.5  731.82
#Mann=5,-1,0
  4264.8    0.05       0  4771.6    0.12       0  5010.1    0.07       0
  5025.1    0.12       0  5616.6    0.05       0
Bank Sta=5010.1,5025.1
Exp/Cntr=0.3,0.1

Type RM Length L Ch R = 1,17904,330,330,330
BEGIN DESCRIPTION:
Mapping XS 5c86fe61
END DESCRIPTION:
XS GIS Cut Line= 2
      2310142.62      7112280.26      2309548.80      7110949.32
#Sta/Elev= 30
  4101.8  736.08  4211.6  731.02  4299.7  724.46  4386.8  721.66  4462.3  717.51
  4485.3  717.75  4507.2  716.08  4542.9  717.03  4572.9  716.31  4589.3  717.43
  4635.8  716.71  4791.9  717.88  4868.6  716.06  4884.4  717.81  4907.6  714.85
  4922.0  714.62  4967.2  716.11  5000.0  713.23  5043.8  707.24  5049.4  705.49
  5051.4  704.99  5066.5  705.49  5075.6  720.46  5133.0  719.80  5150.8  718.22
  5268.5  720.26  5394.0  721.39  5445.9  723.55  5474.6  726.00  5559.2  728.20
#Mann=5,-1,0
  4101.8    0.05       0  4922.0    0.12       0  5049.4    0.07       0
  5066.5    0.12       0  5268.5    0.05       0
Bank Sta=5049.4,5066.5
Exp/Cntr=0.3,0.1

Type RM Length L Ch R = 1,17574,326,326,326
BEGIN DESCRIPTION:
Mapping XS 8c971f08
END DESCRIPTION:
XS GIS Cut Line= 2
      2310235.59      7112095.12      2309843.60      7110309.24
#Sta/Elev= 30
  4254.0  728.41  4306.7  724.68  4566.4  716.52  4627.8  716.73  4658.5  714.13
  4682.7  716.22  4726.5  715.13  4791.6  715.47  4819.2  713.83  4868.1  715.39
  4934.8  713.85  4955.4  717.11  4960.8  714.33  4975.9  710.25  4977.6  705.10
  4979.6  704.60  4994.7  705.10  5009.7  706.16  5016.9  711.72  5037.3  713.92
  5053.5  713.10  5078.3  717.53  5109.0  718.15  5139.7  717.05  5609.8  715.78
  5835.9  716.83  5958.8  720.59  6010.0  721.17  6040.7  724.50  6082.4  724.85
#Mann=5,-1,0
  4254.0    0.05       0  4934.8    0.12       0  4977.6    0.07       0
  4994.7    0.12       0  5139.7    0.05       0
Bank Sta=4977.6,4994.7
Exp/Cntr=0.3,0.1

Type RM Length L Ch R = 1,17248,494,494,494
BEGIN DESCRIPTION:
Mapping XS 248e2188
END DESCRIPTION:
XS GIS Cut Line= 3
      2310420.16      7111854.68      2310323.20      7110702.15
      2310054.73      7110125.15
#Sta/Elev= 30
  4412.9  721.87  4638.4  716.70  4718.7  713.79  4729.3  715.03  4758.8  715.82
  4768.8  714.86  4809.0  715.27  4849.2  711.13  4889.3  710.89  4916.5  711.92
  4959.0  712.66  4981.0  704.57  4983.0  704.07  4998.3  704.57  5009.7  711.05
  5019.7  715.08  5060.8  713.74  5100.0  712.86  5160.2  714.85  5198.7  714.16
  5220.4  715.01  5280.6  713.75  5451.2  714.01  5618.3  712.92  5709.8  714.86
  5847.1  715.09  6018.3  716.94  6086.9  718.54  6115.3  720.61  6205.9  723.81
#Mann=5,-1,0
  4412.9    0.05       0  4916.5    0.12       0  4981.0    0.07       0
  4998.3    0.12       0  5060.8    0.05       0
Bank Sta=4981,4998.3
Exp/Cntr=0.3,0.1

Type RM Length L Ch R = 1,16754,555,555,555
BEGIN DESCRIPTION:
Mapping XS fc340b97
END DESCRIPTION:
XS GIS Cut Line= 3
      2310888.12      7111322.82      2310272.47      7110399.65
      2310104.89      7110123.90
#Sta/Elev= 30
  4659.6  731.70  4668.0  732.45  4675.0  729.92  4683.0  728.80  4806.2  716.26
  4852.3  714.97  4905.4  709.40  4950.4  710.08  4956.4  707.73  4963.5  708.94
  4971.5  708.12  4977.5  704.69  4990.9  703.18  4992.9  702.68  5008.2  703.18
  5015.3  704.96  5022.5  707.02  5028.5  711.26  5035.6  713.77  5049.6  714.16
  5064.6  712.55  5130.7  711.22  5244.9  712.47  5347.0  711.62  5476.2  713.81
  5599.4  714.39  5635.4  715.56  5785.9  715.88  5981.7  718.28  6091.9  723.43
#Mann=5,-1,0
  4659.6    0.05       0  4852.3    0.12       0  4990.9    0.07       0
  5008.2    0.12       0  5015.3    0.05       0
Bank Sta=4990.9,5008.2
Exp/Cntr=0.3,0.1

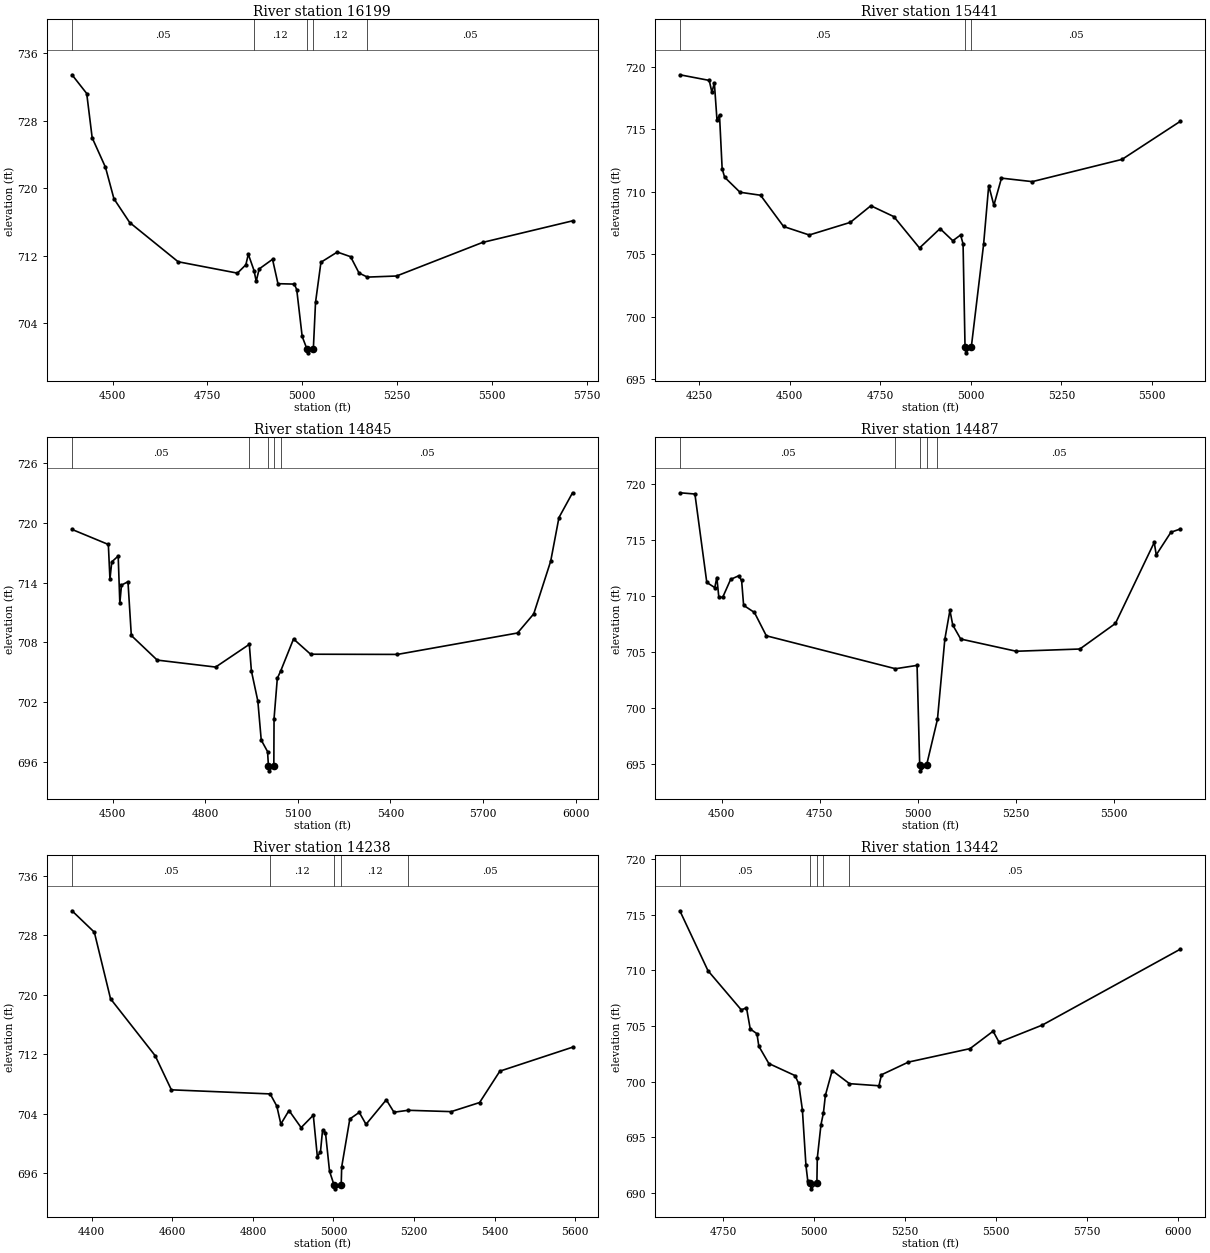
Type RM Length L Ch R = 1,16199,758,758,758
BEGIN DESCRIPTION:
Mapping XS 98d48f69
END DESCRIPTION:
XS GIS Cut Line= 2
      2311364.50      7111029.22      2310343.57      7110191.88
#Sta/Elev= 30
  4392.6  733.45  4431.4  731.23  4445.8  725.98  4480.9  722.48  4503.2  718.75
  4544.8  715.93  4672.6  711.28  4829.0  709.93  4851.2  710.92  4857.7  712.17
  4872.8  710.24  4878.5  708.97  4886.4  710.43  4921.6  711.57  4935.9  708.68
  4979.0  708.63  4985.4  707.98  4999.8  702.42  5012.0  700.98  5014.0  700.48
  5029.3  700.98  5035.0  706.46  5049.3  711.22  5092.4  712.43  5127.5  711.88
  5149.8  709.94  5171.9  709.46  5248.8  709.59  5475.6  713.57  5713.0  716.13
#Mann=5,-1,0
  4392.6    0.05       0  4872.8    0.12       0  5012.0    0.07       0
  5029.3    0.12       0  5171.9    0.05       0
Bank Sta=5012,5029.3
Exp/Cntr=0.3,0.1

Type RM Length L Ch R = 1,15441,596,596,596
BEGIN DESCRIPTION:
Mapping XS 7cd4029d
END DESCRIPTION:
XS GIS Cut Line= 2
      2311525.66      7110598.08      2310517.81      7109653.64
#Sta/Elev= 30
  4197.0  719.35  4278.1  718.90  4285.4  717.95  4292.2  718.70  4299.5  715.71
  4306.4  716.13  4313.7  711.83  4320.6  711.15  4363.0  709.95  4419.7  709.71
  4483.2  707.21  4554.0  706.53  4667.4  707.54  4724.0  708.87  4787.5  708.00
  4858.3  705.49  4915.0  707.04  4950.2  706.07  4971.7  706.53  4978.5  705.82
  4983.9  697.60  4985.9  697.10  5001.4  697.60  5035.2  705.79  5049.3  710.49
  5063.5  708.91  5084.5  711.08  5169.5  710.80  5417.2  712.58  5578.2  715.63
#Mann=3,-1,0
  4197.0    0.05       0  4983.9   0.033       0  5001.4    0.05       0
Bank Sta=4983.9,5001.4
Exp/Cntr=0.3,0.1

Type RM Length L Ch R = 1,14845,358,358,358
BEGIN DESCRIPTION:
Mapping XS 19fd7996
END DESCRIPTION:
XS GIS Cut Line= 2
      2311591.78      7110542.48      2311091.28      7109000.47
#Sta/Elev= 30
  4368.8  719.33  4486.5  717.82  4491.7  714.34  4497.6  716.07  4518.4  716.66
  4523.7  711.92  4529.1  713.74  4550.1  714.08  4560.9  708.68  4644.8  706.21
  4834.0  705.51  4943.1  707.79  4949.8  705.13  4970.7  702.10  4981.7  698.18
  5002.2  697.02  5005.0  695.59  5007.0  695.09  5022.5  695.59  5023.2  700.33
  5033.8  704.38  5045.3  705.16  5086.3  708.33  5141.6  706.80  5422.8  706.78
  5811.8  708.93  5864.3  710.85  5919.3  716.15  5946.0  720.52  5990.0  723.01
#Mann=5,-1,0
  4368.8    0.05       0  4943.1    0.12       0  5005.0    0.07       0
  5022.5    0.12       0  5045.3    0.05       0
Bank Sta=5005,5022.5
Exp/Cntr=0.3,0.1

Type RM Length L Ch R = 1,14487,249,249,249
BEGIN DESCRIPTION:
Mapping XS 9d7a45a9
END DESCRIPTION:
XS GIS Cut Line= 2
      2311778.36      7110457.95      2311584.31      7109196.18
#Sta/Elev= 30
  4393.0  719.18  4431.4  719.07  4461.7  711.18  4482.0  710.72  4487.3  711.62
  4492.3  709.89  4502.2  709.85  4522.5  711.45  4542.7  711.77  4550.5  711.36
  4555.6  709.14  4583.2  708.50  4613.5  706.42  4942.9  703.48  4998.0  703.78
  5004.7  694.87  5006.7  694.37  5022.2  694.87  5050.0  698.97  5068.8  706.11
  5081.8  708.69  5089.0  707.38  5109.3  706.13  5250.9  705.04  5413.2  705.24
  5503.9  707.52  5602.9  714.75  5608.0  713.64  5645.5  715.66  5669.6  715.95
#Mann=5,-1,0
  4393.0    0.05       0  4942.9    0.12       0  5004.7    0.07       0
  5022.2    0.12       0  5050.0    0.05       0
Bank Sta=5004.7,5022.2
Exp/Cntr=0.3,0.1

Type RM Length L Ch R = 1,14238,796,796,796
BEGIN DESCRIPTION:
Mapping XS 20666229
END DESCRIPTION:
XS GIS Cut Line= 2
      2311991.49      7110545.06      2311856.14      7109310.76
#Sta/Elev= 30
  4351.3  731.26  4406.7  728.38  4446.9  719.43  4557.6  711.78  4597.8  707.19
  4842.9  706.64  4859.4  705.00  4869.4  702.59  4889.6  704.41  4919.7  702.11
  4949.9  703.78  4960.0  698.18  4967.7  698.87  4972.8  701.73  4980.1  701.44
  4990.2  696.24  5001.5  694.38  5003.5  693.88  5019.1  694.38  5020.3  696.82
  5040.5  703.27  5063.9  704.16  5080.7  702.55  5131.0  705.85  5150.0  704.18
  5185.0  704.44  5292.0  704.26  5362.4  705.48  5412.7  709.70  5593.0  712.92
#Mann=5,-1,0
  4351.3    0.05       0  4842.9    0.12       0  5001.5    0.07       0
  5019.1    0.12       0  5185.0    0.05       0
Bank Sta=5001.5,5019.1
Exp/Cntr=0.3,0.1

Type RM Length L Ch R = 1,13442,340,340,340
BEGIN DESCRIPTION:
Mapping XS 7140799e
END DESCRIPTION:
XS GIS Cut Line= 3
      2312691.37      7110188.93      2312585.71      7109720.29
      2312289.46      7108873.52
#Sta/Elev= 30
  4630.0  715.37  4707.4  709.98  4799.0  706.46  4813.4  706.64  4823.7  704.74
  4842.2  704.31  4847.3  703.19  4874.9  701.63  4946.7  700.55  4956.9  699.85
  4967.2  697.47  4977.0  692.47  4982.2  691.03  4988.8  690.86  4990.8  690.36
  5007.1  690.86  5008.2  693.11  5018.4  696.14  5025.1  697.19  5030.5  698.77
  5049.2  701.00  5096.8  699.82  5177.9  699.63  5184.9  700.62  5259.0  701.76
  5428.5  702.97  5492.1  704.54  5508.6  703.54  5627.5  705.09  6007.5  711.92
#Mann=5,-1,0
  4630.0    0.05       0  4988.8   0.033       0  5007.1    0.05       0
  5025.1    0.12       0  5096.8    0.05       0
Bank Sta=4988.8,5007.1
Exp/Cntr=0.3,0.1

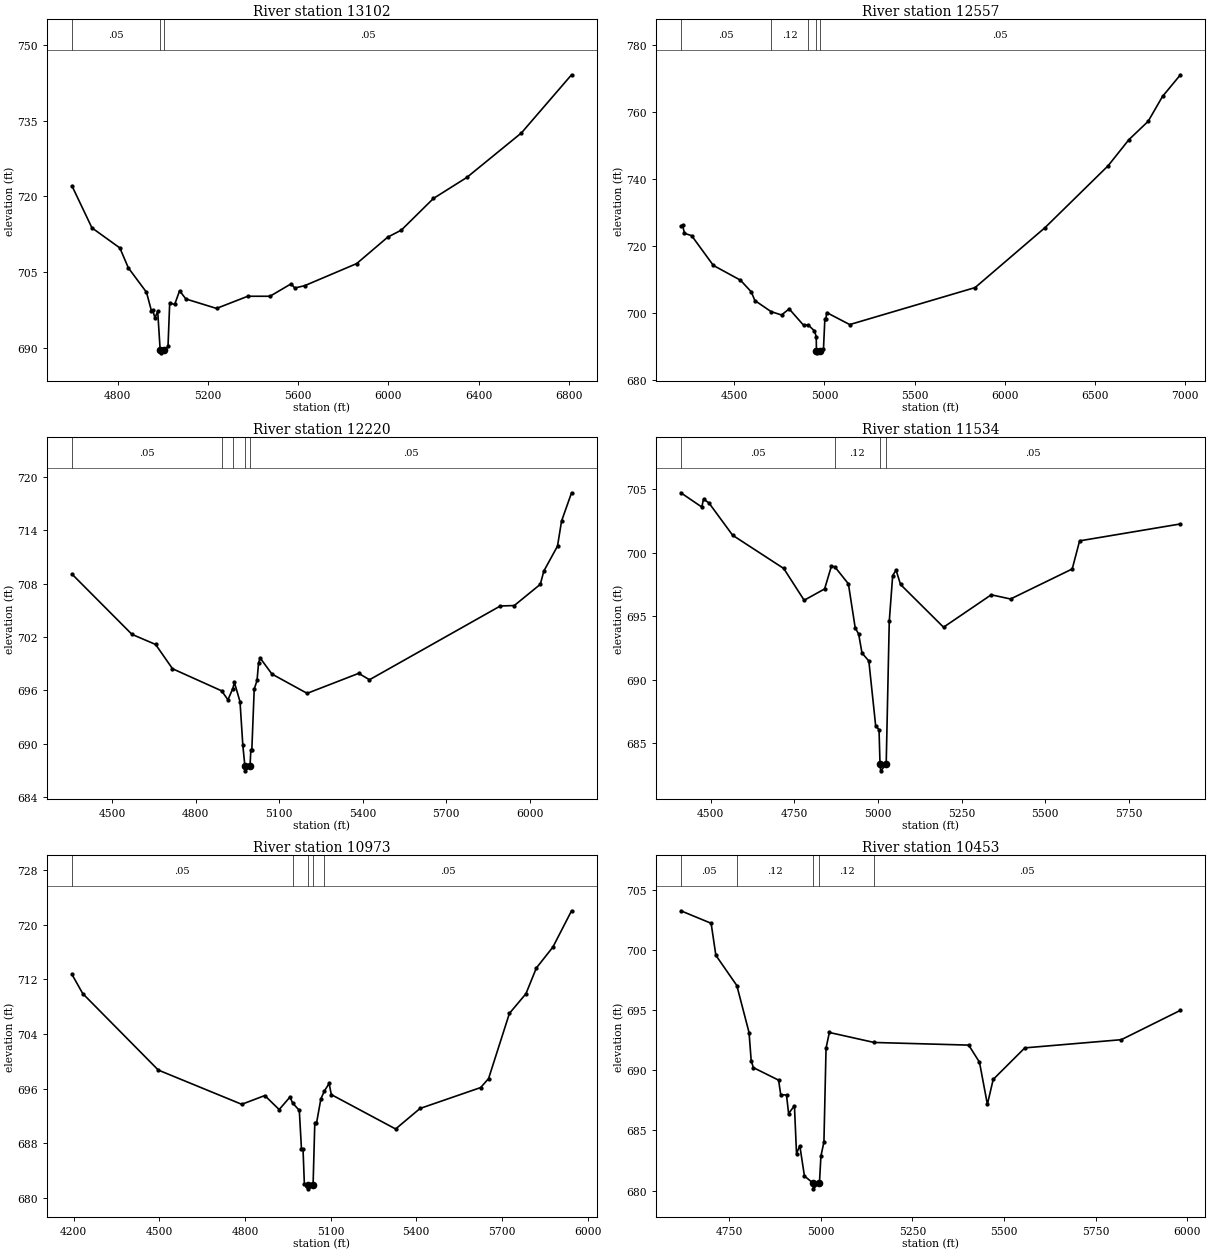
Type RM Length L Ch R = 1,13102,545,545,545
BEGIN DESCRIPTION:
Morris Branch 15.0
END DESCRIPTION:
XS GIS Cut Line= 3
      2313129.01      7110110.02      2312929.00      7109760.00
      2312079.00      7108160.00
#Sta/Elev= 30
  4597.0  722.05  4685.6  713.73  4809.4  709.75  4846.8  705.82  4927.4  700.97
  4949.0  697.35  4954.8  697.44  4964.9  695.90  4977.1  697.21  4988.1  689.47
  4990.1  688.97  5006.4  689.47  5022.8  690.26  5030.3  698.86  5052.3  698.55
  5074.2  701.27  5102.1  699.64  5237.9  697.77  5376.3  700.18  5474.9  700.18
  5568.5  702.64  5584.8  701.81  5628.8  702.28  5859.2  706.65  5996.8  711.89
  6057.1  713.28  6199.6  719.56  6347.6  723.72  6589.6  732.54  6811.9  744.06
#Mann=3,-1,0
  4597.0    0.05       0  4988.1   0.033       0  5006.4    0.05       0
Bank Sta=4988.1,5006.4
Exp/Cntr=0.3,0.1

Type RM Length L Ch R = 1,12557,337,337,337
BEGIN DESCRIPTION:
Morris Branch 14.0
END DESCRIPTION:
XS GIS Cut Line= 3
      2313229.00      7110159.97      2313179.00      7109360.00
      2312029.02      7107760.03
#Sta/Elev= 30
  4202.9  726.05  4212.9  726.23  4222.9  723.84  4263.0  723.14  4383.2  714.25
  4533.5  709.84  4593.6  706.35  4613.7  703.75  4703.4  700.44  4761.5  699.43
  4804.0  701.25  4884.2  696.34  4909.2  696.47  4944.3  694.67  4954.3  692.91
  4955.2  688.61  4957.2  688.11  4973.5  688.61  4994.4  689.34  5001.9  698.12
  5007.5  698.12  5011.8  700.16  5139.9  696.56  5835.6  707.62  6223.5  725.54
  6573.4  744.03  6688.8  751.84  6795.6  757.32  6875.4  764.77  6974.8  771.24
#Mann=5,-1,0
  4202.9    0.05       0  4703.4    0.12       0  4909.2    0.05       0
  4955.2   0.033       0  4973.5    0.05       0
Bank Sta=4955.2,4973.5
Exp/Cntr=0.3,0.1

Type RM Length L Ch R = 1,12220,686,686,686
BEGIN DESCRIPTION:
Mapping XS 27e77fc8
END DESCRIPTION:
XS GIS Cut Line= 3
      2313495.26      7109797.21      2313401.93      7109158.07
      2313017.54      7108076.14
#Sta/Elev= 30
  4355.7  709.08  4571.1  702.30  4656.1  701.16  4716.7  698.43  4893.3  695.94
  4915.9  694.93  4933.3  696.20  4939.0  696.89  4959.2  694.72  4969.3  689.81
  4976.8  687.44  4978.8  686.94  4995.1  687.44  4998.1  689.29  5001.6  689.29
  5010.2  696.15  5020.4  697.11  5025.7  699.07  5031.4  699.64  5073.9  697.83
  5200.2  695.66  5385.3  697.91  5424.1  697.19  5893.9  705.49  5944.1  705.54
  6037.6  707.93  6050.2  709.42  6099.3  712.23  6113.9  715.05  6149.8  718.23
#Mann=5,-1,0
  4355.7    0.05       0  4893.3    0.12       0  4933.3    0.05       0
  4976.8   0.033       0  4995.1    0.05       0
Bank Sta=4976.8,4995.1
Exp/Cntr=0.3,0.1

Type RM Length L Ch R = 1,11534,561,561,561
BEGIN DESCRIPTION:
Mapping XS a164e123
END DESCRIPTION:
XS GIS Cut Line= 4
      2313826.55      7109602.28      2313695.58      7108914.45
      2313463.78      7108730.44      2313234.76      7108288.39
#Sta/Elev= 30
  4410.4  704.71  4473.1  703.59  4478.2  704.21  4494.2  703.92  4565.4  701.37
  4718.1  698.76  4779.2  696.26  4840.3  697.15  4860.6  698.93  4870.9  698.89
  4911.5  697.55  4931.9  694.08  4942.1  693.61  4952.2  692.11  4972.6  691.49
  4993.0  686.40  5003.1  686.08  5006.1  683.35  5008.1  682.85  5024.5  683.35
  5033.7  694.60  5043.9  698.20  5054.0  698.63  5067.4  697.50  5196.0  694.14
  5338.6  696.69  5396.4  696.36  5580.8  698.72  5602.9  700.93  5904.4  702.26
#Mann=4,-1,0
  4410.4    0.05       0  4870.9    0.12       0  5006.1    0.07       0
  5024.5    0.05       0
Bank Sta=5006.1,5024.5
Exp/Cntr=0.3,0.1

Type RM Length L Ch R = 1,10973,520,520,520
BEGIN DESCRIPTION:
Morris Branch 11.0
END DESCRIPTION:
XS GIS Cut Line= 3
      2314078.99      7109660.05      2314179.00      7108860.00
      2313678.99      7108059.98
#Sta/Elev= 30
  4194.2  712.72  4232.0  709.91  4496.6  698.72  4788.8  693.71  4869.5  694.99
  4919.9  692.94  4957.6  694.77  4967.3  693.88  4990.4  692.82  4998.0  687.18
  5003.4  687.18  5008.1  682.07  5020.1  681.84  5022.1  681.34  5038.6  681.84
  5044.7  691.04  5050.6  690.94  5065.9  694.50  5078.1  695.65  5094.8  696.76
  5102.5  695.13  5327.7  690.10  5413.2  693.10  5625.5  696.16  5653.2  697.47
  5726.3  707.02  5784.1  709.89  5820.6  713.66  5878.4  716.71  5943.9  722.03
#Mann=5,-1,0
  4194.2    0.05       0  4967.3    0.12       0  5020.1    0.07       0
  5038.6    0.12       0  5078.1    0.05       0
Bank Sta=5020.1,5038.6
Exp/Cntr=0.3,0.1

Type RM Length L Ch R = 1,10453,682,682,682
BEGIN DESCRIPTION:
MAPPING XS 96962
END DESCRIPTION:
XS GIS Cut Line= 2
      2314839.34      7109121.74      2314161.69      7107938.67
#Sta/Elev= 30
  4618.2  703.24  4700.9  702.20  4713.8  699.54  4771.0  697.03  4804.4  693.12
  4810.2  690.79  4816.1  690.21  4885.0  689.17  4890.8  687.97  4906.6  687.93
  4912.3  686.39  4928.2  687.05  4933.9  683.07  4942.9  683.72  4955.5  681.21
  4977.9  680.64  4979.9  680.14  4996.5  680.64  5000.5  682.86  5008.7  684.03
  5014.5  691.83  5023.5  693.13  5145.8  692.30  5403.8  692.08  5433.2  690.66
  5454.8  687.16  5470.6  689.23  5556.9  691.85  5820.2  692.53  5981.6  694.97
#Mann=5,-1,0
  4618.2    0.05       0  4771.0    0.12       0  4977.9    0.07       0
  4996.5    0.12       0  5145.8    0.05       0
Bank Sta=4977.9,4996.5
Exp/Cntr=0.3,0.1

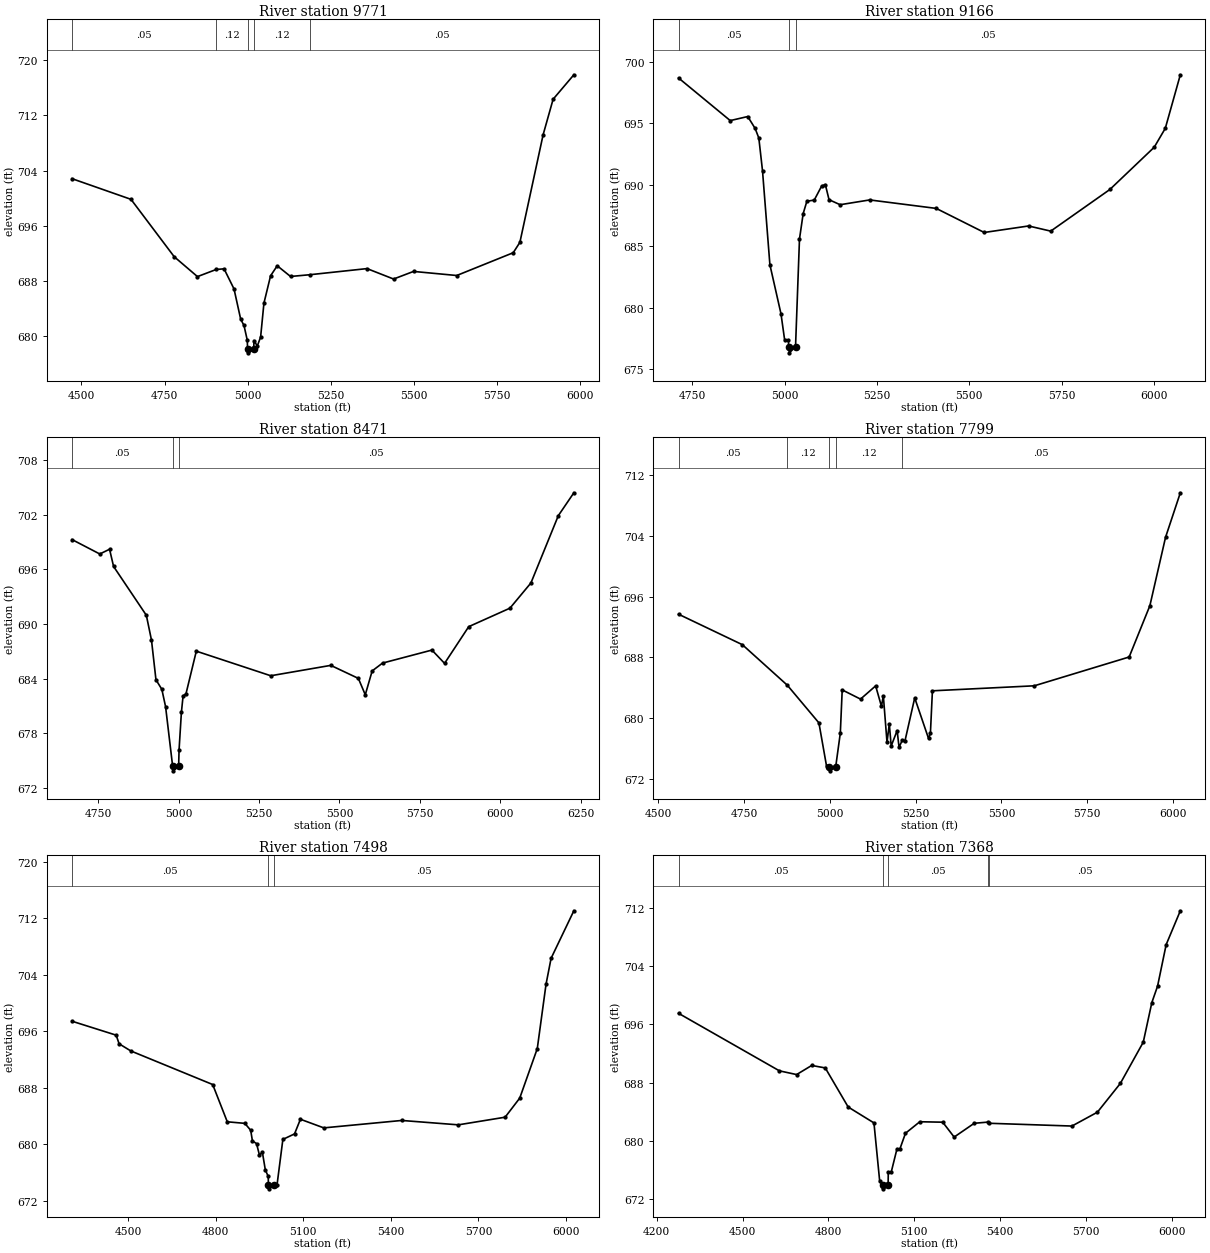
Type RM Length L Ch R = 1,9771,605,605,605
BEGIN DESCRIPTION:
Mapping XS b90dab14
END DESCRIPTION:
XS GIS Cut Line= 2
      2315052.06      7108957.26      2315074.16      7107447.62
#Sta/Elev= 30
  4471.7  702.83  4649.0  699.84  4779.0  691.53  4849.0  688.65  4905.2  689.68
  4929.0  689.78  4959.0  686.86  4979.0  682.49  4989.0  681.57  4999.0  679.41
  4999.7  678.11  5001.7  677.61  5018.3  678.11  5019.0  679.39  5029.0  678.60
  5039.0  679.89  5049.0  684.81  5069.0  688.77  5089.0  690.22  5129.0  688.67
  5186.4  688.92  5359.1  689.81  5439.1  688.30  5499.1  689.40  5629.1  688.81
  5799.1  692.11  5819.1  693.61  5889.1  709.21  5919.1  714.34  5981.5  717.88
#Mann=5,-1,0
  4471.7    0.05       0  4905.2    0.12       0  4999.7    0.07       0
  5018.3    0.12       0  5186.4    0.05       0
Bank Sta=4999.7,5018.3
Exp/Cntr=0.3,0.1

Type RM Length L Ch R = 1,9166,695,695,695
BEGIN DESCRIPTION:
Mapping XS f97d95a8
END DESCRIPTION:
XS GIS Cut Line= 2
      2315558.41      7108997.30      2315514.82      7107639.30
#Sta/Elev= 30
  4712.5  698.70  4852.5  695.23  4899.9  695.56  4919.9  694.59  4929.9  693.81
  4939.9  691.14  4959.9  683.49  4989.9  679.50  4999.9  677.35  5010.0  677.35
  5010.7  676.82  5012.7  676.32  5029.3  676.82  5040.0  685.59  5050.0  687.66
  5060.0  688.66  5080.0  688.76  5100.0  689.90  5110.0  690.02  5120.0  688.79
  5150.0  688.38  5230.1  688.77  5410.2  688.08  5540.2  686.12  5660.3  686.65
  5720.3  686.23  5880.4  689.62  6000.5  693.06  6030.5  694.60  6071.2  698.96
#Mann=3,-1,0
  4712.5    0.05       0  5010.7   0.033       0  5029.3    0.05       0
Bank Sta=5010.7,5029.3
Exp/Cntr=0.3,0.1

Type RM Length L Ch R = 1,8471,672,672,672
BEGIN DESCRIPTION:
Mapping XS 0016a320
END DESCRIPTION:
XS GIS Cut Line= 2
      2316247.37      7108770.38      2315684.03      7107315.00
#Sta/Elev= 30
  4668.6  699.27  4754.8  697.69  4785.2  698.21  4797.7  696.32  4899.6  690.96
  4915.6  688.23  4929.5  683.88  4947.8  682.83  4959.4  680.93  4981.4  674.38
  4983.4  673.88  5000.0  674.38  5001.4  676.20  5008.6  680.30  5013.9  682.11
  5022.9  682.34  5055.0  687.02  5286.5  684.32  5473.2  685.46  5559.0  684.03
  5580.5  682.23  5601.9  684.85  5634.1  685.71  5787.8  687.14  5827.1  685.68
  5902.2  689.71  6030.4  691.74  6095.7  694.51  6180.9  701.90  6229.2  704.41
#Mann=3,-1,0
  4668.6    0.05       0  4981.4   0.035       0  5000.0    0.05       0
Bank Sta=4981.4,5000
Exp/Cntr=0.3,0.1

Type RM Length L Ch R = 1,7799,301,301,301
BEGIN DESCRIPTION:
Mapping XS c721766e
END DESCRIPTION:
XS GIS Cut Line= 2
      2316743.81      7108431.06      2316126.40      7107104.72
#Sta/Elev= 30
  4558.7  693.68  4744.8  689.67  4875.8  684.34  4968.0  679.38  4990.2  673.70
  4998.2  673.57  5000.2  673.07  5016.8  673.57  5030.4  678.04  5035.9  683.72
  5089.3  682.51  5133.4  684.25  5150.3  681.56  5155.8  682.95  5166.5  676.84
  5173.2  679.24  5178.7  676.34  5196.1  678.37  5201.6  676.17  5211.2  677.11
  5219.0  677.03  5247.3  682.67  5287.6  677.33  5293.1  678.05  5298.9  683.60
  5596.0  684.26  5872.5  688.05  5932.9  694.80  5978.6  703.80  6021.7  709.66
#Mann=5,-1,0
  4558.7    0.05       0  4875.8    0.12       0  4998.2    0.07       0
  5016.8    0.12       0  5211.2    0.05       0
Bank Sta=4998.2,5016.8
Exp/Cntr=0.3,0.1

Type RM Length L Ch R = 1,7498,130,130,130
BEGIN DESCRIPTION:
Mapping XS b5d6c2db
END DESCRIPTION:
XS GIS Cut Line= 2
      2316830.23      7108600.82      2316729.56      7106884.88
#Sta/Elev= 30
  4308.1  697.42  4459.2  695.45  4469.2  694.23  4509.3  693.22  4789.8  688.47
  4839.8  683.20  4899.9  682.98  4920.0  682.00  4925.9  680.50  4940.0  680.12
  4950.0  678.49  4960.0  678.90  4970.1  676.40  4980.1  675.47  4980.7  674.22
  4982.7  673.72  4999.5  674.22  5010.1  674.24  5030.2  680.71  5070.2  681.49
  5090.3  683.56  5170.4  682.34  5437.4  683.39  5631.2  682.77  5791.5  683.85
  5841.6  686.55  5901.7  693.55  5931.7  702.66  5949.0  706.32  6027.0  713.04
#Mann=3,-1,0
  4308.1    0.05       0  4980.7   0.033       0  4999.5    0.05       0
Bank Sta=4980.7,4999.5
Exp/Cntr=0.3,0.1

Type RM Length L Ch R = 1,7368,414,414,414
BEGIN DESCRIPTION:
Mapping XS 383e5dc5
END DESCRIPTION:
XS GIS Cut Line= 2
      2316949.50      7108602.19      2316852.93      7106850.55
#Sta/Elev= 30
  4276.3  697.50  4629.0  689.61  4689.1  689.10  4741.9  690.35  4789.3  690.01
  4869.4  684.65  4959.5  682.47  4979.6  674.46  4990.2  673.93  4992.2  673.43
  5009.0  673.93  5009.6  675.68  5019.6  675.68  5039.6  678.85  5049.7  678.85
  5069.7  681.05  5119.8  682.63  5199.9  682.57  5239.9  680.53  5310.1  682.42
  5357.8  682.58  5363.1  682.42  5651.7  682.04  5740.7  683.94  5820.8  687.88
  5901.0  693.54  5931.0  698.97  5951.0  701.22  5981.1  706.92  6030.6  711.56
#Mann=5,-1,0
  4276.3    0.05       0  4990.2    0.04       0  5009.0    0.05       0
  5357.8    0.12       0  5363.1    0.05       0
Bank Sta=4990.2,5009
Exp/Cntr=0.3,0.1

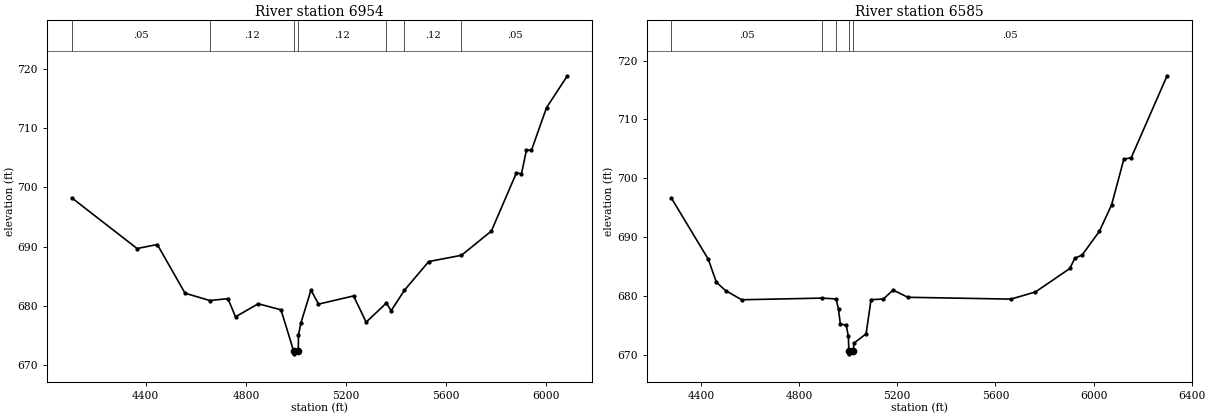
Type RM Length L Ch R = 1,6954,369,369,369
BEGIN DESCRIPTION:
Mapping XS 363555eb
END DESCRIPTION:
XS GIS Cut Line= 3
      2317172.33      7108648.95      2317277.39      7107824.14
      2317333.53      7106676.79
#Sta/Elev= 30
  4104.2  698.24  4365.2  689.69  4445.9  690.37  4556.8  682.16  4655.6  680.93
  4728.2  681.24  4758.4  678.18  4849.1  680.38  4940.3  679.36  4990.5  672.44
  4992.5  671.94  5009.3  672.44  5009.9  675.08  5019.9  677.16  5060.0  682.69
  5090.0  680.32  5230.2  681.70  5280.3  677.28  5361.0  680.49  5380.3  679.21
  5433.5  682.67  5530.5  687.50  5661.3  688.55  5780.8  692.64  5880.9  702.46
  5901.0  702.29  5921.0  706.32  5941.0  706.26  6001.1  713.44  6084.4  718.81
#Mann=7,-1,0
  4104.2    0.05       0  4655.6    0.12       0  4990.5    0.07       0
  5009.3    0.12       0  5361.0    0.05       0  5433.5    0.12       0
  5661.3    0.05       0
Bank Sta=4990.5,5009.3
Exp/Cntr=0.3,0.1

Type RM Length L Ch R = 1,6585,250,250,250
BEGIN DESCRIPTION:
Mapping XS ad51f47e
END DESCRIPTION:
XS GIS Cut Line= 3
      2317360.27      7108640.62      2317577.63      7107936.48
      2317539.17      7106653.98
#Sta/Elev= 30
  4279.5  696.60  4429.8  686.20  4462.5  682.30  4500.4  680.87  4565.7  679.32
  4892.9  679.60  4950.6  679.46  4960.4  677.69  4967.9  675.17  4991.8  675.02
  5000.6  673.08  5002.6  670.62  5004.6  670.12  5021.4  670.62  5022.9  671.92
  5072.9  673.53  5092.9  679.34  5143.0  679.44  5183.0  680.97  5243.0  679.74
  5663.2  679.43  5763.2  680.65  5903.3  684.64  5923.3  686.38  5953.3  686.93
  6023.4  690.95  6073.4  695.46  6123.4  703.24  6153.4  703.48  6299.5  717.42
#Mann=5,-1,0
  4279.5    0.05       0  4892.9    0.12       0  4950.6    0.05       0
  5002.6   0.033       0  5021.4    0.05       0
Bank Sta=5002.6,5021.4
Exp/Cntr=0.3,0.1