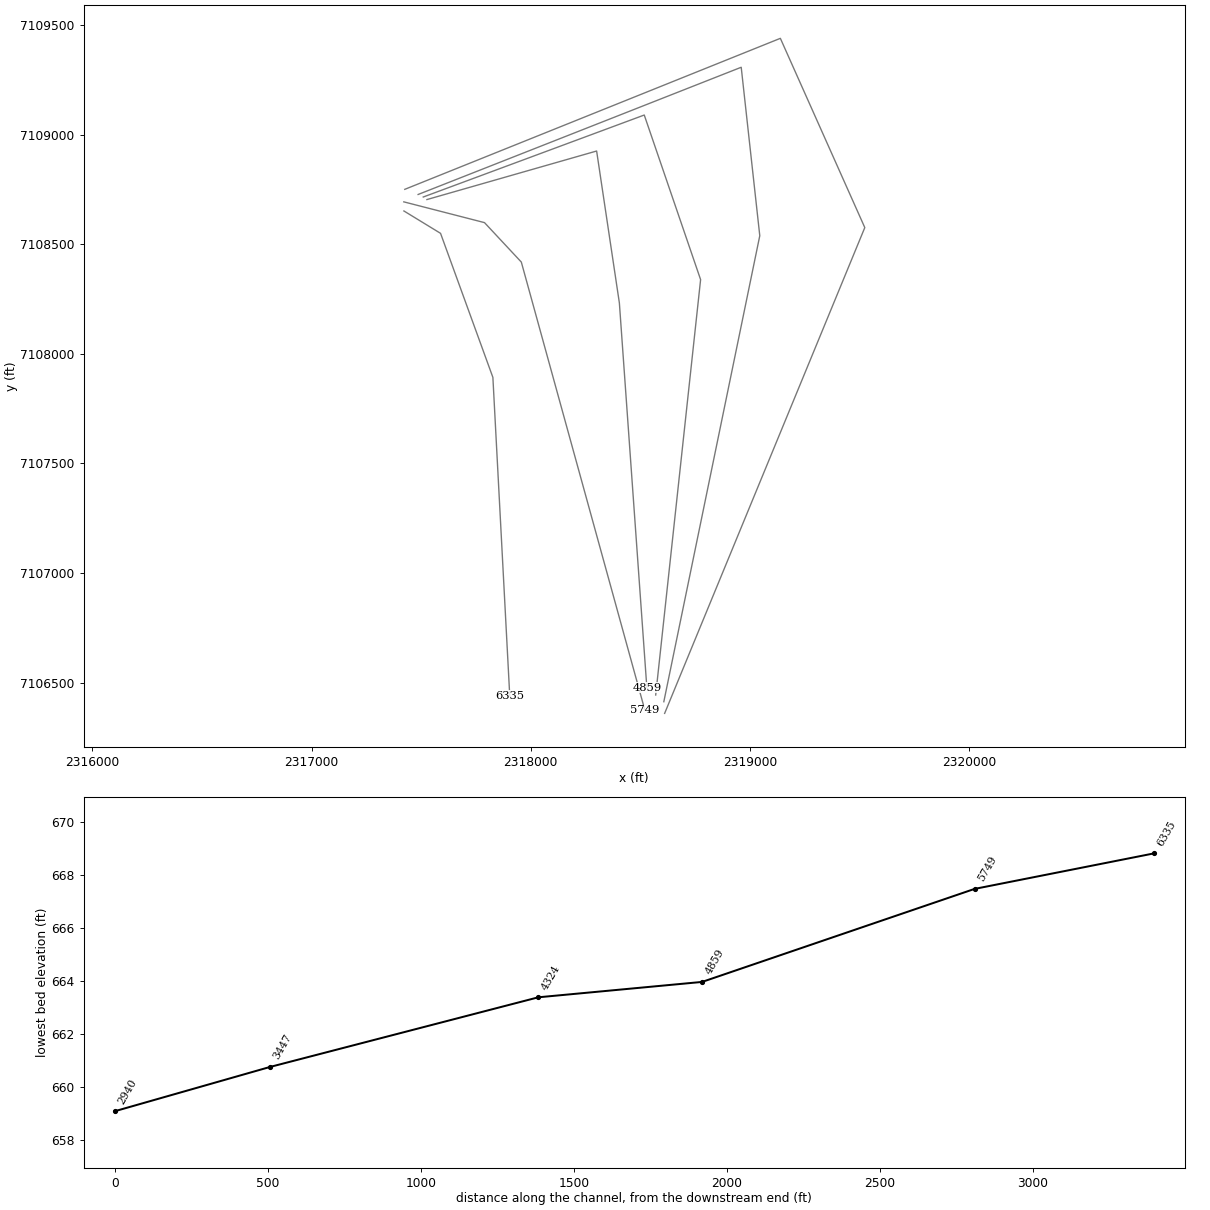
HEC-RAS study Morris Branch.prj: Morris Branch Base Level Engineering

--- Morris Branch.g01 (geometry) --- (continued)

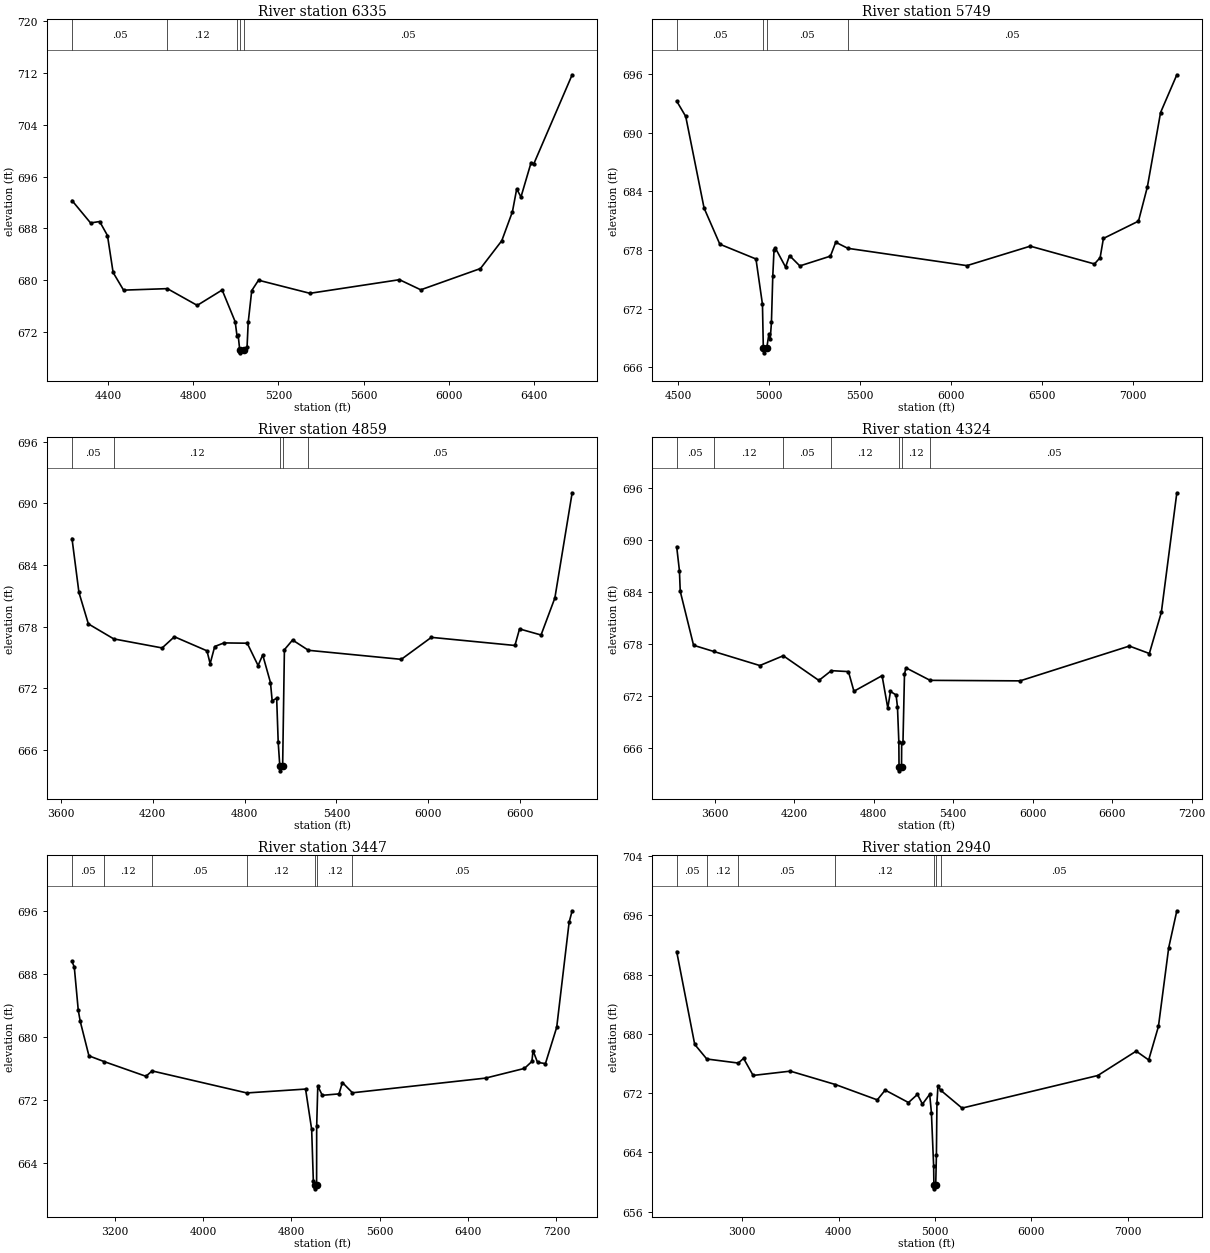
Type RM Length L Ch R = 1,6335,586,586,586
BEGIN DESCRIPTION:
Mapping XS 74e470cd
END DESCRIPTION:
XS GIS Cut Line= 4
      2317421.32      7108651.63      2317588.45      7108549.55
      2317827.14      7107892.44      2317904.05      7106439.83
#Sta/Elev= 30
  4230.1  692.31  4317.4  688.85  4360.0  689.07  4396.8  686.91  4423.3  681.21
  4472.4  678.49  4678.1  678.72  4818.4  676.14  4935.5  678.51  4996.7  673.62
  5005.2  671.46  5010.6  671.58  5017.9  669.32  5019.9  668.82  5036.7  669.32
  5052.6  669.77  5057.9  673.52  5074.5  678.42  5106.4  680.02  5347.8  678.00
  5768.4  680.10  5868.5  678.54  6148.9  681.82  6249.1  686.11  6299.1  690.58
  6319.2  694.10  6339.2  692.85  6386.9  698.17  6399.3  697.95  6579.7  711.70
#Mann=5,-1,0
  4230.1    0.05       0  4678.1    0.12       0  5005.2    0.05       0
  5017.9    0.07       0  5036.7    0.05       0
Bank Sta=5017.9,5036.7
Exp/Cntr=0.3,0.1

Type RM Length L Ch R = 1,5749,890,890,890
BEGIN DESCRIPTION:
Mapping XS 2bca109f
END DESCRIPTION:
XS GIS Cut Line= 4
      2317420.85      7108693.18      2317788.89      7108598.48
      2317956.86      7108418.50      2318520.58      7106373.90
#Sta/Elev= 30
  4493.2  693.23  4542.9  691.66  4643.7  682.29  4730.3  678.59  4928.7  677.08
  4964.4  672.44  4969.1  667.98  4971.1  667.48  4987.9  667.98  4999.5  669.36
  5006.9  668.85  5013.7  670.59  5021.0  675.30  5027.9  678.00  5035.2  678.20
  5091.4  676.25  5112.9  677.43  5169.7  676.37  5337.6  677.37  5366.8  678.79
  5433.3  678.17  6087.3  676.40  6435.2  678.39  6787.9  676.57  6819.0  677.22
  6837.0  679.18  7029.6  680.95  7078.4  684.45  7151.0  692.06  7240.3  695.92
#Mann=4,-1,0
  4493.2    0.05       0  4969.1    0.07       0  4987.9    0.05       0
  5433.3    0.05       0
Bank Sta=4969.1,4987.9
Exp/Cntr=0.3,0.1

Type RM Length L Ch R = 1,4859,535,535,535
BEGIN DESCRIPTION:
Mapping XS 06c7dc89
END DESCRIPTION:
XS GIS Cut Line= 4
      2317526.26      7108703.66      2318300.35      7108925.13
      2318404.13      7108231.84      2318529.43      7106477.37
#Sta/Elev= 30
  3673.3  686.58  3718.7  681.33  3780.2  678.27  3946.0  676.81  4261.8  675.93
  4341.8  677.02  4554.4  675.65  4575.2  674.40  4605.0  676.07  4665.6  676.42
  4817.3  676.39  4888.1  674.22  4918.4  675.25  4969.0  672.56  4980.1  670.78
  5009.4  671.04  5019.5  666.75  5029.7  664.47  5031.7  663.97  5048.5  664.47
  5060.0  675.76  5113.3  676.70  5216.9  675.70  5822.9  674.82  6019.2  676.96
  6564.8  676.17  6594.9  677.78  6735.3  677.19  6825.5  680.79  6938.4  691.03
#Mann=5,-1,0
  3673.3    0.05       0  3946.0    0.12       0  5029.7    0.07       0
  5048.5    0.12       0  5216.9    0.05       0
Bank Sta=5029.7,5048.5
Exp/Cntr=0.3,0.1

Type RM Length L Ch R = 1,4324,877,877,877
BEGIN DESCRIPTION:
Mapping XS 2a211182
END DESCRIPTION:
XS GIS Cut Line= 4
      2317509.50      7108715.30      2318517.58      7109089.27
      2318774.64      7108338.46      2318569.78      7106443.70
#Sta/Elev= 30
  3313.2  689.28  3334.0  686.51  3340.2  684.12  3440.7  677.89  3591.9  677.18
  3940.7  675.55  4117.7  676.68  4386.5  673.83  4480.5  674.96  4609.6  674.85
  4650.9  672.58  4863.3  674.38  4906.5  670.64  4926.7  672.56  4969.1  672.15
  4979.5  670.77  4989.8  666.76  4991.3  663.89  4993.3  663.39  5010.1  663.89
  5011.3  666.58  5021.1  666.75  5032.4  674.53  5043.0  675.29  5225.8  673.84
  5904.6  673.78  6729.4  677.80  6880.3  676.94  6970.8  681.69  7087.8  695.50
#Mann=7,-1,0
  3313.2    0.05       0  3591.9    0.12       0  4117.7    0.05       0
  4480.5    0.12       0  4991.3    0.07       0  5010.1    0.12       0
  5225.8    0.05       0
Bank Sta=4991.3,5010.1
Exp/Cntr=0.3,0.1

Type RM Length L Ch R = 1,3447,507,507,507
BEGIN DESCRIPTION:
Mapping XS 8f1fb9ed
END DESCRIPTION:
XS GIS Cut Line= 4
      2317486.14      7108726.88      2318959.87      7109307.15
      2319044.57      7108538.68      2318606.86      7106413.05
#Sta/Elev= 30
  2814.9  689.57  2835.6  688.87  2871.7  683.39  2889.7  681.97  2968.3  677.61
  3108.3  676.87  3484.3  675.02  3540.0  675.70  4397.3  672.91  4929.1  673.40
  4984.3  668.29  4999.5  661.73  5010.2  661.26  5012.2  660.76  5029.0  661.26
  5029.7  668.68  5039.8  673.80  5080.2  672.61  5231.8  672.79  5262.4  674.23
  5353.6  672.93  6558.5  674.79  6910.7  676.02  6977.7  676.90  6987.9  678.27
  7028.7  676.78  7100.2  676.63  7202.3  681.23  7314.6  694.53  7342.1  695.99
#Mann=7,-1,0
  2814.9    0.05       0  3108.3    0.12       0  3540.0    0.05       0
  4397.3    0.12       0  5010.2    0.07       0  5029.0    0.12       0
  5353.6    0.05       0
Bank Sta=5010.2,5029
Exp/Cntr=0.3,0.1

Type RM Length L Ch R = 1,2940,0,0,0
BEGIN DESCRIPTION:
Morris Branch 3.0
END DESCRIPTION:
XS GIS Cut Line= 4
      2317425.31      7108750.35      2319138.44      7109439.10
      2319523.58      7108575.82      2318610.59      7106359.93
#Sta/Elev= 30
  2319.5  691.13  2506.7  678.59  2631.8  676.62  2959.2  676.07  3013.3  676.71
  3112.5  674.40  3498.3  674.98  3966.8  673.17  4400.4  671.10  4482.5  672.42
  4724.2  670.74  4817.1  671.84  4869.0  670.53  4944.1  671.85  4961.9  669.38
  4985.1  662.16  4987.7  659.59  4989.7  659.09  5006.5  659.59  5013.8  663.66
  5019.3  670.66  5030.0  673.01  5057.5  672.41  5279.7  669.99  6688.1  674.39
  7085.9  677.68  7215.7  676.49  7316.8  681.01  7423.4  691.64  7507.8  696.63
#Mann=7,-1,0
  2319.5    0.05       0  2631.8    0.12       0  2959.2    0.05       0
  3966.8    0.12       0  4987.7    0.07       0  5006.5    0.12       0
  5057.5    0.05       0
Bank Sta=4987.7,5006.5
Exp/Cntr=0.3,0.1

Chan Stop Cuts=-1