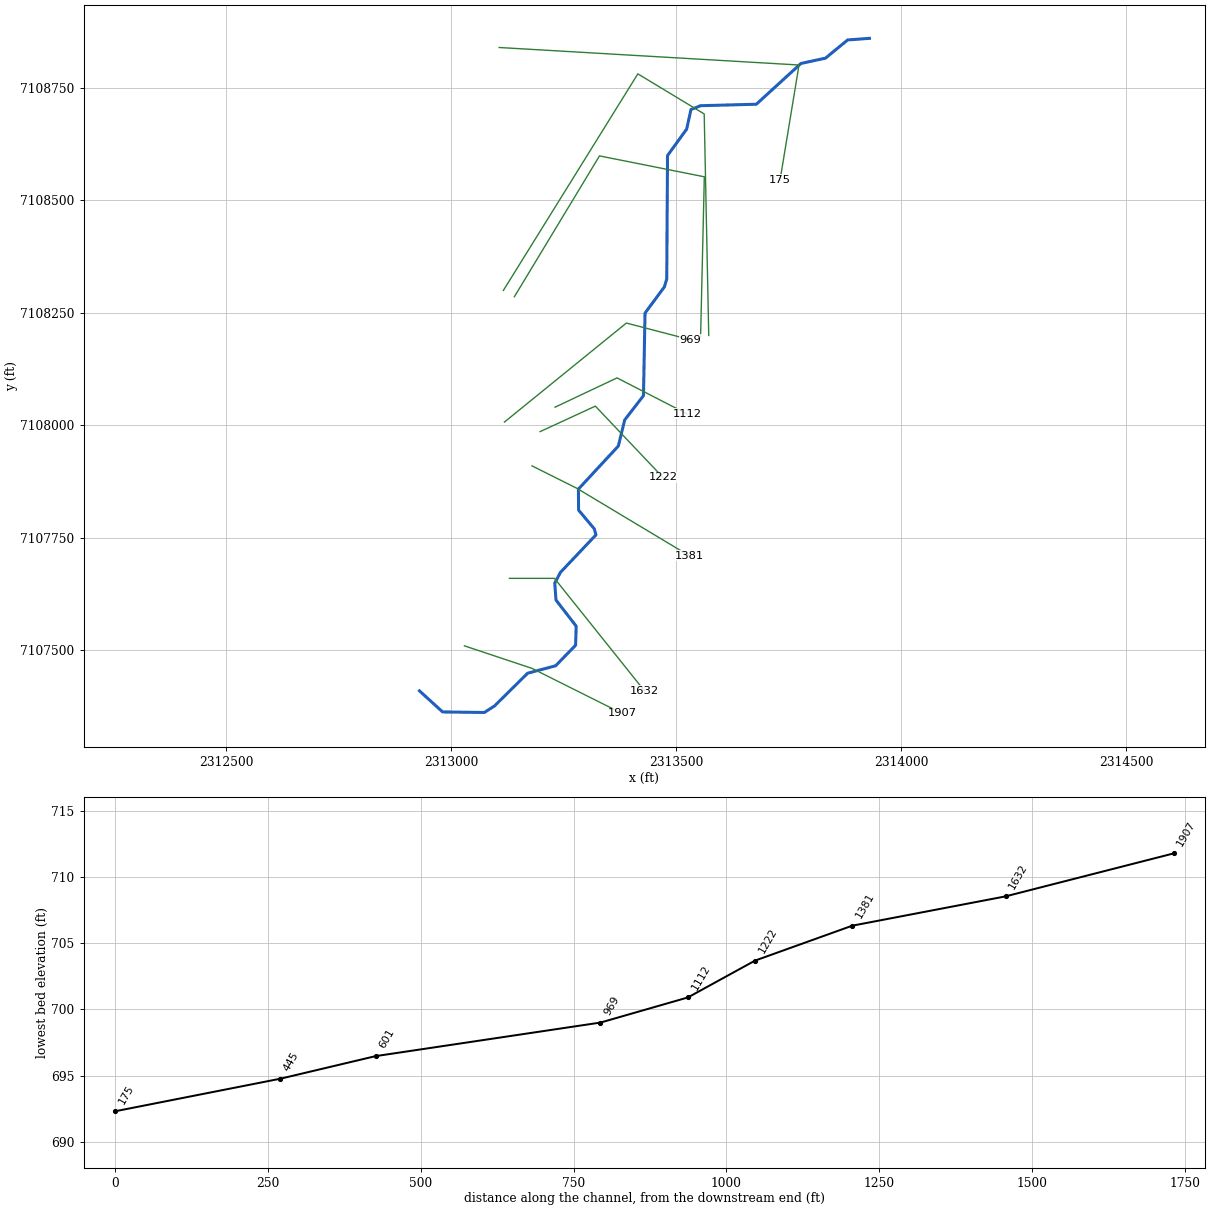
--- Morris Branch Tributary 1.prj (project) ---

Proj Title=Morris Branch Tributary 1 Base Level Engineering
Current Plan=p01
Default Exp/Contr=0.3,0.1
English Units
Geom File=g01
Flow File=f01
Plan File=p01
BEGIN DESCRIPTION:
Morris Branch Tributary 1
END DESCRIPTION:

--- Morris Branch Tributary 1.p01 (plan) ---

Plan Title=Multiple Run
Short Identifier=Multiple
Geom File=g01
Flow File=f01
Subcritical Flow
K Sum by GR= 0
Std Step Tol= 0.01
Critical Tol= 0.01
Num of Std Step Trials= 20
Max Error Tol= 0.3
Flow Tol Ratio= 0.001
Split Flow NTrial= 30
Split Flow Tol= 0.02
Split Flow Ratio= 0.02
Log Output Level= 0
Friction Slope Method= 1
Unsteady Friction Slope Method= 2
Unsteady Bridges Friction Slope Method= 1
Parabolic Critical Depth
Global Vel Dist=  1 , 1 , 1
Global Log Level= 0
CheckData=True
Encroach Param= -1, 0, 0, 0
BEGIN DESCRIPTION:
Multiple Run
END DESCRIPTION:

--- Morris Branch Tributary 1.f01 (steady flow) ---

Flow Title=Multiple
Number of Profiles=7
Profile Names=10-year,25-year,50-year,1pct_min,100-year,1pct_plu,500-year
River Rch & RM= Morris Branch Tr,Reach-1,1907
     293     389     465     278     555    1107     788
Boundary for River Rch & Prof#=Morris Branch Tr,Reach-1,1
Up Type=0
Dn Type=3
Dn Slope=0.007
Boundary for River Rch & Prof#=Morris Branch Tr,Reach-1,2
Up Type=0
Dn Type=3
Dn Slope=0.007
Boundary for River Rch & Prof#=Morris Branch Tr,Reach-1,3
Up Type=0
Dn Type=3
Dn Slope=0.007
Boundary for River Rch & Prof#=Morris Branch Tr,Reach-1,4
Up Type=0
Dn Type=3
Dn Slope=0.007
Boundary for River Rch & Prof#=Morris Branch Tr,Reach-1,5
Up Type=0
Dn Type=3
Dn Slope=0.007
Boundary for River Rch & Prof#=Morris Branch Tr,Reach-1,6
Up Type=0
Dn Type=3
Dn Slope=0.007
Boundary for River Rch & Prof#=Morris Branch Tr,Reach-1,7
Up Type=0
Dn Type=3
Dn Slope=0.007

--- Morris Branch Tributary 1.g01 (geometry) ---

Geom Title=Existing Conditions

River Reach=Morris Branch Tr,Reach-1
Reach XY= 30
      2312929.00      7107410.00      2312980.41      7107363.18
      2313073.12      7107361.96      2313095.74      7107376.44
      2313169.35      7107449.19      2313231.61      7107465.75
      2313275.96      7107511.42      2313277.21      7107553.84
      2313232.38      7107611.73      2313229.62      7107649.38
      2313242.18      7107673.21      2313321.16      7107756.60
      2313317.60      7107769.87      2313282.59      7107811.65
      2313282.17      7107858.35      2313370.84      7107953.95
      2313385.14      7108012.17      2313426.76      7108065.93
      2313430.22      7108249.49      2313473.25      7108307.67
      2313478.48      7108325.22      2313480.19      7108599.52
      2313522.69      7108658.23      2313532.35      7108701.90
      2313553.79      7108710.31      2313677.52      7108713.56
      2313776.70      7108804.17      2313831.24      7108815.97
      2313880.49      7108856.40      2313929.00      7108860.00

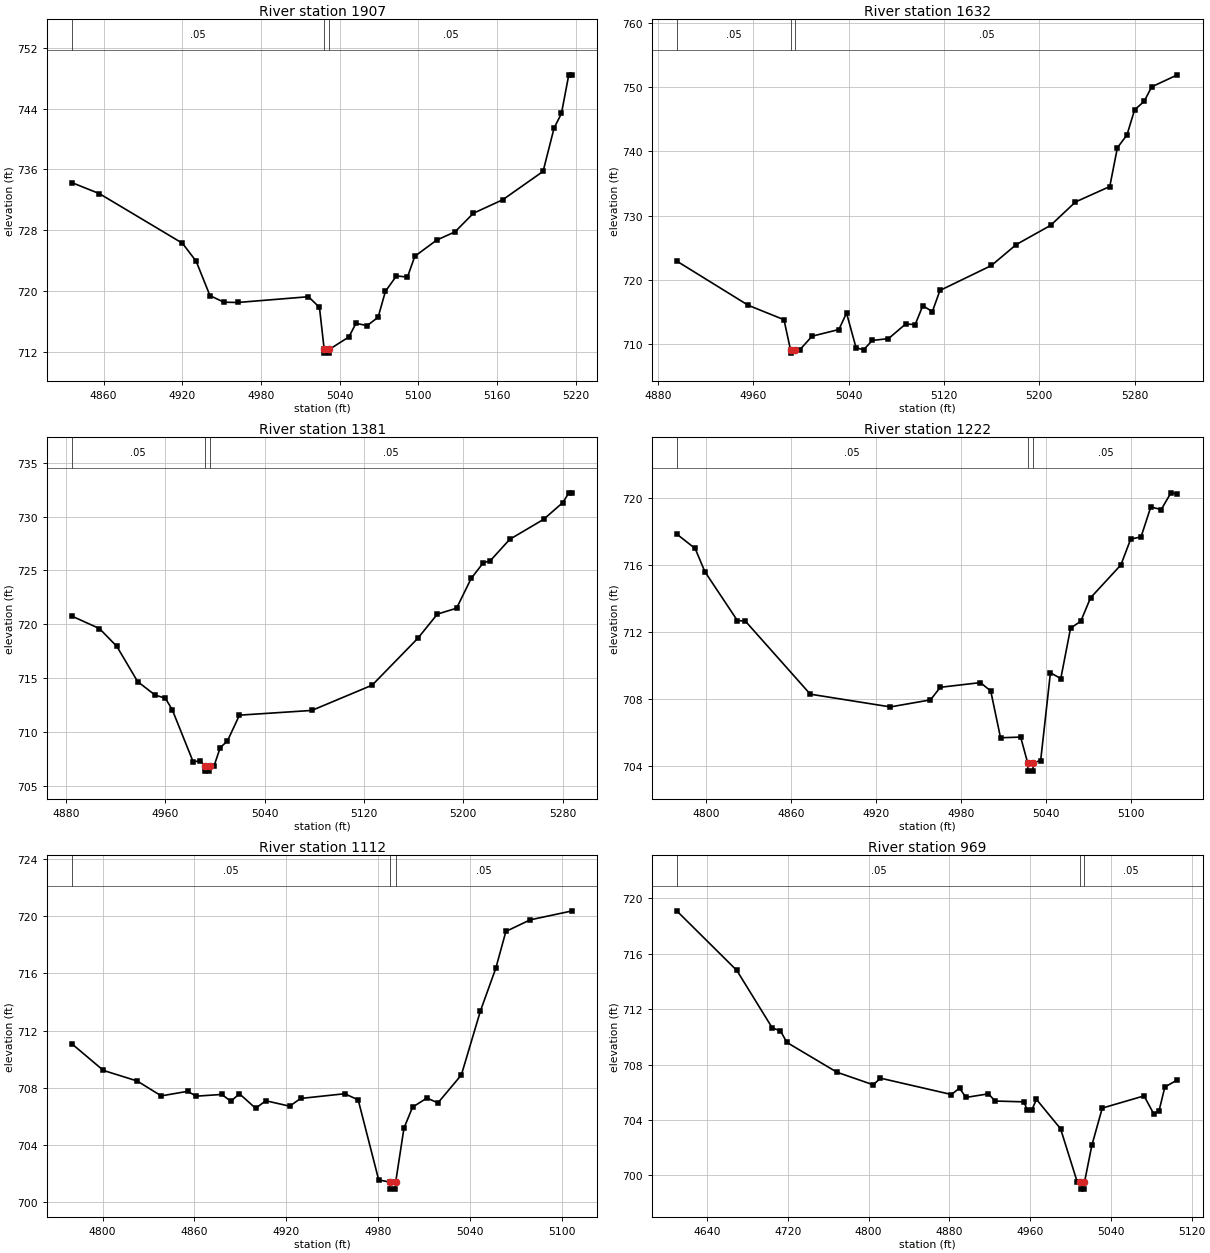
Type RM Length L Ch R = 1,1907,275,275,275
BEGIN DESCRIPTION:
Morris Branch Tributary 1 5.0
END DESCRIPTION:
XS GIS Cut Line= 3
      2313028.97      7107510.01      2313179.00      7107460.00
      2313379.04      7107359.98
#Sta/Elev= 30
  4835.7  734.28  4856.8  732.82  4920.1  726.29  4930.6  723.91  4941.1  719.39
  4951.7  718.52  4962.2  718.48  5016.2  719.24  5024.6  717.84  5028.2  712.31
  5028.4  711.81  5031.9  711.81  5032.2  712.31  5047.0  713.94  5052.5  715.74
  5060.9  715.43  5069.3  716.53  5074.9  719.95  5083.3  721.98  5091.7  721.83
  5097.3  724.57  5114.0  726.70  5128.0  727.79  5142.0  730.24  5164.3  732.01
  5195.1  735.75  5203.5  741.46  5209.1  743.38  5214.7  748.47  5217.5  748.47
#Mann=3,-1,0
  4835.7    0.05       0  5028.2   0.033       0  5032.2    0.05       0
Bank Sta=5028.2,5032.2
Exp/Cntr=0.3,0.1

Type RM Length L Ch R = 1,1632,251,251,251
BEGIN DESCRIPTION:
Morris Branch Tributary 1 4.0
END DESCRIPTION:
XS GIS Cut Line= 3
      2313128.96      7107660.00      2313229.00      7107660.00
      2313429.00      7107410.00
#Sta/Elev= 30
  4895.8  722.91  4955.8  716.02  4985.8  713.77  4991.3  709.06  4991.6  708.56
  4995.3  709.06  4999.0  709.06  5009.4  711.20  5031.9  712.24  5038.3  714.81
  5046.3  709.39  5052.7  709.08  5059.9  710.54  5073.5  710.82  5087.9  713.10
  5095.9  713.01  5102.3  715.95  5110.3  715.03  5116.7  718.33  5159.9  722.22
  5180.7  725.48  5209.5  728.47  5230.4  732.12  5259.2  734.53  5265.6  740.58
  5273.6  742.56  5280.0  746.47  5288.0  747.80  5294.4  750.07  5316.0  751.94
#Mann=3,-1,0
  4895.8    0.05       0  4991.3   0.033       0  4995.3    0.05       0
Bank Sta=4991.3,4995.3
Exp/Cntr=0.3,0.1

Type RM Length L Ch R = 1,1381,159,159,159
BEGIN DESCRIPTION:
Morris Branch Tributary 1 3.0
END DESCRIPTION:
XS GIS Cut Line= 3
      2313179.02      7107909.99      2313279.00      7107860.00
      2313528.97      7107710.02
#Sta/Elev= 30
  4884.6  720.75  4906.9  719.59  4920.9  717.94  4937.7  714.66  4951.7  713.41
  4960.0  713.12  4965.6  712.04  4982.4  707.21  4988.0  707.30  4991.6  706.84
  4991.8  706.34  4995.3  706.34  4995.6  706.84  4999.3  706.84  5004.2  708.52
  5010.0  709.14  5019.7  711.54  5078.0  711.98  5126.6  714.33  5163.5  718.70
  5179.1  720.93  5194.6  721.48  5206.3  724.24  5216.0  725.69  5221.8  725.90
  5237.4  727.88  5264.6  729.73  5280.2  731.30  5285.0  732.20  5287.9  732.20
#Mann=3,-1,0
  4884.6    0.05       0  4991.6   0.033       0  4995.6    0.05       0
Bank Sta=4991.6,4995.6
Exp/Cntr=0.3,0.1

Type RM Length L Ch R = 1,1222,110,110,110
BEGIN DESCRIPTION:
Mapping XS 72762927
END DESCRIPTION:
XS GIS Cut Line= 3
      2313197.16      7107986.09      2313319.83      7108042.72
      2313469.89      7107884.47
#Sta/Elev= 30
  4779.3  717.84  4792.3  716.98  4799.2  715.59  4822.1  712.68  4827.7  712.65
  4873.5  708.29  4930.0  707.53  4958.3  707.95  4965.2  708.70  4993.5  708.98
  5000.8  708.48  5007.7  705.69  5021.9  705.73  5026.8  704.20  5027.0  703.70
  5030.5  703.70  5030.8  704.20  5036.0  704.33  5042.9  709.57  5050.2  709.22
  5057.1  712.23  5064.3  712.64  5071.2  714.04  5092.6  716.00  5099.5  717.54
  5106.8  717.67  5113.7  719.46  5121.0  719.30  5127.9  720.30  5132.5  720.24
#Mann=3,-1,0
  4779.3    0.05       0  5026.8   0.033       0  5030.8    0.05       0
Bank Sta=5026.8,5030.8
Exp/Cntr=0.3,0.1

Type RM Length L Ch R = 1,1112,143,143,143
BEGIN DESCRIPTION:
Mapping XS 629ae8b6
END DESCRIPTION:
XS GIS Cut Line= 3
      2313230.29      7108040.37      2313368.00      7108105.46
      2313523.55      7108025.54
#Sta/Elev= 30
  4779.8  711.08  4800.5  709.21  4822.6  708.47  4838.3  707.43  4855.6  707.75
  4861.1  707.41  4877.9  707.53  4883.8  707.05  4889.4  707.58  4900.0  706.56
  4906.6  707.09  4922.2  706.71  4929.4  707.25  4958.2  707.58  4967.0  707.15
  4980.4  701.55  4987.5  701.41  4987.7  700.91  4991.2  700.91  4991.5  701.41
  4996.9  705.17  5002.5  706.64  5011.9  707.28  5019.1  706.94  5034.4  708.89
  5046.9  713.38  5056.9  716.35  5063.5  718.93  5079.4  719.74  5107.0  720.37
#Mann=3,-1,0
  4779.8    0.05       0  4987.5   0.033       0  4991.5    0.05       0
Bank Sta=4987.5,4991.5
Exp/Cntr=0.3,0.1

Type RM Length L Ch R = 1,969,368,368,368
BEGIN DESCRIPTION:
Mapping XS d004c1a8
END DESCRIPTION:
XS GIS Cut Line= 3
      2313117.88      7108007.39      2313388.79      7108227.36
      2313531.05      7108190.18
#Sta/Elev= 30
  4609.9  719.10  4669.4  714.80  4704.6  710.64  4712.6  710.44  4719.0  709.60
  4768.6  707.45  4804.6  706.54  4811.7  707.02  4882.0  705.84  4890.0  706.30
  4896.4  705.63  4918.7  705.89  4925.2  705.37  4953.9  705.31  4957.0  704.72
  4961.6  704.72  4966.2  705.49  4990.1  703.37  5006.7  699.51  5009.8  699.51
  5010.1  699.01  5013.6  699.01  5013.8  699.51  5021.1  702.17  5031.4  704.86
  5072.8  705.74  5082.4  704.44  5087.6  704.65  5093.4  706.38  5105.9  706.90
#Mann=3,-1,0
  4609.9    0.05       0  5009.8   0.033       0  5013.8    0.05       0
Bank Sta=5009.8,5013.8
Exp/Cntr=0.3,0.1

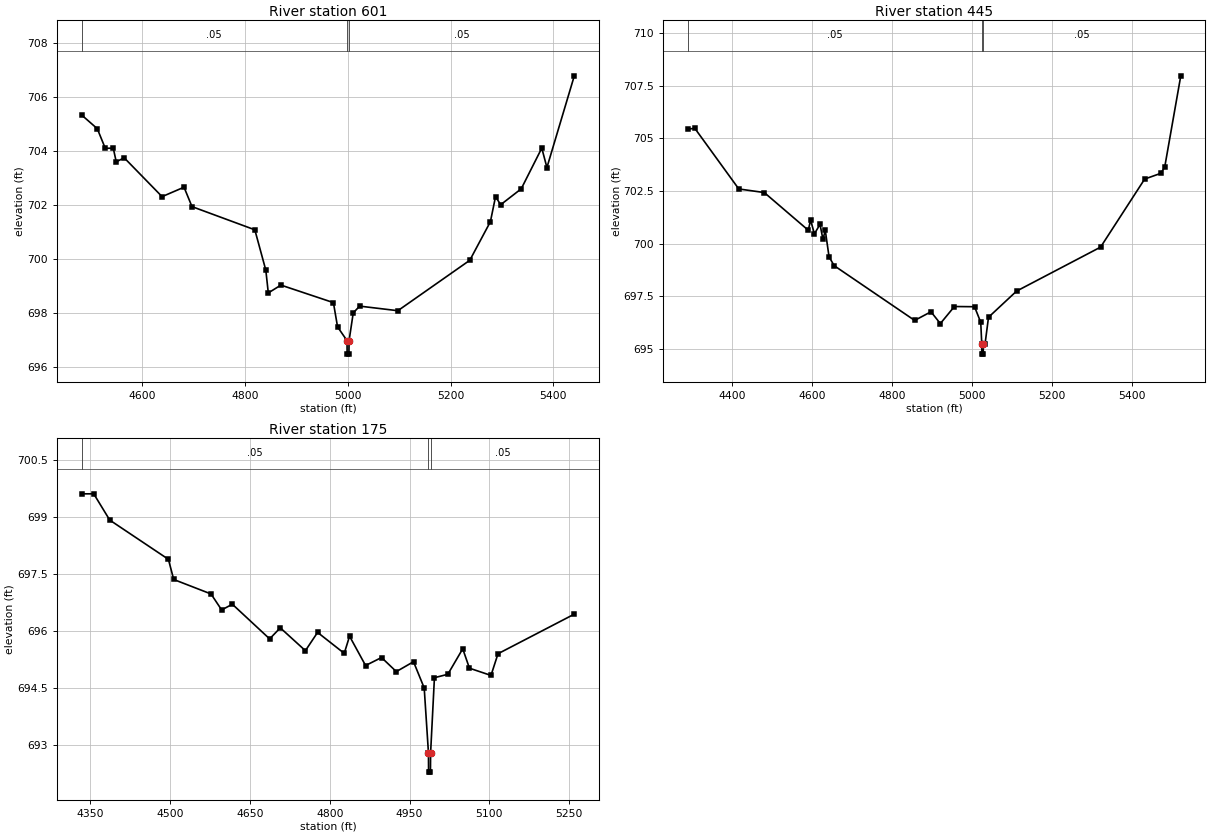
Type RM Length L Ch R = 1,601,156,156,156
BEGIN DESCRIPTION:
Mapping XS 39603368
END DESCRIPTION:
XS GIS Cut Line= 4
      2313139.92      7108285.84      2313329.04      7108598.77
      2313561.99      7108552.33      2313553.70      7108196.70
#Sta/Elev= 30
  4481.9  705.34  4512.5  704.83  4528.1  704.10  4543.6  704.11  4549.4  703.60
  4564.9  703.75  4638.6  702.31  4681.3  702.66  4696.8  701.94  4819.1  701.08
  4840.5  699.58  4845.3  698.74  4869.9  699.03  4972.0  698.38  4980.1  697.48
  4998.5  696.97  4998.7  696.47  5002.2  696.47  5002.5  696.97  5010.6  698.00
  5023.1  698.25  5097.4  698.08  5237.4  699.95  5277.5  701.38  5287.5  702.31
  5297.5  702.01  5337.5  702.60  5377.5  704.11  5387.5  703.39  5440.8  706.79
#Mann=3,-1,0
  4481.9    0.05       0  4998.5   0.035       0  5002.5    0.05       0
Bank Sta=4998.5,5002.5
Exp/Cntr=0.3,0.1

Type RM Length L Ch R = 1,445,270,270,270
BEGIN DESCRIPTION:
Mapping XS a14ce755
END DESCRIPTION:
XS GIS Cut Line= 4
      2313115.52      7108299.92      2313414.26      7108781.06
      2313561.70      7108691.96      2313571.83      7108199.78
#Sta/Elev= 30
  4290.1  705.44  4307.0  705.48  4416.9  702.60  4480.6  702.43  4590.5  700.64
  4596.3  701.12  4605.8  700.47  4619.8  700.92  4627.1  700.21  4633.0  700.63
  4642.4  699.38  4655.1  698.96  4856.2  696.36  4897.0  696.77  4920.4  696.21
  4955.5  697.02  5005.8  697.01  5021.3  696.27  5023.8  695.26  5024.0  694.76
  5027.5  694.76  5027.8  695.26  5032.2  695.26  5040.7  696.51  5110.7  697.75
  5320.7  699.84  5430.8  703.07  5470.8  703.34  5480.8  703.63  5521.0  707.97
#Mann=3,-1,0
  4290.1    0.05       0  5023.8   0.035       0  5027.8    0.05       0
Bank Sta=5023.8,5027.8
Exp/Cntr=0.3,0.1

Type RM Length L Ch R = 1,175,0,0,0
BEGIN DESCRIPTION:
Morris Branch Tributary 1 1.0
END DESCRIPTION:
XS GIS Cut Line= 3
      2313106.12      7108839.65      2313772.40      7108800.74
      2313730.35      7108545.50
#Sta/Elev= 30
  4333.5  699.61  4356.4  699.61  4386.5  698.92  4496.7  697.89  4506.7  697.36
  4576.8  696.98  4596.8  696.56  4616.9  696.71  4687.0  695.80  4707.0  696.09
  4754.2  695.49  4777.1  695.97  4827.2  695.42  4837.2  695.87  4867.3  695.10
  4897.3  695.31  4925.1  694.94  4957.4  695.20  4977.5  694.51  4985.5  692.80
  4985.7  692.30  4989.2  692.30  4989.5  692.80  4996.7  694.78  5021.9  694.87
  5049.9  695.54  5062.5  695.03  5103.0  694.84  5116.2  695.41  5259.6  696.45
#Mann=3,-1,0
  4333.5    0.05       0  4985.5   0.035       0  4989.5    0.05       0
Bank Sta=4985.5,4989.5
Exp/Cntr=0.3,0.1

Chan Stop Cuts=-1