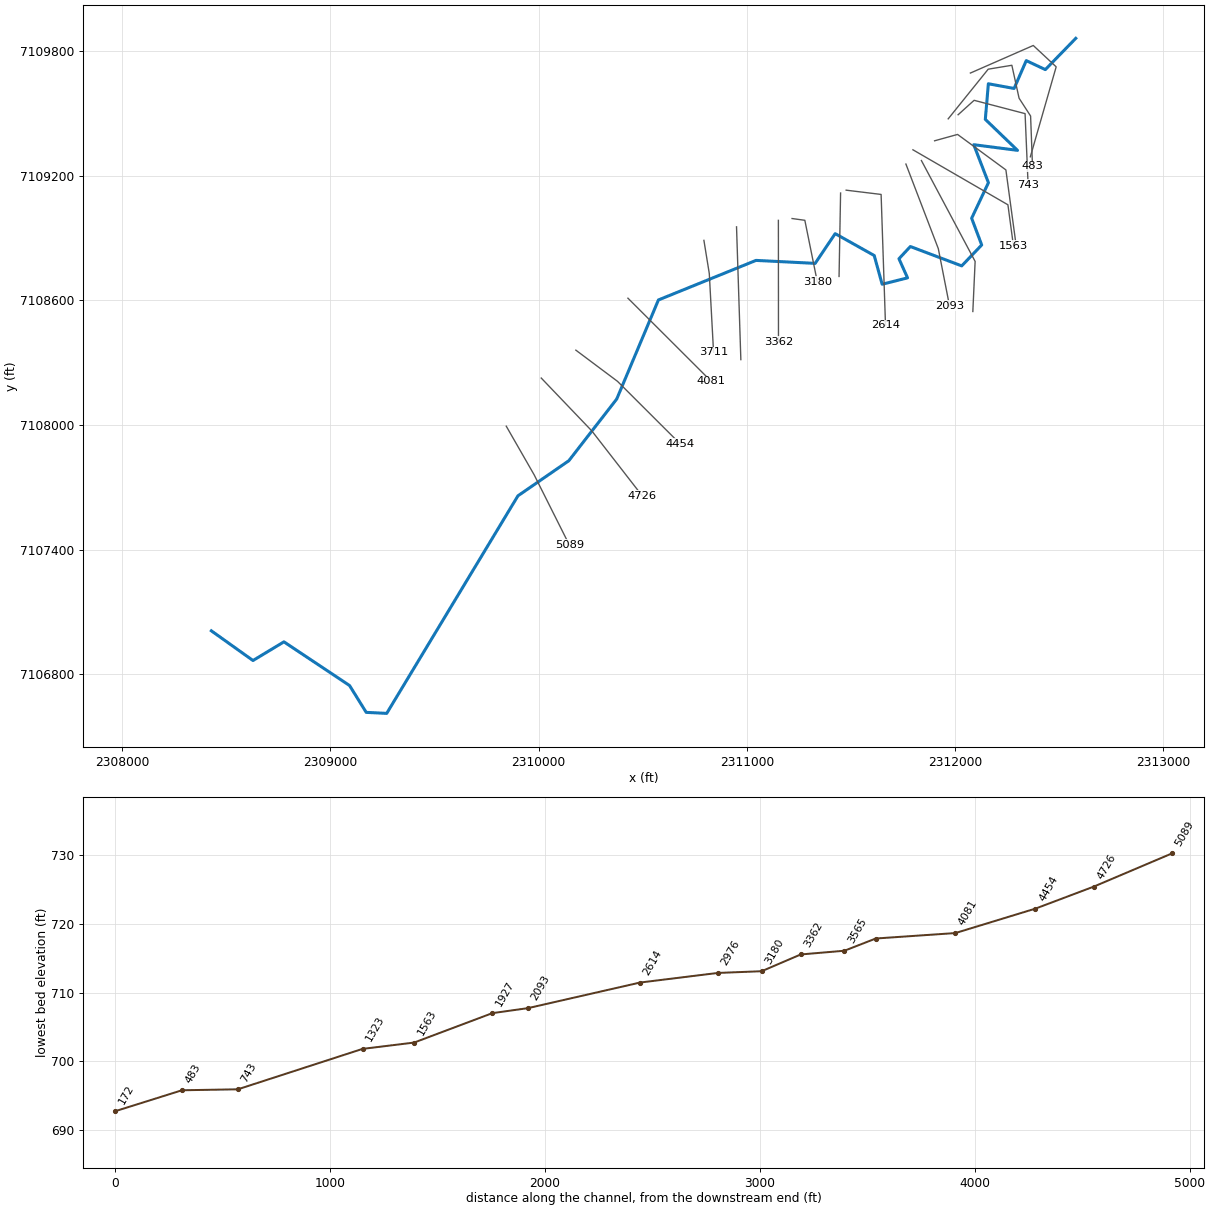
--- Morris Branch Tributary 2.prj (project) ---

Proj Title=Morris Branch Tributary 2 Base Level Engineering
Current Plan=p01
Default Exp/Contr=0.3,0.1
English Units
Geom File=g01
Flow File=f01
Plan File=p01
BEGIN DESCRIPTION:
Morris Branch Tributary 2
END DESCRIPTION:

--- Morris Branch Tributary 2.p01 (plan) ---

Plan Title=Multiple Run
Short Identifier=Multiple
Geom File=g01
Flow File=f01
Subcritical Flow
K Sum by GR= 0
Std Step Tol= 0.01
Critical Tol= 0.01
Num of Std Step Trials= 20
Max Error Tol= 0.3
Flow Tol Ratio= 0.001
Split Flow NTrial= 30
Split Flow Tol= 0.02
Split Flow Ratio= 0.02
Log Output Level= 0
Friction Slope Method= 1
Unsteady Friction Slope Method= 2
Unsteady Bridges Friction Slope Method= 1
Parabolic Critical Depth
Global Vel Dist=  1 , 1 , 1
Global Log Level= 0
CheckData=True
Encroach Param= -1, 0, 0, 0
BEGIN DESCRIPTION:
Multiple Run
END DESCRIPTION:

--- Morris Branch Tributary 2.f01 (steady flow) ---

Flow Title=Multiple
Number of Profiles=7
Profile Names=10-year,25-year,50-year,1pct_min,100-year,1pct_plu,500-year
River Rch & RM= Morris Branch Tr,Reach-1,5089
     682     948    1170     718    1433    2858    2151
River Rch & RM= Morris Branch Tr,Reach-1,3565
     738    1029    1273     782    1561    3114    2350
Boundary for River Rch & Prof#=Morris Branch Tr,Reach-1,1
Up Type=0
Dn Type=3
Dn Slope=0.009
Boundary for River Rch & Prof#=Morris Branch Tr,Reach-1,2
Up Type=0
Dn Type=3
Dn Slope=0.009
Boundary for River Rch & Prof#=Morris Branch Tr,Reach-1,3
Up Type=0
Dn Type=3
Dn Slope=0.009
Boundary for River Rch & Prof#=Morris Branch Tr,Reach-1,4
Up Type=0
Dn Type=3
Dn Slope=0.009
Boundary for River Rch & Prof#=Morris Branch Tr,Reach-1,5
Up Type=0
Dn Type=3
Dn Slope=0.009
Boundary for River Rch & Prof#=Morris Branch Tr,Reach-1,6
Up Type=0
Dn Type=3
Dn Slope=0.009
Boundary for River Rch & Prof#=Morris Branch Tr,Reach-1,7
Up Type=0
Dn Type=3
Dn Slope=0.009

--- Morris Branch Tributary 2.g01 (geometry) ---

Geom Title=Existing Conditions

River Reach=Morris Branch Tr,Reach-1
Reach XY= 30
      2308429.00      7107010.00      2308629.00      7106867.08
      2308777.55      7106956.96      2309092.65      7106746.74
      2309172.60      7106617.62      2309270.98      7106612.84
      2309900.97      7107659.36      2310145.29      7107828.18
      2310375.15      7108124.98      2310575.42      7108601.54
      2311043.77      7108791.80      2311327.89      7108777.51
      2311423.94      7108920.52      2311611.47      7108815.17
      2311649.35      7108677.05      2311771.35      7108707.79
      2311730.11      7108799.73      2311784.85      7108858.51
      2312031.44      7108765.39      2312127.38      7108866.03
      2312079.08      7108994.61      2312159.65      7109165.59
      2312089.25      7109348.38      2312299.24      7109321.19
      2312144.74      7109470.18      2312159.33      7109641.49
      2312282.95      7109618.83      2312341.22      7109752.78
      2312432.85      7109709.62      2312579.00      7109860.00

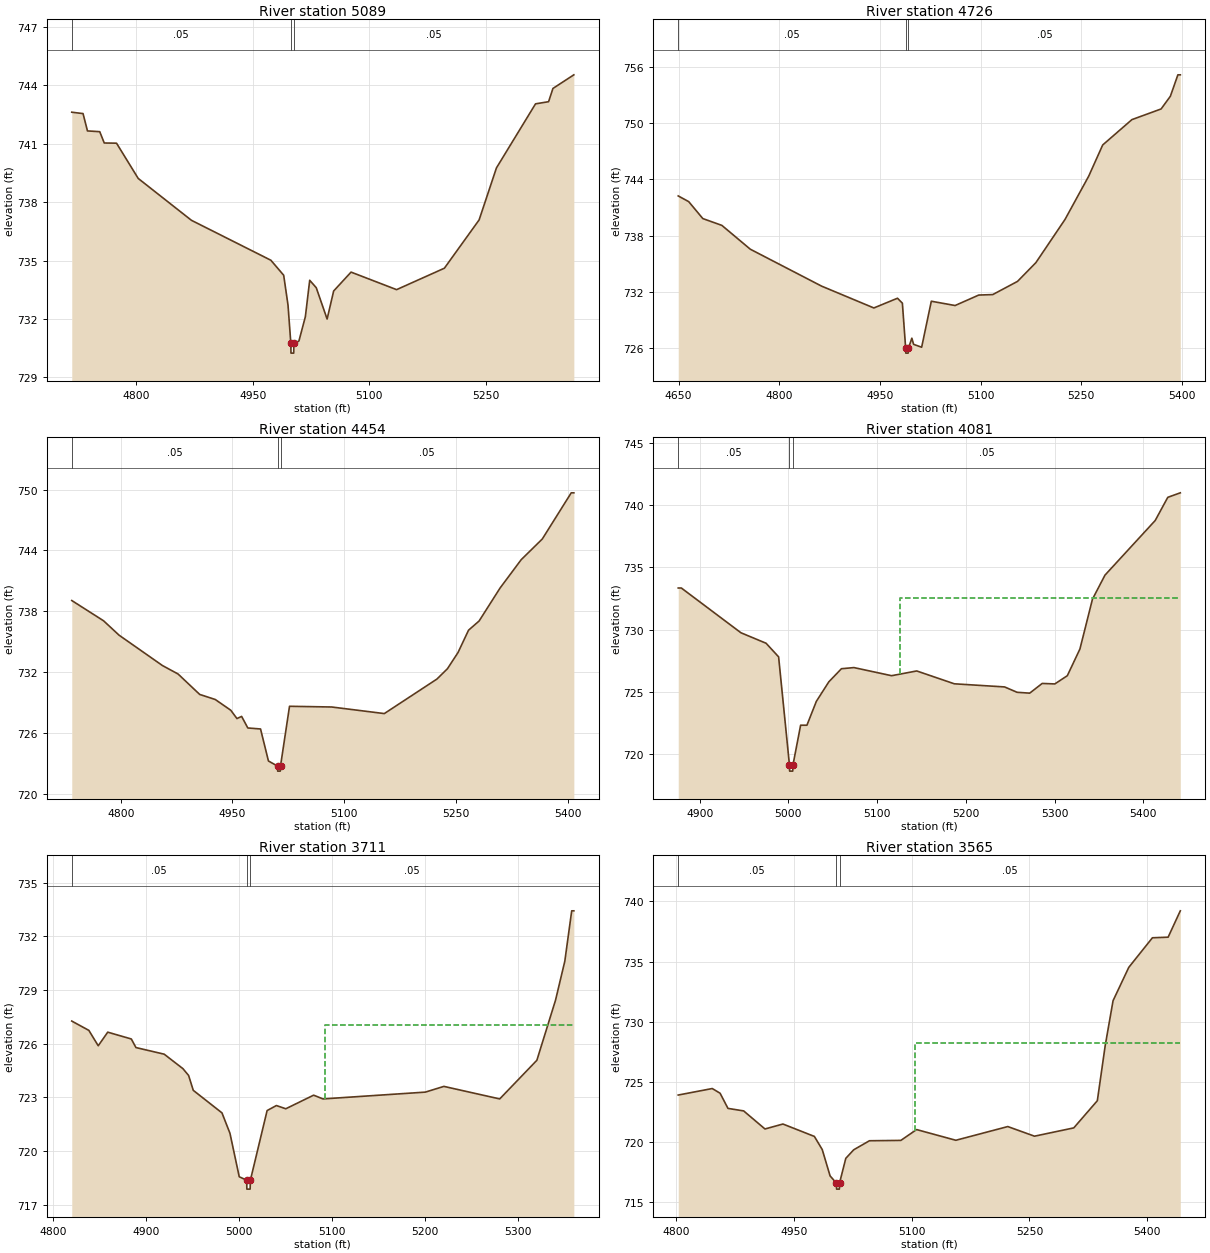
Type RM Length L Ch R = 1,5089,363,363,363
BEGIN DESCRIPTION:
Morris Branch Tributary 2 5.0
END DESCRIPTION:
XS GIS Cut Line= 3
      2309844.92      7107994.23      2309979.00      7107760.00
      2310147.38      7107423.58
#Sta/Elev= 30
  4717.1  742.62  4731.6  742.55  4737.3  741.66  4753.1  741.62  4758.9  741.04
  4774.7  741.03  4802.6  739.22  4871.1  737.07  4973.3  735.02  4989.8  734.25
  4995.4  732.71  4999.0  730.75  4999.2  730.25  5002.7  730.25  5003.0  730.75
  5009.4  730.87  5017.7  732.12  5023.3  733.99  5031.7  733.61  5045.7  732.00
  5054.1  733.44  5076.5  734.41  5135.1  733.51  5196.6  734.61  5241.3  737.09
  5263.6  739.76  5313.9  743.05  5330.7  743.16  5336.3  743.84  5363.2  744.54
#Mann=3,-1,0
  4717.1    0.05       0  4999.0    0.04       0  5003.0    0.05       0
Bank Sta=4999,5003
Exp/Cntr=0.3,0.1

Type RM Length L Ch R = 1,4726,272,272,272
BEGIN DESCRIPTION:
Morris Branch Tributary 2 4.0
END DESCRIPTION:
XS GIS Cut Line= 3
      2310012.85      7108225.86      2310255.85      7107971.32
      2310498.40      7107658.30
#Sta/Elev= 30
  4649.5  742.24  4665.1  741.63  4686.1  739.82  4714.5  739.09  4756.9  736.54
  4863.2  732.59  4940.9  730.26  4976.1  731.30  4983.4  730.77  4988.3  725.93
  4988.5  725.43  4992.0  725.43  4992.3  725.93  4997.5  727.03  5000.1  726.37
  5012.1  726.06  5026.5  730.98  5061.9  730.52  5097.2  731.64  5118.0  731.69
  5154.9  733.10  5182.2  735.10  5225.7  739.73  5261.0  744.36  5281.8  747.69
  5325.3  750.40  5368.8  751.54  5382.6  752.90  5393.8  755.19  5397.4  755.19
#Mann=3,-1,0
  4649.5    0.05       0  4988.3    0.04       0  4992.3    0.05       0
Bank Sta=4988.3,4992.3
Exp/Cntr=0.3,0.1

Type RM Length L Ch R = 1,4454,373,373,373
BEGIN DESCRIPTION:
Morris Branch Tributary 2 3.0
END DESCRIPTION:
XS GIS Cut Line= 3
      2310179.03      7108359.98      2310379.00      7108210.00
      2310678.98      7107910.02
#Sta/Elev= 30
  4734.2  739.06  4776.9  737.06  4797.7  735.64  4856.0  732.64  4876.9  731.81
  4906.0  729.79  4926.9  729.29  4947.7  728.23  4956.0  727.41  4962.3  727.62
  4970.6  726.48  4987.7  726.38  4998.3  723.22  5010.5  722.72  5010.7  722.22
  5014.2  722.22  5014.5  722.72  5026.6  728.62  5083.2  728.55  5153.9  727.90
  5224.6  731.31  5238.7  732.33  5252.9  733.93  5267.0  736.13  5281.2  737.04
  5309.4  740.30  5337.7  743.09  5366.0  745.13  5404.9  749.69  5408.4  749.69
#Mann=3,-1,0
  4734.2    0.05       0  5010.5    0.04       0  5014.5    0.05       0
Bank Sta=5010.5,5014.5
Exp/Cntr=0.3,0.1

Type RM Length L Ch R = 1,4081,370,370,370
BEGIN DESCRIPTION:
Morris Branch Tributary 2 2.0
END DESCRIPTION:
XS GIS Cut Line= 3
      2310428.99      7108610.01      2310529.00      7108510.00
      2310829.00      7108210.00
#Sta/Elev= 30
  4875.9  733.34  4879.4  733.34  4946.6  729.75  4974.9  728.91  4989.0  727.82
  5001.2  719.16  5001.4  718.66  5004.9  718.66  5005.2  719.16  5013.8  722.34
  5020.9  722.34  5031.5  724.25  5045.6  725.82  5059.8  726.87  5073.9  726.96
  5116.3  726.31  5144.6  726.69  5187.0  725.66  5243.6  725.41  5257.7  724.98
  5271.9  724.91  5286.0  725.69  5300.2  725.65  5314.3  726.31  5328.5  728.45
  5342.6  732.44  5356.7  734.37  5413.3  738.75  5427.5  740.61  5441.6  740.97
#Mann=3,-1,0
  4875.9    0.05       0  5001.2   0.033       0  5005.2    0.05       0
#XS Ineff=2,0
    0.00 4874.10  732.57 5125.90    0.00  732.57
Permanent Ineff=
       F       F
Bank Sta=5001.2,5005.2
Exp/Cntr=0.3,0.1

Type RM Length L Ch R = 1,3711,146,146,146
BEGIN DESCRIPTION:
Mapping XS bdafe241
END DESCRIPTION:
XS GIS Cut Line= 3
      2310793.77      7108888.18      2310819.57      7108728.60
      2310840.08      7108350.31
#Sta/Elev= 30
  4820.1  727.26  4838.5  726.74  4848.6  725.88  4858.8  726.64  4884.2  726.26
  4889.2  725.78  4919.6  725.41  4939.8  724.60  4945.9  724.22  4950.9  723.39
  4981.8  722.13  4990.4  720.99  5000.4  718.56  5008.4  718.37  5008.6  717.87
  5012.1  717.87  5012.4  718.37  5030.4  722.26  5040.4  722.54  5050.5  722.36
  5080.5  723.12  5090.5  722.91  5200.7  723.29  5220.7  723.61  5280.8  722.91
  5320.8  725.07  5340.9  728.43  5350.9  730.61  5358.3  733.42  5360.6  733.42
#Mann=3,-1,0
  4820.1    0.05       0  5008.4    0.04       0  5012.4    0.05       0
#XS Ineff=2,0
       0                 5093.10    0.00  727.04
Permanent Ineff=
       F       F
Bank Sta=5008.4,5012.4
Exp/Cntr=0.3,0.1

Type RM Length L Ch R = 1,3565,203,203,203
BEGIN DESCRIPTION:
Mapping XS 320105ea
END DESCRIPTION:
XS GIS Cut Line= 2
      2310950.35      7108953.23      2310971.10      7108314.47
#Sta/Elev= 30
  4802.9  723.91  4846.2  724.45  4856.2  724.06  4866.2  722.80  4886.2  722.59
  4913.3  721.09  4936.2  721.50  4976.2  720.47  4986.2  719.38  4996.2  717.19
  5004.2  716.59  5004.5  716.09  5008.0  716.09  5008.2  716.59  5016.2  718.65
  5026.3  719.36  5046.3  720.11  5086.3  720.14  5106.3  721.04  5156.3  720.15
  5222.4  721.29  5256.4  720.49  5306.4  721.18  5336.4  723.44  5346.4  728.02
  5356.4  731.75  5376.4  734.52  5406.5  736.98  5426.5  737.03  5442.0  739.22
#Mann=3,-1,0
  4802.9    0.05       0  5004.2    0.04       0  5008.2    0.05       0
#XS Ineff=2,0
       0                 5103.90    0.00  728.26
Permanent Ineff=
       F       F
Bank Sta=5004.2,5008.2
Exp/Cntr=0.3,0.1

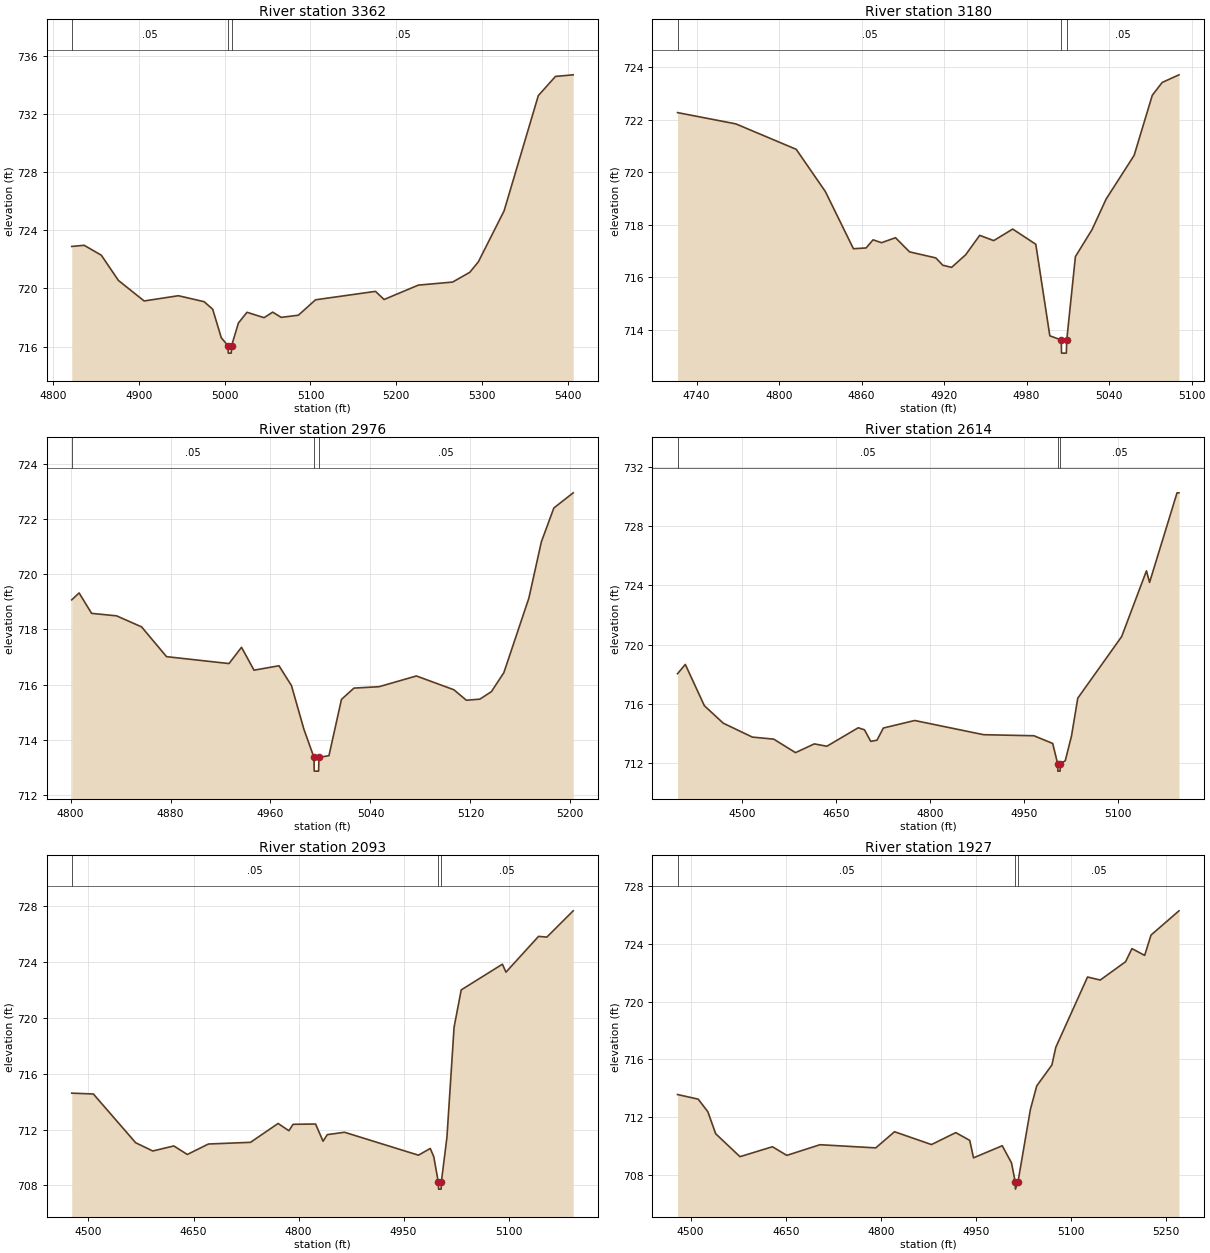
Type RM Length L Ch R = 1,3362,182,182,182
BEGIN DESCRIPTION:
Mapping XS 2013a1d7
END DESCRIPTION:
XS GIS Cut Line= 2
      2311151.32      7108984.48      2311151.73      7108399.28
#Sta/Elev= 30
  4821.4  722.89  4835.9  722.97  4855.9  722.29  4875.9  720.55  4905.9  719.14
  4945.9  719.50  4975.9  719.09  4985.9  718.57  4995.9  716.61  5003.9  716.05
  5004.1  715.55  5007.6  715.55  5007.9  716.05  5015.9  717.62  5025.9  718.36
  5045.9  717.99  5055.9  718.37  5065.9  718.01  5085.9  718.16  5105.9  719.22
  5175.9  719.80  5185.9  719.24  5225.9  720.23  5265.9  720.44  5285.9  721.11
  5295.9  721.83  5325.9  725.33  5365.9  733.27  5385.9  734.59  5406.6  734.70
#Mann=3,-1,0
  4821.4    0.05       0  5003.9    0.04       0  5007.9    0.05       0
Bank Sta=5003.9,5007.9
Exp/Cntr=0.3,0.1

Type RM Length L Ch R = 1,3180,204,204,204
BEGIN DESCRIPTION:
Mapping XS 75616170
END DESCRIPTION:
XS GIS Cut Line= 3
      2311217.01      7108993.19      2311278.29      7108984.74
      2311338.25      7108688.01
#Sta/Elev= 30
  4726.2  722.28  4768.6  721.85  4812.5  720.88  4833.7  719.27  4854.1  717.09
  4863.3  717.12  4868.4  717.43  4874.5  717.32  4884.7  717.51  4894.9  716.97
  4914.0  716.74  4919.1  716.46  4925.5  716.38  4935.7  716.86  4945.9  717.60
  4956.1  717.40  4969.9  717.84  4986.7  717.26  4996.9  713.77  5005.2  713.61
  5005.4  713.11  5008.9  713.11  5009.2  713.61  5015.5  716.79  5027.6  717.82
  5037.8  718.98  5058.2  720.65  5071.4  722.94  5078.6  723.43  5090.8  723.72
#Mann=3,-1,0
  4726.2    0.05       0  5005.2    0.04       0  5009.2    0.05       0
Bank Sta=5005.2,5009.2
Exp/Cntr=0.3,0.1

Type RM Length L Ch R = 1,2976,362,362,362
BEGIN DESCRIPTION:
Mapping XS abcc7f43
END DESCRIPTION:
XS GIS Cut Line= 2
      2311449.91      7109115.85      2311442.55      7108714.52
#Sta/Elev= 30
  4800.9  719.07  4806.8  719.32  4816.8  718.58  4836.8  718.49  4856.8  718.09
  4876.8  717.01  4926.8  716.76  4936.8  717.35  4946.8  716.52  4966.8  716.68
  4976.8  715.96  4986.8  714.37  4994.8  713.36  4995.0  712.86  4998.5  712.86
  4998.8  713.36  5006.8  713.42  5016.8  715.46  5026.8  715.87  5046.8  715.92
  5076.8  716.31  5106.8  715.81  5116.8  715.43  5127.6  715.47  5136.8  715.74
  5146.8  716.43  5166.8  719.13  5176.8  721.17  5186.8  722.40  5202.3  722.95
#Mann=3,-1,0
  4800.9    0.05       0  4994.8    0.04       0  4998.8    0.05       0
Bank Sta=4994.8,4998.8
Exp/Cntr=0.3,0.1

Type RM Length L Ch R = 1,2614,521,521,521
BEGIN DESCRIPTION:
Mapping XS 4275bf12
END DESCRIPTION:
XS GIS Cut Line= 3
      2311476.65      7109129.59      2311644.44      7109109.11
      2311665.59      7108478.70
#Sta/Elev= 30
  4396.9  718.04  4409.3  718.67  4439.7  715.88  4469.8  714.70  4516.2  713.76
  4550.4  713.62  4585.1  712.71  4615.1  713.30  4635.1  713.14  4685.1  714.39
  4695.1  714.25  4705.1  713.47  4715.1  713.55  4725.1  714.37  4775.2  714.88
  4885.2  713.92  4965.3  713.85  4995.3  713.33  5003.2  711.96  5003.5  711.46
  5007.1  711.46  5007.4  711.96  5015.3  712.16  5025.3  713.84  5035.3  716.39
  5105.3  720.55  5144.8  724.99  5149.8  724.21  5193.6  730.26  5196.7  730.26
#Mann=3,-1,0
  4396.9    0.05       0  5003.2   0.033       0  5007.4    0.05       0
Bank Sta=5003.2,5007.4
Exp/Cntr=0.3,0.1

Type RM Length L Ch R = 1,2093,166,166,166
BEGIN DESCRIPTION:
Mapping XS c690d073
END DESCRIPTION:
XS GIS Cut Line= 3
      2311763.51      7109255.27      2311919.06      7108848.34
      2311972.86      7108573.09
#Sta/Elev= 30
  4476.1  714.61  4507.0  714.55  4567.4  711.06  4591.8  710.47  4621.9  710.83
  4641.2  710.22  4671.3  710.97  4731.4  711.09  4770.8  712.44  4786.2  711.92
  4792.2  712.38  4824.3  712.40  4835.0  711.17  4841.0  711.64  4865.7  711.81
  4971.2  710.17  4988.1  710.65  4993.1  710.06  4999.6  708.24  5000.0  707.74
  5003.6  707.74  5003.9  708.24  5011.9  711.45  5022.1  719.33  5032.3  722.00
  5091.1  723.84  5096.2  723.27  5142.7  725.83  5154.6  725.78  5192.2  727.66
#Mann=3,-1,0
  4476.1    0.05       0  4999.6    0.04       0  5003.9    0.05       0
Bank Sta=4999.6,5003.9
Exp/Cntr=0.3,0.1

Type RM Length L Ch R = 1,1927,364,364,364
BEGIN DESCRIPTION:
Mapping XS f782d680
END DESCRIPTION:
XS GIS Cut Line= 3
      2311837.88      7109272.19      2312095.81      7108786.92
      2312084.81      7108545.93
#Sta/Elev= 30
  4479.4  713.57  4512.0  713.25  4527.2  712.38  4539.6  710.85  4577.9  709.26
  4629.1  709.95  4651.7  709.35  4704.1  710.09  4792.0  709.87  4821.6  710.99
  4879.9  710.10  4918.2  710.93  4940.2  710.39  4946.2  709.18  4991.5  710.02
  5006.1  708.83  5012.0  707.51  5012.3  707.01  5016.3  707.51  5035.9  712.54
  5045.9  714.17  5069.8  715.62  5075.9  716.84  5126.0  721.72  5146.0  721.51
  5186.0  722.78  5196.0  723.69  5216.1  723.22  5226.1  724.63  5270.2  726.31
#Mann=3,-1,0
  4479.4    0.05       0  5012.0    0.04       0  5016.3    0.05       0
Bank Sta=5012,5016.3
Exp/Cntr=0.3,0.1

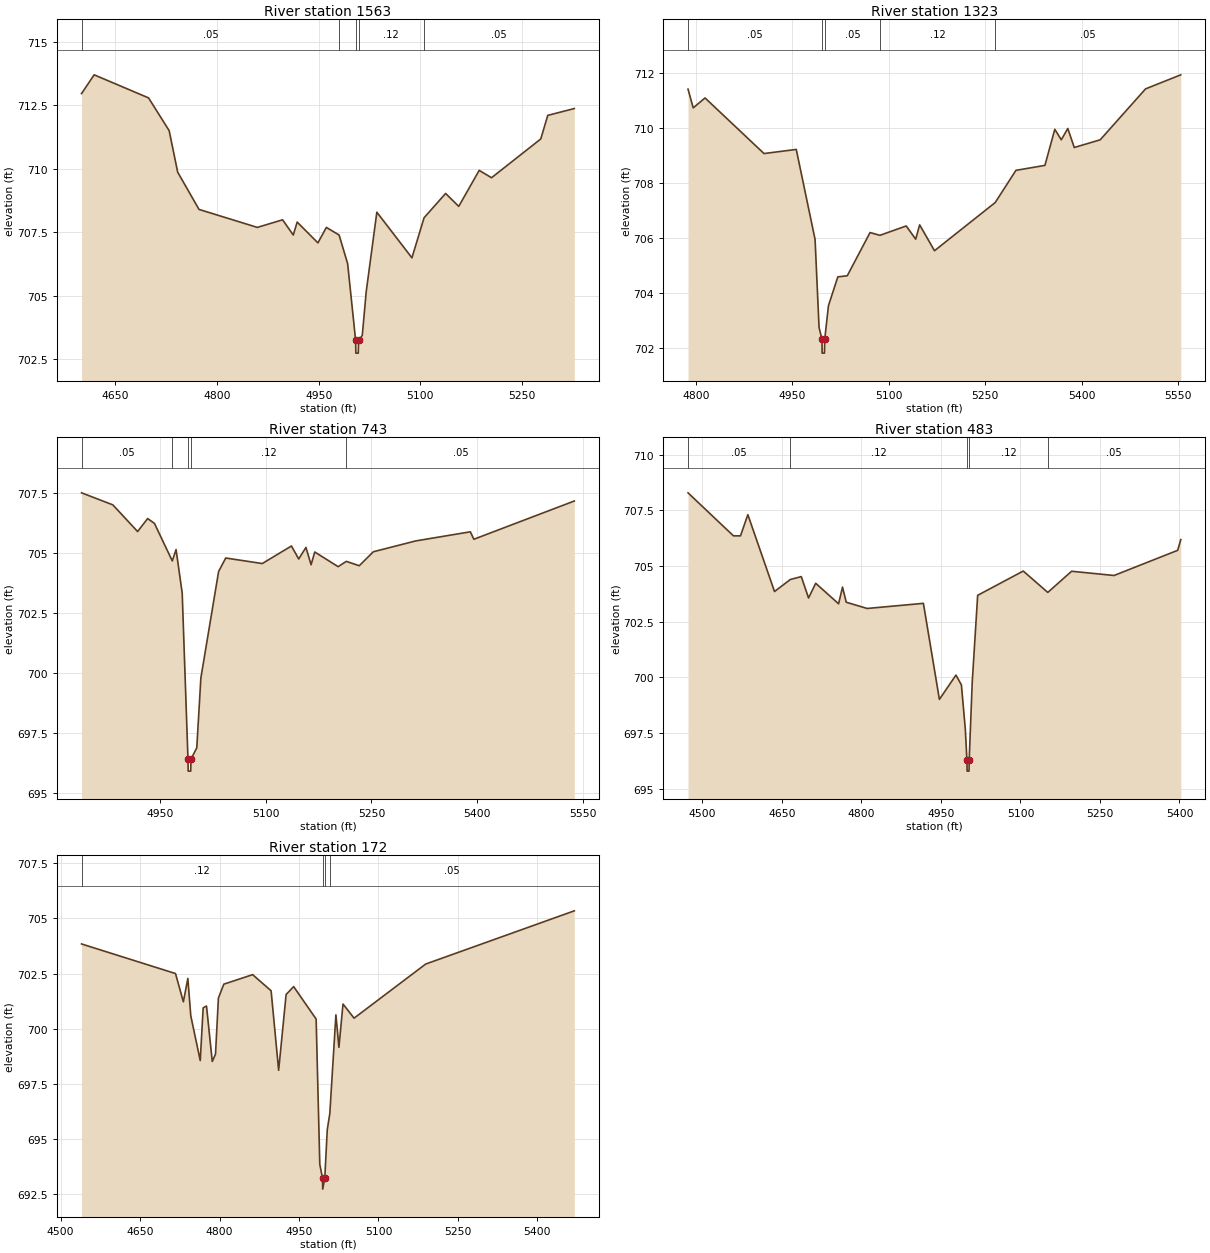
Type RM Length L Ch R = 1,1563,240,240,240
BEGIN DESCRIPTION:
Mapping XS 2c8d5529
END DESCRIPTION:
XS GIS Cut Line= 3
      2311797.18      7109323.86      2312253.21      7109059.30
      2312279.86      7108860.90
#Sta/Elev= 30
  4600.0  712.97  4618.6  713.71  4698.9  712.80  4729.3  711.51  4741.9  709.87
  4773.4  708.40  4859.5  707.69  4896.8  707.99  4912.5  707.39  4918.3  707.90
  4948.9  707.08  4961.4  707.69  4980.2  707.39  4992.8  706.26  5004.6  703.23
  5004.9  702.73  5008.5  702.73  5008.9  703.23  5014.4  703.43  5020.2  705.15
  5035.9  708.29  5087.7  706.49  5105.6  708.07  5137.4  709.03  5156.8  708.52
  5187.0  709.94  5205.2  709.65  5277.9  711.18  5288.2  712.11  5327.4  712.38
#Mann=5,-1,0
  4600.0    0.05       0  4980.2    0.12       0  5004.6    0.07       0
  5008.9    0.12       0  5105.6    0.05       0
Bank Sta=5004.6,5008.9
Exp/Cntr=0.3,0.1

Type RM Length L Ch R = 1,1323,580,580,580
BEGIN DESCRIPTION:
Mapping XS 7807bcd2
END DESCRIPTION:
XS GIS Cut Line= 4
      2311901.24      7109367.16      2312011.54      7109397.76
      2312243.45      7109227.09      2312292.46      7108865.71
#Sta/Elev= 30
  4787.4  711.40  4795.5  710.72  4813.9  711.08  4905.7  709.06  4955.9  709.21
  4985.2  705.94  4991.4  702.74  4995.9  702.31  4996.2  701.81  4999.8  701.81
  5000.2  702.31  5006.0  703.53  5020.6  704.58  5035.3  704.62  5070.8  706.19
  5086.2  706.09  5127.1  706.43  5141.8  705.95  5148.0  706.47  5171.1  705.53
  5265.6  707.28  5297.9  708.45  5343.0  708.63  5358.4  709.94  5368.5  709.56
  5378.6  709.97  5388.7  709.28  5429.1  709.56  5499.7  711.41  5554.5  711.92
#Mann=5,-1,0
  4787.4    0.05       0  4995.9    0.04       0  5000.2    0.05       0
  5086.2    0.12       0  5265.6    0.05       0
Bank Sta=4995.9,5000.2
Exp/Cntr=0.3,0.1

Type RM Length L Ch R = 1,743,260,260,260
BEGIN DESCRIPTION:
Mapping XS 5237eb4b
END DESCRIPTION:
XS GIS Cut Line= 4
      2312014.13      7109492.42      2312090.89      7109561.86
      2312335.60      7109497.82      2312350.16      7109154.99
#Sta/Elev= 30
  4838.5  707.50  4882.9  707.00  4918.1  705.89  4932.3  706.43  4942.0  706.23
  4967.3  704.67  4972.7  705.14  4981.4  703.33  4989.6  696.43  4989.9  695.93
  4993.5  695.93  4993.9  696.43  5002.1  696.90  5007.9  699.80  5033.1  704.23
  5043.2  704.79  5095.1  704.56  5136.5  705.29  5146.8  704.75  5157.1  705.23
  5164.4  704.51  5169.6  705.04  5202.8  704.43  5214.4  704.65  5232.8  704.47
  5252.8  705.05  5312.9  705.50  5390.5  705.88  5395.5  705.57  5538.1  707.16
#Mann=5,-1,0
  4838.5    0.05       0  4967.3    0.12       0  4989.6    0.07       0
  4993.9    0.12       0  5214.4    0.05       0
Bank Sta=4989.6,4993.9
Exp/Cntr=0.3,0.1

Type RM Length L Ch R = 1,483,311,311,311
BEGIN DESCRIPTION:
Mapping XS 376852b3
END DESCRIPTION:
XS GIS Cut Line= 6
      2311966.58      7109472.80      2312158.54      7109711.58
      2312272.10      7109730.44      2312306.78      7109572.01
      2312362.10      7109486.34      2312371.27      7109244.16
#Sta/Elev= 30
  4472.8  708.28  4558.5  706.35  4571.8  706.35  4585.7  707.30  4636.0  703.85
  4665.8  704.39  4686.5  704.52  4700.2  703.56  4713.7  704.22  4756.9  703.30
  4764.3  704.05  4771.3  703.37  4810.8  703.09  4916.9  703.32  4947.1  699.01
  4978.3  700.10  4988.6  699.66  4996.0  697.67  4999.0  696.29  4999.4  695.79
  5003.0  695.79  5003.3  696.29  5009.0  699.77  5019.3  703.68  5105.3  704.77
  5151.6  703.81  5196.5  704.76  5276.6  704.57  5396.7  705.70  5402.5  706.18
#Mann=5,-1,0
  4472.8    0.05       0  4665.8    0.12       0  4999.0    0.07       0
  5003.3    0.12       0  5151.6    0.05       0
Bank Sta=4999,5003.3
Exp/Cntr=0.3,0.1

Type RM Length L Ch R = 1,172,0,0,0
BEGIN DESCRIPTION:
Morris Branch Tributary 2 1.0
END DESCRIPTION:
XS GIS Cut Line= 4
      2312073.03      7109693.03      2312374.96      7109825.64
      2312484.88      7109722.91      2312360.89      7109290.24
#Sta/Elev= 30
  4539.4  703.84  4716.8  702.50  4731.6  701.22  4740.1  702.28  4745.6  700.59
  4763.5  698.56  4769.0  700.95  4775.3  701.03  4786.2  698.52  4792.3  698.85
  4797.8  701.39  4808.0  702.02  4862.4  702.45  4897.3  701.72  4911.5  698.12
  4925.6  701.55  4939.8  701.91  4982.3  700.44  4989.2  693.86  4994.3  693.24
  4994.7  692.74  4998.6  693.24  5003.3  695.43  5008.1  696.16  5019.6  700.63
  5025.3  699.16  5033.0  701.12  5053.9  700.48  5189.1  702.93  5469.7  705.34
#Mann=4,-1,0
  4539.4    0.12       0  4994.3    0.07       0  4998.6    0.12       0
  5008.1    0.05       0
Bank Sta=4994.3,4998.6
Exp/Cntr=0.3,0.1

Chan Stop Cuts=-1