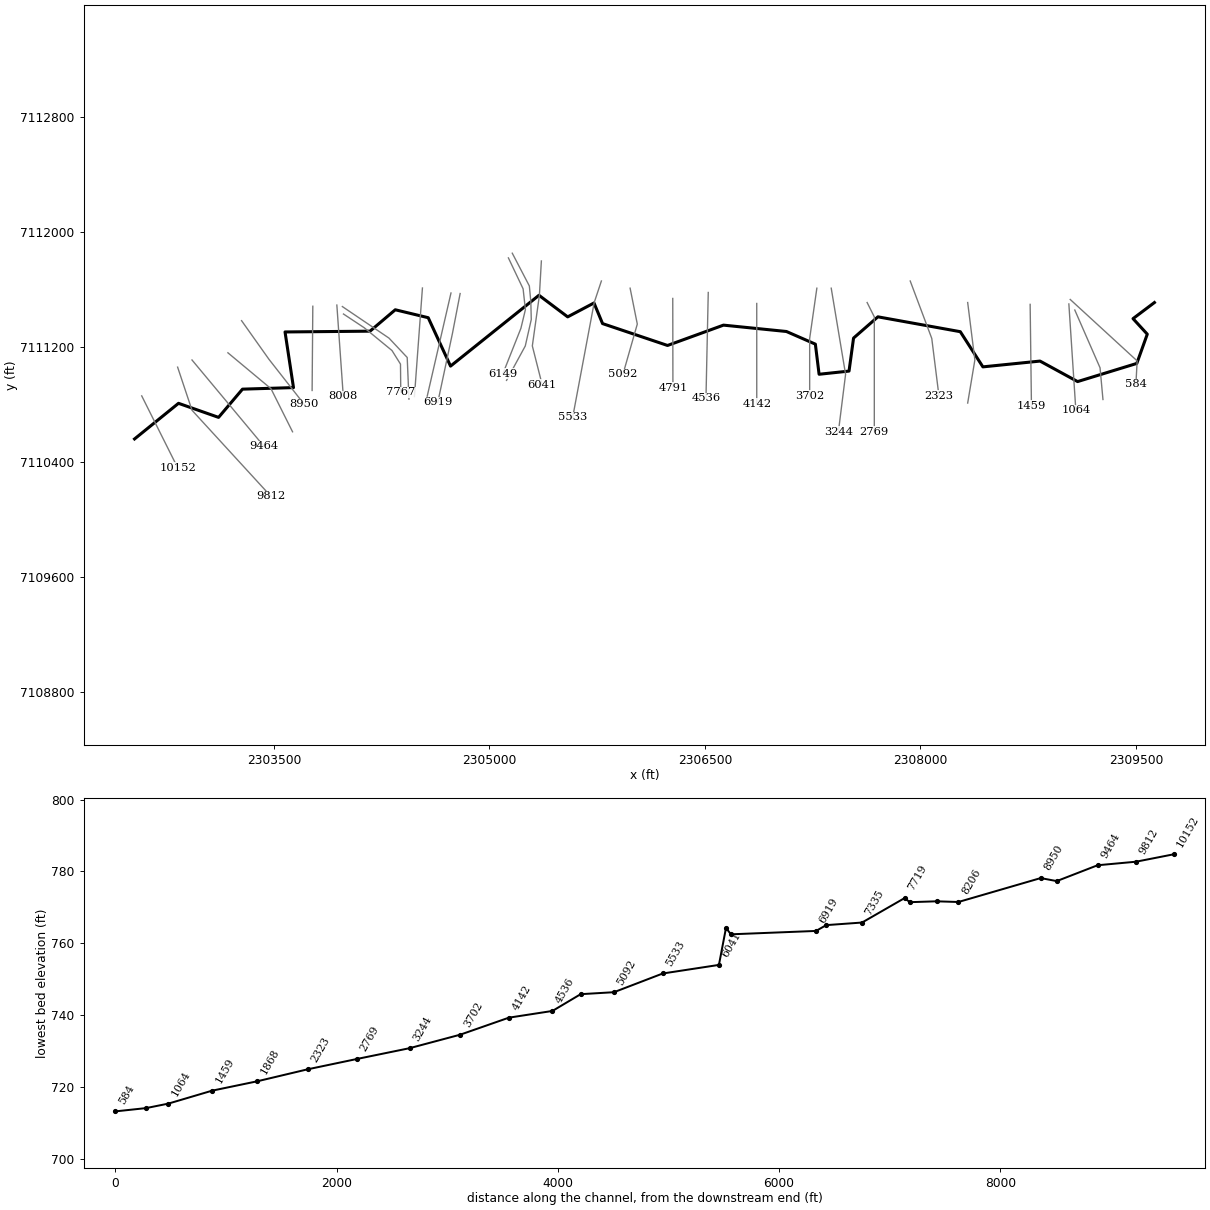
--- Morris Branch Tributary 4.prj (project) ---

Proj Title=Morris Branch Tributary 4 Base Level Engineering
Current Plan=p01
Default Exp/Contr=0.3,0.1
English Units
Geom File=g01
Flow File=f01
Plan File=p01
BEGIN DESCRIPTION:
Morris Branch Tributary 4
END DESCRIPTION:

--- Morris Branch Tributary 4.p01 (plan) ---

Plan Title=Multiple Run
Short Identifier=Multiple
Geom File=g01
Flow File=f01
Subcritical Flow
K Sum by GR= 0
Std Step Tol= 0.01
Critical Tol= 0.01
Num of Std Step Trials= 20
Max Error Tol= 0.3
Flow Tol Ratio= 0.001
Split Flow NTrial= 30
Split Flow Tol= 0.02
Split Flow Ratio= 0.02
Log Output Level= 0
Friction Slope Method= 1
Unsteady Friction Slope Method= 2
Unsteady Bridges Friction Slope Method= 1
Parabolic Critical Depth
Global Vel Dist=  1 , 1 , 1
Global Log Level= 0
CheckData=True
Encroach Param= -1, 0, 0, 0
BEGIN DESCRIPTION:
Multiple Run
END DESCRIPTION:

--- Morris Branch Tributary 4.f01 (steady flow) ---

Flow Title=Multiple
Number of Profiles=7
Profile Names=10-year,25-year,50-year,1pct_min,100-year,1pct_plu,500-year
River Rch & RM= Morris Branch Tr,Reach-1,10152
     678     942    1162     713    1422    2838    2133
River Rch & RM= Morris Branch Tr,Reach-1,6149
     882    1241    1545     954    1903    3797    2898
Boundary for River Rch & Prof#=Morris Branch Tr,Reach-1,1
Up Type=0
Dn Type=3
Dn Slope=0.005
Boundary for River Rch & Prof#=Morris Branch Tr,Reach-1,2
Up Type=0
Dn Type=3
Dn Slope=0.005
Boundary for River Rch & Prof#=Morris Branch Tr,Reach-1,3
Up Type=0
Dn Type=3
Dn Slope=0.005
Boundary for River Rch & Prof#=Morris Branch Tr,Reach-1,4
Up Type=0
Dn Type=3
Dn Slope=0.005
Boundary for River Rch & Prof#=Morris Branch Tr,Reach-1,5
Up Type=0
Dn Type=3
Dn Slope=0.005
Boundary for River Rch & Prof#=Morris Branch Tr,Reach-1,6
Up Type=0
Dn Type=3
Dn Slope=0.005
Boundary for River Rch & Prof#=Morris Branch Tr,Reach-1,7
Up Type=0
Dn Type=3
Dn Slope=0.005

--- Morris Branch Tributary 4.g01 (geometry) ---

Geom Title=Existing Conditions

River Reach=Morris Branch Tr,Reach-1
Reach XY= 30
      2302529.00      7110560.00      2302835.11      7110808.21
      2303113.95      7110710.31      2303280.64      7110906.85
      2303635.57      7110917.70      2303576.73      7111305.13
      2304168.38      7111310.60      2304344.16      7111459.63
      2304573.42      7111404.42      2304728.90      7111067.28
      2305344.48      7111560.55      2305544.35      7111410.19
      2305727.57      7111507.01      2305787.16      7111363.37
      2306239.44      7111211.04      2306628.90      7111352.67
      2307067.17      7111308.34      2307268.66      7111220.24
      2307294.54      7111010.54      2307503.03      7111032.65
      2307534.46      7111262.45      2307703.96      7111410.50
      2308277.61      7111306.97      2308434.84      7111062.05
      2308832.67      7111102.31      2309094.18      7110959.57
      2309506.33      7111085.99      2309579.30      7111289.66
      2309480.10      7111397.93      2309629.00      7111510.00

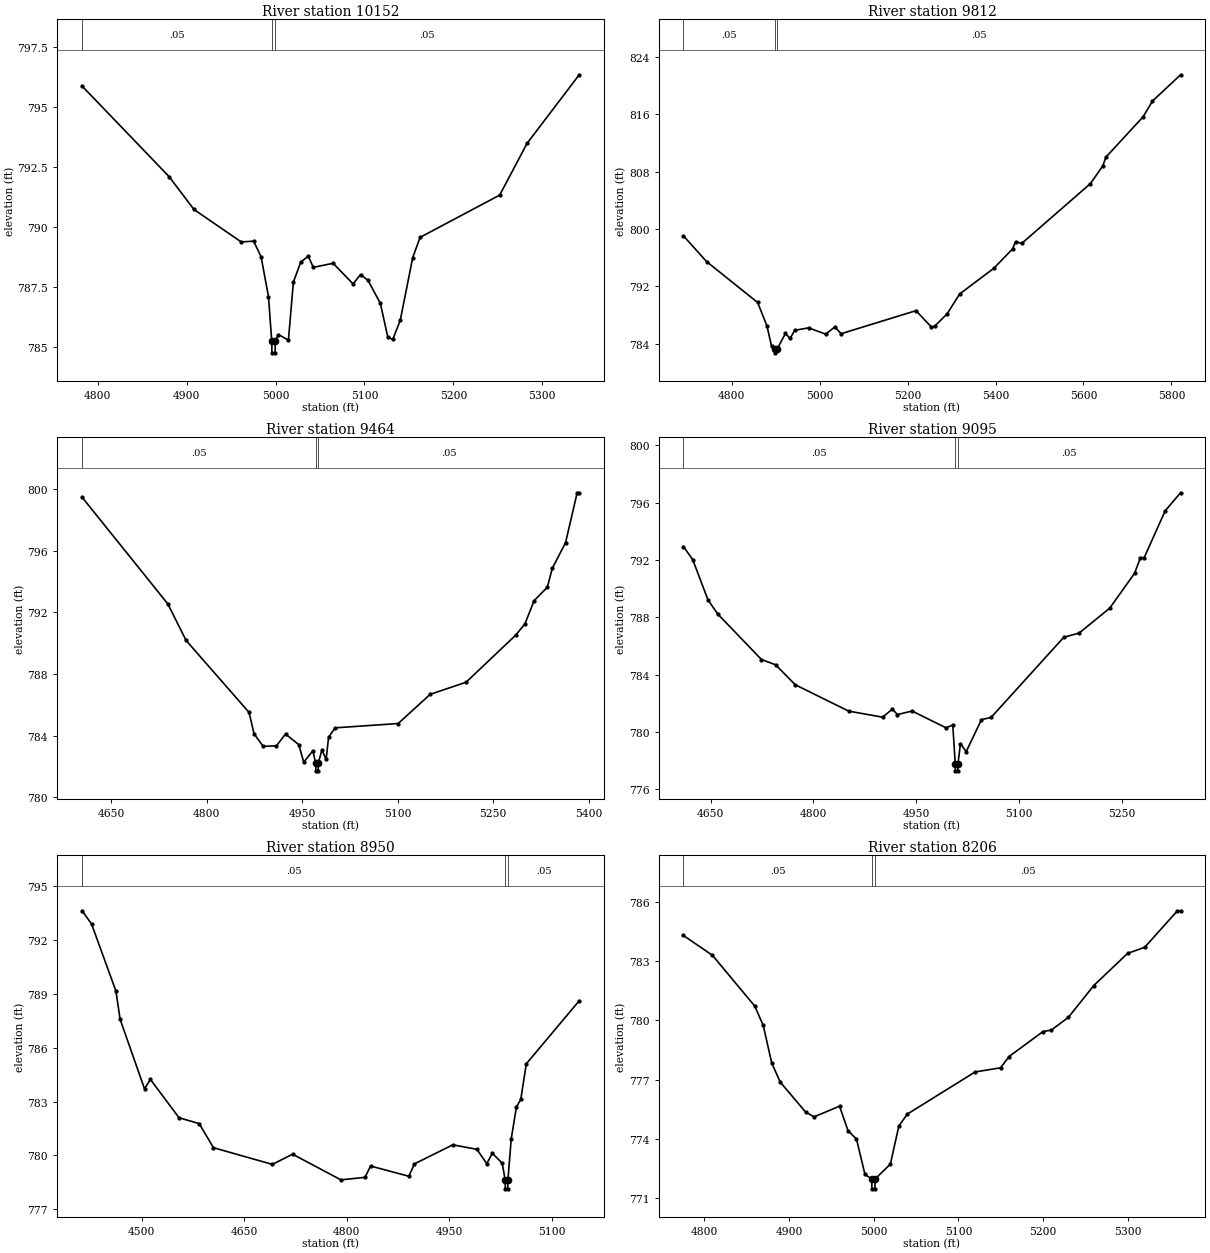
Type RM Length L Ch R = 1,10152,340,340,340
BEGIN DESCRIPTION:
Morris Branch Tributary 4 20.0
END DESCRIPTION:
XS GIS Cut Line= 3
      2302578.99      7110860.02      2302679.00      7110660.00
      2302828.98      7110360.03
#Sta/Elev= 30
  4782.5  795.87  4880.3  792.10  4908.3  790.73  4961.4  789.38  4975.4  789.41
  4983.8  788.76  4992.1  787.10  4995.7  785.26  4996.0  784.76  4999.5  784.76
  4999.7  785.26  5003.3  785.52  5014.5  785.29  5020.1  787.71  5028.5  788.55
  5036.9  788.78  5042.5  788.32  5064.8  788.49  5087.2  787.63  5095.6  788.02
  5104.0  787.78  5117.9  786.82  5126.3  785.41  5131.9  785.32  5140.3  786.12
  5154.3  788.73  5162.6  789.57  5252.1  791.33  5282.8  793.48  5341.5  796.34
#Mann=3,-1,0
  4782.5    0.05       0  4995.7    0.04       0  4999.7    0.05       0
Bank Sta=4995.7,4999.7
Exp/Cntr=0.3,0.1

Type RM Length L Ch R = 1,9812,348,348,348
BEGIN DESCRIPTION:
Morris Branch Tributary 4 19.0
END DESCRIPTION:
XS GIS Cut Line= 3
      2302828.99      7111060.03      2302929.00      7110760.00
      2303479.00      7110160.00
#Sta/Elev= 30
  4690.5  799.04  4743.2  795.44  4859.2  789.73  4880.3  786.47  4890.8  783.65
  4899.4  783.20  4899.6  782.70  4903.4  783.20  4922.4  785.41  4933.0  784.71
  4943.5  785.84  4975.1  786.19  5013.9  785.31  5034.8  786.32  5049.0  785.37
  5219.2  788.59  5254.3  786.30  5261.7  786.41  5290.1  788.16  5318.5  790.92
  5396.2  794.51  5438.7  797.20  5445.5  798.23  5459.7  797.98  5615.7  806.33
  5644.0  808.81  5650.8  810.01  5735.9  815.69  5756.9  817.86  5820.7  821.53
#Mann=3,-1,0
  4690.5    0.05       0  4899.4   0.033       0  4903.4    0.05       0
Bank Sta=4899.4,4903.4
Exp/Cntr=0.3,0.1

Type RM Length L Ch R = 1,9464,369,369,369
BEGIN DESCRIPTION:
Morris Branch Tributary 4 18.0
END DESCRIPTION:
XS GIS Cut Line= 3
      2302929.00      7111110.00      2303179.00      7110810.00
      2303428.98      7110510.02
#Sta/Elev= 30
  4604.4  799.46  4739.1  792.54  4767.8  790.17  4866.7  785.50  4874.5  784.12
  4888.8  783.30  4909.7  783.33  4924.0  784.10  4944.8  783.41  4952.6  782.27
  4966.9  783.01  4971.4  782.21  4971.7  781.71  4975.2  781.71  4975.4  782.21
  4981.2  783.06  4987.8  782.46  4991.7  783.90  5002.1  784.50  5101.0  784.78
  5151.1  786.67  5207.7  787.46  5285.8  790.52  5300.2  791.25  5314.5  792.75
  5335.3  793.62  5343.1  794.85  5363.9  796.51  5382.2  799.75  5385.4  799.75
#Mann=3,-1,0
  4604.4    0.05       0  4971.4   0.033       0  4975.4    0.05       0
Bank Sta=4971.4,4975.4
Exp/Cntr=0.3,0.1

Type RM Length L Ch R = 1,9095,145,145,145
BEGIN DESCRIPTION:
Morris Branch Tributary 4 17.0
END DESCRIPTION:
XS GIS Cut Line= 3
      2303179.03      7111159.98      2303479.00      7110910.00
      2303629.01      7110609.99
#Sta/Elev= 30
  4610.1  792.93  4623.7  792.02  4645.9  789.22  4660.2  788.23  4724.0  785.06
  4744.8  784.69  4773.4  783.30  4851.5  781.46  4901.0  781.04  4915.3  781.61
  4922.5  781.22  4944.0  781.47  4993.4  780.30  5003.4  780.49  5007.0  777.80
  5007.2  777.30  5010.7  777.30  5011.0  777.80  5014.6  779.20  5022.9  778.63
  5045.3  780.87  5059.3  781.02  5165.5  786.61  5187.8  786.90  5232.6  788.64
  5268.9  791.07  5277.3  792.15  5282.9  792.16  5313.6  795.43  5336.0  796.68
#Mann=3,-1,0
  4610.1    0.05       0  5007.0   0.033       0  5011.0    0.05       0
Bank Sta=5007,5011
Exp/Cntr=0.3,0.1

Type RM Length L Ch R = 1,8950,744,744,744
BEGIN DESCRIPTION:
Mapping XS 10f00e16
END DESCRIPTION:
XS GIS Cut Line= 3
      2303274.20      7111383.71      2303464.47      7111115.15
      2303709.84      7110801.70
#Sta/Elev= 30
  4412.9  793.62  4426.7  792.89  4462.4  789.15  4468.5  787.58  4504.2  783.71
  4512.9  784.23  4554.7  782.10  4584.2  781.77  4605.1  780.43  4691.3  779.50
  4720.8  780.07  4791.5  778.64  4826.8  778.78  4834.9  779.41  4890.9  778.84
  4899.1  779.53  4955.1  780.59  4990.4  780.34  5004.9  779.54  5013.0  780.12
  5027.4  779.57  5031.8  778.64  5032.0  778.14  5035.5  778.14  5035.8  778.64
  5040.7  780.94  5048.3  782.70  5054.6  783.12  5062.7  785.10  5140.1  788.61
#Mann=3,-1,0
  4412.9    0.05       0  5031.8   0.033       0  5035.8    0.05       0
Bank Sta=5031.8,5035.8
Exp/Cntr=0.3,0.1

Type RM Length L Ch R = 1,8206,198,198,198
BEGIN DESCRIPTION:
Mapping XS a8dfa030
END DESCRIPTION:
XS GIS Cut Line= 2
      2303770.06      7111484.15      2303765.26      7110897.57
#Sta/Elev= 30
  4775.5  784.29  4809.7  783.29  4859.7  780.72  4869.7  779.74  4879.7  777.84
  4889.7  776.88  4919.7  775.36  4929.7  775.12  4959.7  775.66  4969.7  774.42
  4979.7  774.00  4989.7  772.21  4997.7  771.98  4997.9  771.48  5001.4  771.48
  5001.7  771.98  5019.7  772.73  5029.7  774.66  5039.7  775.26  5119.7  777.39
  5149.7  777.60  5159.7  778.17  5199.7  779.43  5209.7  779.51  5229.7  780.15
  5259.7  781.76  5299.7  783.39  5319.7  783.69  5358.4  785.54  5362.1  785.54
#Mann=3,-1,0
  4775.5    0.05       0  4997.7   0.033       0  5001.7    0.05       0
Bank Sta=4997.7,5001.7
Exp/Cntr=0.3,0.1

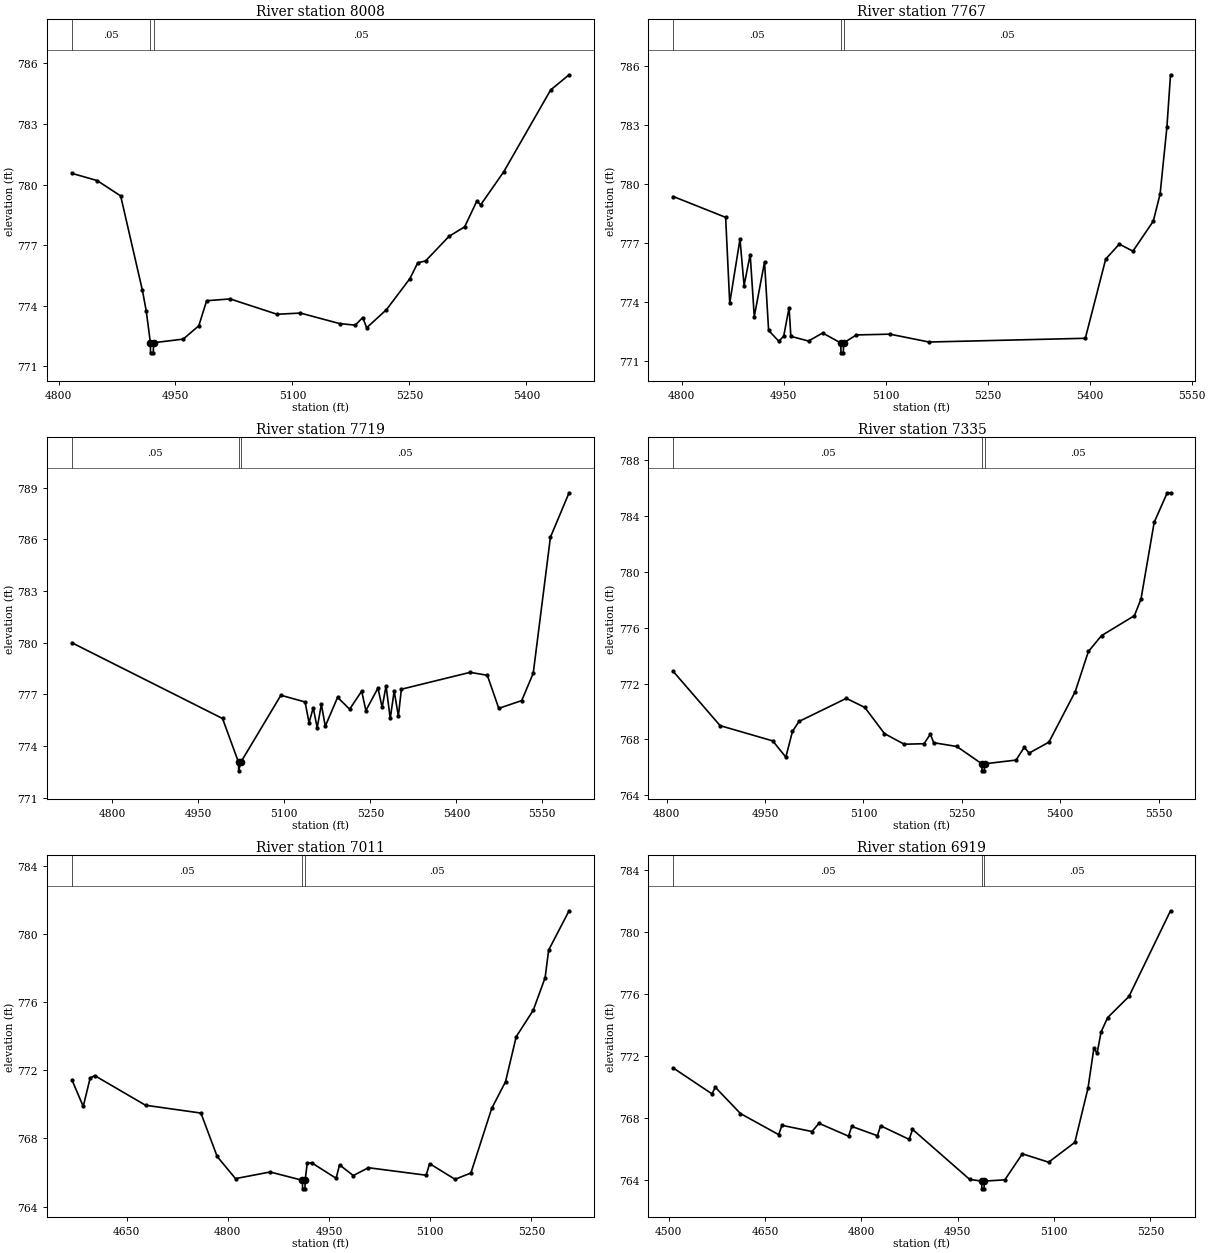
Type RM Length L Ch R = 1,8008,241,241,241
BEGIN DESCRIPTION:
Mapping XS 960b2e8c
END DESCRIPTION:
XS GIS Cut Line= 2
      2303937.43      7111492.40      2303982.29      7110856.48
#Sta/Elev= 30
  4817.1  780.56  4849.6  780.20  4879.7  779.44  4907.6  774.76  4912.6  773.72
  4917.8  772.17  4918.0  771.67  4921.5  771.67  4921.8  772.17  4959.9  772.35
  4979.9  773.01  4989.9  774.25  5020.0  774.34  5080.2  773.58  5110.2  773.64
  5160.3  773.12  5180.4  773.04  5190.1  773.42  5195.1  772.91  5220.5  773.81
  5250.6  775.35  5260.6  776.13  5270.6  776.22  5300.7  777.44  5320.7  777.91
  5336.3  779.18  5341.3  779.00  5370.9  780.64  5431.0  784.69  5454.6  785.44
#Mann=3,-1,0
  4817.1    0.05       0  4917.8   0.033       0  4921.8    0.05       0
Bank Sta=4917.8,4921.8
Exp/Cntr=0.3,0.1

Type RM Length L Ch R = 1,7767,48,48,48
BEGIN DESCRIPTION:
Mapping XS 774748ad
END DESCRIPTION:
XS GIS Cut Line= 5
      2303983.61      7111430.05      2304128.38      7111334.19
      2304321.15      7111176.04      2304380.39      7111081.42
      2304382.44      7110884.74
#Sta/Elev= 30
  4787.6  779.38  4864.6  778.32  4870.6  773.96  4885.7  777.21  4891.7  774.85
  4900.7  776.43  4906.7  773.27  4921.8  776.05  4927.8  772.57  4942.8  772.02
  4950.0  772.28  4957.9  773.73  4960.5  772.27  4986.5  772.03  5007.3  772.44
  5034.0  771.93  5034.2  771.43  5037.7  771.43  5038.0  771.93  5056.8  772.34
  5106.3  772.38  5163.7  771.98  5393.6  772.17  5423.6  776.20  5443.6  776.96
  5463.6  776.60  5493.6  778.13  5503.6  779.51  5513.6  782.91  5518.9  785.57
#Mann=3,-1,0
  4787.6    0.05       0  5034.0   0.033       0  5038.0    0.05       0
Bank Sta=5034,5038
Exp/Cntr=0.3,0.1

Type RM Length L Ch R = 1,7719,384,384,384
BEGIN DESCRIPTION:
Mapping XS 70d92dec
END DESCRIPTION:
XS GIS Cut Line= 4
      2303975.80      7111481.91      2304300.23      7111262.39
      2304427.23      7111127.37      2304439.36      7110837.51
#Sta/Elev= 30
  4729.4  780.00  4992.2  775.60  5020.1  773.06  5020.4  772.56  5024.1  773.06
  5094.0  776.95  5136.2  776.56  5143.1  775.35  5150.4  776.23  5157.3  775.06
  5164.6  776.42  5171.4  775.15  5192.9  776.83  5213.9  776.14  5234.9  777.19
  5242.2  776.06  5263.3  777.37  5270.6  776.24  5277.4  777.50  5284.7  775.60
  5291.6  777.20  5298.9  775.73  5304.1  777.30  5424.0  778.28  5454.0  778.11
  5474.0  776.19  5514.0  776.64  5534.1  778.23  5564.1  786.13  5596.6  788.71
#Mann=3,-1,0
  4729.4    0.05       0  5020.1   0.033       0  5024.1    0.05       0
Bank Sta=5020.1,5024.1
Exp/Cntr=0.3,0.1

Type RM Length L Ch R = 1,7335,324,324,324
BEGIN DESCRIPTION:
Mapping XS cc007eaf
END DESCRIPTION:
XS GIS Cut Line= 2
      2304533.21      7111611.17      2304477.40      7110855.13
#Sta/Elev= 30
  4810.0  772.86  4881.4  768.99  4961.6  767.90  4981.6  766.74  4991.7  768.58
  5001.7  769.29  5073.9  770.94  5102.0  770.29  5132.0  768.42  5162.1  767.66
  5192.2  767.70  5202.0  768.38  5207.0  767.77  5242.3  767.50  5280.5  766.26
  5280.7  765.76  5284.2  765.76  5284.5  766.26  5332.6  766.53  5345.1  767.44
  5352.6  767.03  5382.7  767.81  5422.8  771.42  5442.9  774.29  5462.9  775.42
  5513.1  776.85  5523.1  778.04  5543.2  783.52  5563.1  785.63  5568.1  785.63
#Mann=3,-1,0
  4810.0    0.05       0  5280.5   0.033       0  5284.5    0.05       0
Bank Sta=5280.5,5284.5
Exp/Cntr=0.3,0.1

Type RM Length L Ch R = 1,7011,92,92,92
BEGIN DESCRIPTION:
Mapping XS 0688be77
END DESCRIPTION:
XS GIS Cut Line= 2
      2304731.97      7111576.43      2304566.55      7110858.23
#Sta/Elev= 30
  4568.9  771.45  4585.8  769.88  4596.0  771.54  4602.8  771.69  4678.1  769.95
  4760.2  769.49  4784.3  766.94  4811.5  765.64  4862.8  766.03  4910.7  765.54
  4910.9  765.04  4914.4  765.04  4914.7  765.54  4917.8  766.55  4924.4  766.57
  4960.6  765.66  4965.7  766.45  4986.0  765.82  5008.5  766.28  5094.1  765.84
  5099.2  766.52  5136.9  765.60  5160.4  765.97  5191.2  769.76  5211.7  771.33
  5227.6  773.98  5252.8  775.53  5270.4  777.44  5275.6  779.06  5305.9  781.37
#Mann=3,-1,0
  4568.9    0.05       0  4910.7   0.033       0  4914.7    0.05       0
Bank Sta=4910.7,4914.7
Exp/Cntr=0.3,0.1

Type RM Length L Ch R = 1,6919,770,770,770
BEGIN DESCRIPTION:
Mapping XS 133d2264
END DESCRIPTION:
XS GIS Cut Line= 3
      2304795.71      7111572.75      2304742.19      7111295.15
      2304639.99      7110814.30
#Sta/Elev= 30
  4507.0  771.22  4567.3  769.55  4572.4  769.98  4611.6  768.28  4671.1  766.92
  4676.2  767.52  4723.0  767.12  4733.8  767.65  4779.9  766.82  4784.9  767.45
  4824.8  766.85  4829.9  767.49  4874.4  766.61  4879.5  767.26  4968.5  764.03
  4987.2  763.92  4987.5  763.42  4991.0  763.42  4991.2  763.92  5023.3  764.00
  5050.6  765.68  5091.5  765.14  5132.3  766.42  5152.8  769.92  5161.9  772.48
  5167.0  772.18  5173.2  773.55  5183.5  774.48  5216.6  775.84  5281.3  781.37
#Mann=3,-1,0
  4507.0    0.05       0  4987.2   0.033       0  4991.2    0.05       0
Bank Sta=4987.2,4991.2
Exp/Cntr=0.3,0.1

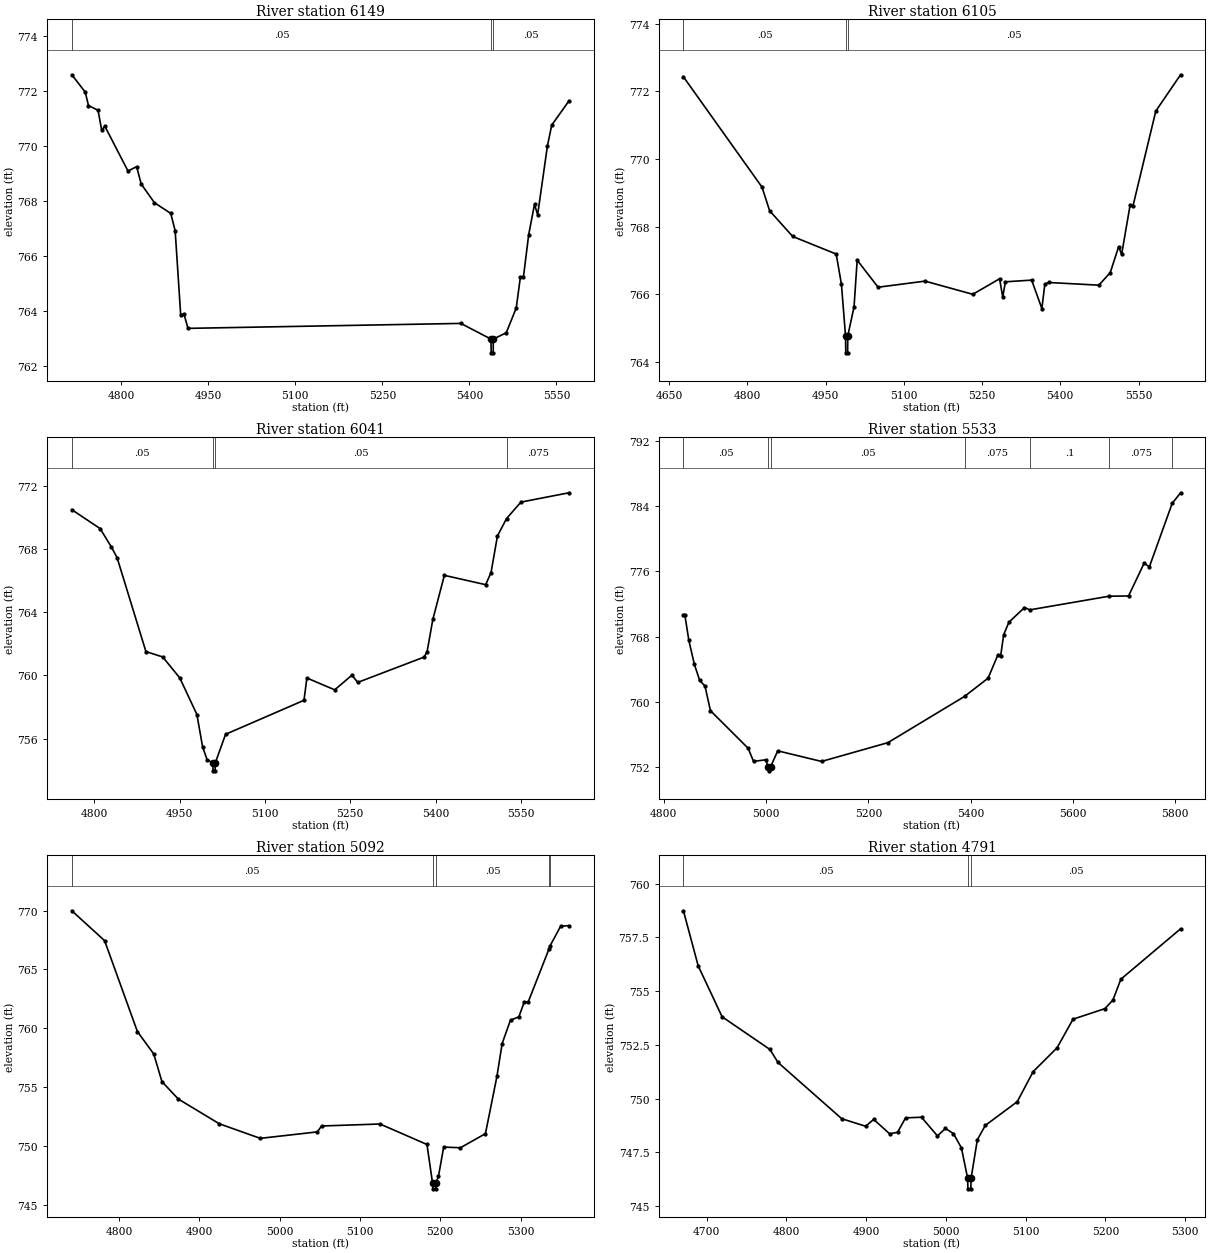
Type RM Length L Ch R = 1,6149,44,44,44
BEGIN DESCRIPTION:
Mapping XS 73b41b68
END DESCRIPTION:
XS GIS Cut Line= 5
      2305131.67      7111820.84      2305234.04      7111605.48
      2305250.11      7111460.63      2305218.72      7111330.44
      2305093.76      7111015.54
#Sta/Elev= 30
  4714.7  772.59  4737.8  771.96  4743.4  771.47  4759.9  771.30  4766.1  770.58
  4771.6  770.72  4811.5  769.09  4826.4  769.25  4834.2  768.62  4857.0  767.94
  4885.2  767.55  4892.8  766.92  4902.4  763.84  4907.9  763.90  4914.9  763.37
  5385.2  763.55  5437.2  762.98  5437.5  762.48  5441.0  762.48  5441.2  762.98
  5463.5  763.21  5480.7  764.11  5487.9  765.24  5493.2  765.25  5502.2  766.78
  5512.2  767.88  5517.6  767.50  5534.5  770.01  5541.9  770.76  5571.6  771.64
#Mann=3,-1,0
  4714.7    0.05       0  5437.2   0.033       0  5441.2    0.05       0
Bank Sta=5437.2,5441.2
Exp/Cntr=0.3,0.1

Type RM Length L Ch R = 1,6105,64,64,64
BEGIN DESCRIPTION:
Mapping XS 9f0509a6
END DESCRIPTION:
XS GIS Cut Line= 6
      2305158.62      7111853.60      2305277.51      7111625.41
      2305287.74      7111517.30      2305290.88      7111391.80
      2305249.13      7111207.39      2305118.78      7110967.99
#Sta/Elev= 30
  4677.5  772.43  4828.1  769.17  4842.8  768.47  4887.0  767.71  4970.4  767.19
  4980.4  766.30  4988.3  764.77  4988.7  764.27  4992.3  764.27  4992.6  764.77
  5004.6  765.63  5010.6  767.01  5050.7  766.21  5140.7  766.39  5232.3  766.00
  5283.6  766.46  5289.7  765.92  5294.8  766.37  5345.1  766.42  5364.7  765.58
  5370.4  766.30  5377.8  766.35  5473.9  766.27  5495.8  766.64  5511.9  767.41
  5517.6  767.18  5533.8  768.63  5539.5  768.62  5583.2  771.42  5630.6  772.49
#Mann=3,-1,0
  4677.5    0.05       0  4988.3   0.033       0  4992.6    0.05       0
Bank Sta=4988.3,4992.6
Exp/Cntr=0.3,0.1

Type RM Length L Ch R = 1,6041,508,508,508
BEGIN DESCRIPTION:
Mapping XS 6e9a9078
END DESCRIPTION:
XS GIS Cut Line= 4
      2305361.24      7111799.47      2305347.37      7111559.05
      2305298.27      7111207.91      2305366.61      7110938.11
#Sta/Elev= 30
  4760.6  770.47  4810.2  769.28  4830.2  768.11  4840.2  767.43  4890.8  761.50
  4920.3  761.16  4950.4  759.83  4980.4  757.52  4990.5  755.46  4998.4  754.66
  5008.4  754.46  5008.8  753.96  5012.4  753.96  5012.7  754.46  5030.8  756.27
  5168.6  758.42  5173.7  759.83  5222.6  759.08  5252.9  760.01  5263.0  759.55
  5379.5  761.15  5384.8  761.46  5395.1  763.54  5415.3  766.32  5487.9  765.73
  5497.3  766.49  5508.6  768.81  5524.6  769.91  5549.8  770.95  5634.3  771.54
#Mann=4,-1,0
  4760.6    0.05       0  5008.4   0.033       0  5012.7    0.05       0
  5524.6   0.075       0
Bank Sta=5008.4,5012.7
Exp/Cntr=0.3,0.1

Type RM Length L Ch R = 1,5533,441,441,441
BEGIN DESCRIPTION:
Morris Branch Tributary 4 10.0
END DESCRIPTION:
XS GIS Cut Line= 3
      2305779.01      7111660.04      2305729.00      7111510.00
      2305579.00      7110710.00
#Sta/Elev= 30
  4838.4  770.70  4841.1  770.70  4849.0  767.55  4859.5  764.68  4870.1  762.65
  4880.6  761.95  4891.2  758.94  4964.9  754.34  4975.5  752.73  4999.1  752.92
  5004.5  752.07  5004.9  751.57  5008.9  752.07  5022.8  754.02  5108.5  752.72
  5238.2  755.02  5388.2  760.69  5434.1  762.92  5453.6  765.81  5458.6  765.59
  5464.6  768.24  5474.8  769.77  5505.3  771.57  5515.9  771.29  5670.6  772.96
  5708.8  772.99  5739.3  777.01  5749.5  776.56  5794.1  784.33  5810.5  785.63
#Mann=7,-1,0
  4838.4    0.05       0  5004.5   0.033       0  5008.9    0.05       0
  5388.2   0.075       0  5515.9     0.1       0  5670.6   0.075       0
  5794.1    0.05       0
Bank Sta=5004.5,5008.9
Exp/Cntr=0.3,0.1

Type RM Length L Ch R = 1,5092,301,301,301
BEGIN DESCRIPTION:
Morris Branch Tributary 4 9.0
END DESCRIPTION:
XS GIS Cut Line= 3
      2305979.00      7111610.02      2306029.00      7111360.00
      2305928.99      7111009.97
#Sta/Elev= 30
  4741.2  769.99  4782.0  767.45  4822.8  759.73  4843.2  757.82  4853.4  755.47
  4873.8  753.99  4924.8  751.89  4975.8  750.65  5046.9  751.20  5052.1  751.70
  5124.9  751.87  5183.4  750.13  5190.3  746.86  5190.7  746.36  5194.3  746.36
  5194.7  746.86  5197.7  747.42  5204.2  749.91  5225.0  749.85  5256.2  751.05
  5270.5  755.91  5277.0  758.71  5287.4  760.70  5297.8  760.97  5304.3  762.20
  5309.5  762.25  5335.2  766.72  5336.4  766.98  5349.8  768.67  5360.2  768.73
#Mann=5,-1,0
  4741.2    0.05       0  5190.3   0.033       0  5194.7    0.05       0
  5335.2   0.075       0  5336.4     0.1       0
Bank Sta=5190.3,5194.7
Exp/Cntr=0.3,0.1

Type RM Length L Ch R = 1,4791,255,255,255
BEGIN DESCRIPTION:
Mapping XS 76d83d1f
END DESCRIPTION:
XS GIS Cut Line= 2
      2306275.88      7111538.48      2306276.97      7110915.18
#Sta/Elev= 30
  4671.0  758.74  4689.5  756.18  4719.5  753.81  4779.5  752.29  4789.5  751.69
  4869.5  749.07  4899.5  748.72  4909.5  749.04  4929.5  748.37  4939.5  748.44
  4949.5  749.11  4969.5  749.14  4989.5  748.27  4999.5  748.62  5009.5  748.38
  5019.5  747.72  5027.3  746.31  5027.7  745.81  5031.3  745.81  5031.7  746.31
  5039.5  748.09  5049.5  748.76  5089.5  749.86  5109.5  751.26  5139.5  752.37
  5159.5  753.70  5199.5  754.19  5209.5  754.59  5219.5  755.56  5294.3  757.90
#Mann=3,-1,0
  4671.0    0.05       0  5027.3   0.033       0  5031.7    0.05       0
Bank Sta=5027.3,5031.7
Exp/Cntr=0.3,0.1

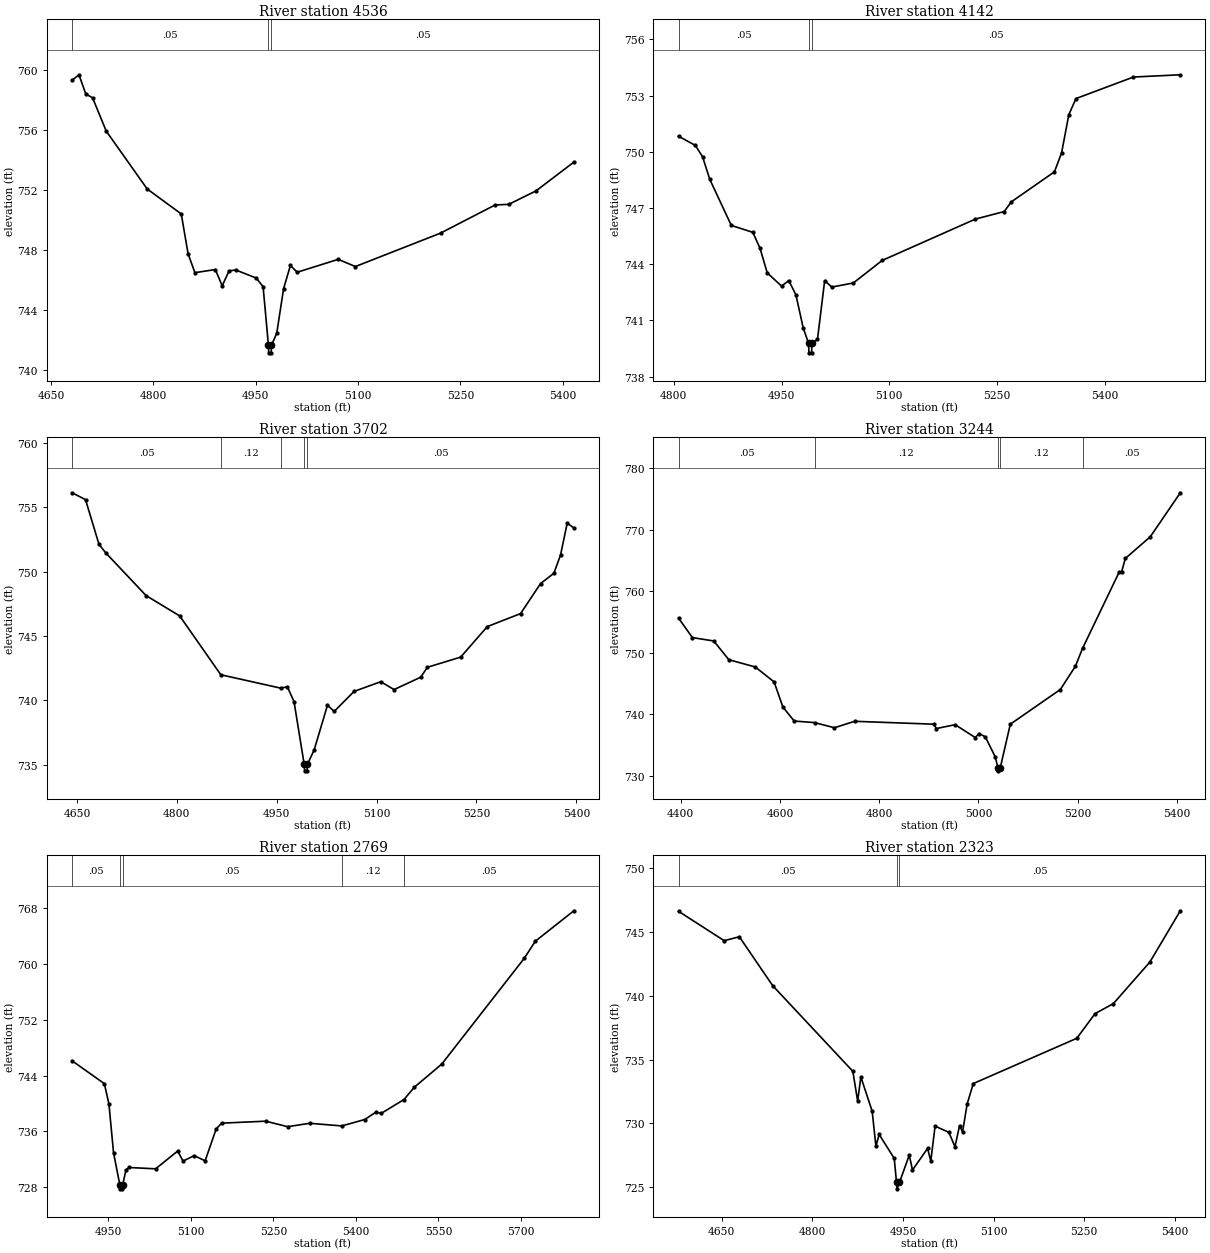
Type RM Length L Ch R = 1,4536,394,394,394
BEGIN DESCRIPTION:
Mapping XS 5b62abfb
END DESCRIPTION:
XS GIS Cut Line= 2
      2306522.99      7111580.07      2306507.08      7110844.54
#Sta/Elev= 30
  4680.7  759.33  4690.8  759.70  4700.8  758.42  4710.8  758.16  4730.8  755.94
  4790.8  752.08  4840.8  750.41  4850.8  747.75  4860.8  746.49  4890.8  746.70
  4900.8  745.61  4910.8  746.61  4920.8  746.67  4950.8  746.13  4960.8  745.55
  4968.6  741.64  4969.0  741.14  4972.6  741.14  4973.0  741.64  4980.8  742.45
  4990.8  745.42  5000.8  746.97  5010.8  746.52  5070.9  747.38  5096.1  746.90
  5220.9  749.13  5300.9  751.01  5320.9  751.05  5360.9  751.95  5416.4  753.87
#Mann=3,-1,0
  4680.7    0.05       0  4968.6   0.033       0  4973.0    0.05       0
Bank Sta=4968.6,4973
Exp/Cntr=0.3,0.1

Type RM Length L Ch R = 1,4142,440,440,440
BEGIN DESCRIPTION:
Mapping XS b5b668c4
END DESCRIPTION:
XS GIS Cut Line= 2
      2306860.53      7111503.50      2306860.61      7110804.70
#Sta/Elev= 30
  4806.5  750.83  4830.0  750.34  4840.0  749.73  4850.0  748.53  4880.0  746.07
  4910.0  745.70  4920.0  744.85  4930.0  743.54  4950.0  742.83  4960.0  743.13
  4970.0  742.36  4980.0  740.62  4987.6  739.77  4988.1  739.27  4991.8  739.27
  4992.3  739.77  5000.0  739.99  5010.0  743.12  5020.0  742.78  5050.0  743.00
  5090.0  744.20  5220.0  746.41  5260.0  746.81  5270.0  747.33  5330.0  748.93
  5340.0  749.95  5350.0  751.98  5360.0  752.84  5440.0  753.99  5505.3  754.11
#Mann=3,-1,0
  4806.5    0.05       0  4987.6   0.033       0  4992.3    0.05       0
Bank Sta=4987.6,4992.3
Exp/Cntr=0.3,0.1

Type RM Length L Ch R = 1,3702,458,458,458
BEGIN DESCRIPTION:
Morris Branch Tributary 4 6.0
END DESCRIPTION:
XS GIS Cut Line= 3
      2307279.00      7111610.00      2307229.00      7111260.00
      2307229.00      7110859.96
#Sta/Elev= 30
  4642.7  756.12  4662.9  755.59  4683.1  752.12  4693.2  751.46  4753.8  748.14
  4804.3  746.56  4866.1  741.99  4956.1  740.95  4966.0  741.06  4976.1  739.89
  4991.3  735.03  4991.9  734.53  4995.6  734.53  4996.1  735.03  5006.3  736.16
  5026.3  739.63  5036.3  739.14  5066.3  740.70  5106.3  741.45  5126.3  740.84
  5166.3  741.80  5176.3  742.57  5226.3  743.36  5266.3  745.73  5316.3  746.74
  5346.3  749.07  5366.3  749.87  5376.3  751.29  5386.3  753.76  5396.3  753.39
#Mann=5,-1,0
  4642.7    0.05       0  4866.1    0.12       0  4956.1    0.05       0
  4991.3   0.033       0  4996.1    0.05       0
Bank Sta=4991.3,4996.1
Exp/Cntr=0.3,0.1

Type RM Length L Ch R = 1,3244,475,475,475
BEGIN DESCRIPTION:
Morris Branch Tributary 4 5.0
END DESCRIPTION:
XS GIS Cut Line= 3
      2307379.00      7111610.00      2307479.00      7111010.00
      2307429.00      7110609.99
#Sta/Elev= 30
  4395.5  755.63  4423.4  752.45  4466.5  751.90  4496.9  748.85  4550.1  747.67
  4588.1  745.24  4605.9  741.14  4628.7  738.87  4669.7  738.62  4709.8  737.78
  4750.3  738.83  4910.0  738.36  4915.1  737.65  4953.1  738.28  4993.6  736.18
  5001.2  736.84  5013.9  736.30  5034.0  733.01  5039.2  731.27  5039.7  730.77
  5044.0  731.27  5064.2  738.36  5165.0  744.00  5195.3  747.77  5209.9  750.71
  5283.4  763.06  5288.5  763.12  5296.0  765.32  5346.4  768.86  5406.9  776.01
#Mann=5,-1,0
  4395.5    0.05       0  4669.7    0.12       0  5039.2    0.07       0
  5044.0    0.12       0  5209.9    0.05       0
Bank Sta=5039.2,5044
Exp/Cntr=0.3,0.1

Type RM Length L Ch R = 1,2769,446,446,446
BEGIN DESCRIPTION:
Morris Branch Tributary 4 4.0
END DESCRIPTION:
XS GIS Cut Line= 3
      2307629.02      7111509.96      2307679.00      7111410.00
      2307679.00      7110609.96
#Sta/Elev= 30
  4884.3  746.13  4943.0  742.85  4951.3  739.92  4959.7  732.92  4971.3  728.27
  4971.8  727.77  4975.5  727.77  4976.1  728.27  4982.1  730.43  4987.7  730.83
  5036.1  730.64  5076.1  733.18  5086.1  731.75  5106.1  732.53  5126.1  731.79
  5146.1  736.35  5156.1  737.19  5236.1  737.47  5276.1  736.68  5316.1  737.17
  5374.3  736.79  5416.1  737.71  5436.1  738.75  5446.1  738.59  5487.3  740.57
  5506.1  742.33  5556.1  745.66  5706.1  760.84  5726.1  763.28  5796.1  767.64
#Mann=5,-1,0
  4884.3    0.05       0  4971.3   0.033       0  4976.1    0.05       0
  5374.3    0.12       0  5487.3    0.05       0
Bank Sta=4971.3,4976.1
Exp/Cntr=0.3,0.1

Type RM Length L Ch R = 1,2323,455,455,455
BEGIN DESCRIPTION:
Morris Branch Tributary 4 3.0
END DESCRIPTION:
XS GIS Cut Line= 3
      2307929.00      7111659.99      2308079.00      7111260.00
      2308129.00      7110860.01
#Sta/Elev= 30
  4578.7  746.59  4654.3  744.29  4679.3  744.60  4734.4  740.78  4867.1  734.08
  4875.1  731.75  4880.4  733.64  4899.1  730.96  4905.3  728.23  4910.7  729.14
  4935.6  727.27  4939.4  725.39  4940.0  724.89  4944.3  725.39  4960.5  727.53
  4965.8  726.36  4990.8  728.05  4996.1  727.07  5003.2  729.79  5026.0  729.31
  5036.1  728.18  5043.7  729.83  5048.7  729.34  5056.3  731.53  5066.4  733.12
  5237.7  736.66  5267.9  738.59  5298.2  739.37  5358.6  742.62  5409.0  746.63
#Mann=3,-1,0
  4578.7    0.05       0  4939.4   0.033       0  4944.3    0.05       0
Bank Sta=4939.4,4944.3
Exp/Cntr=0.3,0.1

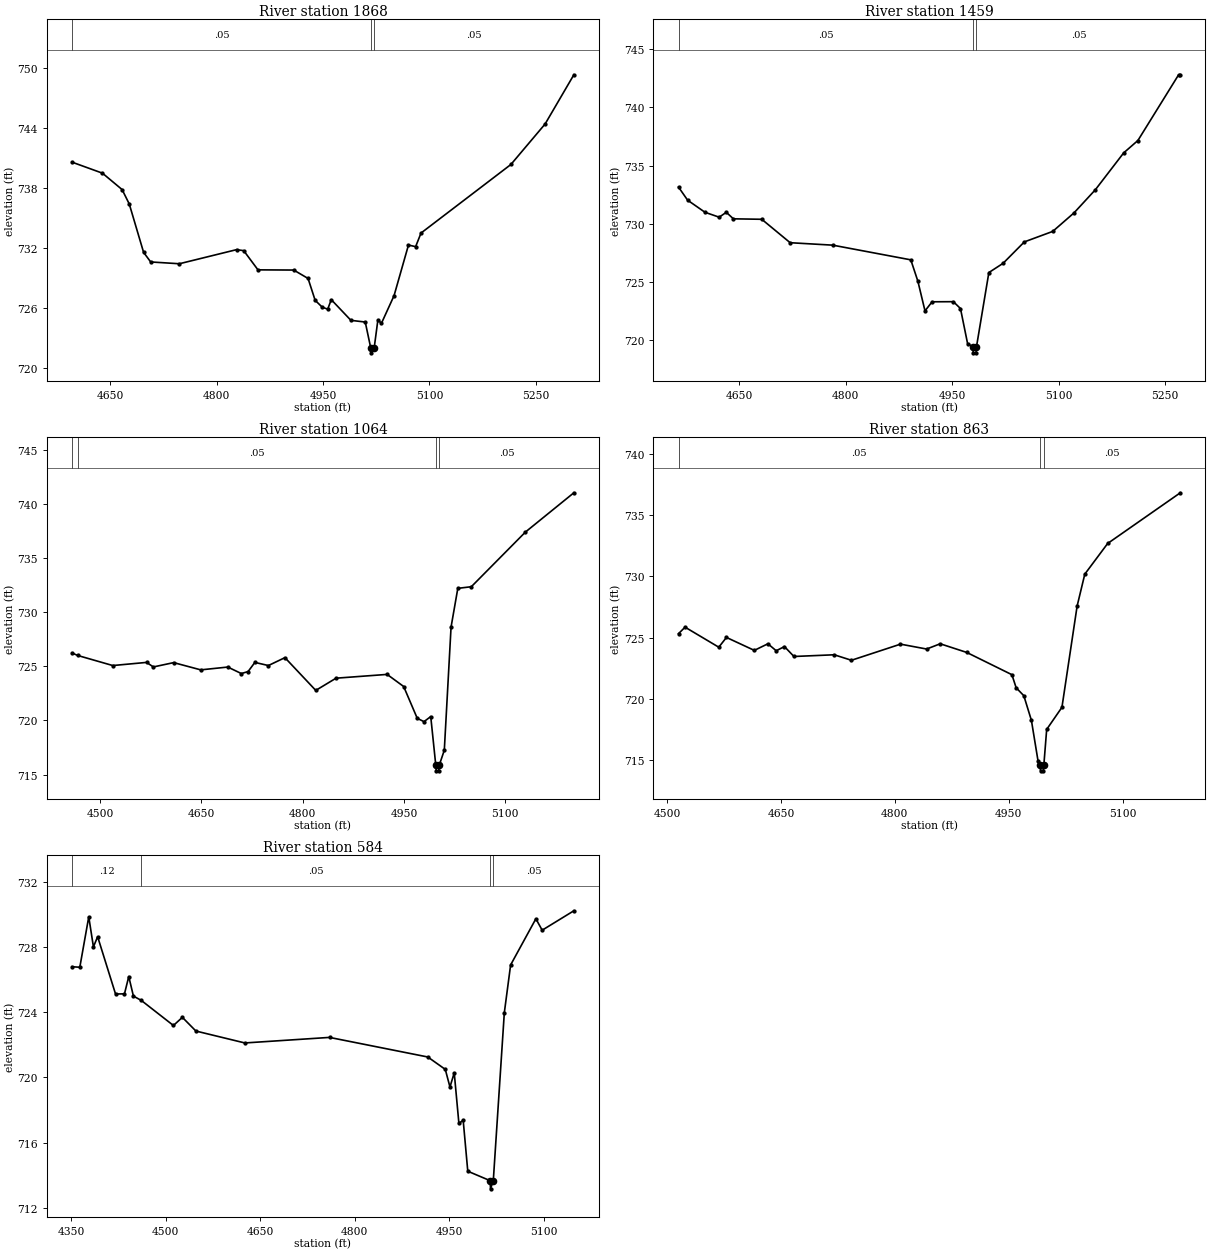
Type RM Length L Ch R = 1,1868,409,409,409
BEGIN DESCRIPTION:
Morris Branch Tributary 4 2.0
END DESCRIPTION:
XS GIS Cut Line= 3
      2308329.00      7111509.99      2308379.00      7111110.00
      2308329.01      7110810.04
#Sta/Elev= 30
  4596.3  740.63  4639.1  739.53  4666.8  737.89  4676.9  736.45  4697.1  731.61
  4707.1  730.65  4747.5  730.47  4828.1  731.88  4838.2  731.78  4858.3  729.86
  4908.7  729.84  4928.9  729.00  4938.9  726.81  4949.0  726.12  4956.6  725.93
  4961.6  726.88  4989.3  724.81  5009.5  724.64  5017.2  722.06  5017.8  721.56
  5022.1  722.06  5027.3  724.85  5032.3  724.51  5050.1  727.28  5070.4  732.34
  5080.5  732.18  5088.1  733.54  5214.8  740.40  5263.0  744.45  5303.5  749.37
#Mann=3,-1,0
  4596.3    0.05       0  5017.2   0.033       0  5022.1    0.05       0
Bank Sta=5017.2,5022.1
Exp/Cntr=0.3,0.1

Type RM Length L Ch R = 1,1459,395,395,395
BEGIN DESCRIPTION:
Mapping XS 2742a605
END DESCRIPTION:
XS GIS Cut Line= 2
      2308763.83      7111497.26      2308772.95      7110790.22
#Sta/Elev= 30
  4564.3  733.16  4577.1  732.04  4601.6  731.00  4621.6  730.58  4631.6  731.00
  4641.6  730.44  4681.6  730.40  4721.6  728.39  4781.6  728.18  4891.6  726.92
  4901.6  725.08  4911.6  722.54  4921.6  723.32  4951.6  723.33  4961.6  722.74
  4971.6  719.74  4979.1  719.44  4979.7  718.94  4983.4  718.94  4984.1  719.44
  5001.6  725.83  5021.6  726.62  5051.6  728.46  5091.6  729.36  5121.6  730.95
  5151.6  732.93  5191.6  736.10  5211.6  737.16  5269.0  742.80  5271.4  742.80
#Mann=3,-1,0
  4564.3    0.05       0  4979.1   0.033       0  4984.1    0.05       0
Bank Sta=4979.1,4984.1
Exp/Cntr=0.3,0.1

Type RM Length L Ch R = 1,1064,201,201,201
BEGIN DESCRIPTION:
Mapping XS b8dc4e78
END DESCRIPTION:
XS GIS Cut Line= 2
      2309033.38      7111500.18      2309082.09      7110758.48
#Sta/Elev= 30
  4458.3  726.24  4466.7  726.01  4518.6  725.08  4568.7  725.37  4578.7  724.95
  4608.8  725.35  4648.9  724.68  4689.0  724.94  4709.0  724.34  4719.0  724.52
  4729.1  725.37  4749.1  725.08  4773.6  725.81  4819.3  722.78  4849.3  723.91
  4925.0  724.26  4949.5  723.14  4969.6  720.20  4979.6  719.89  4989.6  720.36
  4997.1  715.84  4997.8  715.34  5001.5  715.34  5002.1  715.84  5009.7  717.25
  5019.7  728.64  5029.7  732.22  5049.7  732.37  5129.9  737.43  5201.6  741.06
#Mann=4,-1,0
  4458.3    0.12       0  4466.7    0.05       0  4997.1   0.033       0
  5002.1    0.05       0
Bank Sta=4997.1,5002.1
Exp/Cntr=0.3,0.1

Type RM Length L Ch R = 1,863,279,279,279
BEGIN DESCRIPTION:
Mapping XS 6c000f0c
END DESCRIPTION:
XS GIS Cut Line= 3
      2309074.67      7111457.84      2309250.49      7111055.60
      2309270.77      7110834.72
#Sta/Elev= 30
  4515.2  725.32  4523.8  725.85  4568.2  724.21  4578.3  725.01  4615.0  723.95
  4632.9  724.49  4643.8  723.92  4654.7  724.26  4667.2  723.45  4720.2  723.59
  4742.9  723.14  4807.5  724.46  4841.9  724.06  4859.8  724.49  4894.8  723.78
  4954.2  721.96  4959.8  720.89  4969.9  720.24  4979.9  718.22  4988.7  714.87
  4991.3  714.59  4991.9  714.09  4995.6  714.09  4996.3  714.59  5000.0  717.48
  5020.1  719.29  5040.1  727.58  5050.2  730.19  5080.3  732.70  5176.0  736.85
#Mann=3,-1,0
  4515.2    0.05       0  4991.3   0.033       0  4996.3    0.05       0
Bank Sta=4991.3,4996.3
Exp/Cntr=0.3,0.1

Type RM Length L Ch R = 1,584,0,0,0
BEGIN DESCRIPTION:
Morris Branch Tributary 4 1.0
END DESCRIPTION:
XS GIS Cut Line= 3
      2309042.82      7111531.36      2309508.75      7111103.61
      2309500.07      7110939.74
#Sta/Elev= 30
  4351.5  726.78  4363.8  726.75  4378.0  729.84  4385.4  728.00  4392.1  728.62
  4420.5  725.11  4434.7  725.12  4441.5  726.18  4448.9  724.98  4461.3  724.72
  4512.4  723.18  4526.6  723.68  4548.1  722.84  4625.8  722.11  4760.2  722.45
  4916.2  721.25  4944.0  720.49  4951.4  719.41  4958.2  720.28  4965.6  717.18
  4972.4  717.37  4979.7  714.25  5015.2  713.67  5015.8  713.17  5020.2  713.67
  5037.7  723.96  5047.7  726.89  5087.8  729.72  5097.8  729.02  5148.1  730.21
#Mann=4,-1,0
  4351.5    0.12       0  4461.3    0.05       0  5015.2   0.033       0
  5020.2    0.05       0
Bank Sta=5015.2,5020.2
Exp/Cntr=0.3,0.1

Chan Stop Cuts=-1