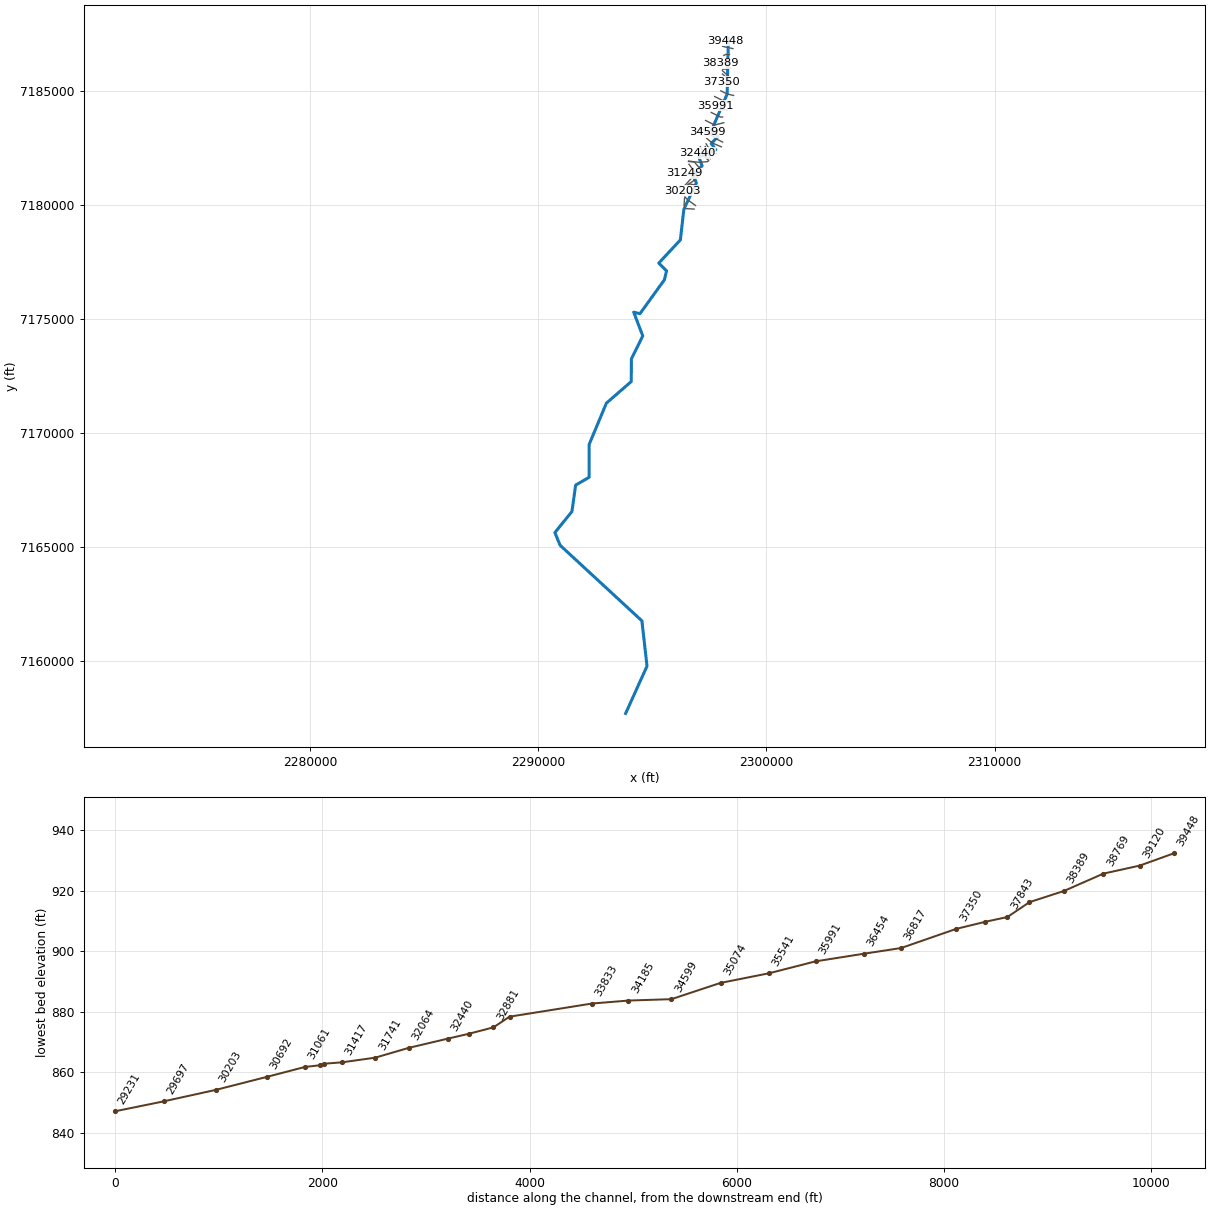
--- North Pecan Creek.prj (project) ---

Proj Title=North Pecan Creek Base Level Engineering
Current Plan=p01
Default Exp/Contr=0.3,0.1
English Units
Geom File=g01
Flow File=f01
Plan File=p01
Y Axis Title=Elevation
X Axis Title(PF)=Main Channel Distance
X Axis Title(XS)=Station
BEGIN DESCRIPTION:
North Pecan Creek
END DESCRIPTION:
DSS Export Rating Curves= 0
DSS Export Rating Curve Sorted= 0
DSS Export Volume Flow Curves= 0
DXF OffsetX= 0
DXF OffsetY= 0
DXF ScaleX= 1
DXF ScaleY= 10

--- North Pecan Creek.p01 (plan) ---

Plan Title=Multiple Run
Short Identifier=Multiple
Geom File=g01
Flow File=f01
Subcritical Flow
K Sum by GR= 0
Std Step Tol= 0.01
Critical Tol= 0.01
Num of Std Step Trials= 20
Max Error Tol= 0.3
Flow Tol Ratio= 0.001
Split Flow NTrial= 30
Split Flow Tol= 0.02
Split Flow Ratio= 0.02
Log Output Level= 0
Friction Slope Method= 1
Unsteady Friction Slope Method= 2
Unsteady Bridges Friction Slope Method= 1
Parabolic Critical Depth
Global Vel Dist=  1 , 1 , 1
Global Log Level= 0
CheckData=True
Encroach Param= -1, 0, 0, 0
BEGIN DESCRIPTION:
Multiple Run
END DESCRIPTION:

--- North Pecan Creek.f01 (steady flow) ---

Flow Title=Multiple
Number of Profiles=7
Profile Names=10-year,25-year,50-year,1pct_min,100-year,1pct_plu,500-year
River Rch & RM= North Pecan Cree,Reach-1,39448
     524     711     864     522    1041    2077    1515
River Rch & RM= North Pecan Cree,Reach-1,36817
     849    1184    1466     901    1798    3587    2708
River Rch & RM= North Pecan Cree,Reach-1,34185
    1058    1492    1861    1151    2298    4584    3509
River Rch & RM= North Pecan Cree,Reach-1,32881
    1089    1538    1920    1189    2371    4732    3626
River Rch & RM= North Pecan Cree,Reach-1,32064
    1393    1992    2507    1563    3118    6222    4839
River Rch & RM= North Pecan Cree,Reach-1,28808
    1535    2201    2776    1734    3459    6902    5387
River Rch & RM= North Pecan Cree,Reach-1,23575
    1790    2584    3273    2052    4094    8169    6424
River Rch & RM= North Pecan Cree,Reach-1,21315
    2287    3333    4250    2679    5346   10667    8485
River Rch & RM= North Pecan Cree,Reach-1,18058
    2441    3568    4556    2877    5741   11454    9140
River Rch & RM= North Pecan Cree,Reach-1,17641
    2648    3875    4954    3131    6246   12463    9958
River Rch & RM= North Pecan Cree,Reach-1,15389
    2737    4009    5128    3241    6468   12904   10318
River Rch & RM= North Pecan Cree,Reach-1,11230
    2818    4124    5271    3329    6642   13252   10576
River Rch & RM= North Pecan Cree,Reach-1,8197
    2899    4244    5424    3425    6834   13635   10879
Boundary for River Rch & Prof#=North Pecan Cree,Reach-1,1
Up Type=0
Dn Type=3
Dn Slope=0.005
Boundary for River Rch & Prof#=North Pecan Cree,Reach-1,2
Up Type=0
Dn Type=3
Dn Slope=0.005
Boundary for River Rch & Prof#=North Pecan Cree,Reach-1,3
Up Type=0
Dn Type=3
Dn Slope=0.005
Boundary for River Rch & Prof#=North Pecan Cree,Reach-1,4
Up Type=0
Dn Type=3
Dn Slope=0.005
Boundary for River Rch & Prof#=North Pecan Cree,Reach-1,5
Up Type=0
Dn Type=3
Dn Slope=0.005
Boundary for River Rch & Prof#=North Pecan Cree,Reach-1,6
Up Type=0
Dn Type=3
Dn Slope=0.005
Boundary for River Rch & Prof#=North Pecan Cree,Reach-1,7
Up Type=0
Dn Type=3
Dn Slope=0.005

--- North Pecan Creek.g01 (geometry) ---

Geom Title=Existing Conditions
Program Version=4.10

River Reach=North Pecan Cree,Reach-1
Reach XY= 30
        2298329.        7187310.      2298278.28      7184870.71
      2297586.23      7183259.69      2297876.89      7183004.12
      2297579.39      7182698.99      2297777.39      7182421.58
      2297032.31      7182108.31       2297178.4      7181720.62
       2296780.5      7181304.15      2296928.77        7180976.
        2296379.        7179810.      2296227.39      7178471.58
      2295280.59      7177453.95      2295621.23      7177113.41
      2295527.08      7176721.95      2294456.29      7175235.84
      2294180.96      7175304.52        2294579.        7174260.
      2294080.62      7173253.96      2294075.47      7172261.45
       2292984.4      7171312.43      2292231.05      7169504.16
      2292225.46      7168061.46      2291636.85      7167716.82
      2291475.86      7166561.64      2290729.27       7165639.7
      2290955.16      7165082.86      2294541.39      7161767.53
       2294765.1      7159782.15        2293829.        7157710.

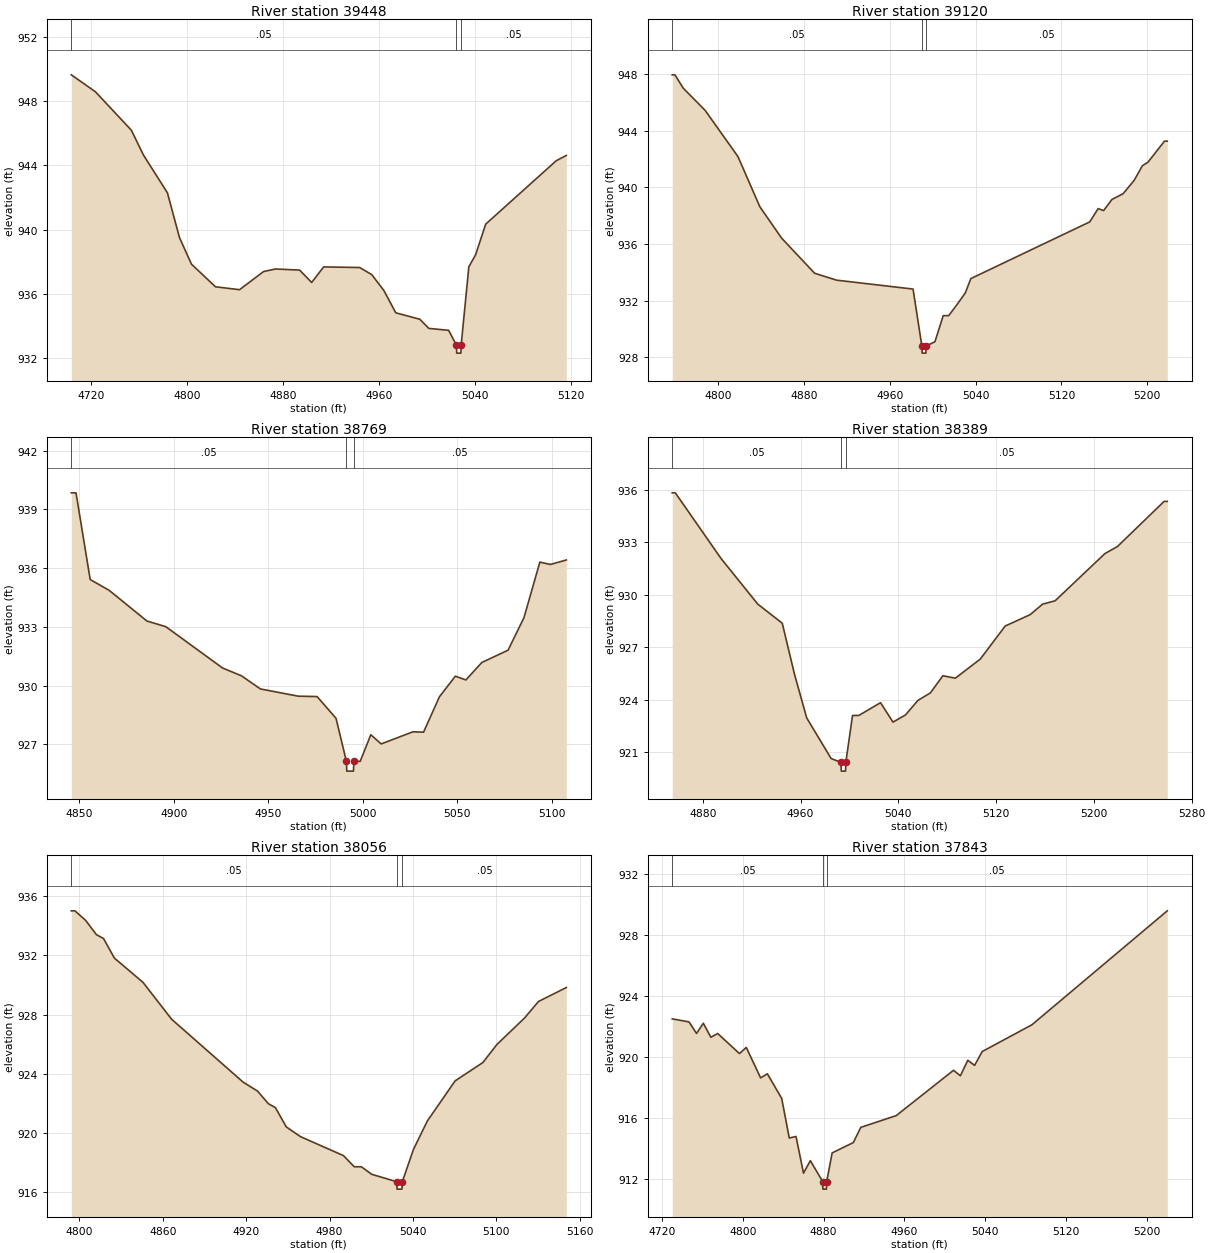
Type RM Length L Ch R = 1 ,39448   ,328,328,328
BEGIN DESCRIPTION:
North Pecan Creek 79.0
END DESCRIPTION:
XS GIS Cut Line= 3
      2298579.05        7187160.        2298279.        7187160.
      2298178.96      7187210.02
#Sta/Elev= 30
  4703.9  949.64  4723.9  948.59  4753.9  946.19  4763.9  944.65  4783.9  942.29
  4793.9  939.51  4803.9  937.85  4823.9  936.44  4843.9  936.26  4863.9  937.39
  4873.9  937.55  4893.9  937.48  4903.9  936.71  4913.9  937.68  4943.9  937.64
  4953.9   937.2  4963.9  936.22  4973.9  934.82  4993.9  934.42  5001.4  933.85
  5017.9  933.73  5024.3  932.81  5024.6  932.31  5028.1  932.31  5028.3  932.81
  5034.7  937.69  5040.3  938.43  5048.7  940.34  5107.4  944.29  5115.8  944.62
#Mann= 3 ,-1 , 0
  4703.9     .05       0  5024.3    .033       0  5028.3     .05       0
Bank Sta=5024.3,5028.3
XS Rating Curve= 0 ,0
Exp/Cntr=0.3,0.1

Type RM Length L Ch R = 1 ,39120   ,351,351,351
BEGIN DESCRIPTION:
North Pecan Creek 78.0
END DESCRIPTION:
XS GIS Cut Line= 3
      2298528.99        7186860.        2298279.        7186910.
        2298079.        7186960.
#Sta/Elev= 30
  4757.5  947.96    4760  947.96  4767.7  947.02  4788.1  945.45  4818.7  942.18
  4839.1  938.63  4859.5   936.4  4890.1  933.93  4910.5  933.44  4981.8  932.81
    4990  928.78  4990.3  928.28  4993.8  928.28    4994  928.78  5002.2  929.09
  5009.9  930.93    5015  930.93  5022.7  931.71  5030.5  932.54  5035.6  933.55
  5146.4  937.56  5154.2   938.5  5159.3  938.36  5167.1  939.15  5177.4  939.55
  5187.7  940.49  5195.4  941.53  5200.6  941.78    5216  943.27  5218.6  943.27
#Mann= 3 ,-1 , 0
  4757.5     .05       0    4990    .033       0    4994     .05       0
Bank Sta=4990,4994
XS Rating Curve= 0 ,0
Exp/Cntr=0.3,0.1

Type RM Length L Ch R = 1 ,38769   ,380,380,380
BEGIN DESCRIPTION:
North Pecan Creek 77.0
END DESCRIPTION:
XS GIS Cut Line= 3
      2298378.97        7186610.        2298229.        7186610.
      2298128.98      7186559.99
#Sta/Elev= 30
  4845.8  939.85  4848.3  939.85  4855.8  935.42  4865.8  934.87  4885.8   933.3
  4895.8  933.01  4925.8   930.9  4935.8   930.5  4945.8  929.83  4965.8  929.46
  4975.8  929.44  4985.8  928.33  4991.3  926.13  4991.5  925.63    4995  925.63
  4995.3  926.13  4998.6  926.13  5004.2  927.49  5009.7  927.02  5026.5  927.64
  5032.1  927.62  5040.5  929.43  5048.9  930.48  5054.5  930.29  5062.9  931.18
  5076.8  931.81  5085.2  933.47  5093.6  936.31  5099.2  936.19  5107.6  936.42
#Mann= 3 ,-1 , 0
  4845.8     .05       0  4991.3    .033       0  4995.3     .05       0
Bank Sta=4991.3,4995.3
XS Rating Curve= 0 ,0
Exp/Cntr=0.3,0.1

Type RM Length L Ch R = 1 ,38389   ,333,333,333
BEGIN DESCRIPTION:
North Pecan Creek 76.0
END DESCRIPTION:
XS GIS Cut Line= 3
      2298379.04        7186260.        2298229.        7186260.
      2297978.99        7186210.
#Sta/Elev= 30
    4855  935.81  4857.5  935.81    4895  932.05    4925  929.45    4945  928.36
    4955  925.45    4965  922.95    4985  920.63    4993  920.41  4993.3  919.91
  4996.8  919.91    4997  920.41  5002.5  923.09  5007.6  923.09  5025.4  923.82
  5035.6  922.71  5045.8  923.12    5056  923.95  5066.2  924.38  5076.4  925.36
  5086.6  925.22    5107  926.31  5127.4   928.2  5147.8  928.85    5158  929.45
  5168.2  929.64    5209  932.34  5219.2  932.74  5257.4  935.32    5260  935.32
#Mann= 3 ,-1 , 0
    4855     .05       0    4993    .033       0    4997     .05       0
Bank Sta=4993,4997
XS Rating Curve= 0 ,0
Exp/Cntr=0.3,0.1

Type RM Length L Ch R = 1 ,38056   ,213,213,213
BEGIN DESCRIPTION:
North Pecan Creek 75.0
END DESCRIPTION:
XS GIS Cut Line= 3
      2298429.04      7186010.01        2298229.        7185960.
        2298079.        7185960.
#Sta/Elev= 30
  4794.2  935.01  4796.8  935.01  4804.5  934.37  4812.3   933.4  4817.4  933.14
  4825.2  931.82  4845.8  930.18  4866.4  927.69  4917.9  923.44  4928.2  922.84
    4936  921.99  4941.1  921.72  4948.9  920.42  4959.2  919.76  4990.1  918.48
  4997.8  917.73  5002.9  917.73  5010.4  917.22  5028.4  916.72  5028.6  916.22
  5032.1  916.22  5032.4  916.72  5040.4   918.9  5050.4  920.82  5070.4  923.53
  5090.4  924.77  5100.4  925.98  5120.4  927.78  5130.4  928.89  5150.4  929.83
#Mann= 3 ,-1 , 0
  4794.2     .05       0  5028.4    .033       0  5032.4     .05       0
Bank Sta=5028.4,5032.4
XS Rating Curve= 0 ,0
Exp/Cntr=0.3,0.1

Type RM Length L Ch R = 1 ,37843   ,212,212,212
BEGIN DESCRIPTION:
Mapping XS 9d96f7e3
END DESCRIPTION:
XS GIS Cut Line= 2
      2298428.28       7185565.6      2298065.45      7185895.97
#Sta/Elev= 30
  4729.9   922.5  4746.5   922.3    4754  921.54  4760.7  922.21  4768.2  921.29
  4774.9  921.54  4796.5  920.22  4803.3  920.62  4817.5  918.62  4824.2  918.89
  4838.4  917.27  4845.9  914.67  4852.6  914.77    4860  912.36  4866.8  913.18
    4879  911.81  4879.2  911.31  4882.7  911.31    4883  911.81  4888.4  913.69
  4909.4  914.37  4916.8  915.37  4951.9  916.14  5008.7  919.12  5015.5  918.76
  5022.9  919.78  5029.6  919.44  5037.1  920.35  5086.4  922.11  5220.6   929.6
#Mann= 3 ,-1 , 0
  4729.9     .05       0    4879    .033       0    4883     .05       0
Bank Sta=4879,4883
XS Rating Curve= 0 ,0
Exp/Cntr=0.3,0.1

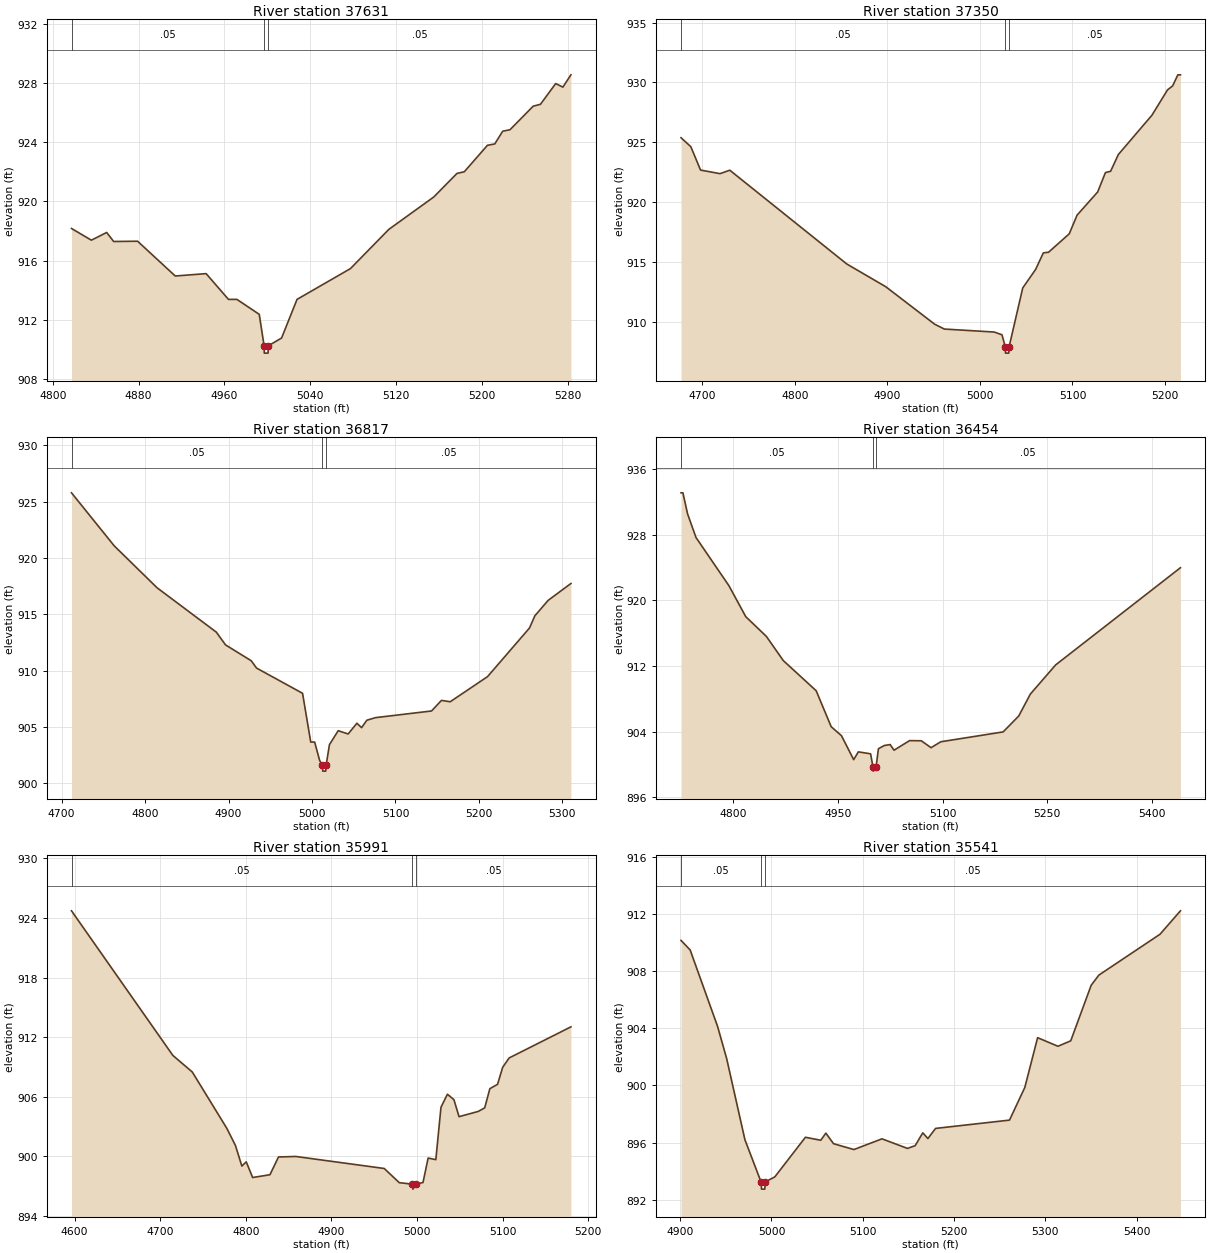
Type RM Length L Ch R = 1 ,37631   ,281,281,281
BEGIN DESCRIPTION:
Mapping XS 66c4ee5c
END DESCRIPTION:
XS GIS Cut Line= 3
      2298394.92      7185409.74      2298257.35      7185578.24
      2298073.34      7185744.47
#Sta/Elev= 30
  4817.5  918.17    4836  917.38  4850.3   917.9  4856.8  917.29  4879.1  917.31
  4914.2  914.96    4943  915.12  4963.8  913.38  4971.7  913.38  4992.5  912.37
    4997  910.25  4997.2  909.75  5000.7  909.75    5001  910.25  5013.3  910.77
  5027.7  913.38  5077.5  915.46  5113.3  918.11  5155.2   920.3  5176.8  921.89
  5183.6     922  5205.2  923.79    5212  923.88  5219.4  924.74  5226.2  924.84
  5247.8  926.43  5254.6  926.56  5268.8  927.96  5275.5  927.72    5283  928.55
#Mann= 3 ,-1 , 0
  4817.5     .05       0    4997    .033       0    5001     .05       0
Bank Sta=4997,5001
XS Rating Curve= 0 ,0
Exp/Cntr=0.3,0.1

Type RM Length L Ch R = 1 ,37350   ,533,533,533
BEGIN DESCRIPTION:
North Pecan Creek 73.0
END DESCRIPTION:
XS GIS Cut Line= 3
      2298529.03      7185410.01        2298229.        7185310.
      2298028.97      7185410.01
#Sta/Elev= 30
  4676.8  925.39  4687.4  924.64  4697.9  922.69    4719  922.39  4729.5  922.68
    4856  914.85  4898.2  912.95  4950.9  909.83  4961.4  909.42  5015.4  909.17
  5023.8  908.94  5027.4  907.91  5027.6  907.41  5031.1  907.41  5031.4  907.91
  5046.2  912.85  5060.1  914.39  5068.5  915.78  5074.1  915.83  5096.5  917.37
  5104.9  918.92  5127.2  920.86  5135.6  922.48  5141.2  922.59  5149.6  923.99
  5185.9  927.27  5202.7  929.38  5208.3  929.72  5213.9  930.64  5216.7  930.64
#Mann= 3 ,-1 , 0
  4676.8     .05       0  5027.4    .033       0  5031.4     .05       0
Bank Sta=5027.4,5031.4
XS Rating Curve= 0 ,0
Exp/Cntr=0.3,0.1

Type RM Length L Ch R = 1 ,36817   ,363,363,363
BEGIN DESCRIPTION:
Mapping XS 7b69419d
END DESCRIPTION:
XS GIS Cut Line= 3
      2298558.91      7184805.52      2298274.89      7184870.14
      2298000.35      7185007.58
#Sta/Elev= 30
  4711.9  925.79  4763.1  921.08  4814.4  917.36  4885.4  913.42  4896.4  912.29
  4927.2  910.88  4933.6  910.23  4988.7  907.99  4998.5  903.66  5003.2  903.66
  5009.1  902.04  5012.5  901.58  5012.9  901.08  5016.5  901.08  5016.9  901.58
  5020.9  903.43  5031.4  904.67  5043.3  904.38  5053.8  905.33  5059.4  904.94
  5065.7   905.6  5076.2  905.83  5143.2  906.42  5155.1  907.36  5165.6  907.24
  5210.3  909.47  5260.6  913.79    5267  914.87  5282.9  916.24  5310.2  917.74
#Mann= 3 ,-1 , 0
  4711.9     .05       0  5012.5    .033       0  5016.9     .05       0
Bank Sta=5012.5,5016.9
XS Rating Curve= 0 ,0
Exp/Cntr=0.3,0.1

Type RM Length L Ch R = 1 ,36454   ,463,463,463
BEGIN DESCRIPTION:
North Pecan Creek 71.0
END DESCRIPTION:
XS GIS Cut Line= 3
      2298378.99        7184460.        2298129.        7184560.
      2297728.97      7184760.02
#Sta/Elev= 30
  4724.8  933.11  4727.5  933.11  4734.2  930.54  4746.3  927.66  4793.5  921.79
  4817.7  918.01  4847.3   915.6  4871.5  912.66  4918.7  908.98  4940.2   904.6
    4955   903.5  4972.5  900.58  4979.2  901.53  4996.8  901.29  5000.2  899.68
  5000.6  899.18  5004.6  899.68    5008  901.91  5016.4   902.3  5024.8  902.42
  5030.4  901.73  5052.7   902.9  5069.5  902.88  5083.5  902.04  5097.5  902.76
  5186.9  903.96  5209.3   905.9    5226  908.58  5262.4  912.14  5441.3  923.98
#Mann= 3 ,-1 , 0
  4724.8     .05       0  5000.2    .033       0  5004.6     .05       0
Bank Sta=5000.2,5004.6
XS Rating Curve= 0 ,0
Exp/Cntr=0.3,0.1

Type RM Length L Ch R = 1 ,35991   ,450,450,450
BEGIN DESCRIPTION:
North Pecan Creek 70.0
END DESCRIPTION:
XS GIS Cut Line= 3
      2298278.98        7184160.        2297879.        7184210.
      2297778.98      7184360.03
#Sta/Elev= 30
  4596.3  924.72  4714.7  910.15  4737.4  908.48  4777.7  902.81  4787.8  901.08
  4795.3     899  4800.4  899.43  4807.9  897.85  4828.1  898.13  4838.1  899.92
  4858.3  899.97  4961.6  898.76  4979.2  897.33  4994.6  897.18  4995.1  896.68
  4999.1  897.18  5006.9  897.35  5012.9  899.81  5021.9  899.65  5027.9  904.93
  5035.4  906.24    5043   905.7    5049  903.98  5071.5  904.51    5079  904.87
    5085   906.8    5094  907.24    5100  908.96  5107.6   909.9  5179.7  913.03
#Mann= 3 ,-1 , 0
  4596.3     .05       0  4994.6    .033       0  4999.1     .05       0
Bank Sta=4994.6,4999.1
XS Rating Curve= 0 ,0
Exp/Cntr=0.3,0.1

Type RM Length L Ch R = 1 ,35541   ,467,467,467
BEGIN DESCRIPTION:
North Pecan Creek 69.0
END DESCRIPTION:
XS GIS Cut Line= 3
      2298078.99        7183860.        2297979.        7183860.
      2297579.01        7184060.
#Sta/Elev= 30
  4900.9  910.15  4910.9  909.48  4940.9  904.14  4950.9  901.88  4970.9   896.2
  4988.6  893.24  4989.1  892.74  4992.7  892.74  4993.1  893.24  5003.7   893.6
  5037.2  896.37    5054  896.16  5059.6  896.66    5068  895.92  5090.3  895.51
  5121.1  896.26    5149  895.59  5157.4  895.78  5165.8  896.68  5171.4  896.28
  5179.8  896.99  5260.8  897.57  5277.6  899.86  5291.6  903.34  5313.9  902.74
  5327.9  903.12  5350.3  907.01  5358.7  907.72  5425.7  910.58  5448.1  912.22
#Mann= 3 ,-1 , 0
  4900.9     .05       0  4988.6    .033       0  4993.1     .05       0
Bank Sta=4988.6,4993.1
XS Rating Curve= 0 ,0
Exp/Cntr=0.3,0.1

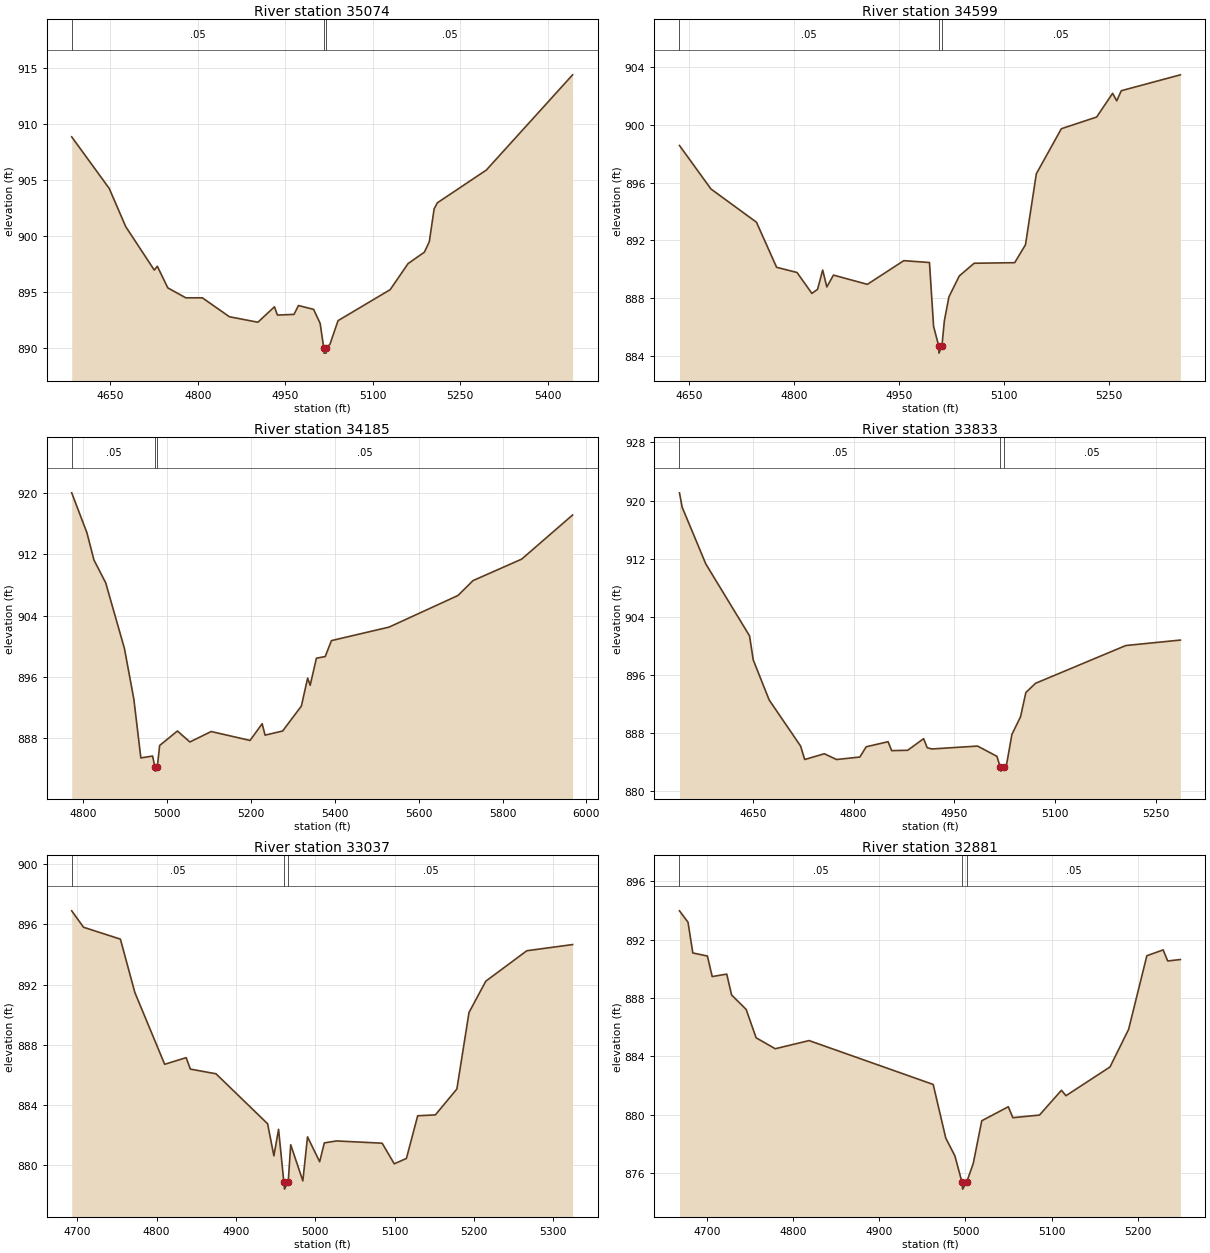
Type RM Length L Ch R = 1 ,35074   ,475,475,475
BEGIN DESCRIPTION:
North Pecan Creek 68.0
END DESCRIPTION:
XS GIS Cut Line= 3
        2298129.        7183610.        2297729.        7183510.
      2297329.02      7183709.99
#Sta/Elev= 30
  4583.5  908.89  4647.9  904.28  4676.3  900.86  4725.2  896.99  4730.4  897.33
  4748.4   895.4  4779.3  894.51  4807.7  894.51  4854.1  892.82    4903  892.33
  4931.4  893.71  4936.5  892.97  4964.9  893.03  4972.6  893.82  4998.6  893.48
  5009.8  892.23  5015.9  890.07  5016.4  889.57    5020  889.57  5020.5  890.07
  5026.6  890.36  5040.5  892.47    5130  895.24  5160.7  897.57  5188.7  898.59
  5197.1  899.52  5205.4  902.46    5211     903  5294.9  905.92    5443  914.43
#Mann= 3 ,-1 , 0
  4583.5     .05       0  5015.9    .033       0  5020.5     .05       0
Bank Sta=5015.9,5020.5
XS Rating Curve= 0 ,0
Exp/Cntr=0.3,0.1

Type RM Length L Ch R = 1 ,34599   ,414,414,414
BEGIN DESCRIPTION:
Mapping XS a7938b31
END DESCRIPTION:
XS GIS Cut Line= 3
      2298017.35      7183372.85       2297573.5      7183100.45
      2297407.12      7183203.16
#Sta/Elev= 30
  4635.9  898.57  4680.9  895.56    4746  893.26  4774.8  890.14    4804  889.78
  4825.3  888.33  4833.4  888.62  4840.7  889.95  4846.6  888.78  4856.1   889.6
  4904.6  888.96  4956.7   890.6  4993.4  890.47  4999.3  886.05  5006.6   884.7
    5007   884.2  5011.2   884.7  5014.7  886.44  5021.2  888.09    5036  889.54
  5057.3  890.42  5115.3  890.46  5130.7   891.7  5146.2  896.61    5182  899.73
  5232.5  900.54  5255.3  902.18  5261.2  901.66  5267.7  902.36  5352.2  903.46
#Mann= 3 ,-1 , 0
  4635.9     .05       0  5006.6    .033       0  5011.2     .05       0
Bank Sta=5006.6,5011.2
XS Rating Curve= 0 ,0
Exp/Cntr=0.3,0.1

Type RM Length L Ch R = 1 ,34185   ,352,352,352
BEGIN DESCRIPTION:
North Pecan Creek 67.0
END DESCRIPTION:
XS GIS Cut Line= 3
      2298079.04      7182759.98        2297879.        7182860.
      2297078.98      7183410.02
#Sta/Elev= 30
  4772.4  920.01  4808.8  914.79  4825.5  911.25  4853.5  908.28  4898.2  899.71
  4920.6  893.12  4937.3  885.46  4965.3  885.71  4970.9  884.24  4971.7  883.74
  4976.4  884.24  4982.1  887.08  5024.5  888.97  5054.2  887.54    5105   888.9
  5197.7  887.74  5226.6  889.92  5233.5  888.43  5275.4  888.97  5320.1  892.22
    5335  895.86  5341.1  894.93    5356  898.46  5376.9  898.67  5391.8  900.75
  5529.2  902.51  5693.6  906.63  5729.4  908.57  5845.5  911.37  5966.9  917.12
#Mann= 3 ,-1 , 0
  4772.4     .05       0  4970.9    .033       0  4976.4     .05       0
Bank Sta=4970.9,4976.4
XS Rating Curve= 0 ,0
Exp/Cntr=0.3,0.1

Type RM Length L Ch R = 1 ,33833   ,796,796,796
BEGIN DESCRIPTION:
Mapping XS f75c72c7
END DESCRIPTION:
XS GIS Cut Line= 3
      2298025.13      7182552.34      2297632.44      7182717.75
      2297383.93      7182918.55
#Sta/Elev= 30
  4540.8  921.07  4544.8  919.09    4580  911.28  4645.1  901.38  4650.6  898.07
  4674.3  892.56  4721.1  886.21  4727.2  884.36  4756.4  885.15  4774.7  884.36
  4809.3   884.7  4818.7  886.11  4851.3  886.81  4856.7  885.58  4880.5  885.63
  4904.2  887.23  4909.6  885.98  4916.4  885.81  4984.5  886.21  5013.3   884.8
  5018.5  883.26  5019.3  882.76    5024  883.26  5027.7  883.66  5035.6   887.8
  5048.5  890.25  5056.4  893.58  5070.8  894.85  5205.2  900.05  5286.4   900.8
#Mann= 3 ,-1 , 0
  4540.8     .05       0  5018.5    .033       0    5024     .05       0
Bank Sta=5018.5,5024
XS Rating Curve= 0 ,0
Exp/Cntr=0.3,0.1

Type RM Length L Ch R = 1 ,33037   ,156,156,156
BEGIN DESCRIPTION:
Mapping XS 192b28a7
END DESCRIPTION:
XS GIS Cut Line= 3
      2297767.58      7182250.33      2297594.03      7182305.04
      2297354.08      7182685.17
#Sta/Elev= 30
    4693   896.9  4707.9  895.81  4754.4  895.02  4772.6  891.48  4810.2  886.71
  4837.3  887.15  4842.6  886.39  4874.9  886.08    4940  882.76  4947.9  880.63
  4953.8  882.39  4960.4  878.92  4961.3  878.42    4966  878.92  4969.1  881.37
  4984.4  878.97  4990.3  881.89  5005.6  880.24  5011.5  881.49  5026.8  881.62
  5084.4  881.47  5099.7   880.1    5115  880.46  5129.2  883.29  5151.5  883.35
  5178.6  885.07  5193.9  890.15  5215.1  892.23  5266.8  894.25  5324.5  894.66
#Mann= 3 ,-1 , 0
    4693     .05       0  4960.4    .033       0    4966     .05       0
Bank Sta=4960.4,4966
XS Rating Curve= 0 ,0
Exp/Cntr=0.3,0.1

Type RM Length L Ch R = 1 ,32881   ,234,234,234
BEGIN DESCRIPTION:
Mapping XS 461c9cdd
END DESCRIPTION:
XS GIS Cut Line= 3
       2297540.3      7182030.09      2297426.15      7182263.29
      2297318.29      7182566.65
#Sta/Elev= 30
  4667.9  893.98  4677.8   893.2  4683.4  891.09  4700.3  890.88  4705.9  889.47
  4722.8  889.64  4728.4  888.21  4745.3  887.22  4756.9  885.27  4779.1  884.52
  4818.4  885.08  4962.5  882.07  4977.1  878.39  4987.7  877.17  4995.8  875.39
  4996.7  874.89  5001.5  875.39    5009  876.65  5018.9  879.58  5049.7  880.54
    5055  879.79  5085.9  879.97  5111.4  881.67  5116.7   881.3  5167.8  883.27
  5189.4  885.85  5210.6   890.9  5229.5   891.3  5234.8  890.54  5249.5  890.64
#Mann= 3 ,-1 , 0
  4667.9     .05       0  4995.8    .033       0  5001.5     .05       0
Bank Sta=4995.8,5001.5
XS Rating Curve= 0 ,0
Exp/Cntr=0.3,0.1

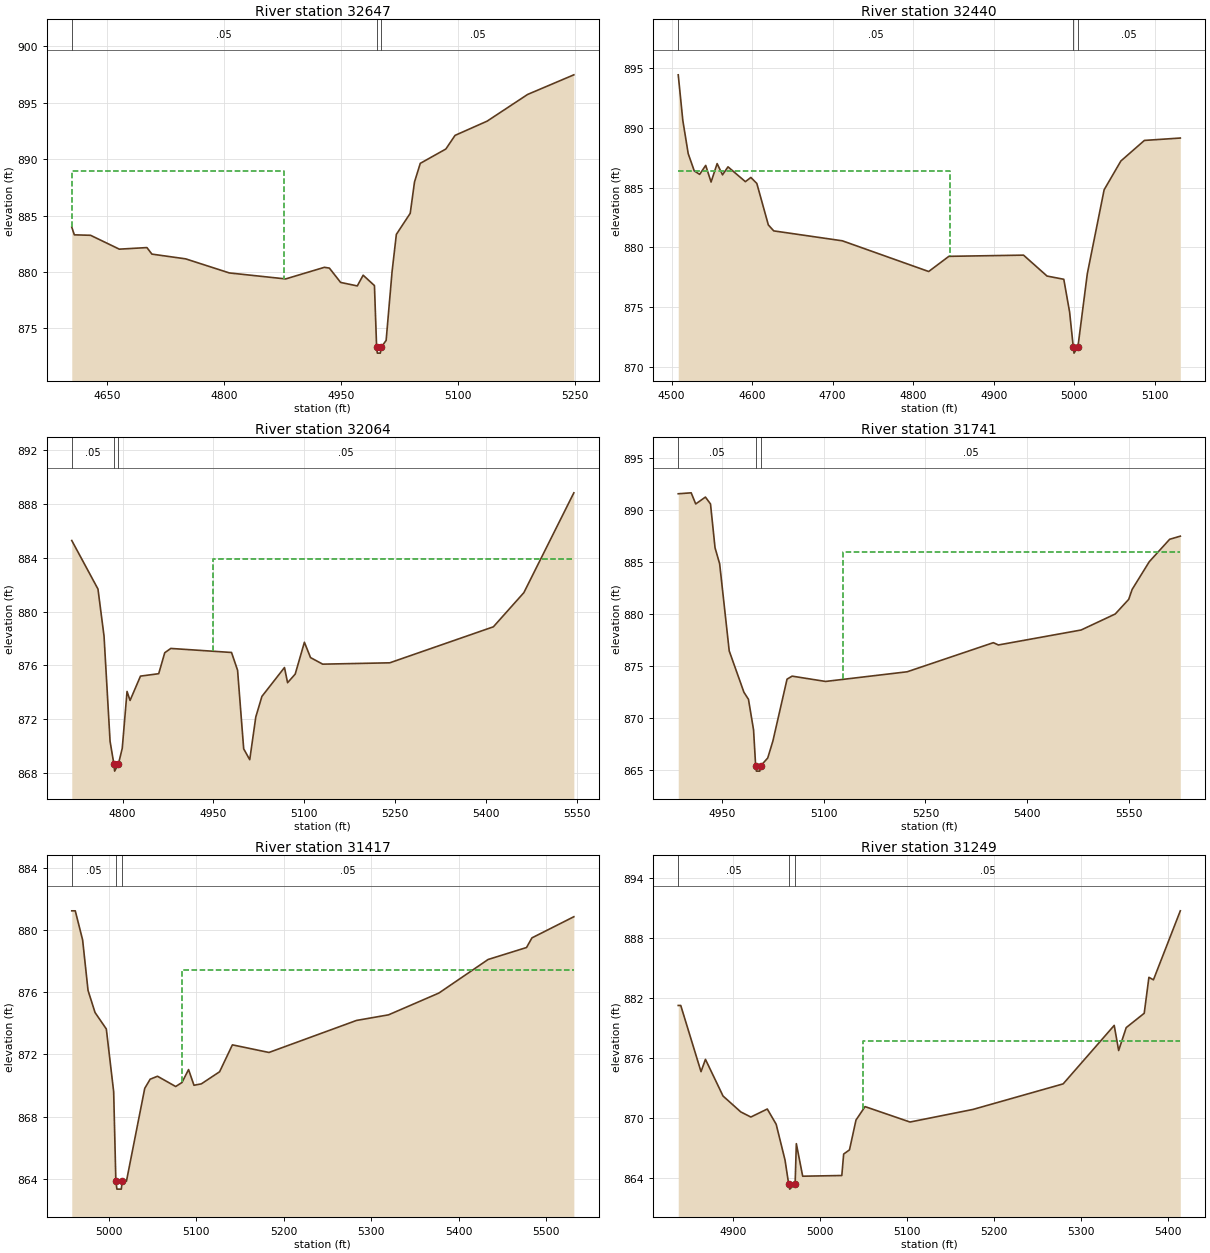
Type RM Length L Ch R = 1 ,32647   ,207,207,207
BEGIN DESCRIPTION:
Mapping XS 955c453f
END DESCRIPTION:
XS GIS Cut Line= 3
      2297445.81      7182022.06      2297200.68      7182333.85
       2297100.3      7182560.06
#Sta/Elev= 30
  4604.5  883.97  4607.8  883.29  4628.6  883.25  4665.5  882.02  4700.9  882.16
  4707.3  881.58  4750.6  881.16  4806.7  879.91  4878.9  879.38  4928.6  880.41
    4935  880.34  4949.4  879.07  4970.8  878.76  4978.3  879.71  4992.8  878.79
  4995.6   873.3  4996.5   872.8  5000.4   872.8  5001.3   873.3  5007.8  873.93
  5015.4  880.02  5020.9  883.33  5038.7   885.2  5044.2  887.98  5051.6  889.63
  5084.4   890.9  5096.2  892.11  5137.3  893.37  5189.3  895.74  5248.6  897.48
#Mann= 3 ,-1 , 0
  4604.5     .05       0  4995.6    .033       0  5001.3     .05       0
#XS Ineff= 2 , 0
       0    4877  888.93               0
Permanent Ineff=
       F       F
Bank Sta=4995.6,5001.3
XS Rating Curve= 0 ,0
Exp/Cntr=0.3,0.1

Type RM Length L Ch R = 1 ,32440   ,376,376,376
BEGIN DESCRIPTION:
Mapping XS be657d6b
END DESCRIPTION:
XS GIS Cut Line= 4
       2297470.7      7181933.99      2297293.19      7182132.21
      2297141.43      7182160.52      2296978.91      7182282.23
#Sta/Elev= 30
  4508.2  894.45  4513.9  890.63  4520.6  887.85  4528.1  886.41  4534.8  886.12
  4542.3  886.87    4549  885.48  4556.5  887.02  4563.2  886.08    4570  886.75
  4591.6  885.51  4598.4  885.86  4605.8  885.36  4620.1  881.89  4626.8  881.39
    4712  880.56  4819.2  877.99  4844.3  879.26    4937  879.36  4966.2  877.61
    4987  877.34  4994.2  874.61  4998.8  871.66  4999.7  871.16  5004.5  871.66
  5016.2   877.8  5037.1  884.83  5057.9  887.24  5087.1  888.96  5131.7  889.16
#Mann= 3 ,-1 , 0
  4508.2     .05       0  4998.8    .033       0  5004.5     .05       0
#XS Ineff= 2 , 0
       0  4845.5  886.38               0
Permanent Ineff=
       F       F
Bank Sta=4998.8,5004.5
XS Rating Curve= 0 ,0
Exp/Cntr=0.3,0.1

Type RM Length L Ch R = 1 ,32064   ,323,323,323
BEGIN DESCRIPTION:
Mapping XS f3c8f232
END DESCRIPTION:
XS GIS Cut Line= 3
      2297412.13      7181902.26      2297044.11      7181873.81
      2296586.98      7181927.57
#Sta/Elev= 30
  4716.1  885.29  4759.4  881.68  4769.4  878.18  4779.4  870.34  4785.8  868.63
  4786.9  868.13    4793  868.63  4799.5  869.83  4807.4  874.06  4812.4  873.39
  4829.6   875.2  4859.7  875.38  4869.7  876.94  4879.7  877.26    4980  876.96
    4990  875.64  5000.1  869.79  5010.1  868.98  5020.1  872.16  5030.2  873.69
  5067.5  875.84  5072.6  874.71  5085.2  875.35  5100.4  877.72  5110.5  876.58
  5130.6  876.09  5241.4  876.19  5412.6  878.87  5462.9  881.41  5545.5  888.84
#Mann= 3 ,-1 , 0
  4716.1     .05       0  4785.8    .033       0    4793     .05       0
#XS Ineff= 2 , 0
    4950       0  883.91               0
Permanent Ineff=
       F       F
Bank Sta=4785.8,4793
XS Rating Curve= 0 ,0
Exp/Cntr=0.3,0.1

Type RM Length L Ch R = 1 ,31741   ,324,324,324
BEGIN DESCRIPTION:
Mapping XS e8fff18e
END DESCRIPTION:
XS GIS Cut Line= 3
      2297159.96      7181524.33      2296836.93      7181887.28
       2296583.4      7181911.89
#Sta/Elev= 30
  4885.4  891.59  4904.5  891.68  4911.2  890.61  4925.5  891.27    4933  890.61
  4939.7  886.39  4946.5  884.85  4960.6  876.47  4982.3  872.49    4989  871.81
  4996.5  868.87  4999.6   865.4  5000.7   864.9  5005.7   864.9  5006.9   865.4
  5017.4  866.16    5025  867.79  5045.9  873.75  5053.4  874.04  5102.7  873.53
  5223.1  874.46  5350.2  877.26  5357.7  877.04  5479.7  878.48    5530  880.02
  5549.9  881.43  5554.9  882.38  5580.2  885.05  5610.3  887.21    5626  887.51
#Mann= 3 ,-1 , 0
  4885.4     .05       0  4999.6    .033       0  5006.9     .05       0
#XS Ineff= 2 , 0
       0                  5127.9       0  885.96
Permanent Ineff=
       F       F
Bank Sta=4999.6,5006.9
XS Rating Curve= 0 ,0
Exp/Cntr=0.3,0.1

Type RM Length L Ch R = 1 ,31417   ,168,168,168
BEGIN DESCRIPTION:
Mapping XS 4d8fbd84
END DESCRIPTION:
XS GIS Cut Line= 2
      2296944.01      7181328.62      2296603.25       7181790.4
#Sta/Elev= 30
  4957.9  881.24  4961.9  881.24  4970.3  879.37  4976.5  876.12  4984.5   874.7
  4997.4  873.64  5005.8   869.6  5008.3  863.84  5009.5  863.34  5014.5  863.34
  5015.6  863.84  5020.4  863.85  5041.3  869.82  5047.5  870.41  5055.9   870.6
  5076.7  869.94  5083.9   870.2  5091.4  871.03  5097.6  870.02    5106  870.11
  5126.9  870.89  5141.5  872.62  5183.3  872.13  5283.4  874.19    5320  874.55
  5377.5  875.95  5433.8  878.11  5477.7  878.88  5483.9   879.5  5531.8  880.86
#Mann= 3 ,-1 , 0
  4957.9     .05       0  5008.3    .033       0  5015.6     .05       0
#XS Ineff= 2 , 0
       0  4915.9  877.45  5084.1       0  877.45
Permanent Ineff=
       F       F
Bank Sta=5008.3,5015.6
XS Rating Curve= 0 ,0
Exp/Cntr=0.3,0.1

Type RM Length L Ch R = 1 ,31249   ,44,44,44
BEGIN DESCRIPTION:
Mapping XS 9eff62f4
END DESCRIPTION:
XS GIS Cut Line= 3
      2296939.62      7181329.89      2296751.46       7181294.2
      2296378.88      7181394.27
#Sta/Elev= 30
    4837  881.24  4839.9  881.24  4863.2  874.63  4868.3  875.86  4888.5   872.2
  4908.9  870.61  4920.5   870.1  4939.4   870.9  4949.6  869.38  4959.8   865.8
    4964   863.4  4965.2   862.9  4971.4   863.4  4972.8  867.44  4980.1  864.19
  5025.1  864.26  5027.2   866.4  5033.9  866.82  5041.4   869.8  5051.8  871.14
  5103.5   869.6    5176  870.86  5279.6  873.41  5338.3  879.25  5343.4  876.74
  5352.1  879.03  5372.8  880.46  5378.2  884.05  5383.4   883.8  5414.3  890.69
#Mann= 3 ,-1 , 0
    4837     .05       0    4964    .033       0  4971.4     .05       0
#XS Ineff= 2 , 0
       0                  5049.7       0  877.73
Permanent Ineff=
       F       F
Bank Sta=4964,4971.4
XS Rating Curve= 0 ,0
Exp/Cntr=0.3,0.1

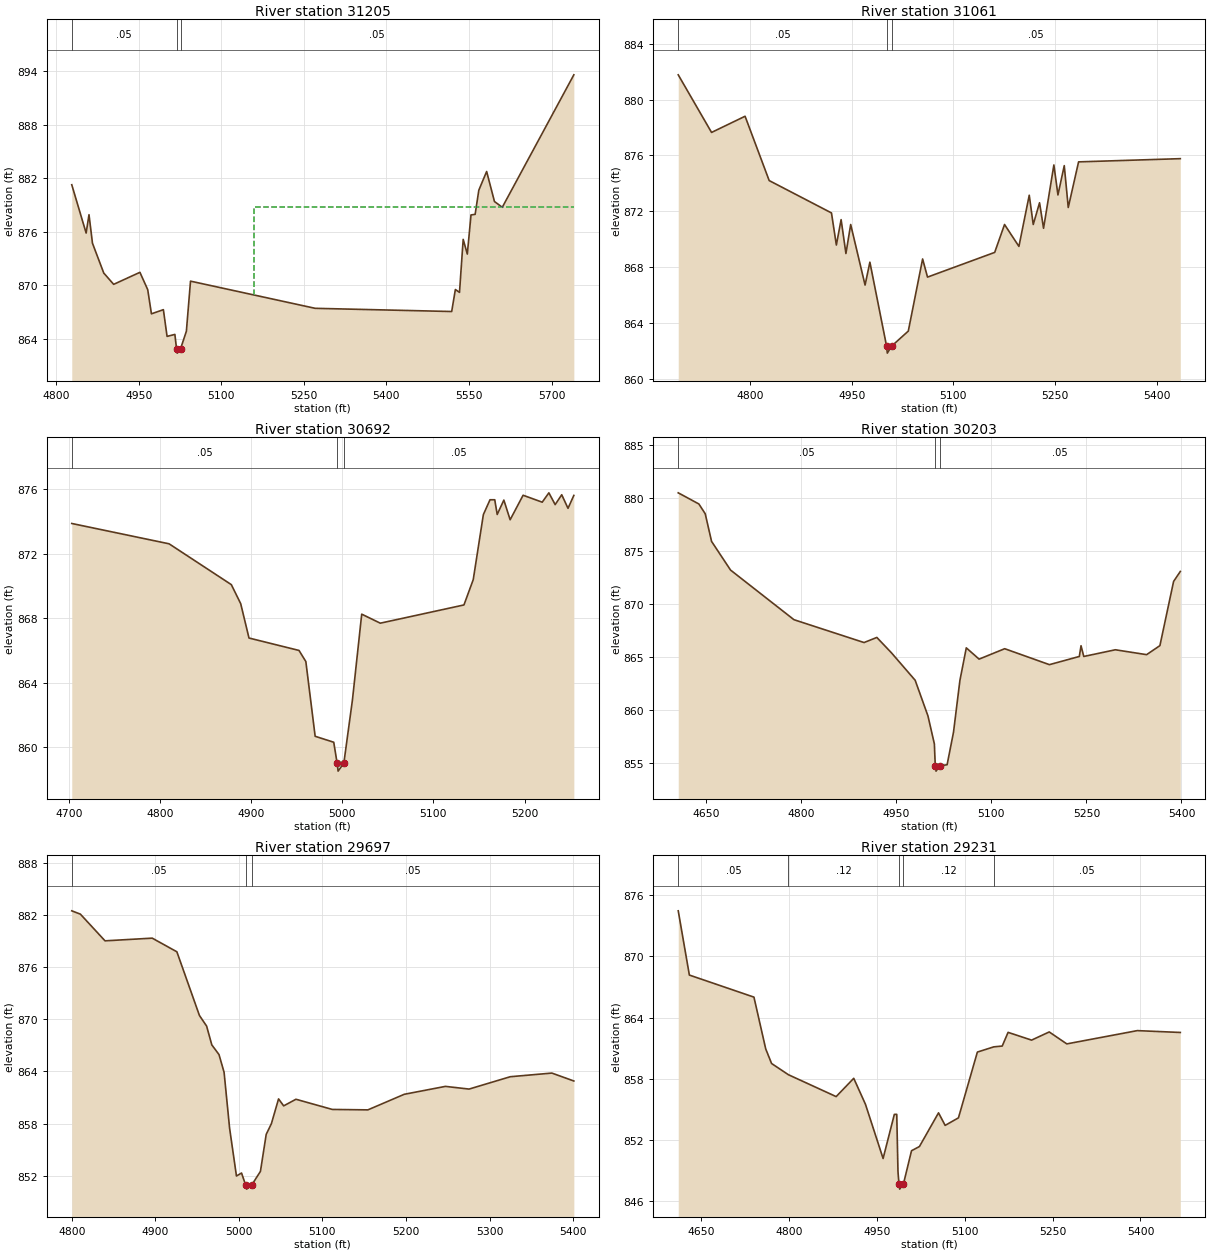
Type RM Length L Ch R = 1 ,31205   ,144,144,144
BEGIN DESCRIPTION:
Mapping XS fc838968
END DESCRIPTION:
XS GIS Cut Line= 4
      2296935.84      7181321.14      2296822.35      7181297.39
      2296372.43      7180801.39      2296248.95      7180828.37
#Sta/Elev= 30
  4828.5  881.28  4854.6  875.86  4859.8  877.92  4866.1  874.72  4886.6  871.37
  4904.6   870.1  4952.3  871.45  4966.5   869.5  4973.2  866.79  4994.9  867.26
  5001.6  864.26  5015.8  864.48  5018.8  862.88    5020  862.38  5026.2  862.88
  5036.7  864.84  5044.2  870.46  5270.6  867.41  5518.6  867.05  5525.3  869.52
  5532.8   869.2  5539.5  875.15    5547   873.5  5553.7  877.89  5561.2  877.96
  5567.9  880.67  5582.1  882.77  5596.3   879.4  5610.5  878.75  5740.5  893.62
#Mann= 3 ,-1 , 0
  4828.5     .05       0  5018.8     .04       0  5026.2     .05       0
#XS Ineff= 2 , 0
       0                  5159.9       0  878.82
Permanent Ineff=
       F       F
Bank Sta=5018.8,5026.2
XS Rating Curve= 0 ,0
Exp/Cntr=0.3,0.1

Type RM Length L Ch R = 1 ,31061   ,369,369,369
BEGIN DESCRIPTION:
Mapping XS 81379cef
END DESCRIPTION:
XS GIS Cut Line= 4
      2297091.83      7181366.53      2296763.95        7181032.
      2296588.56      7180919.81      2296544.29      7180874.73
#Sta/Elev= 30
  4694.5  881.77  4743.6  877.64    4793   878.8  4828.5  874.19  4920.3  871.87
  4927.5  869.57  4934.5  871.39  4941.6  868.96  4948.6  871.04  4969.8   866.7
  4976.9  868.34  5001.5  862.32  5002.6  861.82  5008.9  862.32  5033.5   863.4
  5054.6  868.57  5061.8  867.27  5160.8  869.04  5175.3  871.04  5196.5  869.47
  5211.7  873.14  5217.6  871.04  5226.9   872.6  5232.8  870.77    5248  875.31
    5254  873.16  5263.3  875.26  5269.2  872.26  5284.4  875.53  5434.3  875.76
#Mann= 3 ,-1 , 0
  4694.5     .05       0  5001.5     .05       0  5008.9     .05       0
Bank Sta=5001.5,5008.9
XS Rating Curve= 0 ,0
Exp/Cntr=0.3,0.1

Type RM Length L Ch R = 1 ,30692   ,489,489,489
BEGIN DESCRIPTION:
Mapping XS c7c602c5
END DESCRIPTION:
XS GIS Cut Line= 4
      2297070.08      7180832.53      2296854.87      7180879.68
       2296617.9      7180927.91      2296553.57      7180866.61
#Sta/Elev= 30
  4703.1  873.88  4809.9  872.62  4878.2  870.09  4888.5  868.91  4897.6  866.78
  4952.5  866.01    4960  865.32  4970.2  860.69  4990.6  860.32  4994.3  859.03
  4995.4  858.53  5001.7  859.03  5011.1  862.93  5021.3  868.26  5041.7   867.7
  5133.5  868.83  5143.7   870.4  5154.8  874.43  5162.1  875.35  5167.3  875.35
    5170  874.44  5177.3  875.33  5184.2  874.11  5198.4  875.63  5219.4   875.2
  5226.7  875.78  5233.6  875.05  5240.8  875.66  5247.7  874.82  5254.1  875.62
#Mann= 3 ,-1 , 0
  4703.1     .05       0  4994.3    .033       0  5001.7     .05       0
Bank Sta=4994.3,5001.7
XS Rating Curve= 0 ,0
Exp/Cntr=0.3,0.1

Type RM Length L Ch R = 1 ,30203   ,506,506,506
BEGIN DESCRIPTION:
Mapping XS f5f6d100
END DESCRIPTION:
XS GIS Cut Line= 4
      2297071.54      7180565.67      2296829.72      7180577.32
      2296438.53      7180524.74      2296323.81        7180630.
#Sta/Elev= 30
  4605.7  880.46  4638.3  879.41  4648.3  878.49  4658.3  875.89  4688.3  873.19
  4788.4  868.52    4899  866.37  4919.2  866.85  4942.3   865.4  4979.7  862.82
  4999.9  859.46    5010  856.83  5011.4  854.77  5012.6  854.27  5018.9  854.77
  5030.1  854.87  5040.2  857.93  5050.3   862.8  5060.4  865.87  5080.6  864.81
    5121  865.79  5191.6  864.29  5238.8  865.06  5241.5  866.07  5245.8  865.06
  5295.7  865.69    5345  865.23    5366  866.08  5387.6  872.12  5398.2  873.06
#Mann= 3 ,-1 , 0
  4605.7     .05       0  5011.4    .033       0  5018.9     .05       0
Bank Sta=5011.4,5018.9
XS Rating Curve= 0 ,0
Exp/Cntr=0.3,0.1

Type RM Length L Ch R = 1 ,29697   ,466,466,466
BEGIN DESCRIPTION:
Mapping XS f3a0be9a
END DESCRIPTION:
XS GIS Cut Line= 3
      2296892.71      7179979.26      2296553.73      7180221.48
      2296427.11      7180355.36
#Sta/Elev= 30
    4800  882.45  4810.3  882.07  4839.8     879  4896.3  879.31  4925.8  877.74
  4952.8  870.42  4961.4   869.2  4967.6  867.04  4976.2  865.93  4982.3  863.89
  4988.9  857.46  4997.1  851.97  5003.2  852.31    5008  850.96  5009.2  850.46
  5015.6  850.96  5025.8   852.5  5032.7  856.75  5038.9  857.98  5047.5  860.83
  5053.6  860.03  5068.3  860.79  5111.8  859.62  5154.4  859.57  5197.9  861.36
  5247.2  862.27  5275.5  861.96  5324.8  863.38  5374.6   863.8  5400.9  862.89
#Mann= 3 ,-1 , 0
    4800     .05       0    5008    .033       0  5015.6     .05       0
Bank Sta=5008,5015.6
XS Rating Curve= 0 ,0
Exp/Cntr=0.3,0.1

Type RM Length L Ch R = 1 ,29231   ,423,423,423
BEGIN DESCRIPTION:
Mapping XS c5498827
END DESCRIPTION:
XS GIS Cut Line= 4
        2296828.      7179823.26      2296455.68      7179844.87
       2296387.8      7179993.85       2296410.6      7180313.17
#Sta/Elev= 30
  4611.2  874.46  4630.2  868.17  4740.4  866.01  4760.5  860.94  4770.5  859.51
  4799.3  858.41  4880.7  856.27  4910.7  858.06  4930.7  855.52  4960.8  850.21
    4980  854.53  4984.1  854.53  4986.2  848.92  4987.9  847.71  4989.1  847.21
  4995.5  847.71  5009.3  850.97  5022.8  851.38  5055.4  854.68  5066.7  853.45
  5089.4  854.19  5121.7  860.63  5149.7  861.14  5164.1  861.22  5174.1  862.56
  5214.2   861.8  5244.3   862.6  5274.3  861.43  5394.6  862.73    5468  862.55
#Mann= 5 ,-1 , 0
  4611.2     .05       0  4799.3     .12       0  4987.9     .07       0
  4995.5     .12       0  5149.7     .05       0
Bank Sta=4987.9,4995.5
XS Rating Curve= 0 ,0
Exp/Cntr=0.3,0.1