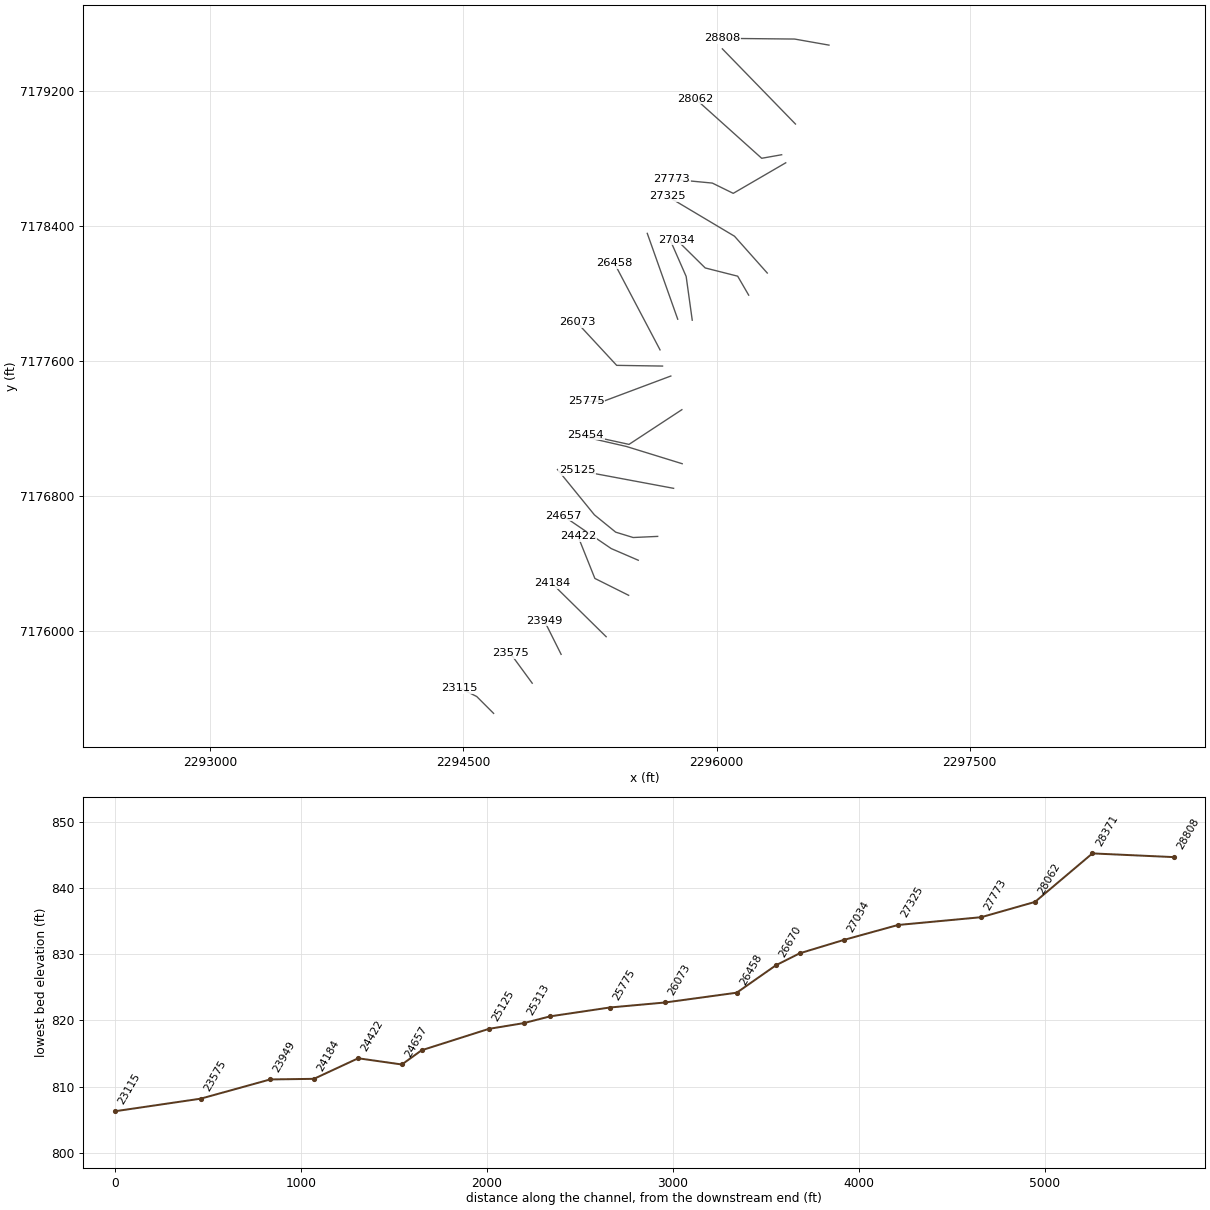
HEC-RAS study North Pecan Creek.prj: North Pecan Creek Base Level Engineering

--- North Pecan Creek.g01 (geometry) --- (continued)

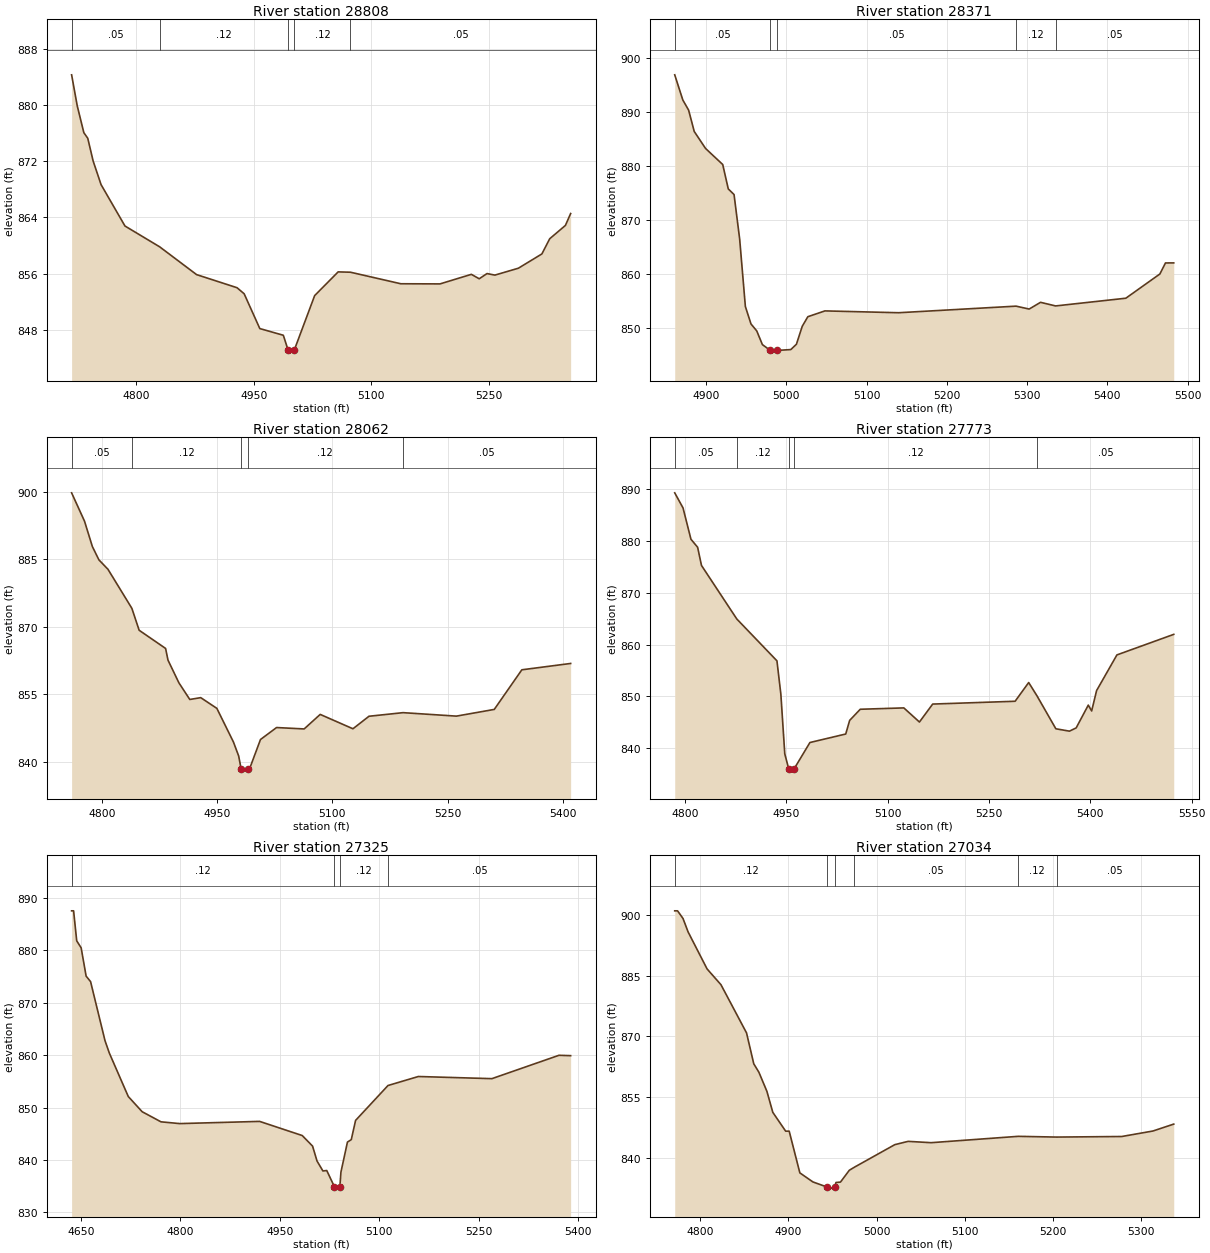
Type RM Length L Ch R = 1 ,28808   ,437,437,437
BEGIN DESCRIPTION:
Mapping XS b1f462a8
END DESCRIPTION:
XS GIS Cut Line= 3
      2296666.04      7179471.71      2296462.24      7179507.72
      2296032.32      7179511.95
#Sta/Elev= 30
  4717.6  884.27  4724.8  879.85  4733.2  876.05  4738.2  875.25  4745.1  872.01
  4755.2  868.66  4785.7  862.78    4830  859.82  4877.1  855.87  4928.7  854.01
  4937.8  853.15  4957.8   848.2  4987.8  847.25  4993.7  845.21  4994.9  844.71
    5002  845.21  5027.8  852.89  5057.8  856.26  5073.5  856.21  5137.8  854.57
  5187.8  854.55  5227.8  855.91  5237.8  855.28  5247.8  856.02  5257.8   855.8
  5287.8  856.78  5317.8  858.81  5327.8  860.97  5347.8  862.86  5354.5  864.55
#Mann= 5 ,-1 , 0
  4717.6     .05       0    4830     .12       0  4993.7     .07       0
    5002     .12       0  5073.5     .05       0
Bank Sta=4993.7,5002
XS Rating Curve= 0 ,0
Exp/Cntr=0.3,0.1

Type RM Length L Ch R = 1 ,28371   ,309,309,309
BEGIN DESCRIPTION:
Mapping XS 363af29e
END DESCRIPTION:
XS GIS Cut Line= 2
      2296467.37      7179003.92      2296034.16       7179449.7
#Sta/Elev= 30
  4861.1  896.87  4871.2   892.2  4878.4  890.33  4885.4  886.37  4899.5  883.22
  4920.9  880.24  4927.8  875.72    4935  874.67    4942  866.41  4949.1  853.91
  4956.1  850.68  4963.3  849.38  4970.3  846.85  4980.2  845.77  4981.5  845.27
  4988.6  845.77  5005.7  845.93  5012.7  846.92  5019.9  850.23  5026.9  852.02
  5048.2   853.1    5140  852.76  5286.3  853.98  5302.6  853.44  5316.8  854.69
  5335.5  854.02    5423  855.45  5465.4  859.94  5472.4  861.99  5482.7     862
#Mann= 5 ,-1 , 0
  4861.1     .05       0  4980.2    .033       0  4988.6     .05       0
  5286.3     .12       0  5335.5     .05       0
Bank Sta=4980.2,4988.6
XS Rating Curve= 0 ,0
Exp/Cntr=0.3,0.1

Type RM Length L Ch R = 1 ,28062   ,289,289,289
BEGIN DESCRIPTION:
Mapping XS 4c85860f
END DESCRIPTION:
XS GIS Cut Line= 3
      2296385.54      7178821.82      2296267.28      7178800.85
      2295873.58      7179154.61
#Sta/Elev= 30
  4760.6  899.81  4777.4   893.5  4787.6  887.87  4796.1  884.91  4807.9  882.81
    4839  874.13  4848.5  869.25  4882.9  865.21    4886  862.62  4900.2  857.57
  4914.4  853.86  4928.6  854.27  4949.6  851.89  4971.2   844.4    4978  841.29
  4981.2  838.43  4982.5  837.93  4989.6  838.43  4992.2  838.46  5006.4  844.96
  5027.3  847.62  5063.2  847.31  5084.1  850.54  5126.7  847.35  5147.6  850.13
  5191.9  850.93  5261.3  850.16  5310.6  851.65  5346.5  860.46    5410  861.87
#Mann= 5 ,-1 , 0
  4760.6     .05       0    4839     .12       0  4981.2     .07       0
  4989.6     .12       0  5191.9     .05       0
Bank Sta=4981.2,4989.6
XS Rating Curve= 0 ,0
Exp/Cntr=0.3,0.1

Type RM Length L Ch R = 1 ,27773   ,448,448,448
BEGIN DESCRIPTION:
Mapping XS 3f25e85c
END DESCRIPTION:
XS GIS Cut Line= 4
      2296409.76      7178774.07      2296098.77      7178592.96
      2295974.91      7178653.83       2295735.3       7178676.8
#Sta/Elev= 30
  4784.9  889.24  4797.2  886.33  4808.9   880.3  4818.8  878.75  4824.5  875.25
  4876.8  864.93  4936.2  856.87    4942  850.43  4947.8  838.94  4953.5  836.12
  4954.8  835.62  4961.9  836.12    4985  841.13    5038  842.77  5043.8  845.39
  5059.5  847.54    5124   847.8  5147.1  845.08  5166.7  848.54  5288.7  849.08
  5308.8  852.69  5321.2   850.1    5349  843.78  5369.1  843.32  5379.1  843.95
    5397  848.34    5402  847.21  5409.3  851.14  5439.4  858.01  5523.5  861.97
#Mann= 5 ,-1 , 0
  4784.9     .05       0  4876.8     .12       0  4953.5     .07       0
  4961.9     .12       0  5321.2     .05       0
Bank Sta=4953.5,4961.9
XS Rating Curve= 0 ,0
Exp/Cntr=0.3,0.1

Type RM Length L Ch R = 1 ,27325   ,291,291,291
BEGIN DESCRIPTION:
Mapping XS fa350244
END DESCRIPTION:
XS GIS Cut Line= 3
      2296300.31      7178120.56       2296106.1      7178338.87
       2295710.3      7178574.86
#Sta/Elev= 30
    4636  887.57    4639  887.57  4643.7  881.84  4650.4   880.5  4657.9   875.1
  4664.6  874.06  4686.4  862.78    4693  860.39  4721.5  852.12  4742.4  849.22
  4770.8  847.29  4799.2  846.95  4919.7  847.37    4984  844.67  4999.6  842.65
  5006.3  839.81  5015.2  837.91    5021  837.99  5032.4  834.94  5033.7  834.44
  5040.8  834.94  5042.4  837.69  5052.2  843.42    5058  843.89  5064.5  847.56
  5113.4  854.22  5159.2  855.94  5270.2  855.53  5371.4  859.99    5389  859.92
#Mann= 4 ,-1 , 0
    4636     .12       0  5032.4     .07       0  5040.8     .12       0
  5113.4     .05       0
Bank Sta=5032.4,5040.8
XS Rating Curve= 0 ,0
Exp/Cntr=0.3,0.1

Type RM Length L Ch R = 1 ,27034   ,237,237,237
BEGIN DESCRIPTION:
Mapping XS cae755f1
END DESCRIPTION:
XS GIS Cut Line= 4
      2296190.27      7177989.51      2296125.11      7178101.84
      2295932.65      7178150.71      2295763.32      7178317.77
#Sta/Elev= 30
  4770.9  901.04  4774.1  901.04  4780.3  899.15  4786.1  895.81  4807.6  886.67
  4823.4  882.75  4852.4  870.83  4860.6  863.19  4866.4  861.11  4875.5  856.38
  4882.2  851.18  4896.8  846.52  4900.8  846.52  4912.9   836.2  4927.7  833.96
    4944  832.68  4945.3  832.18  4952.6  832.68  4953.9  833.82    4959  833.92
    4969  836.84  4974.6  837.58  5020.6  843.18  5035.8     844  5061.8  843.67
  5160.6  845.24  5204.2  845.06  5278.2   845.2  5313.6  846.56  5337.2  848.27
#Mann= 6 ,-1 , 0
  4770.9     .12       0    4944    .033       0  4952.6     .12       0
  4974.6     .05       0  5160.6     .12       0  5204.2     .05       0
Bank Sta=4944,4952.6
XS Rating Curve= 0 ,0
Exp/Cntr=0.3,0.1

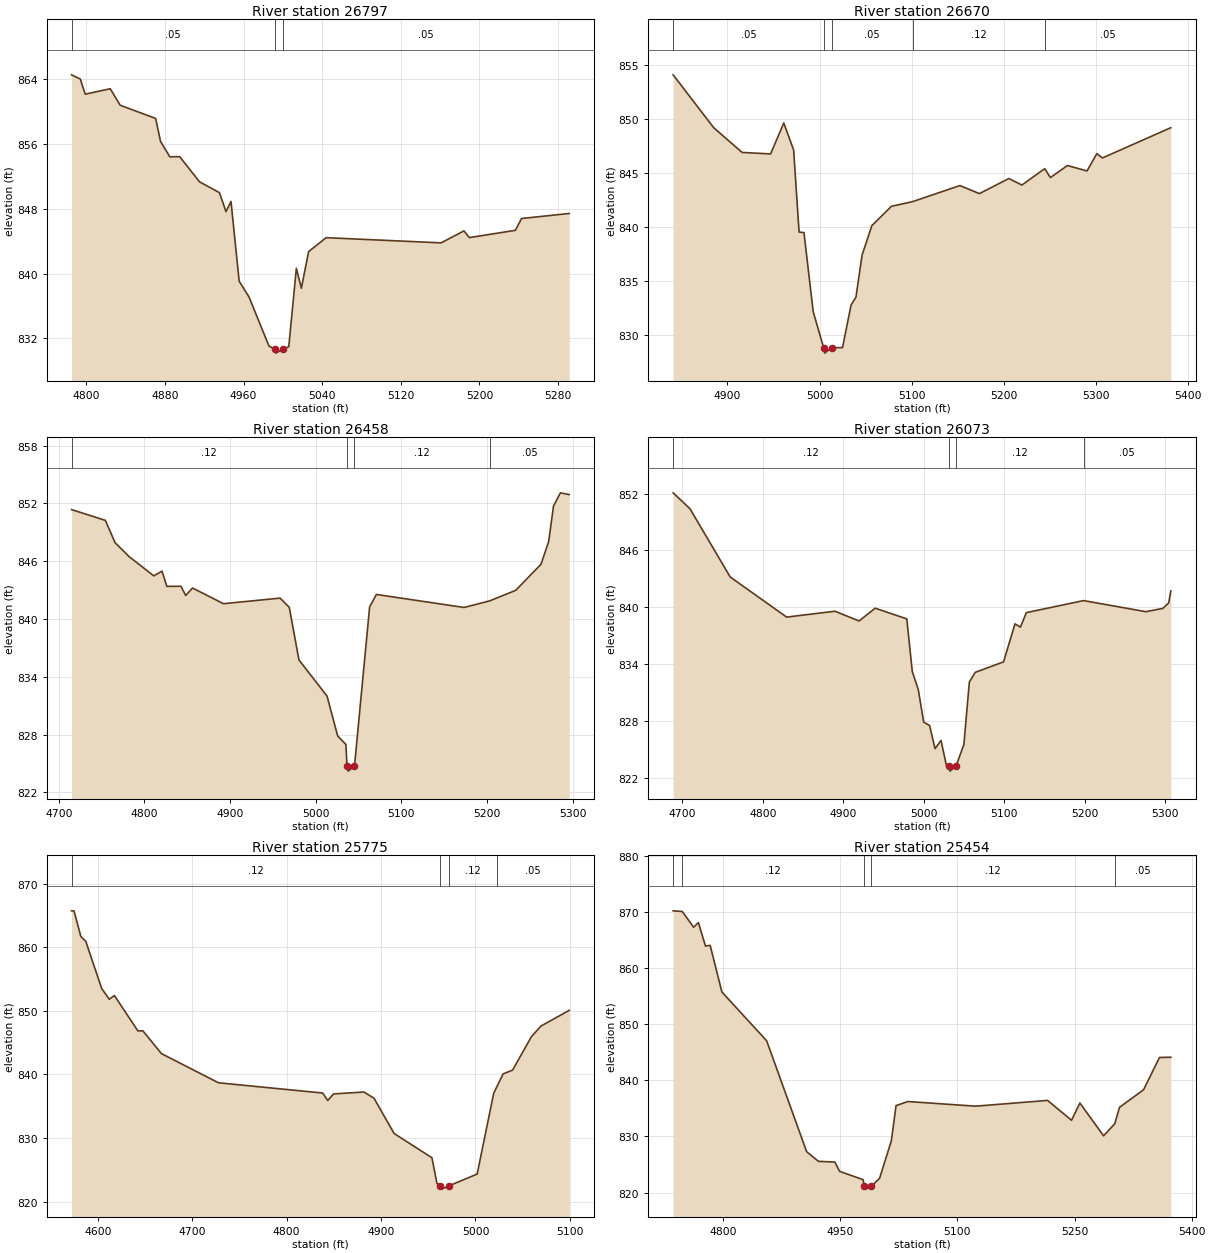
Type RM Length L Ch R = 1 ,26797   ,127,127,127
BEGIN DESCRIPTION:
Mapping XS 06868459
END DESCRIPTION:
XS GIS Cut Line= 3
      2295855.89      7177840.98      2295819.82      7178100.32
      2295721.63      7178324.42
#Sta/Elev= 30
  4784.9  864.56  4793.8  864.04  4798.8  862.17  4824.3  862.84  4834.4   860.8
  4870.5  859.17  4875.5  856.32  4884.9  854.43    4895  854.44  4915.2  851.33
  4935.4     850  4942.1  847.65  4947.2  848.91  4955.5  839.05  4965.6  837.08
  4985.8  831.04  4991.6  830.66  4992.9  830.16  5000.2  830.66    5006  830.96
  5013.7  840.64  5018.8  838.19  5026.2  842.71    5044  844.43    5161  843.79
  5184.3  845.27  5189.8  844.44  5236.6  845.34  5242.9   846.8  5291.4  847.42
#Mann= 3 ,-1 , 0
  4784.9     .05       0  4991.6    .033       0  5000.2     .05       0
Bank Sta=4991.6,5000.2
XS Rating Curve= 0 ,0
Exp/Cntr=0.3,0.1

Type RM Length L Ch R = 1 ,26670   ,212,212,212
BEGIN DESCRIPTION:
Mapping XS fddb6e45
END DESCRIPTION:
XS GIS Cut Line= 2
      2295769.85      7177846.86      2295589.47      7178355.63
#Sta/Elev= 30
  4841.1  854.05  4885.1  849.17  4915.9  846.89  4946.8  846.75  4961.1  849.61
  4971.8  847.11  4977.7  839.54    4983  839.49    4993   832.2  5004.3  828.87
  5005.5  828.37  5012.9  828.87  5024.8  828.88  5034.1  832.81  5039.4  833.54
    5046  837.41  5056.6  840.13  5077.9  841.92  5100.9  842.35  5152.1  843.83
  5173.3  843.09  5205.2  844.48  5219.4  843.88  5244.1  845.39  5250.3  844.57
  5268.8  845.68    5290  845.18  5300.7  846.78  5306.7  846.38  5380.9  849.17
#Mann= 5 ,-1 , 0
  4841.1     .05       0  5004.3    .033       0  5012.9     .05       0
  5100.9     .12       0  5244.1     .05       0
Bank Sta=5004.3,5012.9
XS Rating Curve= 0 ,0
Exp/Cntr=0.3,0.1

Type RM Length L Ch R = 1 ,26458   ,385,385,385
BEGIN DESCRIPTION:
Mapping XS 86127633
END DESCRIPTION:
XS GIS Cut Line= 2
      2295665.06      7177665.05      2295394.36      7178179.13
#Sta/Elev= 30
    4715  851.35  4754.5  850.23  4765.8  847.92  4782.2  846.47    4811  844.47
  4820.6  844.96  4826.3  843.38  4842.7  843.39  4848.3  842.43  4856.2  843.21
  4892.4  841.58  4958.5  842.16  4969.2   841.2  4980.5  835.74  5013.3  831.99
  5025.7  827.85  5035.3  826.97  5036.6   824.7  5037.9   824.2  5045.3   824.7
    5063  841.24  5070.9  842.54  5173.2  841.19  5203.1  841.87  5233.6  842.97
  5263.1  845.68    5272  848.02  5277.7  851.72  5285.7  853.09    5296  852.91
#Mann= 4 ,-1 , 0
    4715     .12       0  5036.6     .07       0  5045.3     .12       0
  5203.1     .05       0
Bank Sta=5036.6,5045.3
XS Rating Curve= 0 ,0
Exp/Cntr=0.3,0.1

Type RM Length L Ch R = 1 ,26073   ,298,298,298
BEGIN DESCRIPTION:
Mapping XS 1ba295ca
END DESCRIPTION:
XS GIS Cut Line= 3
      2295679.94      7177569.03      2295408.15      7177573.19
       2295172.8      7177827.47
#Sta/Elev= 30
  4688.7  852.08  4709.6   850.4  4759.6   843.2  4829.7  838.97  4889.7  839.59
  4919.7  838.56  4939.7  839.91    4979  838.78  4985.8  833.23  4993.2  831.34
    5000  827.89  5007.3  827.53  5014.1  825.09  5021.5  825.96  5028.3  823.28
  5031.3  823.22  5032.6  822.72    5040  823.22  5049.9  825.52  5056.7  832.12
    5064  833.14  5099.2  834.25  5113.4  838.26  5120.2  837.91  5127.5  839.44
  5198.6  840.71  5276.1  839.54  5297.1  839.89  5304.4  840.47    5307  841.73
#Mann= 4 ,-1 , 0
  4688.7     .12       0  5031.3     .07       0    5040     .12       0
  5198.6     .05       0
Bank Sta=5031.3,5040
XS Rating Curve= 0 ,0
Exp/Cntr=0.3,0.1

Type RM Length L Ch R = 1 ,25775   ,321,321,321
BEGIN DESCRIPTION:
North Pecan Creek 48.0
END DESCRIPTION:
XS GIS Cut Line= 3
      2295728.96      7177509.99        2295329.        7177360.
      2295228.96        7177360.
#Sta/Elev= 30
  4572.1  865.72  4574.7  865.72  4581.9  861.71  4587.2  860.91  4604.1  853.48
  4612.1  851.82  4617.5   852.4  4642.4  846.84  4647.7  846.85  4667.3  843.27
  4727.8  838.68  4838.2  837.07  4843.5   835.9  4849.7  836.93  4881.8  837.23
  4892.5  836.26  4913.8  830.71  4953.9  826.89  4959.2  822.85  4962.9  822.46
  4964.1  821.96  4971.6  822.46  5001.8  824.33  5019.3  837.03  5022.6  838.04
  5029.3  840.08  5039.3  840.67  5059.3  845.94  5069.3  847.59  5099.3  850.07
#Mann= 4 ,-1 , 0
  4572.1     .12       0  4962.9     .07       0  4971.6     .12       0
  5022.6     .05       0
Bank Sta=4962.9,4971.6
XS Rating Curve= 0 ,0
Exp/Cntr=0.3,0.1

Type RM Length L Ch R = 1 ,25454   ,141,141,141
BEGIN DESCRIPTION:
Mapping XS ea41744a
END DESCRIPTION:
XS GIS Cut Line= 3
      2295794.43      7177310.44      2295481.22      7177104.68
      2295224.88      7177160.94
#Sta/Elev= 30
  4736.1  870.21  4747.7   870.1  4762.4  867.28  4768.4  868.12  4777.5  863.93
  4783.5  864.06  4798.5  855.75  4855.8  847.06    4907   827.3  4922.1  825.57
  4943.2  825.44  4949.2  823.79  4979.3  822.31    4981  821.12  4982.2  820.62
  4989.7  821.12  5000.4  822.54  5015.5  829.24  5021.5   835.5  5036.6  836.23
  5123.4   835.4  5215.5  836.43  5246.2  832.89  5256.9  835.96  5287.2  830.12
  5301.5  832.26  5307.7  835.21  5338.4  838.32  5358.8  844.08  5373.3  844.12
#Mann= 5 ,-1 , 0
  4736.1     .05       0  4747.7     .12       0    4981     .07       0
  4989.7     .12       0  5301.5     .05       0
Bank Sta=4981,4989.7
XS Rating Curve= 0 ,0
Exp/Cntr=0.3,0.1

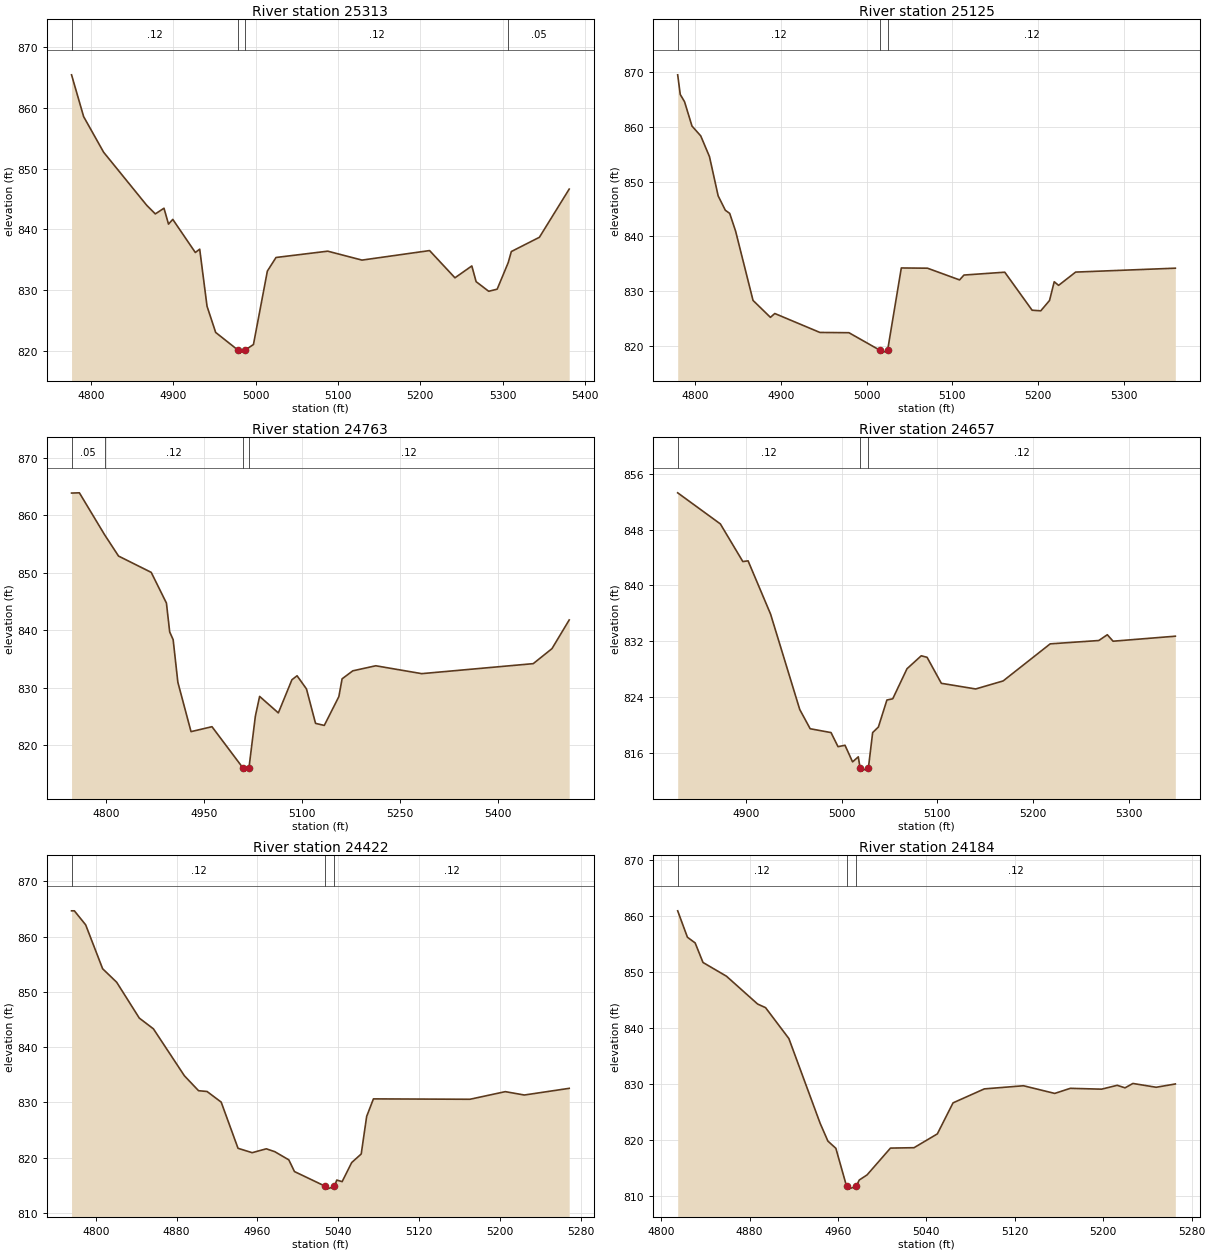
Type RM Length L Ch R = 1 ,25313   ,188,188,188
BEGIN DESCRIPTION:
Mapping XS 7ed2837f
END DESCRIPTION:
XS GIS Cut Line= 3
       2295796.3      7176990.14      2295465.37      7177092.39
      2295213.72      7177150.35
#Sta/Elev= 30
  4776.4  865.46  4791.1  858.57  4815.4   852.7  4867.8  843.95  4878.2  842.54
  4888.7  843.48  4894.2  840.86  4899.4  841.64  4926.8  836.18  4932.1  836.73
    4941  827.33  4951.5  823.01  4978.6   820.1  4979.8   819.6  4987.3   820.1
  4997.4  821.02  5014.3  833.12  5024.8  835.36  5087.6   836.4  5129.3  834.93
  5211.4   836.5  5242.2  832.01  5262.7  833.97  5267.9  831.38  5283.2  829.79
  5293.5  830.14  5306.9  834.51  5310.7  836.34  5344.8  838.69    5381  846.63
#Mann= 4 ,-1 , 0
  4776.4     .12       0  4978.6     .07       0  4987.3     .12       0
  5306.9     .05       0
Bank Sta=4978.6,4987.3
XS Rating Curve= 0 ,0
Exp/Cntr=0.3,0.1

Type RM Length L Ch R = 1 ,25125   ,362,362,362
BEGIN DESCRIPTION:
Mapping XS 7db193df
END DESCRIPTION:
XS GIS Cut Line= 2
      2295745.43      7176844.18      2295174.72      7176950.91
#Sta/Elev= 30
  4779.6  869.45  4782.6  865.87  4787.6  864.55  4796.3  860.11  4806.5  858.32
  4816.7  854.54  4826.8   847.4  4835.2  844.77  4840.3  844.19  4847.2  840.95
  4867.5  828.34  4887.8  825.25  4892.9  825.95  4945.5   822.5  4979.4  822.45
  5015.8  819.23    5017  818.73  5024.5  819.23  5040.5  834.25    5071  834.21
  5108.5  832.07  5113.6  832.96  5161.2  833.48  5193.1  826.55  5203.2  826.44
  5213.4  828.32  5218.9  831.74    5224  831.08  5243.9   833.5  5360.2  834.21
#Mann= 3 ,-1 , 0
  4779.6     .12       0  5015.8     .07       0  5024.5     .12       0
Bank Sta=5015.8,5024.5
XS Rating Curve= 0 ,0
Exp/Cntr=0.3,0.1

Type RM Length L Ch R = 1 ,24763   ,106,106,106
BEGIN DESCRIPTION:
Mapping XS d354b96b
END DESCRIPTION:
XS GIS Cut Line= 5
      2295650.96      7176559.23      2295505.74      7176552.56
      2295402.24       7176584.4      2295276.22      7176687.01
      2295057.65      7176955.78
#Sta/Elev= 30
  4746.8  863.87  4758.8  863.91  4797.5  856.61  4818.8  852.91  4868.9  850.07
  4892.2  844.73  4897.2  839.71  4902.5  838.36  4909.7  830.96  4929.9  822.36
    4962  823.22  5009.8  815.99  5011.1  815.49  5018.6  815.99  5028.5  825.07
    5035  828.49  5063.7  825.62  5084.5  831.39  5092.4  832.08  5106.8  829.79
  5120.7   823.8  5134.1  823.44  5156.4  828.45  5161.4  831.55  5177.8  832.94
    5213  833.82  5283.4  832.45  5454.3  834.19    5483   836.8  5509.4  841.79
#Mann= 4 ,-1 , 0
  4746.8     .05       0  4797.5     .12       0  5009.8     .07       0
  5018.6     .12       0
Bank Sta=5009.8,5018.6
XS Rating Curve= 0 ,0
Exp/Cntr=0.3,0.1

Type RM Length L Ch R = 1 ,24657   ,235,235,235
BEGIN DESCRIPTION:
Mapping XS 0ad9274c
END DESCRIPTION:
XS GIS Cut Line= 3
      2295536.14      7176417.82      2295375.62      7176487.16
      2295090.26      7176681.66
#Sta/Elev= 30
  4828.6  853.27  4873.2  848.81  4896.7  843.41  4902.2  843.51  4925.7  835.87
  4956.2  822.18  4967.1  819.42  4988.9  818.87  4996.2  816.85  5003.5  817.05
  5011.4  814.67  5017.4  815.39  5019.2  813.84  5020.5  813.34    5028  813.84
  5032.4  818.87  5038.4  819.67  5047.3  823.54  5053.4  823.72  5068.3  828.03
  5083.2  829.89  5089.3  829.67  5104.2  825.94  5140.1  825.13  5168.8  826.28
    5218   831.6  5268.8  832.08  5277.7  832.91  5283.7  831.98  5348.8   832.7
#Mann= 3 ,-1 , 0
  4828.6     .12       0  5019.2     .07       0    5028     .12       0
Bank Sta=5019.2,5028
XS Rating Curve= 0 ,0
Exp/Cntr=0.3,0.1

Type RM Length L Ch R = 1 ,24422   ,238,238,238
BEGIN DESCRIPTION:
North Pecan Creek 45.0
END DESCRIPTION:
XS GIS Cut Line= 3
      2295479.01      7176209.99        2295279.        7176310.
      2295178.99      7176560.02
#Sta/Elev= 30
  4775.9  864.67  4778.7  864.67  4789.9  862.13  4806.7  854.18  4820.6  851.74
    4843  845.25    4857   843.3  4887.7   834.8  4901.7   832.1  4910.1  831.96
  4924.1  830.04  4940.8  821.67  4954.8  820.88  4968.8  821.58  4977.2  821.06
  4991.1  819.58  4996.7  817.46  5027.4  814.78  5028.7  814.28  5036.2  814.78
  5038.6  815.92  5043.9  815.64  5053.4   819.1  5062.8  820.64  5068.2  827.45
  5074.9  830.62  5170.5  830.55  5205.5  831.93  5224.4  831.32  5268.8  832.53
#Mann= 3 ,-1 , 0
  4775.9     .12       0  5027.4     .07       0  5036.2     .12       0
Bank Sta=5027.4,5036.2
XS Rating Curve= 0 ,0
Exp/Cntr=0.3,0.1

Type RM Length L Ch R = 1 ,24184   ,235,235,235
BEGIN DESCRIPTION:
Mapping XS 178c8517
END DESCRIPTION:
XS GIS Cut Line= 2
      2295345.83      7175964.52      2295025.02      7176280.38
#Sta/Elev= 30
    4815  860.95  4823.8  856.23  4830.8  855.21  4837.9  851.71  4859.1  849.26
  4887.3  844.28  4894.5  843.63  4915.6   838.1  4943.9  822.93  4950.9  819.76
  4958.1  818.47  4967.8  811.67  4969.1  811.17  4976.6  811.67  4979.2  812.79
  4986.3  813.71  5007.5  818.51  5028.8  818.58  5049.9  821.05  5064.1   826.6
  5092.4   829.1  5127.8  829.66  5156.1  828.29  5170.2   829.2  5198.5  829.05
  5212.6  829.74  5219.7  829.29  5226.8  830.07  5247.9  829.39  5265.2  829.98
#Mann= 3 ,-1 , 0
    4815     .12       0  4967.8     .07       0  4976.6     .12       0
Bank Sta=4967.8,4976.6
XS Rating Curve= 0 ,0
Exp/Cntr=0.3,0.1

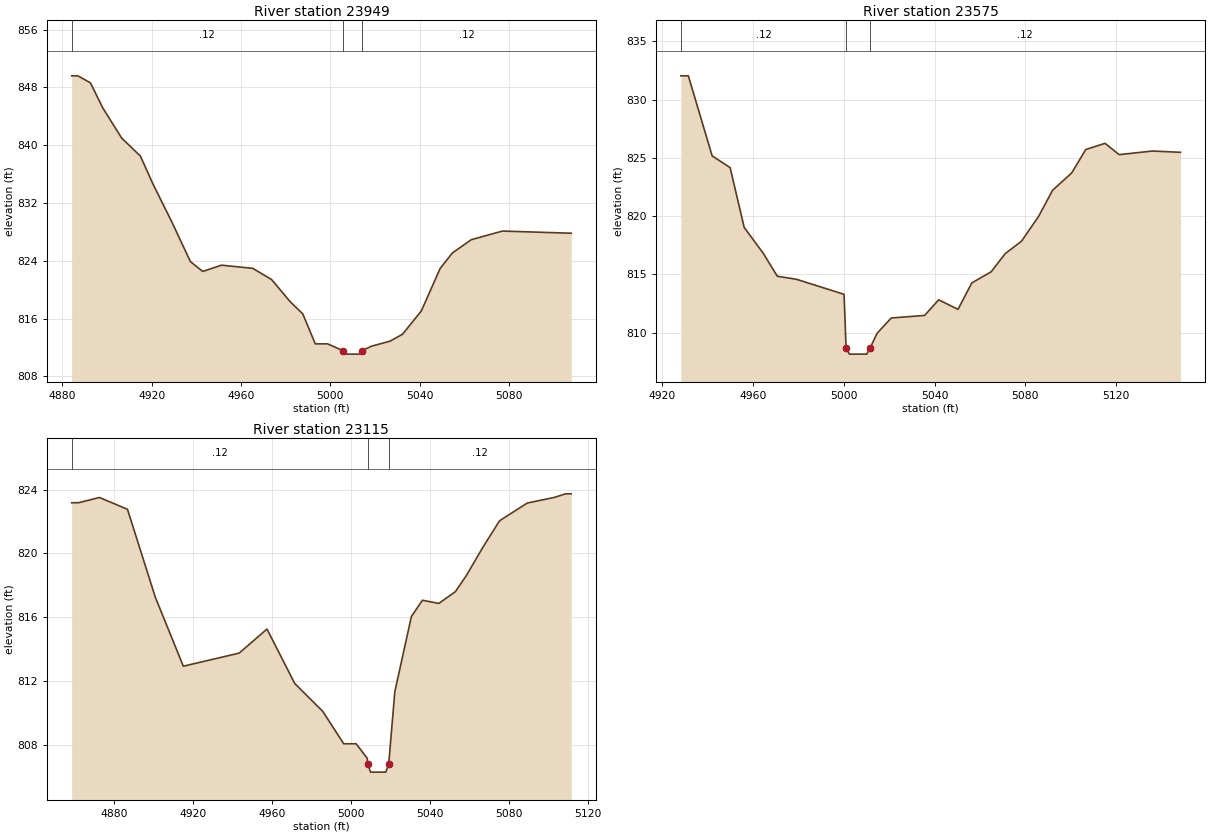
Type RM Length L Ch R = 1 ,23949   ,374,374,374
BEGIN DESCRIPTION:
North Pecan Creek 44.0
END DESCRIPTION:
XS GIS Cut Line= 3
      2295079.02      7175859.96        2295029.        7175960.
      2294978.98      7176060.04
#Sta/Elev= 30
  4884.2  849.59    4887  849.59  4892.6  848.62  4898.2  845.12  4906.6  840.98
    4915  838.48  4920.6  834.63    4929  829.41  4937.4  823.88  4942.9  822.52
  4951.3  823.39  4965.3  822.95  4973.7  821.41  4982.1  818.32  4987.7  816.65
  4993.3   812.5  4998.8   812.5  5005.6  811.58  5006.9  811.08  5013.2  811.08
  5014.4  811.58  5018.4  812.17  5026.8  812.88  5032.4  813.84  5040.8  817.07
  5049.2  822.93  5054.7  825.08  5063.1  826.91  5077.1  828.11  5107.9  827.81
#Mann= 3 ,-1 , 0
  4884.2     .12       0  5005.6     .07       0  5014.4     .12       0
Bank Sta=5005.6,5014.4
XS Rating Curve= 0 ,0
Exp/Cntr=0.3,0.1

Type RM Length L Ch R = 1 ,23575   ,460,460,460
BEGIN DESCRIPTION:
Mapping XS 97865eb4
END DESCRIPTION:
XS GIS Cut Line= 2
      2294907.83       7175688.9      2294777.86      7175866.53
#Sta/Elev= 30
  4928.2  832.04  4931.5  832.04    4942  825.17  4949.9  824.17  4956.1  819.04
  4964.5  816.82  4970.7  814.85  4979.1  814.59  5000.1   813.3    5001  808.67
  5002.5  808.17  5010.1  808.17  5011.5  808.67  5014.7  809.97  5020.9  811.27
  5035.6  811.49  5041.8  812.83  5050.3  812.01  5056.4  814.28  5064.9  815.23
  5071.1  816.79  5078.3  817.86  5085.8  819.98    5092  822.23  5100.4  823.71
  5106.6  825.72  5115.1  826.25  5121.3  825.28    5136  825.59  5148.3  825.48
#Mann= 3 ,-1 , 0
  4928.2     .12       0    5001     .07       0  5011.5     .12       0
Bank Sta=5001,5011.5
XS Rating Curve= 0 ,0
Exp/Cntr=0.3,0.1

Type RM Length L Ch R = 1 ,23115   ,461,461,461
BEGIN DESCRIPTION:
North Pecan Creek 42.0
END DESCRIPTION:
XS GIS Cut Line= 3
        2294679.        7175510.        2294579.        7175610.
      2294479.02      7175659.99
#Sta/Elev= 29
  4858.3  823.18  4861.8  823.18  4872.4  823.51  4886.6  822.77  4900.7  817.25
  4914.9  812.92  4943.2  813.74  4957.3  815.25  4971.4  811.83  4985.6  810.08
  4996.2  808.05  5002.5  808.05  5008.1  807.14  5008.4  806.77  5009.8  806.27
  5017.5  806.27    5019  806.77  5022.1  811.32  5030.5  816.04  5036.1  817.06
  5044.4  816.86  5052.8   817.6  5058.4  818.62  5066.8   820.4  5075.2  822.05
  5089.2  823.16  5103.1  823.52  5108.7  823.74  5111.5  823.74
#Mann= 3 ,-1 , 0
  4858.3     .12       0  5008.4     .07       0    5019     .12       0
Bank Sta=5008.4,5019
XS Rating Curve= 0 ,0
Exp/Cntr=0.3,0.1