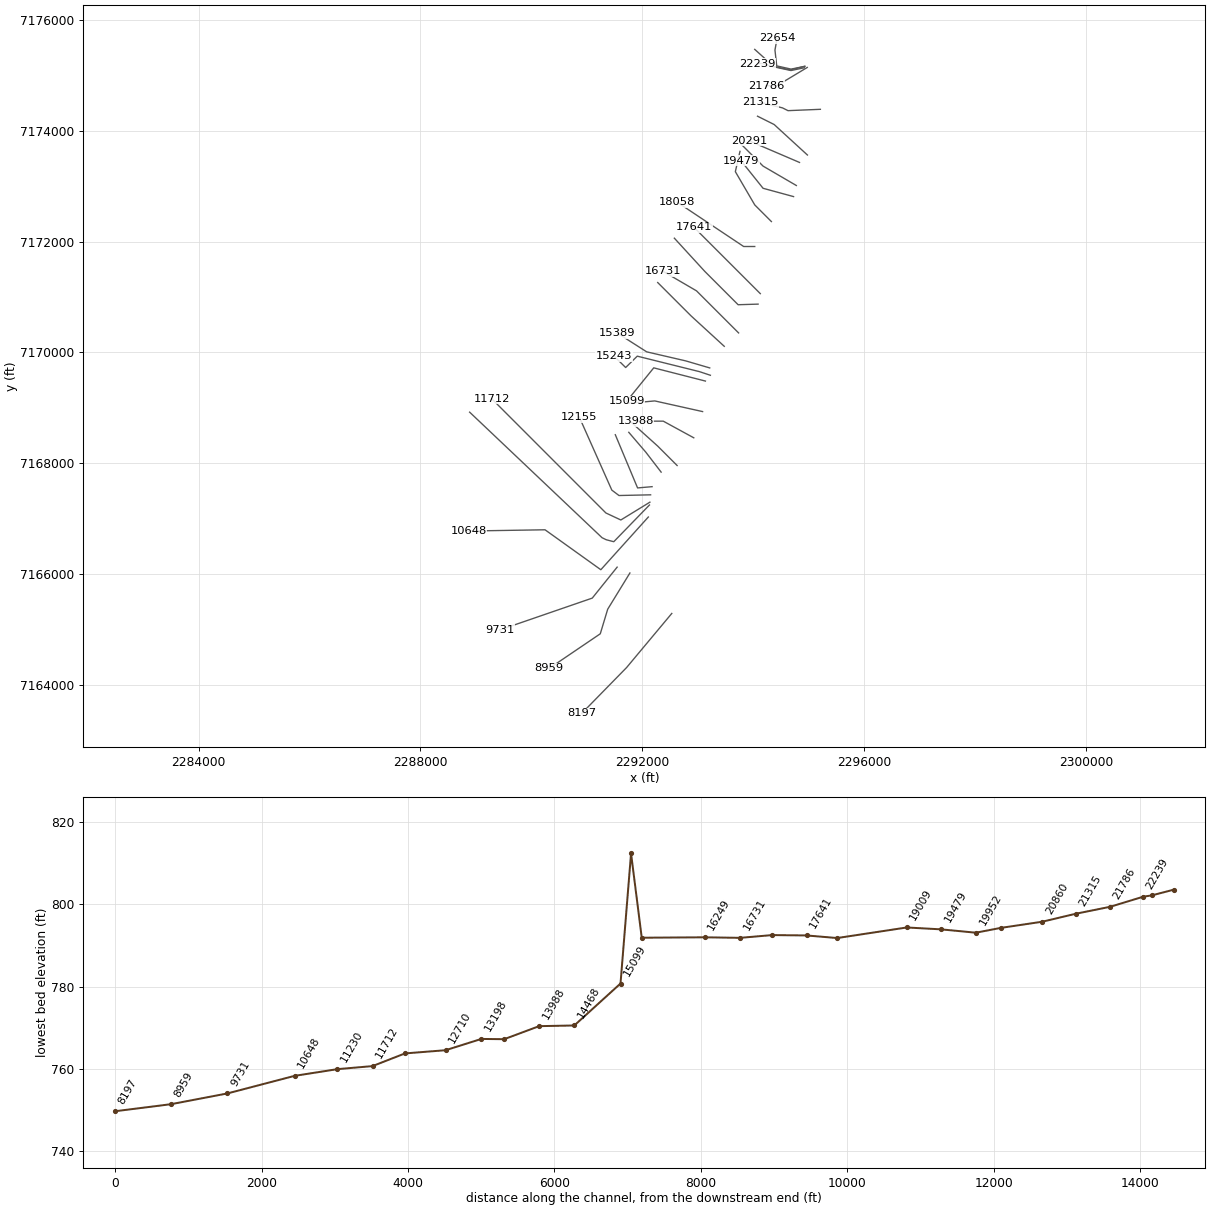
HEC-RAS study North Pecan Creek.prj: North Pecan Creek Base Level Engineering

--- North Pecan Creek.g01 (geometry) --- (continued)

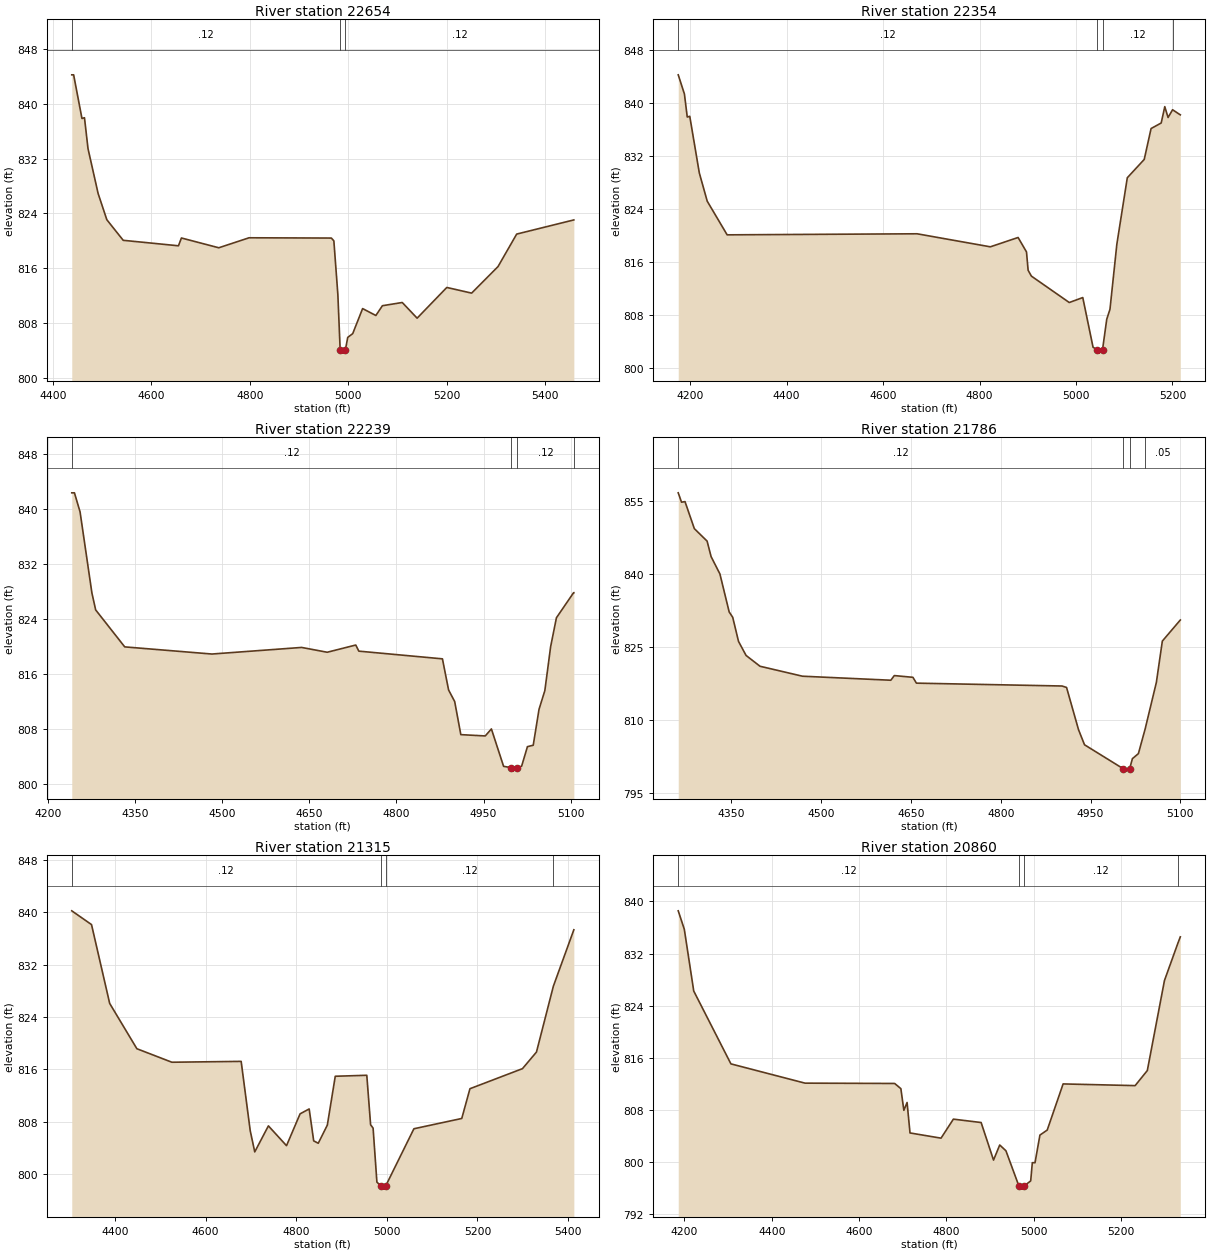
Type RM Length L Ch R = 1 ,22654   ,300,300,300
BEGIN DESCRIPTION:
Mapping XS e80d575b
END DESCRIPTION:
XS GIS Cut Line= 5
      2294931.37      7175159.72      2294684.36      7175109.31
      2294425.29      7175167.37      2294393.51      7175452.13
      2294431.65       7175664.3
#Sta/Elev= 30
  4438.6  844.27  4442.4  844.27  4459.3  837.89  4464.4     838  4471.6  833.48
  4492.1  826.93  4509.8  823.09  4543.1  820.08  4655.3  819.28  4661.3  820.42
  4737.2  818.99  4798.7  820.45  4965.8  820.41  4970.9     820    4979  812.19
  4983.7  804.09  4985.2  803.59  4994.4  804.09  4999.1  805.89  5009.2  806.44
  5029.3   810.1  5056.2  809.09  5069.5  810.52  5109.8  810.99    5140   808.7
  5200.3  813.19  5250.7  812.36  5304.3  816.24  5342.2  820.99  5458.3  823.06
#Mann= 3 ,-1 , 0
  4438.6     .12       0  4983.7     .07       0  4994.4     .12       0
Bank Sta=4983.7,4994.4
XS Rating Curve= 0 ,0
Exp/Cntr=0.3,0.1

Type RM Length L Ch R = 1 ,22354   ,115,115,115
BEGIN DESCRIPTION:
Mapping XS b4fcd1af
END DESCRIPTION:
XS GIS Cut Line= 5
      2294931.39      7175159.72      2294671.69      7175095.14
      2294334.79       7175166.3      2294267.58      7175250.34
       2294028.6      7175465.17
#Sta/Elev= 30
  4175.4  844.27  4188.2  841.38  4194.1  837.89  4199.3     838  4219.1  829.44
  4235.5  825.17  4276.8  820.08  4670.6  820.24  4822.4  818.27    4880  819.68
  4897.4   817.5  4900.8  814.72  4907.6  813.84  4986.1  809.85  5014.1   810.6
  5035.4  803.09  5044.2   802.7  5045.7   802.2    5055   802.7  5063.8  807.33
  5070.5  808.83  5084.7  818.65  5106.4  828.71  5141.5  831.48  5155.7  836.15
  5176.7  836.99  5184.1  839.46  5190.9  837.82  5200.3  838.99  5216.3  838.22
#Mann= 4 ,-1 , 0
  4175.4     .12       0  5044.2     .07       0    5055     .12       0
  5200.3     .05       0
Bank Sta=5044.2,5055
XS Rating Curve= 0 ,0
Exp/Cntr=0.3,0.1

Type RM Length L Ch R = 1 ,22239   ,453,453,453
BEGIN DESCRIPTION:
North Pecan Creek 40.0
END DESCRIPTION:
XS GIS Cut Line= 5
      2294922.96      7175133.67      2294681.76      7175083.51
        2294329.        7175160.        2294179.        7175210.
      2294079.03        7175210.
#Sta/Elev= 30
  4240.3  842.39  4244.9  842.39  4254.6  839.62    4275  827.82  4281.5  825.35
  4331.6  819.97  4481.9  818.93  4636.5  819.89  4680.6  819.19  4729.8  820.24
  4735.1  819.35  4879.2  818.23  4889.8   813.7  4900.3  812.02  4910.9   807.2
    4953  807.01  4963.6  808.03  4984.6  802.59  4997.7  802.39  4999.2  801.89
  5008.5  802.39  5015.7  802.61  5025.7  805.45  5035.7  805.66  5045.7  810.89
  5055.7   813.6  5065.7     820  5075.7  824.21  5105.3  827.86  5105.7  827.86
#Mann= 4 ,-1 , 0
  4240.3     .12       0  4997.7     .07       0  5008.5     .12       0
  5105.3     .05       0
Bank Sta=4997.7,5008.5
XS Rating Curve= 0 ,0
Exp/Cntr=0.3,0.1

Type RM Length L Ch R = 1 ,21786   ,471,471,471
BEGIN DESCRIPTION:
North Pecan Creek 39.0
END DESCRIPTION:
XS GIS Cut Line= 4
      2294976.04      7175139.45        2294429.        7174810.
        2294329.        7174810.      2294228.99        7174810.
#Sta/Elev= 30
  4261.4  856.78  4266.9  854.85  4272.7  854.97  4288.3   849.4  4309.6  846.83
  4316.3  843.63    4331  840.07  4346.5  832.23  4352.4  831.13  4362.1  826.16
  4374.7  823.27    4398  821.04  4468.9  818.99  4616.5  818.16  4622.3  819.12
  4653.4  818.76  4659.2  817.56  4902.5  816.97    4910  816.67    4930  807.97
    4940  804.86  5004.6  799.93  5006.1  799.43  5015.4  799.93    5020     802
    5030  803.04  5041.3  808.13    5060  817.71    5070  826.23    5100  830.57
#Mann= 4 ,-1 , 0
  4261.4     .12       0  5004.6     .07       0  5015.4     .12       0
  5041.3     .05       0
Bank Sta=5004.6,5015.4
XS Rating Curve= 0 ,0
Exp/Cntr=0.3,0.1

Type RM Length L Ch R = 1 ,21315   ,455,455,455
BEGIN DESCRIPTION:
North Pecan Creek 38.0
END DESCRIPTION:
XS GIS Cut Line= 4
      2295212.58      7174384.28        2294629.        7174360.
        2294529.        7174410.        2294129.        7174510.
#Sta/Elev= 30
  4304.5   840.2  4348.1   838.1  4388.2  826.07  4448.2  819.16  4525.5   817.1
  4678.4  817.23  4698.4  806.65  4708.4  803.42  4738.5  807.39  4778.5  804.37
  4808.5  809.23  4828.5  809.97  4838.5   805.1  4848.6  804.74  4868.6  807.51
  4886.1  814.96  4955.7  815.11  4964.1  807.56  4969.6  807.05    4978  798.81
  4986.6  798.24  4988.1  797.74  4997.5  798.24  5059.7  806.95  5165.3  808.52
  5183.4  813.06  5299.3  816.12  5330.2  818.65  5367.5   828.7  5412.7  837.31
#Mann= 4 ,-1 , 0
  4304.5     .12       0  4986.6     .07       0  4997.5     .12       0
  5367.5     .05       0
Bank Sta=4986.6,4997.5
XS Rating Curve= 0 ,0
Exp/Cntr=0.3,0.1

Type RM Length L Ch R = 1 ,20860   ,569,569,569
BEGIN DESCRIPTION:
North Pecan Creek 37.0
END DESCRIPTION:
XS GIS Cut Line= 3
      2294979.03      7173559.97        2294379.        7174110.
      2294078.99        7174260.
#Sta/Elev= 30
    4186  838.56  4199.9  835.73  4221.5  826.24  4306.6  815.05  4476.2  812.09
  4681.5  812.04  4695.7  811.24  4702.5  807.92  4709.9  809.12  4716.6  804.44
  4787.6  803.64  4815.9  806.56  4879.4  806.04  4907.8  800.27    4922  802.59
  4936.2   801.7  4965.8  796.31  4967.5  795.81    4978  796.31  4992.9  797.07
  4996.6  799.87  5002.8  799.87    5014  804.11  5030.7  804.88  5067.1  811.97
    5232  811.71  5259.9  814.03  5299.1  827.85  5330.2  833.65  5335.4  834.56
#Mann= 4 ,-1 , 0
    4186     .12       0  4965.8     .07       0    4978     .12       0
  5330.2     .05       0
Bank Sta=4965.8,4978
XS Rating Curve= 0 ,0
Exp/Cntr=0.3,0.1

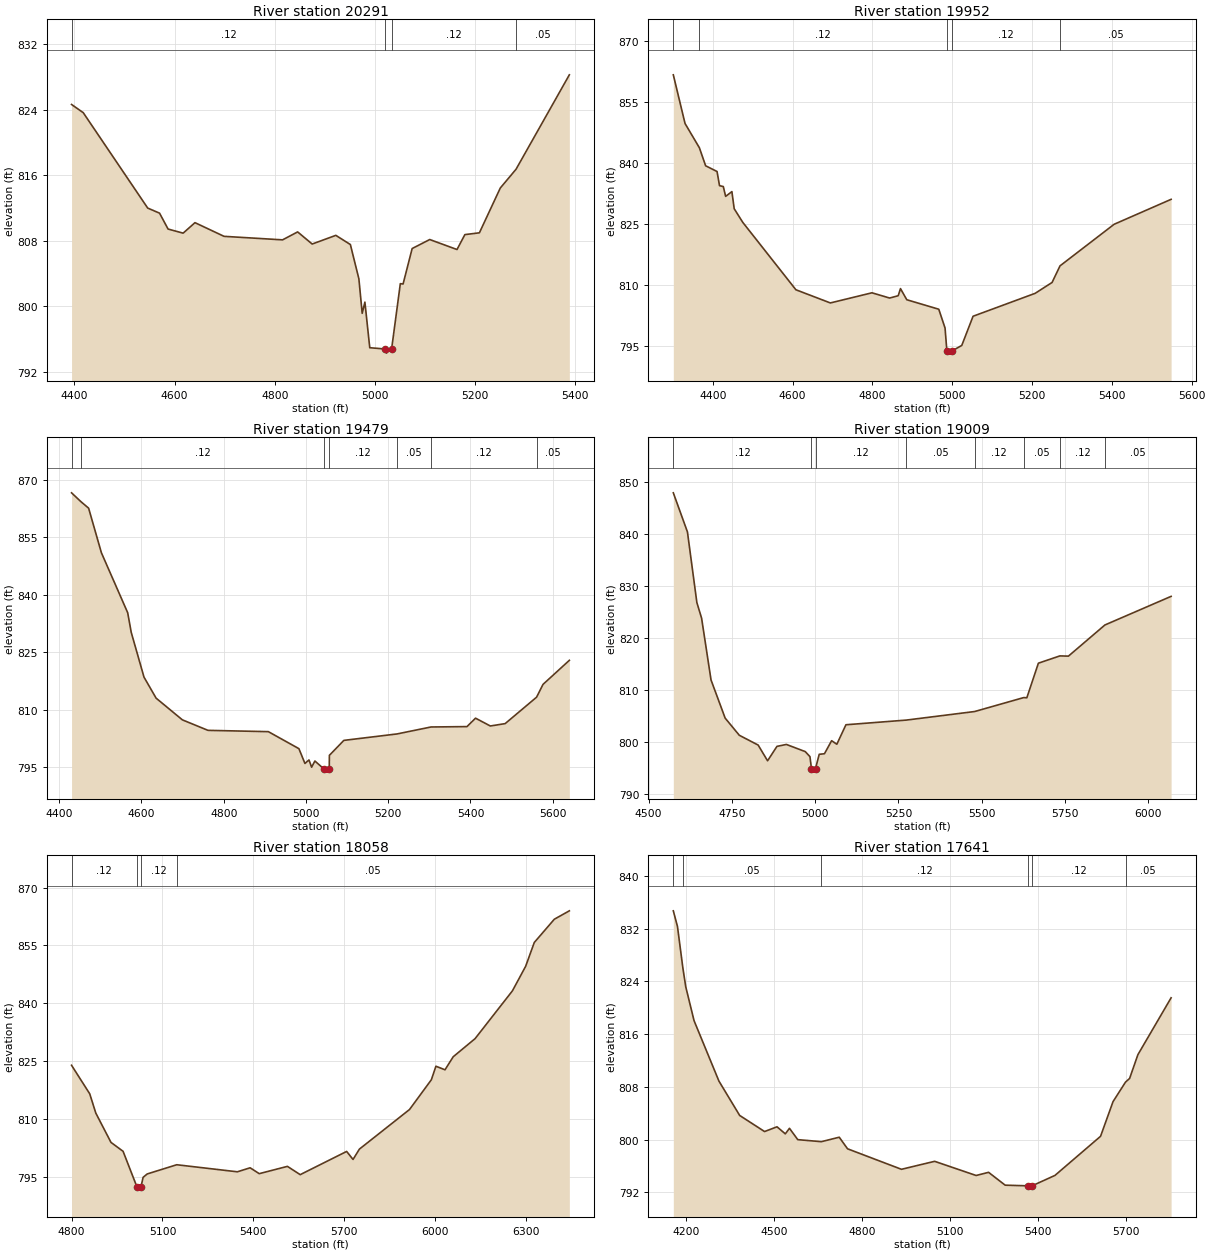
Type RM Length L Ch R = 1 ,20291   ,339,339,339
BEGIN DESCRIPTION:
Mapping XS d521acc4
END DESCRIPTION:
XS GIS Cut Line= 2
      2294836.02       7173426.1      2293922.92      7173817.38
#Sta/Elev= 30
  4394.5  824.66  4417.8  823.66  4546.5  812.01  4570.1  811.39  4587.1  809.45
  4617.2  808.95  4640.8  810.23  4698.8  808.56  4815.6  808.13  4845.7   809.1
  4874.7  807.62  4921.9  808.68  4950.9  807.56  4967.9  803.37  4974.5  799.16
  4979.9  800.53  4989.6  794.96    5021   794.8  5022.7   794.3  5033.2   794.8
  5050.6  802.78  5056.1  802.74  5074.2  807.07  5109.3  808.17  5163.7  806.95
  5179.4  808.77  5208.4  808.99  5250.1  814.46  5281.5  816.75  5387.9  828.28
#Mann= 4 ,-1 , 0
  4394.5     .12       0    5021     .07       0  5033.2     .12       0
  5281.5     .05       0
Bank Sta=5021,5033.2
XS Rating Curve= 0 ,0
Exp/Cntr=0.3,0.1

Type RM Length L Ch R = 1 ,19952   ,473,473,473
BEGIN DESCRIPTION:
North Pecan Creek 35.0
END DESCRIPTION:
XS GIS Cut Line= 4
        2294779.        7173010.        2294179.        7173360.
        2293979.        7173560.      2293788.06      7173750.95
#Sta/Elev= 30
    4301  861.74  4330.4  849.74  4366.3  843.77    4382  839.32  4410.6  837.91
  4416.8  834.42  4426.3   834.2  4432.1  831.78  4447.8  832.95  4453.6  828.73
  4475.1  825.37  4608.2  808.76  4694.6  805.51  4798.8  808.01  4843.1  806.72
  4864.6  807.29  4870.3  809.04  4886.1   806.3  4966.3  803.96    4982  799.32
  4986.6  793.64  4988.3  793.14  4998.8  793.64  5023.9  795.04  5052.2  802.23
  5207.8  807.88  5250.2  810.56  5270.1  814.65  5405.7   824.9  5548.5  831.05
#Mann= 5 ,-1 , 0
    4301     .05       0  4366.3     .12       0  4986.6     .07       0
  4998.8     .12       0  5270.1     .05       0
Bank Sta=4986.6,4998.8
XS Rating Curve= 0 ,0
Exp/Cntr=0.3,0.1

Type RM Length L Ch R = 1 ,19479   ,470,470,470
BEGIN DESCRIPTION:
North Pecan Creek 34.0
END DESCRIPTION:
XS GIS Cut Line= 3
        2294729.        7172810.        2294179.        7172960.
        2293779.        7173460.
#Sta/Elev= 30
    4430  866.64  4452.5  864.36  4471.5  862.63  4502.6  850.98  4566.5  835.32
  4575.1   830.2  4606.2  818.49  4635.6  813.01  4699.5  807.34  4761.7   804.6
  4908.5  804.26  4982.8  799.82  4997.5  795.95  5007.3  796.87  5013.7  794.98
  5021.7  796.59  5044.4  794.45  5046.1  793.95  5056.6  794.45  5056.9  798.07
  5092.1  801.98  5221.3  803.66  5304.1  805.48  5391.5  805.58  5412.3  807.78
  5448.3  805.74  5484.3  806.36  5560.7  813.26  5576.4  816.61  5640.4  822.89
#Mann= 7 ,-1 , 0
    4430     .05       0  4452.5     .12       0  5044.4     .07       0
  5056.6     .12       0  5221.3     .05       0  5304.1     .12       0
  5560.7     .05       0
Bank Sta=5044.4,5056.6
XS Rating Curve= 0 ,0
Exp/Cntr=0.3,0.1

Type RM Length L Ch R = 1 ,19009   ,951,951,951
BEGIN DESCRIPTION:
North Pecan Creek 33.0
END DESCRIPTION:
XS GIS Cut Line= 4
      2294329.01      7172359.99        2294029.        7172660.
        2293679.        7173260.      2293762.52      7173625.69
#Sta/Elev= 30
  4574.4  848.01  4616.8  840.48  4645.1  826.87  4659.3  823.87  4687.6  811.97
    4730  804.62  4772.4  801.32    4829  799.43  4857.3   796.4  4885.5  799.18
  4913.8  799.55  4970.4  798.17  4984.5   797.2    4989  794.91  4990.7  794.41
  5001.2  794.91  5012.3  797.65    5028  797.76  5049.5  800.27  5065.2  799.59
  5092.5  803.34  5273.6  804.24  5478.9  805.89  5625.9  808.57  5635.4  808.54
  5670.1   815.2  5734.5   816.6  5760.3  816.56  5869.8  822.56  6068.4  828.07
#Mann= 8 ,-1 , 0
  4574.4     .12       0    4989     .07       0  5001.2     .12       0
  5273.6     .05       0  5478.9     .12       0  5625.9     .05       0
  5734.5     .12       0  5869.8     .05       0
Bank Sta=4989,5001.2
XS Rating Curve= 0 ,0
Exp/Cntr=0.3,0.1

Type RM Length L Ch R = 1 ,18058   ,417,417,417
BEGIN DESCRIPTION:
North Pecan Creek 31.0
END DESCRIPTION:
XS GIS Cut Line= 3
      2294028.95        7171910.        2293829.        7171910.
      2292628.98      7172710.01
#Sta/Elev= 30
  4800.1  823.94  4860.1  816.54  4880.1  811.55  4930.1  803.96  4970.1  801.64
  5016.2  792.34    5018  791.84  5028.9  792.34  5036.1  794.89  5049.6  795.77
  5147.1  798.16  5347.1  796.33  5389.2  797.37  5419.2  795.85  5512.3  797.74
  5554.4  795.59  5707.6  801.61  5728.7  799.53  5749.7  802.21    5915  812.47
  5987.1  820.19  6002.1  823.69  6032.1  822.77  6059.2  826.15  6131.3  830.84
  6254.5  843.23  6298.1  849.59  6326.6  855.76  6392.7  861.79  6442.3  863.97
#Mann= 4 ,-1 , 0
  4800.1     .12       0  5016.2     .07       0  5028.9     .12       0
  5147.1     .05       0
Bank Sta=5016.2,5028.9
XS Rating Curve= 0 ,0
Exp/Cntr=0.3,0.1

Type RM Length L Ch R = 1 ,17641   ,468,468,468
BEGIN DESCRIPTION:
North Pecan Creek 30.0
END DESCRIPTION:
XS GIS Cut Line= 3
        2294129.        7171060.        2293529.        7171660.
      2292928.96      7172260.04
#Sta/Elev= 30
  4156.3  834.71  4170.4  832.35  4188.7   826.1  4198.7  823.18    4227  818.04
  4311.9  808.86  4382.6  803.65  4467.4  801.21  4509.8  801.93  4538.1  800.86
  4552.3   801.7  4580.6  799.98    4661  799.67    4722  800.35  4750.3  798.59
  4934.1  795.48  5047.2  796.69  5188.7  794.54  5231.1  795.02  5287.7  793.07
  5365.9  792.97  5367.8  792.47  5379.2  792.97  5457.4  794.55  5612.9  800.49
  5655.4  805.75  5697.9  808.71  5711.9  809.27  5740.2  812.88  5853.4  821.51
#Mann= 6 ,-1 , 0
  4156.3     .12       0  4188.7     .05       0    4661     .12       0
  5365.9     .07       0  5379.2     .12       0  5697.9     .05       0
Bank Sta=5365.9,5379.2
XS Rating Curve= 0 ,0
Exp/Cntr=0.3,0.1

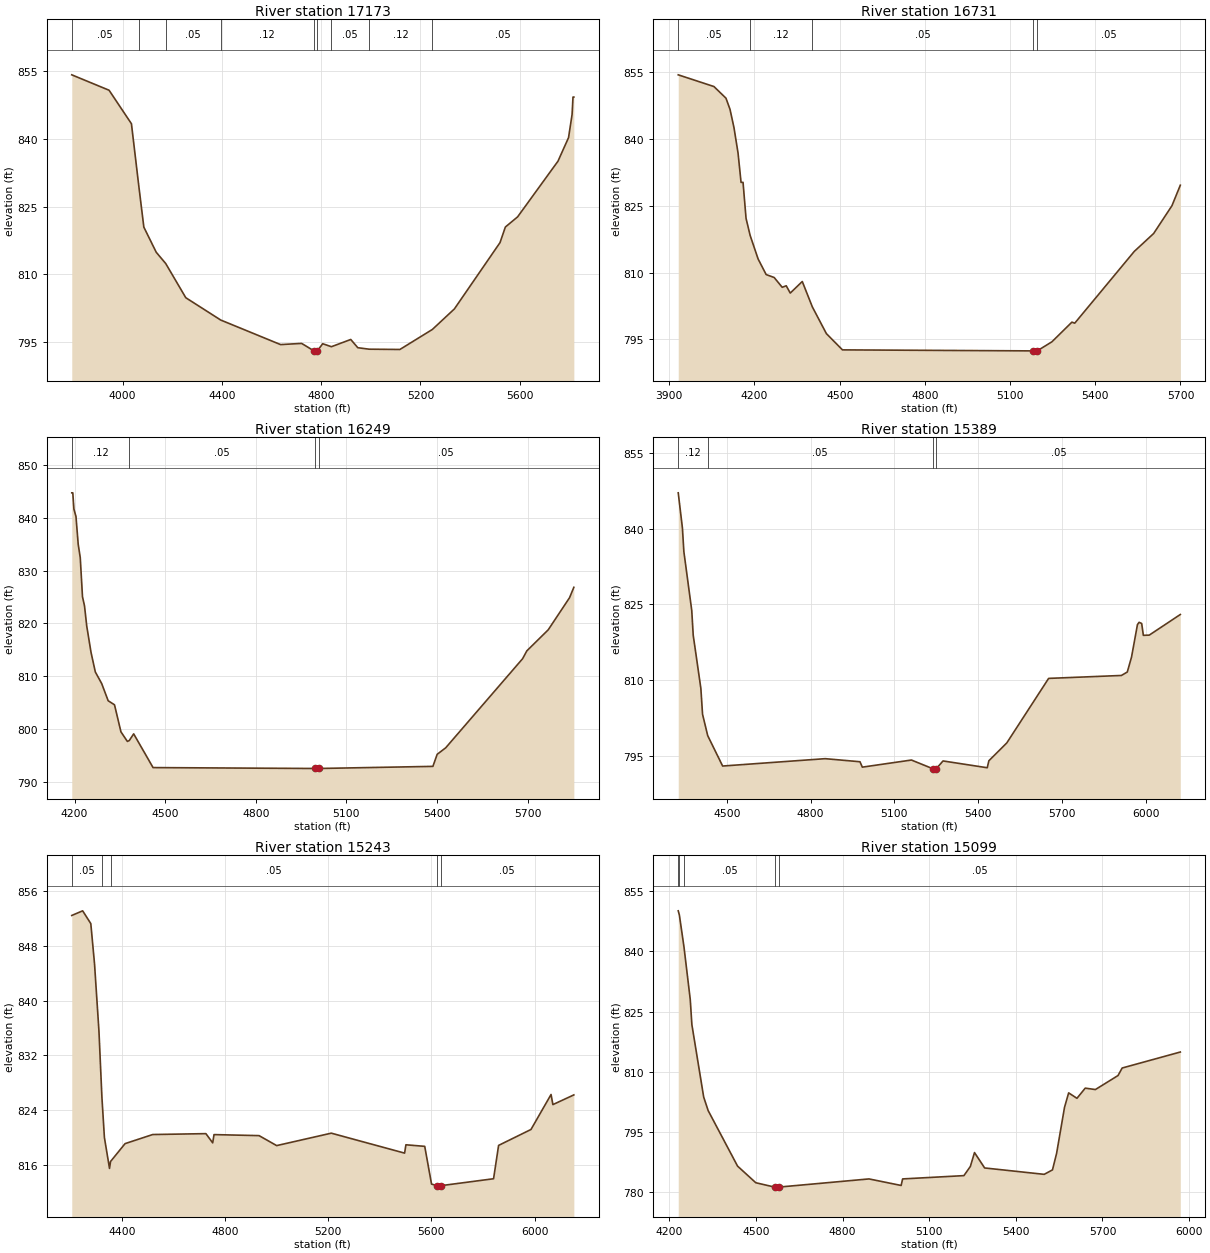
Type RM Length L Ch R = 1 ,17173   ,442,442,442
BEGIN DESCRIPTION:
North Pecan Creek 29.0
END DESCRIPTION:
XS GIS Cut Line= 4
      2294089.27      7170870.77        2293729.        7170860.
        2293129.        7171460.        2292579.        7172060.
#Sta/Elev= 30
  3795.4  854.14  3945.7  850.73  4035.8  843.32  4065.1  829.72  4085.8  820.44
  4135.8  814.87    4174  812.38  4254.8  804.82  4395.6  799.88  4636.7  794.45
  4721.5  794.71  4771.4  793.06  4773.3  792.56  4784.7  793.06  4806.4  794.64
  4841.5  793.98  4919.5  795.58  4947.8  793.76  4993.6  793.43  5117.5  793.37
  5248.1  797.79    5337  802.34  5520.8  817.01  5542.4  820.46  5591.7  822.71
  5754.5  835.04    5797  840.25  5811.2  845.37  5814.9  849.22  5818.3  849.22
#Mann= 9 ,-1 , 0
  3795.4     .05       0  4065.1     .12       0    4174     .05       0
  4395.6     .12       0  4771.4     .07       0  4784.7     .12       0
  4841.5     .05       0  4993.6     .12       0  5248.1     .05       0
Bank Sta=4771.4,4784.7
XS Rating Curve= 0 ,0
Exp/Cntr=0.3,0.1

Type RM Length L Ch R = 1 ,16731   ,482,482,482
BEGIN DESCRIPTION:
North Pecan Creek 28.0
END DESCRIPTION:
XS GIS Cut Line= 4
      2293737.89      7170351.11        2293579.        7170510.
        2292979.        7171110.      2292378.96      7171460.02
#Sta/Elev= 30
  3931.5  854.41  4057.2  851.78  4099.6  849.16  4113.8  846.66  4127.9  842.51
  4142.1  836.83  4152.7  830.25  4159.7  830.25  4170.3  822.16  4184.7  818.33
  4212.8  813.04  4241.1  809.54  4269.3  808.88  4297.6  806.68  4311.8  807.02
  4325.9  805.38  4368.3  807.98  4403.7  802.28  4453.2  796.27  4509.8  792.62
    5182  792.39  5183.9  791.89  5195.4  792.39  5247.4  794.44  5317.7  798.85
  5327.7  798.62  5537.3  814.74  5605.5  818.76    5670  825.01  5699.4  829.61
#Mann= 5 ,-1 , 0
  3931.5     .05       0  4184.7     .12       0  4403.7     .05       0
    5182    .033       0  5195.4     .05       0
Bank Sta=5182,5195.4
XS Rating Curve= 0 ,0
Exp/Cntr=0.3,0.1

Type RM Length L Ch R = 1 ,16249   ,860,860,860
BEGIN DESCRIPTION:
North Pecan Creek 27.0
END DESCRIPTION:
XS GIS Cut Line= 3
        2293479.        7170110.        2292879.        7170660.
      2292278.98      7171260.02
#Sta/Elev= 30
  4190.6  844.75    4194  844.75  4197.7  841.66  4204.5  840.28  4211.9  835.01
  4218.7  832.47  4226.1  825.06  4232.8  823.33  4240.2   819.5  4254.4  814.51
  4268.6  810.81  4289.6  808.62  4311.2  805.35  4332.1  804.59  4353.4  799.47
  4374.7  797.65  4380.8   797.8  4395.6  799.08  4459.8  792.69  4994.5  792.52
  4996.4  792.02  5007.9  792.52  5386.4  792.92  5400.5   795.2  5428.8  796.44
  5683.4  813.32  5697.5  814.81  5768.2  818.79  5838.9  824.88  5853.1  826.85
#Mann= 4 ,-1 , 0
  4190.6     .12       0  4380.8     .05       0  4994.5    .033       0
  5007.9     .05       0
Bank Sta=4994.5,5007.9
XS Rating Curve= 0 ,0
Exp/Cntr=0.3,0.1

Type RM Length L Ch R = 1 ,15389   ,146,146,146
BEGIN DESCRIPTION:
Mapping XS c4d778b2
END DESCRIPTION:
XS GIS Cut Line= 4
       2293216.8      7169720.31       2292782.4       7169847.5
      2292080.18       7170010.1      2291552.75      7170346.47
#Sta/Elev= 30
  4325.6  847.11  4340.6  840.13  4345.8  835.44    4374   823.8  4379.3  818.87
  4406.7  808.32  4412.7   803.2  4431.2  798.96  4484.7  792.93  4852.1  794.39
  4976.8  793.78  4985.3  792.71  5161.2  794.12  5236.8  792.42  5238.8  791.92
  5250.4  792.42  5274.4  793.94  5432.8  792.59  5438.7  793.98  5502.7   797.5
  5652.8  810.31  5913.5  810.89  5934.6  811.57  5949.8  814.53    5971  820.97
  5976.9  821.43  5986.2   821.2  5992.2  818.85  6013.3  818.89  6124.6  822.98
#Mann= 4 ,-1 , 0
  4325.6     .12       0  4431.2     .05       0  5236.8    .033       0
  5250.4     .05       0
Bank Sta=5236.8,5250.4
XS Rating Curve= 0 ,0
Exp/Cntr=0.3,0.1

Type RM Length L Ch R = 1 ,15243   ,144,144,144
BEGIN DESCRIPTION:
Mapping XS df0c4539
END DESCRIPTION:
XS GIS Cut Line= 5
        2293229.      7169587.61      2293031.82      7169653.15
      2291910.19      7169932.26      2291700.59      7169727.52
      2291494.45      7169930.32
#Sta/Elev= 30
  4206.2  852.46  4248.4  853.14    4280  851.27  4294.4  845.39  4311.6  835.51
    4323  825.88  4332.7  819.96  4352.5  815.44  4356.4  816.45  4412.8  819.07
  4519.9   820.4    4726  820.53  4752.4  819.18  4757.5  820.39  4932.1  820.24
  5000.3  818.78    5212   820.6  5496.1  817.68  5501.2   818.9  5574.1  818.67
  5600.5  813.15    5622  812.91  5623.9  812.41  5635.6  812.91  5840.9  813.93
  5860.4  818.81  5985.9  821.14  6063.7  826.26  6070.8  824.78    6152   826.2
#Mann= 5 ,-1 , 0
  4206.2     .05       0    4323     .12       0  4356.4     .05       0
    5622    .033       0  5635.6     .05       0
Bank Sta=5622,5635.6
XS Rating Curve= 0 ,0
Exp/Cntr=0.3,0.1

Type RM Length L Ch R = 1 ,15099   ,631,631,631
BEGIN DESCRIPTION:
Mapping XS fd4e0495
END DESCRIPTION:
XS GIS Cut Line= 3
      2293139.33      7169483.14      2292207.14      7169721.37
      2291718.06      7169117.54
#Sta/Elev= 30
  4230.5  850.07  4234.5  849.01  4250.4  841.08  4272.1  828.01  4277.8  821.72
  4318.7   803.7  4334.1  800.35    4436  786.52  4499.2  782.38  4564.7  781.29
  4566.6  780.79  4578.3  781.29  4891.4  783.33  5002.6   781.7  5007.8  783.33
  5220.1  784.15  5242.4  786.43  5256.8  789.89  5291.9  786.06  5498.2  784.47
  5526.9  785.58  5541.3  789.74  5568.6  801.15  5582.9  804.75  5611.7   803.4
  5640.4  805.93  5675.6  805.58    5754  809.07  5768.3  810.94  5969.7  814.92
#Mann= 5 ,-1 , 0
  4230.5     .05       0  4234.5     .12       0  4250.4     .05       0
  4564.7    .033       0  4578.3     .05       0
Bank Sta=4564.7,4578.3
XS Rating Curve= 0 ,0
Exp/Cntr=0.3,0.1

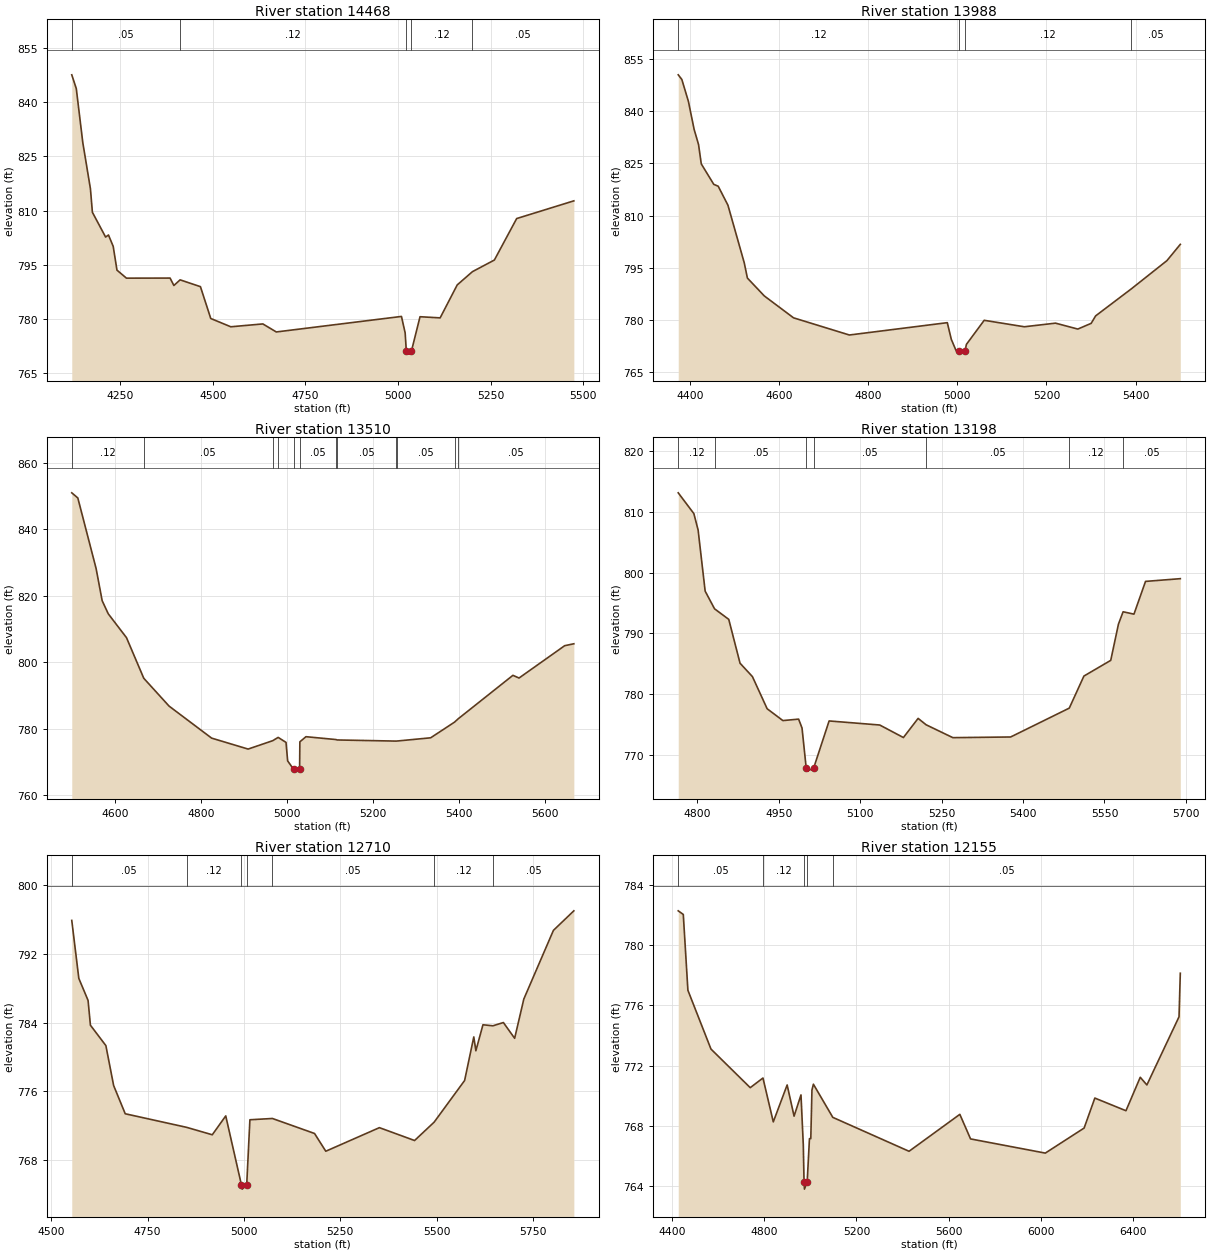
Type RM Length L Ch R = 1 ,14468   ,480,480,480
BEGIN DESCRIPTION:
Mapping XS 7c01917f
END DESCRIPTION:
XS GIS Cut Line= 3
      2293088.18      7168932.87      2292225.74      7169125.01
      2291755.27      7169082.18
#Sta/Elev= 30
  4119.1   847.5  4131.3   843.7    4149  828.69  4169.5  816.02  4174.8  809.52
  4210.5  802.66  4218.2  803.24    4231   800.1  4241.2  793.52  4266.8  791.31
  4384.6  791.33  4394.9  789.28  4411.7  790.84  4466.6  788.96  4494.5  780.16
  4548.6  777.87  4635.2  778.66  4671.5  776.44  5009.5  780.73  5019.5  776.19
  5022.7  771.09  5024.6  770.59  5036.3  771.09  5059.7  780.65    5114  780.33
  5160.1  789.44  5201.2   793.1  5260.5  796.32  5320.7  807.78  5475.1  812.67
#Mann= 5 ,-1 , 0
  4119.1     .05       0  4411.7     .12       0  5022.7     .07       0
  5036.3     .12       0  5201.2     .05       0
Bank Sta=5022.7,5036.3
XS Rating Curve= 0 ,0
Exp/Cntr=0.3,0.1

Type RM Length L Ch R = 1 ,13988   ,478,478,478
BEGIN DESCRIPTION:
North Pecan Creek 23.0
END DESCRIPTION:
XS GIS Cut Line= 3
        2292929.        7168460.        2292379.        7168760.
        2291879.        7168760.
#Sta/Elev= 30
    4374  850.46  4382.1  849.12  4396.8  842.84  4409.6   834.8  4419.6  830.39
  4425.7  824.85  4453.7  818.97  4463.7  818.42  4485.5  812.98  4522.1  796.41
  4529.2  792.01  4567.2  786.87  4632.7  780.58    4758  775.64  4977.7  779.19
  4986.7  774.39  4997.7  771.07  5003.7  770.93  5005.6  770.43  5017.4  770.93
  5020.5  772.93  5060.5  779.87  5150.5  778.01  5220.5  779.05  5270.5  777.35
  5300.5  778.99  5310.5  781.14  5390.9  788.94  5470.5  797.03  5500.5  801.71
#Mann= 4 ,-1 , 0
    4374     .12       0  5003.7     .07       0  5017.4     .12       0
  5390.9     .05       0
Bank Sta=5003.7,5017.4
XS Rating Curve= 0 ,0
Exp/Cntr=0.3,0.1

Type RM Length L Ch R = 1 ,13510   ,312,312,312
BEGIN DESCRIPTION:
North Pecan Creek 22.0
END DESCRIPTION:
XS GIS Cut Line= 3
        2292629.        7167960.        2292279.        7168310.
      2291778.97      7168760.03
#Sta/Elev= 30
  4500.1  850.93  4514.2  849.38  4556.7  828.17  4570.8   818.5    4585  814.55
  4627.4  807.38  4667.6  795.17  4726.4  786.81  4825.4  777.18  4910.2  773.89
  4967.6  776.42  4980.1   777.4  4998.4   775.9  5002.2  770.33  5016.3  767.76
  5018.2  767.26    5030  767.76  5030.6  776.07  5044.8  777.61  5114.6  776.75
  5117.3  776.63  5253.8  776.29  5256.8  776.31  5334.8  777.28  5390.3  781.99
    5399  783.01  5526.1  796.06  5540.3  795.25  5646.5  804.97  5667.8  805.55
#Mann= 12 ,-1 , 0
  4500.1     .12       0  4667.6     .05       0  4967.6     .12       0
  4980.1     .05       0  5016.3    .033       0    5030     .05       0
  5114.6     .12       0  5117.3     .05       0  5253.8     .12       0
  5256.8     .05       0  5390.3     .12       0    5399     .05       0
Bank Sta=5016.3,5030
XS Rating Curve= 0 ,0
Exp/Cntr=0.3,0.1

Type RM Length L Ch R = 1 ,13198   ,488,488,488
BEGIN DESCRIPTION:
Mapping XS 05f287ba
END DESCRIPTION:
XS GIS Cut Line= 3
      2292340.66      7167841.03      2292063.27      7168201.69
      2291757.41      7168558.68
#Sta/Elev= 30
  4764.7  813.13  4793.5  809.71  4801.3  807.02  4814.3  796.95  4831.6  794.04
  4857.8   792.3  4878.6  785.08  4901.4  782.88  4928.5  777.59  4957.5  775.64
  4986.5  775.88  4992.8  774.42  5000.5  767.82  5002.4  767.32  5014.2  767.82
  5042.7  775.58    5136  774.91  5179.6  772.85  5206.7     776  5221.4  774.95
  5270.7  772.83  5377.2  772.94  5485.2  777.69  5512.2  782.97  5561.6  785.55
  5575.8  791.51  5584.4  793.55  5604.4  793.16  5625.7  798.55  5689.8     799
#Mann= 7 ,-1 , 0
  4764.7     .12       0  4831.6     .05       0  5000.5    .033       0
  5014.2     .05       0  5221.4     .05       0  5485.2     .12       0
  5584.4     .05       0
Bank Sta=5000.5,5014.2
XS Rating Curve= 0 ,0
Exp/Cntr=0.3,0.1

Type RM Length L Ch R = 1 ,12710   ,555,555,555
BEGIN DESCRIPTION:
Mapping XS 9fa9aaa4
END DESCRIPTION:
XS GIS Cut Line= 3
       2292177.2      7167578.58      2291915.67      7167555.82
      2291514.18       7168515.4
#Sta/Elev= 30
  4553.2  795.92  4571.5  789.16  4595.5  786.59  4601.6   783.7  4641.7  781.32
  4661.8  776.67  4691.9  773.37  4850.9  771.79  4917.8  770.92  4952.7  773.12
  4993.4  765.08  4995.4  764.58  5007.1  765.08  5015.4  772.67  5073.8  772.82
  5183.1  771.07  5212.3     769  5351.4  771.75  5442.7  770.25  5493.4  772.39
  5572.5  777.25  5596.3  782.33  5601.7  780.72  5620.1  783.75  5645.9  783.63
  5673.1  784.01  5702.3  782.17  5726.1  786.75  5802.9  794.76  5855.9  797.04
#Mann= 7 ,-1 , 0
  4553.2     .05       0  4850.9     .12       0  4993.4     .07       0
  5007.1     .12       0  5073.8     .05       0  5493.4     .12       0
  5645.9     .05       0
Bank Sta=4993.4,5007.1
XS Rating Curve= 0 ,0
Exp/Cntr=0.3,0.1

Type RM Length L Ch R = 1 ,12155   ,443,443,443
BEGIN DESCRIPTION:
Mapping XS ce3fce77
END DESCRIPTION:
XS GIS Cut Line= 4
      2292150.89       7167431.5      2291580.71      7167418.96
      2291451.41      7167516.17      2290864.08      7168835.13
#Sta/Elev= 30
  4427.6  782.26  4449.5  782.02  4469.5  776.99  4569.5  773.09  4739.6  770.53
  4794.8  771.17  4839.6  768.26  4899.6  770.71  4929.6  768.64  4959.6  770.05
  4969.6  766.73  4972.8   764.3  4974.7   763.8  4986.5   764.3  4996.3  767.15
  5002.1  767.15  5007.1  770.37  5013.4  770.76  5097.5  768.56  5427.9  766.31
    5648  768.76  5694.5  767.13  6018.4  766.19  6186.6  767.85  6233.1  769.84
    6368     769  6429.9  771.22  6458.6  770.71  6597.9  775.23  6603.5  778.12
#Mann= 5 ,-1 , 0
  4427.6     .05       0  4794.8     .12       0  4972.8     .07       0
  4986.5     .12       0  5097.5     .05       0
Bank Sta=4972.8,4986.5
XS Rating Curve= 0 ,0
Exp/Cntr=0.3,0.1

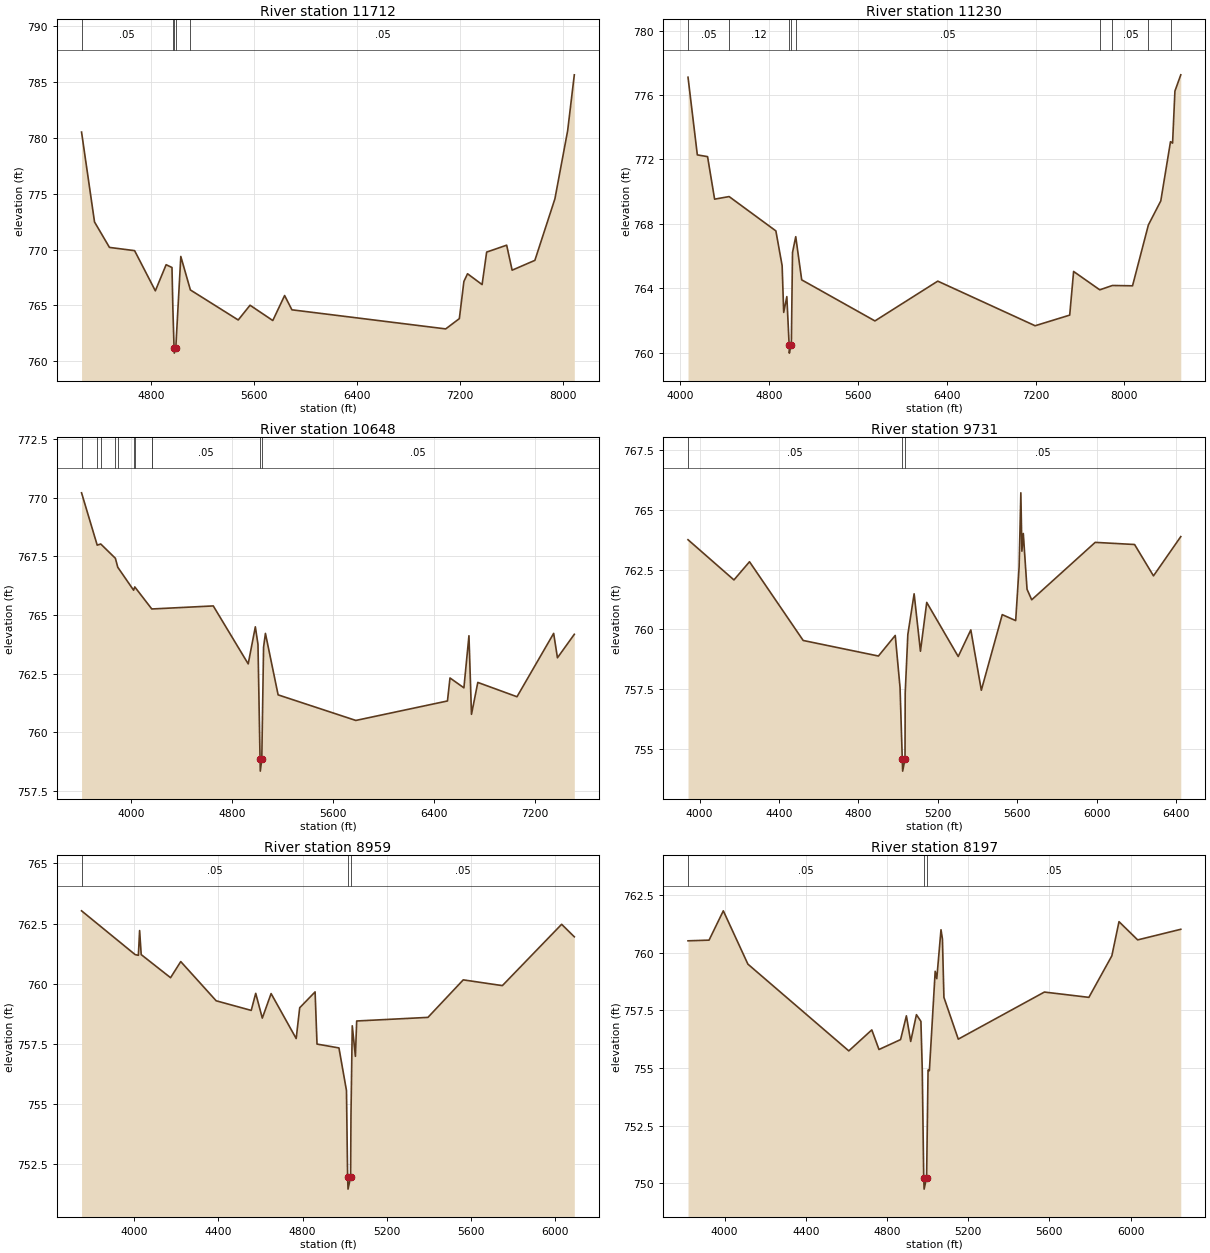
Type RM Length L Ch R = 1 ,11712   ,482,482,482
BEGIN DESCRIPTION:
Mapping XS 6c6129bc
END DESCRIPTION:
XS GIS Cut Line= 4
      2292137.93      7167298.88      2291613.67      7166977.71
      2291344.35      7167104.08      2289282.75      7169167.02
#Sta/Elev= 30
  4259.8  780.52  4360.6  772.47  4476.6  770.19    4672   769.9  4833.2   766.3
  4916.9  768.64  4962.5  768.39  4969.4  764.71  4978.5  761.22  4980.4  760.72
  4992.2  761.22    5031  769.38  5105.5  766.38  5477.1  763.69    5569  765.01
  5745.8  763.64  5837.7  765.88  5894.3   764.6  7089.3  762.89  7195.3  763.81
  7230.7  767.14    7259  767.83  7372.1  766.86  7407.5  769.77    7563  770.39
  7605.5  768.15  7782.2  769.03  7937.8  774.54  8036.8  780.64  8088.6  785.65
#Mann= 5 ,-1 , 0
  4259.8     .05       0  4969.4     .12       0  4978.5     .07       0
  4992.2     .12       0  5105.5     .05       0
Bank Sta=4978.5,4992.2
XS Rating Curve= 0 ,0
Exp/Cntr=0.3,0.1

Type RM Length L Ch R = 1 ,11230   ,582,582,582
BEGIN DESCRIPTION:
Mapping XS 6c68d6fe
END DESCRIPTION:
XS GIS Cut Line= 5
      2292129.92      7167247.85      2291486.44       7166585.8
       2291349.2      7166621.79      2291274.69       7166658.4
      2288886.95      7168922.43
#Sta/Elev= 30
  4069.5   777.1  4153.4  772.28  4245.5  772.17    4309  769.53  4439.8  769.69
  4860.8  767.56  4917.2   765.4  4931.3   762.5  4959.6  763.48  4980.5  760.47
  4982.4  759.97  4994.2  760.47  5000.4   760.6  5010.8  766.22  5039.8   767.2
  5093.5  764.52  5753.2  761.97  6319.1  764.44  7196.1  761.67  7507.6  762.33
  7542.8  765.04  7778.4   763.9  7892.5  764.17  8073.5  764.15  8216.4  767.93
    8328  769.42  8415.6   773.1  8434.3  773.01  8455.4  776.24  8508.1  777.25
#Mann= 9 ,-1 , 0
  4069.5     .05       0  4439.8     .12       0  4980.5     .07       0
  4994.2     .12       0  5039.8     .05       0  7778.4     .12       0
  7892.5     .05       0  8216.4     .12       0  8415.6     .05       0
Bank Sta=4980.5,4994.2
XS Rating Curve= 0 ,0
Exp/Cntr=0.3,0.1

Type RM Length L Ch R = 1 ,10648   ,917,917,917
BEGIN DESCRIPTION:
Mapping XS 7fda8e91
END DESCRIPTION:
XS GIS Cut Line= 4
      2292109.73       7167031.3      2291252.96      7166080.73
       2290246.7      7166800.94      2288865.62      7166778.86
#Sta/Elev= 30
  3610.5  770.21  3734.3  767.98  3762.2  768.03  3878.2  767.42  3896.9  767.04
  4022.2  766.06  4031.6   766.2  4166.2  765.26  4166.3  765.26  4652.6  765.39
  4928.9  762.92  4985.4   764.5  5006.3  763.75  5022.7  758.85  5024.7  758.35
  5036.4  758.85  5050.5  763.63  5065.2  764.22  5165.6   761.6  5780.5  760.51
  6505.4  761.34  6525.4  762.32  6635.4   761.9  6675.4  764.12  6695.4  760.77
  6745.4  762.13  7055.5  761.52  7345.5  764.22  7375.5  763.18  7508.9  764.18
#Mann= 11 ,-1 , 0
  3610.5     .05       0  3734.3     .12       0  3762.2     .05       0
  3878.2     .12       0  3896.9     .05       0  4022.2     .12       0
  4031.6     .05       0  4166.2     .12       0  4166.3     .05       0
  5022.7    .033       0  5036.4     .05       0
Bank Sta=5022.7,5036.4
XS Rating Curve= 0 ,0
Exp/Cntr=0.3,0.1

Type RM Length L Ch R = 1 ,9731    ,772,772,772
BEGIN DESCRIPTION:
Mapping XS 9517341d
END DESCRIPTION:
XS GIS Cut Line= 3
      2291547.25      7166127.49      2291098.57      7165568.84
      2289428.97      7164993.68
#Sta/Elev= 30
  3941.8  763.75  4173.2  762.07  4251.6  762.83    4522  759.54  4901.1  758.89
  4985.7  759.75    5010  757.57  5021.2  754.58  5023.1  754.08  5034.9  754.58
  5035.9  757.33  5049.2  759.79  5080.9  761.49  5112.7  759.09  5144.4  761.13
    5303  758.87  5366.5  759.98  5419.4  757.46  5524.8  760.62  5592.5  760.37
  5609.8  762.62  5618.5  765.71  5623.8  763.27  5630.9  764.01  5649.7  761.68
  5673.2  761.24  5993.1  763.64  6191.5  763.55  6286.7  762.24  6424.2  763.88
#Mann= 3 ,-1 , 0
  3941.8     .05       0  5021.2    .033       0  5034.9     .05       0
Bank Sta=5021.2,5034.9
XS Rating Curve= 0 ,0
Exp/Cntr=0.3,0.1

Type RM Length L Ch R = 1 ,8959    ,762,762,762
BEGIN DESCRIPTION:
Mapping XS 4a652b03
END DESCRIPTION:
XS GIS Cut Line= 4
      2291777.23      7166021.52      2291376.79      7165368.19
      2291243.14      7164925.29      2290323.35      7164301.82
#Sta/Elev= 30
  3750.1  763.03  4004.6  761.21    4020  761.18  4025.8  762.21  4033.4  761.21
  4172.8  760.25  4221.2  760.92  4389.4  759.29  4555.9  758.89  4577.2   759.6
  4608.5  758.57  4650.3  759.59  4769.4  757.72  4786.1     759  4859.2  759.66
  4868.3  757.49  4972.5  757.33  5008.2  755.56  5013.6  751.96  5015.6  751.46
  5027.8  751.96  5029.6  754.53  5035.7  758.25  5050.6  756.98  5056.7  758.45
  5395.1   758.6  5562.8  760.16  5748.5  759.92    6030  762.47  6090.2  761.95
#Mann= 3 ,-1 , 0
  3750.1     .05       0  5013.6    .033       0  5027.8     .05       0
Bank Sta=5013.6,5027.8
XS Rating Curve= 0 ,0
Exp/Cntr=0.3,0.1

Type RM Length L Ch R = 1 ,8197    ,0,0,0
BEGIN DESCRIPTION:
North Pecan Creek 19.0
END DESCRIPTION:
XS GIS Cut Line= 3
      2292532.51      7165292.08      2291718.35      7164317.16
      2290908.85       7163489.9
#Sta/Elev= 30
  3819.7  760.51  3923.4  760.54  3993.6  761.81  4114.7   759.5  4611.8  755.74
  4725.1  756.65  4760.5   755.8  4866.9  756.23  4895.5  757.26  4916.8  756.15
    4945  757.31  4967.1  757.02  4973.6  754.98  4980.9  750.25  4982.9  749.75
  4995.1  750.25  5002.3  754.91  5008.8  754.88  5037.4  759.19  5045.2  758.87
    5066  760.99  5073.1  760.59  5080.4  758.06  5151.1  756.25  5575.4  758.29
  5794.6  758.06  5907.7  759.86    5943  761.34    6035  760.55  6247.3  761.01
#Mann= 3 ,-1 , 0
  3819.7     .05       0  4980.9    .033       0  4995.1     .05       0
Bank Sta=4980.9,4995.1
XS Rating Curve= 0 ,0
Exp/Cntr=0.3,0.1

Chan Stop Cuts=-1
Use User Specified Reach Order=0
Composite Channel Slope=5