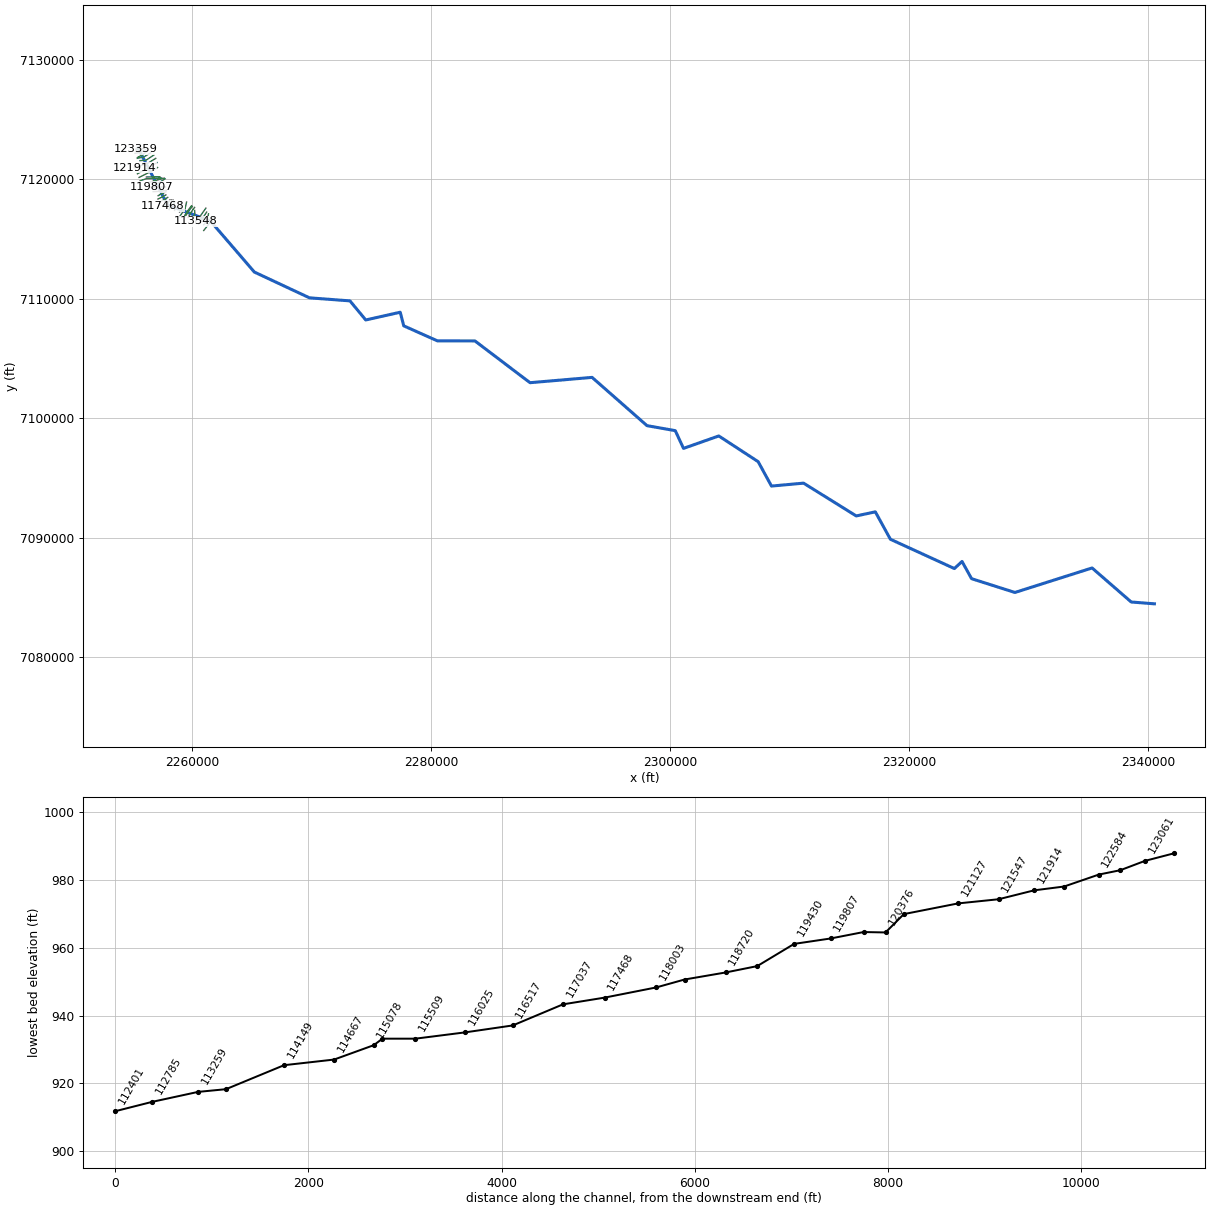
--- Oliver Creek.prj (project) ---

Proj Title=Oliver Creek Base Level Engineering
Current Plan=p01
Default Exp/Contr=0.3,0.1
English Units
Geom File=g01
Flow File=f01
Plan File=p01
BEGIN DESCRIPTION:
Oliver Creek
END DESCRIPTION:

--- Oliver Creek.p01 (plan) ---

Plan Title=Multiple Run
Short Identifier=Multiple
Geom File=g01
Flow File=f01
Subcritical Flow
K Sum by GR= 0
Std Step Tol= 0.01
Critical Tol= 0.01
Num of Std Step Trials= 20
Max Error Tol= 0.3
Flow Tol Ratio= 0.001
Split Flow NTrial= 30
Split Flow Tol= 0.02
Split Flow Ratio= 0.02
Log Output Level= 0
Friction Slope Method= 1
Unsteady Friction Slope Method= 2
Unsteady Bridges Friction Slope Method= 1
Parabolic Critical Depth
Global Vel Dist=  1 , 1 , 1
Global Log Level= 0
CheckData=True
Encroach Param= -1, 0, 0, 0
BEGIN DESCRIPTION:
Multiple Run
END DESCRIPTION:

--- Oliver Creek.f01 (steady flow) ---

Flow Title=Multiple
Number of Profiles=7
Profile Names=10-year,25-year,50-year,1pct_min,100-year,1pct_plu,500-year
River Rch & RM= Oliver Creek,Reach-1,123359
     545     743     906     549    1095    2185    1604
River Rch & RM= Oliver Creek,Reach-1,119807
     604     828    1013     616    1229    2451    1810
River Rch & RM= Oliver Creek,Reach-1,117468
     976    1373    1708    1053    2102    4193    3191
River Rch & RM= Oliver Creek,Reach-1,108765
    1057    1492    1860    1149    2293    4575    3495
River Rch & RM= Oliver Creek,Reach-1,105753
    1276    1817    2280    1416    2826    5639    4358
River Rch & RM= Oliver Creek,Reach-1,103827
    2012    2924    3718    2338    4665    9307    7368
River Rch & RM= Oliver Creek,Reach-1,99771
    2168    3159    4024    2534    5055   10087    8009
River Rch & RM= Oliver Creek,Reach-1,97794
    2235    3259    4154    2617    5222   10420    8283
River Rch & RM= Oliver Creek,Reach-1,96377
    2317    3381    4312    2718    5422   10819    8606
River Rch & RM= Oliver Creek,Reach-1,95451
    2723    3990    5102    3222    6429   12827   10245
River Rch & RM= Oliver Creek,Reach-1,90689
    2785    4080    5217    3295    6574   13116   10473
River Rch & RM= Oliver Creek,Reach-1,89303
    2777    4067    5198    3281    6547   13062   10421
River Rch & RM= Oliver Creek,Reach-1,88303
    3124    4590    5879    3717    7416   14797   11845
River Rch & RM= Oliver Creek,Reach-1,86091
    3164    4649    5955    3766    7513   14991   12003
River Rch & RM= Oliver Creek,Reach-1,85782
    3363    4962    6376    4043    8068   16097   12965
River Rch & RM= Oliver Creek,Reach-1,81572
    3407    5030    6463    4099    8179   16320   13147
River Rch & RM= Oliver Creek,Reach-1,80001
    4360    6486    8379    5339   10653   21256   17283
River Rch & RM= Oliver Creek,Reach-1,76537
    4444    6612    8542    5444   10861   21672   17622
River Rch & RM= Oliver Creek,Reach-1,75910
    4455    6627    8561    5455   10884   21716   17652
River Rch & RM= Oliver Creek,Reach-1,74565
    5072    7568    9797    6254   12479   24899   20314
River Rch & RM= Oliver Creek,Reach-1,71571
    5447    8144   10559    6749   13466   26869   21975
River Rch & RM= Oliver Creek,Reach-1,70808
    5519    8250   10693    6833   13633   27202   22233
River Rch & RM= Oliver Creek,Reach-1,67807
    5766    8633   11203    7166   14298   28529   23367
River Rch & RM= Oliver Creek,Reach-1,65805
    5952    8920   11582    7413   14792   29514   24202
River Rch & RM= Oliver Creek,Reach-1,64142
    5948    8909   11564    7399   14763   29456   24135
River Rch & RM= Oliver Creek,Reach-1,61879
    6002    8986   11661    7459   14882   29694   24317
River Rch & RM= Oliver Creek,Reach-1,58698
    7237   10888   14178    9097   18150   36214   29833
River Rch & RM= Oliver Creek,Reach-1,52638
    7306   10991   14311    9181   18318   36550   30102
River Rch & RM= Oliver Creek,Reach-1,51572
    7434   11182   14560    9340   18635   37182   30617
River Rch & RM= Oliver Creek,Reach-1,50482
    7510   11294   14702    9429   18813   37538   30896
River Rch & RM= Oliver Creek,Reach-1,46720
    7580   11396   14833    9511   18977   37863   31150
River Rch & RM= Oliver Creek,Reach-1,43424
    7859   11821   15390    9871   19694   39296   32342
River Rch & RM= Oliver Creek,Reach-1,40534
    8014   12054   15693   10064   20080   40066   32969
River Rch & RM= Oliver Creek,Reach-1,36127
    8113   12205   15893   10193   20338   40580   33399
River Rch & RM= Oliver Creek,Reach-1,34483
    8111   12199   15882   10184   20320   40544   33359
River Rch & RM= Oliver Creek,Reach-1,32980
    8153   12261   15960   10233   20418   40740   33510
River Rch & RM= Oliver Creek,Reach-1,30428
    8196   12321   16035   10279   20509   40922   33644
River Rch & RM= Oliver Creek,Reach-1,28908
    8238   12383   16117   10331   20613   41128   33810
River Rch & RM= Oliver Creek,Reach-1,26067
    8229   12362   16082   10304   20559   41020   33690
River Rch & RM= Oliver Creek,Reach-1,19764
    8357   12556   16335   10466   20882   41665   34219
River Rch & RM= Oliver Creek,Reach-1,16900
    8341   12516   16270   10416   20782   41465   33996
River Rch & RM= Oliver Creek,Reach-1,11965
    8406   12612   16394   10494   20938   41777   34245
River Rch & RM= Oliver Creek,Reach-1,3345
    8424   12634   16417   10505   20961   41822   34260
Boundary for River Rch & Prof#=Oliver Creek,Reach-1,1
Up Type=0
Dn Type=3
Dn Slope=0.0025
Boundary for River Rch & Prof#=Oliver Creek,Reach-1,2
Up Type=0
Dn Type=3
Dn Slope=0.0025
Boundary for River Rch & Prof#=Oliver Creek,Reach-1,3
Up Type=0
Dn Type=3
Dn Slope=0.0025
Boundary for River Rch & Prof#=Oliver Creek,Reach-1,4
Up Type=0
Dn Type=3
Dn Slope=0.0025
Boundary for River Rch & Prof#=Oliver Creek,Reach-1,5
Up Type=0
Dn Type=3
Dn Slope=0.0025
Boundary for River Rch & Prof#=Oliver Creek,Reach-1,6
Up Type=0
Dn Type=3
Dn Slope=0.0025
Boundary for River Rch & Prof#=Oliver Creek,Reach-1,7
Up Type=0
Dn Type=3
Dn Slope=0.0025

--- Oliver Creek.g01 (geometry) ---

Geom Title=Existing Conditions

River Reach=Oliver Creek,Reach-1
Reach XY= 30
      2255479.00      7122610.00      2257961.78      7117826.21
      2261535.07      7116501.87      2265219.29      7112220.18
      2269830.72      7110063.34      2273217.52      7109808.53
      2274539.43      7108211.05      2277422.91      7108858.44
      2277719.18      7107720.50      2280534.86      7106462.05
      2283677.55      7106456.47      2288284.85      7102962.06
      2293477.50      7103406.39      2298072.94      7099368.14
      2300438.81      7098949.49      2301126.55      7097465.46
      2304077.55      7098506.47      2307373.39      7096354.41
      2308487.30      7094313.07      2311173.15      7094557.94
      2315580.50      7091813.62      2317177.37      7092156.88
      2318437.34      7089863.16      2323790.95      7087411.92
      2324431.74      7088004.66      2325230.47      7086563.55
      2328858.97      7085410.06      2335313.64      7087460.10
      2338587.34      7084613.16      2340529.00      7084460.00

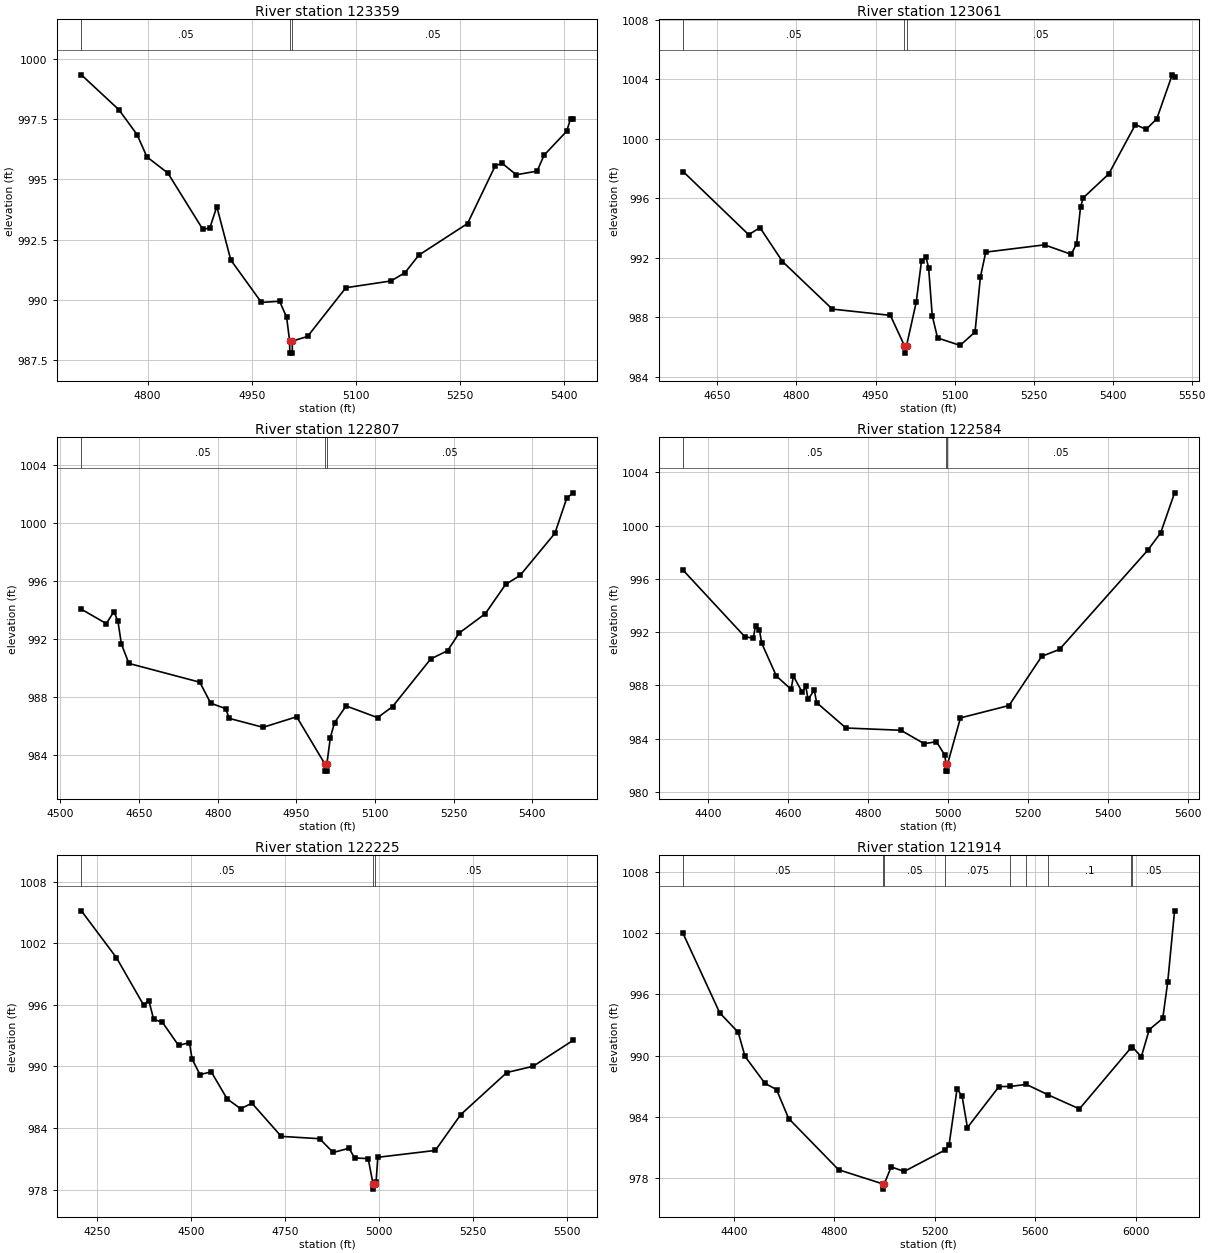
Type RM Length L Ch R = 1,123359,298,298,298
BEGIN DESCRIPTION:
Oliver Creek 176.0
END DESCRIPTION:
XS GIS Cut Line= 3
      2256002.82      7122564.17      2255701.60      7122529.93
      2255297.57      7122504.27
#Sta/Elev= 30
  4704.6  999.33  4758.8  997.88  4784.9  996.85  4799.0  995.93  4829.2  995.26
  4879.5  992.93  4889.6  992.98  4899.7  993.87  4919.8  991.66  4964.0  989.90
  4990.2  989.95  5000.3  989.28  5004.6  988.30  5004.8  987.80  5008.3  987.80
  5008.6  988.30  5030.4  988.49  5085.6  990.51  5150.6  990.79  5170.7  991.13
  5190.7  991.86  5260.9  993.17  5300.9  995.57  5311.0  995.66  5331.0  995.19
  5361.1  995.34  5371.1  996.00  5403.6  996.99  5409.4  997.52  5412.6  997.52
#Mann=3,-1,0
  4704.6    0.05       0  5004.6    0.04       0  5008.6    0.05       0
Bank Sta=5004.6,5008.6
Exp/Cntr=0.3,0.1

Type RM Length L Ch R = 1,123061,254,254,254
BEGIN DESCRIPTION:
Oliver Creek 175.0
END DESCRIPTION:
XS GIS Cut Line= 3
      2256099.82      7122460.33      2255745.81      7122243.39
      2255235.83      7122154.89
#Sta/Elev= 30
  4584.8  997.80  4709.4  993.55  4730.7  994.03  4773.4  991.75  4868.0  988.55
  4978.2  988.13  5004.9  986.09  5005.2  985.59  5008.9  986.09  5027.2  989.00
  5037.4  991.81  5045.8  992.04  5050.8  991.33  5057.7  988.10  5067.8  986.61
  5110.5  986.11  5138.9  987.01  5149.0  990.69  5159.2  992.38  5270.8  992.87
  5321.5  992.23  5331.7  992.96  5339.1  995.41  5344.2  996.03  5392.6  997.63
  5443.3 1000.96  5463.6 1000.63  5483.9 1001.35  5513.1 1004.30  5517.6 1004.15
#Mann=3,-1,0
  4584.8    0.05       0  5004.9    0.04       0  5008.9    0.05       0
Bank Sta=5004.9,5008.9
Exp/Cntr=0.3,0.1

Type RM Length L Ch R = 1,122807,223,223,223
BEGIN DESCRIPTION:
Oliver Creek 174.0
END DESCRIPTION:
XS GIS Cut Line= 3
      2256214.47      7122322.36      2255861.96      7122026.51
      2255438.40      7121806.71
#Sta/Elev= 30
  4539.8  994.05  4587.5  993.05  4601.8  993.89  4609.6  993.21  4616.1  991.65
  4630.4  990.30  4765.7  989.00  4786.5  987.55  4815.1  987.17  4821.7  986.50
  4886.4  985.88  4950.4  986.61  5004.1  983.35  5004.4  982.85  5007.9  982.85
  5008.1  983.35  5014.6  985.16  5022.6  986.20  5044.7  987.36  5104.7  986.55
  5133.2  987.31  5206.1  990.61  5238.2  991.18  5260.3  992.40  5310.2  993.74
  5348.8  995.76  5376.6  996.39  5442.9  999.30  5465.3 1001.71  5477.2 1002.10
#Mann=3,-1,0
  4539.8    0.05       0  5004.1    0.04       0  5008.1    0.05       0
Bank Sta=5004.1,5008.1
Exp/Cntr=0.3,0.1

Type RM Length L Ch R = 1,122584,359,359,359
BEGIN DESCRIPTION:
Oliver Creek 173.0
END DESCRIPTION:
XS GIS Cut Line= 3
      2256542.55      7122197.32      2255978.70      7121850.47
      2255423.39      7121737.39
#Sta/Elev= 30
  4338.0  996.66  4492.0  991.67  4513.3  991.54  4519.2  992.50  4528.7  992.19
  4534.6  991.17  4571.3  988.70  4608.0  987.71  4613.9  988.70  4635.7  987.49
  4644.7  987.92  4650.6  986.95  4666.0  987.65  4671.8  986.71  4745.2  984.80
  4882.5  984.63  4940.9  983.62  4971.3  983.77  4992.6  982.75  4994.9  982.06
  4995.1  981.56  4998.6  981.56  4998.9  982.06  5031.4  985.56  5152.8  986.49
  5234.4  990.18  5279.1  990.71  5499.7  998.16  5532.0  999.47  5566.7 1002.47
#Mann=3,-1,0
  4338.0    0.05       0  4994.9    0.04       0  4998.9    0.05       0
Bank Sta=4994.9,4998.9
Exp/Cntr=0.3,0.1

Type RM Length L Ch R = 1,122225,311,311,311
BEGIN DESCRIPTION:
Oliver Creek 172.0
END DESCRIPTION:
XS GIS Cut Line= 3
      2256818.58      7122018.93      2256158.60      7121579.83
      2255643.57      7121545.03
#Sta/Elev= 30
  4207.3 1005.15  4300.8 1000.58  4372.9  995.98  4387.0  996.40  4399.9  994.57
  4423.0  994.30  4466.1  992.04  4495.1  992.31  4502.2  990.70  4523.2  989.20
  4553.3  989.46  4595.3  986.84  4631.4  985.87  4661.5  986.41  4739.6  983.18
  4841.8  982.95  4877.9  981.61  4920.0  982.02  4935.0  981.08  4971.1  981.01
  4984.1  978.54  4984.3  978.04  4988.1  978.54  4992.1  978.75  4996.8  981.14
  5149.9  981.81  5217.6  985.30  5340.4  989.40  5410.5  990.01  5516.2  992.52
#Mann=3,-1,0
  4207.3    0.05       0  4984.1    0.04       0  4988.1    0.05       0
Bank Sta=4984.1,4988.1
Exp/Cntr=0.3,0.1

Type RM Length L Ch R = 1,121914,367,367,367
BEGIN DESCRIPTION:
Oliver Creek 171.0
END DESCRIPTION:
XS GIS Cut Line= 3
      2256967.02      7121732.47      2256283.19      7121311.73
      2255182.93      7120959.38
#Sta/Elev= 30
  4197.1 1001.96  4343.2  994.18  4416.6  992.28  4443.8  989.92  4523.5  987.27
  4569.3  986.67  4617.7  983.83  4816.6  978.81  4994.4  977.41  4994.7  976.91
  4998.4  977.41  5026.4  979.09  5077.9  978.64  5241.3  980.75  5256.6  981.20
  5288.8  986.75  5308.9  985.99  5329.9  982.94  5455.9  986.96  5500.1  986.97
  5564.8  987.17  5652.2  986.14  5776.2  984.77  5980.3  990.72  5987.0  990.82
  6022.9  989.89  6054.4  992.54  6108.1  993.64  6127.9  997.19  6155.3 1004.18
#Mann=9,-1,0
  4197.1    0.05       0  4994.4    0.04       0  4998.4    0.05       0
  5241.3   0.075       0  5500.1     0.1       0  5564.8   0.075       0
  5652.2     0.1       0  5980.3   0.075       0  5987.0    0.05       0
Bank Sta=4994.4,4998.4
Exp/Cntr=0.3,0.1

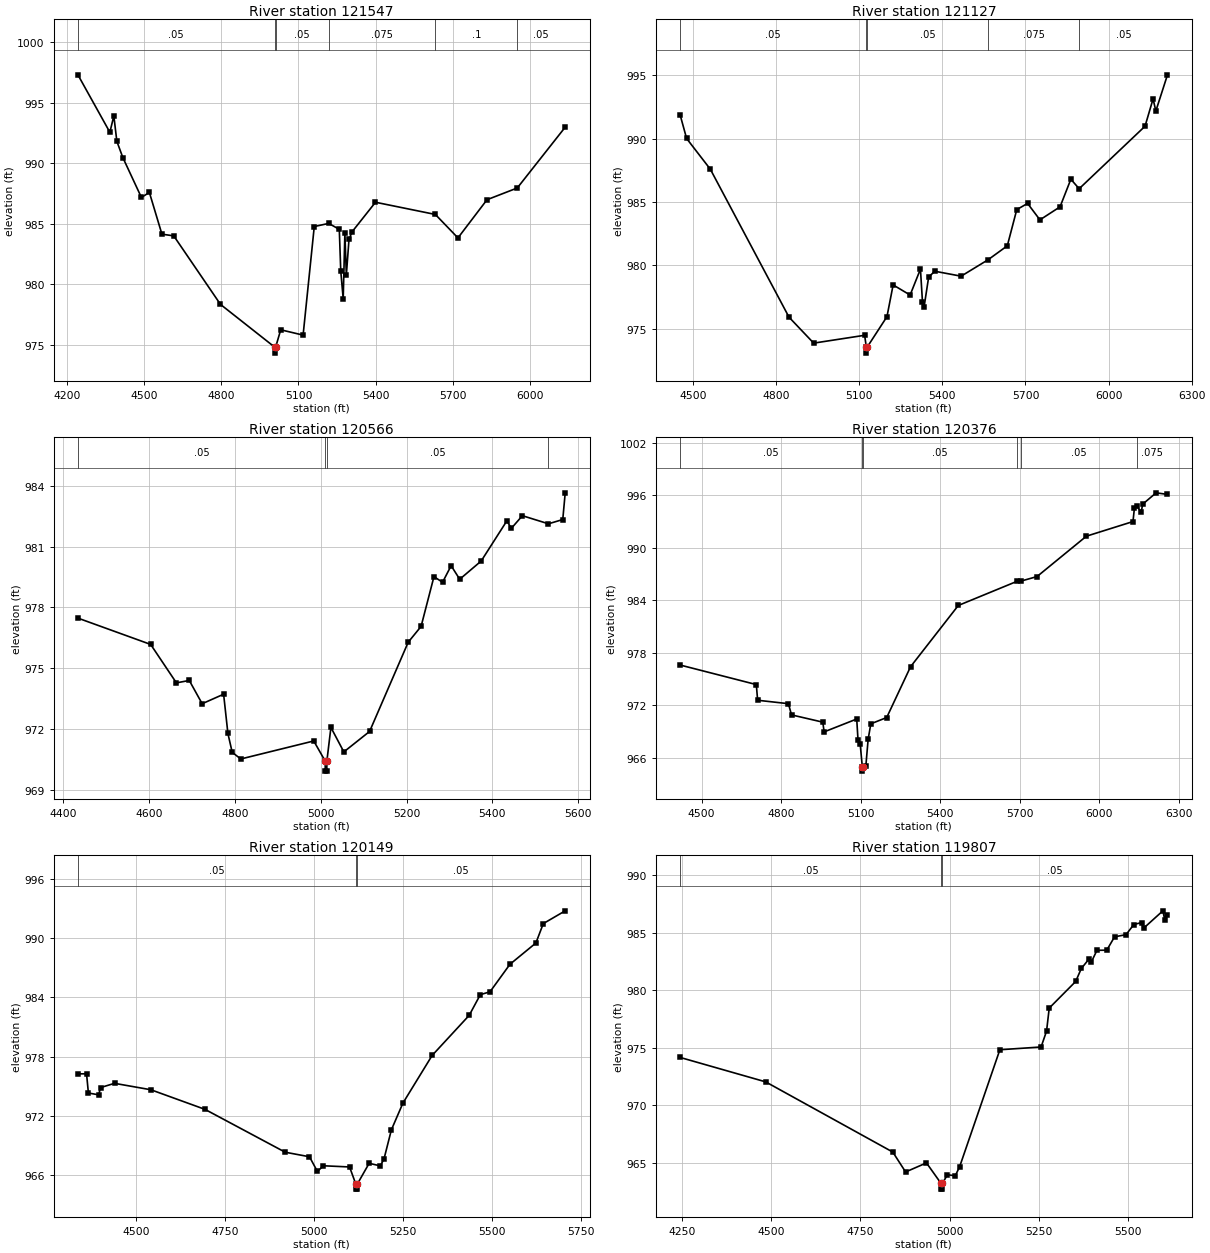
Type RM Length L Ch R = 1,121547,420,420,420
BEGIN DESCRIPTION:
Oliver Creek 170.0
END DESCRIPTION:
XS GIS Cut Line= 3
      2257078.98      7121379.60      2256428.41      7120991.57
      2255434.44      7120439.49
#Sta/Elev= 30
  4242.5  997.31  4366.7  992.56  4382.2  993.91  4393.9  991.81  4417.1  990.47
  4489.3  987.17  4520.4  987.58  4569.1  984.13  4615.1  983.99  4796.8  978.32
  5007.3  974.79  5007.5  974.29  5011.3  974.79  5031.0  976.22  5118.0  975.78
  5161.4  984.76  5217.5  985.02  5258.7  984.53  5264.4  981.07  5273.9  978.78
  5280.4  984.21  5286.1  980.75  5296.4  983.69  5308.2  984.32  5399.4  986.77
  5632.2  985.76  5720.0  983.82  5833.0  986.98  5950.6  987.95  6137.0  992.98
#Mann=6,-1,0
  4242.5    0.05       0  5007.3    0.04       0  5011.3    0.05       0
  5217.5   0.075       0  5632.2     0.1       0  5950.6    0.05       0
Bank Sta=5007.3,5011.3
Exp/Cntr=0.3,0.1

Type RM Length L Ch R = 1,121127,561,561,561
BEGIN DESCRIPTION:
Oliver Creek 169.0
END DESCRIPTION:
XS GIS Cut Line= 3
      2257121.98      7120968.16      2256655.75      7120683.41
      2255572.57      7120138.12
#Sta/Elev= 30
  4453.7  991.87  4476.9  990.02  4562.6  987.59  4846.6  975.90  4935.6  973.85
  5119.5  974.47  5125.5  973.56  5125.8  973.06  5129.5  973.56  5200.1  975.94
  5222.4  978.45  5283.7  977.65  5321.0  979.70  5328.3  977.11  5333.9  976.68
  5350.7  979.08  5373.0  979.53  5467.8  979.14  5565.3  980.44  5634.5  981.54
  5668.7  984.40  5707.7  984.89  5752.3  983.59  5824.9  984.62  5863.9  986.80
  5893.9  986.05  6131.7  990.99  6160.7  993.15  6170.7  992.19  6212.7  995.05
#Mann=5,-1,0
  4453.7    0.05       0  5125.5    0.04       0  5129.5    0.05       0
  5565.3   0.075       0  5893.9    0.05       0
Bank Sta=5125.5,5129.5
Exp/Cntr=0.3,0.1

Type RM Length L Ch R = 1,120566,190,190,190
BEGIN DESCRIPTION:
Mapping XS 56e0e711
END DESCRIPTION:
XS GIS Cut Line= 3
      2257318.52      7120182.83      2256736.77      7120185.78
      2256183.29      7120172.66
#Sta/Elev= 30
  4434.3  977.47  4603.8  976.17  4663.8  974.27  4693.8  974.39  4723.8  973.24
  4773.8  973.71  4783.8  971.77  4793.8  970.84  4813.8  970.51  4983.8  971.40
  5010.4  970.41  5010.7  969.91  5014.2  969.91  5014.4  970.41  5023.8  972.07
  5053.9  970.86  5113.9  971.87  5203.9  976.28  5233.9  977.06  5263.9  979.52
  5283.9  979.24  5303.9  980.06  5323.9  979.39  5373.9  980.29  5433.9  982.28
  5444.0  981.90  5469.9  982.53  5530.6  982.13  5564.0  982.34  5569.7  983.66
#Mann=4,-1,0
  4434.3    0.05       0  5010.4   0.033       0  5014.4    0.05       0
  5530.6   0.075       0
Bank Sta=5010.4,5014.4
Exp/Cntr=0.3,0.1

Type RM Length L Ch R = 1,120376,227,227,227
BEGIN DESCRIPTION:
Oliver Creek 167.0
END DESCRIPTION:
XS GIS Cut Line= 4
      2257466.13      7120098.22      2256771.72      7120042.73
      2256143.44      7120022.27      2255658.46      7119853.01
#Sta/Elev= 30
  4419.4  976.61  4706.7  974.38  4711.7  972.59  4827.8  972.20  4839.6  970.92
  4957.6  970.09  4962.6  968.98  5085.6  970.45  5090.6  968.01  5098.7  967.58
  5106.7  965.00  5107.0  964.50  5110.7  965.00  5119.9  965.03  5128.7  968.13
  5138.8  969.90  5198.8  970.62  5288.8  976.42  5468.9  983.41  5690.7  986.17
  5703.9  986.18  5766.0  986.71  5952.3  991.32  6128.1  992.99  6133.4  994.49
  6142.0  994.78  6159.2  994.05  6164.5  994.97  6215.4  996.27  6258.3  996.09
#Mann=6,-1,0
  4419.4    0.05       0  5106.7   0.033       0  5110.7    0.05       0
  5690.7   0.075       0  5703.9    0.05       0  6142.0   0.075       0
Bank Sta=5106.7,5110.7
Exp/Cntr=0.3,0.1

Type RM Length L Ch R = 1,120149,342,342,342
BEGIN DESCRIPTION:
Oliver Creek 166.0
END DESCRIPTION:
XS GIS Cut Line= 3
      2257677.13      7120081.64      2256921.90      7119869.98
      2256359.90      7119706.22
#Sta/Elev= 30
  4335.6  976.27  4359.9  976.27  4365.1  974.33  4394.0  974.15  4399.2  974.88
  4438.5  975.31  4540.8  974.66  4692.8  972.68  4918.2  968.35  4986.5  967.89
  5008.7  966.41  5025.8  966.98  5099.2  966.86  5116.8  965.12  5117.1  964.62
  5120.6  964.62  5120.8  965.12  5154.2  967.23  5185.4  966.97  5195.9  967.66
  5216.7  970.61  5249.1  973.31  5331.3  978.13  5435.4  982.18  5466.7  984.27
  5494.0  984.56  5550.0  987.34  5622.9  989.49  5643.7  991.45  5705.3  992.74
#Mann=3,-1,0
  4335.6    0.05       0  5116.8    0.04       0  5120.8    0.05       0
Bank Sta=5116.8,5120.8
Exp/Cntr=0.3,0.1

Type RM Length L Ch R = 1,119807,377,377,377
BEGIN DESCRIPTION:
Oliver Creek 165.0
END DESCRIPTION:
XS GIS Cut Line= 3
      2257754.75      7120023.34      2257139.05      7119638.85
      2256578.58      7119331.09
#Sta/Elev= 30
  4245.4  974.16  4484.9  972.04  4841.1  965.94  4877.0  964.21  4935.4  965.00
  4976.2  963.22  4976.4  962.72  4979.9  962.72  4980.2  963.22  4994.2  963.97
  5016.1  963.88  5028.4  964.67  5141.1  974.83  5256.6  975.07  5271.9  976.45
  5279.4  978.45  5353.4  980.76  5369.5  981.90  5391.3  982.73  5397.0  982.43
  5413.1  983.47  5440.6  983.48  5462.4  984.64  5494.6  984.83  5516.4  985.71
  5538.2  985.88  5543.9  985.39  5597.8  986.90  5603.5  986.06  5610.7  986.56
#Mann=3,-1,0
  4245.4    0.05       0  4976.2    0.04       0  4980.2    0.05       0
Bank Sta=4976.2,4980.2
Exp/Cntr=0.3,0.1

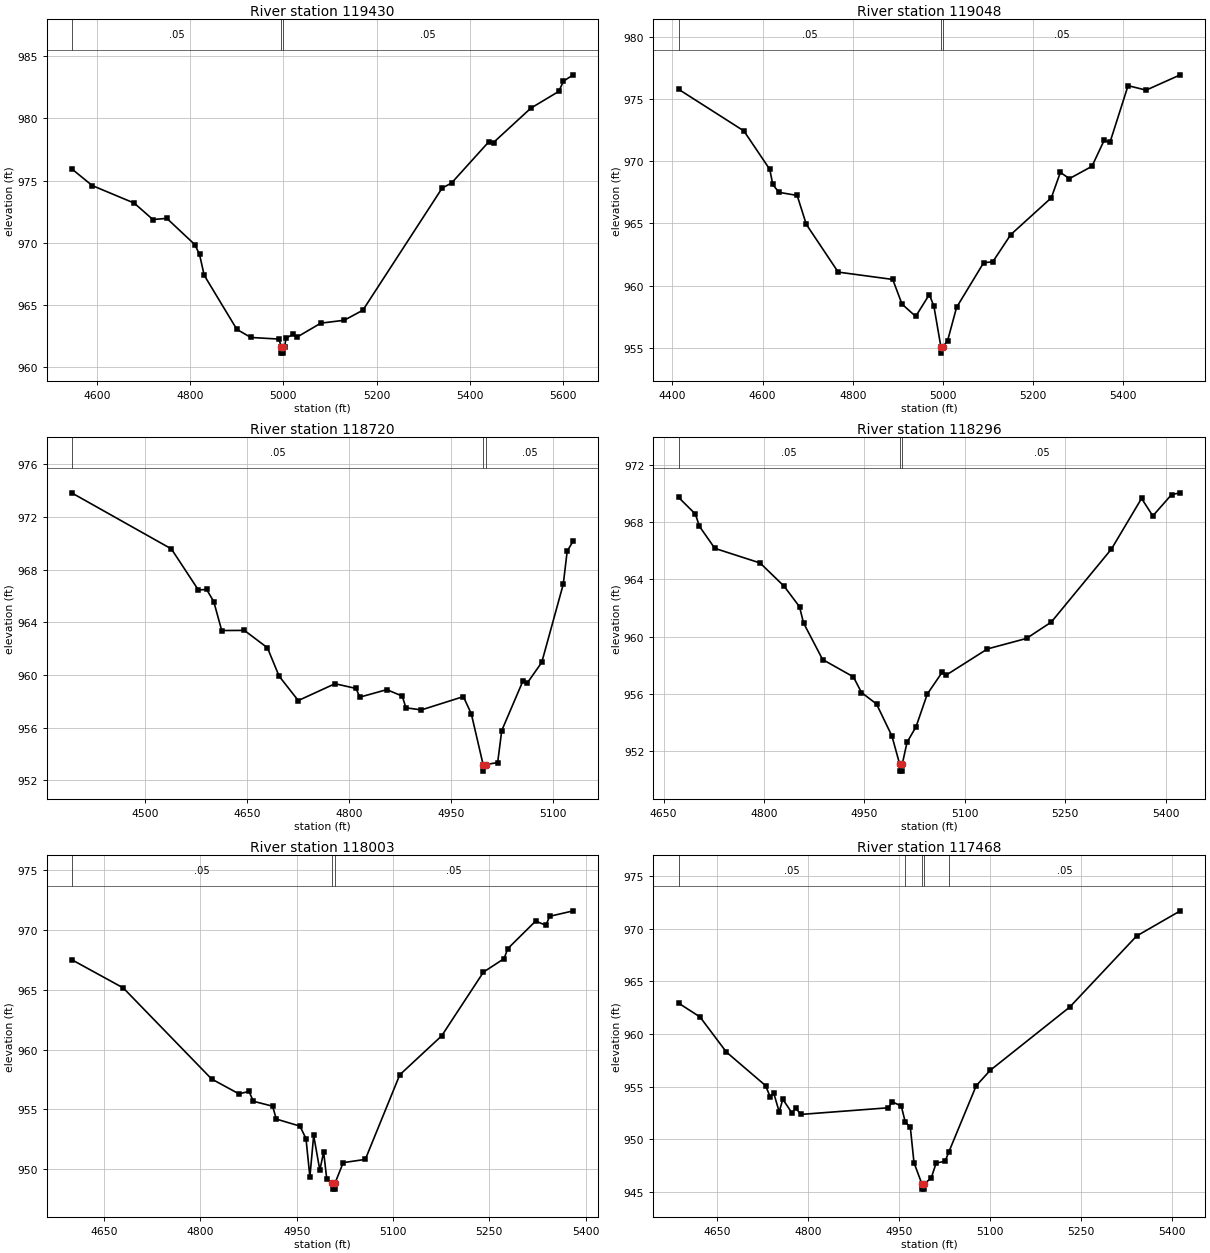
Type RM Length L Ch R = 1,119430,382,382,382
BEGIN DESCRIPTION:
Oliver Creek 164.0
END DESCRIPTION:
XS GIS Cut Line= 3
      2257783.12      7119339.01      2257329.24      7119335.08
      2256707.79      7119327.07
#Sta/Elev= 30
  4546.1  975.95  4590.2  974.60  4680.2  973.19  4720.2  971.87  4750.2  971.96
  4810.2  969.85  4820.2  969.07  4830.2  967.39  4900.2  963.04  4930.2  962.39
  4990.2  962.26  4995.6  961.63  4995.9  961.13  4999.4  961.13  4999.6  961.63
  5002.6  961.63  5005.6  962.34  5020.2  962.63  5030.2  962.44  5080.2  963.54
  5130.2  963.77  5170.3  964.58  5340.3  974.40  5360.3  974.80  5440.3  978.12
  5450.3  978.06  5530.3  980.82  5590.3  982.17  5600.3  983.00  5621.5  983.50
#Mann=3,-1,0
  4546.1    0.05       0  4995.6    0.04       0  4999.6    0.05       0
Bank Sta=4995.6,4999.6
Exp/Cntr=0.3,0.1

Type RM Length L Ch R = 1,119048,328,328,328
BEGIN DESCRIPTION:
Oliver Creek 163.0
END DESCRIPTION:
XS GIS Cut Line= 3
      2257859.03      7119056.25      2257279.34      7118969.17
      2256753.15      7118948.42
#Sta/Elev= 30
  4413.8  975.78  4558.7  972.43  4616.1  969.34  4622.7  968.13  4636.3  967.50
  4676.8  967.25  4697.0  964.93  4767.8  961.09  4888.8  960.50  4909.3  958.52
  4939.7  957.53  4970.0  959.29  4980.1  958.34  4995.6  955.08  4995.9  954.58
  4999.6  955.08  5010.3  955.56  5030.4  958.26  5090.4  961.84  5110.7  961.92
  5150.5  964.10  5240.5  967.06  5260.5  969.10  5280.6  968.60  5330.6  969.59
  5357.6  971.67  5370.6  971.52  5410.7  976.07  5450.7  975.71  5526.6  976.94
#Mann=3,-1,0
  4413.8    0.05       0  4995.6    0.04       0  4999.6    0.05       0
Bank Sta=4995.6,4999.6
Exp/Cntr=0.3,0.1

Type RM Length L Ch R = 1,118720,424,424,424
BEGIN DESCRIPTION:
Oliver Creek 162.0
END DESCRIPTION:
XS GIS Cut Line= 3
      2257827.78      7118937.77      2257279.91      7118673.89
      2257167.60      7118609.63
#Sta/Elev= 30
  4391.9  973.84  4538.5  969.58  4578.2  966.46  4590.3  966.50  4600.8  965.58
  4612.5  963.38  4645.8  963.39  4679.7  962.07  4696.8  959.92  4725.0  958.06
  4779.0  959.34  4809.9  958.98  4815.5  958.32  4855.2  958.89  4877.8  958.40
  4883.3  957.51  4906.0  957.35  4967.7  958.36  4979.4  957.05  4996.7  953.20
  4997.0  952.70  5000.7  953.20  5018.1  953.35  5024.1  955.78  5055.5  959.58
  5061.3  959.37  5082.9  960.96  5114.5  966.89  5120.3  969.41  5129.4  970.20
#Mann=3,-1,0
  4391.9    0.05       0  4996.7   0.033       0  5000.7    0.05       0
Bank Sta=4996.7,5000.7
Exp/Cntr=0.3,0.1

Type RM Length L Ch R = 1,118296,293,293,293
BEGIN DESCRIPTION:
Oliver Creek 161.0
END DESCRIPTION:
XS GIS Cut Line= 3
      2257816.00      7118677.32      2257531.28      7118515.49
      2257153.00      7118328.89
#Sta/Elev= 30
  4672.5  969.71  4697.6  968.55  4703.6  967.70  4726.6  966.16  4794.2  965.14
  4830.1  963.52  4853.1  962.09  4859.1  960.96  4887.6  958.41  4933.6  957.20
  4945.6  956.11  4968.1  955.31  4991.1  953.08  5002.6  951.13  5002.9  950.63
  5006.4  950.63  5006.6  951.13  5013.7  952.64  5027.1  953.72  5043.9  956.00
  5066.4  957.54  5072.0  957.32  5133.8  959.15  5192.1  959.88  5229.1  961.02
  5318.9  966.11  5363.9  969.64  5380.7  968.42  5408.8  969.91  5421.8  970.03
#Mann=3,-1,0
  4672.5    0.05       0  5002.6   0.033       0  5006.6    0.05       0
Bank Sta=5002.6,5006.6
Exp/Cntr=0.3,0.1

Type RM Length L Ch R = 1,118003,535,535,535
BEGIN DESCRIPTION:
Oliver Creek 160.0
END DESCRIPTION:
XS GIS Cut Line= 3
      2257971.03      7118467.73      2257628.60      7118259.83
      2257295.69      7118074.75
#Sta/Elev= 30
  4599.4  967.53  4679.8  965.16  4817.4  957.53  4860.1  956.28  4875.6  956.49
  4882.5  955.66  4912.4  955.25  4918.2  954.17  4955.0  953.58  4964.4  952.54
  4970.5  949.33  4976.4  952.80  4986.0  949.88  4991.9  951.42  4996.8  949.14
  5005.6  948.80  5005.9  948.30  5009.4  948.30  5009.6  948.80  5022.4  950.52
  5056.8  950.79  5110.5  957.88  5175.7  961.14  5240.9  966.49  5272.9  967.61
  5278.7  968.45  5322.1  970.76  5338.1  970.41  5343.9  971.16  5380.9  971.62
#Mann=3,-1,0
  4599.4    0.05       0  5005.6   0.033       0  5009.6    0.05       0
Bank Sta=5005.6,5009.6
Exp/Cntr=0.3,0.1

Type RM Length L Ch R = 1,117468,431,431,431
BEGIN DESCRIPTION:
Oliver Creek 159.0
END DESCRIPTION:
XS GIS Cut Line= 3
      2258158.48      7118259.35      2257928.73      7117914.95
      2257553.53      7117741.38
#Sta/Elev= 30
  4586.0  962.94  4621.3  961.63  4664.8  958.30  4729.5  955.11  4736.9  954.07
  4742.9  954.41  4751.9  952.63  4757.9  953.82  4772.9  952.52  4778.9  952.98
  4787.9  952.38  4932.1  953.01  4938.1  953.58  4953.2  953.18  4959.7  951.68
  4968.2  951.14  4974.2  947.80  4987.2  945.79  4987.5  945.29  4991.0  945.29
  4991.2  945.79  5002.6  946.34  5010.7  947.76  5025.5  947.94  5031.6  948.81
  5076.8  955.10  5099.8  956.56  5231.1  962.57  5341.3  969.31  5413.4  971.70
#Mann=5,-1,0
  4586.0    0.05       0  4959.7    0.12       0  4987.2    0.07       0
  4991.2    0.12       0  5031.6    0.05       0
Bank Sta=4987.2,4991.2
Exp/Cntr=0.3,0.1

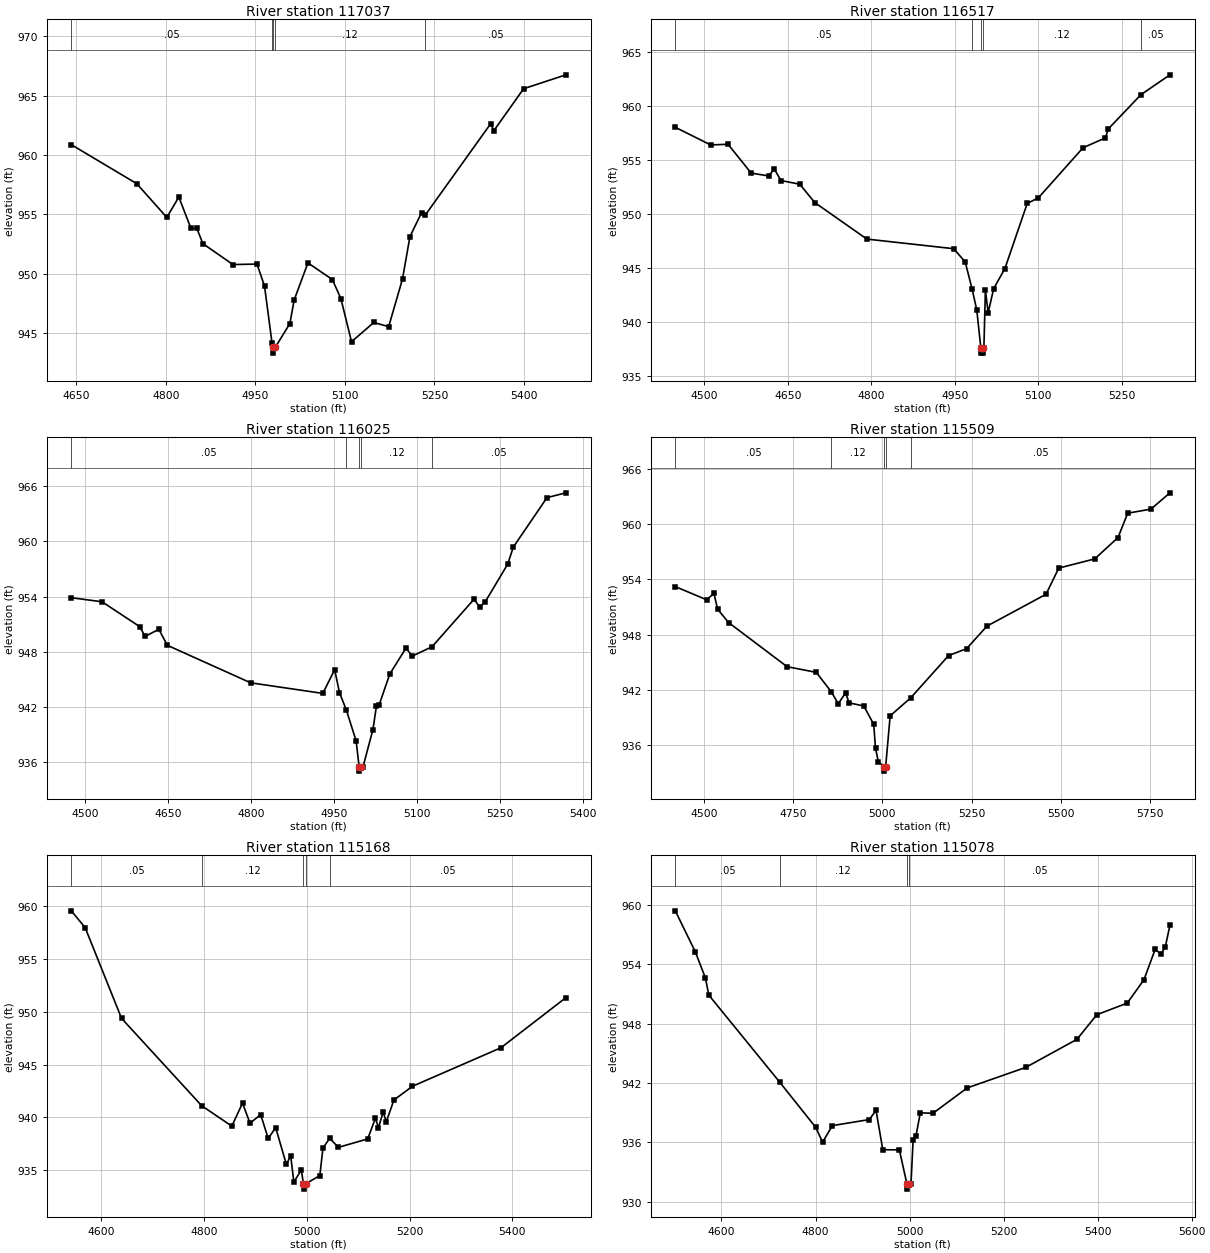
Type RM Length L Ch R = 1,117037,520,520,520
BEGIN DESCRIPTION:
Oliver Creek 158.0
END DESCRIPTION:
XS GIS Cut Line= 3
      2258291.30      7118248.92      2258251.45      7117908.09
      2258080.93      7117453.90
#Sta/Elev= 30
  4641.8  960.87  4751.5  957.58  4801.8  954.74  4821.9  956.46  4842.1  953.83
  4852.1  953.81  4862.2  952.53  4912.6  950.77  4952.8  950.81  4965.4  948.96
  4977.9  944.20  4979.4  943.81  4979.7  943.31  4983.5  943.81  5007.9  945.80
  5015.0  947.78  5038.1  950.91  5079.0  949.51  5093.3  947.90  5111.1  944.27
  5148.4  945.89  5173.3  945.54  5196.5  949.56  5208.9  953.12  5228.5  955.15
  5234.8  954.95  5344.1  962.63  5349.5  962.05  5399.3  965.58  5470.1  966.75
#Mann=5,-1,0
  4641.8    0.05       0  4977.9    0.12       0  4979.4    0.07       0
  4983.5    0.12       0  5234.8    0.05       0
Bank Sta=4979.4,4983.5
Exp/Cntr=0.3,0.1

Type RM Length L Ch R = 1,116517,492,492,492
BEGIN DESCRIPTION:
Oliver Creek 157.0
END DESCRIPTION:
XS GIS Cut Line= 3
      2258422.82      7118241.13      2258574.48      7117710.06
      2258543.95      7117374.45
#Sta/Elev= 30
  4447.7  958.00  4511.3  956.37  4542.5  956.43  4584.1  953.76  4615.3  953.50
  4625.7  954.13  4637.7  953.07  4671.5  952.73  4698.5  951.03  4792.1  947.65
  4948.1  946.76  4968.9  945.54  4981.2  943.04  4989.7  941.09  4997.0  937.59
  4997.4  937.09  5000.9  937.09  5001.2  937.59  5002.5  937.59  5005.2  942.91
  5010.2  940.83  5020.1  943.07  5040.2  944.91  5080.4  950.95  5100.5  951.47
  5180.8  956.11  5221.0  957.02  5226.0  957.84  5284.8  961.02  5337.0  962.86
#Mann=5,-1,0
  4447.7    0.05       0  4981.2    0.12       0  4997.0    0.07       0
  5001.2    0.12       0  5284.8    0.05       0
Bank Sta=4997,5001.2
Exp/Cntr=0.3,0.1

Type RM Length L Ch R = 1,116025,516,516,516
BEGIN DESCRIPTION:
Oliver Creek 156.0
END DESCRIPTION:
XS GIS Cut Line= 3
      2259079.06      7118133.08      2259029.00      7117610.00
      2258963.18      7117246.37
#Sta/Elev= 30
  4474.5  953.88  4530.2  953.44  4598.1  950.75  4608.2  949.68  4632.9  950.45
  4648.4  948.71  4799.1  944.64  4929.6  943.49  4951.1  946.06  4959.8  943.58
  4972.2  941.69  4989.9  938.34  4995.3  935.55  4995.7  935.05  4999.6  935.55
  5002.5  935.55  5020.3  939.55  5026.7  942.11  5031.8  942.28  5050.8  945.59
  5080.2  948.42  5091.4  947.54  5127.2  948.55  5203.2  953.71  5213.4  952.89
  5223.5  953.43  5264.2  957.53  5274.4  959.38  5335.3  964.75  5369.5  965.27
#Mann=5,-1,0
  4474.5    0.05       0  4972.2    0.12       0  4995.3    0.07       0
  4999.6    0.12       0  5127.2    0.05       0
Bank Sta=4995.3,4999.6
Exp/Cntr=0.3,0.1

Type RM Length L Ch R = 1,115509,341,341,341
BEGIN DESCRIPTION:
Oliver Creek 155.0
END DESCRIPTION:
XS GIS Cut Line= 3
      2259545.20      7118075.76      2259419.22      7117509.30
      2258953.40      7116851.42
#Sta/Elev= 30
  4419.7  953.22  4507.6  951.79  4528.0  952.48  4538.3  950.77  4569.0  949.32
  4732.9  944.53  4814.9  943.91  4857.3  941.78  4876.4  940.50  4896.8  941.68
  4907.1  940.60  4948.1  940.26  4975.8  938.27  4980.9  935.65  4989.0  934.19
  5004.9  933.69  5005.3  933.19  5009.3  933.69  5021.9  939.19  5079.6  941.15
  5185.6  945.73  5236.0  946.48  5293.2  948.93  5458.8  952.39  5494.5  955.23
  5595.4  956.23  5660.6  958.55  5687.7  961.19  5752.9  961.63  5806.1  963.40
#Mann=5,-1,0
  4419.7    0.05       0  4857.3    0.12       0  5004.9    0.07       0
  5009.3    0.12       0  5079.6    0.05       0
Bank Sta=5004.9,5009.3
Exp/Cntr=0.3,0.1

Type RM Length L Ch R = 1,115168,90,90,90
BEGIN DESCRIPTION:
Oliver Creek 154.0
END DESCRIPTION:
XS GIS Cut Line= 3
      2259953.26      7117762.51      2259678.79      7117394.87
      2259399.64      7116974.63
#Sta/Elev= 30
  4541.2  959.57  4568.2  957.98  4639.1  949.38  4795.1  941.10  4853.8  939.16
  4874.7  941.34  4889.3  939.44  4910.1  940.25  4924.7  937.99  4939.3  939.02
  4960.1  935.53  4968.5  936.36  4974.7  933.86  4989.3  935.02  4993.3  933.69
  4993.8  933.19  4997.8  933.69  5025.3  934.48  5031.3  937.07  5044.4  938.01
  5061.4  937.15  5118.5  937.95  5133.5  939.91  5139.5  939.02  5148.6  940.50
  5154.6  939.57  5169.6  941.64  5205.7  942.94  5378.0  946.59  5504.5  951.34
#Mann=5,-1,0
  4541.2    0.05       0  4795.1    0.12       0  4993.3    0.07       0
  4997.8    0.12       0  5044.4    0.05       0
Bank Sta=4993.3,4997.8
Exp/Cntr=0.3,0.1

Type RM Length L Ch R = 1,115078,411,411,411
BEGIN DESCRIPTION:
Oliver Creek 153.5
END DESCRIPTION:
XS GIS Cut Line= 3
      2260029.00      7117710.00      2259718.95      7117320.03
      2259420.64      7116853.44
#Sta/Elev= 30
  4501.8  959.40  4544.2  955.27  4565.7  952.63  4573.1  950.88  4723.7  942.09
  4800.5  937.51  4815.0  936.01  4835.8  937.69  4914.3  938.30  4928.7  939.23
  4943.1  935.25  4978.3  935.24  4994.5  931.77  4995.0  931.27  4999.1  931.77
  5003.0  931.77  5007.6  936.23  5013.5  936.61  5022.8  938.98  5049.9  938.94
  5122.6  941.50  5246.9  943.57  5356.0  946.41  5398.3  948.90  5462.9  950.07
  5498.5  952.43  5522.3  955.50  5534.5  955.04  5543.8  955.72  5553.8  957.95
#Mann=4,-1,0
  4501.8    0.05       0  4723.7    0.12       0  4994.5   0.033       0
  4999.1    0.05       0
Bank Sta=4994.5,4999.1
Exp/Cntr=0.3,0.1

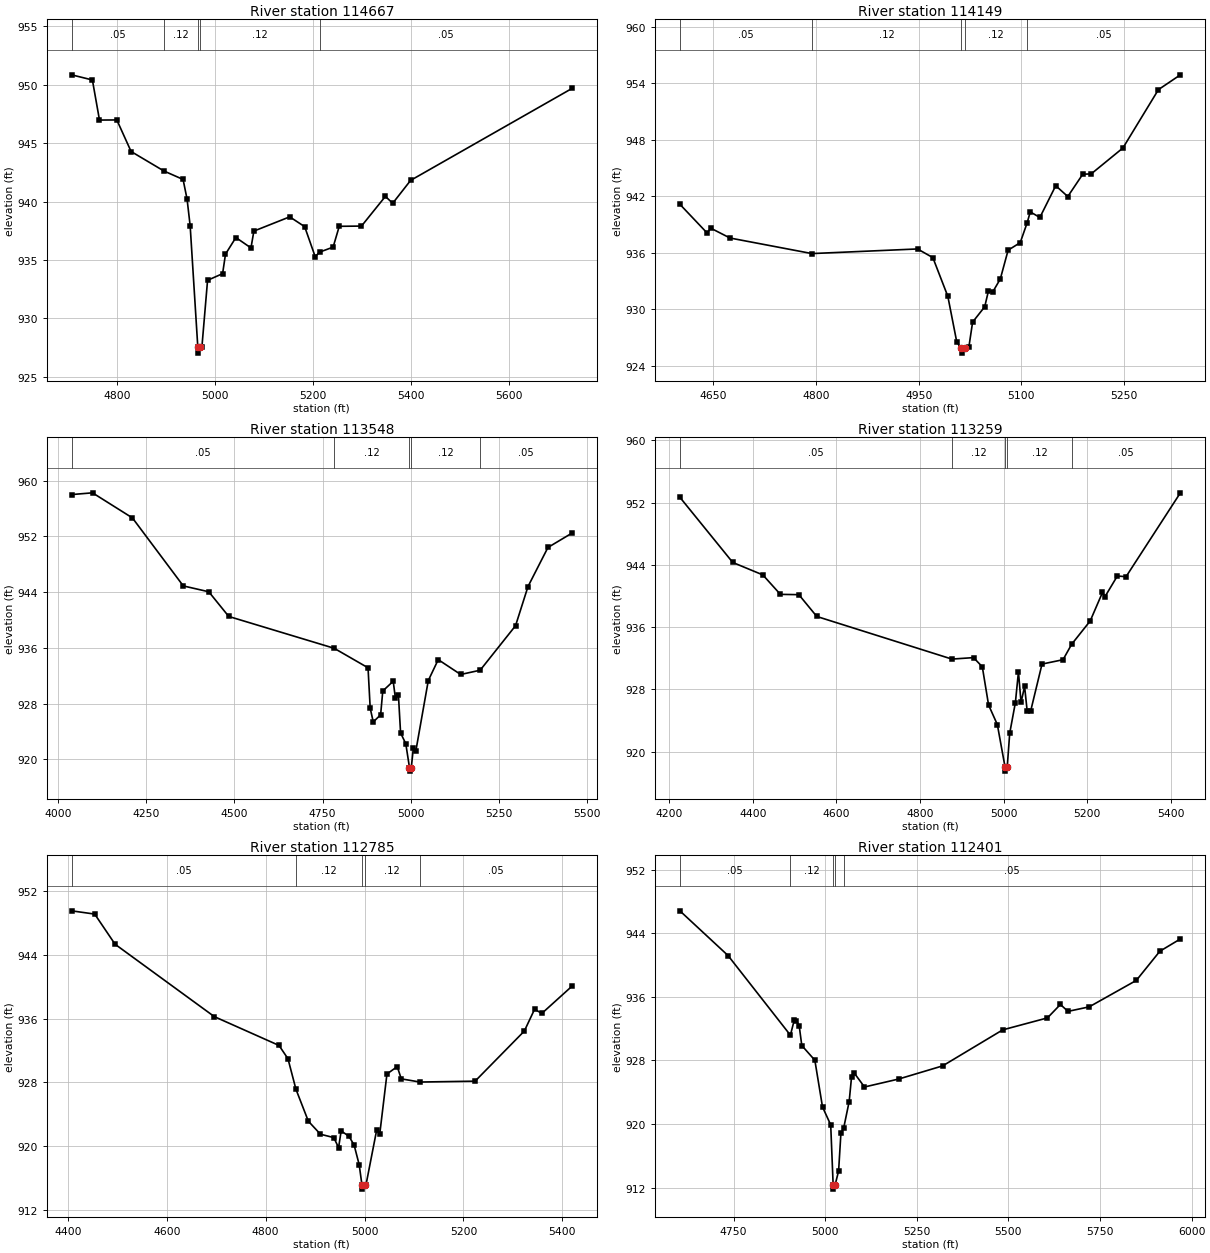
Type RM Length L Ch R = 1,114667,518,518,518
BEGIN DESCRIPTION:
Oliver Creek 153.0
END DESCRIPTION:
XS GIS Cut Line= 3
      2260218.52      7117630.33      2260060.01      7117421.60
      2259659.49      7116776.17
#Sta/Elev= 30
  4707.6  950.84  4750.1  950.40  4764.6  946.97  4800.0  946.98  4829.1  944.28
  4896.2  942.61  4935.2  941.89  4943.4  940.20  4949.7  937.91  4965.3  927.53
  4965.8  927.03  4969.9  927.53  4973.6  927.53  4985.2  933.26  5015.9  933.83
  5021.8  935.50  5043.0  936.92  5073.8  936.03  5079.7  937.47  5152.9  938.69
  5183.4  937.85  5204.9  935.28  5213.8  935.67  5241.5  936.10  5254.0  937.88
  5299.4  937.90  5348.2  940.44  5363.1  939.85  5399.7  941.81  5729.3  949.68
#Mann=5,-1,0
  4707.6    0.05       0  4896.2    0.12       0  4965.3    0.07       0
  4969.9    0.12       0  5213.8    0.05       0
Bank Sta=4965.3,4969.9
Exp/Cntr=0.3,0.1

Type RM Length L Ch R = 1,114149,601,601,601
BEGIN DESCRIPTION:
Mapping XS 9d8fd98b
END DESCRIPTION:
XS GIS Cut Line= 3
      2260220.78      7117373.07      2260244.14      7117070.89
      2260069.04      7116679.77
#Sta/Elev= 30
  4601.0  941.16  4641.0  938.10  4646.0  938.63  4674.3  937.58  4794.0  935.93
  4948.4  936.42  4970.8  935.50  4992.7  931.39  5005.7  926.57  5012.2  925.87
  5012.8  925.37  5017.1  925.87  5023.4  926.00  5028.9  928.66  5046.6  930.29
  5052.1  931.99  5058.4  931.87  5069.4  933.24  5080.8  936.29  5098.5  937.09
  5108.5  939.17  5113.2  940.35  5127.2  939.76  5150.4  943.13  5168.0  941.98
  5189.9  944.35  5202.2  944.38  5248.6  947.13  5300.5  953.32  5332.6  954.89
#Mann=5,-1,0
  4601.0    0.05       0  4794.0    0.12       0  5012.2    0.07       0
  5017.1    0.12       0  5108.5    0.05       0
Bank Sta=5012.2,5017.1
Exp/Cntr=0.3,0.1

Type RM Length L Ch R = 1,113548,289,289,289
BEGIN DESCRIPTION:
Oliver Creek 151.0
END DESCRIPTION:
XS GIS Cut Line= 3
      2261161.75      7117568.66      2260605.98      7116783.57
      2260284.15      7116457.98
#Sta/Elev= 30
  4038.1  957.99  4097.5  958.24  4210.7  954.64  4355.0  944.88  4427.3  944.04
  4483.9  940.50  4783.0  935.93  4879.0  933.13  4885.1  927.34  4893.8  925.36
  4914.7  926.38  4920.8  929.80  4950.4  931.20  4956.5  928.82  4965.2  929.22
  4971.3  923.79  4986.1  922.23  4996.6  918.80  4997.2  918.30  5001.7  918.80
  5007.4  921.57  5014.5  921.17  5049.9  931.30  5078.1  934.30  5141.8  932.17
  5197.0  932.78  5297.4  939.17  5332.7  944.79  5389.3  950.40  5457.8  952.47
#Mann=5,-1,0
  4038.1    0.05       0  4783.0    0.12       0  4996.6    0.07       0
  5001.7    0.12       0  5197.0    0.05       0
Bank Sta=4996.6,5001.7
Exp/Cntr=0.3,0.1

Type RM Length L Ch R = 1,113259,474,474,474
BEGIN DESCRIPTION:
Oliver Creek 150.0
END DESCRIPTION:
XS GIS Cut Line= 3
      2261226.83      7117236.59      2260795.55      7116593.04
      2260547.40      7116250.11
#Sta/Elev= 30
  4225.3  952.70  4351.9  944.32  4423.9  942.72  4465.9  940.22  4510.1  940.18
  4553.0  937.38  4876.5  931.90  4928.2  932.09  4949.2  930.91  4964.2  926.00
  4985.2  923.48  5003.7  918.00  5004.4  917.50  5008.8  918.00  5014.8  922.37
  5028.4  926.32  5035.7  930.26  5041.9  926.33  5050.4  928.38  5056.6  925.22
  5065.1  925.26  5092.1  931.26  5142.4  931.82  5163.1  933.81  5207.4  936.80
  5236.8  940.46  5243.0  939.94  5272.4  942.58  5293.2  942.49  5423.3  953.27
#Mann=5,-1,0
  4225.3    0.05       0  4876.5    0.12       0  5003.7    0.07       0
  5008.8    0.12       0  5163.1    0.05       0
Bank Sta=5003.7,5008.8
Exp/Cntr=0.3,0.1

Type RM Length L Ch R = 1,112785,384,384,384
BEGIN DESCRIPTION:
Oliver Creek 149.0
END DESCRIPTION:
XS GIS Cut Line= 3
      2261381.79      7117085.53      2261242.82      7116509.56
      2260985.53      7116177.72
#Sta/Elev= 30
  4407.5  949.55  4454.3  949.14  4495.5  945.35  4696.3  936.25  4827.1  932.63
  4845.2  930.96  4861.3  927.13  4886.4  923.11  4910.9  921.47  4937.8  921.05
  4947.6  919.79  4952.8  921.89  4968.7  921.20  4979.0  920.11  4989.3  917.63
  4994.9  915.07  4995.6  914.57  5000.0  915.07  5002.9  915.07  5024.6  921.99
  5030.9  921.53  5045.4  929.04  5066.2  929.97  5074.4  928.43  5112.1  928.03
  5223.7  928.14  5323.3  934.44  5344.1  937.19  5358.6  936.65  5419.9  940.09
#Mann=5,-1,0
  4407.5    0.05       0  4861.3    0.12       0  4994.9    0.07       0
  5000.0    0.12       0  5112.1    0.05       0
Bank Sta=4994.9,5000
Exp/Cntr=0.3,0.1

Type RM Length L Ch R = 1,112401,676,676,676
BEGIN DESCRIPTION:
Oliver Creek 148.0
END DESCRIPTION:
XS GIS Cut Line= 3
      2261808.45      7116784.80      2261562.52      7116441.46
      2260983.23      7115696.02
#Sta/Elev= 30
  4603.2  946.84  4734.7  941.21  4905.0  931.18  4915.2  933.04  4921.4  932.98
  4928.9  932.39  4936.1  929.88  4971.7  928.03  4992.6  922.15  5015.0  919.89
  5021.7  912.30  5022.4  911.80  5026.9  912.30  5036.6  914.10  5042.9  918.87
  5050.4  919.49  5065.4  922.83  5071.9  925.93  5078.2  926.48  5107.2  924.66
  5200.4  925.66  5320.7  927.32  5484.5  931.85  5606.7  933.36  5642.0  935.05
  5662.8  934.18  5720.7  934.75  5849.3  938.08  5913.5  941.75  5969.6  943.30
#Mann=5,-1,0
  4603.2    0.05       0  4905.0    0.12       0  5021.7    0.07       0
  5026.9    0.12       0  5050.4    0.05       0
Bank Sta=5021.7,5026.9
Exp/Cntr=0.3,0.1