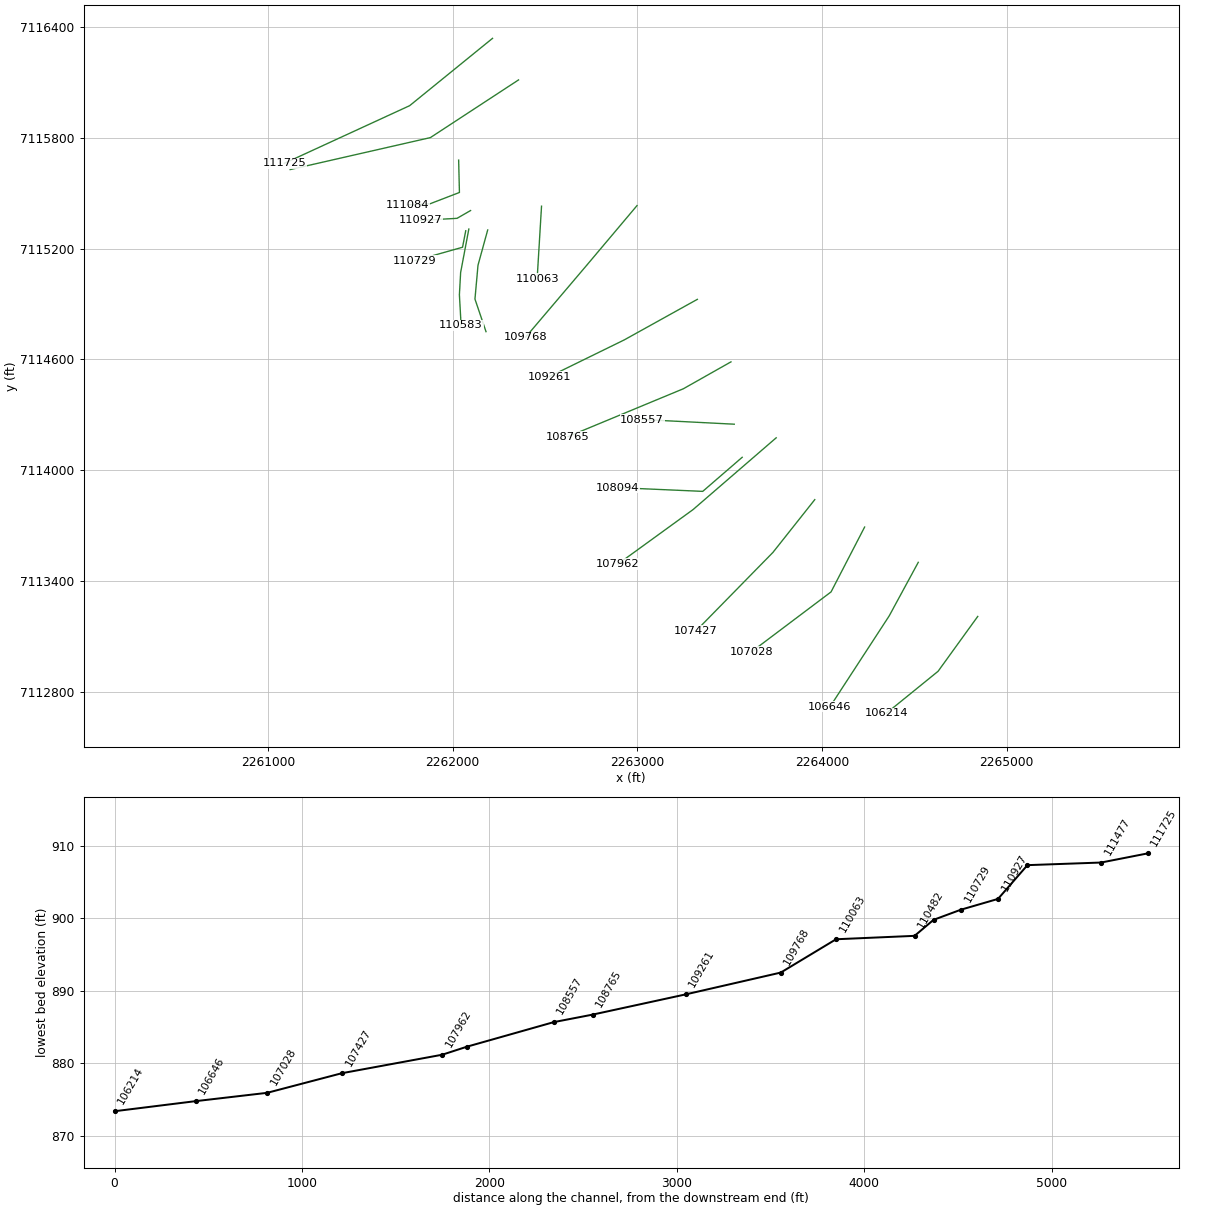
HEC-RAS study Oliver Creek.prj: Oliver Creek Base Level Engineering

--- Oliver Creek.g01 (geometry) --- (continued)

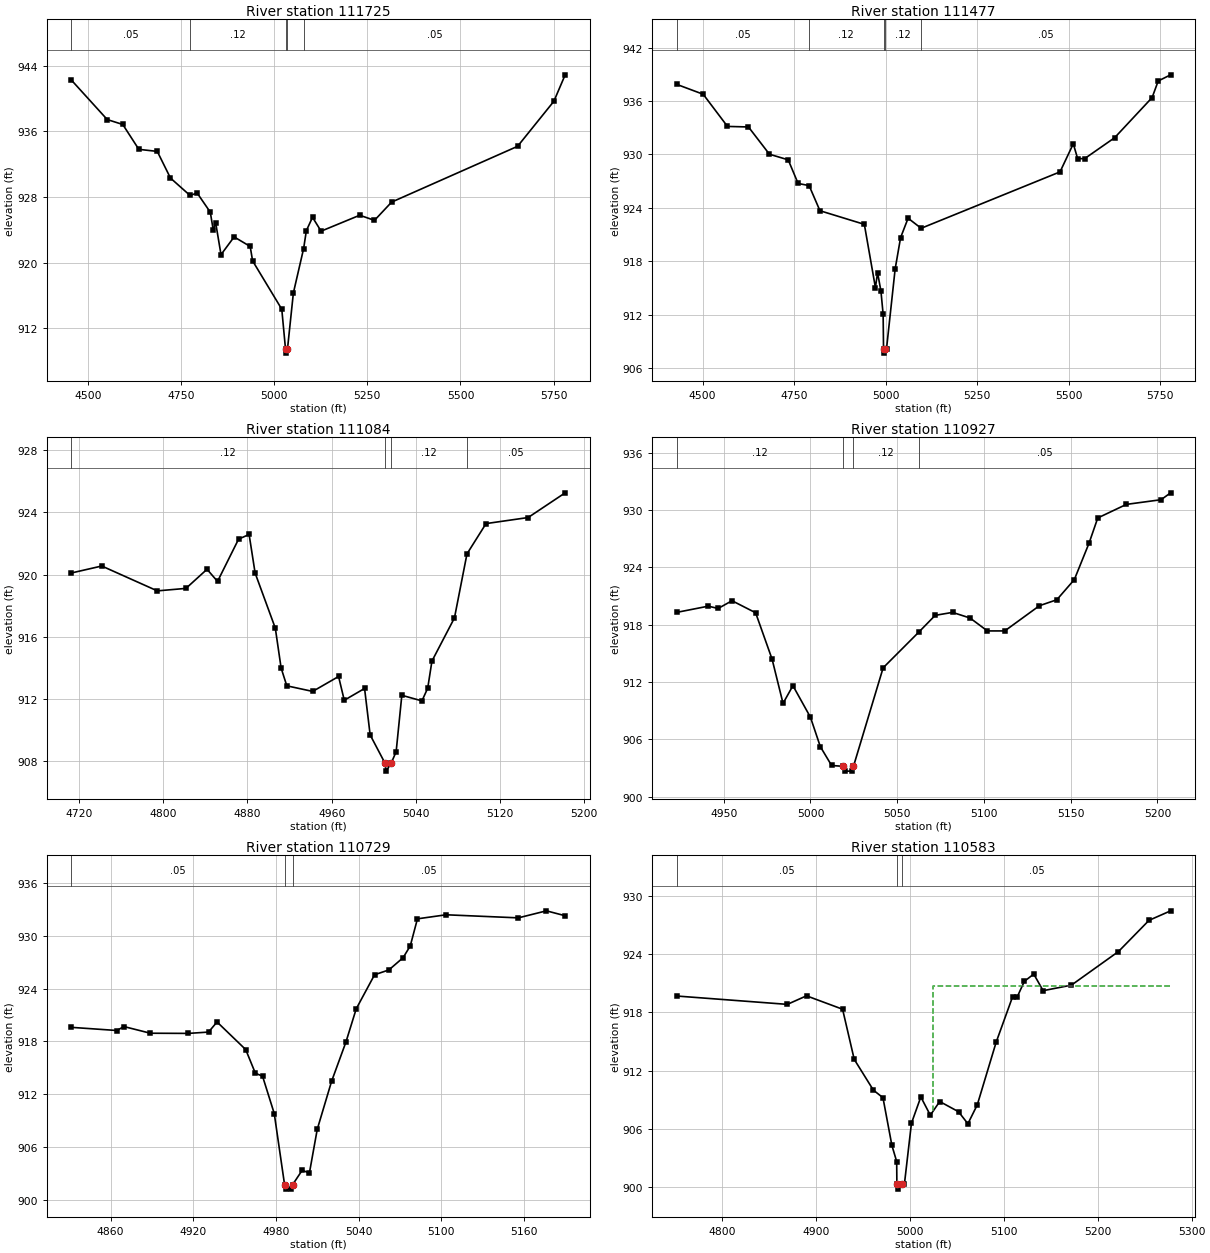
Type RM Length L Ch R = 1,111725,248,248,248
BEGIN DESCRIPTION:
Oliver Creek 147.0
END DESCRIPTION:
XS GIS Cut Line= 3
      2262215.68      7116338.65      2261766.61      7115973.86
      2261088.09      7115661.57
#Sta/Elev= 30
  4455.5  942.26  4552.1  937.43  4593.8  936.83  4636.9  933.80  4686.4  933.55
  4721.8  930.30  4774.1  928.19  4793.5  928.47  4828.7  926.14  4836.6  923.96
  4843.1  924.86  4857.4  920.97  4892.6  923.13  4935.7  921.97  4942.2  920.21
  5020.5  914.32  5030.5  909.47  5031.3  908.97  5035.8  909.47  5051.6  916.30
  5079.1  921.71  5086.5  923.90  5103.0  925.52  5126.0  923.83  5229.6  925.77
  5269.3  925.15  5315.2  927.37  5653.3  934.17  5750.7  939.66  5781.0  942.88
#Mann=5,-1,0
  4455.5    0.05       0  4774.1    0.12       0  5030.5    0.07       0
  5035.8    0.12       0  5079.1    0.05       0
Bank Sta=5030.5,5035.8
Exp/Cntr=0.3,0.1

Type RM Length L Ch R = 1,111477,393,393,393
BEGIN DESCRIPTION:
Oliver Creek 146.0
END DESCRIPTION:
XS GIS Cut Line= 3
      2262356.53      7116113.40      2261878.90      7115800.87
      2261119.79      7115627.72
#Sta/Elev= 30
  4429.2  937.87  4501.6  936.76  4568.0  933.15  4625.3  933.09  4682.6  930.03
  4733.9  929.40  4760.9  926.75  4791.0  926.51  4820.6  923.69  4941.9  922.16
  4972.1  915.07  4978.1  916.73  4987.2  914.67  4993.2  912.08  4994.3  908.21
  4995.1  907.71  4999.6  908.21  5002.5  908.21  5026.0  917.14  5040.9  920.67
  5061.4  922.85  5097.1  921.72  5476.5  928.05  5512.7  931.20  5524.6  929.54
  5543.5  929.53  5625.6  931.88  5728.1  936.39  5744.7  938.25  5778.6  938.94
#Mann=5,-1,0
  4429.2    0.05       0  4791.0    0.12       0  4994.3    0.07       0
  4999.6    0.12       0  5097.1    0.05       0
Bank Sta=4994.3,4999.6
Exp/Cntr=0.3,0.1

Type RM Length L Ch R = 1,111084,157,157,157
BEGIN DESCRIPTION:
Mapping XS 2a478d9e
END DESCRIPTION:
XS GIS Cut Line= 4
      2262032.10      7115678.99      2262036.29      7115503.69
      2261876.51      7115442.25      2261753.88      7115436.53
#Sta/Elev= 30
  4712.6  920.10  4741.6  920.55  4794.4  918.95  4821.6  919.11  4841.6  920.34
  4851.6  919.56  4871.6  922.28  4881.6  922.58  4887.3  920.10  4906.5  916.55
  4912.0  913.99  4917.4  912.84  4942.0  912.48  4966.6  913.44  4972.0  911.91
  4991.3  912.67  4996.6  909.68  5010.8  907.85  5011.7  907.35  5016.5  907.85
  5021.3  908.60  5026.7  912.23  5045.8  911.87  5051.3  912.69  5055.3  914.43
  5076.7  917.21  5088.6  921.33  5106.7  923.28  5146.7  923.67  5181.9  925.26
#Mann=4,-1,0
  4712.6    0.12       0  5010.8    0.07       0  5016.5    0.12       0
  5088.6    0.05       0
Bank Sta=5010.8,5016.5
Exp/Cntr=0.3,0.1

Type RM Length L Ch R = 1,110927,198,198,198
BEGIN DESCRIPTION:
Mapping XS 3793d2da
END DESCRIPTION:
XS GIS Cut Line= 3
      2262096.66      7115405.82      2262023.34      7115363.63
      2261823.54      7115352.60
#Sta/Elev= 30
  4922.9  919.30  4941.1  919.95  4946.8  919.71  4954.8  920.52  4968.4  919.26
  4977.9  914.40  4984.2  909.78  4989.9  911.63  5000.0  908.33  5005.7  905.25
  5012.2  903.28  5019.0  903.19  5019.9  902.69  5023.8  902.69  5024.8  903.19
  5041.9  913.50  5062.7  917.28  5071.9  918.99  5081.9  919.30  5092.0  918.71
  5102.0  917.36  5112.0  917.36  5132.0  920.00  5142.0  920.62  5152.1  922.73
  5160.6  926.55  5165.6  929.18  5182.1  930.60  5202.1  931.09  5207.6  931.81
#Mann=4,-1,0
  4922.9    0.12       0  5019.0    0.07       0  5024.8    0.12       0
  5062.7    0.05       0
Bank Sta=5019,5024.8
Exp/Cntr=0.3,0.1

Type RM Length L Ch R = 1,110729,146,146,146
BEGIN DESCRIPTION:
Mapping XS c0760606
END DESCRIPTION:
XS GIS Cut Line= 3
      2262070.51      7115296.40      2262053.22      7115207.04
      2261795.87      7115134.47
#Sta/Elev= 30
  4831.4  919.60  4864.5  919.24  4869.6  919.69  4888.8  918.93  4916.3  918.91
  4931.0  919.06  4937.2  920.21  4958.0  917.07  4965.0  914.38  4970.2  914.05
  4978.7  909.80  4986.2  901.70  4987.2  901.20  4991.1  901.20  4992.0  901.70
  4999.0  903.35  5004.2  903.02  5009.9  908.00  5020.3  913.46  5030.7  917.92
  5038.2  921.71  5051.5  925.58  5061.9  926.13  5072.2  927.52  5077.4  928.86
  5082.6  931.94  5103.4  932.40  5155.8  932.05  5176.2  932.85  5189.8  932.29
#Mann=3,-1,0
  4831.4    0.05       0  4986.2   0.033       0  4992.0    0.05       0
Bank Sta=4986.2,4992
Exp/Cntr=0.3,0.1

Type RM Length L Ch R = 1,110583,101,101,101
BEGIN DESCRIPTION:
Mapping XS c726b46f
END DESCRIPTION:
XS GIS Cut Line= 4
      2262087.23      7115305.77      2262042.83      7115070.09
      2262036.17      7114950.08      2262045.42      7114784.55
#Sta/Elev= 30
  4751.8  919.68  4869.6  918.82  4890.0  919.70  4928.4  918.32  4940.8  913.16
  4961.2  909.99  4971.4  909.21  4980.9  904.30  4986.0  902.64  4986.2  900.30
  4987.2  899.80  4992.0  900.30  4994.2  900.30  5001.7  906.58  5011.7  909.29
  5021.8  907.41  5031.8  908.82  5051.8  907.77  5061.8  906.53  5071.8  908.48
  5091.9  914.93  5109.4  919.61  5114.4  919.61  5121.9  921.19  5131.9  921.94
  5141.9  920.23  5172.0  920.80  5222.1  924.26  5254.6  927.47  5277.6  928.45
#Mann=3,-1,0
  4751.8    0.05       0  4986.2   0.033       0  4992.0    0.05       0
#XS Ineff=2,0
       0                 5024.70    0.00  920.66
Permanent Ineff=
       F       F
Bank Sta=4986.2,4992
Exp/Cntr=0.3,0.1

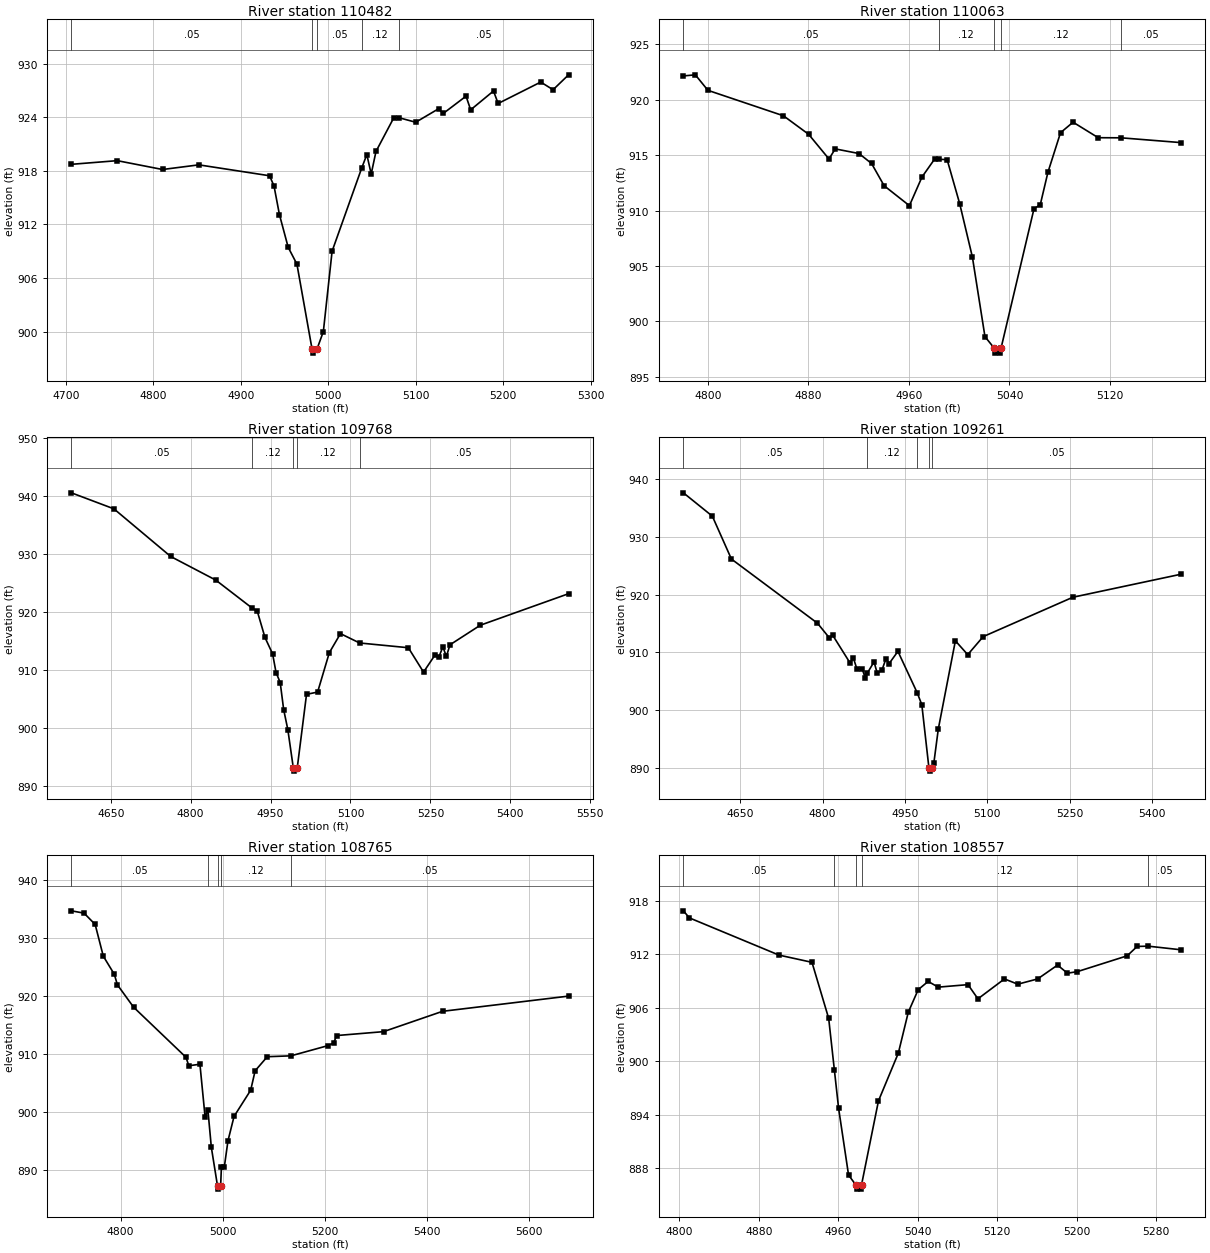
Type RM Length L Ch R = 1,110482,419,419,419
BEGIN DESCRIPTION:
Mapping XS dda2bb3b
END DESCRIPTION:
XS GIS Cut Line= 4
      2262189.42      7115300.52      2262136.87      7115109.39
      2262120.44      7114926.24      2262180.25      7114749.91
#Sta/Elev= 30
  4706.5  918.73  4758.9  919.14  4810.7  918.15  4852.2  918.67  4933.0  917.45
  4938.1  916.31  4944.3  913.10  4954.3  909.44  4964.3  907.55  4981.5  898.09
  4982.4  897.59  4987.4  898.09  4994.5  900.00  5004.5  909.00  5038.3  918.30
  5044.2  919.82  5049.2  917.65  5054.7  920.18  5074.8  923.90  5080.5  923.96
  5100.1  923.44  5126.2  924.95  5131.5  924.42  5157.6  926.36  5162.9  924.83
  5189.0  926.94  5194.3  925.54  5243.0  927.94  5257.1  927.08  5274.8  928.75
#Mann=5,-1,0
  4706.5    0.05       0  4981.5   0.033       0  4987.4    0.05       0
  5038.3    0.12       0  5080.5    0.05       0
Bank Sta=4981.5,4987.4
Exp/Cntr=0.3,0.1

Type RM Length L Ch R = 1,110063,295,295,295
BEGIN DESCRIPTION:
Mapping XS f04c8b05
END DESCRIPTION:
XS GIS Cut Line= 2
      2262481.05      7115429.44      2262457.20      7115034.66
#Sta/Elev= 30
  4780.6  922.16  4790.1  922.26  4800.1  920.86  4860.2  918.56  4880.2  916.89
  4896.4  914.66  4901.4  915.57  4920.3  915.15  4930.3  914.25  4940.3  912.24
  4960.4  910.44  4970.4  913.03  4980.4  914.64  4983.6  914.63  4990.4  914.60
  5000.4  910.62  5010.5  905.80  5020.5  898.61  5027.5  897.62  5028.5  897.12
  5032.5  897.12  5033.4  897.62  5059.5  910.16  5064.5  910.53  5070.6  913.46
  5080.6  917.03  5090.6  917.98  5110.6  916.58  5128.8  916.57  5176.1  916.14
#Mann=5,-1,0
  4780.6    0.05       0  4983.6    0.12       0  5027.5    0.07       0
  5033.4    0.12       0  5128.8    0.05       0
Bank Sta=5027.5,5033.4
Exp/Cntr=0.3,0.1

Type RM Length L Ch R = 1,109768,507,507,507
BEGIN DESCRIPTION:
Oliver Creek 142.0
END DESCRIPTION:
XS GIS Cut Line= 3
      2262998.23      7115432.63      2262725.11      7115108.57
      2262395.39      7114720.41
#Sta/Elev= 30
  4576.2  940.47  4656.0  937.71  4762.6  929.50  4847.1  925.44  4914.3  920.69
  4925.2  920.04  4939.5  915.55  4953.8  912.73  4960.3  909.51  4968.1  907.78
  4974.6  903.12  4982.4  899.68  4992.8  893.02  4993.8  892.52  4998.7  893.02
  5000.0  893.02  5017.5  905.75  5038.3  906.14  5060.3  912.93  5081.2  916.21
  5117.1  914.60  5208.6  913.78  5237.1  909.58  5259.1  912.59  5265.7  912.15
  5273.4  913.92  5280.0  912.29  5286.8  914.29  5343.7  917.66  5509.3  923.09
#Mann=5,-1,0
  4576.2    0.05       0  4914.3    0.12       0  4992.8    0.07       0
  4998.7    0.12       0  5117.1    0.05       0
Bank Sta=4992.8,4998.7
Exp/Cntr=0.3,0.1

Type RM Length L Ch R = 1,109261,496,496,496
BEGIN DESCRIPTION:
Oliver Creek 141.0
END DESCRIPTION:
XS GIS Cut Line= 3
      2263325.05      7114924.81      2262928.51      7114704.77
      2262522.84      7114506.11
#Sta/Elev= 30
  4546.5  937.56  4599.2  933.53  4633.9  926.13  4790.6  915.05  4812.4  912.50
  4818.1  913.01  4850.1  908.16  4855.9  909.07  4862.2  907.21  4871.9  907.17
  4877.6  905.64  4881.1  906.39  4893.6  908.37  4899.4  906.44  4907.9  906.93
  4915.4  908.93  4921.1  908.09  4937.1  910.19  4972.1  903.06  4980.6  900.98
  4993.6  890.01  4994.6  889.51  4999.6  890.01  5002.5  890.91  5010.6  896.77
  5041.7  912.01  5064.2  909.62  5092.3  912.73  5255.6  919.53  5451.7  923.49
#Mann=5,-1,0
  4546.5    0.05       0  4881.1    0.12       0  4972.1    0.05       0
  4993.6   0.033       0  4999.6    0.05       0
Bank Sta=4993.6,4999.6
Exp/Cntr=0.3,0.1

Type RM Length L Ch R = 1,108765,208,208,208
BEGIN DESCRIPTION:
Oliver Creek 140.0
END DESCRIPTION:
XS GIS Cut Line= 3
      2263507.33      7114586.25      2263249.55      7114440.56
      2262624.49      7114181.30
#Sta/Elev= 30
  4703.9  934.72  4728.7  934.32  4750.4  932.37  4766.3  926.90  4787.9  923.77
  4793.9  921.96  4825.5  918.11  4928.0  909.47  4933.7  908.00  4955.4  908.26
  4965.5  899.16  4971.0  900.37  4977.7  893.94  4989.9  887.22  4990.9  886.72
  4995.9  887.22  4997.4  890.48  5003.0  890.48  5010.3  895.07  5022.2  899.27
  5054.7  903.78  5063.4  907.13  5087.2  909.56  5133.5  909.71  5206.3  911.48
  5217.1  911.94  5222.9  913.21  5314.6  913.88  5430.2  917.39  5676.7  920.01
#Mann=5,-1,0
  4703.9    0.05       0  4971.0    0.12       0  4989.9    0.07       0
  4995.9    0.12       0  5133.5    0.05       0
Bank Sta=4989.9,4995.9
Exp/Cntr=0.3,0.1

Type RM Length L Ch R = 1,108557,463,463,463
BEGIN DESCRIPTION:
Mapping XS bd38b2d8
END DESCRIPTION:
XS GIS Cut Line= 2
      2263525.03      7114248.52      2263025.38      7114273.91
#Sta/Elev= 30
  4804.1  916.86  4810.1  916.07  4900.3  911.90  4933.5  911.09  4950.3  904.81
  4956.0  899.06  4960.3  894.72  4970.3  887.26  4977.4  886.18  4978.4  885.68
  4982.4  885.68  4983.4  886.18  5000.4  895.57  5020.4  900.92  5030.4  905.50
  5040.4  908.03  5050.4  908.95  5060.5  908.31  5090.5  908.59  5100.5  907.00
  5127.2  909.23  5140.6  908.64  5160.6  909.23  5180.6  910.78  5190.6  909.87
  5200.6  910.05  5250.7  911.82  5260.7  912.87  5271.9  912.90  5304.4  912.50
#Mann=5,-1,0
  4804.1    0.05       0  4956.0    0.12       0  4977.4    0.07       0
  4983.4    0.12       0  5271.9    0.05       0
Bank Sta=4977.4,4983.4
Exp/Cntr=0.3,0.1

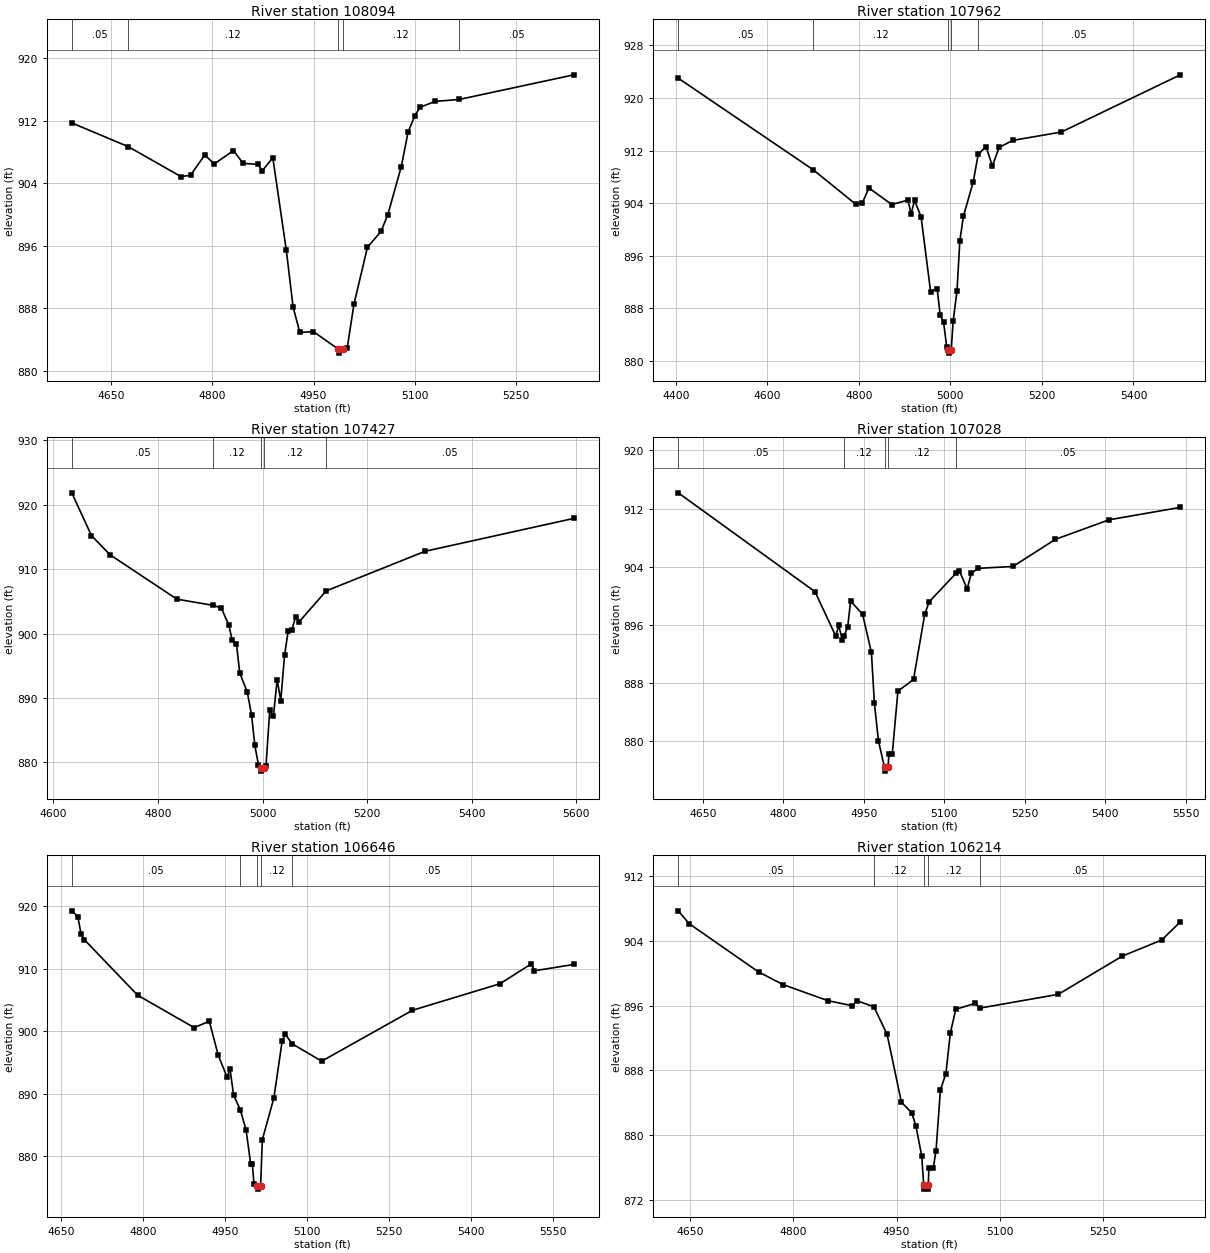
Type RM Length L Ch R = 1,108094,132,132,132
BEGIN DESCRIPTION:
Mapping XS 42a72dc0
END DESCRIPTION:
XS GIS Cut Line= 3
      2263567.92      7114069.14      2263354.25      7113884.63
      2262893.81      7113904.91
#Sta/Elev= 30
  4592.0  911.74  4675.7  908.70  4753.5  904.88  4767.8  905.04  4788.8  907.64
  4802.9  906.49  4831.4  908.20  4845.7  906.56  4867.6  906.44  4874.0  905.62
  4889.6  907.29  4909.6  895.44  4919.6  888.21  4929.6  884.93  4949.6  885.05
  4986.6  882.79  4987.6  882.29  4992.8  882.79  4999.7  882.92  5009.7  888.55
  5029.7  895.83  5049.7  897.85  5059.7  899.96  5079.8  906.16  5089.8  910.56
  5099.8  912.66  5107.4  913.73  5129.8  914.49  5165.6  914.74  5335.2  917.89
#Mann=5,-1,0
  4592.0    0.05       0  4675.7    0.12       0  4986.6    0.07       0
  4992.8    0.12       0  5165.6    0.05       0
Bank Sta=4986.6,4992.8
Exp/Cntr=0.3,0.1

Type RM Length L Ch R = 1,107962,535,535,535
BEGIN DESCRIPTION:
Oliver Creek 138.0
END DESCRIPTION:
XS GIS Cut Line= 3
      2263752.09      7114174.77      2263302.05      7113786.16
      2262895.35      7113491.21
#Sta/Elev= 30
  4405.4  923.00  4700.4  909.06  4793.4  903.82  4807.7  904.02  4821.9  906.31
  4871.9  903.78  4907.5  904.46  4914.1  902.31  4921.7  904.42  4936.0  901.90
  4956.8  890.55  4971.1  890.99  4977.7  886.99  4985.3  885.84  4992.0  882.09
  4995.6  881.68  4996.6  881.18  5001.9  881.68  5006.0  886.03  5014.5  890.65
  5020.7  898.28  5028.5  901.99  5050.0  907.25  5060.8  911.41  5077.9  912.60
  5091.8  909.64  5106.5  912.46  5135.9  913.53  5242.5  914.81  5502.4  923.51
#Mann=5,-1,0
  4405.4    0.05       0  4700.4    0.12       0  4995.6    0.07       0
  5001.9    0.12       0  5060.8    0.05       0
Bank Sta=4995.6,5001.9
Exp/Cntr=0.3,0.1

Type RM Length L Ch R = 1,107427,399,399,399
BEGIN DESCRIPTION:
Oliver Creek 137.0
END DESCRIPTION:
XS GIS Cut Line= 3
      2263961.06      7113839.78      2263734.45      7113553.91
      2263317.88      7113128.91
#Sta/Elev= 30
  4635.2  921.86  4672.8  915.23  4708.0  912.26  4836.2  905.34  4905.6  904.38
  4921.1  903.97  4935.6  901.29  4941.9  898.95  4950.0  898.43  4956.4  893.88
  4970.8  890.90  4978.9  887.36  4985.2  882.63  4992.2  879.56  4996.1  879.13
  4997.2  878.63  5002.5  879.13  5006.6  879.50  5013.7  888.13  5020.7  887.12
  5027.8  892.82  5034.8  889.60  5042.0  896.63  5049.0  900.41  5056.1  900.58
  5063.1  902.60  5070.3  901.86  5121.7  906.63  5310.7  912.78  5595.1  917.89
#Mann=5,-1,0
  4635.2    0.05       0  4905.6    0.12       0  4996.1    0.07       0
  5002.5    0.12       0  5121.7    0.05       0
Bank Sta=4996.1,5002.5
Exp/Cntr=0.3,0.1

Type RM Length L Ch R = 1,107028,382,382,382
BEGIN DESCRIPTION:
Oliver Creek 136.0
END DESCRIPTION:
XS GIS Cut Line= 3
      2264231.19      7113691.38      2264049.34      7113340.05
      2263617.85      7113015.20
#Sta/Elev= 30
  4604.4  914.18  4859.3  900.59  4898.0  894.48  4903.6  895.97  4910.0  893.96
  4913.3  894.53  4920.1  895.69  4925.7  899.29  4947.9  897.51  4964.4  892.23
  4970.0  885.25  4977.5  880.09  4988.9  876.42  4990.0  875.92  4995.3  876.42
  4997.2  878.31  5003.3  878.31  5013.8  886.91  5042.9  888.52  5063.8  897.50
  5072.1  899.20  5122.2  903.13  5128.3  903.46  5142.9  900.97  5150.6  903.14
  5163.7  903.80  5228.3  904.06  5307.4  907.79  5407.3  910.47  5540.1  912.18
#Mann=5,-1,0
  4604.4    0.05       0  4913.3    0.12       0  4988.9    0.07       0
  4995.3    0.12       0  5122.2    0.05       0
Bank Sta=4988.9,4995.3
Exp/Cntr=0.3,0.1

Type RM Length L Ch R = 1,106646,432,432,432
BEGIN DESCRIPTION:
Oliver Creek 135.0
END DESCRIPTION:
XS GIS Cut Line= 3
      2264521.75      7113500.28      2264364.20      7113209.97
      2264043.07      7112717.17
#Sta/Elev= 30
  4669.7  919.25  4680.8  918.34  4686.5  915.61  4692.8  914.63  4790.1  905.77
  4893.7  900.58  4921.3  901.61  4937.5  896.20  4953.6  892.71  4959.3  893.94
  4965.8  889.75  4977.9  887.48  4988.6  884.23  4997.1  878.74  5000.0  878.74
  5003.1  875.59  5008.6  875.27  5009.7  874.77  5015.2  875.27  5018.3  882.67
  5039.4  889.33  5054.5  898.38  5060.5  899.50  5073.0  897.99  5126.9  895.22
  5292.9  903.35  5452.9  907.59  5510.2  910.76  5516.2  909.67  5588.2  910.68
#Mann=5,-1,0
  4669.7    0.05       0  4977.9    0.12       0  5008.6    0.07       0
  5015.2    0.12       0  5073.0    0.05       0
Bank Sta=5008.6,5015.2
Exp/Cntr=0.3,0.1

Type RM Length L Ch R = 1,106214,461,461,461
BEGIN DESCRIPTION:
Oliver Creek 134.0
END DESCRIPTION:
XS GIS Cut Line= 3
      2264844.00      7113207.28      2264628.98      7112909.98
      2264348.11      7112682.09
#Sta/Elev= 30
  4633.1  907.67  4649.2  906.07  4749.8  900.13  4785.3  898.58  4850.3  896.60
  4885.9  895.97  4892.1  896.61  4917.1  895.84  4936.2  892.44  4957.0  884.08
  4971.8  882.81  4977.9  881.21  4986.5  877.42  4989.3  873.88  4990.4  873.38
  4994.9  873.38  4995.9  873.88  4996.9  875.98  5003.2  875.98  5007.2  878.12
  5013.6  885.62  5021.5  887.60  5028.0  892.62  5035.9  895.54  5064.4  896.28
  5070.5  895.68  5184.6  897.38  5277.3  902.08  5334.8  904.08  5361.7  906.31
#Mann=5,-1,0
  4633.1    0.05       0  4917.1    0.12       0  4989.3    0.07       0
  4995.9    0.12       0  5070.5    0.05       0
Bank Sta=4989.3,4995.9
Exp/Cntr=0.3,0.1