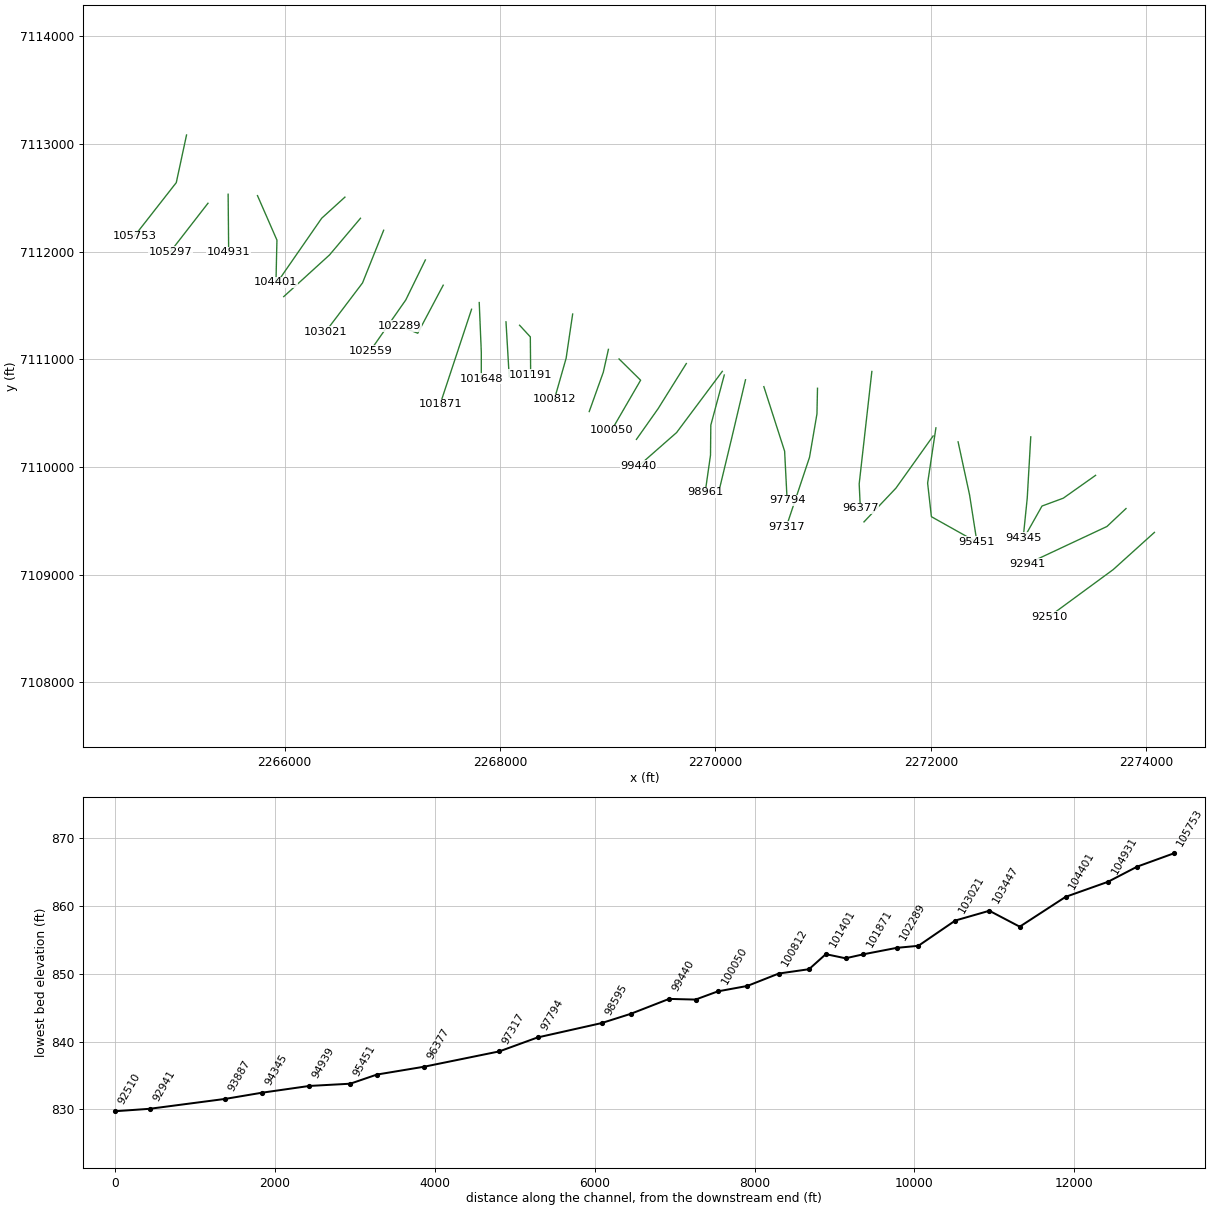
HEC-RAS study Oliver Creek.prj: Oliver Creek Base Level Engineering

--- Oliver Creek.g01 (geometry) --- (continued)

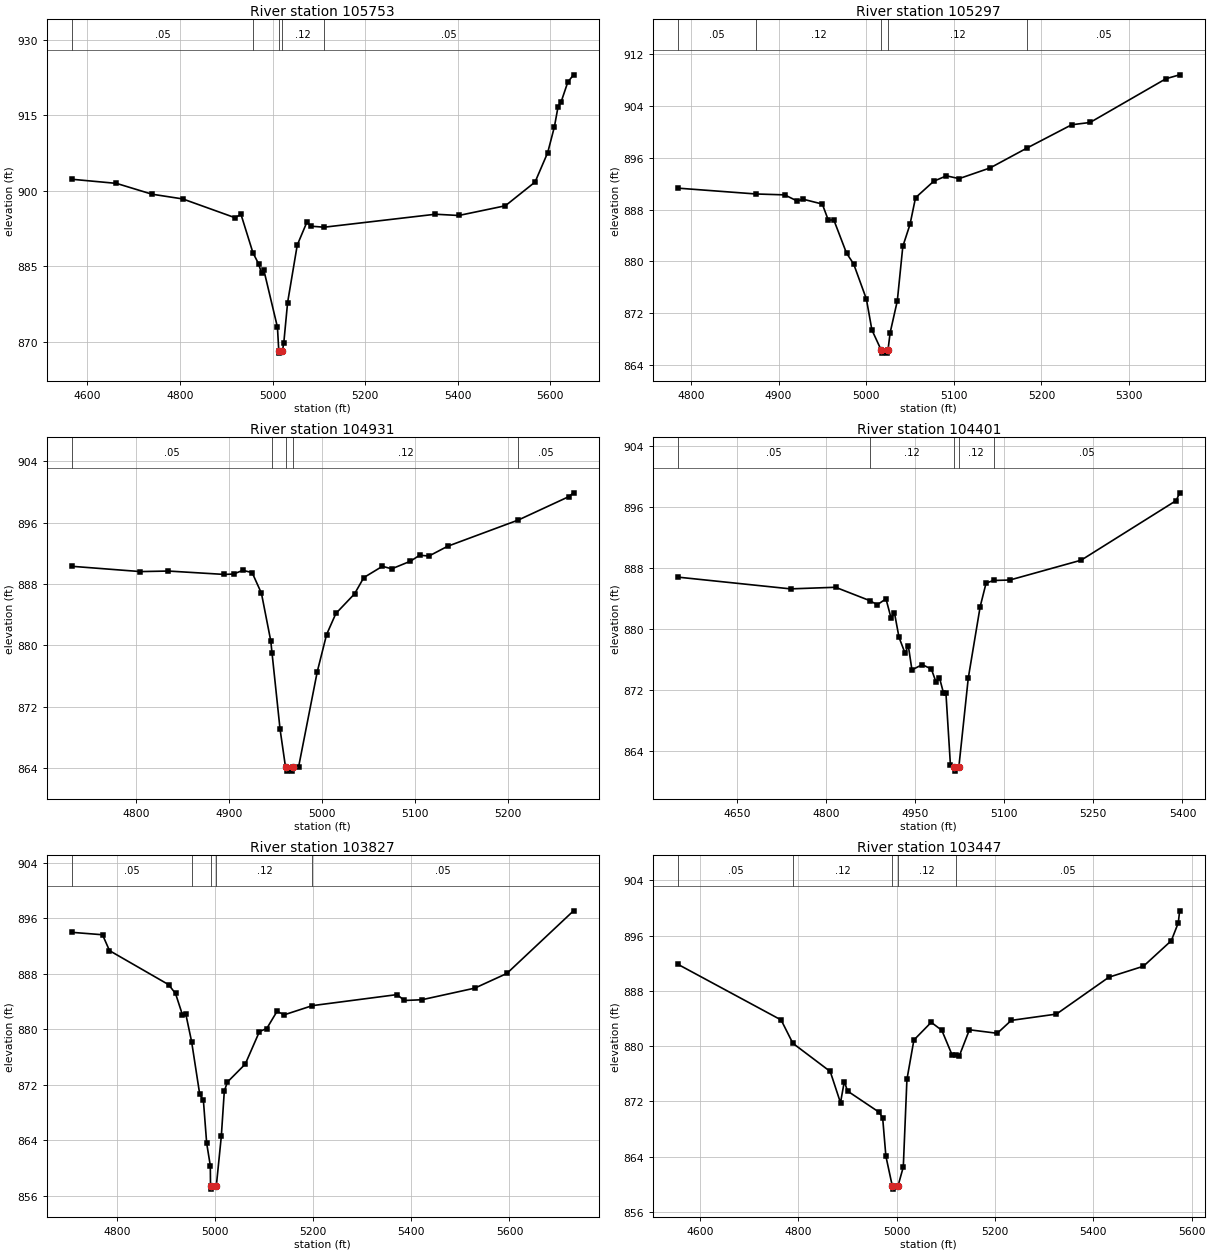
Type RM Length L Ch R = 1,105753,456,456,456
BEGIN DESCRIPTION:
Oliver Creek 133.0
END DESCRIPTION:
XS GIS Cut Line= 3
      2265090.40      7113084.31      2264995.31      7112641.92
      2264606.63      7112144.82
#Sta/Elev= 30
  4566.5  902.32  4663.0  901.50  4739.7  899.35  4806.2  898.41  4918.7  894.69
  4932.0  895.32  4957.8  887.70  4969.8  885.55  4976.3  883.65  4981.4  884.23
  5010.7  872.91  5013.5  868.27  5014.7  867.77  5021.4  868.27  5024.4  869.84
  5032.6  877.82  5053.4  889.23  5074.2  893.78  5082.3  893.00  5111.4  892.79
  5351.8  895.37  5402.2  895.12  5502.8  897.05  5567.0  901.77  5594.2  907.60
  5608.6  912.69  5616.7  916.77  5623.1  917.65  5637.6  921.61  5650.0  923.07
#Mann=5,-1,0
  4566.5    0.05       0  4957.8    0.12       0  5013.5    0.07       0
  5021.4    0.12       0  5111.4    0.05       0
Bank Sta=5013.5,5021.4
Exp/Cntr=0.3,0.1

Type RM Length L Ch R = 1,105297,366,366,366
BEGIN DESCRIPTION:
Mapping XS a8d7375a
END DESCRIPTION:
XS GIS Cut Line= 2
      2265289.48      7112450.36      2264938.57      7111997.63
#Sta/Elev= 30
  4785.0  891.30  4874.0  890.40  4906.9  890.26  4921.4  889.30  4927.7  889.60
  4949.9  888.84  4956.7  886.36  4963.0  886.40  4977.5  881.27  4985.7  879.58
  5000.2  874.17  5006.5  869.40  5017.0  866.32  5018.2  865.82  5023.7  865.82
  5024.9  866.32  5027.3  868.96  5035.5  873.89  5041.8  882.31  5050.0  885.70
  5056.3  889.82  5077.1  892.37  5091.6  893.20  5106.1  892.77  5141.4  894.42
  5183.9  897.52  5234.6  901.09  5255.5  901.44  5342.2  908.20  5357.8  908.80
#Mann=5,-1,0
  4785.0    0.05       0  4874.0    0.12       0  5017.0    0.07       0
  5024.9    0.12       0  5183.9    0.05       0
Bank Sta=5017,5024.9
Exp/Cntr=0.3,0.1

Type RM Length L Ch R = 1,104931,530,530,530
BEGIN DESCRIPTION:
Mapping XS 8384ae11
END DESCRIPTION:
XS GIS Cut Line= 2
      2265476.59      7112533.81      2265481.58      7111994.73
#Sta/Elev= 30
  4731.0  890.29  4804.8  889.60  4834.8  889.67  4894.8  889.23  4904.8  889.28
  4914.8  889.76  4924.8  889.47  4934.8  886.77  4944.8  880.57  4946.2  878.96
  4954.8  869.05  4960.7  864.08  4961.9  863.58  4967.7  863.58  4969.0  864.08
  4974.8  864.18  4994.8  876.56  5004.8  881.39  5014.8  884.14  5034.8  886.69
  5044.8  888.82  5064.8  890.29  5074.8  889.96  5094.8  890.95  5104.8  891.73
  5114.8  891.63  5134.8  892.90  5210.9  896.33  5264.8  899.36  5270.1  899.87
#Mann=5,-1,0
  4731.0    0.05       0  4946.2    0.12       0  4960.7    0.07       0
  4969.0    0.12       0  5210.9    0.05       0
Bank Sta=4960.7,4969
Exp/Cntr=0.3,0.1

Type RM Length L Ch R = 1,104401,574,574,574
BEGIN DESCRIPTION:
Oliver Creek 131.0
END DESCRIPTION:
XS GIS Cut Line= 3
      2265749.05      7112521.07      2265929.56      7112107.61
      2265920.43      7111714.26
#Sta/Elev= 30
  4550.6  886.79  4740.3  885.25  4816.0  885.46  4873.6  883.71  4886.2  883.17
  4900.9  883.94  4909.6  881.38  4915.1  882.14  4922.8  878.91  4933.0  876.82
  4938.5  877.80  4944.6  874.63  4961.9  875.32  4977.3  874.74  4985.3  873.00
  4990.8  873.63  4997.7  871.61  5001.8  871.61  5009.4  862.13  5015.2  861.86
  5016.4  861.36  5023.5  861.86  5039.4  873.54  5059.4  882.90  5069.4  886.01
  5081.9  886.35  5109.4  886.41  5229.4  889.01  5389.5  896.83  5395.2  897.84
#Mann=5,-1,0
  4550.6    0.05       0  4873.6    0.12       0  5015.2    0.07       0
  5023.5    0.12       0  5081.9    0.05       0
Bank Sta=5015.2,5023.5
Exp/Cntr=0.3,0.1

Type RM Length L Ch R = 1,103827,380,380,380
BEGIN DESCRIPTION:
Oliver Creek 130.0
END DESCRIPTION:
XS GIS Cut Line= 3
      2266560.64      7112506.99      2266344.72      7112310.72
      2265929.02      7111710.03
#Sta/Elev= 30
  4708.2  893.99  4770.9  893.64  4785.1  891.35  4905.4  886.45  4919.6  885.17
  4933.8  882.08  4940.5  882.22  4952.4  878.23  4968.9  870.65  4976.4  869.75
  4983.1  863.58  4990.5  860.34  4990.9  857.46  4992.5  856.96  5002.8  857.46
  5012.9  864.56  5019.0  871.08  5025.2  872.39  5061.7  874.99  5090.6  879.68
  5105.5  880.12  5126.4  882.59  5141.3  882.10  5198.5  883.42  5371.0  885.01
  5385.9  884.16  5421.7  884.27  5529.2  885.94  5594.7  888.06  5730.5  897.09
#Mann=5,-1,0
  4708.2    0.05       0  4952.4    0.12       0  4990.9    0.07       0
  5002.8    0.12       0  5198.5    0.05       0
Bank Sta=4990.9,5002.8
Exp/Cntr=0.3,0.1

Type RM Length L Ch R = 1,103447,426,426,426
BEGIN DESCRIPTION:
Oliver Creek 129.0
END DESCRIPTION:
XS GIS Cut Line= 3
      2266704.96      7112310.55      2266418.04      7111970.40
      2265992.71      7111582.57
#Sta/Elev= 30
  4555.0  891.86  4765.0  883.80  4788.9  880.42  4864.9  876.34  4885.8  871.81
  4893.5  874.89  4900.1  873.51  4963.8  870.47  4971.5  869.67  4978.1  864.08
  4991.0  859.81  4992.7  859.31  5002.9  859.81  5013.5  862.51  5020.9  875.19
  5035.1  880.90  5070.3  883.46  5091.9  882.30  5112.8  878.73  5120.3  878.73
  5127.0  878.52  5148.0  882.38  5204.7  881.87  5233.1  883.74  5325.0  884.65
  5431.7  889.99  5502.0  891.58  5558.7  895.28  5572.9  897.87  5575.6  899.60
#Mann=5,-1,0
  4555.0    0.05       0  4788.9    0.12       0  4991.0    0.07       0
  5002.9    0.12       0  5120.3    0.05       0
Bank Sta=4991,5002.9
Exp/Cntr=0.3,0.1

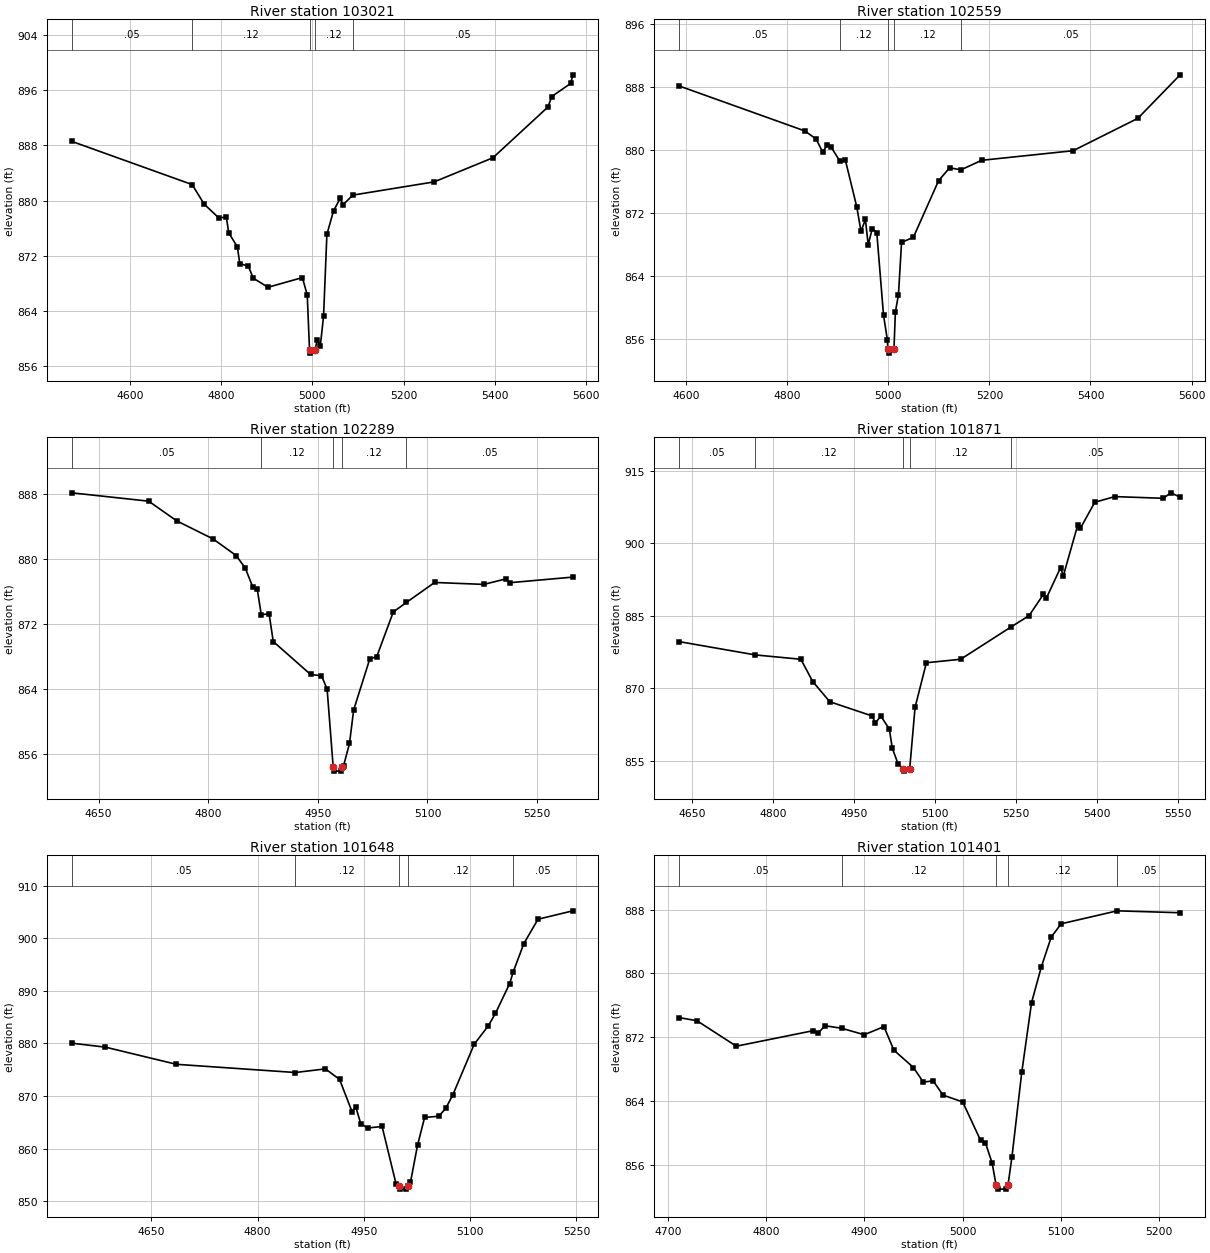
Type RM Length L Ch R = 1,103021,462,462,462
BEGIN DESCRIPTION:
Oliver Creek 128.0
END DESCRIPTION:
XS GIS Cut Line= 3
      2266920.24      7112199.44      2266723.81      7111709.56
      2266379.23      7111254.13
#Sta/Elev= 30
  4472.2  888.59  4736.3  882.32  4762.8  879.47  4794.8  877.48  4811.2  877.61
  4816.6  875.31  4835.4  873.29  4840.8  870.86  4859.5  870.48  4870.4  868.74
  4902.6  867.42  4978.0  868.83  4988.7  866.31  4993.7  858.37  4995.4  857.87
  5005.7  858.37  5011.0  859.83  5017.3  858.89  5024.5  863.23  5031.8  875.10
  5046.4  878.51  5060.9  880.32  5067.2  879.38  5088.5  880.79  5267.0  882.71
  5396.0  886.21  5516.7  893.58  5524.9  895.09  5566.6  897.00  5571.1  898.24
#Mann=5,-1,0
  4472.2    0.05       0  4736.3    0.12       0  4993.7    0.07       0
  5005.7    0.12       0  5088.5    0.05       0
Bank Sta=4993.7,5005.7
Exp/Cntr=0.3,0.1

Type RM Length L Ch R = 1,102559,270,270,270
BEGIN DESCRIPTION:
Oliver Creek 127.0
END DESCRIPTION:
XS GIS Cut Line= 3
      2267307.38      7111923.38      2267125.45      7111551.50
      2266795.26      7111077.95
#Sta/Elev= 30
  4586.0  888.12  4834.7  882.40  4856.9  881.39  4870.2  879.71  4879.2  880.62
  4887.2  880.30  4904.4  878.54  4915.2  878.65  4937.7  872.71  4946.0  869.62
  4954.7  871.14  4960.2  867.92  4968.3  869.98  4977.2  869.47  4990.5  859.00
  4998.1  855.83  4999.2  854.64  5000.9  854.14  5011.2  854.64  5014.0  859.38
  5020.1  861.57  5026.2  868.21  5049.7  868.88  5099.4  876.06  5121.3  877.71
  5143.8  877.45  5184.7  878.66  5365.6  879.88  5493.8  884.00  5577.3  889.53
#Mann=5,-1,0
  4586.0    0.05       0  4904.4    0.12       0  4999.2    0.07       0
  5011.2    0.12       0  5143.8    0.05       0
Bank Sta=4999.2,5011.2
Exp/Cntr=0.3,0.1

Type RM Length L Ch R = 1,102289,418,418,418
BEGIN DESCRIPTION:
Mapping XS f77ec92c
END DESCRIPTION:
XS GIS Cut Line= 3
      2267472.98      7111688.74      2267236.58      7111242.51
      2267068.76      7111309.04
#Sta/Elev= 30
  4613.3  888.15  4718.6  887.12  4757.0  884.69  4806.6  882.47  4838.2  880.42
  4850.6  878.90  4860.8  876.58  4867.0  876.34  4872.6  873.13  4883.3  873.23
  4889.0  869.82  4940.0  865.76  4955.0  865.60  4962.7  863.95  4971.0  854.34
  4972.6  853.84  4981.3  853.84  4983.0  854.34  4985.3  854.53  4993.3  857.26
  4999.0  861.38  5021.0  867.66  5030.6  867.96  5053.2  873.46  5071.2  874.64
  5109.8  877.10  5177.1  876.86  5206.8  877.53  5212.5  877.07  5298.8  877.76
#Mann=5,-1,0
  4613.3    0.05       0  4872.6    0.12       0  4971.0    0.07       0
  4983.0    0.12       0  5071.2    0.05       0
Bank Sta=4971,4983
Exp/Cntr=0.3,0.1

Type RM Length L Ch R = 1,101871,223,223,223
BEGIN DESCRIPTION:
Mapping XS c5567c04
END DESCRIPTION:
XS GIS Cut Line= 2
      2267736.26      7111465.14      2267444.75      7110583.69
#Sta/Elev= 30
  4625.5  879.66  4766.7  876.91  4851.2  876.01  4873.2  871.41  4904.8  867.23
  4983.4  864.29  4989.0  862.86  4999.6  864.24  5015.1  861.59  5020.6  857.64
  5031.2  854.41  5040.8  853.39  5042.5  852.89  5052.9  853.39  5062.8  866.06
  5083.8  875.29  5147.3  876.01  5240.1  882.65  5274.2  885.04  5300.6  889.43
  5305.9  888.60  5332.3  894.93  5337.6  893.29  5364.1  903.71  5369.3  903.12
  5395.8  908.46  5432.8  909.63  5522.7  909.28  5536.7  910.41  5553.9  909.52
#Mann=5,-1,0
  4625.5    0.05       0  4766.7    0.12       0  5040.8    0.07       0
  5052.9    0.12       0  5240.1    0.05       0
Bank Sta=5040.8,5052.9
Exp/Cntr=0.3,0.1

Type RM Length L Ch R = 1,101648,247,247,247
BEGIN DESCRIPTION:
Oliver Creek 125.0
END DESCRIPTION:
XS GIS Cut Line= 3
      2267807.40      7111527.54      2267826.67      7111065.75
      2267826.49      7110820.95
#Sta/Elev= 30
  4537.8  880.06  4585.4  879.30  4685.5  876.04  4853.3  874.48  4895.7  875.17
  4915.7  873.17  4933.4  866.99  4938.4  868.01  4945.7  864.71  4955.7  863.93
  4975.7  864.22  4995.4  853.30  4999.7  852.80  5001.4  852.30  5010.1  852.30
  5011.8  852.80  5015.7  853.57  5025.7  860.63  5035.7  865.94  5055.7  866.16
  5065.7  867.70  5075.7  870.29  5105.7  879.86  5125.7  883.38  5135.7  885.74
  5155.7  891.39  5160.9  893.68  5175.7  899.00  5195.7  903.63  5244.8  905.23
#Mann=5,-1,0
  4537.8    0.05       0  4853.3    0.12       0  4999.7    0.07       0
  5011.8    0.12       0  5160.9    0.05       0
Bank Sta=4999.7,5011.8
Exp/Cntr=0.3,0.1

Type RM Length L Ch R = 1,101401,210,210,210
BEGIN DESCRIPTION:
Mapping XS a88cac1a
END DESCRIPTION:
XS GIS Cut Line= 2
      2268055.79      7111348.20      2268085.74      7110839.08
#Sta/Elev= 30
  4711.3  874.45  4729.5  874.06  4769.6  870.86  4847.9  872.81  4852.9  872.50
  4859.8  873.43  4876.9  873.11  4899.8  872.30  4919.9  873.32  4929.9  870.37
  4949.9  868.18  4959.9  866.35  4969.9  866.51  4980.0  864.72  5000.0  863.86
  5018.2  859.03  5023.2  858.71  5030.0  856.17  5034.0  853.41  5035.7  852.91
  5044.4  852.91  5046.1  853.41  5050.1  856.91  5060.1  867.56  5070.1  876.34
  5080.1  880.84  5090.1  884.56  5100.2  886.23  5157.3  887.86  5221.3  887.62
#Mann=5,-1,0
  4711.3    0.05       0  4876.9    0.12       0  5034.0    0.07       0
  5046.1    0.12       0  5157.3    0.05       0
Bank Sta=5034,5046.1
Exp/Cntr=0.3,0.1

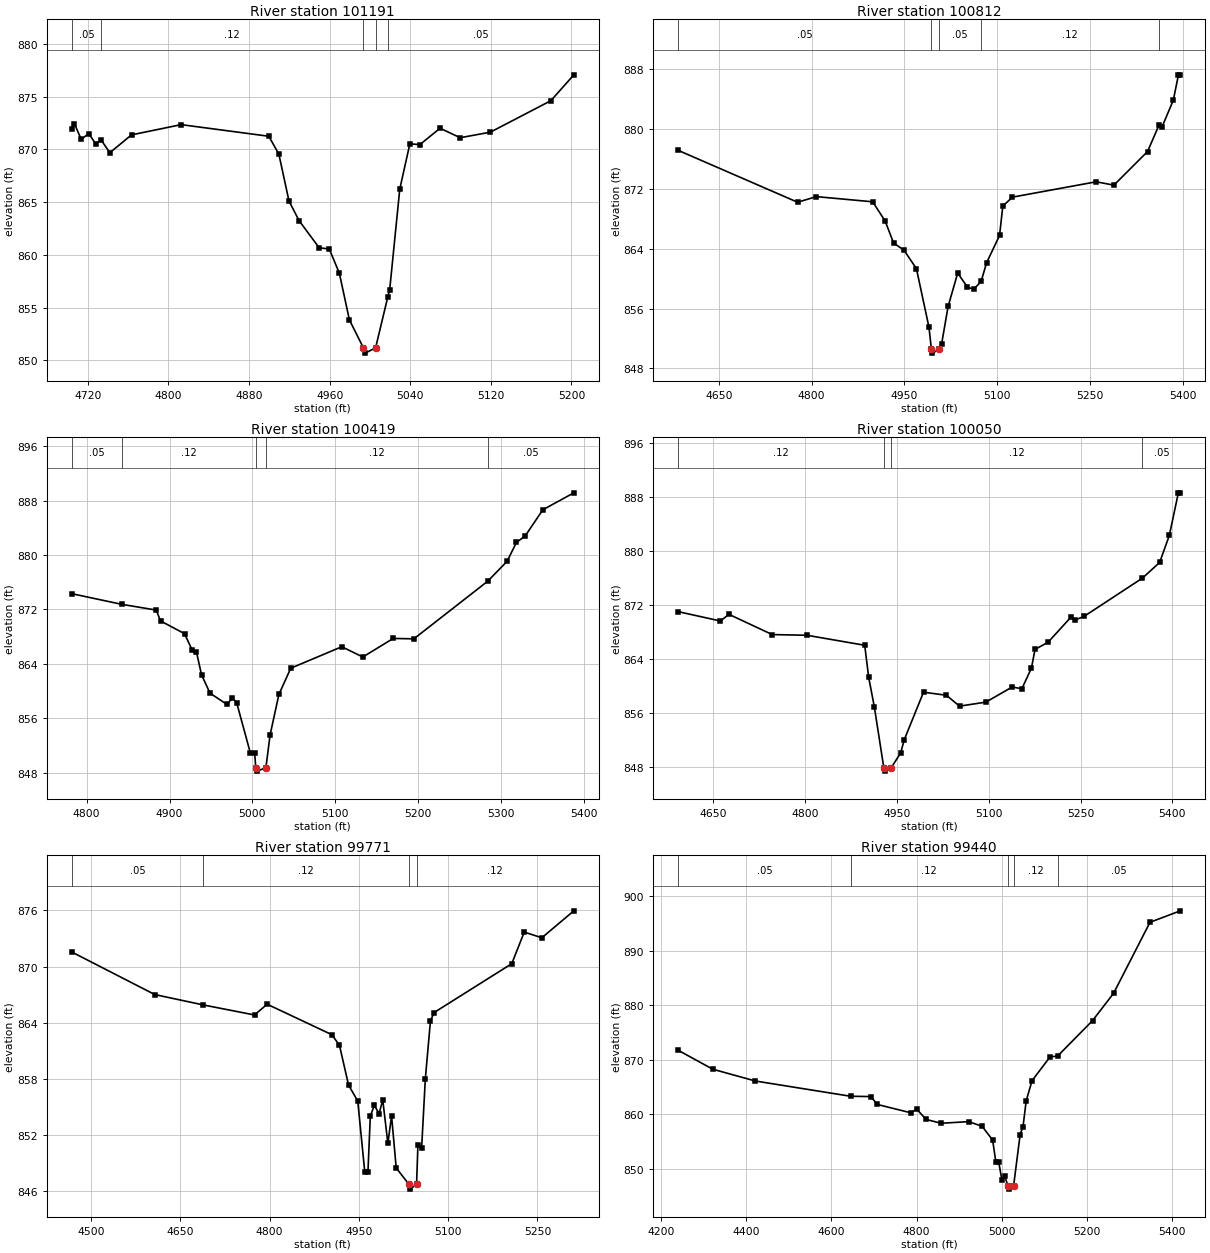
Type RM Length L Ch R = 1,101191,379,379,379
BEGIN DESCRIPTION:
Mapping XS c165ae70
END DESCRIPTION:
XS GIS Cut Line= 3
      2268182.06      7111316.73      2268281.61      7111208.65
      2268284.89      7110857.20
#Sta/Elev= 30
  4704.0  871.95  4706.6  872.44  4713.4  870.94  4720.8  871.50  4727.6  870.54
  4733.2  870.88  4741.8  869.68  4763.3  871.37  4812.6  872.34  4899.6  871.24
  4909.6  869.54  4919.6  865.11  4929.6  863.25  4949.6  860.67  4959.6  860.56
  4969.6  858.27  4979.6  853.84  4993.5  851.19  4995.2  850.69  5005.6  851.19
  5017.8  856.05  5019.6  856.71  5029.6  866.23  5039.6  870.52  5049.6  870.45
  5069.6  872.00  5089.6  871.10  5119.6  871.63  5179.6  874.61  5202.4  877.06
#Mann=5,-1,0
  4704.0    0.05       0  4733.2    0.12       0  4993.5    0.07       0
  5005.6    0.12       0  5017.8    0.05       0
Bank Sta=4993.5,5005.6
Exp/Cntr=0.3,0.1

Type RM Length L Ch R = 1,100812,393,393,393
BEGIN DESCRIPTION:
Oliver Creek 123.6
END DESCRIPTION:
XS GIS Cut Line= 3
      2268674.59      7111420.81      2268613.94      7111009.86
      2268505.32      7110629.15
#Sta/Elev= 30
  4584.6  877.10  4777.5  870.18  4807.8  870.93  4898.8  870.24  4919.0  867.67
  4932.6  864.73  4949.3  863.80  4969.5  861.31  4989.8  853.49  4993.7  850.55
  4995.4  850.05  5005.9  850.55  5010.3  851.32  5020.7  856.29  5036.2  860.73
  5051.8  858.86  5062.2  858.57  5074.0  859.62  5083.0  862.13  5103.8  865.75
  5109.1  869.67  5124.6  870.86  5260.0  872.91  5288.6  872.46  5343.0  876.95
  5361.6  880.50  5366.6  880.27  5384.6  883.80  5392.9  887.18  5395.9  887.18
#Mann=5,-1,0
  4584.6    0.05       0  4993.7   0.033       0  5005.9    0.05       0
  5074.0    0.12       0  5361.6    0.05       0
Bank Sta=4993.7,5005.9
Exp/Cntr=0.3,0.1

Type RM Length L Ch R = 1,100419,369,369,369
BEGIN DESCRIPTION:
Oliver Creek 123.4
END DESCRIPTION:
XS GIS Cut Line= 3
      2269006.67      7111092.85      2268959.05      7110880.12
      2268828.44      7110514.76
#Sta/Elev= 30
  4782.0  874.31  4842.5  872.74  4884.0  871.90  4889.1  870.31  4918.1  868.43
  4927.4  865.99  4932.5  865.74  4938.6  862.39  4948.9  859.68  4969.4  858.02
  4975.9  858.99  4981.0  858.30  4997.5  850.91  5002.7  850.91  5004.1  848.72
  5005.8  848.22  5016.3  848.72  5021.4  853.56  5032.0  859.49  5046.3  863.35
  5107.9  866.51  5133.3  865.00  5170.0  867.73  5194.9  867.67  5284.0  876.14
  5307.4  879.07  5318.7  881.84  5329.3  882.81  5350.6  886.65  5388.0  889.14
#Mann=5,-1,0
  4782.0    0.05       0  4842.5    0.12       0  5004.1    0.07       0
  5016.3    0.12       0  5284.0    0.05       0
Bank Sta=5004.1,5016.3
Exp/Cntr=0.3,0.1

Type RM Length L Ch R = 1,100050,279,279,279
BEGIN DESCRIPTION:
Oliver Creek 123.2
END DESCRIPTION:
XS GIS Cut Line= 3
      2269105.24      7111003.49      2269305.43      7110805.91
      2269034.98      7110339.52
#Sta/Elev= 30
  4592.5  871.00  4661.3  869.62  4675.4  870.60  4746.1  867.61  4802.7  867.51
  4897.2  866.03  4903.7  861.28  4913.0  856.89  4928.4  847.92  4930.1  847.42
  4940.6  847.92  4956.0  850.13  4961.8  852.06  4993.3  859.09  5030.6  858.64
  5052.1  857.03  5095.2  857.62  5138.2  859.86  5154.0  859.60  5169.6  862.65
  5175.5  865.41  5197.0  866.49  5234.3  870.20  5240.1  869.73  5255.8  870.31
  5351.0  875.96  5379.2  878.28  5395.0  882.29  5409.7  888.57  5412.9  888.57
#Mann=4,-1,0
  4592.5    0.12       0  4928.4    0.07       0  4940.6    0.12       0
  5351.0    0.05       0
Bank Sta=4928.4,4940.6
Exp/Cntr=0.3,0.1

Type RM Length L Ch R = 1,99771,331,331,331
BEGIN DESCRIPTION:
Mapping XS 960dd665
END DESCRIPTION:
XS GIS Cut Line= 3
      2269729.58      7110960.65      2269467.75      7110541.39
      2269266.48      7110256.15
#Sta/Elev= 30
  4467.8  871.55  4607.3  867.00  4689.0  865.89  4774.8  864.82  4796.0  865.97
  4904.8  862.71  4917.5  861.57  4932.8  857.32  4948.2  855.62  4960.0  848.04
  4965.3  848.04  4969.3  854.01  4976.0  855.15  4984.1  854.29  4990.2  855.74
  4998.8  851.10  5005.0  854.02  5012.8  848.48  5034.3  846.71  5036.1  846.21
  5047.0  846.71  5049.3  850.97  5055.5  850.60  5061.7  857.98  5070.3  864.18
  5076.4  865.08  5206.9  870.30  5227.9  873.68  5257.4  873.07  5311.2  875.95
#Mann=4,-1,0
  4467.8    0.05       0  4689.0    0.12       0  5034.3    0.07       0
  5047.0    0.12       0
Bank Sta=5034.3,5047
Exp/Cntr=0.3,0.1

Type RM Length L Ch R = 1,99440,479,479,479
BEGIN DESCRIPTION:
Oliver Creek 123.0
END DESCRIPTION:
XS GIS Cut Line= 3
      2270063.81      7110888.21      2269639.36      7110319.61
      2269287.73      7110010.56
#Sta/Elev= 30
  4240.8  871.75  4321.9  868.28  4421.9  866.12  4645.0  863.33  4692.9  863.27
  4707.5  861.83  4786.8  860.29  4800.1  860.98  4822.2  859.08  4857.6  858.38
  4922.3  858.68  4953.8  857.81  4978.3  855.29  4985.9  851.24  4992.5  851.29
  5000.1  847.96  5006.8  848.67  5014.6  846.81  5016.4  846.31  5027.3  846.81
  5042.8  856.32  5049.5  857.75  5057.0  862.49  5070.7  866.18  5113.0  870.55
  5130.6  870.69  5212.6  877.19  5262.0  882.20  5347.4  895.21  5418.5  897.31
#Mann=5,-1,0
  4240.8    0.05       0  4645.0    0.12       0  5014.6    0.07       0
  5027.3    0.12       0  5130.6    0.05       0
Bank Sta=5014.6,5027.3
Exp/Cntr=0.3,0.1

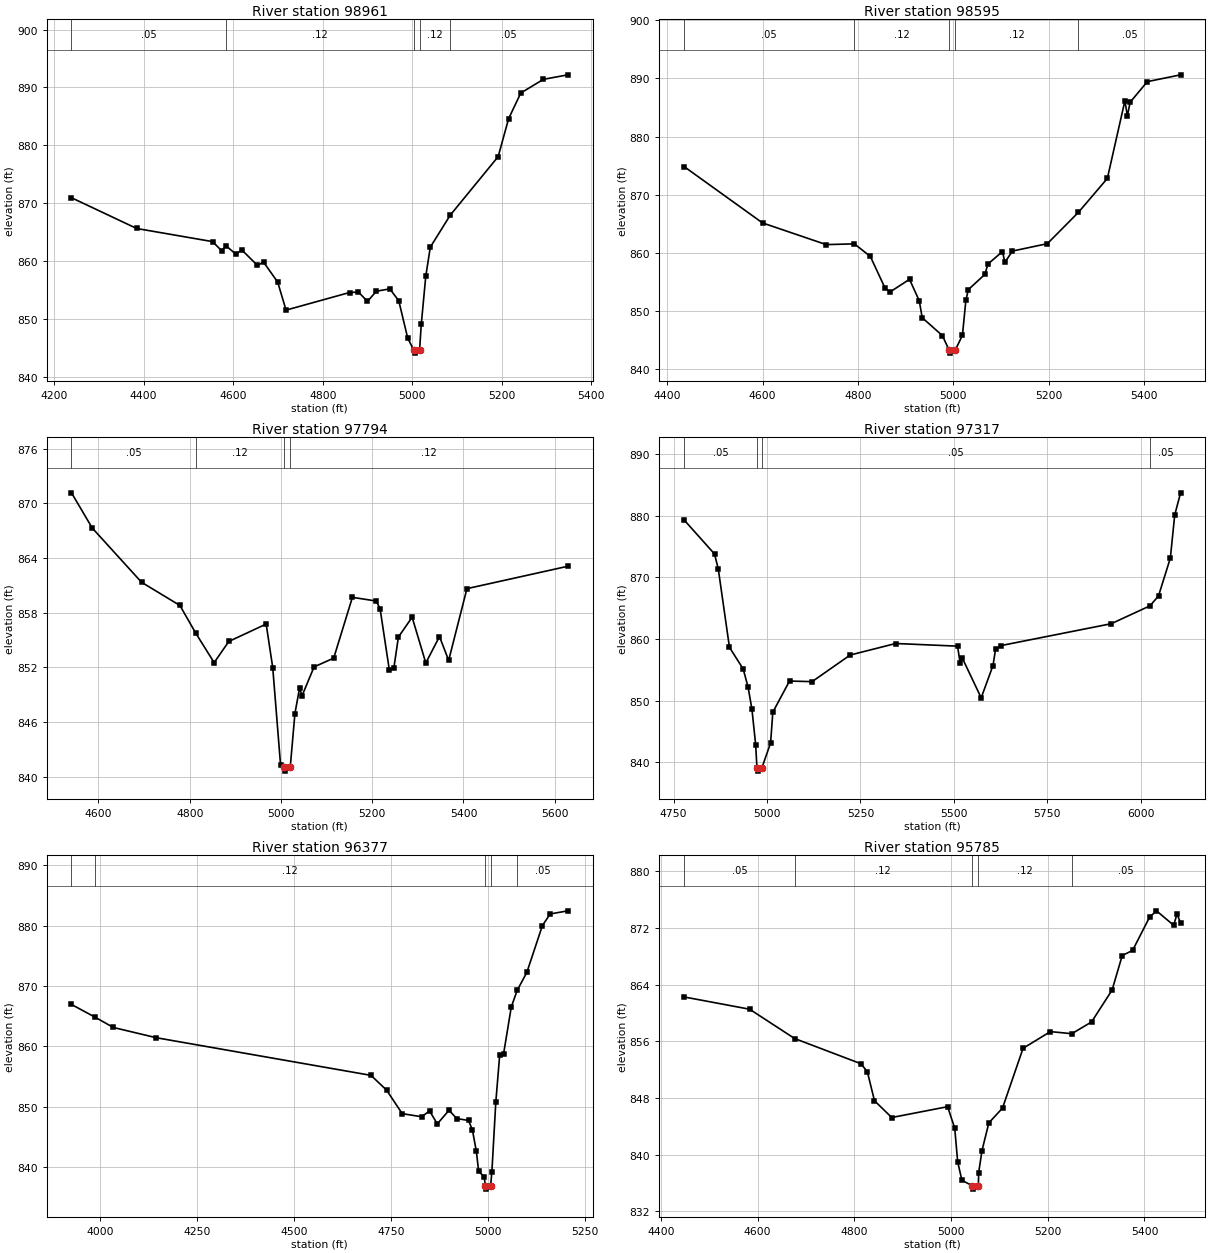
Type RM Length L Ch R = 1,98961,366,366,366
BEGIN DESCRIPTION:
Oliver Creek 122.0
END DESCRIPTION:
XS GIS Cut Line= 4
      2270082.02      7110854.31      2269957.03      7110388.20
      2269954.21      7110109.89      2269904.95      7109765.80
#Sta/Elev= 30
  4239.1  870.95  4384.6  865.64  4554.2  863.37  4574.3  861.80  4584.4  862.64
  4605.9  861.21  4619.5  861.93  4654.3  859.26  4668.0  859.83  4699.5  856.38
  4718.2  851.54  4859.9  854.58  4879.9  854.66  4899.9  853.04  4919.9  854.80
  4949.9  855.21  4969.9  853.15  4989.9  846.68  5003.6  844.61  5005.4  844.11
  5016.3  844.61  5020.1  849.07  5030.2  857.41  5040.3  862.41  5084.8  867.94
  5191.8  878.05  5215.1  884.59  5242.3  889.04  5292.8  891.40  5347.6  892.18
#Mann=5,-1,0
  4239.1    0.05       0  4584.4    0.12       0  5003.6    0.07       0
  5016.3    0.12       0  5084.8    0.05       0
Bank Sta=5003.6,5016.3
Exp/Cntr=0.3,0.1

Type RM Length L Ch R = 1,98595,801,801,801
BEGIN DESCRIPTION:
Oliver Creek 121.0
END DESCRIPTION:
XS GIS Cut Line= 3
      2270279.01      7110810.03      2270149.23      7110260.65
      2270037.77      7109797.06
#Sta/Elev= 30
  4435.5  874.83  4599.9  865.14  4733.5  861.41  4792.5  861.54  4826.0  859.38
  4856.8  853.94  4867.1  853.25  4908.2  855.44  4928.7  851.73  4934.8  848.84
  4977.1  845.76  4991.4  843.24  4993.2  842.74  5004.1  843.24  5019.2  845.82
  5026.4  851.80  5031.5  853.66  5066.3  856.29  5072.7  858.07  5103.1  860.21
  5108.3  858.37  5124.1  860.30  5197.3  861.57  5262.6  866.97  5323.2  872.80
  5360.0  886.17  5365.2  883.54  5370.9  885.90  5407.1  889.45  5476.8  890.62
#Mann=5,-1,0
  4435.5    0.05       0  4792.5    0.12       0  4991.4    0.07       0
  5004.1    0.12       0  5262.6    0.05       0
Bank Sta=4991.4,5004.1
Exp/Cntr=0.3,0.1

Type RM Length L Ch R = 1,97794,477,477,477
BEGIN DESCRIPTION:
Oliver Creek 120.0
END DESCRIPTION:
XS GIS Cut Line= 3
      2270449.42      7110746.18      2270642.20      7110146.50
      2270665.55      7109688.91
#Sta/Elev= 30
  4540.9  871.14  4586.4  867.28  4694.5  861.33  4778.5  858.79  4813.5  855.73
  4853.6  852.52  4885.7  854.84  4967.6  856.75  4982.0  851.97  4999.1  841.33
  5007.6  841.12  5009.4  840.62  5020.5  841.12  5030.6  846.93  5040.9  849.76
  5046.2  848.88  5072.6  852.05  5115.6  853.01  5156.6  859.68  5209.2  859.27
  5217.4  858.39  5237.4  851.76  5247.4  851.90  5257.4  855.32  5287.5  857.50
  5317.5  852.48  5347.5  855.38  5367.6  852.76  5407.6  860.63  5629.0  863.09
#Mann=4,-1,0
  4540.9    0.05       0  4813.5    0.12       0  5007.6    0.07       0
  5020.5    0.12       0
Bank Sta=5007.6,5020.5
Exp/Cntr=0.3,0.1

Type RM Length L Ch R = 1,97317,940,940,940
BEGIN DESCRIPTION:
Oliver Creek 119.0
END DESCRIPTION:
XS GIS Cut Line= 4
      2270947.38      7110731.21      2270942.34      7110493.06
      2270873.32      7110089.84      2270657.72      7109443.96
#Sta/Elev= 30
  4778.5  879.32  4859.7  873.81  4869.7  871.42  4899.7  858.66  4936.5  855.14
  4949.7  852.16  4959.8  848.63  4969.8  842.88  4973.3  839.07  4975.1  838.57
  4986.3  839.07  5009.8  843.15  5015.7  848.13  5060.4  853.19  5120.8  853.09
  5222.7  857.41  5344.5  859.28  5510.0  858.85  5516.8  856.12  5522.1  856.99
  5573.2  850.46  5604.8  855.71  5611.6  858.33  5625.9  858.94  5921.1  862.49
  6025.0  865.40  6047.6  867.00  6079.3  873.15  6091.0  880.14  6106.7  883.73
#Mann=4,-1,0
  4778.5    0.05       0  4973.3    0.07       0  4986.3    0.05       0
  6025.0    0.05       0
Bank Sta=4973.3,4986.3
Exp/Cntr=0.3,0.1

Type RM Length L Ch R = 1,96377,592,592,592
BEGIN DESCRIPTION:
Oliver Creek 118.0
END DESCRIPTION:
XS GIS Cut Line= 3
      2271451.92      7110887.41      2271334.35      7109843.12
      2271345.21      7109614.16
#Sta/Elev= 30
  3925.3  866.94  3985.5  864.85  4033.4  863.12  4144.1  861.42  4697.6  855.18
  4737.8  852.73  4778.1  848.83  4828.4  848.31  4848.5  849.29  4868.6  847.13
  4898.8  849.39  4918.9  848.00  4949.1  847.71  4959.2  846.09  4969.3  842.57
  4975.2  839.24  4989.3  838.39  4992.7  836.81  4994.6  836.31  5006.0  836.81
  5009.3  839.18  5019.4  850.72  5029.4  858.52  5039.4  858.72  5059.4  866.54
  5074.7  869.30  5099.4  872.25  5139.5  880.01  5159.5  881.95  5205.4  882.47
#Mann=5,-1,0
  3925.3    0.05       0  3985.5    0.12       0  4992.7    0.07       0
  5006.0    0.12       0  5074.7    0.05       0
Bank Sta=4992.7,5006
Exp/Cntr=0.3,0.1

Type RM Length L Ch R = 1,95785,334,334,334
BEGIN DESCRIPTION:
Oliver Creek 117.0
END DESCRIPTION:
XS GIS Cut Line= 3
      2272020.76      7110287.87      2271675.71      7109803.50
      2271378.83      7109489.69
#Sta/Elev= 30
  4448.0  862.28  4583.4  860.55  4676.5  856.41  4813.7  852.85  4826.9  851.72
  4841.6  847.63  4877.3  845.26  4992.9  846.79  5007.6  843.74  5013.7  839.00
  5022.4  836.40  5043.2  835.65  5045.1  835.15  5056.5  835.65  5057.1  837.49
  5064.0  840.60  5078.1  844.50  5106.4  846.59  5148.9  855.03  5205.5  857.39
  5249.7  857.09  5290.5  858.75  5333.0  863.25  5354.0  868.13  5375.4  868.85
  5410.6  873.55  5424.8  874.44  5460.4  872.40  5467.3  874.00  5474.7  872.70
#Mann=5,-1,0
  4448.0    0.05       0  4676.5    0.12       0  5043.2    0.07       0
  5056.5    0.12       0  5249.7    0.05       0
Bank Sta=5043.2,5056.5
Exp/Cntr=0.3,0.1

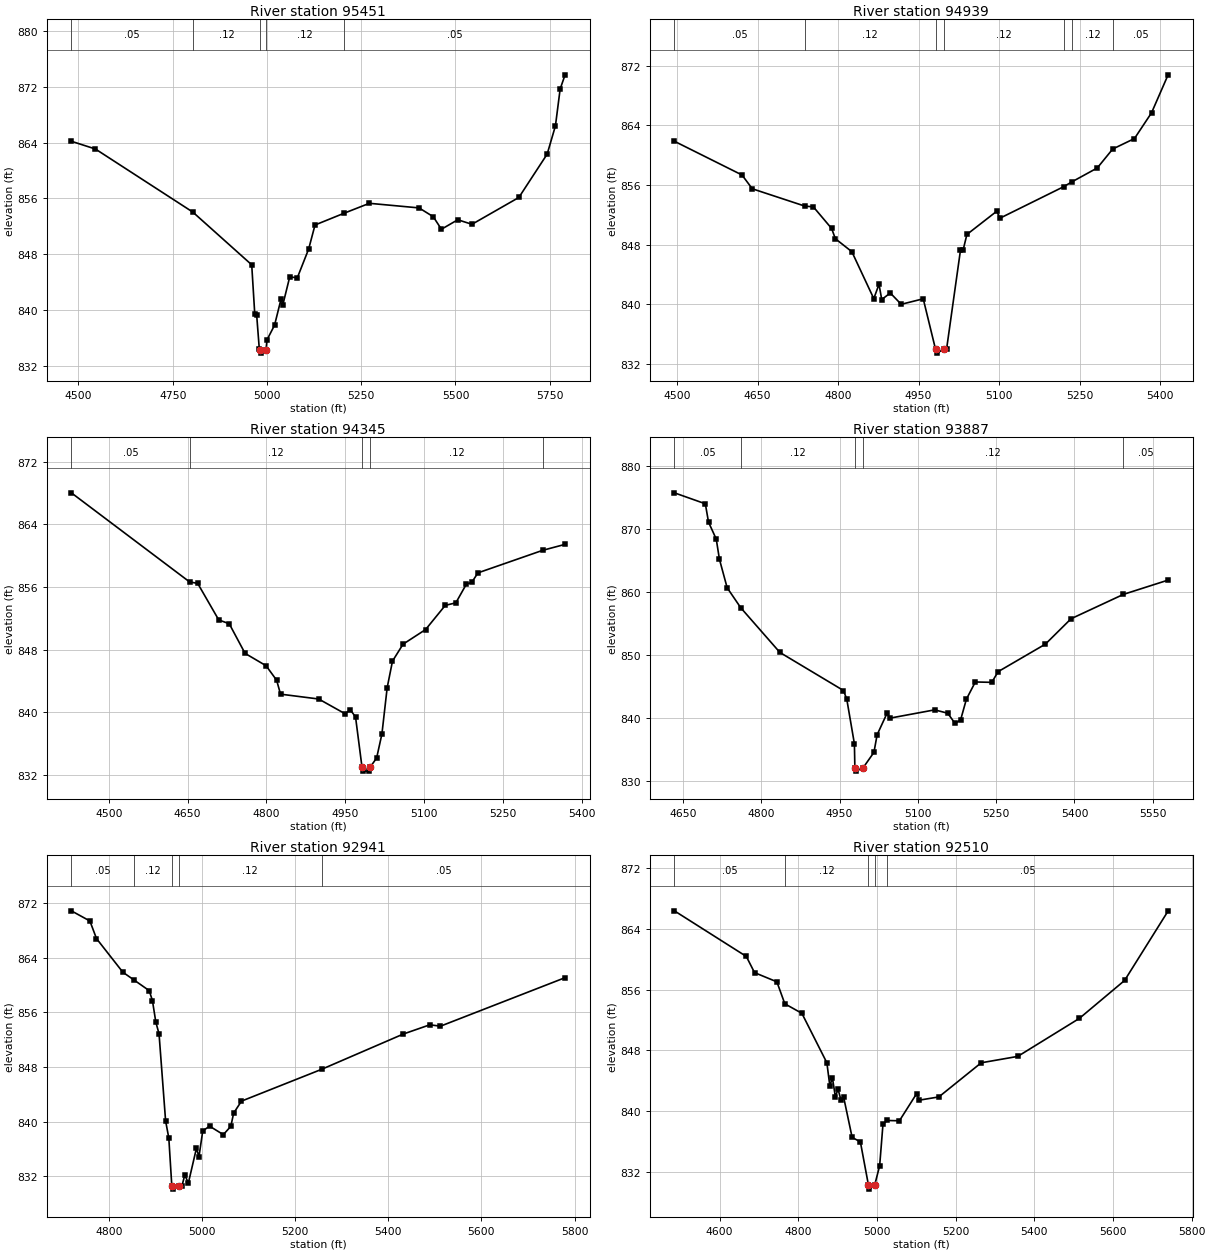
Type RM Length L Ch R = 1,95451,512,512,512
BEGIN DESCRIPTION:
Oliver Creek 116.0
END DESCRIPTION:
XS GIS Cut Line= 4
      2272046.53      7110363.13      2271969.63      7109849.96
      2272004.59      7109538.00      2272420.42      7109304.72
#Sta/Elev= 30
  4481.1  864.19  4544.9  863.08  4803.3  854.03  4959.5  846.47  4967.5  839.48
  4972.6  839.30  4979.7  834.34  4982.3  834.30  4984.3  833.80  4997.5  834.30
  5000.0  835.70  5020.1  837.81  5037.2  841.53  5042.2  840.76  5060.3  844.73
  5080.5  844.61  5110.6  848.74  5127.4  852.18  5205.1  853.88  5271.6  855.29
  5403.4  854.63  5441.0  853.37  5462.7  851.57  5506.1  852.93  5543.7  852.28
  5668.1  856.13  5743.2  862.35  5765.1  866.40  5777.6  871.68  5790.7  873.72
#Mann=5,-1,0
  4481.1    0.05       0  4803.3    0.12       0  4982.3    0.07       0
  4997.5    0.12       0  5205.1    0.05       0
Bank Sta=4982.3,4997.5
Exp/Cntr=0.3,0.1

Type RM Length L Ch R = 1,94939,594,594,594
BEGIN DESCRIPTION:
Oliver Creek 115.0
END DESCRIPTION:
XS GIS Cut Line= 3
      2272252.53      7110233.20      2272359.17      7109739.59
      2272423.11      7109329.54
#Sta/Elev= 30
  4495.0  861.86  4621.0  857.34  4640.2  855.49  4738.1  853.17  4754.0  853.07
  4788.0  850.17  4795.0  848.80  4825.7  847.06  4866.6  840.77  4876.3  842.70
  4881.4  840.65  4897.3  841.53  4917.7  840.01  4958.7  840.75  4981.7  833.97
  4983.7  833.47  4996.9  833.97  5002.3  834.05  5028.1  847.26  5033.2  847.33
  5040.1  849.37  5096.0  852.50  5101.1  851.53  5220.1  855.76  5236.8  856.46
  5283.0  858.28  5311.8  860.82  5352.3  862.22  5384.2  865.68  5415.0  870.76
#Mann=7,-1,0
  4495.0    0.05       0  4738.1    0.12       0  4981.7    0.07       0
  4996.9    0.12       0  5220.1    0.05       0  5236.8    0.12       0
  5311.8    0.05       0
Bank Sta=4981.7,4996.9
Exp/Cntr=0.3,0.1

Type RM Length L Ch R = 1,94345,458,458,458
BEGIN DESCRIPTION:
Oliver Creek 114.0
END DESCRIPTION:
XS GIS Cut Line= 3
      2272927.01      7110280.02      2272894.18      7109709.56
      2272856.89      7109343.16
#Sta/Elev= 30
  4428.6  868.01  4653.7  856.63  4669.0  856.45  4709.1  851.78  4729.1  851.29
  4759.2  847.51  4799.2  845.93  4819.3  844.08  4826.7  842.30  4899.4  841.68
  4949.5  839.80  4959.5  840.31  4969.5  839.38  4981.8  832.97  4983.8  832.47
  4995.2  832.47  4997.2  832.97  5009.6  834.14  5019.7  837.22  5029.7  843.13
  5039.8  846.52  5059.9  848.68  5102.8  850.55  5140.3  853.64  5160.4  853.96
  5180.5  856.36  5190.5  856.56  5202.5  857.79  5325.8  860.67  5368.3  861.43
#Mann=5,-1,0
  4428.6    0.05       0  4653.7    0.12       0  4981.8    0.07       0
  4997.2    0.12       0  5325.8    0.05       0
Bank Sta=4981.8,4997.2
Exp/Cntr=0.3,0.1

Type RM Length L Ch R = 1,93887,946,946,946
BEGIN DESCRIPTION:
Oliver Creek 113.0
END DESCRIPTION:
XS GIS Cut Line= 4
      2273528.56      7109921.98      2273229.00      7109710.00
      2273031.18      7109636.83      2272850.98      7109316.31
#Sta/Elev= 30
  4633.7  875.76  4693.0  874.02  4699.1  871.11  4713.9  868.41  4720.0  865.21
  4734.8  860.68  4760.9  857.50  4835.8  850.41  4957.6  844.36  4963.9  842.98
  4978.5  835.90  4979.4  832.06  4981.4  831.56  4994.9  832.06  5015.9  834.54
  5022.0  837.33  5041.0  840.75  5046.3  839.97  5132.2  841.29  5157.2  840.76
  5171.3  839.13  5181.9  839.69  5193.0  842.99  5210.1  845.72  5241.6  845.66
  5253.8  847.36  5344.3  851.73  5393.4  855.76  5493.7  859.63  5579.3  861.90
#Mann=5,-1,0
  4633.7    0.05       0  4760.9    0.12       0  4979.4    0.07       0
  4994.9    0.12       0  5493.7    0.05       0
Bank Sta=4979.4,4994.9
Exp/Cntr=0.3,0.1

Type RM Length L Ch R = 1,92941,431,431,431
BEGIN DESCRIPTION:
Oliver Creek 111.0
END DESCRIPTION:
XS GIS Cut Line= 3
      2273811.30      7109613.86      2273633.92      7109446.78
      2272894.60      7109099.96
#Sta/Elev= 30
  4719.4  870.90  4759.2  869.41  4773.4  866.83  4830.0  861.90  4854.4  860.74
  4886.6  859.20  4893.5  857.75  4900.8  854.58  4907.7  852.88  4921.8  840.10
  4928.7  837.59  4935.1  830.60  4937.1  830.10  4950.7  830.60  4957.0  830.61
  4963.0  832.16  4970.7  831.00  4987.9  836.06  4993.5  834.88  5001.6  838.64
  5016.3  839.33  5045.8  838.09  5061.9  839.31  5067.9  841.24  5084.7  843.00
  5256.7  847.66  5432.4  852.84  5489.2  854.19  5512.1  853.99  5779.7  861.10
#Mann=5,-1,0
  4719.4    0.05       0  4854.4    0.12       0  4935.1    0.07       0
  4950.7    0.12       0  5256.7    0.05       0
Bank Sta=4935.1,4950.7
Exp/Cntr=0.3,0.1

Type RM Length L Ch R = 1,92510,448,448,448
BEGIN DESCRIPTION:
Oliver Creek 110.0
END DESCRIPTION:
XS GIS Cut Line= 3
      2274074.82      7109392.03      2273692.57      7109046.76
      2273096.09      7108608.62
#Sta/Elev= 30
  4484.9  866.35  4667.8  860.35  4688.7  858.22  4745.5  857.01  4765.7  854.12
  4809.0  852.87  4872.6  846.36  4880.0  843.37  4886.8  844.33  4894.2  841.89
  4901.0  842.89  4908.4  841.46  4915.2  841.84  4936.8  836.55  4957.8  835.95
  4978.4  830.24  4980.4  829.74  4994.0  830.24  5006.8  832.82  5015.2  838.27
  5025.9  838.77  5057.0  838.73  5100.9  842.31  5107.1  841.44  5157.3  841.87
  5265.0  846.36  5357.9  847.20  5514.5  852.20  5629.5  857.19  5740.1  866.33
#Mann=5,-1,0
  4484.9    0.05       0  4765.7    0.12       0  4978.4    0.07       0
  4994.0    0.12       0  5025.9    0.05       0
Bank Sta=4978.4,4994
Exp/Cntr=0.3,0.1