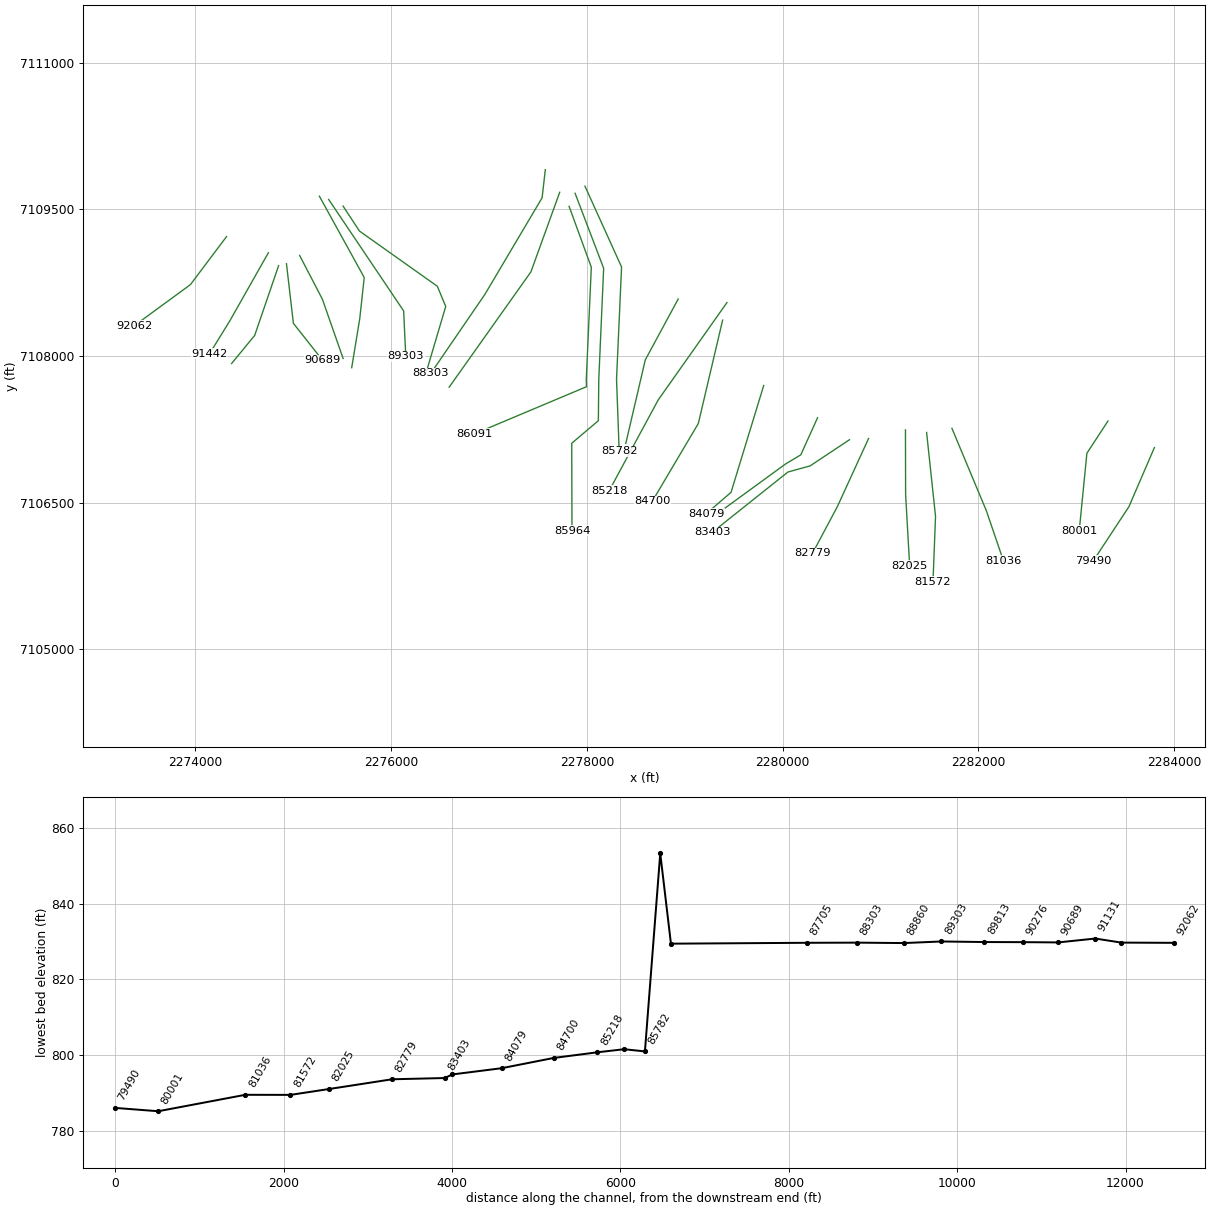
HEC-RAS study Oliver Creek.prj: Oliver Creek Base Level Engineering

--- Oliver Creek.g01 (geometry) --- (continued)

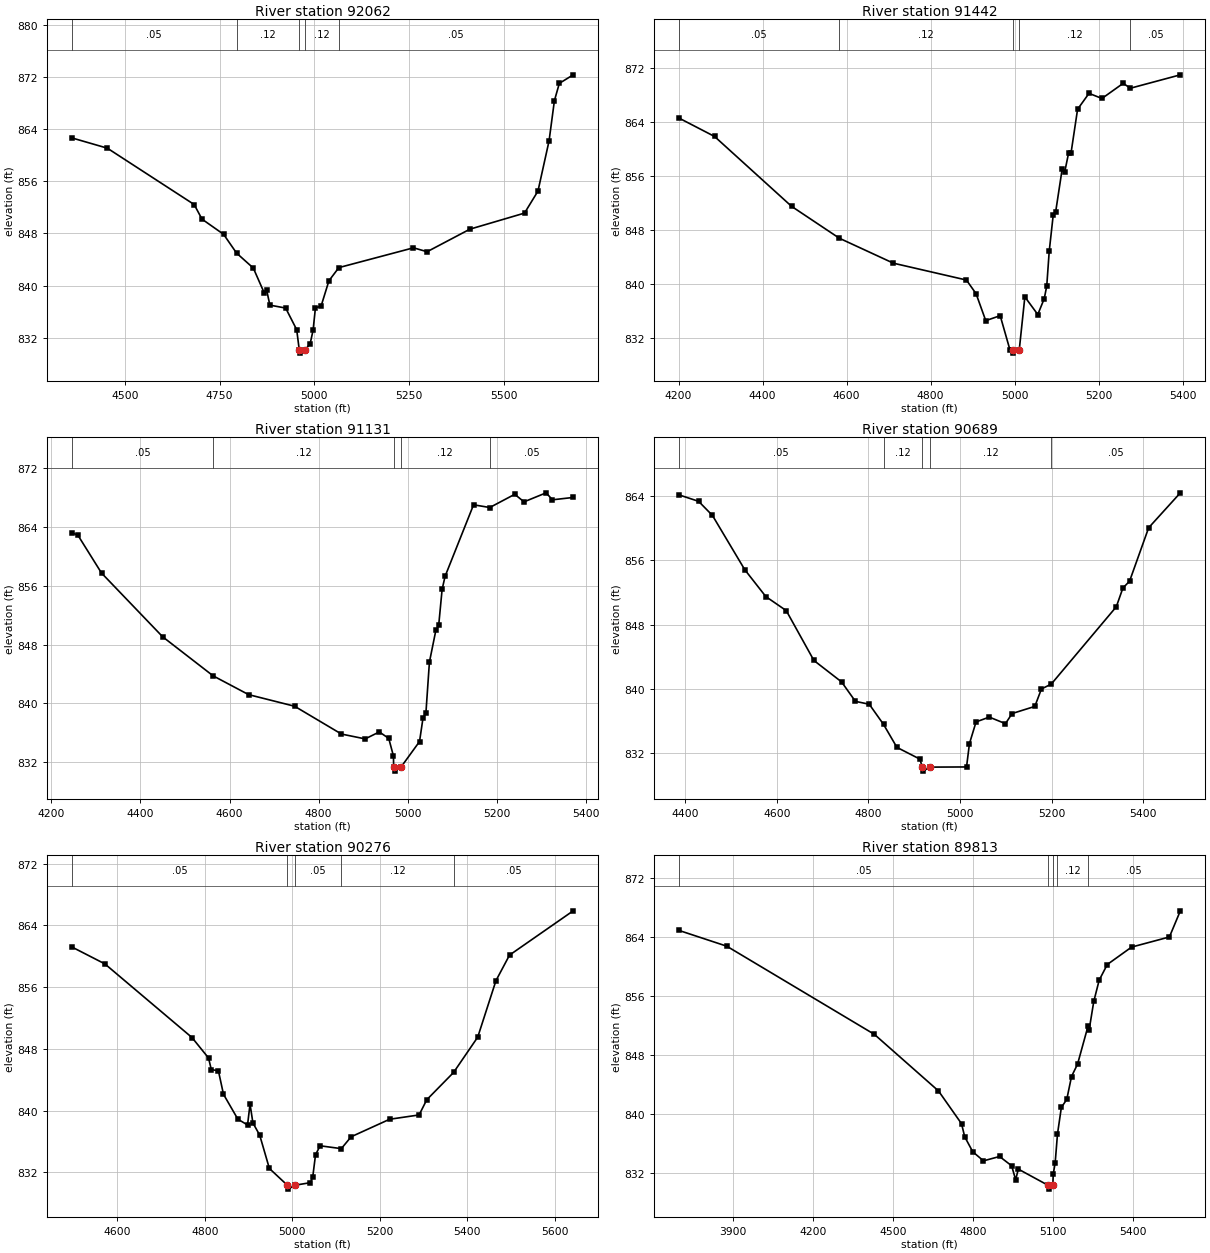
Type RM Length L Ch R = 1,92062,620,620,620
BEGIN DESCRIPTION:
Oliver Creek 109.0
END DESCRIPTION:
XS GIS Cut Line= 3
      2274320.05      7109220.59      2273951.28      7108729.51
      2273379.00      7108310.00
#Sta/Elev= 30
  4359.7  862.68  4453.6  861.10  4682.8  852.45  4703.6  850.20  4760.6  847.87
  4794.8  844.99  4839.0  842.69  4868.1  838.84  4874.4  839.25  4882.7  837.00
  4924.4  836.55  4953.5  833.23  4960.3  830.13  4962.3  829.63  4976.0  830.13
  4989.1  831.09  4996.8  833.15  5003.0  836.61  5017.7  836.81  5038.6  840.74
  5064.8  842.76  5261.8  845.80  5297.8  845.20  5410.6  848.66  5554.9  851.13
  5590.4  854.51  5619.7  862.22  5633.8  868.39  5646.8  871.05  5683.4  872.36
#Mann=5,-1,0
  4359.7    0.05       0  4794.8    0.12       0  4960.3    0.07       0
  4976.0    0.12       0  5064.8    0.05       0
Bank Sta=4960.3,4976
Exp/Cntr=0.3,0.1

Type RM Length L Ch R = 1,91442,311,311,311
BEGIN DESCRIPTION:
Oliver Creek 108.0
END DESCRIPTION:
XS GIS Cut Line= 3
      2274747.58      7109055.67      2274354.04      7108360.08
      2274147.36      7108024.17
#Sta/Elev= 30
  4200.8  864.59  4285.7  861.85  4469.0  851.48  4582.9  846.74  4711.4  843.04
  4885.2  840.54  4908.2  838.51  4931.2  834.51  4965.6  835.25  4988.6  830.22
  4995.1  830.19  4997.1  829.69  5011.0  830.19  5024.3  838.04  5055.1  835.42
  5070.5  837.79  5076.4  839.65  5082.3  844.82  5091.8  850.18  5097.7  850.69
  5113.1  857.00  5119.0  856.53  5128.5  859.42  5134.4  859.47  5149.8  865.89
  5177.0  868.25  5207.8  867.49  5258.4  869.74  5275.4  869.01  5394.4  871.00
#Mann=5,-1,0
  4200.8    0.05       0  4582.9    0.12       0  4995.1    0.07       0
  5011.0    0.12       0  5275.4    0.05       0
Bank Sta=4995.1,5011
Exp/Cntr=0.3,0.1

Type RM Length L Ch R = 1,91131,442,442,442
BEGIN DESCRIPTION:
Oliver Creek 107.0
END DESCRIPTION:
XS GIS Cut Line= 3
      2274851.75      7108923.30      2274607.41      7108209.78
      2274371.63      7107922.56
#Sta/Elev= 30
  4245.8  863.26  4259.9  862.87  4312.7  857.74  4449.9  849.06  4563.2  843.74
  4642.9  841.18  4746.1  839.60  4851.3  835.81  4904.6  835.15  4936.3  836.10
  4957.5  835.22  4968.1  832.81  4968.5  831.26  4970.5  830.76  4984.4  831.26
  5026.6  834.79  5034.5  838.03  5040.9  838.64  5048.8  845.61  5063.2  849.92
  5069.6  850.60  5077.3  855.51  5084.0  857.30  5147.9  867.04  5184.3  866.67
  5240.4  868.47  5261.2  867.44  5310.8  868.67  5325.1  867.72  5371.6  868.04
#Mann=5,-1,0
  4245.8    0.05       0  4563.2    0.12       0  4968.5    0.07       0
  4984.4    0.12       0  5184.3    0.05       0
Bank Sta=4968.5,4984.4
Exp/Cntr=0.3,0.1

Type RM Length L Ch R = 1,90689,413,413,413
BEGIN DESCRIPTION:
Oliver Creek 106.0
END DESCRIPTION:
XS GIS Cut Line= 3
      2274932.04      7108942.85      2275002.80      7108333.14
      2275300.98      7107955.72
#Sta/Elev= 30
  4386.2  864.15  4429.3  863.34  4459.5  861.58  4530.0  854.83  4576.0  851.48
  4620.6  849.73  4681.0  843.52  4741.4  840.85  4771.6  838.43  4801.8  838.07
  4833.0  835.56  4862.2  832.70  4912.6  831.23  4917.4  830.24  4919.4  829.74
  4934.0  830.24  5014.2  830.26  5020.6  833.17  5035.0  835.87  5063.9  836.47
  5099.2  835.65  5113.6  836.91  5163.3  837.80  5177.7  839.97  5199.2  840.58
  5341.2  850.21  5355.6  852.55  5370.1  853.39  5411.8  860.05  5481.0  864.40
#Mann=5,-1,0
  4386.2    0.05       0  4833.0    0.12       0  4917.4    0.07       0
  4934.0    0.12       0  5199.2    0.05       0
Bank Sta=4917.4,4934
Exp/Cntr=0.3,0.1

Type RM Length L Ch R = 1,90276,463,463,463
BEGIN DESCRIPTION:
Oliver Creek 105.0
END DESCRIPTION:
XS GIS Cut Line= 3
      2275066.60      7109027.45      2275298.89      7108580.28
      2275510.73      7107974.02
#Sta/Elev= 30
  4496.1  861.22  4571.8  859.02  4770.9  849.47  4808.7  846.82  4815.1  845.31
  4831.3  845.16  4842.9  842.11  4875.8  838.88  4897.9  838.13  4903.6  840.84
  4910.2  838.39  4925.7  836.81  4947.8  832.49  4989.0  830.31  4991.0  829.81
  5005.6  830.31  5041.6  830.65  5046.9  831.38  5053.3  834.27  5063.8  835.43
  5112.2  835.06  5134.7  836.60  5222.6  838.87  5290.0  839.43  5307.5  841.40
  5368.8  844.94  5424.0  849.52  5465.7  856.85  5496.7  860.16  5642.2  865.90
#Mann=5,-1,0
  4496.1    0.05       0  4989.0   0.033       0  5005.6    0.05       0
  5112.2    0.12       0  5368.8    0.05       0
Bank Sta=4989,5005.6
Exp/Cntr=0.3,0.1

Type RM Length L Ch R = 1,89813,510,510,510
BEGIN DESCRIPTION:
Oliver Creek 104.0
END DESCRIPTION:
XS GIS Cut Line= 4
      2275268.05      7109633.72      2275726.32      7108801.99
      2275680.33      7108379.31      2275598.28      7107879.49
#Sta/Elev= 30
  3696.7  864.88  3876.4  862.74  4430.1  850.80  4670.6  843.14  4757.1  838.70
  4769.0  836.93  4799.2  834.90  4839.4  833.67  4899.8  834.26  4945.1  833.00
  4960.1  831.11  4970.2  832.55  5082.8  830.34  5084.8  829.84  5099.4  830.34
  5101.2  831.88  5108.4  833.40  5117.1  837.31  5131.6  840.90  5151.9  841.99
  5169.7  845.09  5192.4  846.77  5231.4  851.88  5236.0  851.44  5253.2  855.26
  5273.5  858.14  5303.9  860.26  5395.1  862.62  5537.0  863.99  5578.0  867.53
#Mann=5,-1,0
  3696.7    0.05       0  5082.8   0.033       0  5099.4    0.05       0
  5117.1    0.12       0  5231.4    0.05       0
Bank Sta=5082.8,5099.4
Exp/Cntr=0.3,0.1

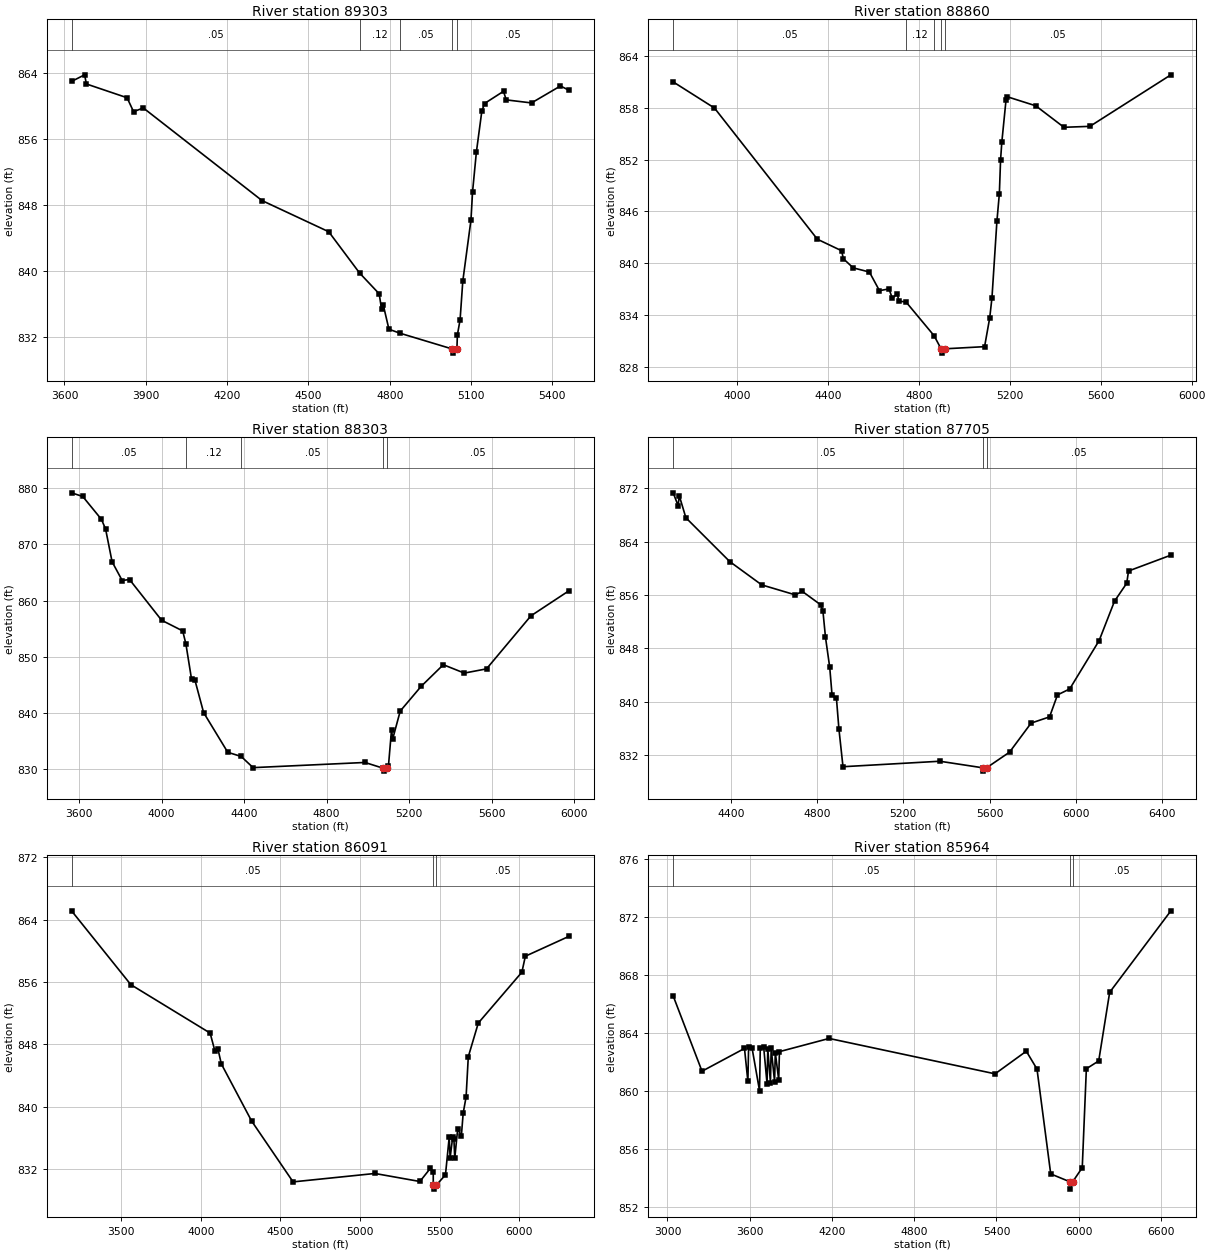
Type RM Length L Ch R = 1,89303,443,443,443
BEGIN DESCRIPTION:
Oliver Creek 103.0
END DESCRIPTION:
XS GIS Cut Line= 3
      2275363.06      7109599.93      2276129.00      7108460.00
      2276150.58      7107997.76
#Sta/Elev= 30
  3626.2  862.96  3674.3  863.76  3681.0  862.65  3831.0  860.98  3855.0  859.29
  3891.0  859.74  4329.0  848.50  4575.0  844.72  4688.6  839.72  4761.1  837.19
  4770.0  835.30  4776.0  835.86  4797.1  832.89  4838.5  832.40  5031.2  830.49
  5033.2  829.99  5047.9  830.49  5049.6  832.19  5059.6  834.03  5069.6  838.73
  5099.7  846.13  5105.7  849.60  5119.7  854.38  5139.7  859.32  5149.7  860.28
  5219.8  861.76  5229.8  860.72  5323.1  860.35  5430.0  862.41  5462.3  861.87
#Mann=5,-1,0
  3626.2    0.05       0  4688.6    0.12       0  4838.5    0.05       0
  5031.2   0.033       0  5047.9    0.05       0
Bank Sta=5031.2,5047.9
Exp/Cntr=0.3,0.1

Type RM Length L Ch R = 1,88860,557,557,557
BEGIN DESCRIPTION:
Oliver Creek 102.0
END DESCRIPTION:
XS GIS Cut Line= 5
      2275510.43      7109531.88      2275677.75      7109276.78
      2276472.94      7108712.56      2276558.56      7108505.55
      2276364.34      7107849.10
#Sta/Elev= 30
  3719.9  861.00  3901.5  857.97  4353.9  842.77  4460.9  841.43  4467.9  840.52
  4511.4  839.45  4582.7  838.97  4627.0  836.81  4668.8  837.01  4683.6  835.93
  4704.5  836.44  4713.2  835.59  4743.8  835.50  4867.5  831.58  4897.9  830.07
  4899.9  829.57  4914.6  830.07  5089.3  830.32  5111.9  833.66  5121.8  835.99
  5143.5  844.85  5154.3  848.04  5159.7  852.00  5165.1  854.01  5183.6  858.91
  5189.0  859.28  5314.5  858.23  5438.4  855.74  5552.6  855.85  5908.6  861.82
#Mann=5,-1,0
  3719.9    0.05       0  4743.8    0.12       0  4867.5    0.05       0
  4897.9   0.033       0  4914.6    0.05       0
Bank Sta=4897.9,4914.6
Exp/Cntr=0.3,0.1

Type RM Length L Ch R = 1,88303,598,598,598
BEGIN DESCRIPTION:
Oliver Creek 101.0
END DESCRIPTION:
XS GIS Cut Line= 4
      2277575.84      7109903.93      2277543.15      7109617.12
      2276958.84      7108629.61      2276407.62      7107823.92
#Sta/Elev= 30
  3563.9  879.16  3618.2  878.51  3708.8  874.44  3728.9  872.72  3760.4  866.90
  3809.4  863.57  3844.8  863.75  4000.3  856.51  4102.6  854.61  4118.1  852.30
  4145.5  846.02  4161.1  845.97  4204.0  840.09  4321.0  833.03  4386.0  832.29
  4443.8  830.30  4986.0  831.22  5075.9  830.18  5077.9  829.68  5094.0  830.18
  5099.8  830.55  5114.7  836.97  5120.8  835.44  5157.0  840.36  5258.3  844.75
  5365.9  848.60  5467.5  847.11  5575.2  847.86  5790.5  857.29  5976.2  861.78
#Mann=5,-1,0
  3563.9    0.05       0  4118.1    0.12       0  4386.0    0.05       0
  5075.9   0.033       0  5094.0    0.05       0
Bank Sta=5075.9,5094
Exp/Cntr=0.3,0.1

Type RM Length L Ch R = 1,87705,1614,1614,1614
BEGIN DESCRIPTION:
Oliver Creek 100.0
END DESCRIPTION:
XS GIS Cut Line= 3
      2277722.86      7109673.55      2277429.00      7108860.00
      2276593.44      7107680.46
#Sta/Elev= 30
  4131.4  871.30  4154.3  869.38  4159.6  870.87  4190.3  867.57  4394.3  861.00
  4542.3  857.52  4698.7  856.02  4730.6  856.55  4815.6  854.55  4826.3  853.68
  4838.4  849.68  4858.2  845.16  4869.0  840.97  4889.1  840.60  4900.7  835.98
  4919.7  830.30  5369.3  831.12  5568.2  830.14  5570.2  829.64  5586.3  830.14
  5692.9  832.48  5793.0  836.83  5878.7  837.76  5915.5  841.05  5972.2  841.94
  6108.8  849.18  6180.2  855.08  6236.8  857.76  6245.4  859.60  6441.9  861.97
#Mann=3,-1,0
  4131.4    0.05       0  5568.2   0.033       0  5586.3    0.05       0
Bank Sta=5568.2,5586.3
Exp/Cntr=0.3,0.1

Type RM Length L Ch R = 1,86091,127,127,127
BEGIN DESCRIPTION:
Oliver Creek 99.0
END DESCRIPTION:
XS GIS Cut Line= 5
      2277818.72      7109529.52      2278045.74      7108907.04
      2277994.22      7107759.48      2277996.42      7107685.47
      2276855.15      7107204.55
#Sta/Elev= 30
  3188.7  865.15  3560.7  855.67  4058.5  849.45  4088.6  847.14  4108.3  847.35
  4128.6  845.50  4318.8  838.16  4579.1  830.34  5092.9  831.42  5375.1  830.39
  5440.7  832.08  5459.0  831.63  5459.1  829.91  5461.1  829.41  5477.4  829.91
  5535.6  831.24  5559.3  836.12  5564.8  833.42  5581.3  836.15  5588.5  835.88
  5593.9  833.37  5612.2  837.11  5635.5  836.28  5646.8  839.16  5665.1  841.26
  5678.9  846.41  5741.7  850.74  6015.3  857.27  6037.0  859.32  6312.5  861.89
#Mann=3,-1,0
  3188.7    0.05       0  5459.1   0.033       0  5477.4    0.05       0
Bank Sta=5459.1,5477.4
Exp/Cntr=0.3,0.1

Type RM Length L Ch R = 1,85964,182,182,182
BEGIN DESCRIPTION:
Oliver Creek 98.8
END DESCRIPTION:
XS GIS Cut Line= 6
      2277879.89      7109663.27      2278171.79      7108896.08
      2278121.88      7107760.02      2278117.71      7107338.18
      2277845.72      7107107.16      2277848.33      7106213.48
#Sta/Elev= 30
  3042.0  866.57  3252.3  861.38  3562.1  862.95  3586.8  860.68  3592.2  863.06
  3616.9  863.00  3671.8  860.04  3677.2  862.95  3701.9  863.06  3726.7  860.51
  3732.0  862.92  3751.4  860.59  3756.8  862.95  3781.6  860.66  3786.9  862.67
  3811.7  860.79  3817.0  862.73  4179.2  863.64  5390.0  861.20  5617.8  862.76
  5695.8  861.53  5795.9  854.30  5937.3  853.75  5939.3  853.25  5955.6  853.75
  6025.9  854.73  6055.9  861.55  6145.9  862.09  6225.9  866.82  6672.4  872.44
#Mann=3,-1,0
  3042.0    0.05       0  5937.3   0.033       0  5955.6    0.05       0
Bank Sta=5937.3,5955.6
Exp/Cntr=0.3,0.1

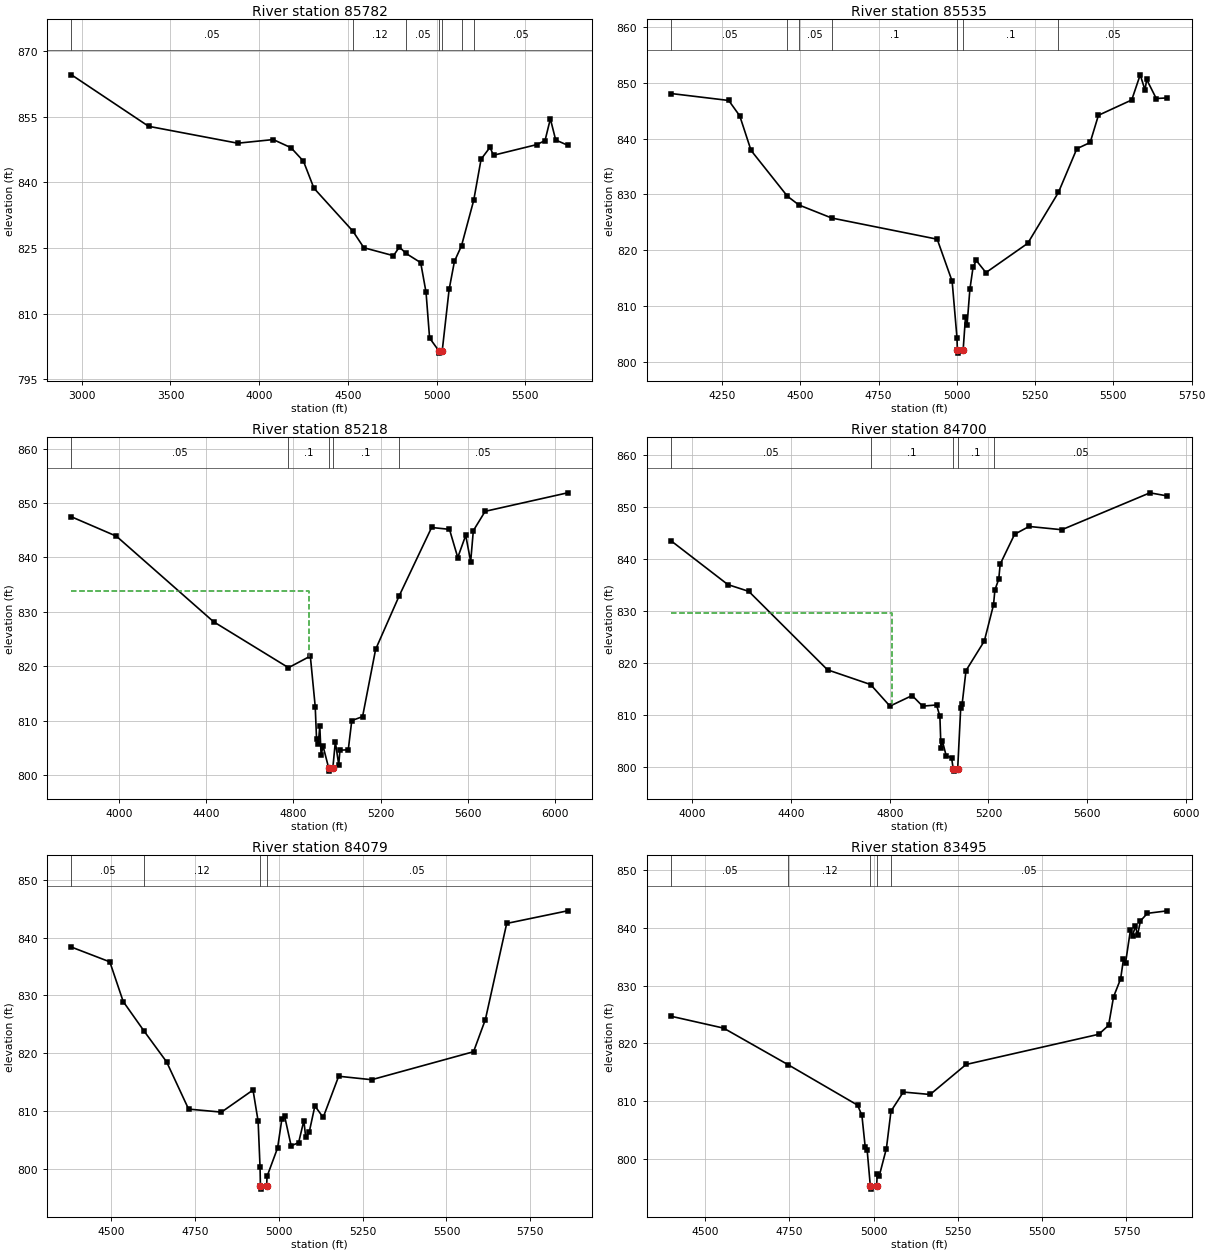
Type RM Length L Ch R = 1,85782,247,247,247
BEGIN DESCRIPTION:
Oliver Creek 98.5
END DESCRIPTION:
XS GIS Cut Line= 4
      2277980.82      7109735.92      2278354.77      7108909.33
      2278303.24      7107761.77      2278330.40      7107023.32
#Sta/Elev= 30
  2942.3  864.53  3376.8  852.77  3878.9  848.91  4079.1  849.74  4179.2  847.88
  4249.3  844.80  4308.4  838.63  4528.0  828.81  4589.6  825.03  4756.6  823.21
  4789.8  825.19  4827.6  823.72  4909.9  821.62  4940.0  814.85  4960.0  804.40
  5012.7  801.45  5014.7  800.95  5031.1  801.45  5070.1  815.50  5100.1  821.93
  5139.9  825.48  5208.6  835.86  5250.2  845.26  5300.2  847.96  5320.2  846.16
  5564.2  848.59  5610.4  849.51  5640.5  854.48  5670.5  849.64  5737.2  848.46
#Mann=7,-1,0
  2942.3    0.05       0  4528.0    0.12       0  4827.6    0.05       0
  5012.7   0.033       0  5031.1    0.05       0  5139.9    0.12       0
  5208.6    0.05       0
Bank Sta=5012.7,5031.1
Exp/Cntr=0.3,0.1

Type RM Length L Ch R = 1,85535,317,317,317
BEGIN DESCRIPTION:
Mapping XS d8a5805e
END DESCRIPTION:
XS GIS Cut Line= 3
      2278933.31      7108582.39      2278597.08      7107960.11
      2278397.80      7107105.44
#Sta/Elev= 30
  4087.5  848.10  4270.9  846.86  4306.2  844.09  4342.2  837.90  4458.4  829.68
  4495.2  828.11  4599.9  825.77  4937.0  821.97  4984.7  814.43  5000.3  804.21
  5001.4  802.03  5003.4  801.53  5019.8  802.03  5027.3  807.95  5032.4  806.58
  5041.4  812.98  5051.6  816.96  5061.9  818.15  5092.7  815.98  5226.2  821.23
  5324.2  830.35  5383.1  838.20  5425.7  839.32  5452.1  844.20  5558.5  846.95
  5585.6  851.46  5601.0  848.72  5606.2  850.63  5636.9  847.21  5672.4  847.32
#Mann=7,-1,0
  4087.5    0.05       0  4458.4    0.12       0  4495.2    0.05       0
  4599.9     0.1       0  5001.4    0.05       0  5019.8     0.1       0
  5324.2    0.05       0
Bank Sta=5001.4,5019.8
Exp/Cntr=0.3,0.1

Type RM Length L Ch R = 1,85218,518,518,518
BEGIN DESCRIPTION:
Oliver Creek 98.0
END DESCRIPTION:
XS GIS Cut Line= 3
      2279431.15      7108545.92      2278728.84      7107549.93
      2278226.28      7106618.80
#Sta/Elev= 30
  3781.3  847.46  3987.5  843.90  4433.4  828.18  4777.3  819.73  4877.6  821.86
  4900.1  812.56  4906.2  806.61  4914.3  805.79  4921.0  808.97  4927.1  803.65
  4935.8  805.35  4962.3  801.22  4964.3  800.72  4980.7  801.22  4992.4  806.11
  5007.9  801.89  5013.6  804.57  5051.7  804.64  5067.9  810.01  5117.4  810.74
  5177.3  823.10  5284.6  832.86  5434.3  845.50  5516.2  845.16  5554.3  839.98
  5590.8  844.06  5613.6  839.24  5625.7  844.91  5680.0  848.47  6058.1  851.87
#Mann=5,-1,0
  3781.3    0.05       0  4777.3     0.1       0  4962.3    0.05       0
  4980.7     0.1       0  5284.6    0.05       0
#XS Ineff=2,0
    0.00 4873.00  833.79               0
Permanent Ineff=
       F       F
Bank Sta=4962.3,4980.7
Exp/Cntr=0.3,0.1

Type RM Length L Ch R = 1,84700,621,621,621
BEGIN DESCRIPTION:
Oliver Creek 97.0
END DESCRIPTION:
XS GIS Cut Line= 3
      2279386.84      7108366.01      2279138.56      7107309.11
      2278668.32      7106513.57
#Sta/Elev= 30
  3915.2  843.50  4144.2  835.12  4229.1  833.81  4548.0  818.72  4722.5  815.89
  4800.9  811.74  4890.9  813.77  4933.3  811.73  4989.7  811.96  5003.3  809.78
  5007.7  803.76  5013.5  805.01  5029.2  802.12  5050.6  801.83  5057.1  799.73
  5059.1  799.23  5075.5  799.73  5087.7  811.42  5093.5  812.15  5109.1  818.57
  5183.3  824.25  5220.6  831.22  5226.2  834.09  5241.8  836.16  5247.6  839.05
  5306.1  844.80  5364.7  846.30  5497.3  845.67  5854.3  852.77  5925.0  852.17
#Mann=5,-1,0
  3915.2    0.05       0  4722.5     0.1       0  5057.1    0.05       0
  5075.5     0.1       0  5220.6    0.05       0
#XS Ineff=2,0
    0.00 4807.70  829.68               0
Permanent Ineff=
       F       F
Bank Sta=5057.1,5075.5
Exp/Cntr=0.3,0.1

Type RM Length L Ch R = 1,84079,584,584,584
BEGIN DESCRIPTION:
Mapping XS ec51a29d
END DESCRIPTION:
XS GIS Cut Line= 3
      2279806.42      7107697.49      2279472.75      7106605.38
      2279217.80      7106385.68
#Sta/Elev= 30
  4382.3  838.34  4496.6  835.79  4536.5  828.93  4598.9  823.81  4665.8  818.51
  4731.4  810.34  4829.3  809.82  4923.4  813.64  4938.6  808.25  4944.3  800.37
  4945.5  797.01  4947.5  796.51  4964.0  797.01  4965.2  798.70  4996.6  803.62
  5009.4  808.61  5017.5  809.13  5037.0  804.00  5059.3  804.54  5075.0  808.37
  5080.3  805.50  5090.7  806.30  5107.8  810.89  5132.5  808.90  5178.7  816.02
  5277.0  815.42  5580.7  820.26  5615.9  825.81  5679.5  842.43  5860.8  844.61
#Mann=4,-1,0
  4382.3    0.05       0  4598.9    0.12       0  4945.5    0.05       0
  4964.0    0.05       0
Bank Sta=4945.5,4964
Exp/Cntr=0.3,0.1

Type RM Length L Ch R = 1,83495,92,92,92
BEGIN DESCRIPTION:
Oliver Creek 95.0
END DESCRIPTION:
XS GIS Cut Line= 4
      2280356.72      7107368.71      2280185.28      7106988.94
      2280028.55      7106894.81      2279324.74      7106381.18
#Sta/Elev= 30
  4400.5  824.69  4555.6  822.65  4747.9  816.30  4952.8  809.36  4965.6  807.59
  4975.3  802.17  4981.1  801.64  4990.6  795.37  4992.6  794.87  5009.1  795.37
  5011.1  797.40  5017.3  797.21  5038.2  801.88  5051.8  808.32  5088.4  811.62
  5167.9  811.20  5274.5  816.38  5667.9  821.59  5697.0  823.13  5711.7  828.05
  5732.6  831.14  5741.1  834.51  5747.2  833.88  5761.9  839.62  5768.1  838.60
  5776.6  840.30  5782.8  838.66  5791.3  841.14  5812.1  842.46  5871.3  842.89
#Mann=5,-1,0
  4400.5    0.05       0  4747.9    0.12       0  4990.6    0.07       0
  5009.1    0.12       0  5051.8    0.05       0
Bank Sta=4990.6,5009.1
Exp/Cntr=0.3,0.1

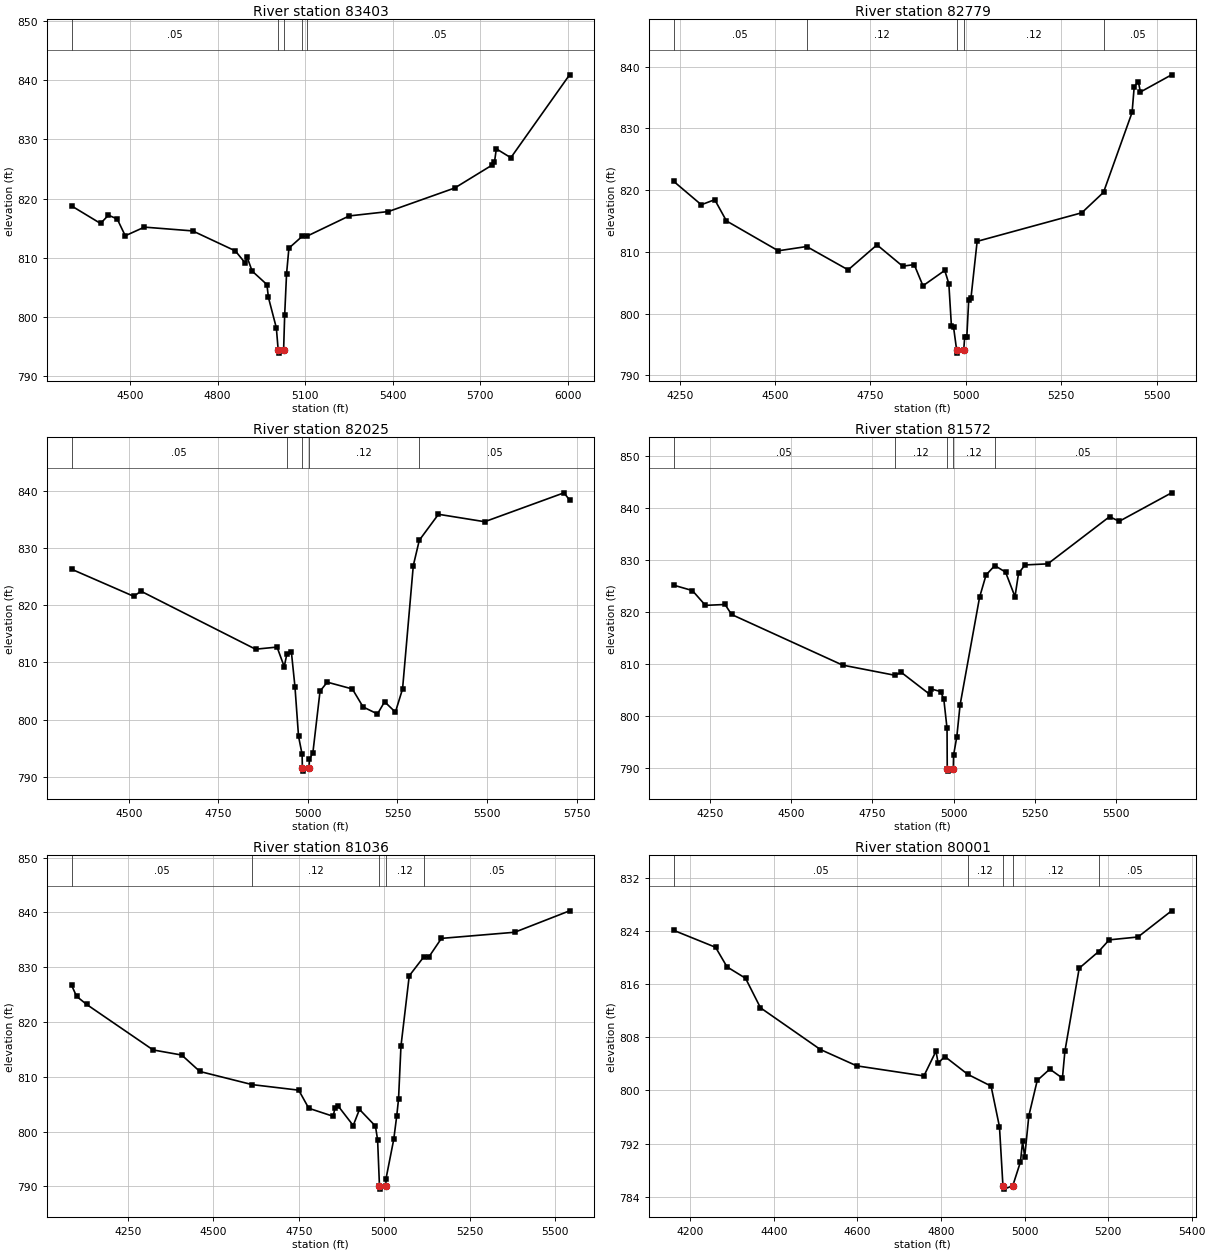
Type RM Length L Ch R = 1,83403,624,624,624
BEGIN DESCRIPTION:
Oliver Creek 94.0
END DESCRIPTION:
XS GIS Cut Line= 4
      2280682.22      7107143.00      2280280.77      7106876.09
      2280053.86      7106813.23      2279280.51      7106196.32
#Sta/Elev= 30
  4299.7  818.78  4399.0  815.82  4426.1  817.22  4456.2  816.57  4483.7  813.74
  4549.3  815.20  4714.7  814.56  4861.1  811.18  4895.4  809.10  4900.6  810.23
  4918.5  807.78  4969.2  805.50  4974.4  803.32  5001.5  798.19  5007.9  794.42
  5009.9  793.92  5026.4  794.42  5030.1  800.38  5036.5  807.30  5044.6  811.65
  5091.1  813.69  5106.9  813.68  5251.1  817.09  5385.6  817.83  5613.0  821.81
  5741.1  825.68  5749.1  826.19  5755.5  828.42  5805.2  826.92  6006.5  840.92
#Mann=5,-1,0
  4299.7    0.05       0  5007.9   0.033       0  5026.4    0.05       0
  5091.1    0.12       0  5106.9    0.05       0
Bank Sta=5007.9,5026.4
Exp/Cntr=0.3,0.1

Type RM Length L Ch R = 1,82779,754,754,754
BEGIN DESCRIPTION:
Oliver Creek 93.0
END DESCRIPTION:
XS GIS Cut Line= 3
      2280877.57      7107156.07      2280558.83      7106459.54
      2280305.43      7105983.48
#Sta/Elev= 30
  4234.0  821.44  4306.7  817.63  4341.9  818.45  4372.6  815.01  4508.5  810.17
  4582.9  810.86  4691.6  807.08  4767.2  811.13  4834.5  807.67  4864.7  807.94
  4887.7  804.50  4944.8  806.99  4955.5  804.85  4962.3  797.96  4967.8  797.83
  4976.0  794.09  4978.0  793.59  4994.6  794.09  4997.0  796.20  5002.6  796.20
  5007.7  802.26  5013.4  802.45  5029.7  811.70  5304.0  816.33  5360.9  819.64
  5435.8  832.59  5441.4  836.75  5452.1  837.57  5457.7  835.90  5539.3  838.68
#Mann=5,-1,0
  4234.0    0.05       0  4582.9    0.12       0  4976.0    0.07       0
  4994.6    0.12       0  5360.9    0.05       0
Bank Sta=4976,4994.6
Exp/Cntr=0.3,0.1

Type RM Length L Ch R = 1,82025,453,453,453
BEGIN DESCRIPTION:
Oliver Creek 92.5
END DESCRIPTION:
XS GIS Cut Line= 3
      2281254.20      7107243.67      2281255.94      7106583.88
      2281297.15      7105854.44
#Sta/Elev= 30
  4340.2  826.29  4513.9  821.55  4533.9  822.45  4853.9  812.31  4913.9  812.68
  4933.9  809.26  4941.5  811.52  4953.9  811.83  4963.9  805.74  4973.9  797.08
  4983.9  793.92  4984.6  791.50  4986.6  791.00  5003.2  791.50  5004.4  793.08
  5013.9  794.20  5033.9  804.97  5054.0  806.55  5124.1  805.36  5154.1  802.22
  5194.2  800.99  5214.2  803.12  5244.3  801.31  5264.3  805.37  5294.3  826.93
  5311.1  831.36  5364.5  835.89  5493.6  834.59  5715.0  839.64  5730.6  838.38
#Mann=5,-1,0
  4340.2    0.05       0  4941.5    0.12       0  4984.6    0.07       0
  5003.2    0.12       0  5311.1    0.05       0
Bank Sta=4984.6,5003.2
Exp/Cntr=0.3,0.1

Type RM Length L Ch R = 1,81572,536,536,536
BEGIN DESCRIPTION:
Oliver Creek 92.0
END DESCRIPTION:
XS GIS Cut Line= 3
      2281470.35      7107217.66      2281561.50      7106359.99
      2281535.45      7105689.00
#Sta/Elev= 30
  4137.5  825.15  4195.5  824.11  4235.7  821.27  4296.1  821.44  4316.2  819.52
  4658.1  809.81  4818.3  807.87  4839.3  808.40  4926.8  804.19  4931.8  805.22
  4959.8  804.74  4969.8  803.34  4979.9  797.67  4980.5  789.97  4982.5  789.47
  4999.3  789.97  5000.0  792.52  5010.0  796.08  5020.0  802.14  5080.1  822.82
  5100.1  827.10  5126.9  828.90  5160.1  827.65  5189.2  822.93  5200.1  827.42
  5220.2  829.03  5290.2  829.23  5480.4  838.28  5510.4  837.40  5671.5  842.86
#Mann=5,-1,0
  4137.5    0.05       0  4818.3    0.12       0  4980.5    0.07       0
  4999.3    0.12       0  5126.9    0.05       0
Bank Sta=4980.5,4999.3
Exp/Cntr=0.3,0.1

Type RM Length L Ch R = 1,81036,1035,1035,1035
BEGIN DESCRIPTION:
Oliver Creek 91.0
END DESCRIPTION:
XS GIS Cut Line= 3
      2281729.01      7107259.97      2282081.30      7106415.83
      2282255.82      7105903.33
#Sta/Elev= 30
  4085.3  826.70  4099.9  824.68  4129.1  823.21  4323.7  814.89  4407.4  813.96
  4460.4  810.96  4613.6  808.56  4749.5  807.55  4778.8  804.25  4850.2  802.78
  4855.6  804.35  4865.5  804.60  4908.8  801.10  4927.1  804.04  4973.8  800.99
  4980.1  798.48  4985.6  789.99  4987.6  789.49  5004.4  789.99  5004.6  791.37
  5027.3  798.57  5036.0  802.83  5041.3  805.92  5048.4  815.59  5072.6  828.42
  5115.2  831.88  5130.1  831.87  5166.7  835.25  5380.9  836.37  5541.4  840.28
#Mann=5,-1,0
  4085.3    0.05       0  4613.6    0.12       0  4985.6    0.07       0
  5004.4    0.12       0  5115.2    0.05       0
Bank Sta=4985.6,5004.4
Exp/Cntr=0.3,0.1

Type RM Length L Ch R = 1,80001,511,511,511
BEGIN DESCRIPTION:
Oliver Creek 90.0
END DESCRIPTION:
XS GIS Cut Line= 3
      2283322.66      7107334.21      2283107.45      7107004.87
      2283029.00      7106209.96
#Sta/Elev= 30
  4159.7  824.12  4260.3  821.56  4287.7  818.61  4332.0  816.90  4367.8  812.45
  4511.2  806.17  4598.2  803.71  4759.0  802.19  4788.0  805.93  4793.0  804.13
  4809.2  805.11  4863.8  802.44  4919.8  800.66  4939.9  794.54  4948.2  785.65
  4950.6  785.15  4971.7  785.65  4990.1  789.24  4995.3  792.35  5000.3  789.99
  5010.2  796.19  5030.3  801.51  5060.4  803.22  5090.6  801.86  5096.5  805.89
  5130.8  818.41  5177.3  820.92  5202.6  822.68  5271.5  823.11  5351.9  827.05
#Mann=5,-1,0
  4159.7    0.05       0  4863.8    0.12       0  4948.2    0.07       0
  4971.7    0.12       0  5177.3    0.05       0
Bank Sta=4948.2,4971.7
Exp/Cntr=0.3,0.1

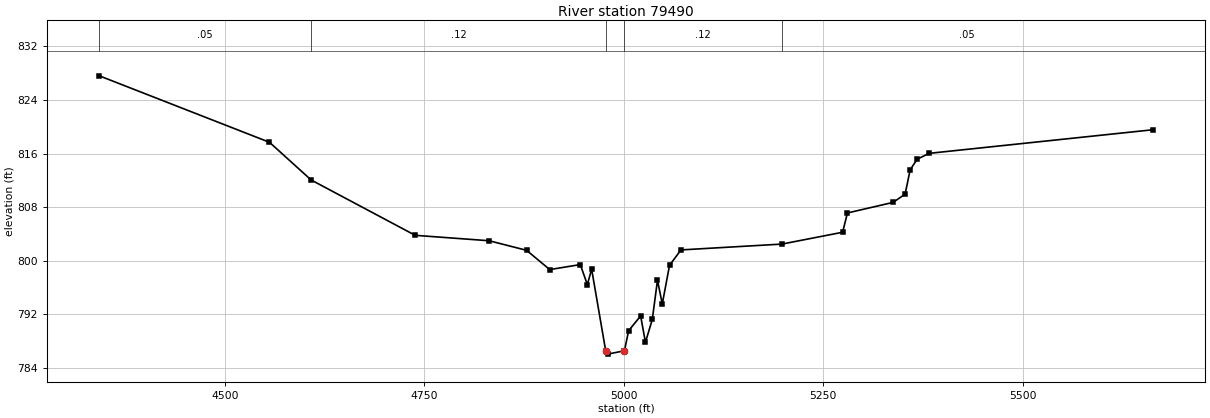
Type RM Length L Ch R = 1,79490,681,681,681
BEGIN DESCRIPTION:
Oliver Creek 89.0
END DESCRIPTION:
XS GIS Cut Line= 3
      2283797.16      7107063.54      2283536.60      7106458.46
      2283173.33      7105905.99
#Sta/Elev= 30
  4342.9  827.61  4556.1  817.68  4608.3  812.05  4738.7  803.78  4831.3  802.97
  4878.3  801.54  4907.3  798.66  4945.6  799.41  4954.4  796.42  4959.8  798.72
  4977.4  786.53  4979.7  786.03  5000.9  786.53  5006.1  789.52  5021.2  791.74
  5027.2  787.80  5035.8  791.21  5042.3  797.08  5048.3  793.52  5057.4  799.30
  5071.7  801.60  5198.1  802.47  5274.3  804.24  5280.3  807.12  5337.5  808.70
  5352.6  809.93  5358.9  813.56  5367.7  815.15  5382.8  816.03  5662.9  819.55
#Mann=5,-1,0
  4342.9    0.05       0  4608.3    0.12       0  4977.4    0.07       0
  5000.9    0.12       0  5198.1    0.05       0
Bank Sta=4977.4,5000.9
Exp/Cntr=0.3,0.1