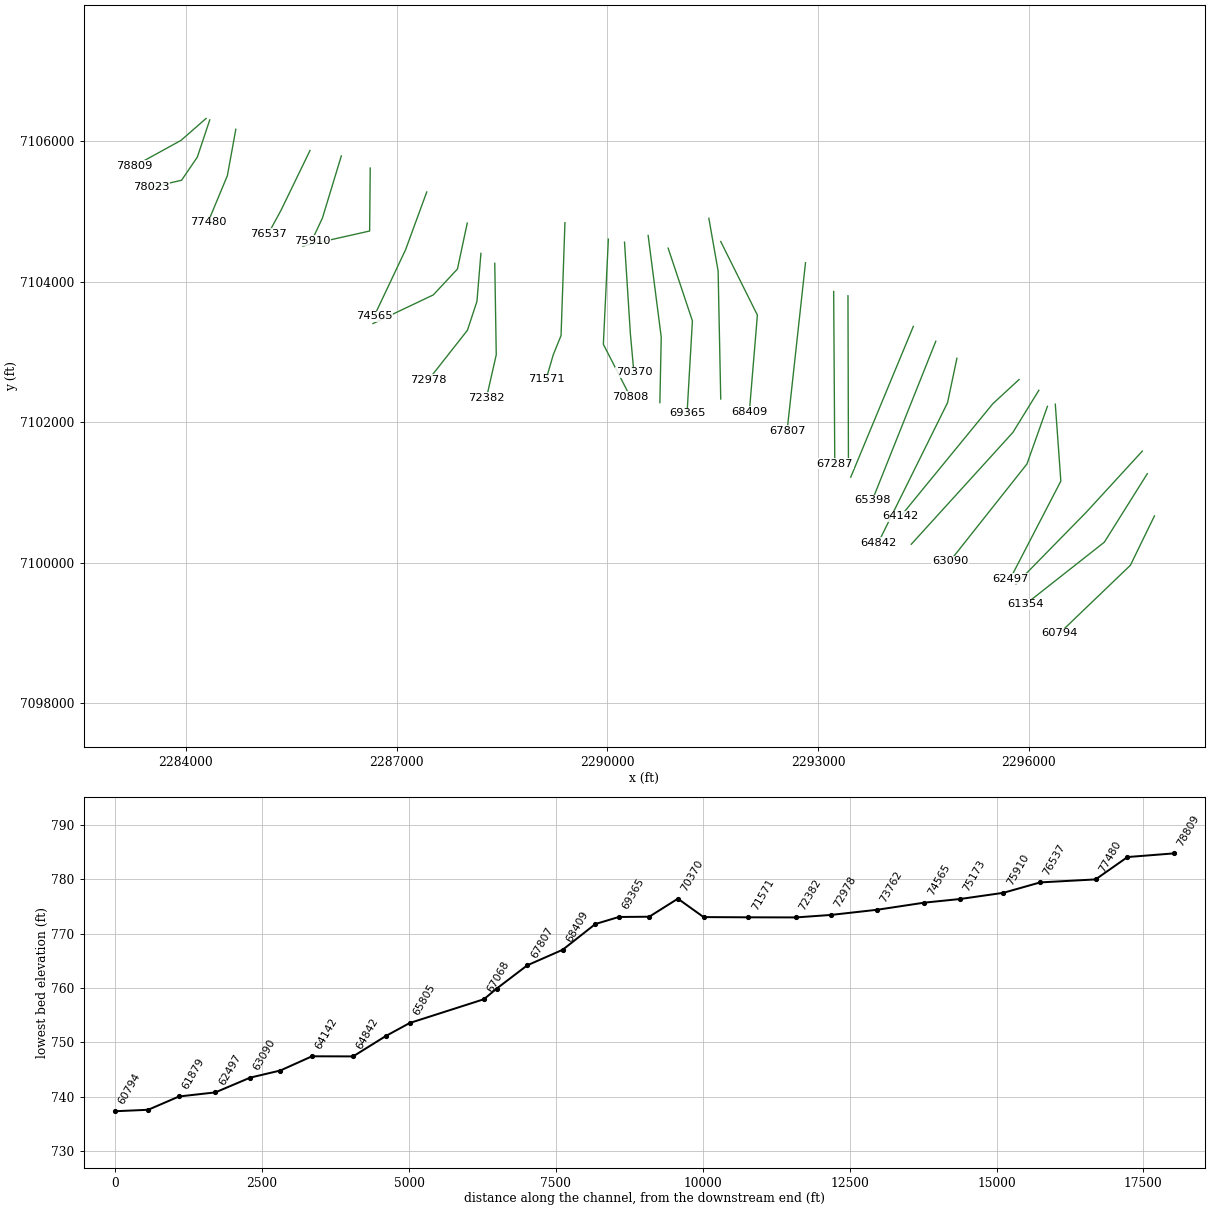
HEC-RAS study Oliver Creek.prj: Oliver Creek Base Level Engineering

--- Oliver Creek.g01 (geometry) --- (continued)

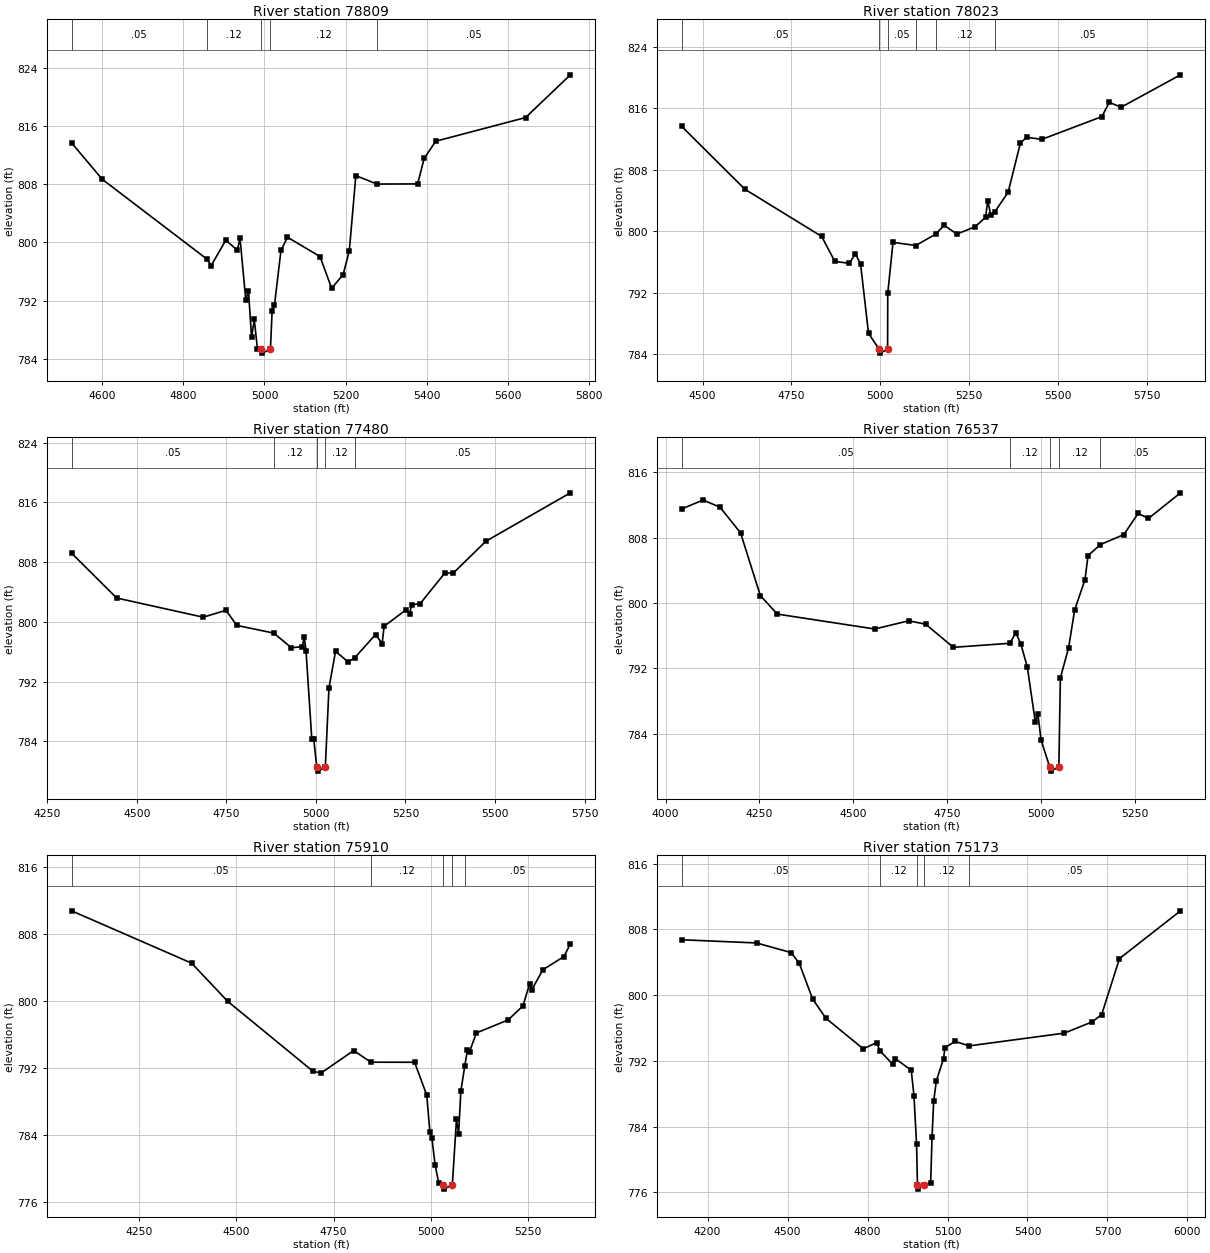
Type RM Length L Ch R = 1,78809,786,786,786
BEGIN DESCRIPTION:
Oliver Creek 88.0
END DESCRIPTION:
XS GIS Cut Line= 3
      2284287.03      7106328.24      2283929.02      7106015.00
      2283267.93      7105651.15
#Sta/Elev= 30
  4524.3  813.66  4600.0  808.66  4857.2  797.74  4868.6  796.81  4904.6  800.30
  4933.1  798.92  4939.7  800.60  4954.0  792.04  4960.6  793.34  4968.2  786.95
  4974.9  789.43  4982.5  785.42  4991.1  785.29  4993.5  784.79  5014.7  785.29
  5018.9  790.61  5024.6  791.35  5040.7  798.89  5056.8  800.71  5137.0  798.05
  5165.7  793.69  5194.1  795.58  5209.3  798.86  5225.4  809.17  5277.2  808.01
  5377.9  808.03  5393.9  811.53  5422.4  813.89  5643.9  817.14  5754.6  823.01
#Mann=5,-1,0
  4524.3    0.05       0  4857.2    0.12       0  4991.1    0.07       0
  5014.7    0.12       0  5277.2    0.05       0
Bank Sta=4991.1,5014.7
Exp/Cntr=0.3,0.1

Type RM Length L Ch R = 1,78023,543,543,543
BEGIN DESCRIPTION:
Oliver Creek 87.0
END DESCRIPTION:
XS GIS Cut Line= 4
      2284339.09      7106307.38      2284162.27      7105777.40
      2283938.03      7105447.76      2283503.85      7105346.54
#Sta/Elev= 30
  4441.3  813.66  4619.2  805.47  4835.2  799.32  4872.1  796.07  4912.9  795.82
  4930.0  797.06  4944.5  795.74  4966.9  786.69  4997.0  784.62  4999.4  784.12
  5020.6  784.62  5021.0  791.91  5035.8  798.56  5099.7  798.14  5156.0  799.63
  5179.5  800.77  5215.4  799.64  5266.3  800.57  5296.2  801.82  5302.2  803.96
  5311.1  802.07  5321.4  802.48  5359.7  805.08  5394.3  811.52  5412.0  812.24
  5454.5  811.97  5623.6  814.94  5644.1  816.79  5677.6  816.16  5844.5  820.38
#Mann=6,-1,0
  4441.3    0.05       0  4997.0   0.033       0  5020.6    0.05       0
  5099.7    0.05       0  5156.0    0.12       0  5321.4    0.05       0
Bank Sta=4997,5020.6
Exp/Cntr=0.3,0.1

Type RM Length L Ch R = 1,77480,943,943,943
BEGIN DESCRIPTION:
Oliver Creek 86.0
END DESCRIPTION:
XS GIS Cut Line= 3
      2284710.30      7106173.88      2284590.10      7105513.02
      2284313.34      7104847.04
#Sta/Elev= 30
  4317.7  809.19  4443.6  803.19  4685.3  800.62  4748.8  801.55  4779.0  799.52
  4882.2  798.49  4931.5  796.53  4962.0  796.67  4967.3  798.01  4972.4  796.06
  4988.4  784.34  4993.7  784.34  5002.5  780.50  5004.9  780.00  5026.2  780.50
  5036.4  791.16  5054.8  796.06  5090.1  794.61  5108.8  795.21  5166.5  798.30
  5184.9  797.09  5190.4  799.40  5252.6  801.65  5261.9  801.10  5267.3  802.31
  5290.5  802.40  5360.9  806.59  5382.5  806.48  5474.5  810.79  5710.6  817.28
#Mann=5,-1,0
  4317.7    0.05       0  4882.2    0.12       0  5002.5    0.07       0
  5026.2    0.12       0  5108.8    0.05       0
Bank Sta=5002.5,5026.2
Exp/Cntr=0.3,0.1

Type RM Length L Ch R = 1,76537,627,627,627
BEGIN DESCRIPTION:
Oliver Creek 85.6
END DESCRIPTION:
XS GIS Cut Line= 3
      2285766.54      7105871.09      2285355.18      7105021.89
      2285171.35      7104683.71
#Sta/Elev= 30
  4043.0  811.49  4100.0  812.58  4145.2  811.70  4199.8  808.56  4252.5  800.90
  4297.7  798.64  4557.2  796.82  4647.5  797.82  4692.7  797.41  4766.5  794.58
  4916.8  795.07  4933.1  796.34  4946.6  794.95  4963.6  792.16  4984.9  785.43
  4991.7  786.46  5000.1  783.27  5023.2  779.95  5025.7  779.45  5047.6  779.95
  5051.6  790.84  5073.5  794.51  5089.6  799.13  5117.2  802.86  5125.3  805.79
  5158.4  807.14  5220.7  808.36  5258.7  810.94  5286.3  810.33  5371.5  813.46
#Mann=5,-1,0
  4043.0    0.05       0  4916.8    0.12       0  5023.2    0.07       0
  5047.6    0.12       0  5158.4    0.05       0
Bank Sta=5023.2,5047.6
Exp/Cntr=0.3,0.1

Type RM Length L Ch R = 1,75910,737,737,737
BEGIN DESCRIPTION:
Oliver Creek 85.4
END DESCRIPTION:
XS GIS Cut Line= 3
      2286212.66      7105793.93      2285943.98      7104909.96
      2285792.15      7104584.87
#Sta/Elev= 30
  4076.1  810.81  4384.8  804.55  4477.4  799.99  4696.9  791.62  4717.8  791.42
  4801.4  794.10  4845.7  792.71  4958.2  792.70  4989.5  788.75  4997.3  784.42
  5002.7  783.59  5011.0  780.39  5020.1  778.30  5030.7  778.03  5033.1  777.53
  5055.2  778.03  5065.8  785.87  5071.3  784.16  5077.2  789.30  5087.4  792.30
  5094.1  794.20  5099.6  793.98  5117.0  796.21  5198.6  797.76  5236.8  799.44
  5253.8  802.07  5259.6  801.38  5288.0  803.76  5342.1  805.34  5358.8  806.86
#Mann=5,-1,0
  4076.1    0.05       0  4845.7    0.12       0  5030.7    0.07       0
  5055.2    0.12       0  5087.4    0.05       0
Bank Sta=5030.7,5055.2
Exp/Cntr=0.3,0.1

Type RM Length L Ch R = 1,75173,608,608,608
BEGIN DESCRIPTION:
Oliver Creek 85.0
END DESCRIPTION:
XS GIS Cut Line= 3
      2286624.20      7105621.13      2286615.93      7104723.97
      2285665.83      7104510.00
#Sta/Elev= 30
  4102.8  806.73  4383.9  806.34  4514.0  805.16  4544.0  803.85  4594.0  799.52
  4644.0  797.17  4784.0  793.46  4834.0  794.21  4846.3  793.24  4894.0  791.59
  4904.0  792.27  4964.0  790.85  4974.0  787.78  4984.0  781.84  4987.2  776.89
  4989.7  776.39  5011.7  776.89  5036.8  777.19  5041.9  782.68  5048.1  787.11
  5058.4  789.60  5085.2  792.26  5090.3  793.62  5128.4  794.36  5181.2  793.82
  5538.2  795.37  5642.6  796.74  5678.3  797.63  5745.1  804.44  5973.9  810.25
#Mann=5,-1,0
  4102.8    0.05       0  4846.3    0.12       0  4987.2    0.07       0
  5011.7    0.12       0  5181.2    0.05       0
Bank Sta=4987.2,5011.7
Exp/Cntr=0.3,0.1

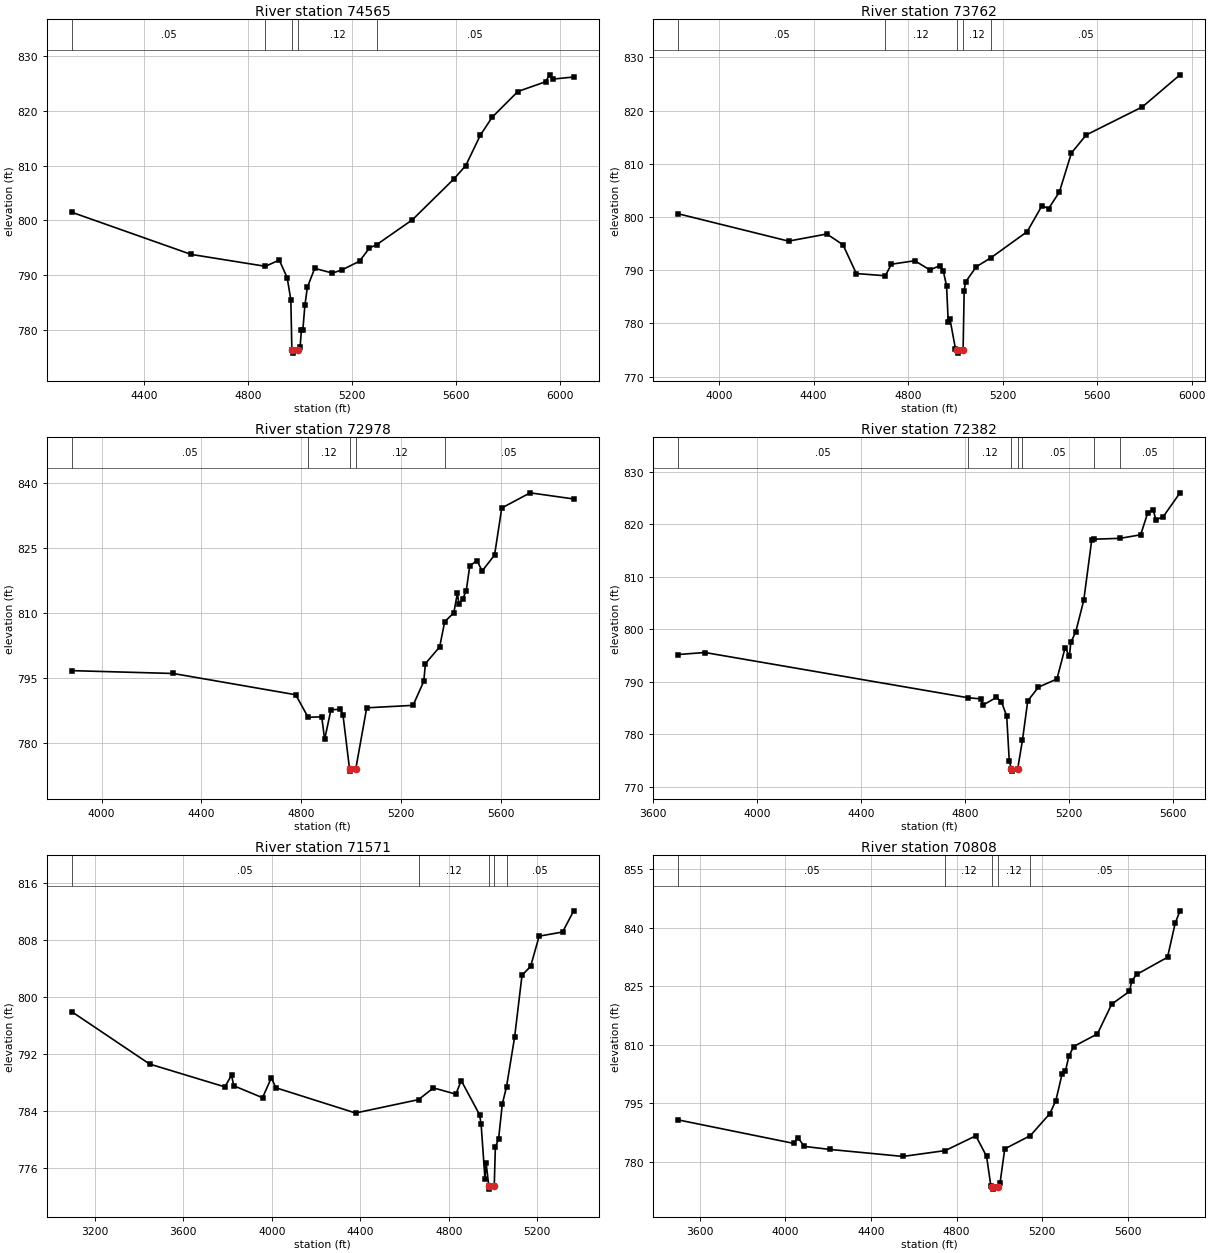
Type RM Length L Ch R = 1,74565,803,803,803
BEGIN DESCRIPTION:
Oliver Creek 84.8
END DESCRIPTION:
XS GIS Cut Line= 3
      2287429.21      7105280.55      2287127.60      7104456.62
      2286678.35      7103506.03
#Sta/Elev= 30
  4122.6  801.49  4581.1  793.78  4867.0  791.60  4919.9  792.75  4950.4  789.51
  4964.5  785.46  4968.4  776.22  4970.9  775.72  4993.4  776.22  5000.0  776.76
  5005.1  780.03  5010.6  779.95  5018.4  784.44  5027.9  787.76  5056.2  791.23
  5124.4  790.36  5162.2  790.97  5228.5  792.54  5266.6  794.96  5293.7  795.54
  5431.4  800.11  5590.8  807.57  5636.3  810.00  5693.1  815.63  5738.4  818.89
  5836.9  823.58  5943.2  825.36  5958.5  826.63  5971.5  825.85  6051.4  826.23
#Mann=5,-1,0
  4122.6    0.05       0  4867.0    0.12       0  4968.4    0.07       0
  4993.4    0.12       0  5293.7    0.05       0
Bank Sta=4968.4,4993.4
Exp/Cntr=0.3,0.1

Type RM Length L Ch R = 1,73762,784,784,784
BEGIN DESCRIPTION:
Oliver Creek 84.6
END DESCRIPTION:
XS GIS Cut Line= 4
      2288005.98      7104837.35      2287866.43      7104182.34
      2287522.51      7103813.44      2286663.83      7103405.07
#Sta/Elev= 30
  3825.9  800.62  4293.5  795.47  4455.6  796.81  4523.9  794.79  4580.6  789.37
  4703.2  788.96  4729.1  791.13  4827.8  791.78  4891.8  790.06  4934.3  790.86
  4948.5  789.90  4962.6  787.05  4969.5  780.29  4976.8  780.85  5000.0  775.26
  5007.5  774.91  5010.0  774.41  5032.5  774.91  5037.1  786.15  5042.8  787.77
  5088.2  790.65  5151.0  792.36  5303.7  797.25  5366.3  802.12  5394.6  801.60
  5440.0  804.69  5491.1  812.04  5553.6  815.43  5791.8  820.72  5950.8  826.74
#Mann=5,-1,0
  3825.9    0.05       0  4703.2    0.12       0  5007.5    0.07       0
  5032.5    0.12       0  5151.0    0.05       0
Bank Sta=5007.5,5032.5
Exp/Cntr=0.3,0.1

Type RM Length L Ch R = 1,72978,596,596,596
BEGIN DESCRIPTION:
Oliver Creek 84.4
END DESCRIPTION:
XS GIS Cut Line= 4
      2288200.73      7104405.58      2288144.03      7103721.45
      2288008.66      7103309.60      2287456.35      7102607.38
#Sta/Elev= 30
  3880.0  796.70  4287.0  796.04  4778.5  791.12  4828.1  785.90  4882.7  786.02
  4894.3  780.79  4919.7  787.66  4957.5  787.75  4968.0  786.43  4994.2  773.96
  4996.7  773.46  5019.2  773.96  5063.1  788.10  5248.9  788.67  5292.1  794.23
  5298.6  798.33  5355.7  802.18  5375.9  808.01  5412.5  810.07  5426.9  814.60
  5433.3  812.07  5447.7  813.23  5462.2  815.12  5476.6  820.96  5505.5  822.12
  5526.3  819.75  5576.0  823.44  5604.9  834.32  5718.8  837.82  5893.4  836.40
#Mann=5,-1,0
  3880.0    0.05       0  4828.1    0.12       0  4994.2    0.07       0
  5019.2    0.12       0  5375.9    0.05       0
Bank Sta=4994.2,5019.2
Exp/Cntr=0.3,0.1

Type RM Length L Ch R = 1,72382,811,811,811
BEGIN DESCRIPTION:
Oliver Creek 84.2
END DESCRIPTION:
XS GIS Cut Line= 3
      2288397.78      7104263.41      2288418.99      7102959.99
      2288280.11      7102349.08
#Sta/Elev= 30
  3696.4  795.20  3799.8  795.58  4812.3  786.96  4860.0  786.76  4870.0  785.60
  4920.0  787.02  4940.0  786.20  4960.0  783.48  4970.0  774.96  4977.5  773.50
  4980.0  773.00  5002.5  773.50  5020.6  778.85  5041.0  786.37  5082.0  788.98
  5153.3  790.54  5184.6  796.49  5201.5  794.89  5206.6  797.51  5225.6  799.52
  5256.4  805.52  5287.1  817.02  5295.7  817.15  5396.6  817.32  5475.2  817.99
  5502.5  822.19  5523.4  822.80  5533.3  820.85  5561.4  821.40  5626.5  825.98
#Mann=7,-1,0
  3696.4    0.05       0  4812.3    0.12       0  4977.5    0.07       0
  5002.5    0.12       0  5020.6    0.05       0  5295.7   0.075       0
  5396.6    0.05       0
Bank Sta=4977.5,5002.5
Exp/Cntr=0.3,0.1

Type RM Length L Ch R = 1,71571,763,763,763
BEGIN DESCRIPTION:
Oliver Creek 84.0
END DESCRIPTION:
XS GIS Cut Line= 4
      2289397.19      7104841.81      2289341.70      7103234.52
      2289230.63      7102959.98      2289129.01      7102610.04
#Sta/Elev= 30
  3095.6  797.96  3447.6  790.60  3787.8  787.39  3817.8  789.04  3827.8  787.55
  3957.9  785.87  3997.9  788.68  4018.0  787.27  4378.2  783.72  4663.1  785.60
  4730.3  787.25  4831.9  786.37  4856.0  788.28  4939.2  783.46  4946.0  782.12
  4963.3  774.48  4968.7  776.66  4980.3  773.52  4982.8  773.02  5005.3  773.52
  5010.4  778.94  5024.9  780.08  5041.6  784.96  5060.7  787.41  5097.2  794.35
  5130.8  803.09  5169.5  804.32  5208.3  808.58  5314.1  809.16  5364.4  812.14
#Mann=5,-1,0
  3095.6    0.05       0  4663.1    0.12       0  4980.3    0.07       0
  5005.3    0.12       0  5060.7    0.05       0
Bank Sta=4980.3,5005.3
Exp/Cntr=0.3,0.1

Type RM Length L Ch R = 1,70808,438,438,438
BEGIN DESCRIPTION:
Oliver Creek 83.0
END DESCRIPTION:
XS GIS Cut Line= 3
      2290015.50      7104608.45      2289944.19      7103109.55
      2290329.02      7102359.96
#Sta/Elev= 30
  3499.4  790.79  4038.5  784.78  4058.5  786.27  4088.5  784.00  4208.7  783.22
  4549.0  781.43  4746.7  782.93  4889.4  786.71  4939.5  781.47  4959.5  773.91
  4967.0  773.56  4969.5  773.06  4992.0  773.56  5002.6  774.67  5024.5  783.37
  5143.9  786.76  5235.2  792.41  5263.0  795.73  5291.8  802.47  5307.4  803.23
  5323.9  807.12  5346.1  809.58  5457.1  812.81  5523.6  820.42  5606.5  823.69
  5618.0  826.44  5640.2  828.03  5784.3  832.43  5820.1  841.14  5842.6  844.32
#Mann=5,-1,0
  3499.4    0.05       0  4746.7    0.12       0  4967.0    0.07       0
  4992.0    0.12       0  5143.9    0.05       0
Bank Sta=4967,4992
Exp/Cntr=0.3,0.1

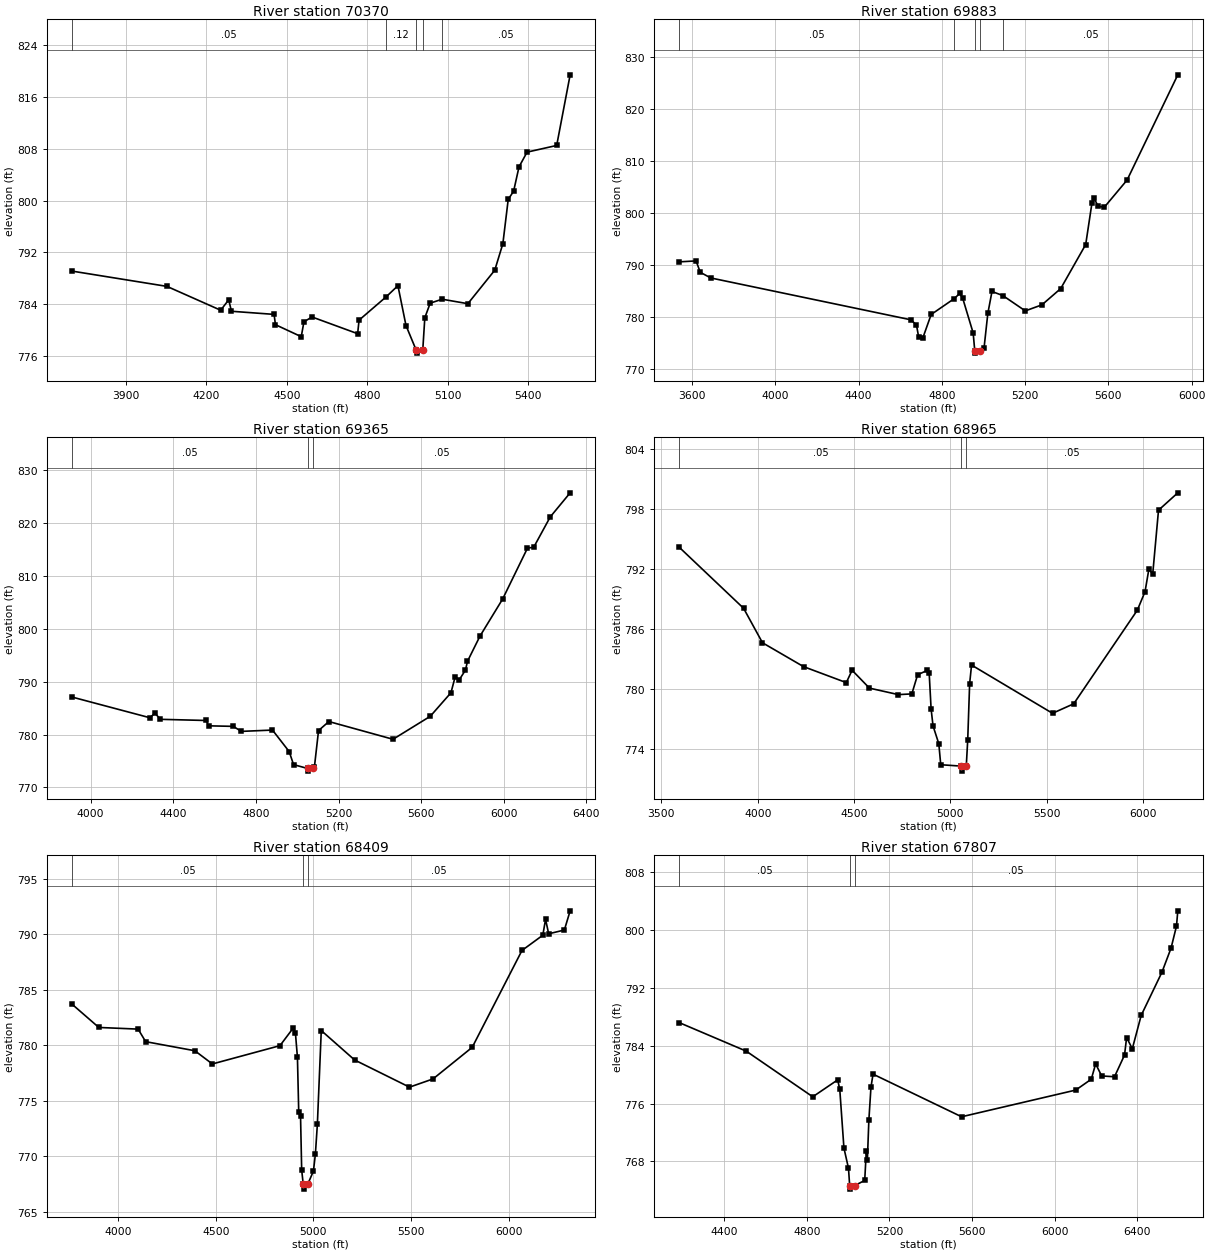
Type RM Length L Ch R = 1,70370,487,487,487
BEGIN DESCRIPTION:
Oliver Creek 82.0
END DESCRIPTION:
XS GIS Cut Line= 3
      2290245.53      7104565.05      2290329.00      7103260.00
      2290379.00      7102709.99
#Sta/Elev= 30
  3696.8  789.12  4052.6  786.75  4253.0  783.07  4283.0  784.68  4293.1  782.91
  4452.3  782.43  4457.3  780.84  4553.6  778.99  4563.6  781.28  4593.7  782.03
  4764.0  779.45  4769.3  781.54  4870.7  785.15  4914.3  786.86  4944.4  780.71
  4982.0  776.95  4984.5  776.45  5007.0  776.95  5014.6  781.90  5034.6  784.16
  5079.1  784.77  5175.2  784.08  5275.6  789.25  5305.8  793.34  5325.8  800.18
  5345.9  801.44  5366.0  805.19  5396.1  807.47  5506.6  808.50  5556.8  819.40
#Mann=5,-1,0
  3696.8    0.05       0  4870.7    0.12       0  4982.0    0.07       0
  5007.0    0.12       0  5079.1    0.05       0
Bank Sta=4982,5007
Exp/Cntr=0.3,0.1

Type RM Length L Ch R = 1,69883,518,518,518
BEGIN DESCRIPTION:
Oliver Creek 81.8
END DESCRIPTION:
XS GIS Cut Line= 3
      2290581.99      7104660.14      2290768.46      7103211.08
      2290749.01      7102277.69
#Sta/Elev= 30
  3539.0  790.65  3619.8  790.83  3640.0  788.64  3690.4  787.56  4652.5  779.52
  4678.5  778.50  4688.5  776.32  4708.7  776.01  4749.0  780.55  4860.5  783.61
  4885.9  784.59  4900.3  783.69  4950.7  777.00  4958.3  773.63  4960.8  773.13
  4983.3  773.63  5003.0  774.12  5021.1  780.74  5041.1  784.96  5093.2  784.18
  5201.1  781.24  5281.1  782.40  5371.2  785.52  5491.2  793.97  5521.2  801.92
  5531.2  802.89  5551.2  801.29  5581.2  801.16  5690.1  806.36  5933.6  826.55
#Mann=5,-1,0
  3539.0    0.05       0  4860.5    0.12       0  4958.3    0.07       0
  4983.3    0.12       0  5093.2    0.05       0
Bank Sta=4958.3,4983.3
Exp/Cntr=0.3,0.1

Type RM Length L Ch R = 1,69365,400,400,400
BEGIN DESCRIPTION:
Oliver Creek 81.6
END DESCRIPTION:
XS GIS Cut Line= 3
      2290866.91      7104479.49      2291212.40      7103443.17
      2291136.08      7102123.87
#Sta/Elev= 30
  3907.6  787.10  4286.5  783.17  4311.2  784.04  4337.5  782.87  4558.9  782.65
  4571.2  781.64  4690.6  781.54  4729.3  780.59  4880.3  780.84  4961.2  776.77
  4982.3  774.31  5050.8  773.58  5053.3  773.08  5075.8  773.58  5083.3  773.88
  5103.3  780.75  5153.4  782.45  5463.9  779.10  5644.2  783.44  5744.4  787.89
  5764.4  790.85  5784.5  790.34  5814.5  792.16  5824.5  793.84  5884.6  798.57
  5994.8  805.61  6115.0  815.23  6145.1  815.38  6225.2  821.12  6321.5  825.67
#Mann=3,-1,0
  3907.6    0.05       0  5050.8   0.033       0  5075.8    0.05       0
Bank Sta=5050.8,5075.8
Exp/Cntr=0.3,0.1

Type RM Length L Ch R = 1,68965,556,556,556
BEGIN DESCRIPTION:
Mapping XS 88a4e99f
END DESCRIPTION:
XS GIS Cut Line= 3
      2291446.52      7104905.48      2291578.48      7104153.67
      2291615.80      7102329.96
#Sta/Elev= 30
  3592.9  794.19  3926.9  788.08  4024.9  784.63  4238.1  782.24  4459.9  780.64
  4489.9  781.88  4579.9  780.09  4730.0  779.44  4800.0  779.51  4830.0  781.43
  4880.0  781.86  4890.0  781.59  4900.0  778.00  4910.0  776.31  4940.0  774.52
  4950.0  772.42  5057.5  772.28  5060.0  771.78  5082.5  772.28  5090.0  774.88
  5100.0  780.54  5109.9  782.40  5530.1  777.57  5640.1  778.52  5970.2  787.89
  6010.2  789.74  6030.2  792.00  6050.2  791.52  6080.2  797.90  6180.3  799.64
#Mann=3,-1,0
  3592.9    0.05       0  5057.5   0.033       0  5082.5    0.05       0
Bank Sta=5057.5,5082.5
Exp/Cntr=0.3,0.1

Type RM Length L Ch R = 1,68409,602,602,602
BEGIN DESCRIPTION:
Oliver Creek 81.4
END DESCRIPTION:
XS GIS Cut Line= 3
      2291615.28      7104574.81      2292137.63      7103525.78
      2292023.53      7102150.49
#Sta/Elev= 30
  3762.1  783.74  3901.5  781.61  4102.6  781.46  4141.2  780.33  4393.1  779.51
  4482.6  778.32  4828.7  779.97  4895.8  781.54  4908.0  781.07  4918.1  778.92
  4924.8  773.95  4934.0  773.62  4939.8  768.77  4947.4  767.54  4949.9  767.04
  4972.4  767.54  5000.0  768.67  5010.0  770.20  5020.1  772.87  5040.1  781.33
  5210.7  778.68  5491.7  776.23  5612.1  776.97  5812.8  779.82  6067.5  788.55
  6174.0  789.92  6188.2  791.35  6204.1  790.05  6284.4  790.39  6314.0  792.12
#Mann=3,-1,0
  3762.1    0.05       0  4947.4   0.033       0  4972.4    0.05       0
Bank Sta=4947.4,4972.4
Exp/Cntr=0.3,0.1

Type RM Length L Ch R = 1,67807,520,520,520
BEGIN DESCRIPTION:
Mapping XS 529b7138
END DESCRIPTION:
XS GIS Cut Line= 2
      2292822.78      7104272.25      2292560.32      7101873.77
#Sta/Elev= 30
  4182.9  787.19  4507.1  783.25  4829.0  776.94  4949.7  779.28  4959.8  777.95
  4979.9  769.86  5002.0  767.06  5007.6  764.68  5010.1  764.18  5032.6  764.68
  5080.5  765.38  5088.2  769.45  5093.3  768.17  5100.6  773.73  5110.7  778.26
  5120.7  780.07  5549.4  774.18  6101.9  777.87  6177.0  779.37  6198.1  781.49
  6227.3  779.82  6289.4  779.71  6337.9  782.71  6348.0  785.13  6375.6  783.58
  6418.4  788.18  6519.0  794.16  6563.1  797.49  6589.4  800.54  6595.7  802.64
#Mann=3,-1,0
  4182.9    0.05       0  5007.6   0.033       0  5032.6    0.05       0
Bank Sta=5007.6,5032.6
Exp/Cntr=0.3,0.1

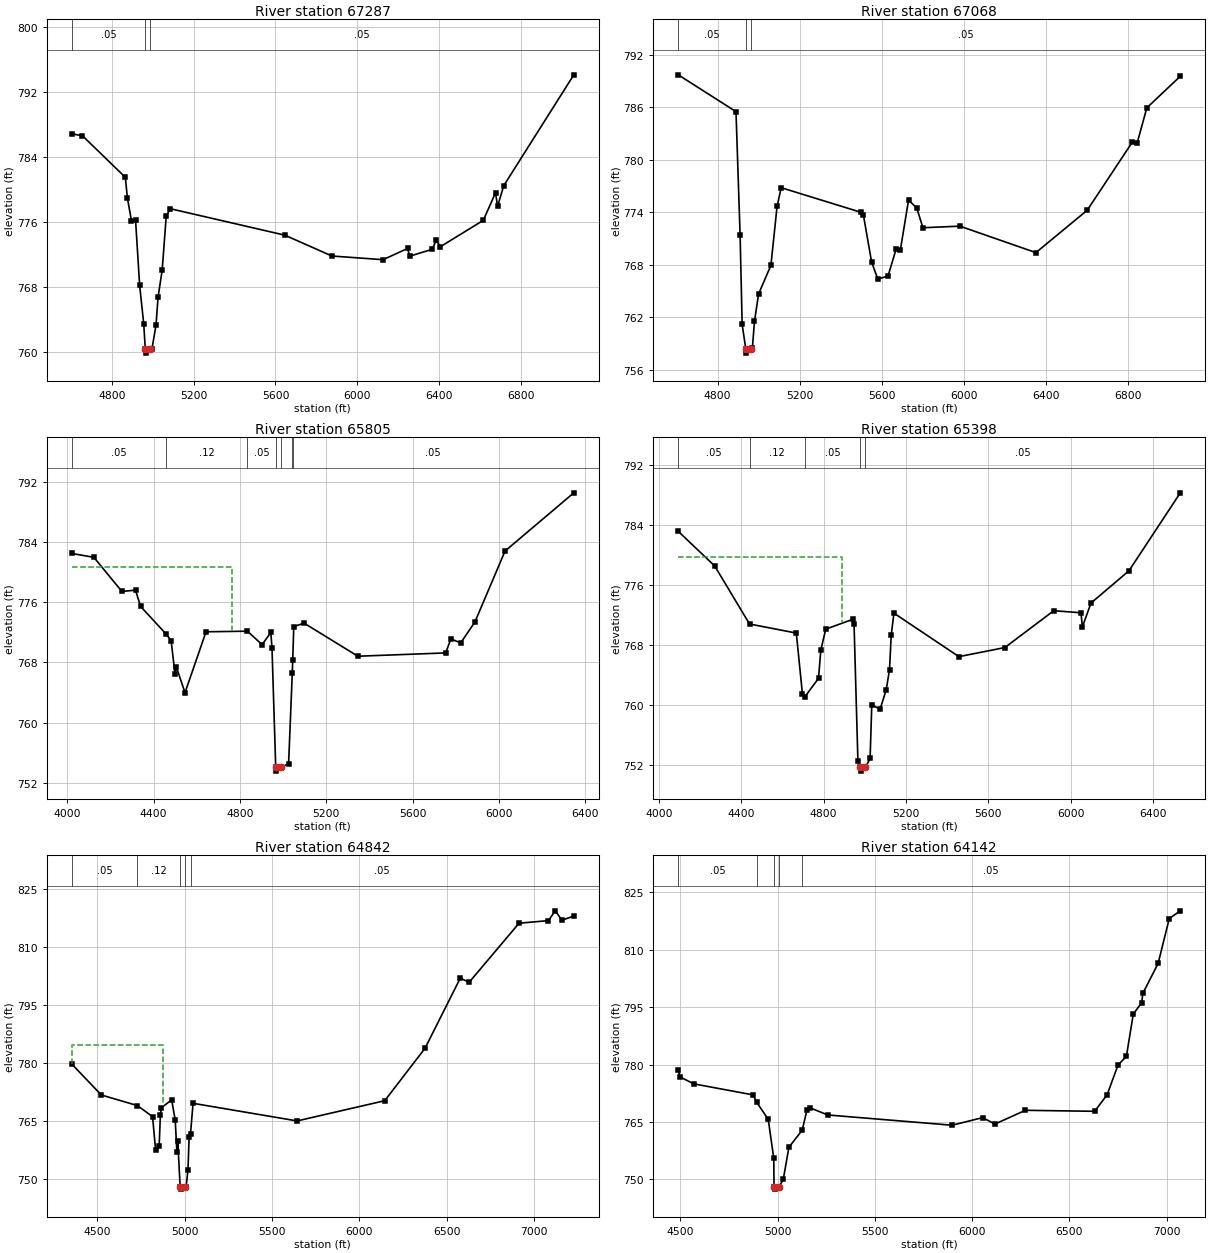
Type RM Length L Ch R = 1,67287,219,219,219
BEGIN DESCRIPTION:
Mapping XS 7eec7c17
END DESCRIPTION:
XS GIS Cut Line= 2
      2293223.99      7103861.88      2293239.96      7101407.43
#Sta/Elev= 30
  4604.2  786.84  4656.1  786.61  4866.1  781.50  4876.1  778.95  4896.1  776.15
  4916.1  776.23  4936.1  768.21  4956.1  763.48  4963.6  760.40  4966.1  759.90
  4988.6  760.40  4996.1  760.40  5016.1  763.35  5026.1  766.79  5046.1  770.06
  5066.1  776.77  5086.1  777.64  5646.1  774.39  5876.1  771.83  6126.1  771.38
  6246.1  772.76  6256.1  771.81  6366.1  772.65  6386.1  773.76  6406.1  772.97
  6616.1  776.21  6676.1  779.61  6686.1  777.93  6716.1  780.47  7058.7  794.09
#Mann=3,-1,0
  4604.2    0.05       0  4963.6   0.033       0  4988.6    0.05       0
Bank Sta=4963.6,4988.6
Exp/Cntr=0.3,0.1

Type RM Length L Ch R = 1,67068,1263,1263,1263
BEGIN DESCRIPTION:
Mapping XS c3a7fcbf
END DESCRIPTION:
XS GIS Cut Line= 2
      2293427.56      7103801.03      2293434.61      7101356.94
#Sta/Elev= 30
  4609.0  789.69  4890.0  785.49  4910.0  771.41  4920.0  761.21  4937.5  758.43
  4940.0  757.93  4962.5  758.43  4970.0  758.57  4980.0  761.56  5000.0  764.68
  5060.0  767.95  5090.0  774.68  5110.0  776.81  5500.0  773.99  5510.0  773.73
  5550.0  768.35  5580.0  766.40  5630.0  766.71  5670.0  769.85  5690.0  769.67
  5730.0  775.39  5770.0  774.49  5800.0  772.24  5980.0  772.42  6350.0  769.40
  6600.0  774.24  6820.0  782.03  6843.7  781.96  6890.0  785.92  7053.1  789.53
#Mann=3,-1,0
  4609.0    0.05       0  4937.5    0.05       0  4962.5    0.05       0
Bank Sta=4937.5,4962.5
Exp/Cntr=0.3,0.1

Type RM Length L Ch R = 1,65805,407,407,407
BEGIN DESCRIPTION:
Mapping XS fe9ae18d
END DESCRIPTION:
XS GIS Cut Line= 2
      2294358.50      7103364.67      2293466.93      7101215.68
#Sta/Elev= 30
  4020.6  782.50  4123.1  781.98  4253.0  777.44  4316.0  777.62  4339.6  775.45
  4459.1  771.74  4480.9  770.92  4499.3  766.42  4504.7  767.45  4545.3  763.98
  4642.8  772.08  4834.8  772.16  4902.6  770.37  4943.1  771.99  4948.5  769.94
  4965.8  754.05  4968.3  753.55  4991.0  754.05  5025.5  754.54  5042.6  766.63
  5044.7  768.36  5049.4  772.77  5097.2  773.23  5346.5  768.83  5753.6  769.27
  5777.4  771.14  5822.9  770.60  5889.2  773.40  6028.6  782.82  6347.2  790.56
#Mann=7,-1,0
  4020.6    0.05       0  4459.1    0.12       0  4834.8    0.05       0
  4965.8   0.033       0  4991.0    0.05       0  5042.6    0.12       0
  5044.7    0.05       0
#XS Ineff=2,0
    0.00 4762.70  780.64               0
Permanent Ineff=
       F       F
Bank Sta=4965.8,4991
Exp/Cntr=0.3,0.1

Type RM Length L Ch R = 1,65398,556,556,556
BEGIN DESCRIPTION:
Mapping XS 387c27ec
END DESCRIPTION:
XS GIS Cut Line= 2
      2294678.28      7103152.81      2293774.68      7100888.34
#Sta/Elev= 30
  4093.9  783.19  4271.0  778.56  4439.9  770.81  4667.1  769.60  4696.8  761.49
  4707.6  761.04  4774.9  763.55  4786.0  767.29  4809.9  770.12  4942.0  771.44
  4947.5  770.79  4966.3  752.52  4977.9  751.65  4980.4  751.15  5003.1  751.65
  5025.5  752.85  5033.6  759.99  5074.1  759.43  5103.7  762.01  5119.8  764.72
  5128.0  769.33  5141.3  772.26  5456.7  766.45  5679.6  767.66  5917.6  772.59
  6049.6  772.31  6056.5  770.42  6098.1  773.61  6282.6  777.92  6532.0  788.34
#Mann=5,-1,0
  4093.9    0.05       0  4439.9    0.12       0  4707.6    0.05       0
  4977.9   0.033       0  5003.1    0.05       0
#XS Ineff=2,0
    0.00 4888.20  779.70               0
Permanent Ineff=
       F       F
Bank Sta=4977.9,5003.1
Exp/Cntr=0.3,0.1

Type RM Length L Ch R = 1,64842,700,700,700
BEGIN DESCRIPTION:
Oliver Creek 76.0
END DESCRIPTION:
XS GIS Cut Line= 3
      2294979.00      7102909.99      2294845.57      7102276.89
      2293857.20      7100279.11
#Sta/Elev= 30
  4353.0  779.72  4522.2  771.72  4728.8  768.99  4815.8  766.13  4833.3  757.49
  4853.7  758.57  4860.5  766.44  4865.6  768.41  4925.3  770.45  4945.7  765.20
  4955.0  757.07  4960.1  759.79  4974.0  747.90  4976.5  747.40  4999.2  747.90
  5008.4  748.07  5018.8  752.42  5025.3  760.99  5033.3  761.76  5047.7  769.57
  5643.6  765.02  6145.7  770.24  6376.8  783.80  6578.7  801.92  6629.1  800.82
  6915.2  816.10  7083.4  816.77  7122.6  819.30  7161.0  816.87  7228.9  817.96
#Mann=5,-1,0
  4353.0    0.05       0  4728.8    0.12       0  4974.0    0.07       0
  4999.2    0.12       0  5033.3    0.05       0
#XS Ineff=2,0
    0.00 4877.30  784.70               0
Permanent Ineff=
       F       F
Bank Sta=4974,4999.2
Exp/Cntr=0.3,0.1

Type RM Length L Ch R = 1,64142,539,539,539
BEGIN DESCRIPTION:
Oliver Creek 75.0
END DESCRIPTION:
XS GIS Cut Line= 3
      2295864.57      7102607.76      2295489.64      7102261.88
      2294179.02      7100660.03
#Sta/Elev= 30
  4489.9  778.48  4499.1  776.75  4570.0  774.94  4874.5  772.06  4893.3  770.08
  4952.2  765.67  4980.6  755.47  4982.1  747.92  4984.6  747.42  5007.4  747.92
  5029.7  750.05  5058.4  758.36  5126.8  762.84  5151.0  768.07  5165.4  768.71
  5258.0  766.81  5896.8  764.13  6053.3  766.11  6117.2  764.44  6273.7  768.03
  6629.7  767.77  6693.6  772.10  6749.6  779.87  6792.7  782.13  6827.8  793.14
  6870.9  796.18  6877.4  798.62  6955.6  806.43  7013.0  818.18  7069.7  820.19
#Mann=5,-1,0
  4489.9    0.05       0  4893.3    0.12       0  4982.1    0.07       0
  5007.4    0.12       0  5126.8    0.05       0
Bank Sta=4982.1,5007.4
Exp/Cntr=0.3,0.1

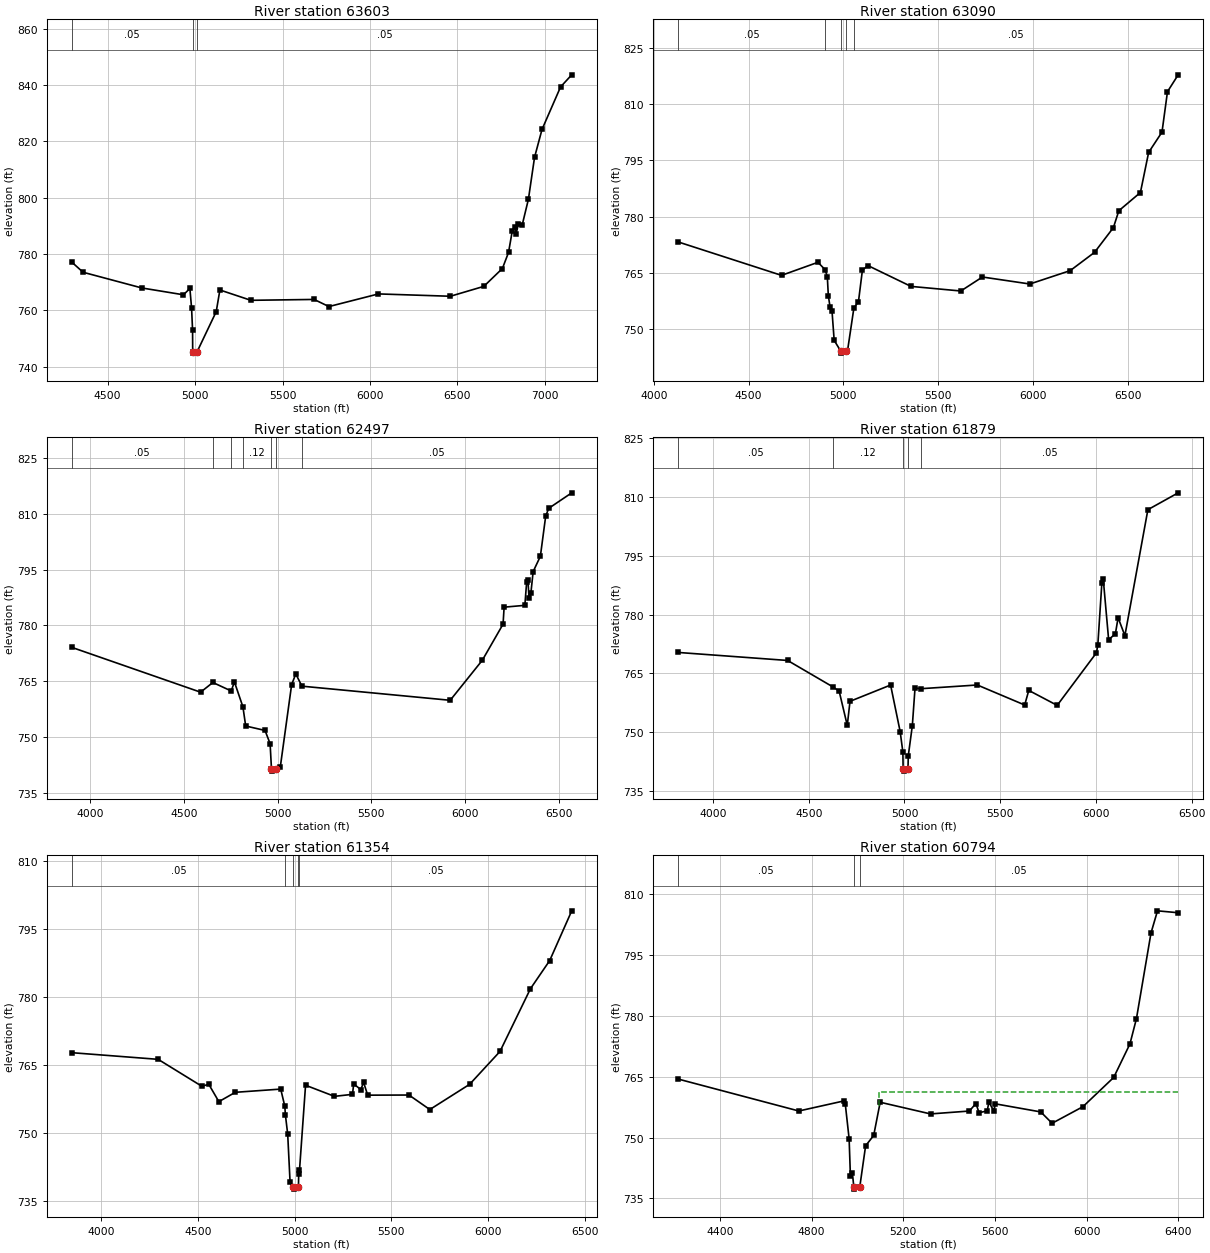
Type RM Length L Ch R = 1,63603,513,513,513
BEGIN DESCRIPTION:
Oliver Creek 74.0
END DESCRIPTION:
XS GIS Cut Line= 3
      2296145.84      7102454.15      2295776.30      7101853.88
      2294329.02      7100260.02
#Sta/Elev= 30
  4295.1  777.15  4360.2  773.51  4696.3  767.93  4934.1  765.51  4970.7  767.76
  4980.3  760.85  4986.1  752.84  4986.7  745.30  4989.2  744.80  5012.0  745.30
  5121.2  759.53  5142.2  767.22  5319.2  763.55  5680.6  763.86  5765.2  761.33
  6048.4  765.82  6459.3  764.99  6650.5  768.50  6756.6  774.84  6791.7  780.54
  6813.4  788.30  6827.6  789.73  6834.3  787.08  6848.5  790.71  6869.4  790.19
  6905.3  799.42  6940.4  814.32  6983.0  824.20  7089.1  839.31  7152.9  843.60
#Mann=3,-1,0
  4295.1    0.05       0  4986.7   0.033       0  5012.0    0.05       0
Bank Sta=4986.7,5012
Exp/Cntr=0.3,0.1

Type RM Length L Ch R = 1,63090,593,593,593
BEGIN DESCRIPTION:
Oliver Creek 73.0
END DESCRIPTION:
XS GIS Cut Line= 3
      2296268.21      7102224.92      2295976.28      7101403.87
      2294880.18      7100019.20
#Sta/Elev= 30
  4128.6  773.22  4674.1  764.28  4866.1  767.77  4904.3  765.78  4915.6  763.87
  4920.9  758.84  4929.8  755.89  4940.4  754.66  4951.7  746.91  4986.7  743.99
  4989.3  743.49  5012.1  743.99  5021.9  744.04  5055.8  755.59  5079.7  757.21
  5100.5  765.63  5129.3  766.91  5356.9  761.33  5619.7  760.10  5733.5  763.84
  5983.6  761.97  6196.7  765.55  6324.9  770.43  6424.3  777.04  6453.1  781.56
  6566.9  786.43  6610.2  797.15  6680.7  802.58  6709.6  813.39  6766.0  817.89
#Mann=5,-1,0
  4128.6    0.05       0  4904.3    0.12       0  4986.7    0.07       0
  5012.1    0.12       0  5055.8    0.05       0
Bank Sta=4986.7,5012.1
Exp/Cntr=0.3,0.1

Type RM Length L Ch R = 1,62497,618,618,618
BEGIN DESCRIPTION:
Oliver Creek 72.0
END DESCRIPTION:
XS GIS Cut Line= 3
      2296380.20      7102256.21      2296458.98      7101159.73
      2295736.97      7099766.62
#Sta/Elev= 30
  3900.7  774.10  4588.7  762.02  4654.1  764.63  4752.0  762.35  4769.1  764.79
  4814.6  758.05  4829.3  752.92  4932.5  751.72  4959.6  748.15  4967.0  741.27
  4969.5  740.77  4992.4  741.27  5013.7  741.78  5074.5  764.07  5096.6  766.93
  5129.5  763.64  5920.6  759.84  6092.0  770.62  6202.7  780.34  6208.3  784.91
  6318.9  785.40  6328.8  791.81  6335.4  792.17  6341.1  787.36  6351.3  788.79
  6363.2  794.48  6401.8  798.62  6430.1  809.41  6446.1  811.51  6569.1  815.69
#Mann=7,-1,0
  3900.7    0.05       0  4654.1    0.12       0  4752.0    0.05       0
  4814.6    0.12       0  4967.0    0.07       0  4992.4    0.12       0
  5129.5    0.05       0
Bank Sta=4967,4992.4
Exp/Cntr=0.3,0.1

Type RM Length L Ch R = 1,61879,525,525,525
BEGIN DESCRIPTION:
Oliver Creek 71.5
END DESCRIPTION:
XS GIS Cut Line= 3
      2297619.77      7101587.83      2296820.96      7100716.33
      2295820.52      7099694.84
#Sta/Elev= 30
  3817.8  770.32  4390.0  768.27  4625.7  761.54  4658.9  760.46  4701.4  751.69
  4715.6  757.84  4927.7  762.00  4977.7  750.10  4991.9  744.84  4993.2  740.52
  4995.8  740.02  5018.6  740.52  5020.0  743.92  5041.2  751.61  5055.3  761.22
  5084.9  761.06  5380.7  762.01  5628.1  756.90  5649.4  760.63  5797.8  756.81
  6002.9  770.23  6010.0  772.16  6031.2  788.04  6038.3  789.13  6066.6  773.58
  6101.9  775.08  6116.0  779.20  6151.5  774.60  6271.6  806.77  6429.8  811.07
#Mann=5,-1,0
  3817.8    0.05       0  4625.7    0.12       0  4993.2    0.07       0
  5018.6    0.12       0  5084.9    0.05       0
Bank Sta=4993.2,5018.6
Exp/Cntr=0.3,0.1

Type RM Length L Ch R = 1,61354,560,560,560
BEGIN DESCRIPTION:
Oliver Creek 71.0
END DESCRIPTION:
XS GIS Cut Line= 3
      2297690.10      7101264.94      2297078.82      7100289.92
      2295954.88      7099404.34
#Sta/Elev= 30
  3849.2  767.66  4295.7  766.19  4520.7  760.27  4557.3  760.67  4609.1  756.86
  4694.0  758.92  4928.5  759.63  4949.7  755.82  4952.4  754.02  4964.5  749.69
  4976.8  739.08  4994.2  738.07  4996.7  737.57  5019.9  738.07  5021.5  741.00
  5025.4  741.71  5056.7  760.48  5205.8  758.03  5298.9  758.47  5305.3  760.75
  5342.2  759.53  5356.2  761.13  5377.5  758.29  5590.7  758.32  5698.2  755.12
  5903.7  760.68  6060.5  767.93  6217.7  781.76  6317.1  787.97  6430.9  798.94
#Mann=5,-1,0
  3849.2    0.05       0  4952.4    0.12       0  4994.2    0.07       0
  5019.9    0.12       0  5025.4    0.05       0
Bank Sta=4994.2,5019.9
Exp/Cntr=0.3,0.1

Type RM Length L Ch R = 1,60794,445,445,445
BEGIN DESCRIPTION:
Oliver Creek 70.0
END DESCRIPTION:
XS GIS Cut Line= 3
      2297791.67      7100663.39      2297449.41      7099960.49
      2296440.07      7098991.47
#Sta/Elev= 30
  4218.2  764.38  4744.7  756.52  4941.6  759.00  4947.2  758.30  4964.1  749.67
  4969.7  740.46  4978.3  741.25  4984.6  737.80  4987.2  737.30  5010.4  737.80
  5036.0  747.96  5071.2  750.50  5099.5  758.67  5319.0  755.80  5488.6  756.51
  5516.9  758.36  5531.0  756.09  5566.5  756.56  5573.5  758.73  5594.8  756.56
  5601.8  758.28  5799.9  756.29  5849.3  753.50  5983.8  757.58  6118.1  764.78
  6188.9  773.03  6217.2  779.24  6280.7  800.31  6309.0  805.76  6399.2  805.29
#Mann=3,-1,0
  4218.2    0.05       0  4984.6    0.04       0  5010.4    0.05       0
#XS Ineff=2,0
       0                 5096.40    0.00  761.17
Permanent Ineff=
       F       F
Bank Sta=4984.6,5010.4
Exp/Cntr=0.3,0.1