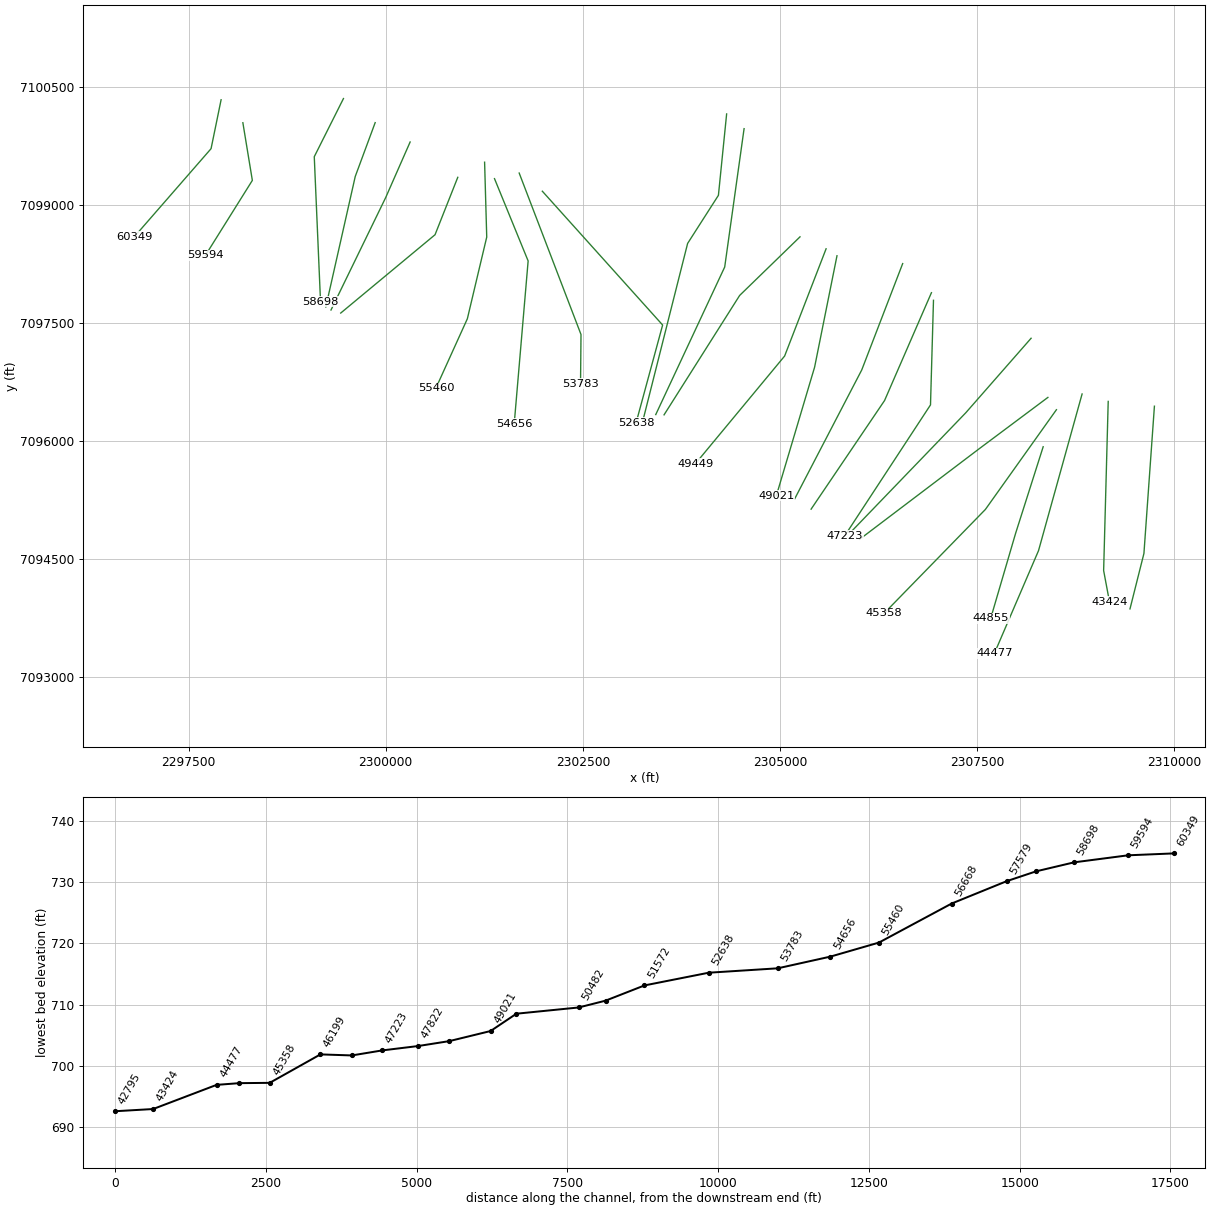
HEC-RAS study Oliver Creek.prj: Oliver Creek Base Level Engineering

--- Oliver Creek.g01 (geometry) --- (continued)

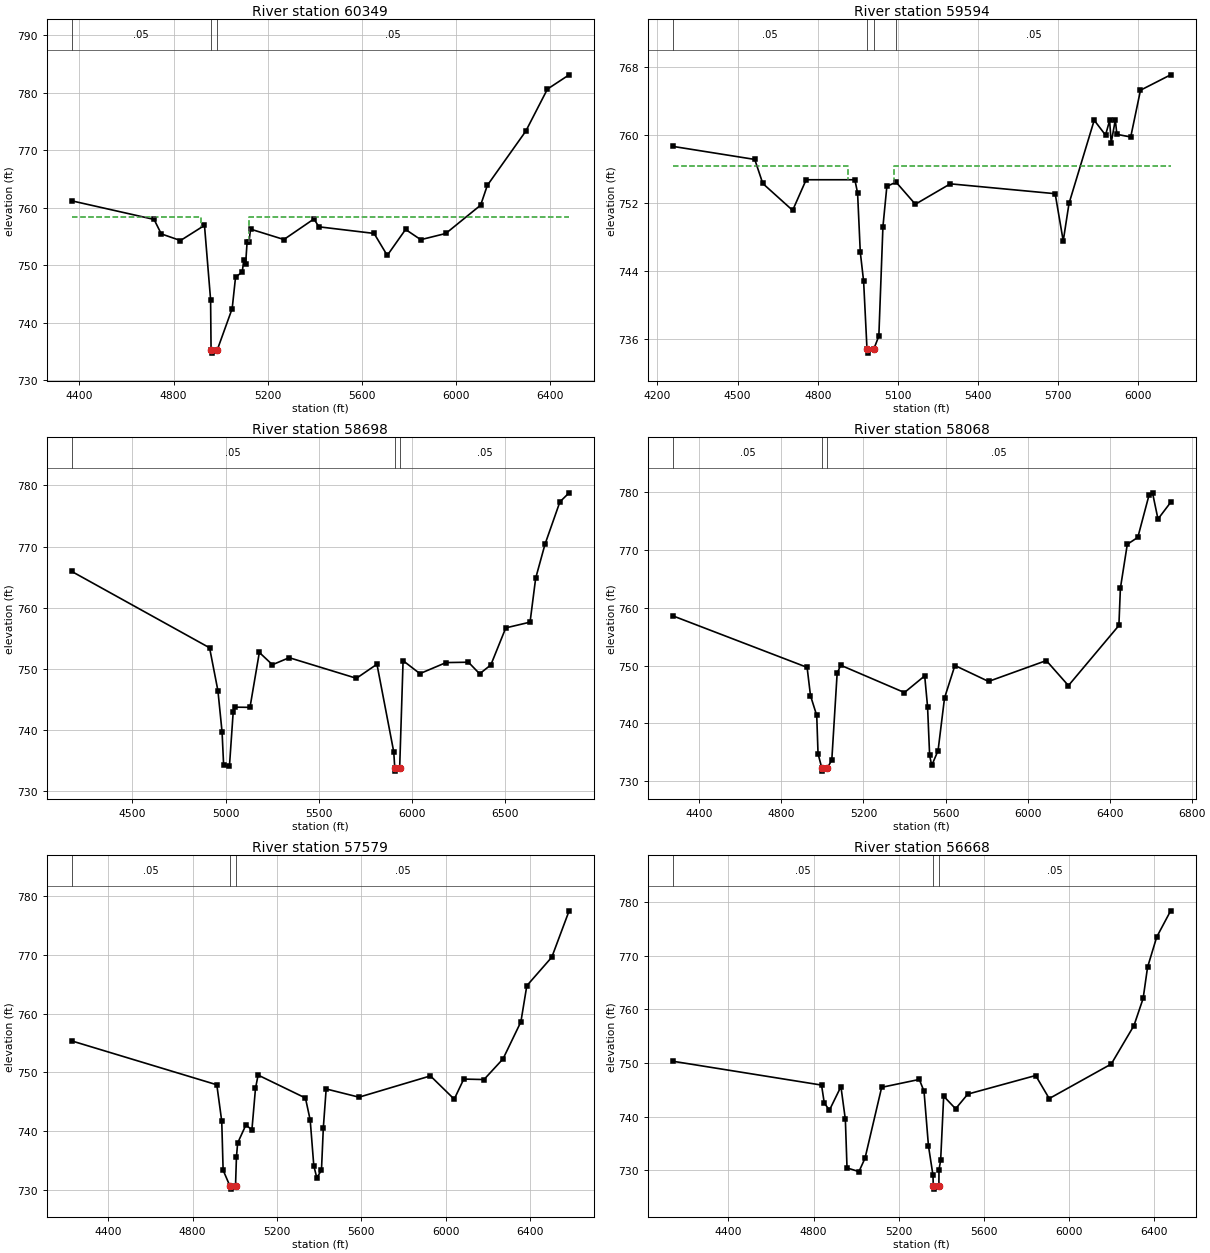
Type RM Length L Ch R = 1,60349,755,755,755
BEGIN DESCRIPTION:
Oliver Creek 69.6
END DESCRIPTION:
XS GIS Cut Line= 3
      2297912.72      7100333.45      2297785.53      7099712.74
      2296813.41      7098595.71
#Sta/Elev= 30
  4366.4  761.22  4717.0  757.98  4747.6  755.46  4829.3  754.30  4931.3  756.94
  4957.3  743.99  4959.3  735.20  4961.8  734.70  4985.1  735.20  5049.0  742.46
  5063.3  747.93  5091.8  748.82  5098.4  750.96  5106.0  750.20  5112.6  754.13
  5120.3  753.96  5126.9  756.29  5268.8  754.48  5396.5  758.06  5417.4  756.69
  5652.0  755.54  5708.0  751.71  5785.8  756.23  5850.4  754.45  5956.7  755.53
  6104.8  760.46  6133.3  763.91  6296.6  773.34  6388.7  780.67  6480.8  783.15
#Mann=3,-1,0
  4366.4    0.05       0  4959.3    0.04       0  4985.1    0.05       0
#XS Ineff=2,0
    0.00 4918.00  758.40 5120.00    0.00  758.40
Permanent Ineff=
       F       F
Bank Sta=4959.3,4985.1
Exp/Cntr=0.3,0.1

Type RM Length L Ch R = 1,59594,896,896,896
BEGIN DESCRIPTION:
Oliver Creek 69.4
END DESCRIPTION:
XS GIS Cut Line= 3
      2298188.75      7100041.83      2298309.01      7099309.95
      2297714.31      7098358.99
#Sta/Elev= 30
  4258.3  758.70  4564.2  757.17  4594.3  754.34  4706.1  751.18  4756.7  754.78
  4939.1  754.78  4949.3  753.22  4959.4  746.27  4971.9  742.83  4984.5  734.89
  4987.1  734.39  5010.3  734.89  5028.9  736.40  5044.2  749.26  5058.9  754.00
  5093.4  754.50  5165.6  751.90  5296.5  754.30  5689.2  753.14  5719.4  747.58
  5741.0  751.99  5835.4  761.78  5877.8  760.03  5893.1  761.75  5899.0  759.12
  5914.4  761.82  5920.3  760.12  5972.1  759.81  6008.7  765.31  6121.6  767.12
#Mann=4,-1,0
  4258.3    0.05       0  4984.5    0.04       0  5010.3    0.05       0
  5093.4    0.05       0
#XS Ineff=2,0
    0.00 4914.80  756.39 5085.20    0.00  756.39
Permanent Ineff=
       F       F
Bank Sta=4984.5,5010.3
Exp/Cntr=0.3,0.1

Type RM Length L Ch R = 1,58698,630,630,630
BEGIN DESCRIPTION:
Oliver Creek 69.0
END DESCRIPTION:
XS GIS Cut Line= 3
      2299464.41      7100348.93      2299094.18      7099610.44
      2299173.60      7097770.75
#Sta/Elev= 30
  4173.9  765.95  4913.9  753.43  4958.6  746.41  4980.9  739.63  4989.3  734.17
  5020.5  734.09  5040.5  742.92  5050.5  743.71  5130.6  743.68  5180.6  752.67
  5250.7  750.66  5340.8  751.81  5701.1  748.44  5811.2  750.74  5901.3  736.38
  5906.7  733.74  5909.3  733.24  5932.9  733.74  5951.3  751.32  6041.4  749.20
  6181.5  751.01  6301.6  751.07  6361.7  749.17  6421.8  750.63  6501.8  756.69
  6632.0  757.63  6662.0  764.81  6712.0  770.37  6792.1  777.33  6841.4  778.80
#Mann=3,-1,0
  4173.9    0.05       0  5906.7   0.033       0  5932.9    0.05       0
Bank Sta=5906.7,5932.9
Exp/Cntr=0.3,0.1

Type RM Length L Ch R = 1,58068,489,489,489
BEGIN DESCRIPTION:
Oliver Creek 68.6
END DESCRIPTION:
XS GIS Cut Line= 3
      2299866.48      7100042.97      2299613.94      7099359.85
      2299240.63      7097703.91
#Sta/Elev= 30
  4271.7  758.57  4925.2  749.69  4941.7  744.81  4972.1  741.38  4978.5  734.79
  4997.0  732.27  4999.6  731.77  5023.2  732.27  5045.6  733.69  5071.6  748.64
  5088.8  750.06  5399.6  745.34  5498.5  748.22  5512.4  742.92  5522.6  734.47
  5532.9  732.75  5563.7  735.33  5595.2  744.41  5645.7  750.01  5809.7  747.26
  6091.3  750.86  6199.2  746.54  6445.2  756.92  6452.6  763.37  6486.2  770.94
  6537.5  772.14  6592.5  779.49  6609.2  779.83  6635.8  775.30  6697.5  778.18
#Mann=3,-1,0
  4271.7    0.05       0  4997.0   0.033       0  5023.2    0.05       0
Bank Sta=4997,5023.2
Exp/Cntr=0.3,0.1

Type RM Length L Ch R = 1,57579,911,911,911
BEGIN DESCRIPTION:
Oliver Creek 68.5
END DESCRIPTION:
XS GIS Cut Line= 3
      2300309.93      7099797.36      2299998.84      7099089.61
      2299306.43      7097664.74
#Sta/Elev= 30
  4226.9  755.38  4915.1  747.91  4938.5  741.71  4945.0  733.39  4977.5  730.66
  4980.1  730.16  5003.7  730.66  5008.1  735.59  5013.7  737.99  5053.2  741.10
  5081.3  740.21  5098.3  747.28  5110.7  749.56  5335.0  745.66  5357.6  741.89
  5374.6  734.13  5388.7  732.11  5410.9  733.36  5419.7  740.57  5433.2  747.20
  5588.8  745.80  5927.1  749.42  6039.9  745.46  6085.0  748.88  6180.8  748.80
  6271.0  752.31  6355.7  758.62  6383.8  764.76  6502.2  769.62  6584.2  777.50
#Mann=3,-1,0
  4226.9    0.05       0  4977.5   0.033       0  5003.7    0.05       0
Bank Sta=4977.5,5003.7
Exp/Cntr=0.3,0.1

Type RM Length L Ch R = 1,56668,1208,1208,1208
BEGIN DESCRIPTION:
Oliver Creek 68.4
END DESCRIPTION:
XS GIS Cut Line= 3
      2300914.12      7099349.08      2300625.82      7098620.22
      2299429.92      7097626.16
#Sta/Elev= 30
  4139.5  750.31  4837.5  745.88  4850.2  742.55  4874.5  741.21  4928.6  745.59
  4949.4  739.48  4957.2  730.46  5013.2  729.77  5041.8  732.26  5120.0  745.46
  5297.0  746.93  5319.2  744.72  5340.0  734.57  5361.3  729.07  5362.7  727.01
  5365.3  726.51  5389.0  727.01  5389.5  730.09  5397.3  731.87  5411.6  743.81
  5467.6  741.47  5524.9  744.20  5843.9  747.66  5907.7  743.37  6199.3  749.80
  6306.1  756.97  6349.1  762.01  6369.9  767.82  6412.9  773.44  6478.4  778.32
#Mann=3,-1,0
  4139.5    0.05       0  5362.7   0.033       0  5389.0    0.05       0
Bank Sta=5362.7,5389
Exp/Cntr=0.3,0.1

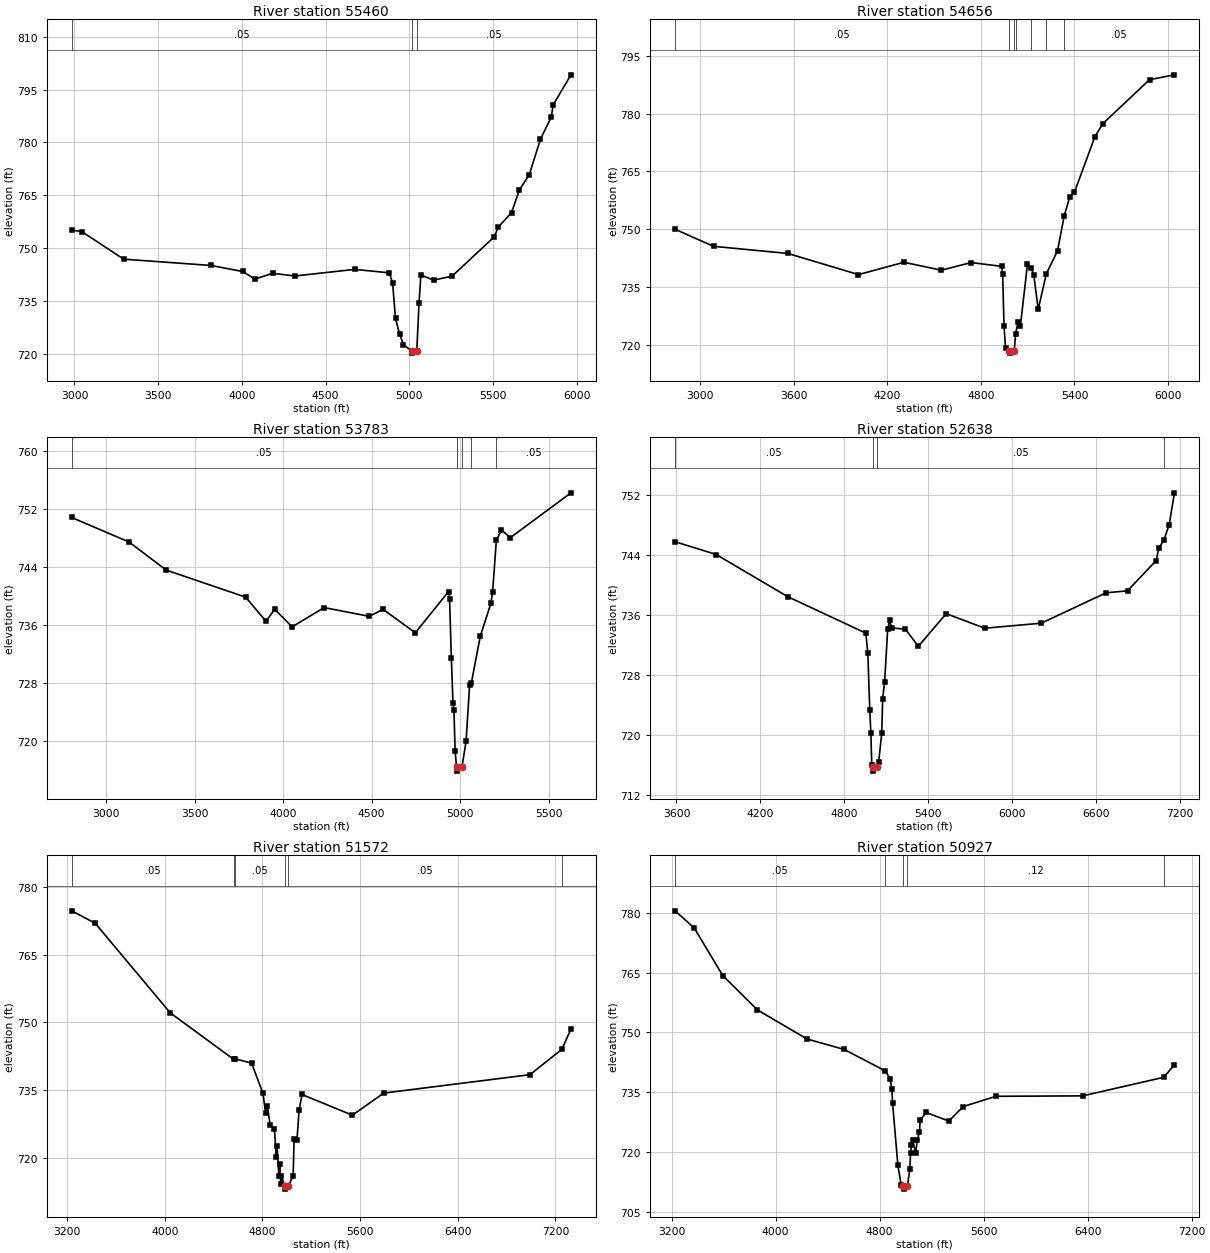
Type RM Length L Ch R = 1,55460,804,804,804
BEGIN DESCRIPTION:
Oliver Creek 68.2
END DESCRIPTION:
XS GIS Cut Line= 4
      2301254.34      7099540.92      2301281.36      7098590.74
      2301035.48      7097553.24      2300637.00      7096673.26
#Sta/Elev= 30
  2983.2  755.09  3044.1  754.65  3294.2  746.82  3814.5  745.04  4005.2  743.32
  4078.4  741.17  4184.4  742.81  4316.3  742.04  4674.5  743.92  4880.7  742.94
  4900.6  740.02  4917.8  729.97  4941.7  725.60  4965.2  722.57  5013.9  720.72
  5016.9  720.12  5044.9  720.72  5058.4  734.44  5069.4  742.33  5144.9  740.86
  5256.0  742.00  5507.9  753.17  5530.5  755.87  5611.2  760.07  5657.4  766.46
  5717.1  770.84  5783.9  780.96  5847.7  787.12  5859.8  790.70  5966.0  799.21
#Mann=3,-1,0
  2983.2    0.05       0  5013.9    0.04       0  5044.9    0.05       0
Bank Sta=5013.9,5044.9
Exp/Cntr=0.3,0.1

Type RM Length L Ch R = 1,54656,873,873,873
BEGIN DESCRIPTION:
Oliver Creek 68.0
END DESCRIPTION:
XS GIS Cut Line= 3
      2301379.94      7099332.08      2301806.44      7098287.51
      2301629.95      7096220.92
#Sta/Elev= 30
  2838.7  749.99  3085.8  745.56  3561.5  743.72  4014.7  738.22  4305.7  741.42
  4546.6  739.37  4737.3  741.35  4934.4  740.36  4939.4  738.32  4948.1  724.92
  4958.1  719.04  4982.7  718.43  4985.7  717.83  5013.7  718.43  5022.8  722.86
  5038.4  726.02  5053.4  724.98  5098.6  740.92  5121.2  740.06  5138.8  738.22
  5167.4  729.16  5219.5  738.43  5291.4  744.40  5333.7  753.39  5369.6  758.42
  5399.7  759.61  5530.2  773.93  5580.4  777.37  5881.4  788.84  6041.1  790.10
#Mann=7,-1,0
  2838.7    0.05       0  4982.7   0.033       0  5013.7    0.05       0
  5022.8    0.12       0  5121.2    0.05       0  5219.5    0.12       0
  5333.7    0.05       0
Bank Sta=4982.7,5013.7
Exp/Cntr=0.3,0.1

Type RM Length L Ch R = 1,53783,1145,1145,1145
BEGIN DESCRIPTION:
Oliver Creek 67.0
END DESCRIPTION:
XS GIS Cut Line= 3
      2301692.89      7099403.18      2302476.83      7097353.91
      2302470.90      7096727.44
#Sta/Elev= 30
  2805.9  750.82  3130.5  747.44  3340.0  743.58  3788.8  739.86  3903.6  736.54
  3953.0  738.19  4051.3  735.77  4232.2  738.42  4486.6  737.22  4565.2  738.17
  4747.2  734.96  4935.3  740.63  4940.7  739.62  4950.7  731.53  4960.1  725.28
  4965.4  724.32  4972.1  718.71  4980.0  716.52  4983.0  715.92  5011.0  716.52
  5033.9  720.01  5053.9  727.71  5063.4  728.00  5113.9  734.45  5173.9  738.99
  5183.9  740.53  5204.9  747.68  5233.9  749.09  5283.9  748.04  5626.5  754.21
#Mann=5,-1,0
  2805.9    0.05       0  4980.0   0.033       0  5011.0    0.05       0
  5063.4    0.12       0  5204.9    0.05       0
Bank Sta=4980,5011
Exp/Cntr=0.3,0.1

Type RM Length L Ch R = 1,52638,1066,1066,1066
BEGIN DESCRIPTION:
Mapping XS 7ef56a52
END DESCRIPTION:
XS GIS Cut Line= 3
      2301986.61      7099172.47      2303512.02      7097474.12
      2303175.65      7096233.85
#Sta/Elev= 30
  3590.4  745.73  3884.3  744.03  4394.1  738.43  4953.2  733.57  4967.4  730.95
  4981.6  723.28  4989.1  720.29  4995.8  715.97  5002.0  715.80  5005.0  715.20
  5033.0  715.80  5045.4  716.48  5066.8  720.23  5073.5  724.86  5087.7  727.11
  5109.4  734.08  5123.6  735.25  5137.8  734.27  5236.5  734.08  5328.4  731.81
  5527.3  736.16  5803.1  734.22  6206.7  734.89  6669.0  738.93  6823.2  739.20
  7027.6  743.22  7046.6  744.88  7082.8  745.94  7120.8  747.99  7158.3  752.24
#Mann=4,-1,0
  3590.4    0.05       0  5002.0   0.033       0  5033.0    0.05       0
  7082.8    0.12       0
Bank Sta=5002,5033
Exp/Cntr=0.3,0.1

Type RM Length L Ch R = 1,51572,645,645,645
BEGIN DESCRIPTION:
Oliver Creek 66.0
END DESCRIPTION:
XS GIS Cut Line= 4
      2304323.67      7100153.34      2304219.50      7099120.38
      2303829.00      7098510.00      2303259.92      7096253.77
#Sta/Elev= 30
  3237.3  774.70  3430.0  771.96  4044.7  752.13  4565.1  741.82  4579.3  741.93
  4710.9  741.00  4804.8  734.28  4825.9  729.93  4841.1  731.41  4862.3  727.42
  4898.6  726.32  4913.8  720.33  4919.8  722.72  4935.0  715.94  4940.9  718.72
  4950.2  714.19  4956.1  715.99  4981.6  713.82  4984.6  713.12  5012.6  713.82
  5051.7  716.07  5059.1  724.16  5082.6  723.93  5100.2  730.58  5123.9  734.06
  5536.4  729.48  5793.3  734.37  6990.6  738.44  7252.1  744.05  7327.0  748.56
#Mann=6,-1,0
  3237.3    0.05       0  4565.1    0.12       0  4579.3    0.05       0
  4981.6   0.033       0  5012.6    0.05       0  7252.1    0.12       0
Bank Sta=4981.6,5012.6
Exp/Cntr=0.3,0.1

Type RM Length L Ch R = 1,50927,445,445,445
BEGIN DESCRIPTION:
Oliver Creek 65.0
END DESCRIPTION:
XS GIS Cut Line= 3
      2304545.02      7099966.70      2304299.23      7098210.42
      2303424.81      7096337.38
#Sta/Elev= 30
  3226.6  780.58  3374.0  776.26  3593.3  764.30  3859.4  755.69  4241.1  748.37
  4525.8  745.75  4844.6  740.33  4879.3  738.40  4893.9  735.90  4899.4  732.16
  4939.8  716.71  4965.3  711.64  4982.2  711.33  4985.2  710.63  5013.2  711.33
  5032.0  715.64  5037.5  719.66  5044.6  721.62  5054.9  722.89  5077.7  719.60
  5088.8  722.88  5106.1  725.05  5111.6  728.01  5157.3  729.90  5331.5  727.73
  5442.7  731.38  5694.1  733.96  6361.6  734.07  6985.2  738.74  7067.1  741.88
#Mann=5,-1,0
  3226.6    0.05       0  4844.6    0.12       0  4982.2   0.033       0
  5013.2    0.12       0  6985.2    0.12       0
Bank Sta=4982.2,5013.2
Exp/Cntr=0.3,0.1

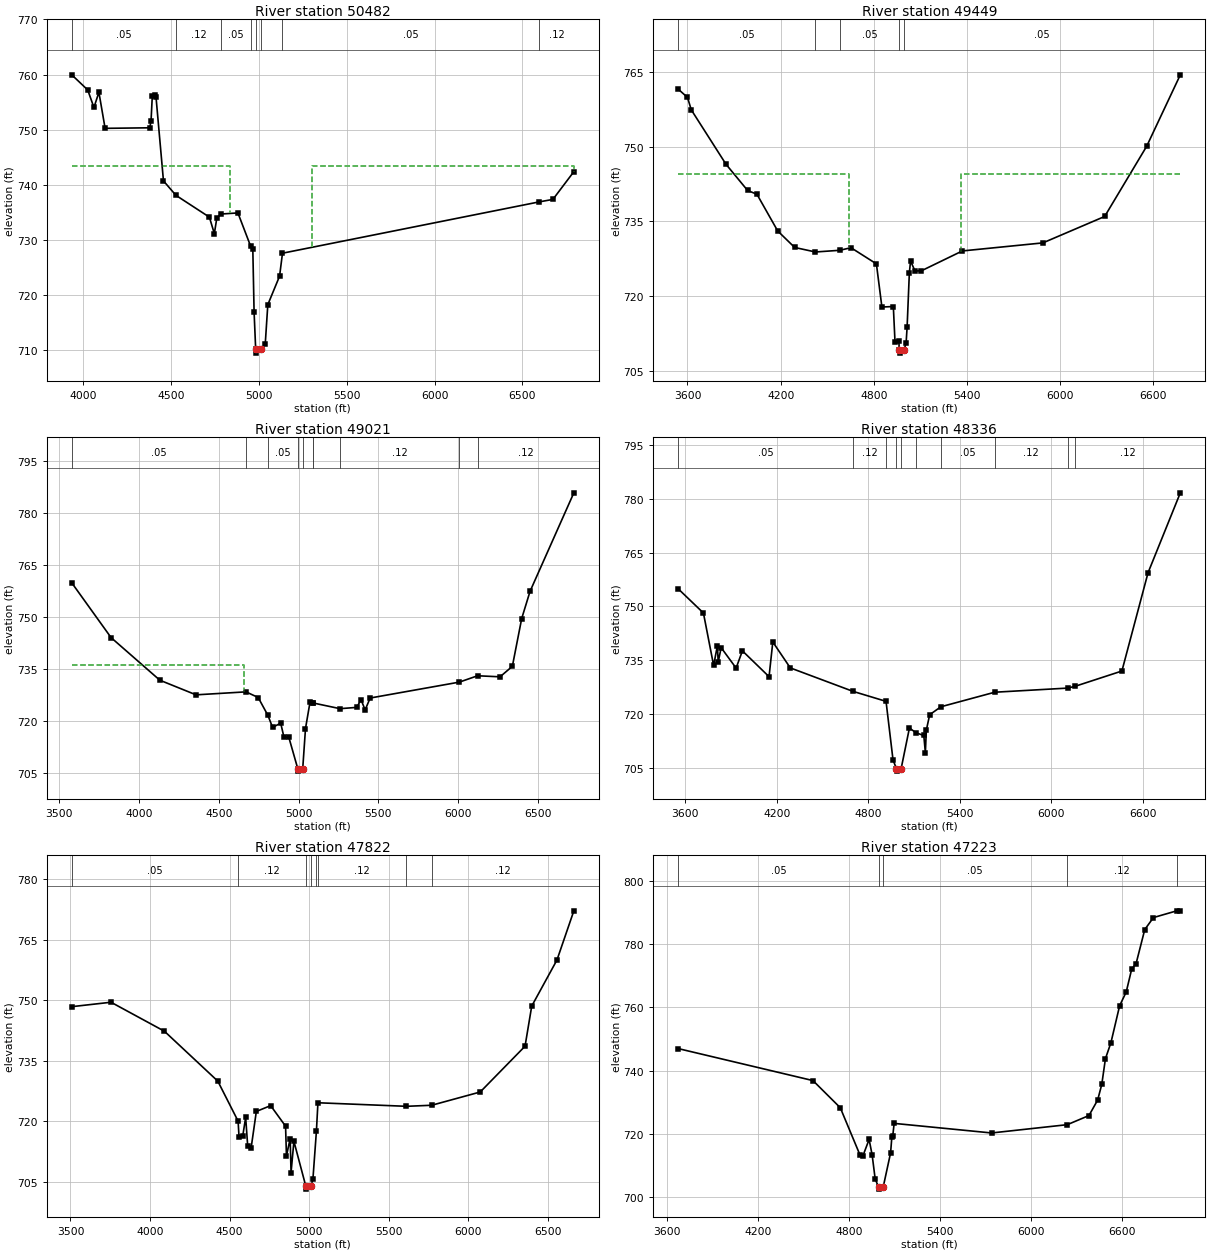
Type RM Length L Ch R = 1,50482,1033,1033,1033
BEGIN DESCRIPTION:
Oliver Creek 64.0
END DESCRIPTION:
XS GIS Cut Line= 3
      2305254.20      7098593.44      2304489.18      7097850.07
      2303530.26      7096334.09
#Sta/Elev= 30
  3933.3  759.96  4024.2  757.22  4059.6  754.04  4087.9  756.80  4123.2  750.26
  4377.8  750.36  4385.0  751.64  4392.0  756.06  4406.1  756.24  4413.3  755.92
  4455.7  740.74  4526.7  738.12  4717.3  734.17  4745.6  731.18  4759.8  734.03
  4783.5  734.73  4879.9  734.93  4952.0  728.93  4964.8  728.35  4972.0  717.01
  4981.1  710.22  4984.1  709.52  5012.1  710.22  5035.6  711.18  5050.2  718.30
  5117.2  723.47  5133.8  727.63  6597.8  736.94  6674.5  737.38  6793.8  742.41
#Mann=8,-1,0
  3933.3    0.05       0  4526.7    0.12       0  4783.5    0.05       0
  4952.0    0.12       0  4981.1    0.07       0  5012.1    0.12       0
  5133.8    0.05       0  6597.8    0.12       0
#XS Ineff=2,0
    0.00 4835.90  743.42 5300.00    0.00  743.42
Permanent Ineff=
       F       F
Bank Sta=4981.1,5012.1
Exp/Cntr=0.3,0.1

Type RM Length L Ch R = 1,49449,428,428,428
BEGIN DESCRIPTION:
Oliver Creek 63.0
END DESCRIPTION:
XS GIS Cut Line= 3
      2305584.96      7098441.58      2305059.13      7097080.31
      2303928.67      7095714.96
#Sta/Elev= 30
  3540.7  761.63  3600.1  759.98  3624.7  757.47  3848.3  746.51  3987.3  741.24
  4047.3  740.48  4181.0  733.09  4290.1  729.77  4424.0  728.86  4580.3  729.20
  4652.7  729.72  4816.3  726.47  4851.7  717.78  4925.3  717.88  4936.2  710.69
  4960.8  710.97  4963.4  709.20  4966.4  708.50  4994.4  709.20  5007.5  710.50
  5014.0  713.75  5028.3  724.58  5036.1  727.05  5064.8  725.03  5106.4  725.08
  5369.5  729.07  5887.9  730.69  6285.7  736.01  6556.1  750.14  6772.6  764.52
#Mann=5,-1,0
  3540.7    0.05       0  4424.0    0.12       0  4580.3    0.05       0
  4963.4   0.033       0  4994.4    0.05       0
#XS Ineff=2,0
    0.00 4639.10  744.48 5360.90    0.00  744.48
Permanent Ineff=
       F       F
Bank Sta=4963.4,4994.4
Exp/Cntr=0.3,0.1

Type RM Length L Ch R = 1,49021,685,685,685
BEGIN DESCRIPTION:
Oliver Creek 62.0
END DESCRIPTION:
XS GIS Cut Line= 3
      2305723.11      7098353.30      2305439.29      7096939.16
      2304953.89      7095306.85
#Sta/Elev= 30
  3578.9  759.99  3825.2  744.19  4130.7  731.90  4357.4  727.68  4670.5  728.54
  4746.7  726.91  4808.0  721.72  4836.8  718.30  4887.8  719.50  4908.2  715.46
  4938.8  715.42  4994.7  706.37  4997.7  705.67  5025.7  706.37  5043.1  717.96
  5071.1  725.49  5087.0  725.39  5092.1  725.32  5259.4  723.69  5364.6  724.06
  5390.7  726.30  5416.8  723.34  5448.1  726.76  6006.9  731.35  6121.2  733.18
  6261.9  732.88  6339.0  735.91  6397.5  749.69  6449.7  757.53  6724.2  785.96
#Mann=10,-1,0
  3578.9    0.05       0  4670.5    0.12       0  4808.0    0.05       0
  4994.7   0.033       0  5025.7    0.05       0  5087.0    0.12       0
  5092.1    0.05       0  5259.4    0.12       0  6006.9    0.05       0
  6121.2    0.12       0
#XS Ineff=2,0
    0.00 4657.30  736.20               0
Permanent Ineff=
       F       F
Bank Sta=4994.7,5025.7
Exp/Cntr=0.3,0.1

Type RM Length L Ch R = 1,48336,514,514,514
BEGIN DESCRIPTION:
Oliver Creek 61.0
END DESCRIPTION:
XS GIS Cut Line= 3
      2306556.31      7098254.06      2306037.32      7096904.30
      2305186.52      7095267.07
#Sta/Elev= 30
  3553.9  754.91  3719.0  748.17  3785.9  733.52  3810.6  739.05  3815.9  734.47
  3835.2  738.49  3933.2  732.79  3974.5  737.60  4149.2  730.39  4173.8  740.08
  4288.5  732.84  4699.5  726.29  4916.1  723.50  4961.8  707.17  4984.1  704.72
  4987.1  704.02  5015.1  704.72  5069.5  716.08  5111.4  714.74  5163.6  713.97
  5173.9  709.19  5180.1  715.45  5202.2  719.77  5275.7  721.99  5628.6  726.05
  6105.7  727.20  6153.0  727.67  6462.2  731.97  6633.5  759.40  6845.1  781.72
#Mann=10,-1,0
  3553.9    0.05       0  4699.5    0.12       0  4916.1    0.05       0
  4984.1   0.033       0  5015.1    0.05       0  5111.4    0.12       0
  5275.7    0.05       0  5628.6    0.12       0  6105.7    0.05       0
  6153.0    0.12       0
Bank Sta=4984.1,5015.1
Exp/Cntr=0.3,0.1

Type RM Length L Ch R = 1,47822,599,599,599
BEGIN DESCRIPTION:
Oliver Creek 60.0
END DESCRIPTION:
XS GIS Cut Line= 3
      2306920.88      7097884.24      2306326.62      7096515.70
      2305394.87      7095136.90
#Sta/Elev= 30
  3508.0  748.45  3754.6  749.55  4090.4  742.36  4426.0  729.99  4553.5  720.08
  4559.7  716.03  4583.1  716.48  4601.1  721.00  4613.7  714.01  4635.5  713.45
  4668.2  722.48  4758.2  723.92  4852.0  718.82  4857.5  711.47  4880.9  715.74
  4886.4  707.34  4904.4  715.07  4979.4  703.92  4982.4  703.22  5010.4  703.92
  5023.8  705.66  5045.7  717.52  5055.4  724.63  5611.8  723.75  5770.4  724.01
  6075.6  727.30  6357.3  738.65  6399.3  748.59  6558.1  760.03  6664.1  772.21
#Mann=8,-1,0
  3508.0    0.05       0  4553.5    0.12       0  4979.4    0.07       0
  5010.4    0.12       0  5045.7    0.05       0  5055.4    0.12       0
  5611.8    0.05       0  5770.4    0.12       0
Bank Sta=4979.4,5010.4
Exp/Cntr=0.3,0.1

Type RM Length L Ch R = 1,47223,503,503,503
BEGIN DESCRIPTION:
Oliver Creek 59.0
END DESCRIPTION:
XS GIS Cut Line= 3
      2306946.93      7097787.89      2306909.01      7096460.03
      2305823.69      7094801.84
#Sta/Elev= 30
  3671.6  746.96  4559.9  736.84  4739.9  728.26  4870.0  713.29  4890.0  713.13
  4930.0  718.21  4950.0  713.34  4970.0  705.71  4992.1  703.20  4995.1  702.50
  5023.1  703.20  5071.7  713.98  5080.0  719.04  5085.9  719.33  5095.1  723.30
  5737.3  720.27  6236.6  722.89  6379.5  725.78  6436.8  730.68  6464.1  735.65
  6488.1  743.76  6524.3  748.83  6581.6  760.50  6625.4  764.92  6661.3  772.13
  6690.1  773.83  6747.4  784.63  6804.7  788.42  6958.4  790.55  6981.8  790.54
#Mann=5,-1,0
  3671.6    0.05       0  4992.1   0.033       0  5023.1    0.05       0
  6236.6    0.12       0  6958.4    0.05       0
Bank Sta=4992.1,5023.1
Exp/Cntr=0.3,0.1

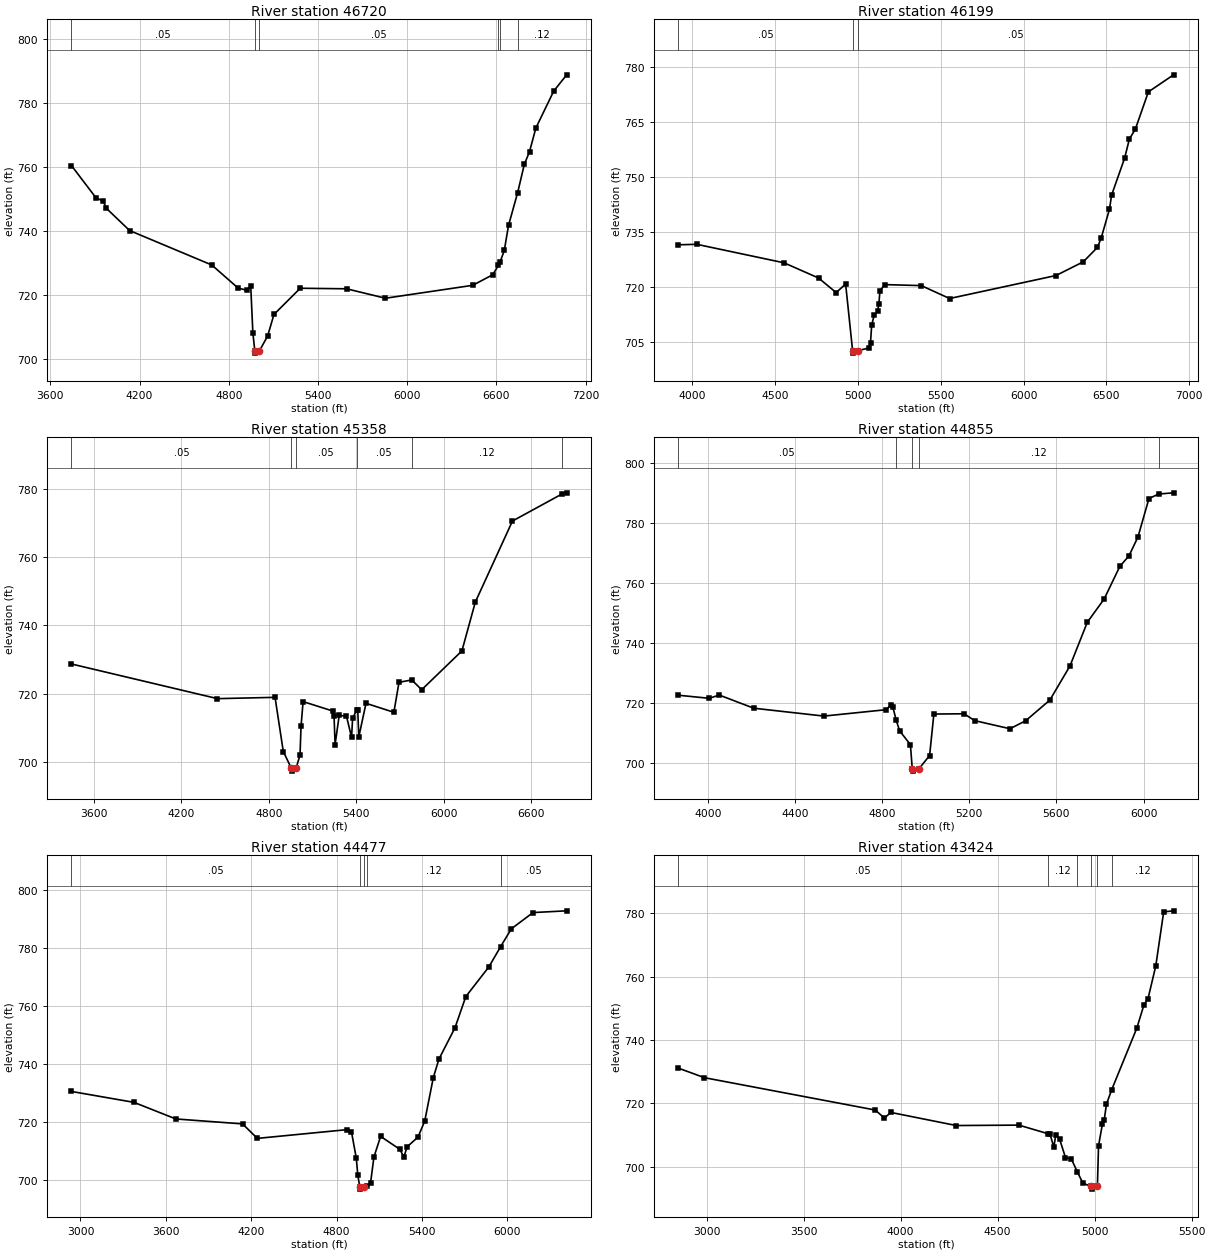
Type RM Length L Ch R = 1,46720,521,521,521
BEGIN DESCRIPTION:
Oliver Creek 58.0
END DESCRIPTION:
XS GIS Cut Line= 3
      2308184.76      7097306.11      2307356.21      7096359.90
      2305919.18      7094866.93
#Sta/Elev= 30
  3742.3  760.32  3906.9  750.25  3956.2  749.18  3977.1  746.95  4133.7  739.99
  4686.0  729.23  4863.5  721.99  4920.1  721.37  4948.0  722.55  4962.2  708.08
  4975.2  702.38  4978.2  701.68  5006.2  702.38  5061.6  707.03  5104.0  713.77
  5280.8  721.96  5592.1  721.79  5853.7  718.84  6440.8  722.88  6575.1  726.19
  6613.1  729.08  6624.6  730.17  6652.8  733.78  6681.1  741.58  6742.7  751.86
  6787.3  760.66  6822.6  764.69  6865.0  772.03  6985.2  783.59  7072.2  788.67
#Mann=6,-1,0
  3742.3    0.05       0  4975.2   0.033       0  5006.2    0.05       0
  6613.1    0.12       0  6624.6    0.05       0  6742.7    0.12       0
Bank Sta=4975.2,5006.2
Exp/Cntr=0.3,0.1

Type RM Length L Ch R = 1,46199,841,841,841
BEGIN DESCRIPTION:
Oliver Creek 57.0
END DESCRIPTION:
XS GIS Cut Line= 3
      2308397.86      7096555.25      2307529.06      7095905.48
      2306010.93      7094754.53
#Sta/Elev= 30
  3915.1  731.46  4026.1  731.60  4553.4  726.54  4761.8  722.38  4868.1  718.40
  4925.2  720.75  4967.2  702.55  4970.2  701.85  4998.2  702.55  5068.1  703.25
  5075.4  704.70  5082.6  709.54  5097.2  712.15  5118.0  713.25  5125.6  715.16
  5132.5  718.93  5161.6  720.58  5382.2  720.31  5552.8  716.78  6195.5  723.07
  6359.9  726.81  6445.2  730.74  6468.0  733.30  6517.9  741.14  6531.1  745.06
  6609.5  755.14  6638.6  760.42  6674.0  763.03  6753.0  773.27  6905.1  777.93
#Mann=3,-1,0
  3915.1    0.05       0  4967.2   0.033       0  4998.2    0.05       0
Bank Sta=4967.2,4998.2
Exp/Cntr=0.3,0.1

Type RM Length L Ch R = 1,45358,503,503,503
BEGIN DESCRIPTION:
Oliver Creek 56.0
END DESCRIPTION:
XS GIS Cut Line= 3
      2308505.97      7096399.04      2307605.16      7095133.13
      2306319.80      7093813.59
#Sta/Elev= 30
  3446.3  728.67  4447.7  718.49  4842.5  718.87  4899.0  702.96  4954.8  698.00
  4957.8  697.20  4985.8  698.00  5013.7  701.89  5020.7  710.35  5034.8  717.62
  5240.0  714.83  5247.0  713.40  5254.2  705.02  5282.4  713.56  5331.9  713.36
  5367.3  707.15  5374.3  712.70  5401.9  715.15  5409.6  715.11  5416.7  707.24
  5466.2  717.12  5657.2  714.48  5692.5  723.29  5779.8  723.98  5848.1  721.11
  6123.8  732.51  6215.9  746.87  6470.3  770.65  6813.0  778.67  6842.1  778.94
#Mann=6,-1,0
  3446.3    0.05       0  4954.8    0.07       0  4985.8    0.05       0
  5401.9    0.05       0  5779.8    0.12       0  6813.0    0.05       0
Bank Sta=4954.8,4985.8
Exp/Cntr=0.3,0.1

Type RM Length L Ch R = 1,44855,378,378,378
BEGIN DESCRIPTION:
Oliver Creek 55.0
END DESCRIPTION:
XS GIS Cut Line= 3
      2308338.01      7095928.74      2307988.02      7094828.77
      2307673.15      7093753.22
#Sta/Elev= 30
  3863.1  722.52  4005.8  721.49  4050.7  722.59  4209.7  718.18  4532.0  715.55
  4816.7  717.68  4837.9  719.11  4848.2  718.66  4864.2  714.11  4879.7  710.63
  4929.3  705.99  4937.7  697.95  4940.7  697.15  4968.7  697.95  5017.4  702.36
  5037.0  716.23  5175.9  716.32  5224.5  714.03  5386.8  711.32  5458.9  714.00
  5569.6  720.88  5662.2  732.30  5741.9  746.92  5819.2  754.68  5891.4  765.61
  5933.1  769.09  5974.7  775.45  6025.0  788.27  6069.7  789.78  6138.1  790.18
#Mann=5,-1,0
  3863.1    0.05       0  4864.2    0.12       0  4937.7    0.07       0
  4968.7    0.12       0  6069.7    0.05       0
Bank Sta=4937.7,4968.7
Exp/Cntr=0.3,0.1

Type RM Length L Ch R = 1,44477,1053,1053,1053
BEGIN DESCRIPTION:
Oliver Creek 54.0
END DESCRIPTION:
XS GIS Cut Line= 3
      2308831.47      7096598.63      2308279.00      7094610.00
      2307720.39      7093308.79
#Sta/Elev= 30
  2936.3  730.56  3375.6  726.80  3670.3  721.07  4138.8  719.37  4242.6  714.37
  4870.0  717.37  4904.3  716.58  4938.0  707.56  4948.9  701.59  4962.4  697.67
  4965.4  696.87  4993.4  697.67  5010.9  697.84  5038.3  699.02  5061.9  707.95
  5109.0  715.06  5243.1  710.63  5272.3  707.99  5295.6  711.48  5371.8  714.83
  5418.9  720.34  5479.1  735.31  5518.5  741.70  5631.4  752.51  5707.6  763.28
  5870.1  773.55  5952.4  780.53  6027.8  786.67  6180.0  792.26  6416.3  792.86
#Mann=5,-1,0
  2936.3    0.05       0  4962.4   0.033       0  4993.4    0.05       0
  5010.9    0.12       0  5952.4    0.05       0
Bank Sta=4962.4,4993.4
Exp/Cntr=0.3,0.1

Type RM Length L Ch R = 1,43424,629,629,629
BEGIN DESCRIPTION:
Oliver Creek 53.0
END DESCRIPTION:
XS GIS Cut Line= 3
      2309162.77      7096504.50      2309104.71      7094357.38
      2309179.01      7093959.97
#Sta/Elev= 30
  2854.6  731.11  2989.2  728.09  3869.5  717.88  3916.8  715.34  3949.5  717.13
  4286.8  712.99  4609.7  713.12  4757.9  710.44  4769.8  710.31  4789.8  706.18
  4799.8  710.01  4819.8  708.64  4849.8  702.89  4879.8  702.45  4911.5  698.31
  4939.9  694.74  4983.2  693.82  4986.2  692.92  5014.2  693.82  5020.2  706.63
  5040.5  713.58  5049.3  714.70  5060.9  719.72  5088.3  724.34  5217.4  743.72
  5254.2  751.09  5275.2  753.04  5315.2  763.39  5355.9  780.43  5406.8  780.75
#Mann=6,-1,0
  2854.6    0.05       0  4757.9    0.12       0  4911.5    0.05       0
  4983.2   0.033       0  5014.2    0.05       0  5088.3    0.12       0
Bank Sta=4983.2,5014.2
Exp/Cntr=0.3,0.1

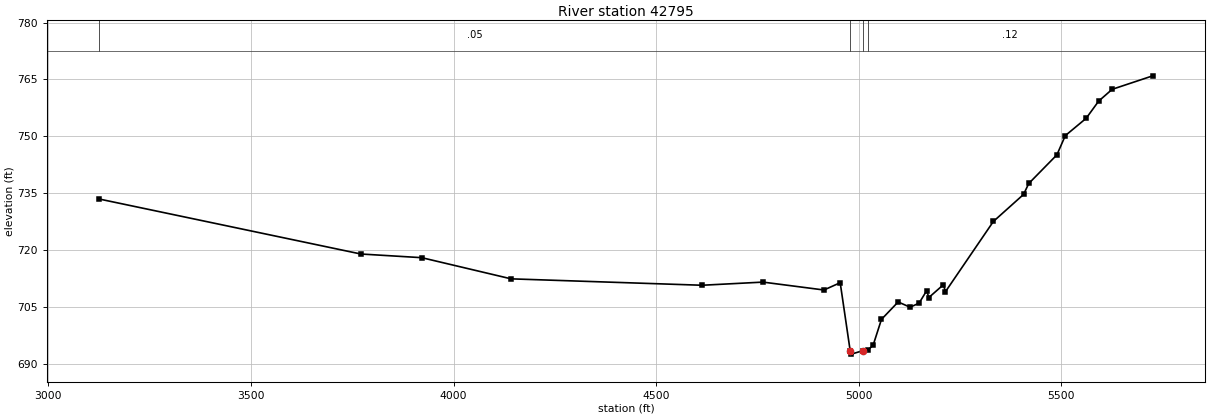
Type RM Length L Ch R = 1,42795,785,785,785
BEGIN DESCRIPTION:
Oliver Creek 52.0
END DESCRIPTION:
XS GIS Cut Line= 3
      2309748.70      7096443.66      2309615.69      7094574.19
      2309438.86      7093870.67
#Sta/Elev= 30
  3125.8  733.45  3771.1  718.96  3921.5  717.99  4142.0  712.41  4613.2  710.72
  4763.6  711.55  4914.0  709.47  4954.1  711.39  4978.7  693.46  4981.7  692.56
  5009.7  693.46  5021.9  693.61  5035.3  694.88  5055.9  701.72  5097.1  706.32
  5126.5  704.93  5148.7  706.00  5167.6  709.30  5172.7  707.47  5208.7  710.85
  5213.9  709.03  5332.1  727.54  5406.5  734.66  5419.5  737.56  5488.9  745.11
  5509.6  750.17  5561.1  754.74  5592.0  759.28  5625.2  762.38  5725.4  765.94
#Mann=4,-1,0
  3125.8    0.05       0  4978.7   0.033       0  5009.7    0.05       0
  5021.9    0.12       0
Bank Sta=4978.7,5009.7
Exp/Cntr=0.3,0.1