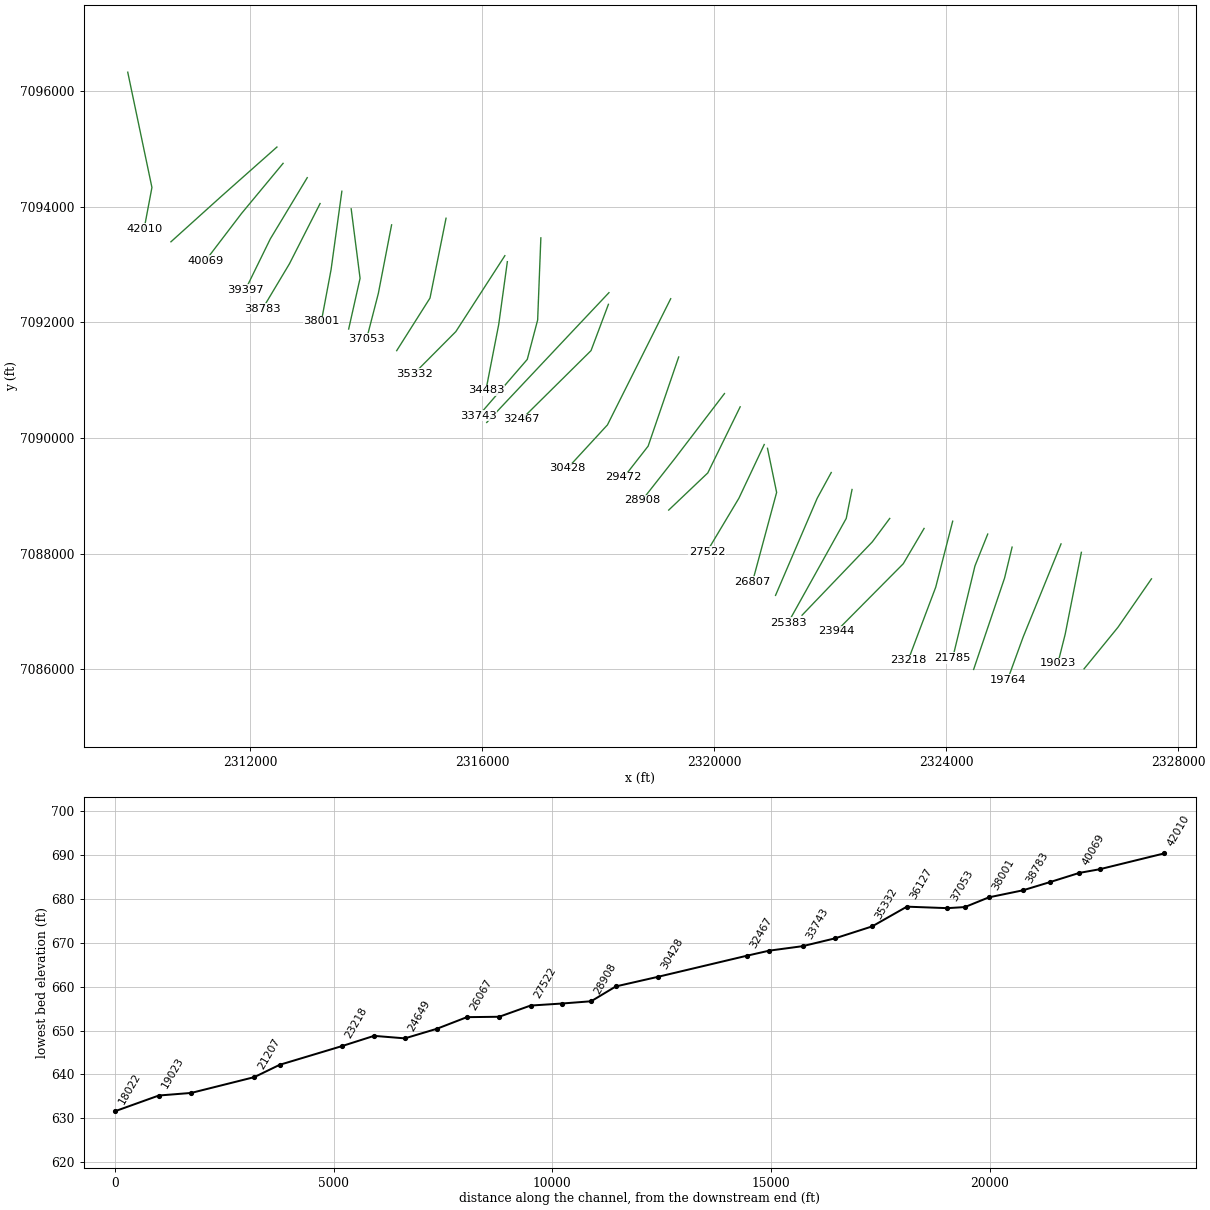
HEC-RAS study Oliver Creek.prj: Oliver Creek Base Level Engineering

--- Oliver Creek.g01 (geometry) --- (continued)

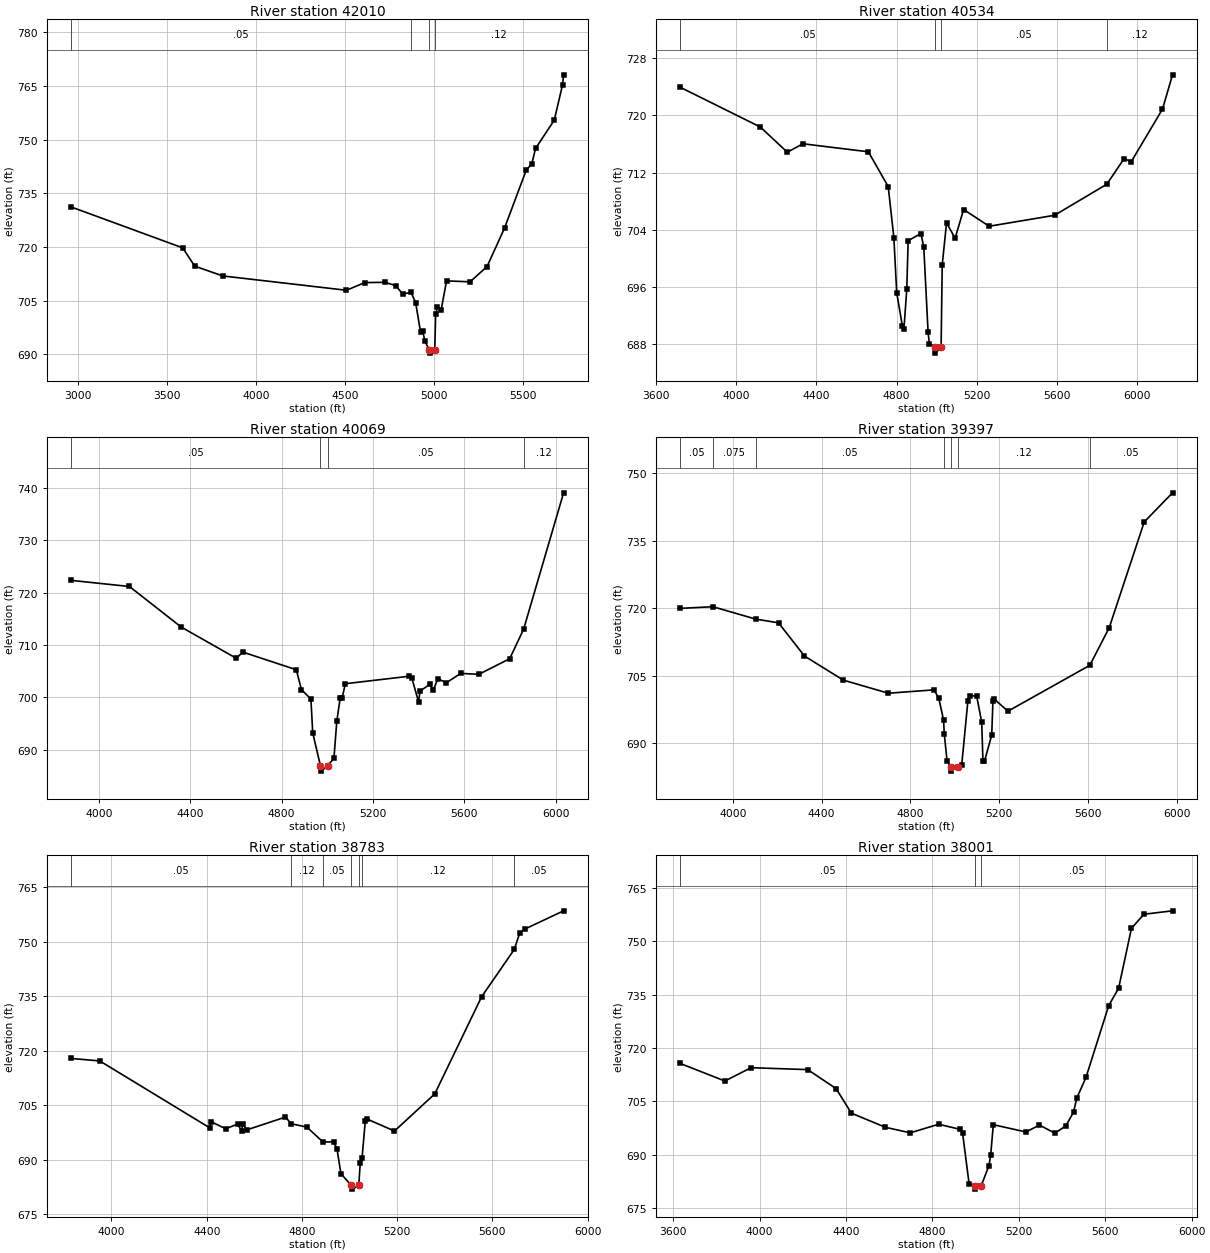
Type RM Length L Ch R = 1,42010,1476,1476,1476
BEGIN DESCRIPTION:
Oliver Creek 51.6
END DESCRIPTION:
XS GIS Cut Line= 3
      2309891.94      7096322.19      2310308.90      7094329.96
      2310174.13      7093614.24
#Sta/Elev= 30
  2964.6  731.16  3590.1  719.75  3657.3  714.65  3814.8  711.91  4509.6  707.91
  4611.7  710.05  4724.1  710.13  4785.7  709.22  4825.4  706.84  4871.5  707.34
  4897.8  704.48  4925.3  696.23  4938.7  696.42  4948.9  693.80  4974.2  691.26
  4977.2  690.36  5005.2  691.26  5010.1  701.26  5020.3  703.10  5040.7  702.38
  5071.2  710.53  5203.5  710.27  5298.4  714.52  5396.8  725.28  5518.9  741.49
  5549.5  743.17  5570.9  747.51  5675.8  755.39  5722.4  765.26  5728.3  768.06
#Mann=4,-1,0
  2964.6    0.05       0  4871.5    0.12       0  4974.2    0.07       0
  5005.2    0.12       0
Bank Sta=4974.2,5005.2
Exp/Cntr=0.3,0.1

Type RM Length L Ch R = 1,40534,465,465,465
BEGIN DESCRIPTION:
Oliver Creek 51.4
END DESCRIPTION:
XS GIS Cut Line= 3
      2312463.79      7095028.76      2311508.61      7094179.84
      2310636.93      7093391.49
#Sta/Elev= 30
  3722.1  723.92  4121.2  718.37  4255.8  714.84  4333.6  716.02  4659.7  714.90
  4758.7  710.03  4786.8  702.87  4801.0  695.18  4829.4  690.51  4837.0  690.14
  4851.2  695.74  4857.9  702.47  4921.4  703.47  4935.7  701.60  4957.4  689.64
  4964.1  688.00  4991.2  687.65  4994.2  686.75  5022.2  687.65  5027.7  699.08
  5049.3  704.97  5091.9  702.81  5134.3  706.83  5261.5  704.49  5587.3  706.02
  5847.7  710.36  5934.0  713.94  5969.9  713.53  6125.3  720.86  6175.3  725.66
#Mann=4,-1,0
  3722.1    0.05       0  4991.2   0.033       0  5022.2    0.05       0
  5847.7    0.12       0
Bank Sta=4991.2,5022.2
Exp/Cntr=0.3,0.1

Type RM Length L Ch R = 1,40069,672,672,672
BEGIN DESCRIPTION:
Oliver Creek 51.0
END DESCRIPTION:
XS GIS Cut Line= 3
      2312569.88      7094746.65      2311855.69      7093883.38
      2311229.03      7093060.04
#Sta/Elev= 30
  3879.6  722.33  4134.1  721.17  4360.7  713.43  4602.1  707.46  4630.3  708.65
  4864.8  705.27  4887.0  701.48  4928.6  699.69  4936.5  693.23  4970.4  686.92
  4973.4  685.92  5001.4  686.92  5029.4  688.38  5042.0  695.48  5056.6  699.83
  5064.8  699.82  5079.4  702.61  5356.1  704.02  5370.5  703.68  5399.6  699.18
  5406.4  701.21  5449.5  702.50  5464.0  701.35  5484.8  703.60  5520.2  702.76
  5584.6  704.58  5663.6  704.40  5798.8  707.38  5860.0  713.05  6034.7  739.05
#Mann=4,-1,0
  3879.6    0.05       0  4970.4   0.033       0  5001.4    0.05       0
  5860.0    0.12       0
Bank Sta=4970.4,5001.4
Exp/Cntr=0.3,0.1

Type RM Length L Ch R = 1,39397,614,614,614
BEGIN DESCRIPTION:
Oliver Creek 50.0
END DESCRIPTION:
XS GIS Cut Line= 3
      2312986.56      7094499.27      2312349.04      7093440.02
      2311918.84      7092559.16
#Sta/Elev= 30
  3763.7  719.99  3911.0  720.35  4103.8  717.60  4206.4  716.77  4323.1  709.40
  4498.1  704.04  4701.0  701.13  4906.6  701.88  4928.2  699.98  4949.6  695.13
  4952.5  692.18  4965.0  686.17  4981.6  684.82  4984.6  683.82  5012.6  684.82
  5031.1  685.15  5059.1  699.48  5066.8  700.61  5098.6  700.47  5121.2  694.69
  5126.7  686.16  5133.6  686.02  5166.2  691.79  5171.8  699.41  5178.1  699.81
  5239.3  697.14  5607.9  707.33  5695.3  715.69  5853.0  739.20  5980.3  745.66
#Mann=7,-1,0
  3763.7    0.05       0  3911.0   0.075       0  4103.8    0.05       0
  4952.5    0.12       0  4981.6    0.07       0  5012.6    0.12       0
  5607.9    0.05       0
Bank Sta=4981.6,5012.6
Exp/Cntr=0.3,0.1

Type RM Length L Ch R = 1,38783,782,782,782
BEGIN DESCRIPTION:
Oliver Creek 49.0
END DESCRIPTION:
XS GIS Cut Line= 3
      2313207.89      7094052.17      2312679.00      7093010.00
      2312218.33      7092237.99
#Sta/Elev= 30
  3831.2  717.92  3950.8  717.24  4412.7  698.83  4418.3  700.52  4479.5  698.58
  4529.7  699.85  4546.3  698.02  4551.9  699.81  4568.6  698.27  4730.8  701.79
  4755.0  699.95  4820.5  699.04  4888.3  694.94  4932.6  694.96  4947.0  693.10
  4963.7  686.20  5007.7  682.96  5010.7  681.96  5038.7  682.96  5044.7  689.08
  5052.5  690.60  5066.1  700.73  5071.9  701.28  5188.7  697.95  5358.0  708.18
  5554.6  734.90  5692.1  747.96  5714.1  752.34  5735.5  753.51  5898.9  758.55
#Mann=7,-1,0
  3831.2    0.05       0  4755.0    0.12       0  4888.3    0.05       0
  5007.7   0.033       0  5038.7    0.05       0  5052.5    0.12       0
  5692.1    0.05       0
Bank Sta=5007.7,5038.7
Exp/Cntr=0.3,0.1

Type RM Length L Ch R = 1,38001,547,547,547
BEGIN DESCRIPTION:
Oliver Creek 48.0
END DESCRIPTION:
XS GIS Cut Line= 3
      2313583.34      7094264.90      2313397.43      7092910.60
      2313229.67      7092014.77
#Sta/Elev= 30
  3633.0  715.66  3839.8  710.73  3960.9  714.47  4223.4  713.93  4354.6  708.58
  4425.3  701.69  4582.9  697.72  4697.8  696.17  4829.0  698.58  4929.9  697.13
  4940.0  696.02  4970.3  681.71  4995.2  681.35  4998.3  680.35  5026.3  681.35
  5061.7  686.93  5069.8  689.84  5082.0  698.46  5232.7  696.41  5295.6  698.34
  5366.9  696.08  5417.7  698.12  5453.3  702.00  5468.6  705.97  5511.0  711.75
  5616.2  731.93  5661.9  736.80  5721.4  753.63  5779.1  757.59  5911.4  758.55
#Mann=3,-1,0
  3633.0    0.05       0  4995.2   0.033       0  5026.3    0.05       0
Bank Sta=4995.2,5026.3
Exp/Cntr=0.3,0.1

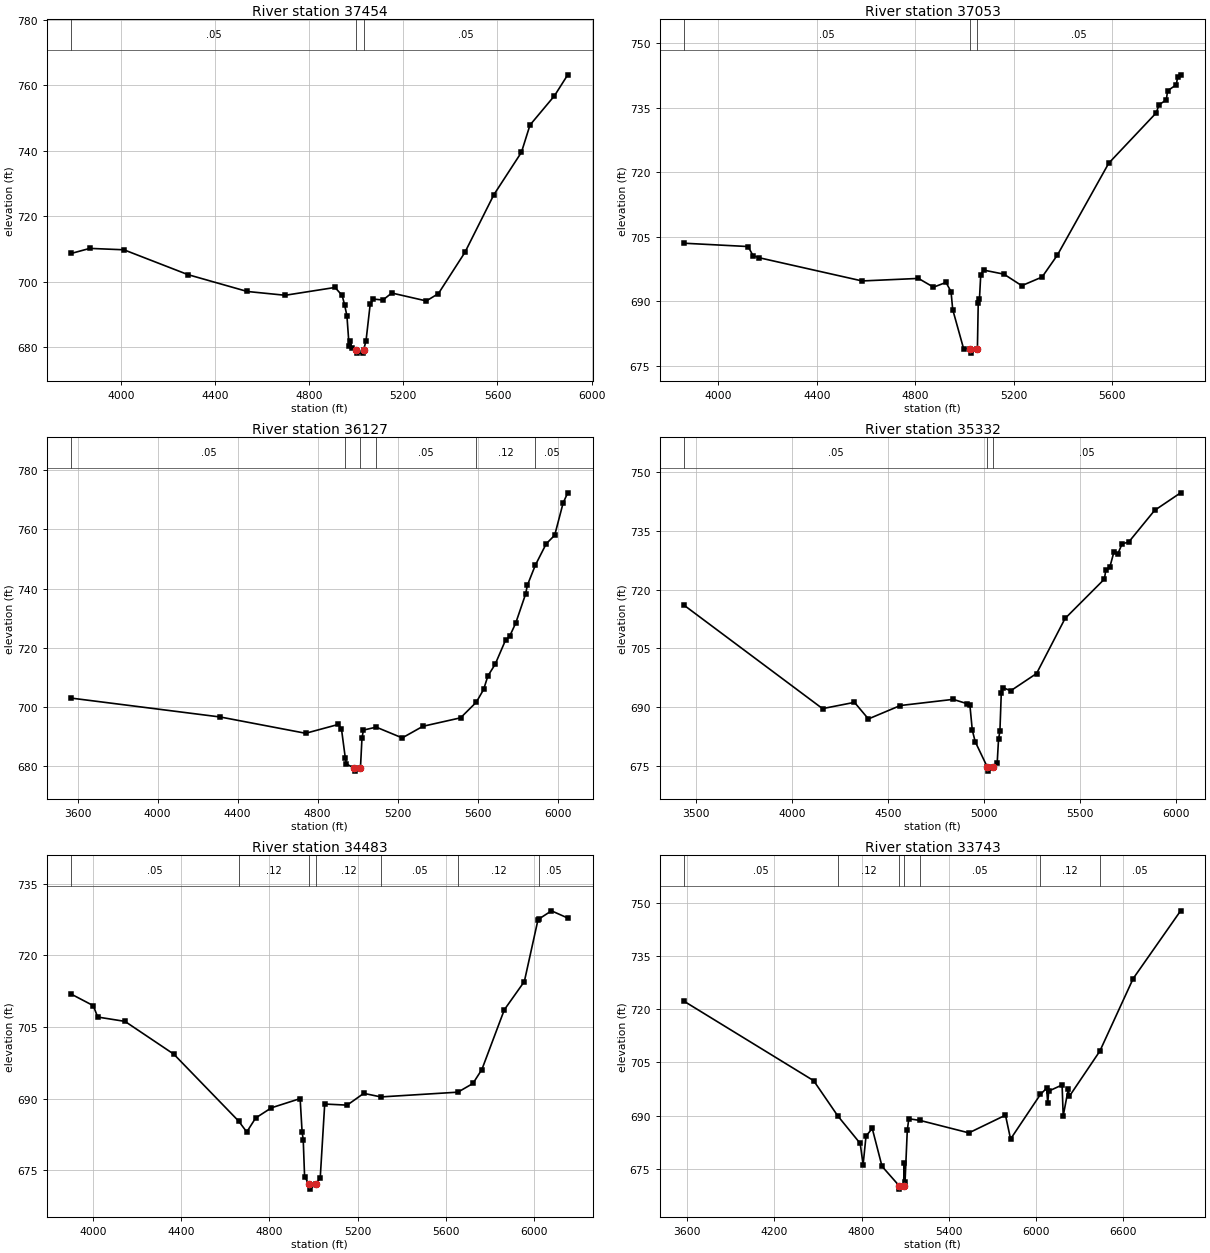
Type RM Length L Ch R = 1,37454,401,401,401
BEGIN DESCRIPTION:
Oliver Creek 47.0
END DESCRIPTION:
XS GIS Cut Line= 3
      2313743.93      7093961.12      2313897.34      7092760.38
      2313700.85      7091883.52
#Sta/Elev= 30
  3789.5  708.61  3867.6  710.13  4012.4  709.70  4284.6  702.11  4536.6  696.97
  4697.9  695.81  4909.6  698.20  4939.9  695.75  4950.0  692.95  4960.1  689.56
  4969.4  680.34  4974.4  681.99  4980.2  679.78  5000.0  679.14  5003.0  678.14
  5028.0  678.14  5031.1  679.14  5041.4  681.95  5058.9  693.00  5072.1  694.66
  5113.1  694.36  5150.7  696.50  5297.6  694.08  5348.8  696.31  5461.5  708.90
  5584.5  726.51  5701.8  739.48  5738.2  747.81  5842.2  756.74  5898.6  763.14
#Mann=3,-1,0
  3789.5    0.05       0  5000.0   0.033       0  5031.1    0.05       0
Bank Sta=5000,5031.1
Exp/Cntr=0.3,0.1

Type RM Length L Ch R = 1,37053,926,926,926
BEGIN DESCRIPTION:
Oliver Creek 46.5
END DESCRIPTION:
XS GIS Cut Line= 3
      2314440.98      7093684.28      2314212.04      7092497.92
      2314010.57      7091714.76
#Sta/Elev= 30
  3861.4  703.47  4120.4  702.70  4140.7  700.58  4164.2  700.11  4584.0  694.69
  4812.9  695.28  4874.0  693.24  4924.9  694.35  4945.3  692.19  4952.1  688.03
  4996.2  678.96  5021.4  678.89  5024.5  677.89  5052.5  678.89  5055.8  689.47
  5060.9  690.58  5066.0  696.12  5077.8  697.22  5160.4  696.27  5232.7  693.59
  5315.3  695.60  5377.3  700.69  5586.3  722.11  5779.5  733.83  5790.3  735.68
  5820.3  736.85  5825.4  738.95  5861.0  740.37  5866.1  742.19  5878.3  742.67
#Mann=3,-1,0
  3861.4    0.05       0  5021.4   0.033       0  5052.5    0.05       0
Bank Sta=5021.4,5052.5
Exp/Cntr=0.3,0.1

Type RM Length L Ch R = 1,36127,795,795,795
BEGIN DESCRIPTION:
Oliver Creek 46.0
END DESCRIPTION:
XS GIS Cut Line= 3
      2315379.50      7093798.30      2315102.97      7092418.79
      2314529.01      7091510.02
#Sta/Elev= 30
  3569.1  702.92  4313.2  696.54  4740.2  691.03  4903.4  694.02  4919.3  692.51
  4938.3  682.79  4944.2  680.66  4982.9  679.23  4985.9  678.23  5014.2  679.23
  5021.9  689.44  5029.1  692.11  5093.1  693.11  5223.2  689.47  5326.7  693.40
  5515.0  696.26  5593.4  701.53  5630.3  705.86  5651.5  710.42  5688.0  714.37
  5739.7  722.52  5760.9  723.92  5790.7  728.29  5839.8  738.06  5849.1  741.11
  5888.5  747.84  5943.2  755.13  5985.6  758.02  6028.0  768.97  6050.9  772.37
#Mann=6,-1,0
  3569.1    0.05       0  4938.3    0.12       0  5014.2    0.12       0
  5093.1    0.05       0  5593.4    0.12       0  5888.5    0.05       0
Bank Sta=4982.9,5014.2
Exp/Cntr=0.3,0.1

Type RM Length L Ch R = 1,35332,849,849,849
BEGIN DESCRIPTION:
Oliver Creek 45.0
END DESCRIPTION:
XS GIS Cut Line= 3
      2316393.52      7093150.87      2315548.82      7091839.59
      2314826.66      7091110.93
#Sta/Elev= 30
  3440.2  715.96  4160.2  689.66  4326.6  691.26  4399.2  687.03  4565.5  690.45
  4840.8  692.02  4913.4  690.92  4928.1  690.52  4940.5  684.19  4955.7  681.23
  5019.2  674.73  5022.3  673.73  5050.6  674.73  5070.3  675.83  5077.4  681.97
  5084.4  683.86  5091.5  693.59  5098.6  695.03  5141.0  694.22  5275.4  698.61
  5423.8  712.63  5628.9  722.68  5636.0  724.92  5657.2  725.74  5678.4  729.57
  5699.6  729.19  5720.8  731.63  5756.2  732.15  5890.5  740.19  6025.9  744.66
#Mann=3,-1,0
  3440.2    0.05       0  5019.2    0.05       0  5050.6    0.05       0
Bank Sta=5019.2,5050.6
Exp/Cntr=0.3,0.1

Type RM Length L Ch R = 1,34483,740,740,740
BEGIN DESCRIPTION:
Oliver Creek 44.4
END DESCRIPTION:
XS GIS Cut Line= 3
      2316436.63      7093047.89      2316288.08      7091964.08
      2316067.24      7090827.58
#Sta/Elev= 30
  3902.0  711.87  4000.8  709.48  4021.0  707.09  4144.7  706.18  4366.2  699.31
  4660.6  685.27  4697.3  682.99  4737.6  685.92  4809.2  688.06  4939.5  689.99
  4948.4  682.98  4953.5  681.39  4959.7  673.65  4979.7  672.01  4982.8  671.01
  5011.2  672.01  5030.7  673.40  5051.0  688.85  5152.9  688.62  5228.2  691.09
  5305.8  690.34  5655.4  691.34  5723.4  693.16  5764.1  696.09  5866.0  708.62
  5956.8  714.54  6018.8  727.51  6025.0  727.71  6079.9  729.36  6153.7  727.85
#Mann=7,-1,0
  3902.0    0.05       0  4660.6    0.12       0  4979.7    0.07       0
  5011.2    0.12       0  5305.8    0.05       0  5655.4    0.12       0
  6025.0    0.05       0
Bank Sta=4979.7,5011.2
Exp/Cntr=0.3,0.1

Type RM Length L Ch R = 1,33743,763,763,763
BEGIN DESCRIPTION:
Oliver Creek 44.2
END DESCRIPTION:
XS GIS Cut Line= 4
      2317014.19      7093459.00      2316958.97      7092040.07
      2316779.81      7091358.35      2315937.81      7090381.80
#Sta/Elev= 30
  3580.0  722.25  4469.7  699.86  4635.9  689.90  4789.9  682.14  4809.9  676.10
  4829.9  684.21  4872.8  686.37  4940.0  675.67  5056.7  670.23  5059.8  669.23
  5088.2  670.23  5093.1  676.60  5098.3  671.13  5113.8  685.80  5124.2  689.11
  5202.1  688.63  5537.7  685.12  5789.4  690.12  5824.5  683.38  6030.0  695.99
  6072.5  697.74  6080.2  693.52  6086.8  696.92  6178.9  698.65  6186.6  689.92
  6221.7  697.52  6229.3  695.47  6438.6  708.21  6668.2  728.72  6994.3  747.84
#Mann=7,-1,0
  3580.0    0.05       0  4635.9    0.12       0  5056.7    0.07       0
  5088.2    0.12       0  5202.1    0.05       0  6030.0    0.12       0
  6438.6    0.05       0
Bank Sta=5056.7,5088.2
Exp/Cntr=0.3,0.1

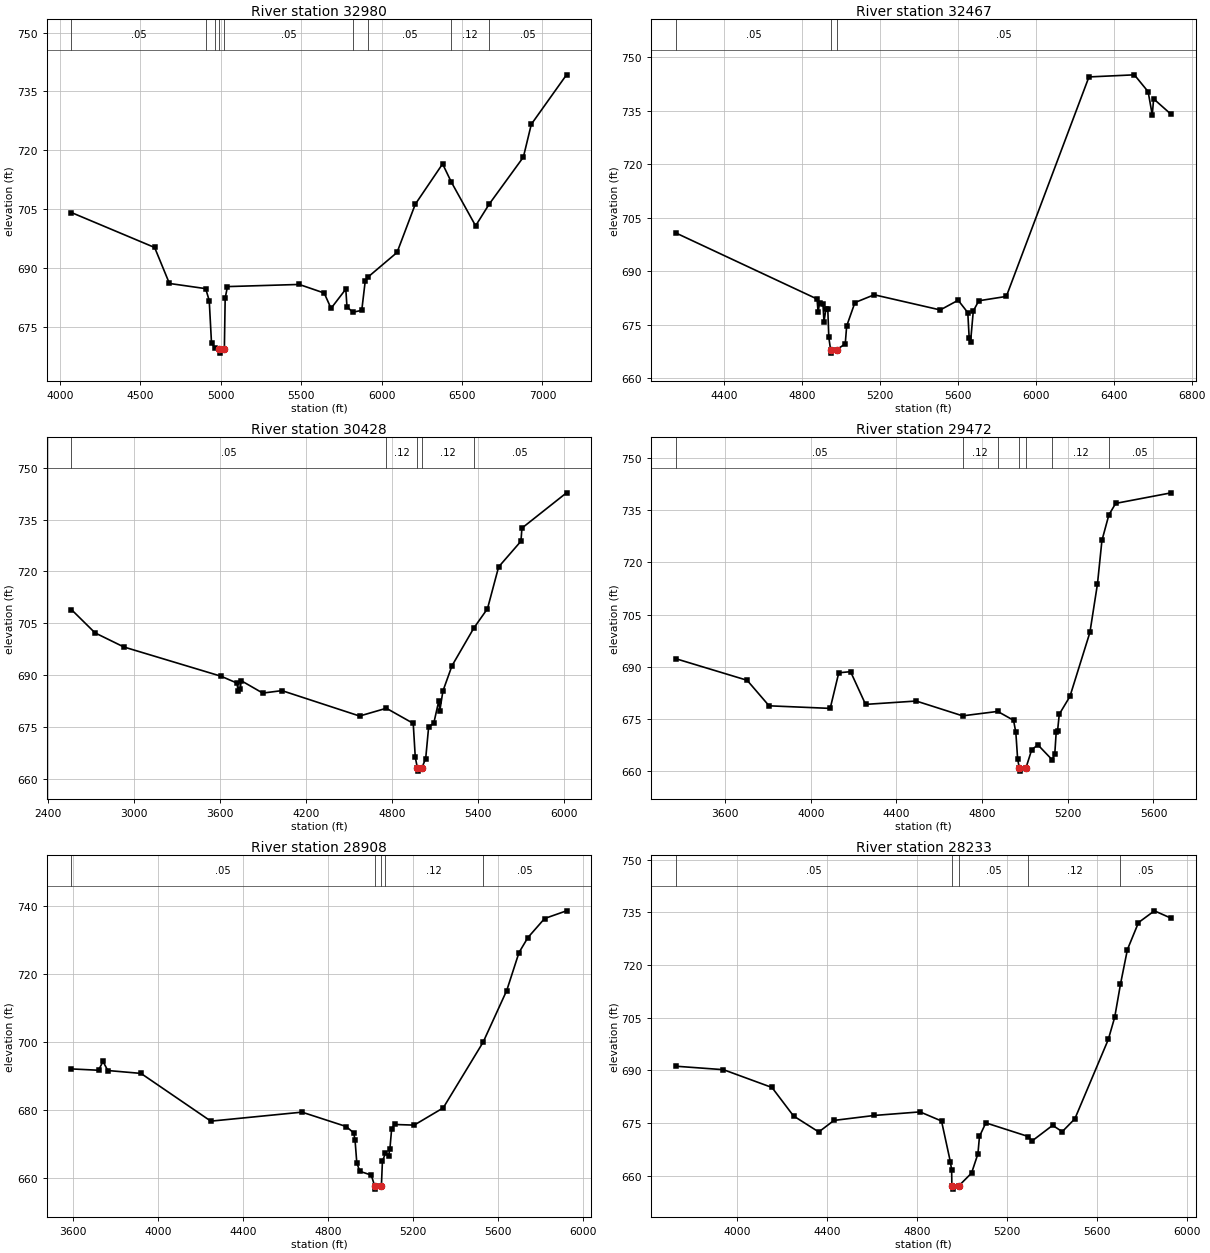
Type RM Length L Ch R = 1,32980,513,513,513
BEGIN DESCRIPTION:
Oliver Creek 44.0
END DESCRIPTION:
XS GIS Cut Line= 3
      2318188.20      7092512.01      2317552.20      7091836.36
      2316081.02      7090268.93
#Sta/Elev= 30
  4072.1  704.09  4589.4  695.17  4681.2  685.99  4906.6  684.67  4928.8  681.61
  4943.0  670.73  4965.8  669.54  4991.1  669.21  4994.2  668.21  5022.8  669.21
  5027.9  682.26  5042.1  685.19  5488.0  685.74  5643.4  683.55  5685.9  679.63
  5777.7  684.54  5785.0  680.07  5820.4  678.65  5876.9  679.12  5898.3  686.54
  5915.8  687.63  6096.2  693.90  6209.5  706.20  6379.4  716.51  6433.7  711.87
  6584.6  700.70  6668.6  706.21  6881.6  718.24  6930.9  726.62  7149.7  739.24
#Mann=9,-1,0
  4072.1    0.05       0  4906.6    0.12       0  4965.8    0.05       0
  4991.1   0.033       0  5022.8    0.05       0  5820.4    0.12       0
  5915.8    0.05       0  6433.7    0.12       0  6668.6    0.05       0
Bank Sta=4991.1,5022.8
Exp/Cntr=0.3,0.1

Type RM Length L Ch R = 1,32467,2039,2039,2039
BEGIN DESCRIPTION:
Oliver Creek 43.0
END DESCRIPTION:
XS GIS Cut Line= 3
      2318179.01      7092310.03      2317879.00      7091510.00
      2316680.00      7090321.04
#Sta/Elev= 30
  4152.2  700.68  4875.8  682.22  4881.1  678.60  4889.2  681.12  4906.1  680.88
  4911.4  675.87  4921.2  679.31  4931.0  679.38  4936.3  671.43  4945.3  668.05
  4948.5  667.05  4977.1  668.05  5020.7  669.63  5027.9  674.62  5070.3  681.21
  5169.3  683.40  5508.7  679.15  5600.6  681.87  5650.1  678.40  5657.2  671.32
  5664.3  670.16  5678.4  678.86  5706.7  681.72  5848.1  682.94  6272.4  744.44
  6505.7  745.03  6576.4  740.31  6597.7  733.79  6604.7  738.30  6695.2  733.92
#Mann=3,-1,0
  4152.2    0.05       0  4945.3   0.033       0  4977.1    0.05       0
Bank Sta=4945.3,4977.1
Exp/Cntr=0.3,0.1

Type RM Length L Ch R = 1,30428,956,956,956
BEGIN DESCRIPTION:
Oliver Creek 41.0
END DESCRIPTION:
XS GIS Cut Line= 3
      2319252.89      7092407.46      2318162.05      7090226.55
      2317472.81      7089476.42
#Sta/Elev= 30
  2561.5  708.97  2726.4  702.23  2927.6  698.15  3606.9  689.68  3718.7  687.68
  3724.3  685.41  3741.0  686.01  3746.6  688.41  3897.5  684.81  4031.7  685.52
  4573.9  678.17  4760.8  680.42  4948.4  676.04  4962.6  666.25  4977.1  663.23
  4980.3  662.23  5009.0  663.23  5035.4  665.87  5056.3  675.13  5091.5  676.03
  5127.2  682.63  5134.0  679.70  5155.6  685.38  5219.1  692.72  5371.4  703.61
  5467.0  709.24  5544.6  721.31  5700.6  728.75  5707.4  732.54  6018.7  742.75
#Mann=5,-1,0
  2561.5    0.05       0  4760.8    0.12       0  4977.1    0.07       0
  5009.0    0.12       0  5371.4    0.05       0
Bank Sta=4977.1,5009
Exp/Cntr=0.3,0.1

Type RM Length L Ch R = 1,29472,564,564,564
BEGIN DESCRIPTION:
Oliver Creek 40.0
END DESCRIPTION:
XS GIS Cut Line= 3
      2319390.43      7091400.37      2318863.94      7089859.86
      2318444.13      7089320.98
#Sta/Elev= 30
  3372.0  692.30  3703.2  686.14  3805.7  678.81  4091.0  678.07  4131.0  688.29
  4186.1  688.61  4256.2  679.22  4492.6  680.18  4709.1  675.93  4872.9  677.20
  4947.0  674.65  4957.6  671.16  4965.9  663.63  4973.3  661.06  4976.5  660.06
  5005.2  661.06  5032.0  666.26  5060.9  667.58  5126.8  663.34  5139.3  664.86
  5146.0  671.27  5152.3  671.57  5160.4  676.40  5210.2  681.51  5303.4  699.89
  5338.7  713.81  5359.5  726.27  5391.8  733.60  5423.7  736.92  5683.1  739.95
#Mann=7,-1,0
  3372.0    0.05       0  4709.1    0.12       0  4872.9    0.05       0
  4973.3   0.033       0  5005.2    0.05       0  5126.8    0.12       0
  5391.8    0.05       0
Bank Sta=4973.3,5005.2
Exp/Cntr=0.3,0.1

Type RM Length L Ch R = 1,28908,675,675,675
BEGIN DESCRIPTION:
Oliver Creek 39.0
END DESCRIPTION:
XS GIS Cut Line= 3
      2320179.79      7090768.09      2319327.29      7089649.27
      2318759.91      7088924.67
#Sta/Elev= 30
  3593.4  692.08  3720.7  691.69  3741.9  694.27  3764.3  691.61  3920.3  690.76
  4248.7  676.70  4677.0  679.35  4884.8  675.12  4920.1  673.24  4926.4  671.15
  4934.7  664.41  4948.8  661.93  5002.7  660.81  5018.3  657.68  5021.5  656.68
  5050.3  657.68  5055.1  664.87  5069.2  667.25  5084.0  666.48  5090.4  668.60
  5098.5  674.45  5112.9  675.72  5204.3  675.53  5340.8  680.60  5528.3  699.94
  5639.2  715.15  5697.0  726.35  5738.7  730.75  5817.3  736.37  5920.3  738.64
#Mann=5,-1,0
  3593.4    0.05       0  5018.3   0.033       0  5050.3    0.05       0
  5069.2    0.12       0  5528.3    0.05       0
Bank Sta=5018.3,5050.3
Exp/Cntr=0.3,0.1

Type RM Length L Ch R = 1,28233,711,711,711
BEGIN DESCRIPTION:
Oliver Creek 38.0
END DESCRIPTION:
XS GIS Cut Line= 3
      2320450.59      7090538.87      2319892.38      7089396.79
      2319218.44      7088754.62
#Sta/Elev= 30
  3728.8  691.18  3939.0  690.20  4154.9  685.13  4250.7  677.02  4363.1  672.45
  4430.7  675.74  4610.8  677.16  4813.5  678.17  4909.1  675.57  4948.6  663.89
  4954.1  661.58  4955.1  657.16  4958.3  656.16  4987.1  657.16  5042.6  660.73
  5071.0  666.22  5077.9  671.19  5106.2  675.04  5295.5  671.14  5311.2  669.86
  5403.4  674.34  5445.9  672.53  5502.2  676.21  5650.9  698.81  5679.3  705.12
  5705.0  714.54  5735.9  724.43  5785.2  732.13  5856.0  735.47  5930.9  733.35
#Mann=5,-1,0
  3728.8    0.05       0  4955.1   0.033       0  4987.1    0.05       0
  5295.5    0.12       0  5705.0    0.05       0
Bank Sta=4955.1,4987.1
Exp/Cntr=0.3,0.1

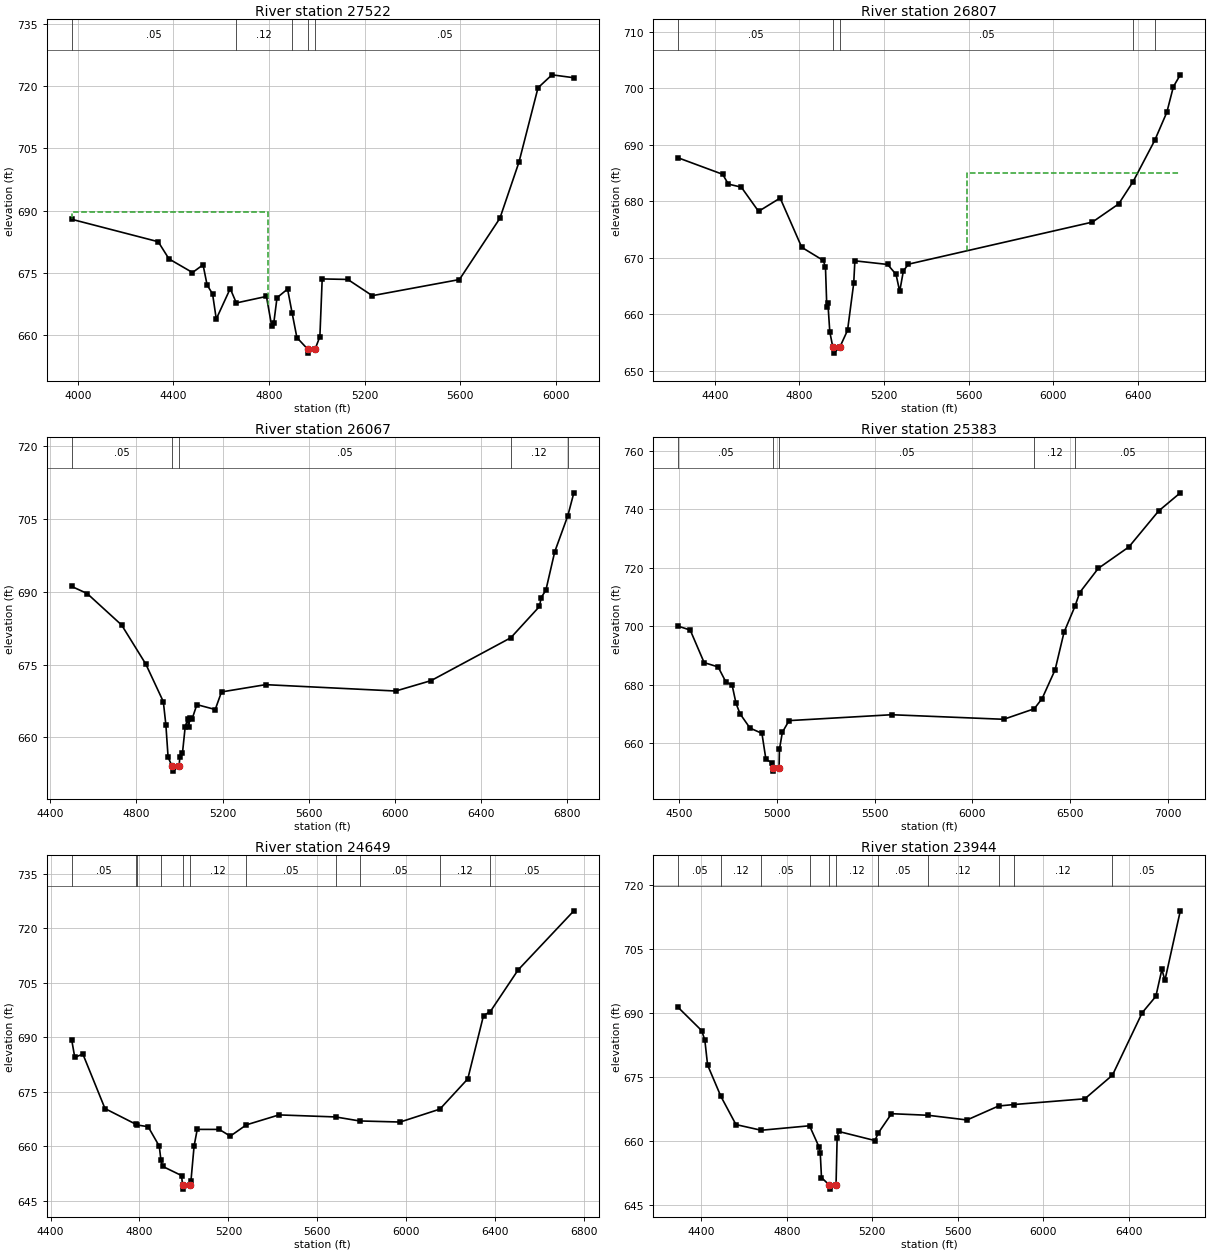
Type RM Length L Ch R = 1,27522,715,715,715
BEGIN DESCRIPTION:
Oliver Creek 37.0
END DESCRIPTION:
XS GIS Cut Line= 3
      2320865.31      7089887.15      2320429.00      7088960.00
      2319877.71      7088035.46
#Sta/Elev= 30
  3974.8  687.91  4336.4  682.52  4381.6  678.38  4480.0  675.10  4524.2  676.96
  4541.2  672.10  4564.0  669.96  4579.5  663.91  4637.9  671.23  4663.4  667.78
  4789.5  669.35  4811.6  662.16  4820.2  662.96  4833.7  669.04  4877.9  671.12
  4896.7  665.43  4916.9  659.44  4961.4  656.70  4964.6  655.70  4993.4  656.70
  5013.1  659.69  5022.8  673.56  5129.9  673.44  5232.3  669.53  5597.0  673.41
  5766.4  688.16  5846.2  701.66  5926.0  719.57  5984.4  722.69  6075.9  721.99
#Mann=5,-1,0
  3974.8    0.05       0  4663.4    0.12       0  4896.7    0.05       0
  4961.4   0.033       0  4993.4    0.05       0
#XS Ineff=2,0
    0.00 4795.70  689.72               0
Permanent Ineff=
       F       F
Bank Sta=4961.4,4993.4
Exp/Cntr=0.3,0.1

Type RM Length L Ch R = 1,26807,740,740,740
BEGIN DESCRIPTION:
Oliver Creek 36.0
END DESCRIPTION:
XS GIS Cut Line= 3
      2320921.75      7089822.05      2321079.00      7089060.00
      2320664.17      7087518.45
#Sta/Elev= 30
  4227.1  687.68  4437.3  684.77  4464.0  683.04  4525.3  682.50  4607.0  678.22
  4709.1  680.57  4811.2  671.86  4913.3  669.53  4923.5  668.30  4929.8  661.24
  4934.9  661.97  4943.9  656.91  4958.5  654.15  4961.8  653.15  4990.6  654.15
  5027.8  657.18  5057.0  665.50  5062.5  669.47  5217.2  668.83  5257.1  667.08
  5274.5  664.06  5291.9  667.69  5315.9  668.88  6185.8  676.32  6310.0  679.53
  6378.5  683.49  6480.5  690.76  6537.9  695.74  6568.9  700.27  6601.6  702.36
#Mann=5,-1,0
  4227.1    0.05       0  4958.5   0.033       0  4990.6    0.05       0
  6378.5    0.12       0  6480.5    0.05       0
#XS Ineff=2,0
    0.00 4407.20  684.94 5592.80    0.00  684.94
Permanent Ineff=
       F       F
Bank Sta=4958.5,4990.6
Exp/Cntr=0.3,0.1

Type RM Length L Ch R = 1,26067,684,684,684
BEGIN DESCRIPTION:
Oliver Creek 35.0
END DESCRIPTION:
XS GIS Cut Line= 3
      2322020.55      7089403.35      2321779.00      7088960.00
      2321060.24      7087280.41
#Sta/Elev= 30
  4499.5  691.09  4570.9  689.64  4731.1  683.15  4843.4  675.10  4924.7  667.37
  4936.5  662.61  4946.9  655.92  4965.5  654.06  4968.8  653.06  4997.8  654.06
  5001.5  655.97  5013.5  656.73  5026.1  662.13  5037.0  663.74  5042.5  662.16
  5047.9  663.95  5058.8  663.86  5080.5  666.76  5165.8  665.75  5194.9  669.37
  5399.9  670.87  6004.0  669.56  6168.2  671.70  6538.5  680.53  6671.6  686.97
  6679.5  688.82  6701.2  690.29  6742.4  698.22  6803.3  705.66  6831.3  710.38
#Mann=5,-1,0
  4499.5    0.05       0  4965.5   0.033       0  4997.8    0.05       0
  6538.5    0.12       0  6803.3    0.05       0
Bank Sta=4965.5,4997.8
Exp/Cntr=0.3,0.1

Type RM Length L Ch R = 1,25383,734,734,734
BEGIN DESCRIPTION:
Oliver Creek 34.0
END DESCRIPTION:
XS GIS Cut Line= 3
      2322379.01      7089110.03      2322279.00      7088610.00
      2321278.98      7086809.96
#Sta/Elev= 30
  4494.3  699.99  4555.5  698.68  4626.9  687.53  4698.3  686.07  4739.1  680.78
  4769.7  679.93  4790.1  673.58  4810.5  670.04  4861.5  665.15  4922.6  663.33
  4943.0  654.41  4973.6  653.31  4977.8  651.42  4981.1  650.42  5010.2  651.42
  5012.2  657.89  5027.1  663.71  5061.4  667.70  5586.5  669.71  6159.6  668.15
  6315.9  671.74  6356.4  675.26  6422.7  685.07  6468.5  697.94  6524.3  706.79
  6548.6  711.50  6643.5  719.76  6800.2  727.10  6952.4  739.40  7063.4  745.61
#Mann=5,-1,0
  4494.3    0.05       0  4977.8   0.033       0  5010.2    0.05       0
  6315.9    0.12       0  6524.3    0.05       0
Bank Sta=4977.8,5010.2
Exp/Cntr=0.3,0.1

Type RM Length L Ch R = 1,24649,705,705,705
BEGIN DESCRIPTION:
Oliver Creek 33.0
END DESCRIPTION:
XS GIS Cut Line= 3
      2323029.03      7088610.04      2322728.52      7088204.80
      2321517.17      7086937.38
#Sta/Elev= 30
  4495.5  689.14  4509.1  684.45  4545.3  685.39  4644.9  670.38  4783.2  666.09
  4791.0  665.85  4838.8  665.40  4888.9  660.05  4896.1  656.36  4903.5  654.51
  4989.1  651.96  4993.9  649.23  4997.2  648.23  5026.3  649.23  5031.4  650.44
  5045.6  660.11  5059.7  664.66  5158.8  664.65  5208.2  662.80  5280.8  665.91
  5427.4  668.64  5681.7  668.08  5789.6  666.98  5972.1  666.68  6150.8  670.23
  6276.3  678.55  6347.0  695.97  6377.3  697.03  6502.4  708.49  6753.2  724.76
#Mann=11,-1,0
  4495.5    0.05       0  4783.2    0.12       0  4791.0    0.05       0
  4896.1    0.12       0  4993.9    0.07       0  5026.3    0.12       0
  5280.8    0.05       0  5681.7    0.12       0  5789.6    0.05       0
  6150.8    0.12       0  6377.3    0.05       0
Bank Sta=4993.9,5026.3
Exp/Cntr=0.3,0.1

Type RM Length L Ch R = 1,23944,726,726,726
BEGIN DESCRIPTION:
Oliver Creek 32.0
END DESCRIPTION:
XS GIS Cut Line= 3
      2323621.32      7088437.37      2323262.49      7087827.04
      2322107.42      7086659.57
#Sta/Elev= 30
  4292.0  691.35  4402.1  685.91  4416.6  683.66  4429.4  677.87  4491.6  670.53
  4562.2  663.92  4680.4  662.59  4906.7  663.64  4950.2  658.78  4956.8  657.27
  4962.6  651.50  4998.3  649.80  5001.6  648.80  5030.7  649.80  5035.8  660.77
  5042.8  662.31  5212.5  660.18  5228.9  661.98  5290.3  666.47  5461.2  666.10
  5643.8  665.00  5791.4  668.27  5864.5  668.62  6195.4  669.96  6324.7  675.50
  6464.1  690.14  6527.8  693.96  6556.1  700.28  6570.2  697.70  6642.3  713.99
#Mann=11,-1,0
  4292.0    0.05       0  4491.6    0.12       0  4680.4    0.05       0
  4906.7    0.12       0  4998.3    0.07       0  5030.7    0.12       0
  5228.9    0.05       0  5461.2    0.12       0  5791.4    0.05       0
  5864.5    0.12       0  6324.7    0.05       0
Bank Sta=4998.3,5030.7
Exp/Cntr=0.3,0.1

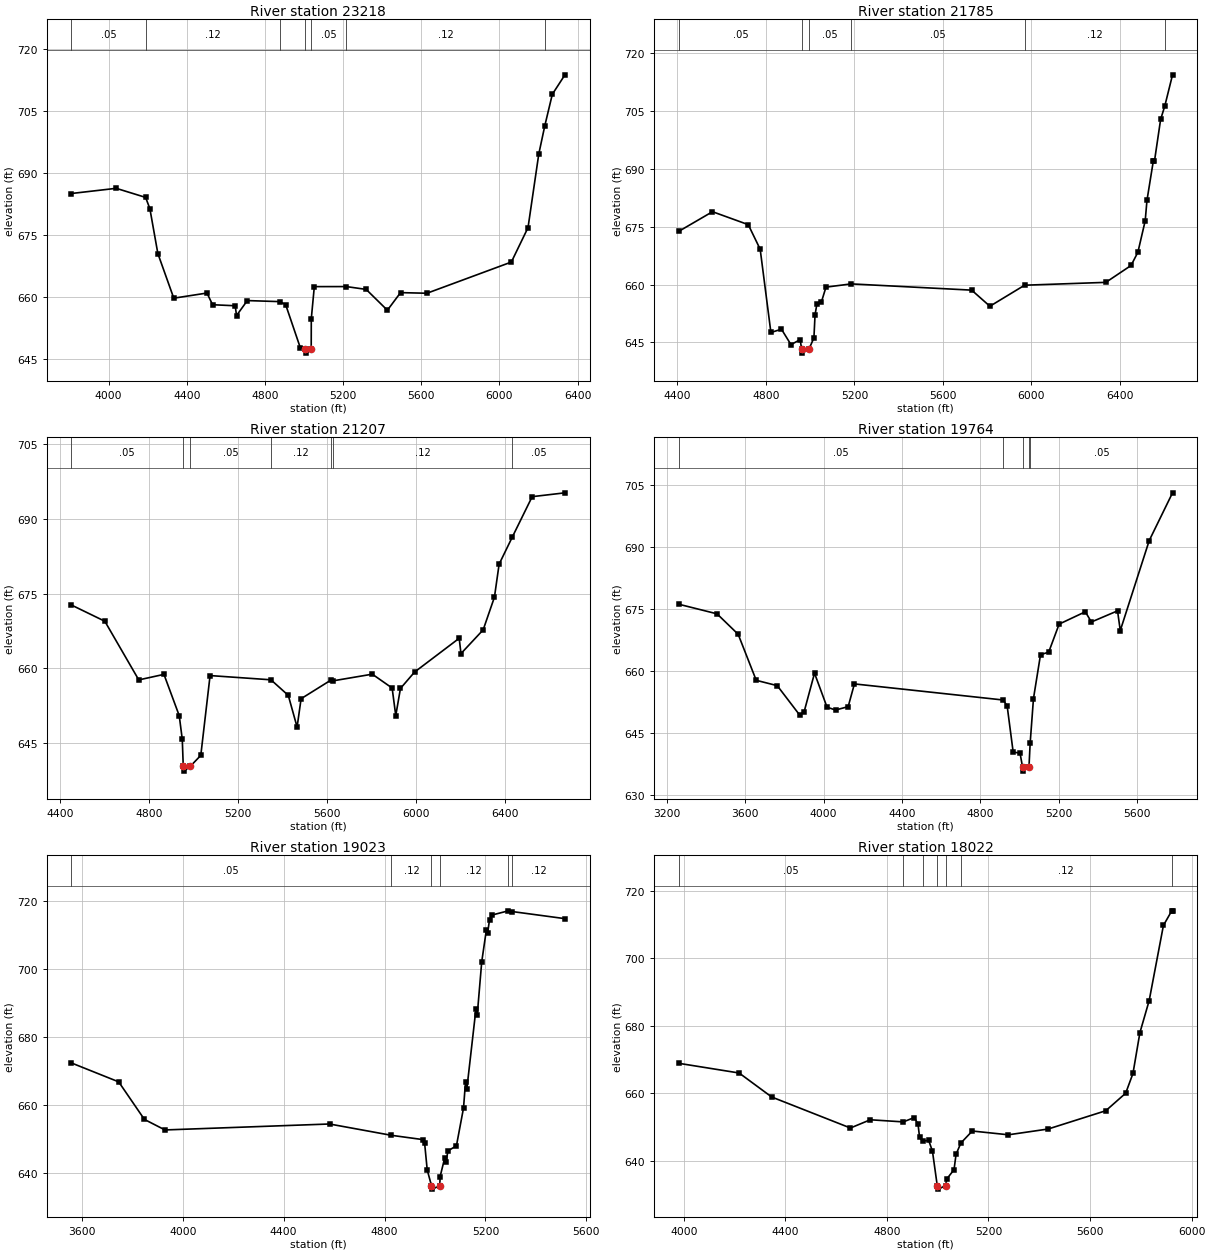
Type RM Length L Ch R = 1,23218,1433,1433,1433
BEGIN DESCRIPTION:
Oliver Creek 31.0
END DESCRIPTION:
XS GIS Cut Line= 3
      2324114.37      7088562.36      2323821.43      7087420.29
      2323346.99      7086159.54
#Sta/Elev= 30
  3809.4  685.01  4039.0  686.26  4189.4  684.07  4211.3  681.35  4252.1  670.53
  4333.6  659.75  4503.5  660.99  4532.3  658.17  4648.1  657.92  4654.7  655.55
  4710.0  659.17  4876.2  658.92  4906.2  658.19  4980.8  647.84  5004.6  647.49
  5007.9  646.49  5037.0  647.49  5037.4  654.80  5052.9  662.54  5216.5  662.55
  5318.2  661.87  5426.8  656.84  5494.2  661.09  5629.3  660.94  6061.3  668.47
  6146.6  676.78  6201.7  694.56  6232.6  701.39  6270.9  708.95  6335.5  713.65
#Mann=7,-1,0
  3809.4    0.05       0  4189.4    0.12       0  4876.2    0.05       0
  5004.6   0.033       0  5037.0    0.05       0  5216.5    0.12       0
  6232.6    0.05       0
Bank Sta=5004.6,5037
Exp/Cntr=0.3,0.1

Type RM Length L Ch R = 1,21785,578,578,578
BEGIN DESCRIPTION:
Oliver Creek 30.0
END DESCRIPTION:
XS GIS Cut Line= 3
      2324718.52      7088340.10      2324498.45      7087789.45
      2324114.36      7086197.73
#Sta/Elev= 30
  4407.0  673.84  4558.6  678.91  4720.2  675.55  4774.1  669.16  4822.5  647.56
  4870.2  648.41  4913.3  644.40  4954.5  645.70  4961.7  643.20  4965.0  642.20
  4994.1  643.20  5016.9  646.15  5022.0  652.14  5030.3  654.92  5050.9  655.51
  5071.4  659.33  5185.4  660.17  5729.8  658.55  5812.1  654.37  5968.9  659.83
  6336.1  660.57  6449.9  664.95  6480.8  668.38  6513.9  676.56  6521.9  681.86
  6550.6  692.08  6555.8  692.05  6583.6  702.87  6602.3  706.32  6637.4  714.44
#Mann=6,-1,0
  4407.0    0.05       0  4961.7    0.07       0  4994.1    0.05       0
  5185.4    0.05       0  5968.9    0.12       0  6602.3    0.05       0
Bank Sta=4961.7,4994.1
Exp/Cntr=0.3,0.1

Type RM Length L Ch R = 1,21207,1443,1443,1443
BEGIN DESCRIPTION:
Oliver Creek 29.0
END DESCRIPTION:
XS GIS Cut Line= 3
      2325138.66      7088114.39      2325009.12      7087580.28
      2324475.47      7085999.84
#Sta/Elev= 30
  4450.4  672.73  4600.8  669.47  4753.3  657.70  4866.5  658.81  4935.1  650.53
  4948.8  645.78  4953.2  640.40  4956.5  639.40  4985.6  640.40  5032.0  642.56
  5073.7  658.57  5347.2  657.72  5425.1  654.60  5464.7  648.24  5482.7  653.93
  5617.0  657.67  5625.7  657.51  5802.6  658.85  5891.7  656.07  5908.0  650.54
  5929.1  655.99  5992.4  659.27  6193.0  666.05  6201.0  662.98  6300.7  667.74
  6351.3  674.29  6372.4  680.92  6430.8  686.28  6520.9  694.46  6668.1  695.23
#Mann=7,-1,0
  4450.4    0.05       0  4953.2   0.033       0  4985.6    0.05       0
  5347.2    0.12       0  5617.0    0.05       0  5625.7    0.12       0
  6430.8    0.05       0
Bank Sta=4953.2,4985.6
Exp/Cntr=0.3,0.1

Type RM Length L Ch R = 1,19764,741,741,741
BEGIN DESCRIPTION:
Oliver Creek 28.0
END DESCRIPTION:
XS GIS Cut Line= 3
      2325982.44      7088170.03      2325329.00      7086560.00
      2325062.29      7085826.25
#Sta/Elev= 30
  3262.3  676.09  3456.6  673.78  3564.5  668.84  3656.6  657.73  3763.8  656.44
  3877.5  649.39  3900.4  650.03  3954.0  659.45  4017.8  651.25  4061.1  650.55
  4125.7  651.37  4157.5  656.86  4917.4  652.97  4937.0  651.48  4967.5  640.41
  5002.5  640.14  5015.4  636.80  5018.8  635.80  5048.2  636.80  5054.2  642.56
  5071.1  653.32  5107.0  663.91  5148.8  664.53  5202.0  671.30  5335.8  674.28
  5366.4  671.81  5500.0  674.50  5514.0  669.74  5661.7  691.48  5780.6  703.00
#Mann=5,-1,0
  3262.3    0.05       0  4917.4    0.12       0  5015.4    0.07       0
  5048.2    0.12       0  5054.2    0.05       0
Bank Sta=5015.4,5048.2
Exp/Cntr=0.3,0.1

Type RM Length L Ch R = 1,19023,1001,1001,1001
BEGIN DESCRIPTION:
Oliver Creek 27.0
END DESCRIPTION:
XS GIS Cut Line= 3
      2326333.11      7088024.14      2326054.08      7086609.80
      2325929.00      7086110.01
#Sta/Elev= 30
  3558.4  672.32  3746.1  666.75  3848.0  655.71  3929.6  652.61  4581.9  654.36
  4826.7  651.04  4951.3  649.78  4959.0  648.68  4969.2  640.87  4986.2  636.21
  4989.6  635.21  5019.0  636.21  5020.4  638.90  5038.7  644.43  5043.9  643.17
  5051.3  646.44  5085.1  647.97  5113.2  659.09  5121.1  666.81  5126.3  664.68
  5162.3  688.10  5167.5  686.39  5185.3  702.04  5203.5  711.31  5208.7  710.52
  5216.3  714.46  5226.6  715.81  5290.7  717.04  5305.8  716.83  5515.2  714.74
#Mann=6,-1,0
  3558.4    0.05       0  4826.7    0.12       0  4986.2    0.07       0
  5019.0    0.12       0  5290.7    0.05       0  5305.8    0.12       0
Bank Sta=4986.2,5019
Exp/Cntr=0.3,0.1

Type RM Length L Ch R = 1,18022,408,408,408
BEGIN DESCRIPTION:
Oliver Creek 26.0
END DESCRIPTION:
XS GIS Cut Line= 3
      2327541.44      7087565.82      2326962.73      7086727.22
      2326379.03      7086010.03
#Sta/Elev= 30
  3981.1  668.90  4218.0  666.04  4346.5  658.92  4656.4  649.74  4734.5  652.18
  4864.7  651.55  4907.6  652.84  4922.5  650.92  4928.6  646.97  4940.6  645.86
  4964.4  646.08  4979.3  642.90  4998.3  632.63  5001.8  631.63  5031.2  632.63
  5035.6  634.63  5064.3  637.39  5072.3  641.96  5091.4  645.30  5136.2  648.85
  5278.4  647.73  5434.8  649.44  5661.9  654.86  5740.2  660.05  5768.9  665.91
  5796.2  677.99  5832.8  687.52  5888.8  709.76  5921.4  714.06  5924.7  714.09
#Mann=7,-1,0
  3981.1    0.05       0  4864.7    0.12       0  4940.6    0.05       0
  4998.3   0.033       0  5031.2    0.05       0  5091.4    0.12       0
  5921.4    0.05       0
Bank Sta=4998.3,5031.2
Exp/Cntr=0.3,0.1