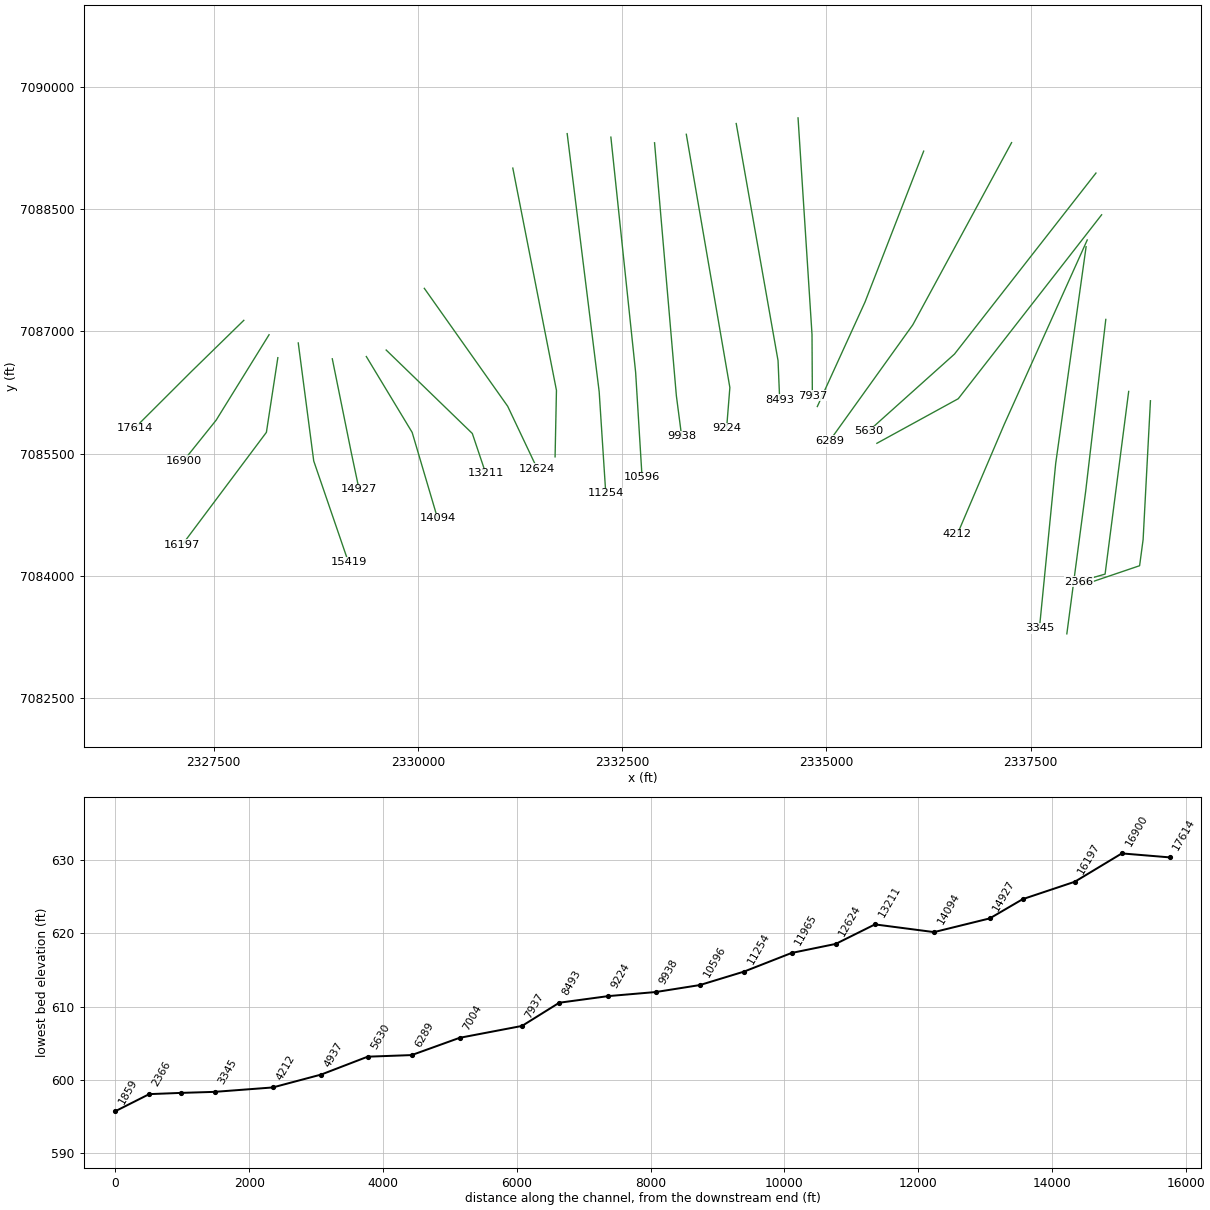
HEC-RAS study Oliver Creek.prj: Oliver Creek Base Level Engineering

--- Oliver Creek.g01 (geometry) --- (continued)

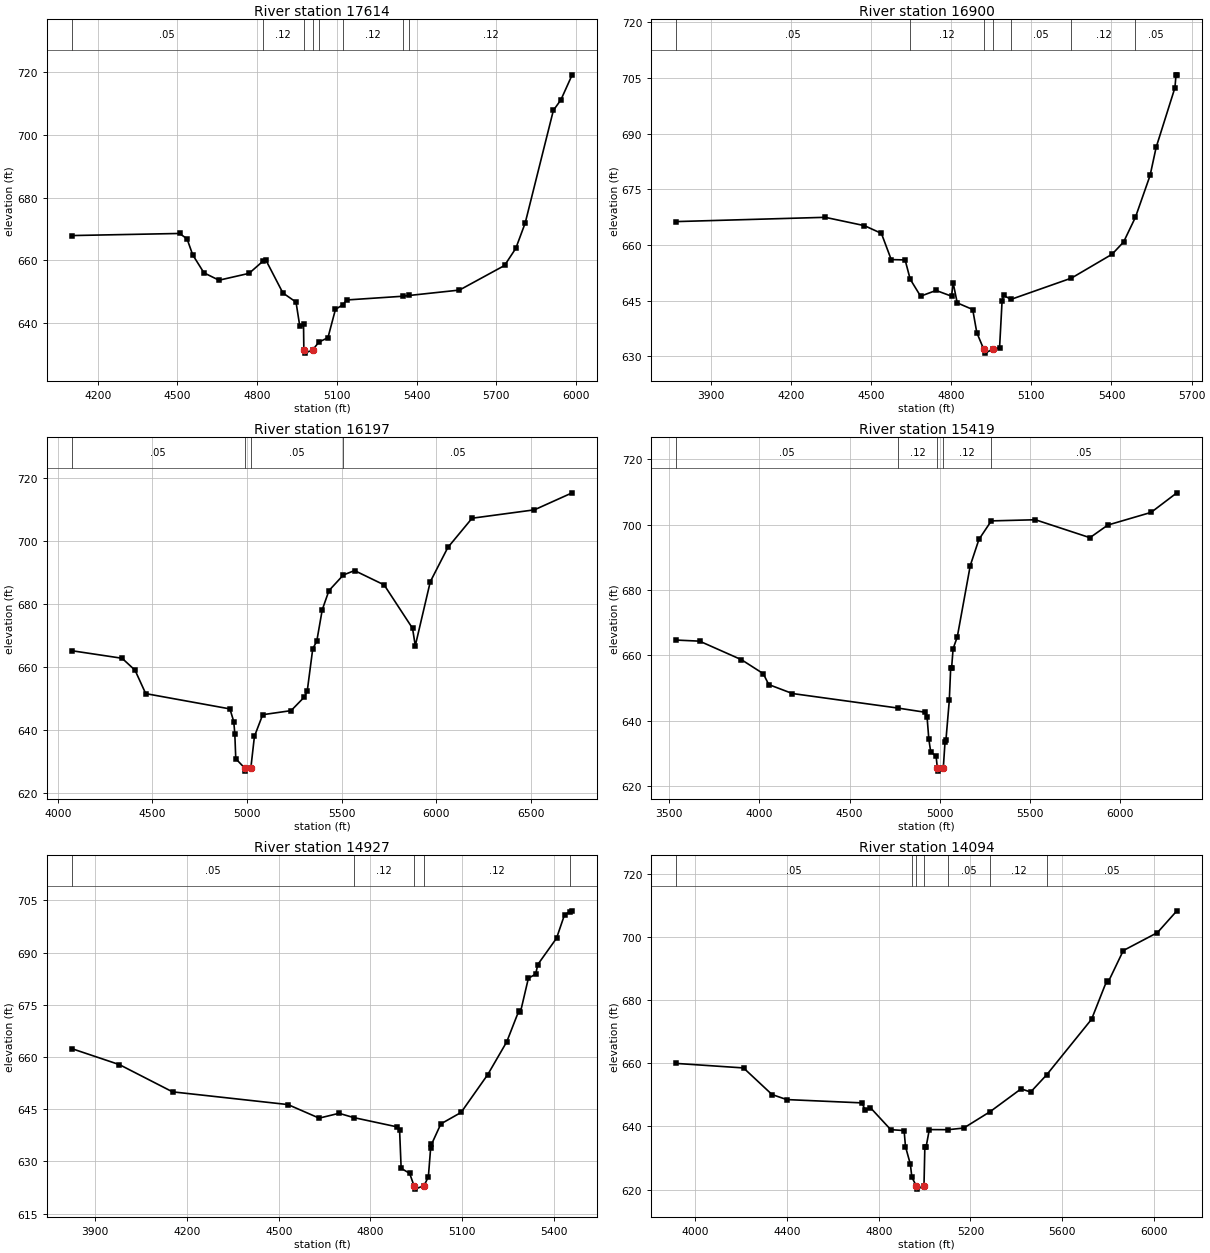
Type RM Length L Ch R = 1,17614,714,714,714
BEGIN DESCRIPTION:
Oliver Creek 25.0
END DESCRIPTION:
XS GIS Cut Line= 3
      2327867.85      7087135.28      2327229.00      7086510.00
      2326528.98      7085809.98
#Sta/Elev= 30
  4102.0  667.87  4507.9  668.54  4536.2  666.83  4557.5  661.72  4599.9  655.96
  4656.5  653.61  4769.7  655.80  4820.8  659.60  4833.3  659.98  4897.0  649.54
  4946.4  646.62  4960.6  638.95  4974.7  639.70  4975.9  631.32  4979.4  630.32
  5008.9  631.32  5032.6  633.85  5066.6  635.25  5094.9  644.30  5122.6  645.76
  5137.3  647.30  5350.0  648.50  5373.0  648.74  5561.6  650.46  5731.3  658.31
  5773.7  663.78  5809.1  671.88  5915.2  707.87  5943.4  711.20  5985.9  719.21
#Mann=8,-1,0
  4102.0    0.05       0  4820.8    0.12       0  4975.9    0.07       0
  5008.9    0.12       0  5032.6    0.05       0  5122.6    0.12       0
  5350.0    0.05       0  5373.0    0.12       0
Bank Sta=4975.9,5008.9
Exp/Cntr=0.3,0.1

Type RM Length L Ch R = 1,16900,703,703,703
BEGIN DESCRIPTION:
Oliver Creek 24.0
END DESCRIPTION:
XS GIS Cut Line= 3
      2328176.88      7086958.22      2327529.00      7085910.00
      2327128.99      7085409.99
#Sta/Elev= 30
  3772.1  666.30  4328.8  667.45  4475.4  665.21  4539.2  663.12  4575.9  656.06
  4627.9  655.97  4646.8  650.79  4685.8  646.20  4743.7  647.75  4801.7  646.20
  4807.5  649.82  4822.9  644.40  4880.8  642.61  4896.2  636.37  4922.3  631.86
  4925.7  630.86  4955.3  631.86  4981.3  632.31  4990.8  645.01  4996.7  646.42
  5024.0  645.34  5250.1  651.07  5402.2  657.50  5445.4  660.80  5489.8  667.49
  5544.6  678.75  5567.1  686.28  5637.5  702.38  5641.5  705.84  5644.7  705.84
#Mann=7,-1,0
  3772.1    0.05       0  4646.8    0.12       0  4922.3    0.07       0
  4955.3    0.12       0  5024.0    0.05       0  5250.1    0.12       0
  5489.8    0.05       0
Bank Sta=4922.3,4955.3
Exp/Cntr=0.3,0.1

Type RM Length L Ch R = 1,16197,778,778,778
BEGIN DESCRIPTION:
Oliver Creek 23.0
END DESCRIPTION:
XS GIS Cut Line= 3
      2328284.50      7086676.92      2328144.36      7085760.87
      2327115.54      7084383.37
#Sta/Elev= 30
  4073.3  665.22  4339.7  662.82  4408.2  659.03  4464.7  651.60  4909.8  646.75
  4930.1  642.75  4935.7  638.91  4940.8  630.94  4987.5  628.00  4990.9  627.00
  5020.5  628.00  5039.4  638.02  5083.2  644.91  5233.3  646.20  5304.1  650.57
  5318.7  652.44  5347.9  665.88  5368.8  668.17  5398.0  678.21  5433.4  684.29
  5509.9  689.27  5568.9  690.65  5725.2  686.11  5875.3  672.34  5889.9  666.80
  5969.1  687.10  6062.0  697.98  6190.1  707.27  6519.5  709.93  6719.3  715.33
#Mann=4,-1,0
  4073.3    0.05       0  4987.5   0.033       0  5020.5    0.05       0
  5509.9    0.05       0
Bank Sta=4987.5,5020.5
Exp/Cntr=0.3,0.1

Type RM Length L Ch R = 1,15419,492,492,492
BEGIN DESCRIPTION:
Oliver Creek 22.0
END DESCRIPTION:
XS GIS Cut Line= 3
      2328534.50      7086857.53      2328723.82      7085409.56
      2329149.10      7084166.49
#Sta/Elev= 30
  3539.7  664.69  3668.3  664.36  3900.3  658.69  4021.3  654.42  4051.6  651.09
  4182.7  648.35  4767.4  643.91  4918.9  642.62  4929.1  641.21  4939.0  634.38
  4949.1  630.62  4979.4  629.12  4986.1  625.63  4989.6  624.63  5019.2  625.63
  5028.7  633.56  5034.0  634.27  5052.4  646.22  5060.0  656.04  5065.3  656.24
  5073.5  662.05  5096.6  665.64  5168.6  687.46  5216.5  695.44  5285.2  701.12
  5529.5  701.47  5831.9  695.99  5931.1  699.85  6170.9  703.72  6313.8  709.70
#Mann=5,-1,0
  3539.7    0.05       0  4767.4    0.12       0  4986.1    0.07       0
  5019.2    0.12       0  5285.2    0.05       0
Bank Sta=4986.1,5019.2
Exp/Cntr=0.3,0.1

Type RM Length L Ch R = 1,14927,833,833,833
BEGIN DESCRIPTION:
Oliver Creek 21.0
END DESCRIPTION:
XS GIS Cut Line= 3
      2328951.17      7086663.03      2329184.20      7085509.53
      2329279.00      7085060.02
#Sta/Elev= 30
  3823.2  662.41  3979.3  657.80  4152.8  649.98  4530.2  646.32  4632.2  642.42
  4697.3  643.81  4744.7  642.59  4887.3  639.90  4895.2  638.97  4900.3  628.00
  4928.1  626.54  4942.2  623.01  4945.6  622.01  4975.3  623.01  4989.3  625.58
  4996.7  633.78  4999.5  634.88  5030.2  640.77  5096.3  644.06  5183.5  654.95
  5245.6  664.37  5285.2  673.31  5290.3  672.88  5316.3  682.64  5340.1  683.82
  5347.0  686.58  5408.3  694.14  5434.5  700.91  5453.7  701.79  5459.4  702.02
#Mann=5,-1,0
  3823.2    0.05       0  4744.7    0.12       0  4942.2    0.07       0
  4975.3    0.12       0  5453.7    0.05       0
Bank Sta=4942.2,4975.3
Exp/Cntr=0.3,0.1

Type RM Length L Ch R = 1,14094,883,883,883
BEGIN DESCRIPTION:
Oliver Creek 20.0
END DESCRIPTION:
XS GIS Cut Line= 3
      2329367.85      7086690.81      2329929.00      7085760.00
      2330239.36      7084708.21
#Sta/Elev= 30
  3917.3  660.00  4210.2  658.57  4334.4  650.14  4398.4  648.54  4726.6  647.49
  4742.1  645.08  4763.4  646.00  4852.4  639.00  4910.8  638.71  4916.8  633.62
  4938.2  628.01  4944.6  623.90  4964.3  621.14  4967.8  620.14  4997.5  621.14
  5001.3  633.57  5006.8  633.57  5020.8  639.02  5103.0  638.99  5171.0  639.51
  5286.5  644.73  5421.2  651.94  5462.9  650.93  5532.6  656.37  5728.7  674.01
  5795.3  686.28  5800.5  685.69  5867.1  695.79  6016.0  701.48  6100.8  708.39
#Mann=7,-1,0
  3917.3    0.05       0  4944.6    0.12       0  4964.3    0.07       0
  4997.5    0.12       0  5103.0    0.05       0  5286.5    0.12       0
  5532.6    0.05       0
Bank Sta=4964.3,4997.5
Exp/Cntr=0.3,0.1

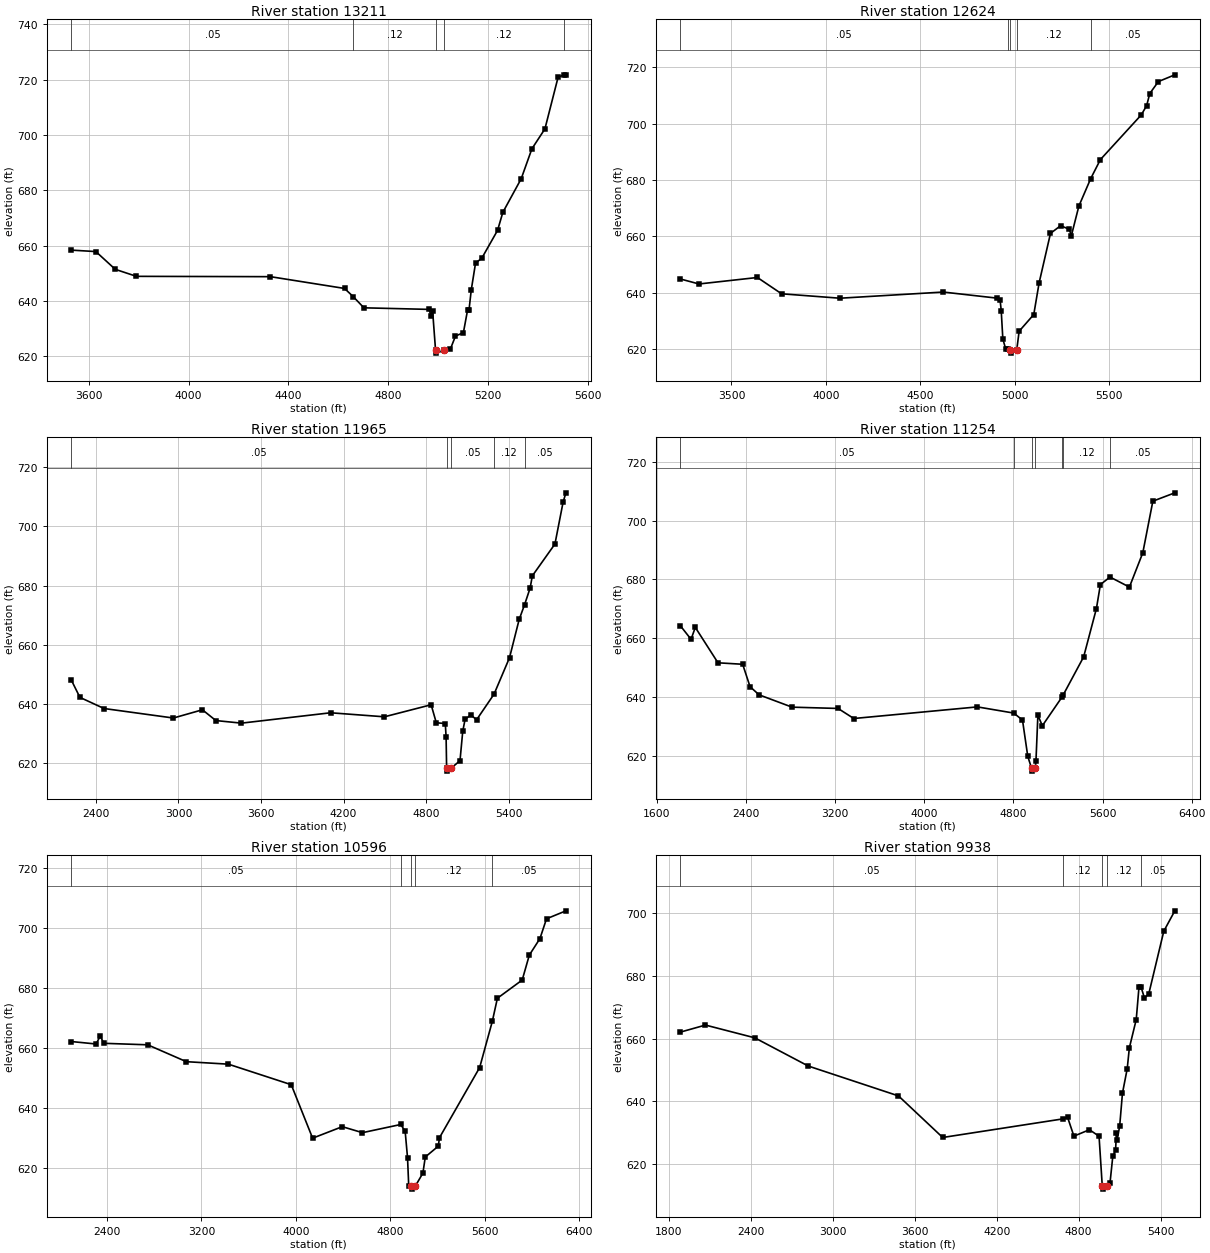
Type RM Length L Ch R = 1,13211,587,587,587
BEGIN DESCRIPTION:
Oliver Creek 19.0
END DESCRIPTION:
XS GIS Cut Line= 3
      2329610.88      7086770.69      2330665.71      7085746.57
      2330828.99      7085260.03
#Sta/Elev= 30
  3529.8  658.40  3627.9  657.88  3705.8  651.46  3790.7  648.93  4328.1  648.81
  4625.1  644.56  4660.3  641.58  4702.9  637.56  4964.5  636.99  4971.6  634.74
  4978.6  636.29  4990.3  622.19  4993.8  621.19  5023.5  622.19  5049.1  622.51
  5070.2  627.36  5101.9  628.58  5119.0  636.91  5124.3  636.64  5133.5  644.05
  5150.6  653.70  5175.7  655.48  5239.0  665.55  5260.1  672.04  5333.9  684.22
  5376.6  695.00  5428.9  702.21  5481.6  720.83  5503.4  721.67  5513.2  721.73
#Mann=5,-1,0
  3529.8    0.05       0  4660.3    0.12       0  4990.3    0.07       0
  5023.5    0.12       0  5503.4    0.05       0
Bank Sta=4990.3,5023.5
Exp/Cntr=0.3,0.1

Type RM Length L Ch R = 1,12624,659,659,659
BEGIN DESCRIPTION:
Oliver Creek 18.0
END DESCRIPTION:
XS GIS Cut Line= 3
      2330077.95      7087527.67      2331098.79      7086080.49
      2331460.58      7085315.09
#Sta/Elev= 30
  3229.0  644.87  3328.2  643.09  3637.3  645.39  3765.3  639.60  4074.4  638.03
  4621.2  640.22  4906.9  638.05  4921.7  637.57  4927.8  633.64  4936.5  623.49
  4951.3  620.10  4965.4  619.94  4976.5  619.53  4980.0  618.53  5009.7  619.53
  5022.7  626.31  5100.1  632.24  5128.5  643.52  5188.6  661.06  5242.3  663.79
  5287.8  662.52  5299.2  660.26  5338.8  670.75  5401.1  680.46  5452.7  687.26
  5668.6  703.09  5697.4  706.38  5714.1  710.72  5759.6  714.96  5846.6  717.36
#Mann=5,-1,0
  3229.0    0.05       0  4965.4    0.12       0  4976.5    0.07       0
  5009.7    0.12       0  5401.1    0.05       0
Bank Sta=4976.5,5009.7
Exp/Cntr=0.3,0.1

Type RM Length L Ch R = 1,11965,711,711,711
BEGIN DESCRIPTION:
Oliver Creek 17.0
END DESCRIPTION:
XS GIS Cut Line= 3
      2331161.53      7089003.01      2331695.75      7086276.46
      2331679.00      7085460.03
#Sta/Elev= 30
  2221.6  648.01  2283.6  642.21  2459.0  638.45  2963.0  635.24  3174.0  638.02
  3271.9  634.38  3457.7  633.51  4105.8  637.01  4497.1  635.65  4836.7  639.72
  4874.1  633.64  4939.6  633.37  4945.4  628.88  4949.2  618.30  4952.7  617.30
  4982.4  618.30  5046.5  620.84  5066.5  630.79  5083.5  634.81  5126.5  636.31
  5166.5  634.61  5294.0  643.31  5406.5  655.63  5476.6  668.54  5515.9  673.52
  5556.6  679.21  5572.2  683.26  5736.6  694.02  5796.6  708.32  5816.6  711.31
#Mann=5,-1,0
  2221.6    0.05       0  4949.2   0.033       0  4982.4    0.05       0
  5294.0    0.12       0  5515.9    0.05       0
Bank Sta=4949.2,4982.4
Exp/Cntr=0.3,0.1

Type RM Length L Ch R = 1,11254,658,658,658
BEGIN DESCRIPTION:
Oliver Creek 16.0
END DESCRIPTION:
XS GIS Cut Line= 3
      2331827.05      7089426.11      2332218.81      7086259.55
      2332299.51      7085013.36
#Sta/Elev= 30
  1809.3  664.26  1906.1  659.60  1944.4  663.65  2148.0  651.61  2369.6  651.11
  2435.6  643.50  2516.6  640.72  2813.0  636.52  3226.1  636.08  3367.2  632.66
  4476.4  636.61  4802.8  634.51  4881.5  632.13  4929.0  619.76  4962.8  615.76
  4966.3  614.76  4996.0  615.76  5002.3  618.06  5019.6  633.79  5059.7  630.20
  5239.5  640.14  5248.4  640.78  5430.4  653.62  5545.1  670.06  5580.8  678.22
  5667.1  680.78  5841.3  677.37  5961.6  689.04  6051.7  706.59  6248.8  709.43
#Mann=7,-1,0
  1809.3    0.05       0  4802.8    0.12       0  4962.8    0.07       0
  4996.0    0.12       0  5239.5    0.05       0  5248.4    0.12       0
  5667.1    0.05       0
Bank Sta=4962.8,4996
Exp/Cntr=0.3,0.1

Type RM Length L Ch R = 1,10596,658,658,658
BEGIN DESCRIPTION:
Oliver Creek 15.0
END DESCRIPTION:
XS GIS Cut Line= 3
      2332362.13      7089383.13      2332665.27      7086496.80
      2332744.03      7085210.11
#Sta/Elev= 30
  2097.8  662.18  2307.1  661.36  2342.3  664.03  2372.4  661.59  2744.5  661.09
  3072.2  655.46  3428.2  654.63  3961.1  647.78  4142.1  629.93  4393.5  633.77
  4564.4  631.77  4889.2  634.50  4926.4  632.23  4946.5  623.45  4956.6  614.08
  4979.2  613.93  4982.7  612.93  5012.5  613.93  5076.9  618.29  5097.0  623.65
  5207.2  627.27  5217.2  630.09  5557.8  653.50  5665.0  668.90  5708.1  676.63
  5918.5  682.71  5978.6  691.02  6068.8  696.55  6124.4  703.14  6289.1  705.80
#Mann=5,-1,0
  2097.8    0.05       0  4889.2    0.12       0  4979.2    0.07       0
  5012.5    0.12       0  5665.0    0.05       0
Bank Sta=4979.2,5012.5
Exp/Cntr=0.3,0.1

Type RM Length L Ch R = 1,9938,714,714,714
BEGIN DESCRIPTION:
Oliver Creek 14.0
END DESCRIPTION:
XS GIS Cut Line= 3
      2332896.84      7089313.76      2333163.94      7086209.83
      2333228.99      7085710.04
#Sta/Elev= 30
  1884.6  662.08  2069.0  664.34  2430.0  660.27  2821.8  651.26  3481.8  641.73
  3805.4  628.46  4686.8  634.41  4718.8  634.96  4765.7  628.89  4879.2  630.94
  4949.6  628.86  4973.1  612.98  4976.6  611.98  5006.4  612.98  5030.1  614.08
  5050.2  622.46  5070.4  624.34  5076.7  629.77  5081.8  627.56  5100.7  632.18
  5120.8  642.57  5155.8  650.43  5171.3  657.06  5221.7  666.10  5241.9  676.49
  5257.2  676.43  5282.2  672.95  5313.9  674.38  5423.4  694.30  5504.0  700.80
#Mann=5,-1,0
  1884.6    0.05       0  4686.8    0.12       0  4973.1    0.07       0
  5006.4    0.12       0  5257.2    0.05       0
Bank Sta=4973.1,5006.4
Exp/Cntr=0.3,0.1

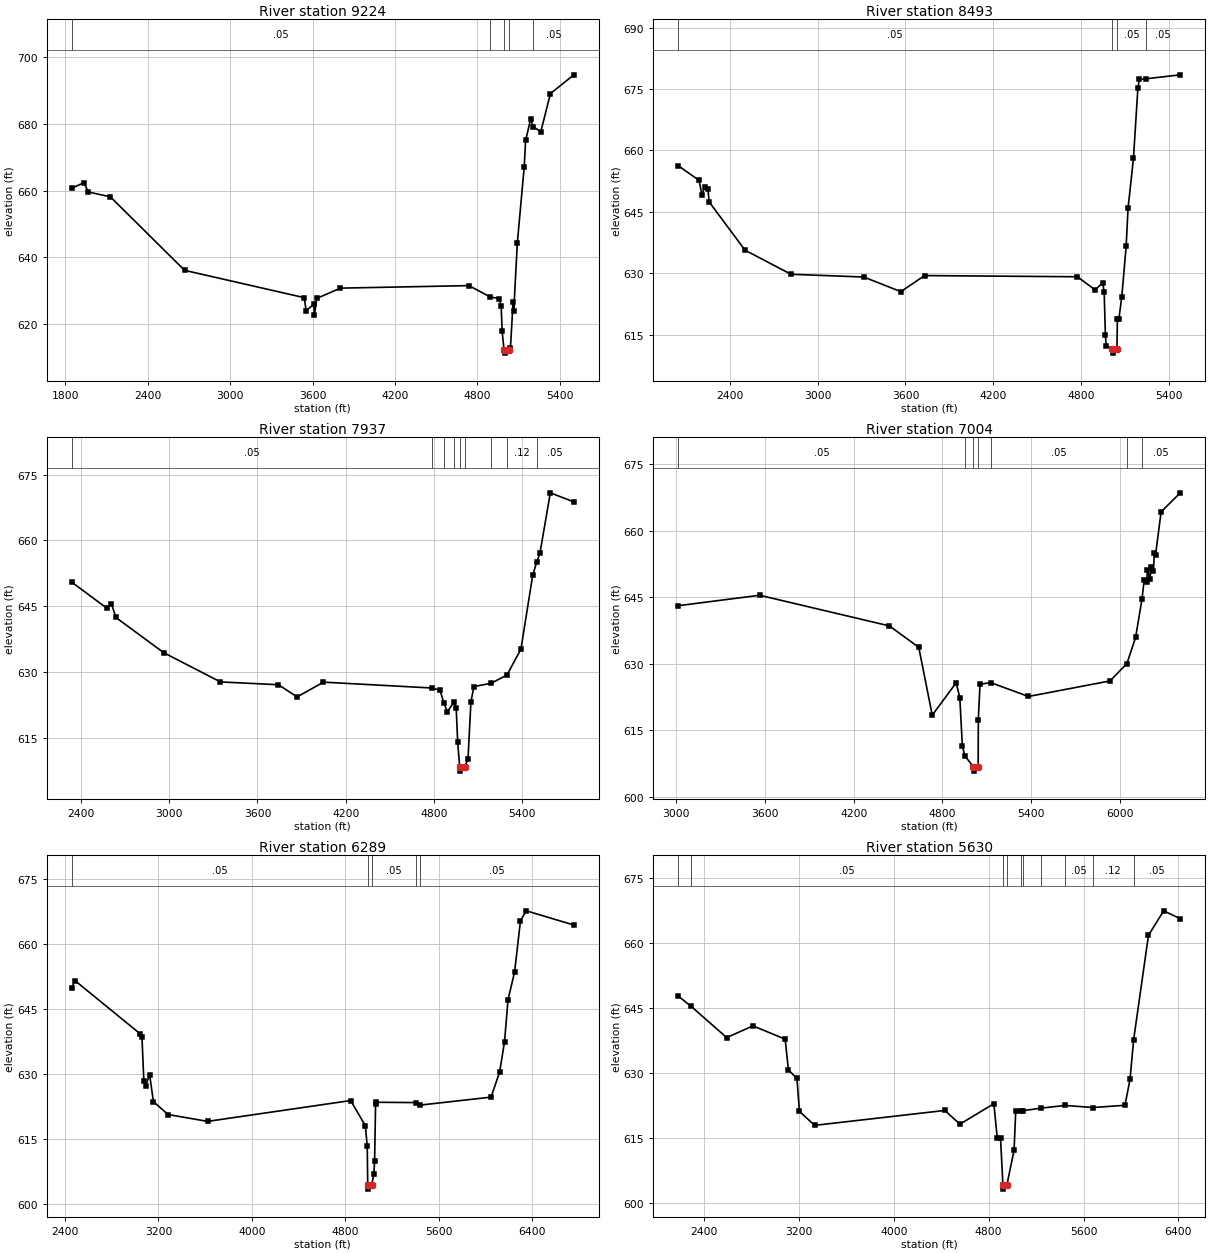
Type RM Length L Ch R = 1,9224,731,731,731
BEGIN DESCRIPTION:
Oliver Creek 13.0
END DESCRIPTION:
XS GIS Cut Line= 3
      2333285.73      7089417.93      2333819.02      7086309.95
      2333779.00      7085810.05
#Sta/Elev= 30
  1846.6  660.67  1935.8  662.38  1966.3  659.58  2127.8  658.11  2667.8  636.16
  3538.9  627.99  3552.6  624.12  3607.6  625.98  3612.7  622.84  3630.2  627.77
  3802.7  630.84  4737.5  631.59  4893.3  628.19  4959.4  627.71  4972.4  625.39
  4979.7  617.95  4993.3  612.42  4996.8  611.42  5026.6  612.42  5040.1  613.08
  5059.0  626.58  5064.0  623.98  5090.2  644.44  5140.4  667.15  5150.4  674.95
  5186.9  681.36  5206.5  679.05  5260.8  677.57  5331.0  688.96  5501.5  694.57
#Mann=5,-1,0
  1846.6    0.05       0  4893.3    0.12       0  4993.3    0.07       0
  5026.6    0.12       0  5206.5    0.05       0
Bank Sta=4993.3,5026.6
Exp/Cntr=0.3,0.1

Type RM Length L Ch R = 1,8493,556,556,556
BEGIN DESCRIPTION:
Oliver Creek 12.0
END DESCRIPTION:
XS GIS Cut Line= 3
      2333896.84      7089549.85      2334408.97      7086640.07
      2334429.00      7086159.99
#Sta/Elev= 30
  2045.5  656.27  2187.5  652.71  2207.8  649.18  2228.1  651.19  2248.4  650.70
  2256.7  647.45  2502.3  635.65  2817.0  629.77  3314.6  629.10  3568.4  625.53
  3730.9  629.45  4776.7  629.16  4898.5  625.93  4949.3  627.74  4959.5  625.44
  4967.9  615.01  4973.0  612.37  5013.4  611.52  5016.9  610.52  5046.7  611.52
  5050.1  618.85  5060.1  618.82  5080.1  624.30  5110.2  636.70  5122.9  645.87
  5160.2  658.16  5190.2  675.21  5200.2  677.31  5247.4  677.49  5480.5  678.45
#Mann=4,-1,0
  2045.5    0.05       0  5013.4   0.033       0  5046.7    0.05       0
  5247.4    0.05       0
Bank Sta=5013.4,5046.7
Exp/Cntr=0.3,0.1

Type RM Length L Ch R = 1,7937,933,933,933
BEGIN DESCRIPTION:
Oliver Creek 11.0
END DESCRIPTION:
XS GIS Cut Line= 3
      2334653.79      7089619.31      2334824.82      7086961.71
      2334829.00      7086210.02
#Sta/Elev= 30
  2336.9  650.47  2576.7  644.50  2606.8  645.55  2636.8  642.42  2962.8  634.37
  3348.3  627.71  3742.8  627.07  3869.4  624.29  4048.8  627.66  4788.0  626.32
  4841.4  625.81  4868.2  622.89  4891.5  620.92  4936.5  623.10  4951.6  621.65
  4961.6  613.94  4975.3  608.36  4978.8  607.36  5008.6  608.36  5031.7  610.07
  5051.7  623.15  5071.7  626.65  5188.8  627.40  5296.7  629.28  5391.7  635.18
  5471.7  652.00  5498.4  654.98  5521.7  657.20  5591.7  670.85  5751.7  668.78
#Mann=9,-1,0
  2336.9    0.05       0  4788.0    0.12       0  4868.2    0.05       0
  4936.5    0.12       0  4975.3    0.07       0  5008.6    0.12       0
  5188.8    0.05       0  5296.7    0.12       0  5498.4    0.05       0
Bank Sta=4975.3,5008.6
Exp/Cntr=0.3,0.1

Type RM Length L Ch R = 1,7004,715,715,715
BEGIN DESCRIPTION:
Oliver Creek 10.0
END DESCRIPTION:
XS GIS Cut Line= 3
      2336191.98      7089211.30      2335473.83      7087359.58
      2334889.90      7086077.61
#Sta/Elev= 30
  3013.9  643.06  3564.6  645.41  4441.4  638.50  4640.1  633.68  4731.4  618.36
  4893.3  625.68  4917.8  622.28  4935.2  611.32  4952.7  609.16  5008.7  606.74
  5012.2  605.74  5042.0  606.74  5042.9  617.38  5054.5  625.34  5126.2  625.71
  5382.1  622.58  5933.6  626.09  6047.7  630.00  6106.6  635.93  6149.5  644.53
  6164.3  648.76  6181.2  648.39  6186.7  651.15  6204.3  649.04  6209.8  651.71
  6227.3  650.89  6232.8  654.87  6241.2  654.55  6278.9  664.23  6408.7  668.52
#Mann=7,-1,0
  3013.9    0.05       0  4952.7    0.12       0  5008.7    0.07       0
  5042.0    0.12       0  5126.2    0.05       0  6047.7    0.12       0
  6149.5    0.05       0
Bank Sta=5008.7,5042
Exp/Cntr=0.3,0.1

Type RM Length L Ch R = 1,6289,659,659,659
BEGIN DESCRIPTION:
Oliver Creek 9.0
END DESCRIPTION:
XS GIS Cut Line= 3
      2337268.36      7089315.45      2336059.16      7087080.38
      2335038.43      7085653.61
#Sta/Elev= 30
  2458.8  649.84  2485.5  651.54  3044.8  639.23  3059.2  638.59  3075.3  628.42
  3090.3  627.16  3124.8  629.84  3157.2  623.59  3282.8  620.61  3621.4  619.03
  4844.8  623.84  4970.4  618.04  4986.6  613.35  4990.9  604.39  4994.5  603.39
  5024.5  604.39  5043.4  606.80  5049.7  609.87  5058.1  623.07  5064.3  623.44
  5406.3  623.37  5436.4  622.78  6045.9  624.63  6119.4  630.43  6161.4  637.45
  6190.9  647.09  6247.4  653.52  6297.8  665.39  6348.1  667.64  6754.3  664.36
#Mann=5,-1,0
  2458.8    0.05       0  4990.9   0.033       0  5024.5    0.05       0
  5406.3    0.12       0  5436.4    0.05       0
Bank Sta=4990.9,5024.5
Exp/Cntr=0.3,0.1

Type RM Length L Ch R = 1,5630,693,693,693
BEGIN DESCRIPTION:
Oliver Creek 8.0
END DESCRIPTION:
XS GIS Cut Line= 3
      2338301.37      7088942.21      2336569.04      7086720.71
      2335515.56      7085774.39
#Sta/Elev= 30
  2182.9  647.73  2292.8  645.33  2591.5  638.15  2813.1  640.86  3084.5  637.78
  3111.7  630.69  3184.0  628.72  3204.8  621.10  3333.3  617.89  4430.3  621.33
  4558.1  618.17  4844.0  622.89  4872.9  614.91  4900.1  615.04  4920.4  604.17
  4923.9  603.17  4954.0  604.17  5014.4  612.11  5028.6  621.31  5070.2  621.27
  5089.2  621.27  5240.7  621.86  5443.4  622.49  5680.1  622.01  5949.5  622.52
  5992.1  628.50  6022.2  637.60  6147.6  661.74  6275.4  667.41  6416.1  665.59
#Mann=10,-1,0
  2182.9   0.075       0  2292.8    0.05       0  4920.4   0.033       0
  4954.0    0.05       0  5070.2    0.12       0  5089.2    0.05       0
  5240.7    0.12       0  5443.4    0.05       0  5680.1    0.12       0
  6022.2    0.05       0
Bank Sta=4920.4,4954
Exp/Cntr=0.3,0.1

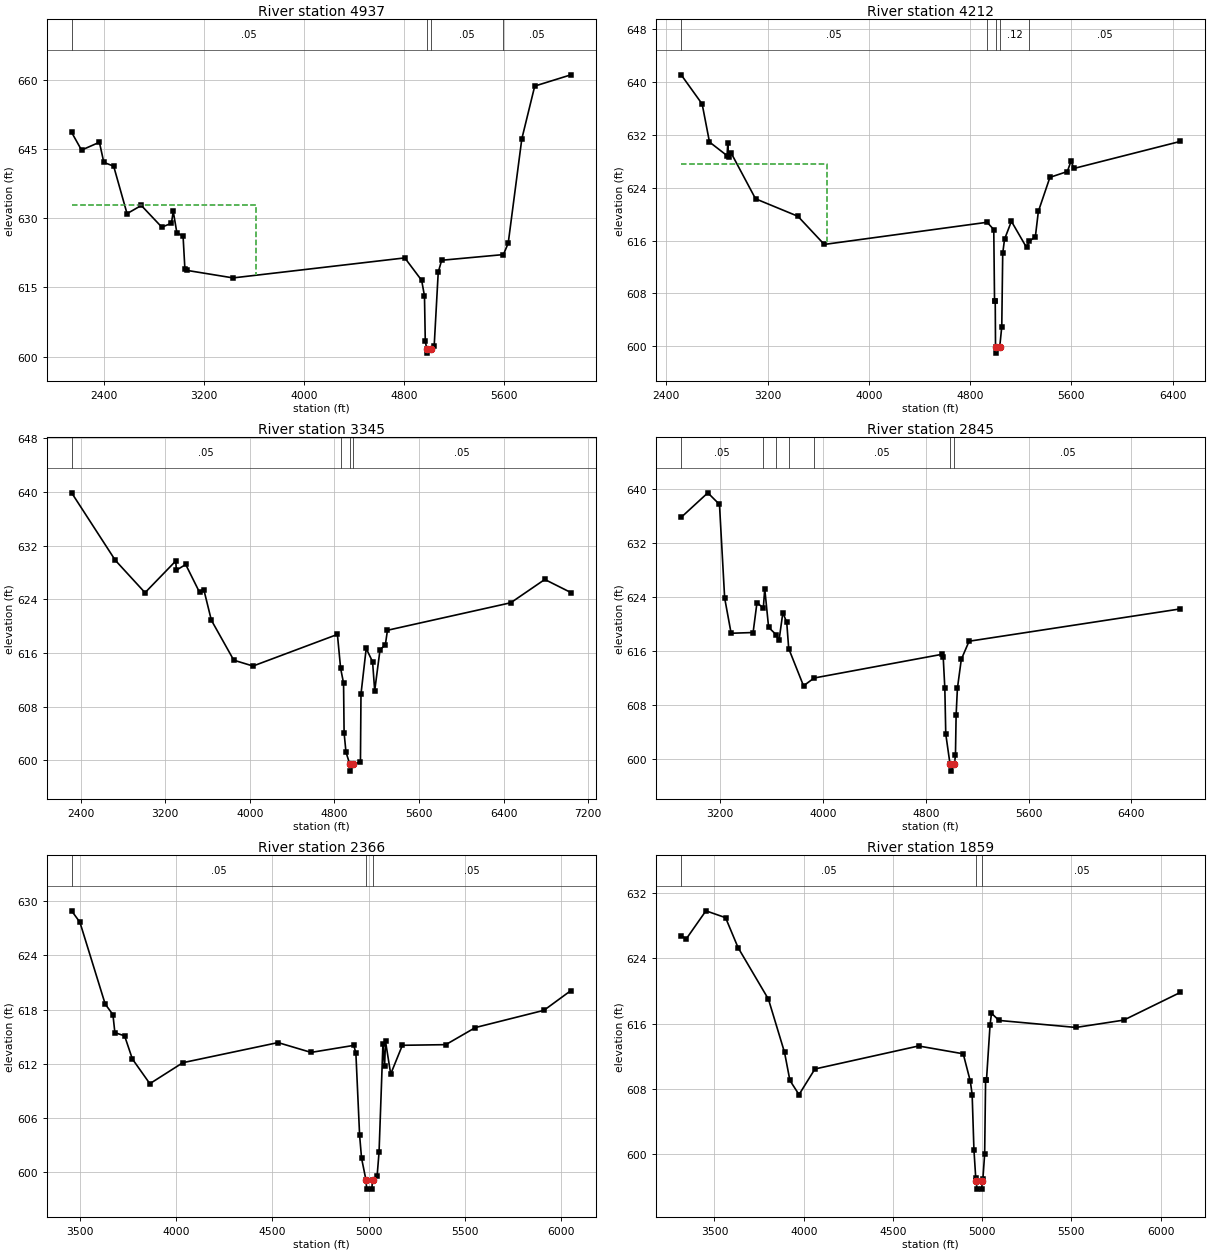
Type RM Length L Ch R = 1,4937,725,725,725
BEGIN DESCRIPTION:
Oliver Creek 7.0
END DESCRIPTION:
XS GIS Cut Line= 3
      2338370.80      7088430.04      2336615.43      7086173.24
      2335619.11      7085626.25
#Sta/Elev= 30
  2140.9  648.63  2220.2  644.79  2363.2  646.49  2398.5  642.12  2477.2  641.31
  2584.4  631.00  2698.4  632.78  2862.7  628.07  2939.6  628.92  2954.1  631.51
  2983.0  626.87  3032.8  626.11  3047.3  619.04  3061.8  618.70  3432.8  617.06
  4807.3  621.40  4942.1  616.53  4964.8  613.13  4971.1  603.40  4982.1  601.74
  4985.6  600.74  5015.7  601.74  5042.6  602.39  5074.8  618.29  5102.3  620.89
  5596.4  622.12  5634.8  624.59  5743.8  647.23  5847.1  658.68  6136.6  661.12
#Mann=4,-1,0
  2140.9    0.05       0  4982.1    0.07       0  5015.7    0.05       0
  5596.4    0.05       0
#XS Ineff=2,0
    0.00 3620.10  632.80               0
Permanent Ineff=
       F       F
Bank Sta=4982.1,5015.7
Exp/Cntr=0.3,0.1

Type RM Length L Ch R = 1,4212,867,867,867
BEGIN DESCRIPTION:
Oliver Creek 6.0
END DESCRIPTION:
XS GIS Cut Line= 3
      2338194.66      7088121.24      2337179.00      7085860.00
      2336604.55      7084510.98
#Sta/Elev= 30
  2516.6  641.05  2682.4  636.63  2740.3  630.89  2879.3  628.83  2884.8  630.73
  2890.7  628.58  2913.4  629.16  3104.2  622.31  3438.8  619.67  3647.1  615.41
  4933.9  618.76  4986.6  617.66  4992.7  606.82  4998.2  606.82  5000.4  599.98
  5004.0  598.98  5034.0  599.98  5049.8  602.98  5057.3  614.05  5071.5  616.18
  5125.9  618.91  5245.5  614.95  5266.1  615.86  5315.3  616.58  5338.9  620.40
  5430.2  625.55  5567.9  626.43  5597.0  628.01  5620.6  626.90  6461.7  630.99
#Mann=5,-1,0
  2516.6    0.05       0  4933.9    0.12       0  5000.4    0.07       0
  5034.0    0.12       0  5266.1    0.05       0
#XS Ineff=2,0
    0.00 3667.00  627.57               0
Permanent Ineff=
       F       F
Bank Sta=5000.4,5034
Exp/Cntr=0.3,0.1

Type RM Length L Ch R = 1,3345,500,500,500
BEGIN DESCRIPTION:
Oliver Creek 5.0
END DESCRIPTION:
XS GIS Cut Line= 3
      2338180.78      7088037.91      2337808.61      7085379.84
      2337608.92      7083354.36
#Sta/Elev= 30
  2316.0  639.85  2729.2  629.79  3009.8  624.97  3300.4  629.70  3305.5  628.32
  3394.3  629.17  3525.6  625.01  3566.0  625.39  3636.7  620.87  3848.7  614.91
  4030.5  614.04  4828.2  618.75  4858.7  613.68  4886.4  611.49  4891.4  604.12
  4909.0  601.22  4946.0  599.38  4949.6  598.38  4979.7  599.38  5046.0  599.75
  5051.1  609.87  5100.3  616.66  5160.6  614.68  5180.7  610.36  5231.0  616.47
  5281.2  617.19  5301.3  619.37  6466.9  623.47  6788.5  626.94  7035.3  624.99
#Mann=4,-1,0
  2316.0    0.05       0  4858.7    0.12       0  4946.0    0.07       0
  4979.7    0.05       0
Bank Sta=4946,4979.7
Exp/Cntr=0.3,0.1

Type RM Length L Ch R = 1,2845,479,479,479
BEGIN DESCRIPTION:
Oliver Creek 4.0
END DESCRIPTION:
XS GIS Cut Line= 3
      2338421.86      7087146.23      2338175.11      7085033.58
      2337944.83      7083288.32
#Sta/Elev= 30
  2895.4  635.83  3103.0  639.46  3193.6  637.74  3233.9  623.88  3284.3  618.66
  3455.4  618.77  3485.6  623.20  3535.1  622.38  3546.0  625.26  3576.2  619.54
  3633.9  618.46  3657.3  617.60  3687.0  621.71  3717.2  620.28  3732.7  616.39
  3848.1  610.87  3930.2  612.03  4925.3  615.54  4935.4  615.20  4948.2  610.53
  4955.5  603.73  4989.0  599.24  4992.6  598.24  5022.8  599.24  5031.0  600.61
  5036.1  606.52  5046.2  610.51  5076.5  614.79  5137.0  617.48  6782.8  622.27
#Mann=7,-1,0
  2895.4    0.05       0  3535.1    0.12       0  3633.9    0.05       0
  3732.7    0.12       0  3930.2    0.05       0  4989.0   0.033       0
  5022.8    0.05       0
Bank Sta=4989,5022.8
Exp/Cntr=0.3,0.1

Type RM Length L Ch R = 1,2366,507,507,507
BEGIN DESCRIPTION:
Trail Cr Trib 2 20.0
END DESCRIPTION:
XS GIS Cut Line= 3
      2338702.04      7086262.69      2338413.21      7084021.36
      2338094.60      7083928.63
#Sta/Elev= 30
  3458.7  628.95  3501.7  627.68  3632.8  618.61  3673.1  617.43  3683.2  615.43
  3733.6  615.08  3774.0  612.51  3864.7  609.77  4036.1  612.10  4530.2  614.33
  4701.6  613.24  4923.4  614.02  4934.2  613.16  4953.6  604.04  4963.7  601.50
  4986.7  599.07  4990.3  598.07  5016.9  598.07  5020.5  599.07  5044.4  599.51
  5054.5  602.18  5074.6  614.17  5083.1  611.71  5088.1  614.46  5115.0  610.84
  5175.5  614.03  5400.9  614.10  5554.7  616.00  5910.4  617.91  6050.4  620.10
#Mann=3,-1,0
  3458.7    0.05       0  4986.7   0.033       0  5020.5    0.05       0
Bank Sta=4986.7,5020.5
Exp/Cntr=0.3,0.1

Type RM Length L Ch R = 1,1859,456,456,456
BEGIN DESCRIPTION:
Oliver Creek 3.0
END DESCRIPTION:
XS GIS Cut Line= 4
      2338968.55      7086148.47      2338878.73      7084444.50
      2338835.88      7084124.10      2338108.24      7083876.82
#Sta/Elev= 30
  3313.4  626.78  3341.9  626.40  3452.1  629.84  3562.2  629.00  3632.3  625.33
  3802.5  619.01  3892.7  612.49  3922.7  609.06  3973.8  607.32  4062.9  610.46
  4643.7  613.28  4894.1  612.32  4934.1  608.93  4944.1  607.33  4954.1  600.57
  4964.2  597.11  4967.2  596.74  4970.9  595.74  4997.5  595.74  5001.1  596.74
  5004.2  596.95  5014.2  600.05  5019.5  609.14  5024.5  609.14  5044.5  615.87
  5052.5  617.28  5094.9  616.41  5525.6  615.55  5793.8  616.45  6111.5  619.85
#Mann=3,-1,0
  3313.4    0.05       0  4967.2   0.033       0  5001.1    0.05       0
Bank Sta=4967.2,5001.1
Exp/Cntr=0.3,0.1