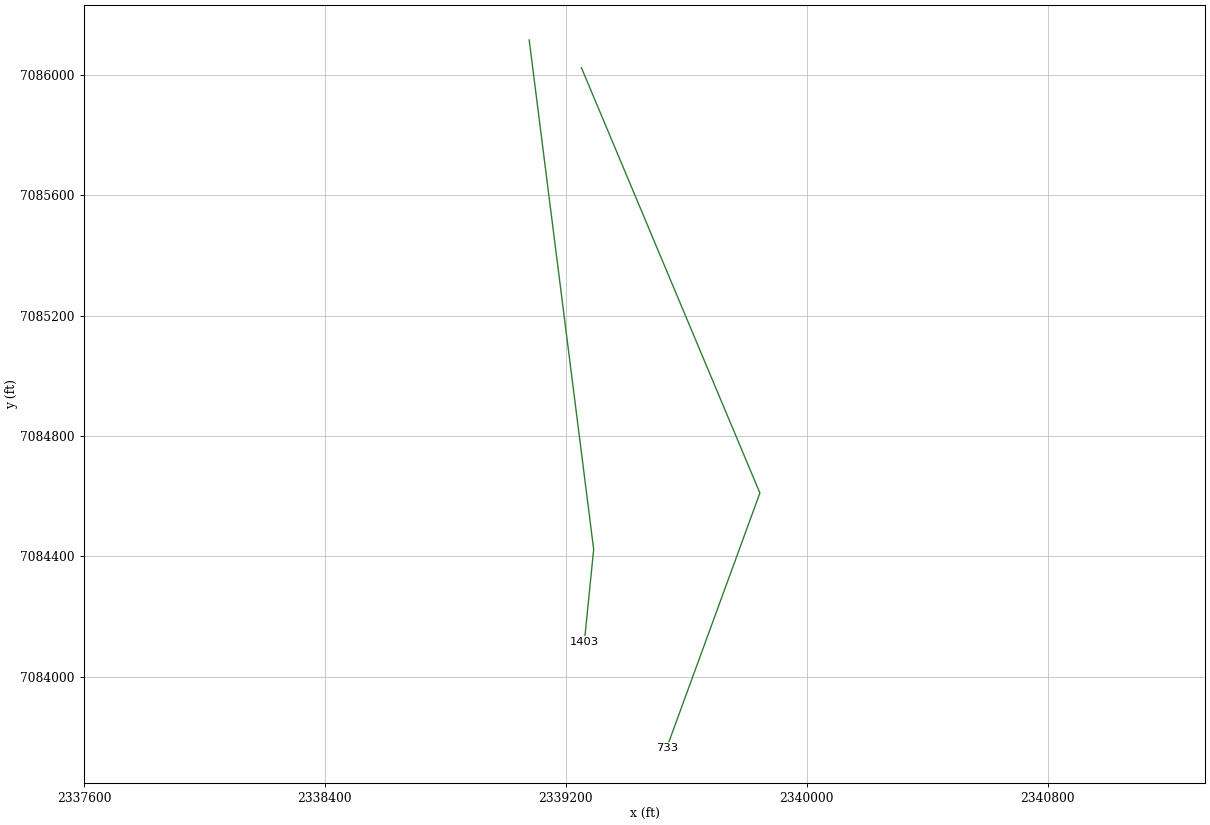
HEC-RAS study Oliver Creek.prj: Oliver Creek Base Level Engineering

--- Oliver Creek.g01 (geometry) --- (continued)

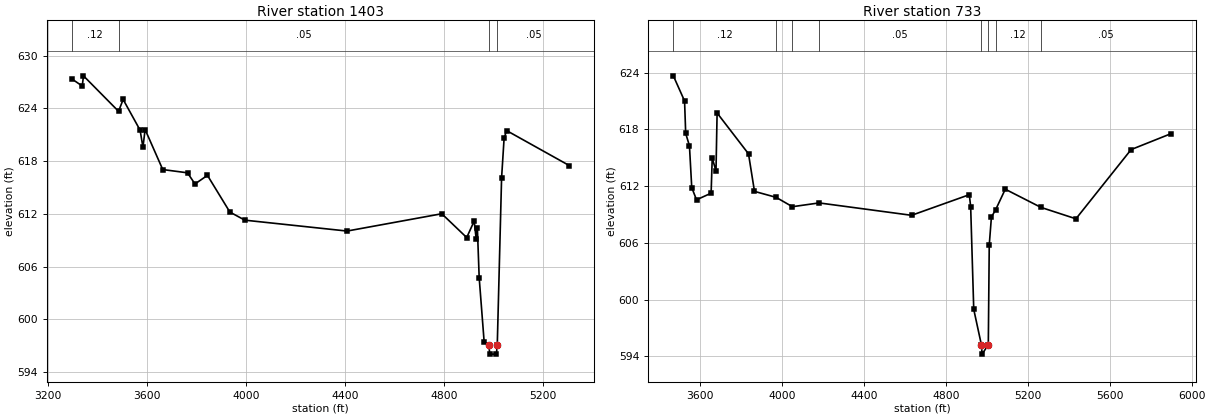
Type RM Length L Ch R = 1,1403,670,670,670
BEGIN DESCRIPTION:
Oliver Creek 2.0
END DESCRIPTION:
XS GIS Cut Line= 3
      2339078.23      7086115.05      2339292.33      7084423.65
      2339261.56      7084117.29
#Sta/Elev= 30
  3295.1  627.38  3338.3  626.55  3343.3  627.71  3485.1  623.67  3503.6  625.02
  3572.3  621.52  3583.7  619.57  3592.5  621.60  3663.8  617.04  3763.9  616.67
  3794.1  615.40  3844.5  616.38  3935.2  612.20  3995.7  611.28  4409.0  610.04
  4792.0  612.01  4892.8  609.30  4923.0  611.18  4930.9  609.18  4935.9  610.38
  4943.2  604.74  4963.4  597.38  4982.4  597.03  4986.0  596.03  5012.6  596.03
  5016.3  597.03  5033.8  616.09  5043.9  620.58  5053.9  621.48  5307.9  617.49
#Mann=4,-1,0
  3295.1    0.12       0  3485.1    0.05       0  4982.4   0.033       0
  5016.3    0.05       0
Bank Sta=4982.4,5016.3
Exp/Cntr=0.3,0.1

Type RM Length L Ch R = 1,733,0,0,0
BEGIN DESCRIPTION:
Oliver Creek 1.0
END DESCRIPTION:
XS GIS Cut Line= 3
      2339251.65      7086022.87      2339844.27      7084610.68
      2339535.25      7083765.50
#Sta/Elev= 30
  3468.5  623.66  3523.3  621.00  3528.8  617.57  3547.1  616.27  3558.4  611.84
  3581.7  610.55  3653.0  611.25  3658.4  614.97  3676.8  613.59  3682.2  619.73
  3835.6  615.41  3864.8  611.44  3970.4  610.81  4050.0  609.82  4180.4  610.22
  4632.0  608.91  4914.0  611.09  4920.6  609.84  4935.7  598.96  4972.9  595.23
  4976.6  594.23  5006.8  595.23  5011.4  605.77  5022.0  608.73  5042.4  609.49
  5089.7  611.67  5263.7  609.75  5434.8  608.54  5704.2  615.86  5899.9  617.55
#Mann=8,-1,0
  3468.5    0.12       0  3970.4    0.05       0  4050.0    0.12       0
  4180.4    0.05       0  4972.9   0.033       0  5006.8    0.05       0
  5042.4    0.12       0  5263.7    0.05       0
Bank Sta=4972.9,5006.8
Exp/Cntr=0.3,0.1

Chan Stop Cuts=-1