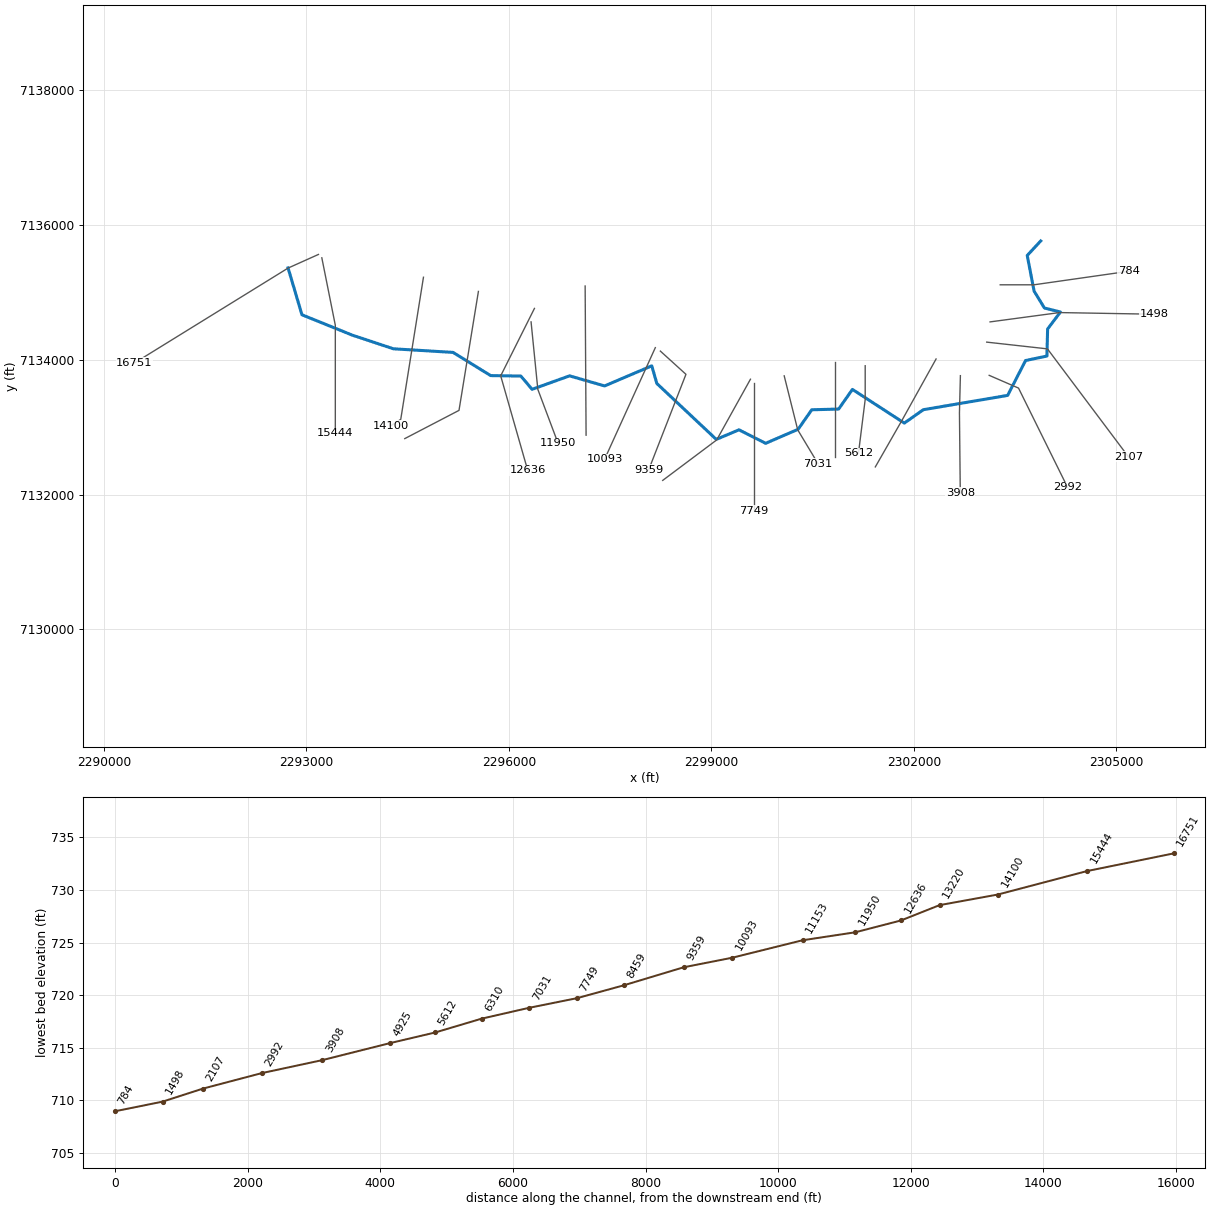
--- Sweetwater Creek DS.prj (project) ---

Proj Title=Sweetwater Creek DS Base Level Engineering
Current Plan=p01
Default Exp/Contr=0.3,0.1
English Units
Geom File=g01
Flow File=f01
Plan File=p01
BEGIN DESCRIPTION:
Sweetwater Creek DS
END DESCRIPTION:

--- Sweetwater Creek DS.p01 (plan) ---

Plan Title=Multiple Run
Short Identifier=Multiple
Geom File=g01
Flow File=f01
Subcritical Flow
K Sum by GR= 0
Std Step Tol= 0.01
Critical Tol= 0.01
Num of Std Step Trials= 20
Max Error Tol= 0.3
Flow Tol Ratio= 0.001
Split Flow NTrial= 30
Split Flow Tol= 0.02
Split Flow Ratio= 0.02
Log Output Level= 0
Friction Slope Method= 1
Unsteady Friction Slope Method= 2
Unsteady Bridges Friction Slope Method= 1
Parabolic Critical Depth
Global Vel Dist=  1 , 1 , 1
Global Log Level= 0
CheckData=True
Encroach Param= -1, 0, 0, 0
BEGIN DESCRIPTION:
Multiple Run
END DESCRIPTION:

--- Sweetwater Creek DS.f01 (steady flow) ---

Flow Title=Multiple
Number of Profiles=7
Profile Names=10-year,25-year,50-year,1pct_min,100-year,1pct_plu,500-year
River Rch & RM= Sweetwater Creek,Reach-1,16751
    9006   13602   17765   11430   22806   45503   37670
River Rch & RM= Sweetwater Creek,Reach-1,15444
    9059   13680   17865   11492   22930   45751   37864
River Rch & RM= Sweetwater Creek,Reach-1,14100
    9068   13683   17858   11481   22909   45709   37784
River Rch & RM= Sweetwater Creek,Reach-1,12636
    9082   13696   17868   11482   22910   45712   37753
River Rch & RM= Sweetwater Creek,Reach-1,8459
    9061   13649   17795   11427   22800   45492   37514
River Rch & RM= Sweetwater Creek,Reach-1,3908
    9270   13963   18203   11687   23318   46527   38354
River Rch & RM= Sweetwater Creek,Reach-1,2992
    9371   14118   18409   11821   23587   47062   38809
Boundary for River Rch & Prof#=Sweetwater Creek,Reach-1,1
Up Type=0
Dn Type=3
Dn Slope=0.001
Boundary for River Rch & Prof#=Sweetwater Creek,Reach-1,2
Up Type=0
Dn Type=3
Dn Slope=0.001
Boundary for River Rch & Prof#=Sweetwater Creek,Reach-1,3
Up Type=0
Dn Type=3
Dn Slope=0.001
Boundary for River Rch & Prof#=Sweetwater Creek,Reach-1,4
Up Type=0
Dn Type=3
Dn Slope=0.001
Boundary for River Rch & Prof#=Sweetwater Creek,Reach-1,5
Up Type=0
Dn Type=3
Dn Slope=0.001
Boundary for River Rch & Prof#=Sweetwater Creek,Reach-1,6
Up Type=0
Dn Type=3
Dn Slope=0.001
Boundary for River Rch & Prof#=Sweetwater Creek,Reach-1,7
Up Type=0
Dn Type=3
Dn Slope=0.001

--- Sweetwater Creek DS.g01 (geometry) ---

Geom Title=Existing Conditions

River Reach=Sweetwater Creek,Reach-1
Reach XY= 30
      2292729.00      7135360.00      2292934.59      7134665.58
      2293680.47      7134363.55      2294289.50      7134161.19
      2295173.06      7134107.74      2295730.55      7133763.75
      2296177.38      7133756.88      2296344.03      7133560.33
      2296898.99      7133760.02      2297418.31      7133610.74
      2298117.19      7133908.40      2298192.36      7133646.65
      2299072.81      7132817.80      2299408.94      7132960.22
      2299804.09      7132759.79      2300285.19      7132967.82
      2300486.97      7133257.07      2300885.48      7133267.69
      2301089.68      7133559.31      2301858.65      7133059.60
      2302140.83      7133258.38      2303389.12      7133470.34
      2303655.10      7133987.30      2303971.33      7134053.48
      2303981.24      7134454.07      2304171.41      7134706.69
      2303934.55      7134765.44      2303781.24      7135015.93
      2303679.24      7135544.78      2303879.00      7135760.00

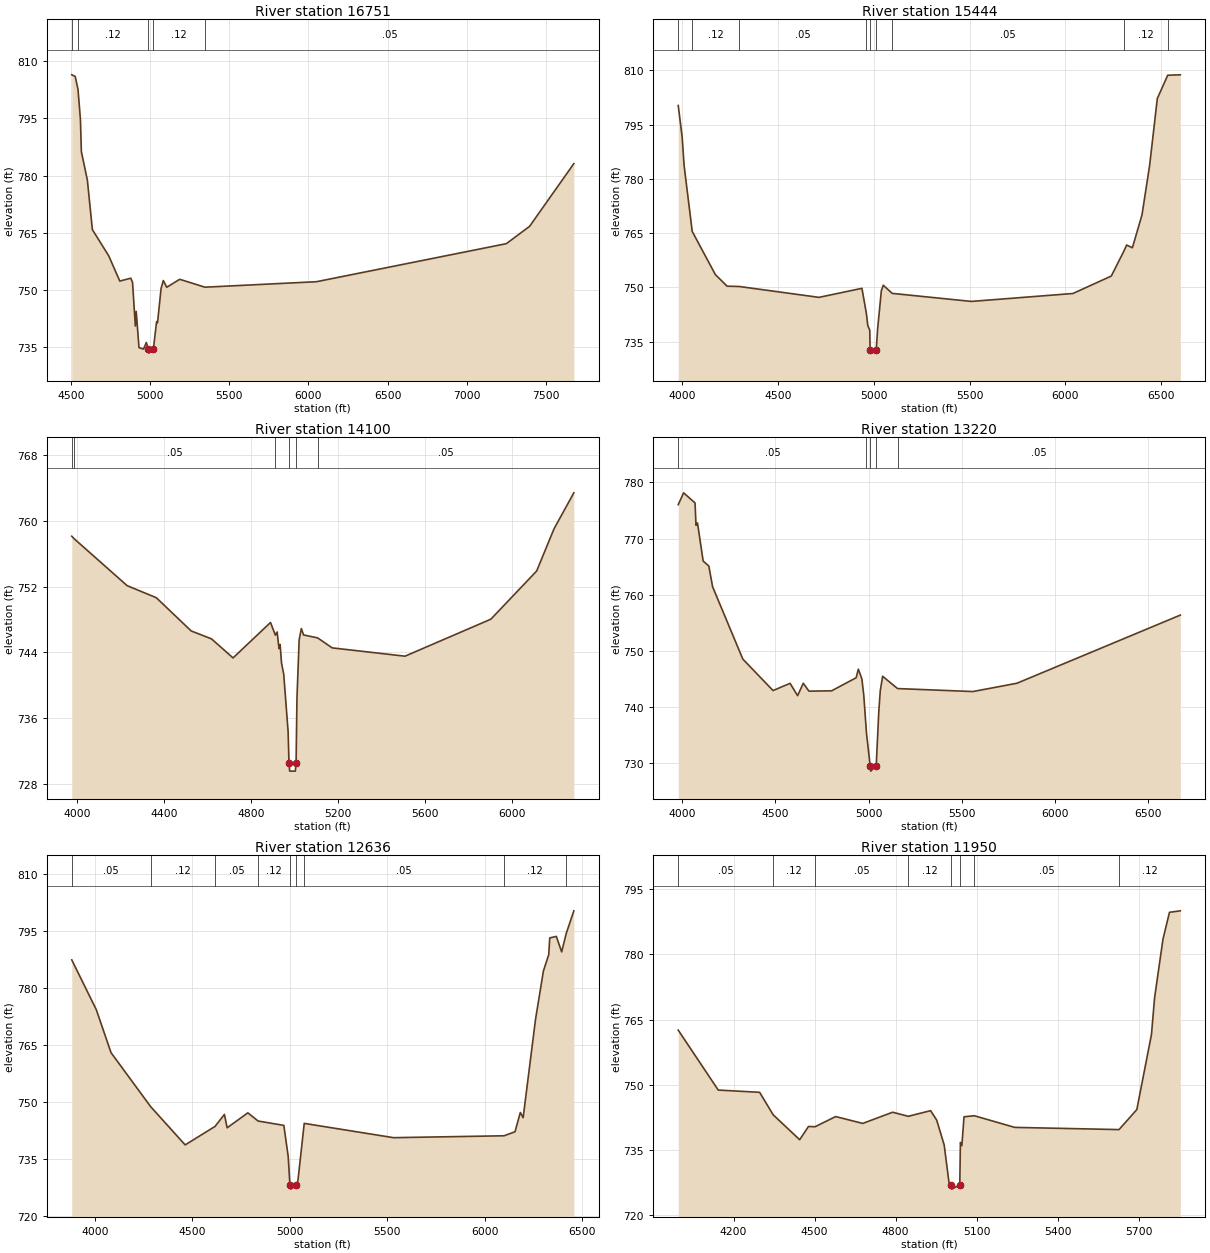
Type RM Length L Ch R = 1,16751,1307,1307,1307
BEGIN DESCRIPTION:
Sweetwater Creek 23.0
END DESCRIPTION:
XS GIS Cut Line= 3
      2293178.96      7135559.98      2292729.19      7135357.93
      2290452.68      7133950.34
#Sta/Elev= 30
  4506.7  806.42  4528.6  806.00  4546.0  802.61  4561.5  794.65  4567.3  786.29
  4605.3  778.80  4636.8  765.85  4740.4  758.96  4809.9  752.36  4879.4  753.12
  4890.4  752.02  4908.1  740.57  4913.5  744.42  4931.2  734.91  4959.9  734.55
  4977.5  736.28  4989.6  734.48  4992.8  733.48  5021.7  734.48  5042.3  741.75
  5048.1  741.43  5070.5  750.43  5084.8  752.51  5106.1  750.74  5188.1  752.83
  5347.7  750.76  6051.7  752.20  7250.3  762.17  7396.9  766.71  7676.3  783.15
#Mann=5,-1,0
  4506.7    0.05       0  4546.0    0.12       0  4989.6    0.07       0
  5021.7    0.12       0  5347.7    0.05       0
Bank Sta=4989.6,5021.7
Exp/Cntr=0.3,0.1

Type RM Length L Ch R = 1,15444,1344,1344,1344
BEGIN DESCRIPTION:
Sweetwater Creek 22.0
END DESCRIPTION:
XS GIS Cut Line= 3
      2293229.00      7135510.00      2293429.00      7134510.00
      2293429.00      7132910.00
#Sta/Elev= 30
  3980.2  800.28  4000.6  791.63  4010.8  783.68  4053.2  765.45  4174.0  753.51
  4235.2  750.31  4299.4  750.22  4714.5  747.22  4938.8  749.72  4961.9  742.78
  4969.4  739.40  4979.6  738.16  4981.3  732.80  4984.6  731.80  5013.7  732.80
  5020.0  738.12  5040.0  749.06  5050.0  750.57  5097.0  748.32  5510.0  746.10
  6040.0  748.29  6240.0  753.12  6304.5  759.90  6320.0  761.69  6350.0  760.94
  6400.0  770.02  6440.0  783.74  6480.0  802.21  6534.4  808.65  6600.0  808.76
#Mann=9,-1,0
  3980.2    0.05       0  4053.2    0.12       0  4299.4    0.05       0
  4961.9    0.12       0  4981.3    0.07       0  5013.7    0.12       0
  5097.0    0.05       0  6304.5    0.12       0  6534.4    0.05       0
Bank Sta=4981.3,5013.7
Exp/Cntr=0.3,0.1

Type RM Length L Ch R = 1,14100,880,880,880
BEGIN DESCRIPTION:
Mapping XS 77690e56
END DESCRIPTION:
XS GIS Cut Line= 3
      2294734.81      7135221.94      2294398.24      7133114.71
      2294252.42      7133020.77
#Sta/Elev= 30
  3975.4  758.14  3985.0  757.87  4229.8  752.13  4364.1  750.66  4524.2  746.62
  4617.5  745.66  4716.6  743.34  4888.8  747.65  4911.2  746.11  4919.2  746.50
  4927.9  744.47  4933.0  744.97  4939.4  742.71  4949.5  741.37  4969.8  734.33
  4973.6  730.57  4977.0  729.57  5002.9  729.57  5006.3  730.57  5010.3  738.43
  5020.4  745.54  5030.5  746.91  5040.7  746.13  5105.0  745.78  5172.3  744.56
  5506.9  743.55  5901.4  748.05  6111.9  753.91  6191.7  759.04  6282.8  763.42
#Mann=6,-1,0
  3975.4    0.12       0  3985.0    0.05       0  4911.2    0.12       0
  4973.6    0.07       0  5006.3    0.12       0  5105.0    0.05       0
Bank Sta=4973.6,5006.3
Exp/Cntr=0.3,0.1

Type RM Length L Ch R = 1,13220,584,584,584
BEGIN DESCRIPTION:
Mapping XS cf9ca1ed
END DESCRIPTION:
XS GIS Cut Line= 3
      2295548.86      7135011.99      2295261.25      7133248.14
      2294457.88      7132829.61
#Sta/Elev= 30
  3979.4  776.04  4008.2  778.15  4069.6  776.35  4074.7  772.36  4082.7  772.78
  4113.1  766.00  4143.5  765.10  4163.8  761.41  4325.9  748.52  4488.0  742.92
  4579.2  744.20  4619.7  742.01  4650.1  744.22  4680.5  742.81  4802.1  742.87
  4933.8  745.20  4945.3  746.73  4964.2  745.02  4974.4  742.16  4989.1  735.34
  5008.7  729.56  5012.1  728.56  5041.4  729.56  5055.4  739.34  5063.2  742.91
  5075.7  745.46  5155.9  743.27  5560.0  742.74  5796.1  744.22  6672.4  756.36
#Mann=5,-1,0
  3979.4    0.05       0  4989.1    0.12       0  5008.7    0.07       0
  5041.4    0.12       0  5155.9    0.05       0
Bank Sta=5008.7,5041.4
Exp/Cntr=0.3,0.1

Type RM Length L Ch R = 1,12636,686,686,686
BEGIN DESCRIPTION:
Sweetwater Creek 18.0
END DESCRIPTION:
XS GIS Cut Line= 3
      2296379.01      7134760.01      2295879.00      7133760.00
      2296279.01      7132359.97
#Sta/Elev= 30
  3882.4  787.39  4008.2  774.29  4083.7  762.99  4286.9  748.79  4463.8  738.73
  4616.7  743.58  4665.0  746.74  4679.0  743.23  4785.2  747.16  4837.9  745.01
  4969.7  743.86  4992.1  735.68  5001.0  728.10  5004.4  727.10  5033.7  728.10
  5042.0  729.37  5074.2  744.39  5532.2  740.63  6099.0  741.13  6154.9  742.19
  6182.2  747.26  6196.5  745.88  6260.2  771.80  6300.5  784.48  6327.8  788.77
  6333.0  793.17  6366.8  793.56  6394.1  789.49  6417.2  794.29  6456.5  800.29
#Mann=9,-1,0
  3882.4    0.05       0  4286.9    0.12       0  4616.7    0.05       0
  4837.9    0.12       0  5001.0    0.07       0  5033.7    0.12       0
  5074.2    0.05       0  6099.0    0.12       0  6417.2    0.05       0
Bank Sta=5001,5033.7
Exp/Cntr=0.3,0.1

Type RM Length L Ch R = 1,11950,797,797,797
BEGIN DESCRIPTION:
Sweetwater Creek 17.0
END DESCRIPTION:
XS GIS Cut Line= 3
      2296329.00      7134559.99      2296429.00      7133560.00
      2296729.01      7132759.98
#Sta/Elev= 30
  3994.9  762.57  4143.1  748.78  4296.4  748.26  4346.4  743.09  4444.6  737.35
  4477.3  740.40  4501.9  740.34  4577.8  742.68  4678.3  741.10  4788.8  743.68
  4847.1  742.74  4929.5  744.04  4952.1  741.86  4979.8  736.15  4997.4  727.64
  5004.9  726.98  5008.2  725.98  5037.6  726.98  5039.9  736.72  5045.3  735.98
  5053.3  742.63  5091.4  742.87  5241.1  740.19  5627.3  739.68  5693.2  744.28
  5747.5  761.58  5759.0  770.00  5790.2  783.53  5814.2  789.69  5854.3  790.03
#Mann=8,-1,0
  3994.9    0.05       0  4346.4    0.12       0  4501.9    0.05       0
  4847.1    0.12       0  5004.9    0.07       0  5037.6    0.12       0
  5091.4    0.05       0  5627.3    0.12       0
Bank Sta=5004.9,5037.6
Exp/Cntr=0.3,0.1

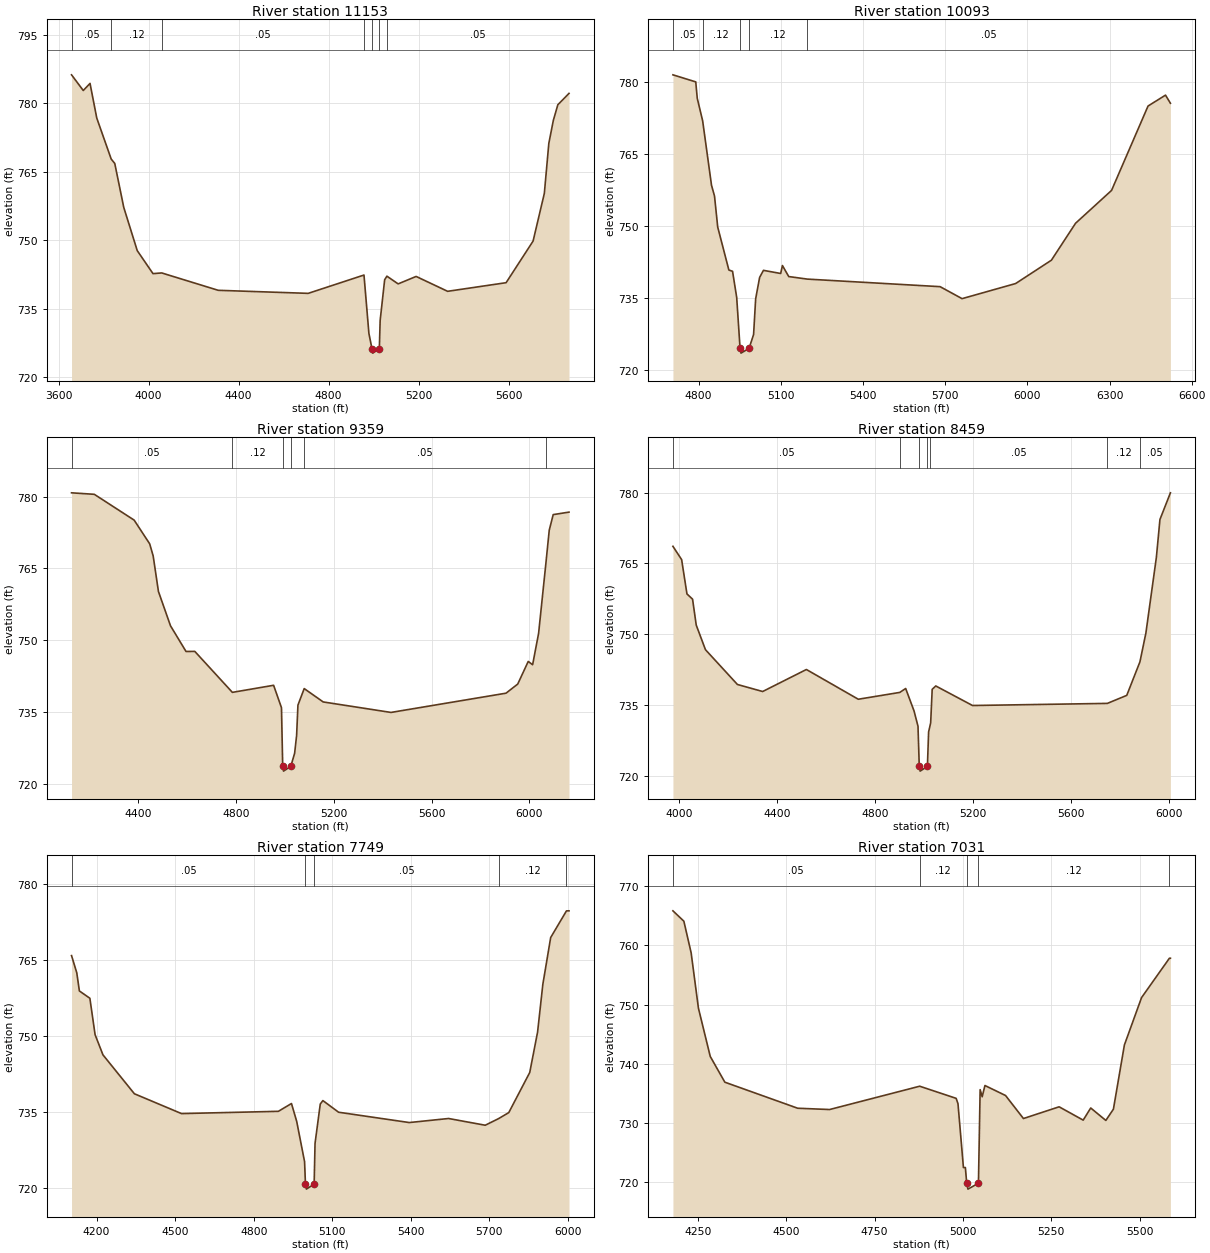
Type RM Length L Ch R = 1,11153,1060,1060,1060
BEGIN DESCRIPTION:
Mapping XS 0e64e72b
END DESCRIPTION:
XS GIS Cut Line= 2
      2297130.10      7135092.17      2297144.01      7132880.32
#Sta/Elev= 30
  3657.1  786.27  3709.3  782.83  3739.3  784.39  3769.3  776.78  3833.4  767.80
  3849.3  766.83  3889.3  757.19  3949.3  747.70  4019.3  742.66  4058.1  742.81
  4309.3  739.00  4709.3  738.33  4957.4  742.35  4979.3  729.54  4992.8  726.22
  4996.2  725.22  5025.7  726.22  5029.3  732.38  5049.3  741.31  5059.3  742.10
  5109.3  740.41  5189.3  742.04  5329.3  738.78  5589.3  740.67  5709.3  749.80
  5759.3  760.26  5779.3  771.24  5799.3  776.27  5819.3  779.70  5869.0  782.20
#Mann=7,-1,0
  3657.1    0.05       0  3833.4    0.12       0  4058.1    0.05       0
  4957.4    0.12       0  4992.8    0.07       0  5025.7    0.12       0
  5059.3    0.05       0
Bank Sta=4992.8,5025.7
Exp/Cntr=0.3,0.1

Type RM Length L Ch R = 1,10093,734,734,734
BEGIN DESCRIPTION:
Mapping XS 3498754b
END DESCRIPTION:
XS GIS Cut Line= 2
      2298169.68      7134178.18      2297418.57      7132524.35
#Sta/Elev= 30
  4706.0  781.39  4789.3  779.92  4794.8  776.50  4814.5  771.83  4846.8  758.46
  4857.8  756.20  4869.5  749.75  4910.2  740.83  4923.7  740.56  4938.8  735.13
  4951.1  724.56  4954.5  723.56  4984.1  724.56  5000.5  727.44  5008.0  734.83
  5022.5  739.29  5036.5  740.76  5099.4  740.11  5105.8  741.76  5128.8  739.47
  5197.1  738.94  5681.5  737.37  5761.7  734.88  5957.3  738.02  6087.9  742.87
  6176.0  750.54  6307.5  757.37  6440.8  774.91  6504.5  777.17  6522.4  775.49
#Mann=5,-1,0
  4706.0    0.05       0  4814.5    0.12       0  4951.1    0.07       0
  4984.1    0.12       0  5197.1    0.05       0
Bank Sta=4951.1,4984.1
Exp/Cntr=0.3,0.1

Type RM Length L Ch R = 1,9359,900,900,900
BEGIN DESCRIPTION:
Mapping XS b829f20d
END DESCRIPTION:
XS GIS Cut Line= 3
      2298244.42      7134126.99      2298623.37      7133782.85
      2298070.59      7132364.67
#Sta/Elev= 30
  4127.6  780.78  4220.7  780.47  4383.6  775.08  4447.1  770.13  4461.3  767.62
  4482.9  760.18  4532.2  753.01  4595.7  747.64  4631.6  747.66  4785.2  739.10
  4953.8  740.58  4986.0  735.90  4991.0  723.65  4994.4  722.65  5024.0  723.65
  5039.7  726.36  5047.9  730.13  5053.3  736.44  5078.9  739.89  5156.6  737.10
  5433.8  734.91  5904.0  738.93  5952.0  740.84  5994.9  745.56  6012.8  744.87
  6037.3  751.43  6067.2  766.11  6080.8  772.98  6097.0  776.23  6161.6  776.75
#Mann=6,-1,0
  4127.6    0.05       0  4785.2    0.12       0  4991.0    0.07       0
  5024.0    0.12       0  5078.9    0.05       0  6067.2    0.12       0
Bank Sta=4991,5024
Exp/Cntr=0.3,0.1

Type RM Length L Ch R = 1,8459,710,710,710
BEGIN DESCRIPTION:
Sweetwater Creek 12.0
END DESCRIPTION:
XS GIS Cut Line= 3
      2299579.01      7133710.01      2299079.00      7132810.00
      2298278.98      7132209.99
#Sta/Elev= 30
  3974.3  768.63  4009.8  765.81  4031.5  758.53  4054.4  757.42  4069.3  751.93
  4107.0  746.70  4237.4  739.32  4340.4  737.83  4518.8  742.50  4730.5  736.19
  4899.9  737.64  4923.8  738.47  4958.1  733.69  4974.1  730.46  4979.3  721.94
  4982.8  720.94  5012.5  721.94  5017.4  729.25  5021.1  730.10  5025.8  731.18
  5032.0  738.29  5046.6  739.01  5196.6  734.86  5746.7  735.31  5825.8  737.01
  5879.6  744.13  5903.9  750.24  5946.6  766.27  5961.2  774.32  6003.9  779.98
#Mann=7,-1,0
  3974.3    0.05       0  4899.9    0.12       0  4979.3    0.07       0
  5012.5    0.12       0  5021.1    0.05       0  5746.7    0.12       0
  5879.6    0.05       0
Bank Sta=4979.3,5012.5
Exp/Cntr=0.3,0.1

Type RM Length L Ch R = 1,7749,718,718,718
BEGIN DESCRIPTION:
Sweetwater Creek 11.0
END DESCRIPTION:
XS GIS Cut Line= 3
      2299629.00      7133659.95      2299629.00      7132760.00
      2299629.00      7131759.95
#Sta/Elev= 30
  4104.3  765.87  4124.3  762.47  4134.3  758.88  4174.3  757.44  4194.3  750.23
  4224.3  746.25  4344.3  738.56  4524.3  734.64  4894.3  735.09  4944.3  736.63
  4964.3  733.09  4994.3  725.15  4997.7  720.71  5001.2  719.71  5030.9  720.71
  5034.3  728.75  5054.3  736.53  5064.3  737.21  5124.3  734.91  5394.3  732.87
  5544.3  733.67  5684.3  732.34  5735.5  733.65  5774.3  734.84  5854.3  742.76
  5884.3  750.76  5904.3  760.17  5934.3  769.44  5994.6  774.71  6004.3  774.72
#Mann=5,-1,0
  4104.3    0.05       0  4997.7    0.04       0  5030.9    0.05       0
  5735.5    0.12       0  5994.6    0.05       0
Bank Sta=4997.7,5030.9
Exp/Cntr=0.3,0.1

Type RM Length L Ch R = 1,7031,721,721,721
BEGIN DESCRIPTION:
Sweetwater Creek 10.0
END DESCRIPTION:
XS GIS Cut Line= 3
      2300079.00      7133759.99      2300279.00      7132960.00
      2300578.99      7132460.01
#Sta/Elev= 30
  4179.3  765.83  4210.2  764.08  4230.8  758.74  4251.4  749.39  4284.9  741.22
  4326.2  736.87  4532.3  732.47  4622.5  732.25  4877.5  736.19  4980.7  734.14
  4985.9  733.24  5001.3  722.45  5006.8  722.45  5010.6  719.80  5014.1  718.80
  5043.8  719.80  5048.6  735.61  5054.4  734.41  5062.2  736.31  5120.5  734.62
  5171.1  730.73  5272.1  732.71  5340.2  730.46  5361.5  732.51  5404.3  730.41
  5425.7  732.31  5456.8  743.16  5505.4  751.17  5584.2  757.82  5587.0  757.82
#Mann=5,-1,0
  4179.3    0.05       0  4877.5    0.12       0  5010.6    0.07       0
  5043.8    0.12       0  5584.2    0.05       0
Bank Sta=5010.6,5043.8
Exp/Cntr=0.3,0.1

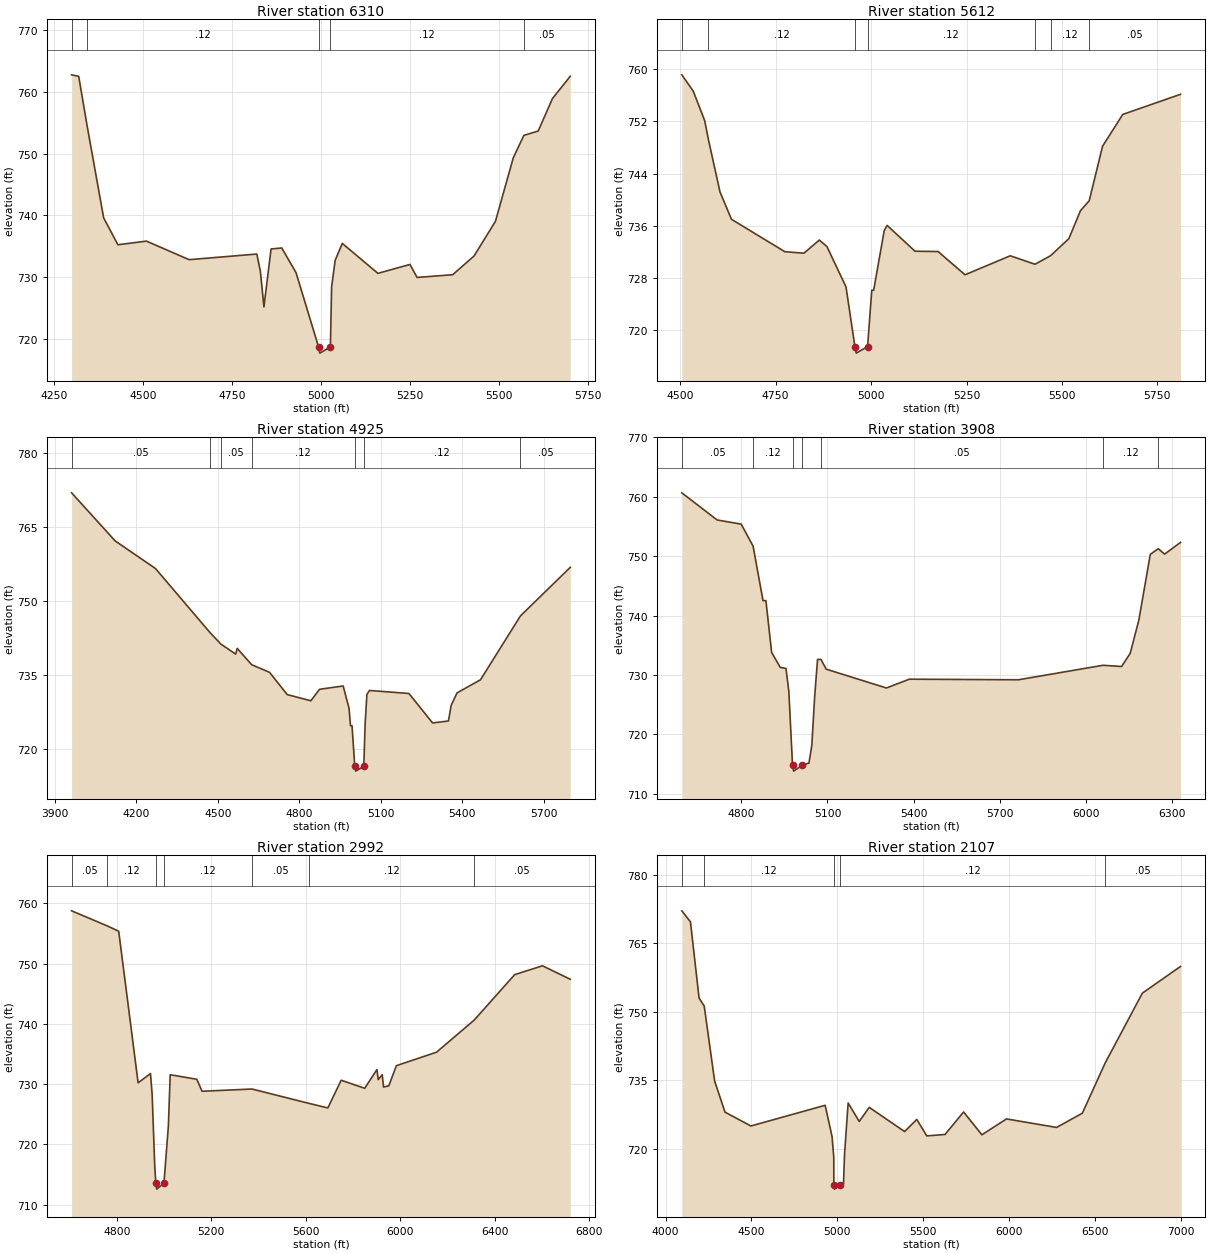
Type RM Length L Ch R = 1,6310,698,698,698
BEGIN DESCRIPTION:
Sweetwater Creek 9.0
END DESCRIPTION:
XS GIS Cut Line= 3
      2300829.00      7133959.97      2300829.00      7133260.00
      2300829.00      7132559.97
#Sta/Elev= 30
  4299.6  762.73  4319.6  762.48  4342.1  754.84  4389.6  739.62  4429.6  735.27
  4509.6  735.86  4629.6  732.86  4819.6  733.77  4829.6  731.00  4839.6  725.23
  4859.6  734.59  4889.6  734.75  4929.6  730.78  4993.0  718.76  4996.5  717.76
  5026.2  718.76  5029.6  728.44  5039.6  732.76  5059.6  735.49  5159.6  730.65
  5249.6  732.09  5269.6  729.99  5369.6  730.43  5429.6  733.46  5489.6  739.06
  5539.6  749.31  5569.3  752.94  5609.6  753.65  5649.6  758.89  5699.6  762.50
#Mann=5,-1,0
  4299.6    0.05       0  4342.1    0.12       0  4993.0    0.07       0
  5026.2    0.12       0  5569.3    0.05       0
Bank Sta=4993,5026.2
Exp/Cntr=0.3,0.1

Type RM Length L Ch R = 1,5612,687,687,687
BEGIN DESCRIPTION:
Sweetwater Creek 8.0
END DESCRIPTION:
XS GIS Cut Line= 3
      2301279.00      7133909.96      2301279.00      7133410.00
      2301179.00      7132609.99
#Sta/Elev= 30
  4504.3  759.16  4534.3  756.65  4564.3  752.11  4573.4  749.37  4604.3  741.19
  4634.3  736.99  4774.3  732.01  4824.3  731.79  4864.3  733.80  4884.3  732.82
  4934.3  726.63  4957.7  717.45  4961.2  716.45  4990.9  717.45  5001.8  726.10
  5006.8  726.10  5034.5  735.26  5042.1  736.05  5115.1  732.09  5175.6  732.04
  5246.1  728.47  5364.5  731.39  5429.5  730.09  5470.1  731.40  5518.2  734.02
  5548.5  738.31  5571.5  739.84  5606.4  748.20  5659.3  753.08  5810.5  756.17
#Mann=7,-1,0
  4504.3    0.05       0  4573.4    0.12       0  4957.7    0.07       0
  4990.9    0.12       0  5429.5    0.05       0  5470.1    0.12       0
  5571.5    0.05       0
Bank Sta=4957.7,4990.9
Exp/Cntr=0.3,0.1

Type RM Length L Ch R = 1,4925,1017,1017,1017
BEGIN DESCRIPTION:
Sweetwater Creek 7.0
END DESCRIPTION:
XS GIS Cut Line= 3
      2302328.99      7134009.99      2301829.00      7133110.00
      2301428.99      7132409.98
#Sta/Elev= 30
  3961.7  771.88  4121.8  762.14  4270.6  756.52  4470.2  743.60  4511.2  741.20
  4565.7  739.17  4571.4  740.33  4624.7  737.01  4690.4  735.47  4755.6  730.95
  4842.5  729.70  4874.6  732.03  4961.5  732.70  4983.2  728.17  4988.4  724.64
  4994.1  724.64  5004.2  716.43  5007.7  715.43  5037.4  716.43  5042.4  725.08
  5048.8  730.98  5058.2  731.79  5203.6  731.18  5290.7  725.20  5349.0  725.60
  5359.1  728.77  5380.7  731.30  5467.1  733.96  5614.1  746.91  5797.5  756.76
#Mann=7,-1,0
  3961.7    0.05       0  4470.2    0.12       0  4511.2    0.05       0
  4624.7    0.12       0  5004.2    0.07       0  5037.4    0.12       0
  5614.1    0.05       0
Bank Sta=5004.2,5037.4
Exp/Cntr=0.3,0.1

Type RM Length L Ch R = 1,3908,916,916,916
BEGIN DESCRIPTION:
Mapping XS 93ca70cb
END DESCRIPTION:
XS GIS Cut Line= 3
      2302689.21      7133763.01      2302675.25      7133212.06
      2302687.60      7132024.85
#Sta/Elev= 30
  4592.2  760.68  4715.2  756.11  4799.1  755.41  4840.6  751.71  4875.3  742.52
  4885.3  742.53  4905.3  733.81  4935.3  731.29  4955.3  731.11  4965.3  727.23
  4978.1  714.82  4981.9  713.82  5012.6  714.82  5035.4  715.17  5045.4  718.16
  5055.4  726.45  5065.4  732.64  5077.5  732.62  5095.4  730.99  5305.4  727.82
  5385.4  729.30  5765.4  729.20  6060.4  731.64  6125.4  731.44  6155.4  733.66
  6185.4  739.24  6225.4  750.32  6253.1  751.27  6275.4  750.36  6330.6  752.33
#Mann=7,-1,0
  4592.2    0.05       0  4840.6    0.12       0  4978.1    0.07       0
  5012.6    0.12       0  5077.5    0.05       0  6060.4    0.12       0
  6253.1    0.05       0
Bank Sta=4978.1,5012.6
Exp/Cntr=0.3,0.1

Type RM Length L Ch R = 1,2992,885,885,885
BEGIN DESCRIPTION:
Mapping XS 682fc074
END DESCRIPTION:
XS GIS Cut Line= 3
      2303115.93      7133767.48      2303550.37      7133578.69
      2304275.99      7132109.38
#Sta/Elev= 30
  4608.4  758.76  4759.5  756.26  4808.0  755.37  4890.2  730.22  4942.6  731.76
  4949.7  728.23  4960.5  716.43  4965.2  713.58  4969.0  712.58  4999.7  713.58
  5018.3  723.02  5026.1  731.56  5138.7  730.81  5161.2  728.82  5372.6  729.19
  5612.8  726.82  5694.0  726.05  5750.3  730.65  5850.2  729.31  5901.8  732.42
  5907.4  730.76  5924.3  731.56  5929.9  729.52  5952.3  729.72  5984.0  733.06
  6154.3  735.30  6313.9  740.63  6485.4  748.17  6603.2  749.64  6720.8  747.40
#Mann=7,-1,0
  4608.4    0.05       0  4759.5    0.12       0  4965.2    0.07       0
  4999.7    0.12       0  5372.6    0.05       0  5612.8    0.12       0
  6313.9    0.05       0
Bank Sta=4965.2,4999.7
Exp/Cntr=0.3,0.1

Type RM Length L Ch R = 1,2107,609,609,609
BEGIN DESCRIPTION:
Sweetwater Creek 3.0
END DESCRIPTION:
XS GIS Cut Line= 3
      2303078.99      7134260.00      2303979.00      7134160.00
      2305179.03      7132559.96
#Sta/Elev= 30
  4094.3  772.16  4144.6  769.74  4194.9  753.00  4224.7  751.28  4285.5  734.82
  4345.9  728.00  4496.8  724.96  4929.4  729.50  4969.7  722.64  4979.7  718.09
  4980.1  712.11  4983.9  711.11  5014.6  712.11  5036.3  712.25  5042.6  718.88
  5063.4  730.00  5128.0  725.95  5186.3  729.04  5392.6  723.74  5463.4  726.40
  5521.7  722.79  5628.0  723.10  5736.3  728.03  5842.6  723.03  5986.3  726.51
  6278.0  724.64  6428.0  727.76  6561.0  738.77  6778.0  754.11  6999.9  759.95
#Mann=5,-1,0
  4094.3    0.05       0  4224.7    0.12       0  4980.1    0.07       0
  5014.6    0.12       0  6561.0    0.05       0
Bank Sta=4980.1,5014.6
Exp/Cntr=0.3,0.1

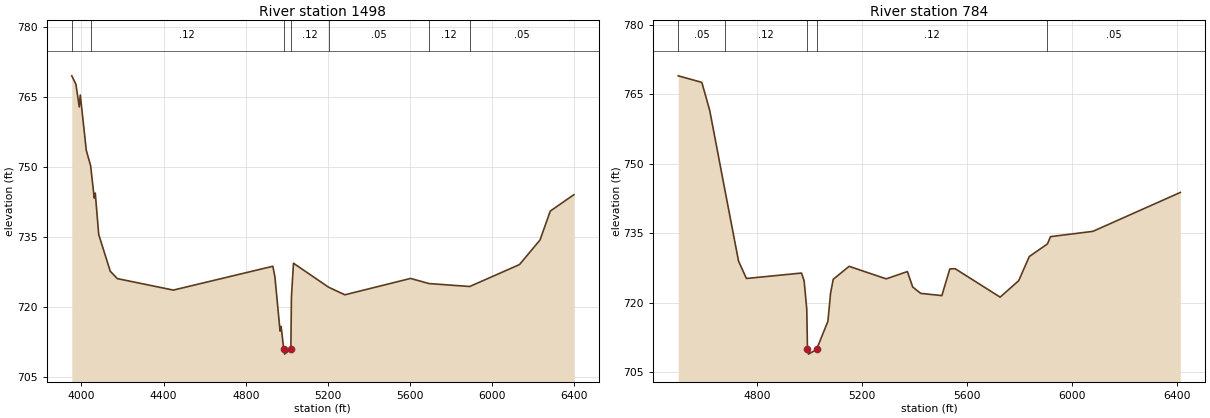
Type RM Length L Ch R = 1,1498,714,714,714
BEGIN DESCRIPTION:
Sweetwater Creek 2.0
END DESCRIPTION:
XS GIS Cut Line= 3
      2303128.96      7134559.99      2304158.07      7134698.21
      2305563.60      7134673.59
#Sta/Elev= 30
  3953.1  769.54  3973.3  767.75  3989.6  762.87  3994.6  765.43  4023.8  753.58
  4045.0  750.24  4062.5  743.33  4067.5  744.40  4084.3  735.53  4140.4  727.65
  4175.1  726.06  4447.5  723.60  4931.9  728.71  4941.9  726.48  4967.2  714.80
  4972.3  715.82  4985.1  710.87  4988.9  709.87  5019.6  710.87  5022.4  722.12
  5032.4  729.36  5203.3  724.22  5282.4  722.59  5602.5  726.10  5692.3  725.00
  5890.2  724.37  6132.6  729.07  6232.6  734.35  6282.6  740.55  6397.2  744.05
#Mann=7,-1,0
  3953.1    0.05       0  4045.0    0.12       0  4985.1    0.07       0
  5019.6    0.12       0  5203.3    0.05       0  5692.3    0.12       0
  5890.2    0.05       0
Bank Sta=4985.1,5019.6
Exp/Cntr=0.3,0.1

Type RM Length L Ch R = 1,784,0,0,0
BEGIN DESCRIPTION:
Sweetwater Creek 1.0
END DESCRIPTION:
XS GIS Cut Line= 3
      2303279.01      7135110.00      2303779.00      7135110.00
      2305179.00      7135310.00
#Sta/Elev= 30
  4500.1  768.96  4590.1  767.55  4620.1  761.51  4677.5  744.50  4730.1  729.01
  4760.1  725.27  4970.1  726.44  4980.1  724.76  4990.1  718.69  4992.9  709.96
  4996.7  708.96  5027.4  709.96  5070.8  716.06  5080.9  722.11  5091.0  725.09
  5151.6  727.89  5293.0  725.19  5373.8  726.76  5394.0  723.44  5424.4  722.06
  5505.2  721.58  5535.5  727.32  5555.7  727.38  5727.4  721.25  5798.1  724.79
  5838.5  730.00  5907.8  732.72  5919.3  734.29  6081.0  735.43  6414.3  743.82
#Mann=5,-1,0
  4500.1    0.05       0  4677.5    0.12       0  4992.9    0.07       0
  5027.4    0.12       0  5907.8    0.05       0
Bank Sta=4992.9,5027.4
Exp/Cntr=0.3,0.1

Chan Stop Cuts=-1