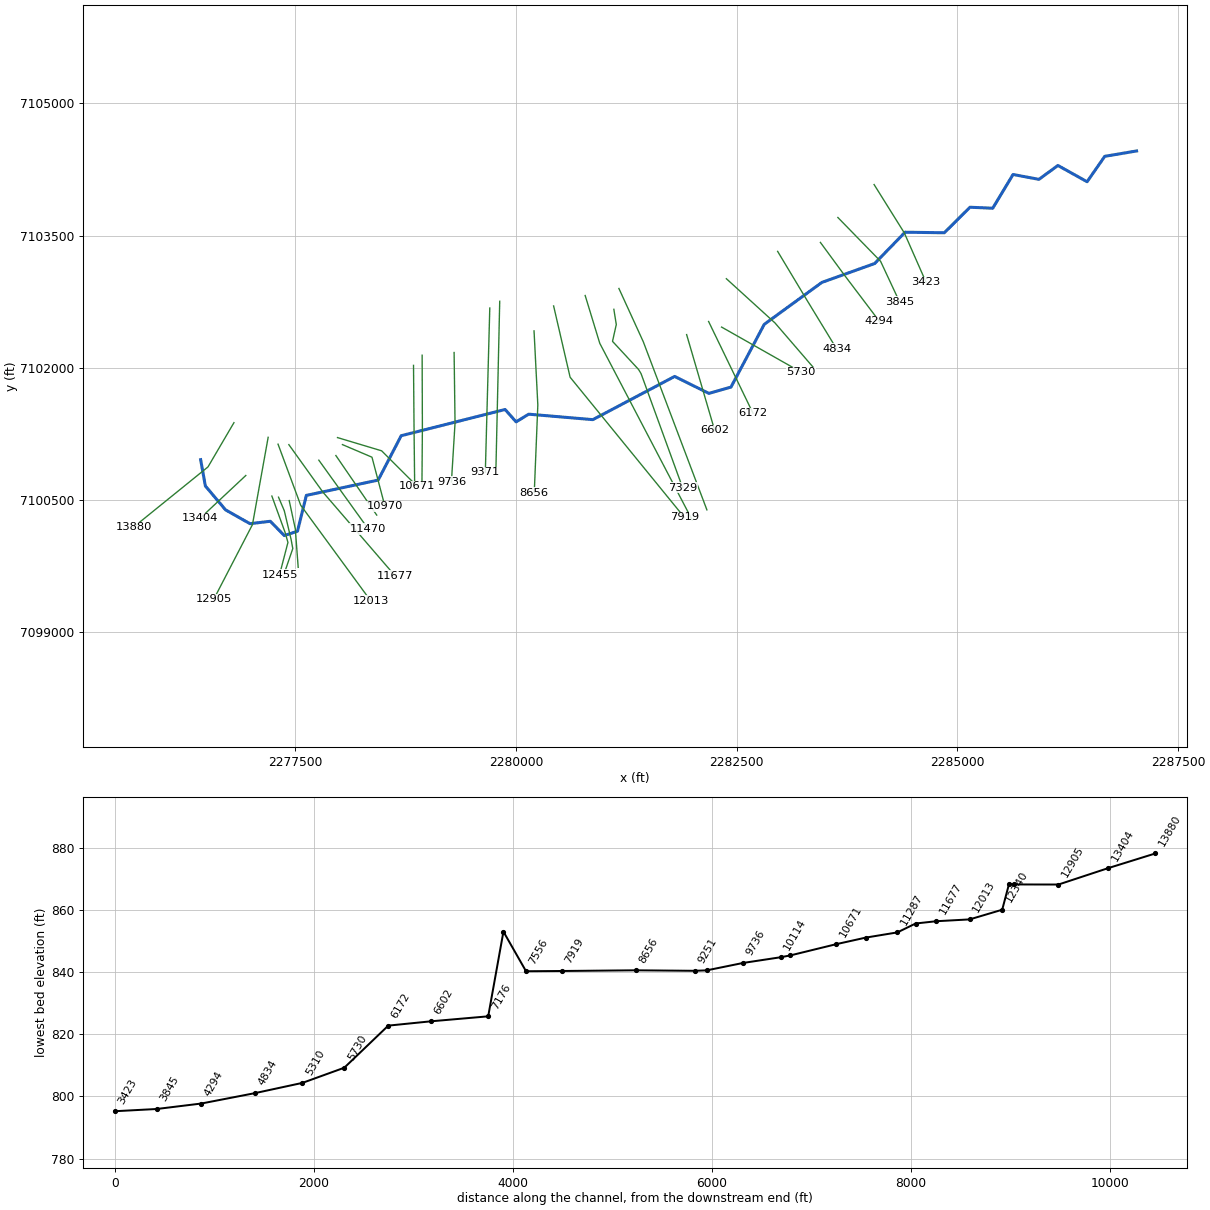
--- Teeter Branch.prj (project) ---

Proj Title=Teeter Branch Base Level Engineering
Current Plan=p01
Default Exp/Contr=0.3,0.1
English Units
Geom File=g01
Flow File=f01
Plan File=p01
BEGIN DESCRIPTION:
Teeter Branch
END DESCRIPTION:

--- Teeter Branch.p01 (plan) ---

Plan Title=Multiple Run
Short Identifier=Multiple
Geom File=g01
Flow File=f01
Subcritical Flow
K Sum by GR= 0
Std Step Tol= 0.01
Critical Tol= 0.01
Num of Std Step Trials= 20
Max Error Tol= 0.3
Flow Tol Ratio= 0.001
Split Flow NTrial= 30
Split Flow Tol= 0.02
Split Flow Ratio= 0.02
Log Output Level= 0
Friction Slope Method= 1
Unsteady Friction Slope Method= 2
Unsteady Bridges Friction Slope Method= 1
Parabolic Critical Depth
Global Vel Dist=  1 , 1 , 1
Global Log Level= 0
CheckData=True
Encroach Param= -1, 0, 0, 0
BEGIN DESCRIPTION:
Multiple Run
END DESCRIPTION:

--- Teeter Branch.f01 (steady flow) ---

Flow Title=Multiple
Number of Profiles=7
Profile Names=10-year,25-year,50-year,1pct_min,100-year,1pct_plu,500-year
River Rch & RM= Teeter Branch,Reach-1,13880
     380     508     611     366     730    1457    1043
River Rch & RM= Teeter Branch,Reach-1,12905
     847    1190    1480     914    1823    3637    2773
River Rch & RM= Teeter Branch,Reach-1,12455
    1173    1671    2097    1304    2602    5191    4019
River Rch & RM= Teeter Branch,Reach-1,7176
    1725    2518    3214    2031    4053    8086    6467
River Rch & RM= Teeter Branch,Reach-1,5310
    1786    2597    3304    2081    4151    8283    6577
Boundary for River Rch & Prof#=Teeter Branch,Reach-1,1
Up Type=0
Dn Type=3
Dn Slope=0.005
Boundary for River Rch & Prof#=Teeter Branch,Reach-1,2
Up Type=0
Dn Type=3
Dn Slope=0.005
Boundary for River Rch & Prof#=Teeter Branch,Reach-1,3
Up Type=0
Dn Type=3
Dn Slope=0.005
Boundary for River Rch & Prof#=Teeter Branch,Reach-1,4
Up Type=0
Dn Type=3
Dn Slope=0.005
Boundary for River Rch & Prof#=Teeter Branch,Reach-1,5
Up Type=0
Dn Type=3
Dn Slope=0.005
Boundary for River Rch & Prof#=Teeter Branch,Reach-1,6
Up Type=0
Dn Type=3
Dn Slope=0.005
Boundary for River Rch & Prof#=Teeter Branch,Reach-1,7
Up Type=0
Dn Type=3
Dn Slope=0.005

--- Teeter Branch.g01 (geometry) ---

Geom Title=Existing Conditions

River Reach=Teeter Branch,Reach-1
Reach XY= 30
      2276429.00      7100960.00      2276482.12      7100661.62
      2276711.30      7100390.04      2276987.75      7100233.90
      2277217.70      7100261.06      2277376.84      7100098.88
      2277525.51      7100148.10      2277626.30      7100554.64
      2278439.51      7100728.07      2278700.34      7101231.21
      2279877.33      7101528.66      2280001.58      7101388.21
      2280144.08      7101475.48      2280870.74      7101413.48
      2281797.07      7101903.23      2282185.22      7101711.02
      2282435.45      7101782.64      2282811.94      7102493.91
      2283464.95      7102969.54      2284062.93      7103183.82
      2284407.22      7103538.81      2284851.50      7103532.22
      2285142.20      7103821.97      2285399.81      7103810.59
      2285630.13      7104193.20      2285923.29      7104138.11
      2286138.27      7104295.62      2286468.71      7104110.97
      2286668.62      7104399.03      2287029.00      7104460.00

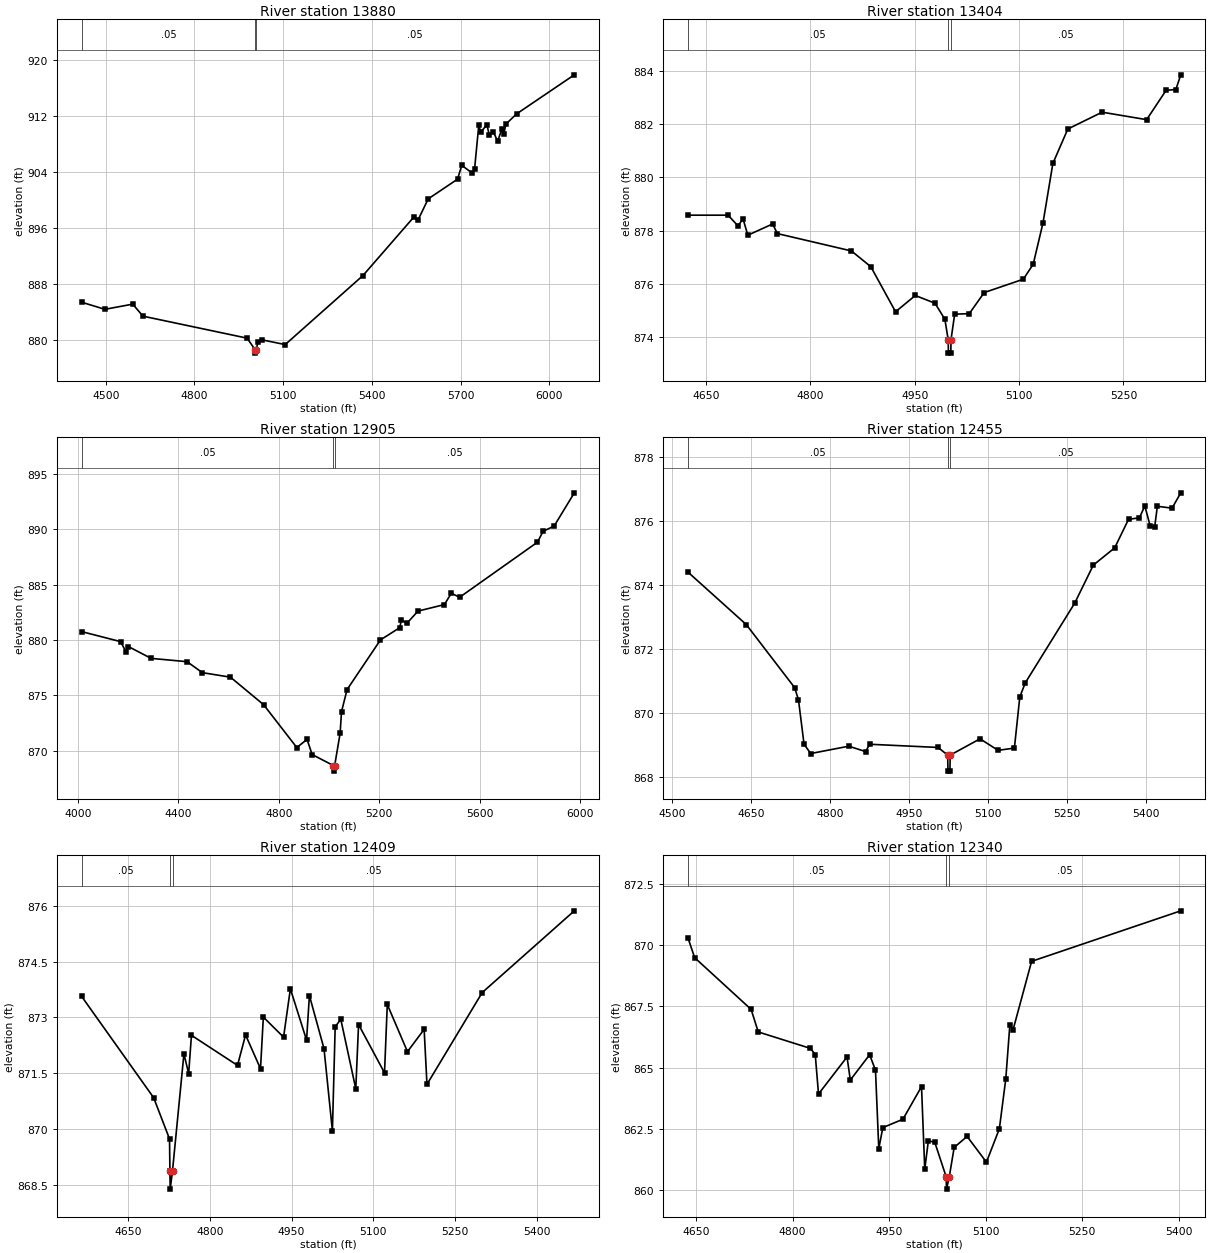
Type RM Length L Ch R = 1,13880,476,476,476
BEGIN DESCRIPTION:
Teeter Branch 22.0
END DESCRIPTION:
XS GIS Cut Line= 3
      2276806.09      7101379.36      2276512.16      7100877.38
      2275669.24      7100194.71
#Sta/Elev= 30
  4418.3  885.43  4497.2  884.41  4591.4  885.15  4626.1  883.43  4978.1  880.29
  5005.1  878.65  5005.4  878.15  5009.1  878.65  5015.1  879.80  5029.5  880.04
  5107.0  879.37  5370.0  889.24  5541.1  897.55  5555.4  897.11  5590.6  900.19
  5689.8  903.01  5704.1  904.99  5739.3  903.88  5747.3  904.41  5761.7  910.76
  5768.1  909.71  5789.0  910.80  5796.9  909.37  5811.2  909.73  5825.6  908.43
  5840.0  910.23  5846.4  909.50  5853.4  910.88  5889.6  912.34  6084.7  917.92
#Mann=3,-1,0
  4418.3    0.05       0  5005.1    0.04       0  5009.1    0.05       0
Bank Sta=5005.1,5009.1
Exp/Cntr=0.3,0.1

Type RM Length L Ch R = 1,13404,499,499,499
BEGIN DESCRIPTION:
Mapping XS f4cb0737
END DESCRIPTION:
XS GIS Cut Line= 2
      2276940.48      7100780.27      2276423.64      7100295.67
#Sta/Elev= 30
  4624.0  878.58  4681.6  878.58  4695.8  878.18  4703.1  878.44  4710.0  877.83
  4745.6  878.25  4752.5  877.89  4858.9  877.24  4886.8  876.65  4922.4  874.96
  4950.8  875.57  4979.1  875.28  4993.3  874.68  4998.1  873.91  4998.4  873.41
  5001.9  873.41  5002.1  873.91  5007.4  874.87  5028.4  874.89  5049.9  875.68
  5106.1  876.18  5120.3  876.74  5134.4  878.29  5148.6  880.52  5170.1  881.81
  5219.4  882.44  5283.4  882.16  5311.4  883.26  5325.4  883.29  5332.5  883.84
#Mann=3,-1,0
  4624.0    0.05       0  4998.1    0.04       0  5002.1    0.05       0
Bank Sta=4998.1,5002.1
Exp/Cntr=0.3,0.1

Type RM Length L Ch R = 1,12905,450,450,450
BEGIN DESCRIPTION:
Teeter Branch 21.0
END DESCRIPTION:
XS GIS Cut Line= 3
      2277193.66      7101213.34      2277015.80      7100223.15
      2276576.52      7099374.88
#Sta/Elev= 30
  4014.8  880.75  4170.6  879.84  4190.9  878.94  4201.1  879.40  4291.6  878.33
  4434.8  878.03  4495.7  877.04  4607.5  876.63  4739.6  874.14  4871.6  870.27
  4912.3  871.01  4932.6  869.64  5017.5  868.64  5018.0  868.14  5022.2  868.64
  5043.9  871.55  5049.5  873.51  5071.6  875.51  5204.6  880.00  5281.7  881.11
  5287.4  881.82  5309.5  881.49  5353.8  882.60  5458.8  883.19  5486.6  884.21
  5519.6  883.85  5829.5  888.83  5851.6  889.81  5895.9  890.29  5976.1  893.29
#Mann=3,-1,0
  4014.8    0.05       0  5017.5    0.04       0  5022.2    0.05       0
Bank Sta=5017.5,5022.2
Exp/Cntr=0.3,0.1

Type RM Length L Ch R = 1,12455,46,46,46
BEGIN DESCRIPTION:
Mapping XS 3d5e27cf
END DESCRIPTION:
XS GIS Cut Line= 4
      2277235.51      7100547.27      2277385.87      7100133.34
      2277417.64      7100021.37      2277322.31      7099653.92
#Sta/Elev= 30
  4529.7  874.39  4640.5  872.75  4732.3  870.78  4739.6  870.40  4750.2  869.01
  4762.9  868.72  4835.3  868.95  4867.3  868.78  4874.7  869.01  5004.9  868.91
  5023.1  868.67  5023.7  868.17  5027.4  868.17  5027.9  868.67  5084.6  869.18
  5118.9  868.82  5149.9  868.89  5160.2  870.49  5170.6  870.93  5264.5  873.42
  5299.9  874.61  5340.5  875.15  5366.8  876.04  5387.5  876.09  5397.8  876.46
  5408.2  875.82  5416.4  875.79  5421.6  876.45  5449.5  876.39  5466.1  876.87
#Mann=3,-1,0
  4529.7    0.05       0  5023.1   0.033       0  5027.9    0.05       0
Bank Sta=5023.1,5027.9
Exp/Cntr=0.3,0.1

Type RM Length L Ch R = 1,12409,69,69,69
BEGIN DESCRIPTION:
Mapping XS e90945fa
END DESCRIPTION:
XS GIS Cut Line= 5
      2277311.17      7100534.02      2277376.41      7100380.25
      2277452.71      7100058.20      2277472.62      7099951.73
      2277376.15      7099670.11
#Sta/Elev= 30
  4564.7  873.57  4697.0  870.84  4726.1  869.73  4726.8  868.88  4727.3  868.38
  4731.6  868.88  4752.5  872.02  4761.2  871.49  4766.3  872.52  4850.8  871.71
  4865.6  872.53  4893.0  871.62  4898.2  873.01  4935.3  872.47  4947.8  873.77
  4977.5  872.39  4982.7  873.59  5009.5  872.16  5024.9  869.95  5030.0  872.75
  5040.3  872.95  5067.8  871.08  5072.9  872.81  5120.5  871.51  5125.6  873.35
  5162.6  872.08  5193.2  872.68  5198.4  871.20  5299.7  873.67  5468.7  875.87
#Mann=3,-1,0
  4564.7    0.05       0  4726.8   0.033       0  4731.6    0.05       0
Bank Sta=4726.8,4731.6
Exp/Cntr=0.3,0.1

Type RM Length L Ch R = 1,12340,327,327,327
BEGIN DESCRIPTION:
Mapping XS 6e290c7c
END DESCRIPTION:
XS GIS Cut Line= 3
      2277431.98      7100495.82      2277501.19      7100173.74
      2277533.70      7099738.98
#Sta/Elev= 30
  4637.6  870.28  4647.9  869.48  4735.6  867.37  4746.7  866.45  4827.7  865.78
  4835.2  865.53  4840.3  863.92  4884.6  865.43  4889.7  864.49  4919.7  865.52
  4928.8  864.89  4933.9  861.69  4940.2  862.55  4971.4  862.89  5000.3  864.22
  5005.3  860.85  5010.9  862.01  5020.9  861.95  5038.6  860.54  5039.1  860.04
  5043.4  860.54  5051.0  861.74  5071.1  862.19  5101.1  861.14  5121.2  862.50
  5131.2  864.54  5137.5  866.74  5142.6  866.55  5171.3  869.33  5403.0  871.39
#Mann=3,-1,0
  4637.6    0.05       0  5038.6   0.033       0  5043.4    0.05       0
Bank Sta=5038.6,5043.4
Exp/Cntr=0.3,0.1

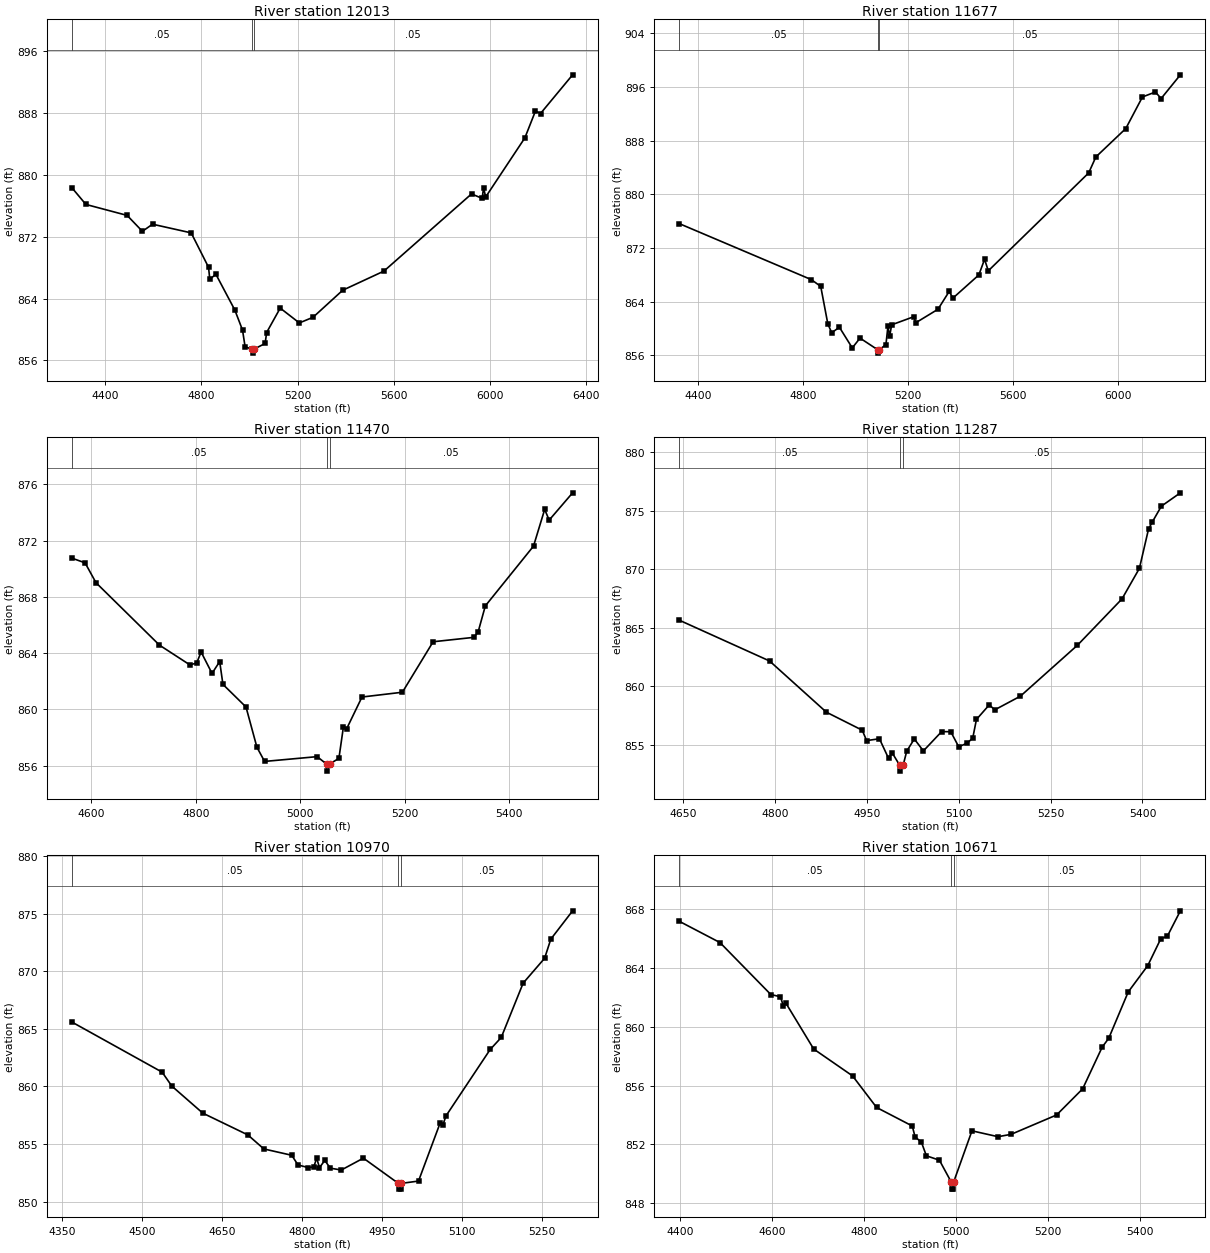
Type RM Length L Ch R = 1,12013,336,336,336
BEGIN DESCRIPTION:
Teeter Branch 20.0
END DESCRIPTION:
XS GIS Cut Line= 3
      2277305.64      7101135.22      2277562.00      7100443.39
      2278354.56      7099359.93
#Sta/Elev= 30
  4262.2  878.37  4321.1  876.18  4492.4  874.76  4555.7  872.70  4597.9  873.62
  4758.3  872.50  4830.4  868.05  4835.7  866.48  4860.8  867.15  4939.6  862.51
  4971.6  859.91  4982.3  857.75  5012.6  857.43  5013.4  856.93  5018.1  857.43
  5065.5  858.18  5071.7  859.60  5128.1  862.76  5207.6  860.84  5264.4  861.57
  5387.5  865.07  5558.9  867.55  5922.6  877.54  5966.6  876.97  5972.8  878.32
  5981.3  877.14  6144.2  884.80  6188.2  888.28  6209.1  887.95  6342.4  892.96
#Mann=3,-1,0
  4262.2    0.05       0  5012.6    0.04       0  5018.1    0.05       0
Bank Sta=5012.6,5018.1
Exp/Cntr=0.3,0.1

Type RM Length L Ch R = 1,11677,207,207,207
BEGIN DESCRIPTION:
Teeter Branch 19.0
END DESCRIPTION:
XS GIS Cut Line= 3
      2277428.01      7101130.03      2277812.43      7100593.11
      2278628.58      7099645.60
#Sta/Elev= 30
  4328.4  875.63  4831.7  867.29  4867.3  866.28  4894.4  860.69  4909.1  859.39
  4938.6  860.19  4987.6  857.12  5017.2  858.58  5084.7  856.84  5085.5  856.34
  5090.3  856.84  5116.0  857.61  5123.6  860.31  5130.2  858.87  5137.9  860.56
  5222.4  861.77  5230.1  860.87  5314.6  862.88  5357.4  865.54  5371.6  864.54
  5470.4  867.99  5492.3  870.32  5506.6  868.61  5889.5  883.20  5916.9  885.58
  6031.0  889.81  6094.6  894.52  6144.0  895.26  6165.9  894.29  6239.3  897.82
#Mann=3,-1,0
  4328.4    0.05       0  5084.7   0.033       0  5090.3    0.05       0
Bank Sta=5084.7,5090.3
Exp/Cntr=0.3,0.1

Type RM Length L Ch R = 1,11470,183,183,183
BEGIN DESCRIPTION:
Mapping XS e00707e2
END DESCRIPTION:
XS GIS Cut Line= 2
      2277767.59      7100953.80      2278327.02      7100174.14
#Sta/Elev= 30
  4562.4  870.76  4588.0  870.42  4608.9  869.01  4730.5  864.57  4788.6  863.17
  4801.7  863.29  4810.3  864.08  4831.2  862.56  4845.9  863.40  4852.1  861.78
  4896.3  860.17  4917.2  857.31  4931.9  856.30  5032.6  856.64  5050.7  856.11
  5051.5  855.61  5056.3  856.11  5074.3  856.52  5082.9  858.75  5089.1  858.62
  5118.5  860.88  5195.9  861.22  5254.8  864.81  5332.2  865.12  5340.8  865.48
  5354.8  867.36  5447.1  871.61  5468.5  874.22  5477.1  873.46  5522.0  875.40
#Mann=3,-1,0
  4562.4    0.05       0  5050.7   0.033       0  5056.3    0.05       0
Bank Sta=5050.7,5056.3
Exp/Cntr=0.3,0.1

Type RM Length L Ch R = 1,11287,317,317,317
BEGIN DESCRIPTION:
Mapping XS 46f2c34e
END DESCRIPTION:
XS GIS Cut Line= 2
      2277960.71      7101006.18      2278422.92      7100331.40
#Sta/Elev= 30
  4644.0  865.65  4791.1  862.17  4883.9  857.79  4942.4  856.25  4949.6  855.36
  4970.5  855.52  4985.4  853.84  4991.5  854.30  5003.6  853.25  5004.4  852.75
  5009.2  853.25  5015.1  854.46  5027.4  855.50  5042.3  854.48  5072.1  856.13
  5087.0  856.12  5100.0  854.83  5114.0  855.15  5122.9  855.58  5128.9  857.17
  5149.9  858.42  5158.8  857.99  5200.7  859.16  5293.9  863.52  5366.6  867.48
  5395.0  870.09  5409.9  873.45  5416.0  874.05  5430.9  875.41  5461.9  876.55
#Mann=3,-1,0
  4644.0    0.05       0  5003.6   0.033       0  5009.2    0.05       0
Bank Sta=5003.6,5009.2
Exp/Cntr=0.3,0.1

Type RM Length L Ch R = 1,10970,299,299,299
BEGIN DESCRIPTION:
Mapping XS 778869a6
END DESCRIPTION:
XS GIS Cut Line= 3
      2278035.11      7101130.38      2278369.38      7100987.66
      2278516.43      7100430.50
#Sta/Elev= 30
  4367.8  865.60  4537.4  861.24  4555.6  860.03  4613.7  857.68  4698.2  855.79
  4728.3  854.57  4780.6  854.02  4792.3  853.18  4811.6  852.95  4821.9  853.01
  4827.4  853.77  4832.6  852.95  4842.6  853.57  4853.0  852.90  4873.6  852.74
  4915.0  853.77  4980.6  851.58  4981.4  851.08  4985.3  851.08  4986.2  851.58
  5018.4  851.78  5058.7  856.79  5063.9  856.63  5070.1  857.45  5152.9  863.21
  5173.6  864.25  5214.7  868.97  5255.0  871.13  5266.6  872.79  5307.5  875.25
#Mann=3,-1,0
  4367.8    0.05       0  4980.6    0.04       0  4986.2    0.05       0
Bank Sta=4980.6,4986.2
Exp/Cntr=0.3,0.1

Type RM Length L Ch R = 1,10671,458,458,458
BEGIN DESCRIPTION:
Teeter Branch 17.0
END DESCRIPTION:
XS GIS Cut Line= 3
      2277978.95      7101210.01      2278479.00      7101060.00
      2278879.04      7100659.96
#Sta/Elev= 30
  4399.0  867.18  4486.9  865.74  4597.4  862.20  4618.3  862.05  4624.4  861.44
  4629.6  861.64  4690.5  858.49  4774.9  856.66  4827.1  854.51  4904.5  853.25
  4910.6  852.52  4924.6  852.13  4935.2  851.22  4963.5  850.92  4988.9  849.45
  4989.8  848.95  4993.7  848.95  4994.6  849.45  5034.2  852.92  5090.8  852.52
  5119.1  852.68  5218.0  854.00  5274.6  855.78  5317.0  858.62  5331.2  859.22
  5373.6  862.38  5416.0  864.17  5444.3  866.00  5458.5  866.17  5486.8  867.90
#Mann=3,-1,0
  4399.0    0.05       0  4988.9    0.04       0  4994.6    0.05       0
Bank Sta=4988.9,4994.6
Exp/Cntr=0.3,0.1

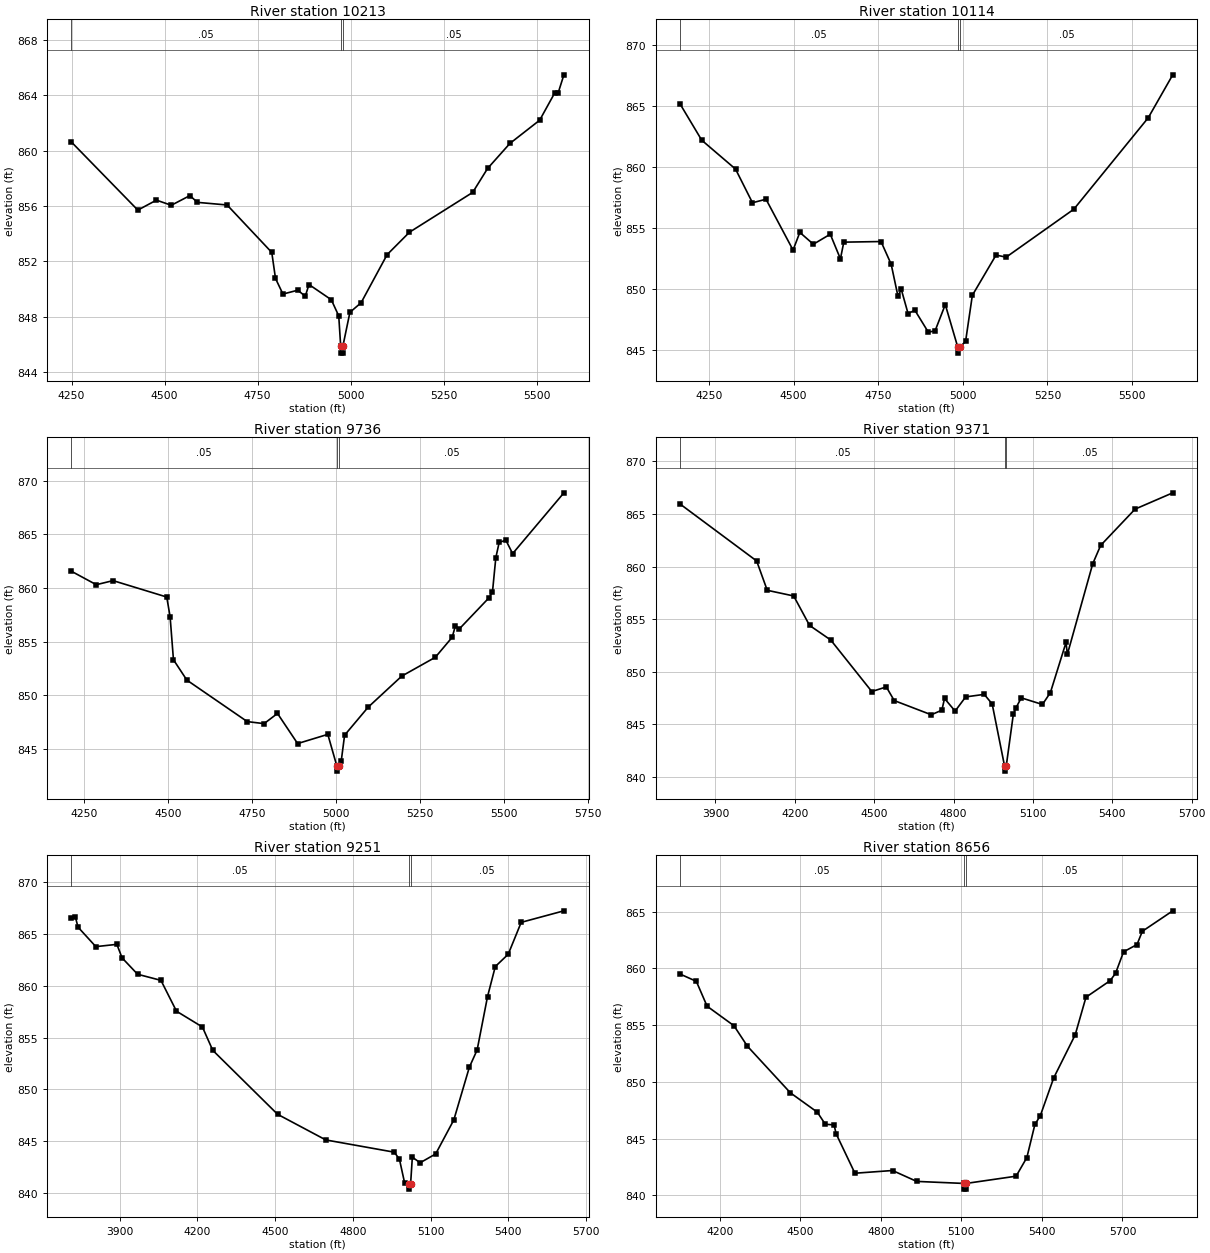
Type RM Length L Ch R = 1,10213,99,99,99
BEGIN DESCRIPTION:
Teeter Branch 16.0
END DESCRIPTION:
XS GIS Cut Line= 3
      2278839.93      7102028.77      2278846.01      7101298.62
      2278852.52      7100704.94
#Sta/Elev= 30
  4249.2  860.63  4428.0  855.70  4478.0  856.42  4518.0  856.05  4568.0  856.75
  4588.0  856.26  4668.0  856.07  4788.0  852.64  4798.0  850.76  4818.0  849.63
  4858.0  849.91  4878.0  849.47  4888.0  850.32  4948.0  849.22  4968.0  848.05
  4973.2  845.86  4974.2  845.36  4978.2  845.36  4979.1  845.86  4998.0  848.31
  5028.0  849.00  5098.0  852.48  5158.0  854.10  5328.0  856.98  5368.0  858.71
  5428.0  860.52  5508.0  862.20  5548.0  864.15  5558.0  864.20  5573.1  865.48
#Mann=3,-1,0
  4249.2    0.05       0  4973.2   0.033       0  4979.1    0.05       0
Bank Sta=4973.2,4979.1
Exp/Cntr=0.3,0.1

Type RM Length L Ch R = 1,10114,378,378,378
BEGIN DESCRIPTION:
Teeter Branch 15.0
END DESCRIPTION:
XS GIS Cut Line= 3
      2278937.59      7102143.76      2278940.32      7101313.86
      2278935.42      7100687.58
#Sta/Elev= 30
  4164.4  865.18  4228.2  862.22  4328.2  859.85  4378.2  857.09  4418.2  857.38
  4498.2  853.21  4518.2  854.66  4558.2  853.69  4608.2  854.51  4638.2  852.49
  4648.2  853.86  4758.2  853.91  4788.2  852.05  4808.2  849.44  4818.2  849.98
  4838.2  848.00  4858.2  848.28  4898.2  846.47  4918.2  846.60  4948.2  848.74
  4985.0  845.26  4986.0  844.76  4991.4  845.26  5008.2  845.72  5028.2  849.50
  5098.2  852.80  5128.2  852.63  5328.2  856.56  5548.2  864.06  5620.6  867.58
#Mann=3,-1,0
  4164.4    0.05       0  4985.0    0.04       0  4991.4    0.05       0
Bank Sta=4985,4991.4
Exp/Cntr=0.3,0.1

Type RM Length L Ch R = 1,9736,365,365,365
BEGIN DESCRIPTION:
Teeter Branch 14.5
END DESCRIPTION:
XS GIS Cut Line= 3
      2279299.57      7102174.50      2279310.18      7101375.12
      2279269.19      7100707.53
#Sta/Elev= 30
  4211.1  861.57  4285.6  860.31  4335.6  860.69  4495.6  859.16  4505.6  857.33
  4515.6  853.31  4555.6  851.41  4735.6  847.54  4785.7  847.35  4825.7  848.30
  4885.7  845.49  4975.7  846.35  5002.4  843.42  5003.5  842.92  5008.8  843.42
  5015.7  843.86  5025.7  846.27  5095.8  848.88  5196.0  851.78  5296.2  853.54
  5346.3  855.40  5356.3  856.50  5366.3  856.14  5456.5  859.10  5466.5  859.63
  5476.5  862.83  5486.6  864.27  5506.6  864.45  5526.6  863.21  5679.4  868.88
#Mann=3,-1,0
  4211.1    0.05       0  5002.4    0.04       0  5008.8    0.05       0
Bank Sta=5002.4,5008.8
Exp/Cntr=0.3,0.1

Type RM Length L Ch R = 1,9371,120,120,120
BEGIN DESCRIPTION:
Mapping XS 37c0a54a
END DESCRIPTION:
XS GIS Cut Line= 2
      2279703.64      7102679.04      2279653.18      7100817.63
#Sta/Elev= 30
  3766.4  865.94  4055.6  860.53  4095.6  857.74  4195.6  857.20  4255.6  854.40
  4335.7  853.01  4490.9  848.11  4545.7  848.55  4575.7  847.25  4715.8  845.90
  4755.8  846.34  4765.8  847.45  4805.8  846.25  4845.8  847.60  4915.9  847.84
  4945.9  846.93  4992.6  841.04  4993.7  840.54  4999.2  841.04  5025.9  845.95
  5035.9  846.56  5055.9  847.51  5135.9  846.88  5166.0  848.01  5225.1  852.78
  5230.1  851.64  5326.0  860.26  5356.0  862.01  5486.1  865.46  5628.5  867.01
#Mann=3,-1,0
  3766.4    0.05       0  4992.6   0.033       0  4999.2    0.05       0
Bank Sta=4992.6,4999.2
Exp/Cntr=0.3,0.1

Type RM Length L Ch R = 1,9251,595,595,595
BEGIN DESCRIPTION:
Mapping XS f46a3b4e
END DESCRIPTION:
XS GIS Cut Line= 2
      2279816.23      7102755.88      2279773.24      7100855.27
#Sta/Elev= 30
  3713.2  866.52  3729.1  866.60  3739.1  865.64  3807.9  863.76  3889.1  863.98
  3909.1  862.68  3969.1  861.10  4059.2  860.51  4119.2  857.54  4219.2  856.02
  4259.2  853.77  4509.3  847.61  4695.3  845.14  4959.4  843.96  4979.4  843.30
  4999.4  841.02  5016.1  840.90  5017.2  840.40  5022.7  840.90  5029.4  843.48
  5059.4  842.94  5119.4  843.79  5189.5  847.07  5249.5  852.15  5279.5  853.81
  5319.5  858.94  5349.5  861.84  5399.5  863.03  5449.5  866.10  5614.3  867.21
#Mann=3,-1,0
  3713.2    0.05       0  5016.1   0.033       0  5022.7    0.05       0
Bank Sta=5016.1,5022.7
Exp/Cntr=0.3,0.1

Type RM Length L Ch R = 1,8656,737,737,737
BEGIN DESCRIPTION:
Teeter Branch 12.0
END DESCRIPTION:
XS GIS Cut Line= 3
      2280204.95      7102420.22      2280247.81      7101578.79
      2280207.55      7100586.93
#Sta/Elev= 30
  4052.2  859.50  4112.5  858.86  4152.6  856.67  4252.7  854.95  4302.7  853.15
  4463.0  849.04  4563.1  847.34  4593.1  846.27  4625.7  846.22  4633.2  845.44
  4703.3  841.96  4843.4  842.20  4933.5  841.24  5110.4  841.06  5111.4  840.56
  5115.9  840.56  5117.0  841.06  5303.8  841.70  5343.9  843.34  5373.9  846.26
  5393.9  847.02  5444.0  850.36  5524.0  854.15  5564.1  857.46  5654.1  858.92
  5674.2  859.56  5704.2  861.46  5754.2  862.10  5774.2  863.27  5887.4  865.07
#Mann=3,-1,0
  4052.2    0.05       0  5110.4   0.033       0  5117.0    0.05       0
Bank Sta=5110.4,5117
Exp/Cntr=0.3,0.1

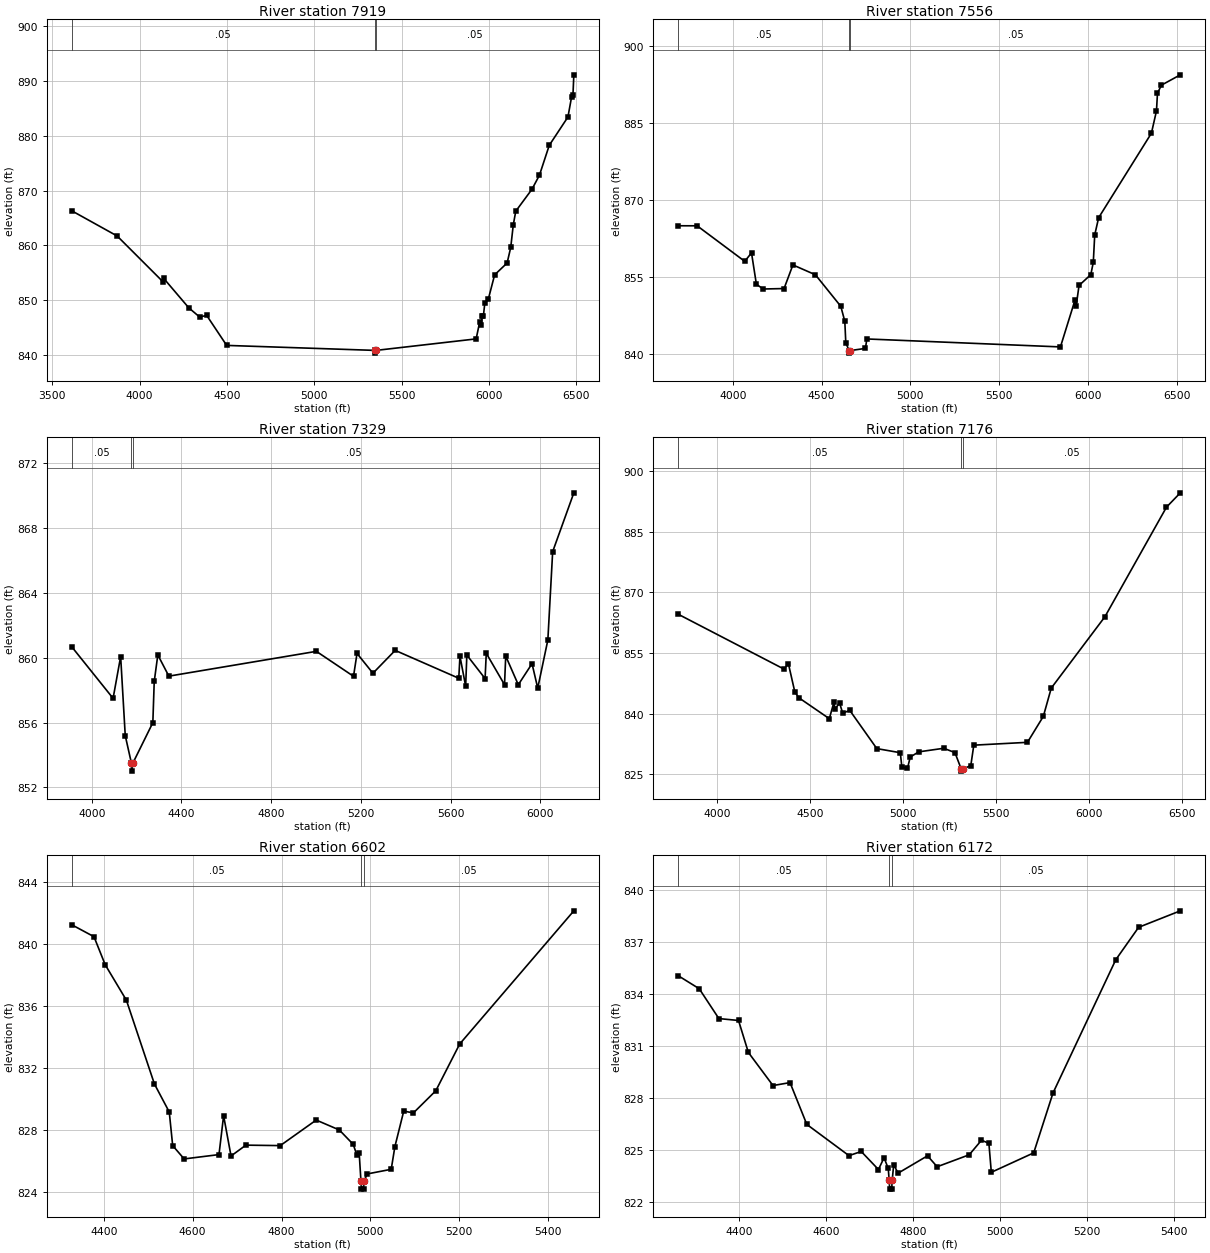
Type RM Length L Ch R = 1,7919,363,363,363
BEGIN DESCRIPTION:
Teeter Branch 11.6
END DESCRIPTION:
XS GIS Cut Line= 3
      2280426.53      7102702.93      2280613.46      7101894.44
      2281904.83      7100308.13
#Sta/Elev= 30
  3611.2  866.33  3871.1  861.73  4132.6  853.40  4137.7  853.99  4281.4  848.61
  4342.9  846.95  4384.0  847.22  4498.3  841.75  5346.9  840.84  5348.0  840.34
  5353.7  840.84  5927.0  842.94  5947.8  846.10  5955.4  845.46  5962.2  847.11
  5968.6  847.15  5976.5  849.46  5997.4  850.28  6032.8  854.63  6104.4  856.80
  6125.2  859.67  6139.5  863.73  6153.9  866.26  6246.6  870.26  6289.7  872.85
  6345.7  878.29  6452.7  883.46  6473.5  887.12  6481.4  887.50  6486.5  891.16
#Mann=3,-1,0
  3611.2    0.05       0  5346.9   0.033       0  5353.7    0.05       0
Bank Sta=5346.9,5353.7
Exp/Cntr=0.3,0.1

Type RM Length L Ch R = 1,7556,227,227,227
BEGIN DESCRIPTION:
Teeter Branch 11.4
END DESCRIPTION:
XS GIS Cut Line= 3
      2280784.19      7102820.90      2280948.93      7102280.03
      2281996.00      7100275.76
#Sta/Elev= 30
  3693.0  865.07  3799.5  865.06  4067.5  858.14  4105.5  859.79  4133.0  853.68
  4171.2  852.75  4288.8  852.84  4338.6  857.44  4465.4  855.52  4608.2  849.38
  4630.8  846.46  4636.4  842.26  4655.1  840.76  4656.2  840.26  4661.9  840.76
  4746.9  841.18  4754.9  843.02  5844.8  841.47  5927.4  850.66  5933.1  849.38
  5949.5  853.44  6015.8  855.55  6029.8  857.95  6037.8  863.28  6059.9  866.64
  6357.0  883.10  6385.5  887.45  6391.1  890.89  6413.4  892.46  6519.7  894.47
#Mann=3,-1,0
  3693.0    0.05       0  4655.1   0.033       0  4661.9    0.05       0
Bank Sta=4655.1,4661.9
Exp/Cntr=0.3,0.1

Type RM Length L Ch R = 1,7329,153,153,153
BEGIN DESCRIPTION:
Teeter Branch 11.2
END DESCRIPTION:
XS GIS Cut Line= 6
      2281108.91      7102664.72      2281136.45      7102491.74
      2281093.64      7102301.33      2281388.19      7101982.88
      2281416.86      7101935.66      2281887.82      7100640.98
#Sta/Elev= 30
  3911.0  860.67  4095.2  857.49  4128.9  860.07  4149.4  855.19  4176.8  853.50
  4177.8  853.00  4183.6  853.50  4272.4  855.99  4278.6  858.53  4294.6  860.17
  4343.8  858.86  5001.4  860.39  5167.0  858.85  5182.6  860.26  5253.6  859.04
  5352.7  860.45  5636.2  858.73  5641.5  860.09  5666.9  858.24  5672.2  860.16
  5753.5  858.71  5758.8  860.27  5840.2  858.33  5845.5  860.10  5901.5  858.33
  5962.8  859.63  5988.2  858.12  6033.3  861.09  6054.8  866.54  6149.2  870.17
#Mann=3,-1,0
  3911.0    0.05       0  4176.8   0.033       0  4183.6    0.05       0
Bank Sta=4176.8,4183.6
Exp/Cntr=0.3,0.1

Type RM Length L Ch R = 1,7176,574,574,574
BEGIN DESCRIPTION:
Teeter Branch 11.0
END DESCRIPTION:
XS GIS Cut Line= 3
      2281166.13      7102900.78      2281442.30      7102296.60
      2282162.65      7100390.38
#Sta/Elev= 30
  3791.2  864.61  4360.8  851.02  4383.9  852.41  4418.8  845.33  4440.9  843.91
  4604.3  838.75  4629.2  842.84  4634.5  841.10  4659.3  842.66  4676.4  840.11
  4714.3  840.81  4859.9  831.34  4986.4  830.32  4994.8  826.73  5024.9  826.44
  5039.8  829.25  5085.3  830.53  5220.2  831.42  5280.5  830.34  5314.3  826.26
  5315.4  825.76  5321.2  826.26  5365.7  827.12  5381.9  832.19  5670.6  832.89
  5756.1  839.32  5798.8  846.33  6087.5  863.99  6418.9  891.13  6493.3  894.68
#Mann=3,-1,0
  3791.2    0.05       0  5314.3   0.033       0  5321.2    0.05       0
Bank Sta=5314.3,5321.2
Exp/Cntr=0.3,0.1

Type RM Length L Ch R = 1,6602,430,430,430
BEGIN DESCRIPTION:
Mapping XS d0cc0d1f
END DESCRIPTION:
XS GIS Cut Line= 2
      2281933.10      7102377.94      2282250.22      7101293.46
#Sta/Elev= 30
  4327.9  841.23  4377.9  840.46  4403.1  838.65  4450.8  836.36  4513.9  830.95
  4547.3  829.14  4555.0  826.97  4580.8  826.11  4659.2  826.39  4669.6  828.90
  4686.3  826.30  4719.8  827.00  4797.1  826.97  4878.0  828.62  4930.0  827.98
  4961.3  827.05  4969.5  826.36  4974.7  826.50  4978.7  824.66  4979.8  824.16
  4984.5  824.16  4985.6  824.66  4992.6  825.14  5046.8  825.44  5055.1  826.91
  5075.0  829.20  5096.7  829.08  5147.1  830.51  5200.9  833.53  5457.8  842.13
#Mann=3,-1,0
  4327.9    0.05       0  4978.7   0.033       0  4985.6    0.05       0
Bank Sta=4978.7,4985.6
Exp/Cntr=0.3,0.1

Type RM Length L Ch R = 1,6172,442,442,442
BEGIN DESCRIPTION:
Mapping XS 2727c730
END DESCRIPTION:
XS GIS Cut Line= 2
      2282181.93      7102526.32      2282684.60      7101486.33
#Sta/Elev= 30
  4259.2  835.07  4307.5  834.32  4352.7  832.60  4397.9  832.49  4420.5  830.65
  4477.2  828.74  4516.4  828.91  4555.0  826.50  4652.0  824.70  4680.2  824.94
  4719.8  823.90  4732.7  824.58  4742.4  823.96  4744.5  823.27  4745.6  822.77
  4750.3  822.77  4751.4  823.27  4754.9  824.18  4765.0  823.69  4832.7  824.69
  4854.9  824.06  4928.7  824.75  4956.9  825.59  4973.9  825.41  4979.5  823.74
  5077.0  824.86  5121.4  828.31  5265.8  835.99  5318.4  837.86  5414.3  838.81
#Mann=3,-1,0
  4259.2    0.05       0  4744.5   0.033       0  4751.4    0.05       0
Bank Sta=4744.5,4751.4
Exp/Cntr=0.3,0.1

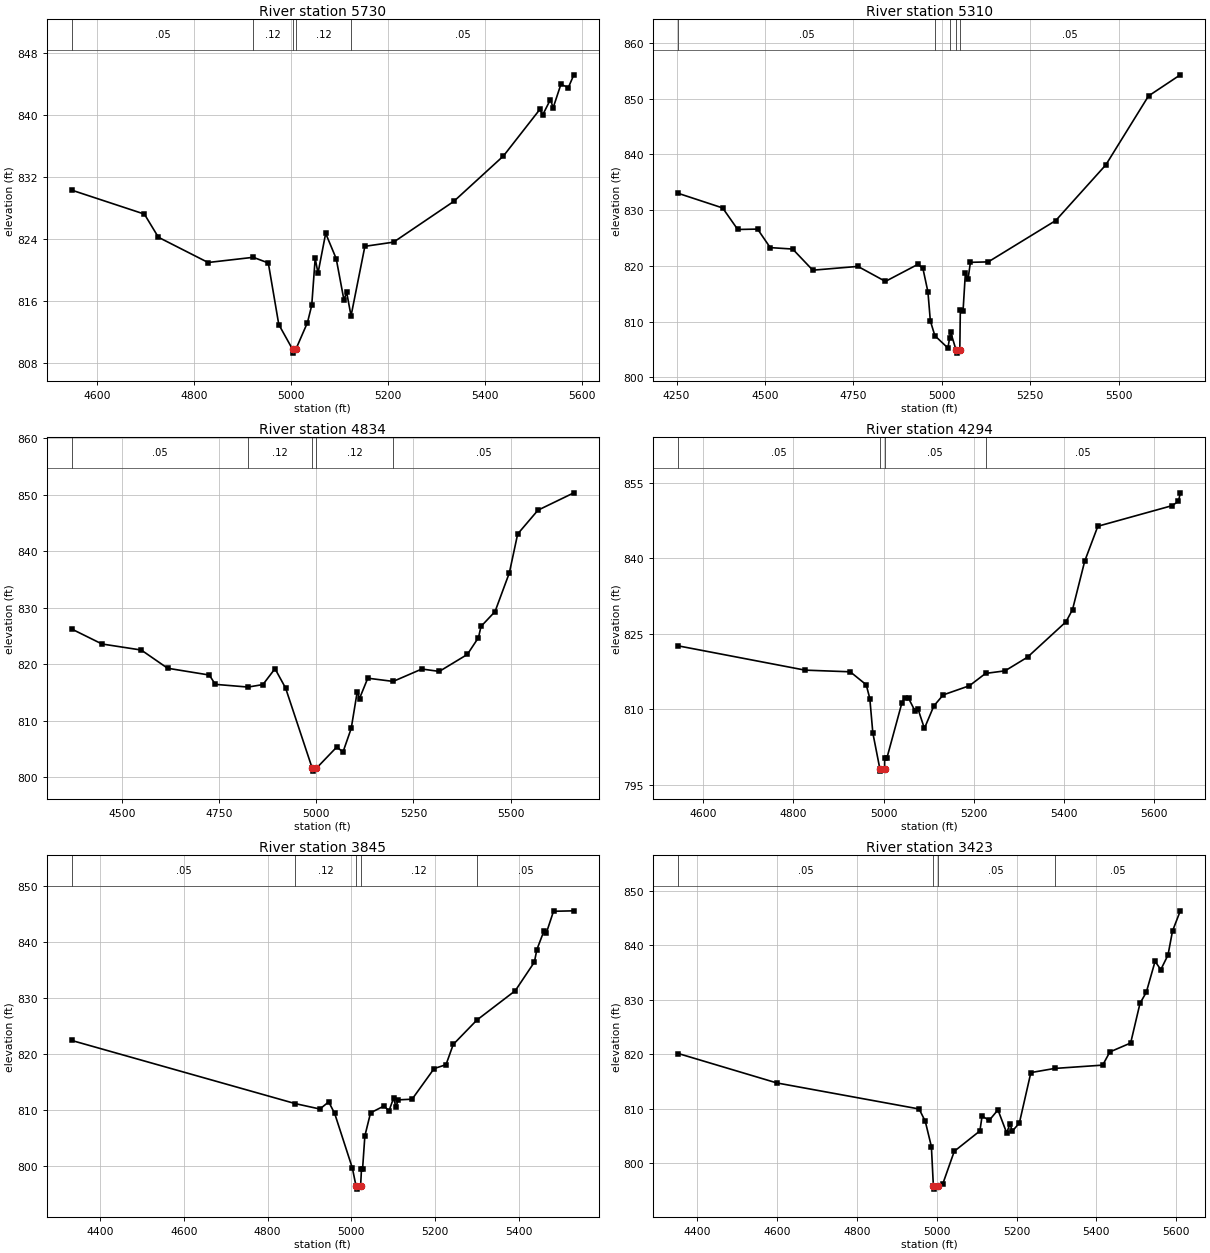
Type RM Length L Ch R = 1,5730,420,420,420
BEGIN DESCRIPTION:
Mapping XS b9f22738
END DESCRIPTION:
XS GIS Cut Line= 2
      2282328.91      7102463.19      2283228.80      7101952.71
#Sta/Elev= 30
  4548.2  830.27  4697.8  827.18  4726.7  824.19  4829.1  820.93  4922.2  821.60
  4953.2  820.87  4974.8  812.92  5003.1  809.73  5004.2  809.23  5010.0  809.73
  5033.9  813.18  5042.7  815.41  5049.8  821.47  5055.6  819.55  5071.4  824.69
  5093.1  821.43  5109.0  816.11  5114.7  817.06  5123.7  814.04  5152.2  823.02
  5211.4  823.56  5335.4  828.82  5437.8  834.69  5512.8  840.70  5518.6  839.99
  5534.5  841.96  5540.2  840.91  5556.1  843.93  5571.5  843.52  5582.8  845.16
#Mann=5,-1,0
  4548.2    0.05       0  4922.2    0.12       0  5003.1    0.07       0
  5010.0    0.12       0  5123.7    0.05       0
Bank Sta=5003.1,5010
Exp/Cntr=0.3,0.1

Type RM Length L Ch R = 1,5310,476,476,476
BEGIN DESCRIPTION:
Teeter Branch 10.0
END DESCRIPTION:
XS GIS Cut Line= 3
      2282383.16      7103011.46      2282934.17      7102509.60
      2283373.99      7101998.49
#Sta/Elev= 30
  4254.7  833.01  4380.3  830.39  4422.9  826.53  4479.0  826.60  4514.8  823.28
  4578.3  823.02  4635.1  819.23  4762.8  819.91  4840.5  817.22  4932.4  820.28
  4946.5  819.55  4960.7  815.34  4967.5  810.15  4980.3  807.48  5017.2  805.28
  5021.8  807.02  5024.8  808.15  5040.5  804.86  5042.0  804.36  5050.8  804.86
  5052.3  812.05  5060.0  811.93  5066.6  818.73  5074.2  817.68  5080.8  820.64
  5131.3  820.72  5322.2  828.14  5463.7  838.11  5584.4  850.47  5674.3  854.26
#Mann=5,-1,0
  4254.7    0.05       0  4980.3    0.12       0  5021.8    0.05       0
  5040.5    0.07       0  5050.8    0.05       0
Bank Sta=5040.5,5050.8
Exp/Cntr=0.3,0.1

Type RM Length L Ch R = 1,4834,540,540,540
BEGIN DESCRIPTION:
Teeter Branch 9.0
END DESCRIPTION:
XS GIS Cut Line= 3
      2282963.86      7103321.39      2283292.65      7102773.26
      2283631.82      7102215.93
#Sta/Elev= 30
  4371.2  826.20  4448.9  823.56  4550.0  822.49  4617.7  819.27  4724.9  818.07
  4740.5  816.42  4824.7  815.94  4862.9  816.38  4894.0  819.19  4921.3  815.76
  4989.8  801.57  4991.3  801.07  5000.4  801.57  5053.3  805.36  5068.8  804.42
  5090.1  808.63  5105.6  815.14  5111.4  813.91  5132.7  817.51  5198.0  816.94
  5271.7  819.13  5316.7  818.71  5388.8  821.71  5417.5  824.70  5423.9  826.66
  5460.1  829.30  5496.9  836.15  5518.3  843.02  5570.5  847.23  5662.8  850.30
#Mann=5,-1,0
  4371.2    0.05       0  4824.7    0.12       0  4989.8    0.07       0
  5000.4    0.12       0  5198.0    0.05       0
Bank Sta=4989.8,5000.4
Exp/Cntr=0.3,0.1

Type RM Length L Ch R = 1,4294,449,449,449
BEGIN DESCRIPTION:
Teeter Branch 8.0
END DESCRIPTION:
XS GIS Cut Line= 3
      2283448.24      7103422.94      2283720.49      7103051.70
      2284115.10      7102529.87
#Sta/Elev= 30
  4544.3  822.60  4825.8  817.78  4926.1  817.45  4961.6  814.88  4969.6  812.13
  4976.3  805.31  4991.8  798.22  4993.3  797.72  5002.4  798.22  5002.6  800.35
  5007.6  800.35  5040.9  811.30  5047.2  812.30  5055.5  812.21  5069.5  809.75
  5076.3  810.14  5090.8  806.20  5111.7  810.66  5132.5  812.86  5190.7  814.68
  5226.6  817.13  5269.8  817.64  5319.7  820.36  5405.1  827.38  5419.6  829.80
  5446.7  839.44  5475.8  846.36  5640.2  850.44  5654.8  851.30  5658.9  853.00
#Mann=4,-1,0
  4544.3    0.05       0  4991.8    0.07       0  5002.4    0.05       0
  5226.6    0.05       0
Bank Sta=4991.8,5002.4
Exp/Cntr=0.3,0.1

Type RM Length L Ch R = 1,3845,422,422,422
BEGIN DESCRIPTION:
Teeter Branch 7.0
END DESCRIPTION:
XS GIS Cut Line= 3
      2283646.17      7103705.48      2284129.32      7103209.67
      2284344.05      7102749.82
#Sta/Elev= 30
  4332.2  822.42  4866.4  811.18  4925.1  810.22  4946.2  811.49  4960.4  809.44
  5002.8  799.69  5011.6  796.46  5013.0  795.96  5022.4  796.46  5024.5  799.53
  5027.1  799.53  5032.6  805.43  5046.2  809.54  5078.3  810.76  5090.3  809.88
  5101.2  812.18  5106.7  810.60  5112.4  811.85  5145.5  811.97  5198.1  817.42
  5226.5  818.11  5243.8  821.72  5300.2  826.05  5392.0  831.28  5437.7  836.37
  5443.5  838.57  5460.5  841.90  5466.0  841.50  5483.4  845.42  5532.0  845.50
#Mann=5,-1,0
  4332.2    0.05       0  4866.4    0.12       0  5011.6    0.07       0
  5022.4    0.12       0  5300.2    0.05       0
Bank Sta=5011.6,5022.4
Exp/Cntr=0.3,0.1

Type RM Length L Ch R = 1,3423,470,470,470
BEGIN DESCRIPTION:
Teeter Branch 6.0
END DESCRIPTION:
XS GIS Cut Line= 3
      2284056.32      7104079.18      2284398.80      7103530.49
      2284644.41      7102972.13
#Sta/Elev= 30
  4353.2  820.13  4600.0  814.73  4956.2  809.95  4971.6  807.68  4986.9  803.05
  4991.9  795.74  4993.4  795.24  5002.8  795.74  5014.9  796.09  5044.2  802.19
  5108.3  805.92  5113.8  808.66  5131.6  807.85  5153.5  809.79  5175.3  805.56
  5183.8  807.23  5189.2  805.86  5207.1  807.37  5235.9  816.63  5295.4  817.39
  5415.7  818.00  5433.6  820.42  5485.7  822.06  5509.1  829.34  5524.9  831.38
  5546.8  837.04  5561.2  835.53  5579.1  838.19  5590.5  842.62  5610.0  846.32
#Mann=4,-1,0
  4353.2    0.05       0  4991.9   0.033       0  5002.8    0.05       0
  5295.4    0.05       0
Bank Sta=4991.9,5002.8
Exp/Cntr=0.3,0.1