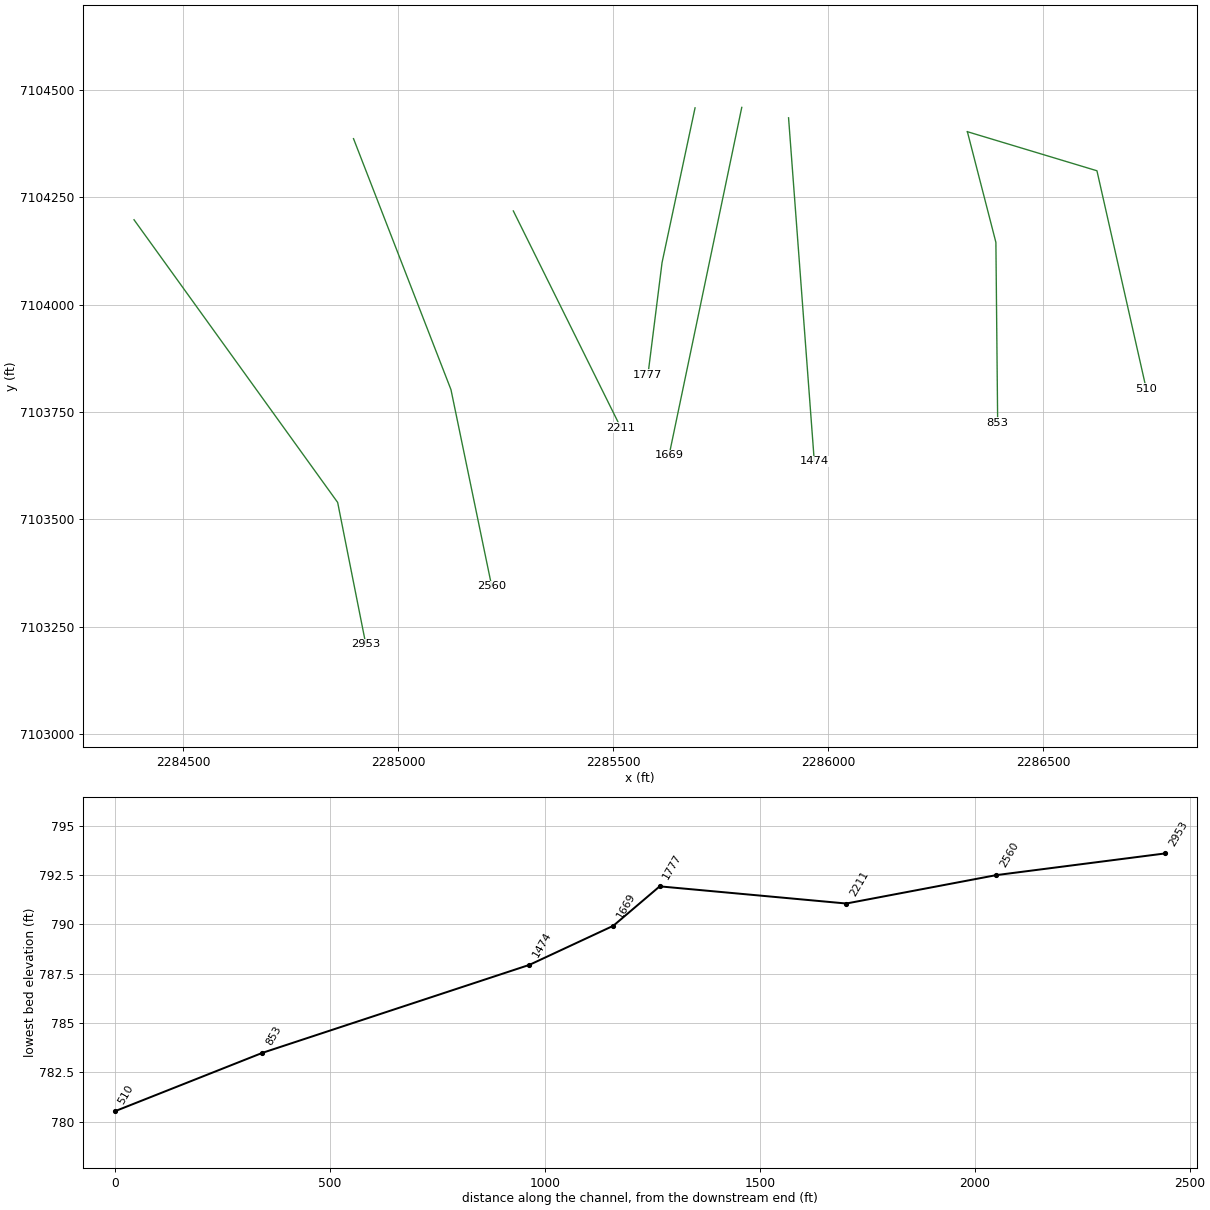
HEC-RAS study Teeter Branch.prj: Teeter Branch Base Level Engineering

--- Teeter Branch.g01 (geometry) --- (continued)

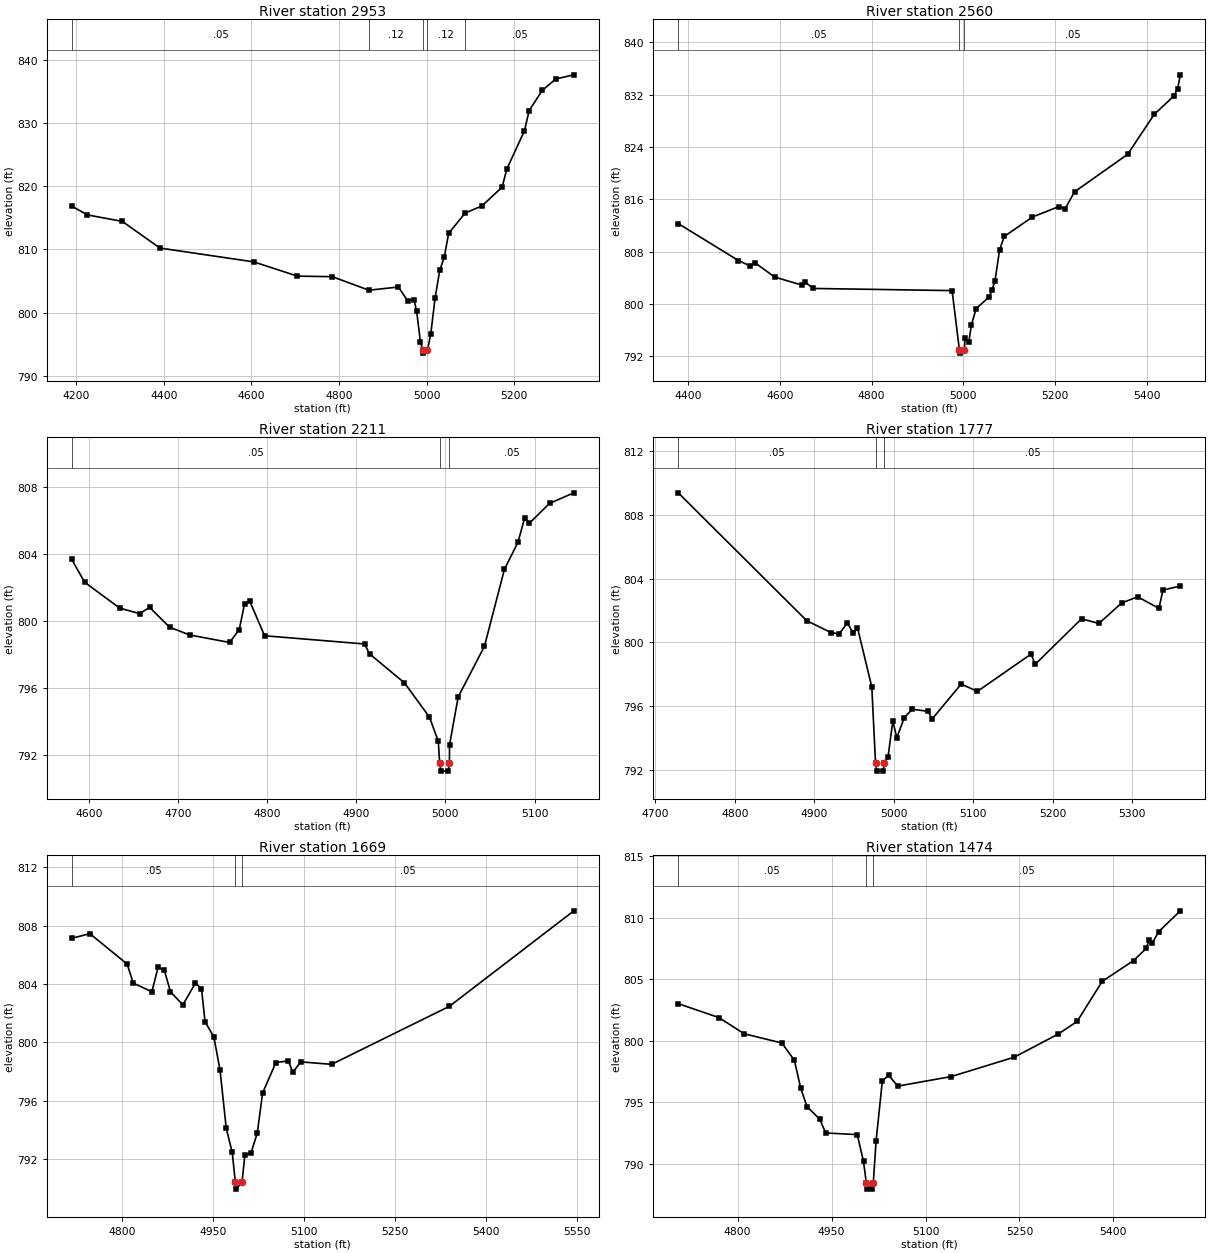
Type RM Length L Ch R = 1,2953,393,393,393
BEGIN DESCRIPTION:
Teeter Branch 5.0
END DESCRIPTION:
XS GIS Cut Line= 3
      2284385.75      7104197.66      2284859.30      7103539.64
      2284924.81      7103209.37
#Sta/Elev= 30
  4189.3  816.85  4225.0  815.46  4304.8  814.44  4390.7  810.22  4605.3  808.03
  4705.0  805.78  4784.7  805.69  4868.6  803.55  4935.7  804.06  4956.6  801.91
  4971.3  802.04  4977.4  800.26  4986.0  795.43  4991.2  794.10  4992.7  793.60
  5002.2  794.10  5009.8  796.66  5019.5  802.27  5030.2  806.69  5040.4  808.73
  5050.6  812.55  5088.3  815.75  5127.0  816.90  5172.9  819.87  5183.3  822.68
  5223.9  828.78  5234.5  831.97  5264.7  835.17  5295.3  836.96  5336.7  837.62
#Mann=5,-1,0
  4189.3    0.05       0  4868.6    0.12       0  4991.2    0.07       0
  5002.2    0.12       0  5088.3    0.05       0
Bank Sta=4991.2,5002.2
Exp/Cntr=0.3,0.1

Type RM Length L Ch R = 1,2560,349,349,349
BEGIN DESCRIPTION:
Teeter Branch 4.0
END DESCRIPTION:
XS GIS Cut Line= 3
      2284896.17      7104386.46      2285122.81      7103802.19
      2285217.61      7103344.29
#Sta/Elev= 30
  4378.4  812.29  4509.7  806.64  4534.2  805.85  4546.2  806.27  4588.7  804.12
  4648.5  802.88  4653.9  803.37  4673.1  802.38  4975.3  802.05  4991.2  793.00
  4992.7  792.50  5002.2  793.00  5003.6  794.76  5011.7  794.18  5017.5  796.85
  5027.7  799.31  5056.8  801.13  5061.9  802.13  5068.6  803.48  5078.8  808.26
  5089.0  810.32  5150.3  813.29  5207.4  814.87  5221.8  814.57  5242.2  817.14
  5357.9  822.87  5415.8  828.97  5458.3  831.75  5466.9  832.88  5472.7  835.01
#Mann=3,-1,0
  4378.4    0.05       0  4991.2   0.033       0  5002.2    0.05       0
Bank Sta=4991.2,5002.2
Exp/Cntr=0.3,0.1

Type RM Length L Ch R = 1,2211,434,434,434
BEGIN DESCRIPTION:
Mapping XS f426254e
END DESCRIPTION:
XS GIS Cut Line= 2
      2285267.78      7104218.24      2285517.76      7103713.78
#Sta/Elev= 30
  4581.0  803.68  4595.4  802.32  4634.7  800.78  4657.1  800.45  4668.3  800.82
  4690.7  799.64  4713.1  799.18  4757.9  798.73  4768.8  799.49  4774.8  801.05
  4780.3  801.23  4797.2  799.13  4909.3  798.64  4914.9  798.05  4954.1  796.32
  4982.1  794.28  4992.0  792.84  4993.5  791.56  4995.0  791.06  5003.0  791.06
  5004.5  791.56  5004.6  792.62  5014.3  795.48  5043.8  798.51  5066.2  803.10
  5081.3  804.70  5088.7  806.12  5094.2  805.84  5116.7  807.02  5144.0  807.65
#Mann=3,-1,0
  4581.0    0.05       0  4993.5   0.033       0  5004.5    0.05       0
Bank Sta=4993.5,5004.5
Exp/Cntr=0.3,0.1

Type RM Length L Ch R = 1,1777,108,108,108
BEGIN DESCRIPTION:
Mapping XS 76a5491b
END DESCRIPTION:
XS GIS Cut Line= 3
      2285690.42      7104458.17      2285613.69      7104098.11
      2285580.85      7103836.71
#Sta/Elev= 30
  4728.9  809.38  4890.6  801.36  4921.3  800.61  4931.5  800.54  4941.7  801.23
  4949.2  800.56  4954.4  800.92  4972.4  797.21  4977.1  792.43  4978.6  791.93
  4986.6  791.93  4988.2  792.43  4992.9  792.84  4998.8  795.07  5003.9  794.02
  5013.3  795.29  5023.5  795.81  5043.2  795.68  5048.3  795.20  5084.9  797.39
  5105.2  796.93  5172.8  799.27  5177.8  798.62  5236.2  801.48  5258.2  801.19
  5286.6  802.47  5306.8  802.86  5333.6  802.14  5338.7  803.28  5360.5  803.54
#Mann=3,-1,0
  4728.9    0.05       0  4977.1    0.04       0  4988.2    0.05       0
Bank Sta=4977.1,4988.2
Exp/Cntr=0.3,0.1

Type RM Length L Ch R = 1,1669,195,195,195
BEGIN DESCRIPTION:
Mapping XS b130c3b7
END DESCRIPTION:
XS GIS Cut Line= 2
      2285799.02      7104459.26      2285629.94      7103649.22
#Sta/Elev= 30
  4717.0  807.14  4746.9  807.45  4808.2  805.37  4818.4  804.06  4849.0  803.47
  4859.3  805.15  4869.5  804.96  4879.7  803.46  4900.1  802.57  4920.6  804.05
  4930.8  803.69  4936.6  801.42  4951.2  800.37  4961.4  798.08  4971.6  794.10
  4981.5  792.45  4986.5  790.43  4988.1  789.93  4997.6  790.43  5002.3  792.26
  5012.5  792.42  5022.7  793.77  5031.5  796.52  5053.4  798.61  5073.8  798.73
  5081.5  797.94  5094.2  798.66  5145.3  798.49  5339.4  802.47  5544.5  809.02
#Mann=3,-1,0
  4717.0    0.05       0  4986.5    0.04       0  4997.6    0.05       0
Bank Sta=4986.5,4997.6
Exp/Cntr=0.3,0.1

Type RM Length L Ch R = 1,1474,621,621,621
BEGIN DESCRIPTION:
Mapping XS 6e655f25
END DESCRIPTION:
XS GIS Cut Line= 2
      2285907.86      7104434.99      2285967.69      7103635.63
#Sta/Elev= 30
  4705.2  803.02  4770.4  801.88  4810.5  800.57  4870.7  799.82  4890.7  798.41
  4900.7  796.16  4910.8  794.65  4930.8  793.65  4940.8  792.51  4991.0  792.38
  5001.0  790.20  5005.5  788.45  5007.0  787.95  5015.1  787.95  5016.6  788.45
  5021.1  791.89  5031.1  796.75  5041.1  797.19  5055.8  796.32  5141.4  797.10
  5241.7  798.67  5311.9  800.55  5342.0  801.57  5382.1  804.83  5432.2  806.52
  5452.3  807.50  5457.3  808.23  5462.3  807.96  5472.3  808.87  5506.8  810.56
#Mann=3,-1,0
  4705.2    0.05       0  5005.5   0.033       0  5016.6    0.05       0
Bank Sta=5005.5,5016.6
Exp/Cntr=0.3,0.1

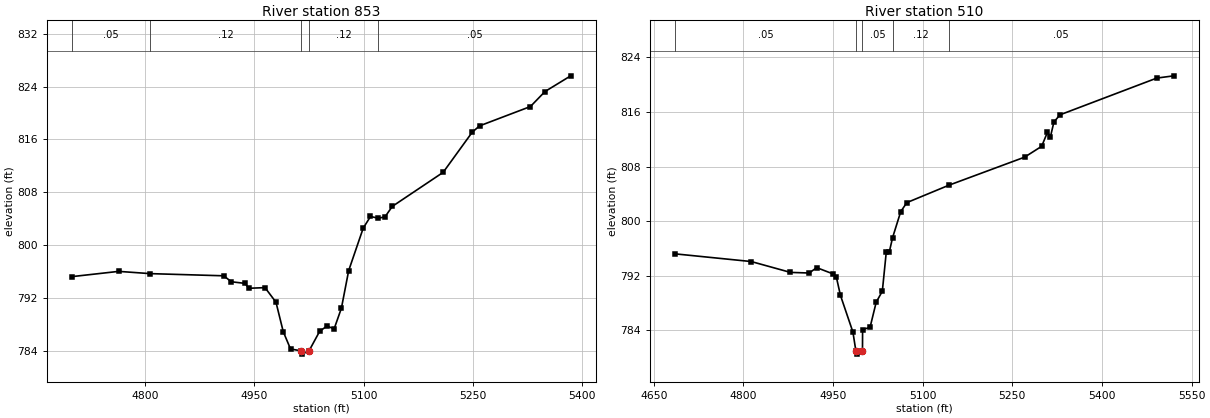
Type RM Length L Ch R = 1,853,343,343,343
BEGIN DESCRIPTION:
Mapping XS 6dcade1a
END DESCRIPTION:
XS GIS Cut Line= 3
      2286323.71      7104402.66      2286390.00      7104145.07
      2286394.16      7103724.58
#Sta/Elev= 30
  4698.5  795.22  4763.2  796.02  4806.4  795.68  4907.8  795.35  4918.1  794.45
  4937.0  794.20  4942.2  793.46  4964.5  793.56  4979.6  791.35  4989.6  786.89
  4999.6  784.27  5014.0  783.99  5015.5  783.49  5025.1  783.99  5039.6  786.93
  5049.6  787.74  5059.6  787.32  5069.6  790.45  5079.6  796.14  5099.6  802.57
  5109.6  804.33  5120.5  804.07  5129.6  804.28  5139.6  805.86  5209.6  811.02
  5249.6  817.10  5259.6  818.05  5329.6  820.98  5349.6  823.25  5385.0  825.63
#Mann=5,-1,0
  4698.5    0.05       0  4806.4    0.12       0  5014.0    0.07       0
  5025.1    0.12       0  5120.5    0.05       0
Bank Sta=5014,5025.1
Exp/Cntr=0.3,0.1

Type RM Length L Ch R = 1,510,0,0,0
BEGIN DESCRIPTION:
Teeter Branch 1.0
END DESCRIPTION:
XS GIS Cut Line= 3
      2286323.73      7104402.64      2286625.01      7104311.71
      2286739.64      7103804.20
#Sta/Elev= 30
  4685.3  795.22  4813.2  794.09  4878.8  792.50  4910.2  792.41  4922.6  793.20
  4950.4  792.27  4955.6  791.81  4962.4  789.15  4983.3  783.76  4988.2  781.03
  4989.7  780.53  4999.3  781.03  4999.5  784.12  5012.0  784.46  5022.3  788.15
  5032.5  789.74  5039.2  795.55  5044.3  795.55  5049.7  797.60  5063.3  801.40
  5073.5  802.72  5143.6  805.26  5270.6  809.38  5299.1  810.97  5308.7  813.01
  5313.8  812.38  5319.6  814.53  5329.8  815.58  5491.7  820.96  5520.3  821.29
#Mann=5,-1,0
  4685.3    0.05       0  4988.2   0.033       0  4999.3    0.05       0
  5049.7    0.12       0  5143.6    0.05       0
Bank Sta=4988.2,4999.3
Exp/Cntr=0.3,0.1

Chan Stop Cuts=-1