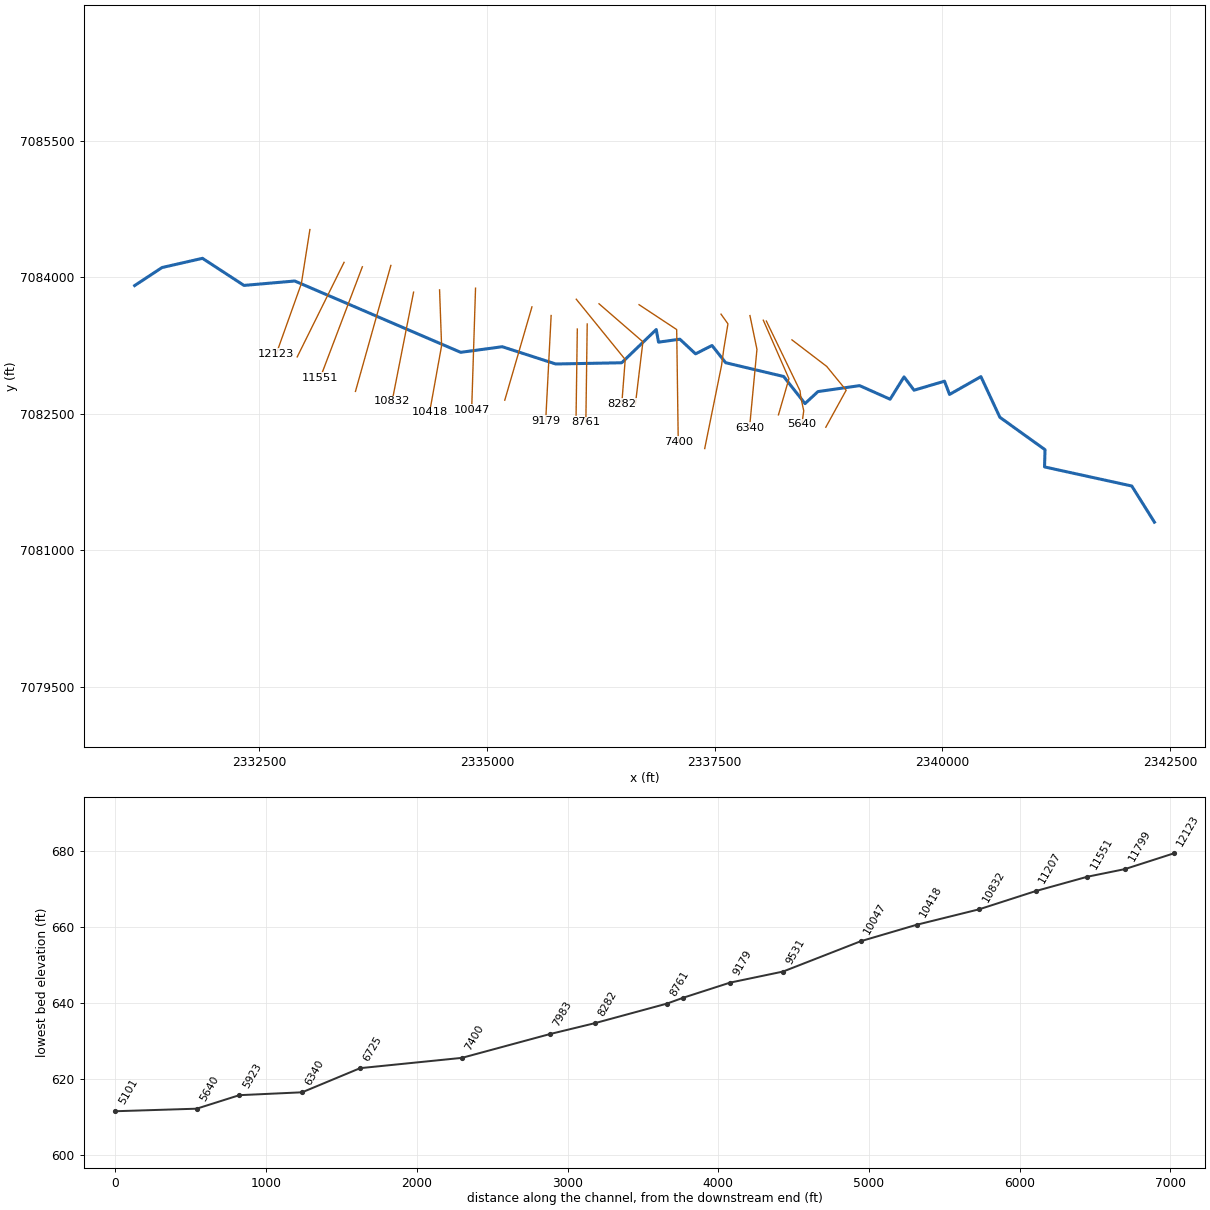
--- Trail Cr Trib 2.prj (project) ---

Proj Title=Trail Cr Trib 2 Base Level Engineering
Current Plan=p01
Default Exp/Contr=0.3,0.1
English Units
Geom File=g01
Flow File=f01
Plan File=p01
BEGIN DESCRIPTION:
Trail Cr Trib 2
END DESCRIPTION:

--- Trail Cr Trib 2.p01 (plan) ---

Plan Title=Multiple Run
Short Identifier=Multiple
Geom File=g01
Flow File=f01
Subcritical Flow
K Sum by GR= 0
Std Step Tol= 0.01
Critical Tol= 0.01
Num of Std Step Trials= 20
Max Error Tol= 0.3
Flow Tol Ratio= 0.001
Split Flow NTrial= 30
Split Flow Tol= 0.02
Split Flow Ratio= 0.02
Log Output Level= 0
Friction Slope Method= 1
Unsteady Friction Slope Method= 2
Unsteady Bridges Friction Slope Method= 1
Parabolic Critical Depth
Global Vel Dist=  1 , 1 , 1
Global Log Level= 0
CheckData=True
Encroach Param= -1, 0, 0, 0
BEGIN DESCRIPTION:
Multiple Run
END DESCRIPTION:

--- Trail Cr Trib 2.f01 (steady flow) ---

Flow Title=Multiple
Number of Profiles=7
Profile Names=10-year,25-year,50-year,1pct_min,100-year,1pct_plu,500-year
River Rch & RM= Trail Cr Trib 2,Reach-1,12123
     336     446     533     318     634    1265     897
River Rch & RM= Trail Cr Trib 2,Reach-1,10047
     438     591     715     430     859    1713    1240
River Rch & RM= Trail Cr Trib 2,Reach-1,6725
     571     782     956     581    1158    2311    1705
Boundary for River Rch & Prof#=Trail Cr Trib 2,Reach-1,1
Up Type=0
Dn Type=3
Dn Slope=0.005
Boundary for River Rch & Prof#=Trail Cr Trib 2,Reach-1,2
Up Type=0
Dn Type=3
Dn Slope=0.005
Boundary for River Rch & Prof#=Trail Cr Trib 2,Reach-1,3
Up Type=0
Dn Type=3
Dn Slope=0.005
Boundary for River Rch & Prof#=Trail Cr Trib 2,Reach-1,4
Up Type=0
Dn Type=3
Dn Slope=0.005
Boundary for River Rch & Prof#=Trail Cr Trib 2,Reach-1,5
Up Type=0
Dn Type=3
Dn Slope=0.005
Boundary for River Rch & Prof#=Trail Cr Trib 2,Reach-1,6
Up Type=0
Dn Type=3
Dn Slope=0.005
Boundary for River Rch & Prof#=Trail Cr Trib 2,Reach-1,7
Up Type=0
Dn Type=3
Dn Slope=0.005

--- Trail Cr Trib 2.g01 (geometry) ---

Geom Title=Existing Conditions

River Reach=Trail Cr Trib 2,Reach-1
Reach XY= 30
      2331129.00      7083910.00      2331429.73      7084108.23
      2331873.78      7084209.47      2332329.73      7083911.77
      2332887.28      7083960.09      2334709.69      7083176.33
      2335166.70      7083237.87      2335753.65      7083048.18
      2336478.26      7083061.73      2336857.46      7083427.01
      2336882.46      7083288.23      2337117.50      7083320.28
      2337289.03      7083159.89      2337470.38      7083251.36
      2337619.76      7083062.11      2338256.91      7082910.88
      2338491.39      7082613.04      2338633.29      7082744.82
      2339091.48      7082810.25      2339426.08      7082661.03
      2339578.99      7082906.47      2339688.99      7082759.98
      2340023.26      7082859.26      2340078.99      7082713.53
      2340423.26      7082909.26      2340631.52      7082462.54
      2341127.53      7082106.01      2341122.08      7081916.91
      2342080.28      7081707.20      2342329.00      7081310.00

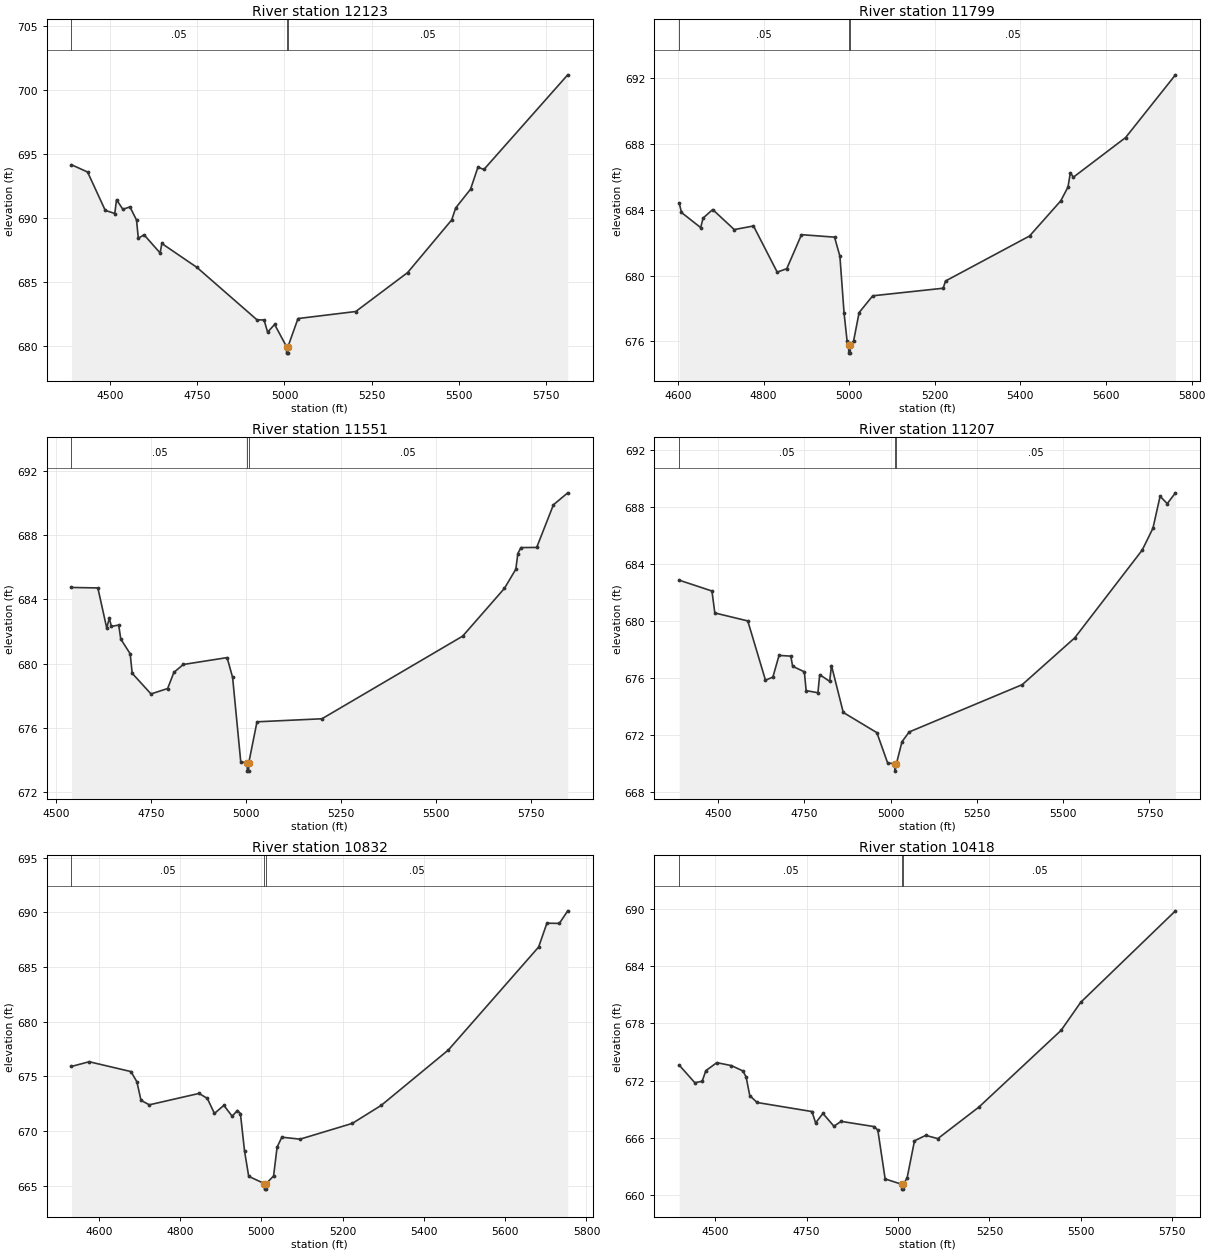
Type RM Length L Ch R = 1,12123,324,324,324
BEGIN DESCRIPTION:
Trail Cr Trib 2 40.0
END DESCRIPTION:
XS GIS Cut Line= 3
      2333053.67      7084525.62      2332960.07      7083932.26
      2332683.56      7083157.52
#Sta/Elev= 30
  4389.2  694.13  4435.4  693.56  4486.0  690.57  4513.4  690.32  4518.4  691.40
  4536.6  690.65  4556.9  690.84  4575.8  689.81  4580.9  688.39  4597.4  688.66
  4643.4  687.24  4648.4  687.98  4749.2  686.11  4921.3  682.02  4941.6  682.01
  4951.7  681.06  4971.9  681.66  5006.1  679.92  5006.3  679.42  5009.8  679.42
  5010.1  679.92  5038.9  682.12  5204.6  682.67  5353.3  685.71  5479.7  689.82
  5491.3  690.76  5533.8  692.22  5555.0  693.94  5572.1  693.76  5812.5  701.15
#Mann=3,-1,0
  4389.2    0.05       0  5006.1   0.033       0  5010.1    0.05       0
Bank Sta=5006.1,5010.1
Exp/Cntr=0.3,0.1

Type RM Length L Ch R = 1,11799,248,248,248
BEGIN DESCRIPTION:
Mapping XS c1334908
END DESCRIPTION:
XS GIS Cut Line= 2
      2333428.64      7084165.12      2332914.47      7083126.30
#Sta/Elev= 30
  4603.1  684.42  4608.4  683.84  4653.3  682.92  4658.8  683.50  4681.3  684.02
  4731.7  682.80  4776.6  683.02  4832.0  680.21  4854.3  680.42  4888.7  682.49
  4965.9  682.34  4978.4  681.18  4988.2  677.71  4995.3  676.00  4998.9  675.78
  4999.1  675.28  5002.6  675.28  5002.9  675.78  5010.5  676.03  5023.3  677.75
  5055.1  678.77  5219.6  679.23  5225.1  679.67  5421.4  682.41  5494.3  684.55
  5511.2  685.39  5516.7  686.26  5523.8  685.99  5645.7  688.40  5762.2  692.22
#Mann=3,-1,0
  4603.1    0.05       0  4998.9   0.033       0  5002.9    0.05       0
Bank Sta=4998.9,5002.9
Exp/Cntr=0.3,0.1

Type RM Length L Ch R = 1,11551,344,344,344
BEGIN DESCRIPTION:
Mapping XS 48be6f91
END DESCRIPTION:
XS GIS Cut Line= 2
      2333629.83      7084116.83      2333166.51      7082894.71
#Sta/Elev= 30
  4540.2  684.75  4609.7  684.72  4633.1  682.21  4639.8  682.84  4645.2  682.32
  4664.6  682.40  4670.0  681.53  4694.8  680.61  4700.1  679.39  4749.7  678.10
  4793.5  678.44  4810.0  679.45  4834.8  679.94  4950.1  680.37  4964.6  679.13
  4986.0  673.87  5003.0  673.78  5003.3  673.28  5006.8  673.28  5007.0  673.78
  5028.8  676.36  5199.9  676.55  5570.5  681.71  5680.4  684.69  5710.5  685.89
  5715.9  686.87  5723.9  687.24  5765.5  687.25  5809.5  689.91  5847.2  690.66
#Mann=3,-1,0
  4540.2    0.05       0  5003.0    0.04       0  5007.0    0.05       0
Bank Sta=5003,5007
Exp/Cntr=0.3,0.1

Type RM Length L Ch R = 1,11207,375,375,375
BEGIN DESCRIPTION:
Mapping XS bce4f110
END DESCRIPTION:
XS GIS Cut Line= 2
      2333942.79      7084131.24      2333554.17      7082747.16
#Sta/Elev= 30
  4387.6  682.89  4482.4  682.13  4490.8  680.59  4586.2  680.03  4637.5  675.87
  4658.9  676.09  4676.8  677.61  4710.9  677.56  4716.1  676.85  4750.1  676.46
  4755.3  675.14  4789.4  674.99  4794.6  676.26  4823.5  675.79  4828.7  676.90
  4862.8  673.61  4960.2  672.19  4991.3  670.07  5012.6  669.99  5012.9  669.49
  5016.6  669.99  5032.9  671.55  5053.9  672.24  5381.4  675.56  5533.3  678.84
  5728.8  685.00  5759.9  686.53  5780.7  688.78  5801.5  688.26  5825.2  689.02
#Mann=3,-1,0
  4387.6    0.05       0  5012.6   0.033       0  5016.6    0.05       0
Bank Sta=5012.6,5016.6
Exp/Cntr=0.3,0.1

Type RM Length L Ch R = 1,10832,414,414,414
BEGIN DESCRIPTION:
Mapping XS e6f6e538
END DESCRIPTION:
XS GIS Cut Line= 2
      2334192.36      7083837.91      2333956.69      7082639.77
#Sta/Elev= 30
  4532.8  675.91  4576.3  676.34  4679.1  675.44  4693.7  674.51  4703.9  672.81
  4724.3  672.40  4846.6  673.44  4867.0  672.99  4884.6  671.61  4907.8  672.35
  4928.1  671.36  4941.1  671.88  4948.5  671.60  4958.7  668.16  4968.9  665.86
  5007.7  665.19  5007.9  664.69  5011.4  664.69  5011.7  665.19  5030.1  665.89
  5038.8  668.53  5050.4  669.44  5095.3  669.26  5223.7  670.70  5295.0  672.35
  5460.1  677.41  5682.3  686.83  5702.7  689.01  5733.3  688.99  5753.9  690.14
#Mann=3,-1,0
  4532.8    0.05       0  5007.7    0.04       0  5011.7    0.05       0
Bank Sta=5007.7,5011.7
Exp/Cntr=0.3,0.1

Type RM Length L Ch R = 1,10418,371,371,371
BEGIN DESCRIPTION:
Mapping XS effdd46f
END DESCRIPTION:
XS GIS Cut Line= 3
      2334477.84      7083862.76      2334500.02      7083249.07
      2334368.49      7082518.00
#Sta/Elev= 30
  4401.7  673.63  4444.5  671.78  4464.5  671.94  4474.5  673.05  4504.5  673.89
  4544.6  673.58  4575.9  673.02  4584.6  672.39  4594.6  670.44  4614.6  669.71
  4764.7  668.76  4774.7  667.57  4794.7  668.56  4824.7  667.22  4844.4  667.73
  4934.8  667.18  4944.8  666.81  4964.8  661.69  5010.8  661.12  5011.1  660.62
  5014.6  660.62  5014.8  661.12  5025.0  661.82  5045.0  665.69  5075.8  666.26
  5108.8  665.92  5221.2  669.23  5445.9  677.28  5499.5  680.22  5758.6  689.82
#Mann=3,-1,0
  4401.7    0.05       0  5010.8   0.033       0  5014.8    0.05       0
Bank Sta=5010.8,5014.8
Exp/Cntr=0.3,0.1

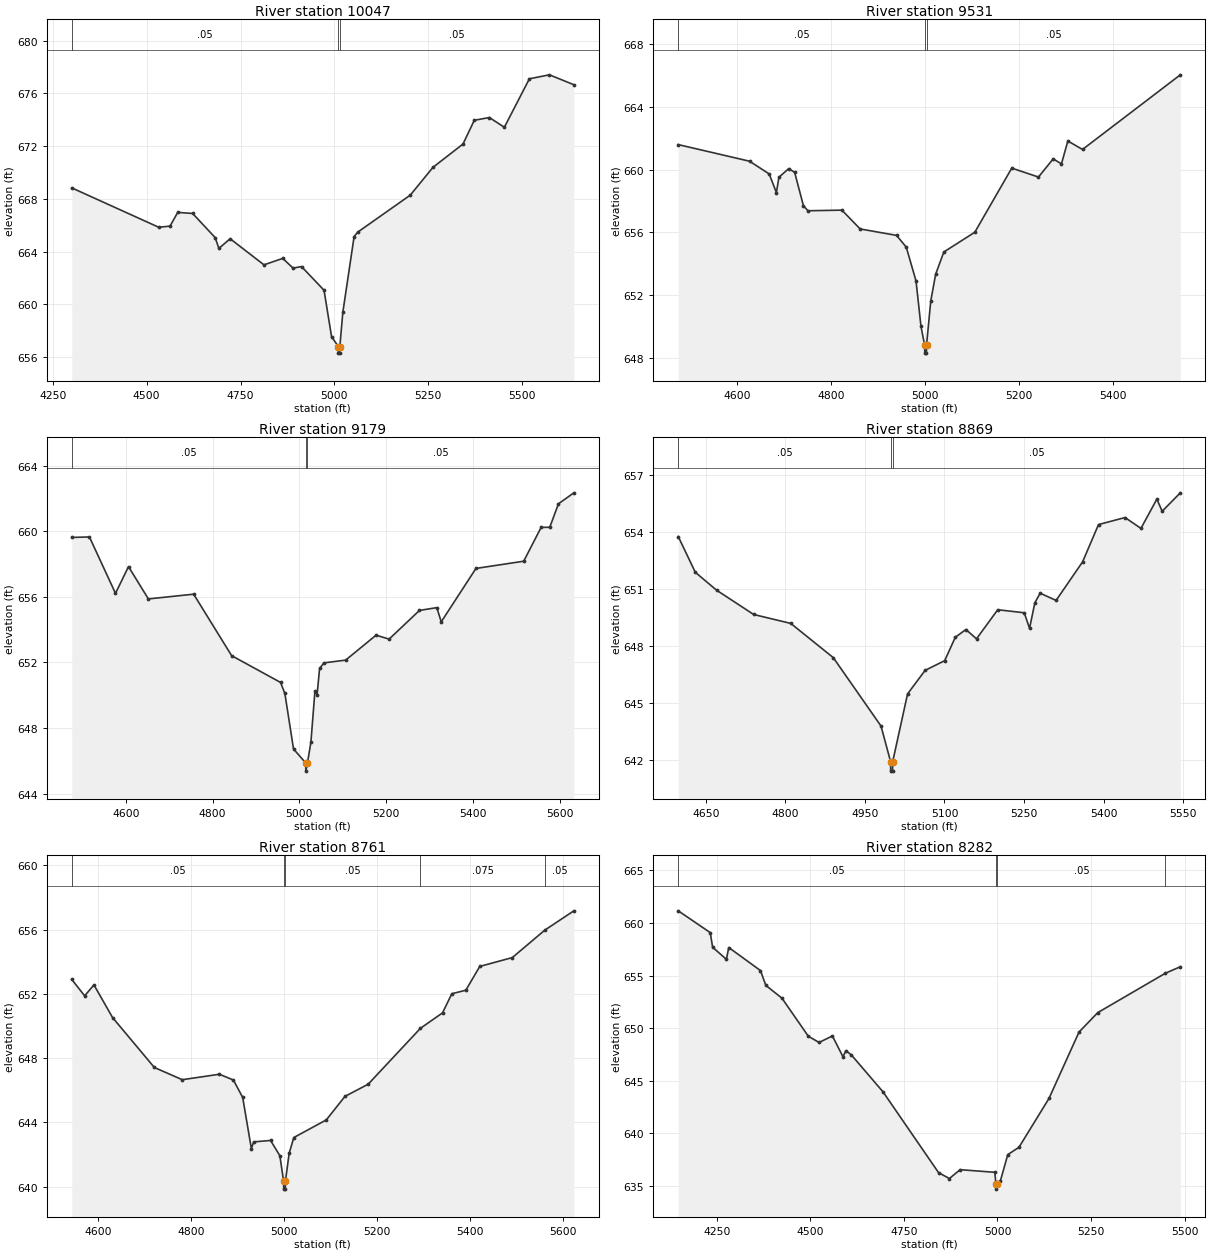
Type RM Length L Ch R = 1,10047,516,516,516
BEGIN DESCRIPTION:
Mapping XS e2dccf9e
END DESCRIPTION:
XS GIS Cut Line= 2
      2334872.83      7083881.71      2334830.29      7082544.98
#Sta/Elev= 30
  4300.5  668.83  4532.3  665.84  4562.3  665.93  4582.7  666.97  4622.4  666.89
  4682.4  665.06  4692.4  664.24  4722.4  664.97  4812.5  662.99  4862.5  663.48
  4890.0  662.74  4912.5  662.86  4972.5  661.06  4992.6  657.53  5010.6  656.79
  5010.8  656.29  5014.3  656.29  5014.6  656.79  5022.6  659.40  5052.6  665.14
  5062.6  665.48  5202.2  668.28  5262.7  670.39  5342.7  672.16  5372.7  673.96
  5412.8  674.17  5452.8  673.43  5519.5  677.11  5572.8  677.41  5637.9  676.66
#Mann=3,-1,0
  4300.5    0.05       0  5010.6    0.04       0  5014.6    0.05       0
Bank Sta=5010.6,5014.6
Exp/Cntr=0.3,0.1

Type RM Length L Ch R = 1,9531,352,352,352
BEGIN DESCRIPTION:
Mapping XS aa240b02
END DESCRIPTION:
XS GIS Cut Line= 2
      2335492.30      7083675.71      2335193.94      7082650.33
#Sta/Elev= 30
  4474.7  661.59  4626.4  660.53  4668.1  659.72  4683.5  658.53  4688.9  659.51
  4709.8  660.06  4722.3  659.82  4741.0  657.69  4750.6  657.37  4822.8  657.41
  4861.6  656.21  4939.0  655.80  4959.7  655.05  4980.5  652.89  4991.0  650.00
  4998.8  648.79  4999.1  648.29  5002.6  648.29  5002.8  648.79  5011.8  651.61
  5022.2  653.32  5039.6  654.74  5105.5  656.00  5184.1  660.09  5240.9  659.52
  5272.2  660.68  5289.8  660.36  5303.4  661.82  5334.6  661.28  5542.6  666.04
#Mann=3,-1,0
  4474.7    0.05       0  4998.8    0.04       0  5002.8    0.05       0
Bank Sta=4998.8,5002.8
Exp/Cntr=0.3,0.1

Type RM Length L Ch R = 1,9179,310,310,310
BEGIN DESCRIPTION:
Mapping XS d0804b0b
END DESCRIPTION:
XS GIS Cut Line= 2
      2335703.15      7083580.63      2335643.41      7082424.57
#Sta/Elev= 30
  4475.4  659.62  4516.1  659.65  4576.2  656.21  4606.2  657.84  4652.0  655.87
  4756.4  656.16  4844.0  652.41  4956.7  650.78  4966.7  650.11  4986.7  646.72
  5014.8  645.87  5015.0  645.37  5018.8  645.87  5026.8  647.14  5036.0  650.24
  5041.0  650.03  5046.8  651.63  5056.8  651.97  5106.9  652.14  5177.0  653.66
  5207.0  653.42  5277.1  655.17  5317.2  655.34  5327.2  654.47  5407.3  657.73
  5517.4  658.17  5557.5  660.23  5577.5  660.24  5597.5  661.67  5633.0  662.34
#Mann=3,-1,0
  4475.4    0.05       0  5014.8   0.033       0  5018.8    0.05       0
Bank Sta=5014.8,5018.8
Exp/Cntr=0.3,0.1

Type RM Length L Ch R = 1,8869,108,108,108
BEGIN DESCRIPTION:
Mapping XS 78c78e2d
END DESCRIPTION:
XS GIS Cut Line= 2
      2335990.62      7083432.22      2335977.11      7082485.82
#Sta/Elev= 30
  4598.1  653.74  4630.3  651.86  4670.3  650.92  4740.3  649.64  4810.3  649.17
  4890.4  647.37  4980.4  643.77  4998.4  641.90  4998.6  641.40  5002.1  641.40
  5002.4  641.90  5030.4  645.46  5063.5  646.70  5100.4  647.21  5120.4  648.44
  5140.4  648.85  5160.4  648.36  5200.4  649.89  5250.4  649.73  5260.4  648.91
  5270.4  650.26  5280.4  650.76  5310.4  650.38  5360.4  652.41  5390.4  654.37
  5440.4  654.74  5470.4  654.17  5500.4  655.71  5510.4  655.07  5544.6  656.04
#Mann=3,-1,0
  4598.1    0.05       0  4998.4   0.033       0  5002.4    0.05       0
Bank Sta=4998.4,5002.4
Exp/Cntr=0.3,0.1

Type RM Length L Ch R = 1,8761,479,479,479
BEGIN DESCRIPTION:
Mapping XS e0511f93
END DESCRIPTION:
XS GIS Cut Line= 2
      2336099.43      7083487.67      2336084.41      7082407.58
#Sta/Elev= 30
  4543.8  652.90  4571.5  651.88  4591.5  652.56  4631.5  650.53  4721.5  647.42
  4781.5  646.66  4861.5  647.00  4891.5  646.64  4911.5  645.56  4930.2  642.37
  4935.2  642.79  4971.5  642.88  4991.5  641.93  4999.5  640.35  4999.8  639.85
  5003.3  639.85  5003.5  640.35  5011.5  642.08  5021.5  643.06  5091.5  644.16
  5131.5  645.62  5181.5  646.38  5294.0  649.86  5341.5  650.82  5361.5  652.01
  5391.6  652.23  5421.6  653.71  5491.6  654.26  5561.6  655.97  5624.0  657.17
#Mann=5,-1,0
  4543.8    0.05       0  4999.5   0.033       0  5003.5    0.05       0
  5294.0   0.075       0  5561.6    0.05       0
Bank Sta=4999.5,5003.5
Exp/Cntr=0.3,0.1

Type RM Length L Ch R = 1,8282,299,299,299
BEGIN DESCRIPTION:
Trail Cr Trib 2 27.0
END DESCRIPTION:
XS GIS Cut Line= 3
      2335978.98      7083760.03      2336516.74      7083097.38
      2336479.00      7082610.04
#Sta/Elev= 30
  4146.6  661.16  4232.1  659.09  4238.6  657.69  4275.3  656.55  4281.7  657.67
  4366.4  655.48  4380.8  654.07  4423.9  652.85  4494.4  649.23  4523.1  648.64
  4558.7  649.26  4587.0  647.28  4594.9  647.86  4609.3  647.46  4694.1  643.94
  4842.7  636.25  4871.5  635.70  4900.2  636.54  4992.9  636.29  4995.8  635.19
  4996.1  634.69  4999.8  635.19  5007.4  635.42  5027.5  637.97  5057.5  638.67
  5137.8  643.32  5218.0  649.63  5268.2  651.48  5449.2  655.23  5488.8  655.84
#Mann=4,-1,0
  4146.6    0.05       0  4995.8   0.033       0  4999.8    0.05       0
  5449.2   0.075       0
Bank Sta=4995.8,4999.8
Exp/Cntr=0.3,0.1

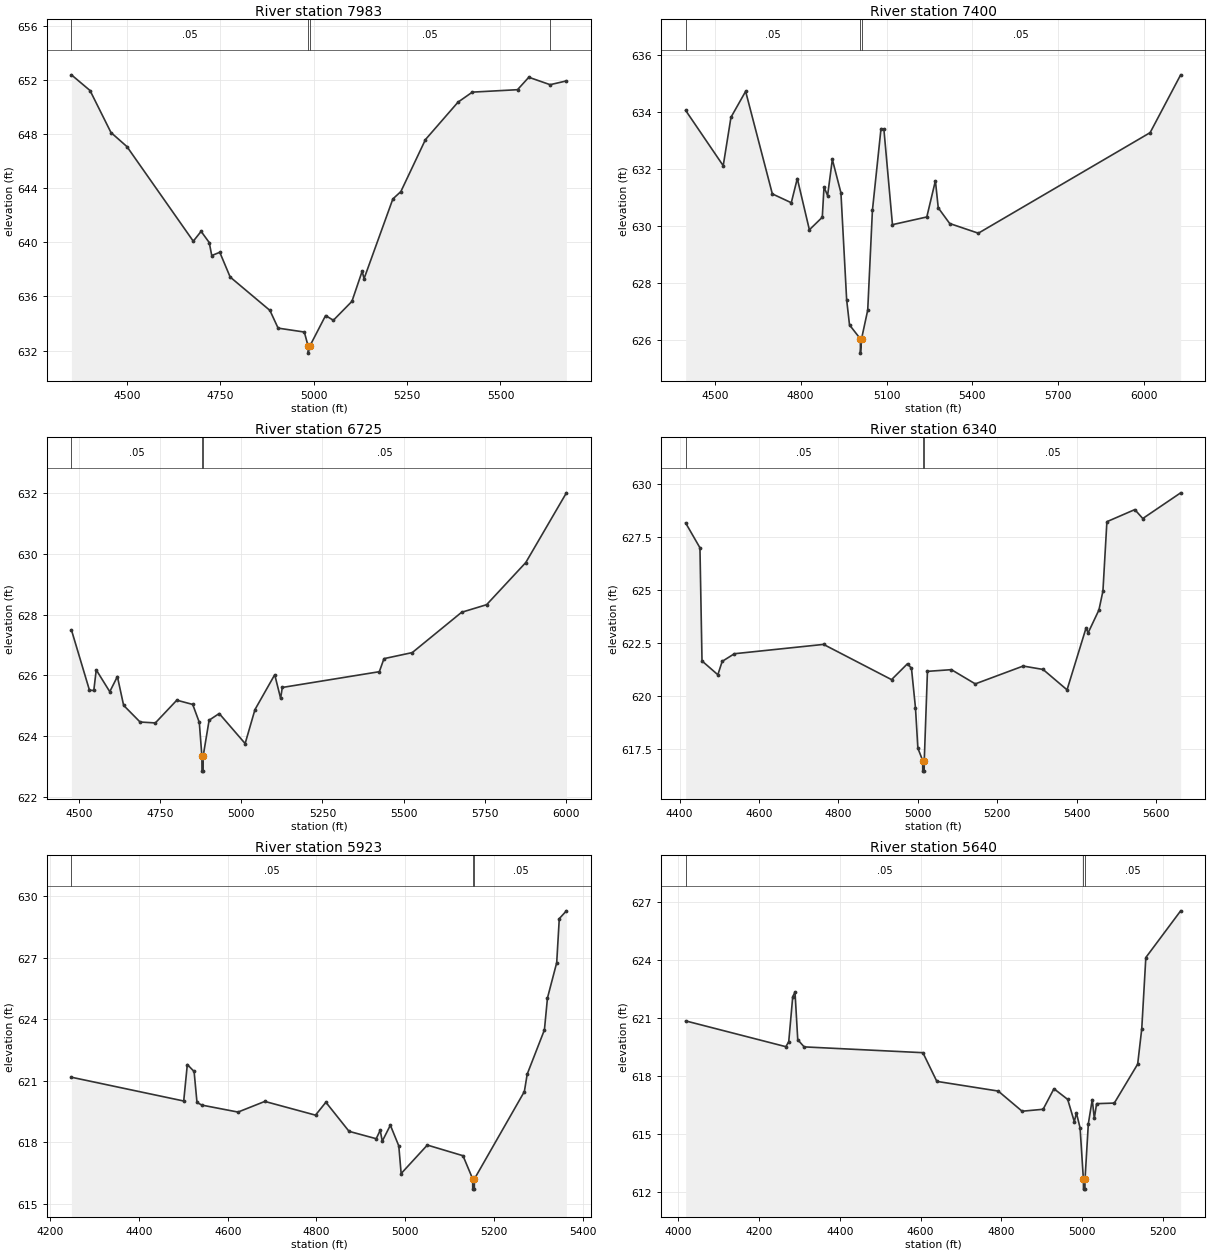
Type RM Length L Ch R = 1,7983,583,583,583
BEGIN DESCRIPTION:
Trail Cr Trib 2 26.0
END DESCRIPTION:
XS GIS Cut Line= 3
      2336229.02      7083709.98      2336711.01      7083292.01
      2336629.00      7082610.00
#Sta/Elev= 30
  4351.6  652.40  4401.4  651.24  4457.5  648.13  4500.2  647.09  4677.8  640.09
  4698.7  640.82  4720.5  639.99  4727.2  639.03  4748.7  639.27  4776.5  637.44
  4882.9  634.97  4904.8  633.66  4975.0  633.37  4985.3  632.31  4985.5  631.81
  4989.3  632.31  5031.9  634.59  5052.7  634.24  5102.4  635.64  5129.8  637.87
  5134.9  637.32  5212.0  643.22  5233.3  643.76  5299.2  647.61  5386.4  650.38
  5424.7  651.12  5545.6  651.30  5575.8  652.22  5632.9  651.67  5676.5  651.95
#Mann=4,-1,0
  4351.6    0.05       0  4985.3   0.033       0  4989.3    0.05       0
  5632.9   0.075       0
Bank Sta=4985.3,4989.3
Exp/Cntr=0.3,0.1

Type RM Length L Ch R = 1,7400,675,675,675
BEGIN DESCRIPTION:
Mapping XS 80f9afbb
END DESCRIPTION:
XS GIS Cut Line= 3
      2336668.51      7083700.01      2337082.07      7083426.63
      2337099.23      7082193.30
#Sta/Elev= 30
  4398.2  634.07  4529.4  632.13  4556.5  633.83  4607.7  634.74  4701.0  631.14
  4767.2  630.83  4788.2  631.68  4830.4  629.88  4875.5  630.32  4881.5  631.38
  4894.0  631.08  4910.6  632.35  4940.6  631.18  4960.6  627.42  4970.6  626.54
  5008.6  626.05  5008.8  625.55  5012.6  626.05  5034.2  627.06  5050.6  630.56
  5080.6  633.43  5090.6  633.42  5120.6  630.06  5240.6  630.33  5270.6  631.60
  5280.6  630.65  5320.6  630.10  5420.6  629.76  6020.7  633.29  6127.4  635.32
#Mann=3,-1,0
  4398.2    0.05       0  5008.6   0.033       0  5012.6    0.05       0
Bank Sta=5008.6,5012.6
Exp/Cntr=0.3,0.1

Type RM Length L Ch R = 1,6725,385,385,385
BEGIN DESCRIPTION:
Train Cr Trib 2 3.0
END DESCRIPTION:
XS GIS Cut Line= 5
      2337568.83      7083596.15      2337645.03      7083489.31
      2337599.68      7083215.11      2337574.83      7083032.87
      2337389.82      7082118.89
#Sta/Elev= 30
  4476.5  627.50  4532.1  625.51  4545.5  625.50  4553.0  626.18  4594.7  625.46
  4618.2  625.96  4637.4  625.01  4688.1  624.46  4735.2  624.43  4801.3  625.18
  4850.3  625.04  4870.6  624.45  4878.6  623.34  4878.9  622.84  4882.4  622.84
  4882.6  623.34  4900.9  624.52  4932.0  624.74  5011.9  623.75  5042.2  624.87
  5103.1  626.02  5121.3  625.24  5126.4  625.60  5425.5  626.12  5439.8  626.55
  5527.0  626.75  5679.1  628.08  5756.1  628.33  5876.8  629.72  6002.1  632.02
#Mann=3,-1,0
  4476.5    0.05       0  4878.6   0.033       0  4882.6    0.05       0
Bank Sta=4878.6,4882.6
Exp/Cntr=0.3,0.1

Type RM Length L Ch R = 1,6340,417,417,417
BEGIN DESCRIPTION:
Mapping XS 47d4dad8
END DESCRIPTION:
XS GIS Cut Line= 3
      2337886.65      7083580.12      2337963.49      7083209.24
      2337881.86      7082345.04
#Sta/Elev= 30
  4415.4  628.17  4451.4  627.00  4456.6  621.67  4496.5  621.02  4507.4  621.65
  4538.1  622.01  4762.7  622.45  4934.0  620.79  4974.2  621.54  4984.2  621.32
  4994.3  619.45  5000.3  617.56  5012.4  616.98  5012.6  616.48  5016.1  616.48
  5016.4  616.98  5024.4  621.18  5084.7  621.26  5144.9  620.59  5265.5  621.43
  5315.6  621.27  5376.0  620.31  5424.0  623.23  5429.0  622.99  5456.3  624.07
  5466.4  624.96  5476.4  628.23  5546.7  628.80  5566.8  628.38  5662.2  629.59
#Mann=3,-1,0
  4415.4    0.05       0  5012.4   0.033       0  5016.4    0.05       0
Bank Sta=5012.4,5016.4
Exp/Cntr=0.3,0.1

Type RM Length L Ch R = 1,5923,283,283,283
BEGIN DESCRIPTION:
Mapping XS 95dc0201
END DESCRIPTION:
XS GIS Cut Line= 3
      2338033.61      7083529.30      2338314.98      7082886.37
      2338199.71      7082488.95
#Sta/Elev= 30
  4247.7  621.18  4500.8  620.02  4508.9  621.80  4524.2  621.46  4530.7  619.95
  4541.7  619.82  4623.2  619.48  4683.6  620.00  4797.8  619.33  4821.2  619.96
  4873.4  618.54  4934.6  618.18  4943.6  618.59  4948.3  618.06  4966.5  618.84
  4985.5  617.83  4990.8  616.48  5049.8  617.87  5130.2  617.35  5152.0  616.22
  5152.2  615.72  5155.7  615.72  5156.0  616.22  5268.5  620.48  5274.9  621.33
  5313.7  623.49  5320.6  625.05  5341.4  626.77  5347.2  628.92  5363.3  629.30
#Mann=3,-1,0
  4247.7    0.05       0  5152.0   0.033       0  5156.0    0.05       0
Bank Sta=5152,5156
Exp/Cntr=0.3,0.1

Type RM Length L Ch R = 1,5640,539,539,539
BEGIN DESCRIPTION:
Mapping XS e874420d
END DESCRIPTION:
XS GIS Cut Line= 5
      2338066.89      7083519.77      2338436.50      7082754.07
      2338444.56      7082687.06      2338477.30      7082533.77
      2338457.21      7082384.60
#Sta/Elev= 30
  4018.6  620.84  4266.6  619.51  4273.7  619.77  4283.6  622.09  4289.2  622.33
  4296.0  619.87  4311.8  619.50  4605.7  619.20  4640.2  617.72  4792.1  617.22
  4851.2  616.18  4903.2  616.28  4930.0  617.34  4964.0  616.79  4980.4  615.64
  4985.6  616.09  4994.7  615.32  5002.9  612.66  5003.2  612.16  5006.7  612.16
  5006.9  612.66  5015.1  615.53  5024.8  616.78  5029.9  615.81  5035.6  616.57
  5079.4  616.60  5137.2  618.61  5147.3  620.43  5157.4  624.11  5243.6  626.52
#Mann=3,-1,0
  4018.6    0.05       0  5002.9   0.033       0  5006.9    0.05       0
Bank Sta=5002.9,5006.9
Exp/Cntr=0.3,0.1

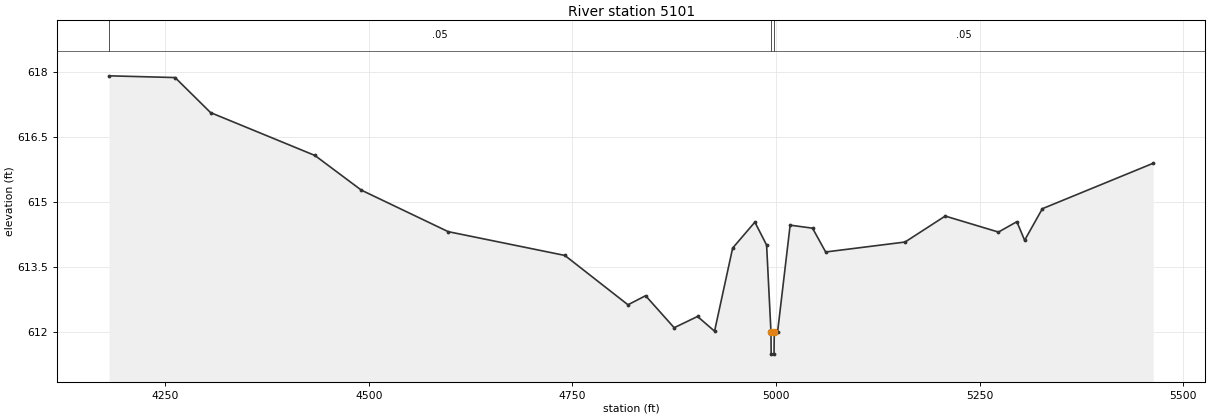
Type RM Length L Ch R = 1,5101,0,0,0
BEGIN DESCRIPTION:
Trail Cr Trib 2 17.0
END DESCRIPTION:
XS GIS Cut Line= 4
      2338348.17      7083313.07      2338729.68      7083021.62
      2338943.37      7082759.99      2338719.82      7082353.27
#Sta/Elev= 30
  4181.1  617.92  4262.1  617.88  4305.7  617.07  4433.8  616.08  4490.7  615.28
  4597.4  614.32  4740.7  613.77  4818.2  612.63  4839.8  612.84  4874.9  612.10
  4903.6  612.36  4924.5  612.02  4946.7  613.94  4974.0  614.54  4988.4  614.01
  4993.8  611.99  4994.0  611.49  4997.5  611.49  4997.8  611.99  5001.8  611.99
  5017.3  614.47  5044.8  614.40  5060.9  613.85  5158.4  614.08  5207.7  614.68
  5273.1  614.31  5295.7  614.55  5305.2  614.12  5327.0  614.85  5463.1  615.90
#Mann=3,-1,0
  4181.1    0.05       0  4993.8    0.04       0  4997.8    0.05       0
Bank Sta=4993.8,4997.8
Exp/Cntr=0.3,0.1

Chan Stop Cuts=-1