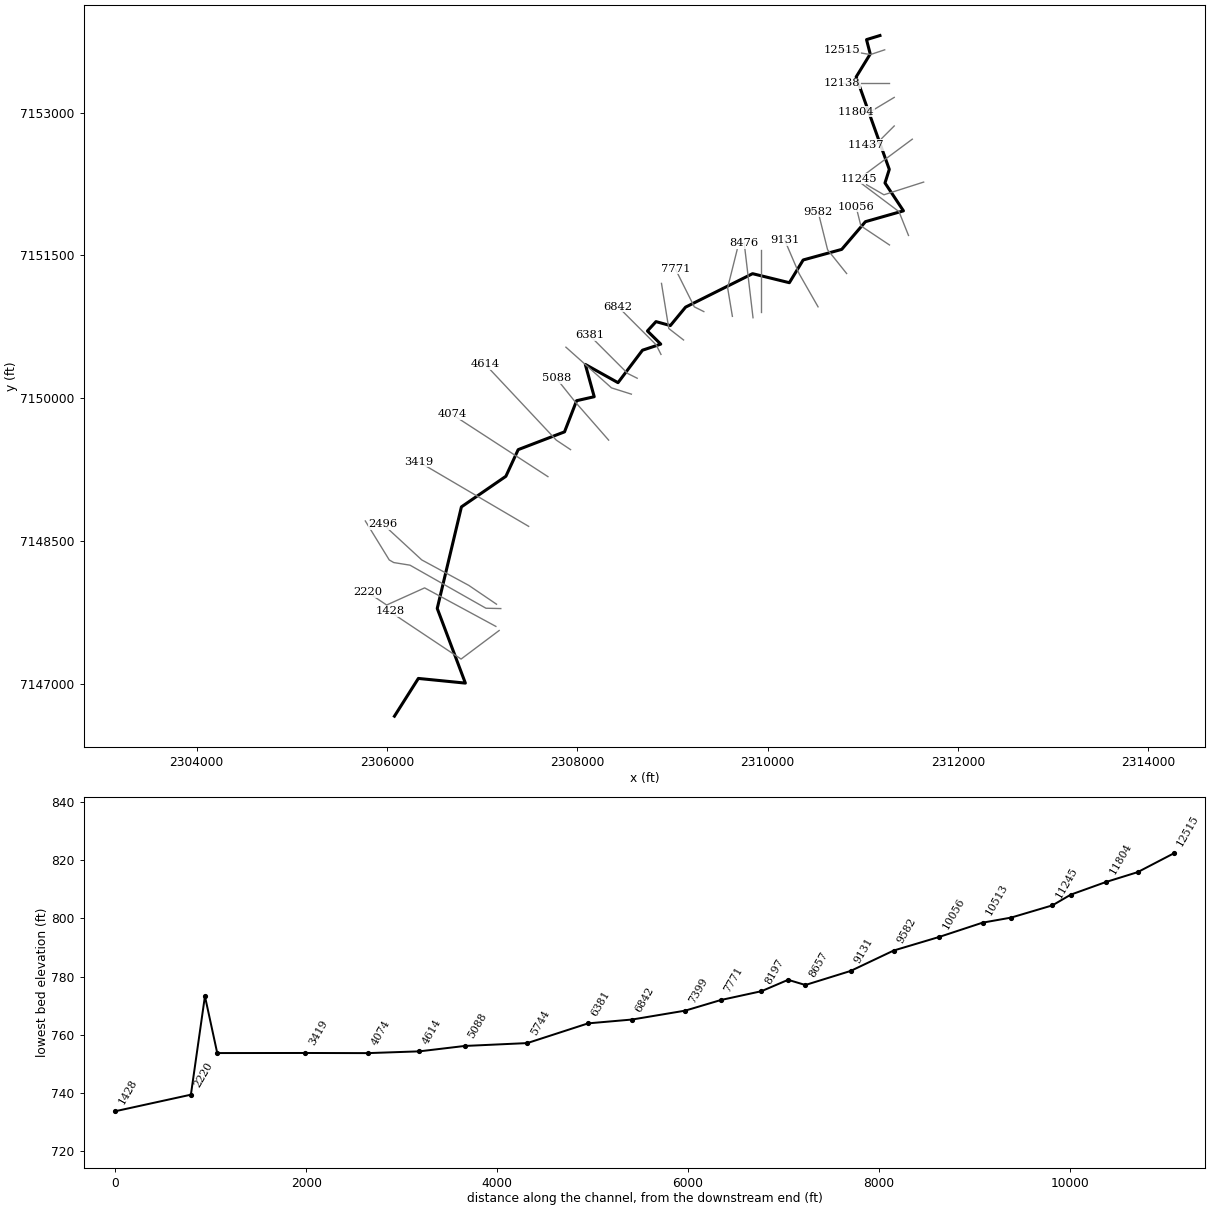
--- Unnamed 48.prj (project) ---

Proj Title=Unnamed 48 Base Level Engineering
Current Plan=p01
Default Exp/Contr=0.3,0.1
English Units
Geom File=g01
Flow File=f01
Plan File=p01
BEGIN DESCRIPTION:
Unnamed 48
END DESCRIPTION:

--- Unnamed 48.p01 (plan) ---

Plan Title=Multiple Run
Short Identifier=Multiple
Geom File=g01
Flow File=f01
Subcritical Flow
K Sum by GR= 0
Std Step Tol= 0.01
Critical Tol= 0.01
Num of Std Step Trials= 20
Max Error Tol= 0.3
Flow Tol Ratio= 0.001
Split Flow NTrial= 30
Split Flow Tol= 0.02
Split Flow Ratio= 0.02
Log Output Level= 0
Friction Slope Method= 1
Unsteady Friction Slope Method= 2
Unsteady Bridges Friction Slope Method= 1
Parabolic Critical Depth
Global Vel Dist=  1 , 1 , 1
Global Log Level= 0
CheckData=True
Encroach Param= -1, 0, 0, 0
BEGIN DESCRIPTION:
Multiple Run
END DESCRIPTION:

--- Unnamed 48.f01 (steady flow) ---

Flow Title=Multiple
Number of Profiles=7
Profile Names=10-year,25-year,50-year,1pct_min,100-year,1pct_plu,500-year
River Rch & RM= Unnamed 48,Reach-1,12515
     496     671     814     492     982    1958    1426
River Rch & RM= Unnamed 48,Reach-1,10812
     836    1169    1449     893    1781    3554    2695
River Rch & RM= Unnamed 48,Reach-1,9582
     973    1375    1718    1065    2125    4240    3260
River Rch & RM= Unnamed 48,Reach-1,6842
    1246    1782    2242    1399    2791    5569    4336
River Rch & RM= Unnamed 48,Reach-1,4614
    1620    2345    2976    1871    3733    7448    5889
River Rch & RM= Unnamed 48,Reach-1,2496
    1679    2433    3090    1943    3878    7737    6125
Boundary for River Rch & Prof#=Unnamed 48,Reach-1,1
Up Type=0
Dn Type=3
Dn Slope=0.005
Boundary for River Rch & Prof#=Unnamed 48,Reach-1,2
Up Type=0
Dn Type=3
Dn Slope=0.005
Boundary for River Rch & Prof#=Unnamed 48,Reach-1,3
Up Type=0
Dn Type=3
Dn Slope=0.005
Boundary for River Rch & Prof#=Unnamed 48,Reach-1,4
Up Type=0
Dn Type=3
Dn Slope=0.005
Boundary for River Rch & Prof#=Unnamed 48,Reach-1,5
Up Type=0
Dn Type=3
Dn Slope=0.005
Boundary for River Rch & Prof#=Unnamed 48,Reach-1,6
Up Type=0
Dn Type=3
Dn Slope=0.005
Boundary for River Rch & Prof#=Unnamed 48,Reach-1,7
Up Type=0
Dn Type=3
Dn Slope=0.005

--- Unnamed 48.g01 (geometry) ---

Geom Title=Existing Conditions

River Reach=Unnamed 48,Reach-1
Reach XY= 30
      2311179.00      7153810.00      2311037.95      7153767.05
      2311077.03      7153615.89      2310929.24      7153375.22
      2311277.20      7152403.89      2311232.04      7152261.42
      2311425.94      7151968.31      2311026.53      7151854.55
      2310777.53      7151563.54      2310372.48      7151452.32
      2310227.52      7151213.45      2309840.87      7151308.45
      2309137.31      7150956.92      2308977.42      7150763.07
      2308826.44      7150804.69      2308736.47      7150706.43
      2308876.56      7150568.20      2308684.58      7150504.42
      2308427.42      7150163.42      2308083.96      7150355.04
      2308177.49      7150015.82      2307992.62      7149974.02
      2307865.64      7149646.65      2307379.00      7149460.00
      2307249.42      7149179.76      2306782.54      7148858.53
      2306528.50      7147791.67      2306824.05      7147007.42
      2306330.23      7147056.57      2306079.00      7146660.00

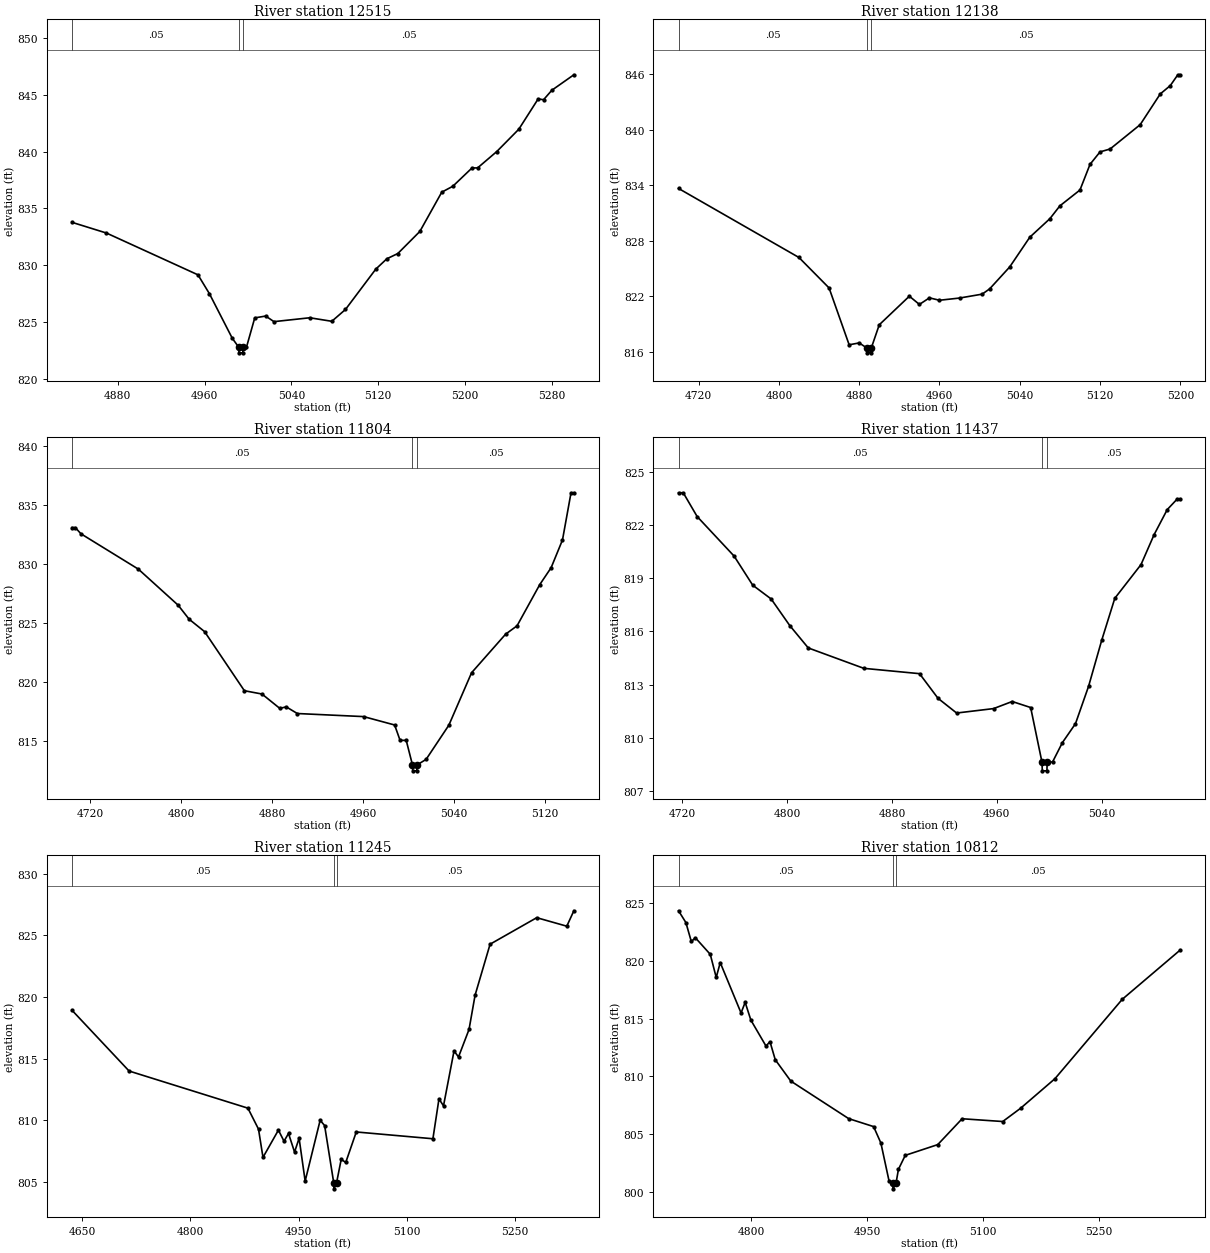
Type RM Length L Ch R = 1,12515,377,377,377
BEGIN DESCRIPTION:
Unnamed 48 27.0
END DESCRIPTION:
XS GIS Cut Line= 3
      2311229.05      7153660.02      2311079.00      7153610.00
      2310779.00      7153660.00
#Sta/Elev= 30
  4837.9  833.78  4869.6  832.84  4953.9  829.17  4964.4  827.52  4985.5  823.60
  4991.4  822.82  4991.7  822.32  4995.2  822.32  4995.4  822.82  4998.6  822.82
  5006.2  825.39  5016.3  825.55  5023.9  825.06  5056.9  825.40  5077.2  825.09
  5089.8  826.13  5117.7  829.67  5127.9  830.58  5138.0  831.04  5158.3  832.98
  5178.5  836.43  5188.7  836.95  5206.4  838.56  5211.5  838.56  5229.2  840.00
  5249.5  841.96  5267.3  844.62  5272.3  844.55  5279.9  845.38  5300.2  846.74
#Mann=3,-1,0
  4837.9    0.05       0  4991.4   0.033       0  4995.4    0.05       0
Bank Sta=4991.4,4995.4
Exp/Cntr=0.3,0.1

Type RM Length L Ch R = 1,12138,334,334,334
BEGIN DESCRIPTION:
Unnamed 48 26.0
END DESCRIPTION:
XS GIS Cut Line= 3
      2311278.98      7153310.00      2310979.00      7153310.00
      2310778.98      7153310.00
#Sta/Elev= 30
  4700.0  833.64  4820.0  826.18  4850.0  822.89  4870.0  816.75  4880.0  816.95
  4888.0  816.38  4888.2  815.88  4891.7  815.88  4892.0  816.38  4900.0  818.91
  4930.0  822.00  4940.0  821.11  4950.0  821.82  4960.0  821.56  4980.0  821.80
  5002.5  822.22  5010.0  822.79  5030.0  825.16  5050.0  828.37  5070.0  830.37
  5080.0  831.76  5100.0  833.47  5110.0  836.24  5120.0  837.59  5130.0  837.90
  5160.0  840.53  5180.0  843.85  5190.0  844.75  5197.5  845.92  5200.0  845.92
#Mann=3,-1,0
  4700.0    0.05       0  4888.0   0.033       0  4892.0    0.05       0
Bank Sta=4888,4892
Exp/Cntr=0.3,0.1

Type RM Length L Ch R = 1,11804,367,367,367
BEGIN DESCRIPTION:
Unnamed 48 25.0
END DESCRIPTION:
XS GIS Cut Line= 3
      2311328.98      7153159.99      2311079.00      7153010.00
      2310929.03      7153010.00
#Sta/Elev= 30
  4703.9  833.05  4706.8  833.05  4711.7  832.53  4762.2  829.54  4797.2  826.49
  4806.9  825.30  4820.5  824.25  4855.5  819.25  4871.0  818.97  4886.6  817.76
  4892.4  817.88  4902.1  817.32  4960.4  817.06  4987.7  816.35  4992.5  815.05
  4997.9  815.05  5003.4  812.97  5003.7  812.47  5007.2  812.47  5007.4  812.97
  5015.4  813.44  5035.4  816.33  5055.4  820.77  5085.4  824.04  5095.4  824.74
  5115.4  828.23  5125.4  829.66  5135.4  832.01  5142.9  836.00  5145.4  836.00
#Mann=3,-1,0
  4703.9    0.05       0  5003.4   0.033       0  5007.4    0.05       0
Bank Sta=5003.4,5007.4
Exp/Cntr=0.3,0.1

Type RM Length L Ch R = 1,11437,192,192,192
BEGIN DESCRIPTION:
Unnamed 48 24.0
END DESCRIPTION:
XS GIS Cut Line= 3
      2311329.01      7152860.01      2311129.00      7152660.00
      2311028.96      7152660.00
#Sta/Elev= 30
  4717.1  823.82  4720.7  823.82  4731.3  822.48  4759.5  820.25  4773.7  818.61
  4787.8  817.83  4802.0  816.33  4816.1  815.07  4858.5  813.92  4901.0  813.62
  4915.1  812.23  4929.3  811.40  4957.5  811.65  4971.7  812.05  4985.8  811.71
  4994.4  808.64  4994.7  808.14  4998.2  808.14  4998.4  808.64  5002.5  808.64
  5010.0  809.73  5020.0  810.80  5030.0  812.91  5040.0  815.50  5050.0  817.87
  5070.0  819.77  5080.0  821.46  5090.0  822.87  5097.5  823.46  5100.0  823.46
#Mann=3,-1,0
  4717.1    0.05       0  4994.4   0.033       0  4998.4    0.05       0
Bank Sta=4994.4,4998.4
Exp/Cntr=0.3,0.1

Type RM Length L Ch R = 1,11245,433,433,433
BEGIN DESCRIPTION:
Mapping XS 12ba3bce
END DESCRIPTION:
XS GIS Cut Line= 2
      2311518.78      7152721.21      2310959.92      7152306.38
#Sta/Elev= 30
  4635.9  818.93  4715.0  814.01  4879.8  811.00  4894.5  809.30  4900.7  807.01
  4922.1  809.22  4929.9  808.32  4936.1  808.95  4944.5  807.44  4950.8  808.56
  4959.2  805.09  4980.0  810.02  4986.2  809.59  4998.8  804.96  4999.1  804.46
  5002.8  804.96  5009.2  806.85  5015.5  806.60  5030.1  809.07  5136.4  808.52
  5144.8  811.75  5151.1  811.19  5165.7  815.64  5171.9  815.15  5186.5  817.38
  5194.9  820.16  5215.7  824.29  5280.4  826.44  5322.1  825.75  5331.9  827.00
#Mann=3,-1,0
  4635.9    0.05       0  4998.8   0.033       0  5002.8    0.05       0
Bank Sta=4998.8,5002.8
Exp/Cntr=0.3,0.1

Type RM Length L Ch R = 1,10812,299,299,299
BEGIN DESCRIPTION:
Mapping XS 50b3ab18
END DESCRIPTION:
XS GIS Cut Line= 3
      2311638.09      7152270.57      2311220.79      7152136.99
      2311038.91      7152242.65
#Sta/Elev= 30
  4706.5  824.33  4716.0  823.31  4723.0  821.67  4728.3  821.99  4747.5  820.56
  4755.2  818.56  4760.4  819.84  4787.3  815.48  4792.6  816.40  4800.0  814.86
  4819.5  812.62  4824.7  812.99  4831.5  811.43  4851.6  809.58  4926.4  806.33
  4958.6  805.64  4968.0  804.22  4978.5  800.95  4983.4  800.75  4983.7  800.25
  4987.6  800.75  4990.7  801.94  4999.5  803.15  5041.5  804.08  5073.0  806.32
  5125.5  806.08  5148.6  807.23  5193.0  809.79  5279.9  816.66  5355.0  820.94
#Mann=3,-1,0
  4706.5    0.05       0  4983.4   0.033       0  4987.6    0.05       0
Bank Sta=4983.4,4987.6
Exp/Cntr=0.3,0.1

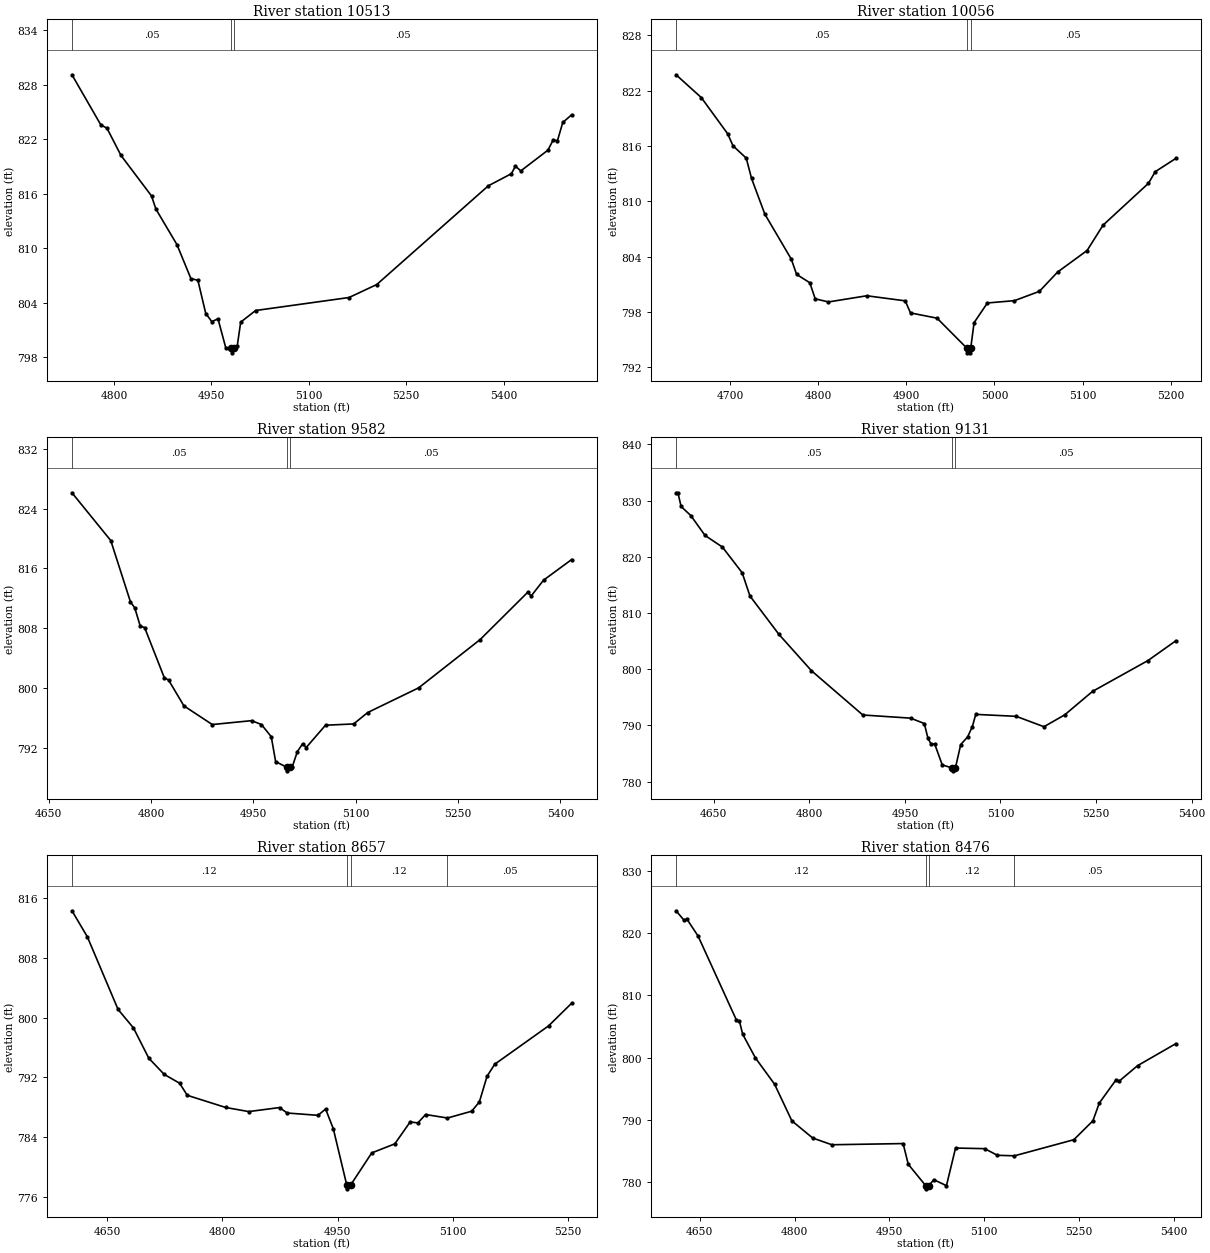
Type RM Length L Ch R = 1,10513,457,457,457
BEGIN DESCRIPTION:
Unnamed 48 22.0
END DESCRIPTION:
XS GIS Cut Line= 3
      2311479.00      7151709.99      2311379.00      7151960.00
      2310978.98      7152260.02
#Sta/Elev= 30
  4735.4  829.12  4779.8  823.61  4789.3  823.24  4810.8  820.25  4857.9  815.78
  4864.7  814.33  4897.0  810.43  4918.5  806.69  4929.3  806.49  4941.4  802.84
  4950.8  801.94  4960.2  802.26  4972.4  799.02  4981.0  799.01  4981.3  798.51
  4985.3  799.01  4989.9  799.28  4995.2  801.89  5018.2  803.17  5162.0  804.60
  5204.7  806.03  5376.5  816.90  5412.0  818.23  5418.2  819.06  5426.5  818.54
  5468.2  820.82  5476.5  821.97  5482.8  821.84  5491.1  823.87  5504.7  824.71
#Mann=3,-1,0
  4735.4    0.05       0  4981.0   0.033       0  4985.3    0.05       0
Bank Sta=4981,4985.3
Exp/Cntr=0.3,0.1

Type RM Length L Ch R = 1,10056,474,474,474
BEGIN DESCRIPTION:
Unnamed 48 21.0
END DESCRIPTION:
XS GIS Cut Line= 3
      2311279.01      7151610.00      2310979.00      7151810.00
      2310929.00      7152009.98
#Sta/Elev= 30
  4638.9  823.73  4667.5  821.26  4697.5  817.32  4703.5  816.02  4718.5  814.69
  4724.5  812.49  4739.6  808.61  4769.6  803.73  4775.6  802.08  4790.6  801.17
  4796.7  799.43  4811.7  799.09  4855.2  799.76  4898.8  799.21  4904.8  797.90
  4934.9  797.33  4968.8  794.07  4969.1  793.57  4972.7  793.57  4973.1  794.07
  4976.9  796.84  4992.0  798.98  5022.7  799.23  5051.0  800.24  5071.6  802.33
  5105.1  804.67  5123.2  807.42  5174.7  811.96  5182.4  813.22  5205.6  814.65
#Mann=3,-1,0
  4638.9    0.05       0  4968.8   0.033       0  4973.1    0.05       0
Bank Sta=4968.8,4973.1
Exp/Cntr=0.3,0.1

Type RM Length L Ch R = 1,9582,451,451,451
BEGIN DESCRIPTION:
Unnamed 48 20.0
END DESCRIPTION:
XS GIS Cut Line= 3
      2310829.02      7151309.98      2310629.00      7151560.00
      2310529.00      7151960.00
#Sta/Elev= 30
  4683.9  826.11  4740.8  819.72  4769.6  811.54  4776.0  810.71  4784.0  808.28
  4790.4  808.09  4819.2  801.40  4825.6  801.06  4848.0  797.62  4889.6  795.12
  4947.3  795.64  4961.7  795.12  4976.1  793.49  4982.5  790.16  4998.5  789.43
  4999.0  788.93  5003.2  789.43  5006.7  789.43  5014.4  791.51  5022.1  792.56
  5027.3  792.05  5055.6  795.03  5096.9  795.20  5117.5  796.73  5192.2  800.03
  5282.4  806.49  5352.0  812.80  5357.1  812.31  5375.2  814.42  5416.4  817.18
#Mann=3,-1,0
  4683.9    0.05       0  4998.5   0.033       0  5003.2    0.05       0
Bank Sta=4998.5,5003.2
Exp/Cntr=0.3,0.1

Type RM Length L Ch R = 1,9131,474,474,474
BEGIN DESCRIPTION:
Unnamed 48 19.0
END DESCRIPTION:
XS GIS Cut Line= 3
      2310529.01      7150959.99      2310329.00      7151310.00
      2310179.01      7151659.98
#Sta/Elev= 30
  4591.0  831.40  4593.9  831.40  4598.9  828.96  4614.1  827.35  4636.4  823.81
  4663.7  821.74  4694.7  817.17  4706.9  813.03  4752.3  806.21  4803.4  799.73
  4884.0  791.85  4958.9  791.29  4980.5  790.33  4986.2  787.69  4991.2  786.67
  4996.8  786.67  5008.6  782.97  5024.4  782.41  5024.9  781.91  5029.2  782.41
  5037.6  786.58  5048.5  787.97  5055.8  789.78  5061.2  791.96  5124.7  791.61
  5168.2  789.76  5200.8  791.88  5244.4  796.05  5331.4  801.54  5374.9  805.04
#Mann=3,-1,0
  4591.0    0.05       0  5024.4   0.033       0  5029.2    0.05       0
Bank Sta=5024.4,5029.2
Exp/Cntr=0.3,0.1

Type RM Length L Ch R = 1,8657,181,181,181
BEGIN DESCRIPTION:
Unnamed 48 18.0
END DESCRIPTION:
XS GIS Cut Line= 3
      2309929.00      7150909.98      2309929.00      7151310.00
      2309929.00      7151559.98
#Sta/Elev= 30
  4604.5  814.30  4624.5  810.82  4664.5  801.09  4684.5  798.62  4704.5  794.56
  4724.5  792.40  4744.5  791.22  4754.5  789.60  4804.5  787.97  4834.5  787.42
  4874.5  787.96  4884.5  787.23  4924.5  786.92  4934.5  787.76  4944.5  785.12
  4962.0  777.58  4962.7  777.08  4967.0  777.58  4994.5  781.89  5024.5  783.10
  5044.5  786.04  5054.5  785.90  5064.5  787.03  5093.0  786.56  5124.5  787.47
  5134.5  788.71  5144.5  792.15  5154.5  793.76  5224.5  798.89  5254.5  801.92
#Mann=4,-1,0
  4604.5    0.12       0  4962.0    0.07       0  4967.0    0.12       0
  5093.0    0.05       0
Bank Sta=4962,4967
Exp/Cntr=0.3,0.1

Type RM Length L Ch R = 1,8476,279,279,279
BEGIN DESCRIPTION:
Mapping XS 657e4674
END DESCRIPTION:
XS GIS Cut Line= 2
      2309845.76      7150845.42      2309753.06      7151629.97
#Sta/Elev= 30
  4612.6  823.64  4624.9  822.15  4630.0  822.26  4647.4  819.57  4707.8  806.09
  4712.8  805.86  4717.9  803.77  4738.0  799.95  4768.3  795.72  4795.7  789.81
  4828.7  787.04  4858.9  785.96  4971.6  786.15  4979.7  782.82  5007.4  779.36
  5008.1  778.86  5012.4  779.36  5020.0  780.34  5040.1  779.37  5054.5  785.43
  5100.5  785.33  5120.7  784.26  5147.7  784.18  5241.5  786.77  5271.7  789.82
  5281.8  792.68  5308.2  796.41  5313.2  796.20  5342.2  798.69  5402.6  802.23
#Mann=4,-1,0
  4612.6    0.12       0  5007.4    0.07       0  5012.4    0.12       0
  5147.7    0.05       0
Bank Sta=5007.4,5012.4
Exp/Cntr=0.3,0.1

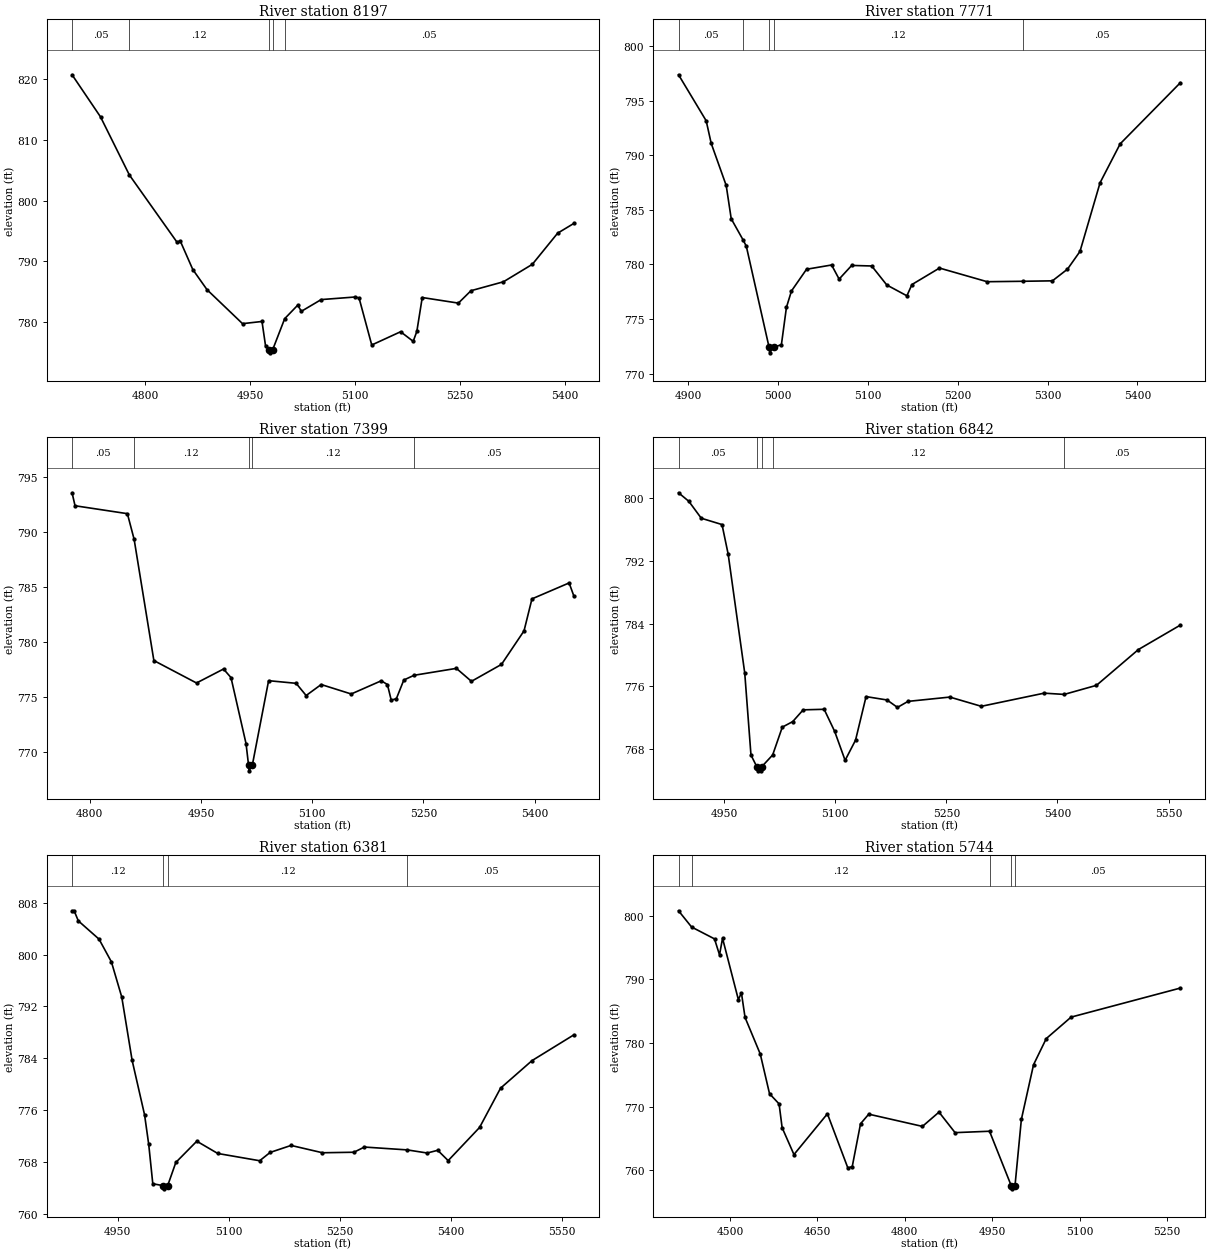
Type RM Length L Ch R = 1,8197,426,426,426
BEGIN DESCRIPTION:
Unnamed 48 17.0
END DESCRIPTION:
XS GIS Cut Line= 3
      2309629.01      7150859.95      2309579.00      7151160.00
      2309679.00      7151560.01
#Sta/Elev= 30
  4695.8  820.69  4736.4  813.77  4777.6  804.21  4845.4  793.19  4850.4  793.32
  4868.2  788.65  4888.5  785.34  4939.2  779.75  4967.0  780.11  4972.1  776.07
  4977.2  775.45  4977.8  774.95  4982.2  775.45  4999.4  780.57  5018.0  782.79
  5023.2  781.78  5051.5  783.71  5100.5  784.14  5105.6  783.97  5123.7  776.24
  5164.9  778.42  5182.9  776.84  5188.1  778.48  5195.8  784.05  5247.4  783.13
  5265.4  785.17  5311.8  786.64  5353.0  789.51  5389.1  794.63  5412.3  796.24
#Mann=5,-1,0
  4695.8    0.05       0  4777.6    0.12       0  4977.2   0.033       0
  4982.2    0.12       0  4999.4    0.05       0
Bank Sta=4977.2,4982.2
Exp/Cntr=0.3,0.1

Type RM Length L Ch R = 1,7771,372,372,372
BEGIN DESCRIPTION:
Unnamed 48 16.0
END DESCRIPTION:
XS GIS Cut Line= 3
      2309329.01      7150909.99      2309229.00      7150960.00
      2309029.01      7151359.97
#Sta/Elev= 30
  4888.9  797.36  4919.7  793.15  4925.3  791.08  4942.0  787.23  4947.6  784.18
  4960.7  782.26  4964.4  781.67  4989.8  772.41  4990.4  771.91  4994.8  772.41
  5003.5  772.66  5009.1  776.07  5014.7  777.57  5031.5  779.56  5059.4  779.95
  5067.8  778.66  5081.8  779.91  5104.1  779.86  5120.9  778.12  5143.3  777.13
  5148.9  778.16  5179.6  779.67  5232.7  778.42  5272.8  778.46  5305.4  778.50
  5322.2  779.57  5336.1  781.19  5358.5  787.48  5380.9  791.04  5447.9  796.63
#Mann=5,-1,0
  4888.9    0.05       0  4960.7    0.12       0  4989.8    0.07       0
  4994.8    0.12       0  5272.8    0.05       0
Bank Sta=4989.8,4994.8
Exp/Cntr=0.3,0.1

Type RM Length L Ch R = 1,7399,557,557,557
BEGIN DESCRIPTION:
Mapping XS 94d70434
END DESCRIPTION:
XS GIS Cut Line= 3
      2309116.15      7150611.75      2308961.25      7150732.04
      2308884.21      7151206.30
#Sta/Elev= 30
  4776.2  793.56  4780.2  792.38  4850.8  791.66  4859.9  789.32  4886.5  778.30
  4944.0  776.26  4980.4  777.53  4990.5  776.75  5010.8  770.74  5014.2  768.77
  5014.8  768.27  5019.2  768.77  5041.2  776.47  5078.3  776.23  5091.8  775.12
  5112.1  776.12  5152.6  775.26  5193.1  776.46  5201.4  776.12  5206.5  774.71
  5213.4  774.82  5223.5  776.53  5237.3  776.96  5294.4  777.59  5314.7  776.41
  5355.2  777.95  5385.6  781.00  5396.3  783.91  5446.4  785.36  5452.8  784.17
#Mann=5,-1,0
  4776.2    0.05       0  4859.9    0.12       0  5014.2    0.07       0
  5019.2    0.12       0  5237.3    0.05       0
Bank Sta=5014.2,5019.2
Exp/Cntr=0.3,0.1

Type RM Length L Ch R = 1,6842,461,461,461
BEGIN DESCRIPTION:
Unnamed 48 14.0
END DESCRIPTION:
XS GIS Cut Line= 3
      2308878.98      7150460.03      2308829.00      7150560.00
      2308428.97      7150960.03
#Sta/Elev= 30
  4888.4  800.72  4902.3  799.63  4919.1  797.47  4947.1  796.66  4955.4  792.89
  4977.8  777.69  4986.2  767.23  4994.2  765.71  4995.3  765.21  4999.5  765.21
  5000.5  765.71  5015.5  767.24  5028.5  770.79  5042.6  771.50  5056.7  773.00
  5085.0  773.07  5099.2  770.25  5113.3  766.55  5127.4  769.13  5141.6  774.69
  5169.9  774.26  5184.0  773.31  5198.2  774.08  5254.7  774.63  5297.2  773.45
  5382.0  775.13  5409.1  774.97  5452.7  776.13  5509.3  780.70  5565.9  783.82
#Mann=5,-1,0
  4888.4    0.05       0  4994.2   0.033       0  5000.5    0.05       0
  5015.5    0.12       0  5409.1    0.05       0
Bank Sta=4994.2,5000.5
Exp/Cntr=0.3,0.1

Type RM Length L Ch R = 1,6381,637,637,637
BEGIN DESCRIPTION:
Unnamed 48 13.0
END DESCRIPTION:
XS GIS Cut Line= 3
      2308629.03      7150209.98      2308529.00      7150260.00
      2308129.02      7150659.98
#Sta/Elev= 30
  4888.2  806.74  4891.0  806.74  4896.6  805.19  4924.6  802.37  4941.3  798.87
  4955.3  793.44  4969.3  783.68  4986.1  775.29  4991.7  770.73  4997.2  764.67
  5011.0  764.39  5012.0  763.89  5017.3  764.39  5028.3  767.96  5056.6  771.23
  5084.9  769.34  5141.5  768.22  5155.6  769.50  5183.9  770.58  5226.3  769.45
  5268.7  769.53  5282.9  770.33  5340.8  769.89  5367.7  769.41  5381.9  769.83
  5396.0  768.24  5438.4  773.35  5466.7  779.40  5509.2  783.65  5565.7  787.62
#Mann=4,-1,0
  4888.2    0.12       0  5011.0    0.07       0  5017.3    0.12       0
  5340.8    0.05       0
Bank Sta=5011,5017.3
Exp/Cntr=0.3,0.1

Type RM Length L Ch R = 1,5744,656,656,656
BEGIN DESCRIPTION:
Mapping XS cae63023
END DESCRIPTION:
XS GIS Cut Line= 3
      2308567.83      7150042.81      2308359.30      7150108.73
      2307880.27      7150536.30
#Sta/Elev= 30
  4411.9  800.75  4434.3  798.20  4473.6  796.34  4482.2  793.83  4487.4  796.43
  4514.5  786.82  4519.8  787.85  4526.0  784.01  4552.1  778.27  4568.0  772.04
  4584.4  770.44  4589.6  766.71  4609.9  762.49  4667.3  768.89  4702.4  760.38
  4709.9  760.61  4724.1  767.32  4738.2  768.83  4830.3  766.91  4858.7  769.15
  4886.3  765.93  4945.4  766.15  4982.6  757.61  4983.6  757.11  4989.1  757.61
  5000.0  768.00  5020.9  776.59  5042.7  780.69  5085.3  784.06  5272.7  788.62
#Mann=5,-1,0
  4411.9    0.05       0  4434.3    0.12       0  4945.4    0.05       0
  4982.6   0.033       0  4989.1    0.05       0
Bank Sta=4982.6,4989.1
Exp/Cntr=0.3,0.1

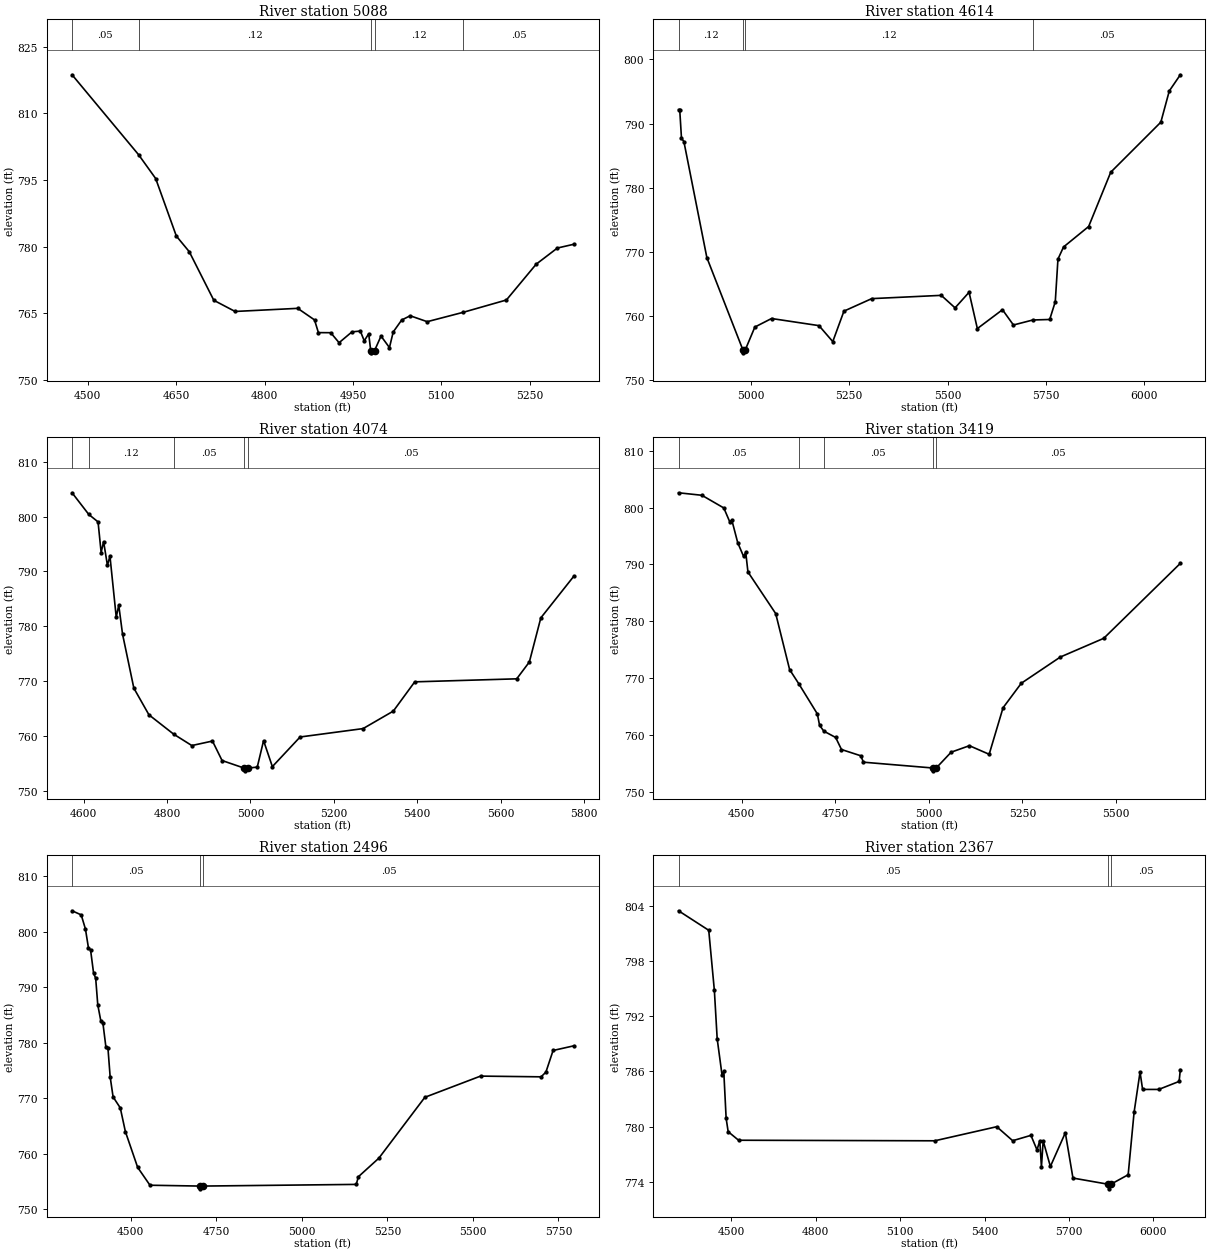
Type RM Length L Ch R = 1,5088,474,474,474
BEGIN DESCRIPTION:
Unnamed 48 11.0
END DESCRIPTION:
XS GIS Cut Line= 3
      2308329.01      7149559.99      2307979.00      7149960.00
      2307778.99      7150210.01
#Sta/Elev= 30
  4473.3  818.68  4586.3  800.68  4615.2  795.34  4650.3  782.39  4672.2  778.88
  4713.9  767.94  4750.0  765.43  4856.3  766.13  4884.8  763.53  4891.4  760.67
  4912.3  760.65  4926.5  758.40  4948.4  760.84  4962.6  761.02  4969.2  758.82
  4976.8  760.41  4980.2  756.62  4981.3  756.12  4986.7  756.62  4997.7  759.89
  5012.0  757.30  5018.4  760.82  5032.8  763.51  5047.2  764.46  5076.1  763.13
  5137.5  765.25  5210.5  768.01  5261.0  776.06  5297.0  779.70  5325.0  780.55
#Mann=5,-1,0
  4473.3    0.05       0  4586.3    0.12       0  4980.2    0.07       0
  4986.7    0.12       0  5137.5    0.05       0
Bank Sta=4980.2,4986.7
Exp/Cntr=0.3,0.1

Type RM Length L Ch R = 1,4614,540,540,540
BEGIN DESCRIPTION:
Unnamed 48 10.0
END DESCRIPTION:
XS GIS Cut Line= 3
      2307929.03      7149459.98      2307779.00      7149560.00
      2307029.00      7150360.00
#Sta/Elev= 30
  4815.5  792.19  4818.5  792.19  4823.0  787.72  4829.1  787.21  4887.6  769.11
  4979.0  754.77  4980.1  754.27  4985.6  754.77  5009.7  758.29  5052.2  759.62
  5172.9  758.51  5208.0  756.02  5236.4  760.77  5307.2  762.72  5484.0  763.23
  5519.2  761.28  5554.8  763.71  5575.9  758.05  5639.8  760.99  5667.7  758.61
  5717.1  759.39  5760.0  759.47  5774.2  762.24  5781.0  768.88  5795.2  770.77
  5859.1  773.96  5915.3  782.42  6042.8  790.22  6064.3  795.09  6092.4  797.61
#Mann=4,-1,0
  4815.5    0.12       0  4979.0    0.07       0  4985.6    0.12       0
  5717.1    0.05       0
Bank Sta=4979,4985.6
Exp/Cntr=0.3,0.1

Type RM Length L Ch R = 1,4074,655,655,655
BEGIN DESCRIPTION:
Mapping XS 501a70af
END DESCRIPTION:
XS GIS Cut Line= 2
      2307691.26      7149176.30      2306682.55      7149831.83
#Sta/Elev= 30
  4572.4  804.34  4612.4  800.40  4634.7  799.03  4642.1  793.45  4648.0  795.44
  4657.2  791.10  4663.2  792.82  4678.3  781.66  4684.3  783.85  4693.4  778.58
  4720.5  768.73  4756.7  763.87  4815.9  760.35  4859.5  758.27  4909.0  759.09
  4932.0  755.54  4984.9  754.16  4986.1  753.66  4993.8  754.16  5016.4  754.34
  5031.5  759.16  5052.6  754.43  5119.1  759.83  5270.1  761.36  5342.6  764.55
  5393.9  769.88  5638.4  770.43  5668.7  773.50  5696.2  781.54  5775.4  789.14
#Mann=5,-1,0
  4572.4    0.05       0  4612.4    0.12       0  4815.9    0.05       0
  4984.9   0.033       0  4993.8    0.05       0
Bank Sta=4984.9,4993.8
Exp/Cntr=0.3,0.1

Type RM Length L Ch R = 1,3419,923,923,923
BEGIN DESCRIPTION:
Mapping XS 2c450e9f
END DESCRIPTION:
XS GIS Cut Line= 2
      2307488.92      7148654.06      2306332.47      7149333.16
#Sta/Elev= 30
  4330.8  802.60  4393.2  802.16  4451.8  799.93  4467.5  797.52  4473.3  797.78
  4489.0  793.82  4504.6  791.42  4510.4  792.12  4516.3  788.68  4590.5  781.36
  4627.7  771.51  4652.1  769.03  4701.8  763.72  4707.7  761.72  4719.1  760.69
  4750.7  759.58  4766.3  757.46  4817.8  756.36  4825.0  755.23  5010.4  754.21
  5011.7  753.71  5019.5  754.21  5059.4  756.99  5108.2  758.13  5161.0  756.62
  5198.1  764.80  5246.9  769.11  5351.2  773.72  5467.2  777.01  5671.9  790.19
#Mann=5,-1,0
  4330.8    0.05       0  4652.1    0.12       0  4719.1    0.05       0
  5010.4   0.033       0  5019.5    0.05       0
Bank Sta=5010.4,5019.5
Exp/Cntr=0.3,0.1

Type RM Length L Ch R = 1,2496,129,129,129
BEGIN DESCRIPTION:
Mapping XS aa1384ac
END DESCRIPTION:
XS GIS Cut Line= 4
      2307151.12      7147836.28      2306859.75      7148034.09
      2306365.84      7148301.48      2305959.45      7148676.20
#Sta/Elev= 30
  4328.4  803.80  4355.1  803.06  4367.5  800.51  4376.4  797.06  4382.4  796.78
  4391.3  792.55  4397.4  791.65  4403.5  786.86  4412.3  783.99  4418.4  783.64
  4427.3  779.23  4433.3  779.02  4439.7  773.88  4448.3  770.25  4469.3  768.27
  4484.2  764.00  4520.1  757.55  4556.1  754.33  4701.9  754.18  4703.3  753.68
  4711.4  754.18  5159.0  754.48  5165.2  755.86  5225.1  759.21  5359.5  770.18
  5522.2  774.00  5699.2  773.87  5713.3  774.72  5734.3  778.62  5795.0  779.46
#Mann=3,-1,0
  4328.4    0.05       0  4701.9   0.033       0  4711.4    0.05       0
Bank Sta=4701.9,4711.4
Exp/Cntr=0.3,0.1

Type RM Length L Ch R = 1,2367,147,147,147
BEGIN DESCRIPTION:
Mapping XS f5877496
END DESCRIPTION:
XS GIS Cut Line= 6
      2307196.24      7147790.44      2307040.01      7147794.00
      2306242.57      7148246.14      2306071.49      7148273.89
      2306024.48      7148301.20      2305773.00      7148710.62
#Sta/Elev= 30
  4312.8  803.44  4420.1  801.32  4440.1  794.78  4450.1  789.53  4467.1  785.65
  4473.5  785.99  4481.9  780.89  4489.1  779.44  4526.1  778.51  5223.0  778.45
  5443.2  779.98  5499.8  778.46  5564.6  779.04  5586.2  777.46  5596.1  778.46
  5601.9  775.62  5608.1  778.44  5633.7  775.66  5686.8  779.32  5713.9  774.40
  5839.0  773.73  5840.3  773.23  5848.5  773.73  5910.0  774.76  5931.1  781.56
  5952.2  785.91  5961.3  784.03  6018.6  784.03  6091.0  784.90  6095.3  786.18
#Mann=3,-1,0
  4312.8    0.05       0  5839.0   0.033       0  5848.5    0.05       0
Bank Sta=5839,5848.5
Exp/Cntr=0.3,0.1

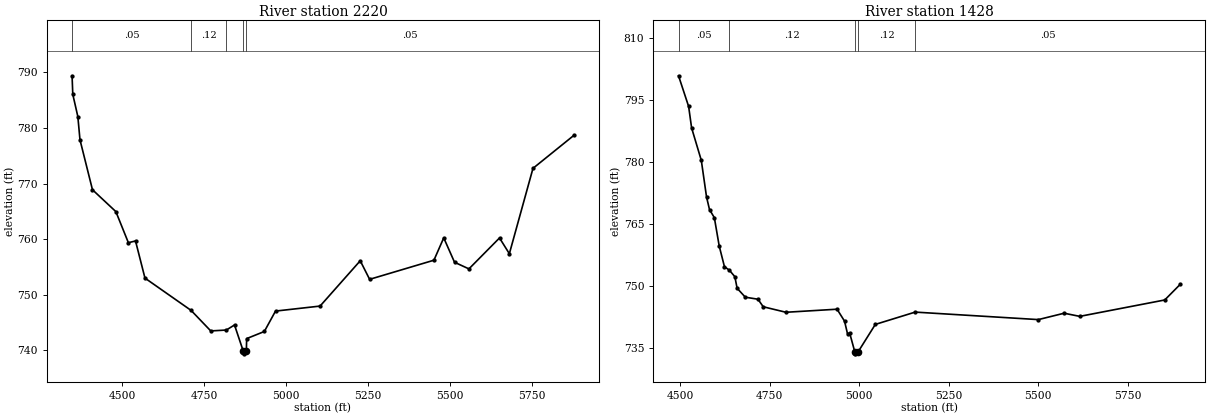
Type RM Length L Ch R = 1,2220,792,792,792
BEGIN DESCRIPTION:
Mapping XS 5b1154a6
END DESCRIPTION:
XS GIS Cut Line= 5
      2307144.45      7147603.12      2306786.93      7147796.60
      2306396.05      7148007.69      2305997.23      7147827.74
      2305796.93      7147961.95
#Sta/Elev= 30
  4347.3  789.38  4349.5  786.04  4364.9  782.04  4371.4  777.87  4409.5  768.88
  4480.8  764.95  4518.9  759.36  4540.7  759.67  4569.5  752.99  4710.1  747.18
  4770.0  743.49  4817.4  743.65  4842.4  744.56  4869.0  739.87  4870.4  739.37
  4878.5  739.87  4879.4  742.11  4933.3  743.39  4967.4  747.06  5103.2  747.96
  5225.6  756.11  5254.2  752.77  5450.2  756.21  5480.1  760.23  5513.0  755.84
  5556.9  754.65  5650.1  760.21  5680.1  757.38  5752.1  772.73  5876.7  778.66
#Mann=5,-1,0
  4347.3    0.05       0  4710.1    0.12       0  4817.4    0.05       0
  4869.0    0.04       0  4878.5    0.05       0
Bank Sta=4869,4878.5
Exp/Cntr=0.3,0.1

Type RM Length L Ch R = 1,1428,0,0,0
BEGIN DESCRIPTION:
Unnamed 48 3.0
END DESCRIPTION:
XS GIS Cut Line= 3
      2307179.02      7147560.02      2306779.00      7147260.00
      2306029.02      7147759.99
#Sta/Elev= 30
  4495.8  800.84  4524.0  793.43  4532.3  788.25  4559.4  780.41  4574.0  771.57
  4582.3  768.52  4595.8  766.58  4609.4  759.72  4624.0  754.74  4638.0  753.86
  4653.1  752.31  4659.4  749.52  4682.3  747.36  4717.7  746.87  4732.3  745.05
  4795.8  743.72  4938.5  744.46  4959.4  741.58  4967.7  738.53  4974.0  738.63
  4988.0  734.18  4989.3  733.68  4997.5  734.18  5045.4  740.79  5156.7  743.76
  5500.6  741.95  5572.7  743.49  5616.3  742.73  5853.7  746.69  5897.2  750.49
#Mann=5,-1,0
  4495.8    0.05       0  4638.0    0.12       0  4988.0    0.07       0
  4997.5    0.12       0  5156.7    0.05       0
Bank Sta=4988,4997.5
Exp/Cntr=0.3,0.1

Chan Stop Cuts=-1