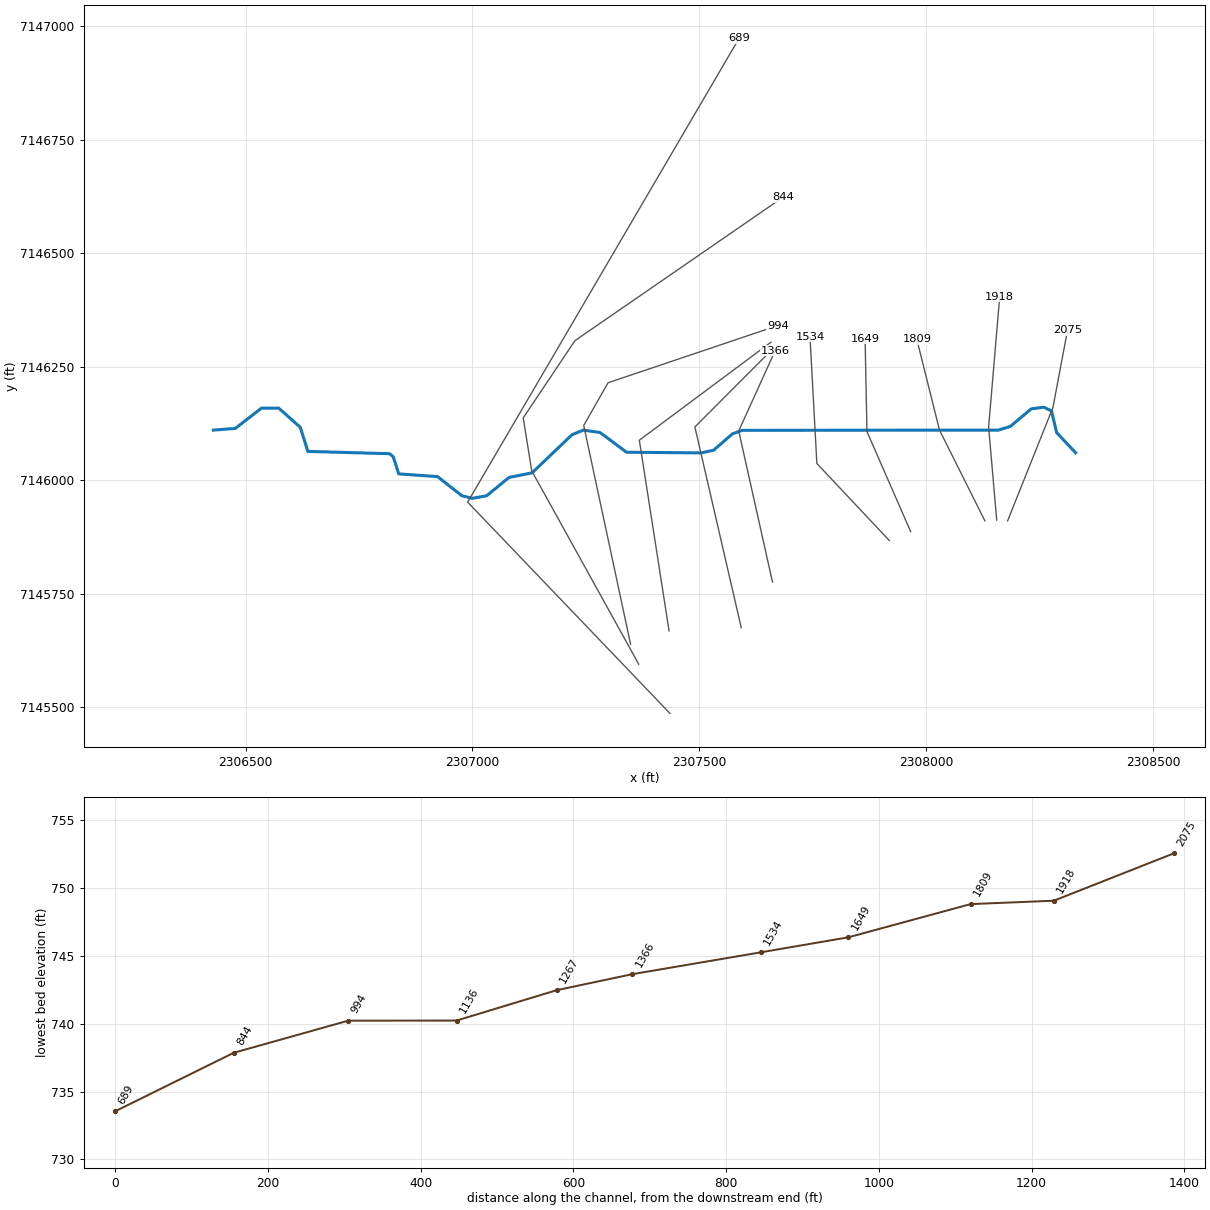
--- Unnamed 48 Trib 1.prj (project) ---

Proj Title=Unnamed 48 Trib 1 Base Level Engineering
Current Plan=p01
Default Exp/Contr=0.3,0.1
English Units
Geom File=g01
Flow File=f01
Plan File=p01
BEGIN DESCRIPTION:
Unnamed 48 Trib 1
END DESCRIPTION:

--- Unnamed 48 Trib 1.p01 (plan) ---

Plan Title=Multiple Run
Short Identifier=Multiple
Geom File=g01
Flow File=f01
Subcritical Flow
K Sum by GR= 0
Std Step Tol= 0.01
Critical Tol= 0.01
Num of Std Step Trials= 20
Max Error Tol= 0.3
Flow Tol Ratio= 0.001
Split Flow NTrial= 30
Split Flow Tol= 0.02
Split Flow Ratio= 0.02
Log Output Level= 0
Friction Slope Method= 1
Unsteady Friction Slope Method= 2
Unsteady Bridges Friction Slope Method= 1
Parabolic Critical Depth
Global Vel Dist=  1 , 1 , 1
Global Log Level= 0
CheckData=True
Encroach Param= -1, 0, 0, 0
BEGIN DESCRIPTION:
Multiple Run
END DESCRIPTION:

--- Unnamed 48 Trib 1.f01 (steady flow) ---

Flow Title=Multiple
Number of Profiles=7
Profile Names=10-year,25-year,50-year,1pct_min,100-year,1pct_plu,500-year
River Rch & RM= Unnamed 48 Trib ,Reach-1,2075
     517     708     867     528    1054    2103    1561
River Rch & RM= Unnamed 48 Trib ,Reach-1,1267
     566     780     959     587    1171    2337    1747
Boundary for River Rch & Prof#=Unnamed 48 Trib ,Reach-1,1
Up Type=0
Dn Type=3
Dn Slope=0.02
Boundary for River Rch & Prof#=Unnamed 48 Trib ,Reach-1,2
Up Type=0
Dn Type=3
Dn Slope=0.02
Boundary for River Rch & Prof#=Unnamed 48 Trib ,Reach-1,3
Up Type=0
Dn Type=3
Dn Slope=0.02
Boundary for River Rch & Prof#=Unnamed 48 Trib ,Reach-1,4
Up Type=0
Dn Type=3
Dn Slope=0.02
Boundary for River Rch & Prof#=Unnamed 48 Trib ,Reach-1,5
Up Type=0
Dn Type=3
Dn Slope=0.02
Boundary for River Rch & Prof#=Unnamed 48 Trib ,Reach-1,6
Up Type=0
Dn Type=3
Dn Slope=0.02
Boundary for River Rch & Prof#=Unnamed 48 Trib ,Reach-1,7
Up Type=0
Dn Type=3
Dn Slope=0.02

--- Unnamed 48 Trib 1.g01 (geometry) ---

Geom Title=Existing Conditions

River Reach=Unnamed 48 Trib ,Reach-1
Reach XY= 30
      2308329.00      7146060.00      2308287.12      7146104.44
      2308275.69      7146152.51      2308258.70      7146160.39
      2308231.10      7146156.82      2308185.12      7146118.20
      2308158.99      7146110.09      2307594.22      7146109.48
      2307572.94      7146101.86      2307531.33      7146065.75
      2307504.08      7146059.80      2307339.50      7146061.24
      2307281.17      7146104.65      2307244.34      7146110.04
      2307219.32      7146099.79      2307131.29      7146015.84
      2307080.74      7146005.75      2307031.20      7145965.34
      2306999.18      7145959.71      2306976.82      7145965.37
      2306922.95      7146007.59      2306837.50      7146013.56
      2306825.42      7146051.42      2306817.03      7146058.04
      2306637.31      7146063.10      2306620.81      7146116.08
      2306573.15      7146158.46      2306535.13      7146158.41
      2306477.51      7146113.69      2306429.00      7146110.00

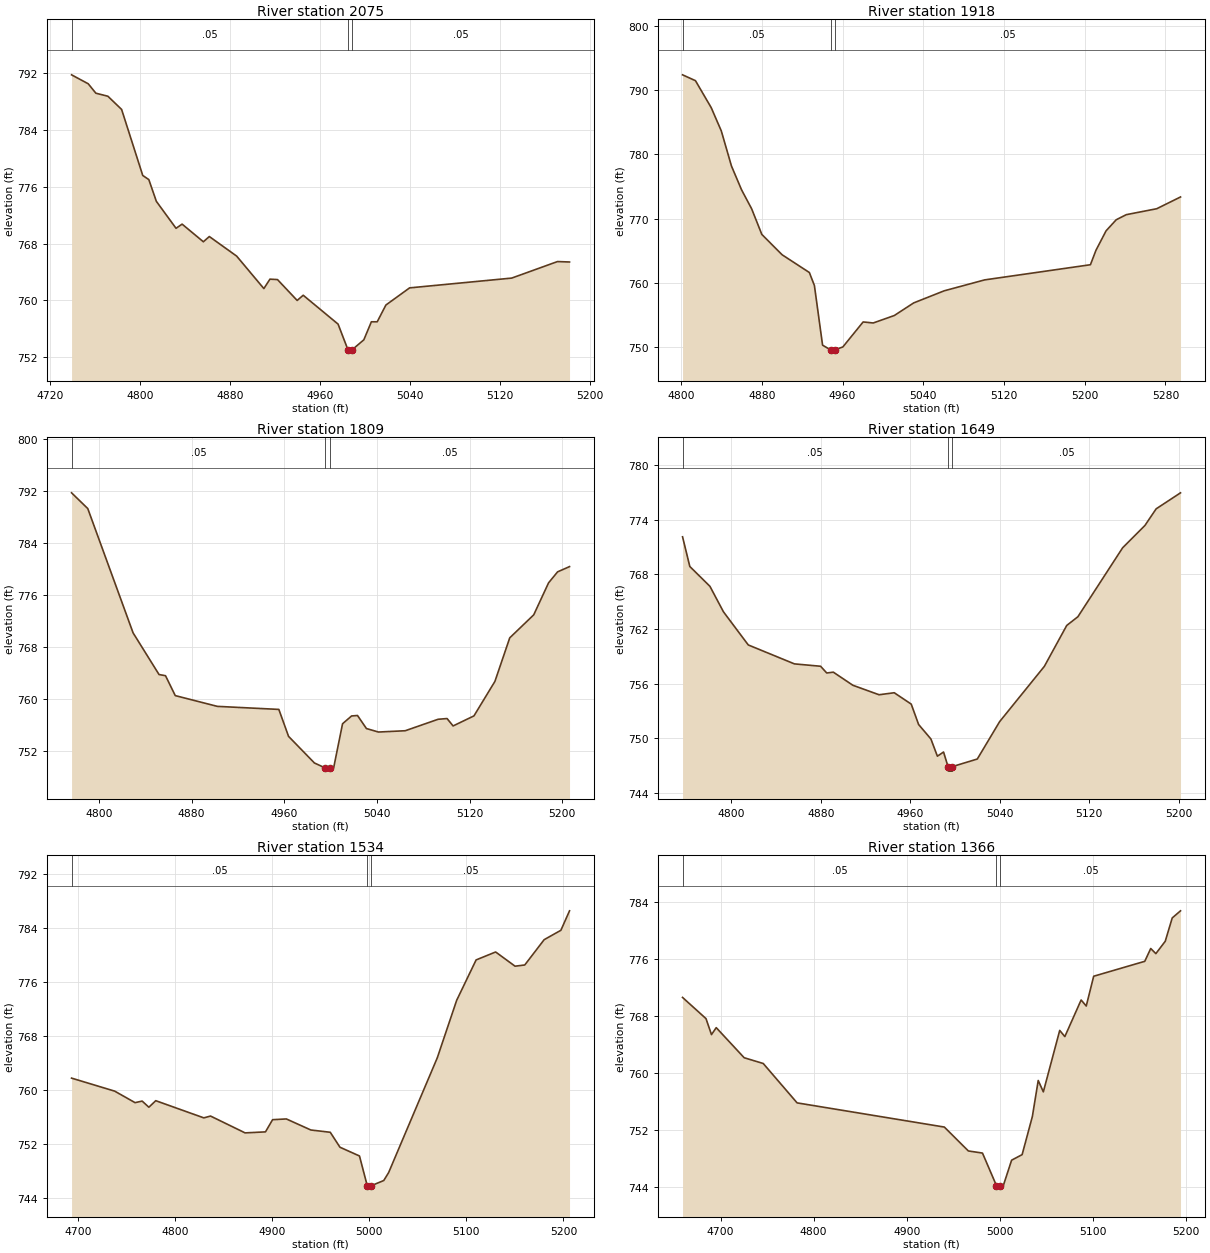
Type RM Length L Ch R = 1,2075,157,157,157
BEGIN DESCRIPTION:
Unnamed 48 Trib 1 3.0
END DESCRIPTION:
XS GIS Cut Line= 3
      2308178.99      7145909.97      2308279.00      7146160.00
      2308311.14      7146330.51
#Sta/Elev= 30
  4739.2  791.81  4754.0  790.55  4760.8  789.22  4771.5  788.79  4783.7  786.93
  4802.5  777.62  4807.9  777.04  4814.6  773.97  4832.1  770.17  4837.5  770.76
  4856.4  768.27  4861.7  769.01  4886.0  766.25  4910.2  761.67  4915.6  763.00
  4922.3  762.94  4939.8  760.00  4945.2  760.73  4976.2  756.66  4984.9  753.07
  4985.2  752.57  4988.9  753.07  4999.1  754.45  5005.8  756.99  5011.0  756.99
  5018.7  759.35  5039.8  761.77  5130.6  763.15  5171.3  765.48  5182.0  765.42
#Mann=3,-1,0
  4739.2    0.05       0  4984.9   0.033       0  4988.9    0.05       0
Bank Sta=4984.9,4988.9
Exp/Cntr=0.3,0.1

Type RM Length L Ch R = 1,1918,109,109,109
BEGIN DESCRIPTION:
Mapping XS f7261ce3
END DESCRIPTION:
XS GIS Cut Line= 3
      2308155.06      7145911.71      2308137.23      7146116.61
      2308161.61      7146403.50
#Sta/Elev= 30
  4801.4  792.37  4814.2  791.46  4829.8  787.27  4839.8  783.65  4849.9  778.18
  4859.9  774.48  4869.9  771.53  4880.0  767.54  4900.1  764.38  4927.1  761.62
  4932.1  759.60  4940.2  750.32  4948.2  749.58  4948.5  749.08  4952.0  749.08
  4952.2  749.58  4960.3  750.04  4980.4  753.93  4990.4  753.77  5011.3  754.93
  5030.5  756.89  5060.7  758.77  5100.8  760.47  5205.7  762.83  5211.2  765.08
  5221.2  768.10  5231.3  769.83  5241.3  770.62  5271.4  771.54  5295.0  773.37
#Mann=3,-1,0
  4801.4    0.05       0  4948.2   0.033       0  4952.2    0.05       0
Bank Sta=4948.2,4952.2
Exp/Cntr=0.3,0.1

Type RM Length L Ch R = 1,1809,160,160,160
BEGIN DESCRIPTION:
Unnamed 48 Trib 1 2.0
END DESCRIPTION:
XS GIS Cut Line= 3
      2308129.01      7145909.99      2308029.00      7146110.00
      2307978.99      7146310.02
#Sta/Elev= 30
  4776.4  791.76  4790.4  789.33  4829.5  770.16  4851.9  763.73  4857.5  763.55
  4865.9  760.48  4902.2  758.82  4955.3  758.35  4963.7  754.19  4986.0  750.09
  4995.2  749.33  4995.5  748.83  4999.2  749.33  5002.6  749.33  5010.3  756.14
  5018.1  757.34  5023.2  757.41  5030.9  755.40  5041.3  754.86  5064.4  755.06
  5092.8  756.83  5100.5  756.94  5105.7  755.80  5123.7  757.35  5141.8  762.67
  5154.6  769.39  5175.3  772.94  5188.1  777.87  5195.9  779.57  5206.2  780.38
#Mann=3,-1,0
  4776.4    0.05       0  4995.2   0.033       0  4999.2    0.05       0
Bank Sta=4995.2,4999.2
Exp/Cntr=0.3,0.1

Type RM Length L Ch R = 1,1649,115,115,115
BEGIN DESCRIPTION:
Mapping XS 95ff88a0
END DESCRIPTION:
XS GIS Cut Line= 3
      2307965.47      7145886.43      2307869.17      7146106.79
      2307865.05      7146311.77
#Sta/Elev= 30
  4756.3  772.12  4762.8  768.86  4780.8  766.68  4792.9  763.88  4815.1  760.24
  4856.4  758.16  4879.8  757.90  4885.3  757.16  4891.2  757.25  4908.7  755.81
  4932.1  754.77  4945.7  754.99  4960.9  753.74  4967.5  751.50  4978.5  749.91
  4984.3  748.02  4989.8  748.48  4993.8  746.88  4994.1  746.38  4997.6  746.38
  4997.8  746.88  5020.0  747.71  5040.0  751.82  5080.0  757.89  5100.0  762.38
  5110.0  763.34  5150.0  770.91  5170.0  773.37  5180.0  775.19  5201.8  776.95
#Mann=3,-1,0
  4756.3    0.05       0  4993.8   0.033       0  4997.8    0.05       0
Bank Sta=4993.8,4997.8
Exp/Cntr=0.3,0.1

Type RM Length L Ch R = 1,1534,168,168,168
BEGIN DESCRIPTION:
Mapping XS 8fd74352
END DESCRIPTION:
XS GIS Cut Line= 3
      2307918.31      7145866.85      2307758.80      7146036.51
      2307743.64      7146316.03
#Sta/Elev= 30
  4693.5  761.75  4737.9  759.82  4758.9  758.11  4766.2  758.34  4773.1  757.43
  4780.2  758.40  4829.7  755.85  4836.6  756.12  4872.2  753.62  4893.2  753.77
  4900.5  755.58  4914.7  755.69  4939.9  754.05  4959.9  753.71  4969.9  751.49
  4990.0  750.19  4998.0  745.77  4998.2  745.27  5002.0  745.77  5015.0  746.55
  5020.0  747.72  5070.1  764.76  5090.1  773.31  5110.1  779.30  5130.2  780.48
  5150.2  778.37  5160.2  778.55  5180.2  782.31  5197.4  783.70  5206.3  786.59
#Mann=3,-1,0
  4693.5    0.05       0  4998.0   0.033       0  5002.0    0.05       0
Bank Sta=4998,5002
Exp/Cntr=0.3,0.1

Type RM Length L Ch R = 1,1366,99,99,99
BEGIN DESCRIPTION:
Mapping XS 0878d8e5
END DESCRIPTION:
XS GIS Cut Line= 3
      2307660.97      7145775.43      2307586.63      7146108.19
      2307666.87      7146284.97
#Sta/Elev= 30
  4659.1  770.62  4684.3  767.64  4690.2  765.39  4695.3  766.37  4725.3  762.14
  4745.8  761.33  4782.2  755.79  4940.4  752.39  4966.2  749.03  4981.4  748.73
  4996.4  744.16  4996.7  743.66  5000.4  744.16  5003.8  744.16  5012.7  747.73
  5024.0  748.51  5035.0  753.87  5041.3  758.94  5046.8  757.34  5064.4  765.98
  5069.9  765.11  5087.4  770.26  5092.9  769.41  5100.9  773.60  5155.8  775.70
  5162.2  777.50  5167.7  776.78  5177.8  778.52  5185.3  781.80  5194.2  782.80
#Mann=3,-1,0
  4659.1    0.05       0  4996.4   0.033       0  5000.4    0.05       0
Bank Sta=4996.4,5000.4
Exp/Cntr=0.3,0.1

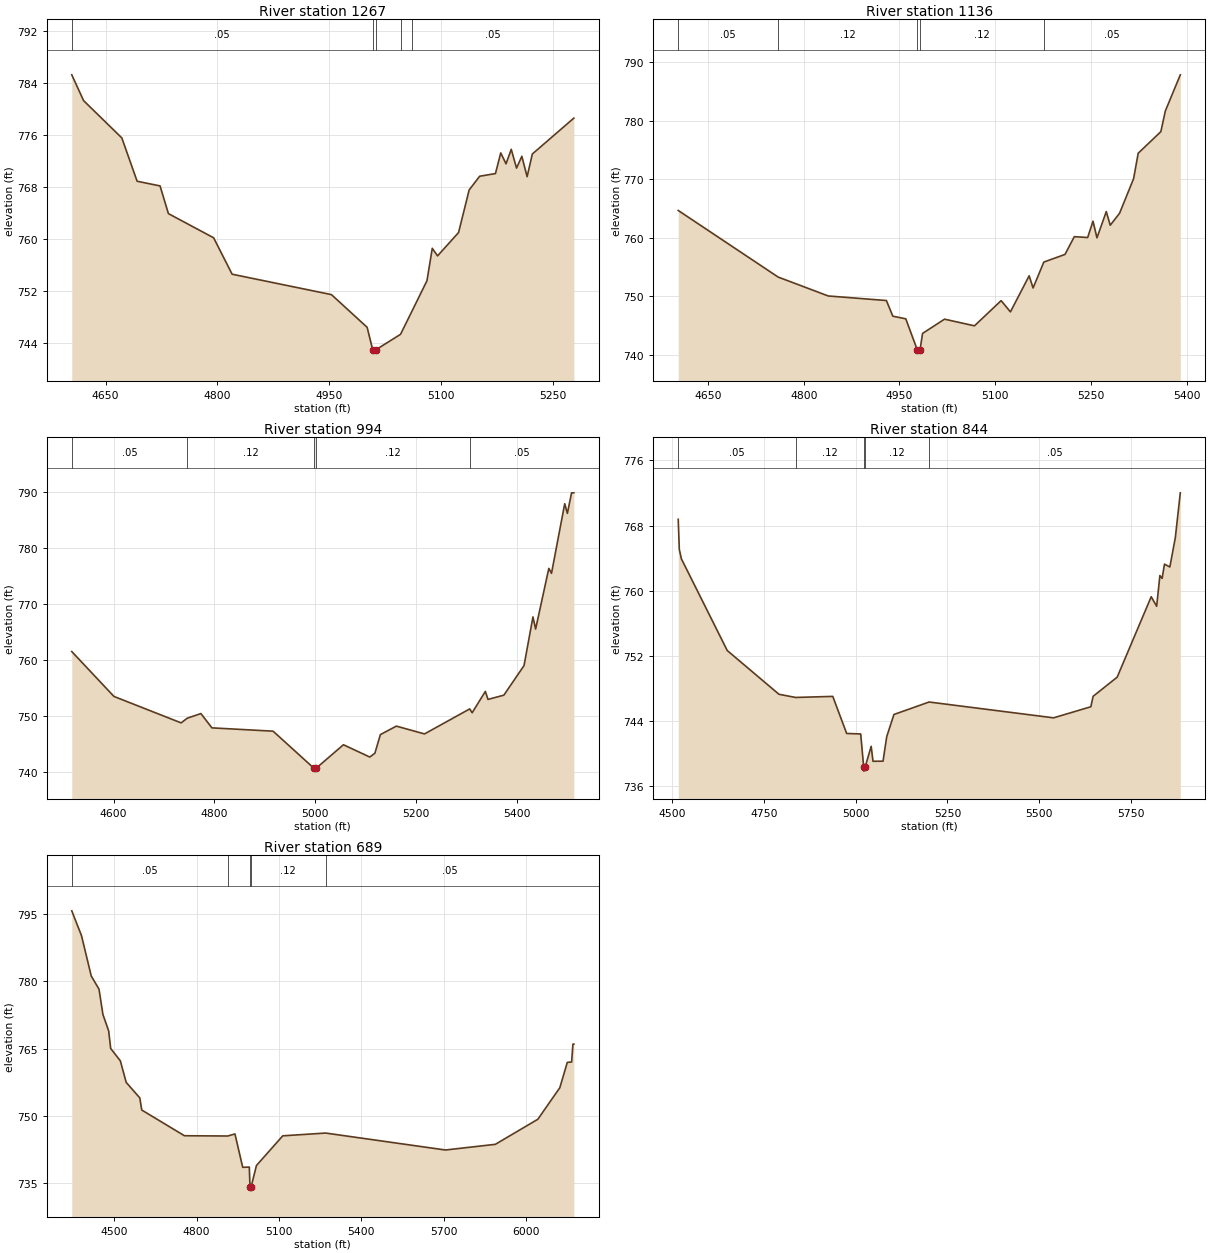
Type RM Length L Ch R = 1,1267,131,131,131
BEGIN DESCRIPTION:
Mapping XS 748d461c
END DESCRIPTION:
XS GIS Cut Line= 3
      2307592.23      7145674.51      2307490.05      7146116.95
      2307645.21      7146272.52
#Sta/Elev= 30
  4604.6  785.29  4620.5  781.32  4671.8  775.58  4692.3  768.92  4723.1  768.20
  4734.3  763.94  4795.0  760.22  4819.8  754.62  4953.1  751.48  5001.0  746.45
  5008.5  742.98  5008.7  742.48  5012.5  742.98  5045.8  745.37  5060.9  748.87
  5081.3  753.62  5088.4  758.60  5095.5  757.44  5123.7  761.03  5137.9  767.58
  5152.0  769.69  5173.2  770.10  5180.3  773.28  5187.4  771.60  5194.4  773.83
  5201.5  770.94  5208.6  772.76  5215.7  769.62  5222.7  773.11  5278.4  778.63
#Mann=5,-1,0
  4604.6    0.05       0  5008.5   0.033       0  5012.5    0.05       0
  5045.8    0.12       0  5060.9    0.05       0
Bank Sta=5008.5,5012.5
Exp/Cntr=0.3,0.1

Type RM Length L Ch R = 1,1136,142,142,142
BEGIN DESCRIPTION:
Mapping XS febf47fe
END DESCRIPTION:
XS GIS Cut Line= 3
      2307433.19      7145667.70      2307367.67      7146087.75
      2307657.73      7146303.77
#Sta/Elev= 30
  4603.4  764.65  4759.9  753.26  4838.5  750.02  4929.6  749.24  4939.7  746.56
  4960.0  746.11  4978.2  740.74  4978.5  740.24  4982.2  740.74  4986.3  743.61
  5020.7  746.05  5067.6  744.91  5109.4  749.22  5124.0  747.30  5153.3  753.47
  5159.5  751.39  5176.3  755.82  5209.5  757.13  5224.1  760.17  5245.0  760.02
  5253.4  762.81  5259.6  759.97  5274.2  764.46  5280.4  762.13  5295.0  764.17
  5317.0  770.09  5324.2  774.44  5359.7  778.14  5366.8  781.69  5390.2  787.86
#Mann=5,-1,0
  4603.4    0.05       0  4759.9    0.12       0  4978.2    0.07       0
  4982.2    0.12       0  5176.3    0.05       0
Bank Sta=4978.2,4982.2
Exp/Cntr=0.3,0.1

Type RM Length L Ch R = 1,994,150,150,150
BEGIN DESCRIPTION:
Mapping XS d4411157
END DESCRIPTION:
XS GIS Cut Line= 4
      2307348.42      7145638.17      2307245.14      7146120.22
      2307298.69      7146214.29      2307672.60      7146340.29
#Sta/Elev= 30
  4517.2  761.54  4600.9  753.54  4734.1  748.83  4746.2  749.66  4773.3  750.49
  4795.2  747.94  4916.5  747.35  4997.7  740.73  4998.0  740.23  5001.7  740.73
  5056.0  744.93  5108.3  742.74  5118.4  743.42  5129.3  746.74  5161.0  748.25
  5216.8  746.86  5306.5  751.32  5311.3  750.63  5337.5  754.44  5342.7  753.01
  5374.2  753.77  5414.2  759.04  5431.9  767.71  5437.2  765.55  5463.4  776.37
  5468.7  775.48  5494.9  787.89  5500.2  786.17  5508.5  789.83  5513.0  789.83
#Mann=5,-1,0
  4517.2    0.05       0  4746.2    0.12       0  4997.7    0.07       0
  5001.7    0.12       0  5306.5    0.05       0
Bank Sta=4997.7,5001.7
Exp/Cntr=0.3,0.1

Type RM Length L Ch R = 1,844,155,155,155
BEGIN DESCRIPTION:
Mapping XS fae3b938
END DESCRIPTION:
XS GIS Cut Line= 5
      2307366.35      7145594.21      2307130.55      7146020.31
      2307111.87      7146136.99      2307225.71      7146307.02
      2307684.50      7146623.25
#Sta/Elev= 30
  4517.2  768.76  4520.1  765.07  4525.8  763.91  4650.6  752.66  4791.5  747.29
  4836.8  746.90  4938.0  747.03  4975.8  742.48  5014.0  742.42  5022.1  738.36
  5022.4  737.86  5026.1  738.36  5042.5  740.91  5047.5  739.07  5074.8  739.08
  5084.9  742.10  5104.5  744.81  5200.2  746.34  5539.2  744.40  5640.6  745.76
  5646.8  747.04  5712.3  749.39  5805.0  759.26  5819.8  758.09  5828.6  761.86
  5834.7  761.51  5841.1  763.26  5855.7  762.91  5870.6  766.50  5884.2  772.01
#Mann=5,-1,0
  4517.2    0.05       0  4836.8    0.12       0  5022.1    0.07       0
  5026.1    0.12       0  5200.2    0.05       0
Bank Sta=5022.1,5026.1
Exp/Cntr=0.3,0.1

Type RM Length L Ch R = 1,689,0,0,0
BEGIN DESCRIPTION:
Unnamed 48 Trib 1 1.0
END DESCRIPTION:
XS GIS Cut Line= 3
      2307435.08      7145485.91      2306989.46      7145951.29
      2307587.42      7146973.17
#Sta/Elev= 30
  4345.5  795.79  4380.9  790.25  4416.4  781.22  4444.7  778.27  4458.9  772.62
  4479.9  768.93  4487.2  765.01  4522.4  762.24  4543.8  757.41  4593.2  753.96
  4600.4  751.24  4755.8  745.49  4913.6  745.43  4939.7  745.89  4968.0  738.43
  4992.0  738.48  4994.5  734.05  4994.7  733.55  4998.5  734.05  5018.0  738.83
  5113.8  745.47  5270.0  746.09  5706.3  742.30  5888.0  743.57  6042.6  749.17
  6122.7  756.22  6150.0  761.90  6165.7  761.98  6170.4  765.98  6173.8  765.98
#Mann=5,-1,0
  4345.5    0.05       0  4913.6    0.12       0  4994.5    0.07       0
  4998.5    0.12       0  5270.0    0.05       0
Bank Sta=4994.5,4998.5
Exp/Cntr=0.3,0.1

Chan Stop Cuts=-1