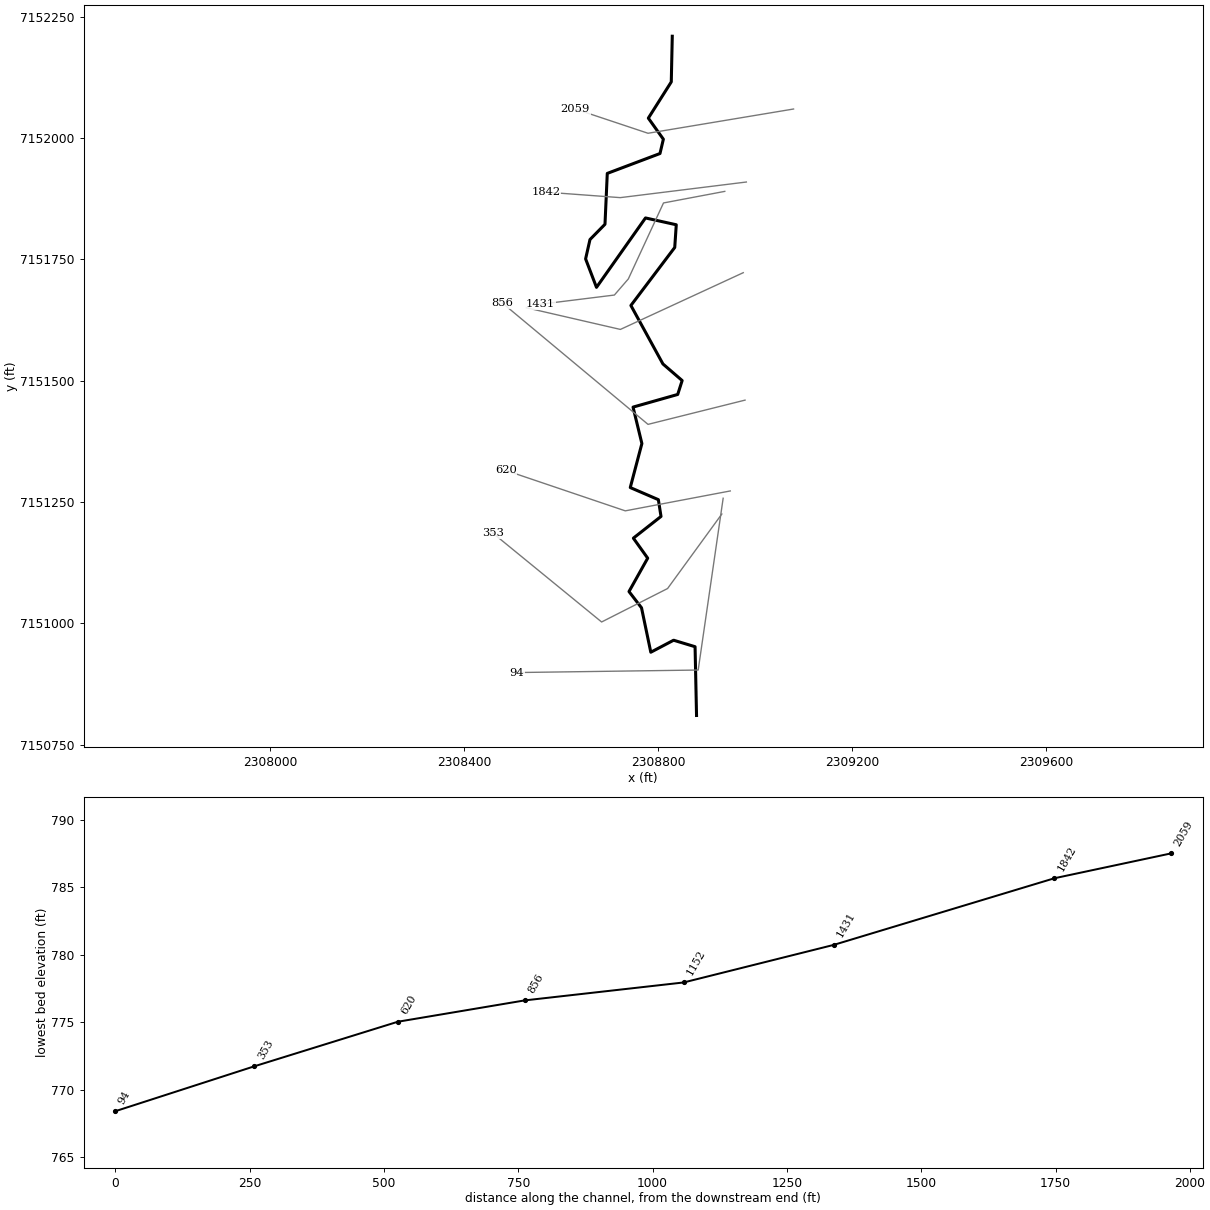
--- Unnamed 48 Trib 3.prj (project) ---

Proj Title=Unnamed 48 Trib 3 Base Level Engineering
Current Plan=p01
Default Exp/Contr=0.3,0.1
English Units
Geom File=g01
Flow File=f01
Plan File=p01
BEGIN DESCRIPTION:
Unnamed 48 Trib 3
END DESCRIPTION:

--- Unnamed 48 Trib 3.p01 (plan) ---

Plan Title=Multiple Run
Short Identifier=Multiple
Geom File=g01
Flow File=f01
Subcritical Flow
K Sum by GR= 0
Std Step Tol= 0.01
Critical Tol= 0.01
Num of Std Step Trials= 20
Max Error Tol= 0.3
Flow Tol Ratio= 0.001
Split Flow NTrial= 30
Split Flow Tol= 0.02
Split Flow Ratio= 0.02
Log Output Level= 0
Friction Slope Method= 1
Unsteady Friction Slope Method= 2
Unsteady Bridges Friction Slope Method= 1
Parabolic Critical Depth
Global Vel Dist=  1 , 1 , 1
Global Log Level= 0
CheckData=True
Encroach Param= -1, 0, 0, 0
BEGIN DESCRIPTION:
Multiple Run
END DESCRIPTION:

--- Unnamed 48 Trib 3.f01 (steady flow) ---

Flow Title=Multiple
Number of Profiles=7
Profile Names=10-year,25-year,50-year,1pct_min,100-year,1pct_plu,500-year
River Rch & RM= Unnamed 48 Trib ,Reach-1,2059
     492     666     810     490     977    1950    1424
Boundary for River Rch & Prof#=Unnamed 48 Trib ,Reach-1,1
Up Type=0
Dn Type=3
Dn Slope=0.005
Boundary for River Rch & Prof#=Unnamed 48 Trib ,Reach-1,2
Up Type=0
Dn Type=3
Dn Slope=0.005
Boundary for River Rch & Prof#=Unnamed 48 Trib ,Reach-1,3
Up Type=0
Dn Type=3
Dn Slope=0.005
Boundary for River Rch & Prof#=Unnamed 48 Trib ,Reach-1,4
Up Type=0
Dn Type=3
Dn Slope=0.005
Boundary for River Rch & Prof#=Unnamed 48 Trib ,Reach-1,5
Up Type=0
Dn Type=3
Dn Slope=0.005
Boundary for River Rch & Prof#=Unnamed 48 Trib ,Reach-1,6
Up Type=0
Dn Type=3
Dn Slope=0.005
Boundary for River Rch & Prof#=Unnamed 48 Trib ,Reach-1,7
Up Type=0
Dn Type=3
Dn Slope=0.005

--- Unnamed 48 Trib 3.g01 (geometry) ---

Geom Title=Existing Conditions

River Reach=Unnamed 48 Trib ,Reach-1
Reach XY= 30
      2308829.00      7152210.00      2308826.93      7152115.86
      2308779.65      7152041.18      2308810.62      7151997.75
      2308803.66      7151968.24      2308695.02      7151927.26
      2308690.31      7151822.46      2308659.38      7151790.96
      2308650.35      7151751.04      2308672.78      7151692.40
      2308773.80      7151835.46      2308837.21      7151821.42
      2308834.07      7151774.63      2308743.71      7151655.06
      2308809.71      7151534.55      2308849.34      7151500.34
      2308840.19      7151471.67      2308748.12      7151445.59
      2308766.36      7151370.46      2308742.39      7151279.78
      2308800.31      7151254.81      2308805.77      7151220.24
      2308748.80      7151175.48      2308778.32      7151134.23
      2308739.78      7151065.43      2308765.59      7151031.94
      2308784.74      7150940.37      2308831.74      7150965.11
      2308875.97      7150951.74      2308879.00      7150810.00

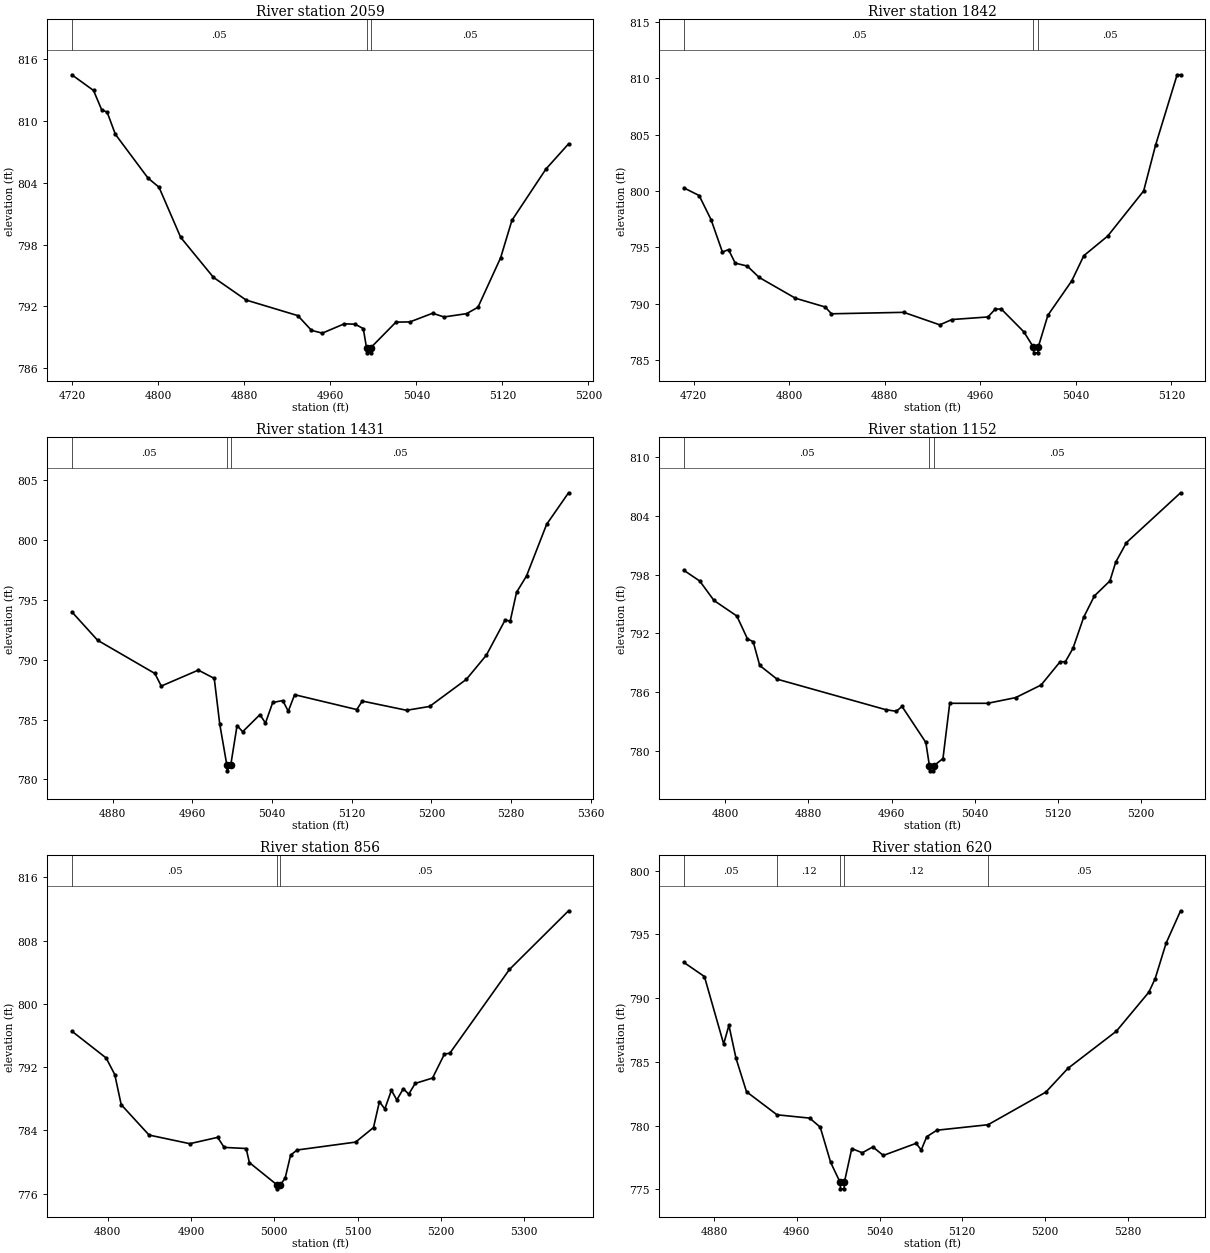
Type RM Length L Ch R = 1,2059,217,217,217
BEGIN DESCRIPTION:
Unnamed 48 Trib 3 4.0
END DESCRIPTION:
XS GIS Cut Line= 3
      2309078.97      7152059.99      2308779.00      7152010.00
      2308629.02      7152059.99
#Sta/Elev= 30
  4719.4  814.47  4739.6  812.95  4747.2  811.07  4752.3  810.84  4759.9  808.70
  4790.3  804.45  4800.5  803.57  4820.7  798.70  4851.2  794.82  4881.6  792.62
  4929.7  791.11  4942.4  789.68  4952.5  789.41  4972.8  790.31  4983.0  790.28
  4990.6  789.85  4993.6  788.00  4993.9  787.50  4997.4  787.50  4997.6  788.00
  5021.0  790.48  5034.0  790.50  5055.1  791.34  5065.7  790.98  5086.7  791.30
  5097.3  791.92  5118.4  796.72  5128.9  800.35  5160.5  805.32  5181.6  807.77
#Mann=3,-1,0
  4719.4    0.05       0  4993.6   0.033       0  4997.6    0.05       0
Bank Sta=4993.6,4997.6
Exp/Cntr=0.3,0.1

Type RM Length L Ch R = 1,1842,411,411,411
BEGIN DESCRIPTION:
Unnamed 48 Trib 3 3.0
END DESCRIPTION:
XS GIS Cut Line= 3
      2308981.67      7151909.52      2308721.73      7151877.33
      2308568.17      7151888.69
#Sta/Elev= 30
  4711.8  800.28  4724.6  799.60  4734.6  797.46  4744.1  794.59  4749.2  794.81
  4754.8  793.61  4764.9  793.35  4774.9  792.34  4805.2  790.50  4830.2  789.72
  4835.4  789.12  4895.9  789.25  4926.1  788.14  4936.2  788.61  4966.4  788.84
  4972.6  789.54  4977.6  789.54  4996.5  787.52  5004.5  786.16  5004.8  785.66
  5008.3  785.66  5008.5  786.16  5016.6  788.99  5036.6  792.04  5046.7  794.27
  5066.7  796.01  5096.8  800.01  5106.8  804.08  5124.8  810.30  5127.7  810.30
#Mann=3,-1,0
  4711.8    0.05       0  5004.5   0.033       0  5008.5    0.05       0
Bank Sta=5004.5,5008.5
Exp/Cntr=0.3,0.1

Type RM Length L Ch R = 1,1431,279,279,279
BEGIN DESCRIPTION:
Mapping XS 051d9398
END DESCRIPTION:
XS GIS Cut Line= 5
      2308937.21      7151890.23      2308810.92      7151866.37
      2308738.41      7151709.77      2308709.67      7151676.56
      2308557.16      7151657.63
#Sta/Elev= 30
  4839.0  793.98  4864.9  791.61  4922.4  788.84  4928.8  787.79  4966.0  789.12
  4982.0  788.43  4987.5  784.63  4994.6  781.22  4994.8  780.72  4998.6  781.22
  5004.9  784.50  5010.5  783.98  5027.9  785.41  5033.4  784.70  5040.7  786.42
  5050.8  786.58  5056.3  785.69  5062.7  787.07  5125.1  785.83  5130.6  786.54
  5175.1  785.77  5198.2  786.09  5235.1  788.35  5255.2  790.37  5274.1  793.31
  5279.1  793.20  5285.5  795.61  5295.5  796.97  5315.7  801.28  5337.7  803.91
#Mann=3,-1,0
  4839.0    0.05       0  4994.6   0.033       0  4998.6    0.05       0
Bank Sta=4994.6,4998.6
Exp/Cntr=0.3,0.1

Type RM Length L Ch R = 1,1152,296,296,296
BEGIN DESCRIPTION:
Mapping XS 76a676dd
END DESCRIPTION:
XS GIS Cut Line= 3
      2308975.30      7151722.65      2308722.06      7151605.70
      2308528.18      7151650.39
#Sta/Elev= 30
  4760.2  798.46  4775.5  797.36  4789.2  795.37  4811.2  793.78  4821.4  791.44
  4826.9  791.16  4833.2  788.72  4849.9  787.32  4954.4  784.20  4964.6  784.03
  4970.1  784.53  4993.0  780.85  4996.5  778.44  4996.8  777.94  5000.3  777.94
  5000.5  778.44  5009.5  779.20  5016.0  784.85  5052.5  784.85  5079.4  785.43
  5103.9  786.72  5122.2  789.10  5127.3  789.11  5134.6  790.48  5144.9  793.66
  5155.2  795.84  5170.1  797.37  5175.7  799.29  5186.0  801.29  5238.1  806.39
#Mann=3,-1,0
  4760.2    0.05       0  4996.5   0.033       0  5000.5    0.05       0
Bank Sta=4996.5,5000.5
Exp/Cntr=0.3,0.1

Type RM Length L Ch R = 1,856,236,236,236
BEGIN DESCRIPTION:
Unnamed 48 Trib 3 2.0
END DESCRIPTION:
XS GIS Cut Line= 3
      2308979.01      7151460.00      2308779.00      7151410.00
      2308478.99      7151660.01
#Sta/Elev= 30
  4756.7  796.55  4797.9  793.16  4808.3  791.06  4816.0  787.26  4849.5  783.41
  4898.4  782.32  4931.9  783.12  4939.7  781.85  4966.1  781.71  4970.0  779.93
  5003.2  777.11  5003.4  776.61  5007.2  777.11  5013.0  777.97  5019.5  780.87
  5027.3  781.52  5097.6  782.52  5119.1  784.36  5126.2  787.63  5132.7  786.71
  5140.6  789.07  5147.1  787.85  5154.9  789.27  5161.4  788.58  5169.2  789.94
  5190.0  790.62  5204.3  793.65  5210.8  793.76  5282.4  804.35  5353.4  811.77
#Mann=3,-1,0
  4756.7    0.05       0  5003.2   0.033       0  5007.2    0.05       0
Bank Sta=5003.2,5007.2
Exp/Cntr=0.3,0.1

Type RM Length L Ch R = 1,620,267,267,267
BEGIN DESCRIPTION:
Mapping XS fef525d4
END DESCRIPTION:
XS GIS Cut Line= 3
      2308948.55      7151272.78      2308732.11      7151231.76
      2308485.73      7151315.12
#Sta/Elev= 30
  4850.7  792.80  4870.6  791.69  4889.2  786.40  4894.3  787.86  4901.1  785.29
  4911.3  782.65  4940.8  780.84  4972.4  780.58  4982.6  779.87  4992.7  777.10
  5001.9  775.53  5002.2  775.03  5005.7  775.03  5005.9  775.53  5013.1  778.19
  5023.3  777.86  5033.5  778.32  5043.6  777.65  5075.3  778.60  5080.3  778.08
  5085.6  779.12  5095.4  779.63  5144.9  780.06  5200.8  782.62  5222.1  784.48
  5269.0  787.40  5300.4  790.46  5306.5  791.52  5317.1  794.31  5331.1  796.85
#Mann=5,-1,0
  4850.7    0.05       0  4940.8    0.12       0  5001.9    0.07       0
  5005.9    0.12       0  5144.9    0.05       0
Bank Sta=5001.9,5005.9
Exp/Cntr=0.3,0.1

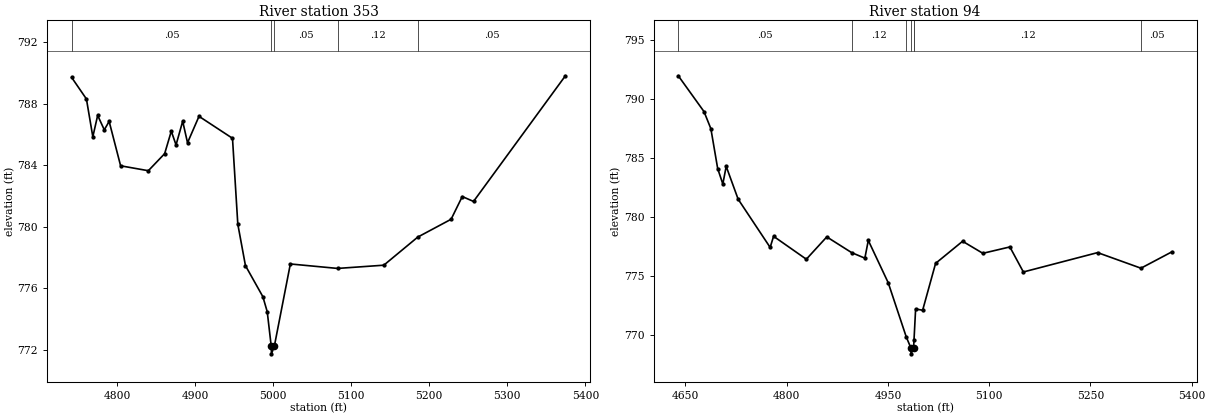
Type RM Length L Ch R = 1,353,259,259,259
BEGIN DESCRIPTION:
Mapping XS 348ffbcb
END DESCRIPTION:
XS GIS Cut Line= 4
      2308931.17      7151225.26      2308819.34      7151071.68
      2308683.36      7151002.71      2308458.84      7151186.18
#Sta/Elev= 30
  4742.0  789.72  4760.9  788.32  4769.1  785.86  4775.3  787.25  4783.8  786.31
  4790.0  786.86  4804.7  783.97  4840.2  783.65  4861.1  784.76  4869.6  786.22
  4875.7  785.33  4884.2  786.87  4890.4  785.47  4905.1  787.19  4948.0  785.76
  4954.8  780.17  4964.6  777.47  4986.9  775.45  4992.5  774.47  4997.6  772.23
  4997.9  771.73  5001.6  772.23  5022.1  777.58  5082.6  777.29  5141.8  777.50
  5185.3  779.33  5228.0  780.49  5242.3  781.97  5256.7  781.65  5374.4  789.83
#Mann=5,-1,0
  4742.0    0.05       0  4997.6    0.05       0  5001.6    0.05       0
  5082.6    0.12       0  5185.3    0.05       0
Bank Sta=4997.6,5001.6
Exp/Cntr=0.3,0.1

Type RM Length L Ch R = 1,94,0,0,0
BEGIN DESCRIPTION:
Unnamed 48 Trib 3 1.0
END DESCRIPTION:
XS GIS Cut Line= 3
      2308933.86      7151257.75      2308882.41      7150903.66
      2308508.85      7150898.49
#Sta/Elev= 30
  4639.4  791.94  4677.5  788.91  4687.7  787.46  4697.8  784.08  4705.4  782.78
  4710.4  784.27  4728.1  781.49  4775.5  777.41  4780.6  778.35  4829.1  776.41
  4859.4  778.30  4896.2  776.97  4915.8  776.50  4920.9  778.00  4950.4  774.42
  4977.2  769.82  4984.0  768.90  4984.2  768.40  4988.0  768.90  4988.6  769.56
  4991.0  772.20  5001.4  772.09  5020.6  776.06  5060.6  777.93  5090.6  776.91
  5130.6  777.45  5150.6  775.33  5260.6  776.97  5324.8  775.65  5370.8  777.04
#Mann=7,-1,0
  4639.4    0.05       0  4896.2    0.12       0  4977.2    0.05       0
  4984.0    0.07       0  4988.0    0.05       0  4988.6    0.12       0
  5324.8    0.05       0
Bank Sta=4984,4988
Exp/Cntr=0.3,0.1

Chan Stop Cuts=-1