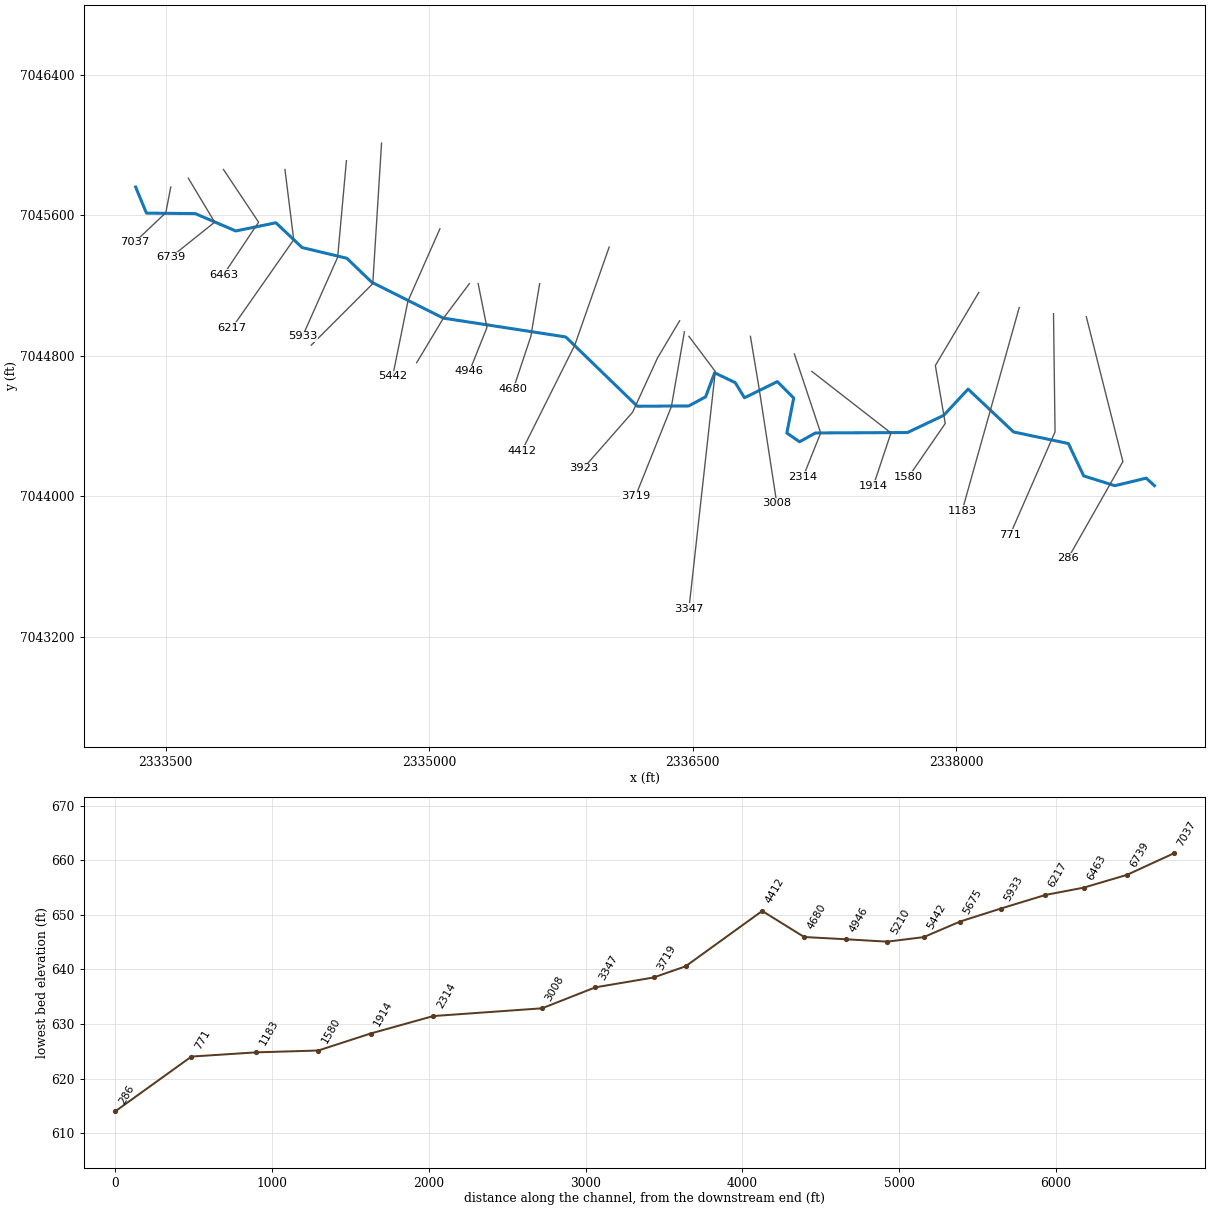
--- Alliance Creek.prj (project) ---

Proj Title=Alliance Creek Base Level Engineering
Current Plan=p01
Default Exp/Contr=0.3,0.1
English Units
Geom File=g01
Flow File=f01
Plan File=p01
Y Axis Title=Elevation
X Axis Title(PF)=Main Channel Distance
X Axis Title(XS)=Station
BEGIN DESCRIPTION:
Alliance Creek
END DESCRIPTION:
DSS File=dss
DSS Export Rating Curves= 0
DSS Export Rating Curve Sorted= 0
DSS Export Volume Flow Curves= 0
DXF OffsetX= 0
DXF OffsetY= 0
DXF ScaleX= 1
DXF ScaleY= 10

--- Alliance Creek.p01 (plan) ---

Plan Title=Multiple Run
Program Version=4.10
Geom File=g01
Flow File=f01
Subcritical Flow
K Sum by GR= 0
Std Step Tol= 0.01
Critical Tol= 0.01
Num of Std Step Trials= 20
Max Error Tol= 0.3
Flow Tol Ratio= 0.001
Split Flow NTrial= 30
Split Flow Tol= 0.02
Split Flow Ratio= 0.02
Log Output Level= 0
Friction Slope Method= 0
Unsteady Friction Slope Method= 2
Unsteady Bridges Friction Slope Method= 1
Parabolic Critical Depth
Global Vel Dist= 1 , 1 , 1
Global Log Level= 0
CheckData=True
Encroach Param=-1 ,0,0, 0
BEGIN DESCRIPTION:
Multiple Run
END DESCRIPTION:
Computation Interval=1HOUR
Output Interval=1HOUR
Run HTab= 0
Run UNet= 0
Run PostProcess= 0
Run WQNet= 0
UNET Theta= 1
UNET Theta Warmup= 1
UNET ZTol= 0.02
UNET ZSATol= 0.05
UNET MxIter= 20
UNET MaxInSteps= 0
UNET DtIC= 0
UNET DtMin= 0
UNET MaxCRTS= 20
UNET WFStab= 2
UNET SFStab= 1
UNET WFX= 1
UNET SFX= 1
UNET DSS MLevel= 4
UNET DZMax Abort= 100
UNET Convert EG Bridges= 0
UNET Use Existing IB Tables=-1
UNET Froude Reduction=False
UNET Froude Limit= 1
UNET Froude Power= 10
UNET Time Slicing=0,0, 5
UNET Junction Losses=0
Instantaneous Interval=1HOUR
DSS File=dss
Write IC File= 0
Write IC File at Sim End=0
Echo Input=False
Echo Parameters=False
Echo Output=False
Write Detailed= 0
WQ AD Non Conservative
WQ ULTIMATE=-1
WQ Max Comp Step=1HOUR
WQ Output Interval=15MIN
WQ Output Selected Increments= 0
WQ Output face flow=0
WQ Output face velocity=0
WQ Output face area=0
WQ Output face dispersion=0
WQ Output cell volume=0
WQ Output cell surface area=0
WQ Output cell continuity=0
WQ Output cumulative cell continuity=0
WQ Output face conc=0
WQ Output face dconc_dx=0
WQ Output face courant=0
WQ Output face peclet=0
WQ Output face adv mass=0
WQ Output face disp mass=0
WQ Output cell mass=0
WQ Output cell source sink temp=0
WQ Output cell source sink nsm=0
WQ Output MaxMinRange=-1
WQ Daily Max Min Mean=-1
WQ Daily Range=0
WQ Daily Time=0
WQ Create Restart=0
WQ Fixed Restart=0
WQ System Summary=0
WQ Use Fixed Temperature=0
Sorting and Armoring Iterations= 10
XS Update Threshold= 0.02
Hydraulics Update Threshold= 0.02
Energy Slope Method= 1
Volume Change Method= 0
XS Weighting Method= 0
Number of US Weighted Cross Sections= 1
Number of DS Weighted Cross Sections= 1
Upstream XS Weight=0.25
Main XS Weight=0.5
Downstream XS Weight=0.25
Number of DS XS's Weighted with US Boundary= 1
Upstream Boundary Weight= 1
Weight of XSs Associated with US Boundary= 0
Number of US XS's Weighted with DS Boundary= 1
Downstream Boundary Weight= 0.5
Weight of XSs Associated with DS Boundary= 0.5
Sediment Output Level= 4
Mass or Volume Output= 0
Output Increment Type= 1
Profile and TS Output Increment= 10
XS Output Flag= 0
XS Output Increment= 10
Disregard all LS=0
Disregard all Conn=0
Disregard all Breaches=0
Disregard all Pumps=0

--- Alliance Creek.f01 (steady flow) ---

Flow Title=Multiple
Number of Profiles=7
Profile Names=10-year,25-year,50-year,1pct_min,100-year,1pct_plu,500-year
River Rch & RM= Alliance Creek,Reach-1,7037
     446     589     702     415     829    1650    1150
River Rch & RM= Alliance Creek,Reach-1,3923
     568     764     922     551    1100    2190    1560
River Rch & RM= Alliance Creek,Reach-1,1580
     732    1000    1220     738    1470    2940    2140
Boundary for River Rch & Prof#=Alliance Creek,Reach-1,1
Up Type=0
Dn Type=3
Dn Slope=0.005
Boundary for River Rch & Prof#=Alliance Creek,Reach-1,2
Up Type=0
Dn Type=3
Dn Slope=0.005
Boundary for River Rch & Prof#=Alliance Creek,Reach-1,3
Up Type=0
Dn Type=3
Dn Slope=0.005
Boundary for River Rch & Prof#=Alliance Creek,Reach-1,4
Up Type=0
Dn Type=3
Dn Slope=0.005
Boundary for River Rch & Prof#=Alliance Creek,Reach-1,5
Up Type=0
Dn Type=3
Dn Slope=0.005
Boundary for River Rch & Prof#=Alliance Creek,Reach-1,6
Up Type=0
Dn Type=3
Dn Slope=0.005
Boundary for River Rch & Prof#=Alliance Creek,Reach-1,7
Up Type=0
Dn Type=3
Dn Slope=0.005

--- Alliance Creek.g01 (geometry) ---

Geom Title=Existing Conditions
Program Version=4.10

River Reach=Alliance Creek  ,Reach-1
Reach XY= 30
        2333329.        7045760.      2333390.51      7045611.49
       2333668.5      7045608.78       2333899.1       7045509.9
       2334127.5      7045556.54      2334276.57      7045415.52
      2334531.43      7045354.48      2334672.94      7045218.14
      2335080.56      7045013.76      2335777.54      7044906.46
      2336184.85      7044512.06      2336477.48      7044513.74
      2336573.75      7044565.45      2336625.31      7044702.35
      2336742.53      7044646.46      2336795.02      7044560.24
      2336982.42      7044652.24      2337075.47      7044558.56
      2337036.23      7044359.62      2337108.64      7044309.64
      2337199.02      7044359.91      2337723.07      7044362.24
        2337929.        7044460.      2338068.31      7044609.47
       2338326.7      7044365.83      2338639.17      7044299.68
      2338726.29       7044115.4      2338903.93      7044059.77
      2339082.45      7044102.77        2339129.        7044060.

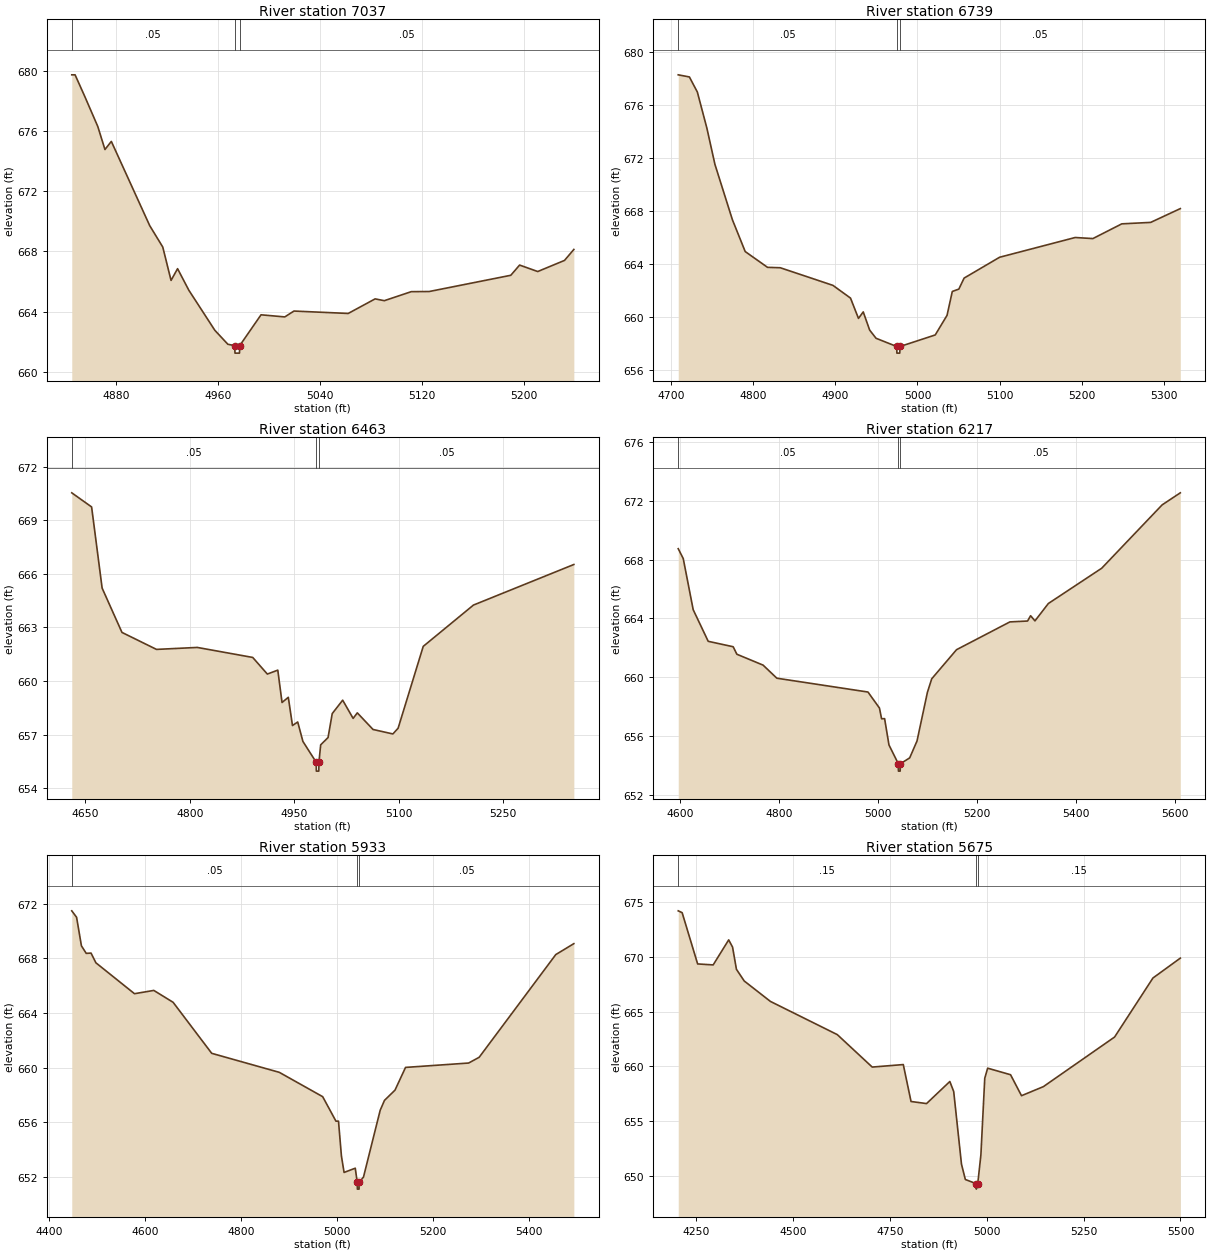
Type RM Length L Ch R = 1 ,7037    ,298,298,298
BEGIN DESCRIPTION:
Alliance Creek 19.0
END DESCRIPTION:
XS GIS Cut Line= 3
      2333529.01      7045760.04      2333500.77      7045613.86
      2333323.41      7045445.54
#Sta/Elev= 30
  4845.4  679.75    4848  679.75  4855.6  678.31  4865.8  676.31  4871.4  674.78
  4876.4  675.32  4906.5  669.71  4916.7  668.29  4923.2  666.07  4928.3  666.85
  4937.1  665.42  4957.5  662.75  4967.7  661.82    4973  661.73  4973.3  661.23
  4976.8  661.23    4977  661.73  4993.7  663.78  5012.3  663.64  5019.5  664.03
    5062  663.87  5083.1  664.84  5090.3  664.72  5111.4  665.32  5125.5  665.33
  5189.4  666.41  5196.3  667.09  5210.5  666.66  5231.5   667.4  5238.8  668.13
#Mann= 3 ,-1 , 0
  4845.4     .05       0    4973     .04       0    4977     .05       0
Bank Sta=4973,4977
XS Rating Curve= 0 ,0
Exp/Cntr=0.3,0.1

Type RM Length L Ch R = 1 ,6739    ,276,276,276
BEGIN DESCRIPTION:
Alliance Creek 18.0
END DESCRIPTION:
XS GIS Cut Line= 3
      2333629.02      7045809.96        2333779.        7045560.
      2333528.97      7045359.97
#Sta/Elev= 30
  4708.5  678.29  4722.1  678.13  4731.8  676.99  4743.4  674.27  4753.2  671.54
  4774.5  667.36  4790.1  664.96  4817.3  663.77  4832.8  663.74    4897  662.41
  4918.4  661.45  4928.1  659.92  4933.9  660.41  4941.7  659.04  4949.5  658.42
  4974.7   657.8  4974.9   657.3  4978.4   657.3  4978.7   657.8  5021.6  658.67
    5036  660.15  5042.4  661.95  5050.4  662.13  5056.8  662.96    5100  664.53
  5192.1  666.02  5213.7  665.94  5248.9  667.05  5284.1  667.16  5320.2   668.2
#Mann= 3 ,-1 , 0
  4708.5     .05       0  4974.7     .04       0  4978.7     .05       0
Bank Sta=4974.7,4978.7
XS Rating Curve= 0 ,0
Exp/Cntr=0.3,0.1

Type RM Length L Ch R = 1 ,6463    ,246,246,246
BEGIN DESCRIPTION:
Alliance Creek 17.0
END DESCRIPTION:
XS GIS Cut Line= 3
      2333829.01      7045859.99        2334029.        7045560.
        2333829.        7045260.
#Sta/Elev= 30
  4630.6  670.53  4659.1  669.74  4674.2   665.2  4702.7  662.72  4752.3  661.77
  4810.9  661.88  4890.5  661.32  4911.5  660.39  4926.5  660.61  4932.6   658.8
  4941.6  659.09  4947.6  657.51  4955.1  657.71  4962.6  656.62  4981.6  655.46
  4981.9  654.96  4985.4  654.96  4985.6  655.46  4988.1  656.43  4998.7  656.84
  5004.7  658.18  5019.7  658.93  5034.7  657.91  5040.7  658.22  5063.3  657.29
  5091.8  657.04  5099.3  657.36  5135.4  661.94  5207.5  664.25  5351.7  666.52
#Mann= 3 ,-1 , 0
  4630.6     .05       0  4981.6     .04       0  4985.6     .05       0
Bank Sta=4981.6,4985.6
XS Rating Curve= 0 ,0
Exp/Cntr=0.3,0.1

Type RM Length L Ch R = 1 ,6217    ,284,284,284
BEGIN DESCRIPTION:
Alliance Creek 16.0
END DESCRIPTION:
XS GIS Cut Line= 3
        2334179.      7045860.01        2334229.        7045460.
      2333878.97      7044959.96
#Sta/Elev= 30
  4596.6  668.74  4606.7  668.07  4626.8  664.59  4657.1  662.44  4707.5  662.07
    4715  661.56  4767.9  660.82  4795.7  659.93  4979.6  658.99  5002.8   657.9
  5007.1  657.17  5013.2  657.18    5022  655.39  5040.9  654.11  5041.1  653.61
  5044.6  653.61  5044.9  654.11  5063.8  654.51  5078.6  655.66  5099.6  658.97
  5108.3  659.89  5158.4  661.87  5266.1  663.76  5301.8  663.82  5307.9  664.18
  5316.7  663.83  5343.7  665.01  5451.4  667.41  5573.4  671.72  5610.1  672.54
#Mann= 3 ,-1 , 0
  4596.6     .05       0  5040.9     .04       0  5044.9     .05       0
Bank Sta=5040.9,5044.9
XS Rating Curve= 0 ,0
Exp/Cntr=0.3,0.1

Type RM Length L Ch R = 1 ,5933    ,258,258,258
BEGIN DESCRIPTION:
Alliance Creek 15.0
END DESCRIPTION:
XS GIS Cut Line= 3
        2334529.      7045909.98        2334479.        7045360.
        2334279.        7044910.
#Sta/Elev= 30
  4447.8  671.47  4457.8     671  4467.9  668.91  4477.9  668.36  4487.9  668.38
    4498  667.67  4578.3  665.41  4618.5  665.65  4658.7  664.78    4739  661.05
  4879.6  659.66  4969.9  657.88  4997.5  656.09  5002.8  656.09  5008.9  653.54
  5014.4  652.34  5037.7  652.65  5041.8  651.62  5042.1  651.12  5045.6  651.12
  5045.8  651.62  5054.8     652  5089.6  656.89  5098.5  657.61  5120.4  658.36
  5142.3  660.02  5273.6  660.34  5295.5  660.76  5454.9  668.27  5492.5  669.07
#Mann= 3 ,-1 , 0
  4447.8     .05       0  5041.8     .04       0  5045.8     .05       0
Bank Sta=5041.8,5045.8
XS Rating Curve= 0 ,0
Exp/Cntr=0.3,0.1

Type RM Length L Ch R = 1 ,5675    ,233,233,233
BEGIN DESCRIPTION:
Alliance Creek 14.0
END DESCRIPTION:
XS GIS Cut Line= 3
        2334729.      7046010.04        2334679.        7045210.
      2334328.98      7044859.98
#Sta/Elev= 30
    4203  674.23  4213.1  674.06  4253.1  669.37  4293.2  669.28  4333.3  671.57
  4343.3  670.91  4353.3  668.88  4373.4  667.81    4441  665.94  4613.8   662.9
    4704  659.93  4784.2  660.16  4804.2  656.78  4844.3  656.59  4904.4  658.61
  4914.4  657.69  4934.5  651.04  4944.5  649.64  4972.5  649.26  4972.8  648.76
  4976.5  649.26  4984.6  651.89  4994.6  658.91  5002.1  659.83  5061.2  659.23
  5089.5  657.31    5146  658.14  5329.9  662.68  5428.9  668.08  5499.6   669.9
#Mann= 3 ,-1 , 0
    4203     .15       0  4972.5     .03       0  4976.5     .15       0
Bank Sta=4972.5,4976.5
XS Rating Curve= 0 ,0
Exp/Cntr=0.5,0.3

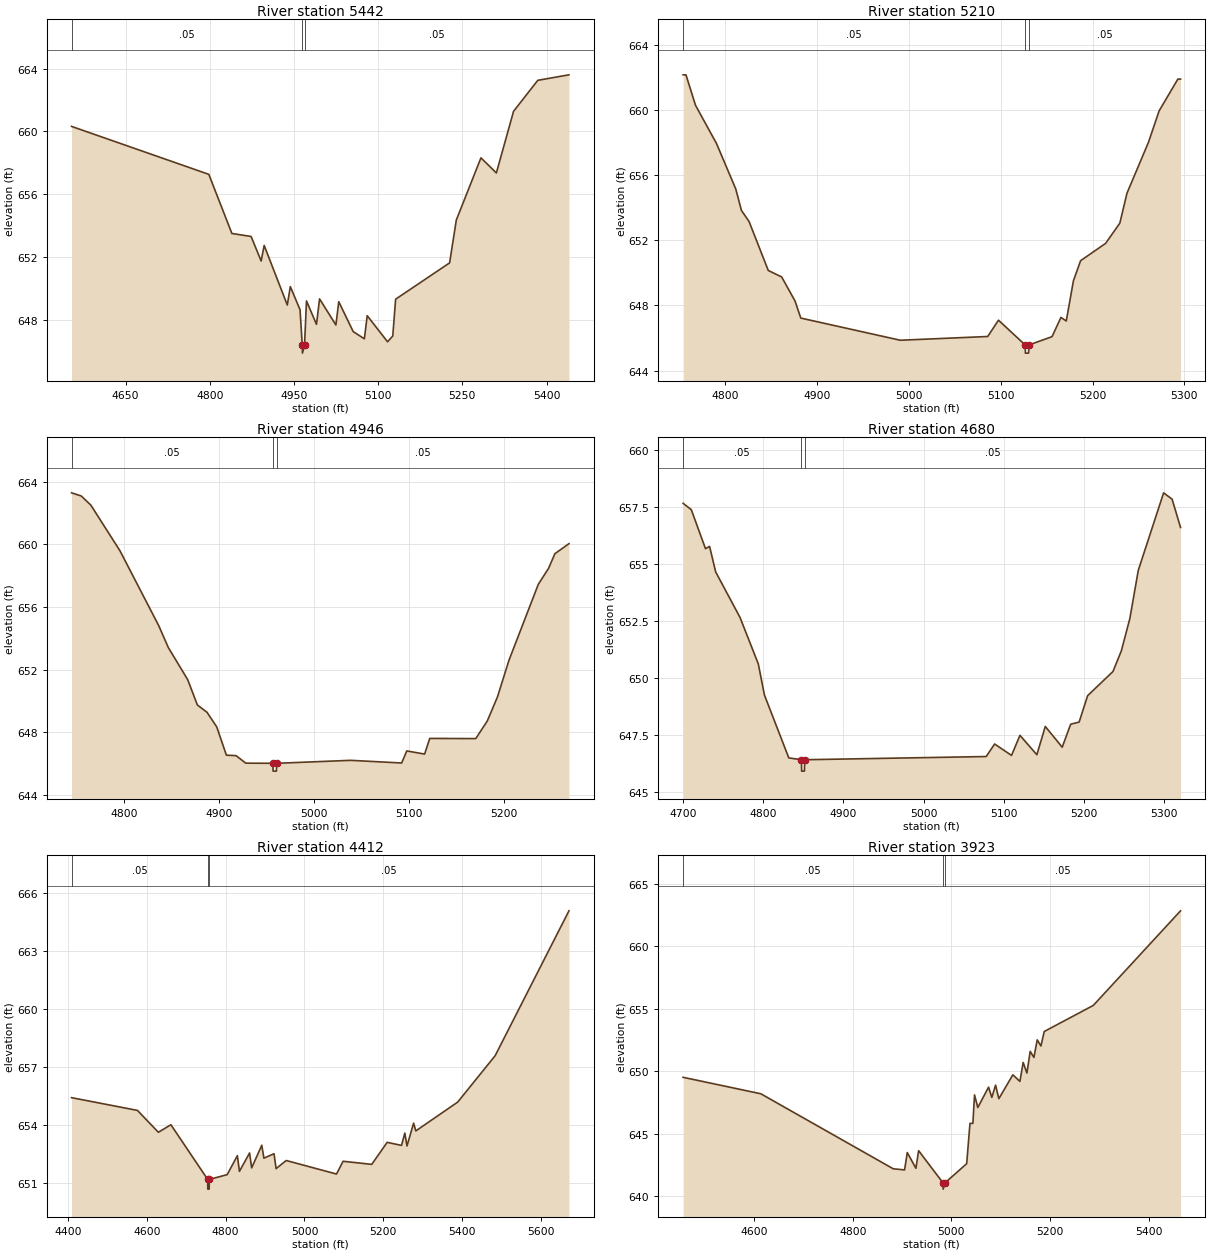
Type RM Length L Ch R = 1 ,5442    ,232,232,232
BEGIN DESCRIPTION:
Alliance Creek 13.0
END DESCRIPTION:
XS GIS Cut Line= 3
      2335061.31       7045522.3        2334879.        7045110.
      2334792.41      7044683.31
#Sta/Elev= 30
  4553.7  660.32  4798.3  657.27  4839.4  653.51  4873.6  653.32  4891.5  651.76
  4896.9  652.75  4938.1  648.96  4943.5  650.13  4960.8  648.66  4964.8   646.4
  4965.1   645.9  4968.8   646.4  4972.3  649.22  4990.1  647.73  4995.6  649.35
  5024.7  647.69  5029.8  649.17  5055.5  647.27  5075.4  646.81  5080.5  648.28
  5116.8  646.62    5126  646.99  5131.1  649.33  5227.3  651.64  5239.2  654.36
  5283.1  658.32  5310.6  657.36  5341.2  661.28  5384.4  663.25  5439.9   663.6
#Mann= 3 ,-1 , 0
  4553.7     .05       0  4964.8    .033       0  4968.8     .05       0
Bank Sta=4964.8,4968.8
XS Rating Curve= 0 ,0
Exp/Cntr=0.3,0.1

Type RM Length L Ch R = 1 ,5210    ,264,264,264
BEGIN DESCRIPTION:
Alliance Creek 12.0
END DESCRIPTION:
XS GIS Cut Line= 3
      2335228.98      7045209.97        2335079.        7045010.
      2334929.01      7044760.01
#Sta/Elev= 30
  4754.3  662.14  4757.4  662.14  4767.8  660.27  4790.7  657.92  4811.6  655.14
  4817.8  653.82  4826.1  653.14    4847  650.14  4861.6  649.74  4876.1  648.27
  4882.4  647.22  4990.7  645.86  5085.9  646.09  5097.6  647.09  5126.7  645.57
  5126.9  645.07  5130.4  645.07  5130.7  645.57  5155.9  646.08  5165.6  647.26
  5171.4  647.04  5179.2  649.51    5187  650.74  5214.2   651.8  5229.7  653.04
  5237.5  654.88  5260.8  657.99  5272.5  659.93  5292.9  661.88  5295.8  661.88
#Mann= 3 ,-1 , 0
  4754.3     .05       0  5126.7    .033       0  5130.7     .05       0
Bank Sta=5126.7,5130.7
XS Rating Curve= 0 ,0
Exp/Cntr=0.3,0.1

Type RM Length L Ch R = 1 ,4946    ,266,266,266
BEGIN DESCRIPTION:
Alliance Creek 11.0
END DESCRIPTION:
XS GIS Cut Line= 3
      2335278.99      7045210.04        2335329.        7044960.
      2335229.02      7044710.04
#Sta/Elev= 30
  4744.6   663.3  4754.8   663.1    4765  662.51  4795.6   659.6  4836.4  654.82
  4846.6  653.41    4867  651.36  4877.2  649.74  4887.4  649.27  4897.6  648.34
  4907.8  646.53    4918   646.5  4928.2  646.02  4956.8  646.01    4957  645.51
  4960.5  645.51  4960.8  646.01  5038.6   646.2  5092.5  646.03  5097.9   646.8
  5116.7   646.6  5122.1   647.6  5170.6  647.59  5182.7  648.71  5193.5  650.26
  5205.6   652.6  5236.5  657.45  5247.3  658.47    5254  659.41  5268.8  660.05
#Mann= 3 ,-1 , 0
  4744.6     .05       0  4956.8    .033       0  4960.8     .05       0
Bank Sta=4956.8,4960.8
XS Rating Curve= 0 ,0
Exp/Cntr=0.3,0.1

Type RM Length L Ch R = 1 ,4680    ,268,268,268
BEGIN DESCRIPTION:
Alliance Creek 10.0
END DESCRIPTION:
XS GIS Cut Line= 3
      2335629.01      7045210.04        2335579.        7044910.
        2335479.        7044610.
#Sta/Elev= 30
  4700.1  657.67  4710.3  657.39    4728  655.68  4733.1  655.78  4740.7  654.66
  4771.1  652.66  4793.9  650.62  4801.5  649.26  4831.9   646.5  4847.7  646.42
  4847.9  645.92  4851.4  645.92  4851.7  646.42  5078.1  646.56  5088.6  647.11
  5109.7  646.61  5120.2  647.49  5141.3  646.64  5151.8  647.88  5172.9  646.97
  5183.5  647.98    5194  648.07  5204.6  649.23  5236.2  650.29  5246.7   651.2
  5257.3  652.62  5267.8  654.73  5299.4  658.13    5310  657.85  5320.5  656.61
#Mann= 3 ,-1 , 0
  4700.1     .05       0  4847.7    .033       0  4851.7     .05       0
Bank Sta=4847.7,4851.7
XS Rating Curve= 0 ,0
Exp/Cntr=0.3,0.1

Type RM Length L Ch R = 1 ,4412    ,489,489,489
BEGIN DESCRIPTION:
Alliance Creek 9.0
END DESCRIPTION:
XS GIS Cut Line= 3
      2336024.72      7045417.87        2335829.        7044860.
      2335529.01      7044260.02
#Sta/Elev= 30
  4409.1  655.42  4576.4  654.76  4629.4  653.63  4661.2  654.02  4754.6  651.19
  4754.8  650.69  4758.3  650.69  4758.6  651.19  4804.1  651.44  4829.8  652.42
  4835.1  651.61  4860.8  652.56  4866.1  651.79  4891.8  652.96  4897.1  652.29
  4922.8  652.52  4928.1  651.75  4953.8  652.17  5081.4  651.47  5098.1  652.13
  5170.8  651.97  5209.9  653.11  5246.3  652.95  5254.7  653.59  5260.2  652.92
    5277   654.1  5282.6   653.7  5388.8  655.19  5483.9  657.59  5671.1  665.08
#Mann= 3 ,-1 , 0
  4409.1     .05       0  4754.6     .05       0  4758.6     .05       0
Bank Sta=4754.6,4758.6
XS Rating Curve= 0 ,0
Exp/Cntr=0.3,0.1

Type RM Length L Ch R = 1 ,3923    ,204,204,204
BEGIN DESCRIPTION:
Alliance Creek 8.0
END DESCRIPTION:
XS GIS Cut Line= 4
      2336425.84      7044998.43      2336299.47      7044785.97
      2336158.43      7044478.26      2335879.01      7044160.01
#Sta/Elev= 30
  4455.8  649.51  4613.5  648.19  4882.1  642.18  4905.1  642.09  4910.6  643.48
  4928.1  642.22  4933.6  643.63  4983.1  641.05  4983.4  640.55  4987.1  641.05
  5031.1  642.59  5037.8  645.82  5043.7  645.82    5047   648.1  5053.7  647.09
  5075.5  648.72  5082.1   647.9  5089.7  648.88  5096.4   647.8  5124.8  649.71
  5139.1  649.18  5145.7   650.7  5153.3  649.85    5160  651.59  5167.5   651.1
  5174.2  652.51  5181.8  652.02  5188.4  653.18    5288  655.27    5465  662.85
#Mann= 3 ,-1 , 0
  4455.8     .05       0  4983.1     .05       0  4987.1     .05       0
Bank Sta=4983.1,4987.1
XS Rating Curve= 0 ,0
Exp/Cntr=0.3,0.1

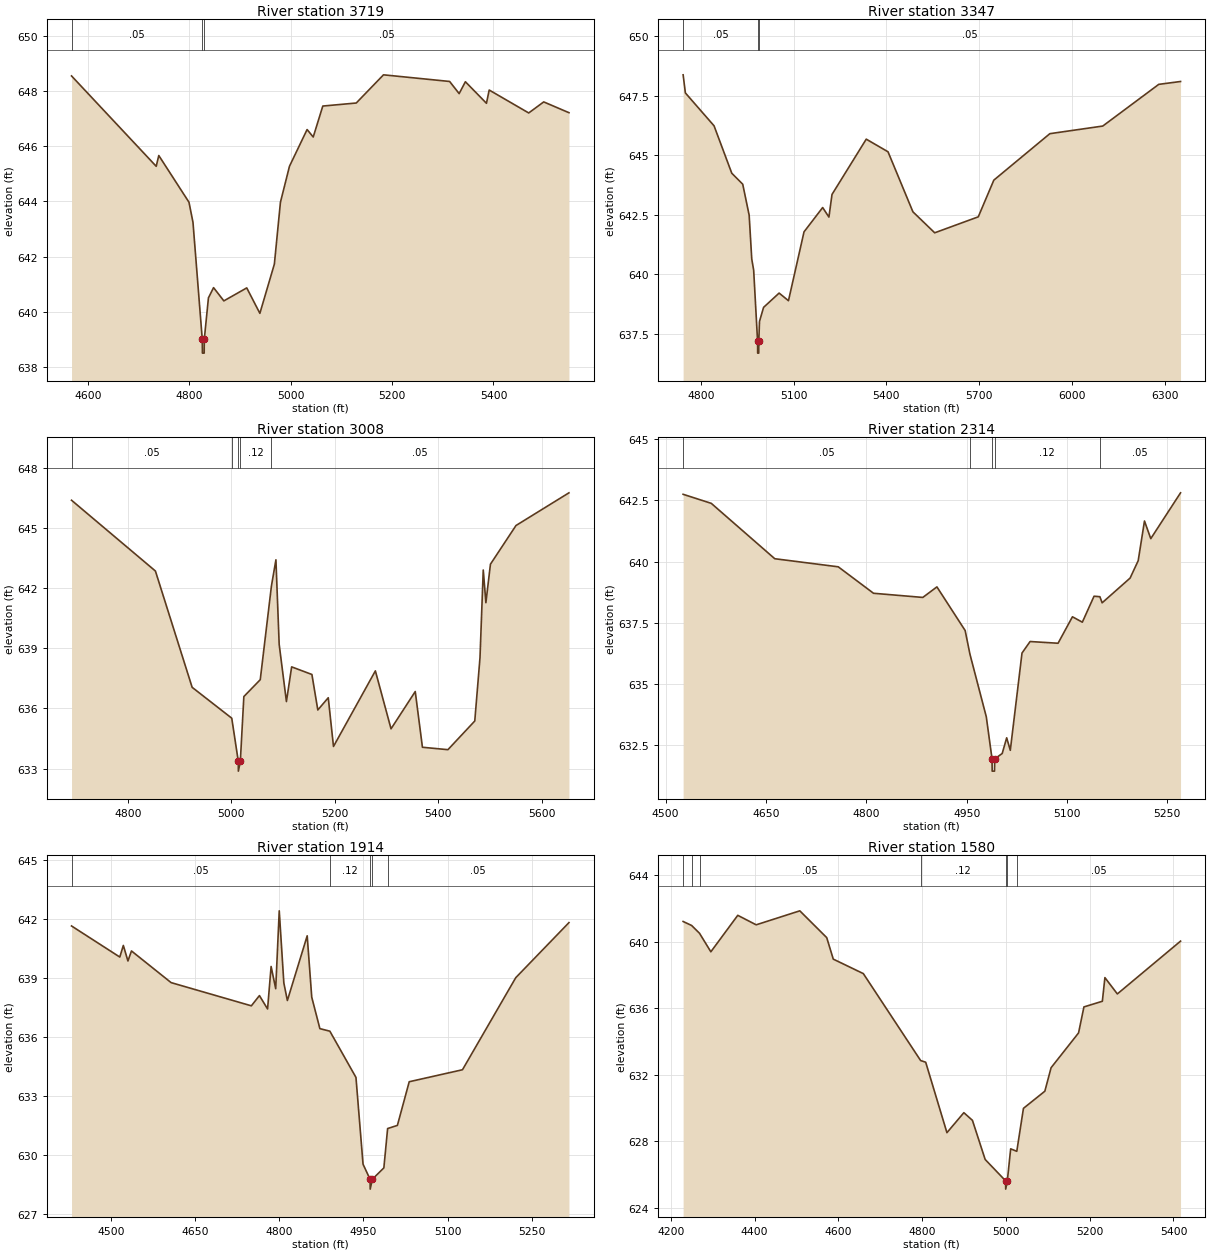
Type RM Length L Ch R = 1 ,3719    ,372,372,372
BEGIN DESCRIPTION:
Alliance Creek 7.0
END DESCRIPTION:
XS GIS Cut Line= 3
      2336453.33      7044936.17        2336379.        7044510.
      2336174.93      7044000.24
#Sta/Elev= 30
  4567.3  648.54  4734.4  645.27  4739.5  645.66  4799.1  643.97    4807  643.24
  4825.3  639.01  4825.6  638.51  4829.1  638.51  4829.3  639.01  4837.5  640.51
  4847.6  640.88  4867.9   640.4  4913.1  640.87    4939  639.95  4967.6  641.73
  4979.6  643.97  4997.4  645.27  5032.2   646.6  5044.3  646.33  5063.2  647.45
  5129.2  647.56    5183  648.58  5313.5  648.34  5332.3   647.9  5344.6  648.33
  5386.2  647.55  5391.6  648.03  5469.6   647.2  5499.2   647.6    5549  647.21
#Mann= 3 ,-1 , 0
  4567.3     .05       0  4825.3    .033       0  4829.3     .05       0
Bank Sta=4825.3,4829.3
XS Rating Curve= 0 ,0
Exp/Cntr=0.3,0.1

Type RM Length L Ch R = 1 ,3347    ,339,339,339
BEGIN DESCRIPTION:
Alliance Creek 6.0
END DESCRIPTION:
XS GIS Cut Line= 3
        2336479.        7044910.        2336629.        7044710.
        2336479.      7043360.01
#Sta/Elev= 30
  4742.7  648.38    4750  647.62  4842.7  646.24    4900  644.25  4935.4  643.79
  4956.2  642.49  4964.6  640.65  4970.8  640.18  4983.4   637.2  4983.7   636.7
  4987.2   636.7  4987.4   637.2  4989.6  638.03  5002.8  638.62  5053.1  639.22
  5083.3   638.9  5133.6  641.79  5193.9  642.81  5214.1  642.41  5224.1  643.36
  5334.8  645.68  5405.2  645.15  5485.7  642.63  5556.1  641.75    5697  642.42
  5747.3  643.96  5928.4  645.91  6099.5  646.23  6280.6  647.98    6351   648.1
#Mann= 3 ,-1 , 0
  4742.7     .05       0  4983.4    .033       0  4987.4     .05       0
Bank Sta=4983.4,4987.4
XS Rating Curve= 0 ,0
Exp/Cntr=0.3,0.1

Type RM Length L Ch R = 1 ,3008    ,694,694,694
BEGIN DESCRIPTION:
Alliance Creek 5.0
END DESCRIPTION:
XS GIS Cut Line= 3
        2336829.      7044910.02        2336879.        7044610.
        2336979.        7043960.
#Sta/Elev= 30
  4691.1  646.38  4853.3  642.85  4924.3  637.05  5000.9  635.51  5013.5  633.37
  5013.7  632.87  5017.5  633.37  5024.3  636.59    5056  637.43  5077.6   642.1
  5086.3  643.41  5092.6  639.19  5106.6  636.34  5116.7  638.07  5155.9  637.69
  5167.3  635.92  5187.5  636.53  5197.6   634.1  5278.6  637.87  5308.9  634.98
  5355.7  636.84  5369.6  634.06  5418.9  633.94  5470.8  635.37  5480.9  638.53
  5487.2   642.9  5492.3  641.27  5501.1  643.19  5550.5  645.12  5652.9  646.75
#Mann= 5 ,-1 , 0
  4691.1     .05       0  5000.9     .12       0  5013.5    .033       0
  5017.5     .12       0  5077.6     .05       0
Bank Sta=5013.5,5017.5
XS Rating Curve= 0 ,0
Exp/Cntr=0.3,0.1

Type RM Length L Ch R = 1 ,2314    ,400,400,400
BEGIN DESCRIPTION:
Alliance Creek 4.0
END DESCRIPTION:
XS GIS Cut Line= 3
      2337079.01      7044809.96        2337229.        7044360.
      2337128.98      7044109.96
#Sta/Elev= 30
  4526.1  642.75  4568.2  642.38  4663.1  640.12    4758  639.79  4810.7  638.71
  4884.4  638.54  4905.5  638.97  4947.7  637.19  4954.9  636.22  4979.3  633.67
  4987.9  631.95  4988.1  631.45  4991.6  631.45  4991.9  631.95  5003.1  632.17
  5009.8  632.81  5015.2   632.3  5032.7  636.27  5044.8  636.74  5086.6  636.67
  5108.1  637.75  5122.9  637.53  5140.4  638.59  5149.1  638.57  5152.5  638.32
  5194.3  639.33  5206.4  640.04  5215.8  641.66  5225.2  640.94  5269.7  642.81
#Mann= 5 ,-1 , 0
  4526.1     .05       0  4954.9     .12       0  4987.9     .07       0
  4991.9     .12       0  5149.1     .05       0
Bank Sta=4987.9,4991.9
XS Rating Curve= 0 ,0
Exp/Cntr=0.3,0.1

Type RM Length L Ch R = 1 ,1914    ,334,334,334
BEGIN DESCRIPTION:
Alliance Creek 3.0
END DESCRIPTION:
XS GIS Cut Line= 3
      2337178.99      7044710.01        2337629.        7044360.
      2337529.01      7044060.03
#Sta/Elev= 30
  4429.8  641.63  4515.8  640.05  4522.1  640.64  4530.3  639.85  4536.6  640.36
  4607.2  638.75  4750.2  637.57  4764.6  638.09  4779.1  637.41  4785.4  639.57
  4793.6  638.44  4799.9   642.4  4808.1  638.73  4814.4  637.84  4849.7  641.13
  4857.8  638.01  4872.3  636.41  4890.1  636.28  4936.6  633.93  4949.2  629.52
  4961.7  628.75    4962  628.25  4965.7  628.75  4986.3  629.33    4993  631.33
  5010.4  631.49  5031.5  633.71  5126.4  634.32  5221.3     639  5316.1   641.8
#Mann= 5 ,-1 , 0
  4429.8     .05       0  4890.1     .12       0  4961.7    .033       0
  4965.7     .12       0    4993     .05       0
Bank Sta=4961.7,4965.7
XS Rating Curve= 0 ,0
Exp/Cntr=0.3,0.1

Type RM Length L Ch R = 1 ,1580    ,397,397,397
BEGIN DESCRIPTION:
Alliance Creek 2.0
END DESCRIPTION:
XS GIS Cut Line= 4
      2338128.98      7045159.97      2337881.77      7044743.79
       2337938.2      7044413.93      2337728.99      7044109.98
#Sta/Elev= 30
  4229.2  641.21  4249.5  640.97  4268.4   640.5  4295.4  639.39  4359.7  641.58
  4403.6  641.01  4507.8  641.85  4572.1  640.24  4587.7  638.95  4659.5  638.08
  4796.3  632.86  4808.4  632.76  4859.1  628.53  4899.5  629.73    4920  629.27
  4950.4  626.92  4999.1  625.64  4999.4  625.14  5003.3  625.64  5011.3  627.56
  5025.9  627.41  5041.8  629.99  5092.9  631.02  5107.8  632.43  5173.4  634.52
  5186.2  636.08  5230.2  636.42  5236.3  637.84    5266  636.86  5416.9  640.03
#Mann= 7 ,-1 , 0
  4229.2     .05       0  4249.5    .075       0  4268.4     .05       0
  4796.3     .12       0  4999.1     .07       0  5003.3     .12       0
  5025.9     .05       0
Bank Sta=4999.1,5003.3
XS Rating Curve= 0 ,0
Exp/Cntr=0.3,0.1

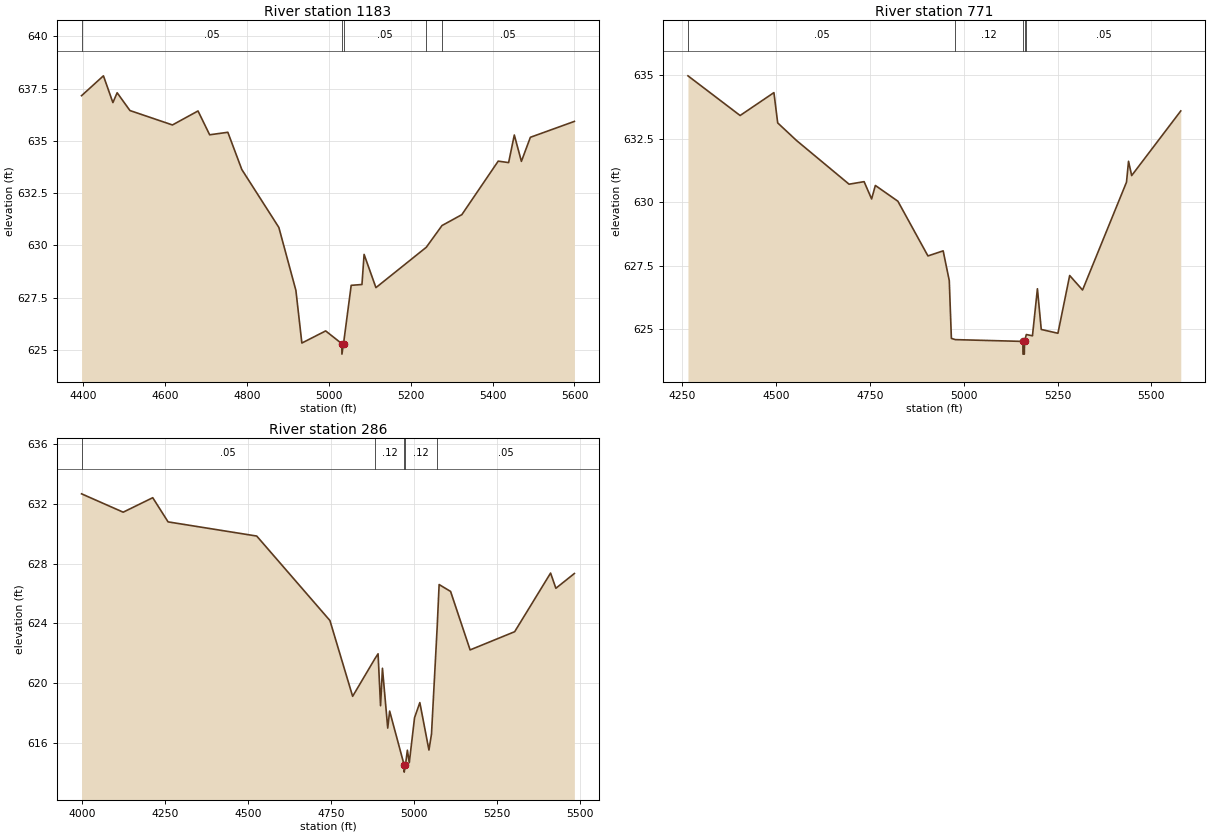
Type RM Length L Ch R = 1 ,1183    ,412,412,412
BEGIN DESCRIPTION:
Alliance Creek 1.7
END DESCRIPTION:
XS GIS Cut Line= 2
      2338359.21      7045073.67      2338033.88      7043915.49
#Sta/Elev= 30
  4396.8  637.16  4450.2  638.11  4473.3  636.83  4483.7   637.3  4514.9  636.45
  4618.7  635.76  4681.1  636.43  4709.5  635.29  4753.9  635.41    4788  633.63
  4878.4  630.86    4920  627.85  4934.6  625.33  4992.7  625.91  5032.1   625.3
  5032.4   624.8  5036.3   625.3    5055  628.09  5081.3  628.13  5086.5  629.57
  5115.4  627.98  5238.3  629.91  5276.7  630.95  5325.1  631.47  5413.9  634.03
  5439.3  633.96  5453.2  635.28  5470.5  634.02  5492.4  635.17  5599.8  635.93
#Mann= 5 ,-1 , 0
  4396.8     .05       0  5032.1    .033       0  5036.3     .05       0
  5238.3     .12       0  5276.7     .05       0
Bank Sta=5032.1,5036.3
XS Rating Curve= 0 ,0
Exp/Cntr=0.3,0.1

Type RM Length L Ch R = 1 ,771     ,485,485,485
BEGIN DESCRIPTION:
Alliance Creek 1.5
END DESCRIPTION:
XS GIS Cut Line= 3
      2338554.52      7045038.92       2338563.2      7044366.19
      2338307.13      7043780.28
#Sta/Elev= 30
    4266  634.97  4404.9  633.41  4494.9  634.31  4504.9  633.12  4554.9  632.43
    4695  630.71    4735  630.81    4755  630.13    4765  630.66    4825  630.04
    4905  627.89  4945.5  628.09  4961.8  626.92  4967.4  624.65  4977.8   624.6
  5157.8  624.53  5158.1  624.03  5161.7  624.03  5162.1  624.53    5167   624.8
  5183.3  624.75  5196.5   626.6  5206.7     625  5251.1  624.85  5282.4  627.12
  5316.7  626.55  5433.7  630.79  5439.1  631.61  5447.5  631.05  5578.2  633.59
#Mann= 5 ,-1 , 0
    4266     .05       0  4977.8     .12       0  5157.8     .07       0
  5162.1     .12       0    5167     .05       0
Bank Sta=5157.8,5162.1
XS Rating Curve= 0 ,0
Exp/Cntr=0.3,0.1

Type RM Length L Ch R = 1 ,286     ,0,0,0
BEGIN DESCRIPTION:
Alliance Creek 1.3
END DESCRIPTION:
XS GIS Cut Line= 3
      2338741.15      7045021.56      2338949.48      7044196.92
      2338636.97      7043645.69
#Sta/Elev= 30
  3999.5  632.67  4124.9  631.44  4213.9  632.41  4260.1  630.79  4527.1  629.84
  4747.5  624.18  4815.9   619.1  4882.7  621.61  4892.5  621.95    4900  618.47
  4905.7  620.98  4921.6  616.97  4927.4  618.11  4970.8  614.52  4971.2  614.02
  4975.1  614.52  4980.8  615.49  4986.5  614.65  5002.4  617.67  5018.3  618.68
  5045.7   615.5  5053.4  616.57  5070.5  623.73  5076.4  626.59  5110.9  626.13
  5169.7  622.21  5303.9  623.43  5412.1  627.36    5428  626.34  5483.7  627.33
#Mann= 5 ,-1 , 0
  3999.5     .05       0  4882.7     .12       0  4970.8     .07       0
  4975.1     .12       0  5070.5     .05       0
Bank Sta=4970.8,4975.1
XS Rating Curve= 0 ,0
Exp/Cntr=0.3,0.1

Chan Stop Cuts=-1
Use User Specified Reach Order=0
Composite Channel Slope=5