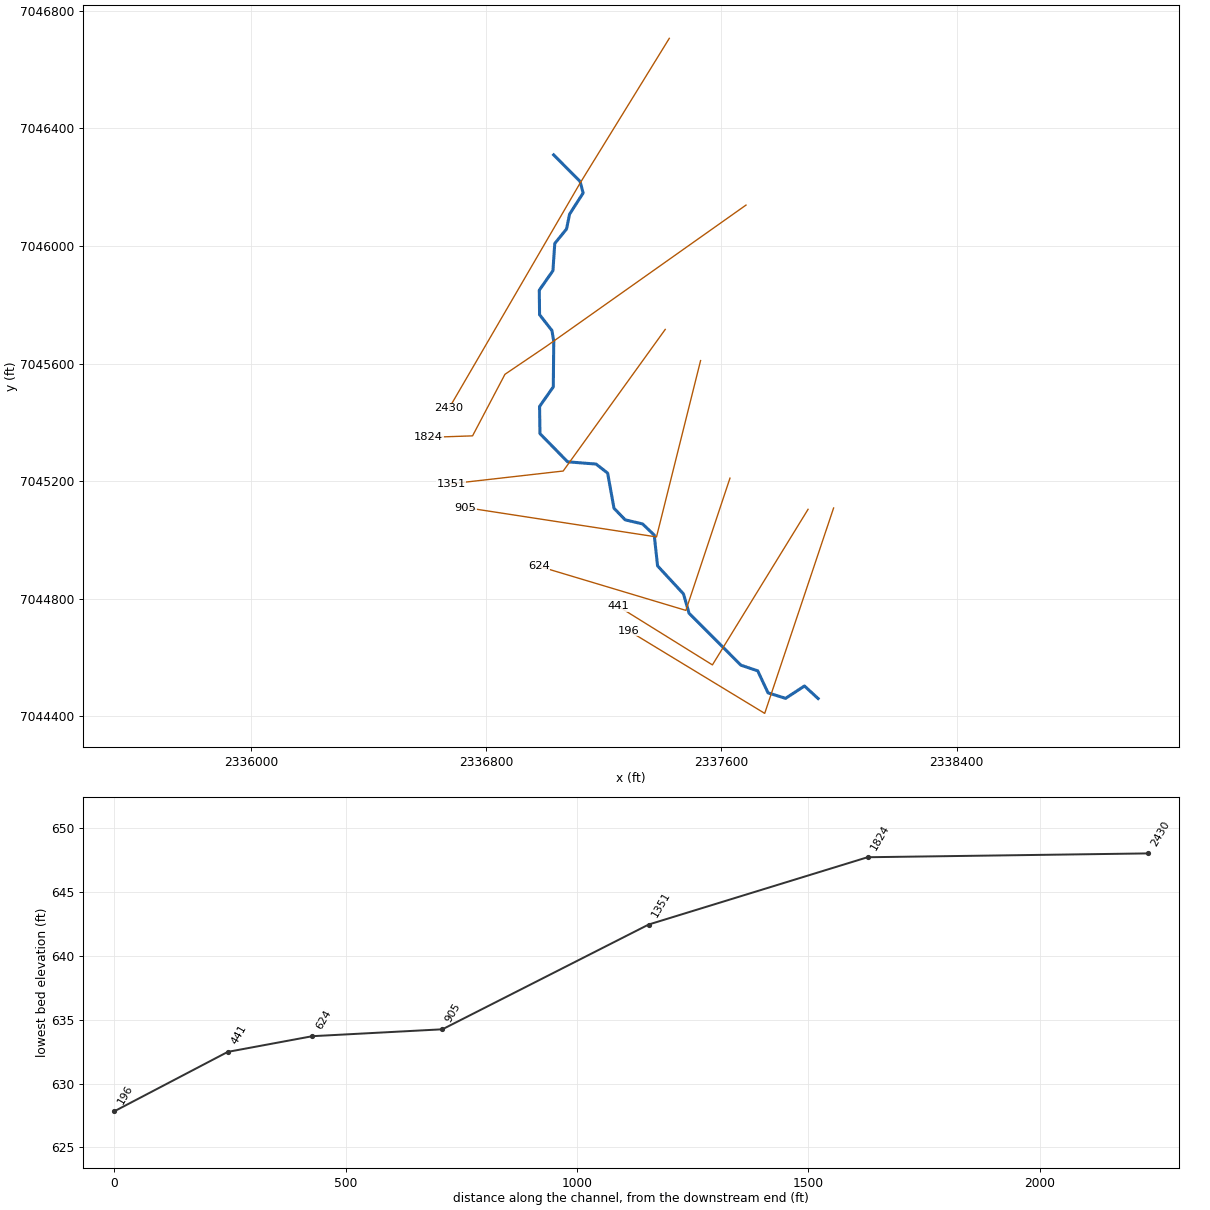
--- Avion Creek.prj (project) ---

Proj Title=Avion Creek Base Level Engineering
Current Plan=p01
Default Exp/Contr=0.3,0.1
English Units
Geom File=g01
Flow File=f01
Plan File=p01
BEGIN DESCRIPTION:
Avion Creek
END DESCRIPTION:

--- Avion Creek.p01 (plan) ---

Plan Title=Multiple Run
Short Identifier=Multiple
Geom File=g01
Flow File=f01
Subcritical Flow
K Sum by GR= 0
Std Step Tol= 0.01
Critical Tol= 0.01
Num of Std Step Trials= 20
Max Error Tol= 0.3
Flow Tol Ratio= 0.001
Split Flow NTrial= 30
Split Flow Tol= 0.02
Split Flow Ratio= 0.02
Log Output Level= 0
Friction Slope Method= 1
Unsteady Friction Slope Method= 2
Unsteady Bridges Friction Slope Method= 1
Parabolic Critical Depth
Global Vel Dist=  1 , 1 , 1
Global Log Level= 0
CheckData=True
Encroach Param= -1, 0, 0, 0
BEGIN DESCRIPTION:
Multiple Run
END DESCRIPTION:

--- Avion Creek.f01 (steady flow) ---

Flow Title=Multiple
Number of Profiles=7
Profile Names=10-year,25-year,50-year,1pct_min,100-year,1pct_plu,500-year
River Rch & RM= Avion Creek,Reach-1,2430
     221     279     323     186     371     740     488
Boundary for River Rch & Prof#=Avion Creek,Reach-1,1
Up Type=0
Dn Type=3
Dn Slope=0.005
Boundary for River Rch & Prof#=Avion Creek,Reach-1,2
Up Type=0
Dn Type=3
Dn Slope=0.005
Boundary for River Rch & Prof#=Avion Creek,Reach-1,3
Up Type=0
Dn Type=3
Dn Slope=0.005
Boundary for River Rch & Prof#=Avion Creek,Reach-1,4
Up Type=0
Dn Type=3
Dn Slope=0.005
Boundary for River Rch & Prof#=Avion Creek,Reach-1,5
Up Type=0
Dn Type=3
Dn Slope=0.005
Boundary for River Rch & Prof#=Avion Creek,Reach-1,6
Up Type=0
Dn Type=3
Dn Slope=0.005
Boundary for River Rch & Prof#=Avion Creek,Reach-1,7
Up Type=0
Dn Type=3
Dn Slope=0.005

--- Avion Creek.g01 (geometry) ---

Geom Title=Existing Conditions

River Reach=Avion Creek,Reach-1
Reach XY= 30
      2337029.00      7046310.00      2337118.92      7046219.71
      2337129.39      7046180.20      2337083.22      7046108.28
      2337072.89      7046057.82      2337032.83      7046008.42
      2337026.64      7045915.97      2336980.10      7045849.45
      2336981.17      7045765.98      2337023.25      7045712.34
      2337029.43      7045675.18      2337027.78      7045520.50
      2336981.16      7045454.02      2336982.45      7045361.48
      2337076.56      7045265.52      2337173.31      7045257.93
      2337212.73      7045227.21      2337234.42      7045107.33
      2337272.65      7045068.03      2337331.55      7045054.25
      2337371.25      7045016.45      2337382.63      7044911.50
      2337470.82      7044816.04      2337489.78      7044750.32
      2337666.02      7044573.72      2337723.37      7044554.34
      2337758.57      7044479.37      2337818.32      7044460.77
      2337882.44      7044502.73      2337929.00      7044460.00

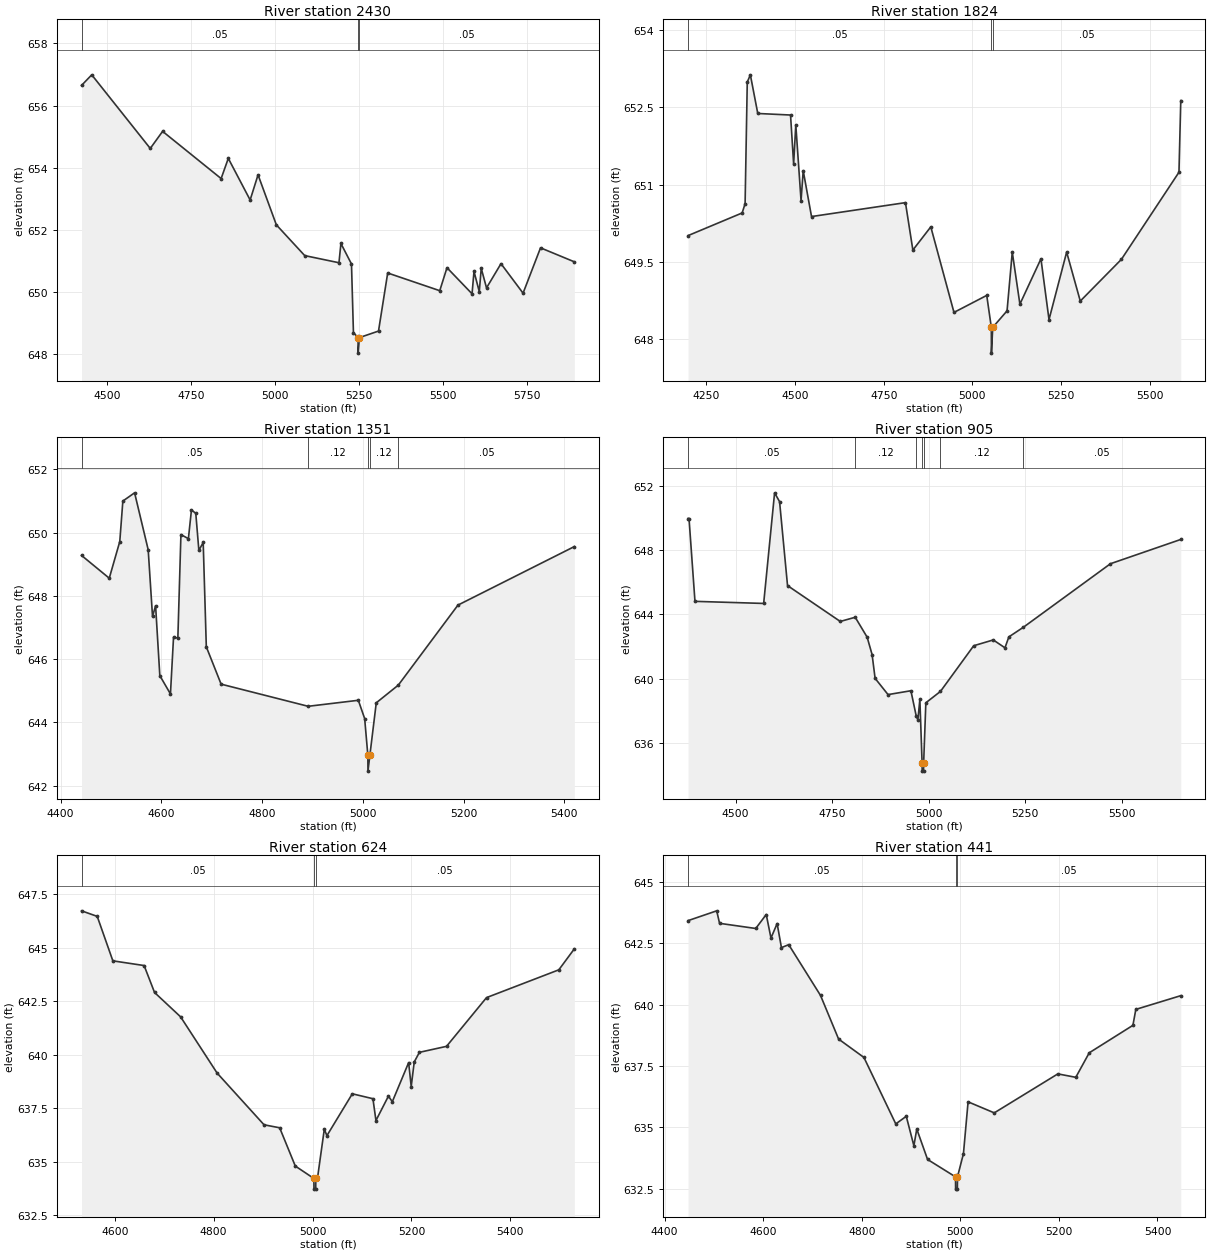
Type RM Length L Ch R = 1,2430,606,606,606
BEGIN DESCRIPTION:
Avion Creek 4.0
END DESCRIPTION:
XS GIS Cut Line= 3
      2337422.56      7046706.54      2337118.06      7046212.33
      2336673.44      7045448.38
#Sta/Elev= 30
  4425.0  656.65  4455.3  656.99  4629.2  654.62  4665.9  655.17  4839.8  653.65
  4861.1  654.30  4926.0  652.96  4949.5  653.77  5003.9  652.16  5088.2  651.17
  5190.0  650.94  5195.8  651.56  5227.2  650.90  5233.0  648.69  5246.7  648.53
  5247.0  648.03  5250.7  648.53  5307.5  648.74  5334.8  650.61  5489.5  650.04
  5511.0  650.78  5585.5  649.94  5591.3  650.66  5607.0  650.01  5612.8  650.76
  5628.5  650.13  5671.5  650.91  5737.1  649.96  5789.0  651.42  5889.4  650.97
#Mann=3,-1,0
  4425.0    0.05       0  5246.7    0.05       0  5250.7    0.05       0
Bank Sta=5246.7,5250.7
Exp/Cntr=0.3,0.1

Type RM Length L Ch R = 1,1824,473,473,473
BEGIN DESCRIPTION:
Avion Creek 3.0
END DESCRIPTION:
XS GIS Cut Line= 5
      2337683.52      7046139.12      2337004.23      7045658.65
      2336863.41      7045563.39      2336753.14      7045353.89
      2336603.93      7045348.79
#Sta/Elev= 30
  4198.8  650.01  4351.3  650.45  4359.6  650.63  4365.7  652.99  4374.4  653.13
  4395.3  652.38  4487.6  652.35  4496.3  651.40  4502.4  652.16  4517.2  650.69
  4523.3  651.27  4546.7  650.38  4811.3  650.65  4832.2  649.73  4882.7  650.18
  4948.0  648.52  5040.3  648.85  5053.2  648.23  5053.5  647.73  5057.2  648.23
  5097.5  648.55  5112.2  649.69  5133.7  648.68  5193.0  649.56  5215.7  648.38
  5265.4  649.69  5303.8  648.74  5419.7  649.55  5581.8  651.24  5586.9  652.63
#Mann=3,-1,0
  4198.8    0.05       0  5053.2   0.033       0  5057.2    0.05       0
Bank Sta=5053.2,5057.2
Exp/Cntr=0.3,0.1

Type RM Length L Ch R = 1,1351,446,446,446
BEGIN DESCRIPTION:
Avion Creek 2.5
END DESCRIPTION:
XS GIS Cut Line= 3
      2337408.70      7045716.04      2337061.46      7045234.24
      2336679.51      7045190.84
#Sta/Elev= 30
  4441.6  649.28  4496.6  648.56  4517.5  649.72  4523.6  651.00  4546.9  651.26
  4573.9  649.46  4582.5  647.35  4588.6  647.69  4597.0  645.48  4618.1  644.90
  4624.2  646.69  4632.8  646.67  4638.9  649.94  4653.7  649.81  4659.8  650.72
  4668.4  650.61  4674.5  649.44  4683.1  649.69  4689.3  646.39  4718.7  645.21
  4891.5  644.51  4991.1  644.70  5003.7  644.12  5010.0  642.96  5010.2  642.46
  5014.0  642.96  5026.7  644.62  5070.5  645.18  5188.9  647.71  5419.9  649.56
#Mann=5,-1,0
  4441.6    0.05       0  4891.5    0.12       0  5010.0    0.07       0
  5014.0    0.12       0  5070.5    0.05       0
Bank Sta=5010,5014
Exp/Cntr=0.3,0.1

Type RM Length L Ch R = 1,905,281,281,281
BEGIN DESCRIPTION:
Avion Creek 2.0
END DESCRIPTION:
XS GIS Cut Line= 3
      2337529.00      7045610.01      2337379.00      7045010.00
      2336729.02      7045110.00
#Sta/Elev= 30
  4377.0  649.96  4379.6  649.96  4395.0  644.81  4572.9  644.68  4601.2  651.56
  4614.1  651.01  4634.7  645.79  4771.3  643.56  4810.0  643.82  4840.9  642.58
  4853.7  641.50  4861.5  640.02  4895.0  639.01  4954.2  639.25  4967.9  637.69
  4972.3  637.44  4977.4  638.71  4983.2  634.75  4983.4  634.25  4986.9  634.25
  4987.2  634.75  4992.9  638.50  5030.8  639.21  5116.9  642.05  5167.5  642.41
  5197.8  641.92  5207.9  642.60  5245.6  643.20  5471.0  647.15  5653.1  648.66
#Mann=7,-1,0
  4377.0    0.05       0  4810.0    0.12       0  4967.9    0.05       0
  4983.2   0.033       0  4987.2    0.05       0  5030.8    0.12       0
  5245.6    0.05       0
Bank Sta=4983.2,4987.2
Exp/Cntr=0.3,0.1

Type RM Length L Ch R = 1,624,183,183,183
BEGIN DESCRIPTION:
Avion Creek 1.0
END DESCRIPTION:
XS GIS Cut Line= 3
      2337629.01      7045210.03      2337479.00      7044760.00
      2336978.99      7044910.00
#Sta/Elev= 30
  4533.0  646.73  4564.7  646.47  4596.3  644.39  4659.5  644.17  4680.6  642.91
  4733.3  641.77  4807.1  639.14  4902.0  636.72  4933.6  636.58  4965.2  634.79
  5002.7  634.21  5003.0  633.71  5006.5  633.71  5006.7  634.21  5010.0  634.21
  5023.9  636.52  5029.1  636.21  5080.5  638.17  5122.2  637.94  5128.3  636.92
  5153.5  638.06  5161.4  637.80  5194.4  639.63  5199.6  638.51  5205.7  639.66
  5216.2  640.11  5271.0  640.39  5351.9  642.67  5498.1  643.97  5529.4  644.95
#Mann=3,-1,0
  4533.0    0.05       0  5002.7   0.033       0  5006.7    0.05       0
Bank Sta=5002.7,5006.7
Exp/Cntr=0.3,0.1

Type RM Length L Ch R = 1,441,245,245,245
BEGIN DESCRIPTION:
Avion Creek 0.5
END DESCRIPTION:
XS GIS Cut Line= 3
      2337894.78      7045104.01      2337569.27      7044574.52
      2337248.11      7044774.16
#Sta/Elev= 30
  4447.6  643.43  4505.8  643.83  4511.6  643.32  4585.0  643.11  4606.3  643.68
  4615.9  642.72  4628.4  643.31  4637.1  642.33  4651.9  642.45  4716.4  640.38
  4753.1  638.60  4804.5  637.85  4869.1  635.14  4890.4  635.45  4905.8  634.25
  4911.7  634.93  4933.6  633.69  4990.3  632.98  4990.5  632.48  4994.0  632.48
  4994.3  632.98  5006.4  633.93  5015.8  636.04  5068.9  635.59  5197.9  637.18
  5234.3  637.04  5261.6  638.04  5350.2  639.16  5356.1  639.81  5447.3  640.37
#Mann=3,-1,0
  4447.6    0.05       0  4990.3   0.033       0  4994.3    0.05       0
Bank Sta=4990.3,4994.3
Exp/Cntr=0.3,0.1

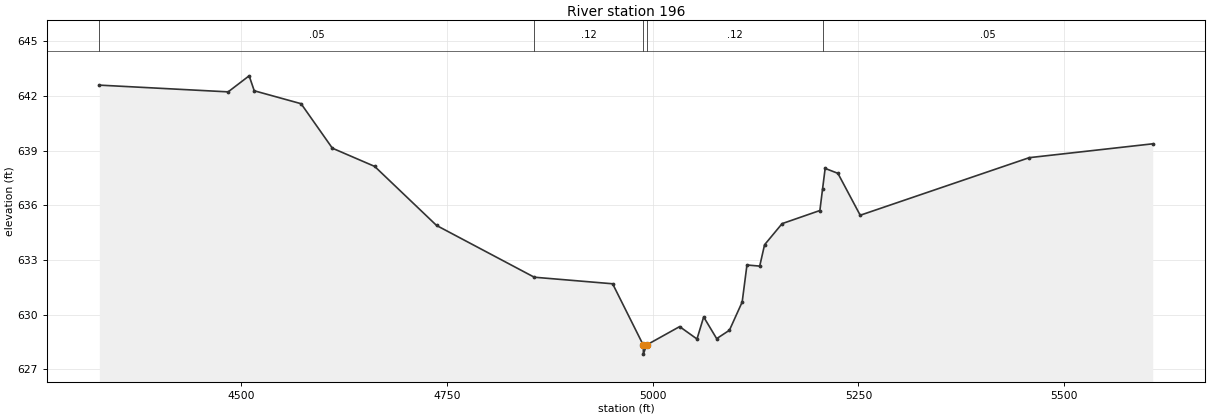
Type RM Length L Ch R = 1,196,0,0,0
BEGIN DESCRIPTION:
Avion Creek 0.1
END DESCRIPTION:
XS GIS Cut Line= 3
      2337981.61      7045108.40      2337747.22      7044409.59
      2337283.37      7044691.37
#Sta/Elev= 30
  4327.8  642.59  4484.3  642.22  4509.8  643.10  4516.0  642.28  4572.9  641.57
  4610.9  639.13  4662.3  638.13  4737.5  634.89  4856.2  632.05  4951.4  631.69
  4988.6  628.33  4988.8  627.83  4992.6  628.33  5032.8  629.34  5053.9  628.66
  5062.0  629.87  5077.8  628.68  5093.3  629.14  5108.8  630.69  5114.6  632.72
  5130.1  632.66  5136.0  633.83  5157.3  634.99  5203.2  635.71  5206.4  636.87
  5209.6  638.02  5225.1  637.75  5252.2  635.45  5457.6  638.61  5607.6  639.37
#Mann=5,-1,0
  4327.8    0.05       0  4856.2    0.12       0  4988.6    0.07       0
  4992.6    0.12       0  5206.4    0.05       0
Bank Sta=4988.6,4992.6
Exp/Cntr=0.3,0.1

Chan Stop Cuts=-1