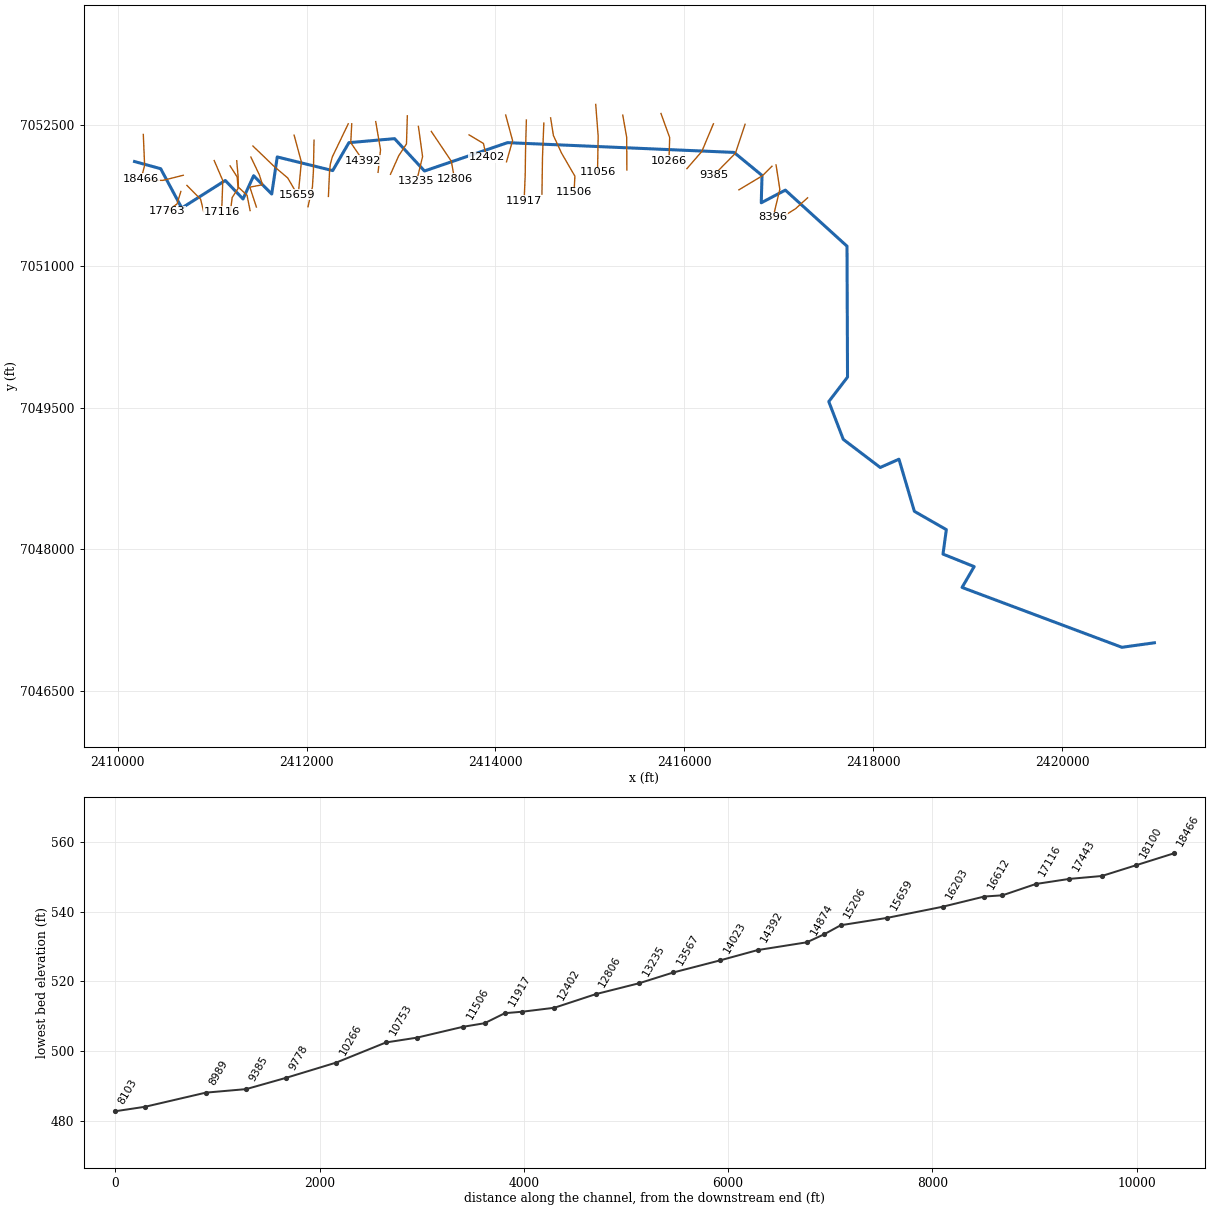
--- Bakers Branch.prj (project) ---

Proj Title=Bakers Branch Base Level Engineering
Current Plan=p01
Default Exp/Contr=0.3,0.1
English Units
Geom File=g01
Flow File=f01
Plan File=p01
Y Axis Title=Elevation
X Axis Title(PF)=Main Channel Distance
X Axis Title(XS)=Station
BEGIN DESCRIPTION:
Bakers Branch
END DESCRIPTION:
DSS Export Rating Curves= 0
DSS Export Rating Curve Sorted= 0
DSS Export Volume Flow Curves= 0
DXF OffsetX= 0
DXF OffsetY= 0
DXF ScaleX= 1
DXF ScaleY= 10

--- Bakers Branch.p01 (plan) ---

Plan Title=Multiple Run
Short Identifier=Multiple
Geom File=g01
Flow File=f01
Subcritical Flow
K Sum by GR= 0
Std Step Tol= 0.01
Critical Tol= 0.01
Num of Std Step Trials= 20
Max Error Tol= 0.3
Flow Tol Ratio= 0.001
Split Flow NTrial= 30
Split Flow Tol= 0.02
Split Flow Ratio= 0.02
Log Output Level= 0
Friction Slope Method= 1
Unsteady Friction Slope Method= 2
Unsteady Bridges Friction Slope Method= 1
Parabolic Critical Depth
Global Vel Dist=  1 , 1 , 1
Global Log Level= 0
CheckData=True
Encroach Param= -1, 0, 0, 0
BEGIN DESCRIPTION:
Multiple Run
END DESCRIPTION:

--- Bakers Branch.f01 (steady flow) ---

Flow Title=Multiple
Program Version=4.10
Number of Profiles= 7
Profile Names=10-year,25-year,50-year,1pct_min,100-year,1pct_plu,500-year
River Rch & RM=Bakers Branch,Reach-1         ,18466
     564     772     943     573    1143    2281    1682
River Rch & RM=Bakers Branch,Reach-1         ,14874
     750    1043    1288     790    1577    3146    2367
River Rch & RM=Bakers Branch,Reach-1         ,12090
     889    1248    1551     957    1909    3808    2898
River Rch & RM=Bakers Branch,Reach-1         ,9778
    1061    1503    1879    1164    2323    4635    3563
River Rch & RM=Bakers Branch,Reach-1         ,7335
    1207    1719    2157    1341    2676    5339    4131
River Rch & RM=Bakers Branch,Reach-1         ,4791
    1649    2366    2982    1857    3705    7393    5726
Boundary for River Rch & Prof#=Bakers Branch,Reach-1         , 1
Up Type= 0
Dn Type= 3
Dn Slope=0.005
Boundary for River Rch & Prof#=Bakers Branch,Reach-1         , 2
Up Type= 0
Dn Type= 3
Dn Slope=0.005
Boundary for River Rch & Prof#=Bakers Branch,Reach-1         , 3
Up Type= 0
Dn Type= 3
Dn Slope=0.005
Boundary for River Rch & Prof#=Bakers Branch,Reach-1         , 4
Up Type= 0
Dn Type= 3
Dn Slope=0.005
Boundary for River Rch & Prof#=Bakers Branch,Reach-1         , 5
Up Type= 0
Dn Type= 3
Dn Slope=0.005
Boundary for River Rch & Prof#=Bakers Branch,Reach-1         , 6
Up Type= 0
Dn Type= 3
Dn Slope=0.005
Boundary for River Rch & Prof#=Bakers Branch,Reach-1         , 7
Up Type= 0
Dn Type= 3
Dn Slope=0.005
DSS Import GetInterval= 0
DSS Import GetPeak= 0
DSS Import FillOption= 0

--- Bakers Branch.g01 (geometry) ---

Geom Title=Existing Conditions
Program Version=4.10

River Reach=Bakers Branch   ,Reach-1
Reach XY= 30
        2410179.        7052110.      2410455.95      7052033.72
       2410679.2      7051617.03      2411139.61      7051909.12
      2411327.77      7051713.37      2411440.13      7051959.66
      2411631.77      7051765.35      2411690.17       7052158.4
      2412277.45      7052013.75      2412449.11      7052309.89
      2412932.71      7052352.34      2413249.22       7052009.5
        2414129.        7052310.      2416527.51      7052206.54
      2416823.71      7051962.68      2416815.59      7051672.84
      2417070.68      7051807.04      2417723.65       7051212.7
      2417729.11      7049825.36      2417530.75       7049566.1
      2417684.18      7049165.44      2418075.59      7048867.77
      2418273.91      7048955.38       2418436.7      7048403.52
      2418775.55      7048208.75      2418740.09      7047949.92
      2419070.18        7047817.      2418942.03      7047596.47
      2420634.86      7046962.05        2420979.        7047010.

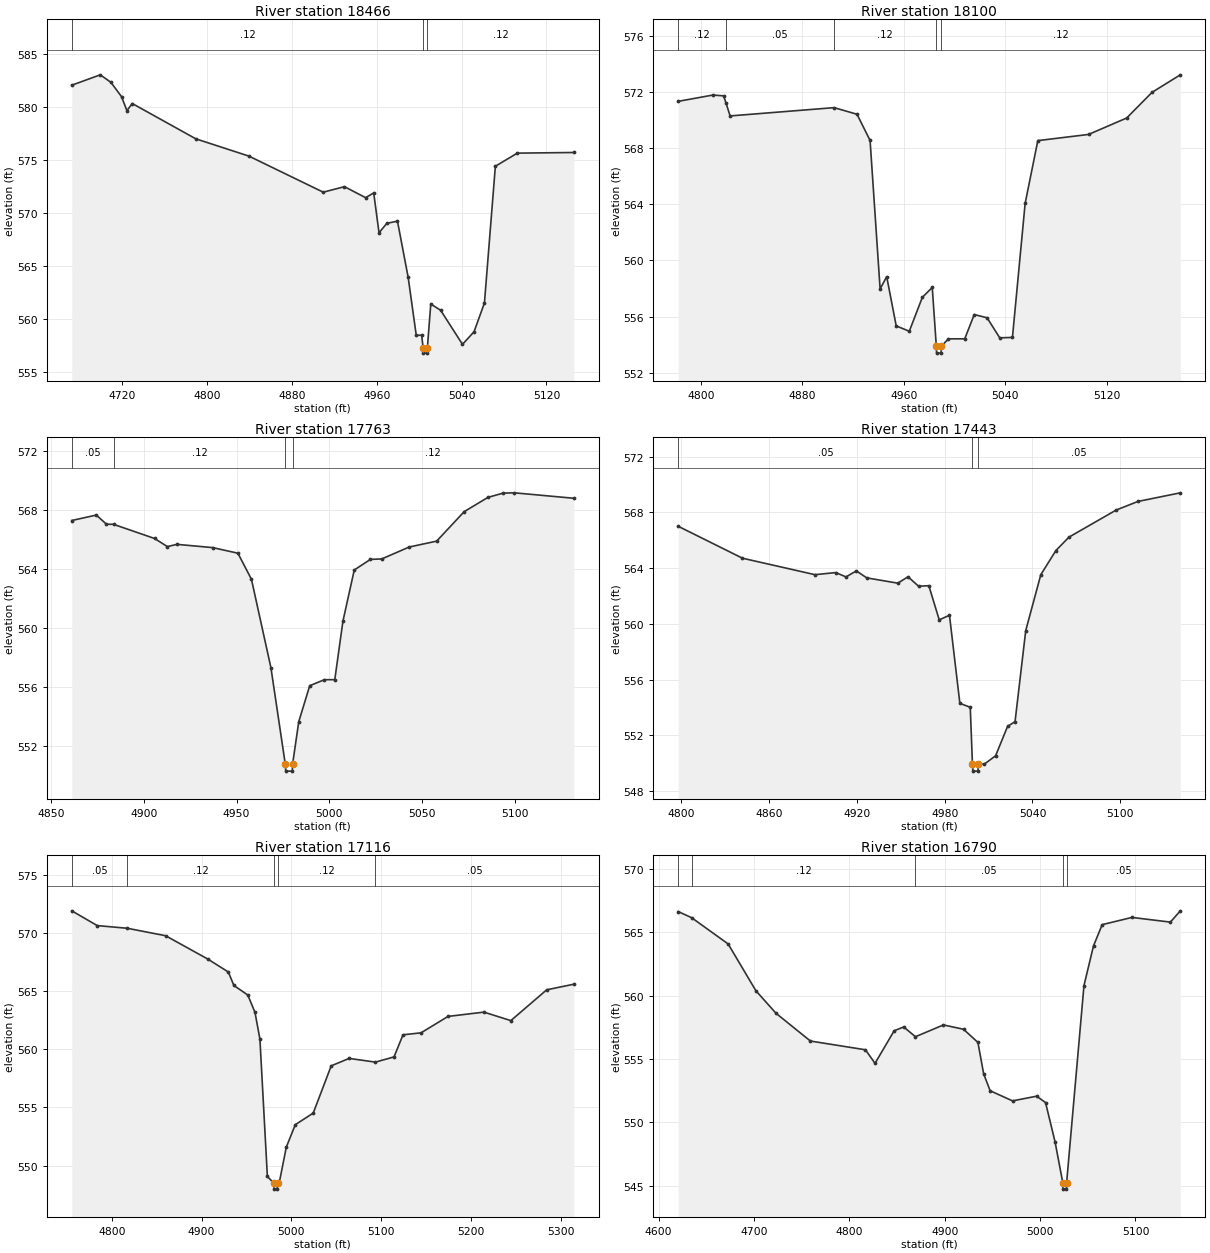
Type RM Length L Ch R = 1 ,18466   ,366,366,366
BEGIN DESCRIPTION:
Bakers Branch 41.0
END DESCRIPTION:
XS GIS Cut Line= 3
      2410271.79      7052396.87      2410285.71      7052069.67
      2410249.52      7051928.33
#Sta/Elev= 30
  4672.5  582.09  4699.4  583.07  4709.4  582.36  4719.4  581.01  4724.5  579.68
  4729.5  580.36  4789.5  577.02  4839.5  575.39  4909.6  571.98  4929.6   572.5
  4949.6  571.46  4957.2  571.91  4962.2  568.14  4969.6  569.04  4979.6  569.24
  4989.7  563.92  4997.3  558.46  5002.4  558.46  5003.8  557.27  5004.1  556.77
  5007.6  556.77  5007.8  557.27    5011  561.41  5020.3  560.82  5040.9   557.6
  5051.8  558.79  5061.6  561.51  5071.9  574.43  5092.6  575.67  5145.9  575.73
#Mann= 3 ,-1 , 0
  4672.5     .12       0  5003.8     .07       0  5007.8     .12       0
Bank Sta=5003.8,5007.8
XS Rating Curve= 0 ,0
Exp/Cntr=0.3,0.1

Type RM Length L Ch R = 1 ,18100   ,337,337,337
BEGIN DESCRIPTION:
Bakers Branch 40.0
END DESCRIPTION:
XS GIS Cut Line= 3
       2410695.6       7051964.5        2410479.        7051910.
      2410306.66      7051912.41
#Sta/Elev= 30
  4782.3  571.34  4809.7  571.79  4818.1  571.73  4819.9  571.23  4823.2   570.3
  4905.1  570.89  4923.2  570.42  4933.5  568.55  4941.4  557.97  4946.6  558.84
  4954.1  555.33  4964.4  554.95  4974.7  557.37  4982.5  558.07  4985.7  553.89
  4985.9  553.39  4989.4  553.39  4989.7  553.89  4995.3  554.41  5008.1  554.41
  5015.6  556.14  5025.7  555.91  5035.7  554.48  5045.7  554.51  5055.7  564.06
  5065.7  568.54  5105.7  568.98  5135.7  570.15  5155.7  571.98    5178  573.23
#Mann= 5 ,-1 , 0
  4782.3     .12       0  4819.9     .05       0  4905.1     .12       0
  4985.7     .07       0  4989.7     .12       0
Bank Sta=4985.7,4989.7
XS Rating Curve= 0 ,0
Exp/Cntr=0.3,0.1

Type RM Length L Ch R = 1 ,17763   ,320,320,320
BEGIN DESCRIPTION:
Bakers Branch 39.0
END DESCRIPTION:
XS GIS Cut Line= 3
      2410669.55      7051792.61        2410629.        7051660.
      2410521.09      7051584.27
#Sta/Elev= 30
  4861.2   567.3  4874.4  567.67  4879.9  567.05  4883.7  567.04  4905.8  566.08
  4912.7  565.53  4917.9  565.68  4937.1  565.46  4950.7  565.08    4958  563.31
  4968.5   557.3  4976.2  550.78  4976.5  550.28    4980  550.28  4980.2  550.78
  4983.5  553.64  4989.4  556.08  4997.3  556.49  5002.9  556.49  5007.3  560.47
  5013.4  563.94  5022.1  564.66  5028.2  564.69    5043   565.5  5057.8   565.9
  5072.6   567.9  5085.4  568.87  5093.6  569.16  5099.7  569.18  5131.7  568.81
#Mann= 4 ,-1 , 0
  4861.2     .05       0  4883.7     .12       0  4976.2     .07       0
  4980.2     .12       0
Bank Sta=4976.2,4980.2
XS Rating Curve= 0 ,0
Exp/Cntr=0.3,0.1

Type RM Length L Ch R = 1 ,17443   ,327,327,327
BEGIN DESCRIPTION:
Bakers Branch 38.0
END DESCRIPTION:
XS GIS Cut Line= 3
      2410733.78      7051856.87        2410879.        7051710.
      2410910.88      7051577.32
#Sta/Elev= 30
    4798     567  4841.9  564.71  4891.4  563.53  4905.6  563.68  4912.6  563.37
  4919.7   563.8  4926.8   563.3    4948  562.92    4955  563.38  4962.2   562.7
  4969.2  562.74  4976.3  560.29  4983.3  560.62  4990.4   554.3  4997.5  554.02
    4999  549.94  4999.3  549.44  5002.8  549.44    5003  549.94  5007.1  549.94
  5014.8  550.54    5023  552.65  5028.1  552.99  5035.4  559.52  5045.7  563.53
    5056  565.26  5064.9  566.22  5097.1  568.16    5112  568.78    5141   569.4
#Mann= 3 ,-1 , 0
    4798     .05       0    4999    .033       0    5003     .05       0
Bank Sta=4999,5003
XS Rating Curve= 0 ,0
Exp/Cntr=0.3,0.1

Type RM Length L Ch R = 1 ,17116   ,326,326,326
BEGIN DESCRIPTION:
Mapping XS 32b685e1
END DESCRIPTION:
XS GIS Cut Line= 3
      2411022.42      7052120.21      2411113.57      7051907.97
      2411101.85      7051579.86
#Sta/Elev= 30
  4755.4  571.91  4783.8  570.64  4817.3  570.41  4859.9  569.77    4907  567.76
  4929.8  566.65    4936  565.49  4951.5  564.67  4959.5  563.18    4965  560.87
  4973.3  549.07  4980.6  548.48  4980.8  547.98  4984.3  547.98  4984.6  548.48
  4986.4  548.48  4994.4  551.59  5004.4  553.52  5024.4  554.52  5044.4  558.58
  5064.4  559.22  5093.7   558.9  5114.4  559.35  5124.4  561.25  5144.5  561.42
  5174.5  562.83  5214.5   563.2  5244.5  562.47  5284.5  565.12  5314.7   565.6
#Mann= 5 ,-1 , 0
  4755.4     .05       0  4817.3     .12       0  4980.6     .07       0
  4984.6     .12       0  5093.7     .05       0
Bank Sta=4980.6,4984.6
XS Rating Curve= 0 ,0
Exp/Cntr=0.3,0.1

Type RM Length L Ch R = 1 ,16790   ,178,178,178
BEGIN DESCRIPTION:
Mapping XS 6c2caf7d
END DESCRIPTION:
XS GIS Cut Line= 5
      2411190.59      7052064.13      2411266.13      7051945.62
      2411275.24      7051824.53      2411212.74      7051728.18
      2411194.51      7051579.71
#Sta/Elev= 30
  4620.6  566.62  4634.6  566.14  4672.9  564.07    4702  560.38  4723.1   558.6
  4759.2  556.41  4816.9  555.72  4826.9  554.65    4847  557.22    4857  557.52
  4869.3  556.75  4898.6  557.68  4919.7  557.34  4934.8   556.3  4940.8  553.83
  4947.6  552.49  4971.1  551.69  4996.3  552.06  5005.7  551.56  5015.7  548.45
  5023.8  545.23  5024.1  544.73  5027.6  544.73  5027.8  545.23    5046  560.79
    5056  563.92  5065.1  565.59  5096.3  566.16  5136.6  565.79    5147  566.68
#Mann= 5 ,-1 , 0
  4620.6     .05       0  4634.6     .12       0  4869.3     .05       0
  5023.8    .033       0  5027.8     .05       0
Bank Sta=5023.8,5027.8
XS Rating Curve= 0 ,0
Exp/Cntr=0.3,0.1

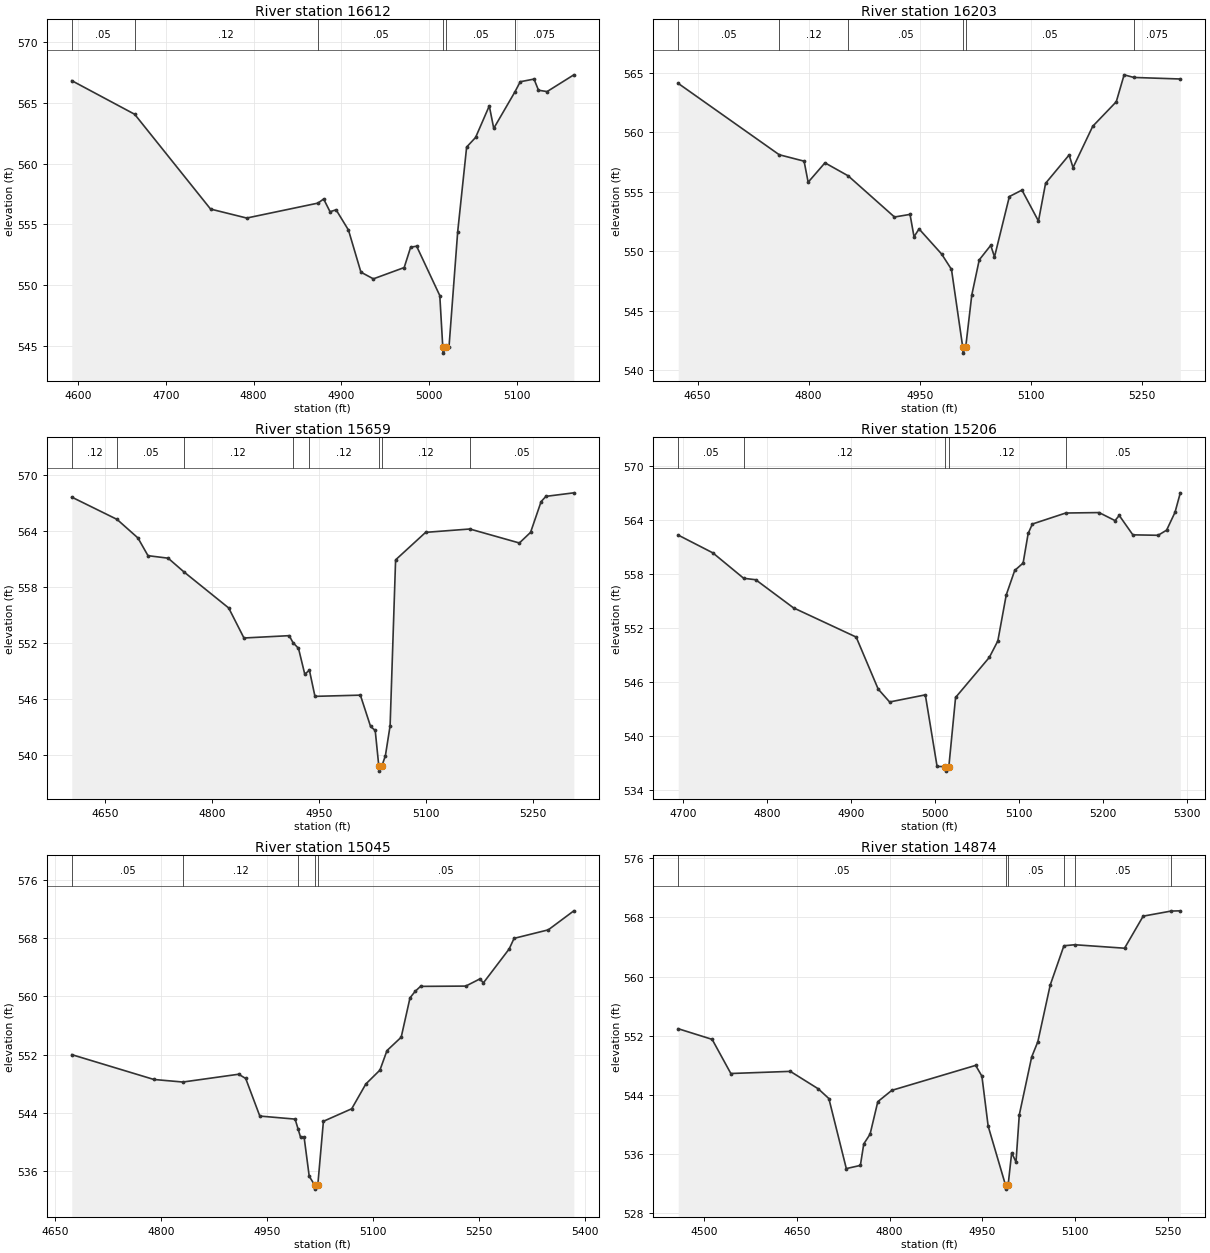
Type RM Length L Ch R = 1 ,16612   ,409,409,409
BEGIN DESCRIPTION:
Mapping XS fe04c256
END DESCRIPTION:
XS GIS Cut Line= 5
      2411260.92      7052118.76      2411275.24      7051957.34
      2411279.15      7051837.55      2411370.29      7051752.92
      2411402.85      7051590.13
#Sta/Elev= 30
  4592.8  566.83  4664.5  564.06    4751  556.25  4792.2  555.51  4873.4  556.74
  4879.9  557.08  4887.2  556.03  4894.1  556.19  4908.2  554.52  4922.4  551.05
  4936.6   550.5  4971.7  551.43  4979.1  553.11  4985.9  553.19  5012.3  549.12
  5015.7  544.88  5015.9  544.38  5019.7  544.88  5022.8  544.89  5032.7  554.38
  5042.9  561.36  5053.1  562.15  5068.7  564.75  5073.8   562.9  5097.9   565.9
    5104  566.74  5119.7  566.96  5124.8  566.04  5134.6  565.93  5165.1  567.31
#Mann= 6 ,-1 , 0
  4592.8     .05       0  4664.5     .12       0  4873.4     .05       0
  5015.7    .033       0  5019.7     .05       0  5097.9    .075       0
Bank Sta=5015.7,5019.7
XS Rating Curve= 0 ,0
Exp/Cntr=0.3,0.1

Type RM Length L Ch R = 1 ,16203   ,544,544,544
BEGIN DESCRIPTION:
Mapping XS 741b2b73
END DESCRIPTION:
XS GIS Cut Line= 5
      2411410.66      7052157.86       2411500.5      7051969.06
      2411534.36      7051863.59      2411400.24      7051838.85
      2411469.26      7051627.88
#Sta/Elev= 30
  4623.8  564.09  4760.2   558.1  4793.8  557.56  4799.3  555.79    4822  557.42
  4853.3  556.33  4915.9  552.87  4936.9  553.09  4942.3  551.21  4949.1  551.87
  4979.6  549.76  4992.9  548.47  5008.1  541.94  5008.4  541.44  5012.1  541.94
  5020.3  546.31  5030.4  549.27  5045.9  550.49    5051  549.52  5071.1  554.59
  5088.1  555.13  5110.4  552.53    5120   555.7  5151.8  558.08  5157.1  557.02
  5183.7  560.49  5215.5  562.55  5226.1  564.81  5239.2  564.59    5302  564.46
#Mann= 6 ,-1 , 0
  4623.8     .05       0  4760.2     .12       0  4853.3     .05       0
  5008.1    .033       0  5012.1     .05       0  5239.2    .075       0
Bank Sta=5008.1,5012.1
XS Rating Curve= 0 ,0
Exp/Cntr=0.3,0.1

Type RM Length L Ch R = 1 ,15659   ,453,453,453
BEGIN DESCRIPTION:
Mapping XS e7841968
END DESCRIPTION:
XS GIS Cut Line= 4
      2411432.26      7052274.61      2411662.29      7052053.26
      2411801.17      7051936.07      2411903.18      7051760.28
#Sta/Elev= 30
  4603.7  567.63  4667.2  565.24  4696.5  563.25  4710.6  561.35  4738.9  561.08
  4760.7  559.63  4823.8  555.74  4845.2  552.52  4908.7  552.77    4914  552.02
  4921.7  551.41  4930.5  548.64    4937  549.06  4944.8  546.26  5008.5  546.39
  5022.8  543.03  5029.3   542.6  5034.4  538.74  5034.6  538.24  5038.4  538.74
  5043.6   539.9  5050.2  543.11  5057.9   560.9    5100  563.85    5162  564.21
  5231.5  562.71  5247.2  563.85    5262  567.15  5268.7  567.71  5307.9  568.09
#Mann= 8 ,-1 , 0
  4603.7     .12       0  4667.2     .05       0  4760.7     .12       0
    4914     .05       0    4937     .12       0  5034.4     .07       0
  5038.4     .12       0    5162     .05       0
Bank Sta=5034.4,5038.4
XS Rating Curve= 0 ,0
Exp/Cntr=0.3,0.1

Type RM Length L Ch R = 1 ,15206   ,161,161,161
BEGIN DESCRIPTION:
Mapping XS cd40d6df
END DESCRIPTION:
XS GIS Cut Line= 3
      2411868.77      7052389.77       2411945.6      7052105.89
      2411917.07      7051803.73
#Sta/Elev= 30
  4694.3  562.31  4735.5  560.34  4772.2  557.52  4786.5  557.36  4831.5  554.24
  4906.1     551  4932.3  545.23  4945.9   543.8  4988.4  544.59  5002.4  536.65
  5012.4  536.63  5012.6  536.13  5016.4  536.63  5024.4   544.3  5064.6  548.75
  5074.7  550.57  5084.7  555.67  5094.8  558.39  5104.8  559.21  5110.8  562.49
  5115.8  563.54  5155.5  564.76  5195.2  564.81  5214.2  563.92  5219.2  564.49
  5235.4  562.34  5265.5  562.29  5275.6  562.86  5285.6  564.84  5291.9     567
#Mann= 5 ,-1 , 0
  4694.3     .05       0  4772.2     .12       0  5012.4     .07       0
  5016.4     .12       0  5155.5     .05       0
Bank Sta=5012.4,5016.4
XS Rating Curve= 0 ,0
Exp/Cntr=0.3,0.1

Type RM Length L Ch R = 1 ,15045   ,171,171,171
BEGIN DESCRIPTION:
Mapping XS 13304132
END DESCRIPTION:
XS GIS Cut Line= 4
      2412079.71      7052336.36       2412073.2      7052009.53
      2412062.78      7051840.26      2412015.91      7051630.62
#Sta/Elev= 30
  4673.1  552.01  4789.5   548.6  4830.5  548.25  4909.5  549.32  4919.5  548.74
  4939.5  543.58  4989.5  543.16  4993.8  541.78  4997.3  540.65  5002.3  540.65
  5009.5  535.32  5017.6  534.05  5017.8  533.55  5021.6  534.05  5029.6  542.86
  5069.7  544.58  5089.7  547.98  5109.7  549.89  5119.7  552.57  5139.8   554.4
  5152.3  559.81  5159.8  560.72  5167.2  561.38  5231.3  561.42  5251.2   562.4
  5256.3  561.87  5292.8  566.52  5299.7  567.97  5348.2  569.14  5384.4  571.75
#Mann= 5 ,-1 , 0
  4673.1     .05       0  4830.5     .12       0  4993.8     .05       0
  5017.6     .05       0  5021.6     .05       0
Bank Sta=5017.6,5021.6
XS Rating Curve= 0 ,0
Exp/Cntr=0.3,0.1

Type RM Length L Ch R = 1 ,14874   ,482,482,482
BEGIN DESCRIPTION:
Mapping XS 85f79d50
END DESCRIPTION:
XS GIS Cut Line= 5
       2412441.9       7052509.4      2412273.27      7052158.63
      2412253.11      7052084.95      2412244.18      7052009.56
      2412232.06      7051740.04
#Sta/Elev= 30
  4458.5  552.94  4513.3   551.5  4543.5  546.88  4639.6  547.17  4684.9   544.8
  4701.9  543.49  4730.1  534.01  4752.8  534.44  4758.3  537.35  4768.5  538.67
    4781  543.07  4803.6   544.6  4939.1  547.98  4949.2  546.52  4959.3  539.76
  4987.5  531.73  4987.7  531.23  4991.5  531.73  4997.3  536.15  5004.3   534.9
  5009.6  541.28  5029.6  549.11  5039.6  551.19  5059.6  558.86  5081.7  564.17
  5099.2  564.31  5179.7  563.84  5209.8  568.18    5255  568.87  5269.8   568.9
#Mann= 6 ,-1 , 0
  4458.5     .05       0  4987.5     .05       0  4991.5     .05       0
  5081.7    .075       0  5099.2     .05       0    5255    .075       0
Bank Sta=4987.5,4991.5
XS Rating Curve= 0 ,0
Exp/Cntr=0.3,0.1

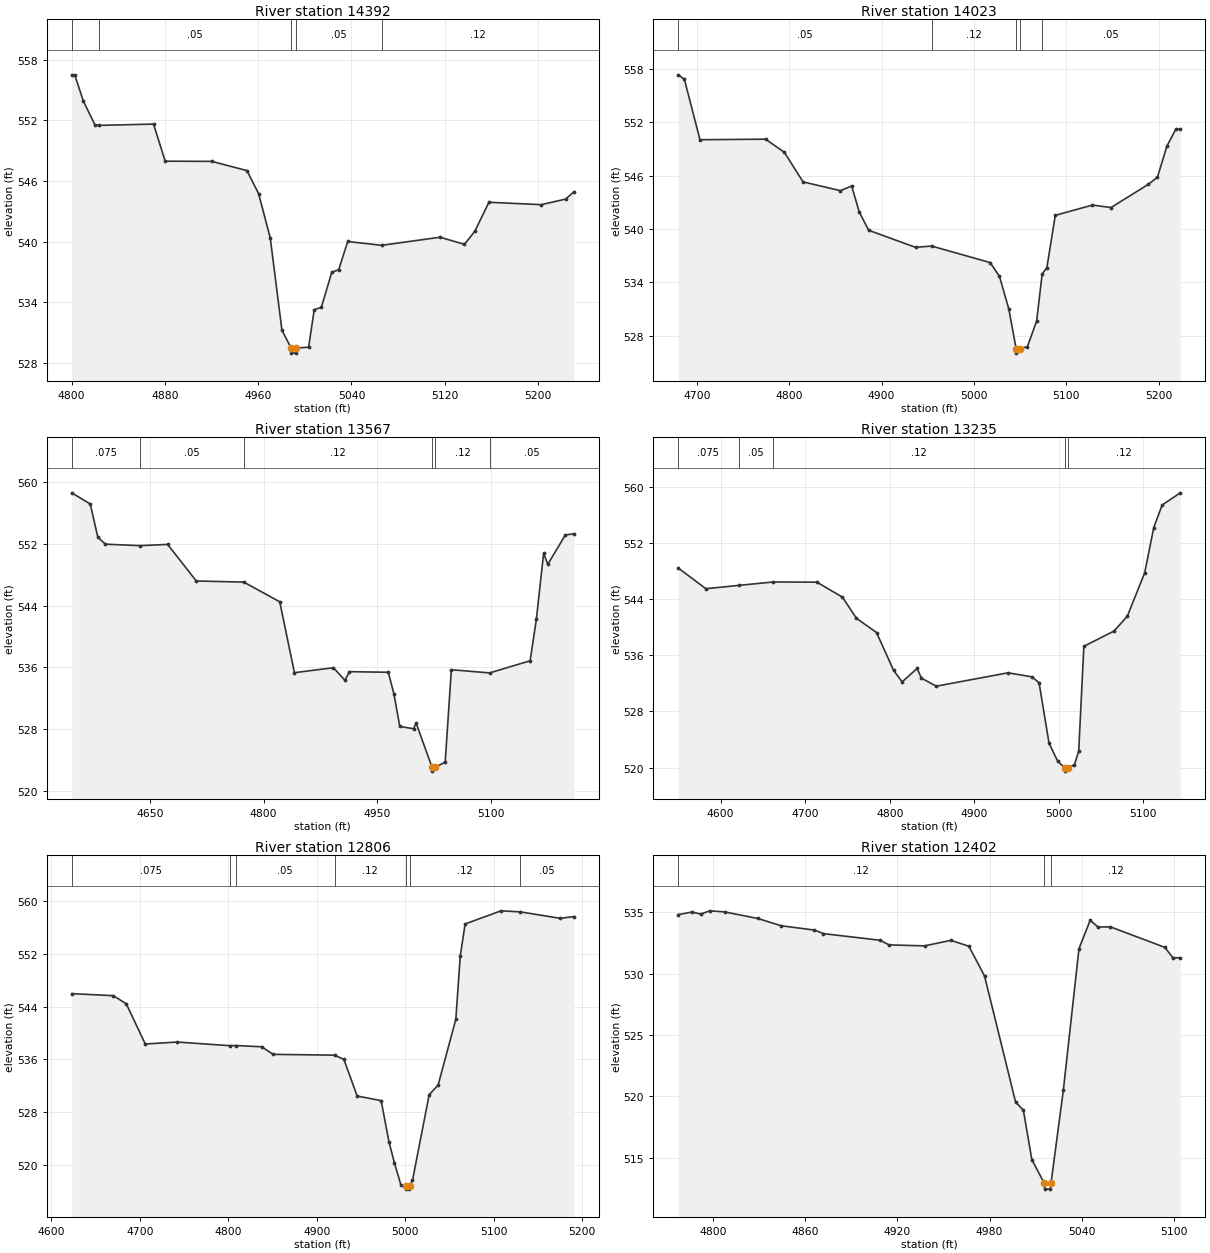
Type RM Length L Ch R = 1 ,14392   ,369,369,369
BEGIN DESCRIPTION:
Bakers Branch 30.0
END DESCRIPTION:
XS GIS Cut Line= 3
        2412479.      7052509.98      2412468.55      7052310.45
      2412598.38      7052119.75
#Sta/Elev= 30
  4800.2  556.51  4802.7  556.51  4810.2  553.89  4820.2  551.54  4823.7  551.51
  4870.3  551.64  4880.3  547.97  4920.3  547.95  4950.4  547.04  4960.4  544.76
  4970.4  540.37  4980.4  531.25  4988.3  529.49  4988.6  528.99  4992.2  528.99
  4992.6  529.49  5003.3  529.58  5008.1  533.29  5014.2  533.51  5023.1  536.98
  5029.1  537.24  5036.8  540.03  5065.9  539.65  5115.9  540.45  5136.9  539.75
  5145.7  541.02  5157.9  543.91  5202.7  543.67  5223.6  544.22  5230.7  544.93
#Mann= 5 ,-1 , 0
  4800.2    .075       0  4823.7     .05       0  4988.3     .05       0
  4992.6     .05       0  5065.9     .12       0
Bank Sta=4988.3,4992.6
XS Rating Curve= 0 ,0
Exp/Cntr=0.3,0.1

Type RM Length L Ch R = 1 ,14023   ,456,456,456
BEGIN DESCRIPTION:
Mapping XS a98e4dca
END DESCRIPTION:
XS GIS Cut Line= 3
      2412733.15      7052533.16      2412783.92      7052233.71
      2412757.88      7051995.45
#Sta/Elev= 30
  4679.9  557.37  4686.6  556.85  4703.4  550.06  4774.4  550.12  4794.7  548.65
    4815  545.31  4855.5  544.32  4867.6  544.85  4875.8  541.92    4886  539.86
  4936.7  537.94  4954.2  538.08  5017.5  536.22  5027.6  534.66  5037.7  530.98
  5045.6  526.52  5045.9  526.02  5049.9  526.52  5057.8  526.75  5067.8  529.63
  5073.8  534.95  5078.9  535.66    5088  541.54  5128.2   542.7  5148.3  542.42
  5188.5  545.02  5198.6  545.84  5208.7  549.32  5218.5  551.25  5223.3  551.25
#Mann= 5 ,-1 , 0
  4679.9     .05       0  4954.2     .12       0  5045.6     .07       0
  5049.9     .12       0  5073.8     .05       0
Bank Sta=5045.6,5049.9
XS Rating Curve= 0 ,0
Exp/Cntr=0.3,0.1

Type RM Length L Ch R = 1 ,13567   ,332,332,332
BEGIN DESCRIPTION:
Mapping XS 75f4b91c
END DESCRIPTION:
XS GIS Cut Line= 4
      2413067.78      7052594.37      2413058.66      7052296.21
      2412976.63      7052171.21      2412889.48      7051974.79
#Sta/Elev= 30
  4546.7   558.6  4571.1  557.15  4581.1  552.85  4591.1  551.95  4636.9  551.76
  4673.2  551.92  4711.1  547.18  4773.7  547.04  4821.2  544.49  4840.6  535.31
  4892.1  535.95  4907.2  534.33  4913.2  535.44  4964.5  535.36    4972  532.53
  4979.6  528.35  4997.8  528.05  5001.2  528.79  5022.2  523.06  5022.6  522.56
  5026.6  523.06  5039.6  523.73  5047.7  535.69  5098.3  535.28  5151.7  536.85
  5159.9   542.2  5169.5  550.76    5175  549.34  5198.2  553.15  5209.4  553.29
#Mann= 6 ,-1 , 0
  4546.7    .075       0  4636.9     .05       0  4773.7     .12       0
  5022.2     .07       0  5026.6     .12       0  5098.3     .05       0
Bank Sta=5022.2,5026.6
XS Rating Curve= 0 ,0
Exp/Cntr=0.3,0.1

Type RM Length L Ch R = 1 ,13235   ,429,429,429
BEGIN DESCRIPTION:
Mapping XS 785b31c1
END DESCRIPTION:
XS GIS Cut Line= 3
      2413184.96      7052482.43      2413229.23      7052162.09
      2413165.44      7051899.11
#Sta/Elev= 30
  4549.8  548.47  4582.5  545.52  4621.2  545.99  4662.3  546.48  4713.8  546.45
  4744.1  544.31  4760.6   541.3  4784.4  539.27  4804.6  533.87  4814.7  532.22
  4832.4  534.14  4837.5  532.76  4855.1  531.61    4940  533.52    4968  532.95
  4976.7  532.11  4988.5  523.47  4998.8  520.89  5006.9  519.99  5007.3  519.49
  5011.3  519.99  5018.5   520.4  5023.6  522.35  5029.7   537.3  5065.4  539.48
  5081.1  541.59  5101.7   547.8  5112.3  554.21  5122.3  557.46  5143.8   559.2
#Mann= 5 ,-1 , 0
  4549.8    .075       0  4621.2     .05       0  4662.3     .12       0
  5006.9     .07       0  5011.3     .12       0
Bank Sta=5006.9,5011.3
XS Rating Curve= 0 ,0
Exp/Cntr=0.3,0.1

Type RM Length L Ch R = 1 ,12806   ,404,404,404
BEGIN DESCRIPTION:
Mapping XS 6c879992
END DESCRIPTION:
XS GIS Cut Line= 3
      2413321.67      7052429.04      2413533.92      7052112.62
      2413566.48        7051929.
#Sta/Elev= 30
  4623.1  545.97  4670.1  545.66  4684.7  544.43  4706.2  538.33  4742.4  538.63
  4802.3  538.07  4808.4   538.1  4837.7  537.91  4850.7  536.76  4920.1  536.64
  4930.7  535.99  4945.7  530.44  4972.8  529.74  4981.7  523.44  4987.8  520.29
  4995.2  516.93  5000.5  516.82  5000.9  516.32  5004.5  516.32  5004.9  516.82
  5008.2  517.63  5027.1  530.65  5037.2   532.1  5057.2  542.08  5062.2  551.67
  5067.7  556.54  5108.3  558.53  5130.2  558.37  5175.4  557.39  5190.6  557.66
#Mann= 7 ,-1 , 0
  4623.1    .075       0  4802.3     .12       0  4808.4     .05       0
  4920.1     .12       0  5000.5     .07       0  5004.9     .12       0
  5130.2     .05       0
Bank Sta=5000.5,5004.9
XS Rating Curve= 0 ,0
Exp/Cntr=0.3,0.1

Type RM Length L Ch R = 1 ,12402   ,312,312,312
BEGIN DESCRIPTION:
Mapping XS b2a29429
END DESCRIPTION:
XS GIS Cut Line= 3
      2413721.38      7052392.59      2413873.77      7052301.42
      2413906.32      7052155.58
#Sta/Elev= 30
  4777.2  534.82  4786.1  535.03  4791.9  534.87  4797.8  535.13  4807.5  535.04
  4828.9  534.51  4844.3  533.91  4865.9  533.56  4871.7  533.27  4908.6  532.73
  4914.5  532.35  4937.6  532.27  4954.8  532.72  4966.5  532.24  4976.7  529.81
  4996.9  519.53    5002  518.85  5007.5  514.83  5015.5  512.92  5015.9  512.42
  5019.5  512.42    5020  512.92    5028  520.47  5038.2  532.04  5045.5  534.36
  5050.6  533.81  5058.7  533.82  5094.1  532.15  5099.4   531.3  5104.2   531.3
#Mann= 3 ,-1 , 0
  4777.2     .12       0  5015.5     .07       0    5020     .12       0
Bank Sta=5015.5,5020
XS Rating Curve= 0 ,0
Exp/Cntr=0.3,0.1

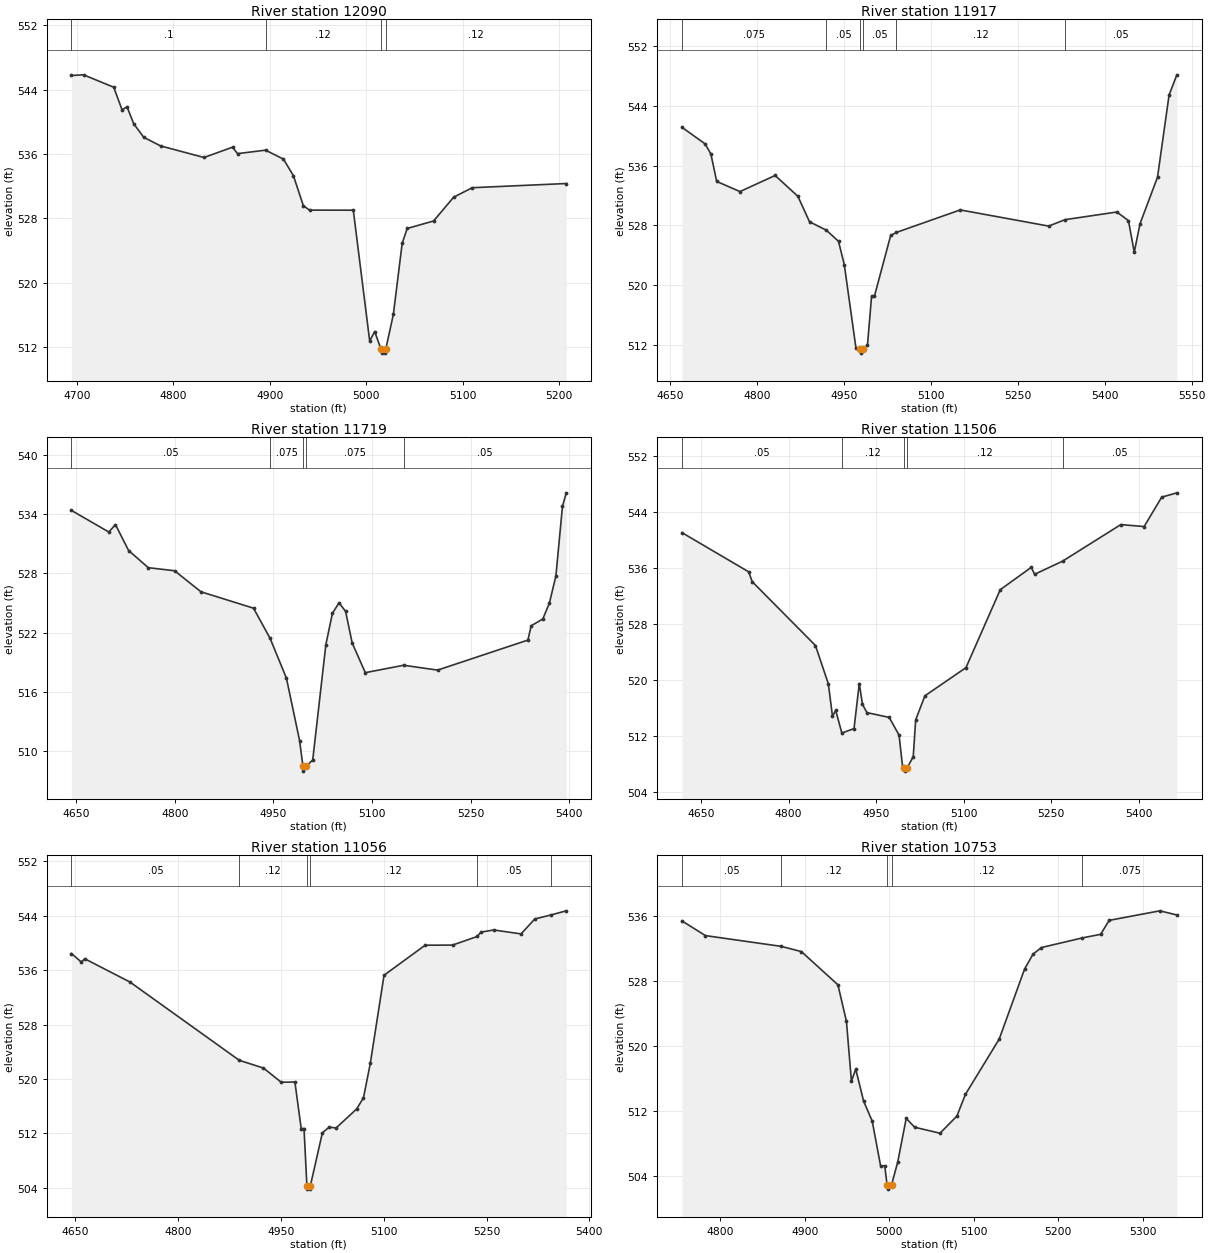
Type RM Length L Ch R = 1 ,12090   ,173,173,173
BEGIN DESCRIPTION:
Mapping XS cd72c582
END DESCRIPTION:
XS GIS Cut Line= 3
      2414109.44      7052602.42      2414182.36      7052331.58
      2414118.11      7052107.59
#Sta/Elev= 30
  4694.1  545.75  4706.7  545.83    4738  544.29  4746.7  541.47  4751.8  541.87
  4758.7  539.77  4769.1  538.08  4786.6  537.01  4831.7  535.57  4861.3  536.85
  4866.5  536.05  4895.5  536.48  4914.1  535.37  4924.4  533.33  4934.8  529.58
  4941.2  529.04  4986.6  529.03  5003.6   512.8  5008.8  513.97  5015.3  511.79
    5016  511.29  5019.7  511.29  5020.3  511.79  5028.2  516.12  5037.3   524.9
  5042.5  526.76  5069.9  527.69  5090.7  530.64    5110  531.82  5207.6  532.34
#Mann= 4 ,-1 , 0
  4694.1      .1       0  4895.5     .12       0  5015.3     .07       0
  5020.3     .12       0
Bank Sta=5015.3,5020.3
XS Rating Curve= 0 ,0
Exp/Cntr=0.3,0.1

Type RM Length L Ch R = 1 ,11917   ,198,198,198
BEGIN DESCRIPTION:
Mapping XS 6d9c99a5
END DESCRIPTION:
XS GIS Cut Line= 4
      2414328.22      7052549.92      2414319.35      7052220.83
      2414316.06      7051970.04      2414304.78      7051696.59
#Sta/Elev= 30
  4670.8  541.15  4710.7  538.93  4720.7  537.56  4730.7  533.89  4770.8  532.53
  4831.5  534.69  4870.8  531.89  4890.8  528.48    4920  527.34  4940.8  525.86
  4950.8  522.72  4970.8   511.6  4978.3  511.36    4979  510.86  4983.3  511.36
  4990.8  511.94  4997.9  518.53  5002.9  518.53  5030.8  526.64  5040.6  527.05
  5150.8  530.07  5303.4   527.9  5331.4  528.76    5421  529.79    5441  528.63
    5451   524.4    5461  528.23  5491.1  534.45  5511.1  545.49  5524.5  548.19
#Mann= 6 ,-1 , 0
  4670.8    .075       0    4920     .05       0  4978.3     .05       0
  4983.3     .05       0  5040.6     .12       0  5331.4     .05       0
Bank Sta=4978.3,4983.3
XS Rating Curve= 0 ,0
Exp/Cntr=0.3,0.1

Type RM Length L Ch R = 1 ,11719   ,213,213,213
BEGIN DESCRIPTION:
Bakers Branch 25.0
END DESCRIPTION:
XS GIS Cut Line= 3
      2414513.11      7052516.93       2414499.1       7052159.9
      2414493.16      7051764.25
#Sta/Elev= 30
  4642.7  534.38  4699.7  532.19  4709.7  532.95  4729.7  530.32  4759.7  528.58
  4799.7  528.27  4839.8  526.14  4919.8  524.48  4944.9  521.44  4969.9  517.39
  4989.9  511.07    4995  508.48  4995.6  507.98    5000  508.48  5009.9  509.11
  5029.9   520.8  5039.9  523.97  5049.9  525.02  5059.9  524.16  5069.9  520.96
  5089.9  517.95  5148.2   518.7  5199.9  518.21  5337.3  521.25  5342.3   522.7
  5359.9  523.38  5369.9  524.97  5379.9  527.74  5389.9   534.8  5395.7  536.16
#Mann= 5 ,-1 , 0
  4642.7     .05       0  4944.9    .075       0    4995     .07       0
    5000    .075       0  5148.2     .05       0
#XS Ineff= 2 , 0
       0                  5049.9       0  525.02
Permanent Ineff=
       F       F
Bank Sta=4995,5000
XS Rating Curve= 0 ,0
Exp/Cntr=0.3,0.1

Type RM Length L Ch R = 1 ,11506   ,450,450,450
BEGIN DESCRIPTION:
Mapping XS 26f66981
END DESCRIPTION:
XS GIS Cut Line= 5
      2414585.14       7052572.9      2414614.65       7052385.4
      2414701.46       7052197.9      2414842.08      7051954.85
      2414833.45      7051783.99
#Sta/Elev= 30
  4617.2  541.02  4731.5  535.42  4737.5  534.02    4846  524.89  4868.1  519.41
  4875.2  514.77  4880.7  515.62  4891.2  512.38  4912.1  513.02  4921.1  519.46
  4926.6  516.49  4934.2   515.3  4972.4  514.62  4989.3  512.08  4995.3  507.61
  4998.3  507.44  4998.9  506.94  5003.4  507.44  5013.6     509  5017.8  514.27
  5033.6   517.7    5104  521.73  5162.8  532.87  5215.9  536.06  5221.7  535.07
  5269.5  536.94  5369.4  542.17  5409.4  541.89  5439.5  546.09  5465.5  546.71
#Mann= 5 ,-1 , 0
  4617.2     .05       0  4891.2     .12       0  4998.3     .07       0
  5003.4     .12       0  5269.5     .05       0
Bank Sta=4998.3,5003.4
XS Rating Curve= 0 ,0
Exp/Cntr=0.3,0.1

Type RM Length L Ch R = 1 ,11056   ,303,303,303
BEGIN DESCRIPTION:
Mapping XS 2bdbe60e
END DESCRIPTION:
XS GIS Cut Line= 3
      2415062.57      7052715.25      2415088.61      7052376.72
      2415081.68      7051994.02
#Sta/Elev= 30
  4644.1  538.43  4658.6  537.18  4663.6  537.66  4729.6  534.24  4889.1  522.75
  4924.4  521.61  4950.3  519.53  4970.3  519.56  4979.5  512.73  4983.6  512.73
  4987.8  504.33  4988.5  503.83  4992.3  503.83  4992.9  504.33  5010.4   512.1
  5020.4  512.94  5030.4  512.81  5060.4   515.6  5070.4  517.25  5080.4  522.32
  5100.4  535.24  5160.4  539.65  5200.4  539.67  5236.4  540.93  5241.9  541.57
  5260.4  541.89  5300.4  541.31  5320.4   543.5  5343.5  544.08  5366.4   544.7
#Mann= 6 ,-1 , 0
  4644.1     .05       0  4889.1     .12       0  4987.8     .07       0
  4992.9     .12       0  5236.4     .05       0  5343.5    .075       0
Bank Sta=4987.8,4992.9
XS Rating Curve= 0 ,0
Exp/Cntr=0.3,0.1

Type RM Length L Ch R = 1 ,10753   ,487,487,487
BEGIN DESCRIPTION:
Mapping XS fa86226d
END DESCRIPTION:
XS GIS Cut Line= 3
      2415349.02      7052601.58      2415390.69      7052365.44
      2415392.43      7052019.93
#Sta/Elev= 30
  4754.9  535.35  4782.7  533.55  4872.3  532.23  4896.1  531.59  4939.3  527.52
  4949.4  523.04  4955.3   515.7  4960.4  517.17  4969.7  513.25  4979.9  510.79
  4989.8  505.31  4994.7  505.31  4997.5  502.95  4998.2  502.45  5002.7  502.95
  5010.1  505.79  5020.1  511.13  5030.1  510.04  5060.1  509.31  5080.1  511.42
  5090.1  514.07  5130.1  520.86  5160.1  529.45  5170.1  531.28  5180.1  532.09
  5228.5  533.27  5250.1  533.71  5260.1  535.42  5320.1  536.59  5340.2  536.08
#Mann= 5 ,-1 , 0
  4754.9     .05       0  4872.3     .12       0  4997.5     .07       0
  5002.7     .12       0  5228.5    .075       0
Bank Sta=4997.5,5002.7
XS Rating Curve= 0 ,0
Exp/Cntr=0.3,0.1

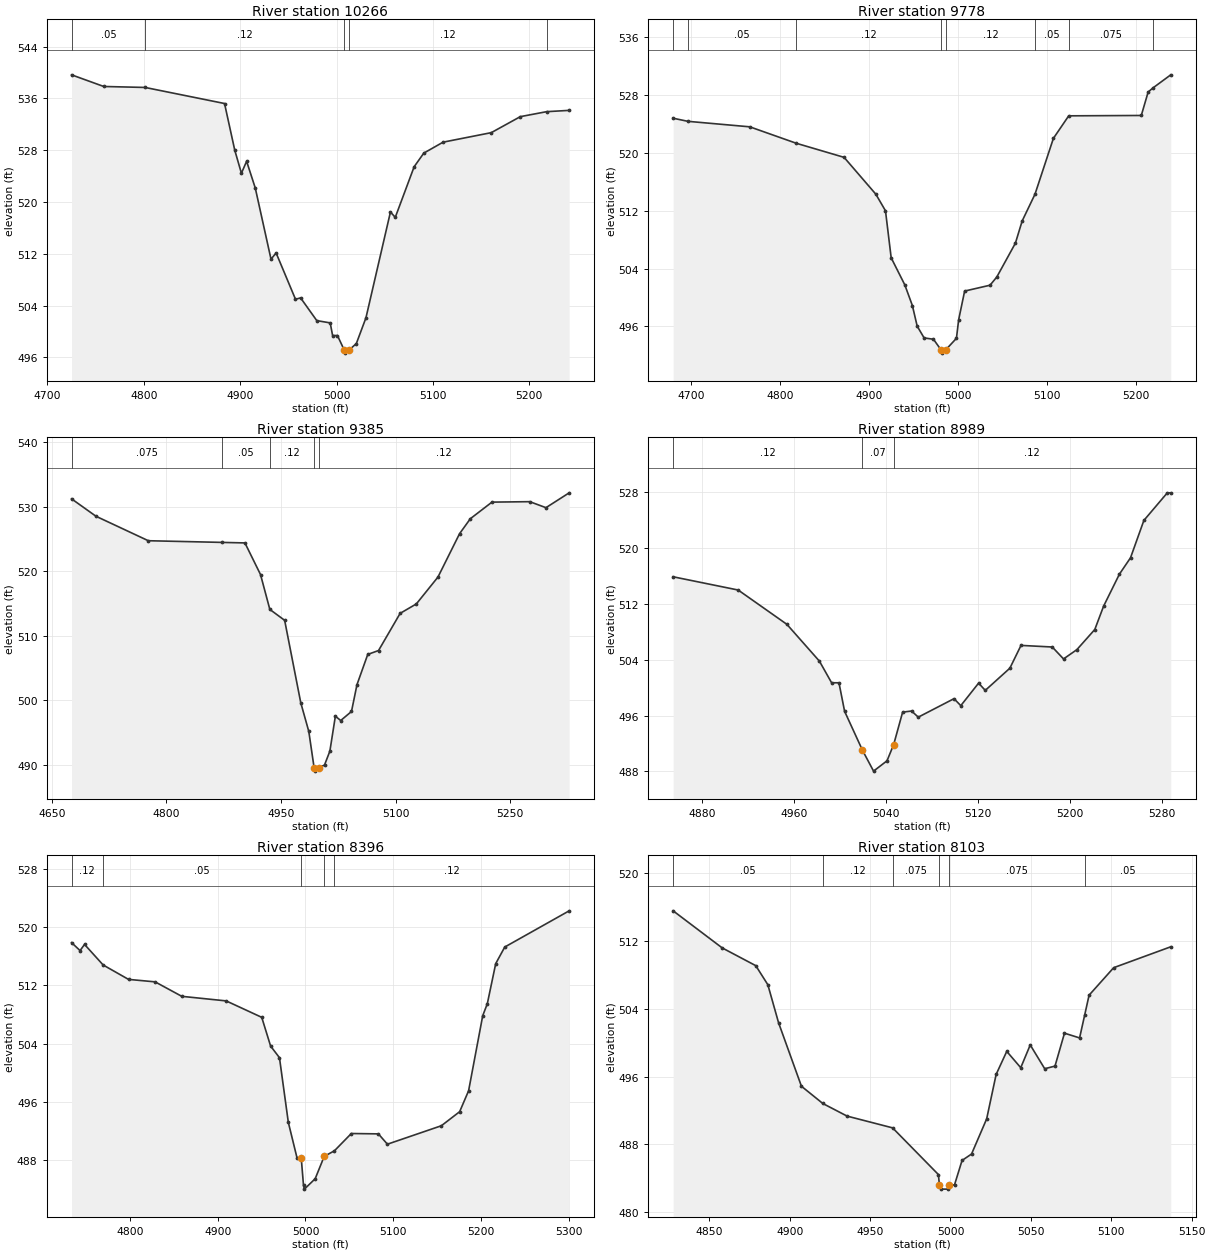
Type RM Length L Ch R = 1 ,10266   ,488,488,488
BEGIN DESCRIPTION:
Mapping XS e86e34ca
END DESCRIPTION:
XS GIS Cut Line= 3
      2415753.68      7052619.29       2415845.7      7052364.06
      2415838.75      7052119.27
#Sta/Elev= 30
  4725.1  539.65  4758.5  537.85  4801.4   537.7  4883.8  535.22  4894.4  528.01
  4901.3  524.45  4906.7   526.3  4915.7  522.16    4932  511.18  4937.3  512.14
  4957.4  504.99  4962.7   505.2  4979.5  501.69  4993.4  501.34  4995.9  499.39
  5000.9  499.39  5007.9  497.17  5008.6  496.67  5013.1  497.17  5020.5  498.14
  5030.5  502.13  5055.9  518.47  5060.9  517.64  5080.5  525.46  5090.5  527.56
  5110.5  529.25  5160.5  530.72  5190.6  533.19  5217.9  533.96  5241.3  534.16
#Mann= 5 ,-1 , 0
  4725.1     .05       0  4801.4     .12       0  5007.9     .07       0
  5013.1     .12       0  5217.9    .075       0
Bank Sta=5007.9,5013.1
XS Rating Curve= 0 ,0
Exp/Cntr=0.3,0.1

Type RM Length L Ch R = 1 ,9778    ,393,393,393
BEGIN DESCRIPTION:
Mapping XS c9dc82b2
END DESCRIPTION:
XS GIS Cut Line= 3
      2416309.24      7052509.89      2416185.98      7052216.49
      2416028.36      7052034.63
#Sta/Elev= 30
  4680.2  524.79  4696.8  524.36  4766.3   523.6  4818.7  521.32  4872.2  519.38
  4907.9  514.28  4918.7  511.99  4925.1  505.49  4940.4  501.75  4948.9  498.89
  4954.3  496.04  4962.1  494.41  4972.6  494.23  4980.8  492.81  4981.8  492.31
  4986.7  492.81  4998.4  494.36  5000.9  496.94  5007.6  500.89  5036.1   501.7
  5043.7  502.83  5064.6  507.51  5072.2  510.58  5086.6  514.28  5107.3  522.01
  5124.5  525.12    5206  525.17  5213.7  528.41  5218.9  528.96  5239.1  530.79
#Mann= 8 ,-1 , 0
  4680.2    .075       0  4696.8     .05       0  4818.7     .12       0
  4980.8     .07       0  4986.7     .12       0  5086.6     .05       0
  5124.5    .075       0  5218.9     .05       0
Bank Sta=4980.8,4986.7
XS Rating Curve= 0 ,0
Exp/Cntr=0.3,0.1

Type RM Length L Ch R = 1 ,9385    ,396,396,396
BEGIN DESCRIPTION:
Mapping XS b0b5d818
END DESCRIPTION:
XS GIS Cut Line= 3
      2416644.31       7052504.7      2416541.88       7052197.4
      2416311.98      7051964.04
#Sta/Elev= 30
  4675.8  531.23  4707.8  528.53  4776.3  524.74  4873.2  524.48  4902.8   524.4
  4923.2   519.5  4935.4   514.1  4954.8  512.41  4975.9  499.64  4986.4   495.2
  4993.4  489.55  4994.4  489.05  4999.3  489.55    5007     490    5014  492.15
  5021.2  497.56  5028.2  496.89  5042.3  498.29  5049.5  502.45  5063.6  507.13
  5077.7  507.73    5106  513.49  5127.2  514.95  5155.5  519.11  5183.8  525.83
  5197.9  528.15  5226.2  530.72  5275.7  530.79  5296.9  529.86  5327.3  532.16
#Mann= 5 ,-1 , 0
  4675.8    .075       0  4873.2     .05       0  4935.4     .12       0
  4993.4     .07       0  4999.3     .12       0
Bank Sta=4993.4,4999.3
XS Rating Curve= 0 ,0
Exp/Cntr=0.3,0.1

Type RM Length L Ch R = 1 ,8989    ,593,593,593
BEGIN DESCRIPTION:
Bakers Branch 19.0
END DESCRIPTION:
XS GIS Cut Line= 3
      2416928.99      7052059.99        2416829.        7051960.
      2416578.96      7051809.98
#Sta/Elev= 30
  4854.9   515.9  4911.5     514  4953.9  509.08  4982.2   503.8  4992.8   500.7
  4999.2   500.7  5004.1  496.61  5019.6  491.04  5029.3  488.03    5041  489.51
  5046.8  491.84  5054.6  496.49  5062.4  496.65  5068.2  495.77  5099.3  498.42
  5105.2  497.42  5120.7  500.65  5126.5  499.61  5147.9  502.79  5157.6  506.06
  5184.8  505.83  5194.6  504.12  5206.2  505.45  5221.8  508.34  5229.5   511.7
  5243.2  516.27  5252.9  518.63  5264.5  523.98  5284.9  527.94  5287.9  527.94
#Mann= 3 ,-1 , 0
  4854.9     .12       0  5019.6     .07       0  5046.8     .12       0
Bank Sta=5019.6,5046.8
XS Rating Curve= 0 ,0
Exp/Cntr=0.3,0.1

Type RM Length L Ch R = 1 ,8396    ,293,293,293
BEGIN DESCRIPTION:
Mapping XS 167f2c95
END DESCRIPTION:
XS GIS Cut Line= 3
      2416972.44      7052074.12      2417012.36      7051815.45
      2416941.19       7051518.6
#Sta/Elev= 30
  4733.5  517.89  4743.2  516.79  4748.3  517.64  4769.5  514.81  4798.4  512.83
  4828.7  512.49  4859.1   510.5  4909.7  509.87  4950.2  507.61  4960.3  503.66
  4970.4  502.06  4980.5  493.16  4990.4  488.28  4995.2  488.28  4997.8  484.48
  4998.8  483.98  5011.1  485.41  5021.4  488.49    5033  489.25  5052.3  491.63
  5083.1  491.58  5093.4  490.16  5154.9   492.7  5175.7  494.63  5185.9  497.51
    5202  507.84  5207.2  509.47  5216.8     515  5227.1  517.28  5300.5  522.26
#Mann= 5 ,-1 , 0
  4733.5     .12       0  4769.5     .05       0  4995.2     .05       0
  5021.4     .05       0    5033     .12       0
Bank Sta=4995.2,5021.4
XS Rating Curve= 0 ,0
Exp/Cntr=0.3,0.1

Type RM Length L Ch R = 1 ,8103    ,330,330,330
BEGIN DESCRIPTION:
Bakers Branch 17.0
END DESCRIPTION:
XS GIS Cut Line= 3
      2417306.38      7051725.67        2417179.        7051610.
      2417062.54      7051537.01
#Sta/Elev= 30
  4827.5  515.58    4858   511.2  4878.9   509.1  4886.4  506.85  4893.1  502.34
  4907.3  494.85  4920.6  492.81  4935.7  491.32    4964  489.93  4992.5  484.41
  4993.1  483.19  4994.2  482.69  4998.2  482.69  4999.2  483.19  5002.5  483.19
  5007.2  486.08  5013.1  486.84  5022.5  490.99  5028.4  496.25    5035  498.97
  5043.7  497.04  5049.6  499.73  5058.6  496.92    5065  497.23  5070.9  501.12
  5080.3  500.56  5083.4  503.21  5086.2  505.61  5101.5  508.86    5137  511.33
#Mann= 6 ,-1 , 0
  4827.5     .05       0  4920.6     .12       0    4964    .075       0
  4993.1     .07       0  4999.2    .075       0  5083.4     .05       0
Bank Sta=4993.1,4999.2
XS Rating Curve= 0 ,0
Exp/Cntr=0.3,0.1