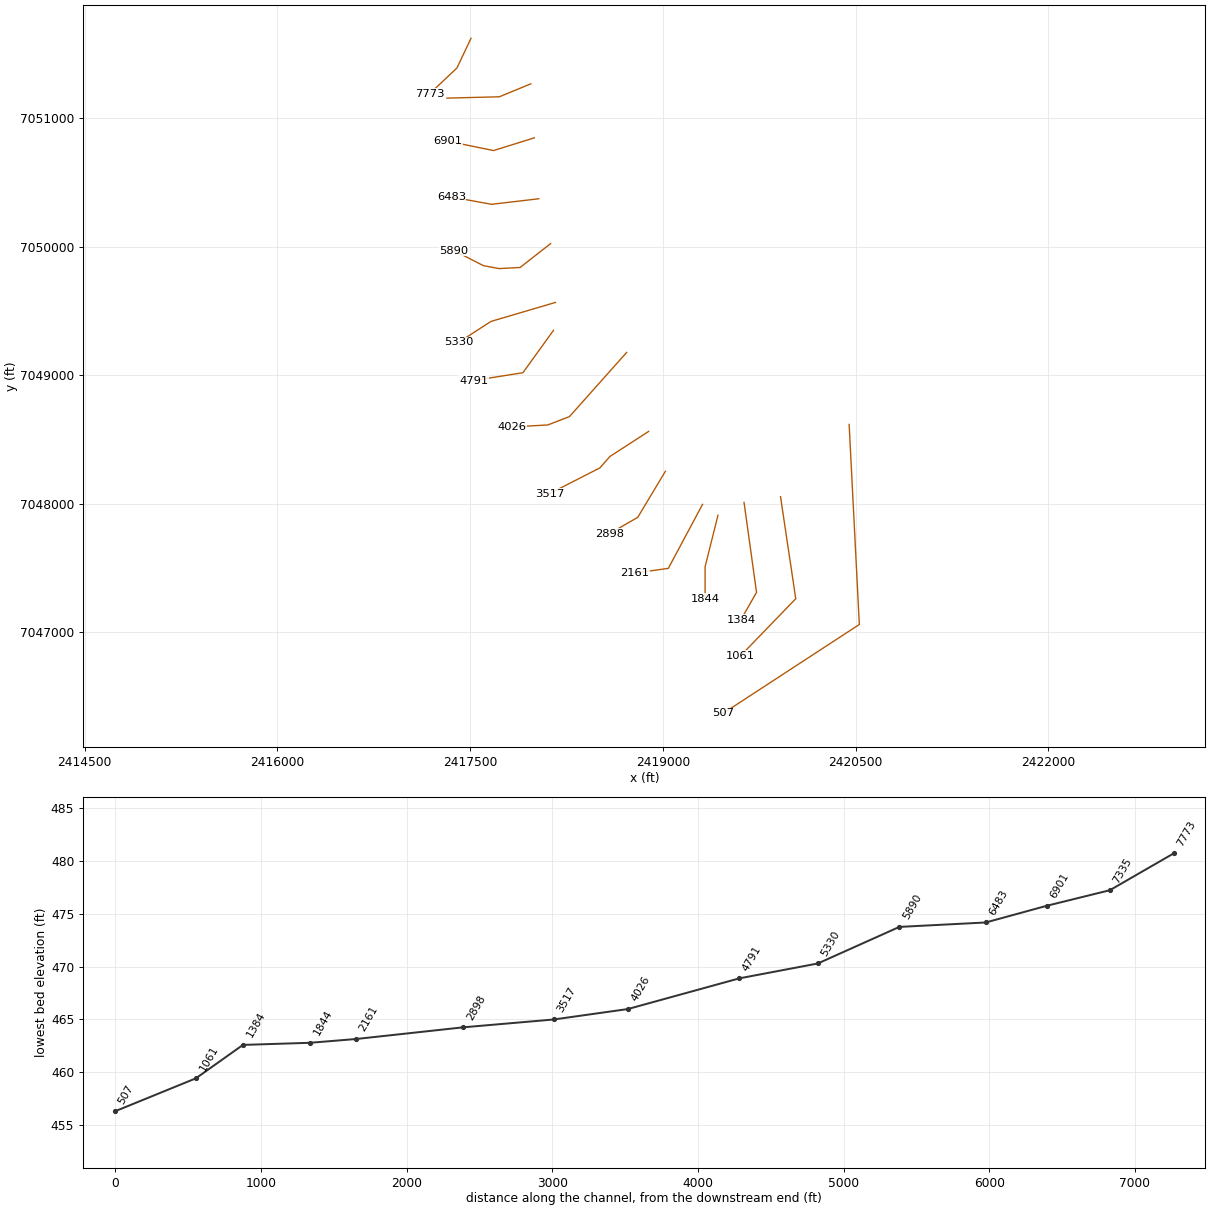
HEC-RAS study Bakers Branch.prj: Bakers Branch Base Level Engineering

--- Bakers Branch.g01 (geometry) --- (continued)

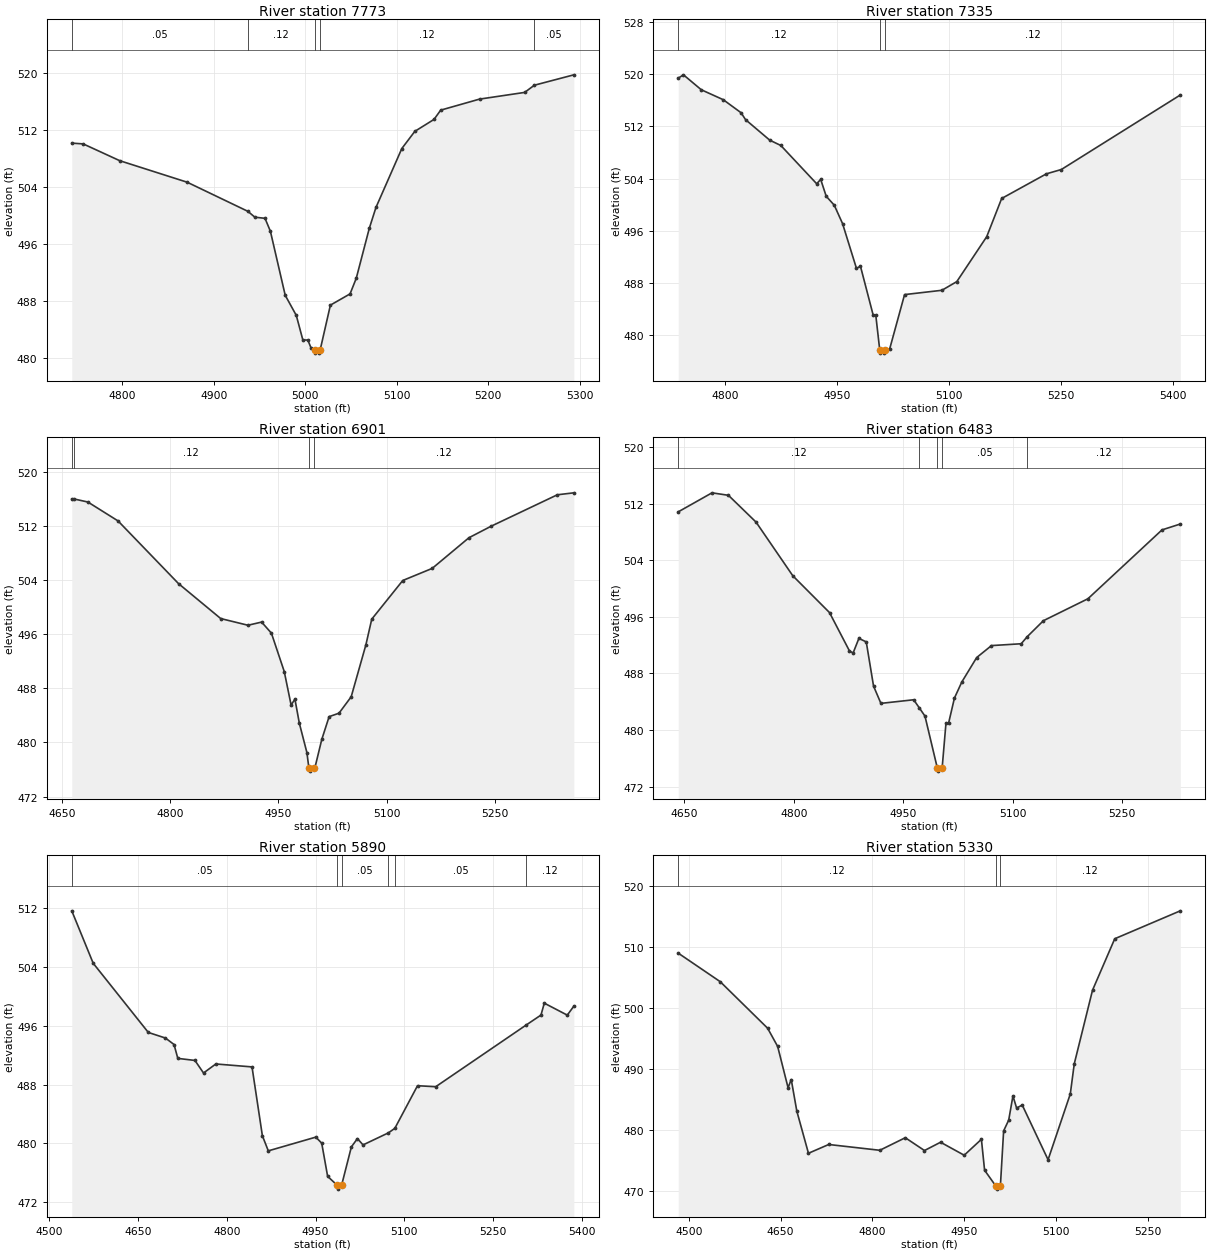
Type RM Length L Ch R = 1 ,7773    ,438,438,438
BEGIN DESCRIPTION:
Mapping XS bace2b3a
END DESCRIPTION:
XS GIS Cut Line= 3
      2417507.14      7051620.97      2417397.78       7051390.1
      2417184.22       7051188.7
#Sta/Elev= 30
  4744.8  510.22  4757.3  510.11  4797.3  507.75    4871  504.73  4937.4  500.64
    4945  499.82  4956.1  499.66    4962  497.84  4978.2  488.85  4990.3  486.03
  4997.5  482.57  5002.9  482.57  5006.6  481.41  5010.3  481.23  5011.3  480.73
  5015.5  480.73  5016.5  481.23  5027.6  487.47  5049.1  489.05  5055.9  491.25
  5070.1  498.24  5077.4  501.18  5105.7  509.46  5119.9  511.87  5140.9  513.55
  5148.2  514.85  5190.7   516.4    5240  517.34  5250.6  518.35  5293.8  519.81
#Mann= 5 ,-1 , 0
  4744.8     .05       0  4937.4     .12       0  5010.3     .07       0
  5016.5     .12       0  5250.6     .05       0
Bank Sta=5010.3,5016.5
XS Rating Curve= 0 ,0
Exp/Cntr=0.3,0.1

Type RM Length L Ch R = 1 ,7335    ,434,434,434
BEGIN DESCRIPTION:
Mapping XS 0fc303f9
END DESCRIPTION:
XS GIS Cut Line= 3
      2417972.41      7051266.83      2417727.64      7051166.15
      2417319.64      7051155.73
#Sta/Elev= 30
  4737.4  519.38  4744.4  519.89  4768.3   517.6  4797.7  516.08  4821.6  514.08
  4827.6  513.02    4860  509.88  4874.9  509.06  4922.9   503.2  4928.3  503.86
  4935.7  501.28  4946.5  499.91  4957.6  497.09  4976.2  490.24  4981.6  490.55
  4998.6  483.08  5002.1  483.08  5007.4  477.74  5008.4  477.24    5013  477.24
  5014.1  477.74  5020.7  477.87  5040.7  486.21  5090.7  486.87  5110.7   488.2
  5150.8  495.09  5170.8  500.94  5230.8  504.72  5250.8  505.38  5410.2   516.8
#Mann= 3 ,-1 , 0
  4737.4     .12       0  5007.4     .07       0  5014.1     .12       0
Bank Sta=5007.4,5014.1
XS Rating Curve= 0 ,0
Exp/Cntr=0.3,0.1

Type RM Length L Ch R = 1 ,6901    ,418,418,418
BEGIN DESCRIPTION:
Mapping XS 6fa30ad3
END DESCRIPTION:
XS GIS Cut Line= 3
      2418000.26      7050846.72       2417682.5      7050747.74
      2417326.61      7050820.66
#Sta/Elev= 30
  4663.6  516.04    4666  516.04  4685.9  515.57  4727.8  512.77  4811.6   503.5
  4870.1  498.33  4907.9  497.34  4926.8  497.81  4940.4  496.17  4958.2  490.49
  4967.7  485.54    4973  486.41  4979.1  482.85  4989.6   478.5  4992.3  476.26
  4993.3  475.76    4999  476.26  5000.7  476.26  5010.2  480.44  5020.4  483.82
  5034.1  484.33    5051  486.76  5071.4  494.45  5079.5  498.24  5122.5  503.96
  5163.3  505.75  5214.3  510.29    5245  511.99  5336.8  516.64  5359.7  516.93
#Mann= 4 ,-1 , 0
  4663.6     .05       0    4666     .12       0  4992.3     .07       0
    4999     .12       0
Bank Sta=4992.3,4999
XS Rating Curve= 0 ,0
Exp/Cntr=0.3,0.1

Type RM Length L Ch R = 1 ,6483    ,593,593,593
BEGIN DESCRIPTION:
Mapping XS f6cc4084
END DESCRIPTION:
XS GIS Cut Line= 3
      2418034.98      7050372.75      2417666.88      7050329.34
      2417354.34      7050386.64
#Sta/Elev= 30
  4641.5  510.84  4687.8  513.53  4710.3  513.18  4748.2  509.39  4798.6   501.8
  4848.9   496.6  4876.3  491.17  4881.3  490.89  4889.2  492.95  4899.3  492.45
  4909.3   486.2  4919.4  483.76  4964.3  484.27  4971.8  483.16  4979.8  481.96
  4996.6  474.68  4997.6  474.18  5003.4  474.68  5008.6  480.97  5012.2  480.97
  5020.2  484.51  5030.3  486.78  5050.7  490.24    5071  491.93  5111.7  492.19
  5120.2  493.21  5142.2  495.45  5203.2  498.55  5304.8  508.29  5329.9  509.12
#Mann= 5 ,-1 , 0
  4641.5     .12       0  4971.8     .05       0  4996.6    .033       0
  5003.4     .05       0  5120.2     .12       0
Bank Sta=4996.6,5003.4
XS Rating Curve= 0 ,0
Exp/Cntr=0.3,0.1

Type RM Length L Ch R = 1 ,5890    ,560,560,560
BEGIN DESCRIPTION:
Mapping XS 4739853b
END DESCRIPTION:
XS GIS Cut Line= 5
      2418126.95      7050023.79       2417889.1      7049838.02
      2417725.91      7049829.34      2417604.38      7049851.91
      2417373.71      7049969.85
#Sta/Elev= 30
  4538.3  511.65  4574.5  504.51  4667.6  495.09  4696.5  494.33    4711  493.45
  4717.4  491.56  4746.3  491.28  4760.8  489.57  4781.6   490.8  4842.7   490.4
  4860.2  481.03  4870.2  478.97  4950.4  480.84  4960.4  480.02  4970.4   475.5
  4986.9  474.26    4988  473.76  4993.9  474.26  5010.5  479.51  5020.7  480.64
  5030.2  479.78    5073  481.42  5083.9  482.04  5122.2  487.84  5152.9   487.7
  5305.1  496.07  5330.7  497.46  5336.3  499.08  5375.1  497.45  5386.2  498.67
#Mann= 6 ,-1 , 0
  4538.3     .05       0  4986.9     .05       0  4993.9     .05       0
    5073     .12       0  5083.9     .05       0  5305.1     .12       0
Bank Sta=4986.9,4993.9
XS Rating Curve= 0 ,0
Exp/Cntr=0.3,0.1

Type RM Length L Ch R = 1 ,5330    ,539,539,539
BEGIN DESCRIPTION:
Mapping XS 09a26236
END DESCRIPTION:
XS GIS Cut Line= 3
      2418164.83      7049565.98      2417663.06       7049418.4
       2417413.5      7049257.23
#Sta/Elev= 30
  4482.8  508.99  4551.4  504.31  4628.8  496.68  4645.2  493.69  4662.2  486.92
  4667.4  488.26  4676.5  483.08  4695.5  476.17  4728.6  477.61    4812  476.66
  4853.7  478.72    4885  476.62  4911.3  477.98  4949.9  475.85    4978  478.46
  4983.2  473.39  5001.6  470.79  5002.8  470.29    5009  470.79  5014.3  479.84
  5022.6  481.61  5029.5  485.57  5035.5  483.59  5044.7  484.08  5086.9  475.11
  5123.2   485.9  5129.7  490.85  5159.5  502.91  5195.8  511.35  5302.9  515.93
#Mann= 3 ,-1 , 0
  4482.8     .12       0  5001.6     .07       0    5009     .12       0
Bank Sta=5001.6,5009
XS Rating Curve= 0 ,0
Exp/Cntr=0.3,0.1

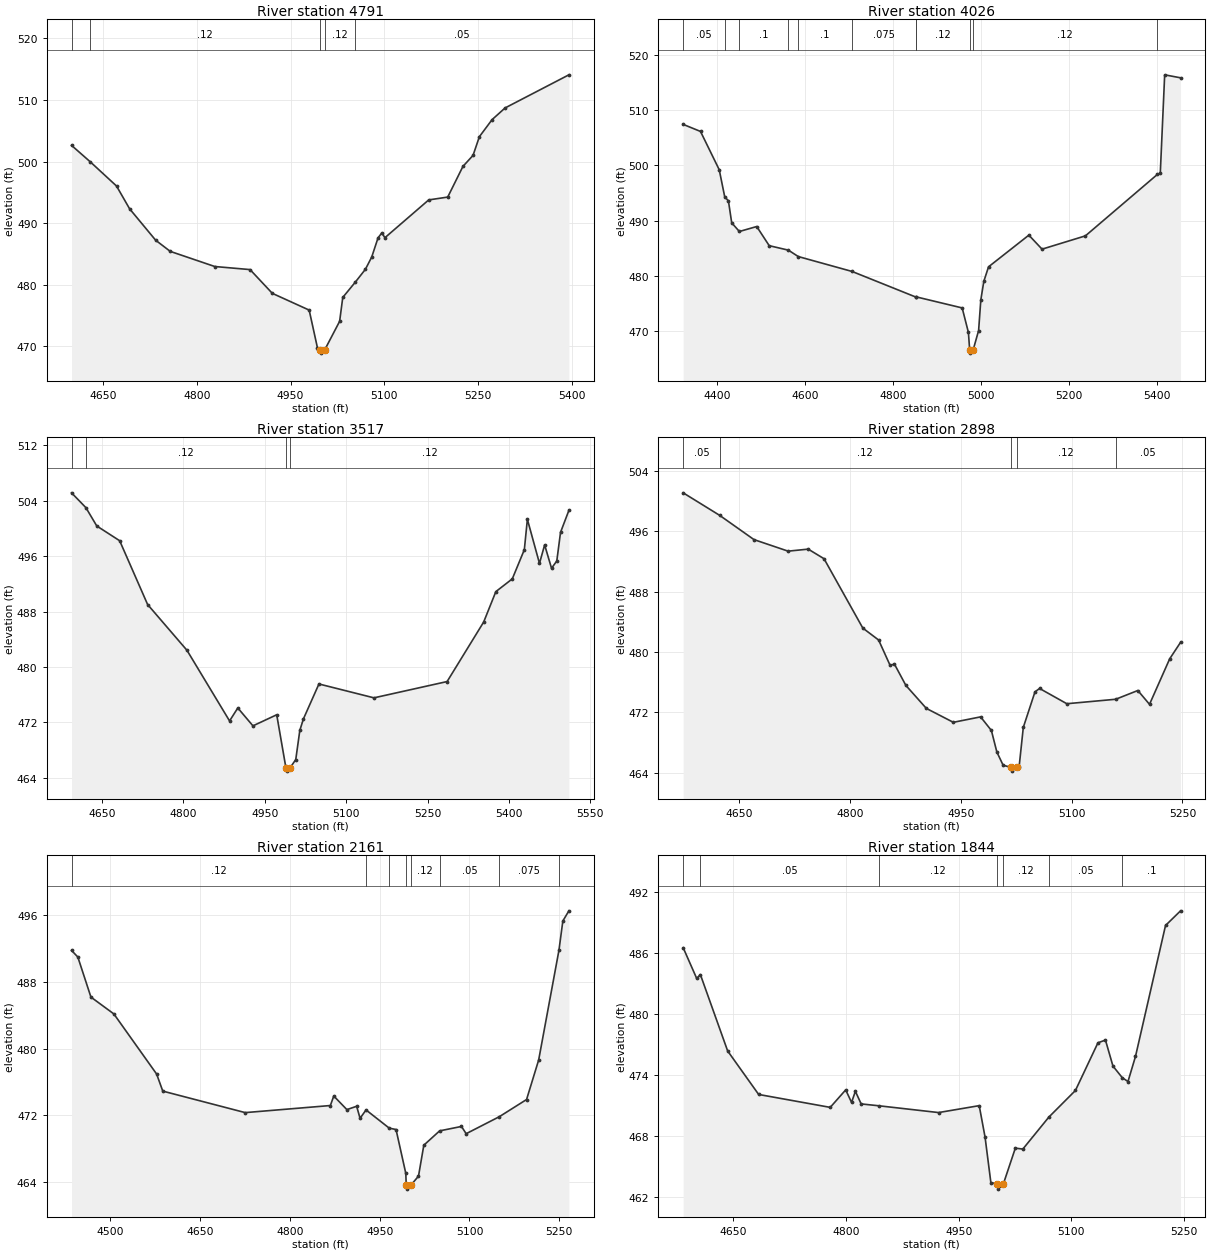
Type RM Length L Ch R = 1 ,4791    ,765,765,765
BEGIN DESCRIPTION:
Mapping XS 80e10f78
END DESCRIPTION:
XS GIS Cut Line= 3
      2418149.18      7049348.97      2417911.32       7049019.1
      2417527.69      7048958.34
#Sta/Elev= 30
  4599.8  502.63  4629.5  499.98  4671.7  496.03  4692.6  492.33  4734.3  487.22
  4757.6  485.41  4828.8  482.95  4885.2  482.45  4920.8  478.59  4979.7  475.87
    4993  469.71  4996.8  469.38    4998  468.88  5004.4  469.38  5028.4  474.05
  5033.4  477.93  5053.2  480.38  5069.6   482.5  5079.7  484.49  5089.8  487.61
  5095.8   488.4  5100.8  487.63  5170.8  493.77  5201.2  494.23  5225.5  499.21
  5241.7  501.01  5251.8  504.04  5272.1  506.81  5292.9  508.71  5394.9  514.09
#Mann= 5 ,-1 , 0
  4599.8     .05       0  4629.5     .12       0  4996.8     .07       0
  5004.4     .12       0  5053.2     .05       0
Bank Sta=4996.8,5004.4
XS Rating Curve= 0 ,0
Exp/Cntr=0.3,0.1

Type RM Length L Ch R = 1 ,4026    ,509,509,509
BEGIN DESCRIPTION:
Mapping XS 0ff5a5c3
END DESCRIPTION:
XS GIS Cut Line= 4
      2418718.19      7049176.65       2418273.3      7048677.52
      2418104.03      7048612.41      2417822.92      7048597.28
#Sta/Elev= 30
    4322  507.42  4361.4  506.14    4404   499.2  4416.5  494.29  4424.9  493.56
  4432.4  489.58  4449.8  488.01  4489.3  488.91  4517.7  485.44  4561.3  484.63
  4583.8  483.47  4706.2  480.77    4851  476.14  4851.8  476.17  4956.7  474.16
  4970.9  469.72  4973.8  466.47  4974.9  465.97  4981.4  466.47  4994.1  470.07
  4999.1   475.6  5005.9  478.97  5016.7  481.61  5108.4  487.35  5138.4  484.81
  5237.1  487.22  5400.9  498.36  5407.4  498.55  5417.4   516.4  5453.5  515.86
#Mann= 11 ,-1 , 0
    4322     .05       0  4416.5    .075       0  4449.8      .1       0
  4561.3    .075       0  4583.8      .1       0  4706.2    .075       0
    4851     .05       0  4851.8     .12       0  4973.8     .07       0
  4981.4     .12       0  5400.9      .1       0
Bank Sta=4973.8,4981.4
XS Rating Curve= 0 ,0
Exp/Cntr=0.3,0.1

Type RM Length L Ch R = 1 ,3517    ,619,619,619
BEGIN DESCRIPTION:
Mapping XS 9d21fe1e
END DESCRIPTION:
XS GIS Cut Line= 4
      2418889.62       7048562.5      2418587.97      7048367.19
      2418509.85      7048278.21      2418119.18      7048078.54
#Sta/Elev= 30
  4593.9  505.12  4620.4  502.98  4640.4  500.34  4682.6  498.21  4734.1  489.01
  4806.6  482.41  4885.1  472.22  4900.3  474.09  4928.2  471.51    4972  473.11
  4988.9  465.48  4990.1  464.98  4996.8  465.48  5007.1  466.65  5014.6  470.87
  5021.3  472.53  5049.8  477.55  5151.2  475.55    5286   477.9  5353.4  486.49
  5375.8  490.87  5406.1  492.71  5428.3  496.92  5433.9   501.3  5456.2  494.94
  5465.7  497.61  5478.4  494.24  5488.1  495.29    5495  499.42  5510.4  502.59
#Mann= 4 ,-1 , 0
  4593.9     .05       0  4620.4     .12       0  4988.9     .07       0
  4996.8     .12       0
Bank Sta=4988.9,4996.8
XS Rating Curve= 0 ,0
Exp/Cntr=0.3,0.1

Type RM Length L Ch R = 1 ,2898    ,737,737,737
BEGIN DESCRIPTION:
Mapping XS 792756af
END DESCRIPTION:
XS GIS Cut Line= 3
      2419019.84      7048252.19      2418804.99       7047894.1
      2418583.83      7047766.17
#Sta/Elev= 30
  4574.4  501.07  4623.9  498.08  4670.2  494.88  4716.4  493.35  4743.6  493.62
    4765  492.35  4817.5  483.17  4838.9  481.59  4854.4  478.24  4860.3   478.4
  4875.8  475.58  4903.5  472.54    4940   470.7  4976.9  471.42  4991.5  469.62
  4998.9  466.77  5007.4  465.02    5018  464.74  5019.2  464.24    5026  464.74
    5029  464.78  5034.7  470.03  5050.5  474.73  5056.7  475.18  5093.6  473.16
  5159.7  473.75  5189.7  474.91  5205.5  473.08  5232.8   479.1  5247.5  481.28
#Mann= 5 ,-1 , 0
  4574.4     .05       0  4623.9     .12       0    5018     .07       0
    5026     .12       0  5159.7     .05       0
Bank Sta=5018,5026
XS Rating Curve= 0 ,0
Exp/Cntr=0.3,0.1

Type RM Length L Ch R = 1 ,2161    ,317,317,317
BEGIN DESCRIPTION:
Bakers Branch 5.0
END DESCRIPTION:
XS GIS Cut Line= 3
       2419308.9      7047994.37      2419042.58      7047496.52
        2418779.        7047460.
#Sta/Elev= 30
  4435.4  491.77  4445.9  490.98  4467.8  486.17  4506.1  484.15  4577.5  476.94
  4587.8  474.89  4725.5  472.31  4867.7  473.16  4873.4   474.3  4895.3  472.67
  4911.6  473.07  4917.3  471.63  4927.3  472.63    4966  470.45  4977.4  470.28
  4993.7  465.02  4994.4  463.63  4995.6  463.13  5002.5  463.63  5014.9  464.69
  5023.8   468.4  5050.2  470.12  5086.7  470.65  5094.5  469.78  5149.9  471.82
  5195.4  473.88  5215.6  478.62  5249.5  491.79    5256   495.3  5266.1  496.52
#Mann= 8 ,-1 , 0
  4435.4     .12       0  4927.3     .05       0    4966     .12       0
  4994.4     .07       0  5002.5     .12       0  5050.2     .05       0
  5149.9    .075       0  5249.5      .1       0
Bank Sta=4994.4,5002.5
XS Rating Curve= 0 ,0
Exp/Cntr=0.3,0.1

Type RM Length L Ch R = 1 ,1844    ,460,460,460
BEGIN DESCRIPTION:
Bakers Branch 4.0
END DESCRIPTION:
XS GIS Cut Line= 3
      2419428.99      7047909.97        2419329.        7047510.
        2419329.      7047259.98
#Sta/Elev= 30
  4583.2  486.51  4601.2  483.49  4606.1  483.87  4642.4  476.36  4683.7  472.08
    4779  470.81  4799.6  472.53  4807.4   471.3  4812.5  472.39  4820.2  471.15
  4844.6  470.96  4923.3   470.3  4977.4  470.98  4985.2  467.88  4992.9  463.42
  5001.4  463.27  5002.6  462.77  5009.5  463.27  5025.5   466.8  5035.5  466.71
  5070.1  469.85  5105.5  472.47  5135.5  477.16  5145.5  477.43  5155.5  474.87
  5167.9  473.73  5175.5  473.35  5185.5  475.82  5225.5   488.7  5245.5  490.14
#Mann= 7 ,-1 , 0
  4583.2     .12       0  4606.1     .05       0  4844.6     .12       0
  5001.4     .07       0  5009.5     .12       0  5070.1     .05       0
  5167.9      .1       0
Bank Sta=5001.4,5009.5
XS Rating Curve= 0 ,0
Exp/Cntr=0.3,0.1

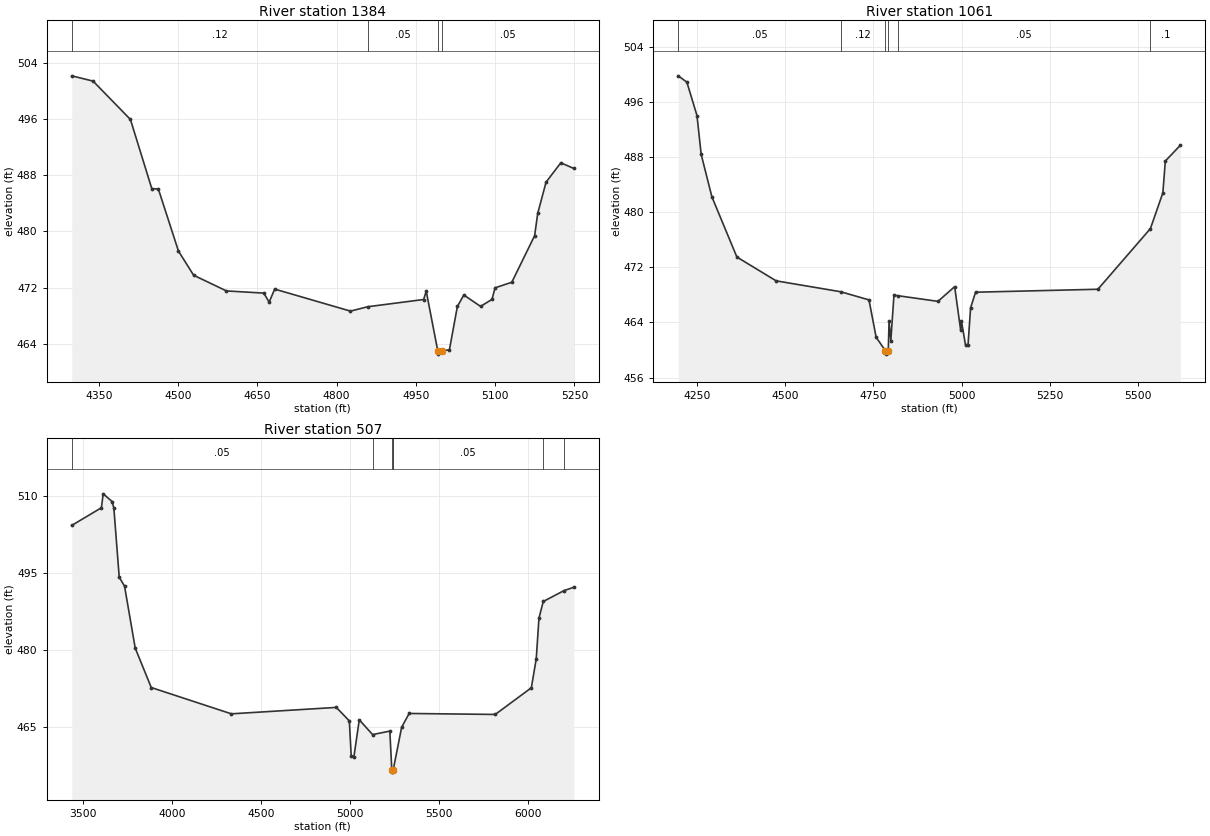
Type RM Length L Ch R = 1 ,1384    ,323,323,323
BEGIN DESCRIPTION:
Bakers Branch 3.0
END DESCRIPTION:
XS GIS Cut Line= 3
      2419631.81      7048009.95        2419729.        7047310.
      2419608.38      7047098.54
#Sta/Elev= 30
  4298.8  502.11  4339.1  501.36  4409.8  495.91  4450.2  486.09  4462.7  486.02
  4500.7  477.21  4529.4  473.78  4591.5  471.55  4662.2  471.24  4672.3  469.95
  4682.8  471.81  4826.2  468.68  4858.6   469.3  4964.6  470.33  4969.6   471.5
  4991.3  463.07  4992.5  462.57  4999.4  463.07  5013.4  463.17  5028.5  469.34
  5040.7  470.97  5072.4  469.35    5094  470.35  5099.8  471.99  5131.5  472.78
  5174.7   479.4  5180.5  482.55  5196.3     487  5224.2  489.75  5248.9  488.95
#Mann= 4 ,-1 , 0
  4298.8     .12       0  4858.6     .05       0  4991.3    .033       0
  4999.4     .05       0
Bank Sta=4991.3,4999.4
XS Rating Curve= 0 ,0
Exp/Cntr=0.3,0.1

Type RM Length L Ch R = 1 ,1061    ,554,554,554
BEGIN DESCRIPTION:
Bakers Branch 2.0
END DESCRIPTION:
XS GIS Cut Line= 3
      2419915.67      7048054.24      2420034.18      7047260.44
      2419603.77       7046815.3
#Sta/Elev= 30
  4197.4  499.85  4221.9  498.93  4250.5  494.07  4262.4  488.42  4292.7  482.26
  4363.5  473.51  4474.7  470.05  4657.3  468.47  4737.6  467.28  4757.8  461.85
  4784.1   459.9  4785.3   459.4  4792.2   459.9  4794.4   464.2  4799.4  461.35
  4808.3  467.97  4818.4   467.9  4932.9  467.07  4980.2  469.21  4997.1  462.92
  4999.4  464.19  5011.1  460.66  5018.1  460.76  5025.3  466.12  5039.4   468.4
  5385.9  468.83  5534.6  477.65  5569.8  482.85  5576.8  487.47  5619.2  489.75
#Mann= 6 ,-1 , 0
  4197.4     .05       0  4657.3     .12       0  4784.1    .033       0
  4792.2     .12       0  4818.4     .05       0  5534.6      .1       0
Bank Sta=4784.1,4792.2
XS Rating Curve= 0 ,0
Exp/Cntr=0.3,0.1

Type RM Length L Ch R = 1 ,507     ,0,0,0
BEGIN DESCRIPTION:
Bakers Branch 1.0
END DESCRIPTION:
XS GIS Cut Line= 3
      2420449.59      7048616.51        2420529.        7047060.
      2419468.71      7046368.28
#Sta/Elev= 30
    3436  504.31  3602.7  507.75  3612.7  510.46  3662.8  508.96  3672.8  507.68
  3702.9  494.24  3732.9  492.48    3793  480.42  3883.1  472.75  4333.7  467.63
  4924.4  468.88  4997.5  466.25  5008.1  459.37  5023.2  459.26  5053.4  466.46
  5128.4  463.59  5225.3  464.27  5236.3  456.78  5237.6  456.28  5244.6  456.78
  5244.8   456.8  5291.8  465.02    5334   467.7  5818.4  467.51  6021.4   472.7
    6049  478.34  6064.2  486.24  6088.4   489.5  6204.7  491.61  6260.5  492.27
#Mann= 7 ,-1 , 0
    3436     .05       0  5128.4     .12       0  5236.3    .033       0
  5244.6     .12       0  5244.8     .05       0  6088.4      .1       0
  6204.7    .075       0
Bank Sta=5236.3,5244.6
XS Rating Curve= 0 ,0
Exp/Cntr=0.3,0.1

Chan Stop Cuts=-1
Use User Specified Reach Order=0
Composite Channel Slope=5