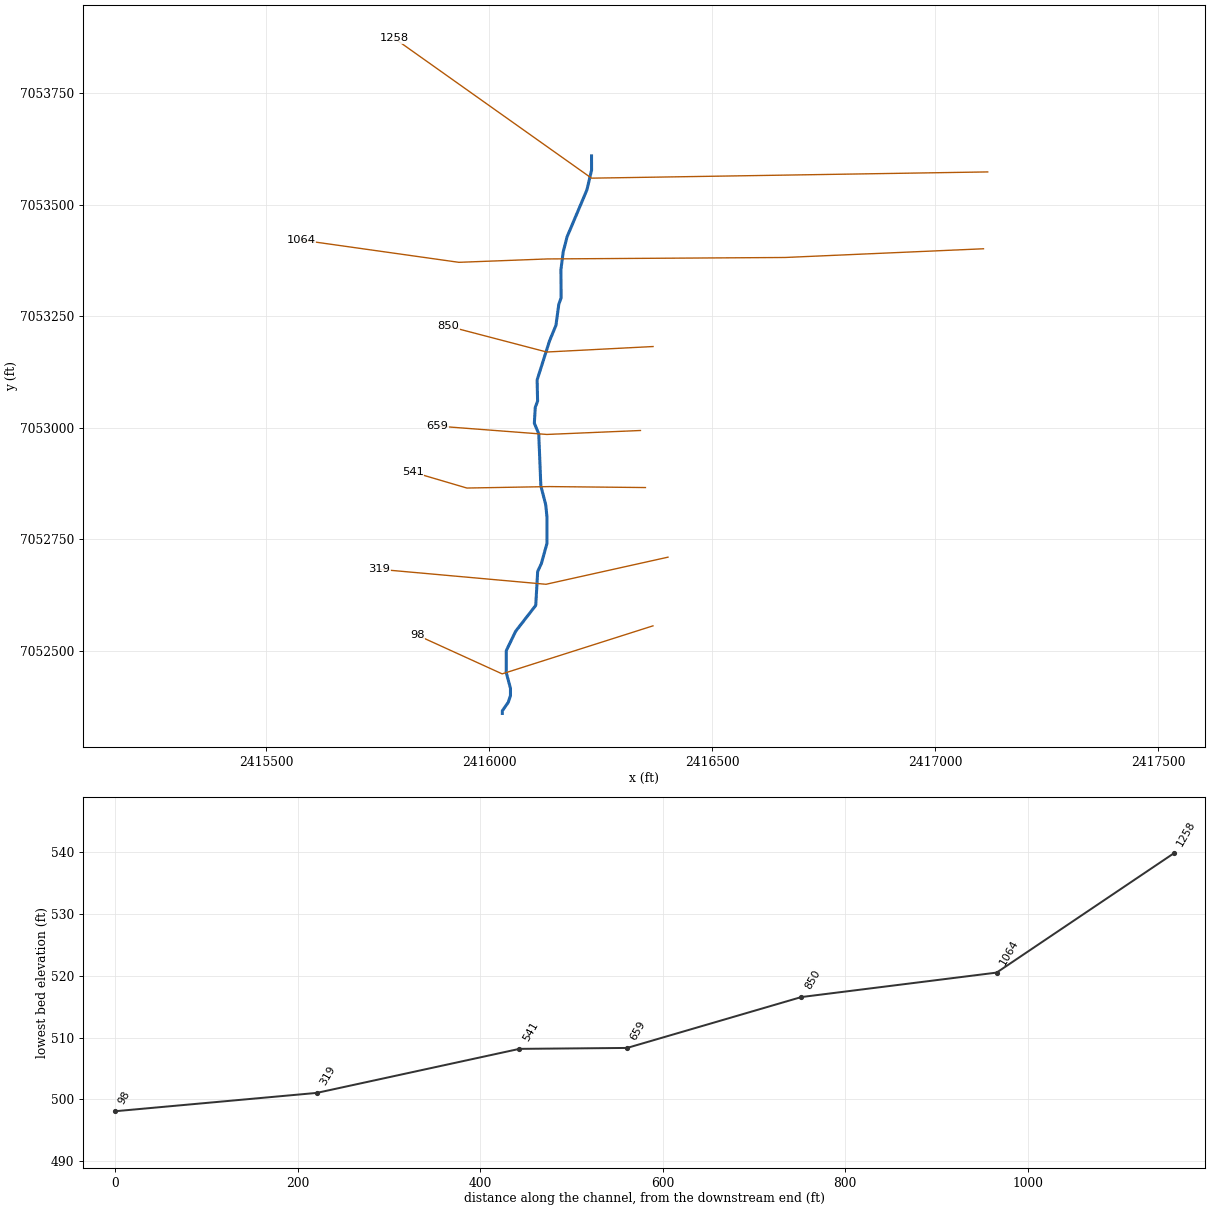
--- Bakers Branch Tr 1.prj (project) ---

Proj Title=Bakers Branch Tr 1 Base Level Engineering
Current Plan=p01
Default Exp/Contr=0.3,0.1
English Units
Geom File=g01
Flow File=f01
Plan File=p01
BEGIN DESCRIPTION:
Bakers Branch Tr 1
END DESCRIPTION:

--- Bakers Branch Tr 1.p01 (plan) ---

Plan Title=Multiple Run
Short Identifier=Multiple
Geom File=g01
Flow File=f01
Subcritical Flow
K Sum by GR= 0
Std Step Tol= 0.01
Critical Tol= 0.01
Num of Std Step Trials= 20
Max Error Tol= 0.3
Flow Tol Ratio= 0.001
Split Flow NTrial= 30
Split Flow Tol= 0.02
Split Flow Ratio= 0.02
Log Output Level= 0
Friction Slope Method= 1
Unsteady Friction Slope Method= 2
Unsteady Bridges Friction Slope Method= 1
Parabolic Critical Depth
Global Vel Dist=  1 , 1 , 1
Global Log Level= 0
CheckData=True
Encroach Param= -1, 0, 0, 0
BEGIN DESCRIPTION:
Multiple Run
END DESCRIPTION:

--- Bakers Branch Tr 1.f01 (steady flow) ---

Flow Title=Multiple
Number of Profiles=7
Profile Names=10-year,25-year,50-year,1pct_min,100-year,1pct_plu,500-year
River Rch & RM= Bakers Branch Tr,Reach-1,1258
     309     409     490     292     583    1163     825
Boundary for River Rch & Prof#=Bakers Branch Tr,Reach-1,1
Up Type=0
Dn Type=3
Dn Slope=0.005
Boundary for River Rch & Prof#=Bakers Branch Tr,Reach-1,2
Up Type=0
Dn Type=3
Dn Slope=0.005
Boundary for River Rch & Prof#=Bakers Branch Tr,Reach-1,3
Up Type=0
Dn Type=3
Dn Slope=0.005
Boundary for River Rch & Prof#=Bakers Branch Tr,Reach-1,4
Up Type=0
Dn Type=3
Dn Slope=0.005
Boundary for River Rch & Prof#=Bakers Branch Tr,Reach-1,5
Up Type=0
Dn Type=3
Dn Slope=0.005
Boundary for River Rch & Prof#=Bakers Branch Tr,Reach-1,6
Up Type=0
Dn Type=3
Dn Slope=0.005
Boundary for River Rch & Prof#=Bakers Branch Tr,Reach-1,7
Up Type=0
Dn Type=3
Dn Slope=0.005

--- Bakers Branch Tr 1.g01 (geometry) ---

Geom Title=Existing Conditions

River Reach=Bakers Branch Tr,Reach-1
Reach XY= 30
      2416229.00      7053610.00      2416229.10      7053578.05
      2416218.70      7053533.84      2416174.22      7053428.59
      2416165.54      7053395.03      2416160.33      7053354.66
      2416160.85      7053291.64      2416155.64      7053277.32
      2416149.20      7053230.00      2416134.84      7053195.22
      2416107.02      7053107.55      2416108.06      7053060.15
      2416102.85      7053046.09      2416100.77      7053010.67
      2416110.66      7052986.71      2416115.35      7052870.05
      2416126.29      7052827.86      2416129.03      7052800.78
      2416129.04      7052741.01      2416116.50      7052695.87
      2416108.25      7052678.08      2416103.91      7052602.12
      2416058.77      7052543.96      2416037.89      7052500.61
      2416037.71      7052451.70      2416047.26      7052416.11
      2416047.26      7052399.61      2416042.05      7052384.42
      2416028.99      7052365.76      2416029.00      7052360.00

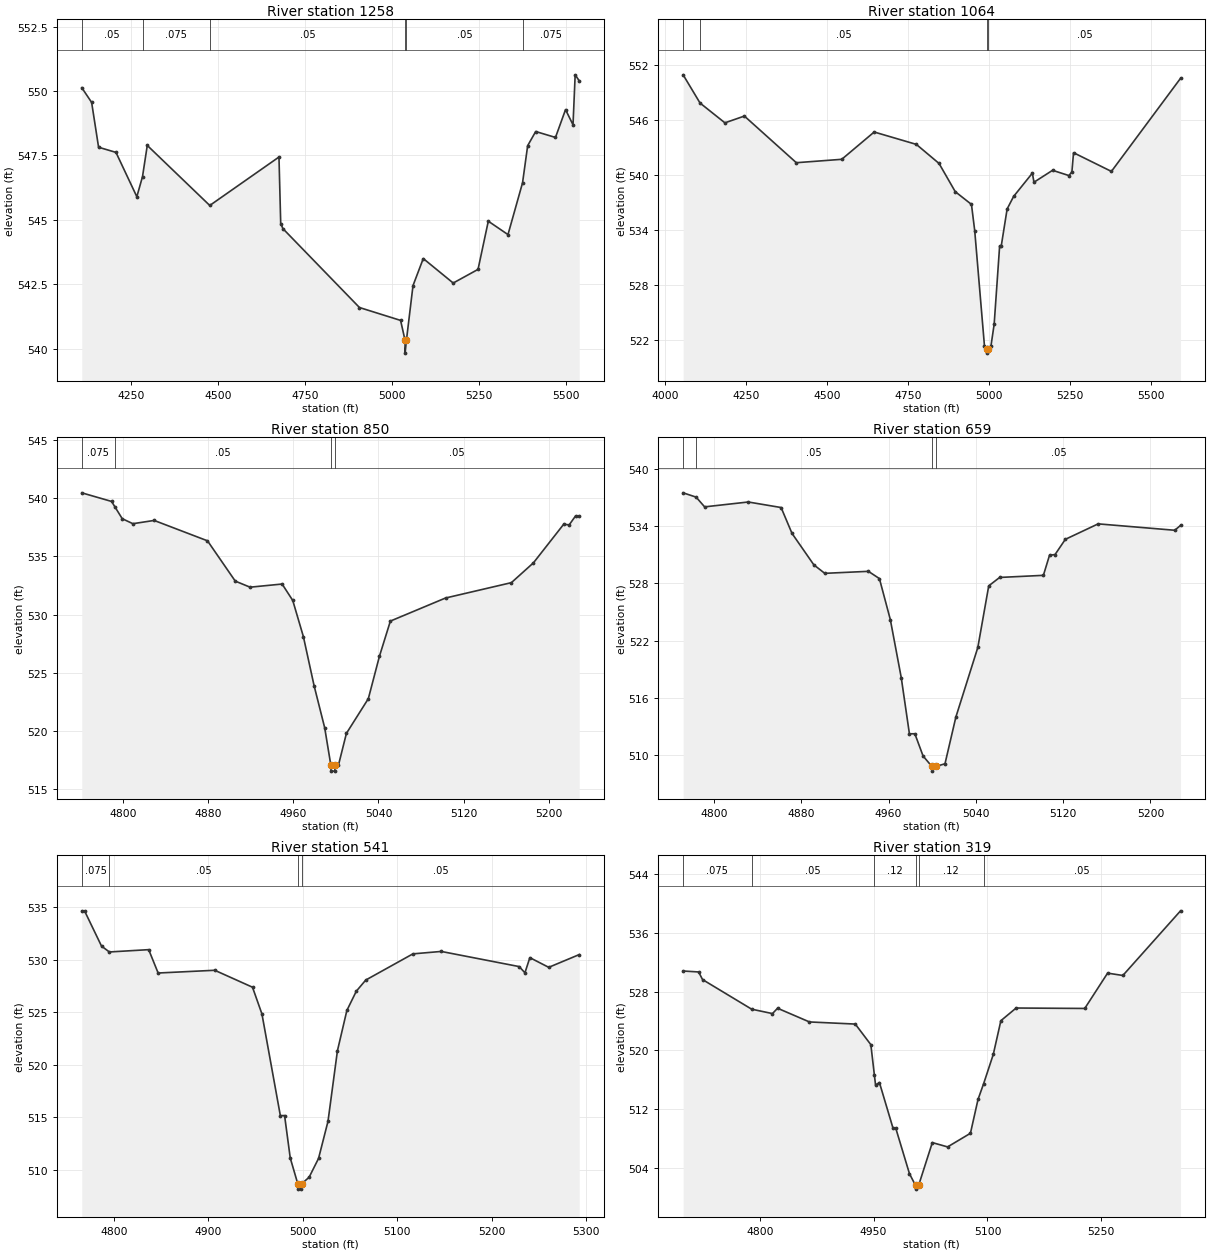
Type RM Length L Ch R = 1,1258,194,194,194
BEGIN DESCRIPTION:
Bakers Branch Tr 1 5.0
END DESCRIPTION:
XS GIS Cut Line= 3
      2417117.29      7053573.98      2416229.00      7053560.00
      2415786.98      7053873.49
#Sta/Elev= 30
  4107.9  550.13  4136.2  549.56  4156.2  547.82  4206.2  547.62  4266.2  545.90
  4282.5  546.68  4296.2  547.89  4475.9  545.56  4674.9  547.44  4679.9  544.86
  4686.3  544.66  4906.3  541.60  5024.6  541.10  5037.4  540.33  5037.6  539.83
  5041.4  540.33  5060.3  542.45  5089.8  543.50  5175.9  542.55  5247.3  543.08
  5276.8  544.95  5333.4  544.43  5375.3  546.44  5390.0  547.88  5413.1  548.43
  5470.0  548.20  5498.9  549.28  5520.4  548.69  5526.6  550.63  5538.2  550.40
#Mann=6,-1,0
  4107.9    0.05       0  4282.5   0.075       0  4475.9    0.05       0
  5037.4    0.05       0  5041.4    0.05       0  5375.3   0.075       0
Bank Sta=5037.4,5041.4
Exp/Cntr=0.3,0.1

Type RM Length L Ch R = 1,1064,214,214,214
BEGIN DESCRIPTION:
Bakers Branch Tr 1 4.0
END DESCRIPTION:
XS GIS Cut Line= 5
      2417107.76      7053401.67      2416662.88      7053382.14
      2416130.15      7053378.88      2415931.54      7053371.29
      2415577.85      7053421.20
#Sta/Elev= 30
  4056.6  550.90  4108.8  547.82  4185.5  545.66  4245.5  546.40  4405.7  541.31
  4545.8  541.68  4645.8  544.66  4775.8  543.31  4845.8  541.23  4895.8  538.15
  4945.8  536.76  4955.8  533.91  4985.8  521.36  4993.8  521.03  4994.0  520.53
  4997.8  521.03  5005.8  521.28  5015.8  523.68  5032.7  532.23  5037.7  532.23
  5055.8  536.26  5075.8  537.63  5133.6  540.17  5138.6  539.18  5195.9  540.48
  5246.1  539.91  5255.5  540.29  5260.6  542.40  5377.4  540.36  5590.6  550.52
#Mann=4,-1,0
  4056.6   0.075       0  4108.8    0.05       0  4993.8    0.05       0
  4997.8    0.05       0
Bank Sta=4993.8,4997.8
Exp/Cntr=0.3,0.1

Type RM Length L Ch R = 1,850,191,191,191
BEGIN DESCRIPTION:
Bakers Branch Tr 1 3.0
END DESCRIPTION:
XS GIS Cut Line= 3
      2416366.94      7053182.49      2416128.55      7053170.19
      2415907.40      7053228.05
#Sta/Elev= 30
  4761.3  540.46  4789.3  539.72  4792.4  539.26  4799.3  538.24  4809.3  537.81
  4829.3  538.09  4879.4  536.34  4905.5  532.88  4919.4  532.36  4949.5  532.63
  4959.5  531.22  4969.5  528.11  4979.5  523.92  4989.5  520.29  4995.3  517.07
  4995.5  516.57  4999.0  516.57  4999.3  517.07  5002.4  517.07  5009.9  519.81
  5030.5  522.79  5040.9  526.42  5051.2  529.45  5103.0  531.43  5164.9  532.75
  5185.6  534.45  5214.0  537.76  5219.2  537.71  5225.2  538.48  5228.6  538.48
#Mann=4,-1,0
  4761.3   0.075       0  4792.4    0.05       0  4995.3    0.05       0
  4999.3    0.05       0
Bank Sta=4995.3,4999.3
Exp/Cntr=0.3,0.1

Type RM Length L Ch R = 1,659,118,118,118
BEGIN DESCRIPTION:
Bakers Branch Tr 1 2.0
END DESCRIPTION:
XS GIS Cut Line= 3
      2416338.69      7052994.22      2416128.99      7052985.37
      2415883.69      7053004.09
#Sta/Elev= 30
  4771.7  537.47  4783.6  537.02  4791.4  536.00  4831.4  536.51  4861.5  535.93
  4871.5  533.22  4891.5  529.93  4901.5  529.04  4941.5  529.25  4951.6  528.49
  4961.6  524.20  4971.6  518.13  4979.1  512.24  4984.1  512.24  4991.6  509.92
  4999.6  508.83  4999.9  508.33  5003.6  508.83  5011.7  509.10  5021.7  514.00
  5041.8  521.28  5051.8  527.73  5061.8  528.61  5101.9  528.83  5107.5  530.93
  5112.6  531.01  5122.0  532.60  5152.1  534.22  5222.3  533.55  5227.6  534.06
#Mann=4,-1,0
  4771.7   0.075       0  4783.6    0.05       0  4999.6    0.05       0
  5003.6    0.05       0
Bank Sta=4999.6,5003.6
Exp/Cntr=0.3,0.1

Type RM Length L Ch R = 1,541,222,222,222
BEGIN DESCRIPTION:
Mapping XS 5d172efb
END DESCRIPTION:
XS GIS Cut Line= 4
      2416349.88      7052866.31      2416135.01      7052868.48
      2415949.46      7052865.23      2415827.98      7052901.02
#Sta/Elev= 30
  4765.8  534.63  4768.7  534.63  4786.7  531.28  4795.0  530.72  4836.7  530.94
  4846.7  528.72  4906.7  528.98  4946.7  527.37  4956.7  524.83  4976.2  515.17
  4980.7  515.17  4986.7  511.14  4994.7  508.68  4994.9  508.18  4998.4  508.18
  4998.7  508.68  5006.7  509.31  5016.7  511.10  5026.7  514.62  5036.7  521.33
  5046.7  525.16  5056.7  526.99  5066.7  528.05  5116.7  530.54  5146.7  530.77
  5229.3  529.33  5235.4  528.74  5240.6  530.18  5260.6  529.26  5292.9  530.47
#Mann=4,-1,0
  4765.8   0.075       0  4795.0    0.05       0  4994.7    0.05       0
  4998.7    0.05       0
Bank Sta=4994.7,4998.7
Exp/Cntr=0.3,0.1

Type RM Length L Ch R = 1,319,221,221,221
BEGIN DESCRIPTION:
Mapping XS a7f8638c
END DESCRIPTION:
XS GIS Cut Line= 3
      2416400.42      7052710.21      2416126.97      7052649.45
      2415753.30      7052683.02
#Sta/Elev= 30
  4699.1  530.81  4719.5  530.68  4724.7  529.64  4789.4  525.60  4816.8  525.00
  4823.5  525.73  4865.5  523.86  4925.9  523.57  4946.4  520.76  4951.1  516.58
  4952.6  515.25  4957.7  515.59  4975.6  509.37  4979.2  509.37  4997.3  503.15
  5005.3  501.55  5005.6  501.05  5009.3  501.55  5027.4  507.40  5047.5  506.81
  5077.6  508.67  5087.6  513.29  5095.0  515.44  5107.7  519.43  5117.7  524.03
  5137.8  525.76  5228.2  525.70  5258.3  530.52  5278.4  530.20  5354.4  539.02
#Mann=6,-1,0
  4699.1   0.075       0  4789.4    0.05       0  4951.1    0.12       0
  5005.3    0.07       0  5009.3    0.12       0  5095.0    0.05       0
Bank Sta=5005.3,5009.3
Exp/Cntr=0.3,0.1

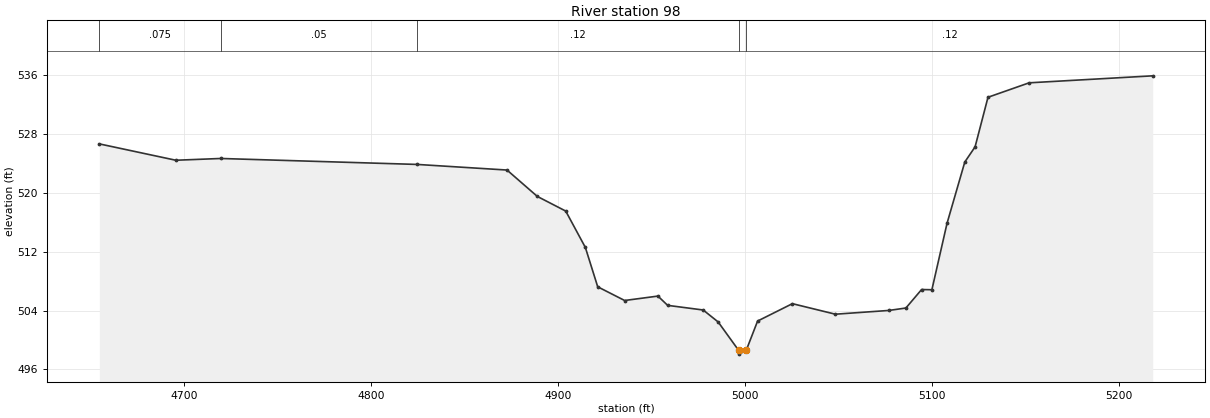
Type RM Length L Ch R = 1,98,0,0,0
BEGIN DESCRIPTION:
Bakers Branch Tr 1 1.0
END DESCRIPTION:
XS GIS Cut Line= 3
      2416366.68      7052556.23      2416028.57      7052448.58
      2415838.86      7052535.00
#Sta/Elev= 30
  4654.8  526.62  4695.7  524.40  4719.7  524.64  4824.9  523.83  4872.8  523.07
  4889.0  519.49  4904.2  517.50  4914.7  512.56  4921.3  507.22  4935.7  505.36
  4953.5  505.96  4958.7  504.70  4977.7  504.07  4985.7  502.45  4996.7  498.58
  4996.9  498.08  5000.7  498.58  5006.8  502.57  5025.4  504.93  5048.4  503.50
  5077.0  504.01  5086.1  504.34  5094.5  506.85  5100.0  506.82  5108.1  515.84
  5117.6  524.16  5123.1  526.22  5130.0  532.95  5152.0  534.91  5218.1  535.86
#Mann=5,-1,0
  4654.8   0.075       0  4719.7    0.05       0  4824.9    0.12       0
  4996.7    0.07       0  5000.7    0.12       0
Bank Sta=4996.7,5000.7
Exp/Cntr=0.3,0.1

Chan Stop Cuts=-1