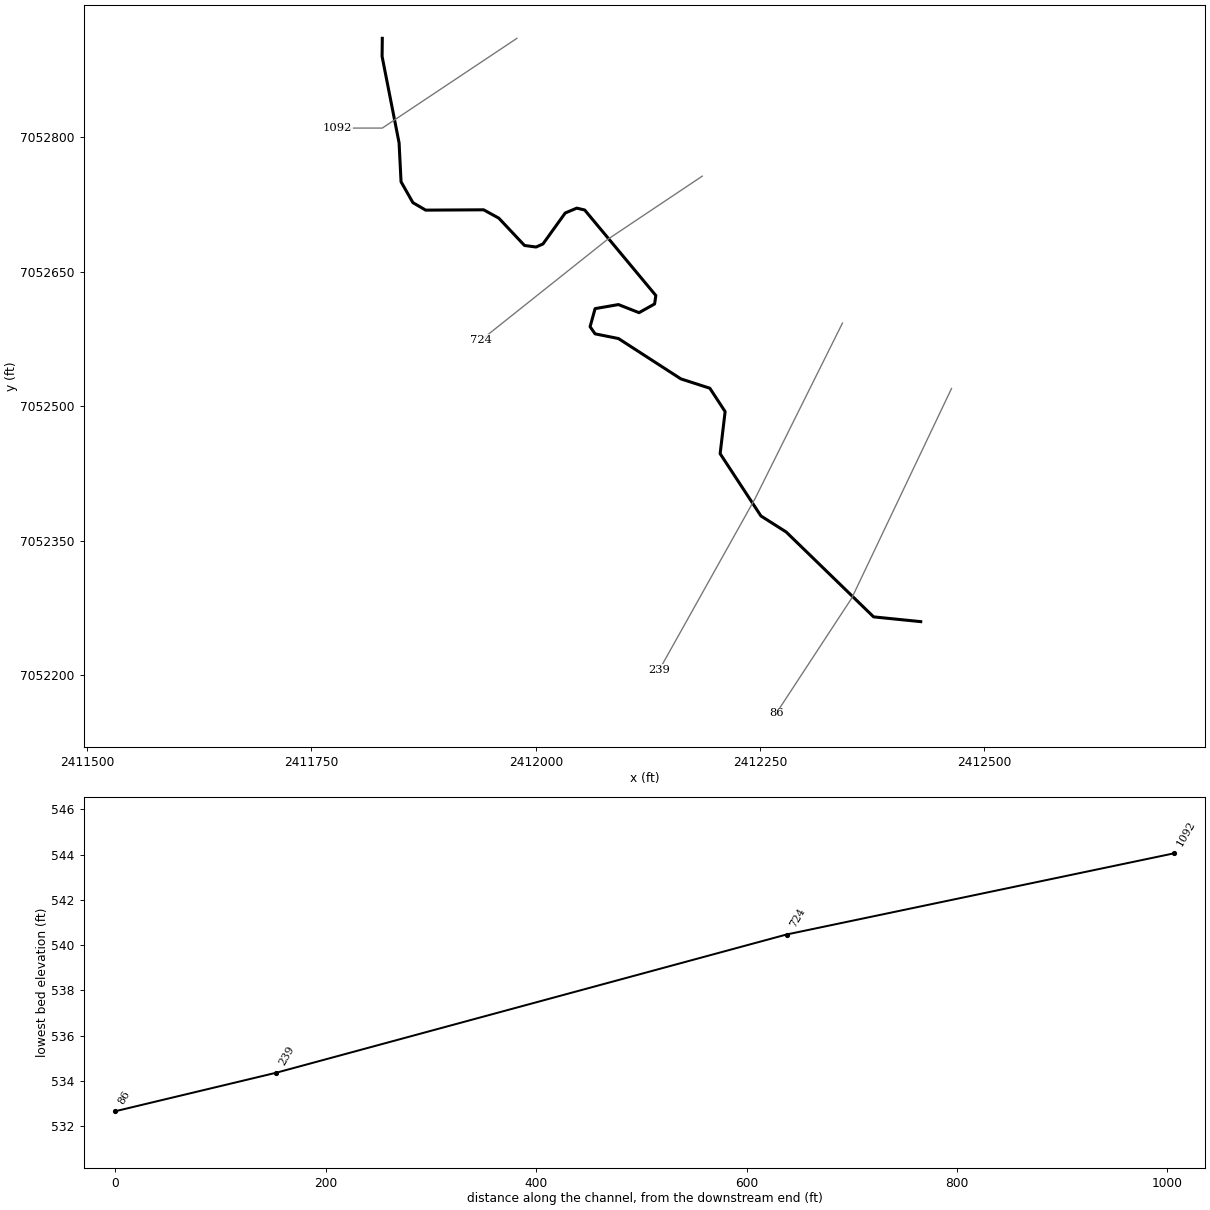
--- Bakers Branch Tr 3.prj (project) ---

Proj Title=Bakers Branch Tr 3 Base Level Engineering
Current Plan=p01
Default Exp/Contr=0.3,0.1
English Units
Geom File=g01
Flow File=f01
Plan File=p01
BEGIN DESCRIPTION:
Bakers Branch Tr 3
END DESCRIPTION:

--- Bakers Branch Tr 3.p01 (plan) ---

Plan Title=Multiple Run
Short Identifier=Multiple
Geom File=g01
Flow File=f01
Subcritical Flow
K Sum by GR= 0
Std Step Tol= 0.01
Critical Tol= 0.01
Num of Std Step Trials= 20
Max Error Tol= 0.3
Flow Tol Ratio= 0.001
Split Flow NTrial= 30
Split Flow Tol= 0.02
Split Flow Ratio= 0.02
Log Output Level= 0
Friction Slope Method= 1
Unsteady Friction Slope Method= 2
Unsteady Bridges Friction Slope Method= 1
Parabolic Critical Depth
Global Vel Dist=  1 , 1 , 1
Global Log Level= 0
CheckData=True
Encroach Param= -1, 0, 0, 0
BEGIN DESCRIPTION:
Multiple Run
END DESCRIPTION:

--- Bakers Branch Tr 3.f01 (steady flow) ---

Flow Title=Multiple
Number of Profiles=7
Profile Names=10-year,25-year,50-year,1pct_min,100-year,1pct_plu,500-year
River Rch & RM= Bakers Branch Tr,Reach-1,1092
     237     307     362     213     424     847     583
Boundary for River Rch & Prof#=Bakers Branch Tr,Reach-1,1
Up Type=0
Dn Type=3
Dn Slope=0.005
Boundary for River Rch & Prof#=Bakers Branch Tr,Reach-1,2
Up Type=0
Dn Type=3
Dn Slope=0.005
Boundary for River Rch & Prof#=Bakers Branch Tr,Reach-1,3
Up Type=0
Dn Type=3
Dn Slope=0.005
Boundary for River Rch & Prof#=Bakers Branch Tr,Reach-1,4
Up Type=0
Dn Type=3
Dn Slope=0.005
Boundary for River Rch & Prof#=Bakers Branch Tr,Reach-1,5
Up Type=0
Dn Type=3
Dn Slope=0.005
Boundary for River Rch & Prof#=Bakers Branch Tr,Reach-1,6
Up Type=0
Dn Type=3
Dn Slope=0.005
Boundary for River Rch & Prof#=Bakers Branch Tr,Reach-1,7
Up Type=0
Dn Type=3
Dn Slope=0.005

--- Bakers Branch Tr 3.g01 (geometry) ---

Geom Title=Existing Conditions

River Reach=Bakers Branch Tr,Reach-1
Reach XY= 30
      2411829.00      7052910.00      2411828.77      7052889.87
      2411847.71      7052793.51      2411849.90      7052750.17
      2411863.10      7052726.90      2411877.34      7052718.57
      2411941.92      7052718.92      2411958.86      7052709.61
      2411987.47      7052679.18      2412000.32      7052677.45
      2412008.03      7052680.85      2412032.86      7052715.40
      2412045.70      7052720.78      2412054.56      7052718.70
      2412133.83      7052623.40      2412132.44      7052614.02
      2412115.08      7052604.30      2412092.16      7052613.33
      2412066.12      7052608.81      2412060.56      7052588.67
      2412066.12      7052580.69      2412092.16      7052575.48
      2412161.72      7052530.51      2412194.01      7052520.10
      2412211.03      7052494.06      2412205.47      7052447.18
      2412250.96      7052377.74      2412279.01      7052359.95
      2412376.48      7052265.31      2412429.00      7052260.00

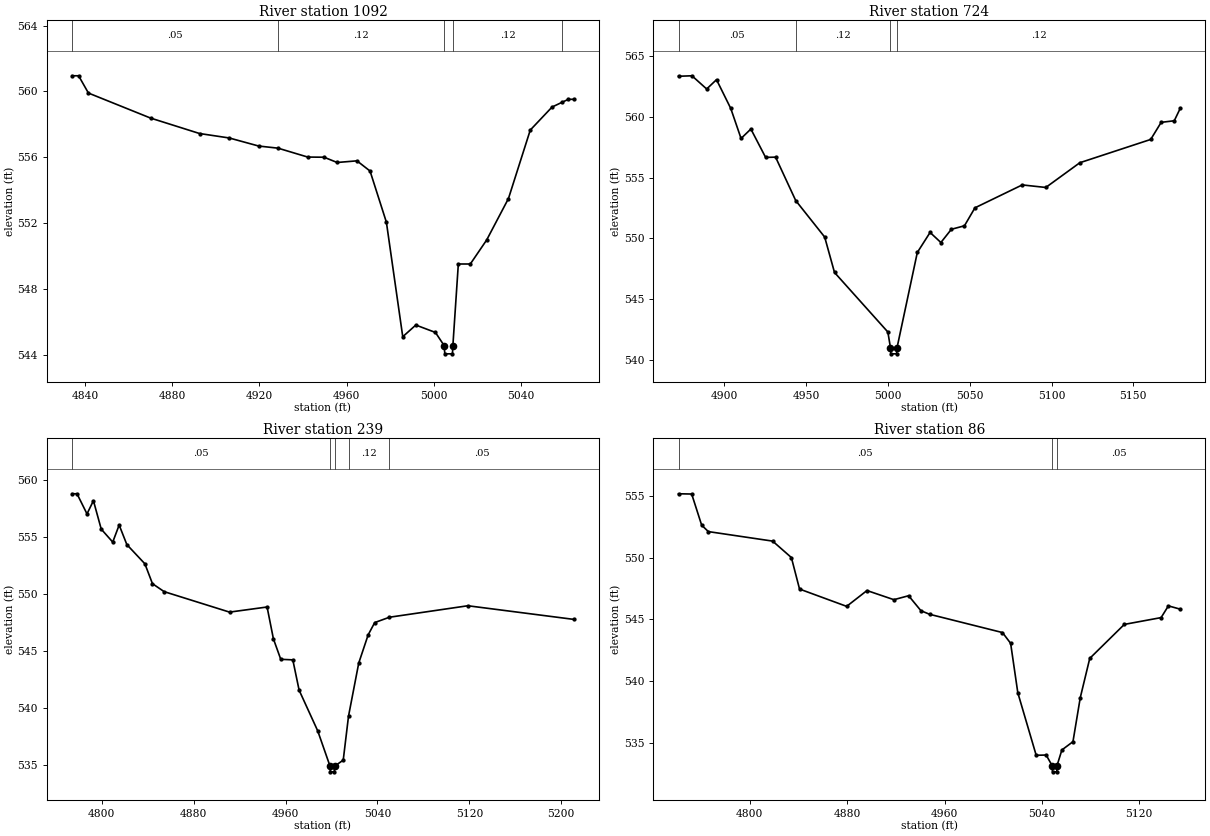
Type RM Length L Ch R = 1,1092,368,368,368
BEGIN DESCRIPTION:
Bakers Branch Tr 3 3.0
END DESCRIPTION:
XS GIS Cut Line= 3
      2411978.96      7052909.97      2411829.00      7052810.00
      2411779.03      7052810.00
#Sta/Elev= 30
  4834.1  560.95  4837.1  560.95  4841.6  559.90  4870.1  558.38  4892.6  557.44
  4906.2  557.17  4919.7  556.68  4928.6  556.55  4942.2  556.01  4949.7  556.00
  4955.7  555.68  4964.8  555.78  4970.8  555.16  4978.3  552.05  4985.8  545.09
  4991.8  545.80  5000.8  545.35  5004.8  544.55  5005.1  544.05  5008.6  544.05
  5008.8  544.55  5011.3  549.51  5016.8  549.51  5024.3  550.97  5034.3  553.49
  5044.3  557.65  5054.3  559.05  5058.9  559.34  5061.8  559.52  5064.3  559.52
#Mann=5,-1,0
  4834.1    0.05       0  4928.6    0.12       0  5004.8    0.07       0
  5008.8    0.12       0  5058.9    0.05       0
Bank Sta=5004.8,5008.8
Exp/Cntr=0.3,0.1

Type RM Length L Ch R = 1,724,485,485,485
BEGIN DESCRIPTION:
Bakers Branch Tr 3 2.0
END DESCRIPTION:
XS GIS Cut Line= 3
      2412185.53      7052756.42      2412079.21      7052685.33
      2411939.39      7052574.04
#Sta/Elev= 30
  4872.1  563.36  4880.3  563.40  4889.3  562.31  4895.3  563.08  4904.0  560.71
  4910.3  558.23  4916.3  559.01  4925.3  556.67  4931.4  556.69  4943.7  553.11
  4961.4  550.10  4967.4  547.18  5000.0  542.27  5001.6  540.97  5001.8  540.47
  5005.3  540.47  5005.6  540.97  5018.0  548.83  5025.8  550.48  5032.4  549.65
  5038.8  550.74  5046.8  551.03  5053.2  552.51  5082.1  554.40  5096.5  554.19
  5117.3  556.23  5160.6  558.15  5167.0  559.56  5175.0  559.69  5178.7  560.73
#Mann=4,-1,0
  4872.1    0.05       0  4943.7    0.12       0  5001.6    0.07       0
  5005.6    0.12       0
Bank Sta=5001.6,5005.6
Exp/Cntr=0.3,0.1

Type RM Length L Ch R = 1,239,153,153,153
BEGIN DESCRIPTION:
Mapping XS e91bcbe3
END DESCRIPTION:
XS GIS Cut Line= 3
      2412341.78      7052592.70      2412244.56      7052397.41
      2412137.81      7052206.47
#Sta/Elev= 30
  4774.1  558.83  4778.4  558.83  4787.1  557.06  4792.7  558.22  4799.5  555.72
  4809.5  554.58  4815.1  556.08  4821.8  554.36  4837.5  552.67  4844.1  550.92
  4854.3  550.22  4911.2  548.42  4943.9  548.87  4949.4  546.07  4955.8  544.27
  4966.3  544.22  4971.8  541.55  4988.0  537.97  4998.7  534.87  4999.0  534.37
  5002.5  534.37  5002.7  534.87  5010.2  535.40  5014.8  539.27  5023.7  543.94
  5031.9  546.42  5037.6  547.50  5050.4  547.97  5118.7  548.98  5211.0  547.78
#Mann=5,-1,0
  4774.1    0.05       0  4998.7   0.033       0  5002.7    0.05       0
  5014.8    0.12       0  5050.4    0.05       0
Bank Sta=4998.7,5002.7
Exp/Cntr=0.3,0.1

Type RM Length L Ch R = 1,86,0,0,0
BEGIN DESCRIPTION:
Bakers Branch Tr 3 1.0
END DESCRIPTION:
XS GIS Cut Line= 3
      2412463.29      7052519.76      2412352.20      7052286.35
      2412267.97      7052157.78
#Sta/Elev= 30
  4741.5  555.17  4752.3  555.15  4760.5  552.63  4766.0  552.11  4818.8  551.34
  4834.2  550.01  4840.9  547.46  4879.6  546.06  4896.3  547.34  4918.4  546.60
  4930.5  546.92  4940.6  545.71  4947.7  545.42  5007.6  543.94  5014.3  543.07
  5020.2  539.07  5035.3  534.01  5043.5  534.03  5048.4  533.17  5048.7  532.67
  5052.2  532.67  5052.4  533.17  5056.4  534.44  5065.5  535.11  5071.5  538.67
  5079.3  541.85  5107.7  544.60  5137.9  545.15  5143.9  546.10  5153.7  545.83
#Mann=3,-1,0
  4741.5    0.05       0  5048.4    0.05       0  5052.4    0.05       0
Bank Sta=5048.4,5052.4
Exp/Cntr=0.3,0.1

Chan Stop Cuts=-1