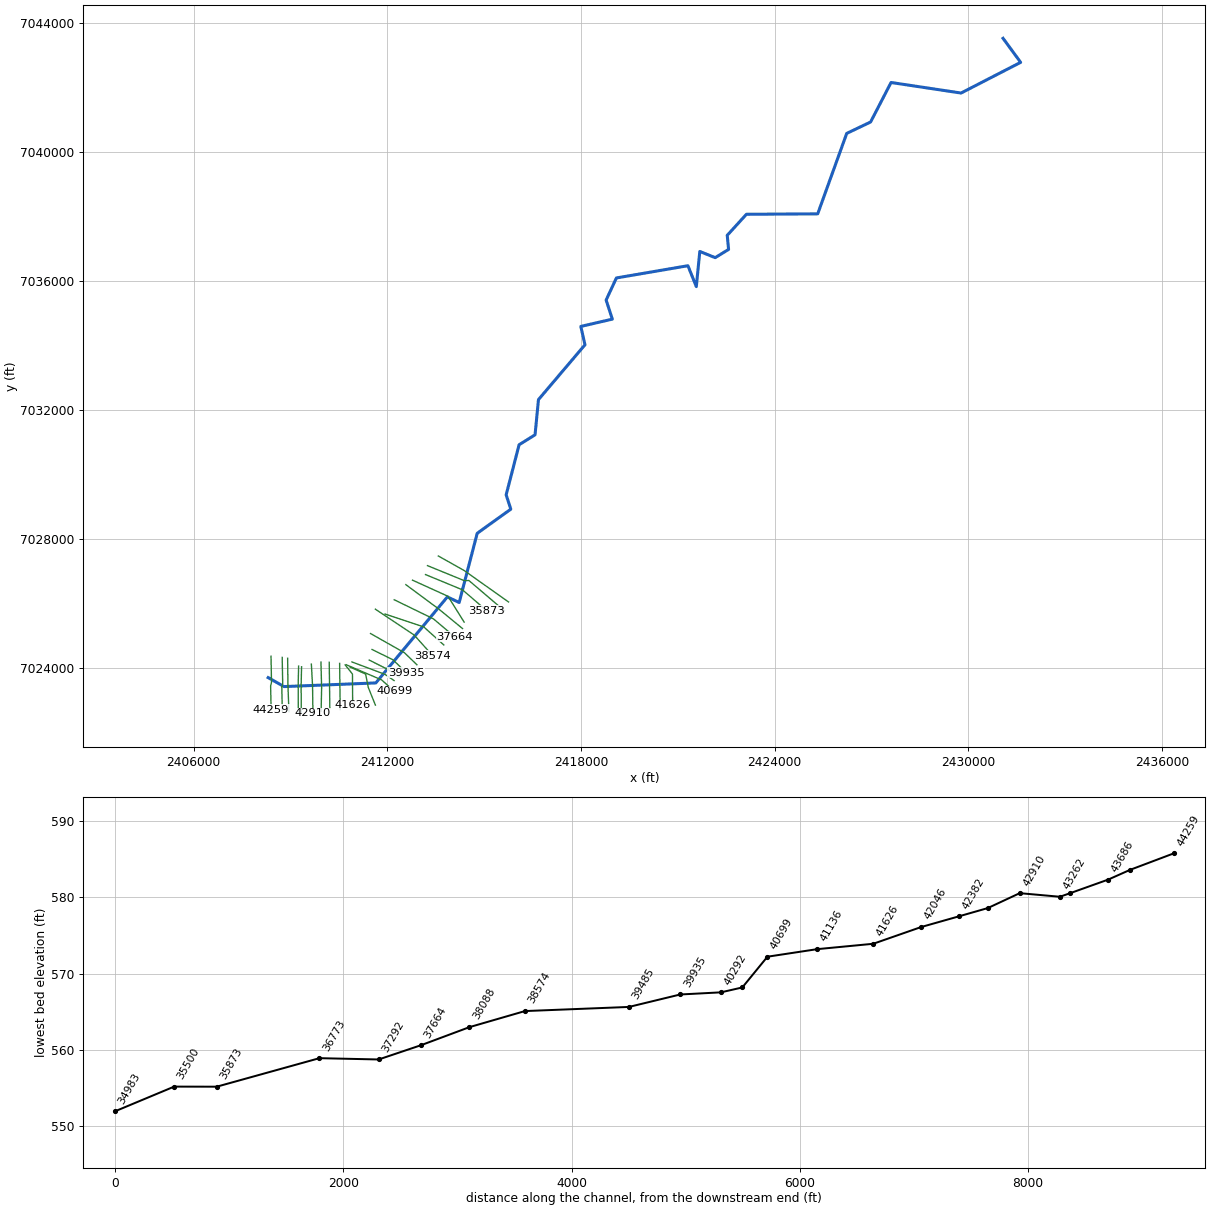
--- COTTONWOOD BR AT DENTON.prj (project) ---

Proj Title=COTTONWOOD BR AT DENTON Base Level Engineering
Current Plan=p01
Default Exp/Contr=0.3,0.1
English Units
Geom File=g01
Flow File=f01
Flow File=f02
Flow File=f03
Plan File=p01
Plan File=p02
Plan File=p03
Y Axis Title=Elevation
X Axis Title(PF)=Main Channel Distance
X Axis Title(XS)=Station
BEGIN DESCRIPTION:
COTTONWOOD BR AT DENTON
END DESCRIPTION:
DSS Export Rating Curves= 0
DSS Export Rating Curve Sorted= 0
DSS Export Volume Flow Curves= 0
DXF OffsetX= 0
DXF OffsetY= 0
DXF ScaleX= 1
DXF ScaleY= 10

--- COTTONWOOD BR AT DENTON.p01 (plan) ---

Plan Title=Multiple Run
Program Version=4.10
Short Identifier=Multiple
Geom File=g01
Flow File=f01
Subcritical Flow
K Sum by GR= 0
Std Step Tol= 0.01
Critical Tol= 0.01
Num of Std Step Trials= 20
Max Error Tol= 0.3
Flow Tol Ratio= 0.001
Split Flow NTrial= 30
Split Flow Tol= 0.02
Split Flow Ratio= 0.02
Log Output Level= 0
Friction Slope Method= 1
Unsteady Friction Slope Method= 2
Unsteady Bridges Friction Slope Method= 1
Parabolic Critical Depth
Global Vel Dist= 1 , 1 , 1
Global Log Level= 0
CheckData=True
Encroach Param=-1 ,0,0, 0
BEGIN DESCRIPTION:
Multiple Run
END DESCRIPTION:
Computation Interval=1HOUR
Output Interval=1HOUR
Run HTab= 0
Run UNet= 0
Run PostProcess= 0
Run WQNet= 0
UNET Theta= 1
UNET Theta Warmup= 1
UNET ZTol= 0.02
UNET ZSATol= 0.05
UNET MxIter= 20
UNET MaxInSteps= 0
UNET DtIC= 0
UNET DtMin= 0
UNET MaxCRTS= 20
UNET WFStab= 2
UNET SFStab= 1
UNET WFX= 1
UNET SFX= 1
UNET DSS MLevel= 4
UNET DZMax Abort= 100
UNET Convert EG Bridges= 0
UNET Use Existing IB Tables=-1
UNET Froude Reduction=False
UNET Froude Limit= 1
UNET Froude Power= 10
UNET Time Slicing=0,0, 5
UNET Junction Losses=0
Instantaneous Interval=1HOUR
Write IC File= 0
Write IC File at Sim End=0
Echo Input=False
Echo Parameters=False
Echo Output=False
Write Detailed= 0
WQ AD Non Conservative
WQ ULTIMATE=-1
WQ Max Comp Step=1HOUR
WQ Output Interval=15MIN
WQ Output Selected Increments= 0
WQ Output face flow=0
WQ Output face velocity=0
WQ Output face area=0
WQ Output face dispersion=0
WQ Output cell volume=0
WQ Output cell surface area=0
WQ Output cell continuity=0
WQ Output cumulative cell continuity=0
WQ Output face conc=0
WQ Output face dconc_dx=0
WQ Output face courant=0
WQ Output face peclet=0
WQ Output face adv mass=0
WQ Output face disp mass=0
WQ Output cell mass=0
WQ Output cell source sink temp=0
WQ Output cell source sink nsm=0
WQ Output MaxMinRange=-1
WQ Daily Max Min Mean=-1
WQ Daily Range=0
WQ Daily Time=0
WQ Create Restart=0
WQ Fixed Restart=0
WQ System Summary=0
WQ Use Fixed Temperature=0
Sorting and Armoring Iterations= 10
XS Update Threshold= 0.02
Hydraulics Update Threshold= 0.02
Energy Slope Method= 1
Volume Change Method= 0
XS Weighting Method= 0
Number of US Weighted Cross Sections= 1
Number of DS Weighted Cross Sections= 1
Upstream XS Weight=0.25
Main XS Weight=0.5
Downstream XS Weight=0.25
Number of DS XS's Weighted with US Boundary= 1
Upstream Boundary Weight= 1
Weight of XSs Associated with US Boundary= 0
Number of US XS's Weighted with DS Boundary= 1
Downstream Boundary Weight= 0.5
Weight of XSs Associated with DS Boundary= 0.5
Sediment Output Level= 4
Mass or Volume Output= 0
Output Increment Type= 1
Profile and TS Output Increment= 10
XS Output Flag= 0
XS Output Increment= 10
Disregard all LS=0
Disregard all Conn=0
Disregard all Breaches=0
Disregard all Pumps=0

--- COTTONWOOD BR AT DENTON.p02 (plan) ---

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Plan Title=Floodway Run
Short Identifier=Floodway
Geom File=g01
Flow File=f02
Global Vel Dist=  1 , 1 , 1
Encroach Param= -1, 0, 0, 0
Floodway Run

--- COTTONWOOD BR AT DENTON.p03 (plan) ---

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Plan Title=100-Year Single
Short Identifier=100Year
Geom File=g01
Flow File=f03
Global Vel Dist=  1 , 1 , 1
Encroach Param= -1, 0, 0, 0
100Year Run

--- COTTONWOOD BR AT DENTON.f01 (steady flow) ---

Flow Title=Multiple
Number of Profiles=7
Profile Names=10-year,25-year,50-year,1pct_minus,100-year,1pct_plus,500-yr
River Rch & RM= COTTONWOOD BR AT,Reach-1,44259
     722     992    1213     735    1467    2928    2146
River Rch & RM= COTTONWOOD BR AT,Reach-1,39485
     975    1362    1686    1033    2061    4113    3082
River Rch & RM= COTTONWOOD BR AT,Reach-1,38574
    1134    1592    1978    1215    2425    4838    3645
River Rch & RM= COTTONWOOD BR AT,Reach-1,35873
    1318    1865    2327    1436    2865    5715    4344
River Rch & RM= COTTONWOOD BR AT,Reach-1,34605
    1467    2083    2607    1612    3216    6417    4899
River Rch & RM= COTTONWOOD BR AT,Reach-1,31352
    1577    2245    2813    1741    3474    6932    5305
River Rch & RM= COTTONWOOD BR AT,Reach-1,28887
    1716    2450    3077    1907    3806    7593    5829
River Rch & RM= COTTONWOOD BR AT,Reach-1,24606
    1801    2573    3231    2003    3997    7975    6123
River Rch & RM= COTTONWOOD BR AT,Reach-1,17234
    1880    2687    3376    2093    4177    8334    6400
River Rch & RM= COTTONWOOD BR AT,Reach-1,12729
    1986    2845    3578    2221    4431    8841    6803
River Rch & RM= COTTONWOOD BR AT,Reach-1,10060
    2060    2952    3715    2306    4601    9181    7068
River Rch & RM= COTTONWOOD BR AT,Reach-1,5776
    2019    2887    3629    2252    4493    8964    6902
River Rch & RM= COTTONWOOD BR AT,Reach-1,4313
    2054    2936    3691    2290    4569    9117    7017
River Rch & RM= COTTONWOOD BR AT,Reach-1,1091
    2185    3132    3944    2451    4891    9758    7534
Boundary for River Rch & Prof#=COTTONWOOD BR AT,Reach-1,1
Up Type=0
Dn Type=3
Dn Slope=0.005
Boundary for River Rch & Prof#=COTTONWOOD BR AT,Reach-1,2
Up Type=0
Dn Type=3
Dn Slope=0.005
Boundary for River Rch & Prof#=COTTONWOOD BR AT,Reach-1,3
Up Type=0
Dn Type=3
Dn Slope=0.005
Boundary for River Rch & Prof#=COTTONWOOD BR AT,Reach-1,4
Up Type=0
Dn Type=3
Dn Slope=0.005
Boundary for River Rch & Prof#=COTTONWOOD BR AT,Reach-1,5
Up Type=0
Dn Type=3
Dn Slope=0.005
Boundary for River Rch & Prof#=COTTONWOOD BR AT,Reach-1,6
Up Type=0
Dn Type=3
Dn Slope=0.005
Boundary for River Rch & Prof#=COTTONWOOD BR AT,Reach-1,7
Up Type=0
Dn Type=3
Dn Slope=0.005

--- COTTONWOOD BR AT DENTON.f02 (steady flow) ---

Flow Title=Floodway
Number of Profiles=2
Profile Names=1pct_minus,100-year
River Rch & RM= COTTONWOOD BR AT,Reach-1,44259
     735    1467
River Rch & RM= COTTONWOOD BR AT,Reach-1,39485
    1033    2061
River Rch & RM= COTTONWOOD BR AT,Reach-1,38574
    1215    2425
River Rch & RM= COTTONWOOD BR AT,Reach-1,35873
    1436    2865
River Rch & RM= COTTONWOOD BR AT,Reach-1,34605
    1612    3216
River Rch & RM= COTTONWOOD BR AT,Reach-1,31352
    1741    3474
River Rch & RM= COTTONWOOD BR AT,Reach-1,28887
    1907    3806
River Rch & RM= COTTONWOOD BR AT,Reach-1,24606
    2003    3997
River Rch & RM= COTTONWOOD BR AT,Reach-1,17234
    2093    4177
River Rch & RM= COTTONWOOD BR AT,Reach-1,12729
    2221    4431
River Rch & RM= COTTONWOOD BR AT,Reach-1,10060
    2306    4601
River Rch & RM= COTTONWOOD BR AT,Reach-1,5776
    2252    4493
River Rch & RM= COTTONWOOD BR AT,Reach-1,4313
    2290    4569
River Rch & RM= COTTONWOOD BR AT,Reach-1,1091
    2451    4891
Boundary for River Rch & Prof#=COTTONWOOD BR AT,Reach-1,1
Up Type=0
Dn Type=3
Dn Slope=0.005
Boundary for River Rch & Prof#=COTTONWOOD BR AT,Reach-1,2
Up Type=0
Dn Type=3
Dn Slope=0.005

--- COTTONWOOD BR AT DENTON.f03 (steady flow) ---

Flow Title=100-year Single
Number of Profiles=1
Profile Names=1pct_minus
River Rch & RM= COTTONWOOD BR AT,Reach-1,44259
     735
River Rch & RM= COTTONWOOD BR AT,Reach-1,39485
    1033
River Rch & RM= COTTONWOOD BR AT,Reach-1,38574
    1215
River Rch & RM= COTTONWOOD BR AT,Reach-1,35873
    1436
River Rch & RM= COTTONWOOD BR AT,Reach-1,34605
    1612
River Rch & RM= COTTONWOOD BR AT,Reach-1,31352
    1741
River Rch & RM= COTTONWOOD BR AT,Reach-1,28887
    1907
River Rch & RM= COTTONWOOD BR AT,Reach-1,24606
    2003
River Rch & RM= COTTONWOOD BR AT,Reach-1,17234
    2093
River Rch & RM= COTTONWOOD BR AT,Reach-1,12729
    2221
River Rch & RM= COTTONWOOD BR AT,Reach-1,10060
    2306
River Rch & RM= COTTONWOOD BR AT,Reach-1,5776
    2252
River Rch & RM= COTTONWOOD BR AT,Reach-1,4313
    2290
River Rch & RM= COTTONWOOD BR AT,Reach-1,1091
    2451
Boundary for River Rch & Prof#=COTTONWOOD BR AT,Reach-1,1
Up Type=0
Dn Type=3
Dn Slope=0.005

--- COTTONWOOD BR AT DENTON.g01 (geometry) ---

Geom Title=Existing Conditions
Program Version=4.10

River Reach=COTTONWOOD BR AT,Reach-1
Reach XY= 30
      2408307.75      7023688.31      2408798.99      7023409.98
       2411642.3       7023523.4      2413858.87      7026190.59
      2414225.99      7026017.94      2414784.29      7028162.67
      2415825.26      7028911.56      2415681.26      7029354.44
      2416082.53      7030908.55      2416576.76      7031215.93
      2416682.82      7032308.44      2418123.54      7034007.53
      2417995.25      7034577.24      2418971.26      7034803.54
      2418779.23      7035394.78      2419098.23      7036080.58
       2421313.8      7036459.52      2421573.75        7035812.
      2421682.06      7036901.72      2422159.04      7036709.74
      2422573.83      7036965.41      2422532.09      7037402.45
      2423126.56      7038054.48      2425335.07      7038068.13
      2426234.46      7040562.47      2426973.83      7040915.41
      2427608.42      7042140.79      2429777.47      7041813.74
      2431623.56      7042765.09        2431079.        7043510.

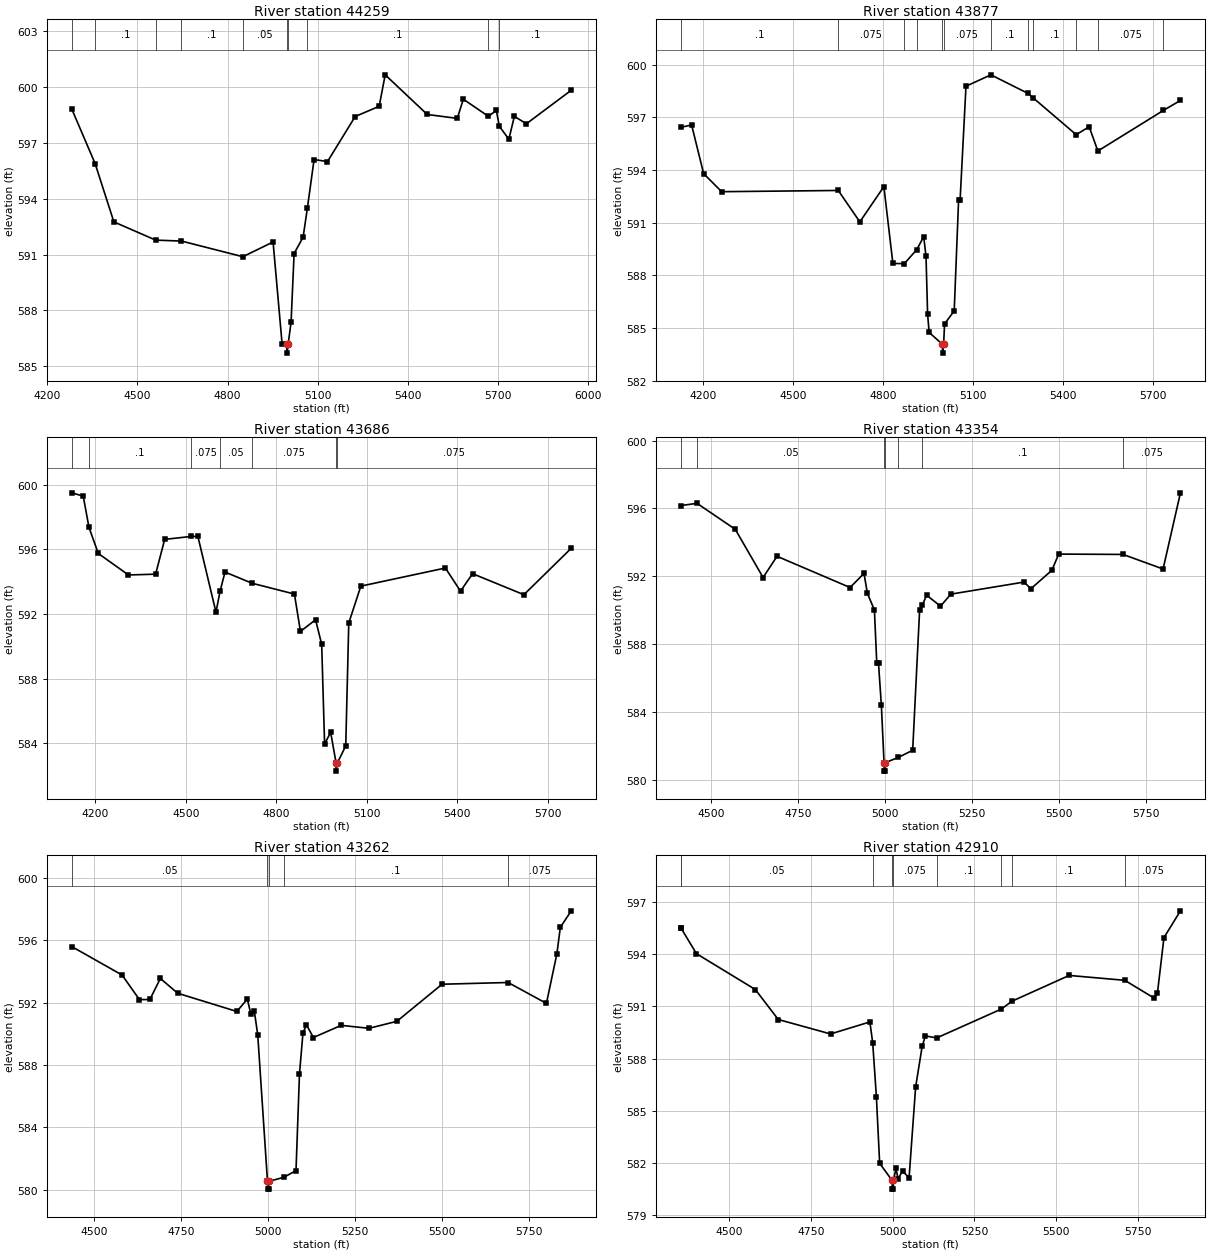
Type RM Length L Ch R = 1 ,44259   ,382,382,382
BEGIN DESCRIPTION:
COTTONWOOD BR AT DENTON 83.0
END DESCRIPTION:
XS GIS Cut Line= 4
      2408395.31      7024350.54      2408410.62      7023542.06
      2408383.06      7023428.76      2408398.37      7022690.75
#Sta/Elev= 30
  4280.9  598.84  4359.1  595.89  4421.5  592.76  4560.9  591.78  4646.6  591.73
    4851  590.89  4951.6  591.68  4981.6  586.21    4998  586.21  4998.3  585.71
    5002  586.21  5011.6  587.39  5021.6  591.06  5051.6  591.94  5066.1  593.53
  5088.1  596.11  5132.8     596  5224.9  598.42  5304.9  598.97  5324.9  600.66
  5464.9  598.53    5565  598.32    5585  599.35  5668.6  598.43    5695  598.75
  5704.8   597.9  5736.7   597.2    5755  598.43    5795  598.03  5944.3  599.83
#Mann= 10 ,-1 , 0
  4280.9    .075       0  4359.1      .1       0  4560.9    .075       0
  4646.6      .1       0    4851     .05       0    4998     .05       0
    5002     .05       0  5066.1      .1       0  5668.6     .05       0
  5704.8      .1       0
Bank Sta=4998,5002
XS Rating Curve= 0 ,0
Exp/Cntr=0.3,0.1

Type RM Length L Ch R = 1 ,43877   ,191,191,191
BEGIN DESCRIPTION:
COTTONWOOD BR AT DENTON 82.0
END DESCRIPTION:
XS GIS Cut Line= 4
      2408741.78      7024315.82      2408757.09      7023507.42
      2408729.53      7023394.11      2408744.84      7022656.13
#Sta/Elev= 30
  4127.1  596.43  4162.9  596.56  4202.9  593.79  4262.9  592.76  4651.1  592.83
    4723  591.04    4803  593.05    4833  588.67  4871.1  588.66  4912.6  589.46
  4935.6   590.2  4943.3  589.08  4948.6  585.78  4953.7  584.74    4998  584.06
  4998.3  583.56    5002  584.06    5005  585.22  5037.2  585.97  5051.8  592.29
  5056.8  592.29  5076.4  598.77  5159.3  599.42  5281.9  598.37  5299.8  598.11
  5443.3  596.01  5486.5  596.46  5515.5  595.08  5733.5  597.39  5790.4  597.96
#Mann= 12 ,-1 , 0
  4127.1      .1       0  4651.1    .075       0  4871.1     .05       0
  4912.6    .075       0    4998     .07       0    5002    .075       0
  5159.3      .1       0  5281.9    .075       0  5299.8      .1       0
  5443.3     .05       0  5515.5    .075       0  5733.5      .1       0
Bank Sta=4998,5002
XS Rating Curve= 0 ,0
Exp/Cntr=0.3,0.1

Type RM Length L Ch R = 1 ,43686   ,332,332,332
BEGIN DESCRIPTION:
COTTONWOOD BR AT DENTON 81.0
END DESCRIPTION:
XS GIS Cut Line= 3
       2408910.2      7024288.29      2408919.39      7023464.55
      2408949.95       7022633.3
#Sta/Elev= 30
  4121.6   599.5  4159.9   599.3  4179.1  597.36  4209.9  595.75  4309.9  594.42
  4399.9  594.47  4429.9  596.62  4516.1   596.8  4539.9  596.81  4599.9  592.12
  4613.9  593.45  4629.9   594.6  4719.3  593.91  4859.9  593.24  4879.9  590.93
  4929.9  591.65  4950.2  590.14  4959.9  583.97    4980  584.69    4998  582.79
  4998.3  582.29    5002  582.79    5030  583.85    5040  591.45    5080  593.73
  5360.2  594.85  5410.3  593.42  5450.3   594.5  5620.4   593.2  5777.2  596.07
#Mann= 7 ,-1 , 0
  4121.6    .075       0  4179.1      .1       0  4516.1    .075       0
  4613.9     .05       0  4719.3    .075       0    4998     .07       0
    5002    .075       0
Bank Sta=4998,5002
XS Rating Curve= 0 ,0
Exp/Cntr=0.3,0.1

Type RM Length L Ch R = 1 ,43354   ,92,92,92
BEGIN DESCRIPTION:
COTTONWOOD BR AT DENTON 80.5
END DESCRIPTION:
XS GIS Cut Line= 3
      2409250.11      7024046.39      2409237.13      7023481.44
      2409240.92      7022610.14
#Sta/Elev= 30
  4413.8  596.17  4460.3   596.3  4570.2  594.77  4650.2  591.93  4690.3  593.18
  4900.3  591.34  4940.3  592.17  4950.3  590.99  4970.3  590.01  4977.1  586.87
  4982.1  586.87  4990.3  584.39    4998  581.02  4998.3  580.52  5001.8  580.52
    5002  581.02  5039.2  581.33  5080.3  581.75  5100.3  590.02    5108  590.29
  5120.3  590.89  5160.3  590.24  5190.3  590.95  5400.3  591.66  5420.3  591.27
  5480.3  592.35  5500.3  593.31  5685.1  593.29  5800.3  592.43  5850.2  596.92
#Mann= 7 ,-1 , 0
  4413.8    .075       0  4460.3     .05       0    4998     .05       0
    5002     .05       0  5039.2    .075       0    5108      .1       0
  5685.1    .075       0
Bank Sta=4998,5002
XS Rating Curve= 0 ,0
Exp/Cntr=0.3,0.1

Type RM Length L Ch R = 1 ,43262   ,352,352,352
BEGIN DESCRIPTION:
COTTONWOOD BR AT DENTON 80.0
END DESCRIPTION:
XS GIS Cut Line= 3
      2409341.98      7024024.96        2409329.        7023460.
      2409332.79      7022588.72
#Sta/Elev= 30
  4434.9  595.61  4579.9  593.78  4629.9   592.2  4659.9  592.21  4689.9  593.56
  4739.9  592.61    4910  591.44    4940  592.24    4950  591.29    4960  591.49
    4970  589.93    4998  580.54  4998.3  580.04  5001.8  580.04    5002  580.54
  5045.2   580.8    5080  581.23    5090  587.44    5100  590.06    5110  590.58
    5130  589.77    5210  590.55    5290  590.36    5370  590.81    5500  593.19
  5689.9   593.3    5800  591.96    5830  595.13    5840  596.84  5871.3   597.9
#Mann= 5 ,-1 , 0
  4434.9     .05       0    4998     .05       0    5002     .05       0
  5045.2      .1       0  5689.9    .075       0
Bank Sta=4998,5002
XS Rating Curve= 0 ,0
Exp/Cntr=0.3,0.1

Type RM Length L Ch R = 1 ,42910   ,280,280,280
BEGIN DESCRIPTION:
COTTONWOOD BR AT DENTON 79.0
END DESCRIPTION:
XS GIS Cut Line= 3
      2409645.14      7024107.61      2409681.89      7023443.11
      2409694.14      7022579.51
#Sta/Elev= 30
  4351.4  595.51  4351.5  595.51  4399.1  594.03  4579.4  591.97  4649.5  590.25
  4809.7  589.42  4929.9  590.11  4938.6  588.92  4949.9  585.81  4959.9  581.99
    4998  581.01  4998.3  580.51  5001.8  580.51    5002  581.01    5010   581.7
    5016  581.11    5030  581.54    5050  581.17    5070  586.37    5090  588.71
    5100  589.31  5134.3  589.19  5332.5  590.85  5364.9   591.3  5540.1  592.78
  5710.2   592.5  5800.1  591.48  5810.1  591.75  5830.1  594.95  5880.6  596.49
#Mann= 9 ,-1 , 0
  4351.4    .075       0  4351.5     .05       0  4938.6    .075       0
    4998     .07       0    5002    .075       0  5134.3      .1       0
  5332.5    .075       0  5364.9      .1       0  5710.2    .075       0
Bank Sta=4998,5002
XS Rating Curve= 0 ,0
Exp/Cntr=0.3,0.1

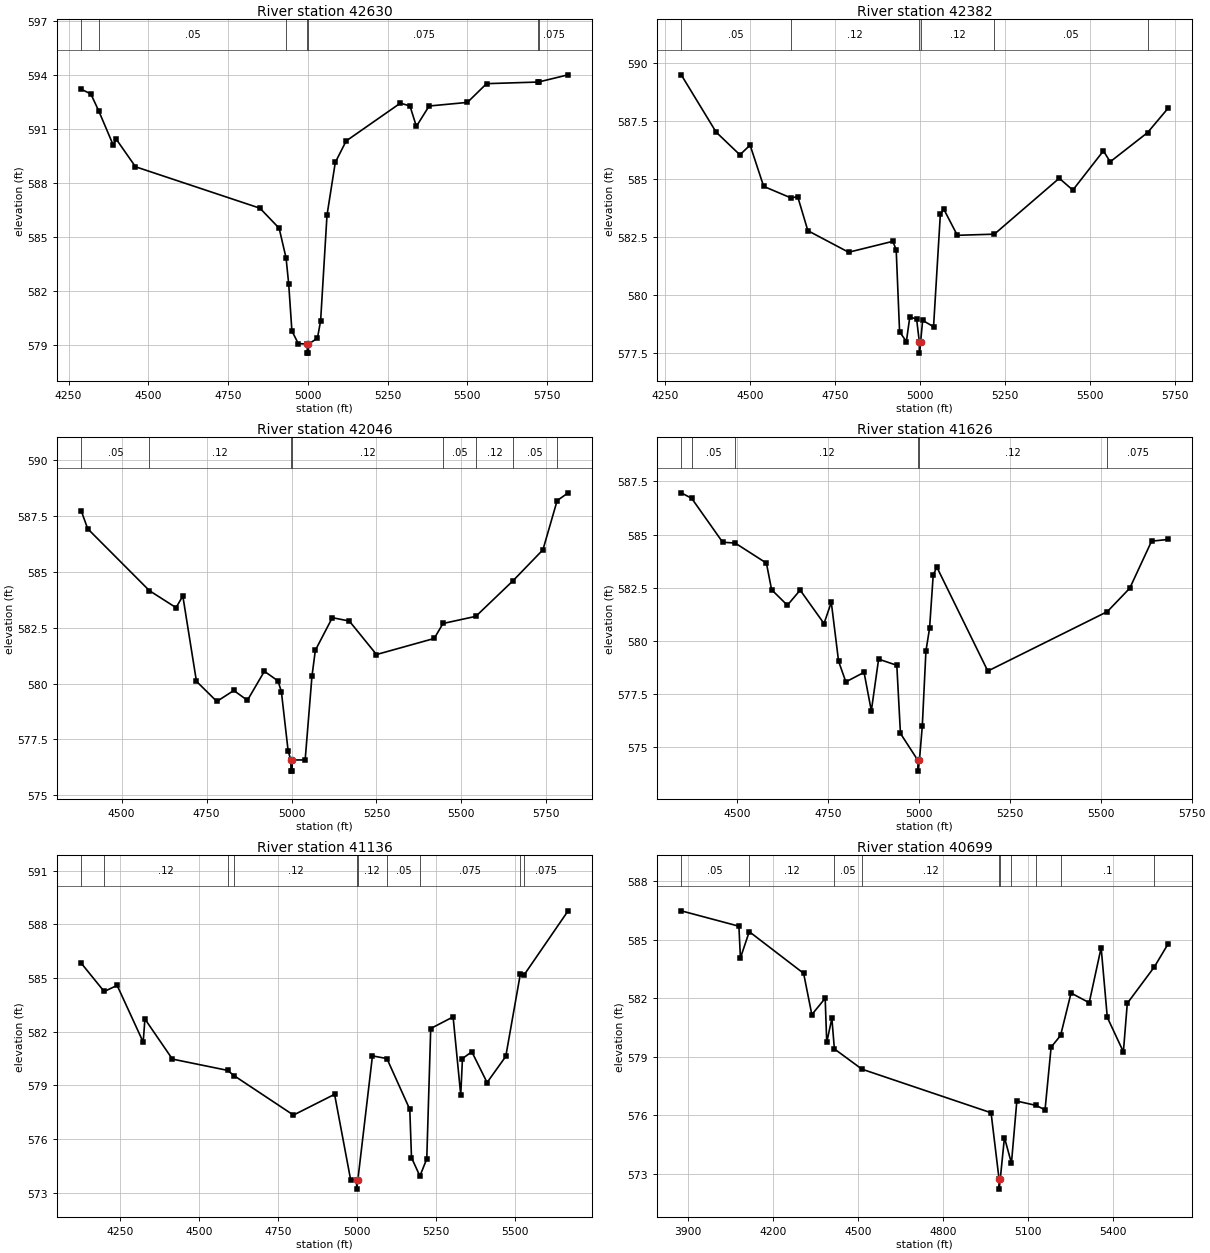
Type RM Length L Ch R = 1 ,42630   ,248,248,248
BEGIN DESCRIPTION:
COTTONWOOD BR AT DENTON 78.0
END DESCRIPTION:
XS GIS Cut Line= 3
      2409942.61      7024169.95      2409963.45      7023373.11
      2409947.83      7022644.49
#Sta/Elev= 30
  4289.8   593.2  4319.8  592.94  4344.8  591.99  4389.8  590.11  4399.8  590.42
  4459.8   588.9  4849.9   586.6    4910  585.49  4931.7  583.84    4940  582.39
    4950  579.79    4970  579.09    4998  579.06  4998.3  578.56  5001.8  578.56
    5002  579.06    5030  579.39    5040  580.35    5060  586.21    5086  589.14
    5120  590.33  5290.1  592.43  5320.1  592.27  5340.1  591.14  5380.1  592.27
  5500.1  592.47  5560.1  593.51  5722.7   593.6  5724.8  593.61  5815.7     594
#Mann= 7 ,-1 , 0
  4289.8    .075       0  4344.8     .05       0  4931.7    .075       0
    4998     .07       0    5002    .075       0  5722.7      .1       0
  5724.8    .075       0
Bank Sta=4998,5002
XS Rating Curve= 0 ,0
Exp/Cntr=0.3,0.1

Type RM Length L Ch R = 1 ,42382   ,336,336,336
BEGIN DESCRIPTION:
COTTONWOOD BR AT DENTON 77.5
END DESCRIPTION:
XS GIS Cut Line= 3
      2410199.42      7024162.73       2410208.6      7023449.23
      2410217.79      7022729.65
#Sta/Elev= 30
  4297.2   589.5  4399.9  587.03  4469.9  586.05  4499.9  586.47  4539.9  584.69
  4620.7  584.19    4640  584.25    4670  582.78    4790  581.85    4920  582.32
    4930  581.96    4940  578.42    4960     578    4970  579.05    4990  578.98
    4998     578  4998.3   577.5    5002     578  5007.9  578.91    5040  578.64
    5060  583.49    5070  583.71    5110  582.58    5219  582.63    5410  585.04
    5450  584.53    5540  586.22    5560  585.75  5670.1  587.01  5730.4  588.06
#Mann= 6 ,-1 , 0
  4297.2     .05       0  4620.7     .12       0    4998     .07       0
    5002     .12       0    5219     .05       0  5670.1    .075       0
Bank Sta=4998,5002
XS Rating Curve= 0 ,0
Exp/Cntr=0.3,0.1

Type RM Length L Ch R = 1 ,42046   ,420,420,420
BEGIN DESCRIPTION:
COTTONWOOD BR AT DENTON 77.0
END DESCRIPTION:
XS GIS Cut Line= 3
      2410520.95      7024129.02      2410530.14      7023415.55
      2410539.33      7022695.94
#Sta/Elev= 30
    4381  587.73    4400  586.93  4581.6  584.16    4660   583.4    4680  583.92
  4720.1   580.1  4780.1   579.2  4830.1  579.69  4870.1  579.25  4920.1  580.55
  4960.1  580.12  4970.1  579.64  4990.1  576.97    4998  576.58  4998.3  576.08
  5001.8  576.08    5002  576.58  5040.1  576.58  5060.1  580.32  5070.1  581.49
  5120.1  582.95  5170.1   582.8  5250.1   581.3  5420.1  582.02  5445.9  582.69
  5542.6  583.01  5652.4  584.61  5740.1  585.99  5781.9  588.19  5814.2  588.54
#Mann= 8 ,-1 , 0
    4381     .05       0  4581.6     .12       0    4998     .07       0
    5002     .12       0  5445.9     .05       0  5542.6     .12       0
  5652.4     .05       0  5781.9    .075       0
Bank Sta=4998,5002
XS Rating Curve= 0 ,0
Exp/Cntr=0.3,0.1

Type RM Length L Ch R = 1 ,41626   ,490,490,490
BEGIN DESCRIPTION:
COTTONWOOD BR AT DENTON 76.0
END DESCRIPTION:
XS GIS Cut Line= 3
      2410692.43      7024083.14      2410919.05      7023798.33
      2410925.17      7022824.72
#Sta/Elev= 30
  4347.6  586.96  4376.4   586.7  4461.4  584.64  4495.9   584.6  4581.6  583.66
  4595.9  582.41  4639.2  581.68  4674.4  582.39  4739.9  580.82  4759.9  581.82
  4779.9  579.05  4799.9  578.08  4849.9  578.53  4869.9  576.72  4889.9  579.15
  4939.9  578.86  4949.9  575.66    4998  574.39  4998.3  573.89    5002  574.39
  5009.9     576  5019.9  579.53  5029.9   580.6  5039.9   583.1  5049.9  583.47
  5189.9  578.59  5518.2  581.38  5579.9  582.48  5639.9  584.69  5685.2  584.77
#Mann= 6 ,-1 , 0
  4347.6     .12       0  4376.4     .05       0  4495.9     .12       0
    4998     .07       0    5002     .12       0  5518.2    .075       0
Bank Sta=4998,5002
XS Rating Curve= 0 ,0
Exp/Cntr=0.3,0.1

Type RM Length L Ch R = 1 ,41136   ,437,437,437
BEGIN DESCRIPTION:
COTTONWOOD BR AT DENTON 75.0
END DESCRIPTION:
XS GIS Cut Line= 4
      2410845.59      7024015.74      2411326.33      7023798.33
      2411409.01      7023384.93      2411629.48      7022836.81
#Sta/Elev= 30
  4127.2  585.82  4199.7  584.24  4240.7  584.58  4323.1  581.41  4328.6   582.7
  4415.5  580.46  4589.9  579.83  4611.7  579.52  4798.4  577.33  4928.5  578.49
  4979.5  573.69    4998  573.69  4998.3  573.19    5002  573.69  5048.3  580.64
    5094  580.49  5166.4  577.65  5171.8  574.95  5198.4  573.92  5220.1  574.88
  5232.6  582.17  5303.4  582.82  5327.6  578.45    5333  580.49  5362.6  580.87
  5410.9  579.15    5470  580.61  5516.2  585.23  5528.9  585.19  5667.2  588.75
#Mann= 10 ,-1 , 0
  4127.2     .05       0  4199.7     .12       0  4589.9     .05       0
  4611.7     .12       0    4998     .07       0    5002     .12       0
    5094     .05       0  5198.4    .075       0  5516.2      .1       0
  5528.9    .075       0
Bank Sta=4998,5002
XS Rating Curve= 0 ,0
Exp/Cntr=0.3,0.1

Type RM Length L Ch R = 1 ,40699   ,220,220,220
BEGIN DESCRIPTION:
COTTONWOOD BR AT DENTON 74.0
END DESCRIPTION:
XS GIS Cut Line= 3
      2410729.18      7024086.19      2411822.42      7023617.66
      2412216.06      7023263.68
#Sta/Elev= 30
  3875.8  586.49  4079.4   585.7  4084.8  584.07    4116  585.42  4307.9  583.28
  4336.9  581.16    4384     582  4389.5  579.73  4407.6  580.97  4416.5   579.4
  4513.7  578.36  4969.7  576.12    4998   572.7  4998.3   572.2    5002   572.7
  5016.9  574.85  5041.6  573.53  5060.6  576.72  5128.3   576.5  5160.2  576.27
  5181.7  579.49  5215.1  580.09  5252.1  582.27  5316.1  581.77  5358.3   584.6
    5380  581.02  5436.8  579.25  5450.6  581.74  5546.1  583.61  5594.6  584.79
#Mann= 10 ,-1 , 0
  3875.8     .05       0    4116     .12       0  4416.5     .05       0
  4513.7     .12       0    4998     .07       0    5002     .12       0
  5041.6     .05       0  5128.3    .075       0  5215.1      .1       0
  5546.1    .075       0
Bank Sta=4998,5002
XS Rating Curve= 0 ,0
Exp/Cntr=0.3,0.1

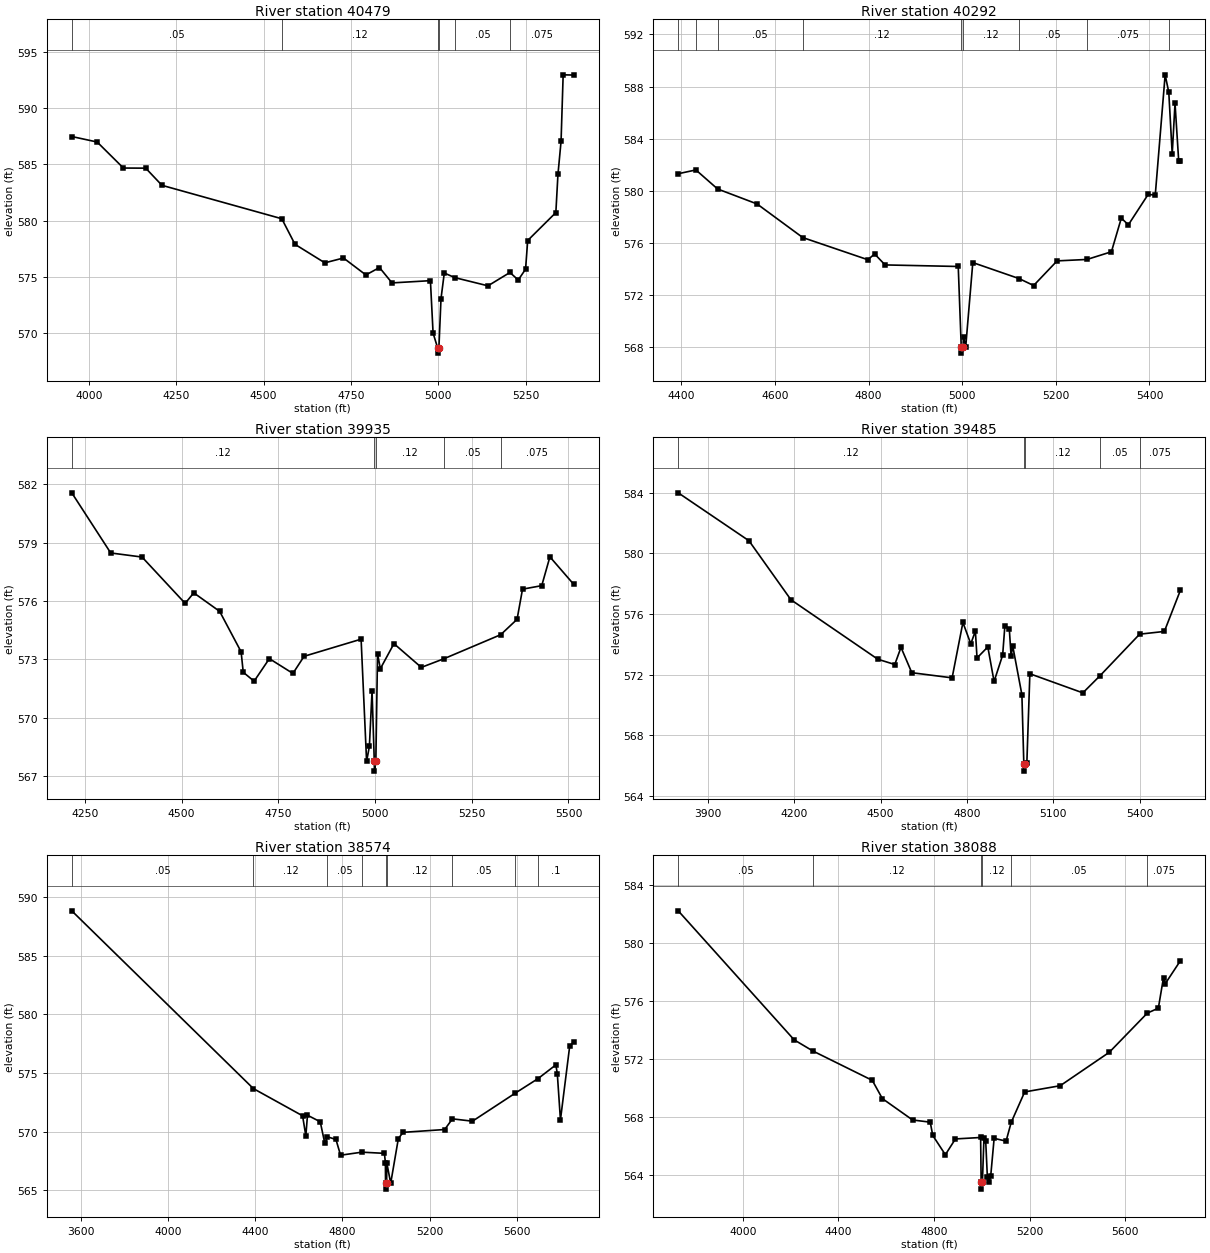
Type RM Length L Ch R = 1 ,40479   ,187,187,187
BEGIN DESCRIPTION:
COTTONWOOD BR AT DENTON 73.0
END DESCRIPTION:
XS GIS Cut Line= 3
      2410900.93       7024175.2      2411926.99      7023789.78
      2412208.24      7023597.07
#Sta/Elev= 30
  3951.2  587.49  4023.9     587    4099  584.68  4162.8  584.67  4209.3  583.14
  4552.3  580.16  4590.1  577.88  4675.5  576.23  4728.9  576.66    4793  575.15
  4831.9  575.81  4867.8  574.44  4977.7  574.64  4985.3  569.97    4998  568.68
  4998.3  568.18    5002  568.68    5008  573.04  5017.4  575.32  5047.7  574.91
  5142.4  574.18  5205.3  575.37    5229   574.7    5250  575.66  5256.1  578.22
  5336.7  580.71  5342.7  584.11  5351.6  587.06  5357.6  592.99  5388.2  592.97
#Mann= 6 ,-1 , 0
  3951.2     .05       0  4552.3     .12       0    4998     .07       0
    5002     .12       0  5047.7     .05       0  5205.3    .075       0
Bank Sta=4998,5002
XS Rating Curve= 0 ,0
Exp/Cntr=0.3,0.1

Type RM Length L Ch R = 1 ,40292   ,357,357,357
BEGIN DESCRIPTION:
COTTONWOOD BR AT DENTON 72.0
END DESCRIPTION:
XS GIS Cut Line= 3
       2411437.4      7024232.49        2411979.        7023960.
      2412369.74      7023706.42
#Sta/Elev= 30
  4393.7  581.31  4431.4   581.6  4477.7  580.14    4562  578.99  4659.6  576.41
  4798.5  574.71  4813.1  575.15  4835.4  574.31  4991.6  574.19    4998  568.04
  4998.3  567.54    5002  568.04    5003  568.79  5007.6  568.04  5022.7  574.49
  5121.6  573.26  5152.6  572.73  5202.7  574.62  5266.6  574.73  5318.7  575.32
  5339.8   577.9  5354.9  577.39  5397.1  579.72  5412.3  579.67  5433.4   588.9
  5441.2  587.56  5448.5  582.81  5454.5  586.72  5462.4  582.26  5465.8  582.26
#Mann= 9 ,-1 , 0
  4393.7     .05       0  4431.4     .12       0  4477.7     .05       0
  4659.6     .12       0    4998     .07       0    5002     .12       0
  5121.6     .05       0  5266.6    .075       0  5441.2      .1       0
Bank Sta=4998,5002
XS Rating Curve= 0 ,0
Exp/Cntr=0.3,0.1

Type RM Length L Ch R = 1 ,39935   ,450,450,450
BEGIN DESCRIPTION:
COTTONWOOD BR AT DENTON 71.0
END DESCRIPTION:
XS GIS Cut Line= 3
      2411525.97       7024560.6      2412171.78       7024242.9
      2412588.42      7023841.88
#Sta/Elev= 30
  4215.9  581.56  4316.6  578.47  4397.6  578.26    4509  575.88  4531.3  576.42
  4598.2  575.47  4653.7  573.39  4659.2  572.34  4687.3  571.88  4726.7  573.04
  4787.6  572.28  4816.5  573.16  4963.9  574.04  4978.1  567.76  4985.3  568.53
  4992.2  571.37    4998  567.76  4998.3  567.26    5002  567.76  5006.4   573.3
  5013.6  572.52  5048.8  573.81  5119.6  572.59  5178.7  573.04  5324.8  574.27
  5367.1  575.06  5381.2  576.61  5430.9  576.79    5452  578.27  5513.9  576.85
#Mann= 5 ,-1 , 0
  4215.9     .12       0    4998     .07       0    5002     .12       0
  5178.7     .05       0  5324.8    .075       0
Bank Sta=4998,5002
XS Rating Curve= 0 ,0
Exp/Cntr=0.3,0.1

Type RM Length L Ch R = 1 ,39485   ,911,911,911
BEGIN DESCRIPTION:
COTTONWOOD BR AT DENTON 70.0
END DESCRIPTION:
XS GIS Cut Line= 3
      2411479.07      7025055.41        2412529.        7024460.
      2412915.31      7024087.87
#Sta/Elev= 30
  3797.6  583.98  4043.2  580.82  4188.9  576.93  4490.4  573.01  4549.5  572.66
  4571.1  573.79  4608.6  572.12  4748.6  571.78  4786.1  575.43  4813.5  574.02
  4829.4  574.87  4835.1  573.09  4872.6  573.82  4894.3  571.54  4924.1  573.28
  4931.8  575.21  4947.1  575.03  4953.4  573.22  4959.1  573.88  4990.9  570.67
  4997.6  566.13  4998.2  565.63  5002.5  566.13  5008.1  566.16  5018.6  572.05
  5202.6  570.79  5262.2  571.92  5399.7  574.66  5485.6  574.84    5541  577.54
#Mann= 5 ,-1 , 0
  3797.6     .12       0  4997.6     .07       0  5002.5     .12       0
  5262.2     .05       0  5399.7    .075       0
Bank Sta=4997.6,5002.5
XS Rating Curve= 0 ,0
Exp/Cntr=0.3,0.1

Type RM Length L Ch R = 1 ,38574   ,486,486,486
BEGIN DESCRIPTION:
COTTONWOOD BR AT DENTON 69.0
END DESCRIPTION:
XS GIS Cut Line= 3
      2411629.03      7025809.98        2412829.        7025010.
      2413405.06      7024369.13
#Sta/Elev= 30
  3557.7  588.81    4391  573.66  4616.8  571.34  4631.8  569.63  4639.3  571.39
  4697.9  570.83  4718.9  568.98  4731.1  569.55    4770  569.32  4791.1  567.98
  4888.6  568.24  4992.4  568.14  4996.9  567.33  4997.5  565.59  4998.1  565.09
  5002.6  565.59  5003.2  567.33  5021.2  565.59  5056.3   569.4    5078  569.93
  5268.8  570.17  5304.5  571.08  5396.4  570.88  5593.5  573.28  5697.3  574.51
  5779.1  575.68  5785.8  574.91  5800.1  570.99  5842.7   577.3  5861.6  577.65
#Mann= 9 ,-1 , 0
  3557.7     .05       0    4391     .12       0  4731.1     .05       0
  4888.6     .12       0  4997.5     .07       0  5002.6     .12       0
  5304.5     .05       0  5593.5    .075       0  5697.3      .1       0
Bank Sta=4997.5,5002.6
XS Rating Curve= 0 ,0
Exp/Cntr=0.3,0.1

Type RM Length L Ch R = 1 ,38088   ,424,424,424
BEGIN DESCRIPTION:
COTTONWOOD BR AT DENTON 68.0
END DESCRIPTION:
XS GIS Cut Line= 3
      2411928.97      7025660.01        2413129.        7025260.
      2413749.87      7024701.27
#Sta/Elev= 30
  3730.3  582.23  4215.2  573.31  4293.5  572.54    4542  570.51  4584.1  569.25
  4710.6  567.77  4784.4  567.62    4795   566.7  4847.7  565.37  4889.8  566.46
  4995.2  566.56  4997.4  563.49  4998.1  562.99  5002.7  563.49  5009.1   566.5
  5016.5   566.3  5023.3  563.86  5030.7  563.49  5037.5  563.92  5051.7   566.5
  5101.7  566.31  5123.2  567.61  5179.5  569.71  5328.2  570.14  5533.4  572.45
  5692.6  575.16  5738.6   575.5  5760.2  577.62    5767  577.18  5830.5  578.77
#Mann= 6 ,-1 , 0
  3730.3     .05       0  4293.5     .12       0  4997.4     .07       0
  5002.7     .12       0  5123.2     .05       0  5692.6    .075       0
Bank Sta=4997.4,5002.7
XS Rating Curve= 0 ,0
Exp/Cntr=0.3,0.1

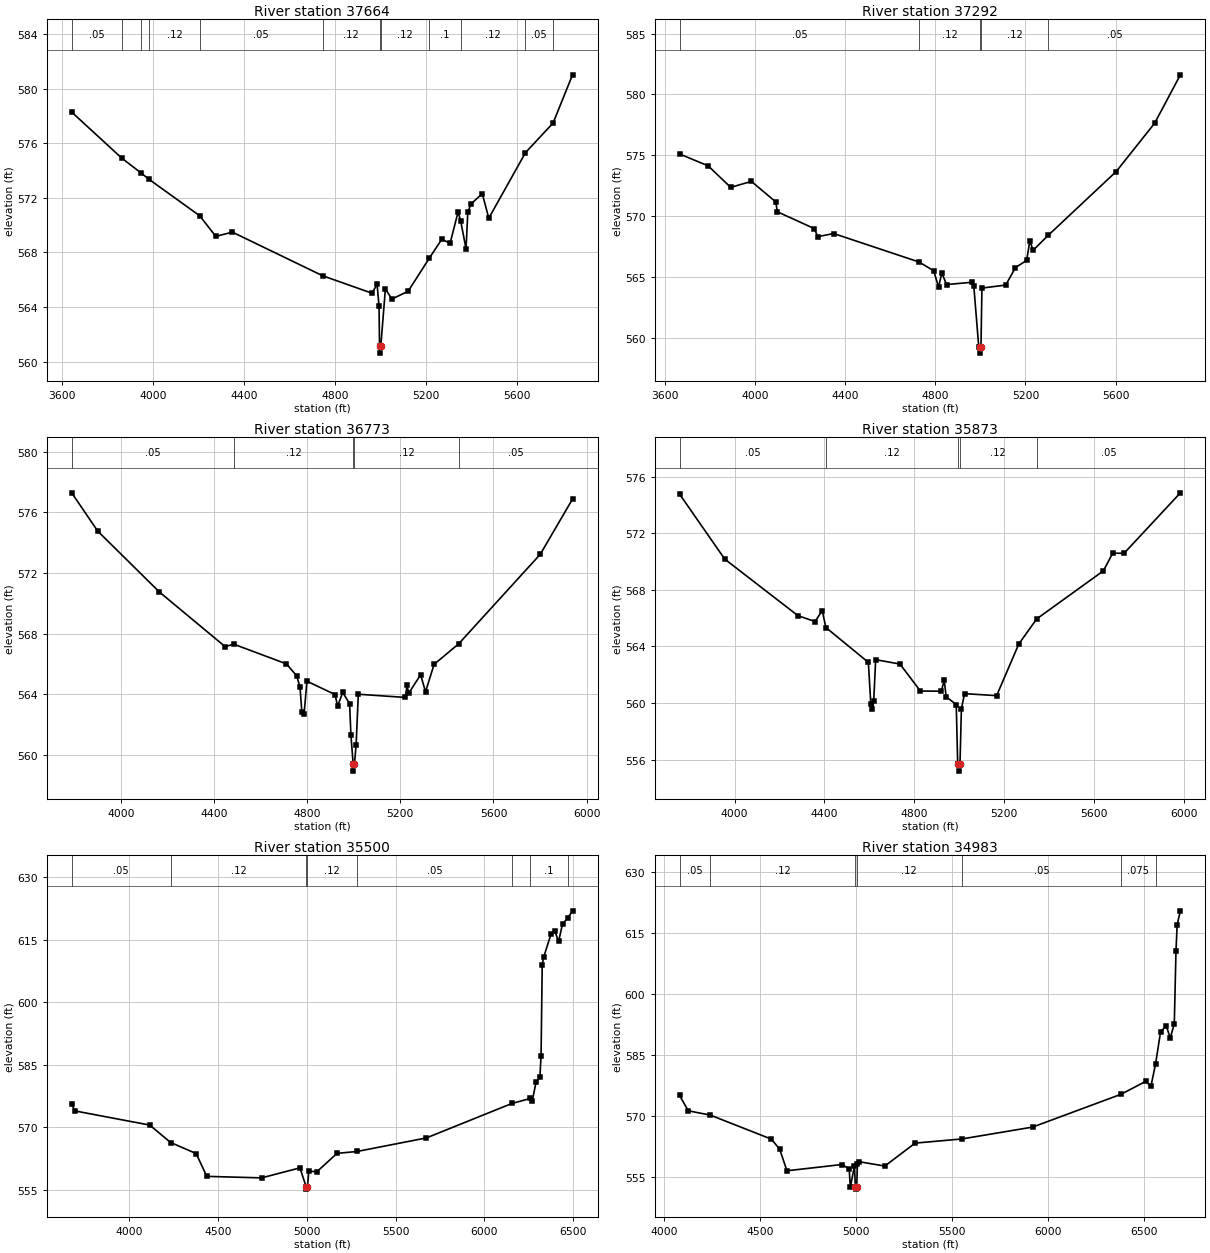
Type RM Length L Ch R = 1 ,37664   ,372,372,372
BEGIN DESCRIPTION:
COTTONWOOD BR AT DENTON 67.0
END DESCRIPTION:
XS GIS Cut Line= 3
      2412213.44      7026102.28        2413429.        7025510.
      2414078.97      7024960.03
#Sta/Elev= 30
  3642.8  578.28  3863.1  574.91  3949.6   573.8  3983.6  573.35  4205.9  570.69
  4276.7  569.18  4349.8  569.49  4747.7  566.29  4963.9  565.02  4986.5  565.67
    4995  564.06  4997.3  561.13  4998.1  560.63  5002.7  561.13    5023  565.34
  5051.5  564.59    5123  565.16  5216.1  567.58  5271.3  568.97  5307.6  568.67
  5342.7  570.96  5354.4  570.31  5377.8  568.25  5385.6  570.96  5399.9  571.56
  5449.3  572.31  5477.9  570.51  5639.3  575.31  5760.8  577.48  5846.4  581.01
#Mann= 12 ,-1 , 0
  3642.8     .05       0  3863.1     .12       0  3949.6     .05       0
  3983.6     .12       0  4205.9     .05       0  4747.7     .12       0
  4997.3     .07       0  5002.7     .12       0  5216.1      .1       0
  5354.4     .12       0  5639.3     .05       0  5760.8    .075       0
Bank Sta=4997.3,5002.7
XS Rating Curve= 0 ,0
Exp/Cntr=0.3,0.1

Type RM Length L Ch R = 1 ,37292   ,519,519,519
BEGIN DESCRIPTION:
COTTONWOOD BR AT DENTON 66.0
END DESCRIPTION:
XS GIS Cut Line= 3
       2412572.8      7026571.04      2413598.86      7025810.61
      2414329.03      7025209.97
#Sta/Elev= 30
  3665.2  575.11    3792  574.14  3892.2  572.37  3984.1  572.86  4092.6  571.17
  4098.8  570.37  4263.7  568.98  4278.3  568.32  4349.2  568.58  4728.4  566.24
  4793.1  565.52  4814.6  564.19  4829.2  565.34  4850.1  564.39  4964.4  564.58
  4970.9  564.31  4993.1  559.26  4997.1  559.26  4998.1  558.76  5002.9  559.26
  5007.2   564.1  5112.9  564.35    5156  565.79  5205.5  566.37  5219.8  567.97
  5234.2   567.2  5302.3  568.45    5603  573.67  5773.7  577.64  5887.8  581.61
#Mann= 5 ,-1 , 0
  3665.2     .05       0  4728.4     .12       0  4997.1     .07       0
  5002.9     .12       0  5302.3     .05       0
Bank Sta=4997.1,5002.9
XS Rating Curve= 0 ,0
Exp/Cntr=0.3,0.1

Type RM Length L Ch R = 1 ,36773   ,900,900,900
BEGIN DESCRIPTION:
COTTONWOOD BR AT DENTON 65.0
END DESCRIPTION:
XS GIS Cut Line= 3
      2412778.98      7026710.01        2413879.        7026210.
      2414378.99      7025410.02
#Sta/Elev= 30
  3788.1  577.28  3900.2  574.75  4164.9  570.74  4447.2  567.14  4484.3   567.3
  4710.8     566  4754.8  565.21    4769  564.47  4776.7  562.85  4786.6  562.72
  4798.7  564.86  4919.5  563.98  4930.5  563.22  4952.5  564.12  4982.1  563.37
  4987.6  561.34  4997.1  559.43    4998  558.93  5002.9  559.43    5010  560.66
  5019.4     564  5220.5  563.79  5229.3  564.58  5235.2  564.05  5287.1  565.28
  5308.3  564.16  5344.9  565.97  5450.4  567.32  5801.3  573.23  5939.8  576.87
#Mann= 5 ,-1 , 0
  3788.1     .05       0  4484.3     .12       0  4997.1     .07       0
  5002.9     .12       0  5450.4     .05       0
Bank Sta=4997.1,5002.9
XS Rating Curve= 0 ,0
Exp/Cntr=0.3,0.1

Type RM Length L Ch R = 1 ,35873   ,373,373,373
BEGIN DESCRIPTION:
COTTONWOOD BR AT DENTON 64.0
END DESCRIPTION:
XS GIS Cut Line= 3
      2413182.18      7026883.54        2414329.        7026410.
      2415077.32      7025764.35
#Sta/Elev= 30
  3755.3  574.76  3956.5  570.17    4282  566.18  4358.6  565.76  4390.2  566.54
  4406.6  565.34  4595.7  562.88  4606.6  559.93    4614  559.56  4619.5  560.14
  4628.2  563.07  4736.4  562.76    4827  560.86  4920.3  560.84  4933.5  561.61
  4941.9  560.45  4986.8   559.9  4993.3   555.7  4996.6   555.7  4997.7   555.2
  5003.5   555.7  5009.8  559.61    5024  560.67  5166.6  560.53  5265.4  564.18
  5345.1  565.95  5641.6  569.34  5683.3  570.59  5733.8  570.58  5984.4  574.85
#Mann= 5 ,-1 , 0
  3755.3     .05       0  4406.6     .12       0  4996.6     .07       0
  5003.5     .12       0  5345.1     .05       0
Bank Sta=4996.6,5003.5
XS Rating Curve= 0 ,0
Exp/Cntr=0.3,0.1

Type RM Length L Ch R = 1 ,35500   ,517,517,517
BEGIN DESCRIPTION:
COTTONWOOD BR AT DENTON 63.0
END DESCRIPTION:
XS GIS Cut Line= 4
      2413244.56      7027160.15      2414381.23      7026695.75
      2414526.63      7026699.45        2415629.        7025760.
#Sta/Elev= 30
  3675.1  575.67  3692.4  573.98  4114.6  570.58  4232.6  566.39  4376.4  563.74
  4436.1  558.27  4745.1  557.91  4960.8  560.31  4996.6  555.71  4997.6  555.21
  5003.5  555.71  5010.8  559.51  5056.7  559.39  5169.8  563.79  5282.1  564.24
  5673.8   567.5  6156.2  575.78    6259  576.96  6270.1   576.4  6290.9  580.82
  6312.9  582.07  6319.5  587.26    6326  609.06  6333.7  610.79  6376.6  616.54
  6397.4  617.04  6418.3  614.63  6440.3  618.82  6470.2  620.28  6496.8  621.98
#Mann= 8 ,-1 , 0
  3675.1     .05       0  4232.6     .12       0  4996.6     .07       0
  5003.5     .12       0  5282.1     .05       0  6156.2    .075       0
    6259      .1       0  6470.2    .075       0
Bank Sta=4996.6,5003.5
XS Rating Curve= 0 ,0
Exp/Cntr=0.3,0.1

Type RM Length L Ch R = 1 ,34983   ,378,378,378
BEGIN DESCRIPTION:
COTTONWOOD BR AT DENTON 62.0
END DESCRIPTION:
XS GIS Cut Line= 3
      2413578.96      7027460.02        2414379.        7027010.
      2415755.57       7026033.8
#Sta/Elev= 30
  4081.8  575.05  4127.4  571.28  4242.4  570.21  4559.6   564.3  4602.9  561.81
  4640.5  556.51  4926.7  558.05  4964.3  556.99  4970.1  552.49  4991.8  557.65
  4996.5  552.49  4997.6  551.99  5003.5  552.49  5007.1  558.09  5013.2  558.76
  5149.8  557.67  5307.3  563.32  5549.6  564.34  5918.8  567.27  6378.8  575.35
  6506.9  578.52  6533.9   577.3  6558.2   582.8  6584.4  590.76  6613.9  592.17
  6634.8  589.19  6655.7  592.75  6664.4  610.55  6670.5  617.08  6687.3  620.52
#Mann= 7 ,-1 , 0
  4081.8     .05       0  4242.4     .12       0  4996.5     .07       0
  5003.5     .12       0  5549.6     .05       0  6378.8    .075       0
  6558.2      .1       0
Bank Sta=4996.5,5003.5
XS Rating Curve= 0 ,0
Exp/Cntr=0.3,0.1