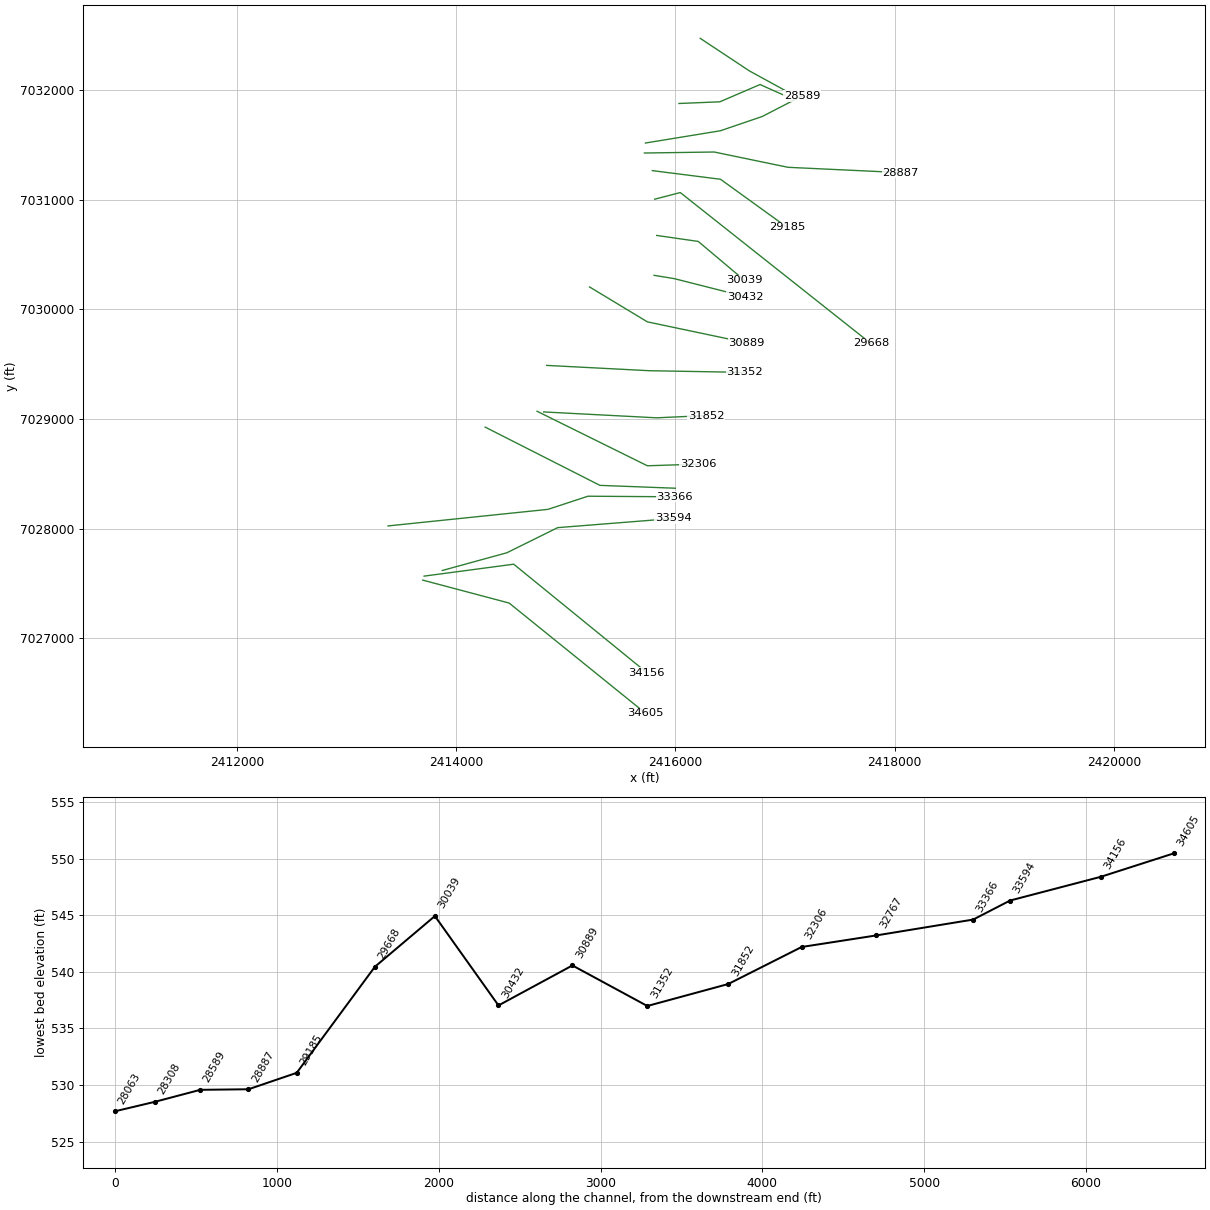
HEC-RAS study COTTONWOOD BR AT DENTON.prj: COTTONWOOD BR AT DENTON Base Level Engineering

--- COTTONWOOD BR AT DENTON.g01 (geometry) --- (continued)

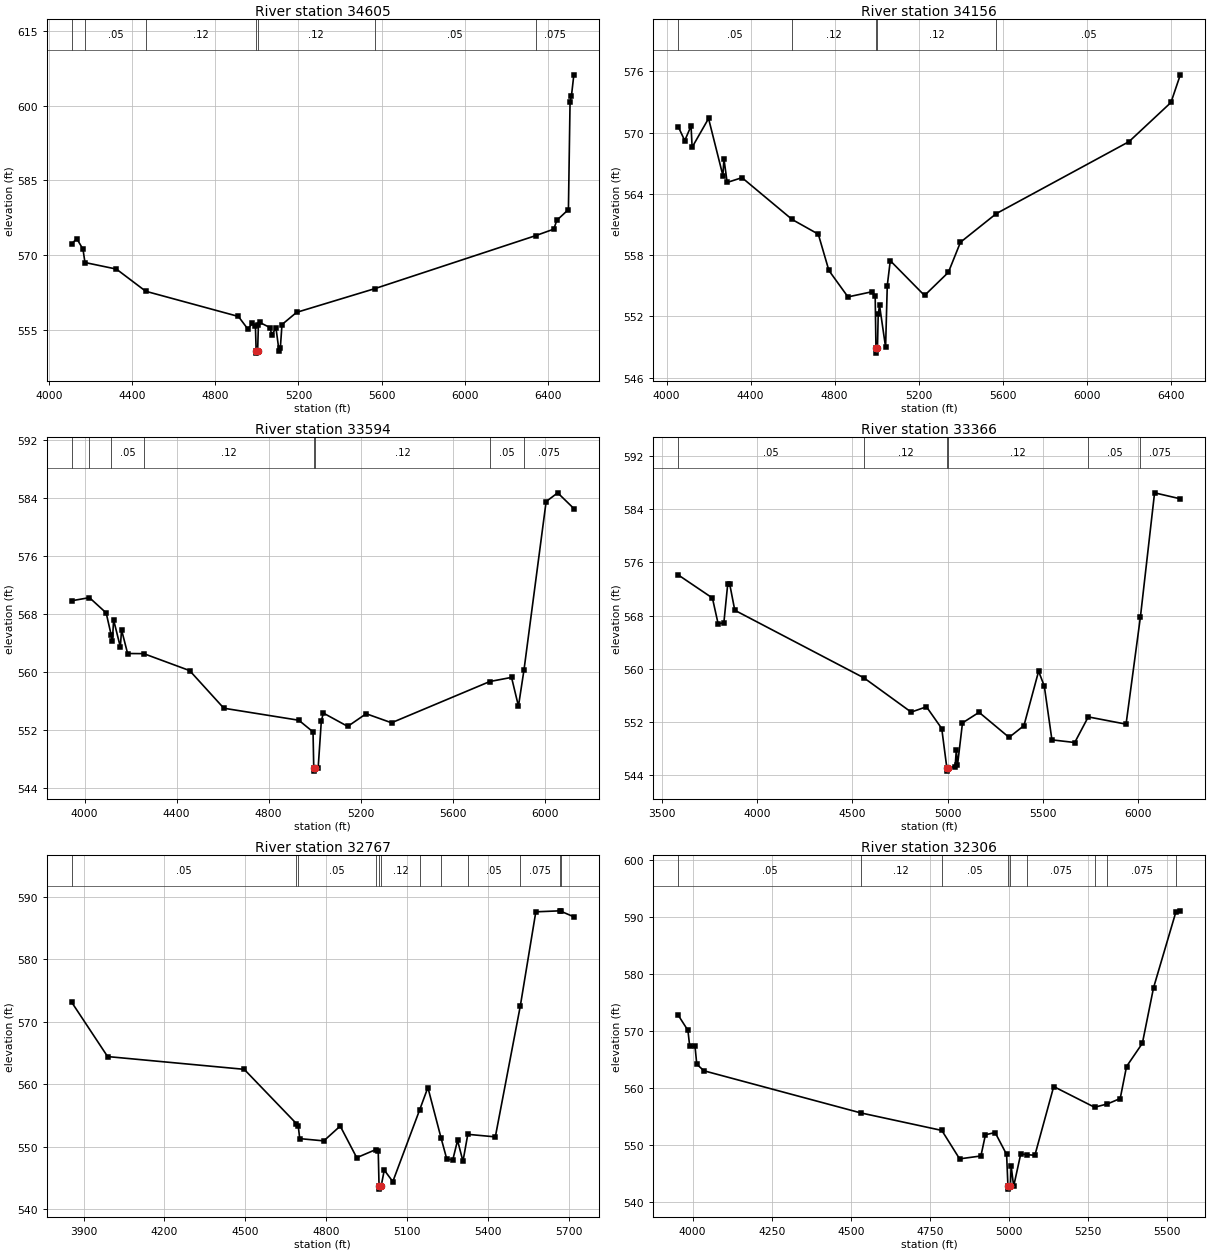
Type RM Length L Ch R = 1 ,34605   ,449,449,449
BEGIN DESCRIPTION:
COTTONWOOD BR AT DENTON 61.0
END DESCRIPTION:
XS GIS Cut Line= 3
      2413696.14      7027529.94      2414484.19      7027320.81
       2415729.6      7026314.79
#Sta/Elev= 30
  4109.1  572.34  4133.1  573.36    4163  571.25  4172.6  568.58  4323.7  567.27
  4465.1  562.83    4911  557.79  4956.3  555.28  4978.5  556.42  4992.9  555.85
  4996.5  550.95  4997.6  550.45  5003.6  550.95  5007.3  556.11  5013.7  556.59
  5063.3  555.56  5071.2  554.16  5092.1  555.42  5106.4  550.95  5112.9  551.49
  5120.8  556.17  5191.2  558.61  5567.9  563.36  6340.9  573.95  6428.9  575.26
  6443.3  577.02  6499.3  579.18  6507.2  600.77  6513.7  601.87  6525.4  606.14
#Mann= 7 ,-1 , 0
  4109.1     .12       0  4172.6     .05       0  4465.1     .12       0
  4996.5     .07       0  5003.6     .12       0  5567.9     .05       0
  6340.9    .075       0
Bank Sta=4996.5,5003.6
XS Rating Curve= 0 ,0
Exp/Cntr=0.3,0.1

Type RM Length L Ch R = 1 ,34156   ,562,562,562
BEGIN DESCRIPTION:
COTTONWOOD BR AT DENTON 60.0
END DESCRIPTION:
XS GIS Cut Line= 3
      2413708.24      7027566.31      2414525.95      7027675.19
      2415739.06       7026687.3
#Sta/Elev= 30
  4055.5  570.59  4086.5  569.22  4116.5  570.66  4121.6  568.57  4199.8  571.39
    4268   565.8    4273  567.43  4288.3  565.12  4358.9  565.59  4597.6  561.49
  4722.1  560.05  4772.5  556.49  4863.3   553.9  4978.4  554.41  4992.8  553.95
  4996.5  548.89  4997.6  548.39  5003.6  548.89  5007.2  552.19  5013.6  553.07
  5042.3  548.97  5050.3  555.01  5064.6  557.45  5227.6  554.04  5341.1  556.31
  5398.6  559.26  5569.5  562.07  6200.7  569.12  6400.4  572.96  6444.9  575.67
#Mann= 5 ,-1 , 0
  4055.5     .05       0  4597.6     .12       0  4996.5     .07       0
  5003.6     .12       0  5569.5     .05       0
Bank Sta=4996.5,5003.6
XS Rating Curve= 0 ,0
Exp/Cntr=0.3,0.1

Type RM Length L Ch R = 1 ,33594   ,228,228,228
BEGIN DESCRIPTION:
COTTONWOOD BR AT DENTON 59.0
END DESCRIPTION:
XS GIS Cut Line= 4
      2413874.87      7027617.89      2414463.45      7027779.36
      2414926.99      7028008.53      2415979.08      7028091.86
#Sta/Elev= 30
  3944.4  569.83  4021.2  570.26  4093.9  568.15  4115.6  565.13  4121.1   564.3
  4126.3  567.19  4155.6  563.43  4160.8  565.81  4187.2  562.54  4257.5  562.52
  4456.8  560.18  4605.5  554.98  4931.5  553.32  4993.3  551.71  4996.4  546.79
  4997.5  546.29  5003.7  546.79  5015.7  546.79  5029.4  553.24  5038.2  554.31
  5144.1  552.47  5224.3  554.22  5334.6  552.97  5761.9  558.67  5856.3  559.24
  5886.4  555.27  5910.5  560.28  6006.7  583.53  6056.9  584.74  6127.2  582.57
#Mann= 8 ,-1 , 0
  3944.4     .05       0  4021.2     .12       0  4115.6     .05       0
  4257.5     .12       0  4996.4     .07       0  5003.7     .12       0
  5761.9     .05       0  5910.5    .075       0
Bank Sta=4996.4,5003.7
XS Rating Curve= 0 ,0
Exp/Cntr=0.3,0.1

Type RM Length L Ch R = 1 ,33366   ,599,599,599
BEGIN DESCRIPTION:
COTTONWOOD BR AT DENTON 58.0
END DESCRIPTION:
XS GIS Cut Line= 4
      2413380.14      7028024.16      2414838.45      7028175.19
      2415203.03      7028294.99      2415994.35      7028289.78
#Sta/Elev= 30
  3583.3   574.1  3763.1  570.63  3793.3  566.74  3823.4  566.93  3843.5   572.7
  3853.6   572.8  3880.7  568.79  4560.6  558.62  4808.7  553.48  4889.1  554.28
  4969.5  551.01  4996.2  545.11  4997.3  544.61  5003.9  545.11  5039.9  545.28
  5046.2  547.84  5052.3  545.47  5078.6  551.86  5165.8  553.45  5323.7  549.68
  5401.9  551.45  5479.1  559.63  5509.1  557.37  5549.1  549.31  5669.1  548.91
  5740.2  552.76  5939.1  551.67  6014.8  567.83  6089.1  586.44  6224.5  585.54
#Mann= 6 ,-1 , 0
  3583.3     .05       0  4560.6     .12       0  4996.2     .07       0
  5003.9     .12       0  5740.2     .05       0  6014.8    .075       0
Bank Sta=4996.2,5003.9
XS Rating Curve= 0 ,0
Exp/Cntr=0.3,0.1

Type RM Length L Ch R = 1 ,32767   ,461,461,461
BEGIN DESCRIPTION:
COTTONWOOD BR AT DENTON 57.0
END DESCRIPTION:
XS GIS Cut Line= 3
      2414265.52       7028925.2      2415312.41      7028393.94
      2415999.95       7028367.9
#Sta/Elev= 30
  3856.5  573.09  3989.4  564.42  4495.9  562.38  4689.6  553.69  4696.5  553.26
  4701.9  551.29  4791.2  550.93  4852.1   553.3  4913.3  548.24  4984.1  549.54
    4993  549.33  4996.1  543.71  4997.3  543.21    5004  543.71  5015.4  546.26
  5047.1  544.41  5147.1  555.94  5177.2  559.47  5225.9  551.42  5247.2  548.03
  5269.5  547.89  5287.2  551.01  5307.3  547.66  5325.2  551.98  5427.3  551.57
    5520  572.53  5577.5  587.58  5667.2  587.74  5672.2  587.64  5718.5  586.78
#Mann= 12 ,-1 , 0
  3856.5     .05       0  4689.6     .12       0  4696.5     .05       0
  4984.1     .12       0  4996.1     .07       0    5004     .12       0
  5147.1     .05       0  5225.9    .075       0  5325.2     .05       0
    5520    .075       0  5667.2      .1       0  5672.2    .075       0
Bank Sta=4996.1,5004
XS Rating Curve= 0 ,0
Exp/Cntr=0.3,0.1

Type RM Length L Ch R = 1 ,32306   ,454,454,454
BEGIN DESCRIPTION:
COTTONWOOD BR AT DENTON 56.0
END DESCRIPTION:
XS GIS Cut Line= 3
      2414738.83      7029069.67      2415745.08       7028572.6
       2416208.8      7028587.75
#Sta/Elev= 30
  3954.4  572.71    3985  570.05  3990.6  567.28  4007.4  567.24    4013  564.11
  4035.5  562.96  4531.6  555.56  4787.2  552.49  4843.4   547.5  4910.7  548.01
    4925  551.73  4955.6  552.12  4991.9  548.27  4996.1  542.69  4997.3  542.19
    5004  542.69  5006.1  546.32  5014.2  542.69  5036.5  548.36    5057  548.23
  5081.2  548.13  5140.7  560.19  5269.7  556.56  5310.4  557.14  5350.8  558.09
  5370.8  563.71  5420.8  567.78  5456.1  577.53  5526.6  590.81  5540.7  591.03
#Mann= 9 ,-1 , 0
  3954.4     .05       0  4531.6     .12       0  4787.2     .05       0
  4996.1    .033       0    5004     .05       0    5057    .075       0
  5269.7      .1       0  5310.4    .075       0  5526.6     .05       0
Bank Sta=4996.1,5004
XS Rating Curve= 0 ,0
Exp/Cntr=0.3,0.1

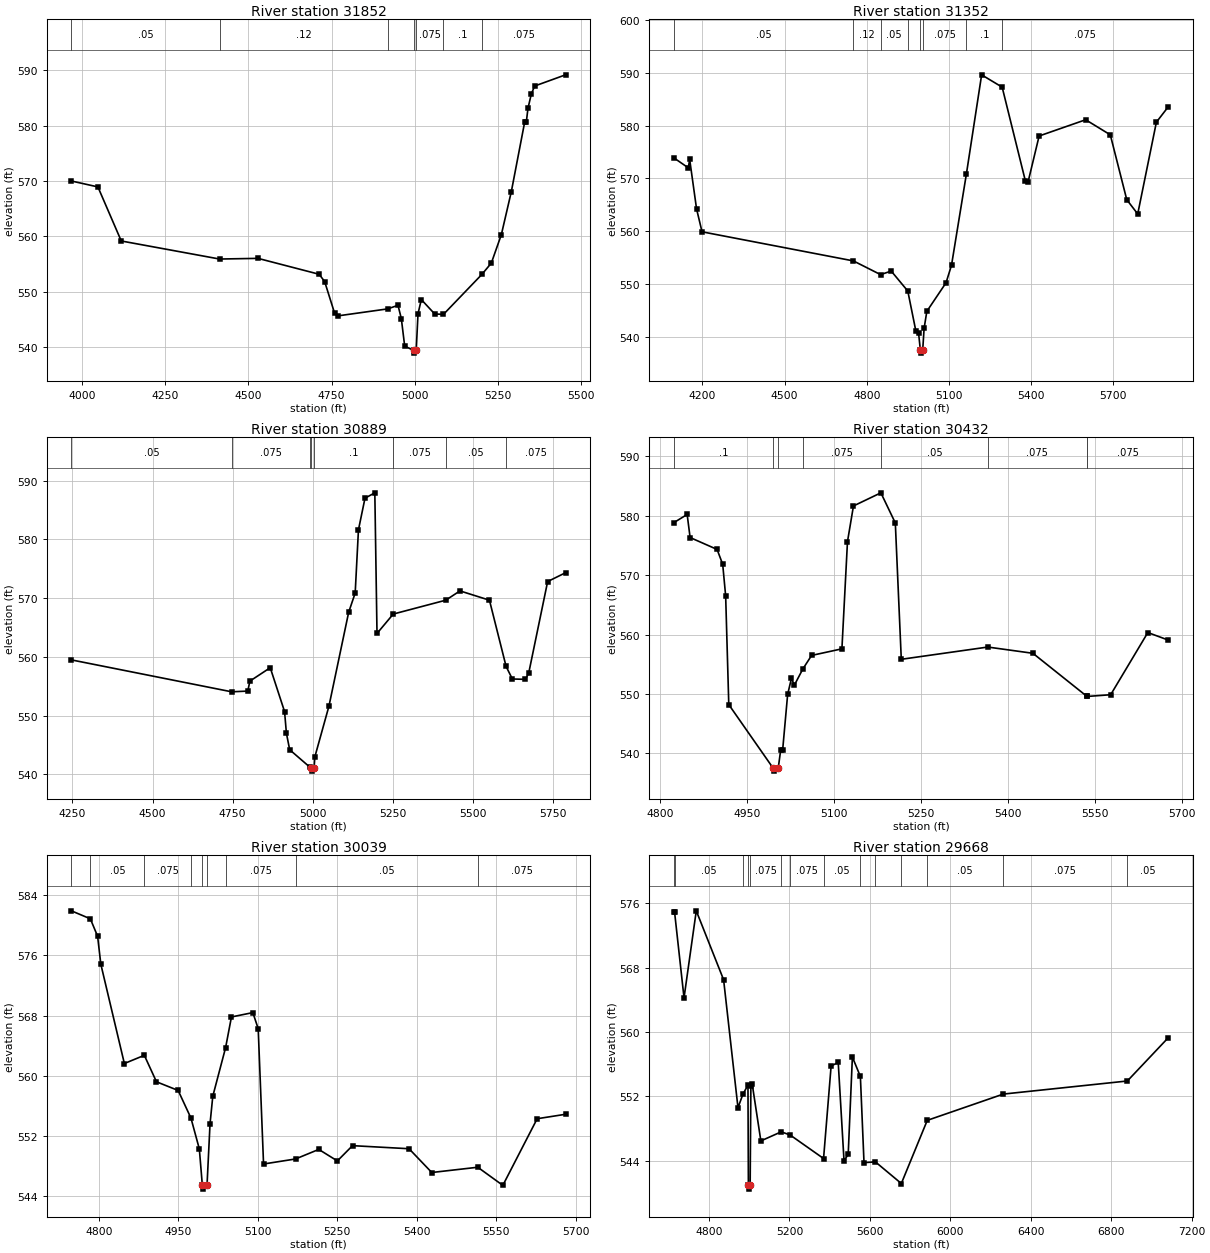
Type RM Length L Ch R = 1 ,31852   ,500,500,500
BEGIN DESCRIPTION:
COTTONWOOD BR AT DENTON 55.0
END DESCRIPTION:
XS GIS Cut Line= 3
       2414799.4      7029063.62        2415829.        7029010.
      2416281.55      7029030.28
#Sta/Elev= 30
  3968.5     570  4048.2  568.93  4118.3  559.17  4413.6  555.91  4528.9  556.03
  4712.6  553.16  4729.1  551.85  4759.2  546.09  4769.2  545.65  4918.7  546.91
  4949.4  547.56  4959.4  545.16  4969.5  540.19    4996  539.42  4997.2  538.92
  5004.1  539.42  5009.5  546.03  5019.5  548.59  5059.6  545.99    5086  545.92
  5201.4  553.14  5229.7  555.18  5259.8  560.32  5289.8  568.09  5329.7  580.59
  5334.7  580.63  5339.8  583.14  5349.8  585.71  5359.9  587.15  5452.5  589.17
#Mann= 7 ,-1 , 0
  3968.5     .05       0  4413.6     .12       0  4918.7    .075       0
    4996     .07       0  5004.1    .075       0    5086      .1       0
  5201.4    .075       0
Bank Sta=4996,5004.1
XS Rating Curve= 0 ,0
Exp/Cntr=0.3,0.1

Type RM Length L Ch R = 1 ,31352   ,463,463,463
BEGIN DESCRIPTION:
COTTONWOOD BR AT DENTON 54.0
END DESCRIPTION:
XS GIS Cut Line= 3
      2414826.71      7029487.96      2415763.27      7029439.46
      2416630.12      7029424.31
#Sta/Elev= 30
  4095.9  573.87  4148.2     572  4153.2  573.59  4178.3  564.25  4198.3  559.91
  4751.1  554.41  4850.4  551.82  4889.3  552.49  4949.8  548.72  4979.4  541.13
  4989.4  540.69  4995.9  537.48  4997.1  536.98  5004.2  537.48  5009.4  541.66
  5019.4  544.88  5089.5  550.28  5109.5  553.59  5164.1  570.91  5219.5  589.58
  5294.5  587.25  5379.5  569.48  5389.5  569.41  5429.5  578.02  5599.5  581.09
  5689.5  578.24  5749.6  565.98  5789.6  563.28  5857.8  580.63  5900.7  583.51
#Mann= 8 ,-1 , 0
  4095.9     .05       0  4751.1     .12       0  4850.4     .05       0
  4949.8    .075       0  4995.9     .07       0  5004.2    .075       0
  5164.1      .1       0  5294.5    .075       0
Bank Sta=4995.9,5004.2
XS Rating Curve= 0 ,0
Exp/Cntr=0.3,0.1

Type RM Length L Ch R = 1 ,30889   ,457,457,457
BEGIN DESCRIPTION:
COTTONWOOD BR AT DENTON 53.0
END DESCRIPTION:
XS GIS Cut Line= 3
      2415217.69      7030203.27      2415745.08      7029885.02
      2416651.31      7029694.07
#Sta/Elev= 30
  4246.8  559.49  4746.9  554.06  4797.3  554.18  4803.9  555.88  4867.4  558.16
  4912.1   550.7  4917.9  546.99  4928.1   544.2  4992.3  541.18  4995.8  541.06
  4997.1  540.56  5004.2  541.06  5006.6  542.98  5050.7  551.64  5112.1  567.58
  5132.5  570.87  5142.7  581.62  5163.1  587.01  5193.8  587.92  5200.6  563.99
  5251.3  567.29  5415.2  569.65  5459.5  571.23  5551.5  569.65  5603.5  558.37
    5623  556.24  5663.9  556.18  5674.1  557.26  5733.1  572.82  5788.9  574.32
#Mann= 8 ,-1 , 0
  4246.8     .05       0  4746.9    .075       0  4992.3      .1       0
  4995.8     .07       0  5004.2      .1       0  5251.3    .075       0
  5415.2     .05       0  5603.5    .075       0
Bank Sta=4995.8,5004.2
XS Rating Curve= 0 ,0
Exp/Cntr=0.3,0.1

Type RM Length L Ch R = 1 ,30432   ,393,393,393
BEGIN DESCRIPTION:
COTTONWOOD BR AT DENTON 52.0
END DESCRIPTION:
XS GIS Cut Line= 3
       2415805.7      7030309.35      2415990.59      7030279.04
      2416635.05      7030115.66
#Sta/Elev= 30
  4824.6  578.84  4847.3   580.2  4852.4  576.32  4898.9  574.32  4908.6  571.82
  4913.7   566.5  4919.1  548.22  4995.6  537.53  4996.9  537.03  5004.4  537.53
  5008.6  540.59    5012  540.59  5020.6  549.93  5027.1  552.61  5032.3  551.51
  5046.8  554.21  5061.9  556.49  5114.2   557.6  5123.8  575.63  5134.1  581.63
  5181.4  583.84  5206.3  578.77  5216.6  555.84  5365.8   557.9  5443.6  556.85
  5536.9  549.59    5537  549.59  5577.7  549.88  5641.8  560.34  5676.8  559.08
#Mann= 8 ,-1 , 0
  4824.6      .1       0  4995.6     .07       0  5004.4      .1       0
  5046.8    .075       0  5181.4     .05       0  5365.8    .075       0
  5536.9     .05       0    5537    .075       0
Bank Sta=4995.6,5004.4
XS Rating Curve= 0 ,0
Exp/Cntr=0.3,0.1

Type RM Length L Ch R = 1 ,30039   ,371,371,371
BEGIN DESCRIPTION:
COTTONWOOD BR AT DENTON 51.0
END DESCRIPTION:
XS GIS Cut Line= 3
      2415829.99      7030673.06      2416208.82      7030618.51
       2416629.5      7030264.42
#Sta/Elev= 30
  4748.4  581.92  4784.2  580.86  4797.9  578.54    4804  574.82  4848.4  561.62
  4886.1  562.71    4909  559.19  4949.9  558.04  4974.1  554.36  4989.9  550.26
  4995.6  545.42  4996.9  544.92  5004.4  545.42  5010.1  553.62  5015.3  557.27
  5039.5  563.74  5050.5  567.81  5090.9  568.39    5101  566.25  5111.1  548.26
  5171.5  548.93  5215.3   550.2  5250.4  548.67    5279   550.7  5385.7  550.29
  5428.6  547.13  5515.4  547.83  5562.7  545.42  5627.5  554.28    5681  554.87
#Mann= 9 ,-1 , 0
  4748.4    .075       0  4784.2     .05       0  4886.1    .075       0
  4974.1     .05       0  4995.6     .05       0  5004.4     .05       0
  5039.5    .075       0  5171.5     .05       0  5515.4    .075       0
Bank Sta=4995.6,5004.4
XS Rating Curve= 0 ,0
Exp/Cntr=0.3,0.1

Type RM Length L Ch R = 1 ,29668   ,483,483,483
BEGIN DESCRIPTION:
COTTONWOOD BR AT DENTON 50.0
END DESCRIPTION:
XS GIS Cut Line= 3
       2415811.8      7031003.46      2416045.15      7031064.07
      2417782.36      7029688.45
#Sta/Elev= 30
  4625.7  574.94  4628.5  574.95  4675.6  564.25  4736.5  575.08  4872.4   566.5
  4943.9  550.57  4967.9  552.22  4993.5   553.4  4995.6  540.94  4996.9  540.44
  5004.4  540.94    5008  553.25  5014.3  553.57  5057.6  546.44  5158.7  547.57
  5202.5  547.19  5369.4  544.25    5407  555.77  5442.3  556.21  5471.1  543.98
  5491.9  544.76  5512.7  556.88  5552.5  554.46  5570.5  543.74  5627.2  543.83
  5756.1  541.14    5885     549    6263  552.27  6879.9   553.9  7082.7  559.27
#Mann= 14 ,-1 , 0
  4625.7    .075       0  4628.5     .05       0  4967.9    .075       0
  4995.6     .07       0  5004.4    .075       0  5158.7     .05       0
  5202.5    .075       0  5369.4     .05       0  5552.5    .075       0
  5627.2     .05       0  5756.1     .12       0    5885     .05       0
    6263    .075       0  6879.9     .05       0
Bank Sta=4995.6,5004.4
XS Rating Curve= 0 ,0
Exp/Cntr=0.3,0.1

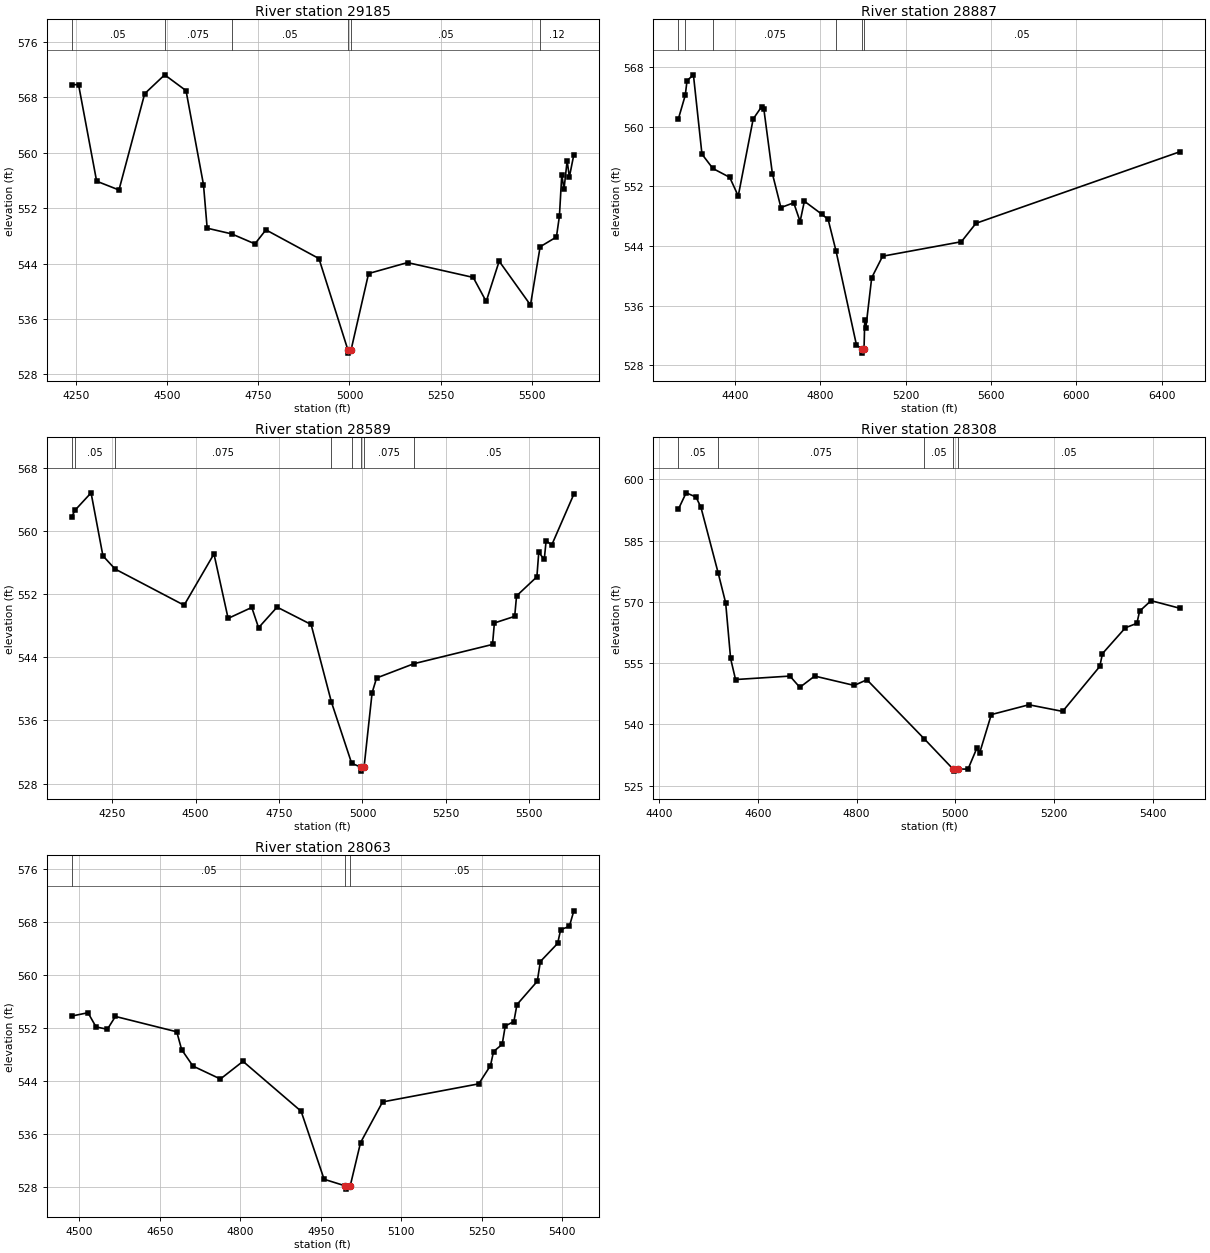
Type RM Length L Ch R = 1 ,29185   ,298,298,298
BEGIN DESCRIPTION:
COTTONWOOD BR AT DENTON 49.0
END DESCRIPTION:
XS GIS Cut Line= 3
       2415790.5      7031264.12       2416411.9      7031185.31
      2417021.14      7030745.81
#Sta/Elev= 30
  4238.1  569.79  4256.7  569.81  4306.3  555.88  4367.6  554.61  4438.2   568.5
    4493  571.22  4551.6  568.94  4599.5  555.38  4609.6   549.1  4676.7  548.28
  4740.6  546.84  4770.8  548.86  4916.3  544.72  4995.5  531.58  4996.8  531.08
  5004.6  531.58  5052.5  542.56  5159.3  544.14  5339.6     542  5375.2  538.53
  5410.8  544.34  5496.7  538.02  5523.2  546.42  5567.9  547.83  5576.1  550.84
  5582.6  556.83  5588.7  554.72  5597.3  558.83  5603.4  556.48  5615.7  559.72
#Mann= 6 ,-1 , 0
  4238.1     .05       0    4493    .075       0  4676.7     .05       0
  4995.5     .05       0  5004.6     .05       0  5523.2     .12       0
Bank Sta=4995.5,5004.6
XS Rating Curve= 0 ,0
Exp/Cntr=0.3,0.1

Type RM Length L Ch R = 1 ,28887   ,298,298,298
BEGIN DESCRIPTION:
COTTONWOOD BR AT DENTON 48.4
END DESCRIPTION:
XS GIS Cut Line= 4
      2415717.76      7031424.75      2416354.31      7031433.85
      2417027.19      7031294.42      2418055.87      7031246.01
#Sta/Elev= 30
  4133.9  560.96  4166.9   564.2  4175.1  566.15  4205.1  566.93  4245.1   556.3
  4296.2  554.38  4375.2  553.19  4415.2  550.69  4485.2  561.01  4525.2  562.68
  4535.2  562.35  4575.2  553.69  4615.2  549.14  4675.2  549.78  4705.2  547.27
  4725.2  549.99  4805.9  548.27  4836.6  547.55  4873.8  543.29  4969.3  530.73
  4995.3  530.13  4996.6  529.63  5004.8  530.13  5008.2  534.01  5013.3  533.01
  5040.8  539.73  5091.9  542.62  5461.1  544.56  5529.6  547.03  6487.5  556.64
#Mann= 6 ,-1 , 0
  4133.9    .075       0  4166.9     .05       0  4296.2    .075       0
  4873.8     .05       0  4995.3    .033       0  5004.8     .05       0
Bank Sta=4995.3,5004.8
XS Rating Curve= 0 ,0
Exp/Cntr=0.3,0.1

Type RM Length L Ch R = 1 ,28589   ,281,281,281
BEGIN DESCRIPTION:
COTTONWOOD BR AT DENTON 48.0
END DESCRIPTION:
XS GIS Cut Line= 4
      2415726.88      7031515.68       2416411.9      7031627.83
       2416793.8      7031758.16      2417154.71      7031944.63
#Sta/Elev= 30
  4129.3  561.83  4139.4  562.65  4187.1  564.84  4222.6  556.86  4258.9  555.19
  4465.8   550.6  4555.2   557.1  4597.6  548.93  4668.5  550.32  4688.8  547.75
  4744.3  550.36  4846.2  548.16  4906.9  538.35  4967.6  530.58  4995.2  530.08
  4996.6  529.58  5004.8  530.08  5028.9  539.51  5042.3  541.38    5154  543.19
  5389.6  545.63  5395.2  548.35    5456  549.19  5461.6  551.78  5522.5   554.2
  5528.1   557.3  5544.6   556.4  5550.2  558.79  5566.8  558.21  5633.2  564.67
#Mann= 8 ,-1 , 0
  4129.3    .075       0  4139.4     .05       0  4258.9    .075       0
  4906.9     .05       0  4967.6    .075       0  4995.2     .07       0
  5004.8    .075       0    5154     .05       0
Bank Sta=4995.2,5004.8
XS Rating Curve= 0 ,0
Exp/Cntr=0.3,0.1

Type RM Length L Ch R = 1 ,28308   ,245,245,245
BEGIN DESCRIPTION:
COTTONWOOD BR AT DENTON 47.2
END DESCRIPTION:
XS GIS Cut Line= 4
      2416033.06      7031876.37      2416405.84      7031891.53
      2416772.59      7032049.14      2416995.46      7031949.75
#Sta/Elev= 30
  4438.9   592.6  4454.9  596.68  4474.9  595.65  4484.9  593.11  4519.8  577.02
  4534.9  569.73  4544.9  556.11  4554.9  550.95    4665   551.8    4685  549.04
  4715.1   551.8  4795.1  549.51  4820.8   550.9    4937  536.42  4995.2  529.02
  4996.6  528.52  5004.8  529.02  5025.5  529.02  5043.6  534.21  5049.1     533
  5072.6  542.37  5148.7  544.77    5217  543.15  5292.2  554.16  5297.6   557.3
  5344.1  563.64  5367.3  564.71  5372.8   567.7    5396  570.27  5455.2  568.38
#Mann= 5 ,-1 , 0
  4438.9     .05       0  4519.8    .075       0    4937     .05       0
  4995.2    .033       0  5004.8     .05       0
Bank Sta=4995.2,5004.8
XS Rating Curve= 0 ,0
Exp/Cntr=0.3,0.1

Type RM Length L Ch R = 1 ,28063   ,273,273,273
BEGIN DESCRIPTION:
COTTONWOOD BR AT DENTON 47.0
END DESCRIPTION:
XS GIS Cut Line= 3
      2416227.01      7032470.44      2416675.59      7032173.41
      2417024.11      7031982.48
#Sta/Elev= 30
    4486  553.83  4516.2  554.33  4531.2  552.19  4552.3  551.83  4567.3  553.77
  4681.6  551.45  4690.7  548.76  4711.7  546.28  4762.9  544.32    4805  546.99
  4913.3  539.45  4956.1  529.18  4995.2  528.19  4996.6  527.69  5004.8  528.19
    5024  534.71  5065.1  540.86  5244.2  543.59  5266.1  546.35  5271.8  548.47
  5287.9  549.55  5293.6  552.33  5309.7     553  5315.4  555.56  5353.3  559.08
    5359  562.06  5391.2   564.8  5396.9  566.89    5413  567.36  5421.4  569.72
#Mann= 3 ,-1 , 0
    4486     .05       0  4995.2    .033       0  5004.8     .05       0
Bank Sta=4995.2,5004.8
XS Rating Curve= 0 ,0
Exp/Cntr=0.3,0.1