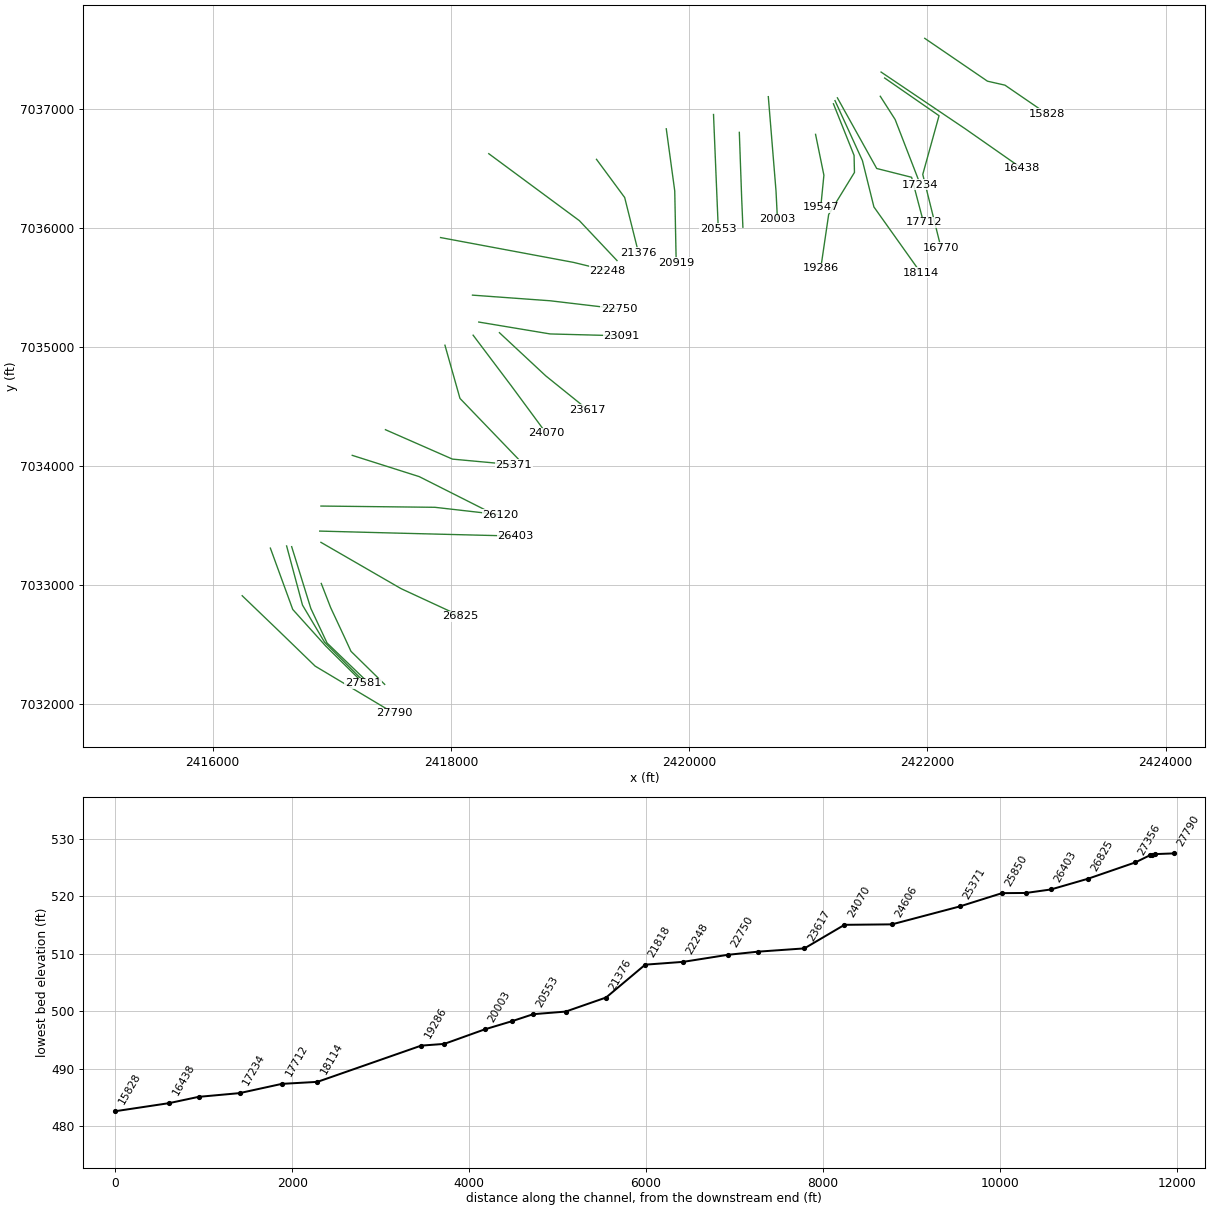
HEC-RAS study COTTONWOOD BR AT DENTON.prj: COTTONWOOD BR AT DENTON Base Level Engineering

--- COTTONWOOD BR AT DENTON.g01 (geometry) --- (continued)

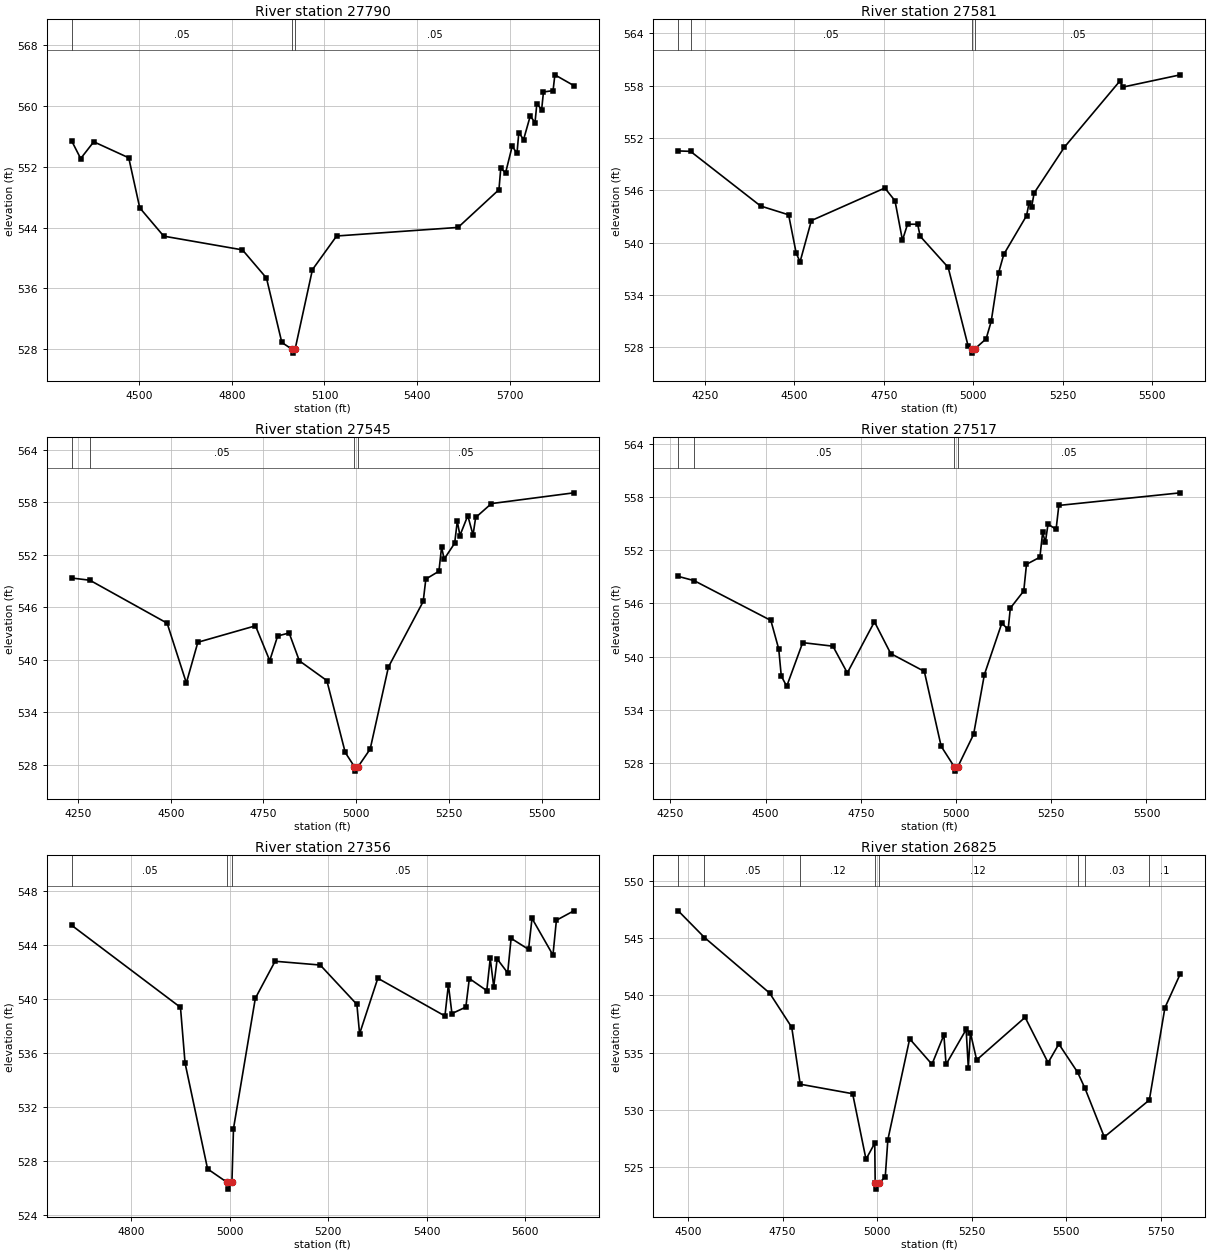
Type RM Length L Ch R = 1 ,27790   ,209,209,209
BEGIN DESCRIPTION:
COTTONWOOD BR AT DENTON 46.4
END DESCRIPTION:
XS GIS Cut Line= 4
       2416248.2      7032909.96      2416557.39       7032612.9
      2416860.48      7032318.89      2417524.09      7031921.94
#Sta/Elev= 30
  4282.4   555.4  4311.2   553.1  4353.5  555.31  4466.7   553.2  4502.3  546.61
  4579.9  542.88  4834.6  541.07  4912.3  537.36  4961.9  528.88  4995.2  527.97
  4996.6  527.47  5004.8  527.97    5061  538.47  5139.3   542.9  5532.2  544.03
  5664.4     549  5670.3  551.84  5685.8  551.21  5707.2  554.72  5722.8   553.8
  5728.6  556.51  5744.2  555.61  5765.6   558.7  5781.1  557.85    5787  560.32
  5802.5  559.54  5808.4  561.87  5839.5  562.05  5845.3  564.13  5906.7  562.71
#Mann= 3 ,-1 , 0
  4282.4     .05       0  4995.2    .033       0  5004.8     .05       0
Bank Sta=4995.2,5004.8
XS Rating Curve= 0 ,0
Exp/Cntr=0.3,0.1

Type RM Length L Ch R = 1 ,27581   ,36,36,36
BEGIN DESCRIPTION:
COTTONWOOD BR AT DENTON 46.2
END DESCRIPTION:
XS GIS Cut Line= 4
      2416484.63      7033310.05      2416672.56      7032794.76
      2416948.38      7032488.63       2417263.6      7032176.44
#Sta/Elev= 30
  4174.9  550.52  4209.3  550.47  4405.2  544.21  4483.6   543.2  4504.9  538.79
  4515.6  537.81  4547.3  542.54  4752.7  546.27  4781.1  544.81    4802  540.29
  4816.2  542.12  4844.6  542.12  4851.4  540.75  4929.8  537.18  4985.9  528.13
  4995.2  527.85  4996.6  527.35  5004.8  527.85    5036  528.99  5050.2  530.99
  5071.1  536.58  5085.3  538.66  5149.1   543.1  5156.1  544.57  5163.2   544.1
  5170.3   545.7  5255.1  550.96  5410.7  558.56  5417.8  557.83  5579.1  559.24
#Mann= 4 ,-1 , 0
  4174.9    .075       0  4209.3     .05       0  4995.2    .033       0
  5004.8     .05       0
Bank Sta=4995.2,5004.8
XS Rating Curve= 0 ,0
Exp/Cntr=0.3,0.1

Type RM Length L Ch R = 1 ,27545   ,28,28,28
BEGIN DESCRIPTION:
COTTONWOOD BR AT DENTON 46.0
END DESCRIPTION:
XS GIS Cut Line= 4
      2416621.03      7033328.24       2416754.4      7032831.13
        2416939.      7032520.57      2417275.71      7032182.52
#Sta/Elev= 30
  4233.3  549.33  4282.1  549.08  4490.3  544.17  4542.1  537.34  4573.1  541.99
  4728.4  543.87  4766.8  539.89  4788.2  542.71  4819.1  543.05  4846.6  539.87
  4920.7  537.61  4970.3  529.39  4995.2  527.76  4996.6  527.26  5004.8  527.76
  5037.5  529.78  5086.7  539.16  5180.4  546.65  5187.5  549.21  5222.8  550.11
  5229.9  552.86    5237   551.5  5265.2  553.31  5272.3  555.83  5279.4  554.19
  5300.6  556.46  5314.7  554.25  5321.8  556.25  5364.2  557.84  5586.4  559.07
#Mann= 4 ,-1 , 0
  4233.3    .075       0  4282.1     .05       0  4995.2    .033       0
  5004.8     .05       0
Bank Sta=4995.2,5004.8
XS Rating Curve= 0 ,0
Exp/Cntr=0.3,0.1

Type RM Length L Ch R = 1 ,27517   ,161,161,161
BEGIN DESCRIPTION:
COTTONWOOD BR AT DENTON 45.8
END DESCRIPTION:
XS GIS Cut Line= 4
      2416663.48      7033322.12      2416824.11      7032803.85
      2416960.51      7032512.88      2417287.86      7032197.65
#Sta/Elev= 30
  4270.5  549.04  4312.3  548.56  4513.7  544.08  4534.4  540.86  4541.1  537.81
  4555.4  536.67  4597.3  541.58  4676.7  541.18  4714.5  538.17  4785.7  543.93
  4828.4  540.35  4916.7  538.34  4960.9  529.91  4995.2  527.61  4996.6  527.11
  5004.8  527.61  5046.1  531.25  5074.4  537.98  5120.1  543.76  5136.9  543.08
  5142.5  545.46  5177.8   547.4    5185   550.4  5220.2   551.2  5227.4     554
  5234.4  552.86  5241.6  554.93  5262.7  554.33  5269.9  557.03  5588.9  558.45
#Mann= 4 ,-1 , 0
  4270.5    .075       0  4312.3     .05       0  4995.2    .033       0
  5004.8     .05       0
Bank Sta=4995.2,5004.8
XS Rating Curve= 0 ,0
Exp/Cntr=0.3,0.1

Type RM Length L Ch R = 1 ,27356   ,531,531,531
BEGIN DESCRIPTION:
COTTONWOOD BR AT DENTON 45.0
END DESCRIPTION:
XS GIS Cut Line= 5
      2416911.99      7033013.03      2416990.82      7032809.91
      2417099.93      7032576.53      2417161.15      7032443.44
      2417444.37      7032165.38
#Sta/Elev= 30
  4679.9  545.46  4900.5  539.38  4909.8  535.25  4955.5   527.4  4995.2   526.4
  4996.5   525.9  5004.9   526.4  5008.1  530.39  5052.4  540.05  5092.5   542.8
  5184.1  542.52  5258.5   539.6    5264  537.42    5301  541.54  5437.2  538.74
  5444.2  541.06  5451.4  538.92  5479.6   539.4  5486.7  541.52  5522.1  540.62
  5529.1  543.01  5536.2  540.92  5543.2  542.97  5564.5  541.94  5571.5   544.5
  5606.9  543.68  5613.9  545.98  5656.4  543.26  5663.4  545.84  5698.8  546.54
#Mann= 3 ,-1 , 0
  4679.9     .05       0  4995.2    .033       0  5004.9     .05       0
Bank Sta=4995.2,5004.9
XS Rating Curve= 0 ,0
Exp/Cntr=0.3,0.1

Type RM Length L Ch R = 1 ,26825   ,422,422,422
BEGIN DESCRIPTION:
COTTONWOOD BR AT DENTON 44.0
END DESCRIPTION:
XS GIS Cut Line= 3
      2416909.15      7033358.44      2417582.02      7032969.43
      2418081.43      7032738.13
#Sta/Elev= 30
  4474.3  547.38  4543.7  545.05  4715.9   540.2  4774.4  537.21  4796.8  532.24
  4935.5  531.41  4970.8  525.69  4993.9  527.09  4995.1  523.58  4996.4  523.08
    5005  523.58  5021.7  524.16  5028.6   527.4  5086.3   536.2  5145.2  533.98
  5176.7  536.54  5182.5  533.97  5235.6  537.02  5241.3  533.69  5246.9  536.72
  5263.4  534.36  5391.5  538.08  5452.3  534.12  5480.7  535.75  5530.2  533.29
    5550  531.87  5600.9  527.63    5720  530.86  5761.2  538.92  5801.9  541.88
#Mann= 8 ,-1 , 0
  4474.3    .075       0  4543.7     .05       0  4796.8     .12       0
  4995.1     .07       0    5005     .12       0  5530.2     .05       0
    5550     .03       0    5720      .1       0
Bank Sta=4995.1,5005
XS Rating Curve= 0 ,0
Exp/Cntr=0.3,0.1

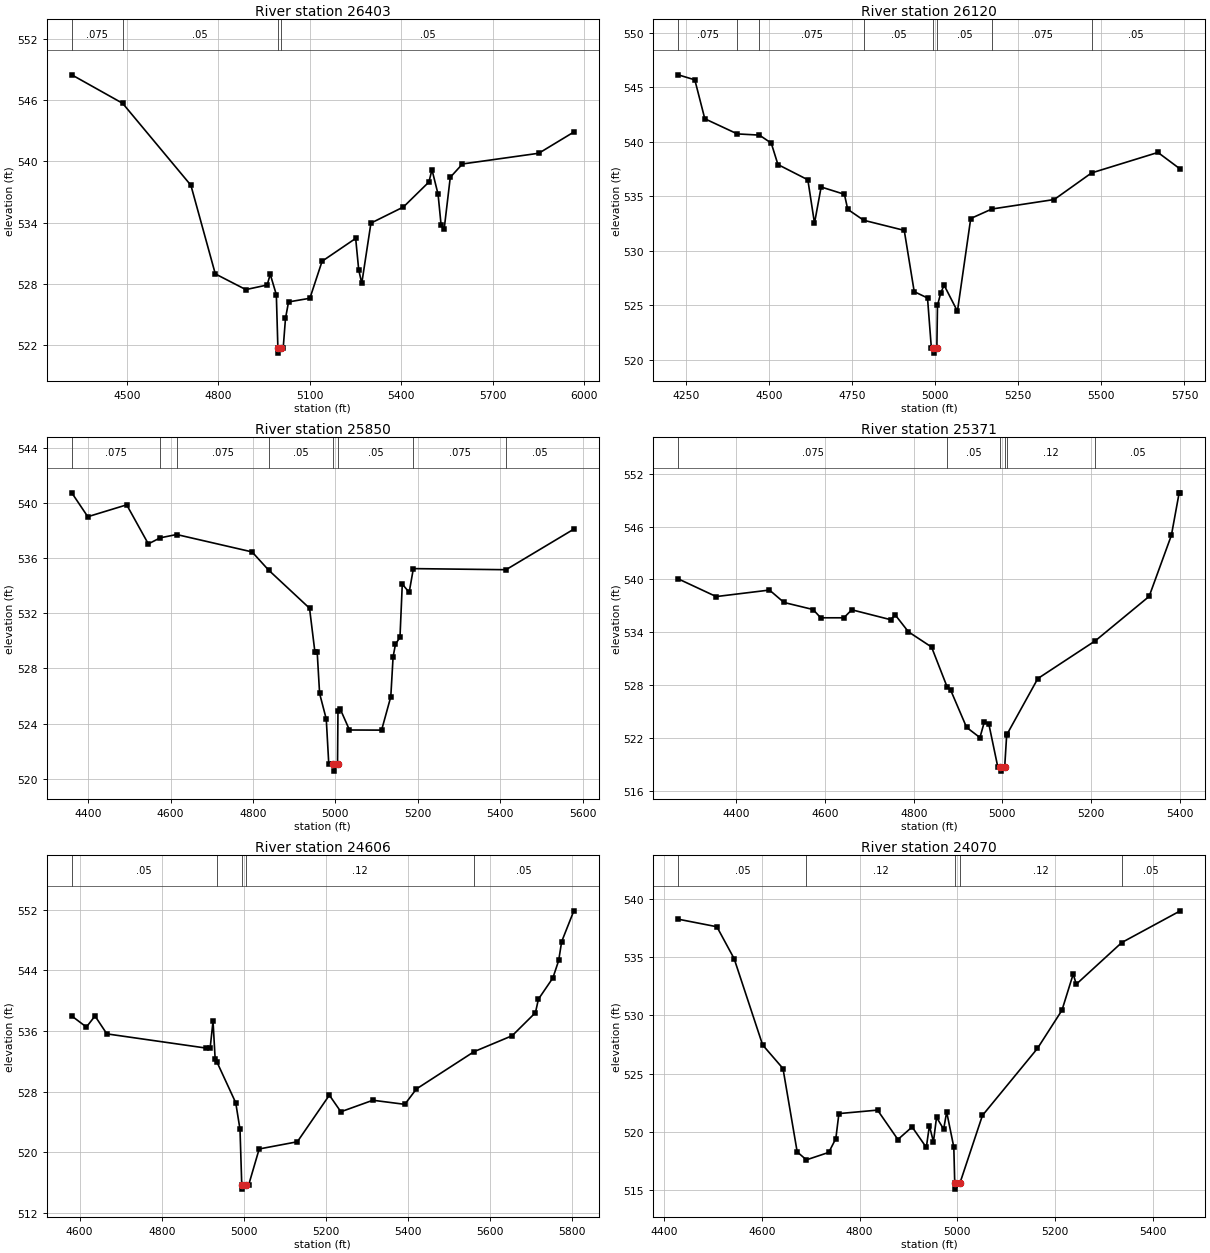
Type RM Length L Ch R = 1 ,26403   ,283,283,283
BEGIN DESCRIPTION:
COTTONWOOD BR AT DENTON 43.0
END DESCRIPTION:
XS GIS Cut Line= 3
      2416898.64      7033453.06      2417497.91      7033437.29
        2418544.        7033411.
#Sta/Elev= 30
  4319.3  548.49  4485.9   545.7  4709.8  537.66  4789.8  528.97  4889.9  527.43
  4959.9  527.88  4969.9  528.94  4989.9  526.93    4995   521.7  4996.4   521.2
    5005   521.7  5012.4   521.7  5019.9   524.6  5029.9  526.22  5099.9  526.58
  5139.9  530.21    5250  532.45    5260  529.35    5270  528.05    5300  533.95
  5406.5  535.53  5490.1  537.98  5500.1  539.19  5520.1  536.78  5530.1  533.74
  5540.1  533.37  5560.1  538.44  5600.1  539.75  5850.2   540.8  5965.2  542.88
#Mann= 4 ,-1 , 0
  4319.3    .075       0  4485.9     .05       0    4995    .033       0
    5005     .05       0
Bank Sta=4995,5005
XS Rating Curve= 0 ,0
Exp/Cntr=0.3,0.1

Type RM Length L Ch R = 1 ,26120   ,270,270,270
BEGIN DESCRIPTION:
COTTONWOOD BR AT DENTON 42.8
END DESCRIPTION:
XS GIS Cut Line= 3
      2416909.14      7033663.33      2417865.88      7033652.81
       2418415.9      7033589.96
#Sta/Elev= 30
  4227.1  546.12    4277  545.66    4307  542.09  4404.8   540.7  4471.4  540.59
    4507  539.85    4527  537.89    4617  536.49    4637  532.51    4657  535.83
    4727  535.16    4737  533.78  4784.9  532.78    4907  531.85    4937  526.23
    4977  525.65  4988.5  521.09    4995  521.09  4996.4  520.59  5005.1  521.09
    5007  524.97    5017  526.13    5027  526.82    5067  524.43    5107  532.94
  5170.6  533.81  5358.1  534.68  5470.4  537.12  5670.2     539  5737.5  537.47
#Mann= 8 ,-1 , 0
  4227.1    .075       0  4404.8      .1       0  4471.4    .075       0
  4784.9     .05       0    4995     .05       0  5005.1     .05       0
  5170.6    .075       0  5470.4     .05       0
Bank Sta=4995,5005.1
XS Rating Curve= 0 ,0
Exp/Cntr=0.3,0.1

Type RM Length L Ch R = 1 ,25850   ,479,479,479
BEGIN DESCRIPTION:
COTTONWOOD BR AT DENTON 42.0
END DESCRIPTION:
XS GIS Cut Line= 3
      2417171.96      7034089.14      2417734.46       7033910.4
      2418295.45      7033627.28
#Sta/Elev= 30
  4360.1  540.72    4399  538.99  4493.4  539.85  4545.9  537.02  4574.8  537.46
  4614.6   537.7  4797.7  536.44  4837.6  535.13  4937.2  532.36  4950.1  529.22
  4955.7  529.22  4961.6  526.19  4977.8  524.33  4983.9  521.06    4995  521.06
  4996.4  520.56  5005.1  521.06  5006.2  524.89  5011.8  525.05  5034.1  523.54
  5112.1  523.53  5134.4  525.95    5140  528.84  5145.8  529.76  5156.7  530.25
  5162.3  534.11    5179  533.51  5189.2  535.23  5414.1  535.15  5578.7  538.09
#Mann= 8 ,-1 , 0
  4360.1    .075       0  4574.8     .05       0  4614.6    .075       0
  4837.6     .05       0    4995    .033       0  5005.1     .05       0
  5189.2    .075       0  5414.1     .05       0
Bank Sta=4995,5005.1
XS Rating Curve= 0 ,0
Exp/Cntr=0.3,0.1

Type RM Length L Ch R = 1 ,25371   ,765,765,765
BEGIN DESCRIPTION:
COTTONWOOD BR AT DENTON 41.0
END DESCRIPTION:
XS GIS Cut Line= 3
       2417450.6      7034304.65      2418013.07      7034057.59
      2418529.04        7034010.
#Sta/Elev= 30
  4268.8  540.07  4354.4  538.06  4474.6   538.8  4507.3  537.39  4572.9  536.59
  4590.2  535.65  4642.4  535.65  4660.2  536.56  4747.6  535.44  4758.5  535.96
    4788  534.06  4840.2  532.33    4875  527.84  4883.1  527.46  4919.2  523.21
  4949.3  522.05  4959.4  523.85  4969.4  523.59  4989.5  518.74  4994.8  518.74
  4996.3  518.24  5005.2  518.74  5009.6  522.32  5010.5  522.43  5079.9  528.75
  5209.9  533.05    5331  538.08  5381.2  545.02  5398.7  549.84  5401.3  549.84
#Mann= 6 ,-1 , 0
  4268.8    .075       0    4875     .05       0  4994.8    .033       0
  5005.2     .05       0  5010.5     .12       0  5209.9     .05       0
Bank Sta=4994.8,5005.2
XS Rating Curve= 0 ,0
Exp/Cntr=0.3,0.1

Type RM Length L Ch R = 1 ,24606   ,536,536,536
BEGIN DESCRIPTION:
COTTONWOOD BR AT DENTON 40.0
END DESCRIPTION:
XS GIS Cut Line= 3
        2417950.      7035014.29      2418076.15      7034567.49
      2418601.83      7034020.79
#Sta/Elev= 30
  4580.8  537.98  4616.4  536.52  4637.4  537.98  4666.2  535.62  4907.4  533.75
  4917.8  533.75  4924.8   537.3    4930  532.29  4933.8  531.97  4980.1  526.53
  4990.5  523.02  4994.8  515.63  4996.3  515.13  5005.2  515.63  5011.3  515.63
  5037.2  520.43  5130.1  521.38  5208.1  527.53  5236.1  525.34  5314.1  526.86
  5391.8  526.32  5420.1  528.35  5560.4  533.27  5653.4  535.38    5710  538.42
  5717.2   540.2  5752.5  543.01  5766.6  545.31  5773.8  547.79  5803.5  551.86
#Mann= 5 ,-1 , 0
  4580.8     .05       0  4933.8     .12       0  4994.8     .07       0
  5005.2     .12       0  5560.4     .05       0
Bank Sta=4994.8,5005.2
XS Rating Curve= 0 ,0
Exp/Cntr=0.3,0.1

Type RM Length L Ch R = 1 ,24070   ,453,453,453
BEGIN DESCRIPTION:
COTTONWOOD BR AT DENTON 39.0
END DESCRIPTION:
XS GIS Cut Line= 3
      2418186.55      7035098.42      2418507.21      7034672.63
      2418800.88      7034274.07
#Sta/Elev= 30
  4428.6  538.28  4507.7  537.63  4543.1  534.88  4601.4  527.46  4643.1  525.43
  4672.2  518.25  4691.1  517.57  4736.8  518.21  4751.3   519.4  4757.6  521.55
  4836.7  521.85  4878.4  519.32  4907.5   520.4  4936.6  518.64  4942.9   520.5
  4951.2  519.12  4957.5  521.23  4972.1  520.21  4978.3  521.69  4992.9  518.66
  4994.8  515.55  4996.2  515.05  5005.3  515.55  5051.5  521.39  5164.2  527.16
  5214.3  530.44  5237.4  533.56  5243.6  532.68  5336.8  536.27  5456.7     539
#Mann= 5 ,-1 , 0
  4428.6     .05       0  4691.1     .12       0  4994.8     .07       0
  5005.3     .12       0  5336.8     .05       0
Bank Sta=4994.8,5005.3
XS Rating Curve= 0 ,0
Exp/Cntr=0.3,0.1

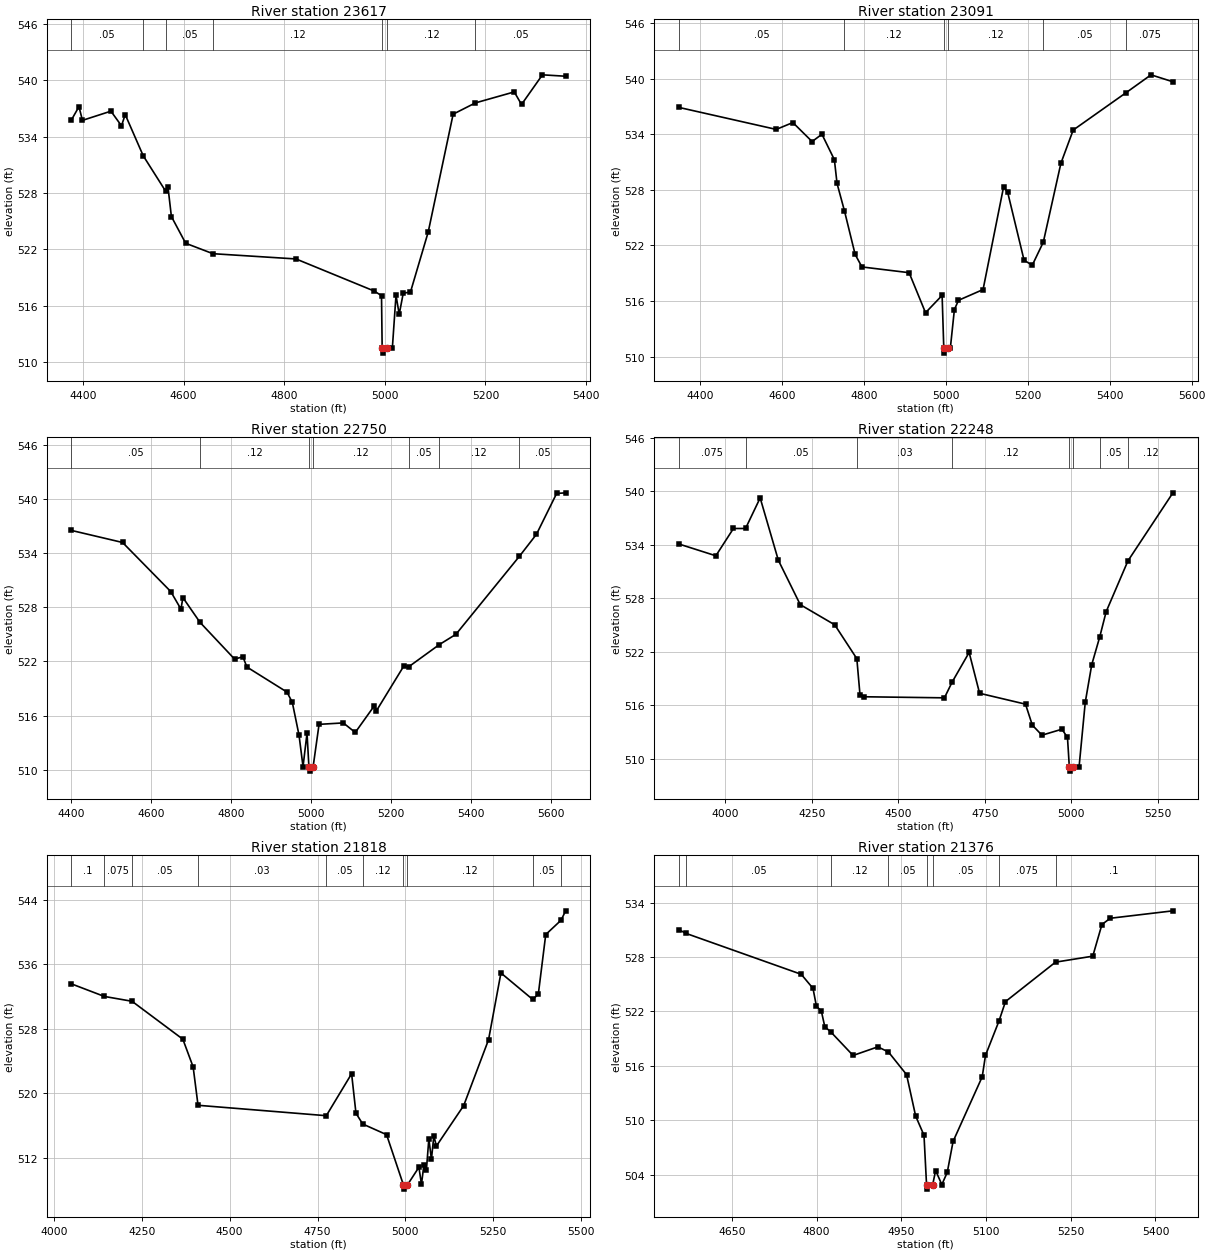
Type RM Length L Ch R = 1 ,23617   ,526,526,526
BEGIN DESCRIPTION:
COTTONWOOD BR AT DENTON 38.0
END DESCRIPTION:
XS GIS Cut Line= 3
      2418407.35      7035119.43      2418796.33      7034756.74
      2419147.21      7034473.94
#Sta/Elev= 30
    4377  535.78  4392.1   537.2    4399  535.74  4455.6  536.72  4476.6  535.16
    4484  536.36  4519.8  531.97  4564.6  528.18    4569  528.65  4575.8   525.5
  4604.2  522.65  4658.4  521.54  4823.5  520.98  4979.1  517.56  4993.5  517.07
  4994.8  511.45  4996.2  510.95  5005.3  511.45    5015  511.45  5022.3  517.11
  5028.7  515.09  5036.7  517.33  5051.1  517.46  5086.3  523.84  5135.9   536.4
  5180.1   537.6  5257.4  538.77  5271.8  537.43  5313.4  540.59  5359.5  540.44
#Mann= 7 ,-1 , 0
    4377     .05       0  4519.8     .12       0  4564.6     .05       0
  4658.4     .12       0  4994.8     .07       0  5005.3     .12       0
  5180.1     .05       0
Bank Sta=4994.8,5005.3
XS Rating Curve= 0 ,0
Exp/Cntr=0.3,0.1

Type RM Length L Ch R = 1 ,23091   ,341,341,341
BEGIN DESCRIPTION:
COTTONWOOD BR AT DENTON 37.0
END DESCRIPTION:
XS GIS Cut Line= 3
      2418233.89      7035208.81      2418833.13      7035108.94
      2419432.42      7035093.17
#Sta/Elev= 30
  4347.2   536.9  4585.5  534.52  4626.1  535.26  4673.1  533.21  4697.1     534
  4727.5  531.25    4734  528.69  4752.1  525.73  4778.2  521.03  4794.8  519.68
    4910  519.06  4950.1  514.74  4990.6  516.61  4994.7  510.88  4996.2  510.38
  5005.3  510.88  5010.6  510.88  5020.6  515.08  5030.6  516.08  5090.6  517.24
  5140.6  528.29  5150.6  527.75  5190.7  520.41  5210.7  519.86  5237.7  522.35
  5280.7  530.87  5310.7  534.45  5440.4   538.5  5500.8  540.41  5554.2  539.66
#Mann= 6 ,-1 , 0
  4347.2     .05       0  4752.1     .12       0  4994.7     .07       0
  5005.3     .12       0  5237.7     .05       0  5440.4    .075       0
Bank Sta=4994.7,5005.3
XS Rating Curve= 0 ,0
Exp/Cntr=0.3,0.1

Type RM Length L Ch R = 1 ,22750   ,502,502,502
BEGIN DESCRIPTION:
COTTONWOOD BR AT DENTON 36.0
END DESCRIPTION:
XS GIS Cut Line= 3
       2418181.3      7035434.86      2418833.13      7035387.55
      2419411.36      7035319.21
#Sta/Elev= 30
  4400.8  536.54  4528.8   535.2  4649.2  529.76  4674.7  527.81  4679.7  529.08
  4722.4  526.34  4808.9  522.26  4829.6  522.52  4839.7  521.38  4939.9   518.6
  4953.2  517.46    4970  513.82    4980  510.33    4990  514.04  4994.7  510.33
  4996.2  509.83  5005.3  510.33  5020.1  515.02  5080.7  515.18  5110.6  514.12
  5158.6   517.1  5163.6  516.53  5231.4  521.45    5244   521.4  5320.8  523.87
  5362.3  525.01  5520.9  533.66  5563.7  536.11  5614.1  540.64  5636.6  540.71
#Mann= 7 ,-1 , 0
  4400.8     .05       0  4722.4     .12       0  4994.7     .07       0
  5005.3     .12       0    5244     .05       0  5320.8     .12       0
  5520.9     .05       0
Bank Sta=4994.7,5005.3
XS Rating Curve= 0 ,0
Exp/Cntr=0.3,0.1

Type RM Length L Ch R = 1 ,22248   ,430,430,430
BEGIN DESCRIPTION:
COTTONWOOD BR AT DENTON 35.0
END DESCRIPTION:
XS GIS Cut Line= 3
      2417913.19      7035918.48        2419029.        7035710.
       2419315.4       7035640.2
#Sta/Elev= 30
  3864.5  534.09  3972.1  532.76    4023  535.82    4058  535.82  4100.3  539.25
  4152.9  532.26  4216.3  527.28    4316  525.02    4380  521.22  4389.2  517.13
  4399.4  516.95  4633.4  516.83  4655.9  518.61  4704.9  521.92  4735.1  517.34
    4868  516.12  4887.7  513.77  4915.5  512.64  4973.3  513.31  4989.4  512.39
  4994.7  509.11  4996.2  508.61  5005.3  509.11    5023  509.11  5040.8  516.32
  5059.6  520.55  5082.8  523.67  5101.3  526.49  5164.2  532.18  5294.4  539.82
#Mann= 8 ,-1 , 0
  3864.5    .075       0    4058     .05       0    4380     .03       0
  4655.9     .12       0  4994.7     .07       0  5005.3     .12       0
  5082.8     .05       0  5164.2     .12       0
Bank Sta=4994.7,5005.3
XS Rating Curve= 0 ,0
Exp/Cntr=0.3,0.1

Type RM Length L Ch R = 1 ,21818   ,442,442,442
BEGIN DESCRIPTION:
COTTONWOOD BR AT DENTON 34.0
END DESCRIPTION:
XS GIS Cut Line= 3
      2418317.94      7036622.91        2419079.        7036060.
      2419394.31      7035725.36
#Sta/Elev= 30
  4049.6  533.56  4143.4     532  4222.2   531.4  4366.8   526.7  4396.1  523.26
    4410  518.51    4775  517.22    4847  522.42  4859.4  517.53  4878.6  516.19
  4946.5  514.87  4994.6  508.62  4996.1  508.12  5005.5  508.62  5038.5  510.83
  5045.8  508.72  5052.6  511.08  5059.9  510.53  5066.8  514.36  5074.1  511.81
    5081  514.71  5088.3  513.46  5165.9  518.47  5236.7  526.64  5271.9  534.91
  5362.3  531.63  5378.3  532.28  5399.4  539.67  5443.1  541.45    5456  542.61
#Mann= 10 ,-1 , 0
  4049.6      .1       0  4143.4    .075       0  4222.2     .05       0
    4410     .03       0    4775     .05       0  4878.6     .12       0
  4994.6     .07       0  5005.5     .12       0  5362.3     .05       0
  5443.1      .1       0
Bank Sta=4994.6,5005.5
XS Rating Curve= 0 ,0
Exp/Cntr=0.3,0.1

Type RM Length L Ch R = 1 ,21376   ,457,457,457
BEGIN DESCRIPTION:
COTTONWOOD BR AT DENTON 33.0
END DESCRIPTION:
XS GIS Cut Line= 3
      2419222.12       7036575.6      2419458.69      7036254.92
      2419574.33      7035792.35
#Sta/Elev= 30
  4555.6  531.03  4568.7  530.61  4772.7   526.1  4793.5  524.55  4799.7  522.56
  4808.2  522.07  4814.4  520.33  4825.6  519.71  4864.5  517.15  4908.4   518.1
  4927.2  517.53  4959.2  515.04  4975.3  510.47  4990.1  508.35  4994.6  502.91
  4996.1  502.41  5005.5  502.91  5010.7  504.46  5021.7  502.91  5031.3  504.26
  5041.6  507.67  5093.2   514.8    5099  517.16  5122.8  520.93  5134.4  523.09
    5223  527.44    5289   528.1  5305.2  531.59  5319.9  532.28  5430.9   533.1
#Mann= 8 ,-1 , 0
  4555.6    .075       0  4568.7     .05       0  4825.6     .12       0
  4927.2     .05       0  4994.6    .033       0  5005.5     .05       0
  5122.8    .075       0    5223      .1       0
Bank Sta=4994.6,5005.5
XS Rating Curve= 0 ,0
Exp/Cntr=0.3,0.1

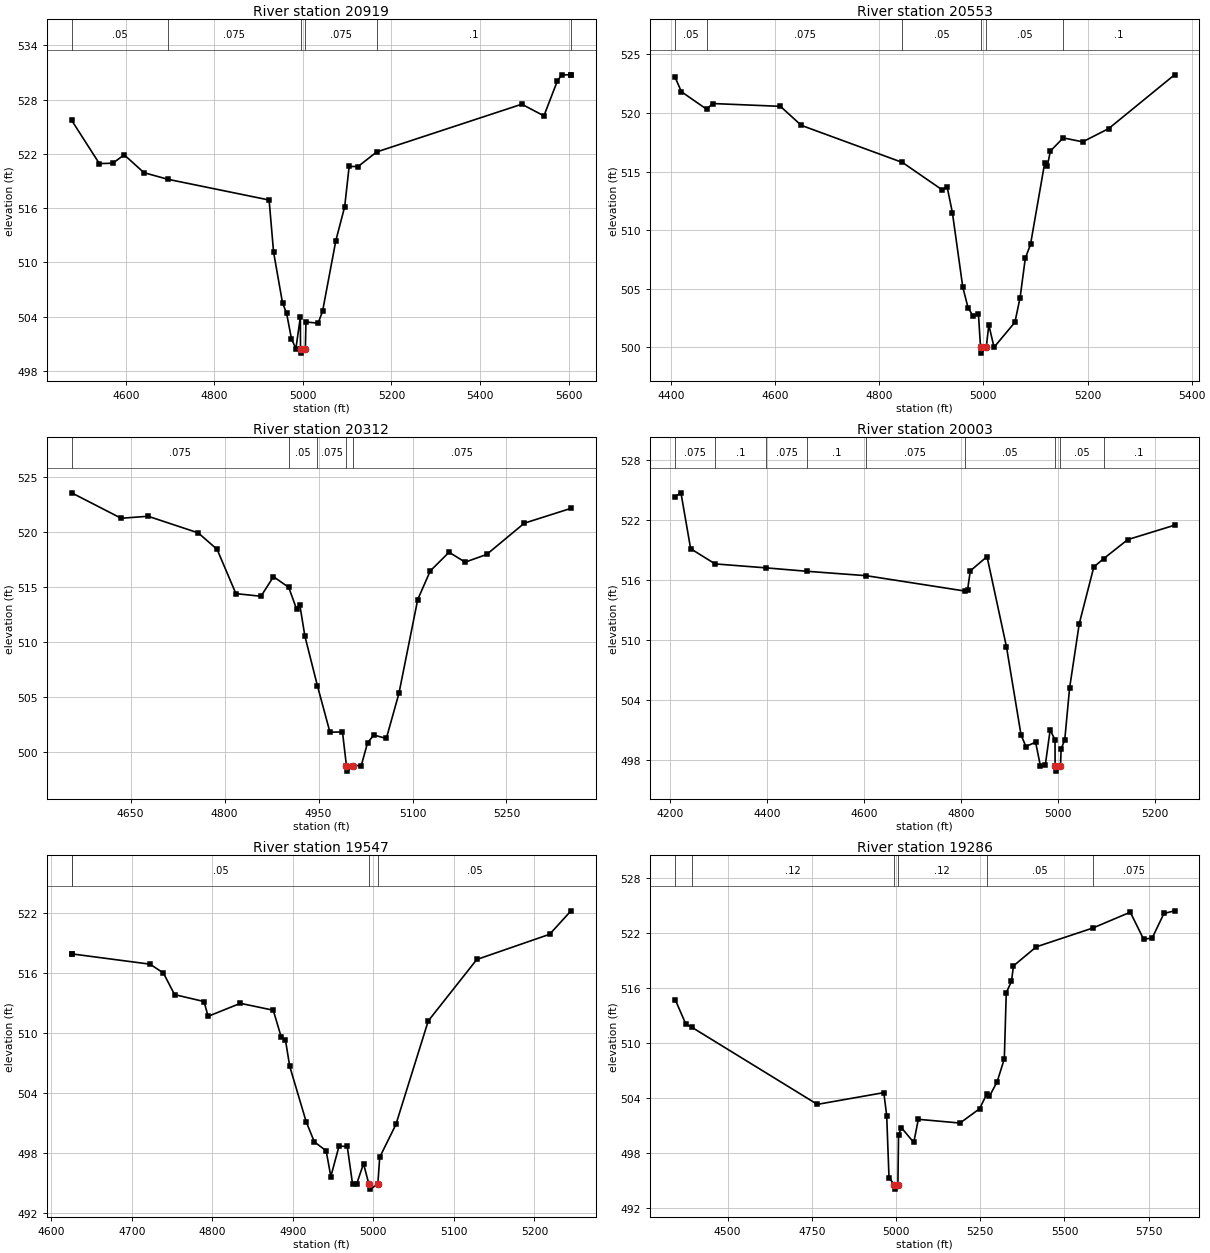
Type RM Length L Ch R = 1 ,20919   ,366,366,366
BEGIN DESCRIPTION:
COTTONWOOD BR AT DENTON 32.0
END DESCRIPTION:
XS GIS Cut Line= 3
      2419807.89      7036832.01        2419879.        7036310.
      2419891.21      7035708.85
#Sta/Elev= 30
  4477.5  525.72  4540.1  520.93  4570.4  520.97  4596.2   521.9    4641  519.92
  4695.2  519.19  4923.6   516.9  4933.7  511.13  4953.9  505.51  4963.1  504.37
  4974.1  501.54  4984.1  500.46  4994.2  503.96  4994.5  500.46    4996  499.96
  5005.5  500.46  5006.8   503.4  5034.3  503.28  5044.3  504.58  5074.3   512.4
  5094.3  516.16  5104.4  520.62  5124.4   520.6  5166.7  522.22  5494.4   527.5
  5544.4  526.21  5574.4  530.03  5584.5  530.75  5604.8  530.75  5605.6  530.75
#Mann= 6 ,-1 , 0
  4477.5     .05       0  4695.2    .075       0  4994.5     .07       0
  5005.5    .075       0  5166.7      .1       0  5604.8    .075       0
Bank Sta=4994.5,5005.5
XS Rating Curve= 0 ,0
Exp/Cntr=0.3,0.1

Type RM Length L Ch R = 1 ,20553   ,241,241,241
BEGIN DESCRIPTION:
COTTONWOOD BR AT DENTON 31.2
END DESCRIPTION:
XS GIS Cut Line= 3
      2420204.48      7036951.99      2420234.48      7036228.78
      2420244.42      7035993.63
#Sta/Elev= 30
  4407.9  523.04  4419.9  521.82  4468.5  520.32    4480  520.81  4610.1  520.57
  4650.1  518.95  4844.6  515.78  4920.3  513.46  4930.3   513.7  4940.4  511.51
  4960.4  505.14  4970.4   503.4  4980.4  502.65  4990.4  502.89  4994.5  500.01
    4996  499.51  5005.5  500.01  5010.4  501.92  5020.4  500.01  5060.5  502.14
  5070.5  504.25  5080.5  507.61  5090.5  508.79  5117.8  515.76  5122.8  515.47
  5128.6  516.75  5153.3  517.88  5190.6  517.54  5240.6  518.67  5367.1  523.26
#Mann= 6 ,-1 , 0
  4407.9     .05       0  4468.5    .075       0  4844.6     .05       0
  4994.5     .05       0  5005.5     .05       0  5153.3      .1       0
Bank Sta=4994.5,5005.5
XS Rating Curve= 0 ,0
Exp/Cntr=0.3,0.1

Type RM Length L Ch R = 1 ,20312   ,309,309,309
BEGIN DESCRIPTION:
COTTONWOOD BR AT DENTON 31.0
END DESCRIPTION:
XS GIS Cut Line= 3
      2420421.11      7036802.02      2420441.11      7036242.11
      2420451.11      7036005.49
#Sta/Elev= 30
  4555.9  523.58  4634.9  521.27    4678  521.45    4758  519.94  4788.1  518.44
  4818.1  514.42  4858.1  514.18  4878.1  515.96  4902.4  514.99  4915.1  512.99
  4920.1   513.4  4928.2  510.56  4948.1  506.07  4968.2  501.83  4988.2  501.85
  4994.5  498.79    4996  498.29  5005.6  498.79  5018.2  498.79  5028.2  500.86
  5038.2  501.57  5058.2  501.26  5078.3  505.35  5108.3  513.88  5128.3  516.48
  5158.3  518.18    5184  517.28  5218.4  517.98  5278.4  520.82    5353  522.17
#Mann= 5 ,-1 , 0
  4555.9    .075       0  4902.4     .05       0  4948.1    .075       0
  4994.5     .07       0  5005.6    .075       0
Bank Sta=4994.5,5005.6
XS Rating Curve= 0 ,0
Exp/Cntr=0.3,0.1

Type RM Length L Ch R = 1 ,20003   ,456,456,456
BEGIN DESCRIPTION:
COTTONWOOD BR AT DENTON 30.0
END DESCRIPTION:
XS GIS Cut Line= 3
      2420664.41      7037101.92        2420729.        7036310.
      2420740.98      7036073.55
#Sta/Elev= 30
  4209.8  524.31  4221.8   524.7  4241.8  519.11  4292.3  517.59  4398.3  517.19
  4482.4  516.85  4604.6  516.41  4807.4  514.88  4813.7  514.98  4819.3  516.89
  4853.9  518.32    4894   509.3  4924.1  500.49  4934.1  499.32  4954.2  499.76
  4964.2  497.36  4974.2  497.46  4984.3  500.99  4994.3  499.97  4994.5  497.36
    4996  496.86  5005.6  497.36  5006.9  499.08  5014.4  499.99  5024.4  505.17
  5044.4  511.62  5074.4  517.28  5094.9  518.12  5144.5  520.02  5241.1  521.46
#Mann= 9 ,-1 , 0
  4209.8    .075       0  4292.3      .1       0  4398.3    .075       0
  4482.4      .1       0  4604.6    .075       0  4807.4     .05       0
  4994.5     .05       0  5005.6     .05       0  5094.9      .1       0
Bank Sta=4994.5,5005.6
XS Rating Curve= 0 ,0
Exp/Cntr=0.3,0.1

Type RM Length L Ch R = 1 ,19547   ,261,261,261
BEGIN DESCRIPTION:
COTTONWOOD BR AT DENTON 29.0
END DESCRIPTION:
XS GIS Cut Line= 3
        2421061.      7036785.37      2421130.99      7036442.07
      2421104.47      7036173.54
#Sta/Elev= 30
  4625.3  517.89  4625.4  517.89  4722.6  516.86  4739.2  515.98  4753.2  513.81
  4789.7  513.12  4794.8  511.64  4834.9  512.94  4875.7  512.25  4885.7  509.53
  4890.8   509.3  4896.1  506.65  4916.5  501.11  4926.7  499.07  4941.4  498.18
  4947.2   495.6  4957.4  498.65  4967.6  498.61  4974.2  494.84  4979.2  494.84
  4987.8  496.88  4994.5  494.84    4996  494.34  5005.6  494.84  5007.9  497.53
    5028  500.81  5068.2  511.18  5128.5  517.33  5218.9  519.85  5245.5   522.2
#Mann= 4 ,-1 , 0
  4625.3    .075       0  4625.4     .05       0  4994.5    .033       0
  5005.6     .05       0
Bank Sta=4994.5,5005.6
XS Rating Curve= 0 ,0
Exp/Cntr=0.3,0.1

Type RM Length L Ch R = 1 ,19286   ,1172,1172,1172
BEGIN DESCRIPTION:
COTTONWOOD BR AT DENTON 28.5
END DESCRIPTION:
XS GIS Cut Line= 5
      2421210.99      7037041.93      2421384.28      7036608.71
      2421387.61       7036465.4      2421170.98      7036112.13
      2421104.32      7035658.85
#Sta/Elev= 30
  4344.3  514.73  4376.3  512.03  4393.1  511.72  4766.4  503.29  4963.8  504.57
  4972.3  502.07  4979.2  495.29  4994.5  494.54    4996  494.04  5005.6  494.54
  5007.5  499.95  5015.9  500.75  5052.7  499.13  5066.2  501.66    5190  501.25
    5248  502.81  5269.3   504.4  5277.3  504.17  5300.2  505.76  5321.5  508.25
  5327.3  515.47  5342.8  516.72  5348.6   518.4  5416.4  520.48    5584  522.53
  5695.4  524.26  5734.7  521.34  5760.1  521.41  5795.3  524.12  5826.8  524.41
#Mann= 6 ,-1 , 0
  4344.3     .05       0  4393.1     .12       0  4994.5     .07       0
  5005.6     .12       0  5269.3     .05       0    5584    .075       0
Bank Sta=4994.5,5005.6
XS Rating Curve= 0 ,0
Exp/Cntr=0.3,0.1

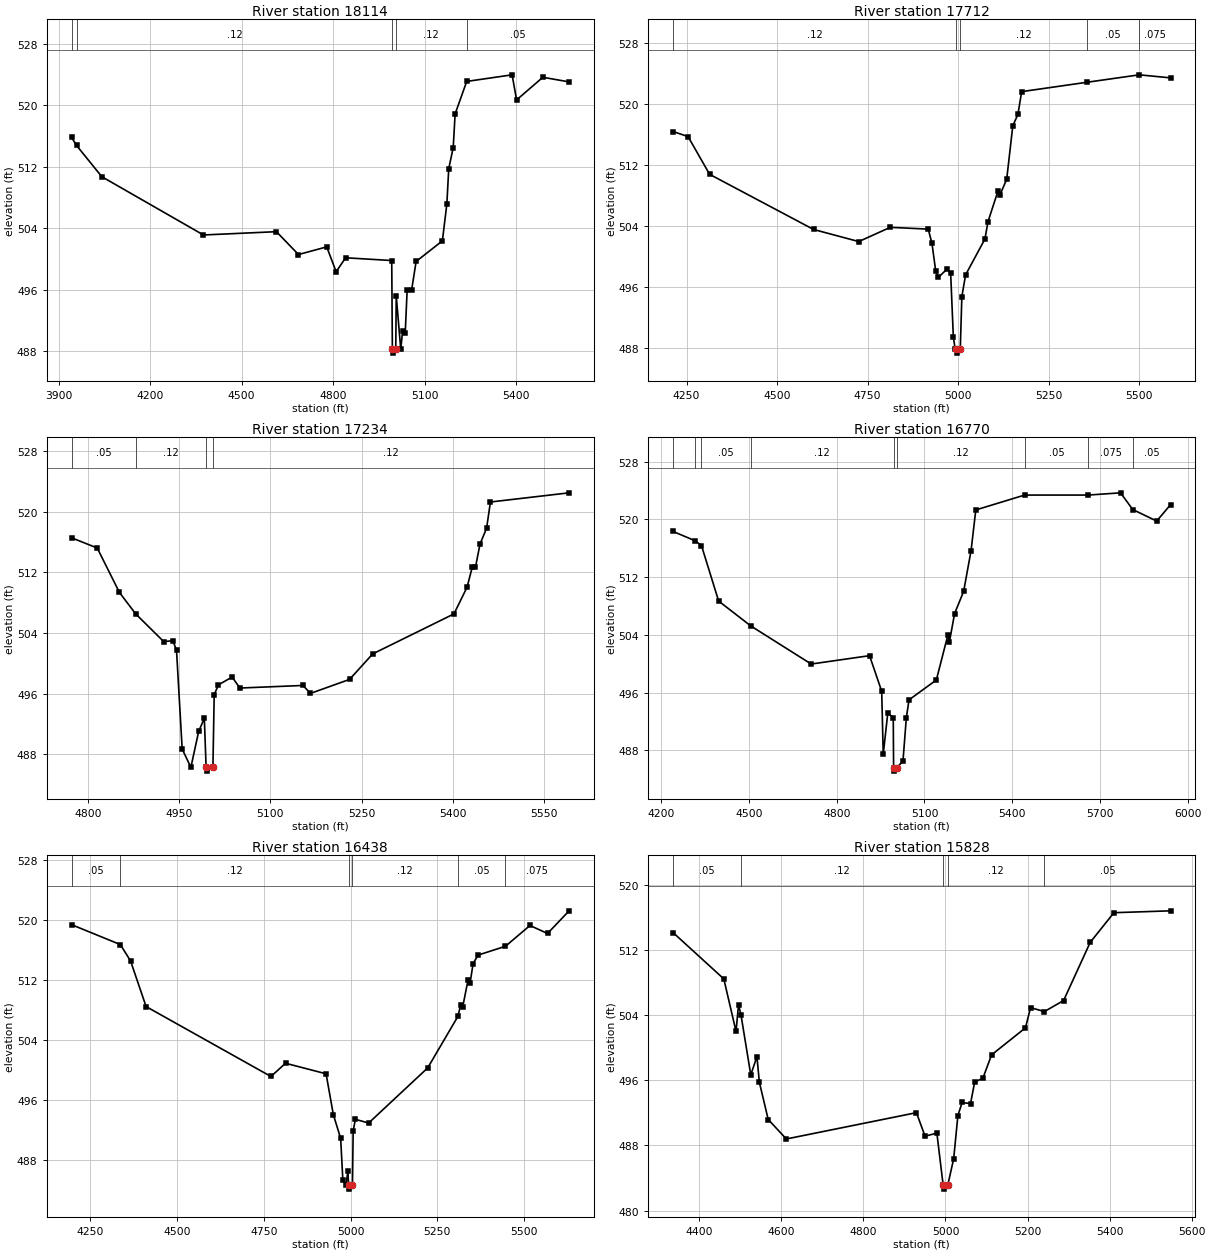
Type RM Length L Ch R = 1 ,18114   ,402,402,402
BEGIN DESCRIPTION:
COTTONWOOD BR AT DENTON 28.0
END DESCRIPTION:
XS GIS Cut Line= 4
      2421224.29      7037068.65      2421454.26      7036565.38
      2421550.91      7036175.45      2421943.12       7035623.7
#Sta/Elev= 30
  3942.2  515.84  3958.6  514.79  4041.5  510.72  4374.8  503.13  4614.2  503.56
  4686.5  500.58  4779.2  501.58  4810.1  498.34  4841.1  500.16  4992.4   499.8
  4994.5  488.24    4996  487.74  5005.6  488.24  5007.2  495.21    5022  488.24
  5028.1  490.65  5036.7  490.37  5042.9   495.9  5057.6  495.94  5072.4  499.68
  5158.5  502.36  5173.2  507.17  5179.4  511.77  5194.1  514.52  5200.3  518.89
  5238.3  523.13  5387.2  523.99    5402  520.72  5488.1  523.67  5574.2  523.07
#Mann= 5 ,-1 , 0
  3942.2     .05       0  3958.6     .12       0  4994.5     .07       0
  5005.6     .12       0  5238.3     .05       0
Bank Sta=4994.5,5005.6
XS Rating Curve= 0 ,0
Exp/Cntr=0.3,0.1

Type RM Length L Ch R = 1 ,17712   ,478,478,478
BEGIN DESCRIPTION:
COTTONWOOD BR AT DENTON 27.0
END DESCRIPTION:
XS GIS Cut Line= 4
      2421244.28      7037091.99      2421574.24      7036498.73
      2421867.35      7036424.71      2421967.51      7036045.47
#Sta/Elev= 30
  4212.8  516.39  4254.2  515.73  4313.7  510.79  4600.8  503.57  4725.4  501.99
  4812.3  503.85  4917.2  503.62  4927.5  501.75  4937.8  498.14  4945.3  497.31
  4968.8  498.38  4979.1  497.84  4986.4  489.56  4991.6  487.89  4994.5  487.89
    4996  487.39  5005.6  487.89    5010   494.8  5020.3  497.63  5073.6  502.32
  5082.2   504.6  5109.5  508.58  5114.7  508.04  5133.8  510.15  5150.6  517.15
  5164.7  518.62    5175  521.61  5355.9  522.84  5499.8  523.81  5586.2  523.41
#Mann= 5 ,-1 , 0
  4212.8     .12       0  4994.5     .07       0  5005.6     .12       0
  5355.9     .05       0  5499.8    .075       0
Bank Sta=4994.5,5005.6
XS Rating Curve= 0 ,0
Exp/Cntr=0.3,0.1

Type RM Length L Ch R = 1 ,17234   ,464,464,464
BEGIN DESCRIPTION:
COTTONWOOD BR AT DENTON 26.0
END DESCRIPTION:
XS GIS Cut Line= 3
      2421604.24      7037105.28        2421729.        7036910.
      2421940.28      7036363.55
#Sta/Elev= 30
  4773.3  516.56  4815.5  515.21  4851.9  509.36  4878.7  506.52  4924.7  502.87
  4939.9  502.98  4945.8   501.7  4955.1  488.69  4969.4  486.28  4982.2  491.02
  4991.5  492.75  4994.4  486.28    4996  485.78  5005.6  486.28  5007.7  495.85
  5014.6  497.16  5037.2  498.19  5049.9  496.74  5153.7  497.08  5165.8  496.03
  5230.2  497.88  5268.1  501.24  5401.7  506.52  5423.2  510.04  5431.7  512.66
    5437  512.67  5444.6  515.76  5455.3  517.81  5461.6  521.28  5590.9  522.49
#Mann= 4 ,-1 , 0
  4773.3     .05       0  4878.7     .12       0  4994.4     .07       0
  5005.6     .12       0
Bank Sta=4994.4,5005.6
XS Rating Curve= 0 ,0
Exp/Cntr=0.3,0.1

Type RM Length L Ch R = 1 ,16770   ,332,332,332
BEGIN DESCRIPTION:
COTTONWOOD BR AT DENTON 25.0
END DESCRIPTION:
XS GIS Cut Line= 4
       2421640.9      7037258.59      2422097.48      7036941.98
      2421960.84      7036448.74      2422113.72      7035833.89
#Sta/Elev= 30
  4240.4  518.32    4316  517.03  4337.6  516.36  4396.3  508.68  4506.1  505.24
  4712.7  499.96  4912.2  501.12  4953.7  496.19  4958.9  487.46  4974.5  493.16
  4993.2  492.55  4994.4  485.63  4995.9  485.13  5005.6  485.63  5026.4   486.5
  5037.9  492.51  5047.1     495  5140.5  497.75  5180.2  504.01  5185.4  503.06
  5202.8  506.93  5233.9  510.03  5259.2  515.66  5275.4   521.3  5442.2  523.36
  5659.7  523.36  5770.2  523.67  5812.1  521.35  5893.9  519.76  5941.4  522.04
#Mann= 9 ,-1 , 0
  4240.4     .05       0    4316     .12       0  4337.6     .05       0
  4506.1     .12       0  4994.4     .07       0  5005.6     .12       0
  5442.2     .05       0  5659.7    .075       0  5812.1     .05       0
Bank Sta=4994.4,5005.6
XS Rating Curve= 0 ,0
Exp/Cntr=0.3,0.1

Type RM Length L Ch R = 1 ,16438   ,610,610,610
BEGIN DESCRIPTION:
COTTONWOOD BR AT DENTON 24.0
END DESCRIPTION:
XS GIS Cut Line= 3
      2421610.92      7037308.57      2422317.44        7036832.
      2422794.04      7036498.72
#Sta/Elev= 30
  4196.1   519.4  4336.7  516.74  4366.1  514.56  4410.9  508.45  4770.7   499.1
  4812.7  500.87  4929.6  499.46  4950.6  493.98  4971.6  490.83  4977.8  485.31
  4986.6  484.54  4992.6  486.48  4994.4  484.54  4995.9  484.04  5005.6  484.54
  5007.6  491.81    5014  493.37  5052.3  492.88  5222.4  500.25  5309.7  507.15
  5317.4   508.7  5323.5  508.45  5338.4  511.94  5344.5  511.57  5353.2   514.2
  5367.5  515.33  5446.5  516.51  5517.1  519.29  5567.7  518.22  5629.9  521.25
#Mann= 6 ,-1 , 0
  4196.1     .05       0  4336.7     .12       0  4994.4     .07       0
  5005.6     .12       0  5309.7     .05       0  5446.5    .075       0
Bank Sta=4994.4,5005.6
XS Rating Curve= 0 ,0
Exp/Cntr=0.3,0.1

Type RM Length L Ch R = 1 ,15828   ,456,456,456
BEGIN DESCRIPTION:
COTTONWOOD BR AT DENTON 23.0
END DESCRIPTION:
XS GIS Cut Line= 4
      2421977.53      7037591.85      2422504.08      7037231.93
      2422650.72      7037198.61      2423000.67      7036958.64
#Sta/Elev= 30
  4336.2  514.14  4459.9  508.45  4489.7     502  4495.8  505.29  4501.9  503.99
  4525.6  496.66  4540.6   498.9  4546.6  495.74  4568.1  491.18  4612.3  488.79
  4929.3  492.02  4950.3  489.13  4979.1  489.51  4994.4  483.13  4995.9  482.63
  5005.7  483.13  5020.1  486.37  5030.3  491.66  5040.6  493.27  5061.1  493.13
  5071.3   495.8  5091.1  496.23  5112.4  499.12    5195  502.44  5207.4  504.92
  5241.1  504.44  5287.9  505.79  5352.7  512.93  5410.5  516.58  5548.7  516.81
#Mann= 5 ,-1 , 0
  4336.2     .05       0  4501.9     .12       0  4994.4     .07       0
  5005.7     .12       0  5241.1     .05       0
Bank Sta=4994.4,5005.7
XS Rating Curve= 0 ,0
Exp/Cntr=0.3,0.1