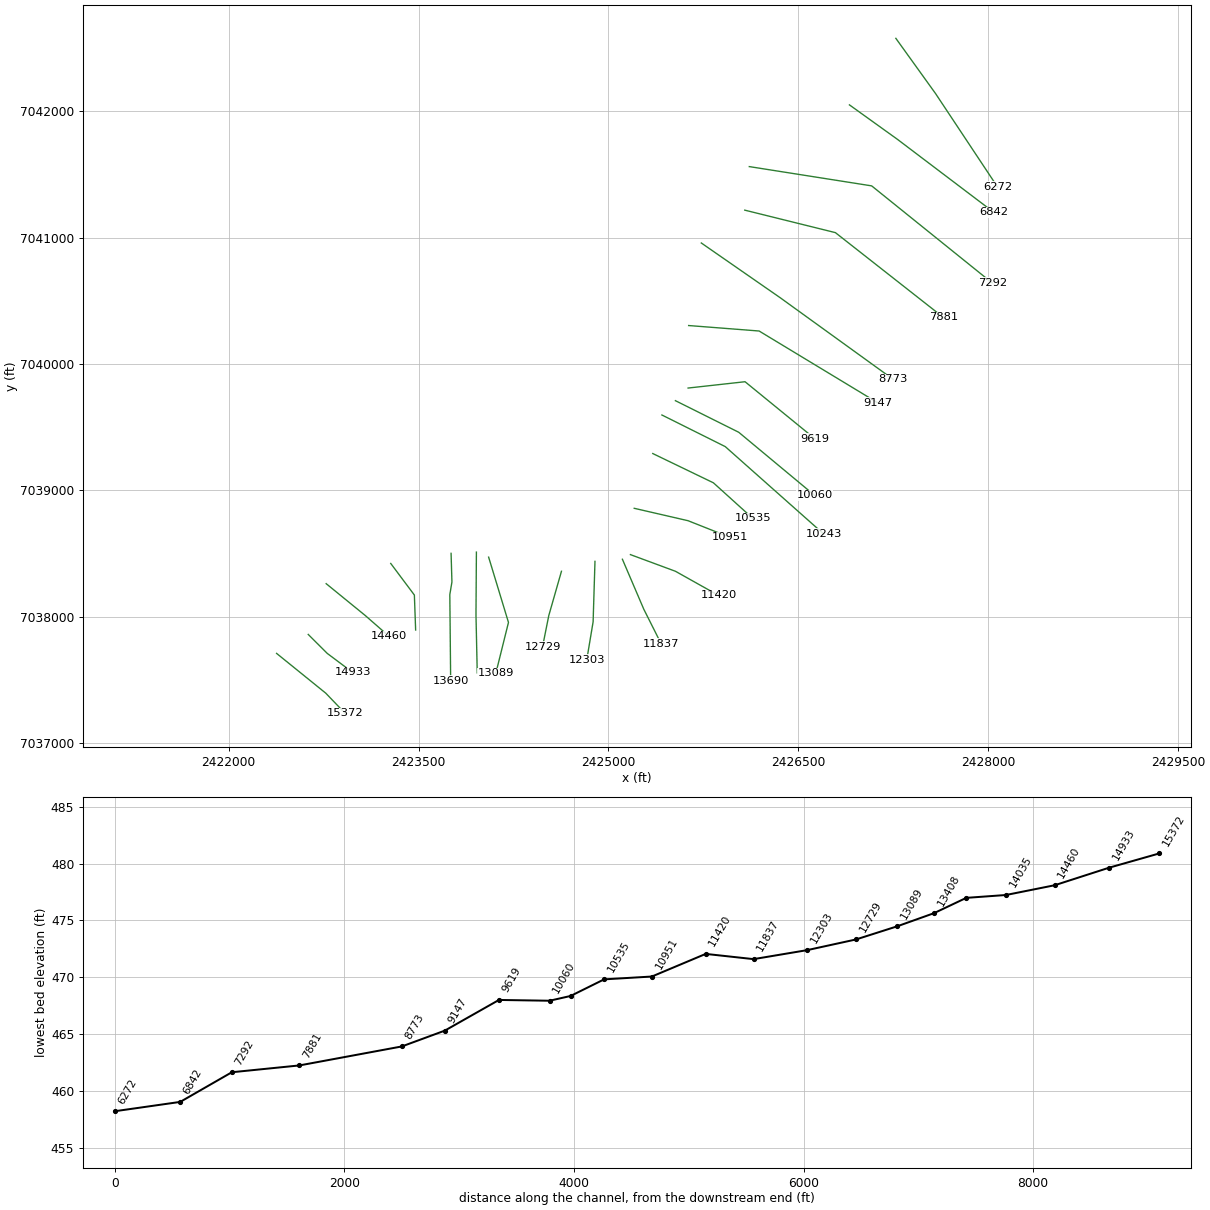
HEC-RAS study COTTONWOOD BR AT DENTON.prj: COTTONWOOD BR AT DENTON Base Level Engineering

--- COTTONWOOD BR AT DENTON.g01 (geometry) --- (continued)

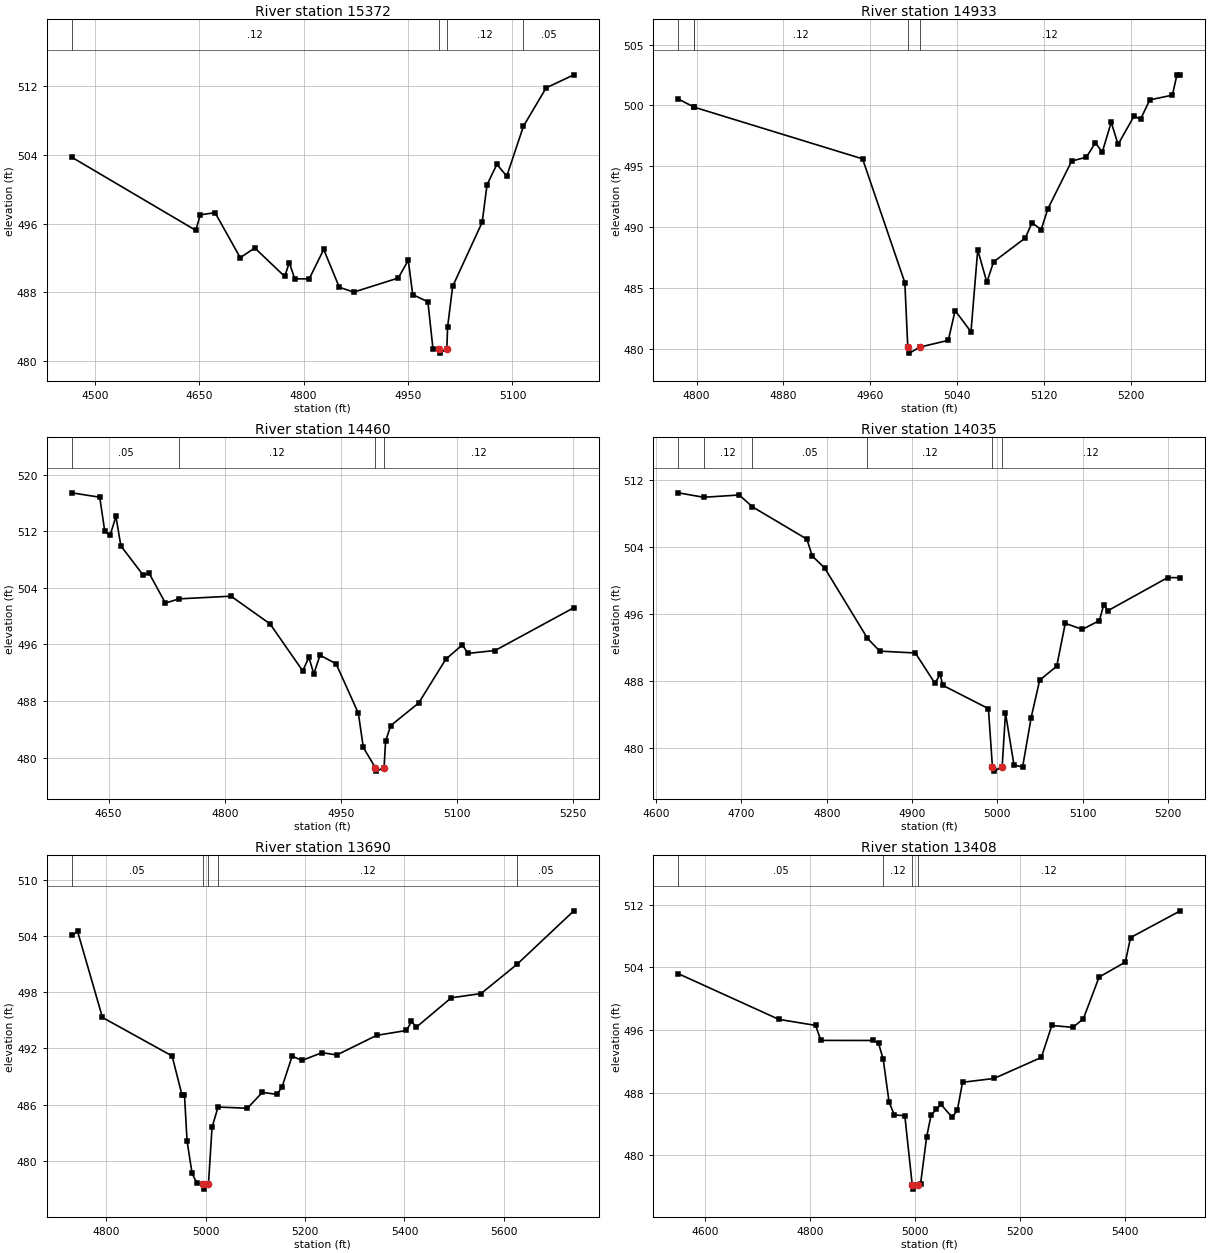
Type RM Length L Ch R = 1 ,15372   ,439,439,439
BEGIN DESCRIPTION:
COTTONWOOD BR AT DENTON 22.0
END DESCRIPTION:
XS GIS Cut Line= 3
      2422379.04      7037709.97      2422767.36      7037395.24
      2422920.65      7037235.28
#Sta/Elev= 30
  4466.8  503.75    4645  495.22  4651.4  497.03  4672.7  497.28  4708.9  492.03
  4729.7  493.17  4772.8  489.84  4779.3  491.47  4787.2  489.56    4808  489.57
  4828.8  492.99  4851.2  488.58    4872  488.02  4935.9  489.66  4950.3  491.73
  4956.7  487.73  4978.5  486.88  4985.8   481.4  4994.4   481.4  4995.9   480.9
  5005.7   481.4  5006.8  483.95  5014.1  488.69  5056.5  496.17  5063.5  500.54
  5077.6  502.92  5091.8  501.54  5115.8  507.37  5148.4  511.84  5188.2  513.36
#Mann= 4 ,-1 , 0
  4466.8     .12       0  4994.4     .07       0  5005.7     .12       0
  5115.8     .05       0
Bank Sta=4994.4,5005.7
XS Rating Curve= 0 ,0
Exp/Cntr=0.3,0.1

Type RM Length L Ch R = 1 ,14933   ,473,473,473
BEGIN DESCRIPTION:
COTTONWOOD BR AT DENTON 21.0
END DESCRIPTION:
XS GIS Cut Line= 3
      2422628.97      7037860.03        2422779.        7037710.
      2422979.02      7037559.99
#Sta/Elev= 30
  4783.1  500.53  4797.6  499.87  4797.8  499.86  4952.8  495.61  4991.7  485.44
  4994.4  480.14  4995.9  479.64  5005.7  480.14  5031.7  480.69    5038  483.14
  5052.6  481.39  5058.8  488.13  5067.2  485.47  5073.4  487.14  5102.6  489.11
  5108.8  490.36  5117.2  489.79  5123.4  491.51  5145.3  495.43  5158.8  495.75
  5167.2  496.94  5173.4  496.15  5181.7  498.62    5188   496.8  5202.6  499.11
  5208.8  498.89  5217.2  500.46    5238  500.85  5242.2  502.52  5245.3  502.52
#Mann= 5 ,-1 , 0
  4783.1     .12       0  4797.6     .05       0  4797.8     .12       0
  4994.4     .07       0  5005.7     .12       0
Bank Sta=4994.4,5005.7
XS Rating Curve= 0 ,0
Exp/Cntr=0.3,0.1

Type RM Length L Ch R = 1 ,14460   ,425,425,425
BEGIN DESCRIPTION:
COTTONWOOD BR AT DENTON 20.0
END DESCRIPTION:
XS GIS Cut Line= 3
      2422770.73      7038261.72        2423079.        7038010.
      2423267.25      7037845.18
#Sta/Elev= 30
  4602.5  517.44  4638.6  516.82  4645.1     512  4651.9  511.41  4659.5   514.1
  4665.9  509.94  4694.6  505.82  4702.5  506.04  4723.4  501.85  4740.8  502.45
  4808.1  502.83  4858.5  498.91  4900.7  492.27  4908.6  494.19    4915  491.85
    4923  494.49  4943.8  493.27  4972.5  486.28  4978.9  481.44  4994.4   478.6
  4995.9   478.1  5005.7   478.6  5007.6  482.31  5014.3  484.54  5050.3  487.72
  5085.4  493.92  5106.8  495.95  5113.9  494.74    5149  495.15  5250.7   501.2
#Mann= 4 ,-1 , 0
  4602.5     .05       0  4740.8     .12       0  4994.4     .07       0
  5005.7     .12       0
Bank Sta=4994.4,5005.7
XS Rating Curve= 0 ,0
Exp/Cntr=0.3,0.1

Type RM Length L Ch R = 1 ,14035   ,345,345,345
BEGIN DESCRIPTION:
COTTONWOOD BR AT DENTON 19.0
END DESCRIPTION:
XS GIS Cut Line= 3
      2423280.62      7038421.71      2423467.24      7038171.77
      2423477.24      7037895.18
#Sta/Elev= 30
  4625.9   510.5  4655.7  509.97  4697.5  510.24  4712.7  508.84  4776.8  504.96
    4783  502.95  4797.6  501.52  4847.8  493.11  4862.2  491.58  4903.9  491.36
  4926.9  487.74  4933.1  488.83  4935.8  487.51  4989.6  484.71  4994.3  477.74
  4995.9  477.24  5005.7  477.74  5009.6  484.19  5019.6  477.96  5029.7  477.74
  5039.7  483.63  5049.7  488.11  5069.7  489.78  5079.7   494.9  5099.7  494.18
  5119.7  495.23  5124.8  497.12  5129.8  496.42  5199.8  500.37  5214.6  500.36
#Mann= 6 ,-1 , 0
  4625.9     .05       0  4655.7     .12       0  4712.7     .05       0
  4847.8     .12       0  4994.3     .07       0  5005.7     .12       0
Bank Sta=4994.3,5005.7
XS Rating Curve= 0 ,0
Exp/Cntr=0.3,0.1

Type RM Length L Ch R = 1 ,13690   ,282,282,282
BEGIN DESCRIPTION:
COTTONWOOD BR AT DENTON 18.2
END DESCRIPTION:
XS GIS Cut Line= 4
      2423757.19      7038501.69      2423763.85      7038275.08
      2423747.19       7038175.1      2423753.84      7037493.39
#Sta/Elev= 30
  4730.8  504.06  4742.5  504.49  4792.5  495.31  4932.6   491.2  4952.5  487.03
  4957.5  487.03  4962.7  482.12  4972.8  478.66  4982.9   477.6  4994.3  477.49
  4995.9  476.99  5005.7  477.49  5012.9  483.58    5025  485.75    5084  485.62
    5114  487.31    5144   487.1    5154  487.94    5174  491.18    5194  490.73
    5234  491.55    5264  491.31    5344   493.4    5404  493.92    5414  494.88
    5424  494.28    5494  497.41    5554  497.86  5626.5  500.99  5740.6  506.69
#Mann= 5 ,-1 , 0
  4730.8     .05       0  4994.3    .033       0  5005.7     .05       0
    5025     .12       0  5626.5     .05       0
Bank Sta=4994.3,5005.7
XS Rating Curve= 0 ,0
Exp/Cntr=0.3,0.1

Type RM Length L Ch R = 1 ,13408   ,319,319,319
BEGIN DESCRIPTION:
COTTONWOOD BR AT DENTON 18.0
END DESCRIPTION:
XS GIS Cut Line= 3
      2423957.15       7038511.7      2423953.82      7038015.13
      2423963.82      7037555.22
#Sta/Elev= 30
  4548.4  503.21  4740.1  497.36  4810.1  496.59  4820.1  494.67  4920.1  494.66
  4930.1  494.29  4938.9  492.27  4950.1  486.77  4960.1  485.14  4980.1  485.03
  4994.3  476.14  4995.9  475.64  5005.7  476.14  5010.1   476.3  5021.7  482.32
  5030.1   485.1    5040  485.85  5049.2  486.47  5070.1  484.84  5080.1  485.71
  5090.1  489.31  5150.1   489.8  5240.2  492.49  5260.2  496.58  5300.2  496.34
  5320.2  497.42  5350.2  502.77  5400.2  504.69  5410.2  507.83    5505  511.25
#Mann= 4 ,-1 , 0
  4548.4     .05       0  4938.9     .12       0  4994.3     .07       0
  5005.7     .12       0
Bank Sta=4994.3,5005.7
XS Rating Curve= 0 ,0
Exp/Cntr=0.3,0.1

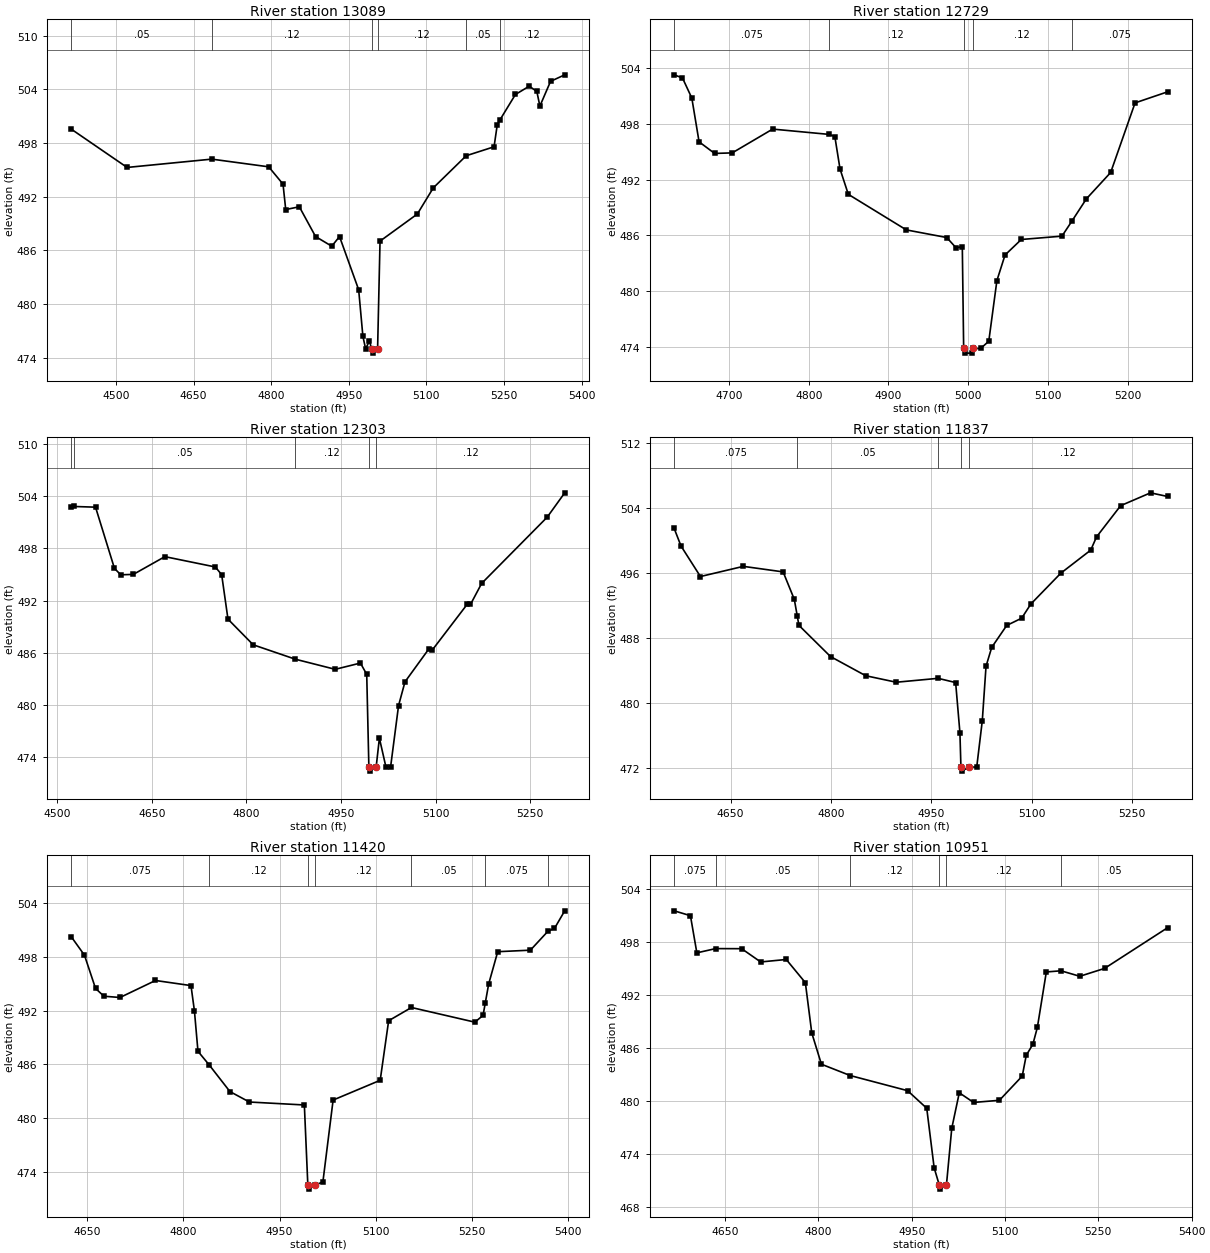
Type RM Length L Ch R = 1 ,13089   ,360,360,360
BEGIN DESCRIPTION:
COTTONWOOD BR AT DENTON 17.0
END DESCRIPTION:
XS GIS Cut Line= 3
      2424053.79      7038471.76      2424210.44      7037955.14
      2424110.85      7037553.45
#Sta/Elev= 30
  4413.7  499.54  4521.5  495.26  4685.1  496.19  4795.2  495.33  4822.9  493.39
  4828.1  490.55  4854.4  490.86  4885.8  487.53  4917.1  486.45  4932.1  487.53
  4969.1  481.58  4977.3  476.35  4982.5  474.99  4989.8  475.82  4994.3  474.99
  4995.9  474.49  5005.7  474.99  5010.4  487.02  5082.5  490.05  5113.4  492.98
    5177  496.57  5230.8  497.57    5237  500.04  5242.2  500.58  5272.1  503.42
  5298.8  504.35  5313.5  503.76  5319.4  502.12    5340  504.89  5367.4  505.62
#Mann= 6 ,-1 , 0
  4413.7     .05       0  4685.1     .12       0  4994.3     .07       0
  5005.7     .12       0    5177     .05       0  5242.2     .12       0
Bank Sta=4994.3,5005.7
XS Rating Curve= 0 ,0
Exp/Cntr=0.3,0.1

Type RM Length L Ch R = 1 ,12729   ,426,426,426
BEGIN DESCRIPTION:
COTTONWOOD BR AT DENTON 16.0
END DESCRIPTION:
XS GIS Cut Line= 3
      2424628.99      7038359.98        2424529.        7038010.
      2424479.01      7037760.03
#Sta/Elev= 30
  4631.2  503.28  4641.6  502.94  4653.3  500.78  4662.4  496.07  4681.9  494.82
    4704  494.88  4754.7  497.44  4825.4  496.87  4832.7  496.64  4839.2  493.15
  4849.6  490.42  4922.4  486.59  4973.1  485.77  4984.8  484.66  4992.6  484.79
  4994.3  473.83  4995.8  473.33  5004.2  473.33  5005.8  473.83  5015.6  473.83
  5025.8  474.61    5036  481.14  5046.2  483.89  5066.6  485.56  5117.6  485.92
  5129.8   487.5  5148.2  489.93  5178.7  492.77  5209.3  500.26  5250.1  501.45
#Mann= 5 ,-1 , 0
  4631.2    .075       0  4825.4     .12       0  4994.3     .07       0
  5005.8     .12       0  5129.8    .075       0
Bank Sta=4994.3,5005.8
XS Rating Curve= 0 ,0
Exp/Cntr=0.3,0.1

Type RM Length L Ch R = 1 ,12303   ,466,466,466
BEGIN DESCRIPTION:
COTTONWOOD BR AT DENTON 15.0
END DESCRIPTION:
XS GIS Cut Line= 3
      2424893.65      7038438.37        2424879.        7037960.
      2424829.01      7037660.03
#Sta/Elev= 30
  4522.2  502.74  4526.3  502.83  4560.6  502.75  4590.6  495.71  4600.6  494.97
  4620.6  495.02  4670.6  497.06  4750.7  495.87  4760.7  494.98  4770.7  489.87
  4810.7  486.92  4877.7  485.26  4940.8   484.1  4980.8  484.82  4990.8  483.52
  4994.2  472.89  4995.8  472.39  5005.8  472.89  5010.9  476.18  5021.1  472.92
  5028.7  472.89  5041.3  479.93  5051.5  482.66  5089.5  486.46  5094.6   486.3
  5150.3  491.59  5155.4  491.56  5173.1  493.98  5277.1   501.6  5304.9   504.4
#Mann= 5 ,-1 , 0
  4522.2    .075       0  4526.3     .05       0  4877.7     .12       0
  4994.2     .07       0  5005.8     .12       0
Bank Sta=4994.2,5005.8
XS Rating Curve= 0 ,0
Exp/Cntr=0.3,0.1

Type RM Length L Ch R = 1 ,11837   ,417,417,417
BEGIN DESCRIPTION:
COTTONWOOD BR AT DENTON 14.0
END DESCRIPTION:
XS GIS Cut Line= 3
       2425110.3      7038455.01        2425279.        7038060.
      2425416.89      7037785.18
#Sta/Elev= 30
  4565.9  501.46  4576.1   499.3  4605.1  495.55  4669.2   496.8  4728.6  496.12
  4745.3  492.74  4749.6  490.75  4752.2  489.54  4799.4   485.7    4852  483.34
  4897.6  482.54  4960.1  483.02  4986.3   482.5  4992.7  476.32  4994.2   472.1
  4995.8   471.6  5005.9   472.1  5017.8   472.1  5026.1  477.79  5031.7  484.51
  5040.2  486.83  5062.6  489.53  5084.9  490.42  5098.7  492.17  5143.4  495.96
  5188.1   498.8  5196.8  500.43  5232.8  504.27  5277.4  505.85  5302.9   505.4
#Mann= 5 ,-1 , 0
  4565.9    .075       0  4749.6     .05       0  4960.1     .12       0
  4994.2     .07       0  5005.9     .12       0
Bank Sta=4994.2,5005.9
XS Rating Curve= 0 ,0
Exp/Cntr=0.3,0.1

Type RM Length L Ch R = 1 ,11420   ,469,469,469
BEGIN DESCRIPTION:
COTTONWOOD BR AT DENTON 13.0
END DESCRIPTION:
XS GIS Cut Line= 3
       2425173.6      7038491.71        2425529.        7038360.
      2425870.17      7038168.42
#Sta/Elev= 30
    4625  500.27  4645.5  498.22  4662.8   494.5  4675.9  493.63    4701  493.49
  4756.4  495.39  4811.8  494.82  4817.2  491.98  4822.7  487.47  4840.1  485.96
  4872.6  482.97    4903   481.8  4988.8  481.47  4994.2  472.56  4995.8  472.06
  5005.9  472.56  5017.7  472.84  5033.7  482.02  5107.2  484.23  5120.4  490.89
    5156  492.37    5255  490.73  5267.8  491.49  5271.2  492.85  5276.6  495.01
  5290.7  498.61  5341.7  498.78  5369.3  500.91  5379.3  501.21  5395.3  503.18
#Mann= 7 ,-1 , 0
    4625    .075       0  4840.1     .12       0  4994.2     .07       0
  5005.9     .12       0    5156     .05       0  5271.2    .075       0
  5369.3     .05       0
Bank Sta=4994.2,5005.9
XS Rating Curve= 0 ,0
Exp/Cntr=0.3,0.1

Type RM Length L Ch R = 1 ,10951   ,416,416,416
BEGIN DESCRIPTION:
COTTONWOOD BR AT DENTON 12.0
END DESCRIPTION:
XS GIS Cut Line= 3
      2425203.57      7038858.32        2425629.        7038760.
      2425960.15      7038628.35
#Sta/Elev= 30
  4568.3  501.53  4594.4  500.98  4604.7  496.78  4634.9  497.26  4676.7  497.25
  4707.3  495.75  4748.4  496.03  4779.1  493.41  4789.4  487.73  4804.9  484.19
  4851.2  482.91  4943.4   481.2  4974.2  479.21  4986.1  472.48  4994.2  470.57
  4995.8  470.07  5005.9  470.57  5014.4  476.94  5026.5  480.96  5049.5  479.87
    5091  480.11  5127.7  482.85  5134.1  485.19  5144.8  486.45    5152  488.35
  5166.4  494.62    5190  494.75  5220.2  494.13    5260  495.02  5361.3  499.62
#Mann= 6 ,-1 , 0
  4568.3    .075       0  4634.9     .05       0  4851.2     .12       0
  4994.2     .07       0  5005.9     .12       0    5190     .05       0
Bank Sta=4994.2,5005.9
XS Rating Curve= 0 ,0
Exp/Cntr=0.3,0.1

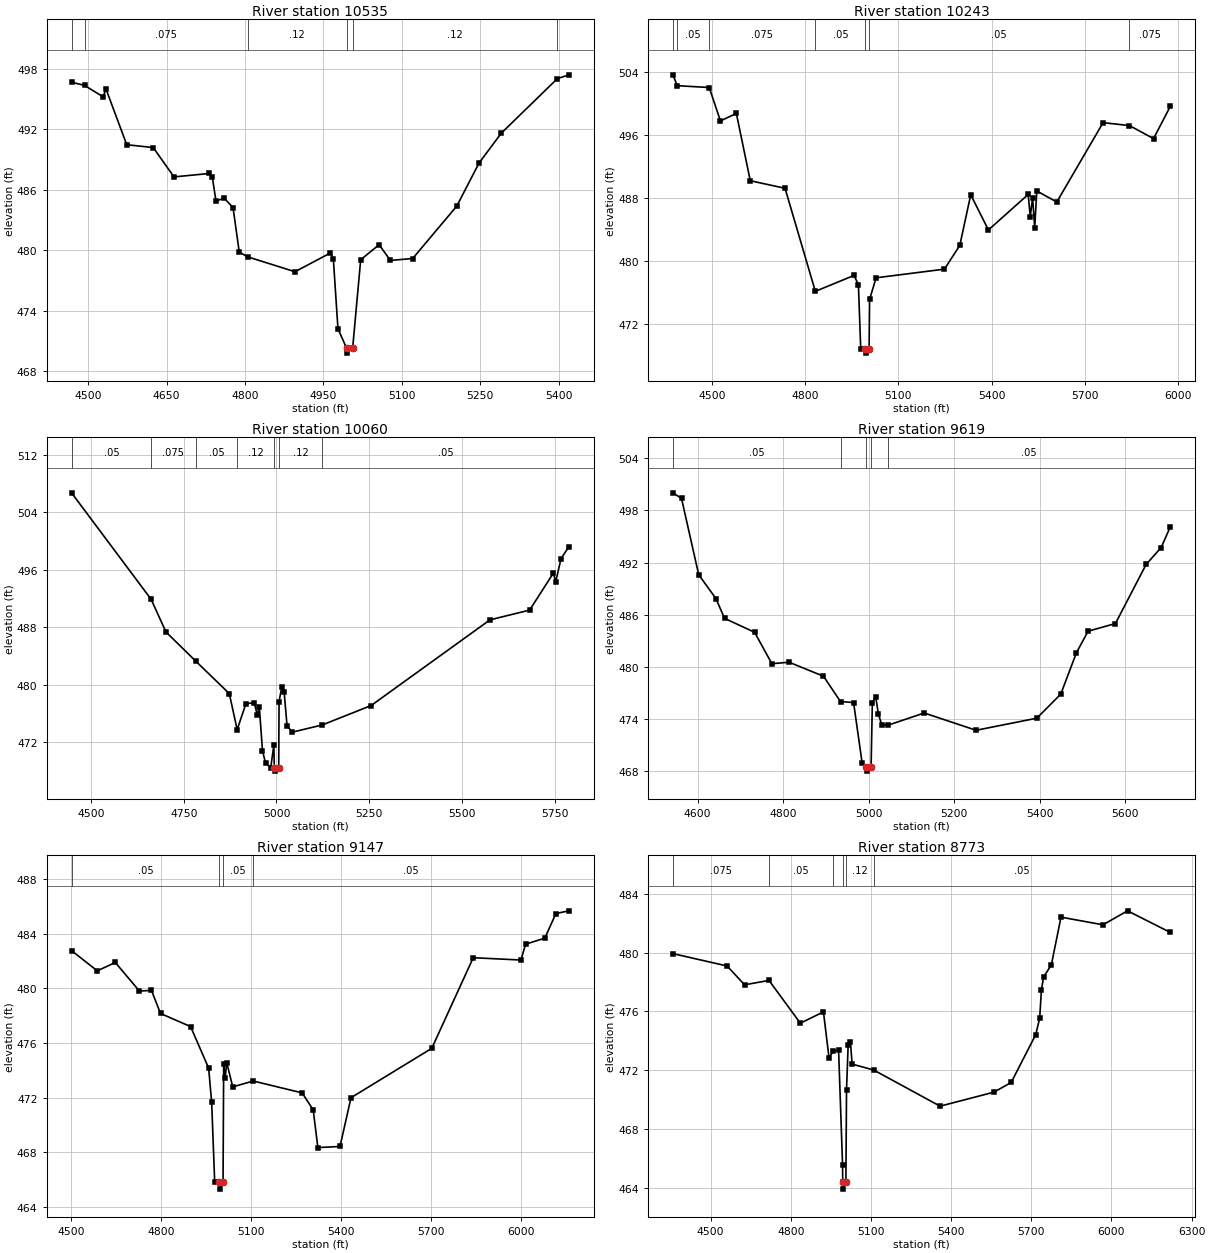
Type RM Length L Ch R = 1 ,10535   ,292,292,292
BEGIN DESCRIPTION:
COTTONWOOD BR AT DENTON 11.0
END DESCRIPTION:
XS GIS Cut Line= 3
      2425350.23      7039291.57        2425829.        7039060.
       2426140.1      7038778.33
#Sta/Elev= 30
  4468.2  496.68  4493.1  496.36  4528.6  495.23  4534.1     496  4573.8  490.48
  4624.5   490.2  4664.1  487.29  4731.9  487.63  4737.5  487.26  4744.5  484.89
    4760  485.19  4777.1  484.25    4789  479.84  4804.8  479.37  4895.6  477.89
  4963.4  479.75  4968.9   479.2  4977.8  472.24  4994.2  470.32  4995.8  469.82
  5005.9  470.32  5021.3  479.08  5056.5  480.57  5078.1  479.01  5120.7   479.2
  5205.1   484.4  5247.7  488.67  5290.3  491.63  5397.4  497.03  5419.7  497.41
#Mann= 6 ,-1 , 0
  4468.2     .05       0  4493.1    .075       0  4804.8     .12       0
  4994.2     .07       0  5005.9     .12       0  5397.4     .05       0
Bank Sta=4994.2,5005.9
XS Rating Curve= 0 ,0
Exp/Cntr=0.3,0.1

Type RM Length L Ch R = 1 ,10243   ,183,183,183
BEGIN DESCRIPTION:
COTTONWOOD BR AT DENTON 10.2
END DESCRIPTION:
XS GIS Cut Line= 3
      2425422.37      7039596.68      2425922.35      7039346.69
      2426699.97      7038655.04
#Sta/Elev= 30
    4375  503.68  4388.9   502.3  4491.8  502.07  4527.8  497.83    4579  498.78
  4623.8  490.24  4735.6  489.28    4833   476.2  4957.3  478.22  4971.5  477.06
    4979  468.86  4994.2  468.86  4995.8  468.36  5005.9  468.86  5007.4  475.17
  5028.4  477.92  5248.3  479.02  5297.6  482.04  5332.7  488.46  5389.6  483.99
  5517.5   488.5  5524.2  485.69  5531.7  488.08  5538.4  484.28  5545.1  488.94
  5609.5  487.54  5758.3  497.61    5843  497.24  5920.6  495.59  5974.7  499.69
#Mann= 7 ,-1 , 0
    4375    .075       0  4388.9     .05       0  4491.8    .075       0
    4833     .05       0  4994.2    .033       0  5005.9     .05       0
    5843    .075       0
Bank Sta=4994.2,5005.9
XS Rating Curve= 0 ,0
Exp/Cntr=0.3,0.1

Type RM Length L Ch R = 1 ,10060   ,441,441,441
BEGIN DESCRIPTION:
COTTONWOOD BR AT DENTON 10.0
END DESCRIPTION:
XS GIS Cut Line= 3
      2425528.99        7039710.        2426029.        7039460.
      2426628.96      7038960.03
#Sta/Elev= 30
  4447.9  506.72  4662.3  491.88  4702.3  487.33    4782  483.29  4872.8  478.75
  4894.1  473.72  4917.5  477.32  4939.8  477.49  4948.2  475.82  4953.8  476.84
  4962.2   470.8  4970.6  469.04  4984.6  468.44  4992.9  471.62  4994.1  468.44
  4995.7  467.94    5006  468.44  5006.9  477.64  5014.1  479.62  5020.6  478.98
  5028.4  474.26  5042.7  473.37  5123.6  474.38  5254.9  477.08  5575.1  489.02
  5681.9  490.38  5745.6  495.52  5752.2  494.35  5766.5  497.55  5787.9  499.24
#Mann= 7 ,-1 , 0
  4447.9     .05       0  4662.3    .075       0    4782     .05       0
  4894.1     .12       0  4994.1     .07       0    5006     .12       0
  5123.6     .05       0
Bank Sta=4994.1,5006
XS Rating Curve= 0 ,0
Exp/Cntr=0.3,0.1

Type RM Length L Ch R = 1 ,9619    ,472,472,472
BEGIN DESCRIPTION:
COTTONWOOD BR AT DENTON 9.0
END DESCRIPTION:
XS GIS Cut Line= 3
      2425629.04        7039810.        2426079.        7039860.
      2426629.03      7039409.97
#Sta/Elev= 30
  4542.5  500.03  4562.6  499.39  4602.8  490.61  4643.1  487.86  4663.2  485.59
  4733.6  483.98  4773.9  480.37  4814.1  480.54  4894.6  478.93  4934.5  476.01
    4965   475.9  4985.2  468.89  4994.1  468.51  4995.7  468.01    5006  468.51
  5008.9  475.88  5016.8  476.56  5023.2  474.53  5031.1  473.34    5046   473.3
  5130.2   474.7  5251.5  472.71  5393.6   474.1  5449.6  476.87  5486.2  481.63
  5513.5  484.11  5577.4  484.99  5649.2  491.79  5684.3  493.73  5705.9  496.13
#Mann= 5 ,-1 , 0
  4542.5     .05       0  4934.5     .12       0  4994.1     .07       0
    5006     .12       0    5046     .05       0
Bank Sta=4994.1,5006
XS Rating Curve= 0 ,0
Exp/Cntr=0.3,0.1

Type RM Length L Ch R = 1 ,9147    ,374,374,374
BEGIN DESCRIPTION:
COTTONWOOD BR AT DENTON 8.0
END DESCRIPTION:
XS GIS Cut Line= 3
      2425633.53      7040304.72      2426190.09       7040261.4
      2427129.95      7039691.48
#Sta/Elev= 30
  4501.2  482.76  4586.9  481.28  4647.1  481.89  4727.3   479.8  4767.5  479.85
  4797.6  478.16  4897.9   477.2    4958  474.16  4968.1  471.65  4978.1  465.84
  4994.1  465.81  4995.7  465.31    5006  465.81  5008.1  474.49  5013.1  473.43
  5018.2  474.57  5038.3  472.79  5106.7  473.22  5269.6  472.35  5306.4   471.1
  5321.9  468.35  5395.6  468.43  5432.4     472  5701.4  475.61  5839.6  482.24
  5998.6  482.07  6014.1  483.23  6078.1  483.67  6114.9  485.47  6158.6  485.67
#Mann= 4 ,-1 , 0
  4501.2     .05       0  4994.1     .05       0    5006     .05       0
  5106.7     .05       0
Bank Sta=4994.1,5006
XS Rating Curve= 0 ,0
Exp/Cntr=0.3,0.1

Type RM Length L Ch R = 1 ,8773    ,892,892,892
BEGIN DESCRIPTION:
COTTONWOOD BR AT DENTON 7.6
END DESCRIPTION:
XS GIS Cut Line= 3
      2425733.52      7040957.93      2426356.73      7040524.68
      2427249.88      7039878.15
#Sta/Elev= 30
  4358.7  479.93  4561.4  479.09  4626.9  477.81  4718.2  478.11  4835.6   475.2
    4922  475.97  4942.9  472.84  4957.6  473.29  4978.7  473.37  4993.6  465.55
  4994.1  464.42  4995.7  463.92    5006  464.42  5008.4  470.67  5014.5  473.71
    5023  473.95  5029.3  472.42  5109.7  472.02  5358.6  469.56  5559.7  470.51
  5624.6  471.17  5716.6  474.43  5731.3  475.55  5737.8  477.49    5746  478.35
  5774.8  479.16    5811  482.41    5968  481.89    6060  482.84  6220.3  481.37
#Mann= 6 ,-1 , 0
  4358.7    .075       0  4718.2     .05       0  4957.6     .12       0
  4994.1     .07       0    5006     .12       0  5109.7     .05       0
Bank Sta=4994.1,5006
XS Rating Curve= 0 ,0
Exp/Cntr=0.3,0.1

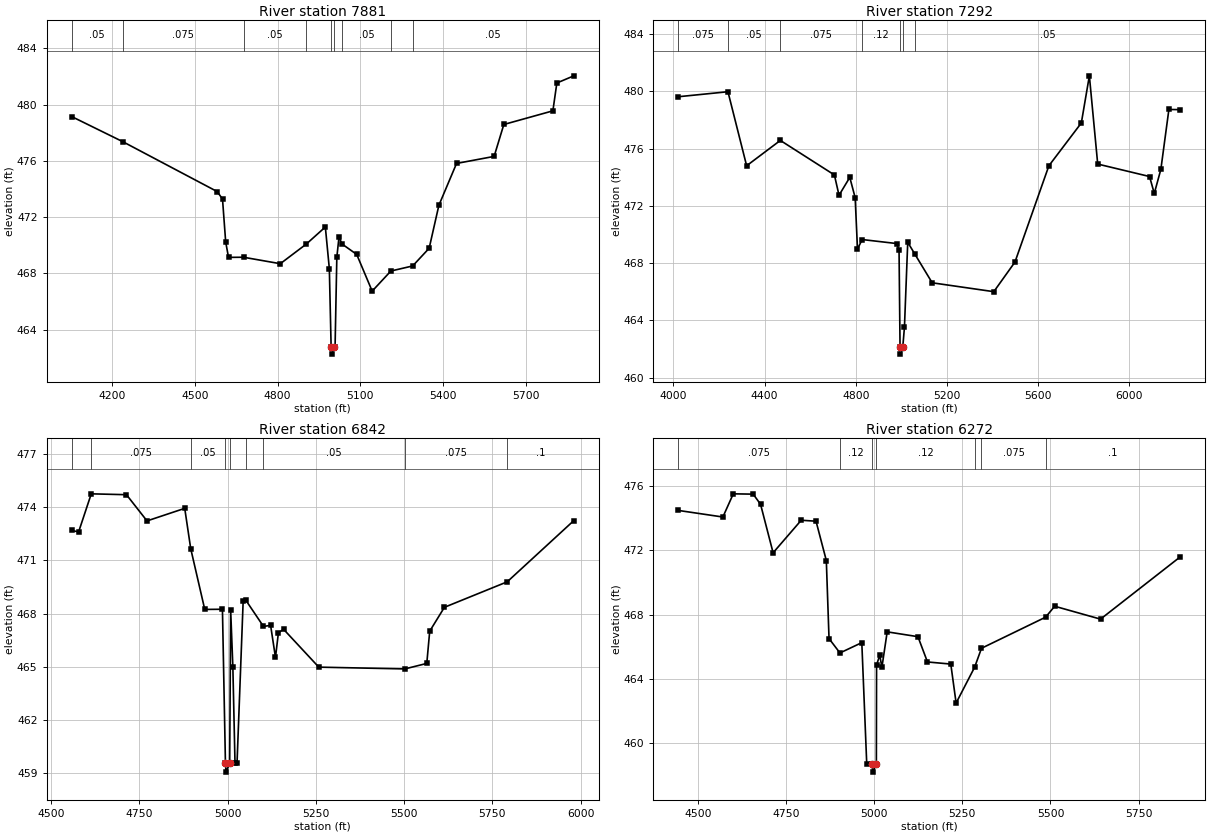
Type RM Length L Ch R = 1 ,7881    ,589,589,589
BEGIN DESCRIPTION:
COTTONWOOD BR AT DENTON 7.2
END DESCRIPTION:
XS GIS Cut Line= 3
      2426076.76       7041217.9      2426792.38      7041040.07
      2427645.25      7040369.03
#Sta/Elev= 30
  4052.5  479.14  4237.4  477.36  4580.3  473.81  4599.7  473.28  4611.2  470.23
  4621.5  469.13  4675.9  469.14  4809.5  468.68  4904.1  470.08    4973  471.29
  4987.5  468.33    4994  462.75  4995.7  462.25    5006  462.75  5008.3  462.75
  5014.7  469.14  5022.7   470.6  5032.9  470.09  5086.9  469.34    5143  466.73
  5210.9  468.16    5290  468.52  5349.9  469.78  5385.1  472.83  5449.3  475.81
  5585.7  476.31  5620.9  478.58    5799  479.55  5813.4  481.53  5875.1  482.04
#Mann= 9 ,-1 , 0
  4052.5     .05       0  4237.4    .075       0  4675.9     .05       0
  4904.1     .12       0    4994     .07       0    5006     .12       0
  5032.9     .05       0  5210.9     .12       0    5290     .05       0
Bank Sta=4994,5006
XS Rating Curve= 0 ,0
Exp/Cntr=0.3,0.1

Type RM Length L Ch R = 1 ,7292    ,450,450,450
BEGIN DESCRIPTION:
COTTONWOOD BR AT DENTON 7.0
END DESCRIPTION:
XS GIS Cut Line= 3
      2426112.65      7041562.52        2427079.        7041410.
      2428030.84      7040641.77
#Sta/Elev= 30
  4021.4  479.62  4239.4  479.97  4321.3   474.8  4469.1  476.57  4706.1  474.16
  4726.4  472.74  4773.6  473.99  4797.2  472.57  4807.4  468.98  4827.8  469.65
  4979.5  469.37  4989.6   468.9    4994  462.15  4995.7  461.65    5006  462.15
  5013.3  463.53  5027.7  469.46  5057.5  468.67  5134.9  466.63  5405.1  466.01
  5497.9  468.08  5646.6   474.8  5788.9  477.79  5824.1  481.08  5860.7  474.92
    6088  474.05  6108.8  472.87  6137.6  474.55  6172.8  478.73  6222.9  478.72
#Mann= 7 ,-1 , 0
  4021.4    .075       0  4239.4     .05       0  4469.1    .075       0
  4827.8     .12       0    4994     .07       0    5006     .12       0
  5057.5     .05       0
Bank Sta=4994,5006
XS Rating Curve= 0 ,0
Exp/Cntr=0.3,0.1

Type RM Length L Ch R = 1 ,6842    ,570,570,570
BEGIN DESCRIPTION:
COTTONWOOD BR AT DENTON 6.0
END DESCRIPTION:
XS GIS Cut Line= 3
      2426903.29      7042051.09      2427283.23      7041777.79
      2428043.12      7041201.21
#Sta/Elev= 30
  4558.8  472.69  4578.2  472.61    4614  474.76  4713.7  474.71  4771.9  473.23
  4878.7  473.94  4895.7  471.66  4935.4  468.23  4985.5  468.24    4994  459.54
  4995.7  459.04    5006  459.54  5008.8  468.19    5015  464.98  5021.1  459.54
  5026.8  459.54  5044.2  468.71  5052.1  468.74  5101.7  467.27  5121.9  467.33
  5135.7  465.52    5144  466.91  5158.6  467.11  5258.4  464.97    5502  464.87
  5564.2  465.18  5572.5     467  5614.1  468.35    5792  469.79  5980.7  473.25
#Mann= 9 ,-1 , 0
  4558.8     .05       0    4614    .075       0  4895.7     .05       0
    4994     .05       0    5006     .05       0  5052.1     .12       0
  5101.7     .05       0    5502    .075       0    5792      .1       0
Bank Sta=4994,5006
XS Rating Curve= 0 ,0
Exp/Cntr=0.3,0.1

Type RM Length L Ch R = 1 ,6272    ,496,496,496
BEGIN DESCRIPTION:
COTTONWOOD BR AT DENTON 5.0
END DESCRIPTION:
XS GIS Cut Line= 3
       2427269.9      7042577.66      2427583.18      7042141.06
      2428073.07      7041401.22
#Sta/Elev= 30
  4443.8  474.47  4570.5  474.06    4600   475.5  4656.5  475.48  4677.4  474.85
    4713  471.84  4792.8  473.86  4834.8   473.8    4864  471.36  4871.7  466.51
  4902.7  465.62  4964.7  466.26  4978.7  458.73    4994  458.72  4995.7  458.22
    5006  458.72  5006.6  464.88  5015.7  465.48  5021.7  464.72  5036.7  466.93
    5124  466.63    5151  465.06  5217.2  464.93  5232.3  462.51    5285  464.74
  5304.3  465.91  5486.2  467.84    5512  468.52  5642.1  467.72  5868.5  471.59
#Mann= 7 ,-1 , 0
  4443.8    .075       0  4902.7     .12       0    4994     .07       0
    5006     .12       0    5285     .05       0  5304.3    .075       0
  5486.2      .1       0
Bank Sta=4994,5006
XS Rating Curve= 0 ,0
Exp/Cntr=0.3,0.1