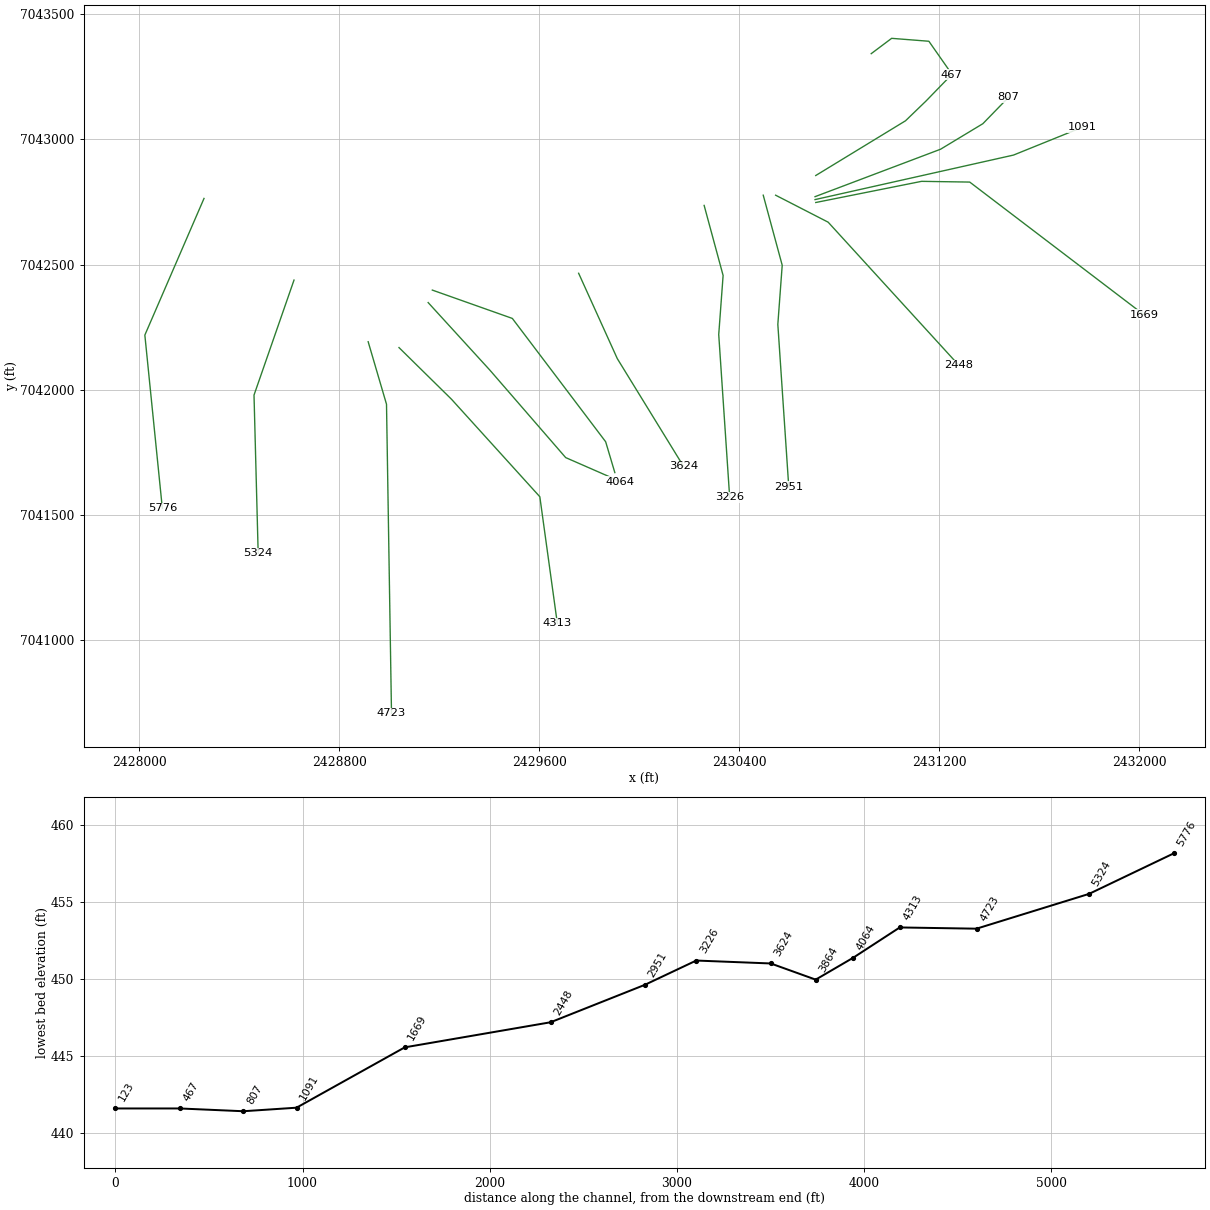
HEC-RAS study COTTONWOOD BR AT DENTON.prj: COTTONWOOD BR AT DENTON Base Level Engineering

--- COTTONWOOD BR AT DENTON.g01 (geometry) --- (continued)

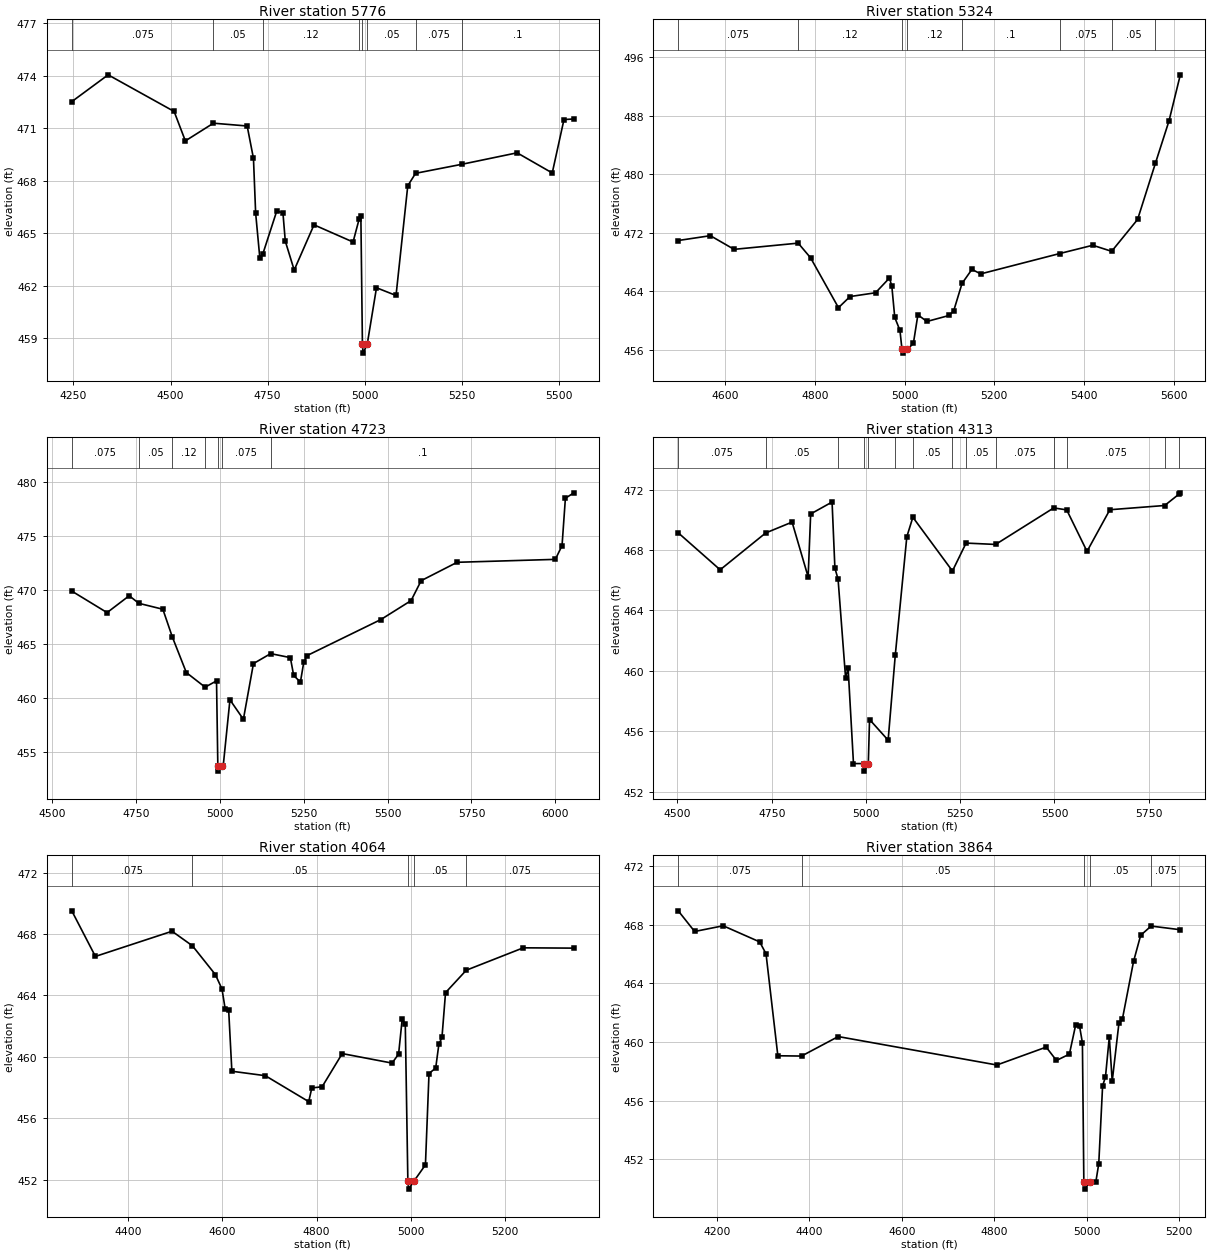
Type RM Length L Ch R = 1 ,5776    ,452,452,452
BEGIN DESCRIPTION:
COTTONWOOD BR AT DENTON 4.0
END DESCRIPTION:
XS GIS Cut Line= 3
      2428259.72      7042764.27       2428023.1      7042217.72
      2428093.07      7041524.72
#Sta/Elev= 30
  4245.9  472.51  4339.5  474.04  4509.3  471.95  4538.2  470.27  4610.5  471.28
  4697.3  471.12  4713.5  469.27  4719.1  466.15    4730  463.56  4737.9  463.84
  4773.6  466.28  4789.4  466.15  4795.4  464.55  4818.3   462.9  4869.3  465.48
  4969.8   464.5  4985.8  465.84  4989.9  465.98  4993.9  458.66  4995.6  458.16
  5006.2  458.66  5030.1  461.89  5080.4  461.45  5110.6  467.71  5130.7  468.42
  5250.8  468.94    5392  469.59  5482.4  468.44  5512.6  471.49    5538  471.52
#Mann= 8 ,-1 , 0
  4245.9    .075       0  4610.5     .05       0  4737.9     .12       0
  4985.8     .05       0  4993.9     .05       0  5006.2     .05       0
  5130.7    .075       0  5250.8      .1       0
Bank Sta=4993.9,5006.2
XS Rating Curve= 0 ,0
Exp/Cntr=0.3,0.1

Type RM Length L Ch R = 1 ,5324    ,601,601,601
BEGIN DESCRIPTION:
COTTONWOOD BR AT DENTON 3.0
END DESCRIPTION:
XS GIS Cut Line= 3
      2428619.67       7042437.7      2428459.69      7041977.76
      2428476.35      7041344.75
#Sta/Elev= 30
  4494.7  470.94  4566.4   471.6  4619.3  469.73  4762.3  470.58    4790  468.57
  4852.2  461.75    4878  463.27  4934.9  463.79    4966  465.81  4971.3  464.66
  4977.8  460.41  4989.4  458.64  4993.9  456.03  4995.6  455.53  5006.2  456.03
  5019.4  456.89  5029.4  460.77  5049.5  459.86  5099.5  460.69  5109.5  461.36
  5127.9  465.07    5150  466.99  5169.5  466.37    5346  469.16  5419.6  470.29
  5461.7  469.46  5519.6  473.82  5559.5  481.54  5589.6  487.29  5614.9  493.61
#Mann= 8 ,-1 , 0
  4494.7    .075       0  4762.3     .12       0  4993.9     .05       0
  5006.2     .12       0  5127.9      .1       0    5346    .075       0
  5461.7     .05       0  5559.5    .075       0
Bank Sta=4993.9,5006.2
XS Rating Curve= 0 ,0
Exp/Cntr=0.3,0.1

Type RM Length L Ch R = 1 ,4723    ,410,410,410
BEGIN DESCRIPTION:
COTTONWOOD BR AT DENTON 2.0
END DESCRIPTION:
XS GIS Cut Line= 3
      2428916.27      7042191.09       2428989.6       7041941.1
      2429009.59      7040704.78
#Sta/Elev= 30
  4558.3  469.91  4663.6  467.92  4729.6  469.48  4758.1  468.78  4829.9  468.23
    4858  465.68  4899.9  462.38  4955.8  461.03  4989.9  461.61  4993.8  453.77
  4995.6  453.27  5006.2  453.77  5009.9  453.77  5029.9  459.86    5070  458.06
    5100  463.21  5151.4  464.13    5210  463.76    5220  462.11    5240   461.5
    5250  463.33    5260  463.95    5480  467.28    5570  469.03    5600  470.87
  5707.3  472.57  6000.1  472.84  6020.1  474.11  6030.1  478.49  6055.3  478.99
#Mann= 7 ,-1 , 0
  4558.3    .075       0  4758.1     .05       0    4858     .12       0
  4955.8    .075       0  4993.8     .07       0  5006.2    .075       0
  5151.4      .1       0
Bank Sta=4993.8,5006.2
XS Rating Curve= 0 ,0
Exp/Cntr=0.3,0.1

Type RM Length L Ch R = 1 ,4313    ,249,249,249
BEGIN DESCRIPTION:
COTTONWOOD BR AT DENTON 1.0
END DESCRIPTION:
XS GIS Cut Line= 4
      2429039.59      7042167.73      2429249.55       7041961.1
      2429602.82      7041571.16      2429672.78      7041064.82
#Sta/Elev= 30
    4502  469.14  4613.2  466.69  4733.9  469.13    4804  469.85  4846.6  466.22
  4853.3  470.39  4910.1  471.18  4917.6   466.8    4926  466.07  4945.9  459.54
  4952.7  460.16  4966.9  453.85  4993.8  453.85  4995.6  453.35  5006.2  453.85
  5009.5  456.77  5058.8   455.4  5077.7  461.02  5108.4  468.88  5124.4  470.17
  5229.4  466.61  5265.6  468.46  5343.9  468.37  5498.1  470.79  5532.5  470.66
  5586.4  467.91    5647  470.67  5792.4  470.95  5829.7  471.69  5833.9  471.79
#Mann= 14 ,-1 , 0
    4502    .075       0  4733.9     .05       0    4926    .075       0
  4993.8     .05       0  5006.2    .075       0  5077.7    .075       0
  5124.4     .05       0  5229.4    .075       0  5265.6     .05       0
  5343.9    .075       0  5498.1     .05       0  5532.5    .075       0
  5792.4     .05       0  5829.7    .075       0
Bank Sta=4993.8,5006.2
XS Rating Curve= 0 ,0
Exp/Cntr=0.3,0.1

Type RM Length L Ch R = 1 ,4064    ,200,200,200
BEGIN DESCRIPTION:
COTTONWOOD BR AT DENTON 0.8
END DESCRIPTION:
XS GIS Cut Line= 5
      2429156.22      7042347.71      2429402.86      7042077.74
      2429706.14       7041727.8      2429919.43      7041634.49
      2429922.79      7041631.13
#Sta/Elev= 30
    4280  469.51  4330.2  466.54    4493  468.18  4536.3  467.23  4584.9  465.36
    4599  464.42  4605.8  463.12  4613.2  463.06    4620  459.06  4691.1  458.77
  4783.2  457.08  4789.8  457.97  4811.7  458.05  4854.4  460.21  4960.3  459.59
  4974.1  460.18  4981.7  462.44  4988.3  462.14  4993.8  451.88  4995.6  451.38
  5006.2  451.88  5031.1  452.96  5038.7  458.91  5052.9  459.27  5059.6  460.81
  5066.2  461.26  5073.8  464.18  5117.8  465.64  5238.9   467.1  5346.3  467.08
#Mann= 5 ,-1 , 0
    4280    .075       0  4536.3     .05       0  4993.8     .05       0
  5006.2     .05       0  5117.8    .075       0
Bank Sta=4993.8,5006.2
XS Rating Curve= 0 ,0
Exp/Cntr=0.3,0.1

Type RM Length L Ch R = 1 ,3864    ,240,240,240
BEGIN DESCRIPTION:
COTTONWOOD BR AT DENTON 0.7
END DESCRIPTION:
XS GIS Cut Line= 4
      2429172.86       7042397.7      2429492.84      7042284.37
      2429866.11      7041791.13      2429902.78      7041667.78
#Sta/Elev= 30
  4115.9  468.95  4151.4  467.54  4213.2  467.93  4292.2  466.83  4305.9  466.02
  4331.5  459.06  4382.8  459.04  4462.2  460.37  4805.5  458.43  4912.3  459.65
  4934.5  458.74  4962.5  459.17  4976.1  461.16  4984.4   461.1  4990.7  459.95
  4993.8  450.46  4995.6  449.96  5006.2  450.46  5019.8  450.46  5026.1   451.7
  5034.4  457.01  5040.6  457.61  5048.9  460.34  5055.2  457.32  5069.7  461.28
  5077.1  461.54  5101.4   465.5  5116.8  467.28  5139.4  467.91  5202.6  467.66
#Mann= 5 ,-1 , 0
  4115.9    .075       0  4382.8     .05       0  4993.8    .033       0
  5006.2     .05       0  5139.4    .075       0
Bank Sta=4993.8,5006.2
XS Rating Curve= 0 ,0
Exp/Cntr=0.3,0.1

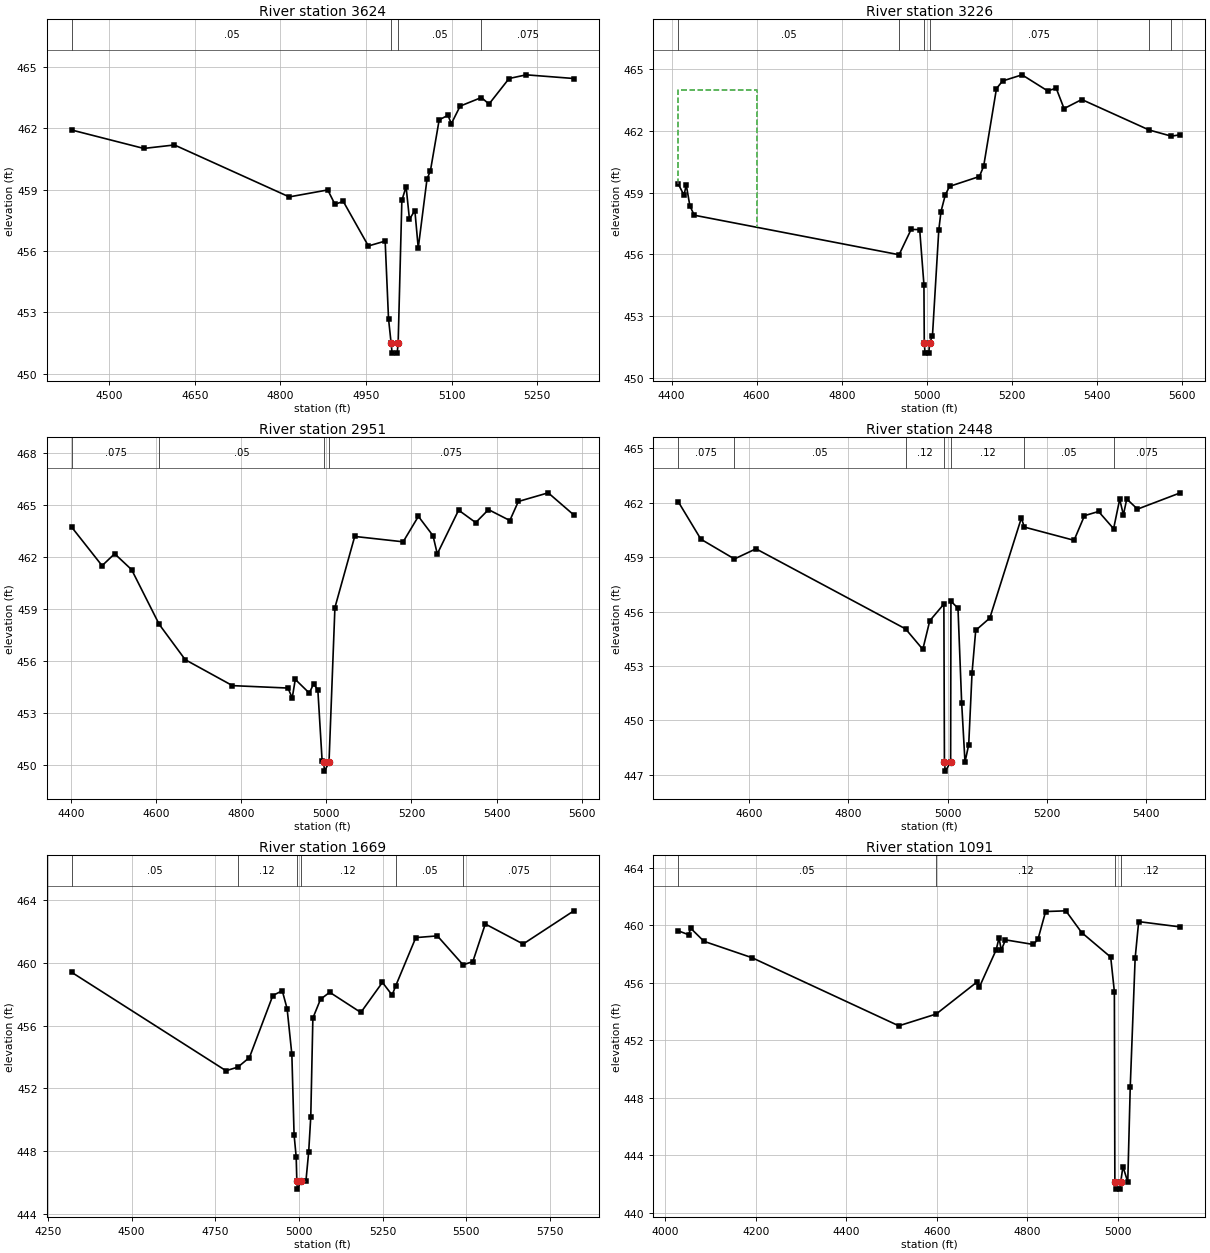
Type RM Length L Ch R = 1 ,3624    ,398,398,398
BEGIN DESCRIPTION:
COTTONWOOD BR AT DENTON 0.6
END DESCRIPTION:
XS GIS Cut Line= 3
      2429758.02      7042464.97       2429912.7      7042123.51
      2430177.22      7041693.29
#Sta/Elev= 30
  4434.2  461.92  4560.4  461.02  4614.1  461.19  4815.3  458.65  4882.8  458.99
  4895.4  458.29    4910  458.43    4954  456.25  4983.4  456.49  4989.3   452.7
  4993.8  451.51  4995.6  451.01  5004.5  451.01  5006.2  451.51  5012.7  458.48
  5020.1  459.15    5026  457.56  5035.5  457.98  5041.4  456.15  5056.8  459.53
  5062.7  459.92  5078.1  462.42  5093.5  462.64  5099.4  462.23  5114.8  463.09
  5152.1  463.51  5165.4  463.19  5200.6  464.44  5230.7  464.62  5314.1  464.44
#Mann= 4 ,-1 , 0
  4434.2     .05       0  4993.8    .033       0  5006.2     .05       0
  5152.1    .075       0
Bank Sta=4993.8,5006.2
XS Rating Curve= 0 ,0
Exp/Cntr=0.3,0.1

Type RM Length L Ch R = 1 ,3226    ,275,275,275
BEGIN DESCRIPTION:
COTTONWOOD BR AT DENTON 0.55
END DESCRIPTION:
XS GIS Cut Line= 4
      2430259.95      7042736.34      2430335.83      7042456.18
      2430318.32      7042219.81      2430362.09      7041569.05
#Sta/Elev= 30
  4415.8  459.42  4429.4  458.87  4434.6  459.38  4443.1  458.36  4453.4   457.9
  4934.6  455.98  4962.9  457.21    4983   457.2    4993  454.53  4993.8   451.7
  4995.6   451.2  5004.5   451.2  5006.2   451.7    5013  452.03  5027.9  457.18
  5033.1  458.08  5043.1  458.88  5053.1   459.3  5123.3  459.78  5133.3  460.28
  5163.4  464.05  5177.6  464.42  5223.5  464.72  5283.6  463.94  5303.7  464.07
  5322.2  463.08  5363.8  463.52    5522  462.04  5574.4  461.74  5595.3  461.81
#Mann= 6 ,-1 , 0
  4415.8     .05       0  4934.6    .075       0  4993.8     .07       0
  5006.2    .075       0    5522      .1       0  5574.4    .075       0
#XS Ineff= 2 , 0
       0    4600     464               0
Permanent Ineff=
       F       F
Bank Sta=4993.8,5006.2
XS Rating Curve= 0 ,0
Exp/Cntr=0.3,0.1

Type RM Length L Ch R = 1 ,2951    ,503,503,503
BEGIN DESCRIPTION:
COTTONWOOD BR AT DENTON 0.5
END DESCRIPTION:
XS GIS Cut Line= 4
      2430496.31      7042777.22      2430572.19      7042497.03
      2430554.69      7042260.66      2430598.46      7041609.93
#Sta/Elev= 30
  4401.9  463.71  4473.1  461.49  4502.6  462.18  4542.5  461.26  4607.3   458.1
  4668.4  456.06  4779.4  454.56  4909.8  454.42  4919.8  453.85    4927  454.92
  4959.9  454.13    4970  454.66    4980  454.31    4990  450.23  4993.8  450.12
  4995.6  449.62  5006.2  450.12  5020.1  459.07  5066.6  463.18  5180.4  462.87
  5216.2  464.34  5250.6  463.22  5260.6  462.17  5310.7   464.7  5350.8  463.98
  5380.9  464.73    5431   464.1    5451   465.2  5521.2   465.7  5581.4  464.42
#Mann= 4 ,-1 , 0
  4401.9    .075       0  4607.3     .05       0  4993.8     .07       0
  5006.2    .075       0
Bank Sta=4993.8,5006.2
XS Rating Curve= 0 ,0
Exp/Cntr=0.3,0.1

Type RM Length L Ch R = 1 ,2448    ,779,779,779
BEGIN DESCRIPTION:
COTTONWOOD BR AT DENTON 0.4
END DESCRIPTION:
XS GIS Cut Line= 3
      2430545.96      7042777.16      2430756.04       7042669.2
       2431278.4      7042097.23
#Sta/Elev= 30
  4457.9  462.06  4503.5  459.99    4571   458.9  4614.4  459.46  4915.6  455.04
  4950.3  453.91  4964.3  455.49  4992.7  456.41  4993.8  447.69  4995.5  447.19
  5006.3  447.69  5006.9  456.57  5021.1  456.18  5028.5  450.96  5035.2  447.69
  5042.7  448.65  5049.4  452.61  5056.8  454.96  5085.2  455.64  5148.7  461.16
  5154.6  460.66  5254.8  459.93  5275.8  461.29  5304.1  461.52  5334.4  460.57
  5346.7   462.2  5354.1  461.33  5360.9  462.21  5382.5  461.65  5468.7  462.55
#Mann= 7 ,-1 , 0
  4457.9    .075       0    4571     .05       0  4915.6     .12       0
  4993.8     .07       0  5006.3     .12       0  5154.6     .05       0
  5334.4    .075       0
Bank Sta=4993.8,5006.3
XS Rating Curve= 0 ,0
Exp/Cntr=0.3,0.1

Type RM Length L Ch R = 1 ,1669    ,578,578,578
BEGIN DESCRIPTION:
COTTONWOOD BR AT DENTON 0.3
END DESCRIPTION:
XS GIS Cut Line= 4
      2430706.41      7042747.99      2431129.56      7042832.62
      2431322.16       7042829.7       2432019.6      7042298.59
#Sta/Elev= 30
    4321   459.4    4782  453.12  4817.4  453.35    4852  453.96    4922  457.92
  4950.2  458.23  4964.7  457.08  4978.9  454.16  4985.5  449.04  4991.8  447.62
  4993.8  446.06  4995.5  445.56  5006.3  446.06  5020.9  446.06  5029.2  447.94
  5035.4  450.18  5041.7  456.48  5064.5  457.68    5092  458.13  5185.1  456.84
  5249.6  458.76  5278.6  457.95  5289.3  458.54  5349.4  461.62  5413.8  461.73
  5490.7  459.88  5519.9  460.09  5557.1  462.49  5670.2  461.21  5821.8  463.33
#Mann= 6 ,-1 , 0
    4321     .05       0  4817.4     .12       0  4993.8     .07       0
  5006.3     .12       0  5289.3     .05       0  5490.7    .075       0
Bank Sta=4993.8,5006.3
XS Rating Curve= 0 ,0
Exp/Cntr=0.3,0.1

Type RM Length L Ch R = 1 ,1091    ,284,284,284
BEGIN DESCRIPTION:
COTTONWOOD BR AT DENTON 0.1
END DESCRIPTION:
XS GIS Cut Line= 3
      2430703.55      7042759.67      2431497.24      7042937.67
      2431771.57      7043048.57
#Sta/Elev= 30
  4028.8  459.61  4051.5  459.34  4056.6  459.78  4085.6  458.88  4191.7  457.74
  4516.1     453  4598.7  453.82    4689  456.05  4694.2   455.7  4731.3  458.29
  4737.5  459.11  4742.6  458.27  4751.8  458.98  4813.3  458.66  4823.5  459.01
  4840.5  460.95  4885.2     461  4920.1  459.49  4984.3  457.78  4992.4  455.38
  4993.5  442.14  4995.4  441.64  5004.7  441.64  5006.5  442.14  5011.3  443.21
    5022  442.14  5027.5  448.77  5038.3   457.7  5046.1  460.25  5138.1  459.88
#Mann= 4 ,-1 , 0
  4028.8     .05       0  4598.7     .12       0  4993.5     .07       0
  5006.5     .12       0
Bank Sta=4993.5,5006.5
XS Rating Curve= 0 ,0
Exp/Cntr=0.3,0.1

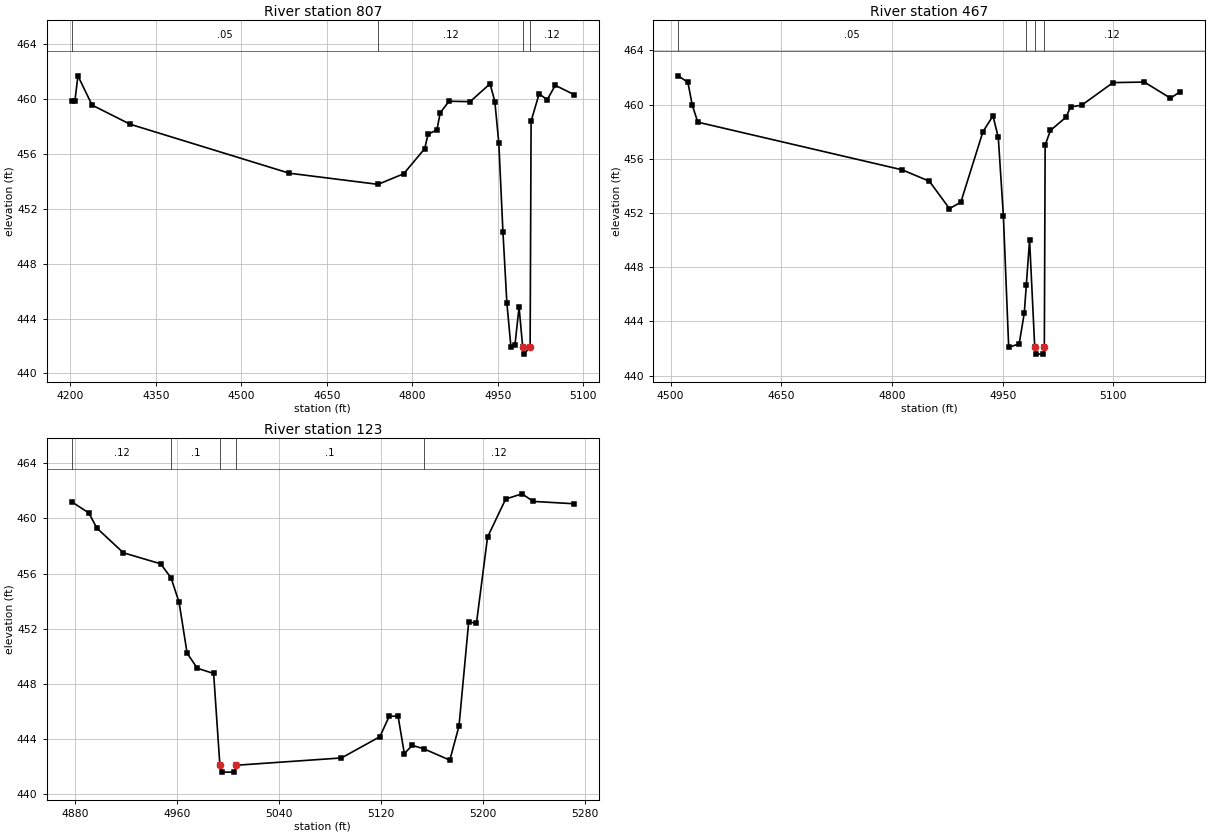
Type RM Length L Ch R = 1 ,807     ,340,340,340
BEGIN DESCRIPTION:
COTTONWOOD BR AT DENTON 0.07
END DESCRIPTION:
XS GIS Cut Line= 4
      2430703.52      7042771.34      2431205.43      7042961.01
      2431374.68      7043063.15      2431476.85      7043168.23
#Sta/Elev= 30
  4202.4  459.81  4207.8  459.81  4213.2  461.67    4238  459.54  4304.5  458.15
  4584.1  454.58  4739.7  453.77  4784.7  454.54  4821.6  456.37  4827.4  457.42
  4842.9  457.73  4848.8  458.98  4864.3  459.82  4901.2  459.79  4936.2  461.09
  4944.6   459.8  4951.6  456.76  4958.8  450.31  4965.7  445.14  4972.9  441.91
  4979.9  442.09  4987.1  444.83  4993.5  441.91  4995.4  441.41  5006.5  441.91
  5008.2  458.37  5022.3  460.36  5036.5  459.93  5050.6  460.98  5083.2  460.31
#Mann= 4 ,-1 , 0
  4202.4     .05       0  4739.7     .12       0  4993.5     .07       0
  5006.5     .12       0
Bank Sta=4993.5,5006.5
XS Rating Curve= 0 ,0
Exp/Cntr=0.3,0.1

Type RM Length L Ch R = 1 ,467     ,344,344,344
BEGIN DESCRIPTION:
COTTONWOOD BR AT DENTON 0.04
END DESCRIPTION:
XS GIS Cut Line= 4
       2430706.4      7042855.94      2431065.36      7043074.82
      2431147.07      7043153.61      2431249.23       7043258.7
#Sta/Elev= 30
  4510.3  462.13  4523.4  461.65  4529.3  459.97  4536.8  458.71  4813.9  455.19
  4850.7  454.35  4877.9  452.33  4893.3   452.8  4923.3  458.01  4936.9  459.17
  4944.1  457.58    4951  451.78  4958.2  442.09  4972.4  442.35  4979.3  444.61
  4982.1  446.71  4986.5  450.02  4993.5  442.09  4995.4  441.59  5004.7  441.59
  5006.5  442.09  5007.6  457.02  5014.8   458.1  5035.9  459.08  5042.1  459.84
  5057.1  459.96  5099.6  461.63    5142  461.67  5177.5  460.48  5190.8  460.97
#Mann= 4 ,-1 , 0
  4510.3     .05       0  4982.1     .12       0  4993.5     .07       0
  5006.5     .12       0
Bank Sta=4993.5,5006.5
XS Rating Curve= 0 ,0
Exp/Cntr=0.3,0.1

Type RM Length L Ch R = 1 ,123     ,0,0,0
BEGIN DESCRIPTION:
COTTONWOOD BR AT DENTON 0.01
END DESCRIPTION:
XS GIS Cut Line= 4
      2430928.19      7043343.27      2431009.92      7043404.57
      2431158.74       7043392.9      2431240.43      7043276.19
#Sta/Elev= 30
  4877.3  461.21  4890.7   460.4    4897   459.3  4917.8  457.51    4947  456.71
  4955.2  455.69  4961.5  453.91  4967.8  450.22  4975.8  449.13  4988.6  448.75
  4993.5  442.09  4995.4  441.59  5004.7  441.59  5006.5  442.09  5088.9  442.62
    5119  444.16  5126.4  445.65  5133.3  445.65  5138.2  442.94  5144.5  443.53
  5153.6  443.28  5173.9  442.46  5181.1  444.94  5188.7  452.49  5194.8   452.4
  5203.5  458.65  5217.7  461.41  5230.6  461.79  5239.3  461.24  5271.2  461.07
#Mann= 5 ,-1 , 0
  4877.3     .12       0  4955.2      .1       0  4993.5     .07       0
  5006.5      .1       0  5153.6     .12       0
Bank Sta=4993.5,5006.5
XS Rating Curve= 0 ,0
Exp/Cntr=0.3,0.1

Chan Stop Cuts=-1
Use User Specified Reach Order=0
Composite Channel Slope=5