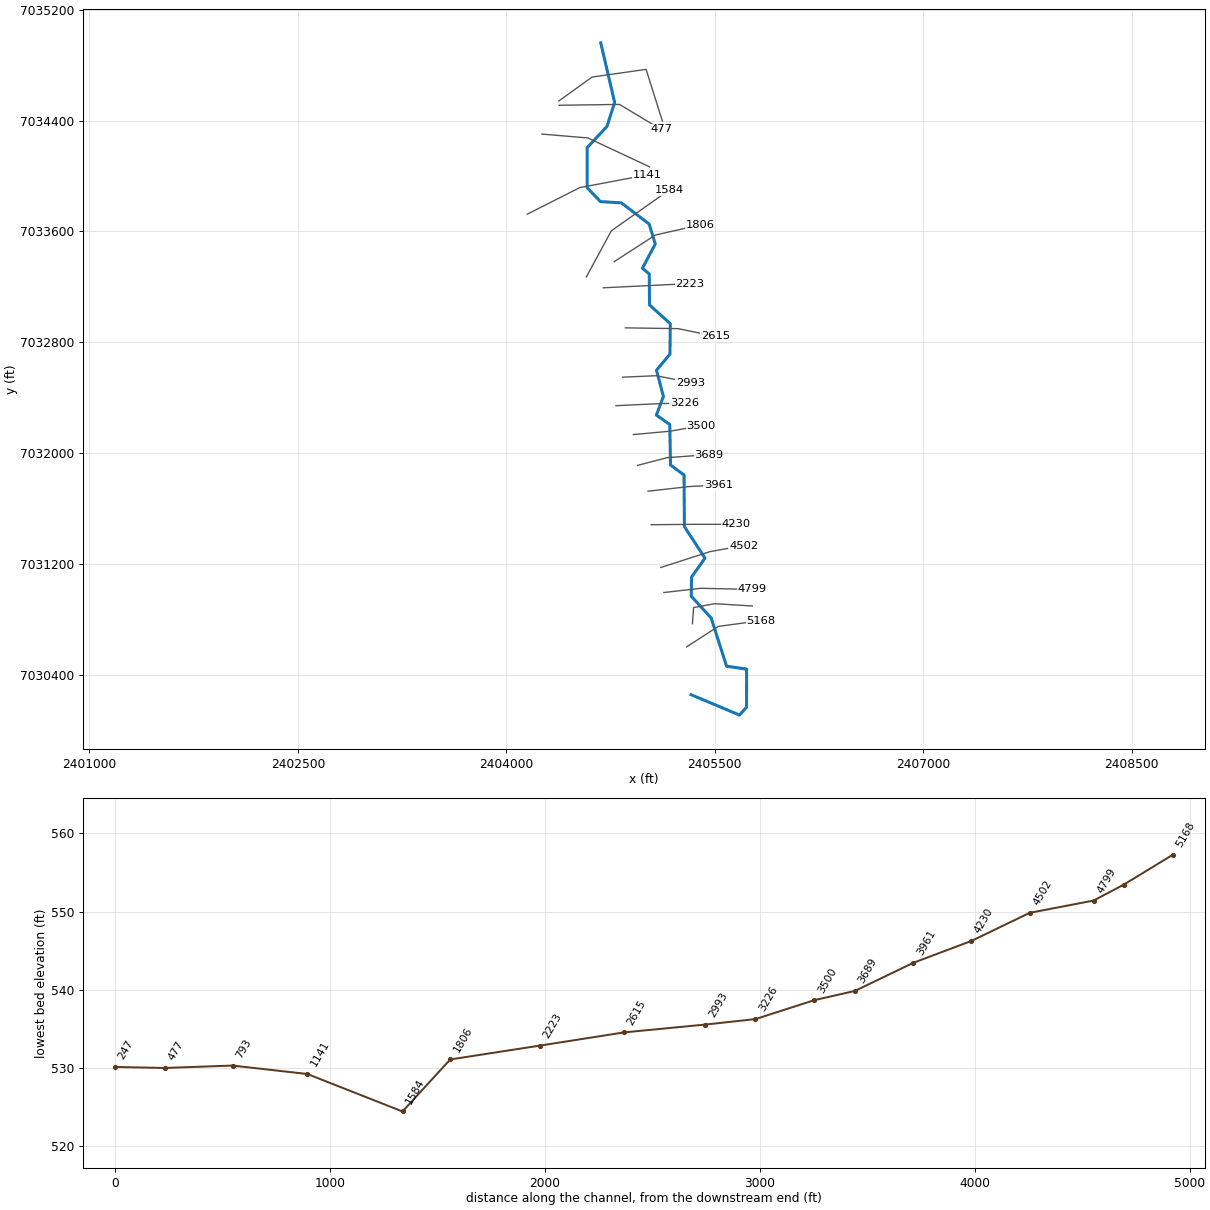
--- Cable Branch.prj (project) ---

Proj Title=Cable Branch Base Level Engineering
Current Plan=p01
Default Exp/Contr=0.3,0.1
English Units
Geom File=g01
Flow File=f01
Plan File=p01
Y Axis Title=Elevation
X Axis Title(PF)=Main Channel Distance
X Axis Title(XS)=Station
BEGIN DESCRIPTION:
Cable Branch
END DESCRIPTION:
DSS Export Rating Curves= 0
DSS Export Rating Curve Sorted= 0
DSS Export Volume Flow Curves= 0
DXF OffsetX= 0
DXF OffsetY= 0
DXF ScaleX= 1
DXF ScaleY= 10

--- Cable Branch.p01 (plan) ---

Plan Title=Multiple Run
Program Version=4.10
Short Identifier=Multiple
Geom File=g01
Flow File=f01
Subcritical Flow
K Sum by GR= 0
Std Step Tol= 0.01
Critical Tol= 0.01
Num of Std Step Trials= 20
Max Error Tol= 0.3
Flow Tol Ratio= 0.001
Split Flow NTrial= 30
Split Flow Tol= 0.02
Split Flow Ratio= 0.02
Log Output Level= 0
Friction Slope Method= 1
Unsteady Friction Slope Method= 2
Unsteady Bridges Friction Slope Method= 1
Parabolic Critical Depth
Global Vel Dist= 1 , 1 , 1
Global Log Level= 0
CheckData=True
Encroach Param=-1 ,0,0, 0
BEGIN DESCRIPTION:
Multiple Run
END DESCRIPTION:
Computation Interval=1HOUR
Output Interval=1HOUR
Run HTab= 0
Run UNet= 0
Run PostProcess= 0
Run WQNet= 0
UNET Theta= 1
UNET Theta Warmup= 1
UNET ZTol= 0.02
UNET ZSATol= 0.05
UNET MxIter= 20
UNET MaxInSteps= 0
UNET DtIC= 0
UNET DtMin= 0
UNET MaxCRTS= 20
UNET WFStab= 2
UNET SFStab= 1
UNET WFX= 1
UNET SFX= 1
UNET DSS MLevel= 4
UNET DZMax Abort= 100
UNET Convert EG Bridges= 0
UNET Use Existing IB Tables=-1
UNET Froude Reduction=False
UNET Froude Limit= 1
UNET Froude Power= 10
UNET Time Slicing=0,0, 5
UNET Junction Losses=0
Instantaneous Interval=1HOUR
Write IC File= 0
Write IC File at Sim End=0
Echo Input=False
Echo Parameters=False
Echo Output=False
Write Detailed= 0
WQ AD Non Conservative
WQ ULTIMATE=-1
WQ Max Comp Step=1HOUR
WQ Output Interval=15MIN
WQ Output Selected Increments= 0
WQ Output face flow=0
WQ Output face velocity=0
WQ Output face area=0
WQ Output face dispersion=0
WQ Output cell volume=0
WQ Output cell surface area=0
WQ Output cell continuity=0
WQ Output cumulative cell continuity=0
WQ Output face conc=0
WQ Output face dconc_dx=0
WQ Output face courant=0
WQ Output face peclet=0
WQ Output face adv mass=0
WQ Output face disp mass=0
WQ Output cell mass=0
WQ Output cell source sink temp=0
WQ Output cell source sink nsm=0
WQ Output MaxMinRange=-1
WQ Daily Max Min Mean=-1
WQ Daily Range=0
WQ Daily Time=0
WQ Create Restart=0
WQ Fixed Restart=0
WQ System Summary=0
WQ Use Fixed Temperature=0
Sorting and Armoring Iterations= 10
XS Update Threshold= 0.02
Hydraulics Update Threshold= 0.02
Energy Slope Method= 1
Volume Change Method= 0
XS Weighting Method= 0
Number of US Weighted Cross Sections= 1
Number of DS Weighted Cross Sections= 1
Upstream XS Weight=0.25
Main XS Weight=0.5
Downstream XS Weight=0.25
Number of DS XS's Weighted with US Boundary= 1
Upstream Boundary Weight= 1
Weight of XSs Associated with US Boundary= 0
Number of US XS's Weighted with DS Boundary= 1
Downstream Boundary Weight= 0.5
Weight of XSs Associated with DS Boundary= 0.5
Sediment Output Level= 4
Mass or Volume Output= 0
Output Increment Type= 1
Profile and TS Output Increment= 10
XS Output Flag= 0
XS Output Increment= 10
Disregard all LS=0
Disregard all Conn=0
Disregard all Breaches=0
Disregard all Pumps=0

--- Cable Branch.f01 (steady flow) ---

Flow Title=Multiple
Number of Profiles=7
Profile Names=10-year,25-year,50-year,1pct_min,100-year,1pct_plu,500-year
River Rch & RM= Cable Branch,Reach-1,5168
     498     672     814     490     977    1949    1405
River Rch & RM= Cable Branch,Reach-1,2223
     502     675     815     489     975    1946    1394
Boundary for River Rch & Prof#=Cable Branch,Reach-1,1
Up Type=0
Dn Type=3
Dn Slope=0.005
Boundary for River Rch & Prof#=Cable Branch,Reach-1,2
Up Type=0
Dn Type=3
Dn Slope=0.005
Boundary for River Rch & Prof#=Cable Branch,Reach-1,3
Up Type=0
Dn Type=3
Dn Slope=0.005
Boundary for River Rch & Prof#=Cable Branch,Reach-1,4
Up Type=0
Dn Type=3
Dn Slope=0.005
Boundary for River Rch & Prof#=Cable Branch,Reach-1,5
Up Type=0
Dn Type=3
Dn Slope=0.005
Boundary for River Rch & Prof#=Cable Branch,Reach-1,6
Up Type=0
Dn Type=3
Dn Slope=0.005
Boundary for River Rch & Prof#=Cable Branch,Reach-1,7
Up Type=0
Dn Type=3
Dn Slope=0.005

--- Cable Branch.g01 (geometry) ---

Geom Title=Existing Conditions

River Reach=Cable Branch,Reach-1
Reach XY= 30
      2405329.00      7030260.00      2405677.61      7030113.03
      2405728.02      7030170.24      2405728.46      7030444.46
      2405584.42      7030465.18      2405473.54      7030812.66
      2405330.18      7030970.48      2405332.54      7031108.53
      2405428.98      7031244.59      2405280.92      7031471.95
      2405278.32      7031844.16      2405181.01      7031915.68
      2405175.52      7032208.74      2405079.25      7032276.02
      2405129.91      7032410.34      2405080.04      7032599.55
      2405176.93      7032715.86      2405179.33      7032935.21
      2405029.99      7033070.28      2405028.00      7033294.06
      2404978.67      7033334.97      2405071.47      7033509.99
      2405026.86      7033654.12      2404827.44      7033806.24
      2404676.53      7033815.46      2404581.05      7033915.84
      2404581.06      7034204.15      2404723.48      7034357.57
      2404779.10      7034530.10      2404679.00      7034960.00

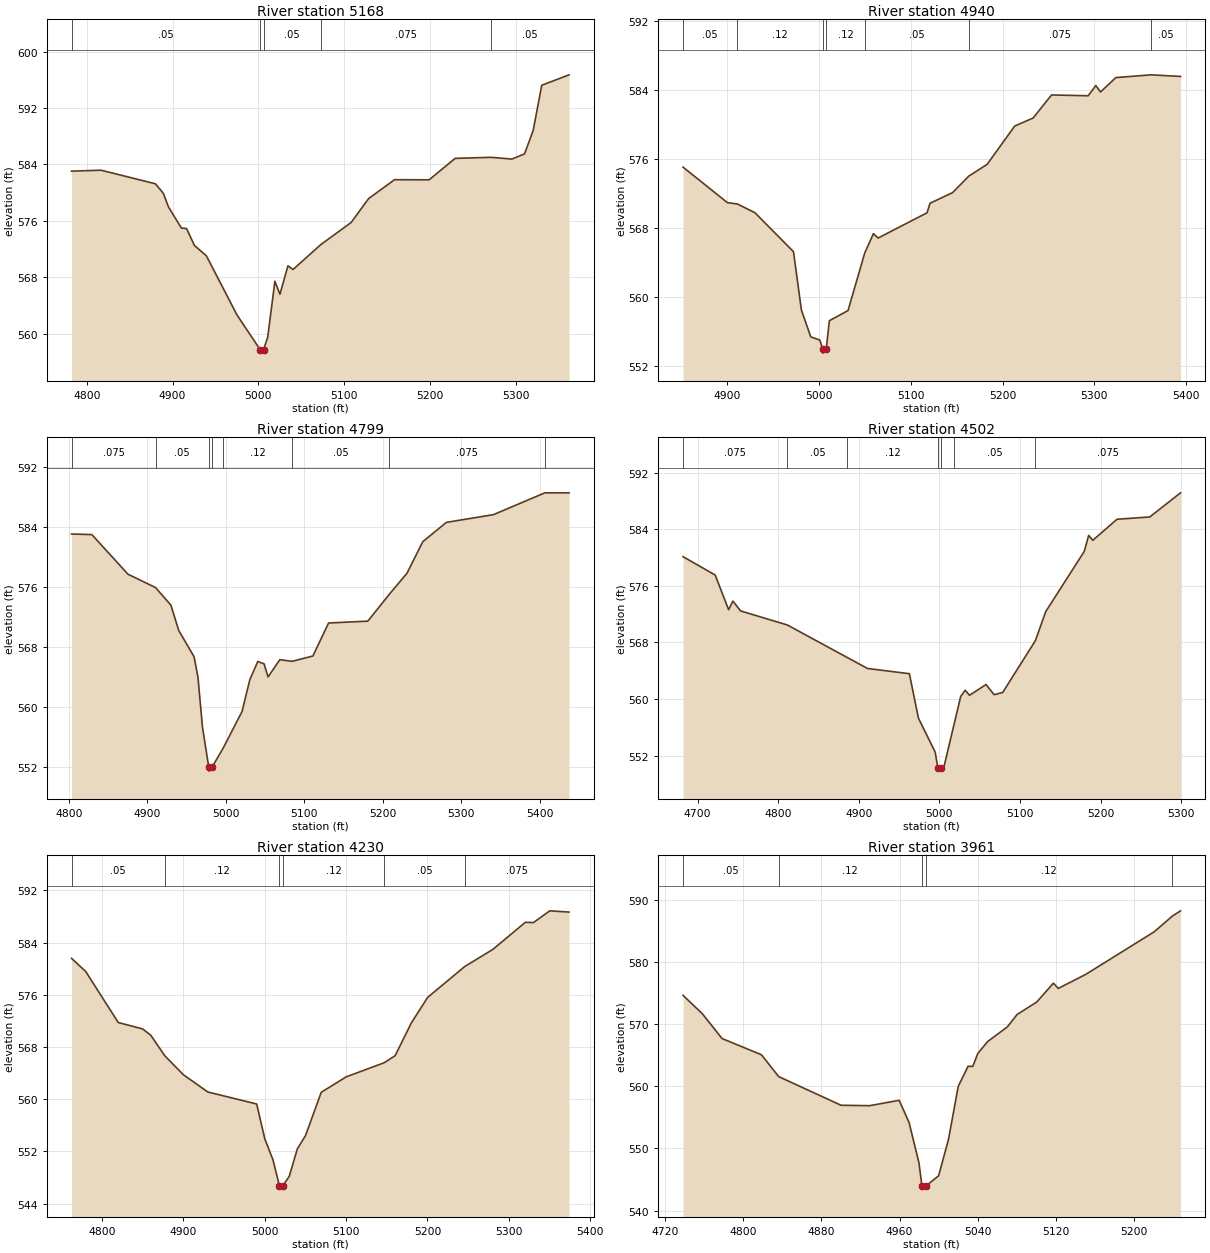
Type RM Length L Ch R = 1,5168,228,228,228
BEGIN DESCRIPTION:
Cable Branch 17.0
END DESCRIPTION:
XS GIS Cut Line= 3
      2405297.12      7030605.06      2405524.90      7030752.29
      2405830.46      7030793.95
#Sta/Elev= 30
  4782.3  583.05  4816.7  583.18  4880.0  581.26  4889.2  579.92  4895.2  577.99
  4910.3  574.98  4916.3  574.91  4925.5  572.51  4939.3  571.07  4975.0  562.68
  5002.0  557.76  5002.3  557.26  5006.0  557.76  5010.8  559.49  5019.2  567.44
  5025.1  565.60  5034.4  569.64  5040.3  569.11  5072.8  572.65  5108.1  575.78
  5128.3  579.15  5158.6  581.84  5198.9  581.82  5229.2  584.86  5271.1  585.01
  5295.2  584.76  5310.0  585.49  5320.1  588.81  5330.1  595.22  5361.9  596.70
#Mann=5,-1,0
  4782.3    0.05       0  5002.0    0.05       0  5006.0    0.05       0
  5072.8   0.075       0  5271.1    0.05       0
Bank Sta=5002,5006
Exp/Cntr=0.3,0.1

Type RM Length L Ch R = 1,4940,141,141,141
BEGIN DESCRIPTION:
Cable Branch 16.0
END DESCRIPTION:
XS GIS Cut Line= 4
      2405338.79      7030771.75      2405347.13      7030888.40
      2405499.90      7030916.18      2405769.36      7030899.51
#Sta/Elev= 30
  4851.8  575.05  4900.2  570.92  4911.0  570.77  4930.2  569.75  4972.2  565.22
  4980.8  558.45  4991.0  555.33  5000.9  554.96  5003.9  553.94  5004.2  553.44
  5007.9  553.94  5011.3  557.21  5031.6  558.38  5049.8  565.06  5059.3  567.32
  5064.4  566.81  5117.7  569.74  5121.0  570.85  5145.6  572.09  5163.2  574.00
  5183.2  575.37  5213.3  579.82  5233.3  580.75  5253.4  583.43  5293.4  583.34
  5301.7  584.53  5306.8  583.78  5323.5  585.45  5362.0  585.77  5394.0  585.58
#Mann=7,-1,0
  4851.8    0.05       0  4911.0    0.12       0  5003.9    0.07       0
  5007.9    0.12       0  5049.8    0.05       0  5163.2   0.075       0
  5362.0    0.05       0
Bank Sta=5003.9,5007.9
Exp/Cntr=0.3,0.1

Type RM Length L Ch R = 1,4799,297,297,297
BEGIN DESCRIPTION:
Cable Branch 15.0
END DESCRIPTION:
XS GIS Cut Line= 3
      2405133.24      7030996.73      2405399.90      7031027.29
      2405765.30      7031018.98
#Sta/Elev= 30
  4803.4  583.02  4829.3  582.94  4875.3  577.66  4910.4  575.88  4930.0  573.54
  4940.0  570.15  4959.5  566.66  4964.5  563.92  4970.2  557.29  4978.3  551.90
  4978.6  551.40  4982.3  551.90  4996.9  554.53  5020.6  559.34  5030.6  563.60
  5040.7  566.02  5048.7  565.71  5053.8  563.96  5068.8  566.26  5084.4  566.04
  5110.9  566.75  5130.9  571.15  5180.9  571.40  5208.2  574.97  5230.9  577.80
  5251.0  582.00  5281.0  584.57  5341.0  585.60  5406.5  588.51  5437.3  588.51
#Mann=8,-1,0
  4803.4   0.075       0  4910.4    0.05       0  4978.3    0.07       0
  4982.3    0.05       0  4996.9    0.12       0  5084.4    0.05       0
  5208.2   0.075       0  5406.5    0.05       0
Bank Sta=4978.3,4982.3
Exp/Cntr=0.3,0.1

Type RM Length L Ch R = 1,4502,272,272,272
BEGIN DESCRIPTION:
Cable Branch 14.0
END DESCRIPTION:
XS GIS Cut Line= 3
      2405111.05      7031177.30      2405463.79      7031291.17
      2405706.54      7031335.31
#Sta/Elev= 30
  4681.9  580.12  4721.8  577.53  4738.5  572.63  4743.8  573.85  4753.3  572.46
  4811.4  570.47  4886.0  565.86  4910.9  564.33  4962.8  563.59  4974.0  557.33
  4994.8  552.52  4998.1  550.33  4998.3  549.83  5002.1  550.33  5005.5  550.34
  5017.9  556.27  5026.5  560.38  5032.1  561.26  5037.4  560.54  5057.9  562.06
  5068.0  560.63  5078.6  560.94  5119.2  568.26  5132.0  572.36  5179.8  580.86
  5185.3  583.13  5190.4  582.43  5220.5  585.41  5261.1  585.73  5299.3  589.14
#Mann=7,-1,0
  4681.9   0.075       0  4811.4    0.05       0  4886.0    0.12       0
  4998.1    0.07       0  5002.1    0.12       0  5017.9    0.05       0
  5119.2   0.075       0
Bank Sta=4998.1,5002.1
Exp/Cntr=0.3,0.1

Type RM Length L Ch R = 1,4230,269,269,269
BEGIN DESCRIPTION:
Cable Branch 13.0
END DESCRIPTION:
XS GIS Cut Line= 3
      2405041.62      7031485.62      2405352.68      7031488.40
      2405652.71      7031488.40
#Sta/Elev= 30
  4762.9  581.58  4780.3  579.57  4820.3  571.75  4850.3  570.77  4860.3  569.79
  4877.3  566.68  4900.3  563.75  4930.3  561.11  4990.3  559.27  5000.3  553.93
  5010.3  550.73  5018.3  546.73  5018.5  546.23  5022.0  546.23  5022.3  546.73
  5030.3  548.18  5040.3  552.41  5050.3  554.43  5069.6  561.06  5100.3  563.43
  5146.9  565.59  5160.3  566.66  5180.3  571.69  5200.3  575.60  5246.0  580.34
  5280.3  582.94  5320.3  587.10  5330.3  587.06  5350.3  588.86  5374.0  588.67
#Mann=6,-1,0
  4762.9    0.05       0  4877.3    0.12       0  5018.3    0.07       0
  5022.3    0.12       0  5146.9    0.05       0  5246.0   0.075       0
Bank Sta=5018.3,5022.3
Exp/Cntr=0.3,0.1

Type RM Length L Ch R = 1,3961,272,272,272
BEGIN DESCRIPTION:
Cable Branch 12.0
END DESCRIPTION:
XS GIS Cut Line= 3
      2405019.36      7031727.28      2405313.79      7031760.62
      2405525.89      7031771.63
#Sta/Elev= 30
  4738.6  574.62  4758.4  571.65  4778.5  567.67  4818.8  565.06  4836.4  561.55
  4900.2  556.94  4929.5  556.87  4959.6  557.74  4969.7  554.18  4979.8  547.71
  4982.9  543.95  4983.1  543.45  4986.6  543.45  4986.9  543.95  4999.9  545.59
  5010.0  551.42  5020.0  559.97  5030.0  563.20  5034.9  563.20  5040.1  565.29
  5050.1  567.19  5070.2  569.54  5080.2  571.54  5100.2  573.53  5117.3  576.57
  5122.3  575.73  5150.3  577.98  5220.4  584.84  5239.0  587.37  5247.3  588.21
#Mann=5,-1,0
  4738.6    0.05       0  4836.4    0.12       0  4982.9    0.07       0
  4986.9    0.12       0  5239.0   0.075       0
Bank Sta=4982.9,4986.9
Exp/Cntr=0.3,0.1

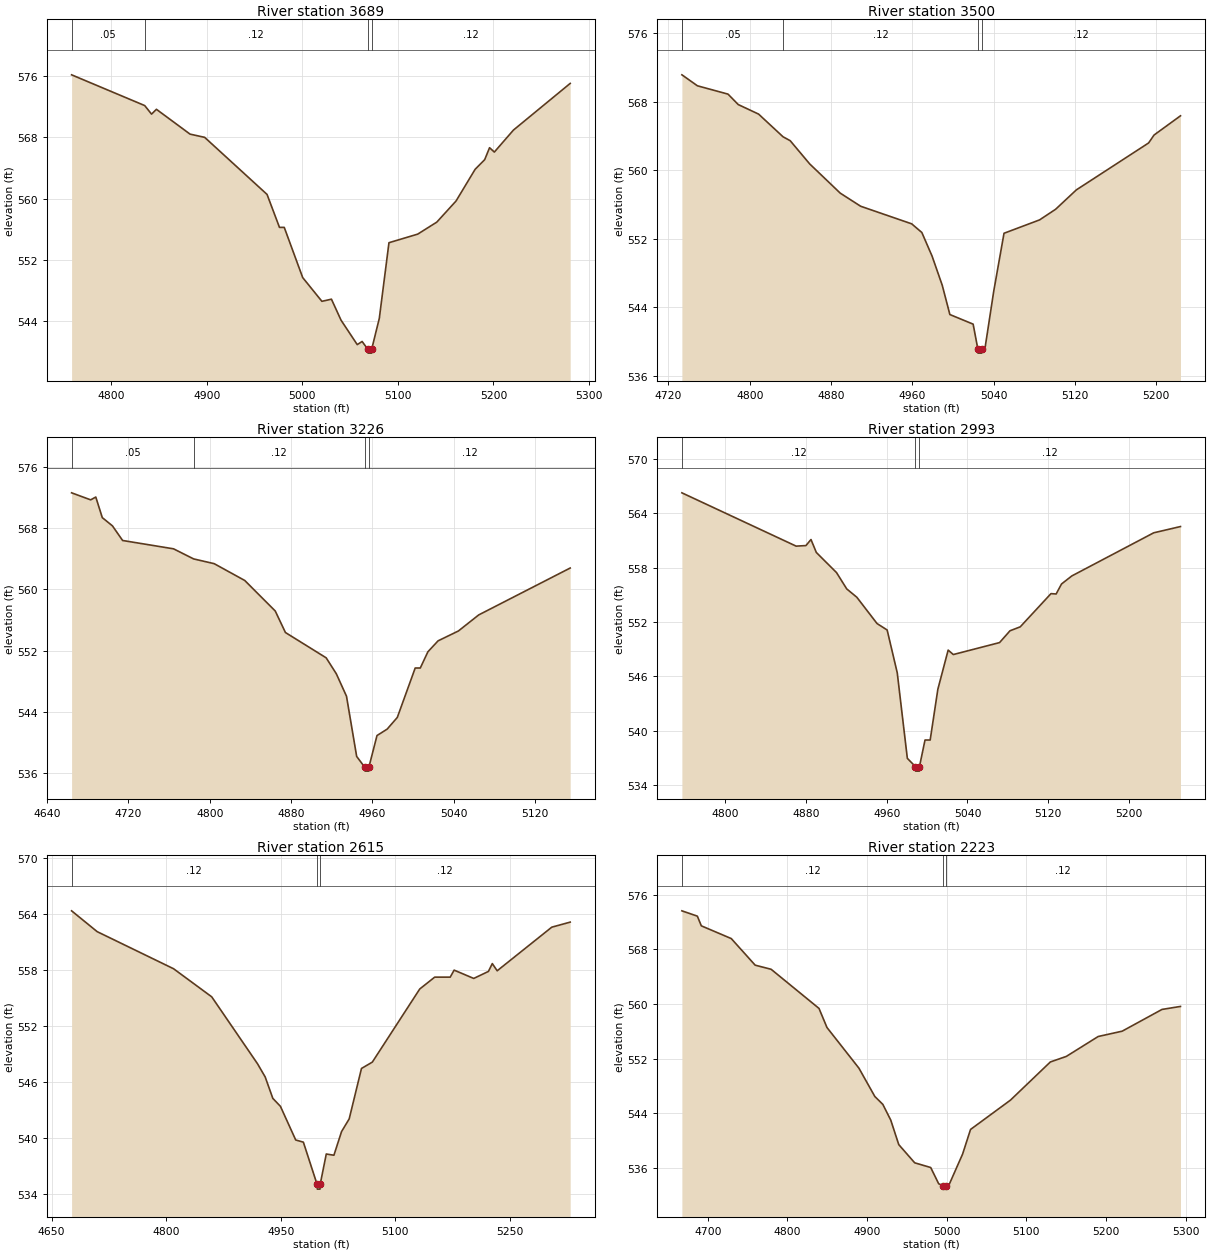
Type RM Length L Ch R = 1,3689,189,189,189
BEGIN DESCRIPTION:
Cable Branch 11.0
END DESCRIPTION:
XS GIS Cut Line= 3
      2404944.32      7031913.39      2405155.46      7031968.95
      2405458.22      7031991.17
#Sta/Elev= 30
  4758.4  576.17  4834.9  572.16  4842.1  571.04  4847.2  571.67  4882.4  568.43
  4897.7  568.01  4963.0  560.56  4976.0  556.26  4981.0  556.26  5000.3  549.71
  5020.4  546.61  5030.4  546.89  5040.4  544.16  5057.4  540.96  5062.5  541.37
  5068.5  540.35  5068.8  539.85  5072.3  539.85  5072.5  540.35  5080.5  544.39
  5090.6  554.26  5120.7  555.38  5140.7  556.95  5160.8  559.70  5180.8  563.84
  5190.8  565.10  5195.9  566.66  5200.9  566.09  5220.9  568.96  5280.3  575.05
#Mann=4,-1,0
  4758.4    0.05       0  4834.9    0.12       0  5068.5    0.07       0
  5072.5    0.12       0
Bank Sta=5068.5,5072.5
Exp/Cntr=0.3,0.1

Type RM Length L Ch R = 1,3500,274,274,274
BEGIN DESCRIPTION:
Cable Branch 10.0
END DESCRIPTION:
XS GIS Cut Line= 3
      2404913.77      7032135.61      2405179.00      7032160.00
      2405399.94      7032199.51
#Sta/Elev= 30
  4733.2  571.13  4733.6  571.10  4748.5  569.85  4778.6  568.88  4788.7  567.66
  4808.7  566.55  4832.8  563.90  4839.8  563.45  4859.0  560.74  4889.1  557.33
  4909.2  555.80  4959.4  553.75  4969.4  552.74  4979.5  549.98  4989.5  546.58
  4997.0  543.17  5019.9  542.05  5024.5  539.17  5024.7  538.67  5028.2  538.67
  5028.5  539.17  5031.5  539.18  5040.2  545.91  5050.3  552.65  5085.3  554.21
  5101.1  555.45  5121.5  557.71  5192.6  563.18  5198.0  564.11  5224.0  566.35
#Mann=5,-1,0
  4733.2   0.075       0  4733.6    0.05       0  4832.8    0.12       0
  5024.5    0.07       0  5028.5    0.12       0
Bank Sta=5024.5,5028.5
Exp/Cntr=0.3,0.1

Type RM Length L Ch R = 1,3226,233,233,233
BEGIN DESCRIPTION:
Cable Branch 9.0
END DESCRIPTION:
XS GIS Cut Line= 3
      2404788.81      7032343.95      2405129.00      7032360.00
      2405279.03      7032360.00
#Sta/Elev= 30
  4664.1  572.63  4682.9  571.71  4687.9  572.08  4694.3  569.39  4704.3  568.31
  4714.3  566.40  4764.4  565.31  4784.2  563.99  4804.4  563.37  4834.5  561.17
  4864.5  557.18  4874.5  554.37  4914.6  551.06  4924.6  548.97  4934.6  546.04
  4944.6  538.17  4952.6  536.75  4952.9  536.25  4956.4  536.25  4956.6  536.75
  4964.6  540.90  4974.6  541.74  4984.6  543.27  5002.2  549.73  5007.2  549.73
  5014.7  551.85  5024.7  553.28  5044.7  554.57  5064.7  556.67  5154.7  562.80
#Mann=4,-1,0
  4664.1    0.05       0  4784.2    0.12       0  4952.6    0.07       0
  4956.6    0.12       0
Bank Sta=4952.6,4956.6
Exp/Cntr=0.3,0.1

Type RM Length L Ch R = 1,2993,378,378,378
BEGIN DESCRIPTION:
Cable Branch 8.0
END DESCRIPTION:
XS GIS Cut Line= 3
      2404835.99      7032549.50      2405079.00      7032560.00
      2405324.47      7032510.70
#Sta/Elev= 30
  4757.3  566.25  4870.4  560.37  4880.1  560.43  4885.1  561.10  4890.4  559.67
  4910.4  557.45  4920.5  555.65  4930.5  554.73  4950.5  551.83  4960.5  551.12
  4970.5  546.40  4980.5  536.96  4988.5  536.05  4988.8  535.55  4992.3  535.55
  4992.5  536.05  4998.0  538.98  5003.1  538.98  5010.7  544.58  5020.9  548.90
  5026.0  548.41  5071.8  549.73  5082.1  551.03  5092.3  551.47  5122.7  555.13
  5127.8  555.09  5133.1  556.19  5143.3  557.08  5224.4  561.84  5250.9  562.53
#Mann=3,-1,0
  4757.3    0.12       0  4988.5    0.07       0  4992.5    0.12       0
Bank Sta=4988.5,4992.5
Exp/Cntr=0.3,0.1

Type RM Length L Ch R = 1,2615,392,392,392
BEGIN DESCRIPTION:
Cable Branch 7.0
END DESCRIPTION:
XS GIS Cut Line= 3
      2404855.50      7032905.06      2405236.02      7032899.50
      2405502.63      7032843.96
#Sta/Elev= 30
  4676.1  564.35  4709.6  562.12  4809.6  558.15  4859.6  555.14  4919.6  547.97
  4929.6  546.56  4939.6  544.27  4949.6  543.41  4969.6  539.81  4979.6  539.58
  4997.6  535.05  4997.9  534.55  5001.4  534.55  5001.6  535.05  5009.6  538.31
  5019.6  538.18  5029.6  540.71  5039.6  542.07  5055.7  547.47  5069.9  548.15
  5132.0  555.98  5151.6  557.25  5171.9  557.25  5177.0  558.00  5202.7  557.11
  5221.9  557.86  5227.0  558.70  5233.4  557.93  5304.9  562.60  5329.0  563.14
#Mann=3,-1,0
  4676.1    0.12       0  4997.6    0.07       0  5001.6    0.12       0
Bank Sta=4997.6,5001.6
Exp/Cntr=0.3,0.1

Type RM Length L Ch R = 1,2223,417,417,417
BEGIN DESCRIPTION:
Cable Branch 6.0
END DESCRIPTION:
XS GIS Cut Line= 3
      2404697.09      7033193.94      2405029.00      7033210.00
      2405322.15      7033224.50
#Sta/Elev= 30
  4667.6  573.67  4687.0  572.89  4692.0  571.47  4729.6  569.60  4759.6  565.70
  4779.6  565.10  4839.7  559.36  4849.7  556.56  4889.8  550.60  4909.8  546.44
  4919.8  545.29  4929.8  542.97  4939.8  539.39  4959.8  536.72  4979.9  536.03
  4989.9  533.65  4995.4  533.36  4995.6  532.86  4999.1  532.86  4999.4  533.36
  5002.4  533.36  5019.9  537.99  5029.9  541.61  5080.0  545.91  5130.1  551.51
  5150.1  552.32  5190.1  555.24  5220.2  556.02  5270.2  559.21  5293.4  559.65
#Mann=3,-1,0
  4667.6    0.12       0  4995.4    0.07       0  4999.4    0.12       0
Bank Sta=4995.4,4999.4
Exp/Cntr=0.3,0.1

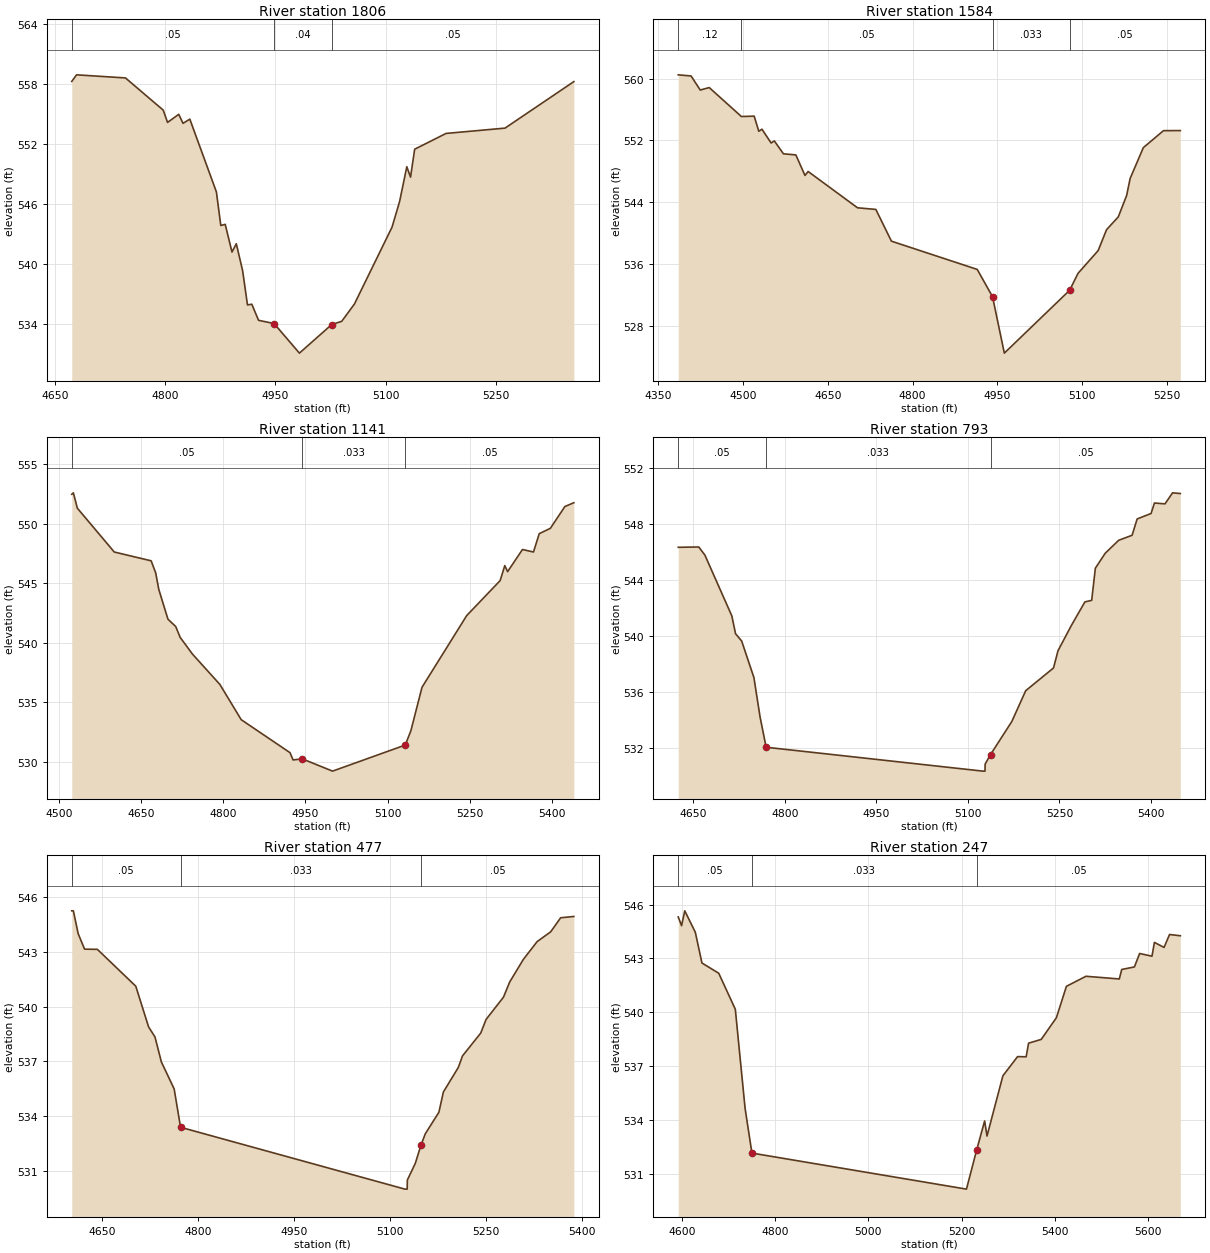
Type RM Length L Ch R = 1,1806,222,222,222
BEGIN DESCRIPTION:
Cable Branch 5.0
END DESCRIPTION:
XS GIS Cut Line= 3
      2404776.41      7033382.68      2405072.13      7033574.50
      2405395.06      7033647.23
#Sta/Elev= 30
  4672.7  558.26  4679.2  558.92  4745.8  558.61  4797.2  555.39  4803.1  554.16
  4818.3  554.97  4824.2  554.07  4833.4  554.49  4869.6  547.21  4875.6  543.85
  4881.6  543.97  4890.8  541.20  4896.7  542.03  4905.3  539.33  4911.9  535.91
  4917.8  535.98  4927.0  534.37  4948.1  534.05  4982.6  531.09  5026.6  533.95
  5040.2  534.27  5057.5  536.00  5108.7  543.69  5119.0  546.25  5128.8  549.73
  5133.9  548.69  5139.5  551.48  5182.3  553.06  5262.5  553.59  5356.2  558.24
#Mann=3,-1,0
  4672.7    0.05       0  4948.1    0.04       0  5026.6    0.05       0
Bank Sta=4948.1,5026.6
Exp/Cntr=0.3,0.1

Type RM Length L Ch R = 1,1584,443,443,443
BEGIN DESCRIPTION:
Cable Branch 4.0
END DESCRIPTION:
XS GIS Cut Line= 3
      2404574.89      7033271.70      2404755.46      7033605.05
      2405172.11      7033899.49
#Sta/Elev= 30
  4385.0  560.48  4407.8  560.33  4424.0  558.51  4439.9  558.83  4496.9  555.08
  4519.5  555.13  4527.7  553.17  4533.3  553.44  4549.5  551.65  4555.2  551.92
  4571.4  550.25  4593.3  550.11  4609.5  547.45  4615.1  547.96  4702.6  543.26
  4735.0  543.05  4762.6  538.94  4914.6  535.28  4941.7  531.75  4962.6  524.44
  5078.3  532.58  5093.1  534.77  5128.8  537.72  5143.6  540.42  5164.5  542.09
  5179.3  544.87  5185.4  547.05  5208.8  551.05  5244.5  553.25  5274.3  553.26
#Mann=4,-1,0
  4385.0    0.12       0  4496.9    0.05       0  4941.7   0.033       0
  5078.3    0.05       0
Bank Sta=4941.7,5078.3
Exp/Cntr=0.3,0.1

Type RM Length L Ch R = 1,1141,348,348,348
BEGIN DESCRIPTION:
Cable Branch 3.0
END DESCRIPTION:
XS GIS Cut Line= 3
      2404149.87      7033724.48      2404527.68      7033916.16
      2405011.01      7034007.83
#Sta/Elev= 30
  4523.8  552.48  4526.7  552.60  4534.0  551.31  4601.3  547.63  4668.6  546.89
  4676.9  545.87  4682.5  544.49  4699.2  541.99  4713.4  541.37  4721.5  540.46
  4743.7  539.07  4793.9  536.51  4832.8  533.55  4921.8  530.78  4927.4  530.17
  4944.1  530.26  4999.4  529.23  5132.0  531.42  5142.2  532.62  5162.5  536.27
  5244.0  542.29  5305.0  545.23  5313.5  546.49  5318.6  545.98  5345.7  547.84
  5365.8  547.63  5376.3  549.17  5396.6  549.62  5423.1  551.45  5439.4  551.77
#Mann=3,-1,0
  4523.8    0.05       0  4944.1   0.033       0  5132.0    0.05       0
Bank Sta=4944.1,5132
Exp/Cntr=0.3,0.1

Type RM Length L Ch R = 1,793,316,316,316
BEGIN DESCRIPTION:
Cable Branch 2.0
END DESCRIPTION:
XS GIS Cut Line= 3
      2404255.47      7034302.27      2404586.02      7034274.50
      2405030.49      7034066.15
#Sta/Elev= 30
  4625.4  546.34  4659.1  546.36  4669.1  545.78  4713.2  541.43  4719.3  540.15
  4729.3  539.63  4749.4  537.01  4759.4  534.21  4769.4  532.02  5124.5  530.31
  5128.0  530.31  5128.2  530.81  5137.1  531.50  5171.9  533.86  5194.7  536.07
  5240.3  537.70  5247.6  538.93  5269.6  540.75  5291.7  542.43  5302.8  542.54
  5308.8  544.84  5324.9  545.91  5347.0  546.84  5369.0  547.20  5377.3  548.37
  5400.1  548.76  5405.6  549.51  5422.9  549.45  5435.3  550.24  5448.0  550.19
#Mann=3,-1,0
  4625.4    0.05       0  4769.4   0.033       0  5137.1    0.05       0
Bank Sta=4769.4,5137.1
Exp/Cntr=0.3,0.1

Type RM Length L Ch R = 1,477,230,230,230
BEGIN DESCRIPTION:
Cable Branch 1.0
END DESCRIPTION:
XS GIS Cut Line= 3
      2404378.95      7034510.00      2404813.79      7034516.16
      2405113.77      7034335.62
#Sta/Elev= 30
  4602.2  545.25  4604.7  545.25  4612.2  544.00  4622.2  543.15  4642.2  543.14
  4702.3  541.12  4722.3  538.89  4732.3  538.34  4742.3  536.97  4762.3  535.49
  4772.3  533.39  5123.1  530.00  5126.6  530.00  5126.9  530.50  5139.3  531.41
  5148.2  532.41  5154.9  533.03  5176.2  534.21  5183.2  535.32  5206.6  536.67
  5213.1  537.30  5241.6  538.55  5250.0  539.30  5277.2  540.52  5286.9  541.35
  5308.3  542.59  5329.7  543.56  5351.0  544.10  5366.6  544.87  5387.2  544.94
#Mann=3,-1,0
  4602.2    0.05       0  4772.3   0.033       0  5148.2    0.05       0
Bank Sta=4772.3,5148.2
Exp/Cntr=0.3,0.1

Type RM Length L Ch R = 1,247,0,0,0
BEGIN DESCRIPTION:
Cable Branch 0.5
END DESCRIPTION:
XS GIS Cut Line= 4
      2404377.67      7034541.15      2404616.57      7034713.38
      2405005.46      7034768.94      2405122.12      7034396.74
#Sta/Elev= 30
  4592.0  545.31  4599.2  544.82  4606.0  545.65  4628.6  544.46  4642.9  542.74
  4678.9  542.17  4714.5  540.16  4735.4  534.65  4750.1  532.14  5210.5  530.13
  5232.4  532.31  5249.5  533.93  5254.6  533.09  5288.7  536.45  5320.2  537.52
  5338.6  537.51  5343.8  538.27  5371.0  538.48  5403.5  539.69  5425.0  541.44
  5466.9  542.00  5538.5  541.85  5543.7  542.38  5570.9  542.52  5582.1  543.27
  5608.6  543.12  5613.8  543.89  5634.5  543.61  5646.3  544.33  5669.4  544.26
#Mann=3,-1,0
  4592.0    0.05       0  4750.1   0.033       0  5232.4    0.05       0
Bank Sta=4750.1,5232.4
Exp/Cntr=0.3,0.1

Chan Stop Cuts=-1