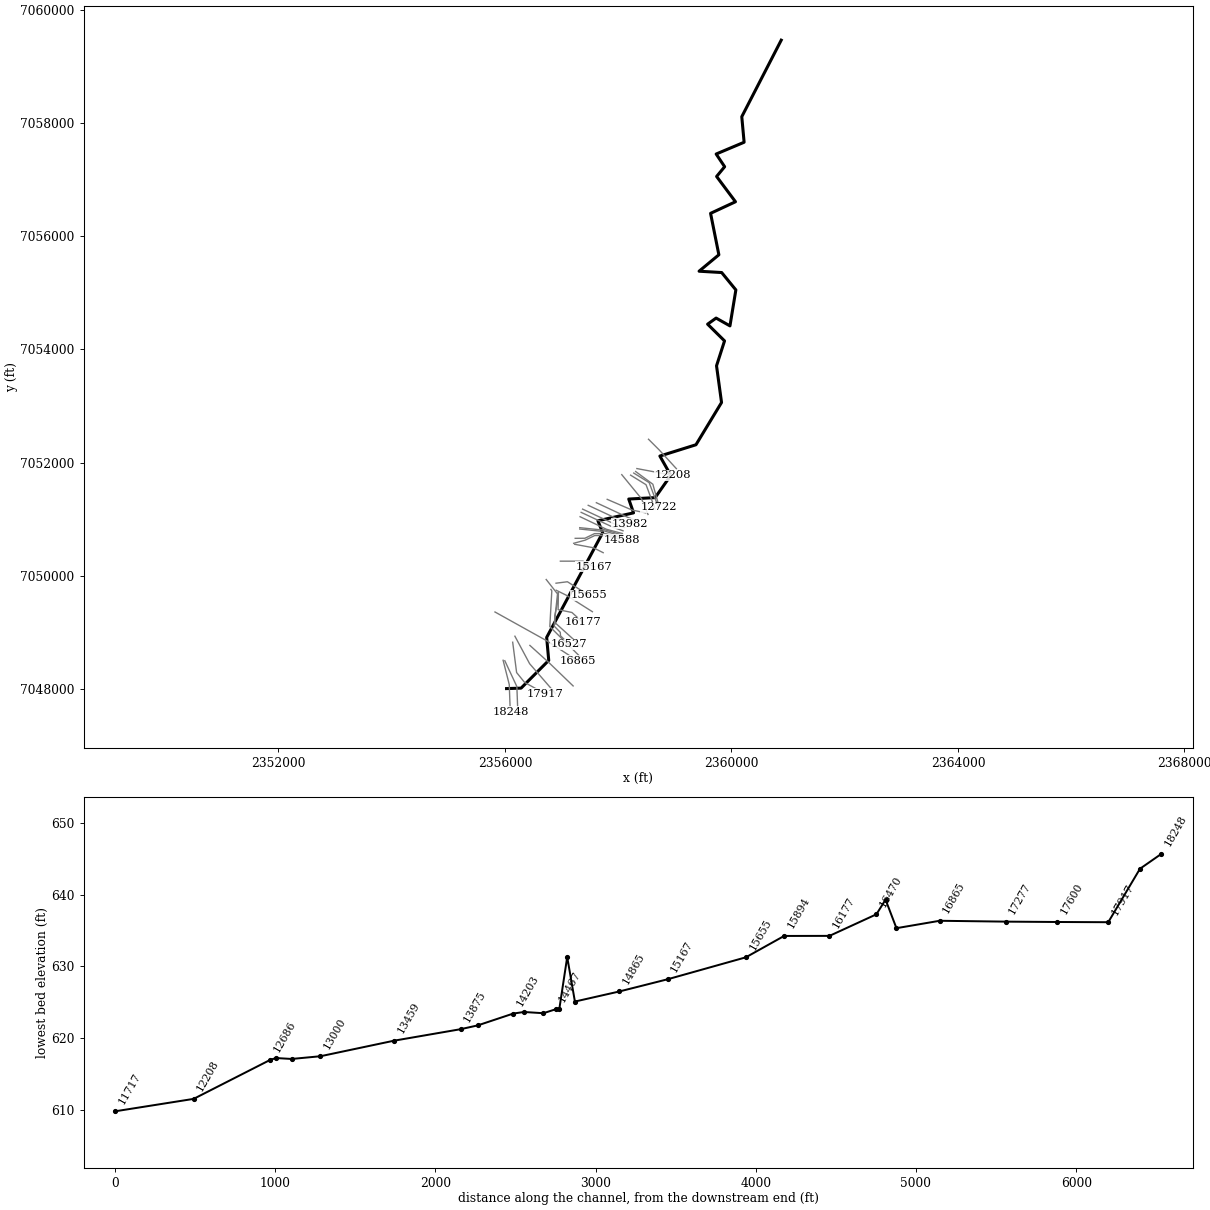
--- Cade Branch.prj (project) ---

Proj Title=Cade Branch Base Level Engineering
Current Plan=p01
Default Exp/Contr=0.3,0.1
English Units
Geom File=g01
Flow File=f01
Plan File=p01
Y Axis Title=Elevation
X Axis Title(PF)=Main Channel Distance
X Axis Title(XS)=Station
BEGIN DESCRIPTION:
Cade Branch
END DESCRIPTION:
DSS Export Rating Curves= 0
DSS Export Rating Curve Sorted= 0
DSS Export Volume Flow Curves= 0
DXF OffsetX= 0
DXF OffsetY= 0
DXF ScaleX= 1
DXF ScaleY= 10

--- Cade Branch.p01 (plan) ---

Plan Title=Multiple Run
Program Version=4.10
Short Identifier=Multiple
Geom File=g01
Flow File=f01
Subcritical Flow
K Sum by GR= 0
Std Step Tol= 0.01
Critical Tol= 0.01
Num of Std Step Trials= 20
Max Error Tol= 0.3
Flow Tol Ratio= 0.001
Split Flow NTrial= 30
Split Flow Tol= 0.02
Split Flow Ratio= 0.02
Log Output Level= 0
Friction Slope Method= 1
Unsteady Friction Slope Method= 2
Unsteady Bridges Friction Slope Method= 1
Parabolic Critical Depth
Global Vel Dist= 1 , 1 , 1
Global Log Level= 0
CheckData=True
Encroach Param=-1 ,0,0, 0
BEGIN DESCRIPTION:
Multiple Run
END DESCRIPTION:
Computation Interval=1HOUR
Output Interval=1HOUR
Run HTab= 0
Run UNet= 0
Run PostProcess= 0
Run WQNet= 0
UNET Theta= 1
UNET Theta Warmup= 1
UNET ZTol= 0.02
UNET ZSATol= 0.05
UNET MxIter= 20
UNET MaxInSteps= 0
UNET DtIC= 0
UNET DtMin= 0
UNET MaxCRTS= 20
UNET WFStab= 2
UNET SFStab= 1
UNET WFX= 1
UNET SFX= 1
UNET DSS MLevel= 4
UNET DZMax Abort= 100
UNET Convert EG Bridges= 0
UNET Use Existing IB Tables=-1
UNET Froude Reduction=False
UNET Froude Limit= 1
UNET Froude Power= 10
UNET Time Slicing=0,0, 5
UNET Junction Losses=0
Instantaneous Interval=1HOUR
Write IC File= 0
Write IC File at Sim End=0
Echo Input=False
Echo Parameters=False
Echo Output=False
Write Detailed= 0
WQ AD Non Conservative
WQ ULTIMATE=-1
WQ Max Comp Step=1HOUR
WQ Output Interval=15MIN
WQ Output Selected Increments= 0
WQ Output face flow=0
WQ Output face velocity=0
WQ Output face area=0
WQ Output face dispersion=0
WQ Output cell volume=0
WQ Output cell surface area=0
WQ Output cell continuity=0
WQ Output cumulative cell continuity=0
WQ Output face conc=0
WQ Output face dconc_dx=0
WQ Output face courant=0
WQ Output face peclet=0
WQ Output face adv mass=0
WQ Output face disp mass=0
WQ Output cell mass=0
WQ Output cell source sink temp=0
WQ Output cell source sink nsm=0
WQ Output MaxMinRange=-1
WQ Daily Max Min Mean=-1
WQ Daily Range=0
WQ Daily Time=0
WQ Create Restart=0
WQ Fixed Restart=0
WQ System Summary=0
WQ Use Fixed Temperature=0
Sorting and Armoring Iterations= 10
XS Update Threshold= 0.02
Hydraulics Update Threshold= 0.02
Energy Slope Method= 1
Volume Change Method= 0
XS Weighting Method= 0
Number of US Weighted Cross Sections= 1
Number of DS Weighted Cross Sections= 1
Upstream XS Weight=0.25
Main XS Weight=0.5
Downstream XS Weight=0.25
Number of DS XS's Weighted with US Boundary= 1
Upstream Boundary Weight= 1
Weight of XSs Associated with US Boundary= 0
Number of US XS's Weighted with DS Boundary= 1
Downstream Boundary Weight= 0.5
Weight of XSs Associated with DS Boundary= 0.5
Sediment Output Level= 4
Mass or Volume Output= 0
Output Increment Type= 1
Profile and TS Output Increment= 10
XS Output Flag= 0
XS Output Increment= 10
Disregard all LS=0
Disregard all Conn=0
Disregard all Breaches=0
Disregard all Pumps=0

--- Cade Branch.f01 (steady flow) ---

Flow Title=Multiple
Number of Profiles=7
Profile Names=10-year,25-year,50-year,1pct_min,100-year,1pct_plu,500-year
River Rch & RM= Cade Branch,Reach-1,18248
     411     541     643     380     758    1512    1050
River Rch & RM= Cade Branch,Reach-1,17600
     586     788     951     569    1135    2264    1614
River Rch & RM= Cade Branch,Reach-1,14270
     652     888    1081     653    1302    2599    1895
River Rch & RM= Cade Branch,Reach-1,11717
     801    1103    1353     823    1641    3275    2421
River Rch & RM= Cade Branch,Reach-1,7756
     974    1356    1675    1025    2046    4082    3059
River Rch & RM= Cade Branch,Reach-1,2872
    1129    1586    1972    1214    2422    4833    3665
Boundary for River Rch & Prof#=Cade Branch,Reach-1,1
Up Type=0
Dn Type=3
Dn Slope=0.005
Boundary for River Rch & Prof#=Cade Branch,Reach-1,2
Up Type=0
Dn Type=3
Dn Slope=0.005
Boundary for River Rch & Prof#=Cade Branch,Reach-1,3
Up Type=0
Dn Type=3
Dn Slope=0.005
Boundary for River Rch & Prof#=Cade Branch,Reach-1,4
Up Type=0
Dn Type=3
Dn Slope=0.005
Boundary for River Rch & Prof#=Cade Branch,Reach-1,5
Up Type=0
Dn Type=3
Dn Slope=0.005
Boundary for River Rch & Prof#=Cade Branch,Reach-1,6
Up Type=0
Dn Type=3
Dn Slope=0.005
Boundary for River Rch & Prof#=Cade Branch,Reach-1,7
Up Type=0
Dn Type=3
Dn Slope=0.005

--- Cade Branch.g01 (geometry) ---

Geom Title=Existing Conditions
Program Version=4.10

River Reach=Cade Branch     ,Reach-1
Reach XY= 30
        2356029.        7048010.      2356285.21       7048017.8
      2356773.61      7048507.56        2356737.      7048913.33
      2357725.86      7050761.64      2357642.52      7050973.44
      2358271.16      7051112.93      2358186.52      7051356.93
      2358652.85      7051382.25      2358929.05      7051775.34
       2358736.2      7052116.08      2359373.42      7052315.58
      2359825.17      7053061.58      2359736.59      7053709.99
      2359877.97      7054149.57      2359579.18      7054444.91
        2359729.       7054552.5      2359973.81      7054414.56
      2360078.03      7055049.75       2359827.3       7055356.7
      2359428.56      7055380.03      2359778.02      7055670.26
      2359631.49      7056401.85      2360071.24      7056606.58
      2359737.83      7057053.06      2359880.04      7057225.18
      2359730.18      7057449.49      2360223.67      7057657.34
      2360182.54      7058108.53        2360879.        7059460.

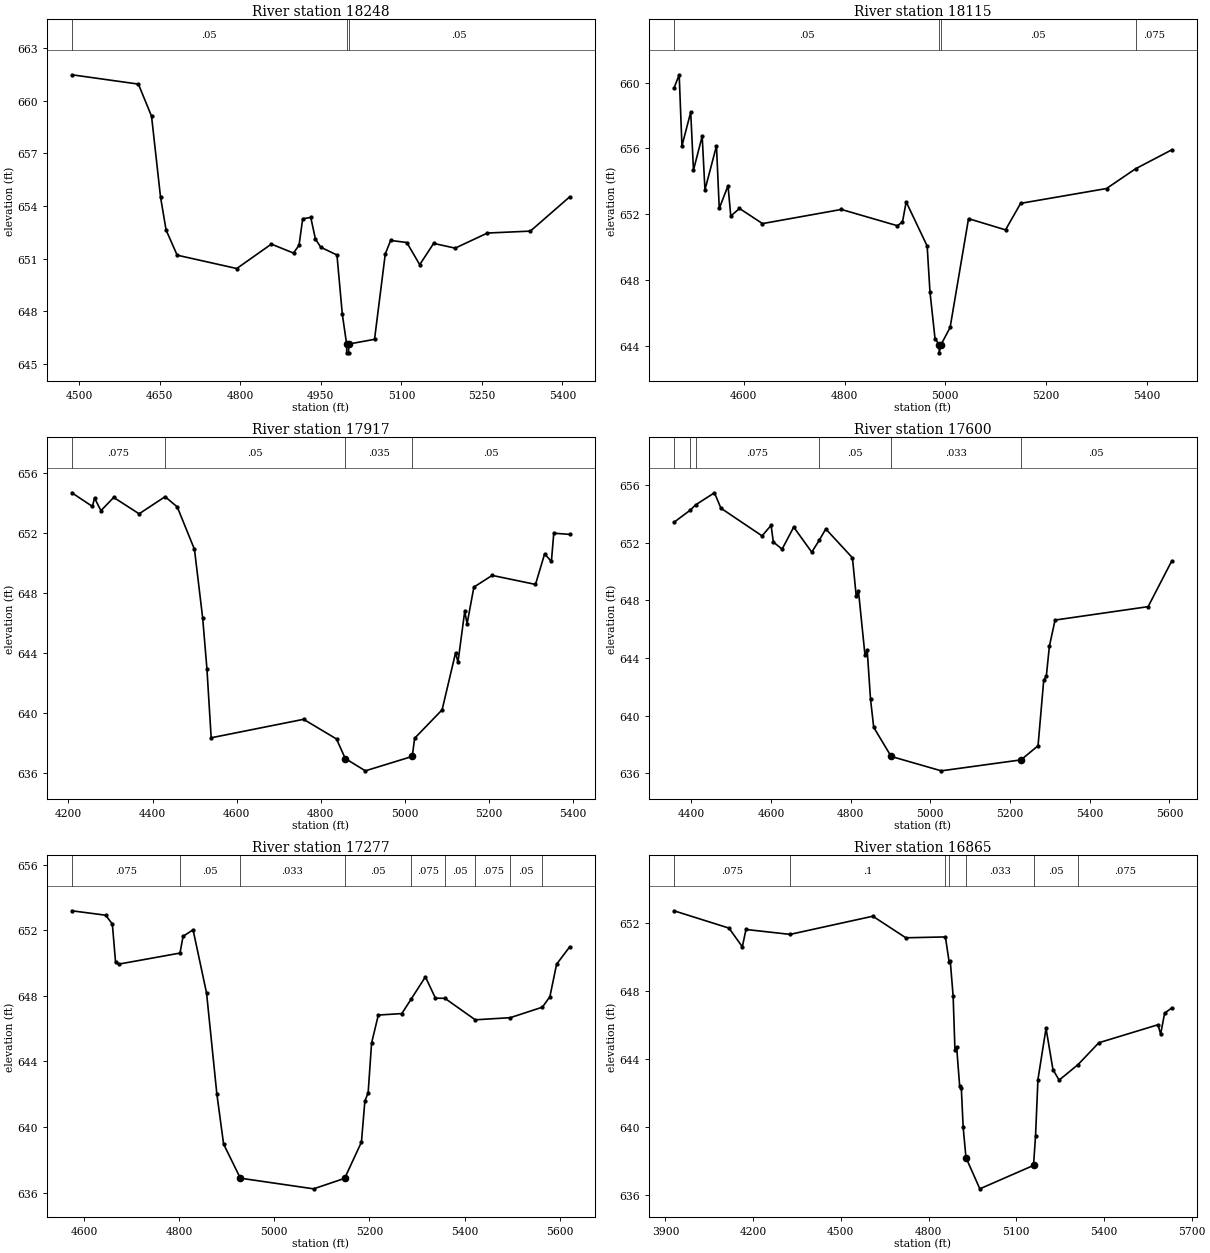
Type RM Length L Ch R = 1 ,18248   ,133,133,133
BEGIN DESCRIPTION:
Cade Branch 39.0
END DESCRIPTION:
XS GIS Cut Line= 3
      2355967.81      7048510.07      2356076.33      7048082.52
      2356094.45      7047596.87
#Sta/Elev= 30
  4486.3  661.47  4610.2  660.94  4634.7  659.11  4651.4  654.51  4661.8  652.63
  4682.4   651.2  4793.4  650.44  4857.8  651.83  4899.1  651.32  4909.4  651.77
  4916.2  653.27  4931.2  653.35  4939.9  652.12  4949.9  651.65    4980  651.21
    4990  647.83    4998  646.14  4998.2  645.64  5001.7  645.64    5002  646.14
    5050  646.41    5070  651.27    5080  652.04  5110.1  651.92  5134.1  650.66
  5160.1  651.87  5200.1   651.6  5260.2  652.46  5340.2  652.57  5413.4  654.52
#Mann= 3 ,-1 , 0
  4486.3     .05       0    4998     .05       0    5002     .05       0
Bank Sta=4998,5002
XS Rating Curve= 0 ,0
Exp/Cntr=0.3,0.1

Type RM Length L Ch R = 1 ,18115   ,198,198,198
BEGIN DESCRIPTION:
Cade Branch 38.0
END DESCRIPTION:
XS GIS Cut Line= 3
      2355998.18       7048501.4      2356210.88      7048045.63
        2356229.      7047560.03
#Sta/Elev= 30
  4461.1  659.65  4471.5  660.47    4477  656.15  4494.4   658.2  4499.9  654.68
  4517.2  656.74  4522.7  653.48  4545.6  656.15  4551.1  652.35  4568.5  653.73
    4574  651.89  4591.3  652.35    4637  651.43  4793.7  652.29    4905   651.3
  4915.1  651.53  4922.4  652.75  4964.1  650.07  4969.7  647.28  4979.7  644.45
  4987.7  644.08    4988  643.58  4991.7  644.08  5009.7  645.12  5046.3  651.73
  5119.8  651.05  5149.8  652.66  5320.4  653.56  5378.1  654.76    5450  655.91
#Mann= 4 ,-1 , 0
  4461.1     .05       0  4987.7     .05       0  4991.7     .05       0
  5378.1    .075       0
Bank Sta=4987.7,4991.7
XS Rating Curve= 0 ,0
Exp/Cntr=0.3,0.1

Type RM Length L Ch R = 1 ,17917   ,317,317,317
BEGIN DESCRIPTION:
Cade Branch 37.0
END DESCRIPTION:
XS GIS Cut Line= 4
      2356137.09      7048828.64      2356206.46      7048292.94
       2356347.6      7048118.98      2356715.25      7047915.69
#Sta/Elev= 30
  4208.1  654.66    4257  653.75    4262  654.31  4277.3  653.47  4307.6  654.35
  4368.1  653.26  4429.9   654.4  4458.8  653.72  4499.8  650.89  4519.3  646.32
  4529.4  642.95  4539.5  638.35  4759.4  639.58  4837.7  638.27  4858.5  636.97
  4906.3  636.15  5017.9  637.11  5023.6  638.32  5088.9  640.21  5120.9     644
  5126.7  643.39  5142.7  646.76  5148.4  645.95  5164.5  648.38    5208  649.16
  5311.1  648.56  5332.8  650.59  5348.9  650.09  5354.6  651.97  5392.4  651.89
#Mann= 4 ,-1 , 0
  4208.1    .075       0  4429.9     .05       0  4858.5    .035       0
  5017.9     .05       0
Bank Sta=4858.5,5017.9
XS Rating Curve= 0 ,0
Exp/Cntr=0.3,0.1

Type RM Length L Ch R = 1 ,17600   ,323,323,323
BEGIN DESCRIPTION:
Cade Branch 36.0
END DESCRIPTION:
XS GIS Cut Line= 3
      2356176.16      7048934.94      2356436.57      7048448.84
      2356894.24      7047921.77
#Sta/Elev= 30
  4356.4  653.42  4397.1  654.26  4410.7  654.63  4458.1  655.47  4474.3   654.4
  4577.6  652.48  4600.2  653.21  4605.9  652.05  4627.9  651.56    4657  653.09
  4702.3  651.35  4721.4  652.19  4737.5  652.96  4804.4  650.96  4813.9  648.31
  4819.6  648.64  4835.8  644.24  4841.5  644.54  4849.8  641.15  4857.8   639.2
  4901.6  637.18  5027.3  636.18  5227.5  636.94  5270.3  637.92  5284.5  642.45
  5291.1  642.76  5298.8  644.83    5313  646.64  5546.6  647.57  5605.9  650.74
#Mann= 6 ,-1 , 0
  4356.4    .075       0  4397.1      .1       0  4410.7    .075       0
  4721.4     .05       0  4901.6    .033       0  5227.5     .05       0
Bank Sta=4901.6,5227.5
XS Rating Curve= 0 ,0
Exp/Cntr=0.3,0.1

Type RM Length L Ch R = 1 ,17277   ,412,412,412
BEGIN DESCRIPTION:
Cade Branch 35.0
END DESCRIPTION:
XS GIS Cut Line= 3
      2356440.92      7048772.18      2356781.63      7048464.03
      2357204.37      7048056.47
#Sta/Elev= 30
  4574.5  653.19  4645.5  652.92  4659.6  652.38  4666.4  650.04  4673.8  649.94
  4801.8  650.61  4808.3  651.63  4829.3  652.03  4857.7  648.17  4879.3  642.02
  4893.5  638.96  4928.7  636.88  5082.7  636.23    5148  636.87  5183.3  639.08
  5190.5  641.58  5197.4  642.09  5204.6  645.12  5218.8  646.83  5268.2  646.92
  5288.2  647.82  5317.8  649.16  5338.9  647.86  5358.8  647.85  5422.6  646.54
  5496.2  646.67  5563.7  647.31  5579.5  647.95  5593.6  649.93  5621.1  650.99
#Mann= 9 ,-1 , 0
  4574.5    .075       0  4801.8     .05       0  4928.7    .033       0
    5148     .05       0  5288.2    .075       0  5358.8     .05       0
  5422.6    .075       0  5496.2     .05       0  5563.7    .075       0
Bank Sta=4928.7,5148
XS Rating Curve= 0 ,0
Exp/Cntr=0.3,0.1

Type RM Length L Ch R = 1 ,16865   ,270,270,270
BEGIN DESCRIPTION:
Cade Branch 34.0
END DESCRIPTION:
XS GIS Cut Line= 3
      2355824.57      7049362.49      2356749.07      7048848.15
      2357289.43      7048496.59
#Sta/Elev= 30
  3929.3  652.72  4117.5   651.7  4163.2   650.6  4175.7  651.62  4326.4  651.33
  4609.5   652.4  4722.3  651.13  4857.7  651.18  4870.8  649.68  4874.4  649.76
  4884.2  647.69  4890.4  644.52  4896.1  644.71  4906.4  642.43  4912.1  642.31
  4918.5  639.97  4928.1  638.19  4975.5  636.35  5159.1  637.73  5166.1  639.48
  5174.2  642.78  5201.9   645.8  5225.6  643.37  5246.7  642.75  5311.7  643.67
  5382.5  644.95  5584.7  646.01  5593.9  645.46  5607.5  646.69  5631.9     647
#Mann= 7 ,-1 , 0
  3929.3    .075       0  4326.4      .1       0  4857.7    .075       0
  4870.8     .05       0  4928.1    .033       0  5159.1     .05       0
  5311.7    .075       0
Bank Sta=4928.1,5159.1
XS Rating Curve= 0 ,0
Exp/Cntr=0.3,0.1

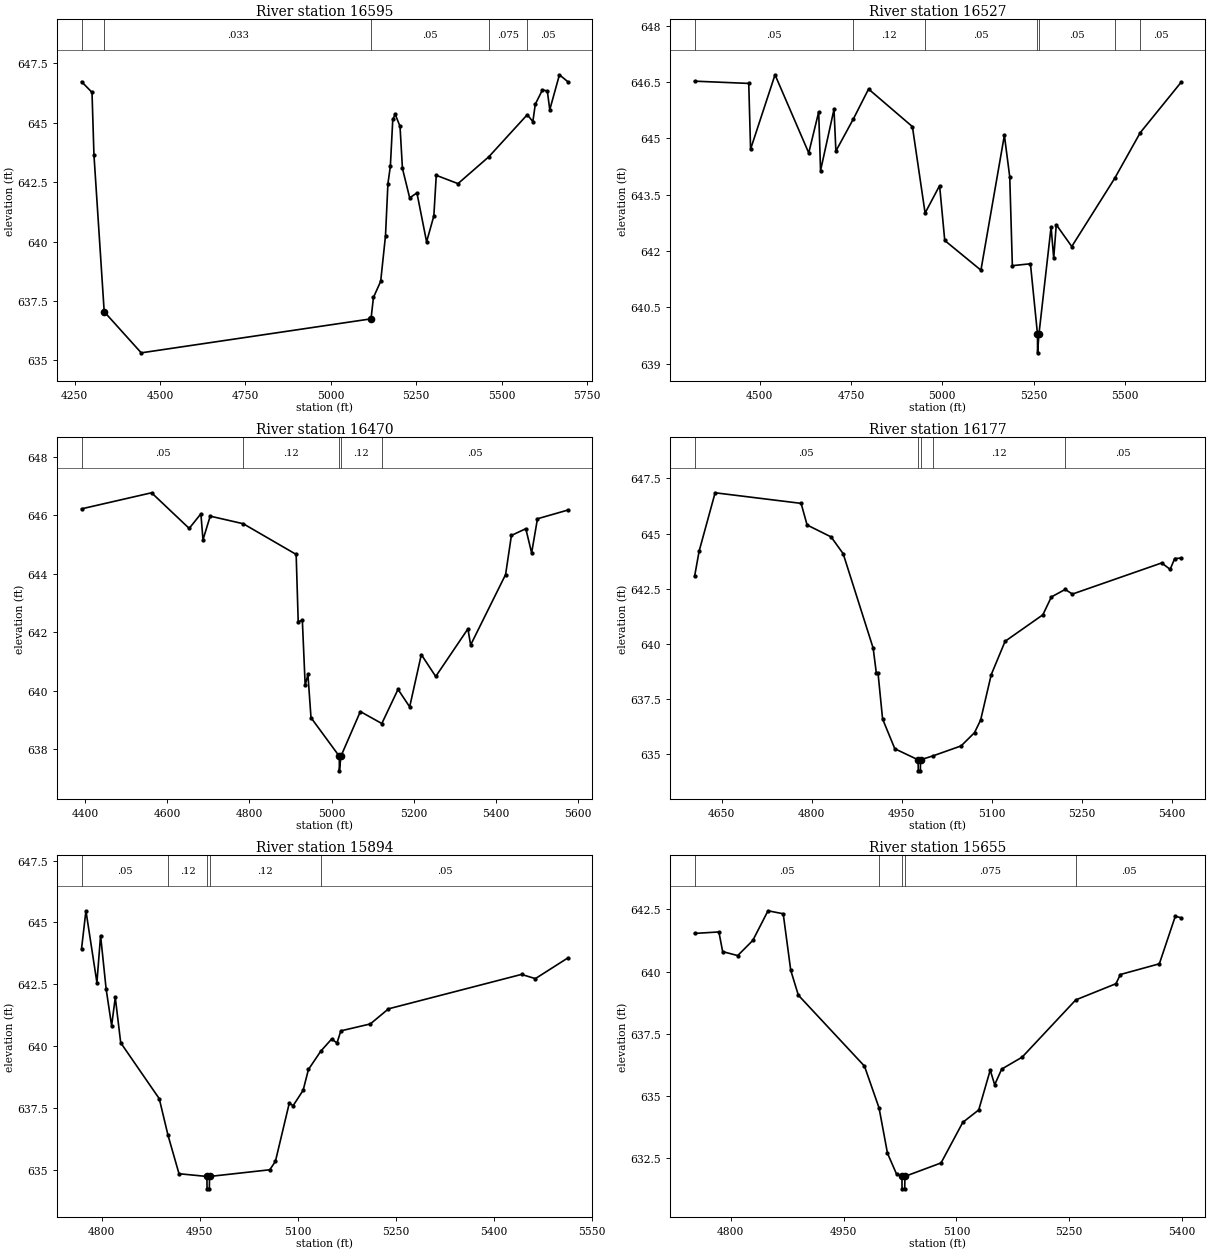
Type RM Length L Ch R = 1 ,16595   ,68,68,68
BEGIN DESCRIPTION:
Cade Branch 33.0
END DESCRIPTION:
XS GIS Cut Line= 4
      2356812.03      7049761.75      2356828.02      7049735.69
      2356792.48      7049104.22      2357332.86      7048568.18
#Sta/Elev= 30
  4270.4  646.73    4301  646.28  4306.7  643.65  4336.7  637.05  4445.1  635.32
  5117.8  636.75  5124.9  637.65  5146.1  638.33  5160.2  640.25  5167.3  642.44
  5174.4  643.17  5181.5  645.14  5188.5  645.36  5202.7  644.85  5209.8  643.08
    5231  641.84  5252.2  642.05  5280.5  639.99  5301.7  641.08  5308.8  642.79
  5372.4  642.44  5462.7  643.57  5575.2  645.34  5591.6  645.05  5598.7  645.78
  5619.8  646.39    5634  646.33  5641.1  645.55  5669.4  647.02  5694.6  646.72
#Mann= 5 ,-1 , 0
  4270.4     .05       0  4336.7    .033       0  5117.8     .05       0
  5462.7    .075       0  5575.2     .05       0
Bank Sta=4336.7,5117.8
XS Rating Curve= 0 ,0
Exp/Cntr=0.3,0.1

Type RM Length L Ch R = 1 ,16527   ,57,57,57
BEGIN DESCRIPTION:
Cade Branch 32.6
END DESCRIPTION:
XS GIS Cut Line= 6
      2356729.05      7049935.95      2356928.45      7049682.17
      2356868.45      7049114.59       2356977.1      7049004.31
      2356981.97      7048941.07      2357137.35      7048790.06
#Sta/Elev= 30
  4322.3  646.52  4470.5  646.46  4475.5  644.71  4542.4  646.69  4634.7  644.61
  4661.9   645.7    4667  644.14  4703.8  645.77    4709  644.66  4757.1  645.52
  4798.4  646.31  4918.4  645.31  4953.1  643.01  4992.8  643.74  5006.9  642.28
  5105.9  641.49  5170.1  645.08  5184.8  643.97  5191.9  641.61  5241.4  641.66
  5260.7  639.79  5260.9  639.29  5264.7  639.79  5297.9  642.64  5305.1  641.81
  5312.1   642.7  5354.5  642.12  5471.7  643.93    5542  645.15  5653.7  646.49
#Mann= 7 ,-1 , 0
  4322.3     .05       0  4757.1     .12       0  4953.1     .05       0
  5260.7    .033       0  5264.7     .05       0  5471.7    .075       0
    5542     .05       0
Bank Sta=5260.7,5264.7
XS Rating Curve= 0 ,0
Exp/Cntr=0.3,0.1

Type RM Length L Ch R = 1 ,16470   ,293,293,293
BEGIN DESCRIPTION:
Cade Branch 32.4
END DESCRIPTION:
XS GIS Cut Line= 5
      2356936.12       7049700.5      2356927.46       7049515.9
      2356879.17      7049296.52      2356884.26      7049174.18
      2357369.72      7048735.31
#Sta/Elev= 30
  4390.5  646.22  4561.2  646.77    4653  645.55  4681.5  646.05  4686.6  645.16
  4704.2  645.97  4784.8  645.71  4913.8  644.66  4918.8  642.36  4928.9   642.4
  4935.8  640.18  4942.5  640.55    4950  639.07    5019  637.75  5019.2  637.25
    5023  637.75  5070.3  639.28  5122.7  638.87  5162.2  640.04  5190.6  639.44
    5219  641.23  5254.1  640.48  5332.6  642.11  5339.3  641.56  5424.5  643.97
  5438.7  645.31  5473.8  645.54    5488  644.71  5502.2  645.88  5576.8  646.18
#Mann= 5 ,-1 , 0
  4390.5     .05       0  4784.8     .12       0    5019     .07       0
    5023     .12       0  5122.7     .05       0
Bank Sta=5019,5023
XS Rating Curve= 0 ,0
Exp/Cntr=0.3,0.1

Type RM Length L Ch R = 1 ,16177   ,283,283,283
BEGIN DESCRIPTION:
Cade Branch 32.0
END DESCRIPTION:
XS GIS Cut Line= 4
      2356944.64      7049707.51      2356939.26      7049404.24
      2357183.04      7049353.75      2357374.85      7049180.43
#Sta/Elev= 30
    4605  643.06  4612.5   644.2  4639.2  646.85  4782.5  646.37  4792.5  645.39
  4832.5  644.85  4852.6  644.09  4902.6  639.81  4907.9  638.68  4910.7  638.68
  4918.3   636.6  4938.7  635.25  4977.5  634.75  4977.8  634.25  4981.3  634.25
  4981.5  634.75  5002.5  634.93  5049.2  635.38  5071.5  635.98  5081.7  636.55
  5099.4  638.61  5122.5  640.12  5185.4  641.32  5199.6  642.13  5222.6  642.47
  5234.7  642.26  5383.4  643.67  5397.6  643.38  5405.1  643.87  5415.8  643.89
#Mann= 5 ,-1 , 0
    4605     .05       0  4977.5    .033       0  4981.5     .05       0
  5002.5     .12       0  5222.6     .05       0
Bank Sta=4977.5,4981.5
XS Rating Curve= 0 ,0
Exp/Cntr=0.3,0.1

Type RM Length L Ch R = 1 ,15894   ,239,239,239
BEGIN DESCRIPTION:
Cade Branch 31.0
END DESCRIPTION:
XS GIS Cut Line= 3
      2356905.28      7049746.61      2357085.45      7049657.61
      2357544.74       7049367.3
#Sta/Elev= 30
  4769.4  643.94  4776.1  645.47  4792.9  642.57  4798.5  644.47    4807  642.31
  4815.4  640.83    4821  641.97  4829.3  640.14  4888.3  637.88  4901.6  636.41
  4918.5  634.85  4961.2  634.74  4961.4  634.24  4964.9  634.24  4965.2  634.74
  5057.4  635.01    5066  635.35  5087.2   637.7  5093.1   637.6  5108.4  638.22
  5116.5  639.06  5135.4   639.8    5152  640.29  5160.2  640.13  5166.1  640.62
  5211.2   640.9    5239  641.51  5442.5   642.9  5463.7  642.73  5513.7  643.57
#Mann= 5 ,-1 , 0
  4769.4     .05       0  4901.6     .12       0  4961.2     .07       0
  4965.2     .12       0  5135.4     .05       0
Bank Sta=4961.2,4965.2
XS Rating Curve= 0 ,0
Exp/Cntr=0.3,0.1

Type RM Length L Ch R = 1 ,15655   ,488,488,488
BEGIN DESCRIPTION:
Cade Branch 30.0
END DESCRIPTION:
XS GIS Cut Line= 3
      2356902.19       7049870.9      2357103.45      7049896.46
      2357479.02      7049659.99
#Sta/Elev= 30
    4752  641.53  4784.3  641.59  4789.3   640.8  4809.3  640.64  4829.4  641.25
  4849.6  642.44  4869.8  642.32  4879.8  640.05  4889.9  639.05  4977.8   636.2
  4997.2  634.52  5008.4   632.7  5020.5  631.86  5027.6  631.77  5027.8  631.27
  5031.3  631.27  5031.6  631.77  5079.6  632.31  5108.5  633.94  5129.7  634.44
    5145  636.04  5150.9  635.45  5160.2  636.08  5187.4  636.56  5258.7  638.86
  5312.1  639.51    5318  639.88  5369.8  640.31    5391  642.22  5398.7  642.16
#Mann= 5 ,-1 , 0
    4752     .05       0  4997.2    .075       0  5027.6     .07       0
  5031.6    .075       0  5258.7     .05       0
Bank Sta=5027.6,5031.6
XS Rating Curve= 0 ,0
Exp/Cntr=0.3,0.1

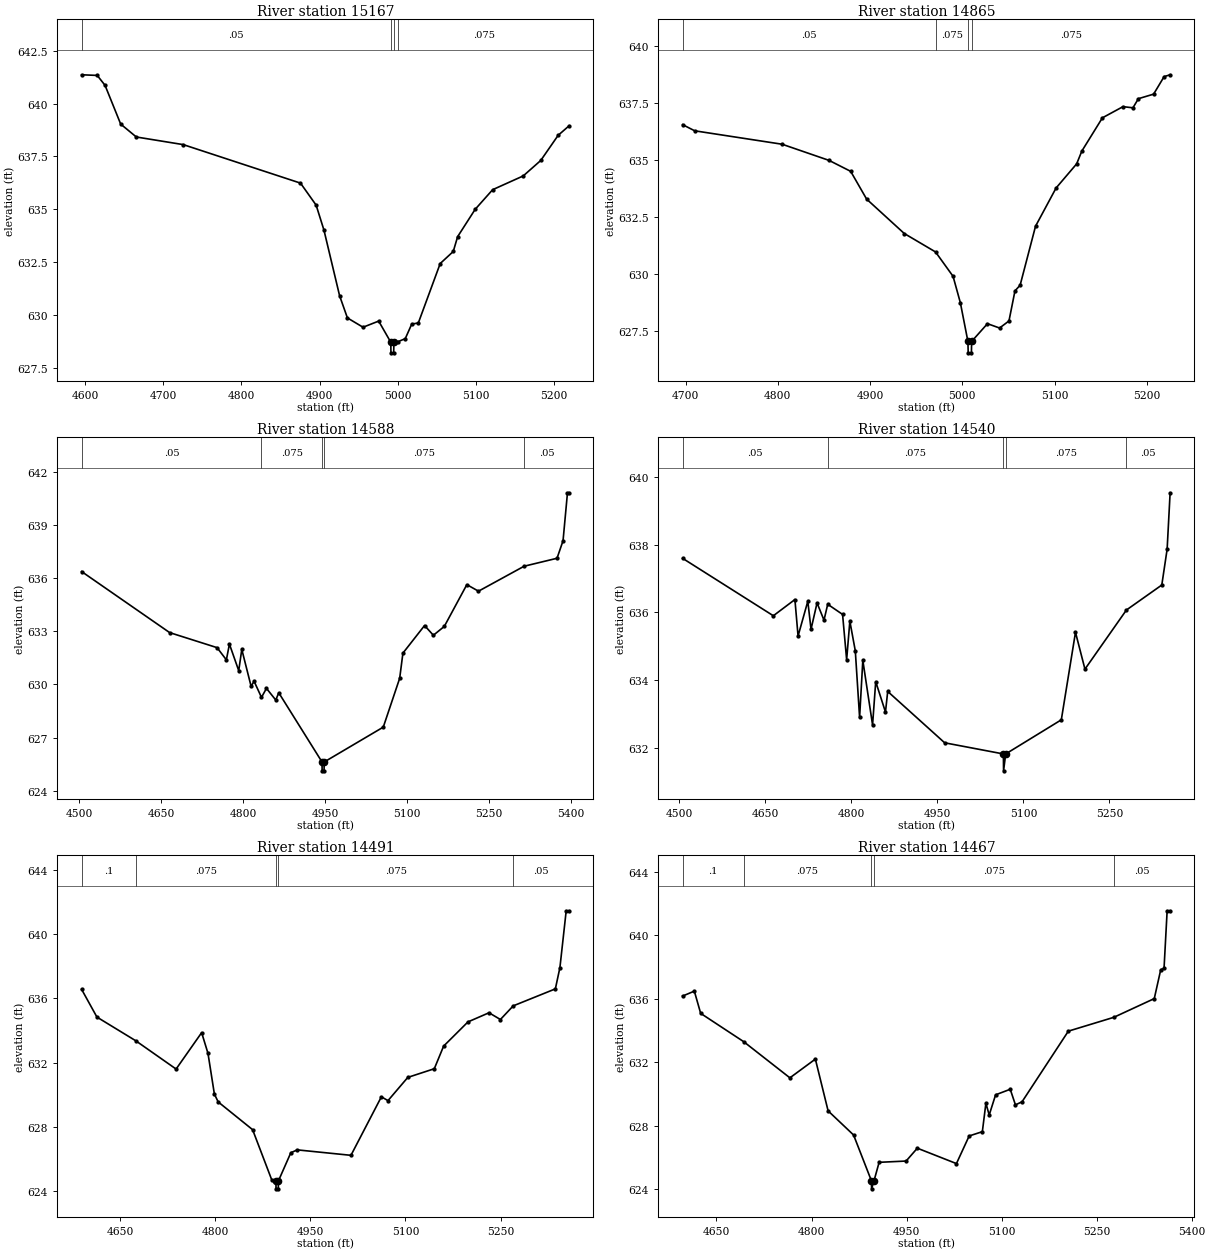
Type RM Length L Ch R = 1 ,15167   ,302,302,302
BEGIN DESCRIPTION:
Cade Branch 29.0
END DESCRIPTION:
XS GIS Cut Line= 3
      2356979.02        7050260.        2357379.        7050260.
      2357579.01        7050160.
#Sta/Elev= 30
  4595.5  641.36  4615.5  641.33  4625.5  640.86  4645.5  639.03  4665.5  638.42
  4725.5  638.06  4875.5  636.24  4895.5   635.2  4905.5  634.02  4925.5  630.92
  4935.5  629.87  4955.5  629.43  4975.5  629.72    4991  628.72  4991.2  628.22
  4994.7  628.22    4995  628.72  5000.3  628.75  5009.5  628.89  5017.8  629.58
  5026.2  629.63  5054.2  632.44  5070.9  633.01  5076.5  633.71  5098.9     635
  5121.3  635.93  5160.4  636.58  5182.8  637.31  5205.1   638.5  5219.1  638.95
#Mann= 4 ,-1 , 0
  4595.5     .05       0    4991    .033       0    4995     .05       0
  5000.3    .075       0
Bank Sta=4991,4995
XS Rating Curve= 0 ,0
Exp/Cntr=0.3,0.1

Type RM Length L Ch R = 1 ,14865   ,277,277,277
BEGIN DESCRIPTION:
Cade Branch 28.0
END DESCRIPTION:
XS GIS Cut Line= 3
      2357232.85      7050557.68      2357561.83        7050497.
      2357735.01      7050409.62
#Sta/Elev= 30
  4696.8  636.54  4709.9  636.27  4804.7  635.68  4855.6  634.97    4879  634.49
  4896.3  633.27  4937.1  631.76    4971  630.95    4990  629.88  4997.9  628.72
  5006.1  627.02  5006.4  626.52  5009.9  626.52  5010.1  627.02  5027.3   627.8
  5040.4  627.61  5050.6  627.92  5057.1  629.24  5062.7  629.49  5079.4  632.08
  5101.7  633.76    5124  634.82  5129.6  635.38  5151.9  636.84  5174.2  637.33
    5185  637.28  5190.9  637.68  5207.4  637.88  5218.8  638.65  5225.3  638.73
#Mann= 4 ,-1 , 0
  4696.8     .05       0    4971    .075       0  5006.1     .07       0
  5010.1    .075       0
Bank Sta=5006.1,5010.1
XS Rating Curve= 0 ,0
Exp/Cntr=0.3,0.1

Type RM Length L Ch R = 1 ,14588   ,48,48,48
BEGIN DESCRIPTION:
Cade Branch 27.4
END DESCRIPTION:
XS GIS Cut Line= 5
      2357213.67      7050575.26      2357418.09      7050631.16
      2357585.79      7050712.61      2357775.85      7050714.21
      2358069.77      7050640.73
#Sta/Elev= 30
  4504.8  636.38  4665.8  632.93  4752.5  632.08  4769.5  631.39  4775.1  632.28
  4792.1  630.78  4797.7  631.98  4814.7   629.9  4820.2  630.18  4833.7  629.27
  4842.8  629.78  4859.8  629.12  4865.3  629.53  4944.4  625.62  4944.6  625.12
  4948.1  625.12  4948.4  625.62  5056.4  627.59  5086.4  630.35  5092.3  631.77
  5131.9  633.33    5148  632.78    5168  633.28  5209.2  635.64  5230.5  635.27
  5313.9  636.68  5374.1  637.13  5385.1  638.12  5393.2  640.83  5396.2  640.83
#Mann= 5 ,-1 , 0
  4504.8     .05       0  4833.7    .075       0  4944.4     .07       0
  4948.4    .075       0  5313.9     .05       0
Bank Sta=4944.4,4948.4
XS Rating Curve= 0 ,0
Exp/Cntr=0.3,0.1

Type RM Length L Ch R = 1 ,14540   ,49,49,49
BEGIN DESCRIPTION:
Cade Branch 27.3
END DESCRIPTION:
XS GIS Cut Line= 5
      2357240.81       7050663.1       2357413.3       7050664.7
        2357581.      7050746.15      2357771.06      7050747.75
      2358063.08      7050674.75
#Sta/Elev= 30
  4505.8   637.6    4664   635.9  4701.6  636.38  4707.1   635.3  4724.1  636.33
  4729.7   635.5  4740.2  636.28  4752.3  635.77  4758.8  636.24  4784.7  635.94
  4791.8   634.6  4797.4  635.74  4806.9  634.86  4814.4  632.89    4820  634.58
    4837  632.67  4842.5  633.95  4859.5  633.05  4863.4  633.66  4962.7  632.14
  5065.1  631.81  5065.4  631.31  5069.1  631.81  5166.1  632.82  5190.8  635.41
  5207.3  634.32  5279.6  636.07  5341.3  636.81  5350.6  637.87  5355.8  639.54
#Mann= 5 ,-1 , 0
  4505.8     .05       0  4758.8    .075       0  5065.1     .07       0
  5069.1    .075       0  5279.6     .05       0
Bank Sta=5065.1,5069.1
XS Rating Curve= 0 ,0
Exp/Cntr=0.3,0.1

Type RM Length L Ch R = 1 ,14491   ,24,24,24
BEGIN DESCRIPTION:
Cade Branch 27.2
END DESCRIPTION:
XS GIS Cut Line= 4
      2357320.67      7050827.61      2357700.79      7050787.68
      2357745.51      7050795.67      2358072.89      7050698.25
#Sta/Elev= 30
    4589  636.57  4613.2  634.84  4674.2  633.37  4738.1   631.6  4778.4  633.87
  4788.4  632.58  4798.5  630.04  4804.5  629.55  4858.8  627.82    4889  624.69
  4895.6  624.63  4895.8  624.13  4899.3  624.13  4899.6  624.63  4919.1  626.38
  4929.2  626.56    5014  626.22    5062  629.87  5072.4  629.63  5103.7  631.08
  5145.5  631.62  5160.2  633.03  5198.6  634.54  5231.8  635.11  5249.8  634.69
    5270  635.54  5336.5   636.6  5343.7  637.93  5353.6  641.47  5358.2  641.47
#Mann= 5 ,-1 , 0
    4589      .1       0  4674.2    .075       0  4895.6     .07       0
  4899.6    .075       0    5270     .05       0
Bank Sta=4895.6,4899.6
XS Rating Curve= 0 ,0
Exp/Cntr=0.3,0.1

Type RM Length L Ch R = 1 ,14467   ,76,76,76
BEGIN DESCRIPTION:
Cade Branch 27.0
END DESCRIPTION:
XS GIS Cut Line= 4
      2357320.65      7050851.57      2357700.79      7050811.64
      2357745.51      7050819.62      2358072.96      7050722.19
#Sta/Elev= 30
  4596.6  636.18  4615.1  636.49  4625.1  635.09  4692.9  633.31  4765.9  631.03
  4806.1  632.21  4826.2  628.95  4866.4  627.43  4894.6  624.54  4894.8  624.04
  4898.6  624.54  4906.7  625.71  4949.3  625.79    4967   626.6  5028.7  625.63
  5048.8  627.37  5069.6  627.64  5075.2  629.43  5080.4  628.69  5090.5  629.96
  5113.6  630.31  5121.8  629.33  5132.2  629.52  5205.3  633.97    5277  634.84
  5340.9  636.02  5351.1  637.84  5356.3  637.92  5361.2  641.55  5365.9  641.55
#Mann= 5 ,-1 , 0
  4596.6      .1       0  4692.9    .075       0  4894.6     .07       0
  4898.6    .075       0    5277     .05       0
Bank Sta=4894.6,4898.6
XS Rating Curve= 0 ,0
Exp/Cntr=0.3,0.1

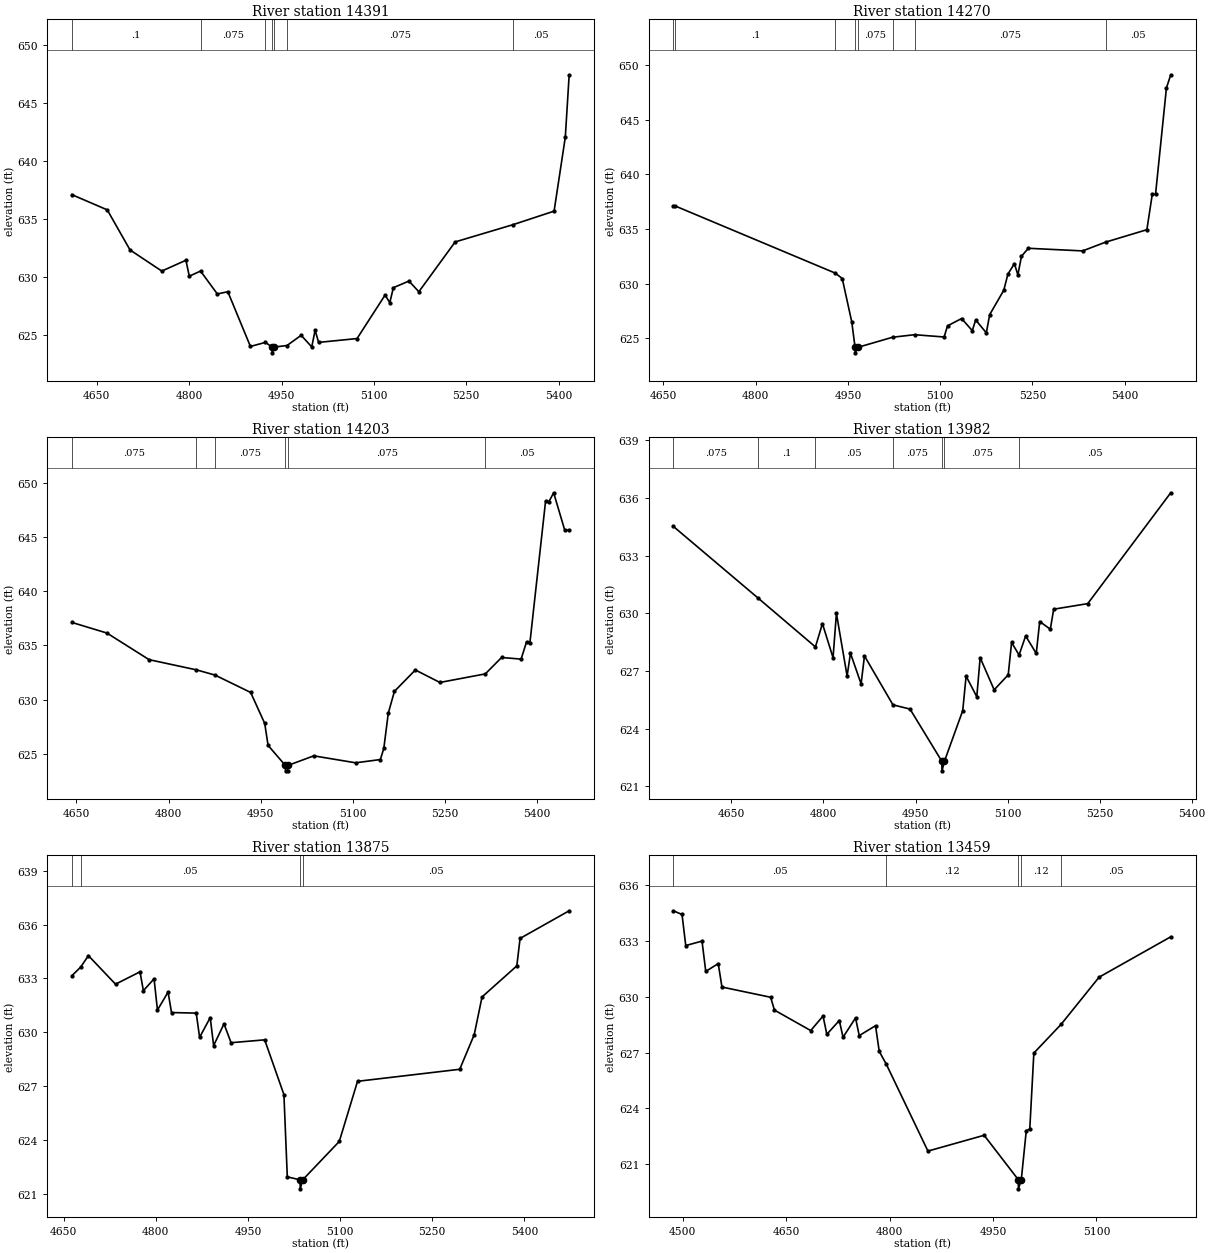
Type RM Length L Ch R = 1 ,14391   ,121,121,121
BEGIN DESCRIPTION:
Cade Branch 26.8
END DESCRIPTION:
XS GIS Cut Line= 3
      2357327.05      7051044.82      2357793.42      7050822.82
      2358075.05      7050748.04
#Sta/Elev= 30
  4609.4  637.12  4666.9  635.81  4703.9  632.36  4755.5  630.54  4794.7  631.47
  4800.2   630.1  4818.5  630.54  4845.7  628.57  4862.8  628.76  4899.5  624.05
  4923.9   624.4  4934.5     624  4934.7   623.5  4938.5     624  4958.9  624.13
  4981.9  625.01  4999.1  624.01  5004.6  625.44  5010.3   624.4  5072.7  624.73
  5118.2  628.47  5125.9  627.82  5131.7  629.11    5157  629.68  5173.1  628.76
  5232.1  633.05  5326.4  634.54  5392.8   635.7    5411  642.06  5417.3  647.44
#Mann= 7 ,-1 , 0
  4609.4      .1       0  4818.5    .075       0  4923.9      .1       0
  4934.5     .07       0  4938.5      .1       0  4958.9    .075       0
  5326.4     .05       0
Bank Sta=4934.5,4938.5
XS Rating Curve= 0 ,0
Exp/Cntr=0.3,0.1

Type RM Length L Ch R = 1 ,14270   ,67,67,67
BEGIN DESCRIPTION:
Cade Branch 26.6
END DESCRIPTION:
XS GIS Cut Line= 3
      2357346.19       7051121.5      2357914.81      7050856.36
      2358085.64      7050796.25
#Sta/Elev= 30
  4666.3   637.1  4669.7   637.1  4929.7  630.96  4940.8  630.47  4956.3  626.49
  4961.6  624.17  4961.9  623.67  4965.9  624.17  5022.8   625.1  5058.4  625.33
  5106.4  625.12  5111.9  626.14  5134.8  626.81  5152.2   625.7  5157.7  626.68
    5175   625.5  5180.5  627.17  5203.4   629.4  5210.1  630.88  5220.7  631.83
  5226.3   630.8  5232.1   632.5  5243.2  633.24  5331.6     633  5368.8   633.8
    5436  634.94  5444.8  638.18  5450.1  638.19  5467.8  647.91  5474.8  649.12
#Mann= 8 ,-1 , 0
  4666.3    .075       0  4669.7      .1       0  4929.7    .075       0
  4961.6     .07       0  4965.9    .075       0  5022.8      .1       0
  5058.4    .075       0  5368.8     .05       0
Bank Sta=4961.6,4965.9
XS Rating Curve= 0 ,0
Exp/Cntr=0.3,0.1

Type RM Length L Ch R = 1 ,14203   ,221,221,221
BEGIN DESCRIPTION:
Cade Branch 26.4
END DESCRIPTION:
XS GIS Cut Line= 3
      2357371.79      7051178.98      2357940.36      7050913.86
      2358112.85      7050853.16
#Sta/Elev= 30
  4642.5  637.12  4699.7  636.14  4768.3  633.69  4845.5  632.75  4875.7  632.27
  4933.8  630.67  4956.7  627.82  4962.2  625.79  4990.3  623.95  4990.7  623.45
  4994.3  623.45  4994.6  623.95  5036.6  624.83  5104.9  624.19  5145.1  624.49
  5150.7  625.51    5158  628.76    5168  630.77  5202.1  632.74  5242.1  631.59
  5316.1  632.38  5342.6  633.89  5374.4  633.74  5383.3  635.34  5388.6  635.18
  5414.3  648.31  5419.6  648.23  5427.4  649.06  5445.2  645.67  5452.7  645.59
#Mann= 6 ,-1 , 0
  4642.5    .075       0  4845.5      .1       0  4875.7    .075       0
  4990.3     .07       0  4994.6    .075       0  5316.1     .05       0
Bank Sta=4990.3,4994.6
XS Rating Curve= 0 ,0
Exp/Cntr=0.3,0.1

Type RM Length L Ch R = 1 ,13982   ,107,107,107
BEGIN DESCRIPTION:
Cade Branch 26.2
END DESCRIPTION:
XS GIS Cut Line= 3
      2357470.76      7051246.08      2358039.39      7050980.94
      2358211.92      7050920.23
#Sta/Elev= 30
  4555.5  634.51  4693.4  630.79  4786.9  628.25  4798.3  629.46  4815.6  627.69
  4821.1  629.99  4838.5  626.74    4844  627.92  4861.3  626.33  4866.8  627.78
  4913.2  625.24    4941  625.02  4992.8  622.31  4993.1  621.81  4997.1  622.31
  5026.9  624.94  5032.4  626.73  5049.8  625.66  5055.3  627.69  5078.1  626.02
    5101   626.8  5106.5  628.48  5118.7  627.83  5129.4  628.82  5146.7  627.91
  5152.3  629.57  5169.6  629.17  5175.1  630.21  5230.6   630.5  5365.8  636.26
#Mann= 7 ,-1 , 0
  4555.5    .075       0  4693.4      .1       0  4786.9     .05       0
  4913.2    .075       0  4992.8     .07       0  4997.1    .075       0
  5118.7     .05       0
Bank Sta=4992.8,4997.1
XS Rating Curve= 0 ,0
Exp/Cntr=0.3,0.1

Type RM Length L Ch R = 1 ,13875   ,416,416,416
BEGIN DESCRIPTION:
Cade Branch 26.0
END DESCRIPTION:
XS GIS Cut Line= 3
      2357614.57      7051292.37      2358183.13      7051027.25
      2358354.78      7050966.86
#Sta/Elev= 30
  4663.5  633.15  4677.8  633.63  4690.5  634.27  4734.6  632.68  4774.4  633.37
  4779.9  632.32  4797.3  632.98  4802.8  631.24  4820.1  632.24  4825.7   631.1
  4865.9  631.07  4871.4  629.72  4888.7  630.82  4894.2  629.26  4911.1  630.47
  4922.6  629.42  4977.3  629.58  5008.6  626.53  5014.1  621.95  5034.8  621.78
  5035.2  621.28  5039.1  621.78  5098.7  623.92  5128.4  627.27  5294.7  627.94
  5318.3  629.87    5331  631.97  5387.6   633.7  5392.9  635.23  5472.8  636.77
#Mann= 4 ,-1 , 0
  4663.5    .075       0  4677.8     .05       0  5034.8     .05       0
  5039.1     .05       0
Bank Sta=5034.8,5039.1
XS Rating Curve= 0 ,0
Exp/Cntr=0.3,0.1

Type RM Length L Ch R = 1 ,13459   ,459,459,459
BEGIN DESCRIPTION:
Cade Branch 25.0
END DESCRIPTION:
XS GIS Cut Line= 3
      2357806.16       7051351.5      2358243.82      7051163.01
      2358483.43      7051113.49
#Sta/Elev= 30
  4486.5  634.63    4499  634.43  4504.4  632.76    4528     633  4533.4  631.37
  4551.5  631.79  4556.9  630.53  4627.5  629.98    4633  629.29  4685.6  628.19
  4703.5  628.97    4709  627.99  4727.1  628.73  4732.5  627.83  4750.6  628.87
    4756  627.92  4779.6  628.45    4785  627.07  4795.1  626.39  4855.6  621.71
  4937.1  622.56  4986.5  620.18  4986.9  619.68    4991  620.18  4998.2   622.8
  5003.3   622.9  5009.2  626.98  5048.6  628.52  5103.8  631.06  5207.7  633.23
#Mann= 5 ,-1 , 0
  4486.5     .05       0  4795.1     .12       0  4986.5     .07       0
    4991     .12       0  5048.6     .05       0
Bank Sta=4986.5,4991
XS Rating Curve= 0 ,0
Exp/Cntr=0.3,0.1

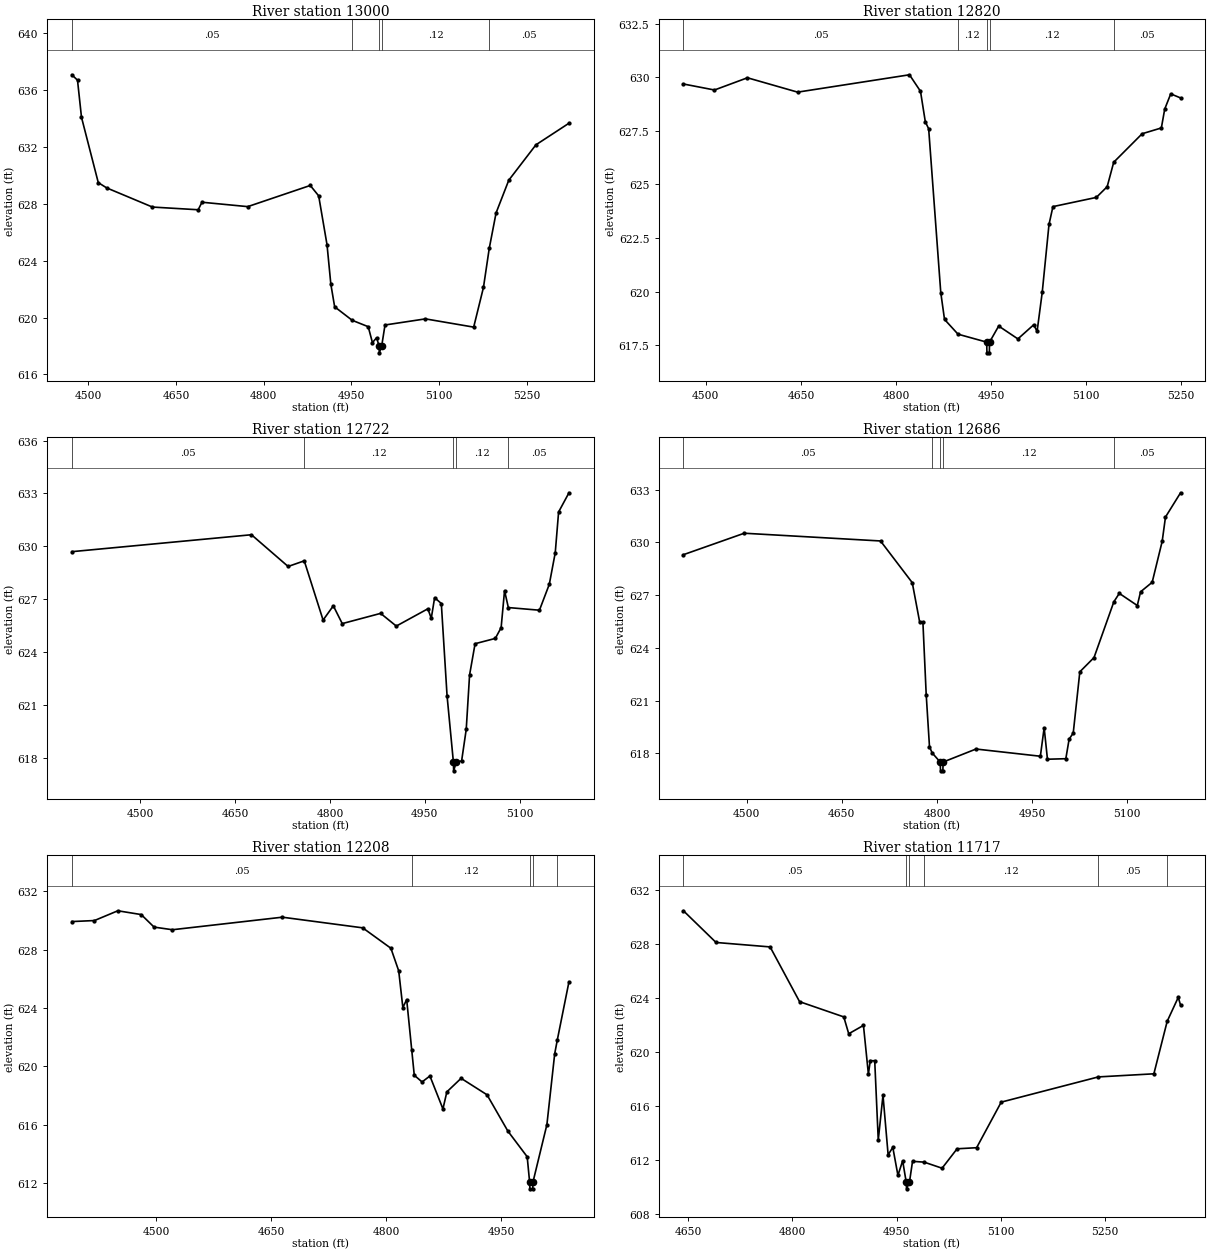
Type RM Length L Ch R = 1 ,13000   ,180,180,180
BEGIN DESCRIPTION:
Cade Branch 24.0
END DESCRIPTION:
XS GIS Cut Line= 3
      2358063.35       7051787.5      2358411.53      7051362.66
      2358526.46      7051084.89
#Sta/Elev= 30
  4472.1  637.09  4481.8  636.71  4488.6   634.1  4517.3   629.5  4531.6  629.13
  4609.9  627.78  4688.1  627.59  4694.6  628.12  4772.8  627.81  4879.7   629.3
  4894.1  628.57  4908.4  625.12  4914.9  622.35  4921.4  620.76  4951.4  619.81
  4978.8  619.36    4986  618.24  4993.1  618.58  4997.3  618.02  4997.8  617.52
  5001.9  618.02  5007.5  619.48  5076.6  619.91  5159.1  619.33  5175.8  622.12
  5185.7  624.87  5197.4  627.37  5219.1  629.67  5265.5  632.16    5322  633.68
#Mann= 5 ,-1 , 0
  4472.1     .05       0  4951.4     .12       0  4997.3     .07       0
  5001.9     .12       0  5185.7     .05       0
Bank Sta=4997.3,5001.9
XS Rating Curve= 0 ,0
Exp/Cntr=0.3,0.1

Type RM Length L Ch R = 1 ,12820   ,98,98,98
BEGIN DESCRIPTION:
Cade Branch 23.2
END DESCRIPTION:
XS GIS Cut Line= 3
      2358219.22       7051778.9       2358491.9      7051609.86
      2358654.19      7051175.52
#Sta/Elev= 30
  4464.6  629.68  4513.6   629.4  4565.6  629.97  4644.8   629.3  4821.3  630.11
  4838.7  629.34  4846.3  627.92  4851.6  627.59  4870.7  619.95  4876.6   618.7
  4897.9  618.01  4943.1  617.64  4943.6  617.14  4947.3  617.14  4947.7  617.64
  4962.1  618.39  4992.4  617.79  5017.4  618.45  5022.7  618.14  5030.8  619.96
  5041.5  623.13  5047.7  623.96  5116.2  624.39  5133.3  624.89  5143.6  626.03
  5188.5  627.36  5218.8  627.63  5224.1  628.51  5233.6  629.22  5249.1  629.03
#Mann= 5 ,-1 , 0
  4464.6     .05       0  4897.9     .12       0  4943.1     .07       0
  4947.7     .12       0  5143.6     .05       0
Bank Sta=4943.1,4947.7
XS Rating Curve= 0 ,0
Exp/Cntr=0.3,0.1

Type RM Length L Ch R = 1 ,12722   ,36,36,36
BEGIN DESCRIPTION:
Cade Branch 23.1
END DESCRIPTION:
XS GIS Cut Line= 3
      2358274.61      7051815.99      2358547.29      7051646.96
       2358710.2      7051210.91
#Sta/Elev= 30
  4391.7   629.7  4675.8  630.66  4733.8  628.86  4759.3  629.18  4789.1  625.82
  4805.3  626.63  4819.4  625.62  4880.1   626.2  4904.9  625.48  4954.8  626.46
  4960.2  625.92  4965.5  627.09  4976.1  626.76  4985.2  621.52  4995.2  617.77
  4995.6  617.27  4999.8  617.77  5008.2  617.83  5015.5  619.62  5020.8  622.71
  5029.5  624.48  5061.5  624.78  5070.7  625.39  5076.1  627.49  5082.1  626.53
  5131.3  626.38  5146.9  627.85  5156.3  629.64  5161.6  631.95    5178  633.04
#Mann= 5 ,-1 , 0
  4391.7     .05       0  4759.3     .12       0  4995.2     .07       0
  4999.8     .12       0  5082.1     .05       0
Bank Sta=4995.2,4999.8
XS Rating Curve= 0 ,0
Exp/Cntr=0.3,0.1

Type RM Length L Ch R = 1 ,12686   ,478,478,478
BEGIN DESCRIPTION:
Cade Branch 23.0
END DESCRIPTION:
XS GIS Cut Line= 3
      2358308.17      7051843.12      2358612.18      7051618.54
      2358721.75      7051226.84
#Sta/Elev= 30
  4399.9   629.3  4495.9  630.52    4711  630.08  4761.1  627.71  4772.8  625.47
  4777.9  625.47  4783.1  621.35  4788.3  618.38  4792.5  618.03  4805.2  617.51
  4805.7  617.01  4809.4  617.01  4809.8  617.51  4861.7  618.25  4963.3  617.84
  4969.3  619.46  4974.5  617.67  5003.5   617.7  5008.7  618.81  5015.2  619.16
  5025.6  622.64    5048  623.45  5079.3  626.62  5087.9   627.1  5116.3  626.41
  5121.5  627.19  5139.8  627.73  5155.6  630.06  5160.8  631.44  5184.6  632.82
#Mann= 5 ,-1 , 0
  4399.9     .05       0  4792.5     .12       0  4805.2     .07       0
  4809.8     .12       0  5079.3     .05       0
Bank Sta=4805.2,4809.8
XS Rating Curve= 0 ,0
Exp/Cntr=0.3,0.1

Type RM Length L Ch R = 1 ,12208   ,491,491,491
BEGIN DESCRIPTION:
Cade Branch 22.0
END DESCRIPTION:
XS GIS Cut Line= 2
      2358330.04      7051895.17      2358967.28      7051774.84
#Sta/Elev= 30
    4390  629.92  4419.5  629.99    4450  630.66  4480.5   630.4  4497.3  629.54
  4521.2  629.36  4664.6  630.22  4769.4  629.49  4806.2  628.09  4816.4  626.54
  4821.8  624.02  4826.8  624.57  4833.4  621.11  4836.7  619.38  4846.9  618.92
  4857.1  619.33  4874.1  617.07  4879.2  618.24  4897.8  619.17  4931.6  618.04
  4958.8  615.55    4984  613.79  4987.1  612.09  4987.5  611.59  4991.2  611.59
  4991.7  612.09  5009.7  615.99  5019.9  620.86  5023.4  621.83  5038.5  625.79
#Mann= 5 ,-1 , 0
    4390     .05       0  4833.4     .12       0  4987.1     .07       0
  4991.7     .12       0  5023.4     .05       0
Bank Sta=4987.1,4991.7
XS Rating Curve= 0 ,0
Exp/Cntr=0.3,0.1

Type RM Length L Ch R = 1 ,11717   ,296,296,296
BEGIN DESCRIPTION:
Cade Branch 21.0
END DESCRIPTION:
XS GIS Cut Line= 3
       2358535.5       7052412.8      2358727.21      7052221.09
      2359027.29      7051893.73
#Sta/Elev= 30
  4643.4  630.48  4690.3  628.13  4768.1   627.8  4810.5  623.74  4874.1  622.61
  4881.2  621.36  4902.4  621.98  4909.5  618.37  4912.2  619.36  4918.6  619.36
  4923.7  613.48  4930.5   616.8  4937.9  612.38  4944.6  612.94    4952  610.86
  4958.8  611.94  4963.9  610.36  4964.4  609.86  4968.6  610.36    4973   611.9
  4989.7  611.84  5015.5  611.39  5037.1  612.83  5065.2  612.91  5100.6  616.29
  5240.3  618.16  5320.2  618.39  5339.4  622.29  5355.3  624.06  5358.6  623.48
#Mann= 6 ,-1 , 0
  4643.4     .05       0  4963.9     .07       0  4968.6     .05       0
  4989.7     .12       0  5240.3     .05       0  5339.4     .12       0
Bank Sta=4963.9,4968.6
XS Rating Curve= 0 ,0
Exp/Cntr=0.3,0.1