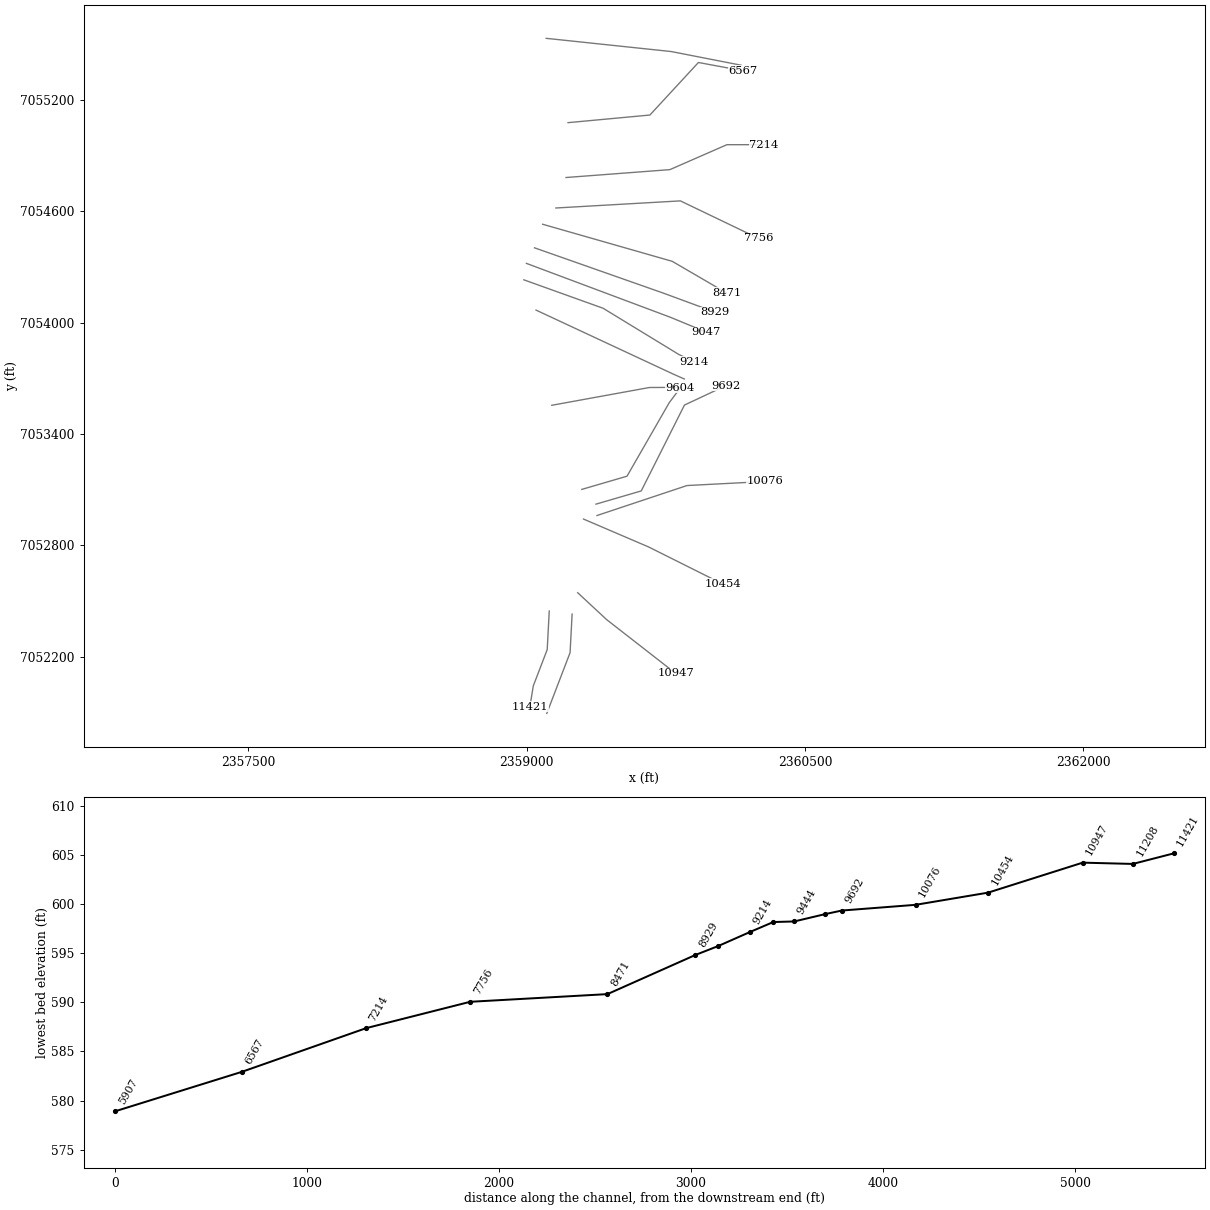
HEC-RAS study Cade Branch.prj: Cade Branch Base Level Engineering

--- Cade Branch.g01 (geometry) --- (continued)

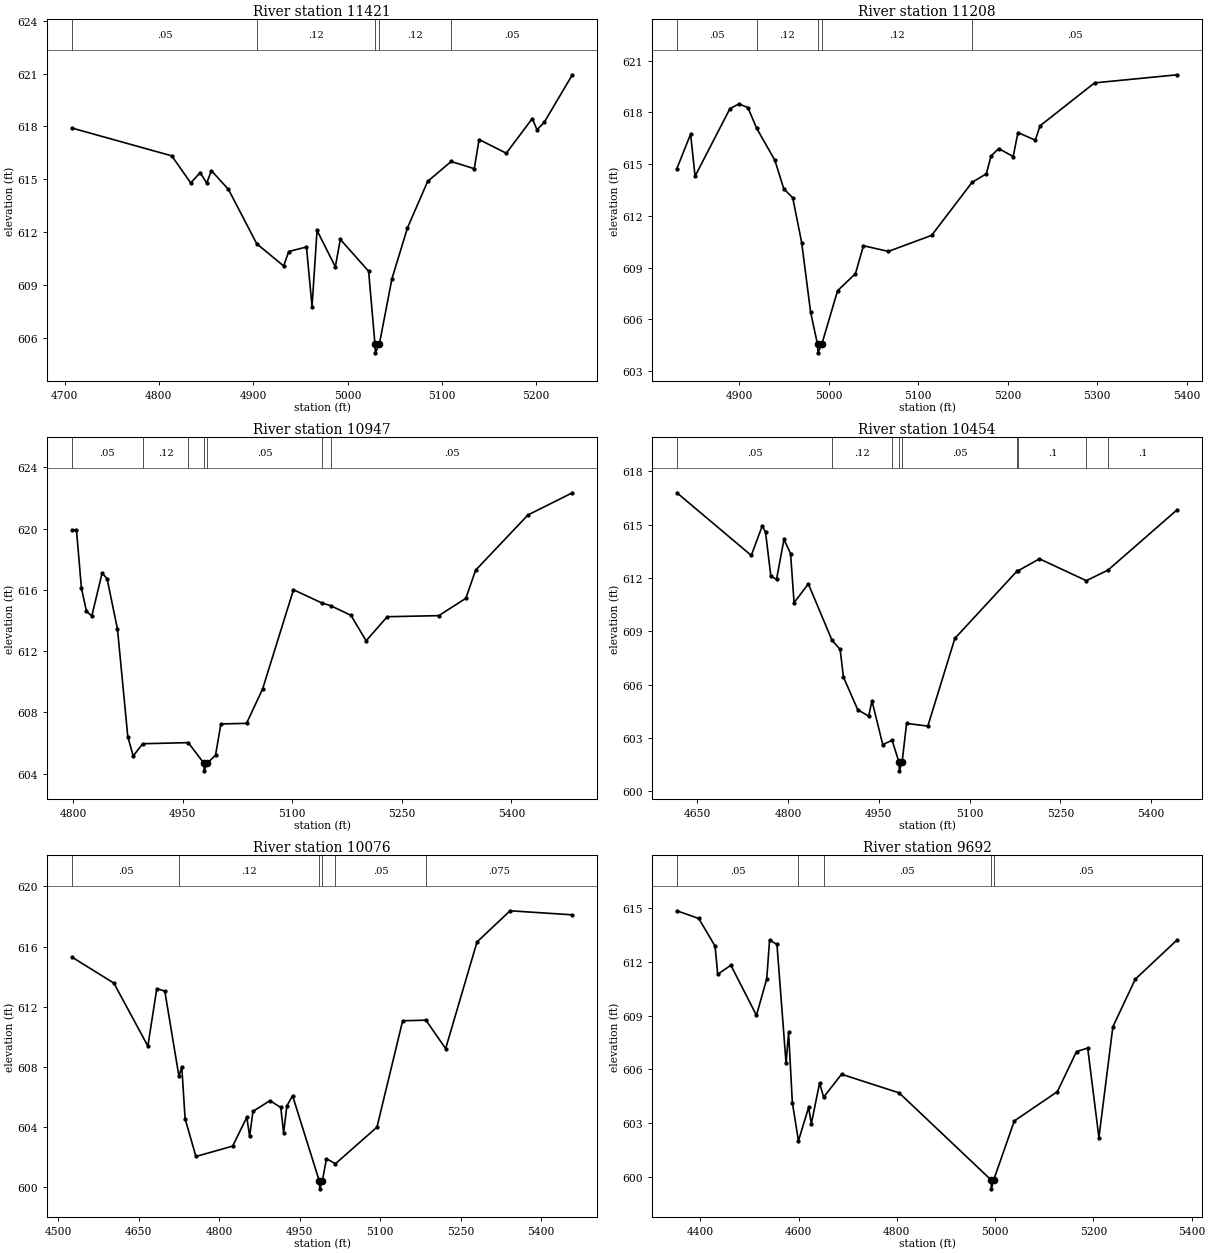
Type RM Length L Ch R = 1 ,11421   ,213,213,213
BEGIN DESCRIPTION:
Cade Branch 20.2
END DESCRIPTION:
XS GIS Cut Line= 4
      2359121.61      7052445.68      2359110.65      7052237.52
      2359035.62      7052041.79      2359017.54      7051930.82
#Sta/Elev= 30
  4707.9  617.91  4813.7  616.33  4833.8  614.79  4843.8  615.38  4850.7  614.78
  4855.7  615.49  4873.8  614.42  4903.8  611.33  4932.3  610.07  4937.7  610.89
  4956.5  611.15  4962.4  607.76  4967.7  612.09  4987.1  610.02  4992.4  611.58
  5022.4  609.77  5029.1  605.63  5029.6  605.13  5033.8  605.63  5047.1  609.34
  5063.6  612.24    5085  614.88  5109.9  616.01  5134.4   615.6  5139.5  617.26
  5168.3  616.48  5195.9  618.45    5201  617.81  5208.8  618.26  5238.4  620.94
#Mann= 5 ,-1 , 0
  4707.9     .05       0  4903.8     .12       0  5029.1     .07       0
  5033.8     .12       0  5109.9     .05       0
Bank Sta=5029.1,5033.8
XS Rating Curve= 0 ,0
Exp/Cntr=0.3,0.1

Type RM Length L Ch R = 1 ,11208   ,261,261,261
BEGIN DESCRIPTION:
Cade Branch 20.0
END DESCRIPTION:
XS GIS Cut Line= 3
      2359244.85      7052429.23       2359233.9      7052221.09
      2359108.42      7051893.75
#Sta/Elev= 30
  4830.5  614.74  4845.8  616.74  4850.8   614.3  4889.8  618.22  4899.8  618.49
  4909.8  618.28  4919.7  617.07  4939.9  615.23  4949.9  613.57  4959.9  613.05
  4969.9  610.45  4979.9  606.41  4987.6  604.56  4988.1  604.06  4992.4  604.56
    5010  607.66    5030  608.65  5038.9  610.27  5066.7  609.94  5115.1  610.87
  5160.2  613.94  5176.2  614.44  5181.5  615.47    5190   615.9  5206.2  615.44
  5211.5  616.83  5230.9  616.39  5236.2  617.22  5297.1  619.71  5389.5  620.18
#Mann= 5 ,-1 , 0
  4830.5     .05       0  4919.7     .12       0  4987.6     .07       0
  4992.4     .12       0  5160.2     .05       0
Bank Sta=4987.6,4992.4
XS Rating Curve= 0 ,0
Exp/Cntr=0.3,0.1

Type RM Length L Ch R = 1 ,10947   ,493,493,493
BEGIN DESCRIPTION:
Cade Branch 19.0
END DESCRIPTION:
XS GIS Cut Line= 3
      2359275.01      7052544.25       2359431.1      7052399.12
      2359803.59      7052108.79
#Sta/Elev= 30
  4798.2  619.92  4804.3  619.92  4811.1  616.12    4818  614.61  4825.3  614.29
  4839.5  617.11  4846.3  616.72  4860.5  613.44  4874.6  606.43    4882  605.16
  4895.1  605.96  4957.5  606.03  4978.8  604.69  4979.3  604.19  4983.6  604.69
  4994.8  605.21  5002.2  607.25  5037.3  607.29  5059.4  609.55  5101.6  616.01
  5140.8  615.14  5152.6  614.97  5180.3  614.34  5201.1  612.68    5230  614.25
  5300.6  614.32  5337.7  615.45    5351  617.28  5422.7  620.89  5483.6  622.34
#Mann= 7 ,-1 , 0
  4798.2     .05       0  4895.1     .12       0  4957.5     .05       0
  4978.8    .033       0  4983.6     .05       0  5140.8    .075       0
  5152.6     .05       0
Bank Sta=4978.8,4983.6
XS Rating Curve= 0 ,0
Exp/Cntr=0.3,0.1

Type RM Length L Ch R = 1 ,10454   ,378,378,378
BEGIN DESCRIPTION:
Cade Branch 18.5
END DESCRIPTION:
XS GIS Cut Line= 3
      2359306.36      7052941.39      2359656.33       7052791.4
      2360055.19      7052591.97
#Sta/Elev= 30
  4616.4   616.8  4739.3  613.27  4757.4  614.93  4762.8  614.59  4771.6  612.11
    4781  611.92  4793.3  614.17  4804.2  613.38    4810  610.61  4833.6  611.67
  4872.7  608.49  4886.1  607.98  4891.6  606.42  4915.2  604.58  4933.3  604.22
  4938.7  605.08  4956.5  602.62    4972  602.86  4983.2  601.64    4984  601.14
  4988.5  601.64  4995.9  603.81    5031  603.66  5075.7   608.6  5178.1  612.38
  5180.8  612.42  5215.4  613.08  5292.9  611.85  5328.9  612.45  5443.1  615.85
#Mann= 9 ,-1 , 0
  4616.4     .05       0  4872.7     .12       0    4972     .05       0
  4983.2    .033       0  4988.5     .05       0  5178.1    .075       0
  5180.8      .1       0  5292.9    .075       0  5328.9      .1       0
Bank Sta=4983.2,4988.5
XS Rating Curve= 0 ,0
Exp/Cntr=0.3,0.1

Type RM Length L Ch R = 1 ,10076   ,384,384,384
BEGIN DESCRIPTION:
Cade Branch 18.0
END DESCRIPTION:
XS GIS Cut Line= 3
      2359379.04      7052960.58      2359863.84      7053122.17
      2360284.85      7053144.05
#Sta/Elev= 30
  4525.7   615.3  4603.8  613.57  4667.1  609.39  4683.8  613.21  4698.7  613.04
    4725  607.38  4730.3  608.02  4736.5  604.56  4756.7  602.05  4825.2  602.74
  4851.5  604.66  4856.8  603.38    4863  605.05  4894.6  605.76  4914.8  605.31
  4920.1  603.63  4926.2  605.41  4936.8  606.09  4986.8   600.4  4987.6   599.9
  4992.2   600.4    5000   601.9  5016.8  601.57  5094.1     604    5142  611.07
  5185.4  611.11  5222.1  609.22  5280.6  616.31  5342.3  618.38  5458.3  618.11
#Mann= 6 ,-1 , 0
  4525.7     .05       0    4725     .12       0  4986.8     .07       0
  4992.2     .12       0  5016.8     .05       0  5185.4    .075       0
Bank Sta=4986.8,4992.2
XS Rating Curve= 0 ,0
Exp/Cntr=0.3,0.1

Type RM Length L Ch R = 1 ,9692    ,88,88,88
BEGIN DESCRIPTION:
Cade Branch 17.0
END DESCRIPTION:
XS GIS Cut Line= 4
      2359373.56      7053021.93      2359617.34      7053093.14
      2359850.14      7053556.01       2360072.8      7053660.65
#Sta/Elev= 30
  4352.5  614.85  4396.9  614.42  4430.3  612.87  4435.5   611.3  4462.3  611.81
  4514.4  609.01  4535.3  611.05  4541.1  613.22  4556.1  612.97  4574.6  606.34
  4579.8  608.06  4587.4  604.14  4599.8     602  4620.5  603.87  4626.1  602.96
  4642.8  605.23  4651.1  604.44  4687.5  605.72  4804.7  604.68  4991.7  599.82
  4992.5  599.32  4997.1  599.82    5039  603.11  5126.7  604.75  5165.6  606.99
  5188.4  607.18  5211.2  602.18  5239.6  608.37  5285.2  611.03  5370.6  613.23
#Mann= 5 ,-1 , 0
  4352.5     .05       0  4599.8     .12       0  4651.1     .05       0
  4991.7     .05       0  4997.1     .05       0
Bank Sta=4991.7,4997.1
XS Rating Curve= 0 ,0
Exp/Cntr=0.3,0.1

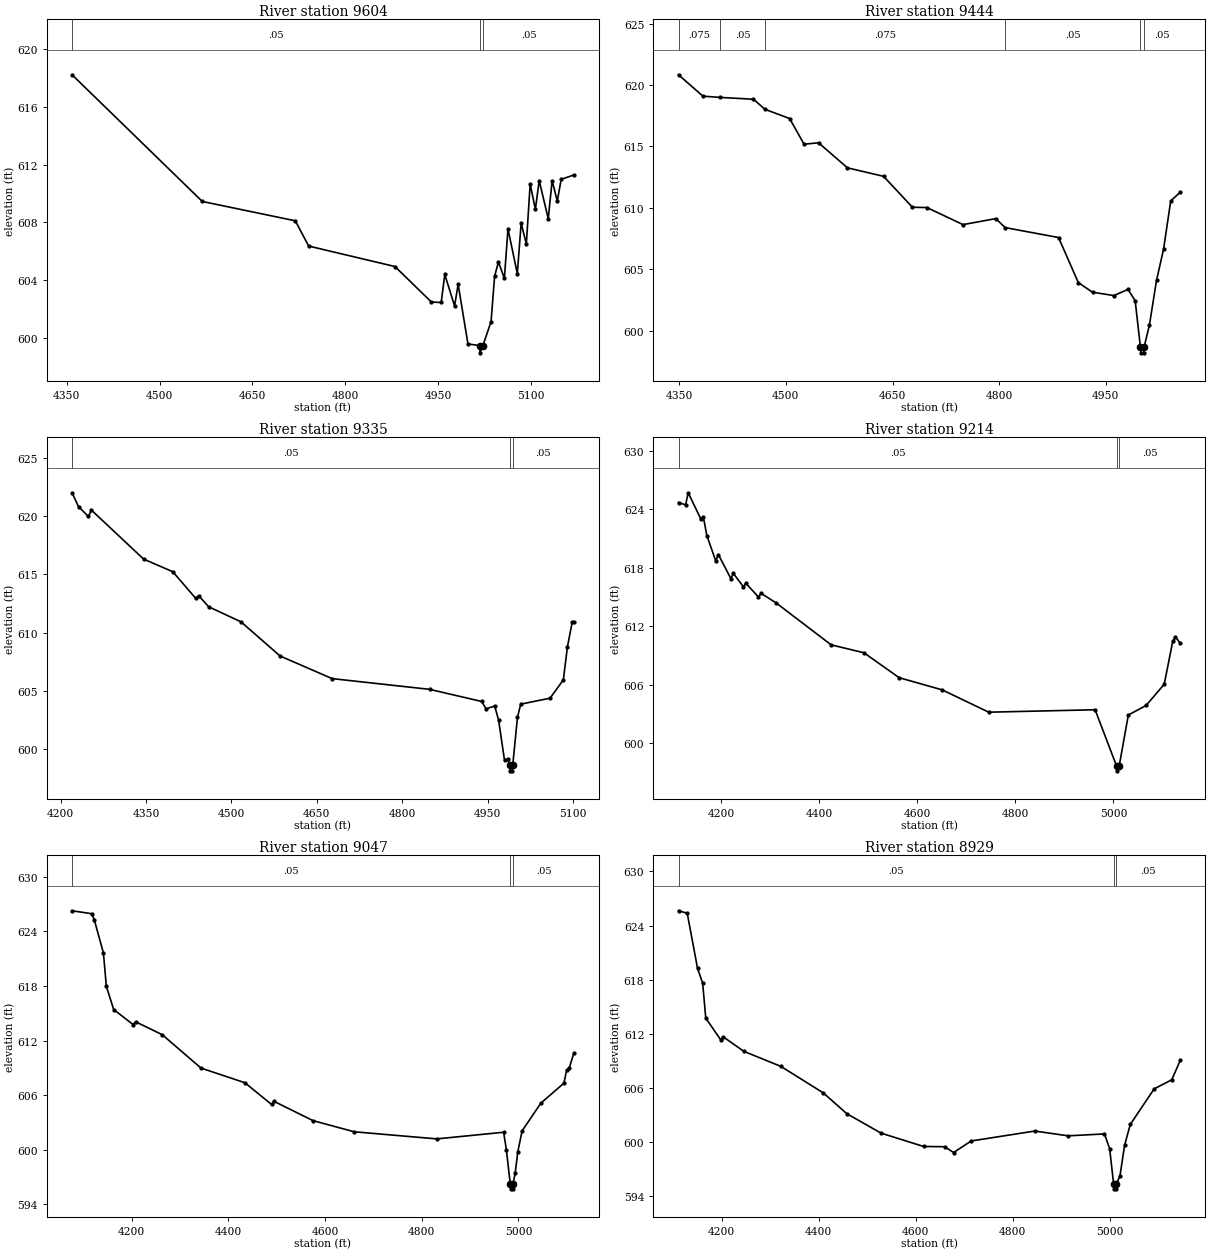
Type RM Length L Ch R = 1 ,9604    ,160,160,160
BEGIN DESCRIPTION:
Cade Branch 16.5
END DESCRIPTION:
XS GIS Cut Line= 4
      2359296.91      7053101.36      2359540.65      7053172.57
      2359767.98      7053568.61      2359828.04       7053649.1
#Sta/Elev= 30
  4358.5  618.22    4569  609.44  4719.3   608.1  4740.9  606.35  4880.4  604.93
  4939.3  602.47  4955.1  602.44  4960.9  604.38  4976.7   602.2  4982.5   603.7
  4998.3  599.57  5017.1  599.45  5017.9  598.95  5022.5  599.45  5035.7  601.12
  5041.4  604.25  5047.6  605.25  5057.2  604.11    5063  607.54  5078.1  604.44
  5084.3  607.93  5092.7   606.5  5098.9  610.65  5107.3   608.9  5113.5  610.88
  5128.1  608.25  5134.4  610.88  5142.7  609.47    5149  610.97  5169.5  611.28
#Mann= 3 ,-1 , 0
  4358.5     .05       0  5017.1     .05       0  5022.5     .05       0
Bank Sta=5017.1,5022.5
XS Rating Curve= 0 ,0
Exp/Cntr=0.3,0.1

Type RM Length L Ch R = 1 ,9444    ,109,109,109
BEGIN DESCRIPTION:
Cade Branch 16.2
END DESCRIPTION:
XS GIS Cut Line= 3
      2359135.26      7053554.91      2359661.16      7053650.77
      2359832.49      7053651.65
#Sta/Elev= 30
    4349  620.83  4383.3  619.09  4407.4  618.99  4454.4  618.84  4470.6  618.02
  4505.3  617.27  4525.6  615.18  4545.9   615.3  4586.6  613.26  4637.4  612.57
  4678.1  610.05  4698.4  610.03  4749.2  608.64  4795.3  609.13  4808.4   608.4
  4883.6  607.59  4911.4  603.92  4931.4  603.14  4961.4  602.87  4981.4  603.37
  4991.4  602.44  4998.7  598.71  4999.5  598.21  5003.3  598.21  5004.1  598.71
  5011.4  600.46  5021.4   604.1  5031.4  606.67  5041.4  610.57  5054.9  611.28
#Mann= 6 ,-1 , 0
    4349    .075       0  4407.4     .05       0  4470.6    .075       0
  4808.4     .05       0  4998.7     .05       0  5004.1     .05       0
Bank Sta=4998.7,5004.1
XS Rating Curve= 0 ,0
Exp/Cntr=0.3,0.1

Type RM Length L Ch R = 1 ,9335    ,121,121,121
BEGIN DESCRIPTION:
Cade Branch 16.0
END DESCRIPTION:
XS GIS Cut Line= 3
      2359050.37      7054068.19      2359789.89      7053723.08
      2359849.24      7053696.76
#Sta/Elev= 30
  4220.2     622  4231.5  620.81  4248.8  619.97  4254.3  620.51  4345.8  616.31
    4397  615.23  4437.2  612.95  4442.7  613.16  4460.1  612.22  4516.8  610.93
  4585.4     608  4676.8  606.06  4847.9  605.14  4939.3   604.1    4947  603.47
  4962.2  603.71  4969.1  602.49  4979.5  599.04    4985  599.19  4988.5  598.65
  4989.2  598.15  4993.1  598.15  4993.9  598.65  5002.2  602.74  5007.9  603.87
  5059.4  604.38  5082.7  605.95    5090  608.81  5098.4  610.93  5101.2  610.93
#Mann= 3 ,-1 , 0
  4220.2     .05       0  4988.5     .05       0  4993.9     .05       0
Bank Sta=4988.5,4993.9
XS Rating Curve= 0 ,0
Exp/Cntr=0.3,0.1

Type RM Length L Ch R = 1 ,9214    ,167,167,167
BEGIN DESCRIPTION:
Cade Branch 15.6
END DESCRIPTION:
XS GIS Cut Line= 4
       2358984.7       7054231.4      2359411.93      7054078.04
      2359820.01       7053828.8      2359902.21      7053790.44
#Sta/Elev= 30
  4113.6  624.68    4128  624.44  4133.3  625.68  4158.7  623.02  4164.1  623.22
  4171.3  621.29  4189.5  618.68  4194.8  619.34  4220.2  616.88  4225.5   617.4
  4245.6  616.04    4251  616.38  4276.4  614.99  4281.7  615.36  4312.4  614.38
  4424.7  610.07  4491.5  609.26  4563.3   606.7    4651  605.45  4745.9  603.16
  4962.7  603.41  5006.4  597.64  5007.1  597.14  5011.8  597.64  5030.4  602.87
  5066.7  603.85  5103.6  606.03    5121  610.46  5126.5  610.89  5136.4  610.23
#Mann= 3 ,-1 , 0
  4113.6     .05       0  5006.4     .05       0  5011.8     .05       0
Bank Sta=5006.4,5011.8
XS Rating Curve= 0 ,0
Exp/Cntr=0.3,0.1

Type RM Length L Ch R = 1 ,9047    ,118,118,118
BEGIN DESCRIPTION:
Cade Branch 15.0
END DESCRIPTION:
XS GIS Cut Line= 3
      2358998.36      7054320.15      2359773.45      7054029.83
      2359967.96      7053949.29
#Sta/Elev= 30
  4076.5  626.26  4117.1  625.94  4122.5  625.26  4141.3  621.64  4147.4  617.96
  4162.6  615.41  4202.6  613.76  4207.9  614.06  4263.1  612.64  4343.3  608.97
  4434.1  607.36  4489.3  604.97  4494.6  605.31  4574.8   603.2  4660.3  601.97
  4831.2  601.19  4969.4  601.92  4975.1  599.98  4983.2   596.2    4984   595.7
  4987.9   595.7  4988.6   596.2  4993.3  597.42  4998.7  599.76  5007.6  602.07
  5046.5  605.12  5094.2  607.32  5099.7  608.74  5105.1  608.97  5114.7  610.63
#Mann= 3 ,-1 , 0
  4076.5     .05       0  4983.2    .033       0  4988.6     .05       0
Bank Sta=4983.2,4988.6
XS Rating Curve= 0 ,0
Exp/Cntr=0.3,0.1

Type RM Length L Ch R = 1 ,8929    ,458,458,458
BEGIN DESCRIPTION:
Cade Branch 14.2
END DESCRIPTION:
XS GIS Cut Line= 3
      2359042.14      7054403.97      2359735.11       7054160.2
      2360015.63      7054056.71
#Sta/Elev= 30
  4111.5  625.64  4129.4  625.37  4150.6  619.27  4161.2   617.6  4167.6  613.73
  4198.5  611.32  4203.8  611.65    4246  610.05  4322.4  608.38    4410  605.43
    4458  603.14  4528.6  600.98  4616.2   599.5  4659.4  599.47  4678.1  598.83
  4714.4  600.11  4845.5  601.21  4913.9  600.68  4988.8  600.89  4999.5  599.26
  5007.8   595.3  5008.6   594.8  5012.5   594.8  5013.2   595.3  5020.8  596.25
  5030.3  599.63  5042.1  601.95  5091.2  605.89  5127.4  606.89  5145.1  609.06
#Mann= 3 ,-1 , 0
  4111.5     .05       0  5007.8     .05       0  5013.2     .05       0
Bank Sta=5007.8,5013.2
XS Rating Curve= 0 ,0
Exp/Cntr=0.3,0.1

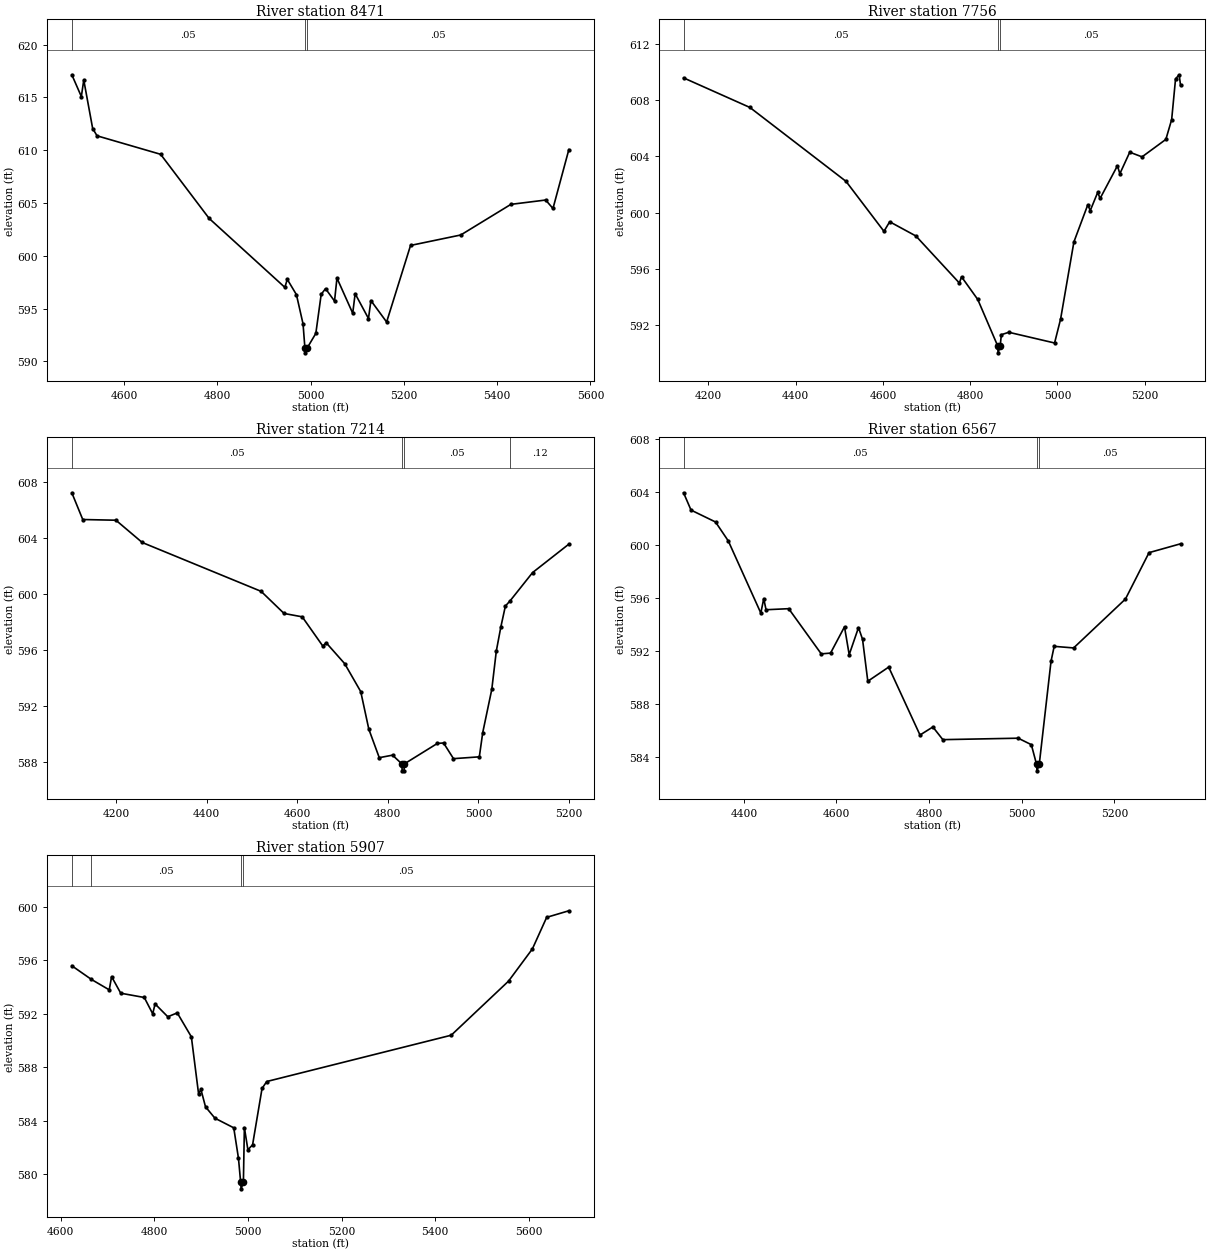
Type RM Length L Ch R = 1 ,8471    ,715,715,715
BEGIN DESCRIPTION:
Cade Branch 14.0
END DESCRIPTION:
XS GIS Cut Line= 3
      2359085.98      7054531.05      2359784.41      7054331.11
      2360077.44      7054160.22
#Sta/Elev= 30
  4487.9  617.15  4508.3  615.09  4513.5  616.65  4532.6  612.06    4542  611.37
  4678.3  609.62  4782.3  603.55  4944.7  597.02  4949.9  597.78  4969.5  596.33
  4983.7  593.56  4987.6  591.32  4988.4  590.82  4993.1  591.32  5011.1  592.66
  5022.6  596.36  5031.9   596.9  5051.2  595.72  5056.4   597.9  5090.2  594.57
  5095.4  596.42    5124  594.07  5129.2  595.77  5162.9  593.74  5214.2  600.99
  5321.9  601.98  5429.4  604.88  5503.9  605.29  5519.6  604.49  5553.6  610.06
#Mann= 3 ,-1 , 0
  4487.9     .05       0  4987.6     .05       0  4993.1     .05       0
Bank Sta=4987.6,4993.1
XS Rating Curve= 0 ,0
Exp/Cntr=0.3,0.1

Type RM Length L Ch R = 1 ,7756    ,542,542,542
BEGIN DESCRIPTION:
Cade Branch 13.5
END DESCRIPTION:
XS GIS Cut Line= 3
      2359157.23      7054618.69      2359828.23      7054657.03
      2360249.34      7054454.68
#Sta/Elev= 30
  4142.9  609.57  4294.9  607.47  4515.3  602.22  4602.3  598.67  4615.4  599.35
  4675.5  598.34  4775.1     595  4780.1  595.44  4817.3  593.83  4862.9  590.54
  4863.9  590.04  4868.7  590.54  4871.4  591.33  4888.5   591.5  4993.4  590.74
  5007.2  592.44  5037.7  597.92  5069.6  600.56  5075.1  600.14  5092.2  601.43
  5097.8  601.01  5137.5  603.33    5143  602.76  5165.7  604.29  5193.9  603.96
  5248.5   605.2  5261.8  606.61  5270.7   609.5  5278.9  609.79  5282.2  609.04
#Mann= 3 ,-1 , 0
  4142.9     .05       0  4862.9    .033       0  4868.7     .05       0
Bank Sta=4862.9,4868.7
XS Rating Curve= 0 ,0
Exp/Cntr=0.3,0.1

Type RM Length L Ch R = 1 ,7214    ,647,647,647
BEGIN DESCRIPTION:
Cade Branch 13.0
END DESCRIPTION:
XS GIS Cut Line= 4
      2359212.01      7054783.02      2359771.63      7054825.53
        2360079.        7054960.      2360278.97        7054960.
#Sta/Elev= 30
  4102.8  607.22  4126.9  605.31  4200.1  605.26  4258.1  603.67  4520.5  600.18
  4571.1   598.6  4611.2  598.36  4656.7  596.27    4664  596.51  4704.8  595.02
  4740.3  593.02  4758.2  590.33  4781.2   588.3  4810.5  588.48  4830.9  587.86
  4831.8  587.36  4835.8  587.36  4836.7  587.86  4909.5  589.32  4923.1  589.35
    4945  588.23    5002  588.36  5009.5  590.09  5029.5  593.18  5039.5  595.92
  5049.5  597.64  5059.5  599.13  5070.1  599.51  5119.5  601.52  5199.5  603.55
#Mann= 4 ,-1 , 0
  4102.8     .05       0  4830.9    .033       0  4836.7     .05       0
  5070.1     .12       0
Bank Sta=4830.9,4836.7
XS Rating Curve= 0 ,0
Exp/Cntr=0.3,0.1

Type RM Length L Ch R = 1 ,6567    ,660,660,660
BEGIN DESCRIPTION:
Cade Branch 12.5
END DESCRIPTION:
XS GIS Cut Line= 4
      2359222.96      7055078.82       2359663.9       7055119.9
      2359925.47      7055403.26      2360165.96      7055358.53
#Sta/Elev= 30
  4269.9  603.96    4286  602.65  4338.9  601.75  4366.4  600.32  4436.7  594.86
    4443  595.95    4448  595.11  4496.9  595.19  4567.2  591.77  4587.3  591.83
  4617.4  593.82  4627.5  591.71  4647.6  593.76  4656.3  592.88  4667.7   589.7
  4712.8  590.77  4780.4  585.63  4808.2  586.24  4829.7  585.28  4992.4  585.39
  5020.8   584.9    5032  583.42    5033  582.92  5037.9  583.42  5063.3  591.21
  5070.1  592.34  5112.1  592.22    5224  595.92  5274.9  599.43    5343   600.1
#Mann= 3 ,-1 , 0
  4269.9     .05       0    5032    .033       0  5037.9     .05       0
Bank Sta=5032,5037.9
XS Rating Curve= 0 ,0
Exp/Cntr=0.3,0.1

Type RM Length L Ch R = 1 ,5907    ,444,444,444
BEGIN DESCRIPTION:
Cade Branch 12.0
END DESCRIPTION:
XS GIS Cut Line= 3
      2359105.19      7055533.46      2359778.93      7055462.25
       2360155.4       7055388.6
#Sta/Elev= 30
    4624  595.58  4665.8  594.56  4703.9  593.78  4708.9  594.77  4728.4  593.53
  4778.7  593.21  4796.7  591.99  4801.7  592.73  4828.9  591.77  4849.1  592.06
  4879.2  590.27  4894.6  586.01  4899.6  586.34  4909.4  585.04  4929.5  584.19
  4969.7  583.47  4979.8  581.19  4984.4  579.41  4985.4  578.91  4990.3  579.41
  4992.4  583.49  4999.9  581.83  5009.9   582.2  5030.1  586.41  5040.1  586.93
    5434  590.39  5556.3  594.43  5607.3  596.84  5637.8   599.2  5685.1  599.69
#Mann= 4 ,-1 , 0
    4624    .075       0  4665.8     .05       0  4984.4    .033       0
  4990.3     .05       0
Bank Sta=4984.4,4990.3
XS Rating Curve= 0 ,0
Exp/Cntr=0.3,0.1