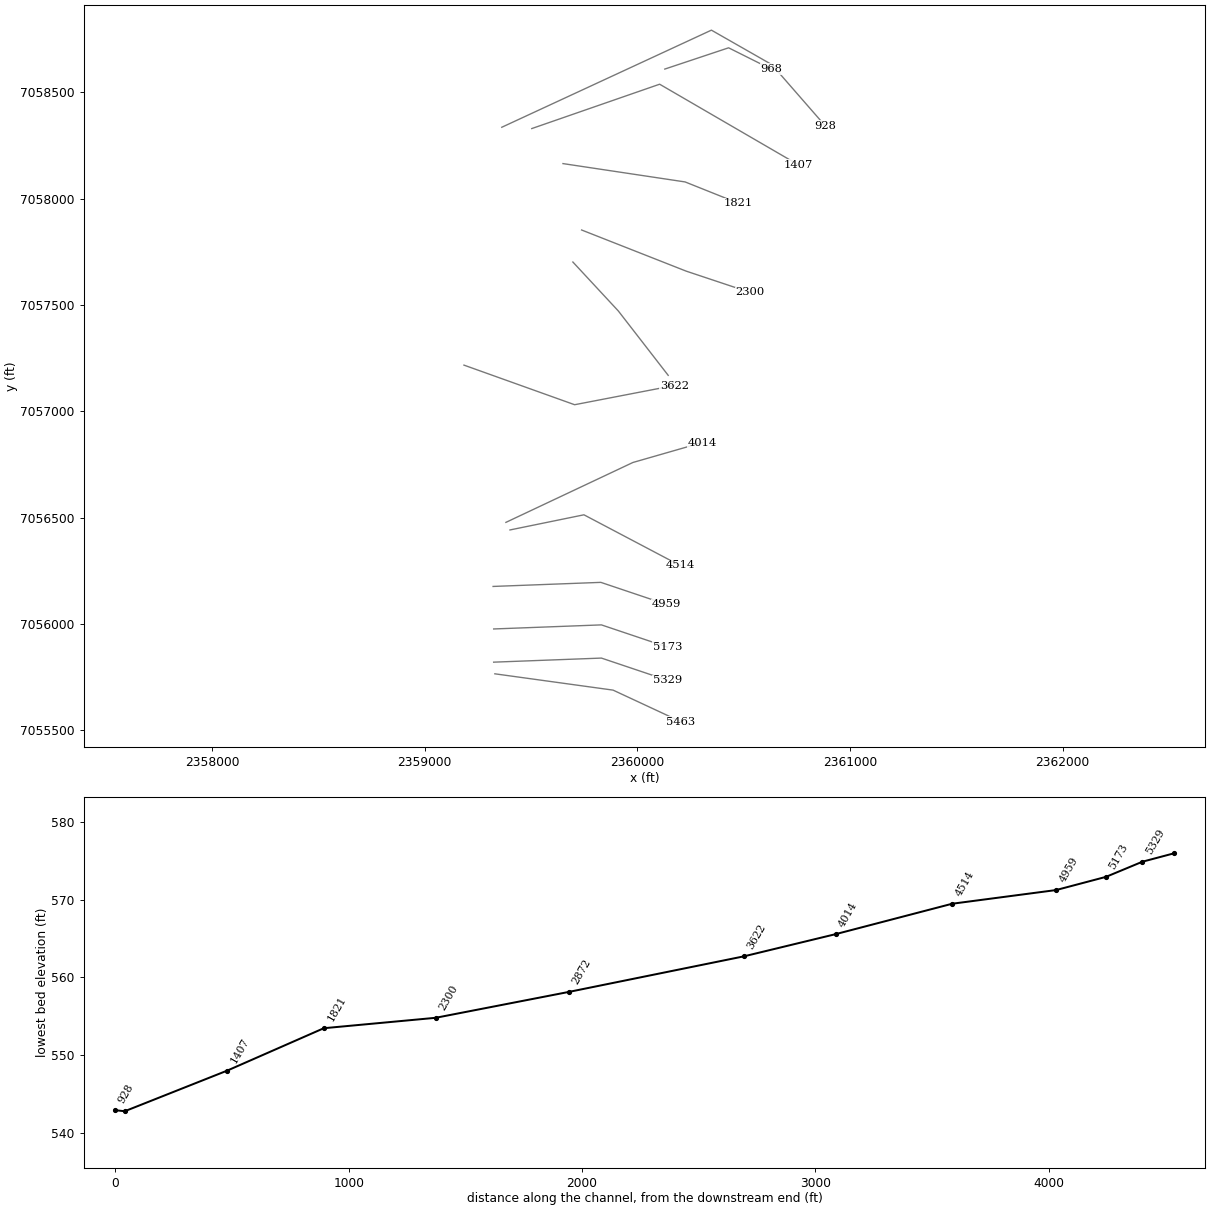
HEC-RAS study Cade Branch.prj: Cade Branch Base Level Engineering

--- Cade Branch.g01 (geometry) --- (continued)

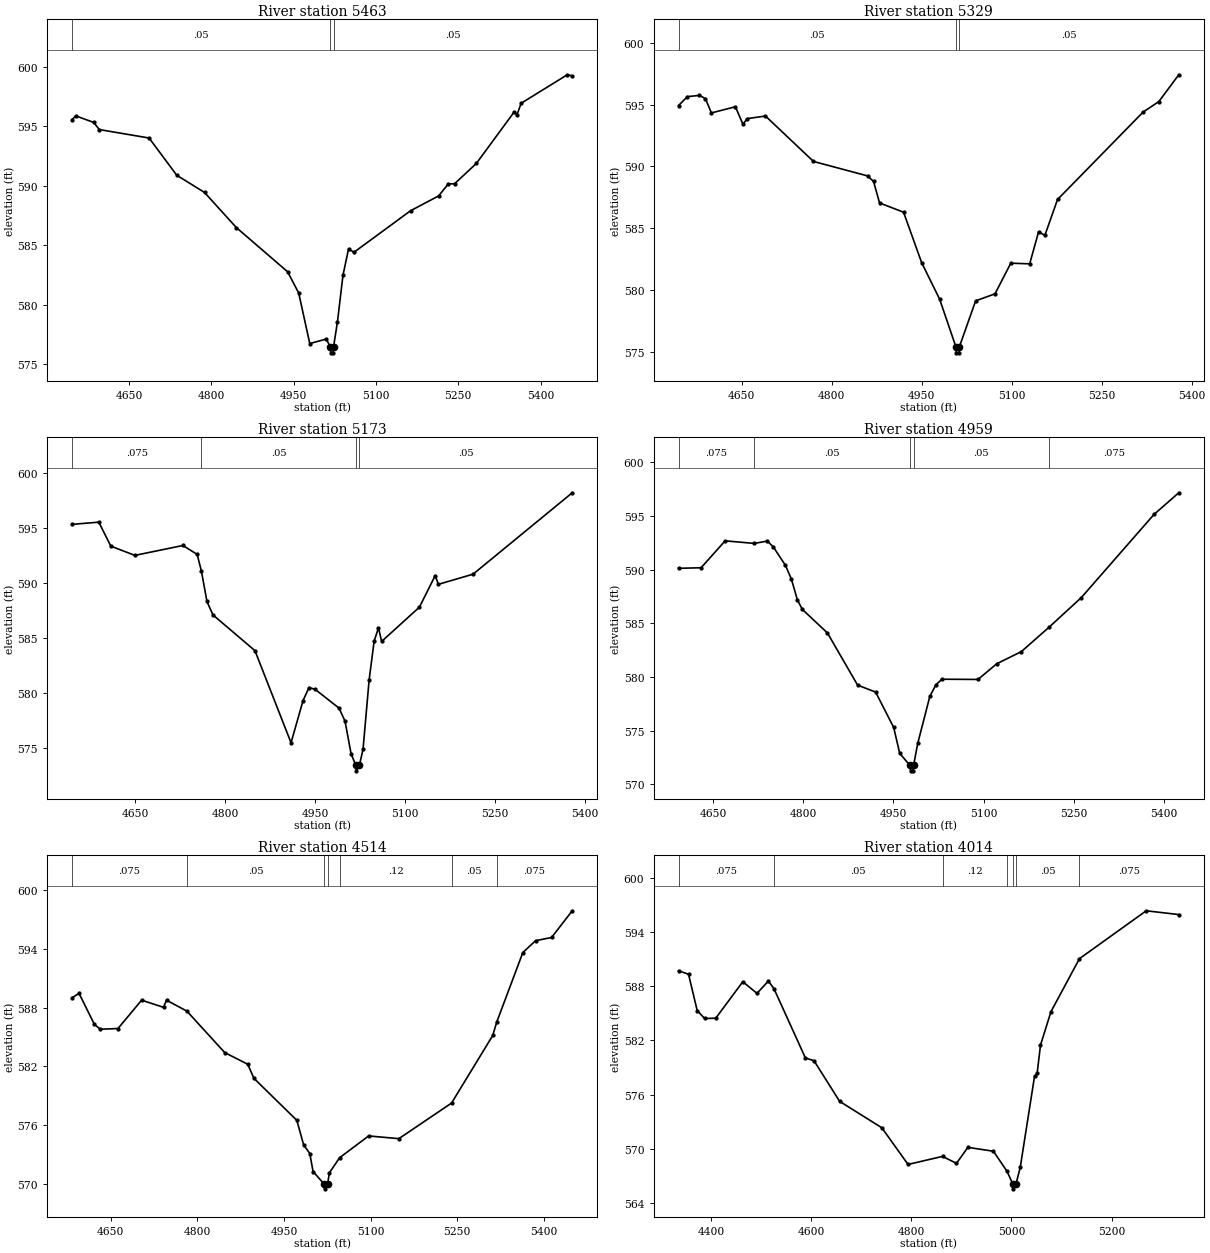
Type RM Length L Ch R = 1 ,5463    ,134,134,134
BEGIN DESCRIPTION:
Cade Branch 11.0
END DESCRIPTION:
XS GIS Cut Line= 3
      2359329.81      7055766.26      2359885.75      7055689.58
      2360203.41       7055541.7
#Sta/Elev= 30
  4546.1  595.54  4552.8  595.87  4585.7  595.32  4595.8  594.72  4686.6  594.01
  4737.1  590.88  4787.6  589.44  4845.6  586.49    4939  582.78  4959.2     581
  4979.4  576.75  5009.6  577.13  5016.7  576.47  5017.7  575.97  5021.7  575.97
  5022.7  576.47  5029.8  578.55  5039.9  582.48    5050  584.68  5060.1  584.42
    5163   587.9  5214.3  589.15  5231.7  590.15  5243.3  590.17  5282.9  591.87
  5351.6  596.18  5357.1  595.97  5364.6  596.93  5448.6  599.32  5457.7  599.23
#Mann= 3 ,-1 , 0
  4546.1     .05       0  5016.7    .033       0  5022.7     .05       0
Bank Sta=5016.7,5022.7
XS Rating Curve= 0 ,0
Exp/Cntr=0.3,0.1

Type RM Length L Ch R = 1 ,5329    ,156,156,156
BEGIN DESCRIPTION:
Cade Branch 10.6
END DESCRIPTION:
XS GIS Cut Line= 3
      2359324.23      7055821.04      2359830.97      7055840.22
      2360140.44      7055736.15
#Sta/Elev= 30
  4544.9  594.93  4559.7  595.65  4579.7  595.75  4589.7  595.49  4599.7  594.33
  4639.7  594.83  4652.2  593.42  4659.7  593.87  4689.8  594.08  4769.8   590.4
  4859.9  589.23  4869.9  588.78  4879.9  587.04  4919.9  586.29    4950  582.21
    4980  579.25    5007   575.4    5008   574.9    5012   574.9    5013   575.4
    5040  579.11  5072.3  579.68  5098.6  582.16  5130.1  582.11  5144.9   584.7
  5155.4  584.42  5176.5  587.32  5319.1   594.4  5345.3  595.25  5378.5  597.42
#Mann= 3 ,-1 , 0
  4544.9     .05       0    5007    .033       0    5013     .05       0
Bank Sta=5007,5013
XS Rating Curve= 0 ,0
Exp/Cntr=0.3,0.1

Type RM Length L Ch R = 1 ,5173    ,214,214,214
BEGIN DESCRIPTION:
Cade Branch 10.4
END DESCRIPTION:
XS GIS Cut Line= 3
       2359324.3      7055977.16      2359830.97      7055996.33
       2360140.5      7055892.24
#Sta/Elev= 30
  4544.7  595.35  4589.4  595.55  4609.4  593.37  4649.5  592.53  4729.5  593.43
  4753.3  592.62  4760.4  591.09  4769.6  588.34  4779.6  587.12  4849.6  583.87
  4909.7   575.5  4929.7  579.33  4939.7  580.52  4949.7  580.36  4989.7  578.65
  4999.7  577.46  5009.7  574.52  5017.6  573.45  5018.6  572.95  5023.6  573.45
  5029.7  574.91  5039.8  581.19  5048.2  584.74  5055.4  585.95  5060.7  584.71
  5123.7  587.83    5150   590.7  5155.2   589.9    5213  590.82  5378.3  598.22
#Mann= 4 ,-1 , 0
  4544.7    .075       0  4760.4     .05       0  5017.6     .05       0
  5023.6     .05       0
Bank Sta=5017.6,5023.6
XS Rating Curve= 0 ,0
Exp/Cntr=0.3,0.1

Type RM Length L Ch R = 1 ,4959    ,445,445,445
BEGIN DESCRIPTION:
Cade Branch 10.0
END DESCRIPTION:
XS GIS Cut Line= 3
      2359321.54       7056177.1      2359828.23      7056196.27
      2360135.85      7056092.82
#Sta/Elev= 30
  4592.7  590.13  4630.2  590.18  4670.2  592.69  4718.7  592.45  4740.3  592.67
  4750.3  592.12  4770.3  590.42  4780.3  589.13  4790.3  587.19  4798.5   586.3
  4840.3   584.1  4890.4  579.24  4920.4  578.59  4950.4  575.29  4960.4  572.89
  4977.4  571.75  4978.4  571.25  4982.4  571.25  4983.4  571.75  4990.4  573.82
  5010.5  578.19  5020.5  579.26  5030.5  579.79  5090.5  579.77  5121.7  581.23
  5162.5  582.36  5208.9  584.65  5262.3   587.4  5383.1  595.15  5424.3  597.17
#Mann= 5 ,-1 , 0
  4592.7    .075       0  4718.7     .05       0  4977.4    .033       0
  4983.4     .05       0  5208.9    .075       0
Bank Sta=4977.4,4983.4
XS Rating Curve= 0 ,0
Exp/Cntr=0.3,0.1

Type RM Length L Ch R = 1 ,4514    ,500,500,500
BEGIN DESCRIPTION:
Cade Branch 9.0
END DESCRIPTION:
XS GIS Cut Line= 3
      2359400.99      7056442.77       2359748.8      7056513.97
       2360200.7       7056275.7
#Sta/Elev= 30
  4583.1  589.02  4595.3  589.48  4621.9   586.3  4632.1  585.81  4662.7  585.88
  4703.6  588.78  4741.5  588.05  4746.7  588.78    4782  587.66  4847.5  583.42
  4887.3  582.23    4898  580.79  4972.3  576.49    4984     574  4994.7   573.1
  5000.4  571.26  5019.4  569.99  5020.4  569.49  5025.4  569.99  5028.8  571.14
  5046.3  572.67  5096.6   574.9  5148.9  574.62  5240.1  578.26  5311.4  585.17
  5318.3  586.54  5363.5  593.65  5385.5  594.86  5413.2  595.19    5449  597.92
#Mann= 7 ,-1 , 0
  4583.1    .075       0    4782     .05       0  5019.4    .033       0
  5025.4     .05       0  5046.3     .12       0  5240.1     .05       0
  5318.3    .075       0
Bank Sta=5019.4,5025.4
XS Rating Curve= 0 ,0
Exp/Cntr=0.3,0.1

Type RM Length L Ch R = 1 ,4014    ,392,392,392
BEGIN DESCRIPTION:
Cade Branch 8.0
END DESCRIPTION:
XS GIS Cut Line= 3
      2359381.84      7056478.39        2359979.        7056760.
      2360304.41      7056853.48
#Sta/Elev= 30
  4335.2   589.7  4355.2  589.32  4372.5   585.3  4387.3  584.42  4409.5  584.45
  4463.6  588.49  4491.9   587.2  4514.7  588.57    4526  587.69  4588.5  580.06
  4605.8  579.74  4656.9  575.25  4741.1  572.33  4793.5  568.27  4862.3  569.16
  4890.2  568.39  4912.9  570.16    4964  569.73  4991.3  567.49  5002.8  566.07
  5003.8  565.57  5008.8  566.07  5017.5  567.94    5046  578.01  5051.2  578.34
  5057.9  581.46  5078.7  585.16  5135.7  591.04  5269.1  596.34    5334  595.92
#Mann= 7 ,-1 , 0
  4335.2    .075       0    4526     .05       0  4862.3     .12       0
  4991.3     .05       0  5002.8    .033       0  5008.8     .05       0
  5135.7    .075       0
Bank Sta=5002.8,5008.8
XS Rating Curve= 0 ,0
Exp/Cntr=0.3,0.1

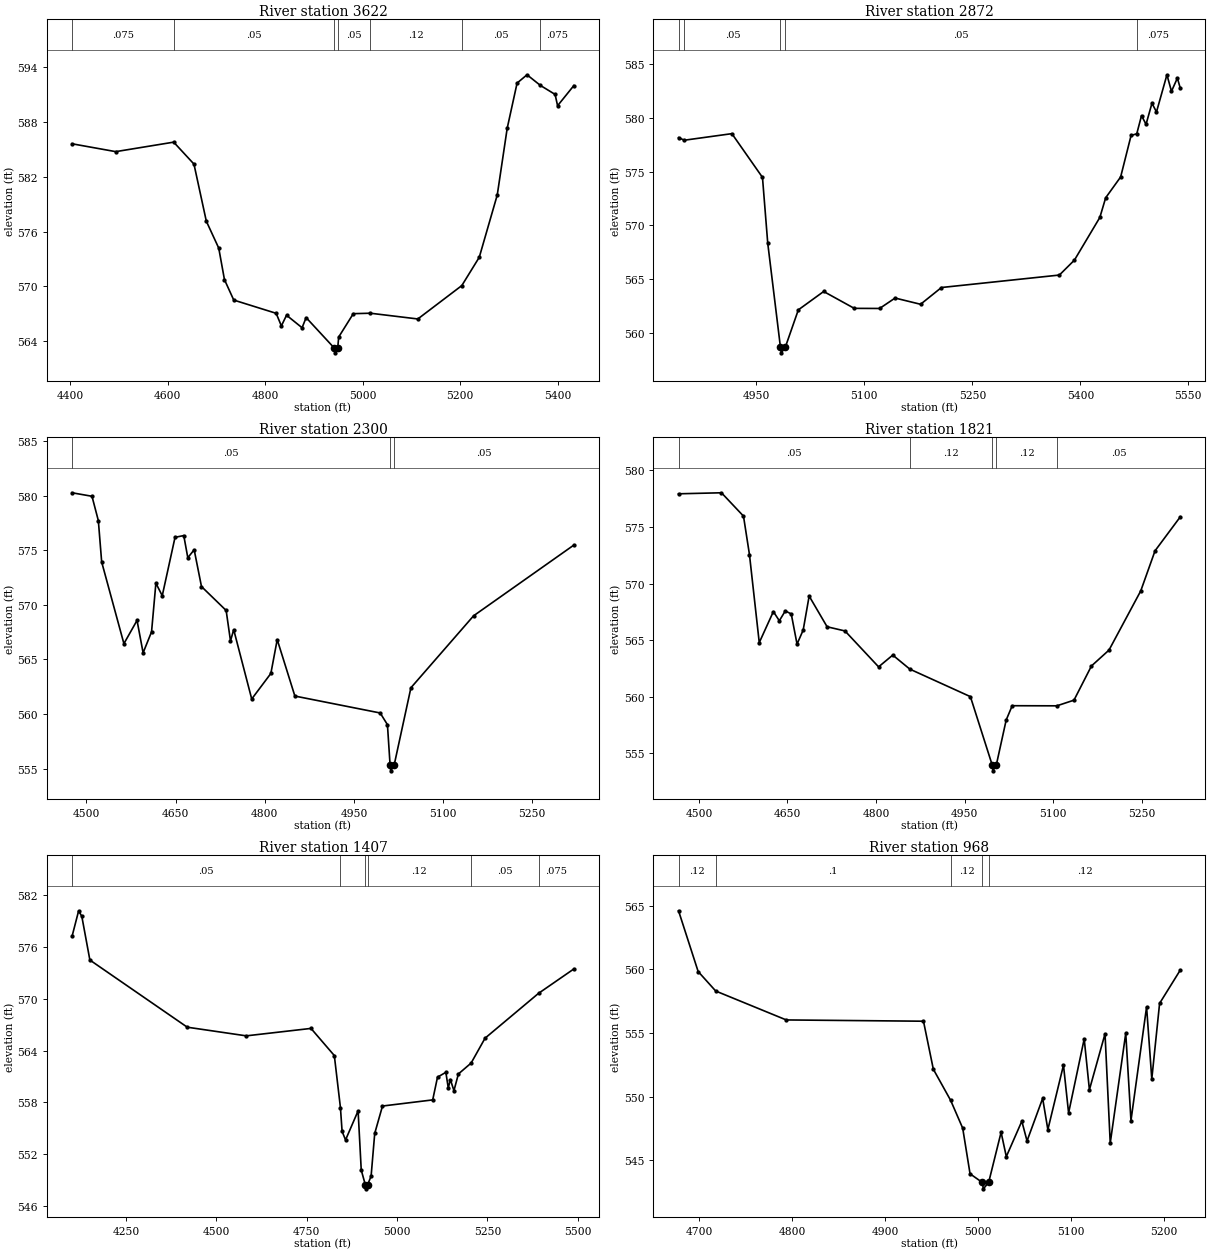
Type RM Length L Ch R = 1 ,3622    ,750,750,750
BEGIN DESCRIPTION:
Cade Branch 7.0
END DESCRIPTION:
XS GIS Cut Line= 3
      2359184.62      7057217.85      2359704.98      7057031.62
      2360173.36      7057122.01
#Sta/Elev= 30
  4403.7  585.62  4493.3  584.76  4612.2   585.8  4653.8   583.4  4679.2  577.14
  4704.7  574.19  4716.4  570.74  4735.5   568.5  4822.5  567.05  4833.2  565.67
  4843.8  566.84  4875.7  565.47    4884  566.58  4942.2  563.22  4943.3  562.72
  4948.8  563.22  4950.8  564.45  4980.8  567.01  5015.8  567.06  5113.2  566.43
  5203.5  570.09  5239.3  573.19  5276.2  580.01  5296.6  587.32  5316.9  592.27
  5337.3  593.18  5364.8  592.01  5394.9  591.03    5400  589.79  5433.4     592
#Mann= 7 ,-1 , 0
  4403.7    .075       0  4612.2     .05       0  4942.2    .033       0
  4948.8     .05       0  5015.8     .12       0  5203.5     .05       0
  5364.8    .075       0
Bank Sta=4942.2,4948.8
XS Rating Curve= 0 ,0
Exp/Cntr=0.3,0.1

Type RM Length L Ch R = 1 ,2872    ,572,572,572
BEGIN DESCRIPTION:
Cade Branch 6.0
END DESCRIPTION:
XS GIS Cut Line= 3
      2359696.75      7057702.66       2359910.4      7057472.57
      2360144.98       7057169.8
#Sta/Elev= 30
  4841.9  578.17    4850  577.93    4916  578.54  4958.5  574.47  4965.8  568.35
  4983.5  558.64  4984.6  558.14  4990.1  558.64  5008.3  562.14  5043.5  563.85
    5086  562.28  5121.2  562.27  5142.7  563.24  5178.1  562.66  5207.1  564.22
  5370.9  565.38  5391.8  566.77  5427.1  570.74  5435.2  572.57    5456  574.51
  5470.5  578.37  5478.4  578.53    5485  580.22  5491.3  579.41  5499.5  581.37
  5505.8  580.56  5520.3  584.02  5526.6  582.48  5534.8  583.71  5538.9  582.76
#Mann= 5 ,-1 , 0
  4841.9    .075       0    4850     .05       0  4983.5    .033       0
  4990.1     .05       0  5478.4    .075       0
Bank Sta=4983.5,4990.1
XS Rating Curve= 0 ,0
Exp/Cntr=0.3,0.1

Type RM Length L Ch R = 1 ,2300    ,479,479,479
BEGIN DESCRIPTION:
Cade Branch 5.0
END DESCRIPTION:
XS GIS Cut Line= 3
      2359737.82      7057853.29        2360229.        7057660.
      2360529.03      7057559.99
#Sta/Elev= 30
  4475.8  580.27  4509.3  579.95    4520  577.72  4525.6  573.93    4563  566.45
  4585.1  568.58  4595.3  565.61  4609.5  567.53  4616.8  571.99  4627.5  570.84
    4649  576.19  4663.7  576.35  4670.5  574.32  4681.2  575.05  4693.5  571.68
    4735  569.49  4742.3   566.7  4747.7  567.73    4778  561.38  4810.2  563.72
  4820.9  566.82  4850.6  561.65  4994.1   560.1  5006.3  559.03  5010.8   555.3
  5011.9   554.8  5017.5   555.3  5045.8  562.41  5151.2     569  5319.9  575.48
#Mann= 3 ,-1 , 0
  4475.8     .05       0  5010.8    .033       0  5017.5     .05       0
Bank Sta=5010.8,5017.5
XS Rating Curve= 0 ,0
Exp/Cntr=0.3,0.1

Type RM Length L Ch R = 1 ,1821    ,414,414,414
BEGIN DESCRIPTION:
Cade Branch 4.0
END DESCRIPTION:
XS GIS Cut Line= 3
      2359650.21       7058165.5       2360224.6      7058079.26
      2360474.33      7057979.37
#Sta/Elev= 30
  4465.5  577.92  4538.2  578.01  4575.5  575.95  4585.6  572.56  4602.2  564.78
  4626.1  567.52  4636.2  566.71  4646.3  567.58  4656.4  567.31  4666.2  564.65
  4676.6  565.89  4686.7  568.89  4717.1  566.18  4747.4  565.81  4804.3  562.64
  4828.3  563.68  4857.2  562.44  4959.8  560.01  4996.8  553.96  4997.9  553.46
  5003.6  553.96  5020.4  557.95  5030.6  559.21  5106.2   559.2  5135.2   559.7
  5164.8  562.72  5194.5  564.12  5248.3  569.35  5272.5  572.89  5315.3  575.89
#Mann= 5 ,-1 , 0
  4465.5     .05       0  4857.2     .12       0  4996.8     .07       0
  5003.6     .12       0  5106.2     .05       0
Bank Sta=4996.8,5003.6
XS Rating Curve= 0 ,0
Exp/Cntr=0.3,0.1

Type RM Length L Ch R = 1 ,1407    ,439,439,439
BEGIN DESCRIPTION:
Cade Branch 3.0
END DESCRIPTION:
XS GIS Cut Line= 3
      2359503.45      7058330.21      2360104.74      7058538.82
      2360755.34      7058160.82
#Sta/Elev= 30
  4100.5  577.22  4118.7  580.17  4127.5  579.52  4149.8  574.47  4419.4   566.7
  4582.7   565.7  4761.8  566.56  4826.4  563.42  4843.3   557.4  4847.9  554.64
  4857.5  553.66  4892.2  557.02  4900.9  550.17    4912   548.5  4913.1     548
  4918.8   548.5  4928.2  549.47  4938.2  554.41  4959.7  557.58  5098.7  558.29
    5112  560.92  5135.1  561.48  5141.8  559.67  5147.6  560.64  5157.5  559.36
  5169.8  561.29    5205  562.55  5243.6  565.43  5391.7  570.62  5489.4  573.44
#Mann= 6 ,-1 , 0
  4100.5     .05       0  4843.3     .12       0    4912     .07       0
  4918.8     .12       0    5205     .05       0  5391.7    .075       0
Bank Sta=4912,4918.8
XS Rating Curve= 0 ,0
Exp/Cntr=0.3,0.1

Type RM Length L Ch R = 1 ,968     ,40,40,40
BEGIN DESCRIPTION:
Cade Branch 2.0
END DESCRIPTION:
XS GIS Cut Line= 3
        2360129.        7058610.        2360429.        7058710.
      2360628.97      7058610.02
#Sta/Elev= 30
  4677.7   564.6  4698.8  559.83  4717.7   558.3  4793.6  556.03  4941.2  555.93
  4951.8  552.16  4970.4  549.72  4983.4  547.53  4991.3  543.95  5004.5  543.27
  5005.6  542.77  5011.3  543.27  5024.7  547.21  5030.3   545.3    5047  548.08
  5052.6  546.53  5069.4  549.87    5075  547.42  5091.8  552.48  5097.3  548.73
  5114.1  554.54  5119.7  550.55  5136.5  554.94  5142.1  546.36  5158.8  554.99
  5164.4  548.13  5181.2  557.05  5186.8   551.4  5195.2  557.33  5217.5  559.95
#Mann= 5 ,-1 , 0
  4677.7     .12       0  4717.7      .1       0  4970.4     .12       0
  5004.5     .07       0  5011.3     .12       0
Bank Sta=5004.5,5011.3
XS Rating Curve= 0 ,0
Exp/Cntr=0.3,0.1

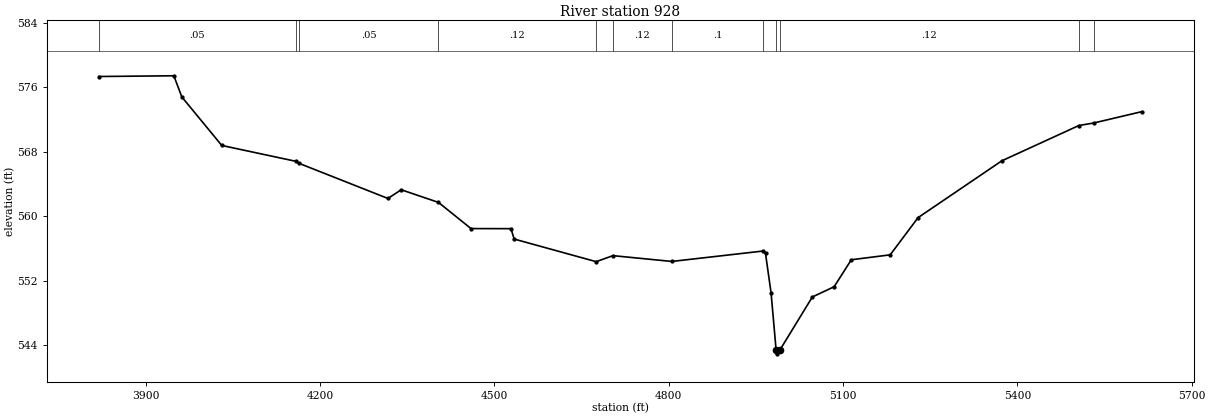
Type RM Length L Ch R = 1 ,928     ,0,0,0
BEGIN DESCRIPTION:
Cade Branch 1.0
END DESCRIPTION:
XS GIS Cut Line= 4
       2359362.3      7058336.33      2360348.19      7058793.05
       2360632.4      7058630.86      2360882.87      7058343.73
#Sta/Elev= 30
  3819.5  577.33  3948.1  577.42  3961.9  574.79  4030.6  568.77  4157.6  566.81
  4164.3  566.53  4316.6  562.19  4339.5  563.27  4403.6   561.7  4459.6  558.45
  4528.4  558.44  4533.9  557.15  4675.1  554.34  4703.9  555.09  4805.2  554.37
  4961.9  555.66  4966.5  555.36  4976.1  550.45  4984.7   543.4  4985.7   542.9
  4991.5   543.4  5047.1  549.96  5084.6  551.23  5114.2  554.58  5181.1  555.19
  5229.1  559.81  5373.2  566.86  5505.7  571.24  5531.6  571.56  5614.3  572.97
#Mann= 12 ,-1 , 0
  3819.5     .05       0  4157.6     .12       0  4164.3     .05       0
  4403.6     .12       0  4675.1      .1       0  4703.9     .12       0
  4805.2      .1       0  4961.9     .12       0  4984.7     .07       0
  4991.5     .12       0  5505.7     .05       0  5531.6     .12       0
Bank Sta=4984.7,4991.5
XS Rating Curve= 0 ,0
Exp/Cntr=0.3,0.1

Chan Stop Cuts=-1
Use User Specified Reach Order=0
Composite Channel Slope=5