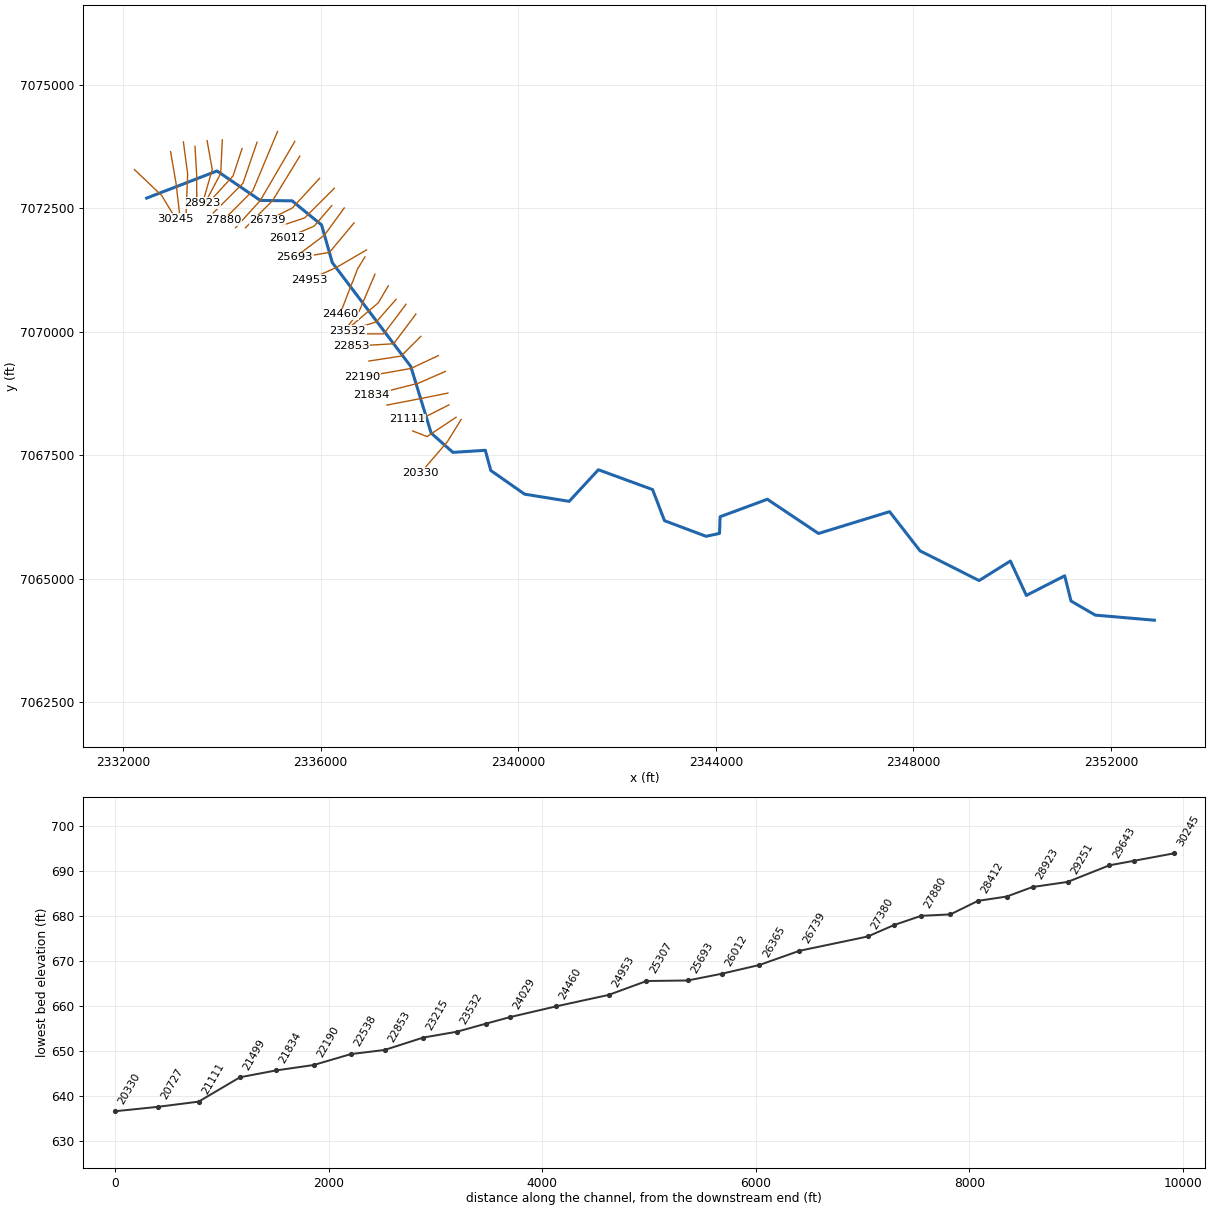
--- Catherine Branch.prj (project) ---

Proj Title=Catherine Branch Base Level Engineering
Current Plan=p01
Default Exp/Contr=0.3,0.1
English Units
Geom File=g01
Flow File=f01
Plan File=p01
Y Axis Title=Elevation
X Axis Title(PF)=Main Channel Distance
X Axis Title(XS)=Station
BEGIN DESCRIPTION:
Catherine Branch
END DESCRIPTION:
DSS Export Rating Curves= 0
DSS Export Rating Curve Sorted= 0
DSS Export Volume Flow Curves= 0
DXF OffsetX= 0
DXF OffsetY= 0
DXF ScaleX= 1
DXF ScaleY= 10

--- Catherine Branch.p01 (plan) ---

Plan Title=Multiple Run
Program Version=4.10
Short Identifier=Multiple
Geom File=g01
Flow File=f01
Subcritical Flow
K Sum by GR= 0
Std Step Tol= 0.01
Critical Tol= 0.01
Num of Std Step Trials= 20
Max Error Tol= 0.3
Flow Tol Ratio= 0.001
Split Flow NTrial= 30
Split Flow Tol= 0.02
Split Flow Ratio= 0.02
Log Output Level= 0
Friction Slope Method= 1
Unsteady Friction Slope Method= 2
Unsteady Bridges Friction Slope Method= 1
Parabolic Critical Depth
Global Vel Dist= 1 , 1 , 1
Global Log Level= 0
CheckData=True
Encroach Param=-1 ,0,0, 0
BEGIN DESCRIPTION:
Multiple Run
END DESCRIPTION:
Computation Interval=1HOUR
Output Interval=1HOUR
Run HTab= 0
Run UNet= 0
Run PostProcess= 0
Run WQNet= 0
UNET Theta= 1
UNET Theta Warmup= 1
UNET ZTol= 0.02
UNET ZSATol= 0.05
UNET MxIter= 20
UNET MaxInSteps= 0
UNET DtIC= 0
UNET DtMin= 0
UNET MaxCRTS= 20
UNET WFStab= 2
UNET SFStab= 1
UNET WFX= 1
UNET SFX= 1
UNET DSS MLevel= 4
UNET DZMax Abort= 100
UNET Convert EG Bridges= 0
UNET Use Existing IB Tables=-1
UNET Froude Reduction=False
UNET Froude Limit= 1
UNET Froude Power= 10
UNET Time Slicing=0,0, 5
UNET Junction Losses=0
Instantaneous Interval=1HOUR
Write IC File= 0
Write IC File at Sim End=0
Echo Input=False
Echo Parameters=False
Echo Output=False
Write Detailed= 0
WQ AD Non Conservative
WQ ULTIMATE=-1
WQ Max Comp Step=1HOUR
WQ Output Interval=15MIN
WQ Output Selected Increments= 0
WQ Output face flow=0
WQ Output face velocity=0
WQ Output face area=0
WQ Output face dispersion=0
WQ Output cell volume=0
WQ Output cell surface area=0
WQ Output cell continuity=0
WQ Output cumulative cell continuity=0
WQ Output face conc=0
WQ Output face dconc_dx=0
WQ Output face courant=0
WQ Output face peclet=0
WQ Output face adv mass=0
WQ Output face disp mass=0
WQ Output cell mass=0
WQ Output cell source sink temp=0
WQ Output cell source sink nsm=0
WQ Output MaxMinRange=-1
WQ Daily Max Min Mean=-1
WQ Daily Range=0
WQ Daily Time=0
WQ Create Restart=0
WQ Fixed Restart=0
WQ System Summary=0
WQ Use Fixed Temperature=0
Sorting and Armoring Iterations= 10
XS Update Threshold= 0.02
Hydraulics Update Threshold= 0.02
Energy Slope Method= 1
Volume Change Method= 0
XS Weighting Method= 0
Number of US Weighted Cross Sections= 1
Number of DS Weighted Cross Sections= 1
Upstream XS Weight=0.25
Main XS Weight=0.5
Downstream XS Weight=0.25
Number of DS XS's Weighted with US Boundary= 1
Upstream Boundary Weight= 1
Weight of XSs Associated with US Boundary= 0
Number of US XS's Weighted with DS Boundary= 1
Downstream Boundary Weight= 0.5
Weight of XSs Associated with DS Boundary= 0.5
Sediment Output Level= 4
Mass or Volume Output= 0
Output Increment Type= 1
Profile and TS Output Increment= 10
XS Output Flag= 0
XS Output Increment= 10
Disregard all LS=0
Disregard all Conn=0
Disregard all Breaches=0
Disregard all Pumps=0

--- Catherine Branch.f01 (steady flow) ---

Flow Title=Multiple
Number of Profiles=7
Profile Names=10-year,25-year,50-year,1pct_min,100-year,1pct_plu,500-year
River Rch & RM= Catherine Branch,Reach-1,30245
     342     451     537     318     635    1268     890
River Rch & RM= Catherine Branch,Reach-1,26739
     508     685     828     498     993    1981    1429
River Rch & RM= Catherine Branch,Reach-1,20330
    1127    1591    1984    1226    2446    4879    3726
River Rch & RM= Catherine Branch,Reach-1,17926
    1506    2153    2708    1684    3361    6706    5197
River Rch & RM= Catherine Branch,Reach-1,10890
    1557    2221    2790    1733    3458    6899    5330
River Rch & RM= Catherine Branch,Reach-1,9577
    1790    2568    3237    2018    4026    8032    6247
River Rch & RM= Catherine Branch,Reach-1,5552
    1890    2715    3425    2137    4263    8507    6627
Boundary for River Rch & Prof#=Catherine Branch,Reach-1,1
Up Type=0
Dn Type=3
Dn Slope=0.005
Boundary for River Rch & Prof#=Catherine Branch,Reach-1,2
Up Type=0
Dn Type=3
Dn Slope=0.005
Boundary for River Rch & Prof#=Catherine Branch,Reach-1,3
Up Type=0
Dn Type=3
Dn Slope=0.005
Boundary for River Rch & Prof#=Catherine Branch,Reach-1,4
Up Type=0
Dn Type=3
Dn Slope=0.005
Boundary for River Rch & Prof#=Catherine Branch,Reach-1,5
Up Type=0
Dn Type=3
Dn Slope=0.005
Boundary for River Rch & Prof#=Catherine Branch,Reach-1,6
Up Type=0
Dn Type=3
Dn Slope=0.005
Boundary for River Rch & Prof#=Catherine Branch,Reach-1,7
Up Type=0
Dn Type=3
Dn Slope=0.005

--- Catherine Branch.g01 (geometry) ---

Geom Title=Existing Conditions

River Reach=Catherine Branch,Reach-1
Reach XY= 30
      2332479.00      7072710.00      2333904.03      7073260.31
      2334780.46      7072663.54      2335424.00      7072655.00
      2336021.15      7072166.19      2336237.16      7071403.95
      2337825.83      7069301.66      2338239.32      7067949.83
      2338679.00      7067560.00      2339335.21      7067602.20
      2339445.41      7067193.20      2340130.50      7066713.61
      2341032.35      7066568.03      2341623.32      7067208.03
      2342720.90      7066806.65      2342961.85      7066176.45
      2343803.88      7065859.71      2344076.03      7065918.31
      2344087.46      7066256.50      2345044.34      7066610.05
      2346079.00      7065917.09      2347518.56      7066358.97
      2348134.61      7065565.59      2349330.47      7064963.55
      2349963.40      7065359.60      2350286.85      7064662.92
      2351062.99      7065059.54      2351189.78      7064549.61
      2351680.65      7064263.65      2352879.00      7064160.00

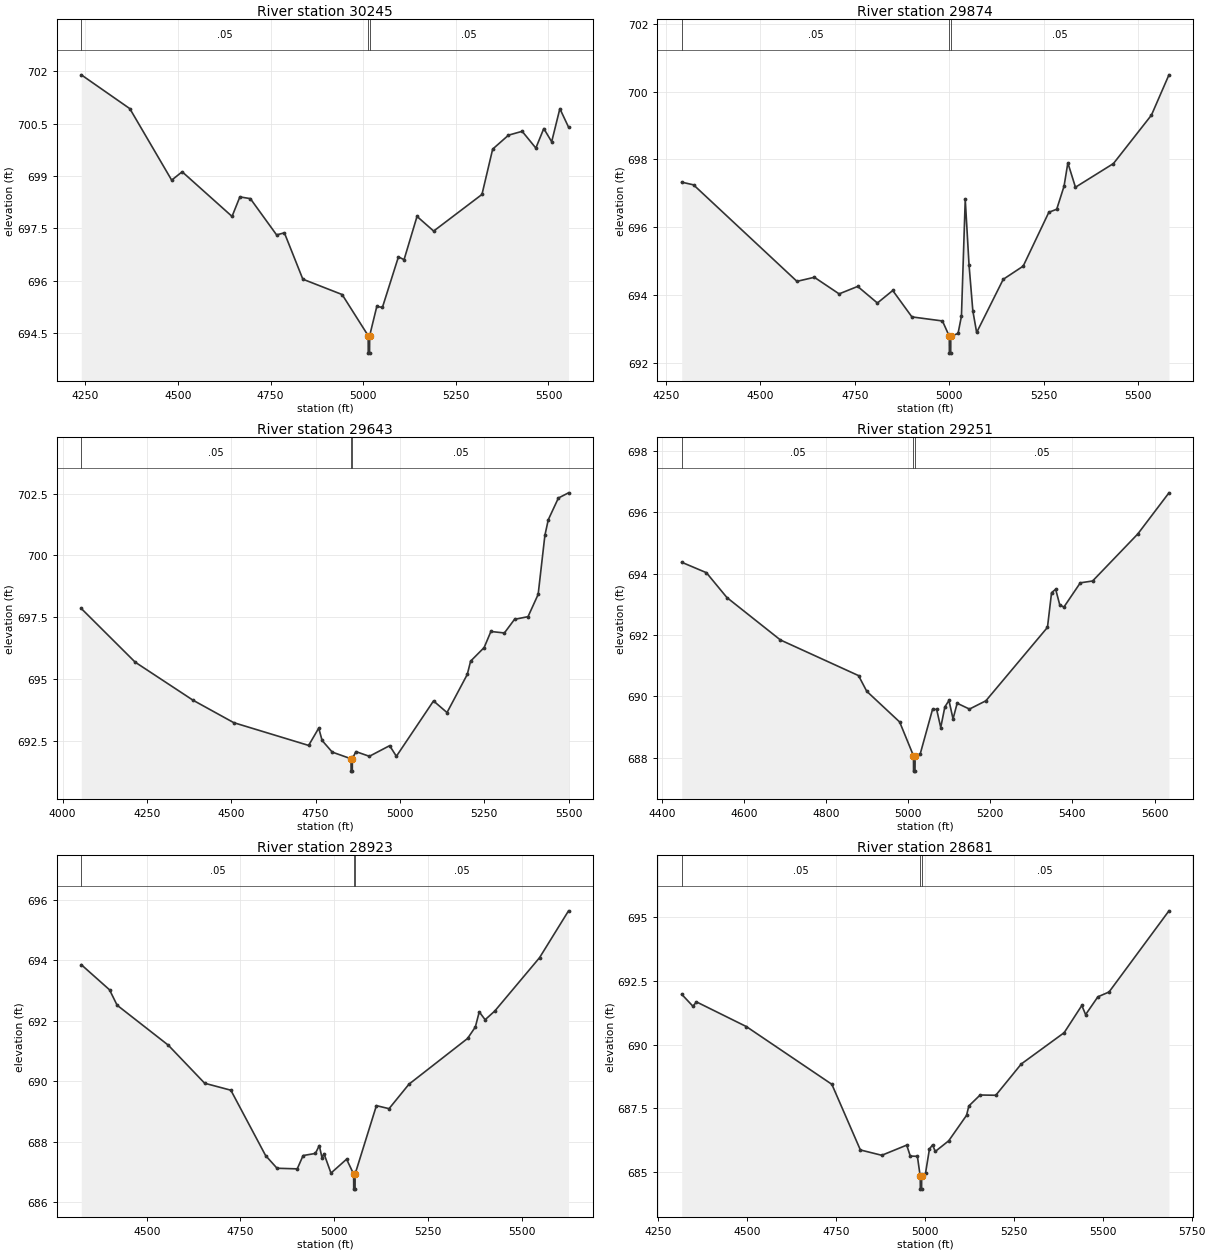
Type RM Length L Ch R = 1,30245,371,371,371
BEGIN DESCRIPTION:
Catherine Branch 58.0
END DESCRIPTION:
XS GIS Cut Line= 3
      2332232.16      7073288.18      2332783.69      7072764.51
      2333069.83      7072289.93
#Sta/Elev= 30
  4239.4  701.90  4370.4  700.93  4483.3  698.88  4511.6  699.12  4646.2  697.84
  4667.3  698.40  4695.6  698.35  4766.4  697.31  4787.4  697.37  4837.2  696.04
  4943.2  695.60  5013.5  694.42  5013.7  693.92  5017.2  693.92  5017.5  694.42
  5036.8  695.26  5051.9  695.23  5095.1  696.68  5110.3  696.60  5145.3  697.84
  5190.2  697.42  5320.5  698.47  5349.4  699.77  5392.1  700.17  5429.0  700.28
  5465.9  699.80  5487.3  700.36  5508.6  699.98  5530.7  700.93  5554.1  700.40
#Mann=3,-1,0
  4239.4    0.05       0  5013.5   0.033       0  5017.5    0.05       0
Bank Sta=5013.5,5017.5
Exp/Cntr=0.3,0.1

Type RM Length L Ch R = 1,29874,231,231,231
BEGIN DESCRIPTION:
Catherine Branch 57.0
END DESCRIPTION:
XS GIS Cut Line= 3
      2332964.37      7073650.93      2333076.06      7073001.56
      2333148.67      7072373.95
#Sta/Elev= 30
  4291.4  697.33  4322.8  697.25  4596.7  694.40  4642.8  694.52  4708.4  694.03
  4757.6  694.25  4809.8  693.76  4850.4  694.13  4901.2  693.35  4982.1  693.23
  5000.2  692.78  5000.5  692.28  5004.0  692.28  5004.2  692.78  5023.4  692.86
  5032.4  693.37  5042.5  696.82  5052.5  694.89  5062.6  693.53  5072.7  692.89
  5143.1  694.46  5196.0  694.85  5263.9  696.44  5284.8  696.53  5304.2  697.21
  5314.3  697.90  5334.4  697.18  5435.1  697.88  5535.7  699.31  5582.1  700.50
#Mann=3,-1,0
  4291.4    0.05       0  5000.2   0.033       0  5004.2    0.05       0
Bank Sta=5000.2,5004.2
Exp/Cntr=0.3,0.1

Type RM Length L Ch R = 1,29643,392,392,392
BEGIN DESCRIPTION:
Catherine Branch 56.0
END DESCRIPTION:
XS GIS Cut Line= 3
      2333224.12      7073848.32      2333309.84      7073198.97
      2333279.00      7072409.96
#Sta/Elev= 30
  4055.2  697.85  4214.9  695.68  4386.4  694.14  4507.4  693.23  4729.2  692.31
  4759.2  693.01  4769.2  692.51  4799.2  692.04  4854.9  691.77  4855.2  691.27
  4858.7  691.27  4858.9  691.77  4869.3  692.06  4909.3  691.87  4969.4  692.30
  4989.4  691.87  5099.5  694.11  5139.5  693.64  5199.5  695.18  5209.5  695.72
  5249.6  696.27  5269.6  696.92  5309.6  696.86  5339.6  697.41  5379.7  697.52
  5409.7  698.42  5429.7  700.81  5439.7  701.44  5469.7  702.32  5499.8  702.53
#Mann=3,-1,0
  4055.2    0.05       0  4854.9   0.033       0  4858.9    0.05       0
Bank Sta=4854.9,4858.9
Exp/Cntr=0.3,0.1

Type RM Length L Ch R = 1,29251,328,328,328
BEGIN DESCRIPTION:
Catherine Branch 55.5
END DESCRIPTION:
XS GIS Cut Line= 3
      2333457.89      7073760.04      2333491.66      7073193.77
      2333494.25      7072573.96
#Sta/Elev= 30
  4448.1  694.37  4508.3  694.03  4558.3  693.22  4688.6  691.84  4878.9  690.68
  4898.9  690.17  4979.1  689.17  5012.8  688.07  5013.0  687.57  5016.5  687.57
  5016.8  688.07  5029.2  688.13  5059.2  689.58  5069.2  689.58  5079.2  688.99
  5089.2  689.66  5099.2  689.87  5109.2  689.27  5119.2  689.78  5149.2  689.59
  5189.2  689.86  5339.2  692.25  5349.2  693.38  5359.2  693.49  5369.2  692.98
  5379.2  692.91  5419.2  693.70  5449.2  693.76  5559.2  695.29  5635.2  696.63
#Mann=3,-1,0
  4448.1    0.05       0  5012.8   0.033       0  5016.8    0.05       0
Bank Sta=5012.8,5016.8
Exp/Cntr=0.3,0.1

Type RM Length L Ch R = 1,28923,242,242,242
BEGIN DESCRIPTION:
Catherine Branch 55.0
END DESCRIPTION:
XS GIS Cut Line= 3
      2333703.52      7073874.13      2333807.69      7073288.18
      2333612.38      7072611.12
#Sta/Elev= 30
  4325.3  693.86  4400.6  693.03  4420.9  692.52  4557.3  691.20  4654.5  689.94
  4724.3  689.71  4817.0  687.55  4847.5  687.13  4901.4  687.11  4917.0  687.55
  4949.8  687.62  4960.2  687.88  4967.6  687.47  4972.8  687.61  4991.4  686.97
  5033.0  687.43  5051.8  686.94  5052.1  686.44  5055.6  686.44  5055.8  686.94
  5112.6  689.20  5146.3  689.10  5199.5  689.91  5355.7  691.42  5376.5  691.80
  5386.9  692.30  5402.6  692.04  5428.5  692.33  5547.7  694.09  5625.1  695.64
#Mann=3,-1,0
  4325.3    0.05       0  5051.8    0.04       0  5055.8    0.05       0
Bank Sta=5051.8,5055.8
Exp/Cntr=0.3,0.1

Type RM Length L Ch R = 1,28681,269,269,269
BEGIN DESCRIPTION:
Catherine Branch 54.0
END DESCRIPTION:
XS GIS Cut Line= 3
      2334011.68      7073891.45      2333979.00      7073210.00
      2333656.45      7072603.69
#Sta/Elev= 30
  4317.2  691.98  4348.7  691.51  4358.7  691.68  4498.9  690.71  4739.1  688.44
  4819.2  685.86  4879.3  685.65  4949.4  686.05  4959.4  685.62  4979.4  685.61
  4987.4  684.82  4987.7  684.32  4991.2  684.32  4991.4  684.82  5002.3  684.95
  5013.3  685.90  5022.1  686.06  5029.6  685.80  5067.4  686.22  5117.5  687.22
  5124.0  687.59  5155.7  688.02  5199.7  688.01  5271.3  689.24  5391.8  690.47
  5441.4  691.54  5452.0  691.18  5486.5  691.88  5517.9  692.07  5686.2  695.26
#Mann=3,-1,0
  4317.2    0.05       0  4987.4    0.04       0  4991.4    0.05       0
Bank Sta=4987.4,4991.4
Exp/Cntr=0.3,0.1

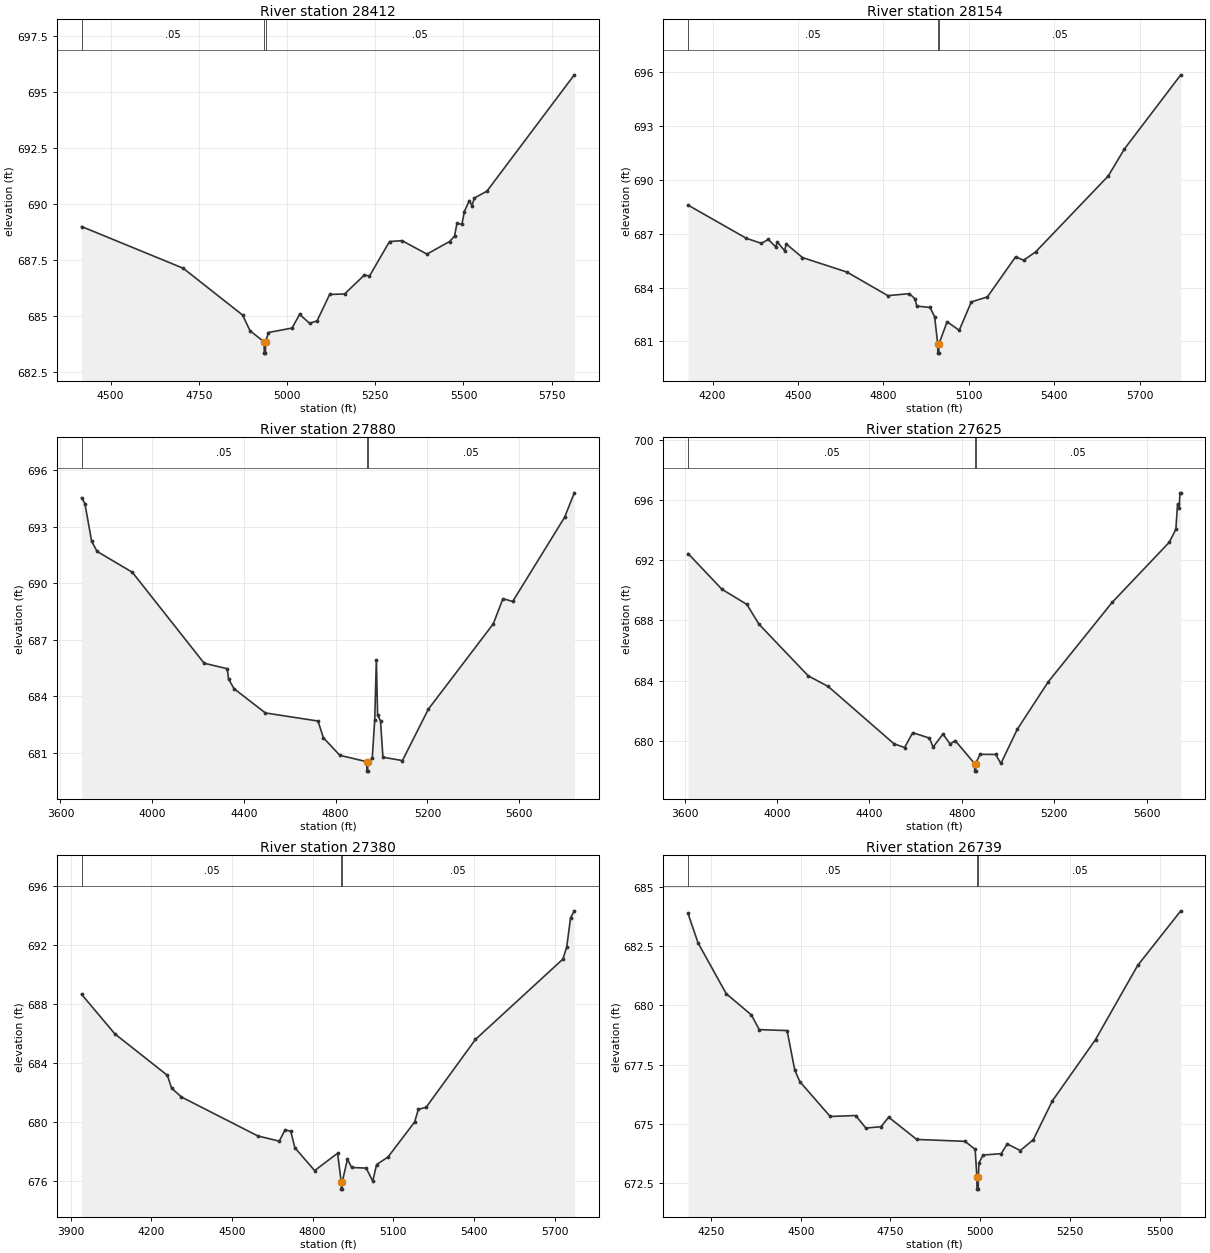
Type RM Length L Ch R = 1,28412,258,258,258
BEGIN DESCRIPTION:
Catherine Branch 53.0
END DESCRIPTION:
XS GIS Cut Line= 3
      2334410.98      7073713.53      2334229.00      7073160.00
      2333679.01      7072560.01
#Sta/Elev= 30
  4417.6  689.01  4705.5  687.15  4874.0  685.06  4895.0  684.36  4935.1  683.86
  4935.4  683.36  4938.9  683.36  4939.1  683.86  4947.3  684.28  5014.2  684.48
  5035.7  685.09  5064.1  684.69  5085.1  684.80  5120.8  685.98  5163.1  686.00
  5219.5  686.85  5233.7  686.80  5290.4  688.34  5325.9  688.38  5396.5  687.78
  5460.6  688.34  5474.8  688.58  5481.5  689.15  5495.7  689.11  5502.5  689.68
  5516.7  690.17  5524.1  689.94  5530.9  690.28  5566.6  690.59  5814.2  695.78
#Mann=3,-1,0
  4417.6    0.05       0  4935.1   0.033       0  4939.1    0.05       0
Bank Sta=4935.1,4939.1
Exp/Cntr=0.3,0.1

Type RM Length L Ch R = 1,28154,274,274,274
BEGIN DESCRIPTION:
Catherine Branch 52.0
END DESCRIPTION:
XS GIS Cut Line= 3
      2334714.79      7073843.70      2334429.00      7073010.00
      2333828.96      7072409.96
#Sta/Elev= 30
  4114.0  688.59  4318.8  686.74  4371.6  686.46  4396.0  686.68  4422.0  686.26
  4427.3  686.54  4453.3  686.05  4458.6  686.43  4515.8  685.67  4672.2  684.86
  4815.6  683.55  4891.1  683.66  4910.8  683.37  4917.1  682.97  4963.6  682.89
  4979.7  682.38  4990.7  680.85  4990.9  680.35  4994.4  680.35  4994.7  680.85
  5023.6  682.10  5066.0  681.62  5108.5  683.20  5165.0  683.48  5264.0  685.71
  5292.3  685.52  5334.7  685.99  5589.3  690.21  5645.9  691.71  5843.9  695.84
#Mann=3,-1,0
  4114.0    0.05       0  4990.7    0.04       0  4994.7    0.05       0
Bank Sta=4990.7,4994.7
Exp/Cntr=0.3,0.1

Type RM Length L Ch R = 1,27880,255,255,255
BEGIN DESCRIPTION:
Catherine Branch 51.0
END DESCRIPTION:
XS GIS Cut Line= 3
      2335128.99      7074059.98      2334629.00      7072860.00
      2334029.00      7072260.00
#Sta/Elev= 30
  3692.1  694.55  3706.7  694.24  3736.0  692.24  3759.8  691.70  3913.6  690.59
  4226.7  685.76  4327.5  685.47  4332.9  684.93  4356.7  684.41  4493.7  683.12
  4722.9  682.69  4746.7  681.80  4818.2  680.87  4935.9  680.53  4936.2  680.03
  4939.7  680.03  4939.9  680.53  4959.6  680.73  4970.4  682.76  4977.5  685.93
  4982.9  683.01  4995.6  682.70  5006.2  680.77  5091.1  680.59  5204.2  683.32
  5487.1  687.85  5529.5  689.19  5571.9  689.04  5798.2  693.51  5840.6  694.81
#Mann=3,-1,0
  3692.1    0.05       0  4935.9   0.033       0  4939.9    0.05       0
Bank Sta=4935.9,4939.9
Exp/Cntr=0.3,0.1

Type RM Length L Ch R = 1,27625,245,245,245
BEGIN DESCRIPTION:
Catherine Branch 50.0
END DESCRIPTION:
XS GIS Cut Line= 3
      2335478.98      7073859.96      2334779.00      7072660.00
      2334279.00      7072110.00
#Sta/Elev= 30
  3614.7  692.46  3761.4  690.08  3869.3  689.07  3921.9  687.75  4135.2  684.31
  4221.2  683.61  4506.1  679.79  4552.0  679.54  4587.1  680.53  4659.5  680.17
  4675.2  679.57  4718.2  680.44  4749.2  679.77  4771.1  680.00  4855.1  678.47
  4855.4  677.97  4858.9  677.97  4859.1  678.47  4878.6  679.09  4946.0  679.08
  4968.8  678.48  5039.4  680.75  5173.8  683.92  5449.9  689.20  5697.5  693.21
  5725.9  694.07  5733.3  695.76  5740.1  695.46  5743.8  696.50  5747.2  696.50
#Mann=3,-1,0
  3614.7    0.05       0  4855.1    0.04       0  4859.1    0.05       0
Bank Sta=4855.1,4859.1
Exp/Cntr=0.3,0.1

Type RM Length L Ch R = 1,27380,641,641,641
BEGIN DESCRIPTION:
Catherine Branch 49.0
END DESCRIPTION:
XS GIS Cut Line= 3
      2335578.99      7073559.98      2335029.00      7072660.00
      2334479.03      7072110.03
#Sta/Elev= 30
  3941.0  688.67  4064.8  685.98  4260.3  683.16  4275.8  682.29  4312.5  681.69
  4597.0  679.04  4676.4  678.69  4697.7  679.46  4719.0  679.36  4734.4  678.24
  4807.9  676.69  4893.2  677.87  4906.6  675.93  4906.9  675.43  4910.4  675.43
  4910.6  675.93  4929.9  677.47  4945.4  676.90  4999.3  676.86  5024.0  675.98
  5038.2  677.10  5080.6  677.61  5179.6  679.99  5193.7  680.86  5222.0  680.98
  5405.8  685.60  5731.1  691.06  5745.3  691.88  5759.4  693.85  5773.5  694.34
#Mann=3,-1,0
  3941.0    0.05       0  4906.6    0.04       0  4910.6    0.05       0
Bank Sta=4906.6,4910.6
Exp/Cntr=0.3,0.1

Type RM Length L Ch R = 1,26739,374,374,374
BEGIN DESCRIPTION:
Catherine Branch 48.0
END DESCRIPTION:
XS GIS Cut Line= 3
      2335979.03      7073110.03      2335429.00      7072510.00
      2334929.00      7072260.00
#Sta/Elev= 30
  4185.9  683.89  4214.0  682.64  4292.3  680.50  4362.6  679.60  4384.2  678.98
  4461.9  678.94  4483.5  677.26  4497.6  676.78  4582.1  675.31  4653.0  675.35
  4681.4  674.82  4723.9  674.88  4744.9  675.28  4823.2  674.34  4957.6  674.26
  4986.0  673.92  4990.8  672.74  4991.0  672.24  4994.5  672.24  4994.8  672.74
  4996.5  673.35  5008.3  673.68  5058.6  673.74  5075.3  674.15  5111.7  673.87
  5148.0  674.33  5201.1  675.97  5321.3  678.56  5438.7  681.69  5558.9  684.00
#Mann=3,-1,0
  4185.9    0.05       0  4990.8    0.04       0  4994.8    0.05       0
Bank Sta=4990.8,4994.8
Exp/Cntr=0.3,0.1

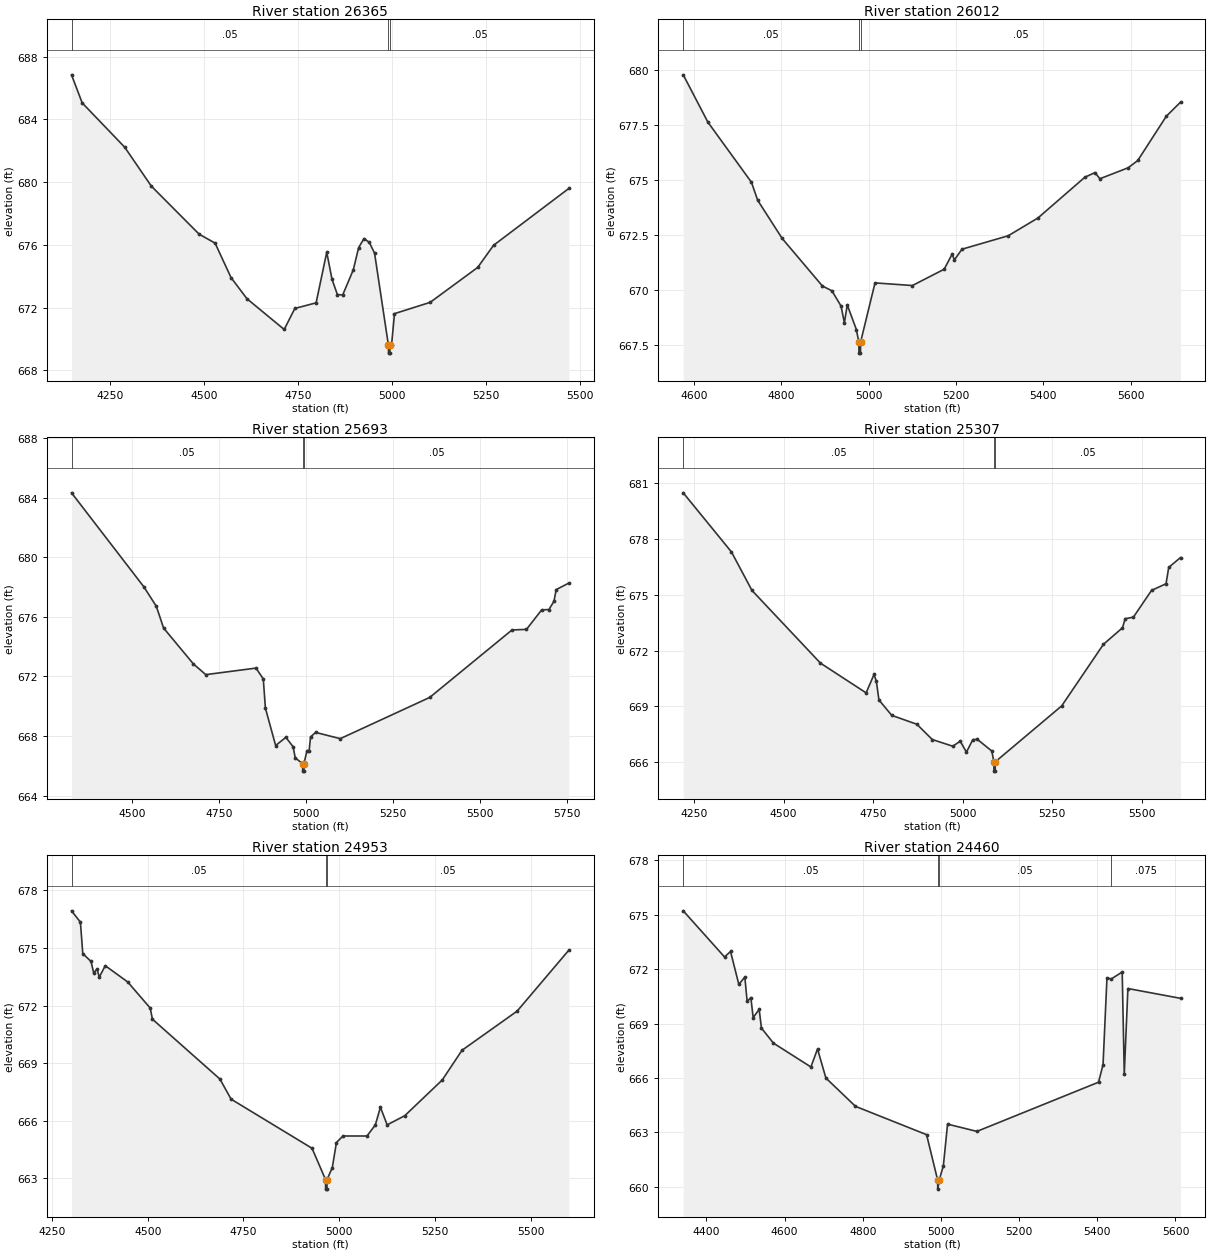
Type RM Length L Ch R = 1,26365,353,353,353
BEGIN DESCRIPTION:
Catherine Branch 47.0
END DESCRIPTION:
XS GIS Cut Line= 3
      2336279.03      7072910.03      2335679.00      7072310.00
      2335229.02      7072160.01
#Sta/Elev= 30
  4147.0  686.85  4175.3  685.06  4288.5  682.23  4359.2  679.75  4486.5  676.68
  4528.9  676.11  4571.3  673.91  4613.7  672.56  4712.7  670.60  4741.0  671.94
  4797.6  672.30  4825.9  675.53  4840.0  673.79  4854.2  672.83  4868.3  672.80
  4896.6  674.41  4910.7  675.82  4924.9  676.40  4939.0  676.16  4953.1  675.47
  4990.0  669.59  4990.3  669.09  4993.8  669.09  4994.0  669.59  4998.2  669.59
  5006.1  671.61  5101.0  672.33  5227.5  674.56  5269.6  675.97  5469.9  679.60
#Mann=3,-1,0
  4147.0    0.05       0  4990.0   0.033       0  4994.0    0.05       0
Bank Sta=4990,4994
Exp/Cntr=0.3,0.1

Type RM Length L Ch R = 1,26012,319,319,319
BEGIN DESCRIPTION:
Catherine Branch 46.0
END DESCRIPTION:
XS GIS Cut Line= 3
      2336229.01      7072560.01      2335869.32      7072142.34
      2335328.96      7071909.98
#Sta/Elev= 30
  4575.1  679.78  4631.6  677.63  4731.4  674.90  4745.7  674.08  4801.7  672.35
  4893.9  670.19  4915.8  669.97  4936.6  669.28  4944.3  668.52  4950.9  669.33
  4971.8  668.21  4977.4  667.64  4977.7  667.14  4981.2  667.14  4981.4  667.64
  5014.5  670.33  5100.1  670.21  5172.9  670.95  5191.0  671.63  5196.5  671.38
  5213.7  671.86  5319.6  672.47  5387.9  673.28  5495.3  675.13  5518.5  675.34
  5529.7  675.06  5594.7  675.56  5616.5  675.89  5681.9  677.90  5714.5  678.54
#Mann=3,-1,0
  4575.1    0.05       0  4977.4   0.033       0  4981.4    0.05       0
Bank Sta=4977.4,4981.4
Exp/Cntr=0.3,0.1

Type RM Length L Ch R = 1,25693,386,386,386
BEGIN DESCRIPTION:
Catherine Branch 45.0
END DESCRIPTION:
XS GIS Cut Line= 3
      2336478.98      7072509.97      2336079.00      7071960.00
      2335479.03      7071510.02
#Sta/Elev= 30
  4325.5  684.33  4533.7  678.01  4569.3  676.71  4590.2  675.25  4675.9  672.84
  4711.5  672.12  4856.0  672.56  4876.9  671.83  4883.0  669.87  4912.4  667.36
  4941.8  667.91  4962.6  667.28  4968.8  666.53  4990.0  666.14  4990.3  665.64
  4993.8  665.64  4994.0  666.14  5002.4  667.01  5008.7  667.01  5012.8  667.94
  5027.4  668.24  5098.2  667.82  5355.5  670.59  5592.0  675.12  5633.7  675.16
  5677.4  676.47  5698.2  676.49  5712.8  677.05  5719.1  677.83  5755.5  678.27
#Mann=3,-1,0
  4325.5    0.05       0  4990.0   0.033       0  4994.0    0.05       0
Bank Sta=4990,4994
Exp/Cntr=0.3,0.1

Type RM Length L Ch R = 1,25307,354,354,354
BEGIN DESCRIPTION:
Catherine Branch 44.0
END DESCRIPTION:
XS GIS Cut Line= 3
      2336678.98      7072209.98      2336179.00      7071610.00
      2335578.97      7071509.99
#Sta/Elev= 30
  4219.5  680.49  4354.2  677.31  4411.5  675.24  4602.8  671.33  4730.4  669.73
  4752.5  670.72  4759.0  670.35  4766.2  669.35  4802.0  668.52  4872.3  668.04
  4915.2  667.22  4972.5  666.86  4993.3  667.13  5010.6  666.54  5028.4  667.21
  5041.0  667.23  5081.6  666.60  5087.2  666.02  5087.5  665.52  5091.0  665.52
  5091.2  666.02  5276.8  669.03  5393.3  672.34  5446.6  673.23  5454.2  673.72
  5477.0  673.80  5527.7  675.24  5568.2  675.60  5575.8  676.48  5608.8  677.01
#Mann=3,-1,0
  4219.5    0.05       0  5087.2    0.04       0  5091.2    0.05       0
Bank Sta=5087.2,5091.2
Exp/Cntr=0.3,0.1

Type RM Length L Ch R = 1,24953,493,493,493
BEGIN DESCRIPTION:
Catherine Branch 43.0
END DESCRIPTION:
XS GIS Cut Line= 3
      2336929.04      7071660.02      2336329.00      7071310.00
      2335779.02      7071060.01
#Sta/Elev= 30
  4301.0  676.94  4324.2  676.35  4330.4  674.71  4351.9  674.30  4358.9  673.70
  4367.6  673.91  4373.4  673.48  4389.1  674.08  4447.8  673.23  4506.5  671.87
  4512.3  671.29  4688.5  668.17  4717.8  667.12  4929.1  664.56  4964.3  662.93
  4964.6  662.43  4968.1  662.43  4968.3  662.93  4982.0  663.55  4992.8  664.86
  5010.0  665.20  5072.6  665.20  5094.5  665.78  5107.7  666.70  5125.3  665.78
  5171.4  666.26  5269.2  668.12  5320.8  669.67  5464.7  671.71  5599.8  674.89
#Mann=3,-1,0
  4301.0    0.05       0  4964.3    0.04       0  4968.3    0.05       0
Bank Sta=4964.3,4968.3
Exp/Cntr=0.3,0.1

Type RM Length L Ch R = 1,24460,431,431,431
BEGIN DESCRIPTION:
Catherine Branch 42.0
END DESCRIPTION:
XS GIS Cut Line= 3
      2336897.95      7071517.33      2336750.39      7071278.63
      2336390.30      7070354.54
#Sta/Elev= 30
  4340.6  675.21  4446.2  672.67  4461.6  672.97  4482.8  671.16  4498.2  671.56
  4504.1  670.22  4513.6  670.43  4519.5  669.33  4534.9  669.78  4540.7  668.75
  4571.5  667.92  4667.2  666.61  4684.2  667.60  4705.6  666.00  4781.3  664.44
  4963.2  662.88  4991.5  660.38  4991.7  659.88  4995.5  660.38  5006.1  661.16
  5016.9  663.46  5092.0  663.06  5403.2  665.77  5414.7  666.74  5424.7  671.51
  5436.0  671.46  5463.7  671.84  5469.0  666.21  5478.3  670.93  5613.0  670.39
#Mann=4,-1,0
  4340.6    0.05       0  4991.5   0.033       0  4995.5    0.05       0
  5436.0   0.075       0
Bank Sta=4991.5,4995.5
Exp/Cntr=0.3,0.1

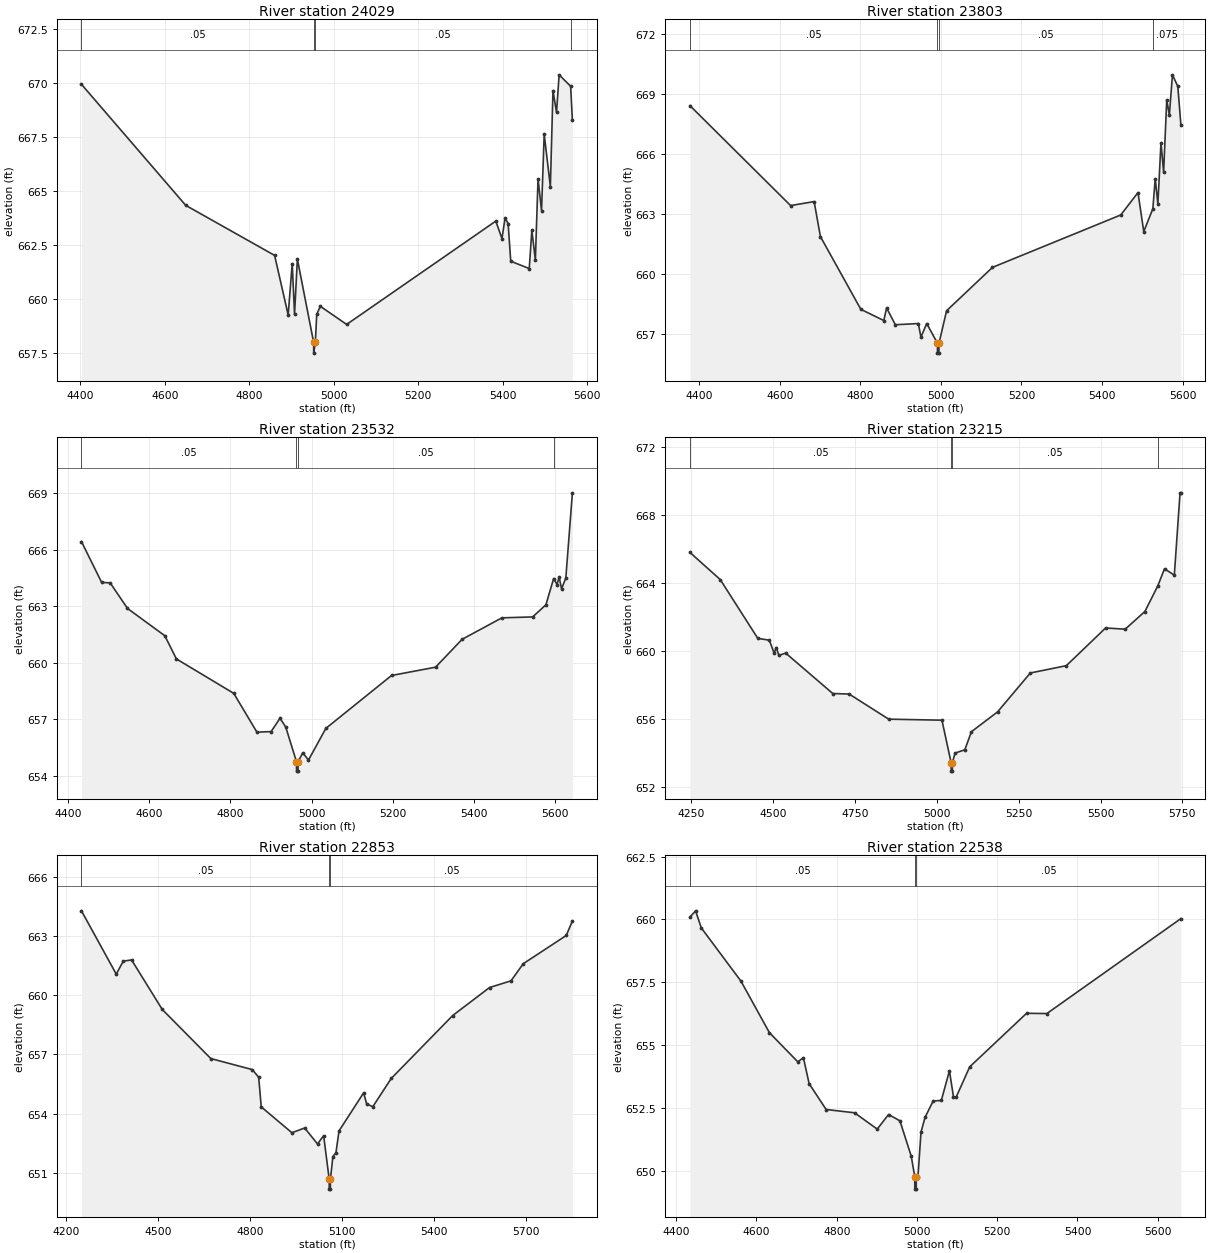
Type RM Length L Ch R = 1,24029,226,226,226
BEGIN DESCRIPTION:
Catherine Branch 41.0
END DESCRIPTION:
XS GIS Cut Line= 3
      2337101.94      7071170.09      2336780.78      7070419.25
      2336573.20      7070142.49
#Sta/Elev= 30
  4402.4  669.95  4649.3  664.34  4859.8  662.02  4891.9  659.26  4901.5  661.64
  4907.0  659.29  4913.7  661.85  4952.2  657.99  4952.4  657.49  4956.2  657.99
  4959.6  659.29  4968.1  659.66  5030.4  658.82  5383.6  663.61  5398.2  662.80
  5405.6  663.76  5412.8  663.49  5419.0  661.75  5462.8  661.41  5469.0  663.18
  5477.3  661.80  5483.6  665.57  5491.9  664.10  5498.2  667.64  5512.8  665.21
  5519.0  669.66  5527.4  668.65  5533.6  670.39  5560.8  669.86  5565.0  668.29
#Mann=4,-1,0
  4402.4    0.05       0  4952.2   0.033       0  4956.2    0.05       0
  5560.8   0.075       0
Bank Sta=4952.2,4956.2
Exp/Cntr=0.3,0.1

Type RM Length L Ch R = 1,23803,271,271,271
BEGIN DESCRIPTION:
Catherine Branch 40.0
END DESCRIPTION:
XS GIS Cut Line= 3
      2337371.04      7070931.38      2337167.06      7070588.52
      2336543.21      7070055.65
#Sta/Elev= 30
  4376.5  668.41  4626.6  663.41  4685.0  663.61  4700.6  661.86  4801.0  658.22
  4858.1  657.66  4865.0  658.29  4886.7  657.45  4943.8  657.51  4950.3  656.83
  4964.6  657.51  4991.2  656.53  4991.4  656.03  4994.9  656.03  4995.2  656.53
  5014.0  658.15  5128.0  660.32  5446.6  662.94  5489.4  664.06  5503.7  662.11
  5526.3  663.25  5532.2  664.76  5538.8  663.49  5546.5  666.56  5553.1  665.08
  5560.8  668.70  5567.3  667.94  5575.0  669.95  5588.3  669.37  5595.9  667.46
#Mann=4,-1,0
  4376.5    0.05       0  4991.2   0.033       0  4995.2    0.05       0
  5526.3   0.075       0
Bank Sta=4991.2,4995.2
Exp/Cntr=0.3,0.1

Type RM Length L Ch R = 1,23532,317,317,317
BEGIN DESCRIPTION:
Catherine Branch 39.0
END DESCRIPTION:
XS GIS Cut Line= 3
      2337528.99      7070659.98      2337128.00      7070202.24
      2336553.52      7070025.14
#Sta/Elev= 30
  4432.8  666.43  4482.6  664.26  4503.5  664.24  4546.2  662.88  4638.2  661.43
  4666.7  660.20  4808.1  658.37  4865.1  656.31  4900.2  656.34  4922.0  657.05
  4936.2  656.58  4962.6  654.74  4962.8  654.24  4966.3  654.24  4966.6  654.74
  4978.0  655.21  4992.2  654.83  5035.0  656.51  5196.9  659.32  5305.3  659.76
  5370.7  661.24  5468.7  662.38  5544.5  662.43  5577.2  663.07  5596.3  664.47
  5604.6  664.15  5609.8  664.55  5615.8  663.92  5626.3  664.50  5642.5  669.02
#Mann=4,-1,0
  4432.8    0.05       0  4962.6   0.033       0  4966.6    0.05       0
  5596.3   0.075       0
Bank Sta=4962.6,4966.6
Exp/Cntr=0.3,0.1

Type RM Length L Ch R = 1,23215,362,362,362
BEGIN DESCRIPTION:
Catherine Branch 38.0
END DESCRIPTION:
XS GIS Cut Line= 3
      2337729.01      7070560.01      2337279.00      7069960.00
      2336529.01      7069960.00
#Sta/Elev= 30
  4245.4  665.81  4338.1  664.21  4452.7  660.75  4488.1  660.64  4502.7  659.87
  4509.0  660.21  4517.3  659.75  4538.1  659.88  4681.9  657.50  4731.9  657.47
  4852.7  655.99  5015.4  655.93  5043.4  653.43  5043.7  652.93  5047.2  652.93
  5047.4  653.43  5055.4  653.99  5085.4  654.19  5105.4  655.25  5185.4  656.42
  5285.4  658.71  5395.4  659.14  5515.4  661.36  5575.4  661.29  5635.4  662.33
  5674.7  663.83  5695.4  664.85  5725.4  664.47  5742.9  669.32  5745.4  669.32
#Mann=4,-1,0
  4245.4    0.05       0  5043.4   0.033       0  5047.4    0.05       0
  5674.7   0.075       0
Bank Sta=5043.4,5047.4
Exp/Cntr=0.3,0.1

Type RM Length L Ch R = 1,22853,315,315,315
BEGIN DESCRIPTION:
Catherine Branch 37.0
END DESCRIPTION:
XS GIS Cut Line= 3
      2337928.99      7070359.98      2337479.00      7069760.00
      2336629.05      7069710.00
#Sta/Elev= 30
  4250.5  664.28  4364.0  661.07  4386.9  661.73  4414.0  661.79  4514.0  659.28
  4672.4  656.79  4807.8  656.23  4828.6  655.84  4836.9  654.34  4936.9  653.03
  4978.6  653.27  5020.5  652.46  5040.5  652.88  5058.6  650.67  5058.8  650.17
  5062.3  650.17  5062.6  650.67  5070.6  651.82  5080.6  652.01  5090.6  653.12
  5170.8  655.05  5180.8  654.49  5200.8  654.35  5260.9  655.78  5461.3  658.97
  5581.5  660.39  5651.6  660.73  5691.7  661.60  5831.9  663.03  5851.9  663.77
#Mann=3,-1,0
  4250.5    0.05       0  5058.6   0.033       0  5062.6    0.05       0
Bank Sta=5058.6,5062.6
Exp/Cntr=0.3,0.1

Type RM Length L Ch R = 1,22538,348,348,348
BEGIN DESCRIPTION:
Catherine Branch 36.0
END DESCRIPTION:
XS GIS Cut Line= 3
      2338028.98      7069909.98      2337629.00      7069510.00
      2336979.00      7069410.00
#Sta/Elev= 30
  4434.3  660.09  4448.4  660.34  4462.6  659.66  4561.5  657.54  4632.3  655.49
  4703.0  654.33  4717.1  654.49  4731.3  653.46  4773.7  652.43  4844.4  652.30
  4901.0  651.65  4929.2  652.23  4957.5  651.98  4985.8  650.57  4994.4  649.76
  4994.7  649.26  4998.2  649.26  4998.4  649.76  5002.5  649.76  5010.1  651.53
  5020.2  652.12  5040.4  652.77  5060.7  652.79  5080.9  653.97  5091.0  652.94
  5097.3  652.91  5131.5  654.13  5273.1  656.26  5323.7  656.25  5657.6  660.03
#Mann=3,-1,0
  4434.3    0.05       0  4994.4   0.033       0  4998.4    0.05       0
Bank Sta=4994.4,4998.4
Exp/Cntr=0.3,0.1

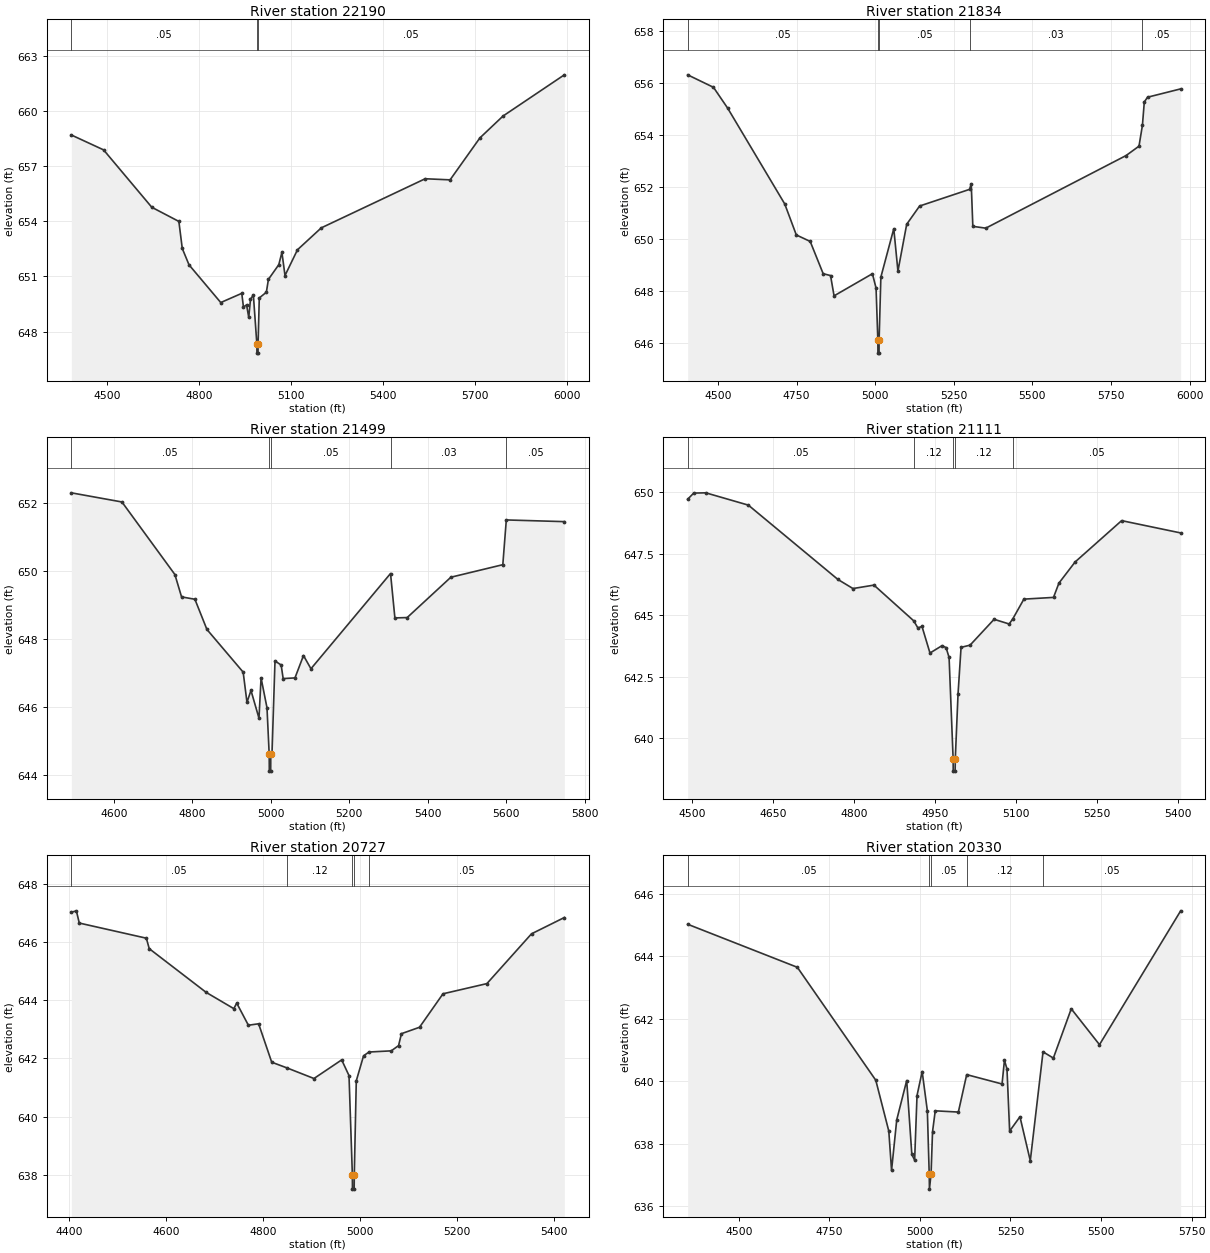
Type RM Length L Ch R = 1,22190,356,356,356
BEGIN DESCRIPTION:
Catherine Branch 35.0
END DESCRIPTION:
XS GIS Cut Line= 3
      2338386.69      7069520.82      2337829.00      7069260.00
      2336852.14      7069087.13
#Sta/Elev= 30
  4384.5  658.69  4489.7  657.88  4646.9  654.76  4735.2  653.99  4746.3  652.52
  4768.3  651.63  4871.8  649.58  4940.3  650.08  4945.8  649.34  4956.0  649.45
  4963.1  648.77  4968.7  649.75  4978.1  650.00  4989.5  647.33  4989.8  646.83
  4993.3  646.83  4993.5  647.33  4997.4  649.83  5020.5  650.14  5027.2  650.84
  5061.1  651.64  5071.2  652.31  5081.3  651.05  5122.0  652.45  5199.6  653.64
  5538.4  656.31  5619.6  656.25  5716.8  658.53  5792.3  659.72  5992.2  661.96
#Mann=3,-1,0
  4384.5    0.05       0  4989.5   0.033       0  4993.5    0.05       0
Bank Sta=4989.5,4993.5
Exp/Cntr=0.3,0.1

Type RM Length L Ch R = 1,21834,335,335,335
BEGIN DESCRIPTION:
Catherine Branch 34.0
END DESCRIPTION:
XS GIS Cut Line= 3
      2338525.57      7069199.64      2337979.00      7068960.00
      2337036.84      7068722.20
#Sta/Elev= 30
  4403.2  656.30  4485.4  655.82  4530.5  655.02  4712.1  651.34  4748.9  650.15
  4793.1  649.90  4834.4  648.66  4857.8  648.59  4869.0  647.81  4991.0  648.66
  5002.6  648.11  5008.3  646.11  5008.6  645.61  5012.1  645.61  5012.3  646.11
  5017.9  648.53  5059.0  650.39  5072.2  648.76  5100.1  650.56  5141.1  651.26
  5300.0  651.90  5305.4  652.11  5310.5  650.48  5351.6  650.41  5798.1  653.20
  5839.1  653.56  5850.0  654.36  5856.0  655.26  5866.3  655.44  5971.7  655.76
#Mann=5,-1,0
  4403.2    0.05       0  5008.3   0.033       0  5012.3    0.05       0
  5300.0    0.03       0  5850.0    0.05       0
Bank Sta=5008.3,5012.3
Exp/Cntr=0.3,0.1

Type RM Length L Ch R = 1,21499,388,388,388
BEGIN DESCRIPTION:
Catherine Branch 33.0
END DESCRIPTION:
XS GIS Cut Line= 3
      2338577.61      7068761.26      2338079.00      7068660.00
      2337345.06      7068518.22
#Sta/Elev= 30
  4491.6  652.31  4620.6  652.04  4755.5  649.90  4772.5  649.24  4806.5  649.17
  4837.1  648.28  4929.5  647.02  4939.2  646.13  4949.4  646.48  4969.8  645.66
  4975.1  646.85  4990.2  645.97  4995.8  644.60  4996.1  644.10  4999.6  644.10
  4999.8  644.60  5002.9  644.60  5010.6  647.35  5026.3  647.23  5031.4  646.83
  5061.5  646.85  5083.2  647.51  5102.2  647.12  5305.0  649.93  5316.1  648.62
  5347.4  648.63  5458.7  649.82  5591.1  650.19  5600.0  651.51  5747.9  651.46
#Mann=5,-1,0
  4491.6    0.05       0  4995.8   0.033       0  4999.8    0.05       0
  5305.0    0.03       0  5600.0    0.05       0
Bank Sta=4995.8,4999.8
Exp/Cntr=0.3,0.1

Type RM Length L Ch R = 1,21111,384,384,384
BEGIN DESCRIPTION:
Catherine Branch 32.0
END DESCRIPTION:
XS GIS Cut Line= 3
      2338599.34      7068522.55      2338043.80      7068240.43
      2337753.50      7068231.77
#Sta/Elev= 30
  4492.2  649.72  4503.5  649.97  4525.8  649.98  4604.7  649.48  4770.6  646.46
  4798.5  646.09  4837.4  646.23  4911.0  644.78  4918.8  644.49  4926.4  644.55
  4941.2  643.47  4963.6  643.77  4971.0  643.69  4976.6  643.29  4984.1  639.17
  4984.3  638.67  4987.8  638.67  4988.1  639.17  4993.2  641.81  4998.8  643.70
  5015.5  643.79  5060.0  644.84  5087.9  644.65  5094.7  644.86  5115.2  645.66
  5170.1  645.73  5180.1  646.31  5210.1  647.17  5296.3  648.85  5405.7  648.35
#Mann=5,-1,0
  4492.2    0.05       0  4911.0    0.12       0  4984.1    0.07       0
  4988.1    0.12       0  5094.7    0.05       0
Bank Sta=4984.1,4988.1
Exp/Cntr=0.3,0.1

Type RM Length L Ch R = 1,20727,397,397,397
BEGIN DESCRIPTION:
Catherine Branch 31.0
END DESCRIPTION:
XS GIS Cut Line= 3
      2338742.58      7068270.81      2338156.64      7067880.19
      2337865.87      7067993.03
#Sta/Elev= 30
  4404.7  647.02  4415.1  647.07  4421.1  646.65  4559.3  646.13  4565.3  645.77
  4682.5  644.27  4739.6  643.71  4745.6  643.90  4769.6  643.14  4790.7  643.19
  4817.7  641.87  4849.8  641.67  4904.8  641.31  4961.9  641.95  4977.0  641.41
  4983.9  638.01  4984.1  637.51  4987.6  637.51  4987.9  638.01  4992.0  641.23
  5007.0  642.09  5018.2  642.22  5064.1  642.26  5079.1  642.44  5085.1  642.85
  5122.3  643.07  5170.7  644.22  5261.2  644.57  5353.1  646.28  5420.8  646.84
#Mann=5,-1,0
  4404.7    0.05       0  4849.8    0.12       0  4983.9    0.07       0
  4987.9    0.12       0  5018.2    0.05       0
Bank Sta=4983.9,4987.9
Exp/Cntr=0.3,0.1

Type RM Length L Ch R = 1,20330,388,388,388
BEGIN DESCRIPTION:
Catherine Branch 30.0
END DESCRIPTION:
XS GIS Cut Line= 3
      2338846.76      7068227.44      2338564.63      7067771.68
      2338026.44      7067146.69
#Sta/Elev= 30
  4359.0  645.03  4661.8  643.65  4878.3  640.03  4914.2  638.40  4921.8  637.14
  4936.1  638.76  4963.6  640.02  4977.8  637.65  4985.5  637.47  4992.1  639.54
  5006.3  640.31  5020.6  639.05  5025.7  637.04  5026.4  636.54  5030.9  637.04
  5034.9  638.38  5042.4  639.05  5106.2  639.01  5129.2  640.21  5226.8  639.91
  5233.4  640.67  5240.4  640.39  5247.7  638.40  5276.2  638.86  5304.7  637.45
  5339.9  640.94  5368.4  640.74  5417.8  642.32  5495.7  641.17  5719.8  645.46
#Mann=5,-1,0
  4359.0    0.05       0  5025.7   0.033       0  5030.9    0.05       0
  5129.2    0.12       0  5339.9    0.05       0
Bank Sta=5025.7,5030.9
Exp/Cntr=0.3,0.1