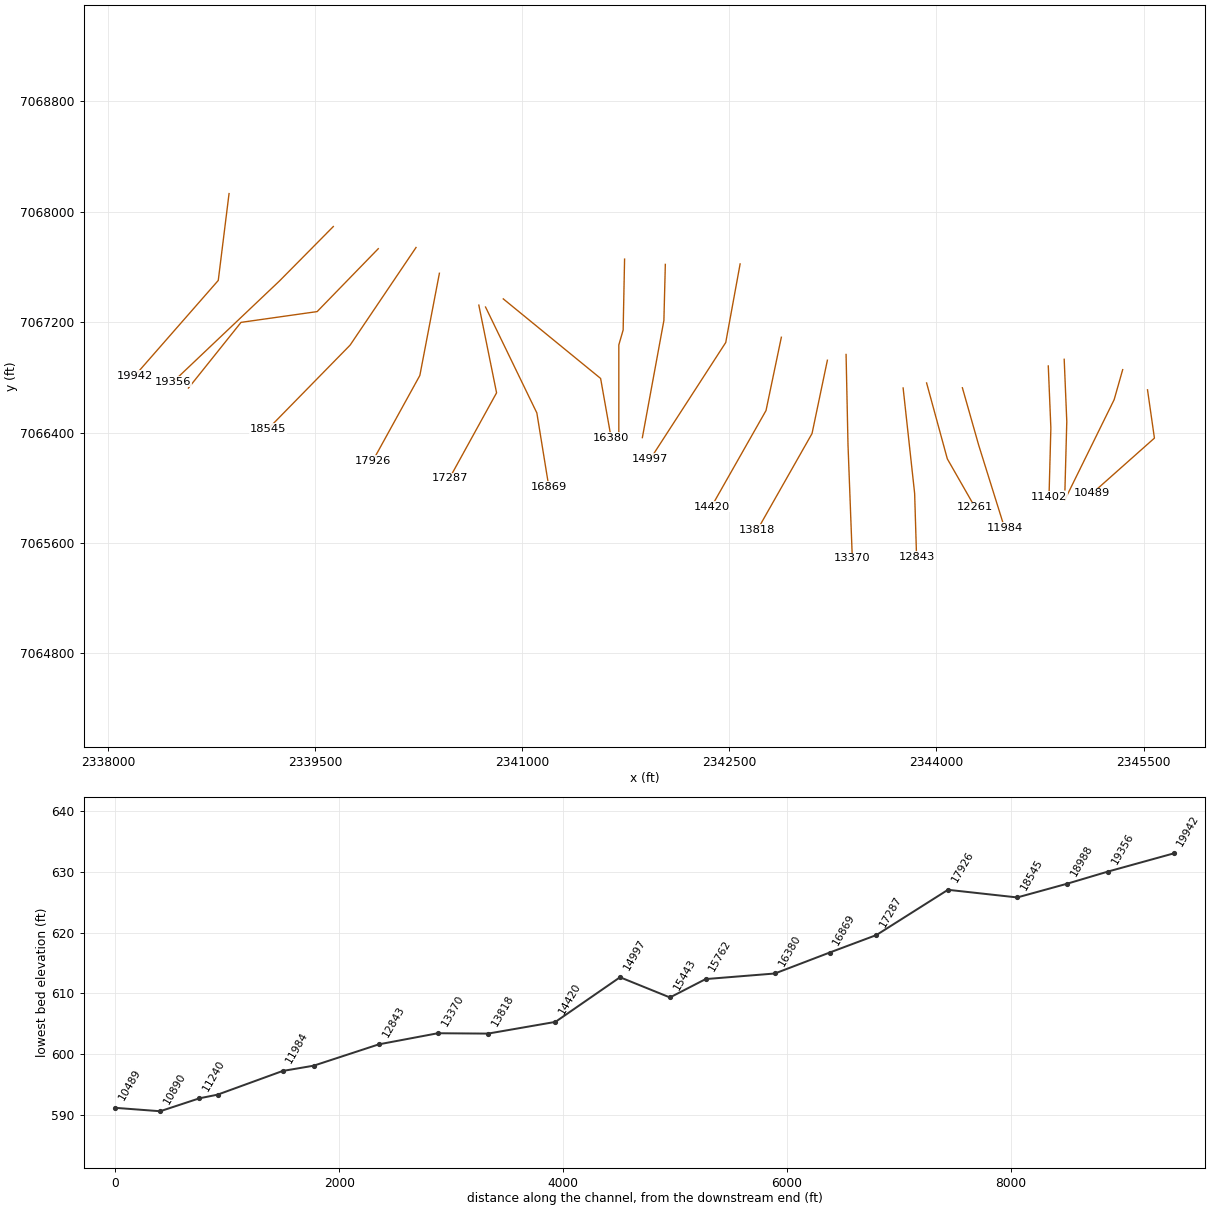
HEC-RAS study Catherine Branch.prj: Catherine Branch Base Level Engineering

--- Catherine Branch.g01 (geometry) --- (continued)

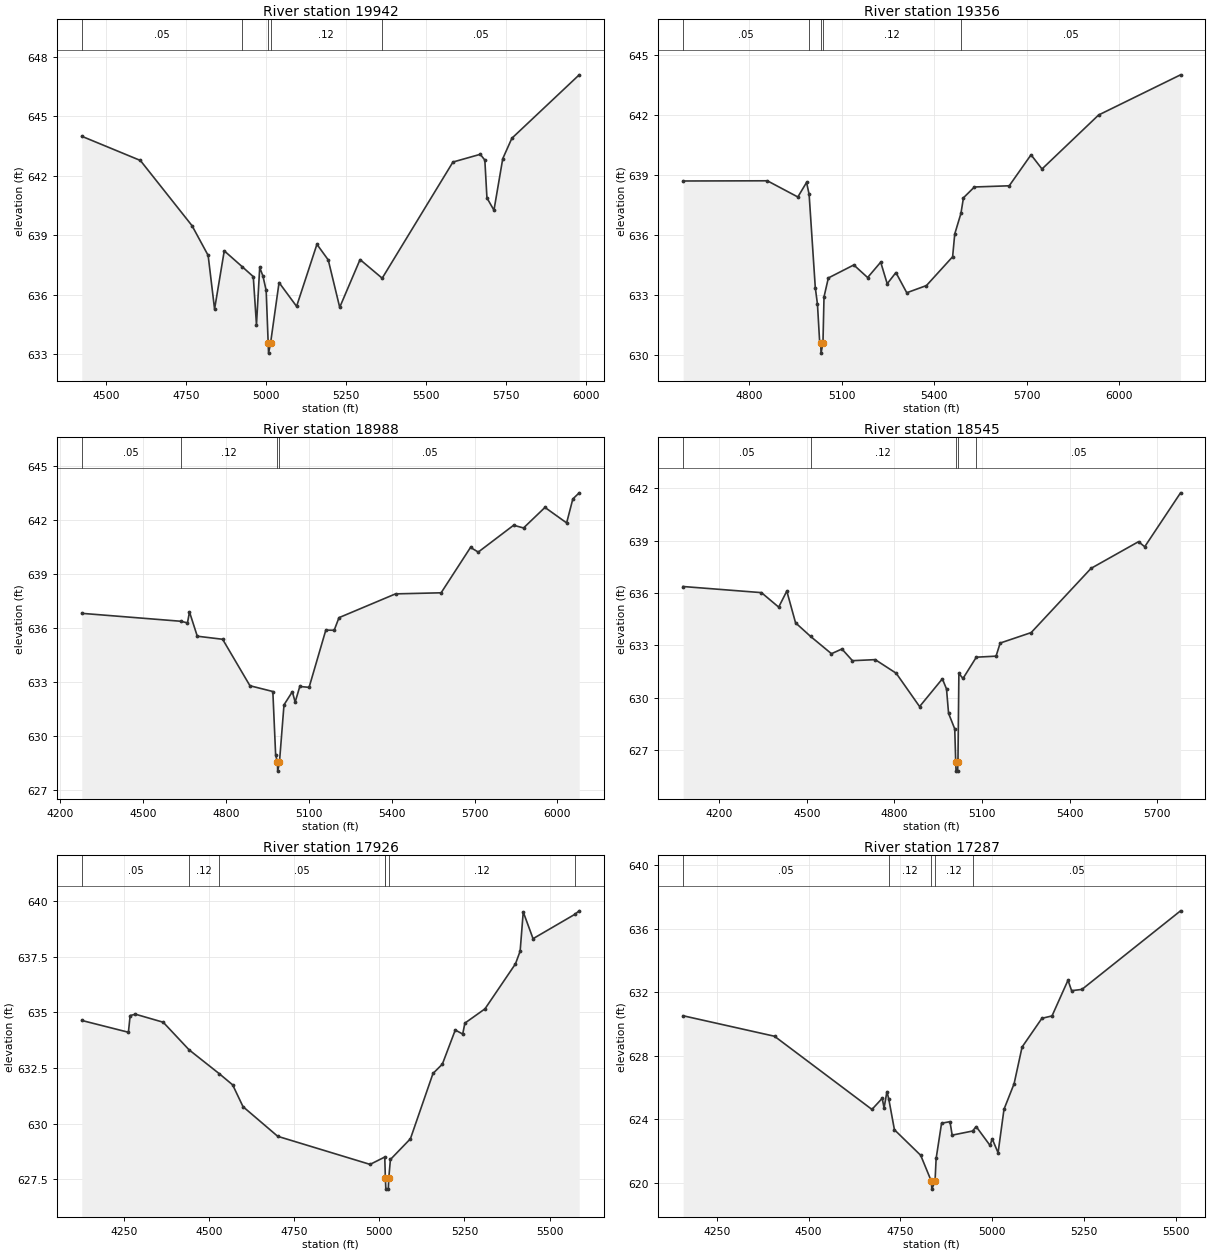
Type RM Length L Ch R = 1,19942,586,586,586
BEGIN DESCRIPTION:
Catherine Branch 29.5
END DESCRIPTION:
XS GIS Cut Line= 3
      2338877.13      7068131.97      2338799.00      7067502.59
      2338192.66      7066809.62
#Sta/Elev= 30
  4423.8  644.00  4606.9  642.78  4768.4  639.49  4818.8  637.99  4838.9  635.28
  4869.2  638.22  4924.6  637.43  4959.9  636.92  4969.9  634.49  4980.0  637.38
  4990.1  636.95  5000.2  636.22  5006.5  633.56  5007.7  633.06  5013.9  633.56
  5040.5  636.62  5095.3  635.42  5158.9  638.55  5194.3  637.76  5230.1  635.37
  5293.7  637.78  5362.9  636.84  5584.1  642.70  5669.5  643.09  5683.8  642.80
  5690.4  640.89  5712.3  640.27  5739.8  642.87  5768.3  643.90  5978.8  647.10
#Mann=5,-1,0
  4423.8    0.05       0  4924.6    0.12       0  5006.5    0.07       0
  5013.9    0.12       0  5362.9    0.05       0
Bank Sta=5006.5,5013.9
Exp/Cntr=0.3,0.1

Type RM Length L Ch R = 1,19356,368,368,368
BEGIN DESCRIPTION:
Catherine Branch 29.0
END DESCRIPTION:
XS GIS Cut Line= 3
      2339632.34      7067893.21      2339241.71      7067498.25
      2338473.76      7066769.35
#Sta/Elev= 30
  4585.0  638.68  4858.3  638.69  4957.3  637.88  4985.6  638.61  4993.9  638.01
  5013.9  633.35  5021.0  632.51  5028.0  630.65  5031.4  630.57  5032.6  630.07
  5038.8  630.57  5042.2  632.88  5056.3  633.83  5138.9  634.48  5183.8  633.85
  5226.2  634.62  5247.3  633.54  5275.6  634.10  5310.8  633.09  5374.7  633.45
  5459.6  634.89  5466.5  636.03  5486.6  637.06  5494.8  637.84  5530.3  638.38
  5643.3  638.44  5714.1  639.99  5749.7  639.28  5933.3  641.98  6199.3  643.99
#Mann=5,-1,0
  4585.0    0.05       0  4993.9    0.12       0  5031.4    0.07       0
  5038.8    0.12       0  5486.6    0.05       0
Bank Sta=5031.4,5038.8
Exp/Cntr=0.3,0.1

Type RM Length L Ch R = 1,18988,443,443,443
BEGIN DESCRIPTION:
Catherine Branch 28.0
END DESCRIPTION:
XS GIS Cut Line= 4
      2339957.88      7067732.65      2339515.15      7067276.89
      2338963.94      7067198.77      2338583.01      7066722.61
#Sta/Elev= 30
  4277.2  636.81  4635.8  636.37  4660.1  636.28  4667.3  636.89  4695.6  635.54
  4787.4  635.37  4886.4  632.79  4969.3  632.47  4979.4  628.96  4985.8  628.55
  4986.9  628.05  4993.3  628.55  5009.7  631.73  5040.0  632.46  5050.1  631.88
  5066.9  632.75  5100.6  632.70  5161.2  635.88  5191.5  635.87  5208.9  636.57
  5413.7  637.89  5578.9  637.95  5685.4  640.47  5713.4  640.21  5841.5  641.70
  5877.5  641.55  5955.1  642.69  6033.6  641.83  6056.0  643.16  6079.1  643.50
#Mann=4,-1,0
  4277.2    0.05       0  4635.8    0.12       0  4985.8   0.033       0
  4993.3    0.05       0
Bank Sta=4985.8,4993.3
Exp/Cntr=0.3,0.1

Type RM Length L Ch R = 1,18545,619,619,619
BEGIN DESCRIPTION:
Catherine Branch 27.0
END DESCRIPTION:
XS GIS Cut Line= 3
      2340231.32      7067741.34      2339753.87      7067033.84
      2339159.25      7066426.20
#Sta/Elev= 30
  4076.5  636.38  4344.7  636.03  4403.8  635.20  4431.6  636.12  4461.6  634.30
  4513.1  633.52  4584.5  632.53  4620.4  632.80  4656.4  632.13  4734.4  632.19
  4806.3  631.41  4886.4  629.50  4964.4  631.09  4978.6  630.51  4985.7  629.11
  5006.8  628.22  5010.2  626.30  5011.3  625.80  5016.6  625.80  5017.8  626.30
  5021.0  631.40  5035.1  631.11  5080.7  632.33  5148.3  632.39  5162.4  633.14
  5268.6  633.74  5473.6  637.42  5636.2  638.95  5657.5  638.66  5780.2  641.75
#Mann=5,-1,0
  4076.5    0.05       0  4513.1    0.12       0  5010.2    0.07       0
  5017.8    0.12       0  5080.7    0.05       0
Bank Sta=5010.2,5017.8
Exp/Cntr=0.3,0.1

Type RM Length L Ch R = 1,17926,639,639,639
BEGIN DESCRIPTION:
Catherine Branch 26.5
END DESCRIPTION:
XS GIS Cut Line= 3
      2340400.57      7067554.69      2340259.07      7066814.22
      2339918.80      7066196.17
#Sta/Elev= 30
  4127.2  634.63  4264.0  634.10  4269.1  634.85  4284.7  634.91  4366.1  634.55
  4442.1  633.31  4530.6  632.24  4569.8  631.74  4600.3  630.76  4702.1  629.43
  4973.0  628.17  5016.1  628.50  5017.9  627.56  5019.3  627.06  5026.5  627.06
  5027.9  627.56  5032.7  628.39  5091.4  629.32  5157.6  632.25  5185.1  632.67
  5223.0  634.20  5244.8  634.02  5251.2  634.51  5310.1  635.15  5399.6  637.17
  5413.3  637.74  5422.4  639.50  5451.2  638.30  5573.5  639.39  5586.6  639.55
#Mann=7,-1,0
  4127.2    0.05       0  4442.1    0.12       0  4530.6    0.05       0
  5016.1    0.12       0  5017.9   0.033       0  5027.9    0.12       0
  5573.5    0.05       0
Bank Sta=5017.9,5027.9
Exp/Cntr=0.3,0.1

Type RM Length L Ch R = 1,17287,418,418,418
BEGIN DESCRIPTION:
Catherine Branch 26.0
END DESCRIPTION:
XS GIS Cut Line= 3
      2340686.17      7067323.72      2340814.63      7066688.35
      2340474.33      7066070.26
#Sta/Elev= 30
  4158.7  630.52  4407.4  629.23  4672.6  624.62  4700.5  625.32  4705.6  624.72
  4713.4  625.74  4718.2  625.30  4733.8  623.34  4805.3  621.73  4834.2  620.10
  4835.6  619.60  4844.3  620.10  4847.3  621.53  4862.1  623.75  4885.0  623.85
  4890.9  623.00  4946.4  623.26  4956.3  623.54  4994.1  622.35  4999.8  622.77
  5015.9  621.89  5032.0  624.63  5059.5  626.24  5081.2  628.55  5135.2  630.36
  5162.7  630.51  5206.2  632.76  5216.0  632.10  5244.1  632.18  5512.5  637.13
#Mann=5,-1,0
  4158.7    0.05       0  4718.2    0.12       0  4834.2   0.033       0
  4844.3    0.12       0  4946.4    0.05       0
Bank Sta=4834.2,4844.3
Exp/Cntr=0.3,0.1

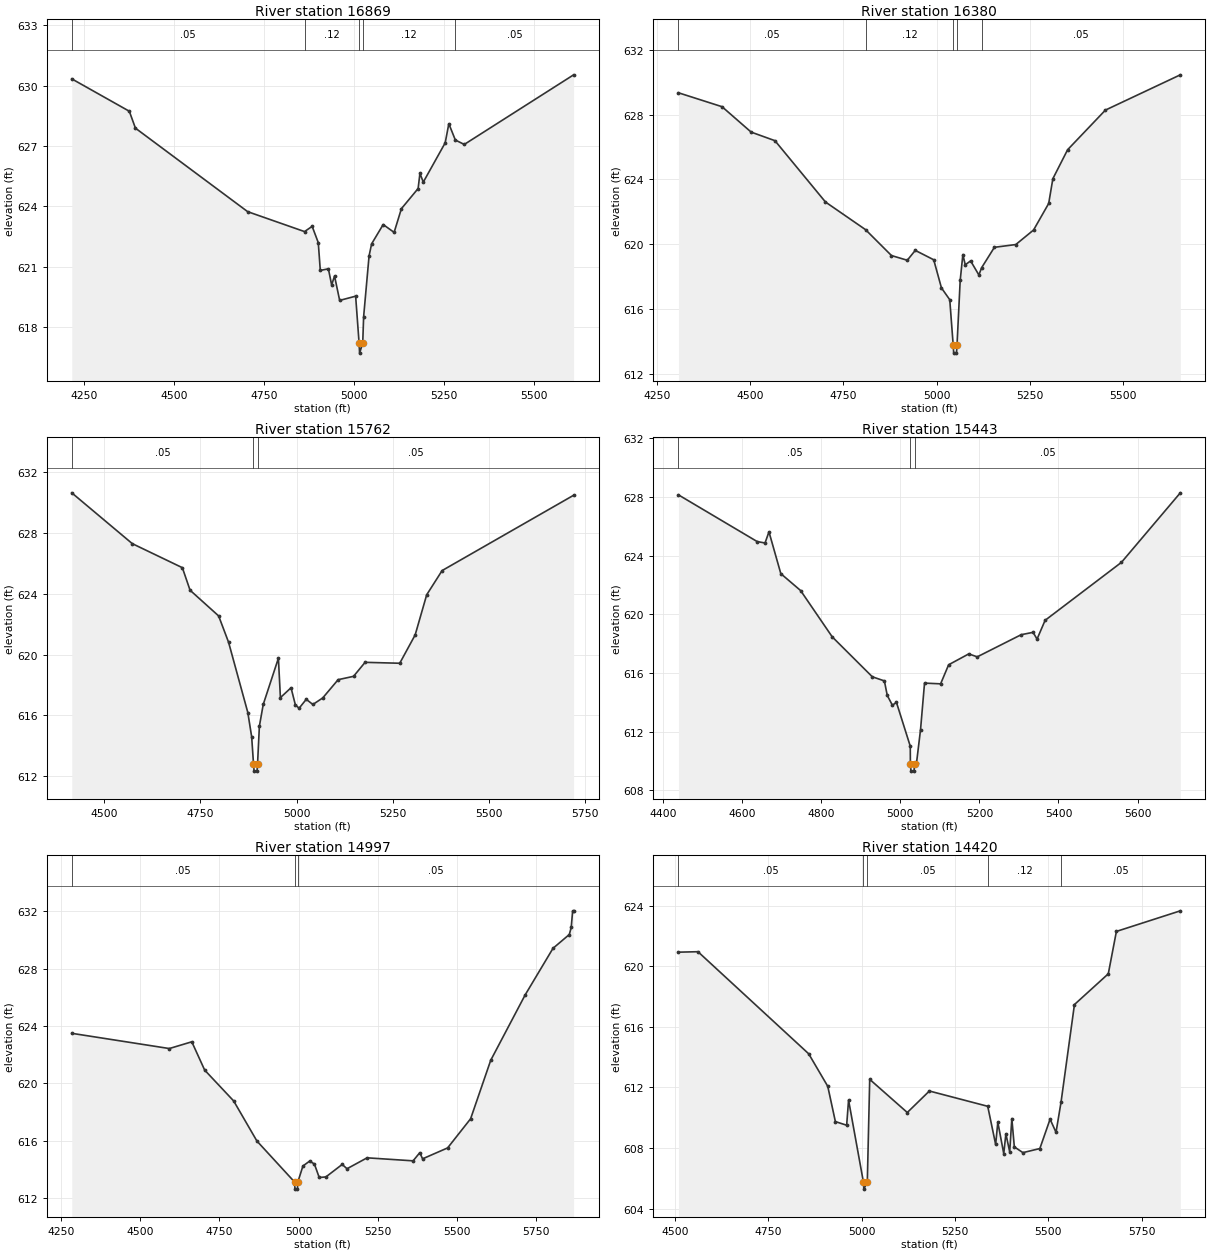
Type RM Length L Ch R = 1,16869,489,489,489
BEGIN DESCRIPTION:
Catherine Branch 25.0
END DESCRIPTION:
XS GIS Cut Line= 3
      2340734.77      7067309.87      2341106.30      7066542.52
      2341193.10      7066007.78
#Sta/Elev= 30
  4215.0  630.34  4374.9  628.73  4391.9  627.89  4703.7  623.74  4861.7  622.75
  4882.9  623.01  4899.9  622.20  4905.5  620.82  4928.0  620.90  4937.0  620.10
  4945.1  620.54  4959.3  619.33  5003.7  619.54  5013.3  617.21  5014.7  616.71
  5023.4  617.21  5025.9  618.52  5041.0  621.54  5048.1  622.14  5080.2  623.10
  5110.6  622.71  5130.9  623.89  5177.3  624.89  5182.3  625.64  5191.7  625.21
  5252.5  627.16  5262.6  628.11  5280.7  627.30  5305.5  627.08  5609.3  630.54
#Mann=5,-1,0
  4215.0    0.05       0  4861.7    0.12       0  5013.3    0.07       0
  5023.4    0.12       0  5280.7    0.05       0
Bank Sta=5013.3,5023.4
Exp/Cntr=0.3,0.1

Type RM Length L Ch R = 1,16380,618,618,618
BEGIN DESCRIPTION:
Catherine Branch 24.0
END DESCRIPTION:
XS GIS Cut Line= 3
      2340863.26      7067368.89      2341568.10      7066792.52
      2341644.49      7066361.94
#Sta/Elev= 30
  4306.9  629.35  4423.9  628.49  4502.1  626.92  4566.0  626.39  4701.7  622.60
  4809.4  620.89  4879.0  619.29  4921.4  619.00  4942.9  619.61  4992.4  619.03
  5013.2  617.29  5035.5  616.56  5044.7  613.76  5046.1  613.26  5053.5  613.26
  5055.0  613.76  5063.5  617.75  5070.7  619.35  5077.1  618.72  5091.5  618.96
  5113.7  618.09  5121.1  618.54  5155.4  619.80  5212.8  619.97  5260.6  620.87
  5301.2  622.51  5312.4  624.04  5352.0  625.83  5453.5  628.28  5654.7  630.46
#Mann=5,-1,0
  4306.9    0.05       0  4809.4    0.12       0  5044.7    0.07       0
  5055.0    0.12       0  5121.1    0.05       0
Bank Sta=5044.7,5055
Exp/Cntr=0.3,0.1

Type RM Length L Ch R = 1,15762,319,319,319
BEGIN DESCRIPTION:
Catherine Branch 23.0
END DESCRIPTION:
XS GIS Cut Line= 4
      2341741.71      7067657.14      2341731.30      7067143.21
      2341700.05      7067035.57      2341700.05      7066358.49
#Sta/Elev= 30
  4416.2  630.63  4573.4  627.29  4703.4  625.71  4723.4  624.23  4797.6  622.54
  4823.4  620.81  4873.4  616.19  4883.4  614.59  4888.1  612.84  4889.6  612.34
  4897.3  612.34  4898.7  612.84  4903.4  615.29  4913.4  616.72  4952.8  619.76
  4958.0  617.17  4985.6  617.82  4996.8  616.70  5006.5  616.47  5025.1  617.06
  5042.3  616.72  5067.9  617.15  5107.9  618.35  5147.9  618.57  5177.9  619.49
  5267.9  619.43  5307.9  621.29  5337.9  623.93  5377.9  625.52  5719.4  630.47
#Mann=3,-1,0
  4416.2    0.05       0  4888.1   0.033       0  4898.7    0.05       0
Bank Sta=4888.1,4898.7
Exp/Cntr=0.3,0.1

Type RM Length L Ch R = 1,15443,446,446,446
BEGIN DESCRIPTION:
Catherine Branch 22.0
END DESCRIPTION:
XS GIS Cut Line= 3
      2342036.85      7067618.95      2342026.44      7067212.66
      2341870.46      7066363.48
#Sta/Elev= 30
  4438.5  628.14  4637.5  624.96  4657.5  624.86  4667.5  625.62  4697.5  622.77
  4747.5  621.62  4827.6  618.46  4929.0  615.74  4959.5  615.46  4966.8  614.47
  4979.8  613.80  4990.0  614.00  5025.0  611.01  5025.3  609.81  5026.8  609.31
  5034.5  609.31  5035.9  609.81  5040.8  609.86  5051.0  612.14  5061.1  615.31
  5101.8  615.26  5122.1  616.56  5173.0  617.30  5194.5  617.10  5305.7  618.61
  5335.7  618.77  5345.8  618.31  5366.2  619.59  5559.3  623.54  5708.3  628.28
#Mann=3,-1,0
  4438.5    0.05       0  5025.3   0.033       0  5035.9    0.05       0
Bank Sta=5025.3,5035.9
Exp/Cntr=0.3,0.1

Type RM Length L Ch R = 1,14997,577,577,577
BEGIN DESCRIPTION:
Catherine Branch 21.0
END DESCRIPTION:
XS GIS Cut Line= 3
      2342578.52      7067622.39      2342474.35      7067052.93
      2341928.98      7066209.97
#Sta/Elev= 30
  4284.7  623.49  4592.4  622.43  4663.3  622.90  4703.9  620.93  4795.4  618.78
  4868.7  615.99  4987.3  613.14  4988.8  612.64  4996.5  612.64  4997.9  613.14
  5013.8  614.25  5034.9  614.59  5050.0  614.39  5065.2  613.45  5086.3  613.49
  5137.7  614.36  5152.9  614.06  5216.2  614.82  5361.3  614.61  5382.5  615.18
  5391.2  614.75  5470.2  615.51  5542.7  617.54  5606.1  621.61  5714.9  626.17
  5802.6  629.41  5854.0  630.37  5860.0  630.86  5864.6  632.02  5867.6  632.02
#Mann=3,-1,0
  4284.7    0.05       0  4987.3   0.033       0  4997.9    0.05       0
Bank Sta=4987.3,4997.9
Exp/Cntr=0.3,0.1

Type RM Length L Ch R = 1,14420,602,602,602
BEGIN DESCRIPTION:
Catherine Branch 20.5
END DESCRIPTION:
XS GIS Cut Line= 3
      2342877.12      7067091.10      2342766.02      7066559.88
      2342371.06      7065863.50
#Sta/Elev= 30
  4510.0  620.93  4562.2  620.96  4858.5  614.22  4909.6  612.07  4930.0  609.74
  4960.2  609.50  4965.3  611.16  5004.8  605.78  5006.3  605.28  5015.5  605.78
  5021.9  612.53  5122.5  610.34  5181.6  611.76  5337.8  610.75  5359.0  608.23
  5364.8  609.70  5380.7  607.62  5386.4  608.94  5396.6  607.74  5402.3  609.94
  5409.0  608.07  5432.0  607.69  5477.3  607.96  5504.7  609.90  5520.6  609.03
  5534.0  611.02  5569.9  617.47  5660.5  619.50  5682.2  622.30  5853.3  623.66
#Mann=5,-1,0
  4510.0    0.05       0  5004.8   0.033       0  5015.5    0.05       0
  5337.8    0.12       0  5534.0    0.05       0
Bank Sta=5004.8,5015.5
Exp/Cntr=0.3,0.1

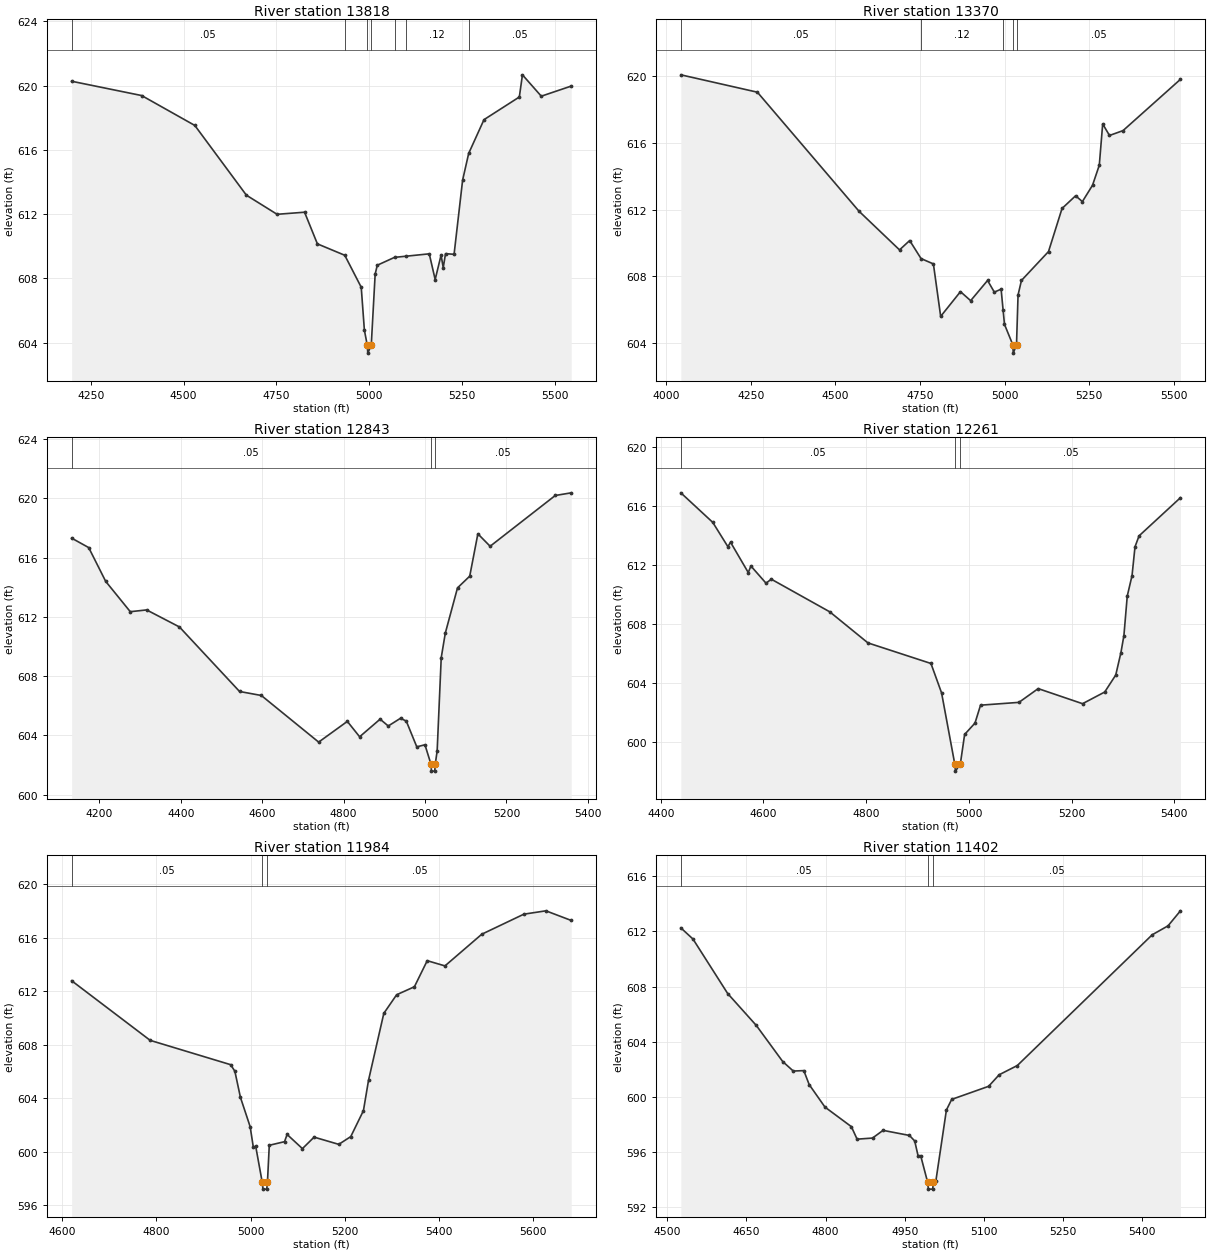
Type RM Length L Ch R = 1,13818,448,448,448
BEGIN DESCRIPTION:
Catherine Branch 20.2
END DESCRIPTION:
XS GIS Cut Line= 3
      2343210.47      7066924.48      2343099.35      7066393.21
      2342703.78      7065695.75
#Sta/Elev= 30
  4198.9  620.27  4387.4  619.38  4530.4  617.52  4669.2  613.18  4751.8  611.99
  4825.8  612.12  4860.3  610.15  4934.0  609.44  4978.3  607.45  4986.8  604.78
  4994.5  603.85  4996.0  603.35  5005.3  603.85  5015.8  608.27  5021.5  608.82
  5067.9  609.31  5098.2  609.38  5161.4  609.53  5177.3  607.93  5193.2  609.45
  5199.0  608.67  5205.2  609.54  5228.2  609.50  5251.2  614.12  5267.5  615.78
  5308.7  617.88  5403.8  619.29  5412.2  620.67  5462.9  619.34  5543.5  619.97
#Mann=7,-1,0
  4198.9    0.05       0  4934.0    0.12       0  4994.5    0.07       0
  5005.3    0.12       0  5067.9    0.05       0  5098.2    0.12       0
  5267.5    0.05       0
Bank Sta=4994.5,5005.3
Exp/Cntr=0.3,0.1

Type RM Length L Ch R = 1,13370,527,527,527
BEGIN DESCRIPTION:
Catherine Branch 20.0
END DESCRIPTION:
XS GIS Cut Line= 3
      2343345.88      7066966.16      2343359.77      7066313.35
      2343391.02      7065490.40
#Sta/Elev= 30
  4043.4  620.07  4269.6  619.03  4569.7  611.91  4689.7  609.59  4719.7  610.15
  4753.3  609.07  4789.8  608.75  4811.3  605.61  4869.8  607.09  4899.9  606.55
  4949.9  607.76  4969.9  607.06  4989.9  607.24  4995.9  605.97  4999.9  605.13
  5024.5  603.91  5025.9  603.41  5035.4  603.91  5040.0  606.89  5050.0  607.76
  5130.0  609.49  5170.0  612.07  5210.1  612.83  5230.1  612.48  5260.1  613.46
  5280.1  614.66  5290.1  617.13  5310.2  616.44  5350.2  616.73  5519.9  619.80
#Mann=5,-1,0
  4043.4    0.05       0  4753.3    0.12       0  4995.9    0.05       0
  5024.5   0.035       0  5035.4    0.05       0
Bank Sta=5024.5,5035.4
Exp/Cntr=0.3,0.1

Type RM Length L Ch R = 1,12843,582,582,582
BEGIN DESCRIPTION:
Catherine Branch 19.5
END DESCRIPTION:
XS GIS Cut Line= 3
      2343759.07      7066723.11      2343842.41      7065959.18
      2343856.30      7065500.85
#Sta/Elev= 30
  4132.0  617.32  4173.9  616.68  4215.6  614.40  4276.0  612.35  4316.2  612.47
  4396.7  611.32  4544.4  606.96  4597.9  606.69  4738.7  603.54  4809.1  604.94
  4839.3  603.90  4889.6  605.09  4909.6  604.63  4939.7  605.15  4953.9  604.96
  4979.7  603.22  4999.7  603.36  5014.2  602.08  5015.7  601.58  5023.7  601.58
  5025.2  602.08  5029.7  602.94  5039.7  609.24  5049.7  610.90  5079.7  613.96
  5109.7  614.75  5129.7  617.61  5159.8  616.77  5319.8  620.20  5359.0  620.38
#Mann=3,-1,0
  4132.0    0.05       0  5014.2   0.035       0  5025.2    0.05       0
Bank Sta=5014.2,5025.2
Exp/Cntr=0.3,0.1

Type RM Length L Ch R = 1,12261,277,277,277
BEGIN DESCRIPTION:
Catherine Branch 19.0
END DESCRIPTION:
XS GIS Cut Line= 3
      2343928.99      7066760.02      2344079.00      7066210.00
      2344278.99      7065860.02
#Sta/Elev= 30
  4439.0  616.88  4501.2  614.88  4530.6  613.24  4535.8  613.54  4570.3  611.49
  4575.5  611.93  4604.9  610.77  4615.2  611.04  4729.2  608.83  4803.5  606.73
  4926.2  605.34  4946.9  603.35  4972.5  598.56  4974.0  598.06  4983.5  598.56
  4991.8  600.54  5012.0  601.31  5022.8  602.52  5097.6  602.71  5135.1  603.64
  5221.5  602.62  5264.7  603.41  5286.2  604.56  5296.3  606.08  5302.1  607.23
  5308.6  609.90  5317.9  611.28  5323.7  613.23  5331.6  613.97  5412.2  616.55
#Mann=3,-1,0
  4439.0    0.05       0  4972.5   0.033       0  4983.5    0.05       0
Bank Sta=4972.5,4983.5
Exp/Cntr=0.3,0.1

Type RM Length L Ch R = 1,11984,582,582,582
BEGIN DESCRIPTION:
Catherine Branch 18.0
END DESCRIPTION:
XS GIS Cut Line= 3
      2344188.25      7066724.83      2344306.23      7066309.22
      2344493.89      7065708.69
#Sta/Elev= 30
  4619.9  612.78  4786.7  608.32  4957.6  606.50  4966.6  606.01  4978.4  604.06
  4999.1  601.86  5005.7  600.35  5010.9  600.39  5024.8  597.69  5026.3  597.19
  5034.3  597.19  5035.8  597.69  5039.7  600.47  5072.1  600.74  5077.6  601.28
  5110.1  600.22  5134.9  601.08  5187.3  600.54  5212.8  601.12  5239.7  603.06
  5250.5  605.33  5283.0  610.34  5310.2  611.73  5348.0  612.33  5375.2  614.28
  5412.9  613.89  5491.1  616.26  5580.5  617.76  5627.3  618.01  5681.1  617.29
#Mann=3,-1,0
  4619.9    0.05       0  5024.8   0.033       0  5035.8    0.05       0
Bank Sta=5024.8,5035.8
Exp/Cntr=0.3,0.1

Type RM Length L Ch R = 1,11402,162,162,162
BEGIN DESCRIPTION:
Catherine Branch 17.2
END DESCRIPTION:
XS GIS Cut Line= 3
      2344810.27      7066882.95      2344829.03      7066432.55
      2344815.63      7065936.52
#Sta/Elev= 30
  4525.7  612.26  4548.7  611.45  4614.5  607.49  4668.8  605.17  4718.8  602.55
  4738.8  601.86  4758.8  601.89  4768.9  600.88  4798.9  599.24  4848.9  597.82
  4859.8  596.91  4889.0  596.99  4909.0  597.55  4959.0  597.18  4969.0  596.78
  4975.3  595.71  4980.3  595.71  4993.5  593.78  4995.0  593.28  5003.0  593.28
  5004.5  593.78  5009.0  593.85  5029.1  599.03  5039.1  599.80  5109.1  600.75
  5129.1  601.59  5163.5  602.26  5419.2  611.76  5449.2  612.41  5472.7  613.50
#Mann=3,-1,0
  4525.7    0.05       0  4993.5   0.033       0  5004.5    0.05       0
Bank Sta=4993.5,5004.5
Exp/Cntr=0.3,0.1

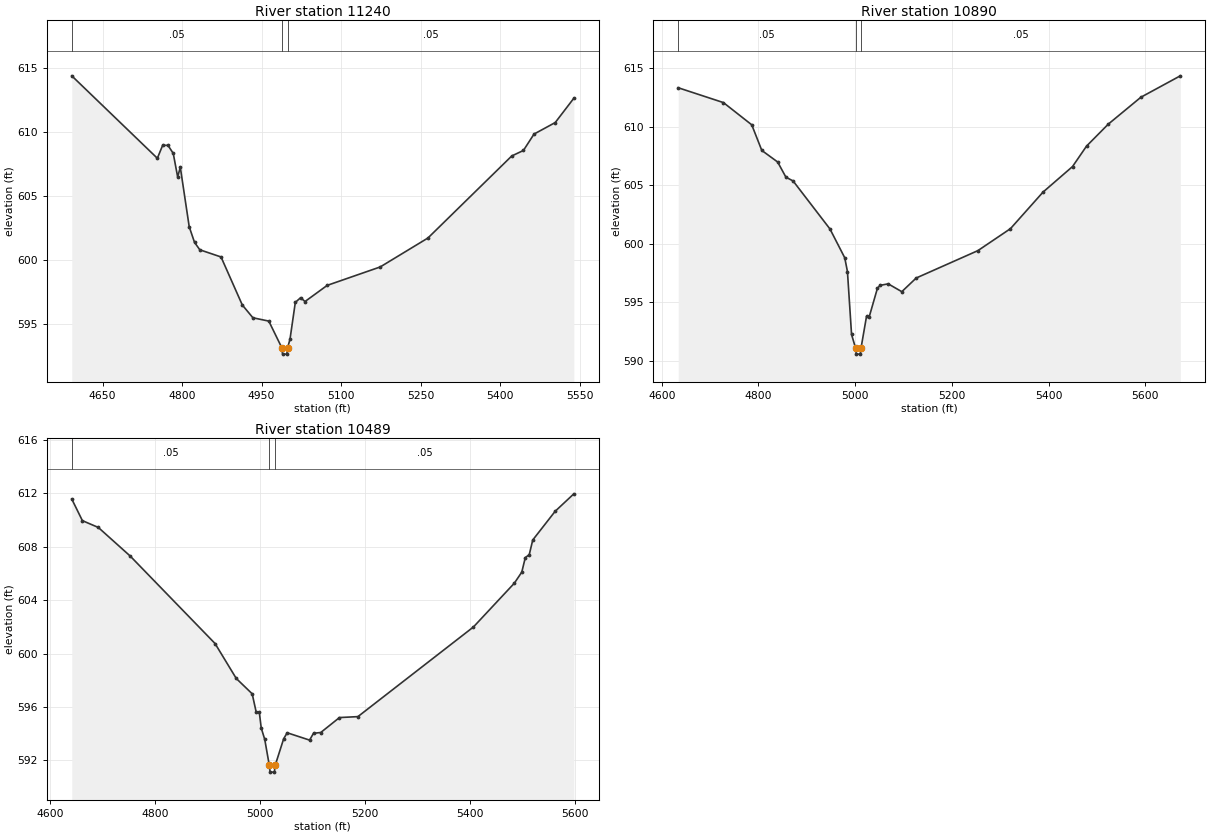
Type RM Length L Ch R = 1,11240,350,350,350
BEGIN DESCRIPTION:
Catherine Branch 17.0
END DESCRIPTION:
XS GIS Cut Line= 3
      2344925.55      7066931.27      2344944.32      7066480.81
      2344930.92      7065984.94
#Sta/Elev= 30
  4592.0  614.42  4753.4  607.98  4763.4  608.99  4773.4  608.99  4783.4  608.36
  4791.7  606.52  4796.7  607.28  4813.5  602.63  4823.5  601.41  4833.5  600.83
  4873.5  600.27  4913.6  596.52  4933.6  595.52  4963.6  595.26  4988.1  593.18
  4989.6  592.68  4997.6  592.68  4999.1  593.18  5003.6  593.85  5013.6  596.72
  5023.6  597.09  5031.9  596.79  5073.7  598.05  5173.7  599.49  5263.7  601.75
  5421.8  608.16  5443.8  608.59  5463.8  609.87  5503.8  610.77  5538.9  612.67
#Mann=3,-1,0
  4592.0    0.05       0  4988.1   0.033       0  4999.1    0.05       0
Bank Sta=4988.1,4999.1
Exp/Cntr=0.3,0.1

Type RM Length L Ch R = 1,10890,401,401,401
BEGIN DESCRIPTION:
Catherine Branch 16.0
END DESCRIPTION:
XS GIS Cut Line= 3
      2345349.17      7066856.19      2345287.50      7066638.99
      2344928.98      7065909.96
#Sta/Elev= 30
  4634.2  613.33  4727.7  612.06  4786.2  610.16  4807.0  607.97  4839.8  606.98
  4856.9  605.68  4871.7  605.36  4948.0  601.25  4978.5  598.79  4984.1  597.61
  4992.6  592.23  5001.0  591.05  5002.5  590.55  5010.6  590.55  5012.1  591.05
  5023.5  593.77  5029.1  593.74  5046.0  596.17  5051.5  596.43  5068.4  596.56
  5096.5  595.89  5126.3  597.06  5253.8  599.40  5321.2  601.28  5388.6  604.41
  5449.5  606.59  5478.5  608.34  5523.5  610.22  5590.9  612.52  5672.4  614.35
#Mann=3,-1,0
  4634.2    0.05       0  5001.0   0.033       0  5012.1    0.05       0
Bank Sta=5001,5012.1
Exp/Cntr=0.3,0.1

Type RM Length L Ch R = 1,10489,447,447,447
BEGIN DESCRIPTION:
Catherine Branch 15.0
END DESCRIPTION:
XS GIS Cut Line= 3
      2345529.01      7066709.96      2345579.00      7066360.00
      2345128.99      7065959.99
#Sta/Elev= 30
  4642.0  611.58  4662.2  609.96  4692.5  609.45  4753.1  607.31  4914.7  600.75
  4955.1  598.13  4985.4  596.98  4993.0  595.61  4998.9  595.61  5002.6  594.42
  5009.3  593.56  5018.0  591.61  5019.5  591.11  5027.6  591.11  5029.1  591.61
  5045.3  593.61  5052.0  594.06  5094.6  593.51  5102.1  594.02  5115.9  594.08
  5151.5  595.20  5186.6  595.27  5406.5  601.99  5484.3  605.27  5498.5  606.10
  5505.2  607.19  5512.7  607.41  5519.4  608.51  5562.0  610.66  5597.6  611.97
#Mann=3,-1,0
  4642.0    0.05       0  5018.0    0.04       0  5029.1    0.05       0
Bank Sta=5018,5029.1
Exp/Cntr=0.3,0.1