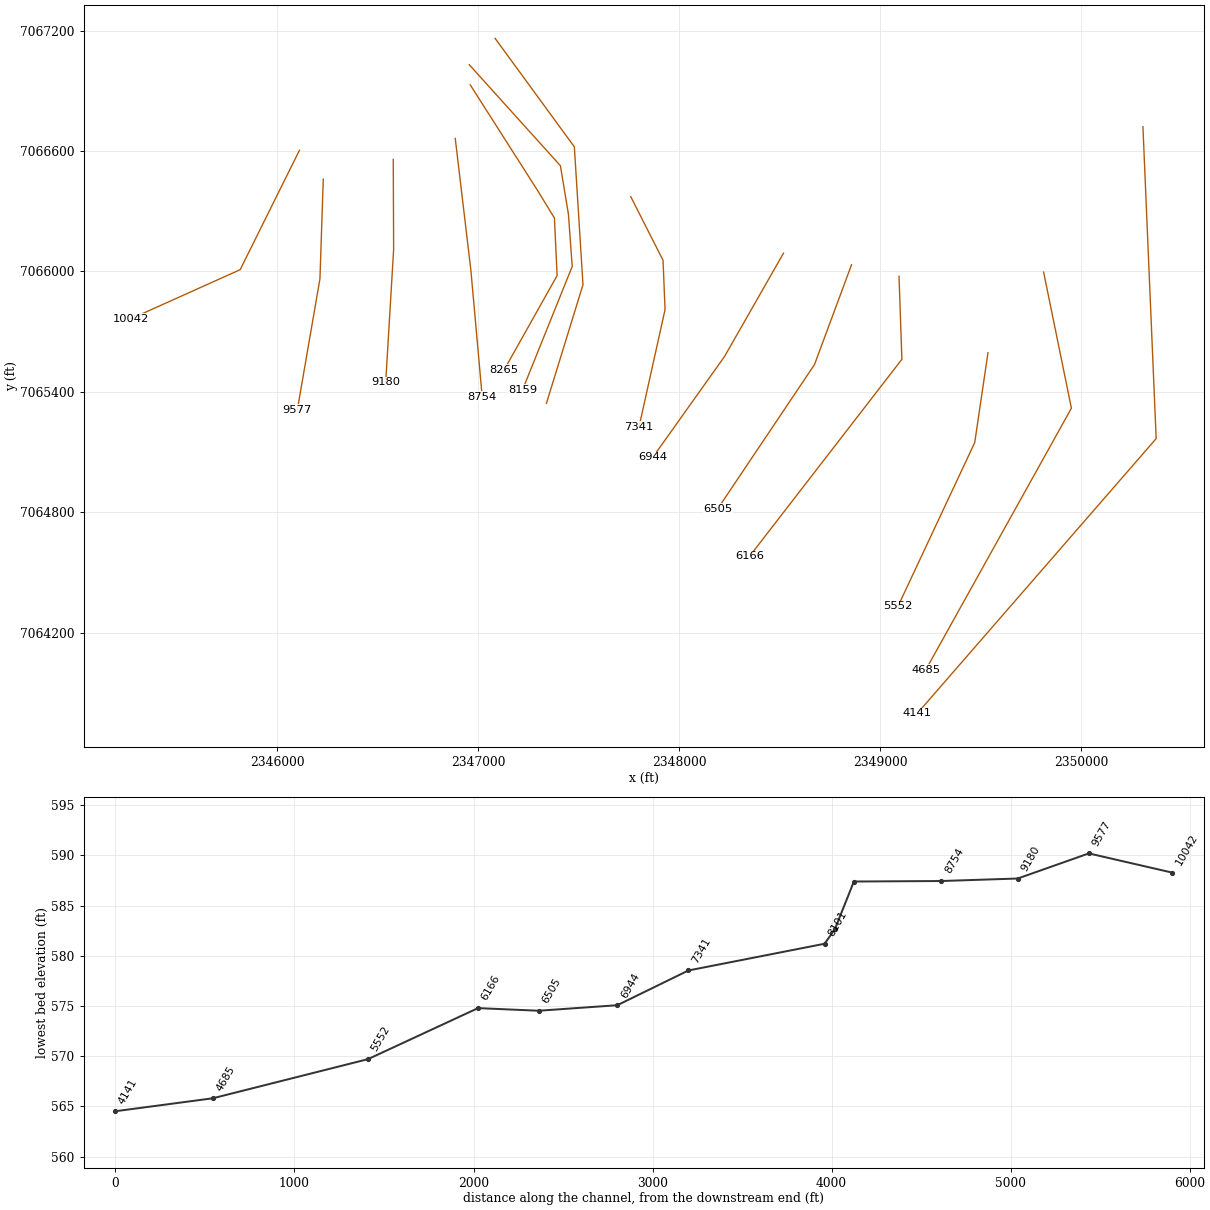
HEC-RAS study Catherine Branch.prj: Catherine Branch Base Level Engineering

--- Catherine Branch.g01 (geometry) --- (continued)

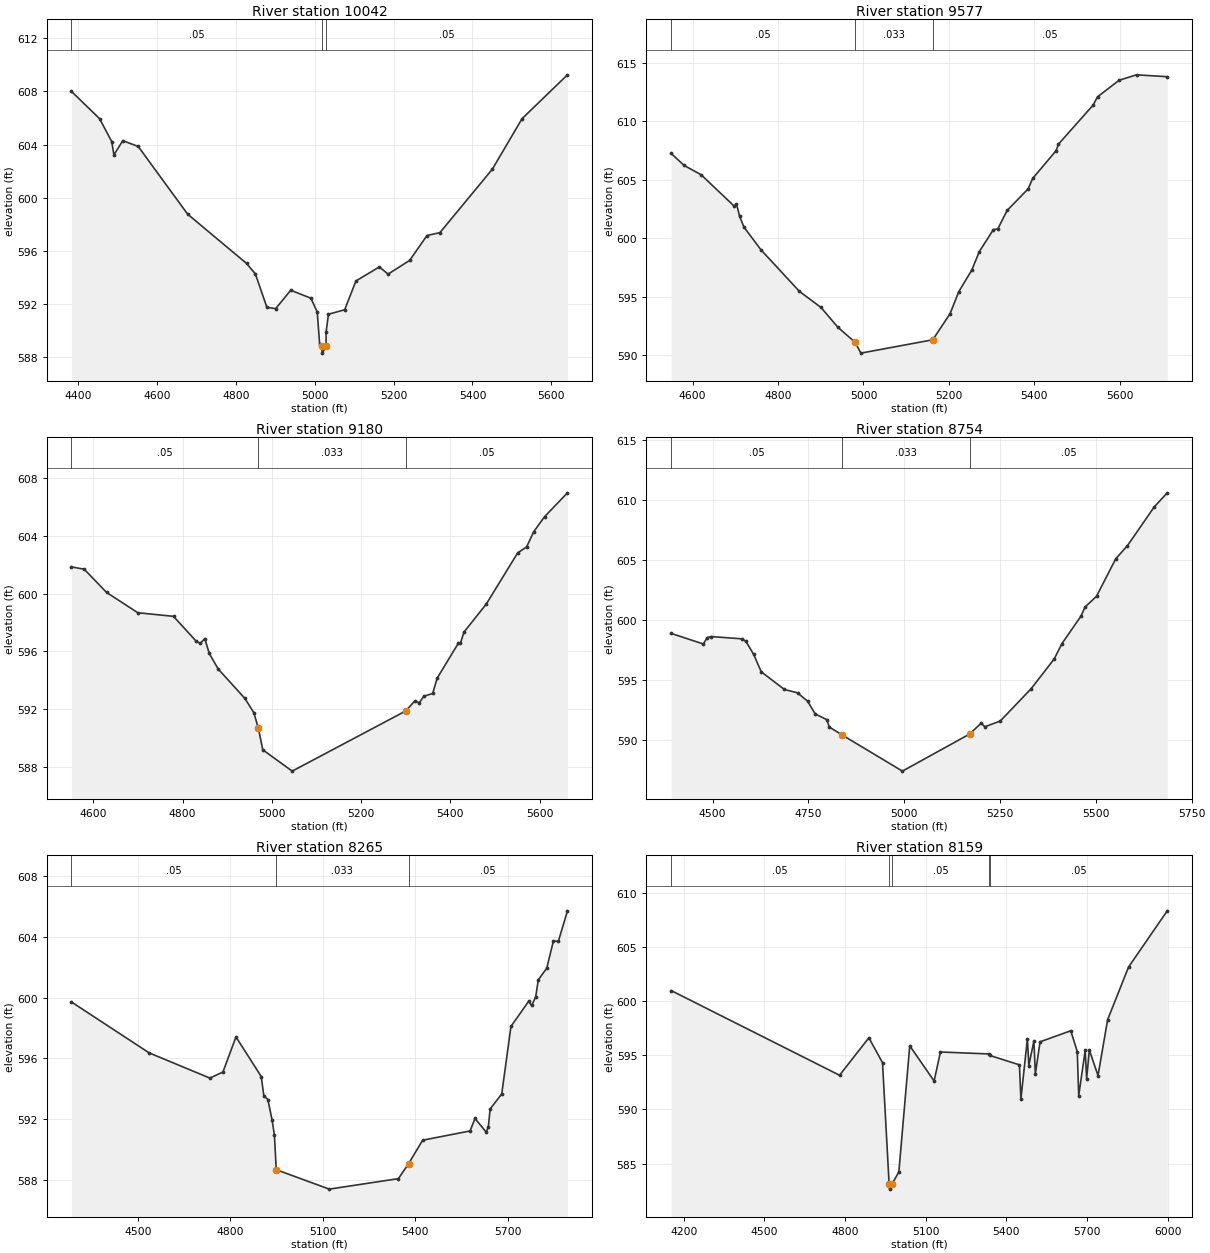
Type RM Length L Ch R = 1,10042,465,465,465
BEGIN DESCRIPTION:
Catherine Branch 14.0
END DESCRIPTION:
XS GIS Cut Line= 3
      2346110.56      7066604.09      2345815.67      7066008.94
      2345274.09      7065764.96
#Sta/Elev= 30
  4382.8  608.00  4454.3  605.94  4484.9  604.22  4490.5  603.22  4513.0  604.29
  4552.2  603.85  4677.5  598.75  4826.9  595.04  4849.3  594.25  4878.4  591.74
  4900.7  591.63  4939.0  593.02  4990.0  592.42  5006.2  591.39  5012.3  588.99
  5017.5  588.78  5019.0  588.28  5028.6  588.78  5028.7  589.86  5034.7  591.21
  5075.9  591.55  5104.5  593.72  5164.0  594.78  5185.9  594.23  5240.8  595.27
  5284.6  597.14  5317.5  597.36  5450.4  602.14  5525.9  605.95  5641.0  609.25
#Mann=3,-1,0
  4382.8    0.05       0  5017.5   0.033       0  5028.6    0.05       0
Bank Sta=5017.5,5028.6
Exp/Cntr=0.3,0.1

Type RM Length L Ch R = 1,9577,397,397,397
BEGIN DESCRIPTION:
Catherine Branch 13.0
END DESCRIPTION:
XS GIS Cut Line= 3
      2346229.00      7066459.97      2346212.46      7065963.36
      2346099.86      7065309.17
#Sta/Elev= 30
  4550.2  607.25  4580.2  606.23  4620.2  605.43  4697.8  602.74  4702.8  602.94
  4710.3  601.87  4720.3  600.96  4760.3  599.01  4850.3  595.46  4900.4  594.10
  4940.4  592.39  4980.4  591.12  4994.0  590.19  5162.1  591.33  5202.7  593.56
  5223.0  595.44  5253.4  597.28  5271.2  598.87  5304.2  600.75  5314.3  600.80
  5336.2  602.38  5385.4  604.23  5396.1  605.12  5451.0  607.50  5456.4  608.05
  5537.6  611.39  5547.7  612.09  5598.4  613.51  5639.0  613.97  5710.9  613.81
#Mann=3,-1,0
  4550.2    0.05       0  4980.4   0.033       0  5162.1    0.05       0
Bank Sta=4980.4,5162.1
Exp/Cntr=0.3,0.1

Type RM Length L Ch R = 1,9180,426,426,426
BEGIN DESCRIPTION:
Catherine Branch 12.0
END DESCRIPTION:
XS GIS Cut Line= 3
      2346577.09      7066558.57      2346579.00      7066110.00
      2346539.56      7065448.64
#Sta/Elev= 30
  4551.1  601.86  4579.7  601.70  4629.7  600.09  4699.7  598.68  4779.7  598.43
  4829.7  596.73  4839.7  596.55  4849.7  596.89  4859.7  595.86  4879.7  594.78
  4939.7  592.73  4959.7  591.74  4969.7  590.67  4979.7  589.17  5045.6  587.69
  5300.2  591.87  5320.2  592.56  5330.3  592.43  5340.3  592.88  5360.3  593.08
  5370.3  594.14  5417.5  596.55  5422.5  596.56  5430.4  597.34  5480.5  599.29
  5550.6  602.83  5570.7  603.25  5586.6  604.30  5610.8  605.34  5662.2  607.00
#Mann=3,-1,0
  4551.1    0.05       0  4969.7   0.033       0  5300.2    0.05       0
Bank Sta=4969.7,5300.2
Exp/Cntr=0.3,0.1

Type RM Length L Ch R = 1,8754,489,489,489
BEGIN DESCRIPTION:
Catherine Branch 11.0
END DESCRIPTION:
XS GIS Cut Line= 3
      2346885.41      7066663.15      2346963.16      7066006.26
      2347019.46      7065376.24
#Sta/Elev= 30
  4392.3  598.89  4476.0  598.01  4486.1  598.54  4496.2  598.63  4576.7  598.44
  4586.8  598.24  4606.9  597.17  4627.1  595.70  4687.5  594.23  4721.7  593.95
  4747.9  593.26  4768.1  592.19  4798.3  591.72  4804.5  591.11  4838.5  590.44
  4995.4  587.44  5170.5  590.52  5200.6  591.42  5210.7  591.13  5250.8  591.61
  5331.1  594.29  5391.4  596.77  5411.5  598.04  5461.7  600.35  5471.7  601.08
  5501.8  601.98  5552.0  605.10  5582.1  606.17  5652.4  609.41  5686.3  610.58
#Mann=3,-1,0
  4392.3    0.05       0  4838.5   0.033       0  5170.5    0.05       0
Bank Sta=4838.5,5170.5
Exp/Cntr=0.3,0.1

Type RM Length L Ch R = 1,8265,106,106,106
BEGIN DESCRIPTION:
Catherine Branch 10.0
END DESCRIPTION:
XS GIS Cut Line= 5
      2346960.09      7066929.75      2347295.26      7066403.11
      2347378.73      7066266.32      2347392.13      7065979.45
      2347129.02      7065510.04
#Sta/Elev= 30
  4283.9  599.71  4535.9  596.36  4733.1  594.70  4775.5  595.10  4817.8  597.41
  4899.9  594.80  4908.1  593.55  4921.3  593.29  4935.2  591.92  4942.6  590.94
  4948.5  588.67  5120.5  587.39  5345.0  588.08  5377.9  589.06  5423.7  590.61
  5577.6  591.22  5593.6  592.04  5630.1  591.14  5636.9  591.49  5642.7  592.67
  5680.3  593.65  5710.3  598.10  5767.6  599.75  5777.3  599.48  5790.6  600.04
  5799.0  601.17  5826.4  601.93  5848.1  603.73  5864.1  603.70  5893.7  605.71
#Mann=3,-1,0
  4283.9    0.05       0  4948.5   0.033       0  5377.9    0.05       0
Bank Sta=4948.5,5377.9
Exp/Cntr=0.3,0.1

Type RM Length L Ch R = 1,8159,58,58,58
BEGIN DESCRIPTION:
Catherine Branch 9.5
END DESCRIPTION:
XS GIS Cut Line= 5
      2346955.25      7067030.38      2347408.38      7066527.10
      2347448.43      7066285.09      2347467.20      7066025.02
      2347220.55      7065411.08
#Sta/Elev= 30
  4153.9  600.98  4779.9  593.16  4889.0  596.62  4939.7  594.32  4964.2  583.14
  4965.8  582.64  4975.9  583.14  5000.5  584.23  5041.0  595.88  5131.6  592.63
  5155.2  595.31  5334.2  595.13  5338.8  594.99  5449.0  594.12  5454.4  590.94
  5478.6  596.54  5484.0  594.06  5502.8  596.33  5508.2  593.29  5525.8  596.25
  5639.9  597.27  5664.1  595.35  5669.5  591.28  5693.6  595.45  5699.0  592.85
  5709.0  595.49  5741.3  593.13  5777.0  598.29  5854.9  603.16  5998.8  608.35
#Mann=5,-1,0
  4153.9    0.05       0  4964.2   0.033       0  4975.9    0.05       0
  5334.2    0.12       0  5338.8    0.05       0
Bank Sta=4964.2,4975.9
Exp/Cntr=0.3,0.1

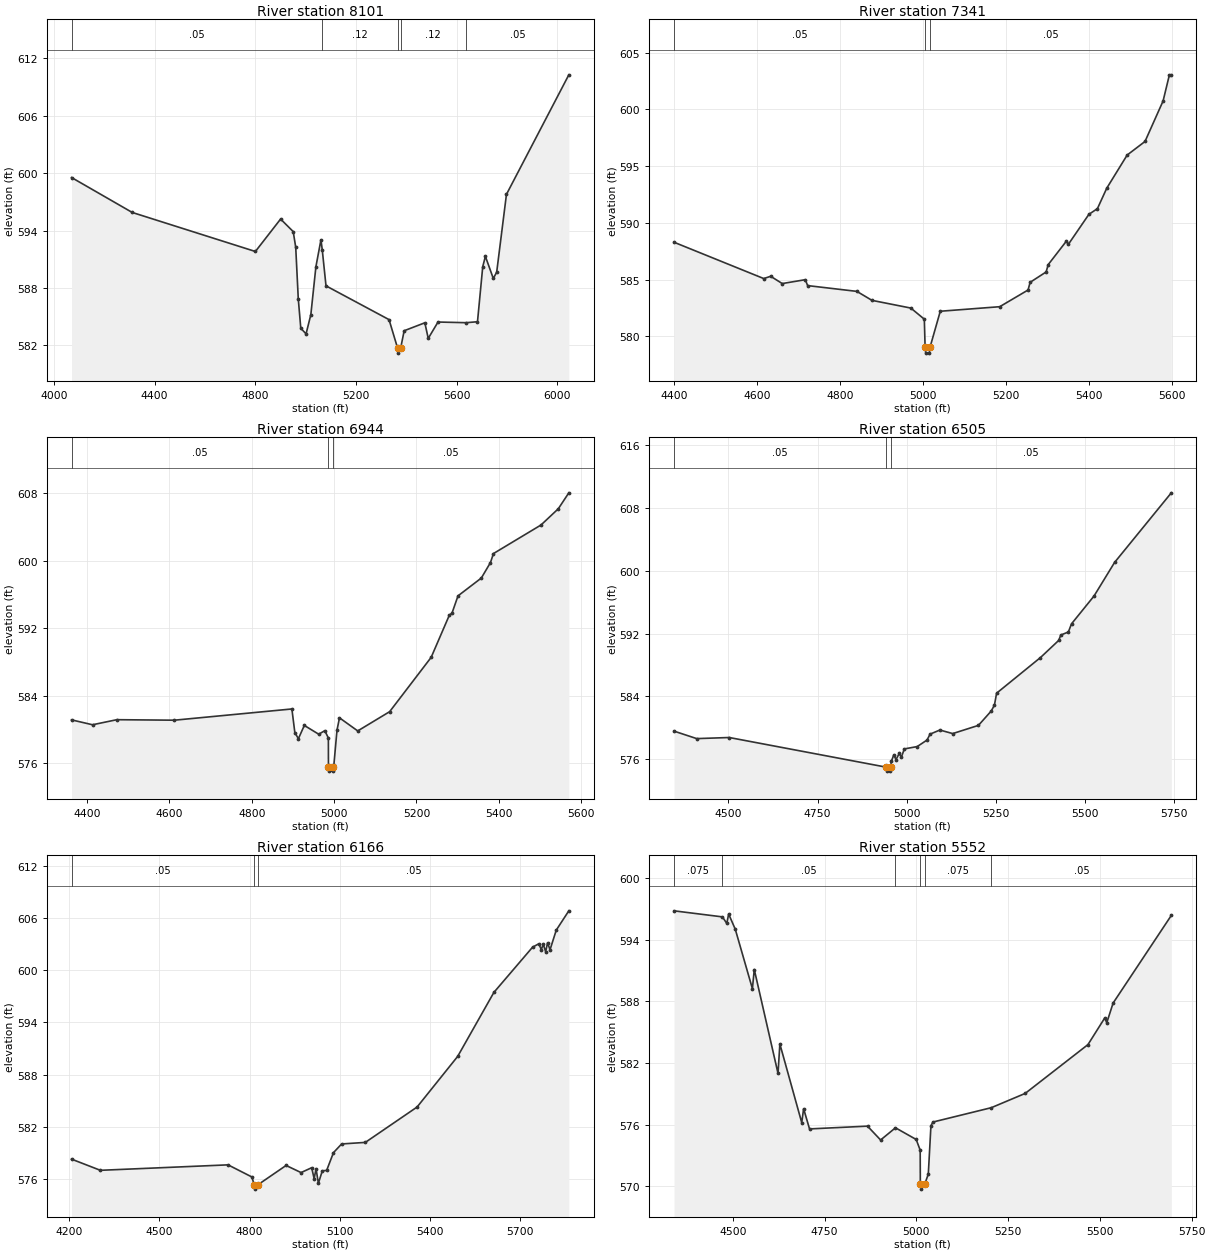
Type RM Length L Ch R = 1,8101,760,760,760
BEGIN DESCRIPTION:
Catherine Branch 9.0
END DESCRIPTION:
XS GIS Cut Line= 4
      2347083.51      7067161.89      2347477.87      7066621.04
      2347520.82      7065933.87      2347339.07      7065343.17
#Sta/Elev= 30
  4069.6  599.54  4310.7  595.89  4800.1  591.81  4900.3  595.20  4950.4  593.89
  4960.4  592.25  4970.5  586.88  4980.5  583.79  5001.5  583.20  5020.5  585.22
  5040.6  590.22  5060.6  593.03  5065.8  591.99  5080.7  588.22  5331.2  584.69
  5365.4  581.69  5367.0  581.19  5377.1  581.69  5391.3  583.53  5473.4  584.36
  5486.9  582.73  5525.7  584.44  5637.1  584.37  5682.6  584.47  5703.5  590.23
  5714.0  591.30  5745.4  588.99  5758.9  589.65  5797.7  597.78  6045.5  610.27
#Mann=5,-1,0
  4069.6    0.05       0  5065.8    0.12       0  5365.4   0.033       0
  5377.1    0.12       0  5637.1    0.05       0
Bank Sta=5365.4,5377.1
Exp/Cntr=0.3,0.1

Type RM Length L Ch R = 1,7341,397,397,397
BEGIN DESCRIPTION:
Catherine Branch 8.0
END DESCRIPTION:
XS GIS Cut Line= 4
      2347758.53      7066372.58      2347918.95      7066055.76
      2347929.00      7065810.00      2347799.65      7065226.04
#Sta/Elev= 30
  4398.9  588.30  4615.3  585.10  4632.0  585.30  4659.9  584.66  4715.5  585.00
  4721.1  584.48  4839.9  583.97  4876.2  583.18  4970.0  582.50  5002.5  581.52
  5004.4  579.03  5006.0  578.53  5014.5  578.53  5016.1  579.03  5041.0  582.22
  5184.3  582.62  5252.6  584.09  5257.7  584.77  5296.2  585.68  5301.3  586.33
  5344.9  588.39  5350.1  588.13  5399.4  590.76  5419.9  591.26  5442.4  593.06
  5491.6  595.98  5534.7  597.18  5578.3  600.75  5593.5  603.05  5598.1  603.05
#Mann=3,-1,0
  4398.9    0.05       0  5004.4   0.033       0  5016.1    0.05       0
Bank Sta=5004.4,5016.1
Exp/Cntr=0.3,0.1

Type RM Length L Ch R = 1,6944,439,439,439
BEGIN DESCRIPTION:
Catherine Branch 7.0
END DESCRIPTION:
XS GIS Cut Line= 3
      2348518.18      7066091.16      2348224.34      7065575.40
      2347868.70      7065074.87
#Sta/Elev= 30
  4362.4  581.14  4413.4  580.56  4472.5  581.16  4612.2  581.10  4897.5  582.43
  4904.7  579.63  4913.3  578.91  4927.7  580.48  4962.7  579.44  4977.4  579.86
  4986.1  578.99  4986.3  575.57  4987.9  575.07  4996.4  575.07  4998.1  575.57
  4999.4  575.76  5007.0  579.91  5013.1  581.38  5057.4  579.83  5134.9  582.11
  5235.7  588.54  5280.0  593.55  5286.2  593.76  5300.9  595.82  5357.5  597.93
  5379.7  599.76  5387.0  600.83  5502.4  604.21  5544.4  606.13  5570.0  608.02
#Mann=3,-1,0
  4362.4    0.05       0  4986.3    0.04       0  4998.1    0.05       0
Bank Sta=4986.3,4998.1
Exp/Cntr=0.3,0.1

Type RM Length L Ch R = 1,6505,339,339,339
BEGIN DESCRIPTION:
Catherine Branch 6.0
END DESCRIPTION:
XS GIS Cut Line= 3
      2348856.60      7066033.43      2348672.28      7065535.87
      2348191.39      7064817.83
#Sta/Elev= 30
  4347.5  579.60  4411.2  578.65  4502.4  578.79  4943.2  575.02  4944.9  574.52
  4953.4  574.52  4955.0  575.02  4957.4  575.81  4964.1  576.60  4970.1  575.98
  4979.1  576.76  4985.2  576.30  4993.5  577.34  5029.6  577.64  5057.2  578.47
  5065.7  579.22  5093.2  579.74  5129.2  579.29  5201.3  580.33  5237.3  582.16
  5246.2  582.91  5252.3  584.42  5375.4  588.95  5426.4  591.12  5432.4  591.81
  5453.5  592.19  5462.4  593.23  5525.5  596.76  5583.2  601.03  5742.3  609.87
#Mann=3,-1,0
  4347.5    0.05       0  4943.2   0.033       0  4955.0    0.05       0
Bank Sta=4943.2,4955
Exp/Cntr=0.3,0.1

Type RM Length L Ch R = 1,6166,614,614,614
BEGIN DESCRIPTION:
Catherine Branch 5.0
END DESCRIPTION:
XS GIS Cut Line= 3
      2349092.72      7065975.80      2349107.05      7065562.22
      2348349.49      7064580.70
#Sta/Elev= 30
  4208.1  578.24  4304.0  576.95  4728.6  577.58  4807.4  576.19  4816.0  575.28
  4817.7  574.78  4827.8  575.28  4921.6  577.51  4971.4  576.69  5006.7  577.25
  5014.9  575.99  5021.2  577.14  5029.0  575.45  5042.0  576.89  5056.5  576.94
  5079.2  578.99  5106.3  579.99  5185.1  580.17  5357.2  584.25  5492.2  590.09
  5612.6  597.47  5741.3  602.69  5762.1  603.08  5770.3  602.40  5776.6  603.03
  5784.8  602.17  5791.1  603.20  5799.3  602.39  5820.1  604.66  5861.8  606.88
#Mann=3,-1,0
  4208.1    0.05       0  4816.0   0.033       0  4827.8    0.05       0
Bank Sta=4816,4827.8
Exp/Cntr=0.3,0.1

Type RM Length L Ch R = 1,5552,867,867,867
BEGIN DESCRIPTION:
Catherine Branch 4.0
END DESCRIPTION:
XS GIS Cut Line= 3
      2349535.22      7065595.17      2349469.35      7065147.22
      2349087.30      7064330.42
#Sta/Elev= 30
  4340.1  596.83  4471.9  596.24  4483.9  595.60  4488.9  596.52  4507.0  595.03
  4553.6  589.24  4558.7  591.11  4623.4  580.98  4628.4  583.85  4688.0  576.18
  4693.1  577.54  4709.2  575.57  4867.1  575.84  4902.8  574.49  4943.3  575.68
  4999.7  574.54  5010.6  573.50  5011.0  570.20  5012.7  569.70  5023.1  570.20
  5032.7  571.16  5039.9  575.88  5045.4  576.24  5204.4  577.64  5296.6  579.03
  5467.6  583.79  5513.2  586.38  5518.8  585.92  5536.1  587.84  5694.6  596.38
#Mann=6,-1,0
  4340.1   0.075       0  4471.9    0.05       0  4943.3   0.075       0
  5011.0    0.07       0  5023.1   0.075       0  5204.4    0.05       0
Bank Sta=5011,5023.1
Exp/Cntr=0.3,0.1

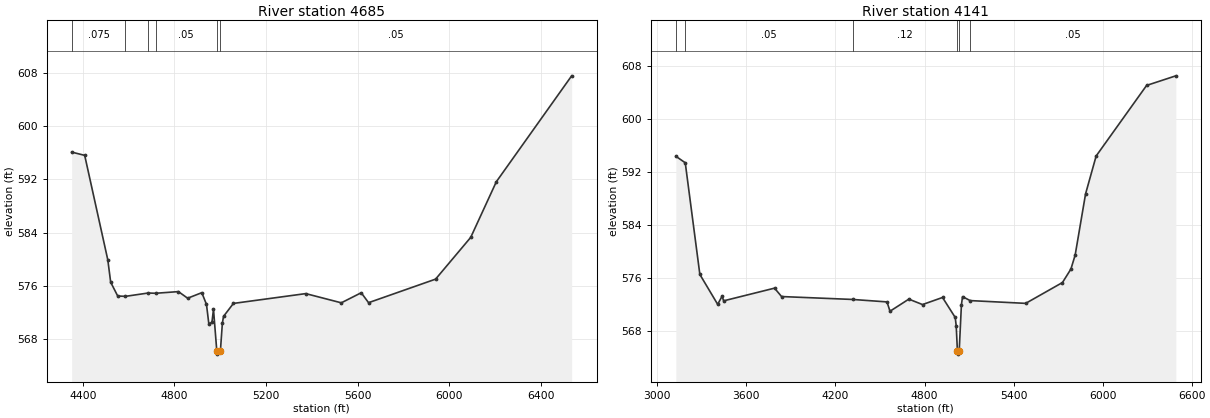
Type RM Length L Ch R = 1,4685,544,544,544
BEGIN DESCRIPTION:
Catherine Branch 3.0
END DESCRIPTION:
XS GIS Cut Line= 3
      2349811.89      7065997.01      2349950.23      7065318.49
      2349225.83      7064014.58
#Sta/Elev= 30
  4350.9  596.08  4407.8  595.59  4508.8  579.92  4521.3  576.58  4552.0  574.51
  4585.9  574.46  4685.3  574.96  4717.6  574.92  4817.3  575.17  4857.5  574.18
  4919.4  575.01  4939.8  573.25  4950.0  570.36  4963.7  570.56  4970.4  572.53
  4984.8  566.30  4986.5  565.80  4996.9  566.30  5001.0  566.46  5009.2  570.44
  5014.3  571.46  5057.5  573.40  5373.4  574.87  5528.8  573.49  5615.8  575.00
  5647.8  573.51  5940.6  577.04  6094.1  583.30  6206.0  591.64  6535.0  607.51
#Mann=6,-1,0
  4350.9   0.075       0  4585.9    0.05       0  4685.3    0.12       0
  4717.6    0.05       0  4984.8   0.033       0  4996.9    0.05       0
Bank Sta=4984.8,4996.9
Exp/Cntr=0.3,0.1

Type RM Length L Ch R = 1,4141,0,0,0
BEGIN DESCRIPTION:
Catherine Branch 2.0
END DESCRIPTION:
XS GIS Cut Line= 3
      2350305.94      7066721.63      2350371.82      7065166.98
      2349183.80      7063797.52
#Sta/Elev= 30
  3124.5  594.41  3187.9  593.42  3286.3  576.55  3406.4  572.03  3436.4  573.28
  3446.4  572.56  3789.5  574.48  3836.8  573.21  4315.9  572.77  4547.4  572.40
  4567.4  570.99  4694.4  572.82  4786.6  572.00  4921.4  573.07  5006.9  570.05
  5013.5  568.82  5021.7  565.01  5023.4  564.51  5033.8  565.01  5048.7  571.96
  5056.3  573.20  5107.2  572.60  5481.7  572.18  5729.6  575.33  5786.6  577.37
  5815.1  579.48  5885.3  588.73  5956.6  594.45  6296.5  605.11  6493.5  606.56
#Mann=6,-1,0
  3124.5   0.075       0  3187.9    0.05       0  4315.9    0.12       0
  5021.7    0.07       0  5033.8    0.12       0  5107.2    0.05       0
Bank Sta=5021.7,5033.8
Exp/Cntr=0.3,0.1

Chan Stop Cuts=-1