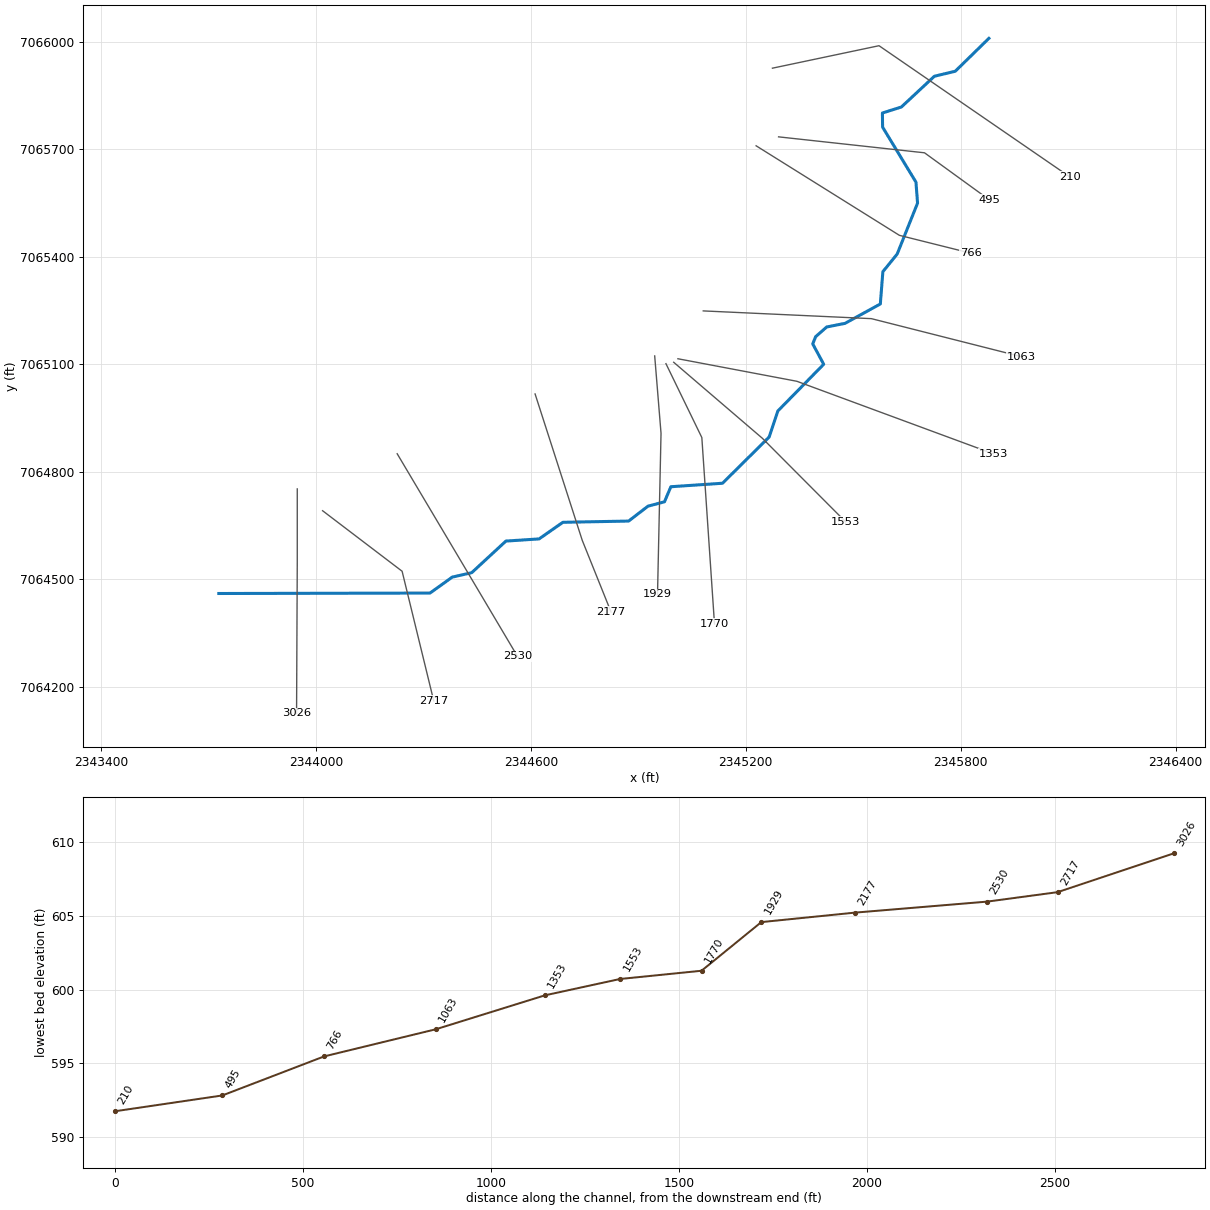
--- Catherine Branch Tr 2.prj (project) ---

Proj Title=Catherine Branch Tr 2 Base Level Engineering
Current Plan=p01
Default Exp/Contr=0.3,0.1
English Units
Geom File=g01
Flow File=f01
Plan File=p01
Y Axis Title=Elevation
X Axis Title(PF)=Main Channel Distance
X Axis Title(XS)=Station
BEGIN DESCRIPTION:
Catherine Branch Tr 2
END DESCRIPTION:
DSS Export Rating Curves= 0
DSS Export Rating Curve Sorted= 0
DSS Export Volume Flow Curves= 0
DXF OffsetX= 0
DXF OffsetY= 0
DXF ScaleX= 1
DXF ScaleY= 10

--- Catherine Branch Tr 2.p01 (plan) ---

Plan Title=Multiple Run
Program Version=4.10
Short Identifier=Multiple
Geom File=g01
Flow File=f01
Subcritical Flow
K Sum by GR= 0
Std Step Tol= 0.01
Critical Tol= 0.01
Num of Std Step Trials= 20
Max Error Tol= 0.3
Flow Tol Ratio= 0.001
Split Flow NTrial= 30
Split Flow Tol= 0.02
Split Flow Ratio= 0.02
Log Output Level= 0
Friction Slope Method= 1
Unsteady Friction Slope Method= 2
Unsteady Bridges Friction Slope Method= 1
Parabolic Critical Depth
Global Vel Dist= 1 , 1 , 1
Global Log Level= 0
CheckData=True
Encroach Param=-1 ,0,0, 0
BEGIN DESCRIPTION:
Multiple Run
END DESCRIPTION:
Computation Interval=1HOUR
Output Interval=1HOUR
Run HTab= 0
Run UNet= 0
Run PostProcess= 0
Run WQNet= 0
UNET Theta= 1
UNET Theta Warmup= 1
UNET ZTol= 0.02
UNET ZSATol= 0.05
UNET MxIter= 20
UNET MaxInSteps= 0
UNET DtIC= 0
UNET DtMin= 0
UNET MaxCRTS= 20
UNET WFStab= 2
UNET SFStab= 1
UNET WFX= 1
UNET SFX= 1
UNET DSS MLevel= 4
UNET DZMax Abort= 100
UNET Convert EG Bridges= 0
UNET Use Existing IB Tables=-1
UNET Froude Reduction=False
UNET Froude Limit= 1
UNET Froude Power= 10
UNET Time Slicing=0,0, 5
UNET Junction Losses=0
Instantaneous Interval=1HOUR
Write IC File= 0
Write IC File at Sim End=0
Echo Input=False
Echo Parameters=False
Echo Output=False
Write Detailed= 0
WQ AD Non Conservative
WQ ULTIMATE=-1
WQ Max Comp Step=1HOUR
WQ Output Interval=15MIN
WQ Output Selected Increments= 0
WQ Output face flow=0
WQ Output face velocity=0
WQ Output face area=0
WQ Output face dispersion=0
WQ Output cell volume=0
WQ Output cell surface area=0
WQ Output cell continuity=0
WQ Output cumulative cell continuity=0
WQ Output face conc=0
WQ Output face dconc_dx=0
WQ Output face courant=0
WQ Output face peclet=0
WQ Output face adv mass=0
WQ Output face disp mass=0
WQ Output cell mass=0
WQ Output cell source sink temp=0
WQ Output cell source sink nsm=0
WQ Output MaxMinRange=-1
WQ Daily Max Min Mean=-1
WQ Daily Range=0
WQ Daily Time=0
WQ Create Restart=0
WQ Fixed Restart=0
WQ System Summary=0
WQ Use Fixed Temperature=0
Sorting and Armoring Iterations= 10
XS Update Threshold= 0.02
Hydraulics Update Threshold= 0.02
Energy Slope Method= 1
Volume Change Method= 0
XS Weighting Method= 0
Number of US Weighted Cross Sections= 1
Number of DS Weighted Cross Sections= 1
Upstream XS Weight=0.25
Main XS Weight=0.5
Downstream XS Weight=0.25
Number of DS XS's Weighted with US Boundary= 1
Upstream Boundary Weight= 1
Weight of XSs Associated with US Boundary= 0
Number of US XS's Weighted with DS Boundary= 1
Downstream Boundary Weight= 0.5
Weight of XSs Associated with DS Boundary= 0.5
Sediment Output Level= 4
Mass or Volume Output= 0
Output Increment Type= 1
Profile and TS Output Increment= 10
XS Output Flag= 0
XS Output Increment= 10
Disregard all LS=0
Disregard all Conn=0
Disregard all Breaches=0
Disregard all Pumps=0

--- Catherine Branch Tr 2.f01 (steady flow) ---

Flow Title=Multiple
Number of Profiles=7
Profile Names=10-year,25-year,50-year,1pct_min,100-year,1pct_plu,500-year
River Rch & RM= Catherine Branch,Reach-1,3026
     372     492     588     349     696    1388     977
Boundary for River Rch & Prof#=Catherine Branch,Reach-1,1
Up Type=0
Dn Type=3
Dn Slope=0.005
Boundary for River Rch & Prof#=Catherine Branch,Reach-1,2
Up Type=0
Dn Type=3
Dn Slope=0.005
Boundary for River Rch & Prof#=Catherine Branch,Reach-1,3
Up Type=0
Dn Type=3
Dn Slope=0.005
Boundary for River Rch & Prof#=Catherine Branch,Reach-1,4
Up Type=0
Dn Type=3
Dn Slope=0.005
Boundary for River Rch & Prof#=Catherine Branch,Reach-1,5
Up Type=0
Dn Type=3
Dn Slope=0.005
Boundary for River Rch & Prof#=Catherine Branch,Reach-1,6
Up Type=0
Dn Type=3
Dn Slope=0.005
Boundary for River Rch & Prof#=Catherine Branch,Reach-1,7
Up Type=0
Dn Type=3
Dn Slope=0.005

--- Catherine Branch Tr 2.g01 (geometry) ---

Geom Title=Existing Conditions
Program Version=4.10

River Reach=Catherine Branch,Reach-1
Reach XY= 30
        2343729.        7064460.       2344318.5       7064461.2
      2344380.75      7064505.78      2344435.05      7064518.16
       2344530.5      7064606.38      2344623.02      7064612.36
       2344689.5      7064658.78       2344873.1      7064662.23
      2344927.14      7064703.78      2344973.21      7064716.03
      2344990.95      7064758.07      2345135.19      7064767.82
      2345265.37      7064896.79      2345289.78      7064969.68
      2345417.75      7065100.01      2345387.08      7065156.85
      2345395.24      7065177.04      2345426.16      7065204.17
      2345477.23      7065214.18      2345575.85      7065268.32
      2345582.86      7065358.34      2345622.89      7065407.81
      2345679.78      7065549.95      2345675.33      7065608.42
      2345582.16       7065762.1      2345581.63      7065801.52
      2345634.64       7065818.3      2345726.71      7065904.14
      2345785.07      7065918.11        2345879.        7066010.

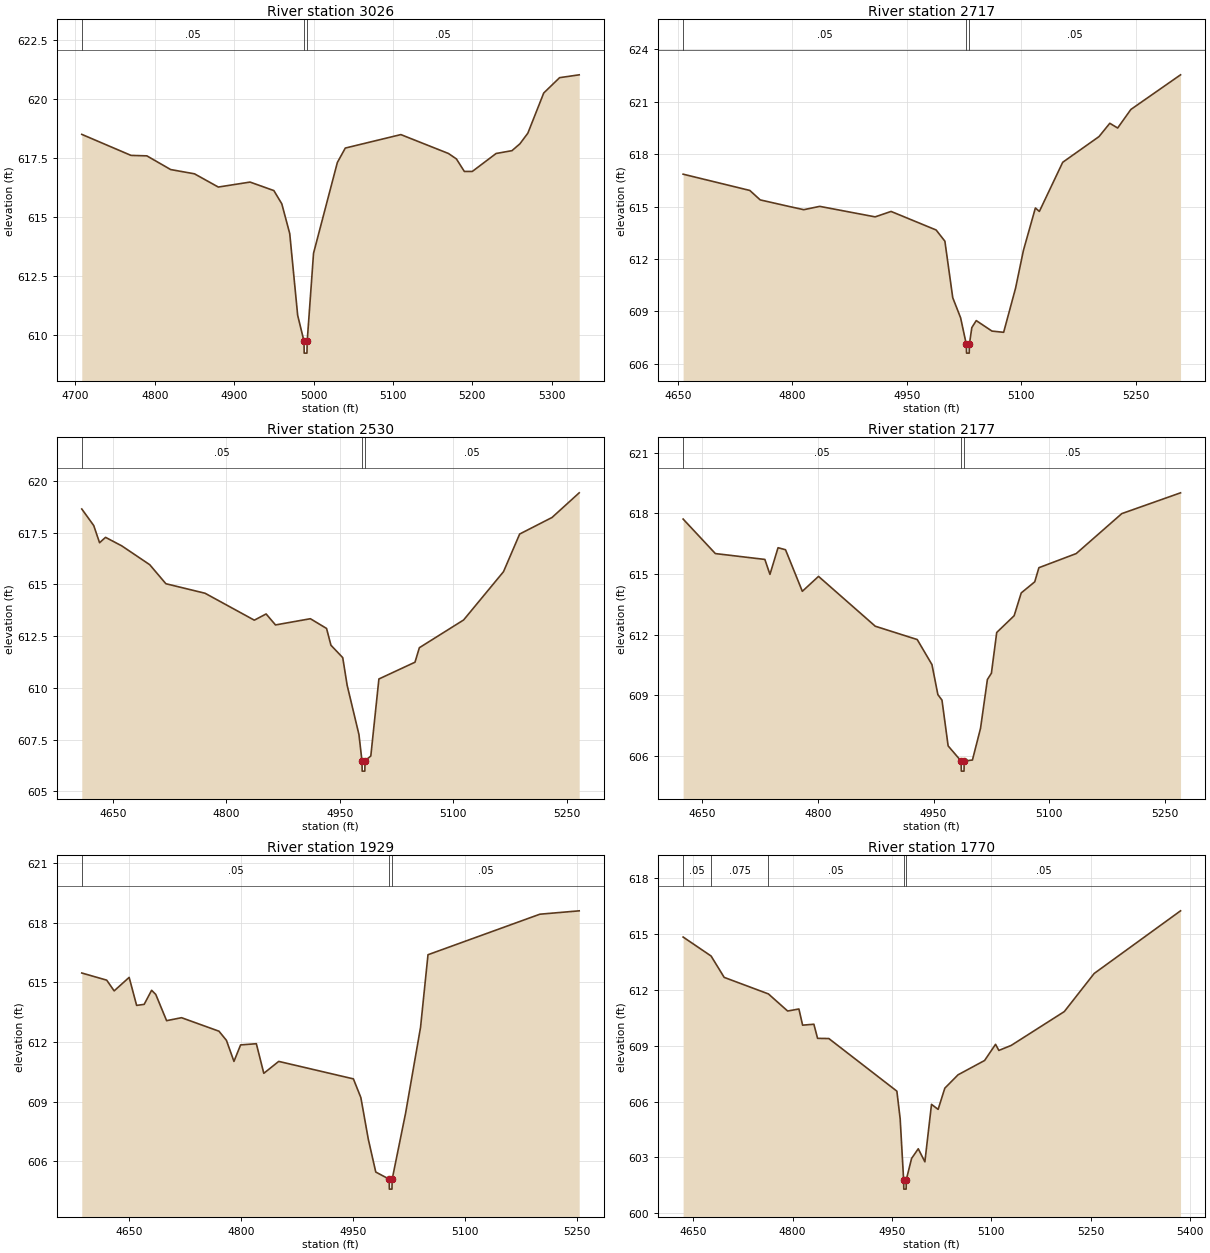
Type RM Length L Ch R = 1 ,3026    ,309,309,309
BEGIN DESCRIPTION:
Catherine Branch Tr 2 9.0
END DESCRIPTION:
XS GIS Cut Line= 3
      2343947.93      7064751.99      2343947.93      7064547.68
      2343945.97       7064125.3
#Sta/Elev= 30
    4708  618.51    4770  617.62    4790   617.6    4820  617.02    4850  616.84
    4880  616.28    4920  616.49    4950  616.13    4960  615.57    4970  614.31
    4980  610.85    4988  609.75  4988.2  609.25  4991.7  609.25    4992  609.75
    5000  613.48    5030  617.32    5040  617.93    5110   618.5    5170   617.7
    5180  617.47    5190  616.94    5200  616.94    5230   617.7    5250  617.82
    5260  618.11    5270  618.56    5290  620.26    5310  620.91  5334.7  621.03
#Mann= 3 ,-1 , 0
    4708     .05       0    4988     .05       0    4992     .05       0
Bank Sta=4988,4992
XS Rating Curve= 0 ,0
Exp/Cntr=0.3,0.1

Type RM Length L Ch R = 1 ,2717    ,187,187,187
BEGIN DESCRIPTION:
Catherine Branch Tr 2 8.0
END DESCRIPTION:
XS GIS Cut Line= 3
      2344018.62      7064691.11      2344240.63      7064522.14
      2344329.01      7064159.97
#Sta/Elev= 30
  4656.8  616.85  4744.2  615.92  4757.8  615.38  4794.1  615.02  4814.9  614.82
  4835.8  615.01  4908.4  614.41  4929.3  614.72  4988.3  613.66  4999.8  613.02
  5010.1  609.79  5020.4  608.64  5027.9  607.12  5028.2  606.62  5031.7  606.62
  5031.9  607.12  5035.1  608.08  5040.9  608.48  5061.5  607.88  5076.8  607.81
  5092.4  610.33  5102.7  612.49  5118.4  614.92  5123.6  614.72  5154.2  617.53
  5201.8     619  5215.9  619.76  5226.2  619.49  5243.5  620.55  5308.6  622.53
#Mann= 3 ,-1 , 0
  4656.8     .05       0  5027.9     .05       0  5031.9     .05       0
Bank Sta=5027.9,5031.9
XS Rating Curve= 0 ,0
Exp/Cntr=0.3,0.1

Type RM Length L Ch R = 1 ,2530    ,353,353,353
BEGIN DESCRIPTION:
Catherine Branch Tr 2 7.0
END DESCRIPTION:
XS GIS Cut Line= 3
       2344226.9      7064850.17        2344429.        7064510.
      2344562.63      7064284.73
#Sta/Elev= 30
  4608.7  618.64  4624.5  617.84  4632.2  617.01  4640.1  617.27  4661.5  616.86
  4698.5  615.95  4719.9  615.03  4771.7  614.57  4836.8  613.27  4852.4  613.57
  4864.8  613.04  4910.9  613.34  4932.3  612.87  4938.1  612.06  4953.7  611.46
  4959.5  610.13  4975.1  607.75  4979.1  606.48  4979.4  605.98  4982.9  605.98
  4983.1  606.48  4990.8  606.71  5001.5  610.43  5049.2  611.24    5055  611.94
  5113.5  613.28  5166.2  615.61  5187.6  617.43  5230.4  618.23  5266.3  619.42
#Mann= 3 ,-1 , 0
  4608.7     .05       0  4979.1     .05       0  4983.1     .05       0
Bank Sta=4979.1,4983.1
XS Rating Curve= 0 ,0
Exp/Cntr=0.3,0.1

Type RM Length L Ch R = 1 ,2177    ,248,248,248
BEGIN DESCRIPTION:
Catherine Branch Tr 2 6.0
END DESCRIPTION:
XS GIS Cut Line= 3
      2344611.92      7065017.15      2344743.53      7064608.58
      2344824.03       7064408.3
#Sta/Elev= 30
  4625.2  617.72    4667  616.01  4731.2  615.72  4737.8  614.98  4748.3   616.3
    4758   616.2  4779.8  614.14  4800.8  614.88  4874.4  612.41  4928.8  611.75
  4947.9  610.51  4955.6  609.02  4960.9  608.75  4968.9  606.48  4985.7  605.73
    4986  605.23  4989.5  605.23  4989.7  605.73  5000.4  605.78  5010.9  607.35
  5019.8  609.77    5025  610.08  5031.9   612.1  5054.5  612.93  5063.7  614.06
  5081.2  614.61  5086.6  615.31    5135  616.01  5194.1  617.99  5270.3  619.02
#Mann= 3 ,-1 , 0
  4625.2     .05       0  4985.7     .05       0  4989.7     .05       0
Bank Sta=4985.7,4989.7
XS Rating Curve= 0 ,0
Exp/Cntr=0.3,0.1

Type RM Length L Ch R = 1 ,1929    ,159,159,159
BEGIN DESCRIPTION:
Catherine Branch Tr 2 5.2
END DESCRIPTION:
XS GIS Cut Line= 3
      2344945.86       7065123.3      2344963.54      7064907.17
      2344953.72      7064457.33
#Sta/Elev= 30
  4586.7  615.47  4620.1  615.11  4630.1  614.57  4650.2  615.25  4660.2  613.84
  4670.3  613.89  4680.3   614.6  4685.9  614.39  4700.4  613.07  4720.4  613.22
  4770.6  612.54  4780.6  612.08  4790.7  611.02  4799.6  611.85  4820.7  611.91
  4830.7  610.42  4850.7  611.02  4950.8  610.14  4960.8   609.2  4970.8   607.1
  4980.8  605.45  4998.8  605.09    4999  604.59  5002.5  604.59  5002.8  605.09
  5020.8  608.42  5040.8  612.73  5050.8  616.39  5200.8  618.43  5253.5   618.6
#Mann= 3 ,-1 , 0
  4586.7     .05       0  4998.8     .05       0  5002.8     .05       0
Bank Sta=4998.8,5002.8
XS Rating Curve= 0 ,0
Exp/Cntr=0.3,0.1

Type RM Length L Ch R = 1 ,1770    ,217,217,217
BEGIN DESCRIPTION:
Catherine Branch Tr 2 5.0
END DESCRIPTION:
XS GIS Cut Line= 3
       2344977.3      7065101.64      2345077.48      7064895.38
      2345112.83      7064374.88
#Sta/Elev= 30
  4634.6  614.85  4676.8  613.83  4696.6  612.68  4763.4  611.79  4792.4  610.87
  4809.4  610.98    4815  610.11    4832  610.16  4837.6   609.4  4854.6  609.39
  4957.3  606.56  4962.3  605.07  4967.5  601.79  4967.8  601.29  4971.3  601.29
  4971.5  601.79  4979.5  602.94  4989.6  603.46  4999.6  602.76  5009.6  605.85
  5019.6  605.58  5029.7  606.72  5049.7  607.44  5089.8  608.21  5106.3  609.08
  5111.3  608.75  5129.9  609.02  5210.1  610.84  5255.2  612.89  5385.6  616.26
#Mann= 5 ,-1 , 0
  4634.6     .05       0  4676.8    .075       0  4763.4     .05       0
  4967.5     .05       0  4971.5     .05       0
Bank Sta=4967.5,4971.5
XS Rating Curve= 0 ,0
Exp/Cntr=0.3,0.1

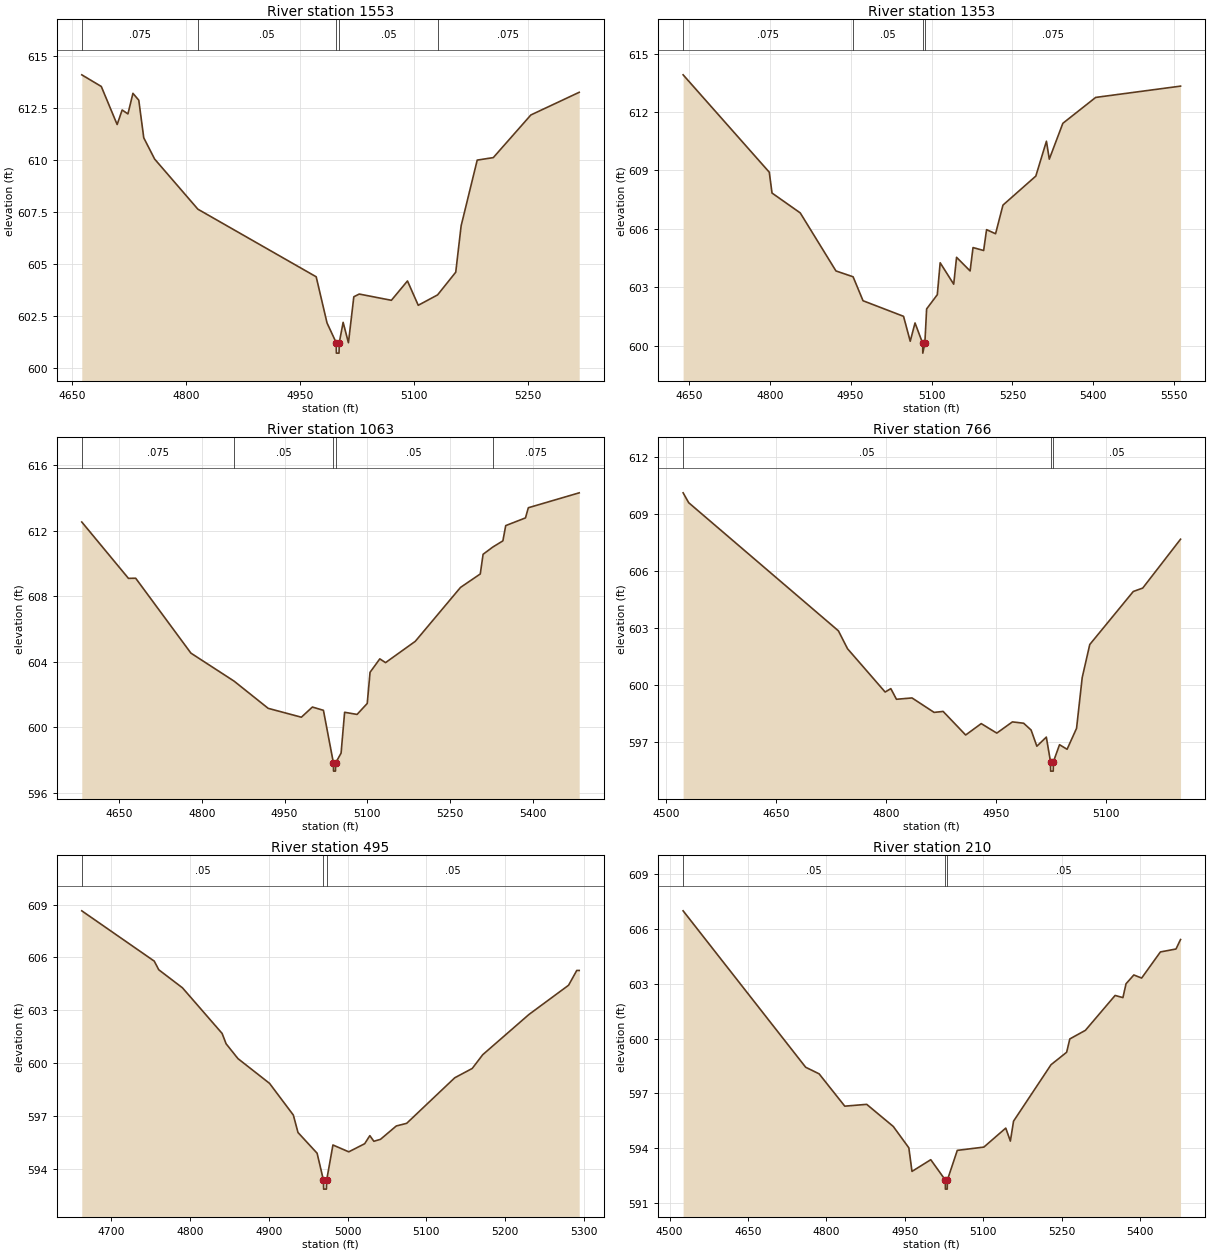
Type RM Length L Ch R = 1 ,1553    ,200,200,200
BEGIN DESCRIPTION:
Catherine Branch Tr 2 4.0
END DESCRIPTION:
XS GIS Cut Line= 3
      2344998.93      7065105.55      2345246.42      7064893.42
      2345479.02      7064659.98
#Sta/Elev= 30
  4662.4  614.11  4688.1  613.55    4709  611.72  4715.6  612.42  4723.2  612.23
  4729.8  613.22  4737.5  612.89  4744.1  611.08  4758.4  610.06  4815.4  607.65
  4971.3   604.4  4985.6  602.18  4997.7  601.23  4997.9  600.73  5001.4  600.73
  5001.7  601.23  5006.8  602.21  5013.8  601.23  5020.9  603.44    5028  603.57
  5070.4  603.27  5091.6   604.2  5105.8  603.03  5131.3  603.53  5155.2  604.62
  5162.3  606.85  5183.5  610.01  5204.7  610.13  5254.2  612.18  5317.9  613.27
#Mann= 5 ,-1 , 0
  4662.4    .075       0  4815.4     .05       0  4997.7     .05       0
  5001.7     .05       0  5131.3    .075       0
Bank Sta=4997.7,5001.7
XS Rating Curve= 0 ,0
Exp/Cntr=0.3,0.1

Type RM Length L Ch R = 1 ,1353    ,290,290,290
BEGIN DESCRIPTION:
Catherine Branch Tr 2 3.5
END DESCRIPTION:
XS GIS Cut Line= 3
      2345010.68       7065115.4      2345342.68      7065052.54
      2345890.72      7064850.21
#Sta/Elev= 30
  4639.5  613.91  4799.2  608.91  4804.3  607.84  4856.6  606.82  4922.8  603.84
  4954.6  603.54    4973  602.31  5048.1  601.51  5060.5  600.23  5069.4  601.17
  5083.6  600.12  5083.8  599.62  5087.6  600.12  5090.9  601.89  5110.7  602.62
    5116  604.26  5141.1  603.16  5146.4  604.54  5171.5  603.84  5176.9  605.04
  5196.6  604.89    5202  605.96  5218.7  605.75  5232.4  607.22  5293.3  608.71
    5313   610.5  5318.3  609.58  5343.4  611.42  5404.3  612.75  5561.6  613.33
#Mann= 4 ,-1 , 0
  4639.5    .075       0  4954.6     .05       0  5083.6     .05       0
  5087.6    .075       0
Bank Sta=5083.6,5087.6
XS Rating Curve= 0 ,0
Exp/Cntr=0.3,0.1

Type RM Length L Ch R = 1 ,1063    ,297,297,297
BEGIN DESCRIPTION:
Catherine Branch Tr 2 3.0
END DESCRIPTION:
XS GIS Cut Line= 3
      2345081.41      7065248.98       2345550.9      7065227.37
      2345969.28       7065121.3
#Sta/Elev= 30
  4582.4  612.52    4667  609.08  4680.1  609.09  4780.2  604.52  4858.5  602.81
  4920.3  601.15  4980.4  600.61  5000.4  601.23  5020.4  601.03  5038.5  597.82
  5038.7  597.32  5042.2  597.32  5042.5  597.82  5052.4  598.42  5058.8  600.91
  5081.4  600.78  5099.8  601.45  5104.9  603.35  5122.6  604.17    5133  603.94
  5186.9  605.24  5268.9  608.53  5304.7  609.35  5309.8  610.55  5326.9  610.98
  5345.7  611.37  5350.8   612.3  5386.6  612.77  5391.8  613.39    5484   614.3
#Mann= 5 ,-1 , 0
  4582.4    .075       0  4858.5     .05       0  5038.5     .04       0
  5042.5     .05       0  5326.9    .075       0
Bank Sta=5038.5,5042.5
XS Rating Curve= 0 ,0
Exp/Cntr=0.3,0.1

Type RM Length L Ch R = 1 ,766     ,271,271,271
BEGIN DESCRIPTION:
Catherine Branch Tr 2 2.0
END DESCRIPTION:
XS GIS Cut Line= 3
      2345229.03      7065709.98        2345629.        7065460.
      2345828.98      7065410.01
#Sta/Elev= 30
  4523.7  610.12  4531.3   609.6  4735.3  602.86  4747.7  601.92    4799  599.64
  4806.7  599.82  4814.4  599.26  4835.6  599.33  4865.7  598.57    4878  598.62
  4908.7  597.38  4929.9  597.98  4951.1  597.48  4972.4  598.07  4987.7     598
  4997.9  597.64  5005.7  596.79  5018.6  597.27  5024.3  595.98  5024.5  595.48
    5028  595.48  5028.3  595.98  5036.6  596.87  5046.9  596.63  5059.8  597.73
  5067.5   600.4  5077.8  602.14  5137.1  604.93    5150  605.11  5201.5  607.68
#Mann= 3 ,-1 , 0
  4523.7     .05       0  5024.3    .033       0  5028.3     .05       0
Bank Sta=5024.3,5028.3
XS Rating Curve= 0 ,0
Exp/Cntr=0.3,0.1

Type RM Length L Ch R = 1 ,495     ,285,285,285
BEGIN DESCRIPTION:
Catherine Branch Tr 2 1.0
END DESCRIPTION:
XS GIS Cut Line= 3
      2345291.77      7065734.93       2345699.2      7065690.42
      2345879.02      7065559.99
#Sta/Elev= 30
  4662.3  608.65  4754.4  605.79  4760.1   605.3  4790.3  604.27  4840.6  601.68
  4845.7  601.09  4860.7  600.25  4900.9  598.84  4931.1  597.04    4937  596.05
  4961.3  594.87  4969.4  593.33  4969.6  592.83  4973.1  592.83  4973.4  593.33
  4981.4  595.34  5001.5  594.95  5021.7  595.41  5028.3  595.87  5033.4  595.55
  5041.8  595.66  5061.9  596.42  5075.1  596.57  5136.2  599.16  5158.4  599.69
  5171.7  600.47  5230.5  602.76  5280.8  604.42  5291.2  605.26  5294.3  605.26
#Mann= 3 ,-1 , 0
  4662.3     .05       0  4969.4    .033       0  4973.4     .05       0
Bank Sta=4969.4,4973.4
XS Rating Curve= 0 ,0
Exp/Cntr=0.3,0.1

Type RM Length L Ch R = 1 ,210     ,0,0,0
BEGIN DESCRIPTION:
Catherine Branch Tr 2 0.5
END DESCRIPTION:
XS GIS Cut Line= 3
       2345274.6      7065926.69      2345572.15      7065989.42
      2346105.32      7065622.87
#Sta/Elev= 30
    4526  606.99  4760.3  598.43    4786  598.07  4835.1   596.3    4877   596.4
  4927.8  595.19  4957.6  594.02  4963.6  592.73  4999.5  593.37  5027.3  592.26
  5027.5  591.76    5031  591.76  5031.3  592.26  5050.2  593.88    5101  594.06
  5142.9   595.1  5151.7  594.39  5157.8  595.48  5229.5  598.57  5259.3  599.25
  5265.4  599.98  5295.2  600.45    5352  602.36  5366.9  602.24  5372.9     603
  5387.8  603.48  5402.7  603.31  5438.6  604.74  5468.4   604.9  5477.1  605.42
#Mann= 3 ,-1 , 0
    4526     .05       0  5027.3     .04       0  5031.3     .05       0
Bank Sta=5027.3,5031.3
XS Rating Curve= 0 ,0
Exp/Cntr=0.3,0.1

Chan Stop Cuts=-1
Use User Specified Reach Order=0
Composite Channel Slope=5