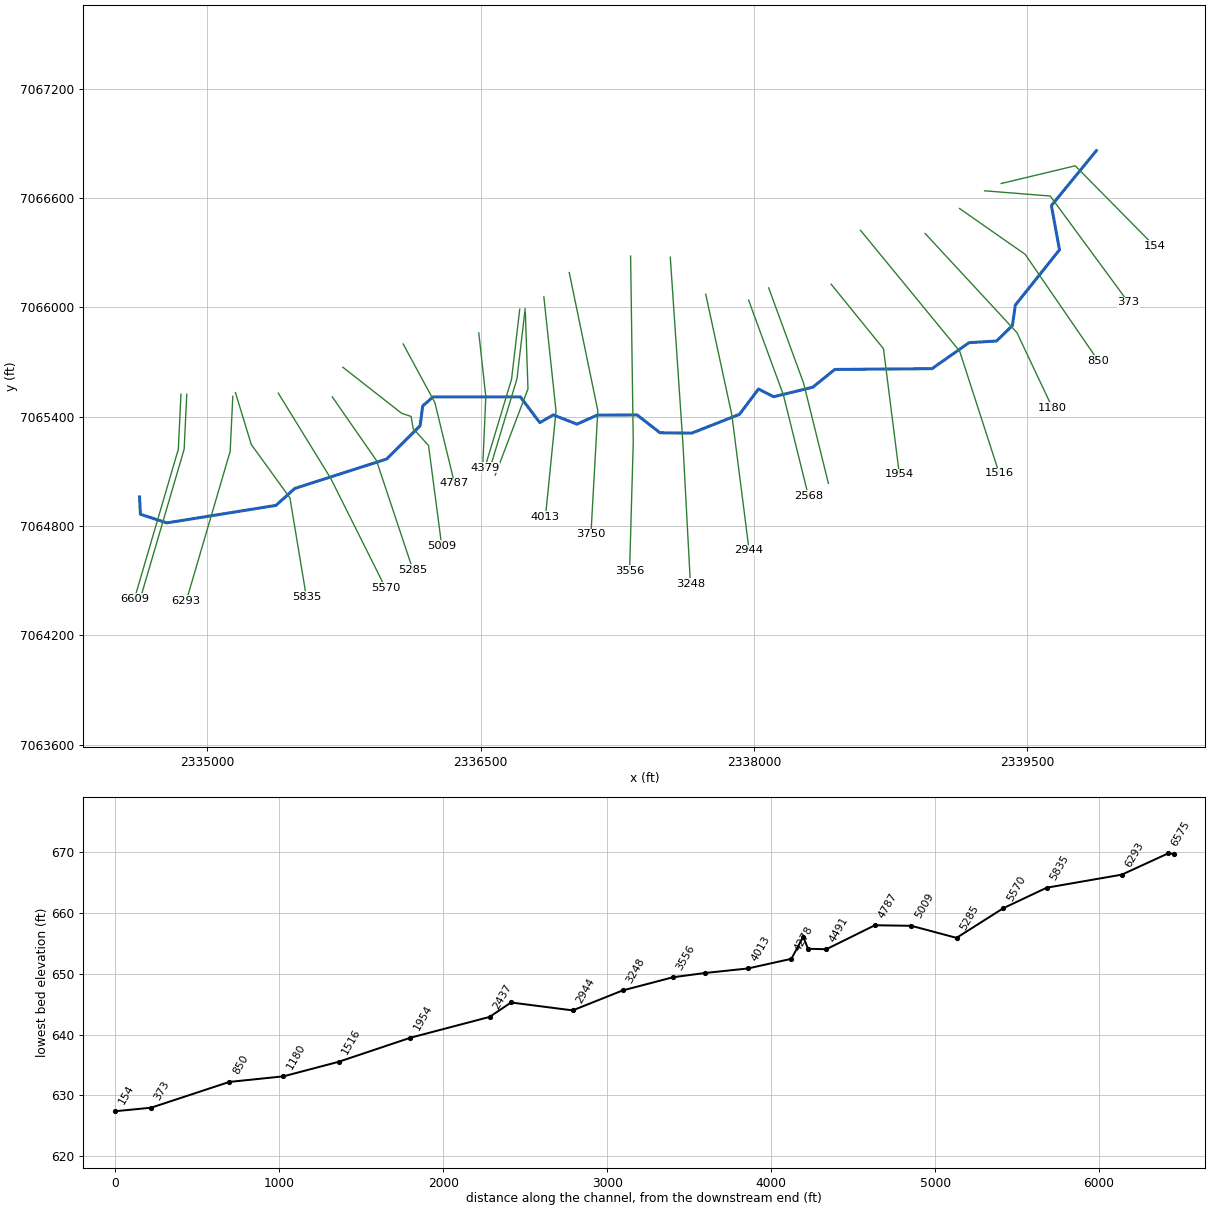
--- Catherine Branch Tr 3.prj (project) ---

Proj Title=Catherine Branch Tr 3 Base Level Engineering
Current Plan=p01
Default Exp/Contr=0.3,0.1
English Units
Geom File=g01
Flow File=f01
Plan File=p01
Y Axis Title=Elevation
X Axis Title(PF)=Main Channel Distance
X Axis Title(XS)=Station
BEGIN DESCRIPTION:
Catherine Branch Tr 3
END DESCRIPTION:
DSS Export Rating Curves= 0
DSS Export Rating Curve Sorted= 0
DSS Export Volume Flow Curves= 0
DXF OffsetX= 0
DXF OffsetY= 0
DXF ScaleX= 1
DXF ScaleY= 10

--- Catherine Branch Tr 3.p01 (plan) ---

Plan Title=Multiple Run
Short Identifier=Multiple
Geom File=g01
Flow File=f01
Subcritical Flow
K Sum by GR= 0
Std Step Tol= 0.01
Critical Tol= 0.01
Num of Std Step Trials= 20
Max Error Tol= 0.3
Flow Tol Ratio= 0.001
Split Flow NTrial= 30
Split Flow Tol= 0.02
Split Flow Ratio= 0.02
Log Output Level= 0
Friction Slope Method= 1
Unsteady Friction Slope Method= 2
Unsteady Bridges Friction Slope Method= 1
Parabolic Critical Depth
Global Vel Dist=  1 , 1 , 1
Global Log Level= 0
CheckData=True
Encroach Param= -1, 0, 0, 0
BEGIN DESCRIPTION:
Multiple Run
END DESCRIPTION:

--- Catherine Branch Tr 3.f01 (steady flow) ---

Flow Title=Multiple
Number of Profiles=7
Profile Names=10-year,25-year,50-year,1pct_min,100-year,1pct_plu,500-year
River Rch & RM= Catherine Branch,Reach-1,6609
     351     465     556     331     660    1317     931
River Rch & RM= Catherine Branch,Reach-1,3248
     523     710     862     520    1038    2072    1509
Boundary for River Rch & Prof#=Catherine Branch,Reach-1,1
Up Type=0
Dn Type=3
Dn Slope=0.005
Boundary for River Rch & Prof#=Catherine Branch,Reach-1,2
Up Type=0
Dn Type=3
Dn Slope=0.005
Boundary for River Rch & Prof#=Catherine Branch,Reach-1,3
Up Type=0
Dn Type=3
Dn Slope=0.005
Boundary for River Rch & Prof#=Catherine Branch,Reach-1,4
Up Type=0
Dn Type=3
Dn Slope=0.005
Boundary for River Rch & Prof#=Catherine Branch,Reach-1,5
Up Type=0
Dn Type=3
Dn Slope=0.005
Boundary for River Rch & Prof#=Catherine Branch,Reach-1,6
Up Type=0
Dn Type=3
Dn Slope=0.005
Boundary for River Rch & Prof#=Catherine Branch,Reach-1,7
Up Type=0
Dn Type=3
Dn Slope=0.005

--- Catherine Branch Tr 3.g01 (geometry) ---

Geom Title=Existing Conditions

River Reach=Catherine Branch,Reach-1
Reach XY= 30
      2334629.00      7064960.00      2334633.82      7064864.87
      2334779.00      7064817.56      2335377.53      7064913.56
      2335480.50      7065006.38      2335985.06      7065168.14
      2336168.48      7065350.22      2336182.51      7065458.75
      2336239.26      7065509.02      2336718.72      7065509.01
      2336825.34      7065367.72      2336899.13      7065410.16
      2337029.00      7065359.19      2337139.50      7065408.78
      2337359.02      7065410.04      2337484.86      7065312.06
      2337658.97      7065310.06      2337920.66      7065413.17
      2338025.58      7065552.19      2338108.79      7065509.79
      2338323.14      7065562.08      2338444.16      7065659.61
      2338977.45      7065663.75      2339180.47      7065806.45
      2339331.46      7065815.46      2339418.49      7065900.19
      2339434.52      7066012.43      2339676.86      7066315.97
      2339632.46      7066558.50      2339879.00      7066860.00

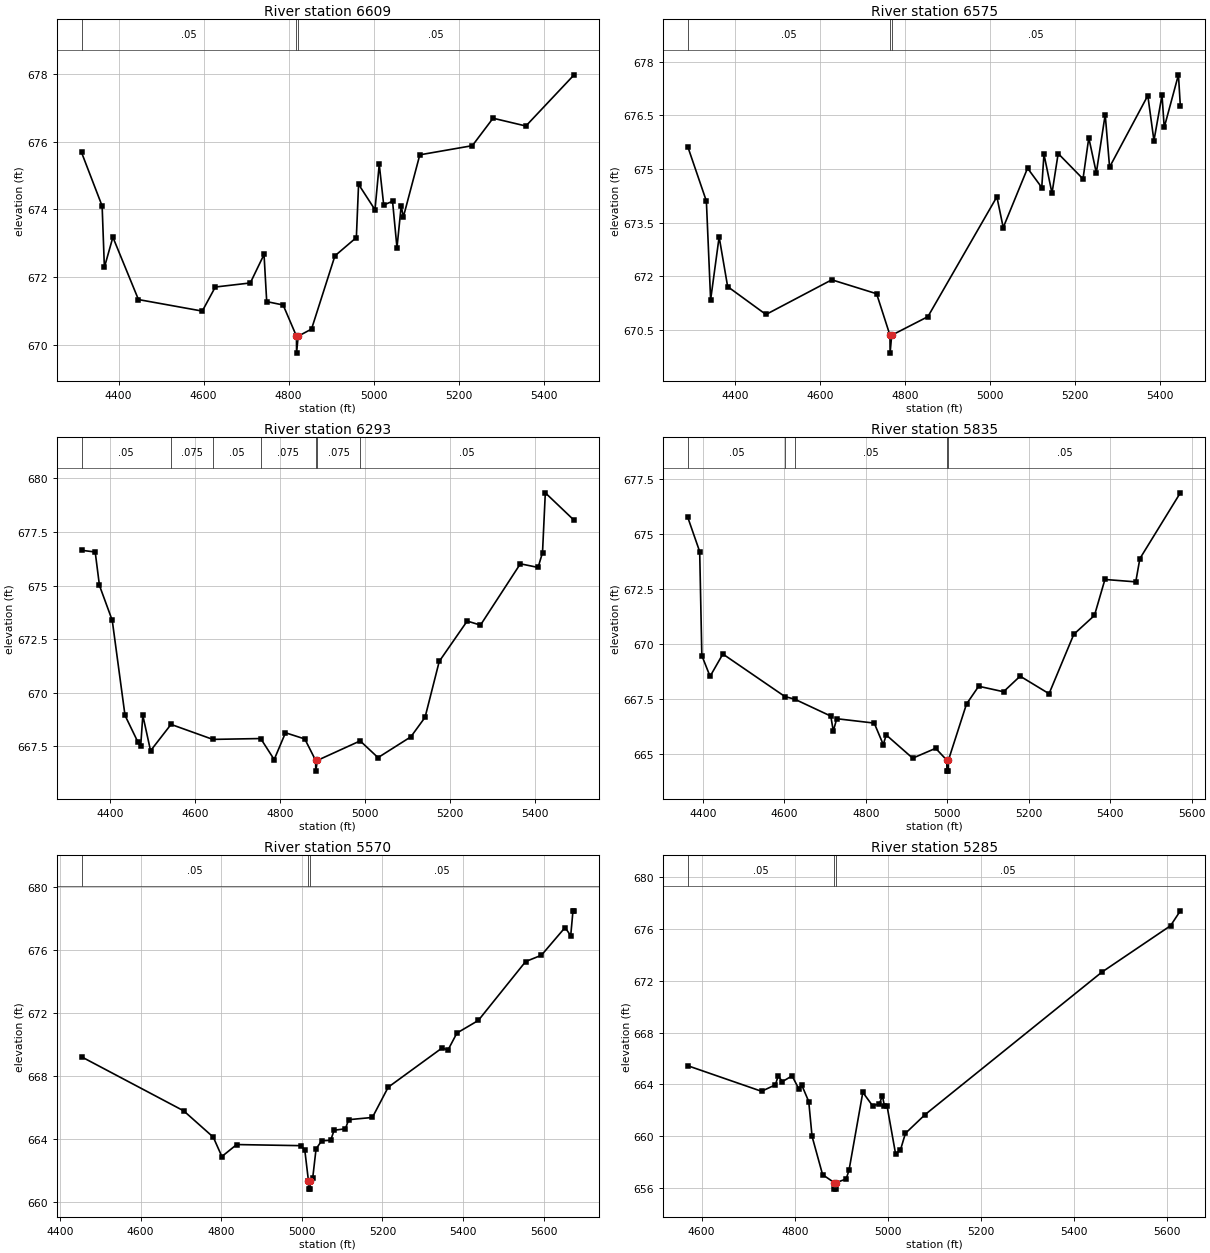
Type RM Length L Ch R = 1,6609,34,34,34
BEGIN DESCRIPTION:
Catherine Branch Tr 3 19.0
END DESCRIPTION:
XS GIS Cut Line= 3
      2334856.31      7065523.62      2334841.80      7065221.79
      2334600.88      7064400.37
#Sta/Elev= 30
  4313.0  675.68  4361.4  674.10  4366.7  672.29  4386.7  673.18  4446.8  671.34
  4596.9  671.00  4627.5  671.71  4709.8  671.83  4742.1  672.67  4748.4  671.28
  4787.0  671.18  4818.4  670.26  4818.6  669.76  4822.4  670.26  4853.8  670.47
  4908.8  672.63  4959.2  673.17  4964.4  674.74  5003.0  673.99  5013.0  675.33
  5023.5  674.13  5044.3  674.24  5054.7  672.87  5064.6  674.10  5069.8  673.78
  5108.4  675.61  5231.9  675.88  5280.6  676.69  5357.8  676.46  5471.2  677.97
#Mann=3,-1,0
  4313.0    0.05       0  4818.4   0.033       0  4822.4    0.05       0
Bank Sta=4818.4,4822.4
Exp/Cntr=0.3,0.1

Type RM Length L Ch R = 1,6575,282,282,282
BEGIN DESCRIPTION:
Catherine Branch Tr 3 18.0
END DESCRIPTION:
XS GIS Cut Line= 3
      2334888.24      7065523.62      2334873.73      7065221.79
      2334632.81      7064400.37
#Sta/Elev= 30
  4289.6  675.62  4333.3  674.10  4343.3  671.34  4363.3  673.10  4383.3  671.71
  4473.4  670.93  4628.2  671.90  4733.6  671.51  4765.0  670.35  4765.3  669.85
  4769.0  670.35  4854.2  670.87  5016.4  674.22  5031.3  673.36  5088.5  675.02
  5121.9  674.48  5127.1  675.41  5146.0  674.32  5160.5  675.43  5218.9  674.72
  5232.5  675.87  5250.2  674.89  5271.1  676.52  5281.4  675.05  5371.3  677.05
  5385.7  675.79  5404.7  677.06  5409.9  676.16  5443.3  677.63  5447.8  676.75
#Mann=3,-1,0
  4289.6    0.05       0  4765.0   0.033       0  4769.0    0.05       0
Bank Sta=4765,4769
Exp/Cntr=0.3,0.1

Type RM Length L Ch R = 1,6293,458,458,458
BEGIN DESCRIPTION:
Catherine Branch Tr 3 17.0
END DESCRIPTION:
XS GIS Cut Line= 3
      2335140.77      7065512.07      2335126.25      7065210.18
      2334885.33      7064388.72
#Sta/Elev= 30
  4332.8  676.65  4364.9  676.57  4374.9  675.01  4405.0  673.38  4435.0  668.95
  4465.0  667.72  4471.9  667.52  4476.9  668.95  4495.1  667.30  4543.2  668.53
  4641.5  667.83  4754.1  667.87  4785.8  666.89  4812.4  668.14  4857.8  667.85
  4883.3  666.85  4883.6  666.35  4887.3  666.85  4988.0  667.76  5030.0  666.98
  5107.2  667.95  5140.6  668.86  5174.0  671.47  5239.7  673.35  5270.9  673.16
  5364.7  676.02  5406.4  675.85  5416.8  676.54  5423.4  679.33  5491.1  678.05
#Mann=7,-1,0
  4332.8    0.05       0  4543.2   0.075       0  4641.5    0.05       0
  4754.1   0.075       0  4883.3    0.05       0  4887.3   0.075       0
  4988.0    0.05       0
Bank Sta=4883.3,4887.3
Exp/Cntr=0.3,0.1

Type RM Length L Ch R = 1,5835,265,265,265
BEGIN DESCRIPTION:
Catherine Branch Tr 3 16.0
END DESCRIPTION:
XS GIS Cut Line= 4
      2335155.28      7065532.36      2335242.14      7065247.75
      2335454.25      7064954.75      2335544.23      7064411.94
#Sta/Elev= 30
  4362.8  675.77  4392.0  674.21  4397.3  669.47  4417.5  668.52  4448.9  669.54
  4601.3  667.60  4625.4  667.48  4713.9  666.71  4720.1  666.03  4728.6  666.59
  4820.6  666.39  4842.8  665.41  4850.0  665.85  4915.0  664.79  4971.4  665.24
  4998.8  664.70  4999.1  664.20  5002.6  664.20  5002.8  664.70  5047.2  667.26
  5077.1  668.07  5138.1  667.82  5178.9  668.53  5249.9  667.73  5310.7  670.44
  5361.4  671.30  5387.1  672.94  5462.8  672.83  5472.9  673.89  5572.3  676.89
#Mann=5,-1,0
  4362.8    0.05       0  4601.3   0.075       0  4625.4    0.05       0
  4998.8   0.033       0  5002.8    0.05       0
Bank Sta=4998.8,5002.8
Exp/Cntr=0.3,0.1

Type RM Length L Ch R = 1,5570,285,285,285
BEGIN DESCRIPTION:
Catherine Branch Tr 3 15.0
END DESCRIPTION:
XS GIS Cut Line= 3
      2335390.42      7065529.43      2335679.00      7065060.00
      2335979.02      7064459.96
#Sta/Elev= 30
  4453.6  669.22  4707.0  665.79  4780.4  664.12  4801.7  662.89  4838.4  663.65
  4996.9  663.58  5007.4  663.30  5016.6  661.32  5016.9  660.82  5020.4  660.82
  5020.6  661.32  5027.0  661.51  5035.4  663.38  5049.4  663.89  5071.7  663.92
  5080.1  664.56  5108.1  664.65  5116.4  665.23  5175.1  665.37  5214.3  667.29
  5348.4  669.79  5362.4  669.64  5384.8  670.73  5437.9  671.53  5555.3  675.27
  5594.4  675.67  5653.1  677.43  5667.1  676.91  5672.7  678.49  5675.5  678.49
#Mann=3,-1,0
  4453.6    0.05       0  5016.6   0.033       0  5020.6    0.05       0
Bank Sta=5016.6,5020.6
Exp/Cntr=0.3,0.1

Type RM Length L Ch R = 1,5285,276,276,276
BEGIN DESCRIPTION:
Catherine Branch Tr 3 14.0
END DESCRIPTION:
XS GIS Cut Line= 3
      2335686.48      7065509.13      2335929.00      7065160.00
      2336129.01      7064559.96
#Sta/Elev= 30
  4570.3  665.44  4728.7  663.47  4758.4  663.97  4764.5  664.67  4773.2  664.21
  4794.2  664.66  4809.0  663.64  4815.1  663.94  4830.0  662.68  4837.1  660.00
  4859.7  657.05  4884.7  656.43  4884.9  655.93  4888.4  655.93  4888.7  656.43
  4910.2  656.71  4916.4  657.37  4946.1  663.39  4967.0  662.36  4981.9  662.50
  4988.0  663.14  4992.4  662.37  4998.0  662.37  5016.5  658.64  5027.0  658.96
  5037.6  660.23  5079.7  661.67  5459.2  672.65  5606.8  676.23  5627.9  677.38
#Mann=3,-1,0
  4570.3    0.05       0  4884.7   0.033       0  4888.7    0.05       0
Bank Sta=4884.7,4888.7
Exp/Cntr=0.3,0.1

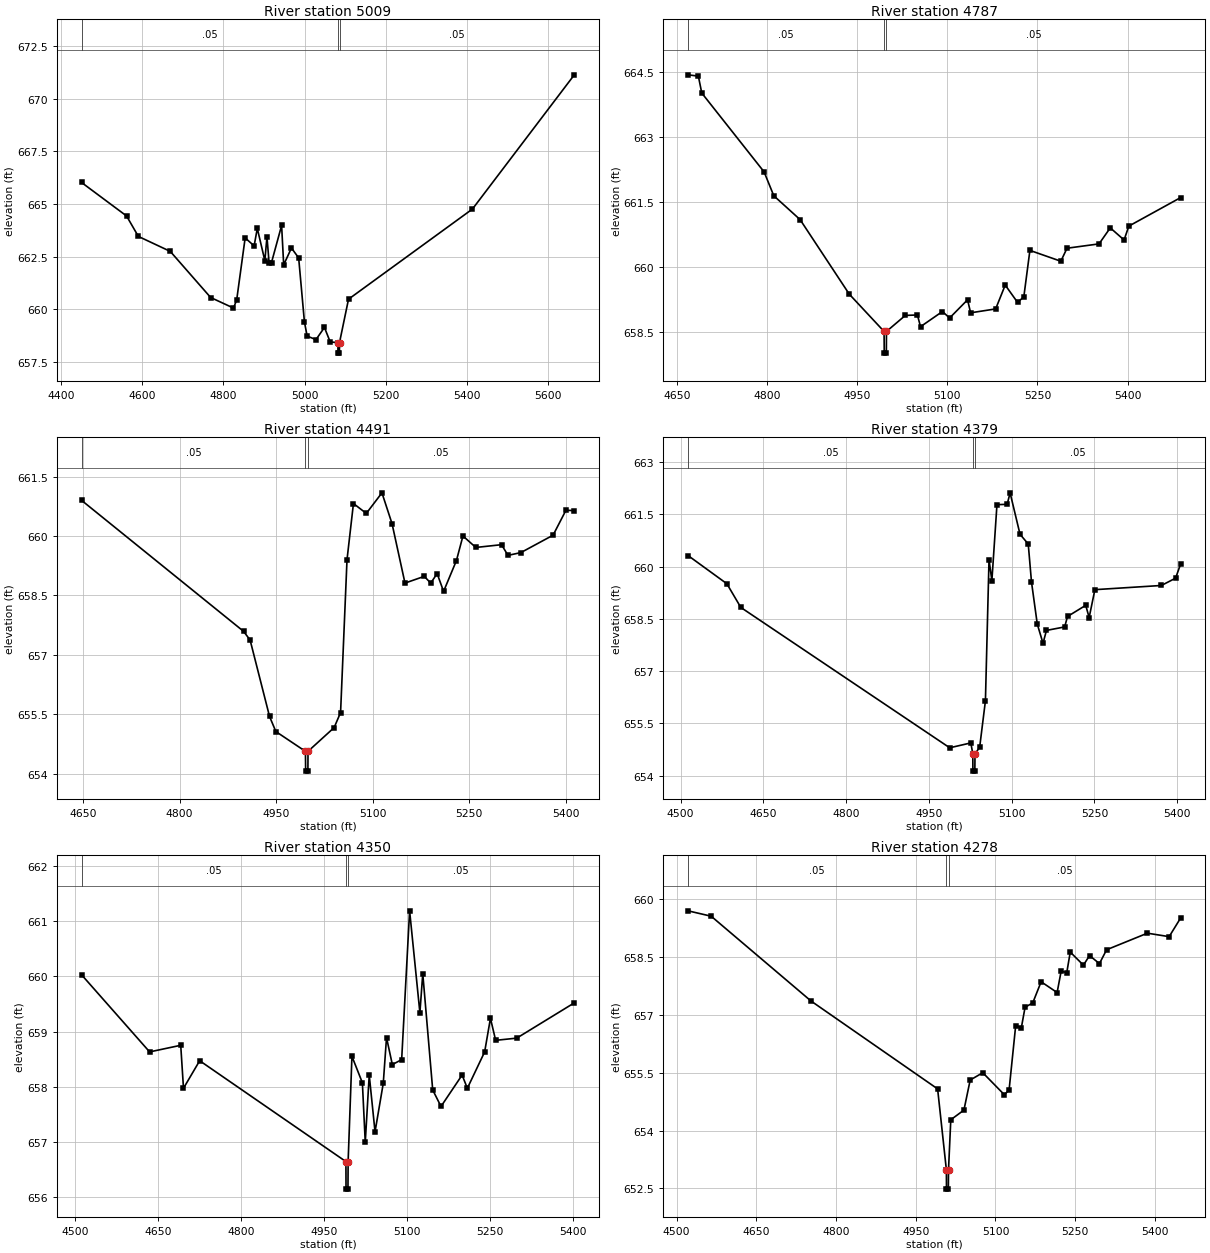
Type RM Length L Ch R = 1,5009,222,222,222
BEGIN DESCRIPTION:
Catherine Branch Tr 3 13.0
END DESCRIPTION:
XS GIS Cut Line= 6
      2335744.49      7065671.72      2336066.71      7065419.17
      2336118.95      7065401.75      2336130.56      7065334.99
      2336214.74      7065242.11      2336287.30      7064690.65
#Sta/Elev= 30
  4450.8  666.02  4561.7  664.43  4590.7  663.46  4669.3  662.75  4768.8  660.56
  4825.0  660.06  4832.9  660.44  4853.8  663.39  4875.9  663.01  4883.7  663.84
  4902.3  662.31  4907.5  663.44  4912.7  662.22  4918.7  662.22  4943.6  663.98
  4948.7  662.11  4967.8  662.91  4985.6  662.44  4999.8  659.40  5006.5  658.73
  5028.2  658.56  5049.1  659.14  5063.3  658.45  5082.2  658.42  5082.5  657.92
  5086.0  657.92  5086.2  658.42  5108.4  660.48  5413.7  664.76  5664.6  671.13
#Mann=3,-1,0
  4450.8    0.05       0  5082.2   0.033       0  5086.2    0.05       0
Bank Sta=5082.2,5086.2
Exp/Cntr=0.3,0.1

Type RM Length L Ch R = 1,4787,296,296,296
BEGIN DESCRIPTION:
Catherine Branch Tr 3 12.4
END DESCRIPTION:
XS GIS Cut Line= 3
      2336075.40      7065799.43      2336249.57      7065477.22
      2336356.98      7065035.97
#Sta/Elev= 30
  4668.2  664.43  4685.4  664.40  4691.1  664.01  4794.9  662.19  4811.0  661.64
  4854.8  661.09  4936.7  659.37  4994.6  658.51  4994.9  658.01  4998.4  658.01
  4998.6  658.51  5030.0  658.88  5050.1  658.89  5055.3  658.62  5091.8  658.97
  5103.7  658.82  5133.6  659.24  5138.7  658.94  5180.4  659.03  5196.3  659.58
  5216.9  659.18  5227.3  659.31  5237.4  660.38  5288.9  660.13  5299.2  660.43
  5352.5  660.53  5371.2  660.90  5394.2  660.62  5402.1  660.94  5488.6  661.60
#Mann=3,-1,0
  4668.2    0.05       0  4994.6   0.033       0  4998.6    0.05       0
Bank Sta=4994.6,4998.6
Exp/Cntr=0.3,0.1

Type RM Length L Ch R = 1,4491,112,112,112
BEGIN DESCRIPTION:
Catherine Branch Tr 3 12.0
END DESCRIPTION:
XS GIS Cut Line= 3
      2336490.49      7065860.41      2336529.00      7065510.00
      2336510.81      7065097.02
#Sta/Elev= 30
  4647.5  660.90  4899.4  657.59  4909.5  657.37  4939.7  655.44  4949.5  655.06
  4995.5  654.56  4995.8  654.06  4999.3  654.06  4999.5  654.56  5040.1  655.16
  5050.1  655.54  5060.1  659.40  5070.1  660.82  5090.1  660.57  5114.4  661.09
  5130.1  660.31  5150.2  658.81  5180.2  658.98  5190.2  658.81  5200.2  659.05
  5210.2  658.60  5230.2  659.38  5240.3  660.00  5260.3  659.71  5300.3  659.78
  5310.3  659.51  5330.3  659.58  5380.4  660.02  5400.4  660.65  5413.4  660.64
#Mann=3,-1,0
  4647.5    0.05       0  4995.5   0.033       0  4999.5    0.05       0
Bank Sta=4995.5,4999.5
Exp/Cntr=0.3,0.1

Type RM Length L Ch R = 1,4379,29,29,29
BEGIN DESCRIPTION:
Catherine Branch Tr 3 11.2
END DESCRIPTION:
XS GIS Cut Line= 3
      2336715.08      7065989.97      2336670.37      7065606.24
      2336523.93      7065120.98
#Sta/Elev= 30
  4513.3  660.32  4583.7  659.51  4609.0  658.83  4987.7  654.80  5025.9  654.94
  5029.5  654.63  5029.7  654.13  5033.2  654.13  5033.5  654.63  5041.9  654.81
  5052.4  656.15  5058.9  660.20  5064.1  659.60  5073.3  661.78  5091.8  661.79
  5097.1  662.12  5115.1  660.93  5130.0  660.65  5135.9  659.56  5146.4  658.35
  5156.8  657.80  5163.0  658.17  5196.0  658.27  5201.2  658.57  5234.2  658.89
  5240.4  658.54  5250.8  659.34  5371.3  659.46  5397.1  659.67  5406.5  660.09
#Mann=3,-1,0
  4513.3    0.05       0  5029.5   0.033       0  5033.5    0.05       0
Bank Sta=5029.5,5033.5
Exp/Cntr=0.3,0.1

Type RM Length L Ch R = 1,4350,72,72,72
BEGIN DESCRIPTION:
Catherine Branch Tr 3 11.1
END DESCRIPTION:
XS GIS Cut Line= 3
      2336744.87      7065992.38      2336700.17      7065608.73
      2336554.08      7065124.64
#Sta/Elev= 30
  4511.0  660.03  4634.2  658.63  4690.5  658.75  4695.5  657.97  4724.8  658.47
  4989.5  656.64  4989.7  656.14  4993.2  656.14  4993.5  656.64  5000.4  658.55
  5019.3  658.07  5024.5  656.99  5031.7  658.21  5042.2  657.18  5057.1  658.06
  5063.0  658.89  5073.5  658.40  5090.4  658.49  5104.8  661.19  5123.4  659.34
  5128.6  660.05  5146.6  657.94  5161.6  657.64  5199.8  658.21  5209.3  657.97
  5240.6  658.63  5251.1  659.24  5260.5  658.84  5298.7  658.88  5402.9  659.52
#Mann=3,-1,0
  4511.0    0.05       0  4989.5   0.033       0  4993.5    0.05       0
Bank Sta=4989.5,4993.5
Exp/Cntr=0.3,0.1

Type RM Length L Ch R = 1,4278,265,265,265
BEGIN DESCRIPTION:
Catherine Branch Tr 3 11.0
END DESCRIPTION:
XS GIS Cut Line= 3
      2336745.92      7065973.54      2336760.43      7065552.69
      2336580.47      7065079.56
#Sta/Elev= 30
  4521.4  659.70  4565.0  659.56  4752.9  657.36  4991.1  655.08  5007.6  652.98
  5007.8  652.48  5011.3  652.48  5011.6  652.98  5015.9  654.28  5040.6  654.53
  5052.4  655.31  5076.1  655.50  5116.6  654.93  5125.6  655.05  5138.0  656.72
  5148.7  656.67  5155.7  657.20  5170.1  657.31  5185.9  657.86  5216.0  657.58
  5223.5  658.13  5234.2  658.10  5240.7  658.63  5265.5  658.29  5277.0  658.54
  5295.6  658.33  5309.1  658.69  5385.9  659.12  5426.8  659.03  5448.7  659.52
#Mann=3,-1,0
  4521.4    0.05       0  5007.6   0.033       0  5011.6    0.05       0
Bank Sta=5007.6,5011.6
Exp/Cntr=0.3,0.1

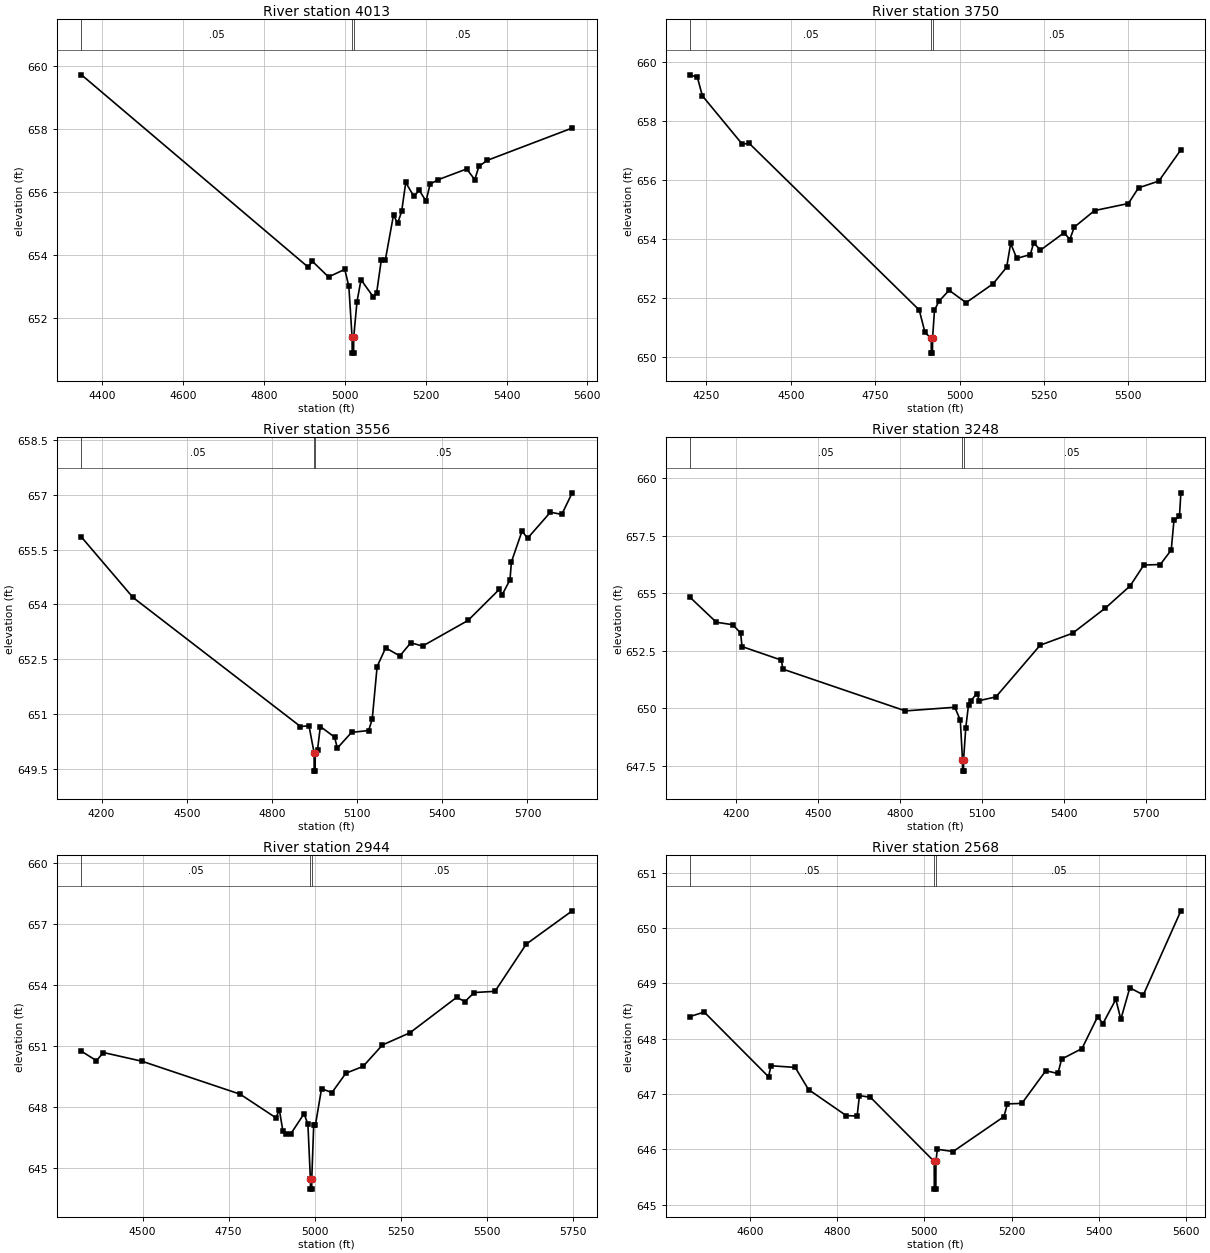
Type RM Length L Ch R = 1,4013,263,263,263
BEGIN DESCRIPTION:
Catherine Branch Tr 3 10.0
END DESCRIPTION:
XS GIS Cut Line= 3
      2336847.52      7066057.70      2336914.27      7065430.78
      2336856.22      7064850.24
#Sta/Elev= 30
  4348.6  659.73  4909.5  653.62  4919.5  653.81  4959.7  653.31  4999.9  653.55
  5010.0  653.01  5018.0  651.39  5018.3  650.89  5021.8  650.89  5022.0  651.39
  5030.1  652.52  5040.1  653.22  5070.3  652.68  5078.8  652.81  5090.4  653.86
  5100.4  653.86  5120.5  655.28  5130.6  655.01  5140.6  655.39  5150.7  656.31
  5170.8  655.87  5184.3  656.06  5200.9  655.72  5211.0  656.26  5231.1  656.40
  5301.4  656.74  5321.5  656.40  5331.6  656.82  5351.7  657.01  5562.5  658.04
#Mann=3,-1,0
  4348.6    0.05       0  5018.0   0.033       0  5022.0    0.05       0
Bank Sta=5018,5022
Exp/Cntr=0.3,0.1

Type RM Length L Ch R = 1,3750,194,194,194
BEGIN DESCRIPTION:
Catherine Branch Tr 3 9.0
END DESCRIPTION:
XS GIS Cut Line= 3
      2336986.83      7066191.30      2337143.58      7065433.68
      2337105.86      7064754.69
#Sta/Elev= 30
  4201.8  659.57  4223.5  659.48  4238.0  658.86  4356.3  657.22  4376.7  657.25
  4880.5  651.60  4897.5  650.84  4916.0  650.64  4916.2  650.14  4919.7  650.14
  4920.0  650.64  4925.6  651.59  4938.4  651.89  4969.0  652.27  5019.2  651.85
  5099.3  652.49  5139.4  653.05  5151.3  653.86  5169.4  653.35  5209.5  653.48
  5219.5  653.88  5239.6  653.63  5309.7  654.22  5326.6  653.99  5339.7  654.41
  5399.8  654.97  5500.0  655.21  5530.0  655.74  5590.1  655.97  5655.5  657.03
#Mann=3,-1,0
  4201.8    0.05       0  4916.0   0.033       0  4920.0    0.05       0
Bank Sta=4916,4920
Exp/Cntr=0.3,0.1

Type RM Length L Ch R = 1,3556,308,308,308
BEGIN DESCRIPTION:
Catherine Branch Tr 3 8.5
END DESCRIPTION:
XS GIS Cut Line= 3
      2337323.54      7066281.29      2337338.06      7065259.52
      2337317.79      7064553.19
#Sta/Elev= 30
  4129.1  655.84  4310.4  654.19  4900.5  650.66  4930.5  650.68  4948.5  649.94
  4948.7  649.44  4952.2  649.44  4952.5  649.94  4960.5  650.02  4970.5  650.66
  5020.5  650.37  5030.5  650.07  5080.5  650.50  5140.5  650.55  5153.2  650.86
  5170.5  652.30  5200.5  652.81  5250.5  652.59  5289.0  652.95  5330.6  652.86
  5490.6  653.56  5600.7  654.41  5610.7  654.26  5638.4  654.67  5643.4  655.16
  5680.7  656.00  5700.7  655.81  5780.8  656.52  5820.8  656.46  5857.6  657.05
#Mann=3,-1,0
  4129.1    0.05       0  4948.5   0.033       0  4952.5    0.05       0
Bank Sta=4948.5,4952.5
Exp/Cntr=0.3,0.1

Type RM Length L Ch R = 1,3248,304,304,304
BEGIN DESCRIPTION:
Catherine Branch Tr 3 8.0
END DESCRIPTION:
XS GIS Cut Line= 3
      2337541.24      7066275.43      2337610.90      7065247.91
      2337651.53      7064484.77
#Sta/Elev= 30
  4032.1  654.82  4127.8  653.74  4187.9  653.63  4216.8  653.27  4221.8  652.68
  4365.9  652.09  4370.9  651.70  4819.3  649.88  4999.7  650.04  5019.8  649.48
  5027.8  647.76  5028.1  647.26  5031.6  647.26  5031.8  647.76  5039.8  649.14
  5049.9  650.15  5058.4  650.32  5079.9  650.63  5089.9  650.33  5150.0  650.49
  5311.8  652.74  5430.4  653.26  5550.6  654.36  5640.7  655.32  5690.8  656.23
  5750.9  656.25  5790.9  656.88  5800.9  658.17  5821.0  658.34  5826.2  659.37
#Mann=3,-1,0
  4032.1    0.05       0  5027.8   0.033       0  5031.8    0.05       0
Bank Sta=5027.8,5031.8
Exp/Cntr=0.3,0.1

Type RM Length L Ch R = 1,2944,376,376,376
BEGIN DESCRIPTION:
Catherine Branch Tr 3 7.0
END DESCRIPTION:
XS GIS Cut Line= 3
      2337735.72      7066072.23      2337879.00      7065410.00
      2337973.74      7064667.37
#Sta/Elev= 30
  4322.3  650.76  4366.0  650.30  4386.0  650.70  4498.4  650.27  4783.5  648.65
  4887.3  647.49  4897.5  647.87  4907.8  646.83  4918.0  646.70  4931.1  646.71
  4969.2  647.69  4980.4  647.17  4987.6  644.48  4987.9  643.98  4991.4  643.98
  4991.6  644.48  4997.3  647.15  5002.4  647.15  5020.0  648.92  5050.3  648.73
  5090.6  649.68  5141.0  650.02  5196.9  651.07  5276.8  651.67  5413.2  653.42
  5436.4  653.20  5463.6  653.65  5524.1  653.71  5614.8  656.03  5748.5  657.67
#Mann=3,-1,0
  4322.3    0.05       0  4987.6   0.033       0  4991.6    0.05       0
Bank Sta=4987.6,4991.6
Exp/Cntr=0.3,0.1

Type RM Length L Ch R = 1,2568,131,131,131
BEGIN DESCRIPTION:
Catherine Branch Tr 3 6.2
END DESCRIPTION:
XS GIS Cut Line= 3
      2337970.82      7066040.36      2338162.40      7065517.86
      2338298.82      7064966.40
#Sta/Elev= 30
  4463.3  648.40  4495.6  648.48  4643.1  647.31  4648.5  647.51  4704.1  647.48
  4734.6  647.08  4820.8  646.61  4846.0  646.60  4851.3  646.97  4876.5  646.94
  5022.6  645.78  5022.9  645.28  5026.4  645.28  5026.6  645.78  5029.8  646.00
  5066.0  645.96  5182.4  646.59  5190.3  646.82  5223.6  646.83  5278.3  647.42
  5306.1  647.37  5314.6  647.63  5361.2  647.82  5397.4  648.40  5409.1  648.27
  5438.9  648.71  5450.3  648.35  5470.9  648.92  5501.8  648.79  5587.9  650.31
#Mann=3,-1,0
  4463.3    0.05       0  5022.6   0.033       0  5026.6    0.05       0
Bank Sta=5022.6,5026.6
Exp/Cntr=0.3,0.1

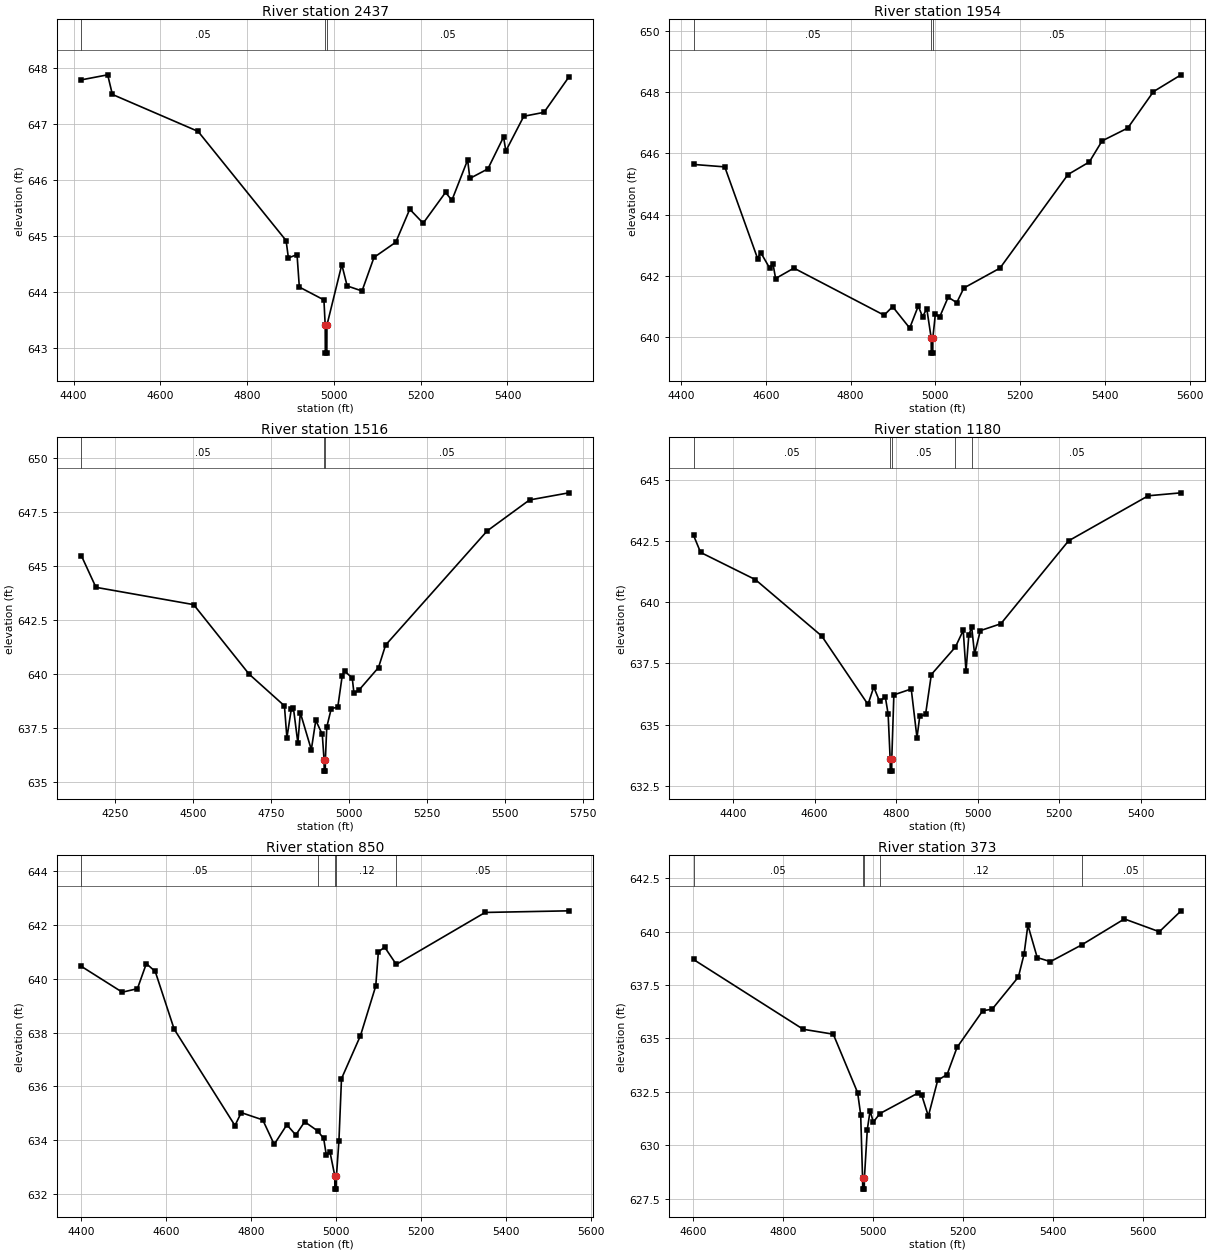
Type RM Length L Ch R = 1,2437,483,483,483
BEGIN DESCRIPTION:
Catherine Branch Tr 3 6.0
END DESCRIPTION:
XS GIS Cut Line= 3
      2338081.13      7066107.09      2338272.70      7065584.62
      2338408.89      7065034.09
#Sta/Elev= 30
  4417.8  647.78  4478.6  647.87  4489.4  647.52  4686.9  646.86  4889.8  644.91
  4895.1  644.60  4915.0  644.66  4920.3  644.08  4977.0  643.85  4979.9  643.40
  4980.2  642.90  4983.7  642.90  4983.9  643.40  5018.2  644.48  5030.5  644.10
  5064.8  644.01  5092.4  644.61  5142.5  644.88  5174.8  645.47  5205.7  645.22
  5257.2  645.77  5271.9  645.63  5308.2  646.35  5313.3  646.02  5354.8  646.19
  5391.0  646.76  5396.2  646.51  5437.6  647.13  5484.2  647.20  5541.4  647.83
#Mann=3,-1,0
  4417.8    0.05       0  4979.9   0.033       0  4983.9    0.05       0
Bank Sta=4979.9,4983.9
Exp/Cntr=0.3,0.1

Type RM Length L Ch R = 1,1954,438,438,438
BEGIN DESCRIPTION:
Catherine Branch Tr 3 5.0
END DESCRIPTION:
XS GIS Cut Line= 3
      2338423.66      7066127.38      2338711.00      7065773.29
      2338798.08      7065085.39
#Sta/Elev= 30
  4429.8  645.64  4503.5  645.56  4581.0  642.56  4588.2  642.76  4609.0  642.26
  4617.0  642.40  4623.4  641.91  4666.5  642.25  4879.2  640.71  4899.2  640.99
  4939.5  640.29  4959.7  641.01  4969.8  640.66  4979.8  640.92  4990.1  639.97
  4990.4  639.47  4993.9  639.47  4994.1  639.97  5000.0  640.75  5010.1  640.65
  5030.2  641.30  5050.4  641.12  5067.2  641.60  5152.4  642.25  5312.7  645.31
  5362.9  645.72  5393.1  646.41  5453.6  646.83  5514.1  648.02  5579.2  648.57
#Mann=3,-1,0
  4429.8    0.05       0  4990.1   0.033       0  4994.1    0.05       0
Bank Sta=4990.1,4994.1
Exp/Cntr=0.3,0.1

Type RM Length L Ch R = 1,1516,336,336,336
BEGIN DESCRIPTION:
Catherine Branch Tr 3 4.0
END DESCRIPTION:
XS GIS Cut Line= 3
      2338585.32      7066422.50      2339129.00      7065760.00
      2339345.80      7065090.24
#Sta/Elev= 30
  4143.0  645.47  4189.9  644.00  4502.7  643.20  4680.0  639.99  4793.4  638.52
  4801.3  637.04  4815.6  638.39  4822.1  638.43  4836.4  636.80  4844.3  638.20
  4879.5  636.49  4893.8  637.85  4914.6  637.20  4920.4  636.00  4920.7  635.50
  4924.2  635.50  4924.4  636.00  4929.0  637.54  4943.3  638.39  4964.2  638.46
  4978.5  639.92  4986.4  640.12  5010.5  639.81  5016.0  639.11  5031.6  639.24
  5094.6  640.29  5117.3  641.33  5442.6  646.61  5578.1  648.04  5704.0  648.37
#Mann=3,-1,0
  4143.0    0.05       0  4920.4   0.033       0  4924.4    0.05       0
Bank Sta=4920.4,4924.4
Exp/Cntr=0.3,0.1

Type RM Length L Ch R = 1,1180,330,330,330
BEGIN DESCRIPTION:
Catherine Branch Tr 3 3.0
END DESCRIPTION:
XS GIS Cut Line= 3
      2338939.84      7066405.31      2339443.00      7065862.13
      2339637.41      7065450.43
#Sta/Elev= 30
  4303.2  642.73  4320.6  642.03  4455.0  640.92  4617.7  638.62  4731.1  635.83
  4745.3  636.54  4759.5  635.96  4773.6  636.14  4780.5  635.44  4785.5  633.61
  4785.8  633.11  4789.3  633.11  4789.5  633.61  4794.6  636.22  4837.2  636.46
  4851.3  634.47  4858.1  635.35  4872.3  635.42  4886.5  637.05  4945.5  638.17
  4964.7  638.85  4971.5  637.18  4978.4  638.65  4985.4  638.99  4992.5  637.89
  5006.7  638.84  5057.0  639.12  5222.9  642.50  5418.5  644.34  5498.9  644.46
#Mann=5,-1,0
  4303.2    0.05       0  4785.5   0.035       0  4789.5    0.05       0
  4945.5    0.12       0  4985.4    0.05       0
Bank Sta=4785.5,4789.5
Exp/Cntr=0.3,0.1

Type RM Length L Ch R = 1,850,477,477,477
BEGIN DESCRIPTION:
Catherine Branch Tr 3 2.0
END DESCRIPTION:
XS GIS Cut Line= 3
      2339128.53      7066542.53      2339488.74      7066290.96
      2339888.98      7065707.74
#Sta/Elev= 30
  4401.3  640.46  4497.6  639.50  4533.3  639.63  4554.3  640.56  4575.2  640.27
  4619.7  638.13  4762.7  634.55  4777.5  635.03  4828.1  634.76  4855.0  633.85
  4884.8  634.58  4905.8  634.20  4926.7  634.69  4957.3  634.35  4971.4  634.07
  4977.5  633.46  4986.3  633.56  4997.5  632.69  4997.7  632.19  5001.2  632.19
  5001.5  632.69  5007.3  633.99  5013.3  636.29  5058.0  637.89  5093.9  639.73
  5100.0  641.00  5114.9  641.17  5142.2  640.53  5351.2  642.46  5548.0  642.52
#Mann=5,-1,0
  4401.3    0.05       0  4957.3    0.12       0  4997.5    0.07       0
  5001.5    0.12       0  5142.2    0.05       0
Bank Sta=4997.5,5001.5
Exp/Cntr=0.3,0.1

Type RM Length L Ch R = 1,373,219,219,219
BEGIN DESCRIPTION:
Catherine Branch Tr 3 1.0
END DESCRIPTION:
XS GIS Cut Line= 3
      2339265.78      7066639.73      2339625.96      7066611.15
      2340054.37      7066028.51
#Sta/Elev= 30
  4600.3  638.70  4844.3  635.43  4911.2  635.20  4965.4  632.46  4972.2  631.42
  4976.4  628.44  4976.7  627.94  4980.2  627.94  4980.4  628.44  4986.9  630.73
  4993.1  631.61  5000.3  631.08  5014.9  631.48  5099.6  632.44  5108.0  632.34
  5122.7  631.36  5143.5  633.04  5164.4  633.31  5186.5  634.58  5243.8  636.30
  5264.6  636.37  5323.0  637.88  5335.6  638.95  5344.1  640.31  5364.9  638.79
  5394.2  638.60  5463.5  639.38  5558.8  640.60  5636.5  640.00  5684.8  640.98
#Mann=5,-1,0
  4600.3    0.05       0  4976.4   0.033       0  4980.4    0.05       0
  5014.9    0.12       0  5463.5    0.05       0
Bank Sta=4976.4,4980.4
Exp/Cntr=0.3,0.1

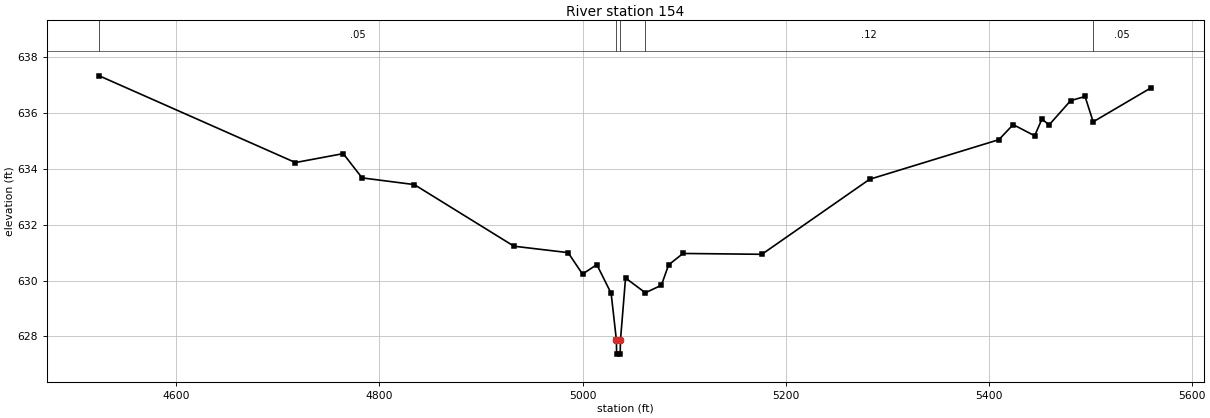
Type RM Length L Ch R = 1,154,0,0,0
BEGIN DESCRIPTION:
Catherine Branch Tr 3 0.5
END DESCRIPTION:
XS GIS Cut Line= 3
      2339357.24      7066679.76      2339763.19      7066776.96
      2340197.72      7066336.71
#Sta/Elev= 30
  4524.0  637.34  4717.2  634.23  4764.3  634.55  4782.9  633.68  4834.3  633.44
  4932.5  631.23  4985.8  631.00  5000.0  630.23  5014.1  630.57  5028.2  629.54
  5033.4  627.86  5033.6  627.36  5037.1  627.36  5037.4  627.86  5042.4  630.09
  5061.9  629.56  5077.7  629.83  5084.8  630.56  5099.0  630.97  5176.7  630.94
  5282.8  633.63  5410.1  635.05  5424.2  635.59  5445.4  635.19  5452.5  635.79
  5459.6  635.58  5480.8  636.45  5495.0  636.60  5503.0  635.69  5560.0  636.91
#Mann=5,-1,0
  4524.0    0.05       0  5033.4   0.033       0  5037.4    0.05       0
  5061.9    0.12       0  5503.0    0.05       0
Bank Sta=5033.4,5037.4
Exp/Cntr=0.3,0.1

Chan Stop Cuts=-1