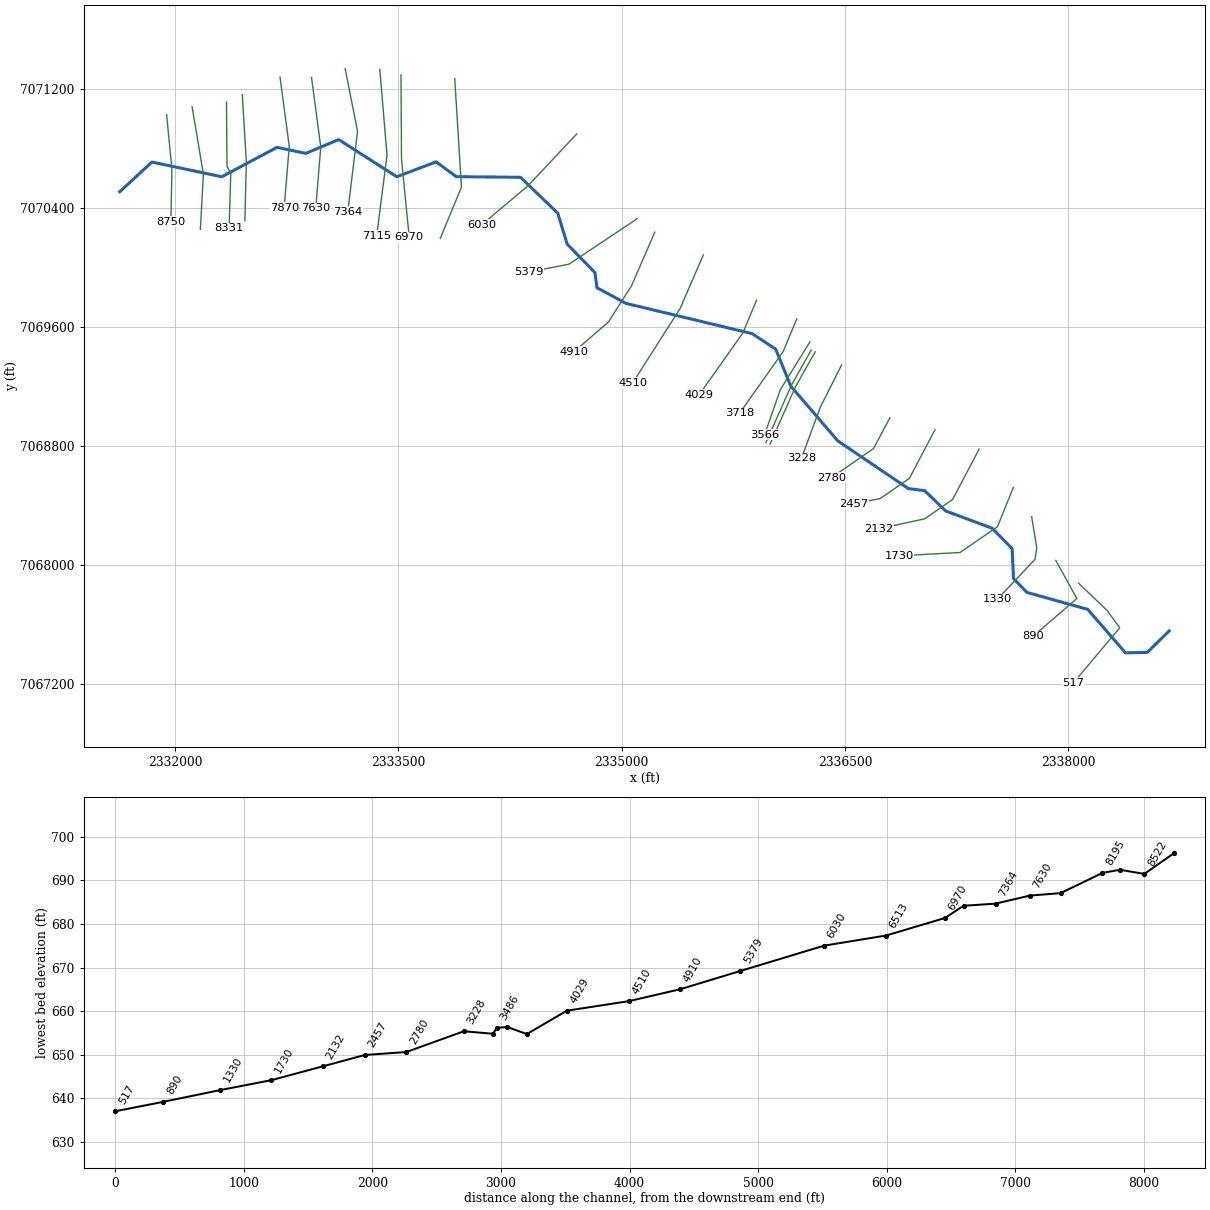
--- Catherine Branch Tr 4.prj (project) ---

Proj Title=Catherine Branch Tr 4 Base Level Engineering
Current Plan=p01
Default Exp/Contr=0.3,0.1
English Units
Geom File=g01
Flow File=f01
Plan File=p01
Y Axis Title=Elevation
X Axis Title(PF)=Main Channel Distance
X Axis Title(XS)=Station
BEGIN DESCRIPTION:
Catherine Branch Tr 4
END DESCRIPTION:
DSS Export Rating Curves= 0
DSS Export Rating Curve Sorted= 0
DSS Export Volume Flow Curves= 0
DXF OffsetX= 0
DXF OffsetY= 0
DXF ScaleX= 1
DXF ScaleY= 10

--- Catherine Branch Tr 4.p01 (plan) ---

Plan Title=Multiple Run
Program Version=4.10
Short Identifier=Multiple
Geom File=g01
Flow File=f01
Subcritical Flow
K Sum by GR= 0
Std Step Tol= 0.01
Critical Tol= 0.01
Num of Std Step Trials= 20
Max Error Tol= 0.3
Flow Tol Ratio= 0.001
Split Flow NTrial= 30
Split Flow Tol= 0.02
Split Flow Ratio= 0.02
Log Output Level= 0
Friction Slope Method= 1
Unsteady Friction Slope Method= 2
Unsteady Bridges Friction Slope Method= 1
Parabolic Critical Depth
Global Vel Dist= 1 , 1 , 1
Global Log Level= 0
CheckData=True
Encroach Param=-1 ,0,0, 0
BEGIN DESCRIPTION:
Multiple Run
END DESCRIPTION:
Computation Interval=1HOUR
Output Interval=1HOUR
Run HTab= 0
Run UNet= 0
Run PostProcess= 0
Run WQNet= 0
UNET Theta= 1
UNET Theta Warmup= 1
UNET ZTol= 0.02
UNET ZSATol= 0.05
UNET MxIter= 20
UNET MaxInSteps= 0
UNET DtIC= 0
UNET DtMin= 0
UNET MaxCRTS= 20
UNET WFStab= 2
UNET SFStab= 1
UNET WFX= 1
UNET SFX= 1
UNET DSS MLevel= 4
UNET DZMax Abort= 100
UNET Convert EG Bridges= 0
UNET Use Existing IB Tables=-1
UNET Froude Reduction=False
UNET Froude Limit= 1
UNET Froude Power= 10
UNET Time Slicing=0,0, 5
UNET Junction Losses=0
Instantaneous Interval=1HOUR
Write IC File= 0
Write IC File at Sim End=0
Echo Input=False
Echo Parameters=False
Echo Output=False
Write Detailed= 0
WQ AD Non Conservative
WQ ULTIMATE=-1
WQ Max Comp Step=1HOUR
WQ Output Interval=15MIN
WQ Output Selected Increments= 0
WQ Output face flow=0
WQ Output face velocity=0
WQ Output face area=0
WQ Output face dispersion=0
WQ Output cell volume=0
WQ Output cell surface area=0
WQ Output cell continuity=0
WQ Output cumulative cell continuity=0
WQ Output face conc=0
WQ Output face dconc_dx=0
WQ Output face courant=0
WQ Output face peclet=0
WQ Output face adv mass=0
WQ Output face disp mass=0
WQ Output cell mass=0
WQ Output cell source sink temp=0
WQ Output cell source sink nsm=0
WQ Output MaxMinRange=-1
WQ Daily Max Min Mean=-1
WQ Daily Range=0
WQ Daily Time=0
WQ Create Restart=0
WQ Fixed Restart=0
WQ System Summary=0
WQ Use Fixed Temperature=0
Sorting and Armoring Iterations= 10
XS Update Threshold= 0.02
Hydraulics Update Threshold= 0.02
Energy Slope Method= 1
Volume Change Method= 0
XS Weighting Method= 0
Number of US Weighted Cross Sections= 1
Number of DS Weighted Cross Sections= 1
Upstream XS Weight=0.25
Main XS Weight=0.5
Downstream XS Weight=0.25
Number of DS XS's Weighted with US Boundary= 1
Upstream Boundary Weight= 1
Weight of XSs Associated with US Boundary= 0
Number of US XS's Weighted with DS Boundary= 1
Downstream Boundary Weight= 0.5
Weight of XSs Associated with DS Boundary= 0.5
Sediment Output Level= 4
Mass or Volume Output= 0
Output Increment Type= 1
Profile and TS Output Increment= 10
XS Output Flag= 0
XS Output Increment= 10
Disregard all LS=0
Disregard all Conn=0
Disregard all Breaches=0
Disregard all Pumps=0

--- Catherine Branch Tr 4.f01 (steady flow) ---

Flow Title=Multiple
Number of Profiles=7
Profile Names=10-year,25-year,50-year,1pct_min,100-year,1pct_plu,500-year
River Rch & RM= Catherine Branch,Reach-1,8750
     334     441     526     312     623    1243     874
River Rch & RM= Catherine Branch,Reach-1,4910
     794    1107    1368     839    1675    3342    2516
River Rch & RM= Catherine Branch,Reach-1,2780
     832    1160    1435     881    1757    3506    2642
Boundary for River Rch & Prof#=Catherine Branch,Reach-1,1
Up Type=0
Dn Type=3
Dn Slope=0.005
Boundary for River Rch & Prof#=Catherine Branch,Reach-1,2
Up Type=0
Dn Type=3
Dn Slope=0.005
Boundary for River Rch & Prof#=Catherine Branch,Reach-1,3
Up Type=0
Dn Type=3
Dn Slope=0.005
Boundary for River Rch & Prof#=Catherine Branch,Reach-1,4
Up Type=0
Dn Type=3
Dn Slope=0.005
Boundary for River Rch & Prof#=Catherine Branch,Reach-1,5
Up Type=0
Dn Type=3
Dn Slope=0.005
Boundary for River Rch & Prof#=Catherine Branch,Reach-1,6
Up Type=0
Dn Type=3
Dn Slope=0.005
Boundary for River Rch & Prof#=Catherine Branch,Reach-1,7
Up Type=0
Dn Type=3
Dn Slope=0.005

--- Catherine Branch Tr 4.g01 (geometry) ---

Geom Title=Existing Conditions

River Reach=Catherine Branch,Reach-1
Reach XY= 30
      2331629.00      7070510.00      2331844.90      7070709.46
      2332313.84      7070610.39      2332684.86      7070807.94
      2332879.00      7070767.56      2333099.18      7070860.29
      2333489.62      7070610.60      2333754.04      7070710.49
      2333889.44      7070611.06      2334320.69      7070606.90
      2334570.84      7070366.05      2334634.54      7070157.58
      2334821.19      7069966.38      2334834.11      7069865.11
      2335029.00      7069760.00      2335877.50      7069556.38
      2336035.33      7069451.96      2336136.86      7069203.83
      2336452.18      7068836.29      2336926.57      7068515.52
      2337035.17      7068502.14      2337176.57      7068365.52
      2337488.79      7068249.48      2337623.54      7068112.45
      2337632.53      7067911.45      2337722.92      7067818.13
      2338131.31      7067704.18      2338384.86      7067412.05
      2338531.70      7067415.35      2338679.00      7067560.00

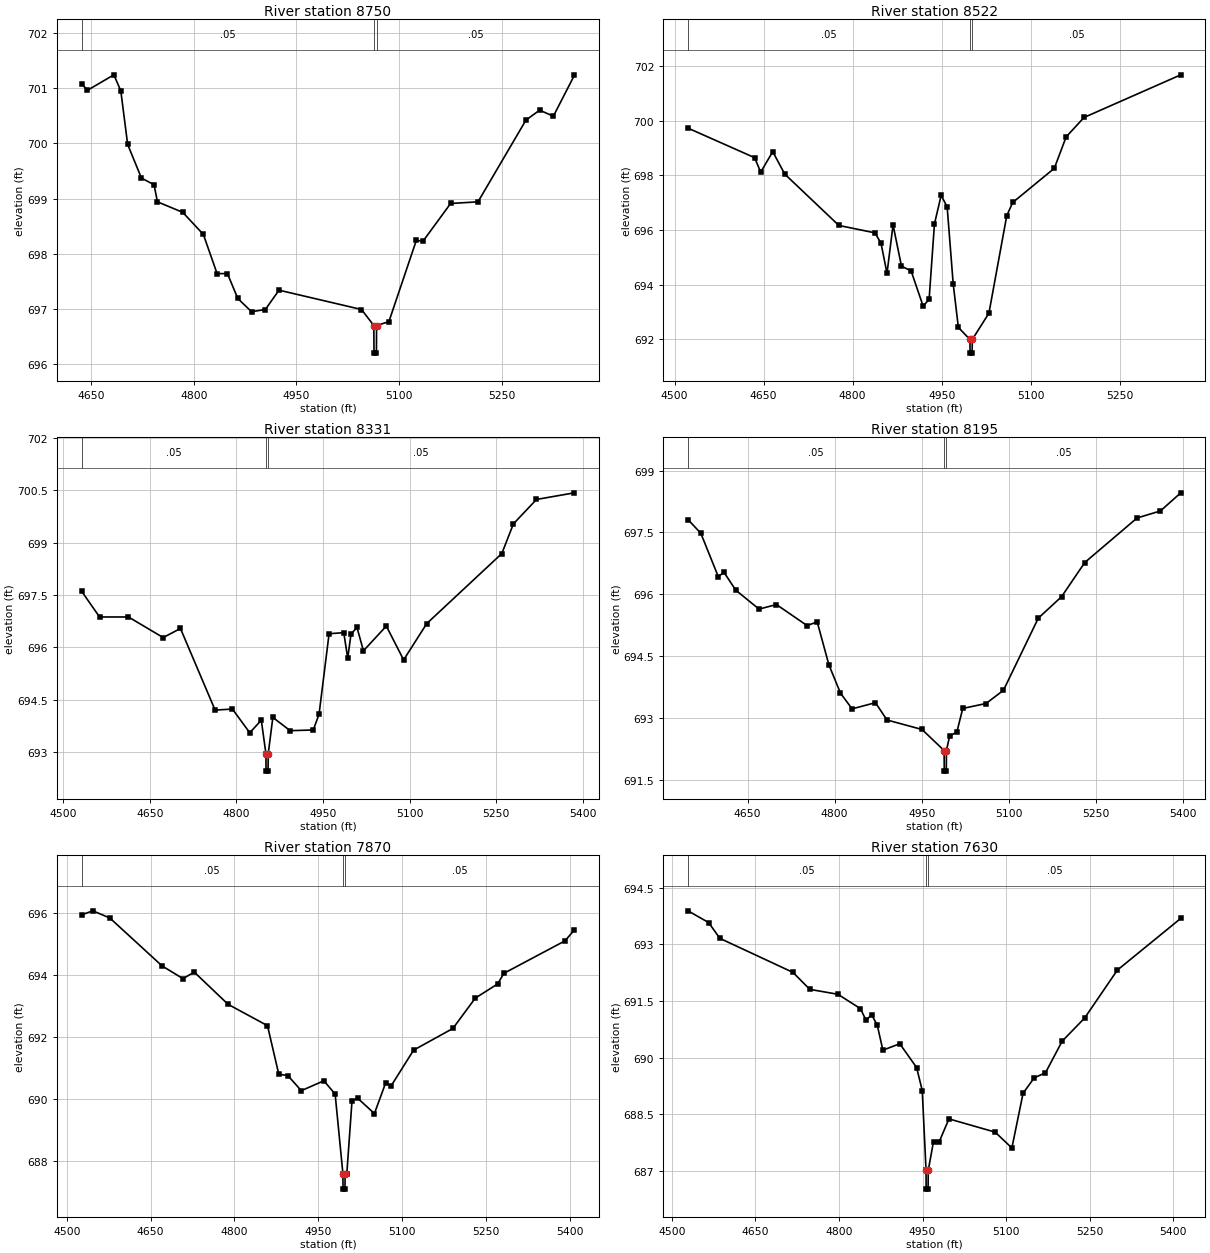
Type RM Length L Ch R = 1,8750,228,228,228
BEGIN DESCRIPTION:
Catherine Branch Tr 4_2 11.0
END DESCRIPTION:
XS GIS Cut Line= 3
      2331943.50      7071027.00      2331979.00      7070660.00
      2331972.02      7070309.39
#Sta/Elev= 30
  4636.2  701.08  4644.8  700.96  4683.4  701.24  4693.5  700.95  4703.5  699.98
  4723.6  699.37  4742.0  699.25  4747.0  698.94  4783.9  698.75  4814.0  698.35
  4834.1  697.64  4849.2  697.64  4864.3  697.19  4884.4  696.95  4904.5  696.99
  4924.5  697.34  5044.9  696.99  5062.9  696.70  5063.2  696.20  5066.7  696.20
  5066.9  696.70  5084.9  696.77  5124.9  698.24  5134.9  698.23  5175.0  698.91
  5215.0  698.94  5285.0  700.42  5305.0  700.60  5325.0  700.49  5355.6  701.23
#Mann=3,-1,0
  4636.2    0.05       0  5062.9    0.04       0  5066.9    0.05       0
Bank Sta=5062.9,5066.9
Exp/Cntr=0.3,0.1

Type RM Length L Ch R = 1,8522,191,191,191
BEGIN DESCRIPTION:
Catherine Branch Tr 4_2 10.0
END DESCRIPTION:
XS GIS Cut Line= 3
      2332114.60      7071080.80      2332190.63      7070627.78
      2332170.04      7070257.11
#Sta/Elev= 30
  4522.5  699.73  4634.7  698.65  4645.0  698.12  4665.3  698.87  4685.5  698.05
  4776.8  696.17  4837.6  695.90  4847.8  695.52  4857.9  694.42  4868.1  696.19
  4882.3  694.68  4898.5  694.51  4918.8  693.22  4928.9  693.47  4937.9  696.23
  4949.2  697.27  4959.3  696.85  4969.5  694.03  4978.2  692.44  4997.7  692.00
  4997.9  691.50  5001.4  691.50  5001.7  692.00  5029.7  692.96  5059.8  696.53
  5069.8  697.01  5139.9  698.26  5159.9  699.41  5190.0  700.12  5353.1  701.68
#Mann=3,-1,0
  4522.5    0.05       0  4997.7   0.033       0  5001.7    0.05       0
Bank Sta=4997.7,5001.7
Exp/Cntr=0.3,0.1

Type RM Length L Ch R = 1,8331,136,136,136
BEGIN DESCRIPTION:
Catherine Branch Tr 4_2 9.5
END DESCRIPTION:
XS GIS Cut Line= 4
      2332345.72      7071111.25      2332349.05      7070680.05
      2332374.39      7070634.11      2332363.09      7070264.56
#Sta/Elev= 30
  4531.7  697.61  4562.9  696.87  4613.0  696.87  4673.0  696.28  4703.0  696.54
  4763.0  694.20  4793.0  694.23  4823.0  693.55  4843.0  693.91  4851.0  692.95
  4851.2  692.45  4854.7  692.45  4855.0  692.95  4863.0  693.99  4893.0  693.61
  4933.0  693.63  4943.0  694.08  4960.4  696.39  4985.8  696.42  4992.7  695.69
  4998.4  696.38  5008.7  696.57  5019.9  695.90  5059.5  696.61  5089.5  695.64
  5129.5  696.68  5259.6  698.69  5279.6  699.54  5319.6  700.24  5385.1  700.43
#Mann=3,-1,0
  4531.7    0.05       0  4851.0   0.033       0  4855.0    0.05       0
Bank Sta=4851,4855
Exp/Cntr=0.3,0.1

Type RM Length L Ch R = 1,8195,325,325,325
BEGIN DESCRIPTION:
Catherine Branch Tr 4_2 9.0
END DESCRIPTION:
XS GIS Cut Line= 3
      2332451.86      7071161.93      2332479.00      7070710.00
      2332469.22      7070314.87
#Sta/Elev= 30
  4547.6  697.81  4569.6  697.48  4599.6  696.43  4609.6  696.53  4629.7  696.10
  4669.8  695.64  4699.8  695.75  4752.5  695.24  4769.9  695.33  4790.0  694.29
  4810.0  693.60  4830.0  693.22  4870.1  693.37  4890.1  692.95  4950.3  692.72
  4988.3  692.21  4988.6  691.71  4992.1  691.71  4992.3  692.21  4997.8  692.56
  5010.3  692.66  5020.4  693.23  5060.4  693.35  5090.4  693.67  5150.4  695.42
  5190.4  695.94  5230.4  696.77  5320.4  697.85  5360.5  698.02  5395.6  698.46
#Mann=3,-1,0
  4547.6    0.05       0  4988.3    0.04       0  4992.3    0.05       0
Bank Sta=4988.3,4992.3
Exp/Cntr=0.3,0.1

Type RM Length L Ch R = 1,7870,240,240,240
BEGIN DESCRIPTION:
Catherine Branch Tr 4_2 8.5
END DESCRIPTION:
XS GIS Cut Line= 3
      2332705.33      7071280.03      2332767.19      7070813.47
      2332733.25      7070403.32
#Sta/Elev= 30
  4526.3  695.95  4546.5  696.08  4576.8  695.85  4670.5  694.30  4707.9  693.89
  4728.1  694.10  4788.6  693.06  4859.2  692.37  4879.4  690.80  4895.6  690.76
  4919.7  690.27  4960.1  690.59  4980.3  690.16  4994.2  687.59  4994.4  687.09
  4997.9  687.09  4998.2  687.59  5001.2  687.59  5010.5  689.94  5020.5  690.03
  5050.6  689.53  5070.7  690.52  5080.7  690.43  5120.8  691.58  5191.1  692.28
  5231.2  693.26  5271.4  693.72  5282.3  694.06  5391.8  695.11  5408.5  695.46
#Mann=3,-1,0
  4526.3    0.05       0  4994.2    0.04       0  4998.2    0.05       0
Bank Sta=4994.2,4998.2
Exp/Cntr=0.3,0.1

Type RM Length L Ch R = 1,7630,266,266,266
BEGIN DESCRIPTION:
Catherine Branch Tr 4_2 8.0
END DESCRIPTION:
XS GIS Cut Line= 3
      2332917.13      7071276.58      2332979.00      7070810.00
      2332944.91      7070398.07
#Sta/Elev= 30
  4529.3  693.89  4566.2  693.58  4586.5  693.16  4717.5  692.26  4747.8  691.81
  4798.2  691.68  4838.6  691.30  4848.7  690.99  4858.7  691.14  4868.8  690.86
  4878.9  690.20  4909.2  690.37  4939.4  689.74  4949.5  689.13  4956.3  687.02
  4956.5  686.52  4960.0  686.52  4960.3  687.02  4969.7  687.78  4979.8  687.77
  4997.4  688.38  5080.2  688.03  5110.3  687.61  5130.4  689.06  5150.5  689.47
  5170.5  689.60  5200.6  690.44  5240.8  691.05  5299.5  692.32  5413.3  693.69
#Mann=3,-1,0
  4529.3    0.05       0  4956.3    0.04       0  4960.3    0.05       0
Bank Sta=4956.3,4960.3
Exp/Cntr=0.3,0.1

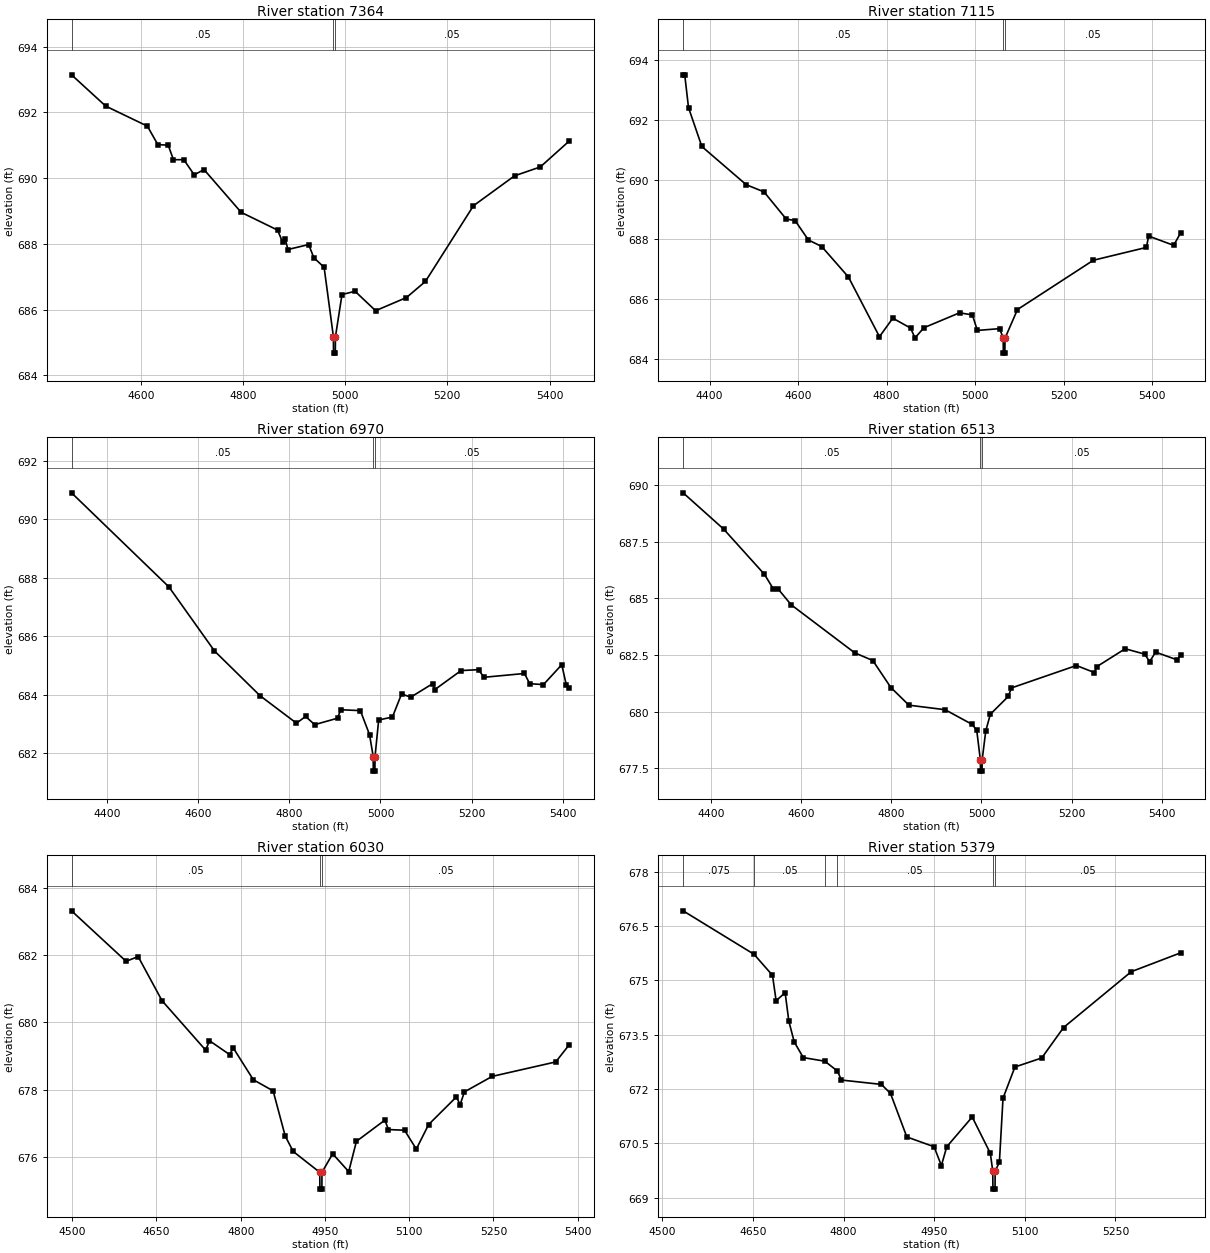
Type RM Length L Ch R = 1,7364,249,249,249
BEGIN DESCRIPTION:
Catherine Branch Tr 4_2 7.0
END DESCRIPTION:
XS GIS Cut Line= 3
      2333142.84      7071335.54      2333226.16      7070915.45
      2333160.27      7070374.43
#Sta/Elev= 30
  4464.6  693.14  4531.4  692.19  4613.0  691.58  4633.4  691.02  4653.8  691.00
  4664.0  690.56  4684.3  690.56  4704.7  690.10  4723.8  690.26  4796.5  688.96
  4867.8  688.42  4877.4  688.06  4882.5  688.16  4888.0  687.83  4928.6  687.98
  4938.7  687.58  4958.8  687.29  4977.0  685.18  4977.2  684.68  4980.7  684.68
  4981.0  685.18  4993.8  686.46  5019.3  686.56  5059.6  685.97  5120.0  686.37
  5157.1  686.86  5251.0  689.16  5331.5  690.07  5381.9  690.34  5437.9  691.12
#Mann=3,-1,0
  4464.6    0.05       0  4977.0    0.04       0  4981.0    0.05       0
Bank Sta=4977,4981
Exp/Cntr=0.3,0.1

Type RM Length L Ch R = 1,7115,145,145,145
BEGIN DESCRIPTION:
Catherine Branch Tr 4_2 6.0
END DESCRIPTION:
XS GIS Cut Line= 3
      2333375.46      7071332.13      2333424.08      7070755.73
      2333354.69      7070214.51
#Sta/Elev= 30
  4340.3  693.51  4343.9  693.51  4352.5  692.41  4382.6  691.11  4482.9  689.83
  4523.1  689.59  4573.3  688.68  4593.3  688.63  4623.4  687.98  4653.5  687.76
  4713.8  686.74  4784.0  684.74  4814.1  685.36  4854.2  685.03  4864.3  684.70
  4884.4  685.04  4964.9  685.54  4994.0  685.47  5005.2  684.95  5055.6  685.01
  5063.7  684.69  5063.9  684.19  5067.4  684.19  5067.7  684.69  5095.9  685.65
  5267.3  687.30  5387.2  687.73  5392.3  688.11  5448.8  687.80  5464.4  688.21
#Mann=3,-1,0
  4340.3    0.05       0  5063.7    0.04       0  5067.7    0.05       0
Bank Sta=5063.7,5067.7
Exp/Cntr=0.3,0.1

Type RM Length L Ch R = 1,6970,457,457,457
BEGIN DESCRIPTION:
Catherine Branch Tr 4_2 5.0
END DESCRIPTION:
XS GIS Cut Line= 3
      2333517.83      7071293.89      2333521.30      7070727.95
      2333573.32      7070204.28
#Sta/Elev= 30
  4321.7  690.90  4535.6  687.68  4635.6  685.49  4735.6  683.96  4815.6  683.02
  4835.6  683.25  4855.6  682.97  4905.7  683.19  4912.8  683.48  4955.9  683.45
  4976.0  682.63  4984.1  681.88  4984.3  681.38  4987.8  681.38  4988.1  681.88
  4996.1  683.13  5026.3  683.23  5046.4  684.02  5066.5  683.91  5114.5  684.37
  5119.5  684.17  5177.0  684.82  5215.3  684.85  5227.3  684.59  5316.2  684.72
  5327.8  684.37  5357.9  684.34  5398.1  685.02  5408.2  684.32  5413.9  684.24
#Mann=3,-1,0
  4321.7    0.05       0  4984.1   0.033       0  4988.1    0.05       0
Bank Sta=4984.1,4988.1
Exp/Cntr=0.3,0.1

Type RM Length L Ch R = 1,6513,483,483,483
BEGIN DESCRIPTION:
Catherine Branch Tr 4_2 4.0
END DESCRIPTION:
XS GIS Cut Line= 3
      2333878.94      7071269.65      2333924.08      7070540.45
      2333781.70      7070196.67
#Sta/Elev= 30
  4338.6  689.65  4428.4  688.05  4518.6  686.06  4538.6  685.41  4548.7  685.42
  4578.1  684.71  4719.0  682.59  4759.1  682.25  4799.1  681.06  4839.2  680.28
  4919.4  680.08  4979.5  679.43  4989.5  679.17  4997.5  677.87  4997.8  677.37
  5001.3  677.37  5001.5  677.87  5009.5  679.14  5019.6  679.88  5059.6  680.67
  5066.3  681.04  5210.4  682.03  5250.3  681.72  5255.7  681.98  5318.6  682.77
  5362.1  682.53  5372.7  682.20  5386.0  682.62  5433.8  682.28  5441.3  682.51
#Mann=3,-1,0
  4338.6    0.05       0  4997.5   0.033       0  5001.5    0.05       0
Bank Sta=4997.5,5001.5
Exp/Cntr=0.3,0.1

Type RM Length L Ch R = 1,6030,651,651,651
BEGIN DESCRIPTION:
Catherine Branch Tr 4_2 3.0
END DESCRIPTION:
XS GIS Cut Line= 3
      2334698.38      7070898.08      2334371.99      7070550.87
      2334059.46      7070286.95
#Sta/Elev= 30
  4498.8  683.31  4595.9  681.81  4617.4  681.95  4659.9  680.64  4737.6  679.17
  4744.4  679.45  4780.1  679.04  4786.9  679.23  4822.5  678.29  4857.7  677.96
  4879.2  676.62  4893.4  676.16  4940.7  675.54  4941.0  675.04  4944.5  675.04
  4944.7  675.54  4963.7  676.09  4992.3  675.56  5006.0  676.46  5056.6  677.09
  5063.1  676.81  5091.7  676.79  5112.6  676.23  5134.6  676.96  5184.0  677.78
  5190.6  677.55  5198.3  677.93  5247.7  678.39  5360.9  678.82  5384.4  679.32
#Mann=3,-1,0
  4498.8    0.05       0  4940.7    0.04       0  4944.7    0.05       0
Bank Sta=4940.7,4944.7
Exp/Cntr=0.3,0.1

Type RM Length L Ch R = 1,5379,469,469,469
BEGIN DESCRIPTION:
Catherine Branch Tr 4_2 2.0
END DESCRIPTION:
XS GIS Cut Line= 3
      2335104.61      7070328.63      2334646.30      7070023.09
      2334378.94      7069971.01
#Sta/Elev= 30
  4534.5  676.92  4651.9  675.72  4682.4  675.14  4688.4  674.44  4703.3  674.66
  4709.5  673.87  4718.4  673.30  4733.4  672.87  4769.0  672.77  4789.8  672.50
  4796.5  672.25  4862.6  672.13  4877.7  671.88  4904.7  670.68  4949.8  670.41
  4961.9  669.89  4970.8  670.41  5012.9  671.23  5042.9  670.23  5046.9  669.74
  5047.2  669.24  5050.7  669.24  5050.9  669.74  5057.9  669.98  5063.9  671.75
  5083.6  672.61  5128.0  672.86  5164.1  673.70  5276.1  675.24  5357.7  675.76
#Mann=6,-1,0
  4534.5   0.075       0  4651.9    0.05       0  4769.0   0.075       0
  4789.8    0.05       0  5046.9   0.033       0  5050.9    0.05       0
Bank Sta=5046.9,5050.9
Exp/Cntr=0.3,0.1

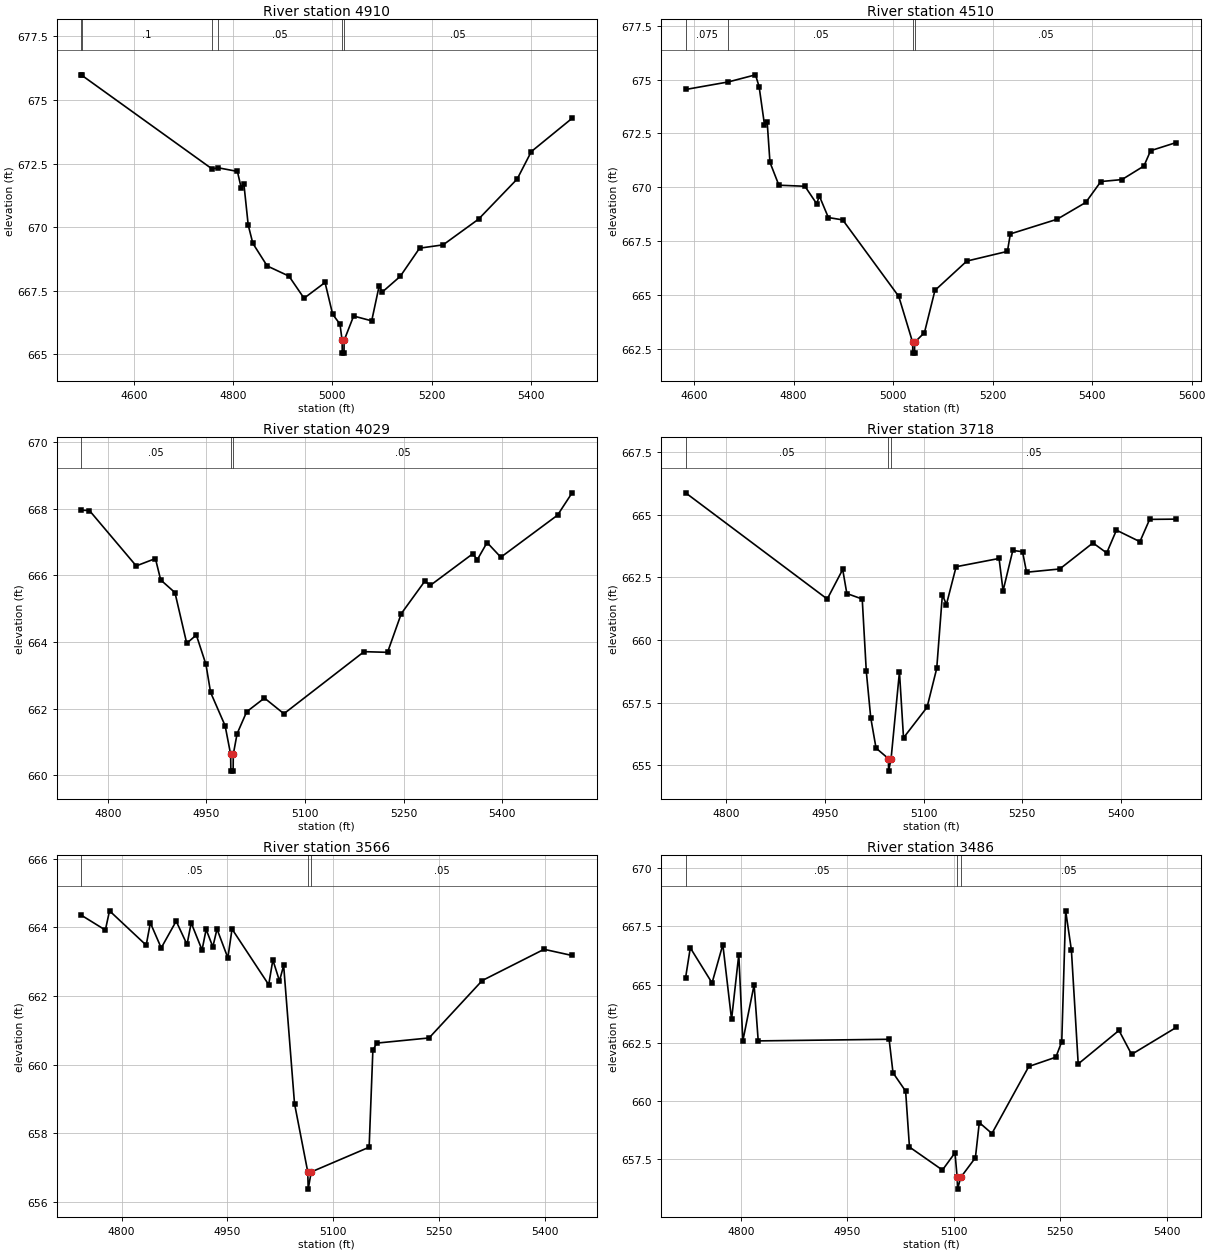
Type RM Length L Ch R = 1,4910,400,400,400
BEGIN DESCRIPTION:
Catherine Branch Tr 4_2 1.4
END DESCRIPTION:
XS GIS Cut Line= 4
      2335222.69      7070238.37      2335066.85      7069878.40
      2334911.19      7069634.52      2334678.80      7069433.89
#Sta/Elev= 30
  4494.7  675.99  4495.5  675.97  4757.7  672.29  4770.8  672.33  4808.9  672.19
  4816.5  671.55  4821.9  671.71  4830.7  670.08  4840.0  669.36  4868.9  668.47
  4912.8  668.07  4943.2  667.20  4985.5  667.82  5000.8  666.57  5015.6  666.18
  5019.9  665.54  5020.2  665.04  5023.7  665.04  5023.9  665.54  5043.1  666.50
  5079.5  666.31  5094.7  667.70  5100.6  667.44  5137.0  668.06  5176.0  669.17
  5223.4  669.30  5294.7  670.31  5372.6  671.89  5401.1  672.97  5483.3  674.28
#Mann=6,-1,0
  4494.7   0.075       0  4495.5     0.1       0  4757.7   0.075       0
  4770.8    0.05       0  5019.9   0.033       0  5023.9    0.05       0
Bank Sta=5019.9,5023.9
Exp/Cntr=0.3,0.1

Type RM Length L Ch R = 1,4510,481,481,481
BEGIN DESCRIPTION:
Catherine Branch Tr 4_2 1.0
END DESCRIPTION:
XS GIS Cut Line= 3
      2335549.07      7070085.57      2335393.24      7069725.63
      2335073.84      7069225.19
#Sta/Elev= 30
  4583.2  674.54  4668.9  674.89  4723.6  675.22  4730.9  674.67  4741.7  672.90
  4747.1  673.03  4752.7  671.16  4770.6  670.10  4823.0  670.05  4846.5  669.24
  4851.9  669.60  4870.0  668.60  4898.9  668.49  5011.5  664.94  5039.4  662.81
  5039.7  662.31  5043.2  662.31  5043.4  662.81  5063.1  663.26  5084.2  665.22
  5148.2  666.58  5229.8  667.03  5235.7  667.84  5329.6  668.52  5387.2  669.30
  5417.6  670.27  5459.9  670.36  5504.1  670.99  5517.5  671.70  5569.1  672.08
#Mann=4,-1,0
  4583.2   0.075       0  4668.9    0.05       0  5039.4   0.033       0
  5043.4    0.05       0
Bank Sta=5039.4,5043.4
Exp/Cntr=0.3,0.1

Type RM Length L Ch R = 1,4029,311,311,311
BEGIN DESCRIPTION:
Catherine Branch Tr 4 11.0
END DESCRIPTION:
XS GIS Cut Line= 3
      2335906.41      7069781.18      2335814.14      7069560.62
      2335521.51      7069146.45
#Sta/Elev= 30
  4760.0  667.95  4772.1  667.94  4843.3  666.28  4872.5  666.50  4880.5  665.86
  4902.2  665.48  4920.1  663.96  4934.7  664.21  4949.3  663.33  4956.4  662.49
  4978.5  661.49  4986.9  660.63  4987.2  660.13  4990.7  660.13  4990.9  660.63
  4996.7  661.25  5011.3  661.91  5038.3  662.32  5067.9  661.85  5189.8  663.71
  5225.5  663.69  5246.4  664.85  5282.1  665.82  5290.8  665.70  5354.9  666.64
  5362.1  666.47  5376.9  666.98  5397.8  666.54  5484.0  667.80  5506.2  668.47
#Mann=3,-1,0
  4760.0    0.05       0  4986.9   0.033       0  4990.9    0.05       0
Bank Sta=4986.9,4990.9
Exp/Cntr=0.3,0.1

Type RM Length L Ch R = 1,3718,152,152,152
BEGIN DESCRIPTION:
Catherine Branch Tr 4 10.0
END DESCRIPTION:
XS GIS Cut Line= 3
      2336176.53      7069655.17      2336084.24      7069434.58
      2335791.64      7069020.43
#Sta/Elev= 30
  4738.2  665.88  4953.6  661.64  4977.1  662.82  4983.4  661.86  5006.8  661.64
  5013.0  658.75  5019.7  656.91  5027.8  655.69  5046.6  655.27  5046.9  654.77
  5050.7  655.27  5063.4  658.73  5069.6  656.10  5105.4  657.32  5120.1  658.87
  5128.7  661.81  5134.8  661.42  5149.6  662.93  5214.9  663.26  5221.0  661.97
  5235.8  663.58  5250.6  663.53  5256.7  662.71  5307.2  662.84  5357.7  663.88
  5378.6  663.48  5393.4  664.39  5429.1  663.93  5443.9  664.82  5484.4  664.83
#Mann=3,-1,0
  4738.2    0.05       0  5046.6   0.033       0  5050.7    0.05       0
Bank Sta=5046.6,5050.7
Exp/Cntr=0.3,0.1

Type RM Length L Ch R = 1,3566,80,80,80
BEGIN DESCRIPTION:
Catherine Branch Tr 4 9.0
END DESCRIPTION:
XS GIS Cut Line= 3
      2336264.32      7069499.87      2336066.23      7069180.23
      2335960.43      7068878.59
#Sta/Elev= 30
  4743.2  664.35  4777.1  663.92  4783.0  664.48  4835.0  663.48  4840.9  664.13
  4856.3  663.40  4877.5  664.18  4892.9  663.50  4898.8  664.13  4914.2  663.34
  4920.0  663.94  4929.5  663.43  4935.4  663.95  4950.8  663.11  4956.7  663.95
  5008.7  662.33  5014.6  663.05  5024.0  662.44  5029.9  662.89  5045.3  658.87
  5064.1  656.88  5064.7  656.38  5069.0  656.88  5151.1  657.60  5156.4  660.42
  5161.9  660.63  5236.1  660.78  5311.4  662.45  5399.1  663.36  5438.9  663.18
#Mann=3,-1,0
  4743.2    0.05       0  5064.1   0.033       0  5069.0    0.05       0
Bank Sta=5064.1,5069
Exp/Cntr=0.3,0.1

Type RM Length L Ch R = 1,3486,32,32,32
BEGIN DESCRIPTION:
Catherine Branch Tr 4 8.0
END DESCRIPTION:
XS GIS Cut Line= 3
      2336273.29      7069445.79      2336140.51      7069209.49
      2335969.55      7068824.82
#Sta/Elev= 30
  4721.7  665.30  4728.3  666.58  4759.0  665.07  4774.2  666.72  4786.5  663.50
  4796.7  666.29  4802.4  662.58  4818.3  664.99  4824.1  662.58  5008.7  662.65
  5014.2  661.21  5032.0  660.42  5037.4  658.02  5083.9  657.03  5101.6  657.77
  5104.7  656.71  5105.3  656.21  5109.6  656.71  5130.4  657.56  5135.9  659.07
  5153.7  658.60  5205.7  661.48  5243.9  661.88  5252.2  662.55  5257.7  668.17
  5265.8  666.48  5275.4  661.59  5332.9  663.03  5350.7  662.00  5413.7  663.16
#Mann=3,-1,0
  4721.7    0.05       0  5104.7   0.033       0  5109.6    0.05       0
Bank Sta=5104.7,5109.6
Exp/Cntr=0.3,0.1

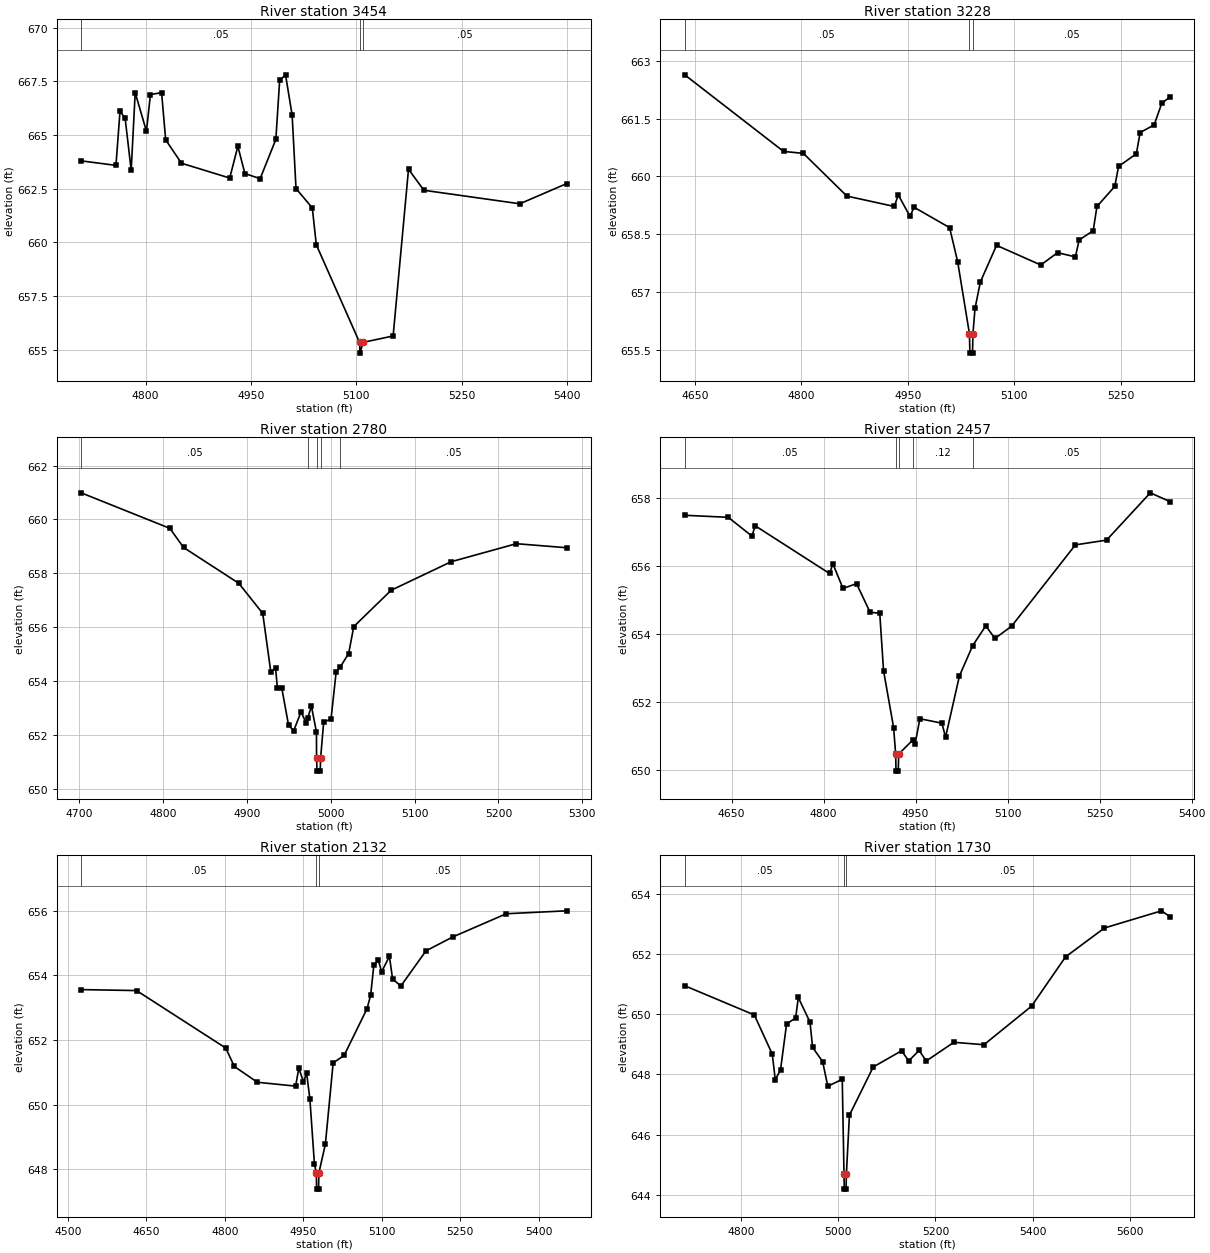
Type RM Length L Ch R = 1,3454,226,226,226
BEGIN DESCRIPTION:
Catherine Branch Tr 4 7.0
END DESCRIPTION:
XS GIS Cut Line= 3
      2336300.30      7069434.53      2336167.52      7069198.23
      2335996.84      7068814.20
#Sta/Elev= 30
  4708.2  663.80  4757.7  663.59  4763.5  666.12  4770.8  665.78  4779.4  663.36
  4785.1  666.98  4801.1  665.18  4806.8  666.89  4822.7  666.98  4828.5  664.78
  4851.0  663.69  4919.7  663.00  4931.3  664.48  4941.3  663.21  4963.0  662.97
  4985.4  664.80  4990.8  667.55  4999.2  667.81  5008.6  665.93  5014.1  662.51
  5037.3  661.61  5043.0  659.89  5104.6  655.34  5105.2  654.84  5109.5  655.34
  5152.4  655.64  5174.3  663.41  5196.2  662.43  5332.8  661.80  5399.5  662.74
#Mann=3,-1,0
  4708.2    0.05       0  5104.6   0.033       0  5109.5    0.05       0
Bank Sta=5104.6,5109.5
Exp/Cntr=0.3,0.1

Type RM Length L Ch R = 1,3228,448,448,448
BEGIN DESCRIPTION:
Catherine Branch Tr 4 6.0
END DESCRIPTION:
XS GIS Cut Line= 3
      2336478.13      7069346.77      2336334.09      7069060.93
      2336208.04      7068718.80
#Sta/Elev= 30
  4635.3  662.64  4774.7  660.65  4802.6  660.60  4864.0  659.49  4930.9  659.22
  4936.5  659.52  4953.1  658.96  4958.7  659.20  5008.9  658.67  5020.3  657.78
  5036.9  655.91  5037.5  655.41  5041.2  655.41  5041.8  655.91  5044.7  656.57
  5052.3  657.26  5075.1  658.21  5137.5  657.70  5161.2  658.02  5186.3  657.91
  5191.6  658.35  5211.4  658.59  5216.7  659.22  5241.8  659.74  5247.2  660.26
  5272.3  660.59  5277.6  661.14  5297.4  661.34  5308.1  661.90  5320.0  662.07
#Mann=3,-1,0
  4635.3    0.05       0  5036.9    0.05       0  5041.8    0.05       0
Bank Sta=5036.9,5041.8
Exp/Cntr=0.3,0.1

Type RM Length L Ch R = 1,2780,323,323,323
BEGIN DESCRIPTION:
Catherine Branch Tr 4 5.0
END DESCRIPTION:
XS GIS Cut Line= 3
      2336802.26      7068991.14      2336691.97      7068784.08
      2336408.40      7068588.28
#Sta/Elev= 30
  4702.2  660.99  4808.0  659.67  4824.3  658.96  4890.2  657.63  4918.8  656.51
  4928.5  654.32  4934.1  654.49  4936.3  653.72  4941.6  653.72  4949.6  652.36
  4955.7  652.15  4964.5  652.85  4970.6  652.44  4972.4  652.62  4976.9  653.06
  4982.9  652.10  4983.0  651.15  4983.6  650.65  4987.3  650.65  4987.9  651.15
  4991.5  652.47  5000.3  652.59  5006.4  654.34  5011.5  654.53  5021.3  655.02
  5027.4  656.02  5072.0  657.37  5143.6  658.43  5221.4  659.10  5281.4  658.95
#Mann=5,-1,0
  4702.2    0.05       0  4972.4    0.12       0  4983.0    0.07       0
  4987.9    0.12       0  5011.5    0.05       0
Bank Sta=4983,4987.9
Exp/Cntr=0.3,0.1

Type RM Length L Ch R = 1,2457,325,325,325
BEGIN DESCRIPTION:
Catherine Branch Tr 4 4.0
END DESCRIPTION:
XS GIS Cut Line= 4
      2337105.14      7068911.40      2336932.82      7068583.75
      2336736.54      7068448.22      2336557.17      7068414.13
#Sta/Elev= 30
  4573.7  657.49  4644.7  657.43  4683.1  656.88  4688.7  657.18  4809.7  655.78
  4815.3  656.06  4831.7  655.34  4853.8  655.48  4875.8  654.64  4891.6  654.61
  4897.8  652.92  4914.2  651.25  4917.5  650.47  4918.1  649.97  4921.8  649.97
  4922.4  650.47  4945.2  650.88  4949.3  650.78  4957.0  651.51  4992.8  651.38
  4998.9  650.97  5021.5  652.77  5043.1  653.66  5064.4  654.24  5079.3  653.87
  5106.5  654.23  5210.5  656.62  5261.3  656.76  5332.6  658.15  5365.0  657.89
#Mann=5,-1,0
  4573.7    0.05       0  4917.5    0.07       0  4922.4    0.05       0
  4945.2    0.12       0  5043.1    0.05       0
Bank Sta=4917.5,4922.4
Exp/Cntr=0.3,0.1

Type RM Length L Ch R = 1,2132,402,402,402
BEGIN DESCRIPTION:
Catherine Branch Tr 4 3.0
END DESCRIPTION:
XS GIS Cut Line= 4
      2337402.03      7068781.04      2337223.18      7068441.94
      2337035.94      7068312.66      2336726.22      7068245.18
#Sta/Elev= 30
  4525.5  653.56  4631.3  653.53  4801.8  651.75  4818.2  651.18  4862.2  650.69
  4935.4  650.57  4941.5  651.13  4950.3  650.70  4956.4  650.97  4962.6  650.18
  4971.3  648.16  4974.9  647.88  4975.5  647.38  4979.2  647.38  4979.8  647.88
  4992.2  648.77  5007.1  651.29  5028.0  651.52  5071.9  652.97  5078.8  653.39
  5084.8  654.31  5093.6  654.47  5099.7  654.11  5114.6  654.59  5120.7  653.89
  5136.4  653.67  5184.5  654.76  5235.6  655.19  5338.0  655.91  5453.4  656.00
#Mann=3,-1,0
  4525.5    0.05       0  4974.9   0.033       0  4979.8    0.05       0
Bank Sta=4974.9,4979.8
Exp/Cntr=0.3,0.1

Type RM Length L Ch R = 1,1730,400,400,400
BEGIN DESCRIPTION:
Catherine Branch Tr 4 2.0
END DESCRIPTION:
XS GIS Cut Line= 4
      2337631.33      7068522.76      2337524.79      7068259.62
      2337273.79      7068086.31      2336863.90      7068064.15
#Sta/Elev= 30
  4683.8  650.95  4827.0  649.98  4864.0  648.68  4870.2  647.83  4881.0  648.15
  4893.5  649.68  4912.2  649.88  4917.6  650.56  4941.7  649.74  4947.1  648.90
  4967.7  648.43  4978.3  647.61  5008.1  647.84  5011.7  644.69  5012.3  644.19
  5016.0  644.19  5016.6  644.69  5022.9  646.65  5071.9  648.25  5130.4  648.79
  5144.9  648.45  5166.3  648.80  5181.1  648.45  5237.9  649.07  5299.8  648.99
  5397.7  650.27  5467.8  651.91  5547.9  652.87  5665.3  653.44  5683.2  653.24
#Mann=3,-1,0
  4683.8    0.05       0  5011.7   0.033       0  5016.6    0.05       0
Bank Sta=5011.7,5016.6
Exp/Cntr=0.3,0.1

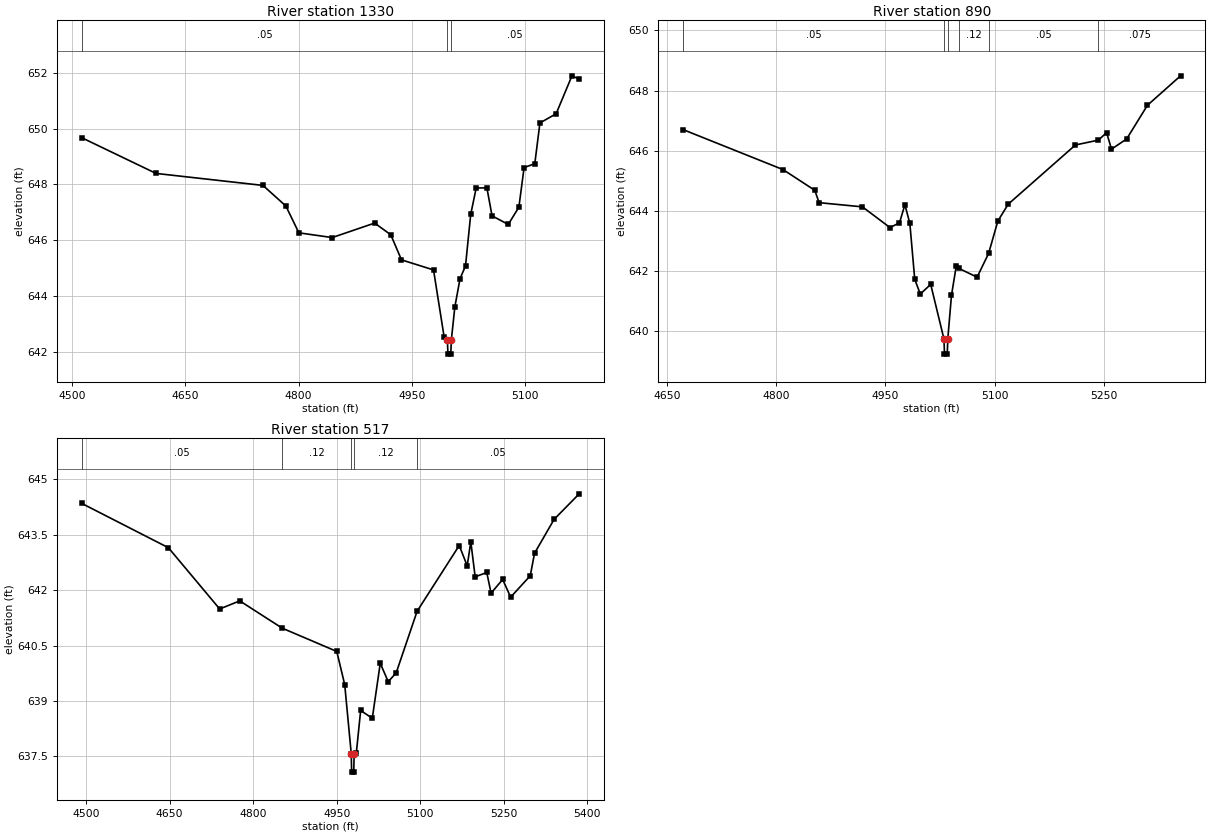
Type RM Length L Ch R = 1,1330,440,440,440
BEGIN DESCRIPTION:
Catherine Branch Tr 4 1.4
END DESCRIPTION:
XS GIS Cut Line= 4
      2337754.43      7068327.24      2337788.80      7068117.16
      2337777.40      7068040.83      2337523.76      7067771.93
#Sta/Elev= 30
  4512.5  649.67  4611.0  648.39  4752.8  647.96  4783.2  647.22  4800.4  646.26
  4844.6  646.09  4900.9  646.61  4922.3  646.19  4936.5  645.29  4979.0  644.93
  4993.1  642.52  4997.4  642.41  4998.1  641.91  5001.9  641.91  5002.6  642.41
  5007.3  643.61  5014.2  644.62  5021.4  645.07  5028.3  646.92  5035.6  647.87
  5049.8  647.87  5056.6  646.87  5078.1  646.56  5092.2  647.18  5099.1  648.60
  5113.3  648.74  5120.1  650.20  5141.6  650.53  5162.6  651.89  5172.2  651.77
#Mann=3,-1,0
  4512.5    0.05       0  4997.4   0.033       0  5002.6    0.05       0
Bank Sta=4997.4,5002.6
Exp/Cntr=0.3,0.1

Type RM Length L Ch R = 1,890,373,373,373
BEGIN DESCRIPTION:
Catherine Branch Tr 4 1.2
END DESCRIPTION:
XS GIS Cut Line= 3
      2337916.77      7068033.18      2338058.02      7067777.40
      2337763.06      7067522.40
#Sta/Elev= 30
  4672.5  646.70  4809.5  645.37  4853.1  644.68  4858.9  644.27  4918.4  644.13
  4956.2  643.44  4969.2  643.60  4976.6  644.20  4983.4  643.58  4990.1  641.72
  4997.7  641.23  5012.0  641.55  5030.2  639.73  5030.9  639.23  5034.7  639.23
  5035.4  639.73  5040.5  641.19  5047.1  642.17  5050.9  642.08  5075.6  641.79
  5091.4  642.58  5104.1  643.66  5118.3  644.22  5210.5  646.19  5241.9  646.35
  5253.2  646.60  5259.9  646.05  5280.7  646.39  5309.2  647.51  5354.6  648.49
#Mann=6,-1,0
  4672.5    0.05       0  5030.2   0.033       0  5035.4    0.05       0
  5050.9    0.12       0  5091.4    0.05       0  5241.9   0.075       0
Bank Sta=5030.2,5035.4
Exp/Cntr=0.3,0.1

Type RM Length L Ch R = 1,517,0,0,0
BEGIN DESCRIPTION:
Catherine Branch Tr 4 1.0
END DESCRIPTION:
XS GIS Cut Line= 4
      2338069.51      7067880.45      2338262.34      7067695.87
      2338346.27      7067580.77      2338035.11      7067210.43
#Sta/Elev= 30
  4492.4  644.35  4647.9  643.15  4740.0  641.49  4776.0  641.71  4852.3  640.97
  4950.2  640.34  4964.5  639.44  4976.2  637.57  4976.9  637.07  4980.7  637.07
  4981.4  637.57  4985.4  637.60  4993.1  638.74  5014.0  638.53  5028.3  640.02
  5042.6  639.52  5056.9  639.76  5094.5  641.43  5170.1  643.21  5184.4  642.66
  5190.9  643.31  5198.7  642.36  5219.5  642.48  5227.3  641.92  5248.1  642.29
  5262.4  641.81  5297.6  642.39  5305.3  643.00  5340.5  643.92  5385.5  644.61
#Mann=5,-1,0
  4492.4    0.05       0  4852.3    0.12       0  4976.2    0.07       0
  4981.4    0.12       0  5094.5    0.05       0
Bank Sta=4976.2,4981.4
Exp/Cntr=0.3,0.1

Chan Stop Cuts=-1