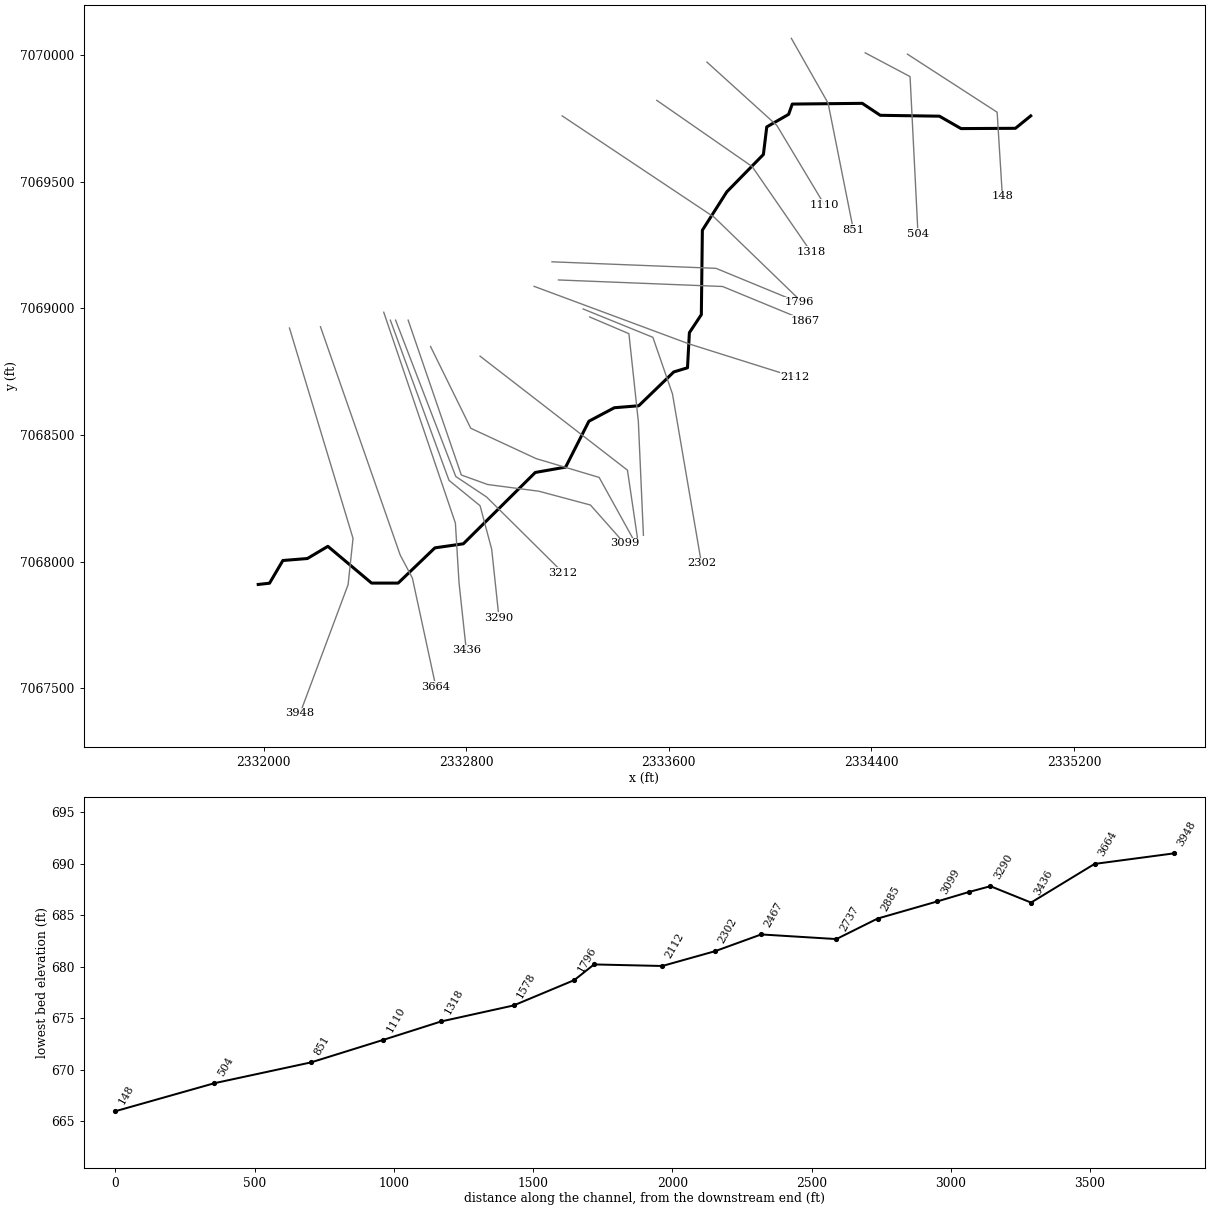
--- Catherine Branch Tr 4_3.prj (project) ---

Proj Title=Catherine Branch Tr 4_3 Base Level Engineering
Current Plan=p01
Default Exp/Contr=0.3,0.1
English Units
Geom File=g01
Flow File=f01
Plan File=p01
Y Axis Title=Elevation
X Axis Title(PF)=Main Channel Distance
X Axis Title(XS)=Station
BEGIN DESCRIPTION:
Catherine Branch Tr 4_3
END DESCRIPTION:
DSS Export Rating Curves= 0
DSS Export Rating Curve Sorted= 0
DSS Export Volume Flow Curves= 0
DXF OffsetX= 0
DXF OffsetY= 0
DXF ScaleX= 1
DXF ScaleY= 10

--- Catherine Branch Tr 4_3.p01 (plan) ---

Plan Title=Multiple Run
Program Version=4.10
Short Identifier=Multiple
Geom File=g01
Flow File=f01
Subcritical Flow
K Sum by GR= 0
Std Step Tol= 0.01
Critical Tol= 0.01
Num of Std Step Trials= 20
Max Error Tol= 0.3
Flow Tol Ratio= 0.001
Split Flow NTrial= 30
Split Flow Tol= 0.02
Split Flow Ratio= 0.02
Log Output Level= 0
Friction Slope Method= 1
Unsteady Friction Slope Method= 2
Unsteady Bridges Friction Slope Method= 1
Parabolic Critical Depth
Global Vel Dist= 1 , 1 , 1
Global Log Level= 0
CheckData=True
Encroach Param=-1 ,0,0, 0
BEGIN DESCRIPTION:
Multiple Run
END DESCRIPTION:
Computation Interval=1HOUR
Output Interval=1HOUR
Run HTab= 0
Run UNet= 0
Run PostProcess= 0
Run WQNet= 0
UNET Theta= 1
UNET Theta Warmup= 1
UNET ZTol= 0.02
UNET ZSATol= 0.05
UNET MxIter= 20
UNET MaxInSteps= 0
UNET DtIC= 0
UNET DtMin= 0
UNET MaxCRTS= 20
UNET WFStab= 2
UNET SFStab= 1
UNET WFX= 1
UNET SFX= 1
UNET DSS MLevel= 4
UNET DZMax Abort= 100
UNET Convert EG Bridges= 0
UNET Use Existing IB Tables=-1
UNET Froude Reduction=False
UNET Froude Limit= 1
UNET Froude Power= 10
UNET Time Slicing=0,0, 5
UNET Junction Losses=0
Instantaneous Interval=1HOUR
Write IC File= 0
Write IC File at Sim End=0
Echo Input=False
Echo Parameters=False
Echo Output=False
Write Detailed= 0
WQ AD Non Conservative
WQ ULTIMATE=-1
WQ Max Comp Step=1HOUR
WQ Output Interval=15MIN
WQ Output Selected Increments= 0
WQ Output face flow=0
WQ Output face velocity=0
WQ Output face area=0
WQ Output face dispersion=0
WQ Output cell volume=0
WQ Output cell surface area=0
WQ Output cell continuity=0
WQ Output cumulative cell continuity=0
WQ Output face conc=0
WQ Output face dconc_dx=0
WQ Output face courant=0
WQ Output face peclet=0
WQ Output face adv mass=0
WQ Output face disp mass=0
WQ Output cell mass=0
WQ Output cell source sink temp=0
WQ Output cell source sink nsm=0
WQ Output MaxMinRange=-1
WQ Daily Max Min Mean=-1
WQ Daily Range=0
WQ Daily Time=0
WQ Create Restart=0
WQ Fixed Restart=0
WQ System Summary=0
WQ Use Fixed Temperature=0
Sorting and Armoring Iterations= 10
XS Update Threshold= 0.02
Hydraulics Update Threshold= 0.02
Energy Slope Method= 1
Volume Change Method= 0
XS Weighting Method= 0
Number of US Weighted Cross Sections= 1
Number of DS Weighted Cross Sections= 1
Upstream XS Weight=0.25
Main XS Weight=0.5
Downstream XS Weight=0.25
Number of DS XS's Weighted with US Boundary= 1
Upstream Boundary Weight= 1
Weight of XSs Associated with US Boundary= 0
Number of US XS's Weighted with DS Boundary= 1
Downstream Boundary Weight= 0.5
Weight of XSs Associated with DS Boundary= 0.5
Sediment Output Level= 4
Mass or Volume Output= 0
Output Increment Type= 1
Profile and TS Output Increment= 10
XS Output Flag= 0
XS Output Increment= 10
Disregard all LS=0
Disregard all Conn=0
Disregard all Breaches=0
Disregard all Pumps=0

--- Catherine Branch Tr 4_3.f01 (steady flow) ---

Flow Title=Multiple
Number of Profiles=7
Profile Names=10-year,25-year,50-year,1pct_min,100-year,1pct_plu,500-year
River Rch & RM= Catherine Branch,Reach-1,3948
     246     318     374     219     438     874     599
River Rch & RM= Catherine Branch,Reach-1,1578
     318     418     498     295     588    1174     821
Boundary for River Rch & Prof#=Catherine Branch,Reach-1,1
Up Type=0
Dn Type=3
Dn Slope=0.005
Boundary for River Rch & Prof#=Catherine Branch,Reach-1,2
Up Type=0
Dn Type=3
Dn Slope=0.005
Boundary for River Rch & Prof#=Catherine Branch,Reach-1,3
Up Type=0
Dn Type=3
Dn Slope=0.005
Boundary for River Rch & Prof#=Catherine Branch,Reach-1,4
Up Type=0
Dn Type=3
Dn Slope=0.005
Boundary for River Rch & Prof#=Catherine Branch,Reach-1,5
Up Type=0
Dn Type=3
Dn Slope=0.005
Boundary for River Rch & Prof#=Catherine Branch,Reach-1,6
Up Type=0
Dn Type=3
Dn Slope=0.005
Boundary for River Rch & Prof#=Catherine Branch,Reach-1,7
Up Type=0
Dn Type=3
Dn Slope=0.005

--- Catherine Branch Tr 4_3.g01 (geometry) ---

Geom Title=Existing Conditions

River Reach=Catherine Branch,Reach-1
Reach XY= 30
      2331979.00      7067910.00      2332023.65      7067914.96
      2332076.33      7068004.58      2332173.03      7068012.38
      2332254.04      7068060.50      2332426.57      7067915.40
      2332531.43      7067915.40      2332676.57      7068054.48
      2332788.79      7068070.52      2333072.83      7068352.14
      2333192.66      7068373.26      2333284.58      7068554.42
      2333384.94      7068607.68      2333481.43      7068615.52
      2333619.63      7068749.09      2333673.81      7068765.44
      2333681.28      7068904.05      2333728.48      7068975.22
      2333732.54      7069308.54      2333829.00      7069460.00
      2333973.48      7069607.57      2333986.79      7069716.44
      2334073.16      7069766.08      2334087.44      7069806.60
      2334363.78      7069809.48      2334434.94      7069762.26
      2334668.50      7069758.78      2334753.92      7069709.80
      2334968.60      7069710.96      2335029.00      7069760.00

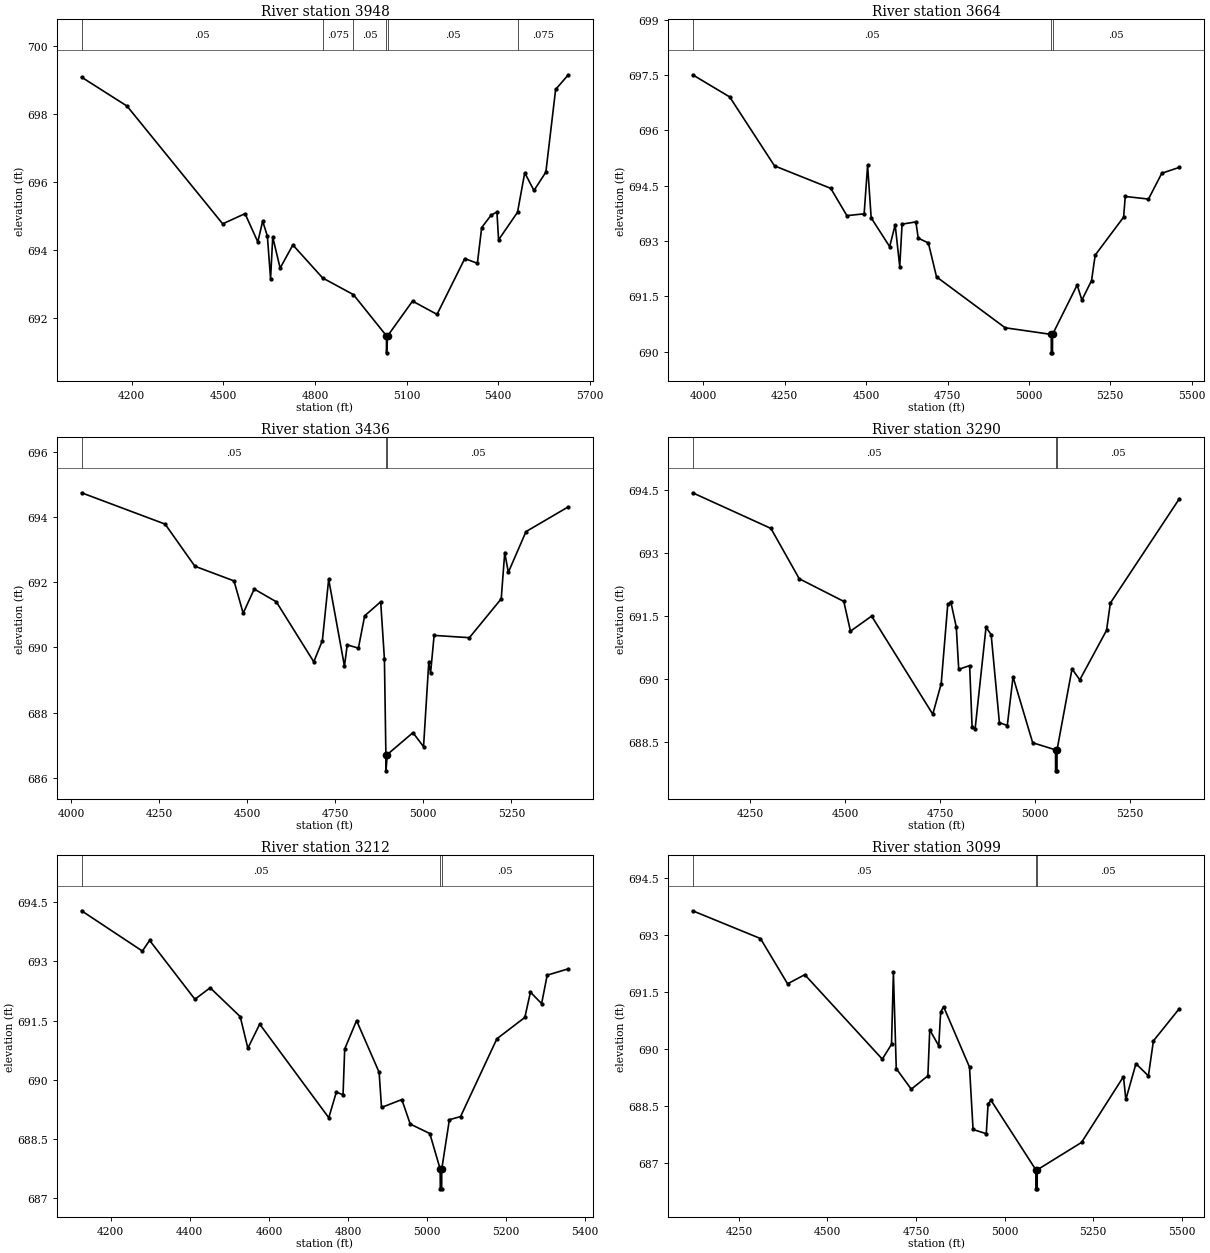
Type RM Length L Ch R = 1,3948,284,284,284
BEGIN DESCRIPTION:
Catherine Branch Tr 4_3 11.0
END DESCRIPTION:
XS GIS Cut Line= 4
      2332102.39      7068922.33      2332353.35      7068091.79
      2332333.86      7067909.30      2332144.11      7067401.01
#Sta/Elev= 30
  4036.1  699.09  4185.0  698.24  4498.2  694.78  4571.3  695.08  4613.1  694.25
  4629.1  694.86  4644.4  694.42  4654.9  693.17  4662.0  694.39  4686.2  693.48
  4727.9  694.16  4825.4  693.19  4926.2  692.70  5034.3  691.49  5034.5  690.99
  5038.3  691.49  5119.7  692.51  5199.9  692.12  5290.8  693.76  5332.0  693.62
  5346.1  694.67  5376.4  695.03  5396.0  695.13  5401.4  694.31  5463.4  695.12
  5487.0  696.28  5517.3  695.76  5556.2  696.30  5588.2  698.73  5629.8  699.16
#Mann=6,-1,0
  4036.1    0.05       0  4825.4   0.075       0  4926.2    0.05       0
  5034.3   0.033       0  5038.3    0.05       0  5463.4   0.075       0
Bank Sta=5034.3,5038.3
Exp/Cntr=0.3,0.1

Type RM Length L Ch R = 1,3664,228,228,228
BEGIN DESCRIPTION:
Catherine Branch Tr 4_3 10.0
END DESCRIPTION:
XS GIS Cut Line= 4
      2332224.73      7068927.51      2332539.66      7068025.87
      2332587.67      7067935.12      2332680.10      7067507.11
#Sta/Elev= 30
  3966.8  697.51  4080.6  696.91  4218.4  695.04  4391.2  694.43  4440.8  693.69
  4493.8  693.74  4504.4  695.05  4515.4  693.63  4572.2  692.85  4589.1  693.44
  4603.2  692.31  4610.3  693.46  4652.7  693.52  4660.0  693.08  4691.1  692.95
  4716.2  692.03  4927.0  690.65  5068.7  690.47  5068.9  689.97  5072.4  689.97
  5072.7  690.47  5148.3  691.81  5162.8  691.40  5192.5  691.93  5203.7  692.62
  5291.0  693.65  5296.1  694.21  5367.4  694.14  5408.3  694.84  5462.4  695.00
#Mann=3,-1,0
  3966.8    0.05       0  5068.7   0.033       0  5072.7    0.05       0
Bank Sta=5068.7,5072.7
Exp/Cntr=0.3,0.1

Type RM Length L Ch R = 1,3436,146,146,146
BEGIN DESCRIPTION:
Catherine Branch Tr 4_3 9.4
END DESCRIPTION:
XS GIS Cut Line= 4
      2332474.60      7068984.76      2332757.50      7068151.99
      2332771.83      7067916.95      2332800.49      7067650.37
#Sta/Elev= 30
  4028.8  694.74  4266.2  693.78  4350.7  692.49  4461.9  692.04  4488.0  691.05
  4519.4  691.79  4582.1  691.40  4688.6  689.56  4713.0  690.21  4730.9  692.09
  4775.7  689.43  4783.7  690.08  4815.4  689.98  4833.2  690.97  4878.7  691.40
  4889.3  689.65  4893.5  686.72  4893.7  686.22  4897.5  686.72  4970.4  687.39
  5000.5  686.96  5015.3  689.54  5020.5  689.22  5030.5  690.37  5130.7  690.30
  5221.2  691.49  5231.2  692.91  5241.3  692.30  5291.6  693.55  5411.9  694.31
#Mann=3,-1,0
  4028.8    0.05       0  4893.5   0.033       0  4897.5    0.05       0
Bank Sta=4893.5,4897.5
Exp/Cntr=0.3,0.1

Type RM Length L Ch R = 1,3290,78,78,78
BEGIN DESCRIPTION:
Catherine Branch Tr 4_3 9.2
END DESCRIPTION:
XS GIS Cut Line= 5
      2332500.63      7068953.51      2332732.21      7068320.99
      2332854.95      7068220.78      2332900.81      7068048.80
      2332929.48      7067779.34
#Sta/Elev= 30
  4098.6  694.44  4304.7  693.59  4379.2  692.39  4496.4  691.85  4514.0  691.14
  4569.7  691.50  4730.6  689.16  4752.8  689.89  4770.0  691.78  4778.1  691.84
  4792.4  691.24  4798.9  690.23  4827.6  690.32  4834.1  688.85  4842.0  688.81
  4870.7  691.23  4884.2  691.06  4905.9  688.96  4926.7  688.89  4941.8  690.05
  4993.5  688.48  5053.6  688.31  5053.9  687.81  5057.4  687.81  5057.6  688.31
  5097.0  690.24  5117.5  689.98  5187.9  691.16  5197.9  691.81  5379.6  694.30
#Mann=3,-1,0
  4098.6    0.05       0  5053.6   0.033       0  5057.6    0.05       0
Bank Sta=5053.6,5057.6
Exp/Cntr=0.3,0.1

Type RM Length L Ch R = 1,3212,113,113,113
BEGIN DESCRIPTION:
Catherine Branch Tr 4_3 9.0
END DESCRIPTION:
XS GIS Cut Line= 4
      2332521.44      7068953.56      2332758.93      7068336.31
      2332880.75      7068255.17      2333181.69      7067957.10
#Sta/Elev= 30
  4126.2  694.28  4280.0  693.26  4298.3  693.53  4412.9  692.04  4451.5  692.33
  4527.5  691.60  4546.8  690.80  4576.8  691.41  4751.5  689.04  4770.7  689.69
  4787.6  689.62  4791.8  690.78  4821.8  691.50  4878.9  690.19  4884.9  689.30
  4936.3  689.50  4957.6  688.88  5007.1  688.64  5033.3  687.74  5033.6  687.24
  5037.1  687.24  5037.3  687.74  5056.6  688.99  5084.9  689.07  5176.8  691.04
  5247.5  691.58  5261.6  692.22  5289.9  691.93  5304.0  692.65  5357.5  692.81
#Mann=3,-1,0
  4126.2    0.05       0  5033.3   0.033       0  5037.3    0.05       0
Bank Sta=5033.3,5037.3
Exp/Cntr=0.3,0.1

Type RM Length L Ch R = 1,3099,214,214,214
BEGIN DESCRIPTION:
Catherine Branch Tr 4_3 8.5
END DESCRIPTION:
XS GIS Cut Line= 6
      2332570.91      7068953.51      2332780.87      7068342.11
      2332885.04      7068304.54      2333087.12      7068278.10
      2333290.63      7068223.64      2333424.68      7068072.48
#Sta/Elev= 30
  4119.4  693.64  4310.9  692.91  4387.4  691.72  4435.9  691.96  4654.7  689.74
  4680.7  690.13  4686.0  692.02  4694.1  689.49  4736.4  688.95  4783.3  689.30
  4788.6  690.51  4814.0  690.09  4819.3  690.97  4827.6  691.12  4900.8  689.53
  4910.8  687.89  4948.1  687.78  4953.2  688.56  4961.3  688.66  5088.0  686.83
  5088.2  686.33  5091.7  686.33  5092.0  686.83  5216.9  687.55  5335.3  689.28
  5342.0  688.68  5370.5  689.62  5405.6  689.30  5419.8  690.22  5493.1  691.07
#Mann=3,-1,0
  4119.4    0.05       0  5088.0   0.033       0  5092.0    0.05       0
Bank Sta=5088,5092
Exp/Cntr=0.3,0.1

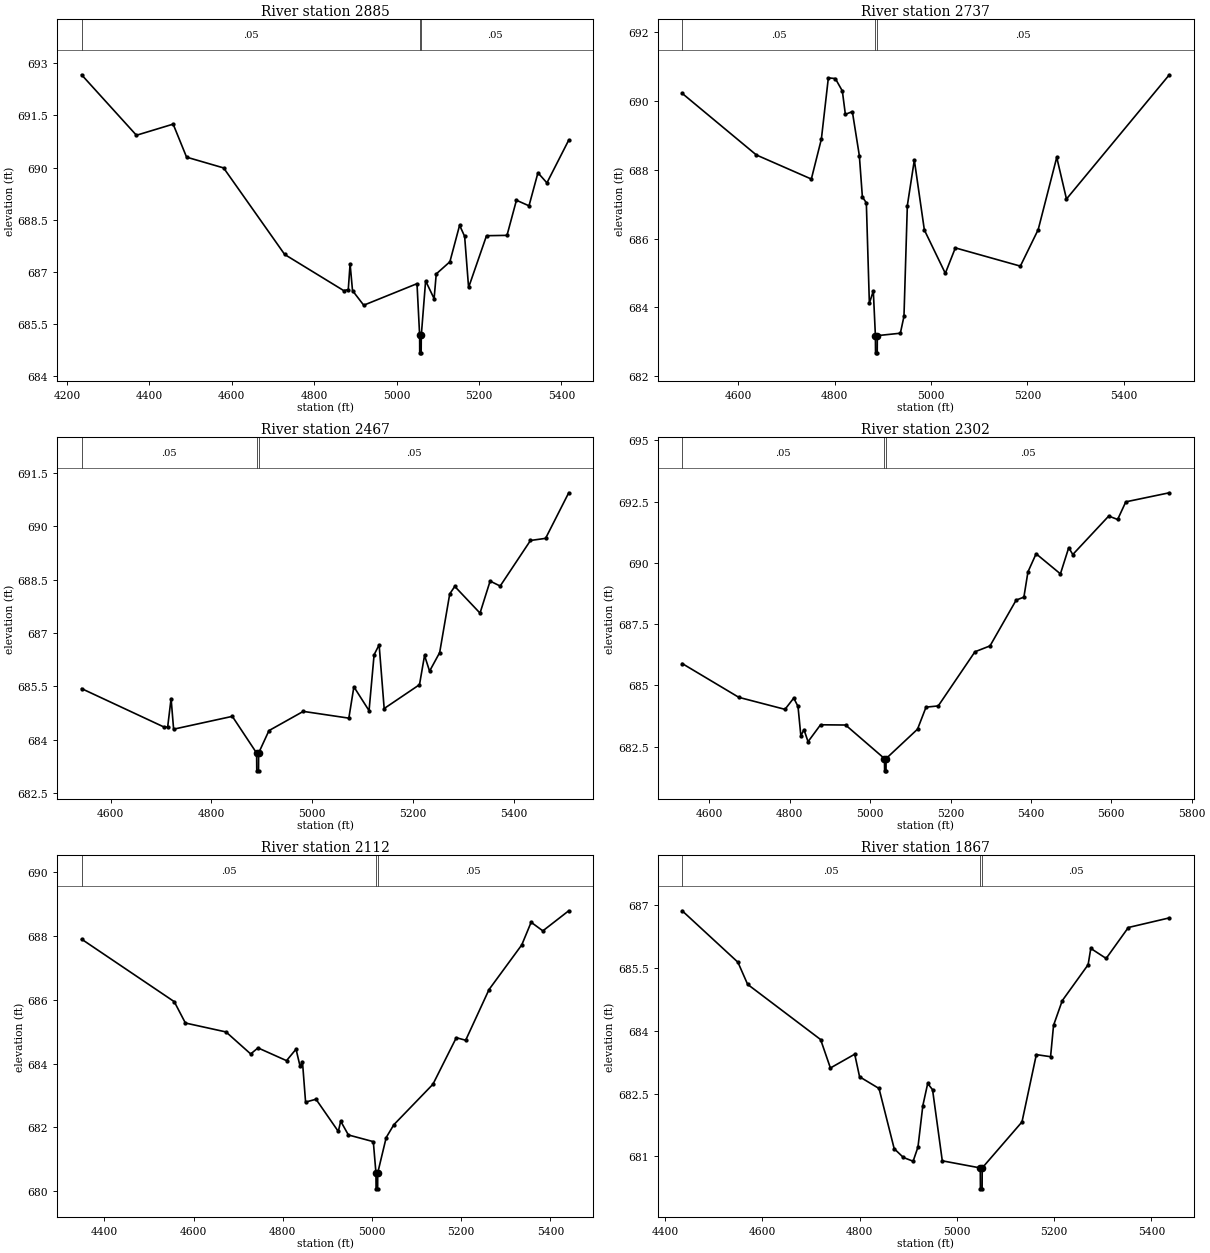
Type RM Length L Ch R = 1,2885,148,148,148
BEGIN DESCRIPTION:
Catherine Branch Tr 4_3 8.3
END DESCRIPTION:
XS GIS Cut Line= 5
      2332659.41      7068849.39      2332818.16      7068526.68
      2333075.66      7068407.09      2333325.02      7068332.56
      2333459.73      7068088.95
#Sta/Elev= 30
  4235.4  692.67  4368.5  690.93  4457.6  691.25  4490.2  690.30  4580.1  689.99
  4728.3  687.50  4871.6  686.46  4882.6  686.49  4887.0  687.23  4892.9  686.46
  4920.1  686.04  5049.4  686.66  5055.8  685.17  5056.0  684.67  5059.5  684.67
  5059.8  685.17  5070.3  686.74  5090.9  686.23  5096.1  686.94  5129.2  687.29
  5152.8  688.34  5165.0  688.02  5174.6  686.55  5218.1  688.04  5267.8  688.05
  5290.7  689.06  5321.2  688.90  5342.9  689.85  5364.7  689.56  5417.6  690.79
#Mann=3,-1,0
  4235.4    0.05       0  5055.8   0.033       0  5059.8    0.05       0
Bank Sta=5055.8,5059.8
Exp/Cntr=0.3,0.1

Type RM Length L Ch R = 1,2737,270,270,270
BEGIN DESCRIPTION:
Catherine Branch Tr 4_3 8.0
END DESCRIPTION:
XS GIS Cut Line= 3
      2332854.96      7068811.23      2333436.81      7068361.22
      2333476.94      7068088.93
#Sta/Elev= 30
  4483.7  690.22  4637.6  688.43  4751.7  687.73  4772.5  688.89  4787.0  690.67
  4801.5  690.65  4816.0  690.29  4822.3  689.61  4836.8  689.69  4851.3  688.41
  4857.6  687.21  4865.8  687.04  4872.1  684.12  4880.3  684.48  4884.6  683.18
  4884.9  682.68  4888.4  682.68  4888.6  683.18  4936.4  683.25  4943.9  683.74
  4950.9  686.96  4965.4  688.28  4986.2  686.25  5029.7  684.99  5050.5  685.73
  5185.4  685.20  5222.4  686.26  5260.9  688.36  5281.1  687.15  5494.5  690.76
#Mann=3,-1,0
  4483.7    0.05       0  4884.6   0.033       0  4888.6    0.05       0
Bank Sta=4884.6,4888.6
Exp/Cntr=0.3,0.1

Type RM Length L Ch R = 1,2467,165,165,165
BEGIN DESCRIPTION:
Catherine Branch Tr 4_3 7.2
END DESCRIPTION:
XS GIS Cut Line= 4
      2333287.77      7068966.01      2333442.54      7068900.09
      2333479.80      7068553.27      2333499.83      7068104.15
#Sta/Elev= 30
  4542.3  685.44  4705.9  684.36  4713.1  684.36  4719.9  685.16  4724.9  684.30
  4841.4  684.66  4889.6  683.63  4889.9  683.13  4893.4  683.13  4893.6  683.63
  4914.1  684.26  4982.2  684.80  5072.6  684.61  5082.6  685.49  5112.7  684.82
  5122.7  686.39  5132.7  686.67  5142.7  684.88  5212.8  685.55  5222.8  686.37
  5232.8  685.93  5252.8  686.45  5272.8  688.10  5282.8  688.31  5332.9  687.56
  5352.9  688.46  5372.9  688.32  5433.0  689.60  5463.0  689.66  5508.9  690.94
#Mann=3,-1,0
  4542.3    0.05       0  4889.6   0.033       0  4893.6    0.05       0
Bank Sta=4889.6,4893.6
Exp/Cntr=0.3,0.1

Type RM Length L Ch R = 1,2302,190,190,190
BEGIN DESCRIPTION:
Catherine Branch Tr 4_3 7.0
END DESCRIPTION:
XS GIS Cut Line= 4
      2333261.98      7068997.53      2333537.13      7068885.76
      2333614.52      7068662.19      2333728.87      7067993.26
#Sta/Elev= 30
  4532.2  685.89  4673.2  684.51  4788.0  684.02  4809.8  684.48  4820.4  684.14
  4827.5  682.94  4835.3  683.19  4845.4  682.70  4876.5  683.39  4938.9  683.38
  5035.6  682.01  5035.9  681.51  5039.4  681.51  5039.6  682.01  5117.8  683.21
  5139.0  684.11  5169.4  684.16  5260.7  686.37  5298.2  686.61  5363.3  688.48
  5382.5  688.60  5392.6  689.63  5412.9  690.37  5473.4  689.55  5494.1  690.62
  5504.2  690.34  5593.6  691.91  5615.8  691.77  5636.1  692.49  5744.4  692.86
#Mann=3,-1,0
  4532.2    0.05       0  5035.6   0.033       0  5039.6    0.05       0
Bank Sta=5035.6,5039.6
Exp/Cntr=0.3,0.1

Type RM Length L Ch R = 1,2112,245,245,245
BEGIN DESCRIPTION:
Catherine Branch Tr 4_3 6.0
END DESCRIPTION:
XS GIS Cut Line= 3
      2333068.19      7069086.97      2333679.00      7068860.00
      2334099.43      7068727.60
#Sta/Elev= 30
  4348.7  687.90  4556.5  685.94  4581.5  685.27  4672.6  684.99  4727.9  684.30
  4744.3  684.49  4808.3  684.09  4829.6  684.45  4838.7  683.91  4844.0  684.06
  4851.0  682.79  4874.4  682.88  4924.4  681.87  4929.8  682.19  4947.0  681.76
  5002.9  681.55  5008.8  680.57  5009.1  680.07  5012.6  680.07  5012.8  680.57
  5031.8  681.68  5048.9  682.08  5136.6  683.35  5189.0  684.81  5210.0  684.73
  5262.4  686.32  5335.8  687.72  5356.8  688.43  5383.1  688.16  5441.1  688.79
#Mann=3,-1,0
  4348.7    0.05       0  5008.8    0.04       0  5012.8    0.05       0
Bank Sta=5008.8,5012.8
Exp/Cntr=0.3,0.1

Type RM Length L Ch R = 1,1867,71,71,71
BEGIN DESCRIPTION:
Catherine Branch Tr 4_3 5.2
END DESCRIPTION:
XS GIS Cut Line= 3
      2333164.48      7069112.19      2333812.29      7069086.40
      2334139.09      7068951.67
#Sta/Elev= 30
  4435.0  686.87  4549.6  685.64  4569.6  685.11  4719.7  683.79  4739.8  683.11
  4789.8  683.44  4799.8  682.90  4839.8  682.62  4871.0  681.18  4889.9  680.97
  4909.9  680.88  4919.9  681.22  4929.9  682.21  4939.9  682.74  4949.9  682.59
  4969.9  680.89  5048.0  680.72  5048.3  680.22  5051.8  680.22  5052.0  680.72
  5133.8  681.82  5163.3  683.43  5192.6  683.38  5198.7  684.13  5216.6  684.72
  5269.8  685.58  5275.3  685.97  5306.9  685.73  5352.5  686.47  5436.8  686.70
#Mann=3,-1,0
  4435.0    0.05       0  5048.0    0.04       0  5052.0    0.05       0
Bank Sta=5048,5052
Exp/Cntr=0.3,0.1

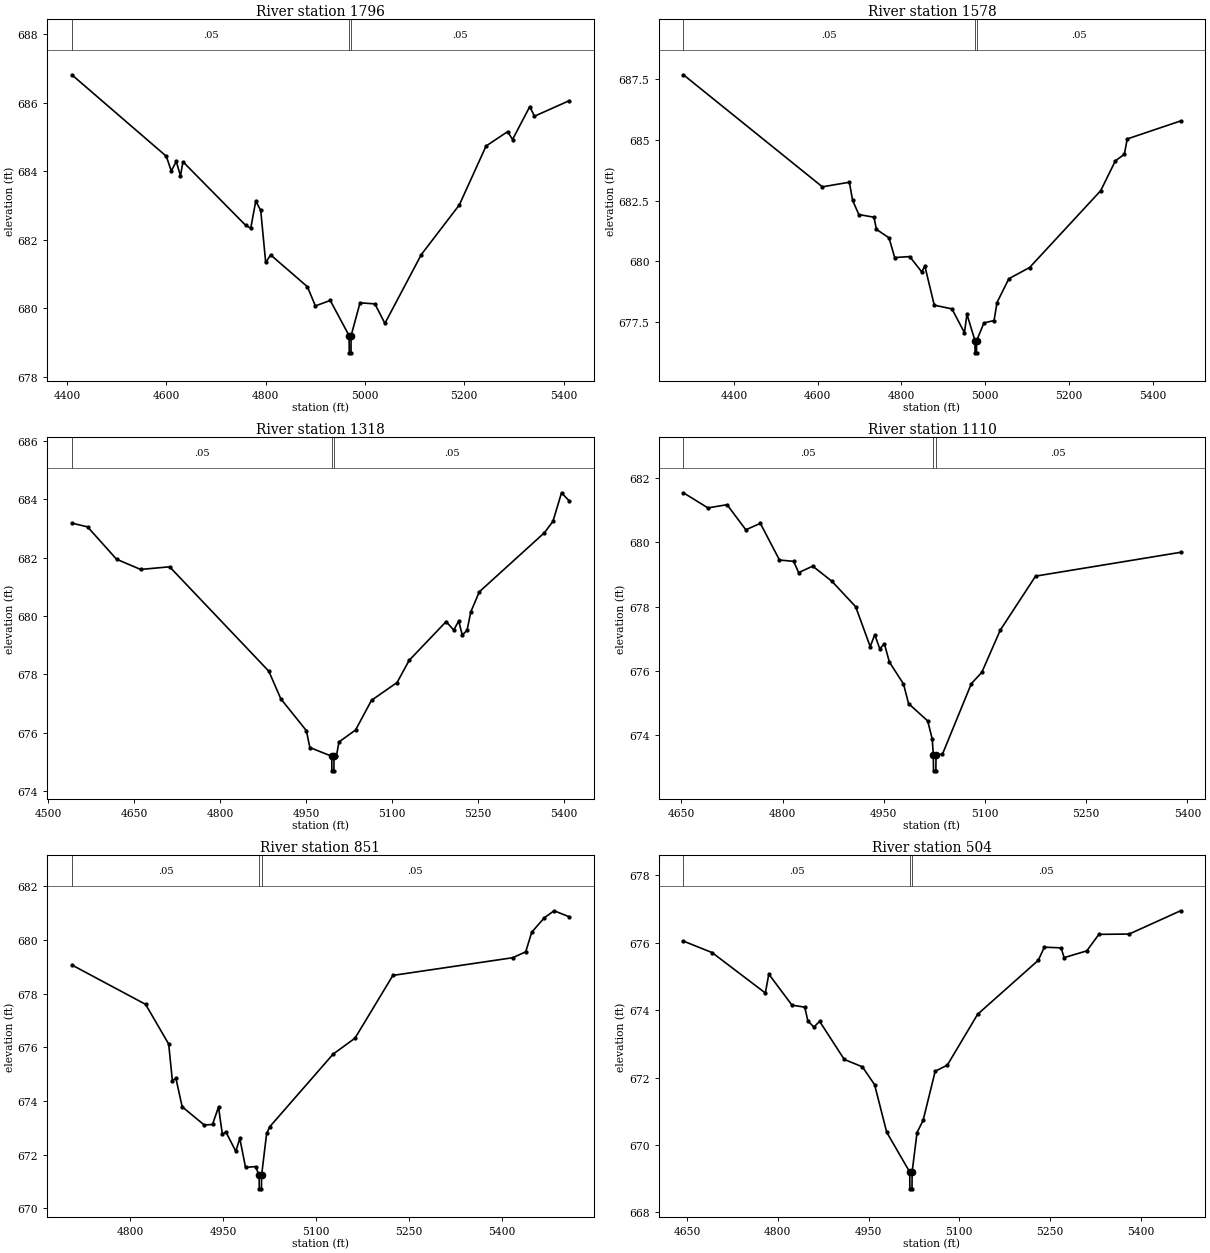
Type RM Length L Ch R = 1,1796,218,218,218
BEGIN DESCRIPTION:
Catherine Branch Tr 4_3 5.0
END DESCRIPTION:
XS GIS Cut Line= 3
      2333138.74      7069183.85      2333786.50      7069158.05
      2334113.24      7069023.34
#Sta/Elev= 30
  4409.3  686.82  4599.7  684.44  4609.7  684.01  4619.7  684.29  4628.2  683.87
  4633.2  684.28  4759.8  682.42  4769.8  682.34  4779.9  683.13  4789.9  682.86
  4799.9  681.34  4809.9  681.56  4884.0  680.63  4900.0  680.07  4930.0  680.23
  4968.0  679.20  4968.3  678.70  4971.8  678.70  4972.0  679.20  4990.0  680.16
  5020.0  680.13  5040.1  679.56  5113.5  681.57  5190.1  683.02  5244.0  684.74
  5287.4  685.16  5297.3  684.93  5332.0  685.89  5341.5  685.61  5411.0  686.06
#Mann=3,-1,0
  4409.3    0.05       0  4968.0    0.04       0  4972.0    0.05       0
Bank Sta=4968,4972
Exp/Cntr=0.3,0.1

Type RM Length L Ch R = 1,1578,260,260,260
BEGIN DESCRIPTION:
Catherine Branch Tr 4_3 4.0
END DESCRIPTION:
XS GIS Cut Line= 3
      2333179.00      7069760.00      2333779.00      7069360.00
      2334114.49      7069035.44
#Sta/Elev= 30
  4279.0  687.68  4611.0  683.07  4675.6  683.26  4683.1  682.52  4698.1  681.93
  4734.2  681.82  4740.2  681.32  4770.3  680.97  4783.8  680.16  4819.8  680.20
  4848.4  679.57  4855.9  679.81  4878.4  678.20  4920.5  678.05  4950.5  677.07
  4956.5  677.83  4975.6  676.74  4975.8  676.24  4979.3  676.24  4979.6  676.74
  4997.1  677.47  5021.3  677.57  5028.3  678.31  5056.6  679.29  5106.2  679.75
  5276.0  682.91  5311.2  684.14  5332.6  684.41  5339.5  685.04  5466.9  685.78
#Mann=3,-1,0
  4279.0    0.05       0  4975.6    0.04       0  4979.6    0.05       0
Bank Sta=4975.6,4979.6
Exp/Cntr=0.3,0.1

Type RM Length L Ch R = 1,1318,208,208,208
BEGIN DESCRIPTION:
Catherine Branch Tr 4_3 3.0
END DESCRIPTION:
XS GIS Cut Line= 3
      2333552.58      7069821.33      2333929.00      7069560.00
      2334161.02      7069223.71
#Sta/Elev= 30
  4541.5  683.19  4568.9  683.06  4619.5  681.95  4661.4  681.60  4712.0  681.69
  4884.9  678.11  4905.9  677.16  4950.4  676.07  4956.5  675.49  4994.7  675.19
  4994.9  674.69  4998.4  674.69  4998.7  675.19  5002.8  675.19  5007.2  675.68
  5036.2  676.09  5064.0  677.11  5108.6  677.72  5129.6  678.48  5194.1  679.81
  5207.3  679.52  5216.1  679.83  5222.2  679.35  5230.6  679.51  5237.1  680.14
  5251.9  680.83  5365.5  682.86  5380.4  683.25  5395.3  684.23  5408.3  683.96
#Mann=3,-1,0
  4541.5    0.05       0  4994.7    0.04       0  4998.7    0.05       0
Bank Sta=4994.7,4998.7
Exp/Cntr=0.3,0.1

Type RM Length L Ch R = 1,1110,259,259,259
BEGIN DESCRIPTION:
Catherine Branch Tr 4_3 2.0
END DESCRIPTION:
XS GIS Cut Line= 3
      2333750.45      7069972.41      2334026.51      7069722.39
      2334214.02      7069409.88
#Sta/Elev= 30
  4653.0  681.54  4689.3  681.07  4717.7  681.17  4745.5  680.39  4767.0  680.59
  4795.4  679.45  4816.3  679.41  4823.8  679.06  4844.7  679.26  4873.1  678.79
  4908.3  678.00  4929.9  676.76  4936.6  677.13  4944.1  676.69  4950.8  676.85
  4958.3  676.28  4979.2  675.60  4986.7  674.99  5015.1  674.45  5021.8  673.89
  5023.4  673.40  5023.7  672.90  5027.2  672.90  5027.4  673.40  5037.0  673.42
  5079.8  675.61  5095.3  675.96  5122.6  677.27  5175.0  678.95  5389.9  679.69
#Mann=3,-1,0
  4653.0    0.05       0  5023.4    0.04       0  5027.4    0.05       0
Bank Sta=5023.4,5027.4
Exp/Cntr=0.3,0.1

Type RM Length L Ch R = 1,851,347,347,347
BEGIN DESCRIPTION:
Catherine Branch Tr 4_3 1.0
END DESCRIPTION:
XS GIS Cut Line= 3
      2334083.80      7070066.14      2334229.00      7069810.00
      2334328.58      7069310.98
#Sta/Elev= 30
  4705.6  679.07  4824.8  677.60  4862.1  676.12  4868.0  674.76  4873.8  674.84
  4883.9  673.78  4919.6  673.10  4932.9  673.12  4942.6  673.77  4948.8  672.76
  4954.6  672.84  4970.5  672.12  4977.0  672.60  4986.3  671.52  5002.6  671.55
  5008.2  671.22  5008.5  670.72  5012.0  670.72  5012.2  671.22  5020.4  672.79
  5025.6  673.04  5127.6  675.74  5163.2  676.34  5224.4  678.68  5418.1  679.34
  5439.0  679.56  5448.7  680.29  5469.1  680.83  5484.9  681.09  5508.9  680.87
#Mann=3,-1,0
  4705.6    0.05       0  5008.2   0.033       0  5012.2    0.05       0
Bank Sta=5008.2,5012.2
Exp/Cntr=0.3,0.1

Type RM Length L Ch R = 1,504,356,356,356
BEGIN DESCRIPTION:
Catherine Branch Tr 4_3 0.6
END DESCRIPTION:
XS GIS Cut Line= 3
      2334375.42      7070008.88      2334552.55      7069915.10
      2334583.80      7069295.31
#Sta/Elev= 30
  4644.3  676.05  4691.6  675.71  4779.6  674.51  4785.3  675.07  4823.6  674.15
  4844.7  674.09  4849.8  673.68  4859.8  673.50  4869.2  673.67  4909.9  672.54
  4939.9  672.32  4960.0  671.79  4980.0  670.38  5018.0  669.20  5018.3  668.70
  5021.8  668.70  5022.0  669.20  5030.1  670.37  5040.1  670.73  5060.1  672.19
  5080.1  672.37  5130.2  673.88  5230.3  675.48  5240.3  675.87  5268.0  675.85
  5273.0  675.56  5310.4  675.76  5330.4  676.25  5380.5  676.26  5465.3  676.95
#Mann=3,-1,0
  4644.3    0.05       0  5018.0   0.033       0  5022.0    0.05       0
Bank Sta=5018,5022
Exp/Cntr=0.3,0.1

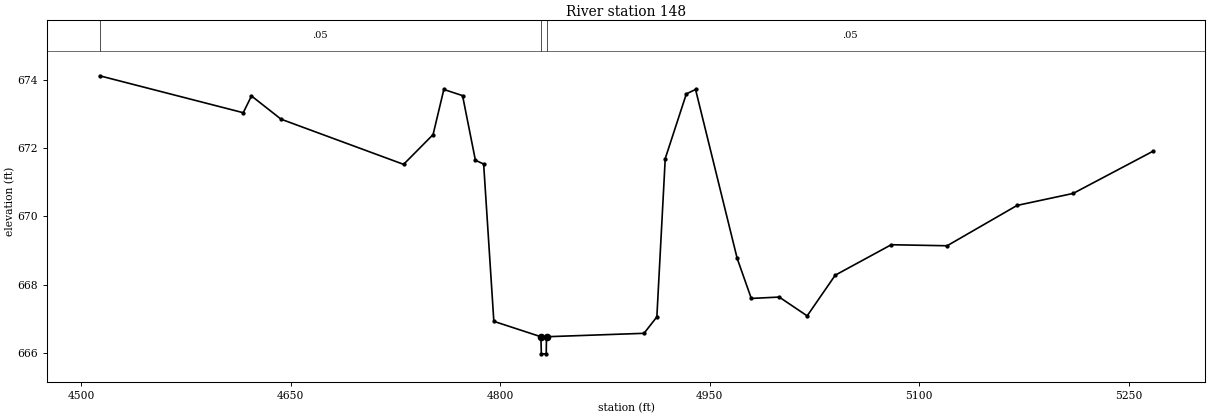
Type RM Length L Ch R = 1,148,0,0,0
BEGIN DESCRIPTION:
Catherine Branch Tr 4_3 0.3
END DESCRIPTION:
XS GIS Cut Line= 3
      2334542.09      7070003.67      2334896.30      7069774.48
      2334917.01      7069443.12
#Sta/Elev= 30
  4513.3  674.11  4616.1  673.03  4622.0  673.52  4643.2  672.84  4730.9  671.52
  4752.0  672.39  4759.7  673.71  4773.1  673.53  4782.3  671.64  4788.2  671.53
  4795.5  666.93  4829.2  666.48  4829.5  665.98  4833.0  665.98  4833.2  666.48
  4903.0  666.58  4912.2  667.06  4918.2  671.69  4933.3  673.58  4939.9  673.71
  4969.7  668.77  4979.8  667.60  4999.8  667.64  5019.8  667.09  5039.9  668.28
  5080.0  669.17  5120.0  669.14  5170.1  670.32  5210.2  670.67  5267.2  671.90
#Mann=3,-1,0
  4513.3    0.05       0  4829.2   0.033       0  4833.2    0.05       0
Bank Sta=4829.2,4833.2
Exp/Cntr=0.3,0.1

Chan Stop Cuts=-1