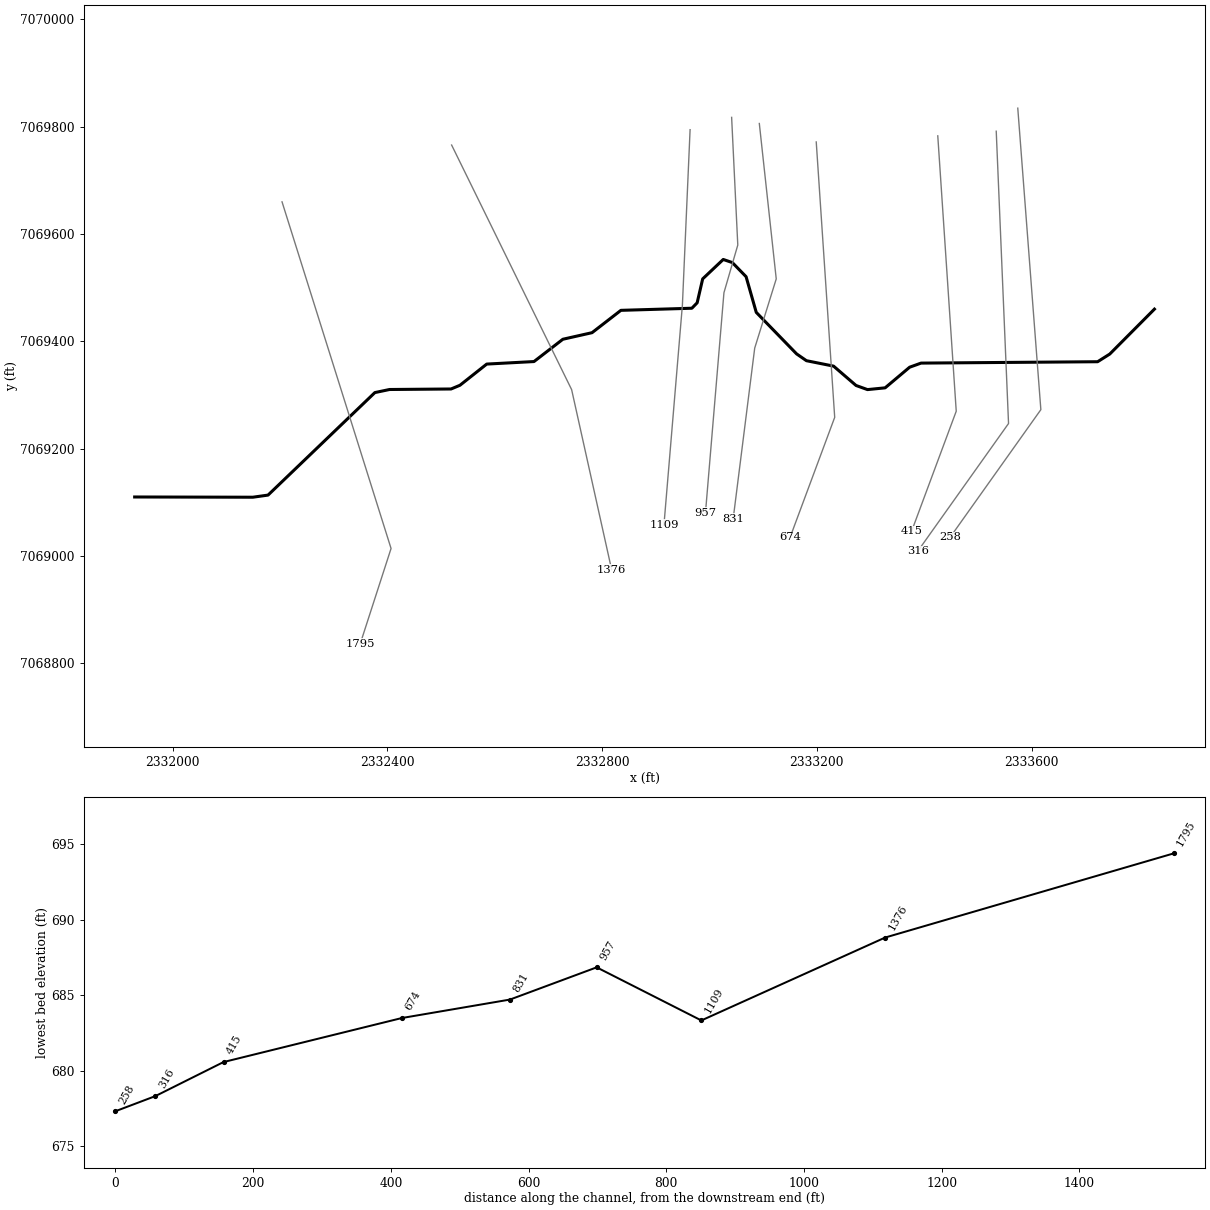
--- Catherine Branch Tr 4_3_1.prj (project) ---

Proj Title=Catherine Branch Tr 4_3_1 Base Level Engineering
Current Plan=p01
Default Exp/Contr=0.3,0.1
English Units
Geom File=g01
Flow File=f01
Plan File=p01
Y Axis Title=Elevation
X Axis Title(PF)=Main Channel Distance
X Axis Title(XS)=Station
BEGIN DESCRIPTION:
Catherine Branch Tr 4_3_1
END DESCRIPTION:
DSS Export Rating Curves= 0
DSS Export Rating Curve Sorted= 0
DSS Export Volume Flow Curves= 0
DXF OffsetX= 0
DXF OffsetY= 0
DXF ScaleX= 1
DXF ScaleY= 10

--- Catherine Branch Tr 4_3_1.p01 (plan) ---

Plan Title=Multiple Run
Program Version=4.10
Short Identifier=Multiple
Geom File=g01
Flow File=f01
Subcritical Flow
K Sum by GR= 0
Std Step Tol= 0.01
Critical Tol= 0.01
Num of Std Step Trials= 20
Max Error Tol= 0.3
Flow Tol Ratio= 0.001
Split Flow NTrial= 30
Split Flow Tol= 0.02
Split Flow Ratio= 0.02
Log Output Level= 0
Friction Slope Method= 1
Unsteady Friction Slope Method= 2
Unsteady Bridges Friction Slope Method= 1
Parabolic Critical Depth
Global Vel Dist= 1 , 1 , 1
Global Log Level= 0
CheckData=True
Encroach Param=-1 ,0,0, 0
BEGIN DESCRIPTION:
Multiple Run
END DESCRIPTION:
Computation Interval=1HOUR
Output Interval=1HOUR
Run HTab= 0
Run UNet= 0
Run PostProcess= 0
Run WQNet= 0
UNET Theta= 1
UNET Theta Warmup= 1
UNET ZTol= 0.02
UNET ZSATol= 0.05
UNET MxIter= 20
UNET MaxInSteps= 0
UNET DtIC= 0
UNET DtMin= 0
UNET MaxCRTS= 20
UNET WFStab= 2
UNET SFStab= 1
UNET WFX= 1
UNET SFX= 1
UNET DSS MLevel= 4
UNET DZMax Abort= 100
UNET Convert EG Bridges= 0
UNET Use Existing IB Tables=-1
UNET Froude Reduction=False
UNET Froude Limit= 1
UNET Froude Power= 10
UNET Time Slicing=0,0, 5
UNET Junction Losses=0
Instantaneous Interval=1HOUR
Write IC File= 0
Write IC File at Sim End=0
Echo Input=False
Echo Parameters=False
Echo Output=False
Write Detailed= 0
WQ AD Non Conservative
WQ ULTIMATE=-1
WQ Max Comp Step=1HOUR
WQ Output Interval=15MIN
WQ Output Selected Increments= 0
WQ Output face flow=0
WQ Output face velocity=0
WQ Output face area=0
WQ Output face dispersion=0
WQ Output cell volume=0
WQ Output cell surface area=0
WQ Output cell continuity=0
WQ Output cumulative cell continuity=0
WQ Output face conc=0
WQ Output face dconc_dx=0
WQ Output face courant=0
WQ Output face peclet=0
WQ Output face adv mass=0
WQ Output face disp mass=0
WQ Output cell mass=0
WQ Output cell source sink temp=0
WQ Output cell source sink nsm=0
WQ Output MaxMinRange=-1
WQ Daily Max Min Mean=-1
WQ Daily Range=0
WQ Daily Time=0
WQ Create Restart=0
WQ Fixed Restart=0
WQ System Summary=0
WQ Use Fixed Temperature=0
Sorting and Armoring Iterations= 10
XS Update Threshold= 0.02
Hydraulics Update Threshold= 0.02
Energy Slope Method= 1
Volume Change Method= 0
XS Weighting Method= 0
Number of US Weighted Cross Sections= 1
Number of DS Weighted Cross Sections= 1
Upstream XS Weight=0.25
Main XS Weight=0.5
Downstream XS Weight=0.25
Number of DS XS's Weighted with US Boundary= 1
Upstream Boundary Weight= 1
Weight of XSs Associated with US Boundary= 0
Number of US XS's Weighted with DS Boundary= 1
Downstream Boundary Weight= 0.5
Weight of XSs Associated with DS Boundary= 0.5
Sediment Output Level= 4
Mass or Volume Output= 0
Output Increment Type= 1
Profile and TS Output Increment= 10
XS Output Flag= 0
XS Output Increment= 10
Disregard all LS=0
Disregard all Conn=0
Disregard all Breaches=0
Disregard all Pumps=0

--- Catherine Branch Tr 4_3_1.f01 (steady flow) ---

Flow Title=Multiple
Number of Profiles=7
Profile Names=10-year,25-year,50-year,1pct_min,100-year,1pct_plu,500-year
River Rch & RM= Catherine Branch,Reach-1,1795
      83      99     110      61     122     244     150
Boundary for River Rch & Prof#=Catherine Branch,Reach-1,1
Up Type=0
Dn Type=3
Dn Slope=0.005
Boundary for River Rch & Prof#=Catherine Branch,Reach-1,2
Up Type=0
Dn Type=3
Dn Slope=0.005
Boundary for River Rch & Prof#=Catherine Branch,Reach-1,3
Up Type=0
Dn Type=3
Dn Slope=0.005
Boundary for River Rch & Prof#=Catherine Branch,Reach-1,4
Up Type=0
Dn Type=3
Dn Slope=0.005
Boundary for River Rch & Prof#=Catherine Branch,Reach-1,5
Up Type=0
Dn Type=3
Dn Slope=0.005
Boundary for River Rch & Prof#=Catherine Branch,Reach-1,6
Up Type=0
Dn Type=3
Dn Slope=0.005
Boundary for River Rch & Prof#=Catherine Branch,Reach-1,7
Up Type=0
Dn Type=3
Dn Slope=0.005

--- Catherine Branch Tr 4_3_1.g01 (geometry) ---

Geom Title=Existing Conditions

River Reach=Catherine Branch,Reach-1
Reach XY= 30
      2331929.00      7069110.00      2332149.18      7069109.57
      2332177.54      7069113.53      2332376.55      7069304.53
      2332403.89      7069310.27      2332518.49      7069311.23
      2332535.06      7069318.14      2332584.98      7069357.64
      2332673.03      7069362.33      2332726.82      7069403.89
      2332781.18      7069416.12      2332834.94      7069457.75
      2332967.17      7069461.68      2332977.02      7069471.79
      2332987.32      7069516.37      2333025.62      7069552.55
      2333042.58      7069546.77      2333068.20      7069520.44
      2333087.15      7069453.98      2333162.29      7069376.63
      2333180.62      7069363.94      2333231.18      7069353.82
      2333273.06      7069317.76      2333294.39      7069310.08
      2333327.26      7069313.37      2333372.92      7069351.81
      2333394.21      7069359.46      2333723.16      7069362.02
      2333745.81      7069376.33      2333829.00      7069460.00

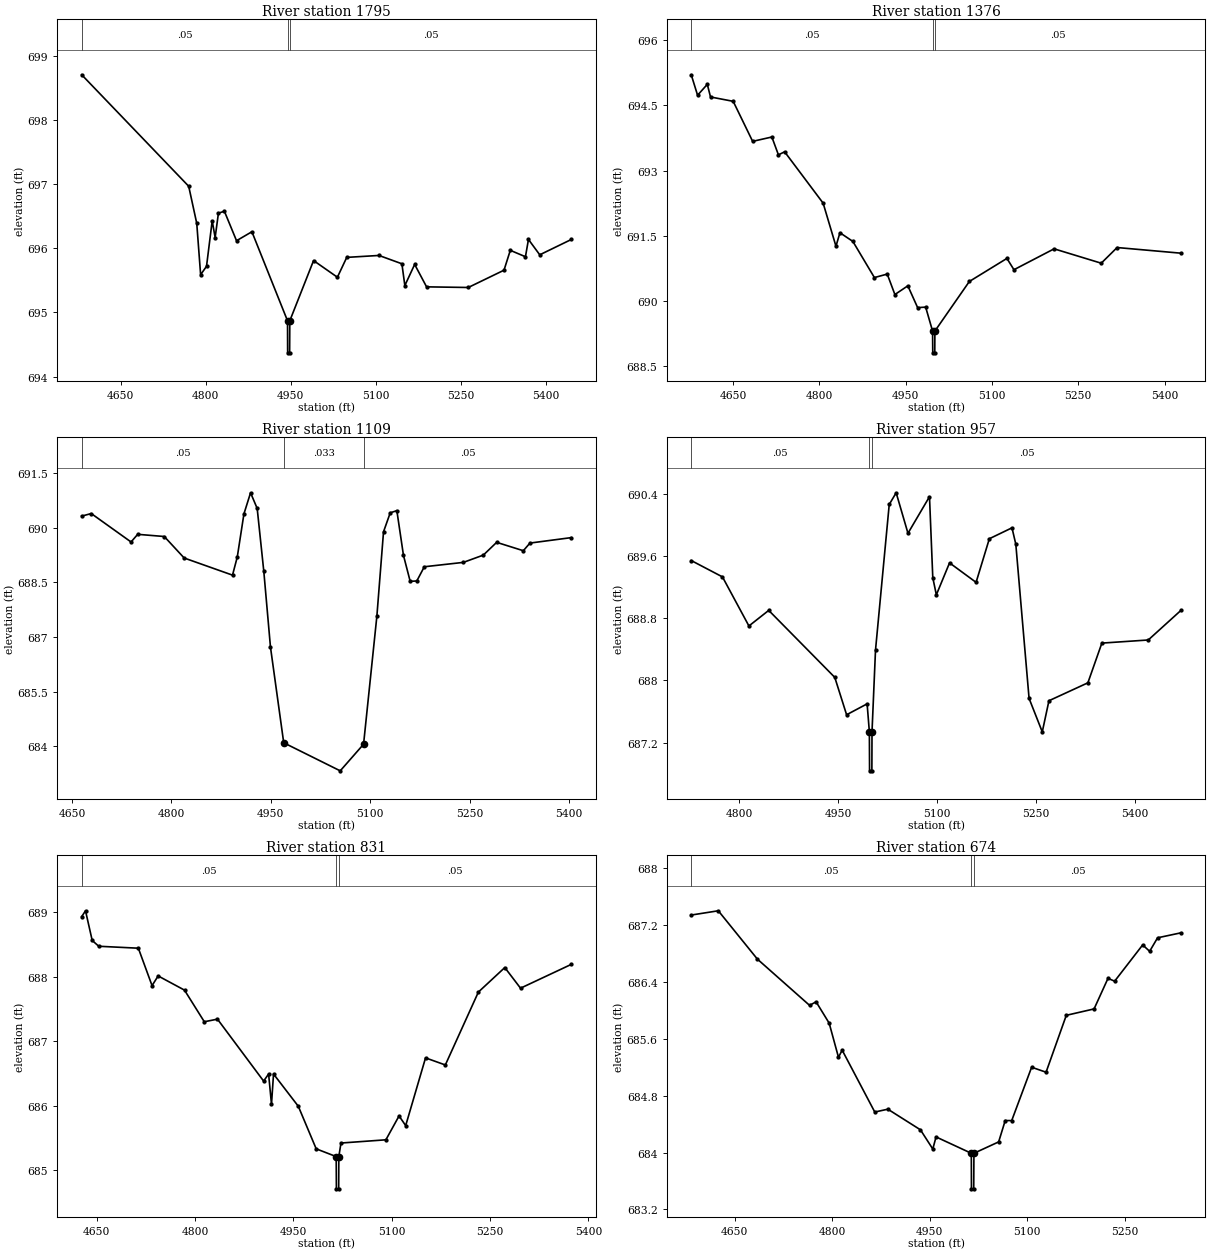
Type RM Length L Ch R = 1,1795,419,419,419
BEGIN DESCRIPTION:
Catherine Branch Tr 4_3_1 10.0
END DESCRIPTION:
XS GIS Cut Line= 3
      2332203.59      7069659.90      2332406.72      7069014.06
      2332349.41      7068836.93
#Sta/Elev= 30
  4581.4  698.71  4770.0  696.97  4784.2  696.39  4791.0  695.59  4801.4  695.72
  4811.4  696.43  4816.6  696.17  4822.4  696.55  4832.9  696.58  4854.3  696.12
  4881.4  696.26  4944.2  694.87  4944.4  694.37  4947.9  694.37  4948.2  694.87
  4990.1  695.81  5032.1  695.55  5048.6  695.86  5105.4  695.89  5145.8  695.76
  5151.0  695.42  5168.3  695.75  5189.3  695.40  5262.8  695.39  5325.8  695.66
  5336.9  695.97  5363.6  695.87  5368.9  696.14  5388.8  695.90  5444.6  696.14
#Mann=3,-1,0
  4581.4    0.05       0  4944.2   0.033       0  4948.2    0.05       0
Bank Sta=4944.2,4948.2
Exp/Cntr=0.3,0.1

Type RM Length L Ch R = 1,1376,267,267,267
BEGIN DESCRIPTION:
Catherine Branch Tr 4_3_1 7.0
END DESCRIPTION:
XS GIS Cut Line= 3
      2332519.57      7069765.75      2332743.17      7069309.97
      2332817.64      7068974.82
#Sta/Elev= 30
  4577.5  695.20  4588.5  694.73  4605.4  694.98  4611.0  694.69  4650.4  694.59
  4684.2  693.67  4717.6  693.77  4729.0  693.36  4739.8  693.43  4806.7  692.25
  4829.0  691.26  4835.9  691.57  4858.4  691.37  4895.8  690.54  4918.1  690.62
  4931.4  690.15  4953.9  690.35  4970.9  689.85  4984.9  689.86  4996.9  689.31
  4997.2  688.81  5000.7  688.81  5000.9  689.31  5060.8  690.45  5126.1  690.98
  5138.3  690.72  5208.1  691.20  5290.0  690.87  5317.6  691.23  5428.5  691.10
#Mann=3,-1,0
  4577.5    0.05       0  4996.9   0.033       0  5000.9    0.05       0
Bank Sta=4996.9,5000.9
Exp/Cntr=0.3,0.1

Type RM Length L Ch R = 1,1109,152,152,152
BEGIN DESCRIPTION:
Catherine Branch Tr 4_3_1 6.0
END DESCRIPTION:
XS GIS Cut Line= 3
      2332963.87      7069794.36      2332949.54      7069467.61
      2332915.14      7069057.71
#Sta/Elev= 30
  4664.8  690.32  4679.2  690.39  4739.2  689.61  4749.2  689.82  4789.3  689.76
  4819.3  689.17  4892.2  688.70  4899.4  689.20  4909.4  690.38  4919.4  690.96
  4929.4  690.53  4939.4  688.80  4949.4  686.73  4969.4  684.10  5054.6  683.33
  5089.8  684.06  5109.9  687.58  5119.9  689.89  5130.0  690.41  5140.0  690.47
  5150.0  689.24  5160.1  688.53  5170.1  688.54  5181.4  688.93  5240.3  689.05
  5270.4  689.25  5290.5  689.60  5330.7  689.37  5340.7  689.58  5403.2  689.73
#Mann=3,-1,0
  4664.8    0.05       0  4969.4   0.033       0  5089.8    0.05       0
Bank Sta=4969.4,5089.8
Exp/Cntr=0.3,0.1

Type RM Length L Ch R = 1,957,126,126,126
BEGIN DESCRIPTION:
Catherine Branch Tr 4_3_1 5.0
END DESCRIPTION:
XS GIS Cut Line= 4
      2333041.26      7069817.28      2333052.73      7069579.40
      2333026.93      7069490.54      2332992.53      7069080.67
#Sta/Elev= 30
  4727.4  689.54  4774.7  689.33  4814.8  688.70  4844.8  688.90  4944.9  688.04
  4962.8  687.56  4993.9  687.70  4997.3  687.34  4997.6  686.84  5001.1  686.84
  5001.3  687.34  5006.6  688.39  5027.4  690.26  5037.9  690.41  5055.8  689.89
  5088.4  690.36  5093.4  689.32  5098.8  689.10  5118.8  689.51  5159.0  689.26
  5179.1  689.82  5213.4  689.96  5219.2  689.75  5239.3  687.77  5259.3  687.34
  5269.4  687.74  5328.4  687.97  5349.6  688.48  5419.9  688.52  5469.4  688.90
#Mann=3,-1,0
  4727.4    0.05       0  4997.3   0.033       0  5001.3    0.05       0
Bank Sta=4997.3,5001.3
Exp/Cntr=0.3,0.1

Type RM Length L Ch R = 1,831,157,157,157
BEGIN DESCRIPTION:
Catherine Branch Tr 4_3_1 4.0
END DESCRIPTION:
XS GIS Cut Line= 4
      2333092.85      7069805.88      2333124.38      7069516.34
      2333084.25      7069387.36      2333044.13      7069069.21
#Sta/Elev= 30
  4627.2  688.93  4633.0  689.02  4643.2  688.56  4653.2  688.47  4713.6  688.44
  4734.5  687.86  4743.8  688.01  4784.0  687.79  4814.2  687.30  4834.3  687.34
  4904.7  686.38  4912.3  686.49  4916.7  686.02  4919.8  686.49  4957.6  685.99
  4984.9  685.33  5015.4  685.21  5015.7  684.71  5019.2  684.71  5019.4  685.21
  5022.7  685.42  5091.2  685.47  5111.3  685.84  5121.4  685.69  5151.7  686.74
  5181.9  686.63  5232.3  687.76  5272.6  688.14  5296.6  687.82  5374.2  688.19
#Mann=3,-1,0
  4627.2    0.05       0  5015.4   0.033       0  5019.4    0.05       0
Bank Sta=5015.4,5019.4
Exp/Cntr=0.3,0.1

Type RM Length L Ch R = 1,674,259,259,259
BEGIN DESCRIPTION:
Catherine Branch Tr 4_3_1 3.0
END DESCRIPTION:
XS GIS Cut Line= 3
      2333198.90      7069771.48      2333233.30      7069258.37
      2333150.21      7069034.88
#Sta/Elev= 30
  4583.5  687.34  4625.1  687.40  4685.2  686.72  4765.4  686.07  4775.4  686.12
  4795.5  685.82  4809.8  685.34  4815.5  685.44  4865.6  684.57  4885.7  684.61
  4935.8  684.32  4954.8  684.05  4959.8  684.22  5014.0  683.99  5014.2  683.49
  5017.7  683.49  5018.0  683.99  5056.0  684.15  5066.1  684.45  5076.1  684.45
  5106.7  685.20  5128.9  685.13  5160.0  685.93  5202.7  686.02  5224.1  686.45
  5234.3  686.41  5277.4  686.92  5288.1  686.83  5300.3  687.02  5336.2  687.09
#Mann=3,-1,0
  4583.5    0.05       0  5014.0   0.033       0  5018.0    0.05       0
Bank Sta=5014,5018
Exp/Cntr=0.3,0.1

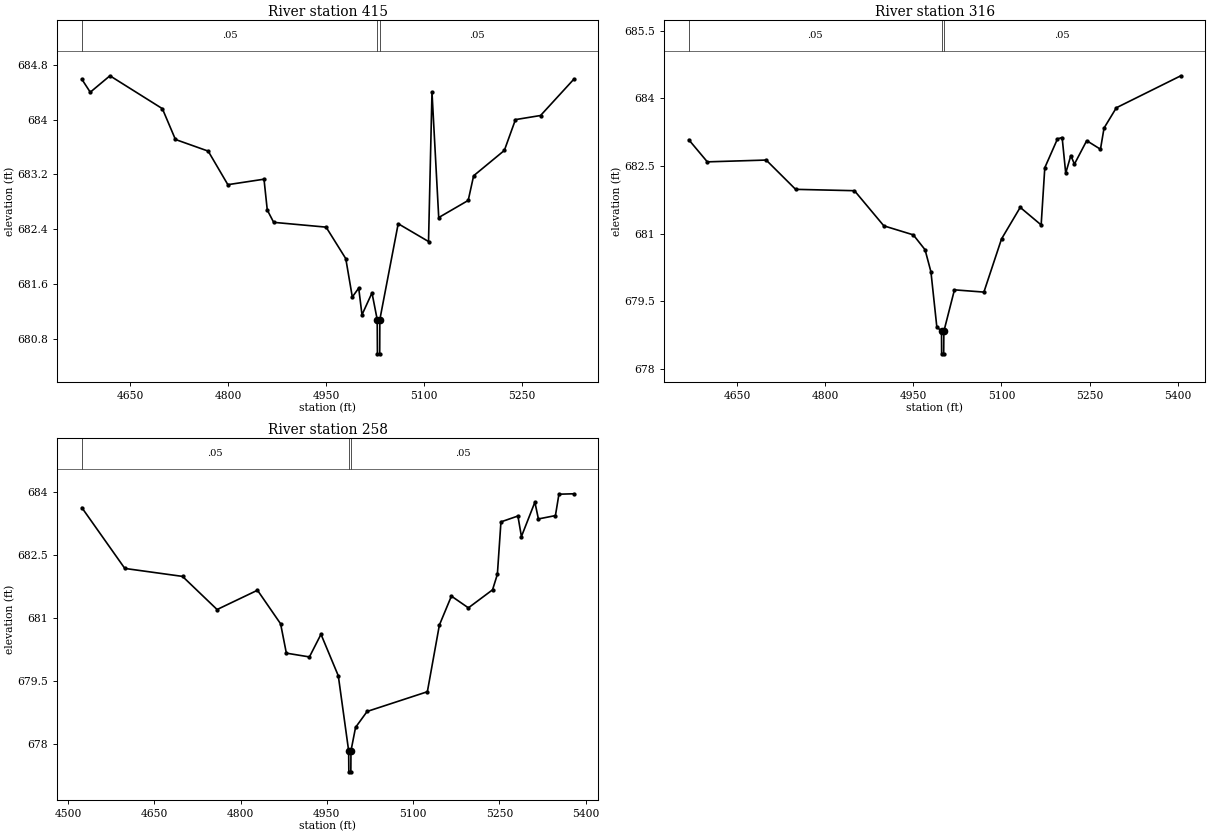
Type RM Length L Ch R = 1,415,99,99,99
BEGIN DESCRIPTION:
Catherine Branch Tr 4_3_1 2.0
END DESCRIPTION:
XS GIS Cut Line= 3
      2333425.34      7069782.89      2333459.74      7069269.84
      2333376.63      7069046.29
#Sta/Elev= 30
  4576.4  684.59  4589.3  684.40  4619.4  684.64  4699.6  684.16  4719.6  683.71
  4769.7  683.54  4799.8  683.05  4855.1  683.13  4860.1  682.68  4869.9  682.50
  4950.1  682.43  4980.2  681.97  4990.2  681.41  5000.0  681.54  5005.0  681.15
  5020.3  681.47  5028.3  681.08  5028.6  680.58  5032.1  680.58  5032.3  681.08
  5060.4  682.48  5106.8  682.22  5112.1  684.40  5122.4  682.57  5167.5  682.82
  5175.8  683.18  5222.8  683.55  5239.8  684.00  5278.2  684.06  5329.1  684.59
#Mann=3,-1,0
  4576.4    0.05       0  5028.3   0.033       0  5032.3    0.05       0
Bank Sta=5028.3,5032.3
Exp/Cntr=0.3,0.1

Type RM Length L Ch R = 1,316,58,58,58
BEGIN DESCRIPTION:
Catherine Branch Tr 4_3_1 1.5
END DESCRIPTION:
XS GIS Cut Line= 3
      2333534.26      7069791.51      2333557.19      7069246.91
      2333388.06      7069008.98
#Sta/Elev= 30
  4568.1  683.08  4599.6  682.59  4699.7  682.63  4749.8  681.98  4849.9  681.95
  4899.9  681.17  4950.0  680.97  4970.0  680.64  4980.0  680.15  4990.0  678.93
  4998.0  678.83  4998.2  678.33  5001.7  678.33  5002.0  678.83  5020.0  679.75
  5070.1  679.70  5100.1  680.88  5131.9  681.58  5167.5  681.19  5173.7  682.46
  5195.3  683.10  5203.2  683.13  5209.3  682.34  5218.0  682.73  5224.1  682.54
  5245.0  683.06  5268.4  682.87  5274.5  683.34  5295.4  683.79  5405.1  684.50
#Mann=3,-1,0
  4568.1    0.05       0  4998.0   0.033       0  5002.0    0.05       0
Bank Sta=4998,5002
Exp/Cntr=0.3,0.1

Type RM Length L Ch R = 1,258,0,0,0
BEGIN DESCRIPTION:
Catherine Branch Tr 4_3_1 1.0
END DESCRIPTION:
XS GIS Cut Line= 3
      2333574.39      7069834.45      2333617.39      7069272.71
      2333448.32      7069034.86
#Sta/Elev= 30
  4524.1  683.63  4598.8  682.18  4699.1  681.99  4759.2  681.20  4829.4  681.66
  4869.6  680.86  4879.6  680.16  4919.7  680.07  4939.8  680.61  4969.9  679.62
  4987.9  677.83  4988.2  677.33  4991.7  677.33  4991.9  677.83  4999.9  678.39
  5020.0  678.77  5124.7  679.24  5145.6  680.83  5166.5  681.52  5196.0  681.24
  5238.0  681.67  5246.4  682.04  5252.6  683.29  5282.1  683.43  5288.2  682.94
  5311.6  683.76  5317.7  683.36  5347.3  683.44  5353.4  683.95  5379.3  683.96
#Mann=3,-1,0
  4524.1    0.05       0  4987.9   0.033       0  4991.9    0.05       0
Bank Sta=4987.9,4991.9
Exp/Cntr=0.3,0.1

Chan Stop Cuts=-1