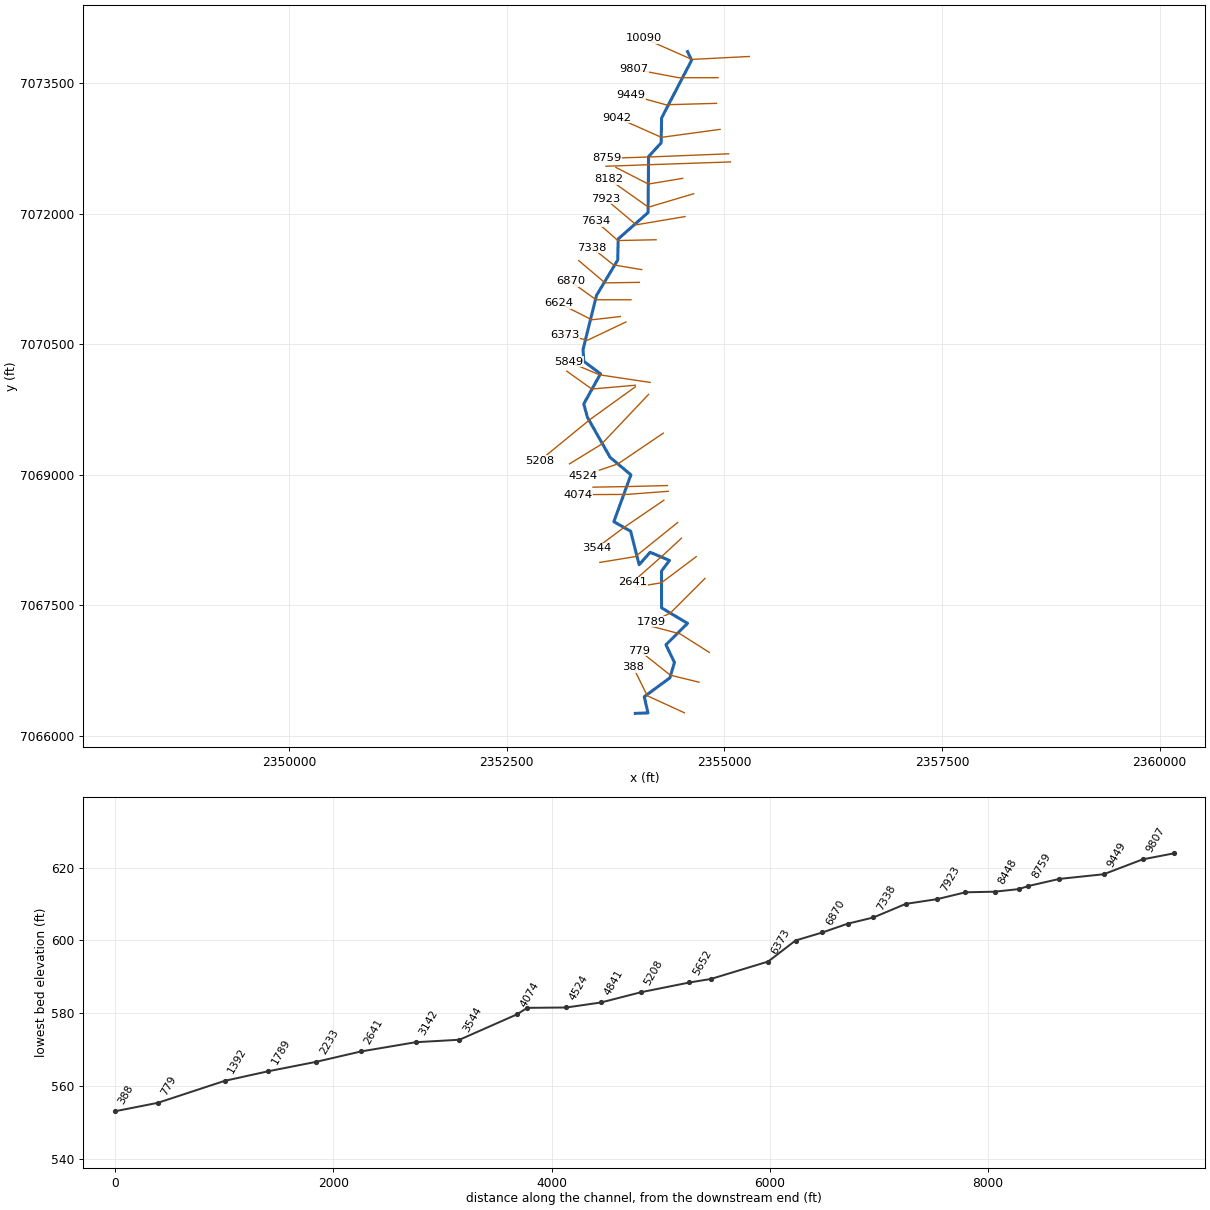
--- Cleveland Branch.prj (project) ---

Proj Title=Cleveland Branch Base Level Engineering
Current Plan=p01
Default Exp/Contr=0.3,0.1
English Units
Geom File=g01
Flow File=f01
Plan File=p01
Y Axis Title=Elevation
X Axis Title(PF)=Main Channel Distance
X Axis Title(XS)=Station
BEGIN DESCRIPTION:
Cleveland Branch
END DESCRIPTION:
DSS Export Rating Curves= 0
DSS Export Rating Curve Sorted= 0
DSS Export Volume Flow Curves= 0
DXF OffsetX= 0
DXF OffsetY= 0
DXF ScaleX= 1
DXF ScaleY= 10

--- Cleveland Branch.p01 (plan) ---

Plan Title=Multiple Run
Short Identifier=Multiple
Geom File=g01
Flow File=f01
Subcritical Flow
K Sum by GR= 0
Std Step Tol= 0.01
Critical Tol= 0.01
Num of Std Step Trials= 20
Max Error Tol= 0.3
Flow Tol Ratio= 0.001
Split Flow NTrial= 30
Split Flow Tol= 0.02
Split Flow Ratio= 0.02
Log Output Level= 0
Friction Slope Method= 1
Unsteady Friction Slope Method= 2
Unsteady Bridges Friction Slope Method= 1
Parabolic Critical Depth
Global Vel Dist=  1 , 1 , 1
Global Log Level= 0
CheckData=True
Encroach Param= -1, 0, 0, 0
BEGIN DESCRIPTION:
Multiple Run
END DESCRIPTION:

--- Cleveland Branch.f01 (steady flow) ---

Flow Title=Multiple
Number of Profiles=7
Profile Names=10-year,25-year,50-year,1pct_min,100-year,1pct_plu,500-year
River Rch & RM= Cleveland Branch,Reach-1,10090
     365     483     578     344     687    1370     969
River Rch & RM= Cleveland Branch,Reach-1,5849
     564     768     936     567    1131    2256    1653
River Rch & RM= Cleveland Branch,Reach-1,5208
     738    1020    1255     766    1529    3050    2273
Boundary for River Rch & Prof#=Cleveland Branch,Reach-1,1
Up Type=0
Dn Type=3
Dn Slope=0.005
Boundary for River Rch & Prof#=Cleveland Branch,Reach-1,2
Up Type=0
Dn Type=3
Dn Slope=0.005
Boundary for River Rch & Prof#=Cleveland Branch,Reach-1,3
Up Type=0
Dn Type=3
Dn Slope=0.005
Boundary for River Rch & Prof#=Cleveland Branch,Reach-1,4
Up Type=0
Dn Type=3
Dn Slope=0.005
Boundary for River Rch & Prof#=Cleveland Branch,Reach-1,5
Up Type=0
Dn Type=3
Dn Slope=0.005
Boundary for River Rch & Prof#=Cleveland Branch,Reach-1,6
Up Type=0
Dn Type=3
Dn Slope=0.005
Boundary for River Rch & Prof#=Cleveland Branch,Reach-1,7
Up Type=0
Dn Type=3
Dn Slope=0.005

--- Cleveland Branch.g01 (geometry) ---

Geom Title=Existing Conditions
Program Version=4.10

River Reach=Cleveland Branch,Reach-1
Reach XY= 30
        2354579.        7073860.      2354625.64      7073761.32
      2354280.97      7073098.03      2354275.46      7072811.46
      2354131.06      7072654.15      2354125.46      7072011.46
      2353782.54      7071708.54      2353776.76      7071465.93
      2353532.62       7071058.5      2353379.05      7070439.96
       2353386.8      7070303.79        2353579.        7070160.
      2353386.85      7069813.23        2353429.        7069660.
       2353689.7      7069200.03      2353928.46      7068999.53
      2353732.44      7068461.25       2353925.5      7068351.54
      2354022.92       7067967.2      2354149.19      7068109.98
      2354371.55      7068016.05      2354279.66      7067894.15
      2354280.51      7067471.87      2354578.84      7067293.98
      2354330.51      7067048.13      2354428.75      7066844.78
      2354375.63      7066668.15      2354081.96      7066451.38
      2354124.13      7066264.98        2353979.        7066260.

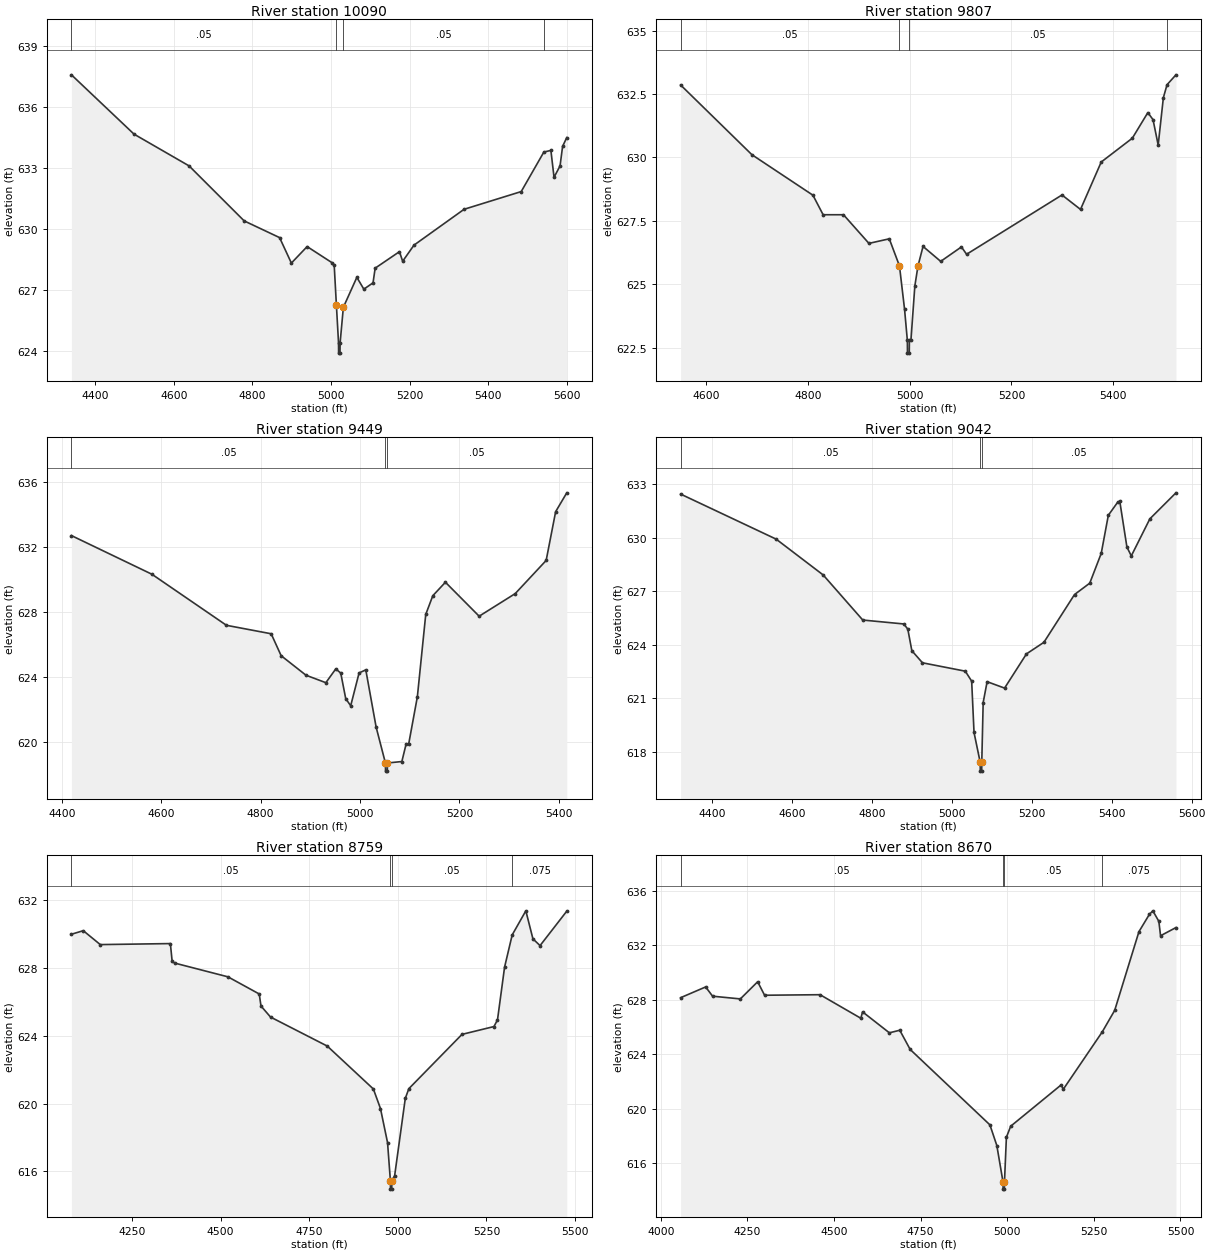
Type RM Length L Ch R = 1 ,10090   ,283,283,283
BEGIN DESCRIPTION:
Cleveland Branch 28.0
END DESCRIPTION:
XS GIS Cut Line= 3
      2355288.02      7073803.94      2354628.17      7073770.37
      2354079.34      7074012.33
#Sta/Elev= 30
  4339.3  637.57  4498.5  634.66  4638.7   633.1  4778.9   630.4    4869  629.58
    4899  628.33  4939.1  629.14  5002.3  628.35    5008  628.22  5013.5  626.29
    5019  624.41  5019.2  623.91  5022.7  623.91    5023  624.41  5031.3  626.16
  5065.6  627.63  5083.4  627.05  5106.8  627.36  5112.2  628.08    5174  628.89
  5182.2  628.42    5211  629.21  5338.5  630.97  5483.9  631.84  5541.5  633.78
  5559.4  633.86  5567.4  632.54  5582.7   633.1  5589.2  634.06  5599.8  634.49
#Mann= 4 ,-1 , 0
  4339.3     .05       0  5013.5    .033       0  5031.3     .05       0
  5541.5    .075       0
Bank Sta=5013.5,5031.3
XS Rating Curve= 0 ,0
Exp/Cntr=0.3,0.1

Type RM Length L Ch R = 1 ,9807    ,358,358,358
BEGIN DESCRIPTION:
Cleveland Branch 27.0
END DESCRIPTION:
XS GIS Cut Line= 3
      2354928.98        7073560.        2354479.        7073560.
      2353964.74      7073656.42
#Sta/Elev= 30
    4550  632.86    4690  630.11    4810  628.51    4830  627.74    4870  627.74
    4920  626.61    4960  626.79    4980  625.72    4990  624.01  4995.5  622.78
  4995.7  622.28  4999.2  622.28  4999.5  622.78  5002.5  622.78  5010.2  624.93
 5016.35 625.716  5026.3  626.49    5061   625.9  5101.7  626.47  5111.9  626.18
  5299.3  628.52  5335.7  627.95  5376.4  629.82  5437.5  630.76    5468  631.77
  5478.2  631.49  5488.3  630.49  5498.5  632.36  5505.7  632.87  5523.2  633.26
#Mann= 4 ,-1 , 0
    4550     .05       0    4980    .033       0  4999.5     .05       0
  5505.7    .075       0
Bank Sta=4980,5016.35
XS Rating Curve= 0 ,0
Exp/Cntr=0.3,0.1

Type RM Length L Ch R = 1 ,9449    ,407,407,407
BEGIN DESCRIPTION:
Cleveland Branch 26.0
END DESCRIPTION:
XS GIS Cut Line= 3
      2354910.99      7073265.79      2354330.22      7073249.49
      2353928.96      7073360.01
#Sta/Elev= 30
    4419  632.68  4581.1   630.3  4731.1  627.16  4821.1  626.64  4841.2  625.29
  4891.2  624.09  4931.2  623.63  4951.2  624.48  4961.2  624.22  4971.2  622.65
  4981.2  622.21  4998.1  624.23  5011.6  624.42  5032.4   620.9  5051.1  618.69
  5051.4  618.19  5054.9  618.19  5055.1  618.69  5084.2  618.78  5092.8  619.86
  5097.9  619.85  5115.4  622.76  5132.3  627.83  5146.5  628.98  5171.9  629.81
  5239.8  627.72  5312.4  629.11  5374.7  631.15  5393.8  634.15  5416.2  635.31
#Mann= 3 ,-1 , 0
    4419     .05       0  5051.1    .033       0  5055.1     .05       0
Bank Sta=5051.1,5055.1
XS Rating Curve= 0 ,0
Exp/Cntr=0.3,0.1

Type RM Length L Ch R = 1 ,9042    ,283,283,283
BEGIN DESCRIPTION:
Cleveland Branch 25.0
END DESCRIPTION:
XS GIS Cut Line= 3
      2354952.67      7072967.18      2354279.33      7072875.17
      2353766.83      7073102.61
#Sta/Elev= 30
  4320.4  632.45  4559.7  629.92  4677.4  627.91  4776.5  625.38  4879.2  625.16
  4889.3  624.87  4899.4  623.66    4926  622.98  5033.2  622.51  5049.2  621.95
  5055.1  619.07  5070.5   617.4  5070.8   616.9  5074.3   616.9  5074.5   617.4
    5078  620.75  5087.9  621.92  5131.6  621.56  5186.4  623.48  5230.1  624.13
  5306.7  626.81  5344.9  627.45  5373.6  629.12  5391.4  631.26  5414.7  631.99
  5420.1  632.04  5437.9  629.48  5448.9  628.98  5495.4  631.06  5560.7  632.52
#Mann= 3 ,-1 , 0
  4320.4     .05       0  5070.5    .035       0  5074.5     .05       0
Bank Sta=5070.5,5074.5
XS Rating Curve= 0 ,0
Exp/Cntr=0.3,0.1

Type RM Length L Ch R = 1 ,8759    ,89,89,89
BEGIN DESCRIPTION:
Cleveland Branch 24.0
END DESCRIPTION:
XS GIS Cut Line= 3
      2355050.32      7072686.21      2354130.05      7072649.57
       2353653.6      7072634.14
#Sta/Elev= 30
    4079  629.98  4112.4  630.19  4160.4  629.37  4358.2  629.43  4363.2  628.38
  4370.5  628.28  4520.7  627.47  4608.9  626.46  4613.9  625.75  4640.8   625.1
  4800.9  623.39    4931  620.86    4951  619.71    4971   617.7    4979  615.46
  4979.3  614.96  4982.8  614.96    4983  615.46    4991  615.75  5021.1  620.31
  5031.1  620.88  5181.1  624.08  5271.2  624.54  5281.2  624.93  5301.2  628.04
  5322.7  629.94  5361.2  631.36  5381.2  629.71  5401.3  629.31  5476.7  631.34
#Mann= 4 ,-1 , 0
    4079     .05       0    4979    .035       0    4983     .05       0
  5322.7    .075       0
Bank Sta=4979,4983
XS Rating Curve= 0 ,0
Exp/Cntr=0.3,0.1

Type RM Length L Ch R = 1 ,8670    ,222,222,222
BEGIN DESCRIPTION:
Mapping XS 775d078f
END DESCRIPTION:
XS GIS Cut Line= 4
      2355071.26      7072592.81       2354128.9      7072560.69
      2353792.61      7072548.54      2353642.31      7072543.39
#Sta/Elev= 30
  4057.1  628.16  4129.4  628.95  4149.4  628.27  4229.5  628.07  4279.5  629.33
  4299.5  628.34  4459.6  628.38  4577.3  626.65  4582.3  627.12  4659.7  625.58
  4689.7  625.77  4719.7  624.36  4949.9  618.82  4969.9   617.3  4987.9   614.6
  4988.1   614.1  4991.6   614.1  4991.9   614.6  4997.5  617.91  5009.9  618.72
  5156.3  621.77  5161.3  621.42    5274  625.64  5310.1  627.23  5380.1  633.01
  5410.2  634.28  5420.2  634.54  5437.5  633.77  5442.5  632.71  5486.9  633.31
#Mann= 4 ,-1 , 0
  4057.1     .05       0  4987.9     .05       0  4991.9     .05       0
    5274    .075       0
Bank Sta=4987.9,4991.9
XS Rating Curve= 0 ,0
Exp/Cntr=0.3,0.1

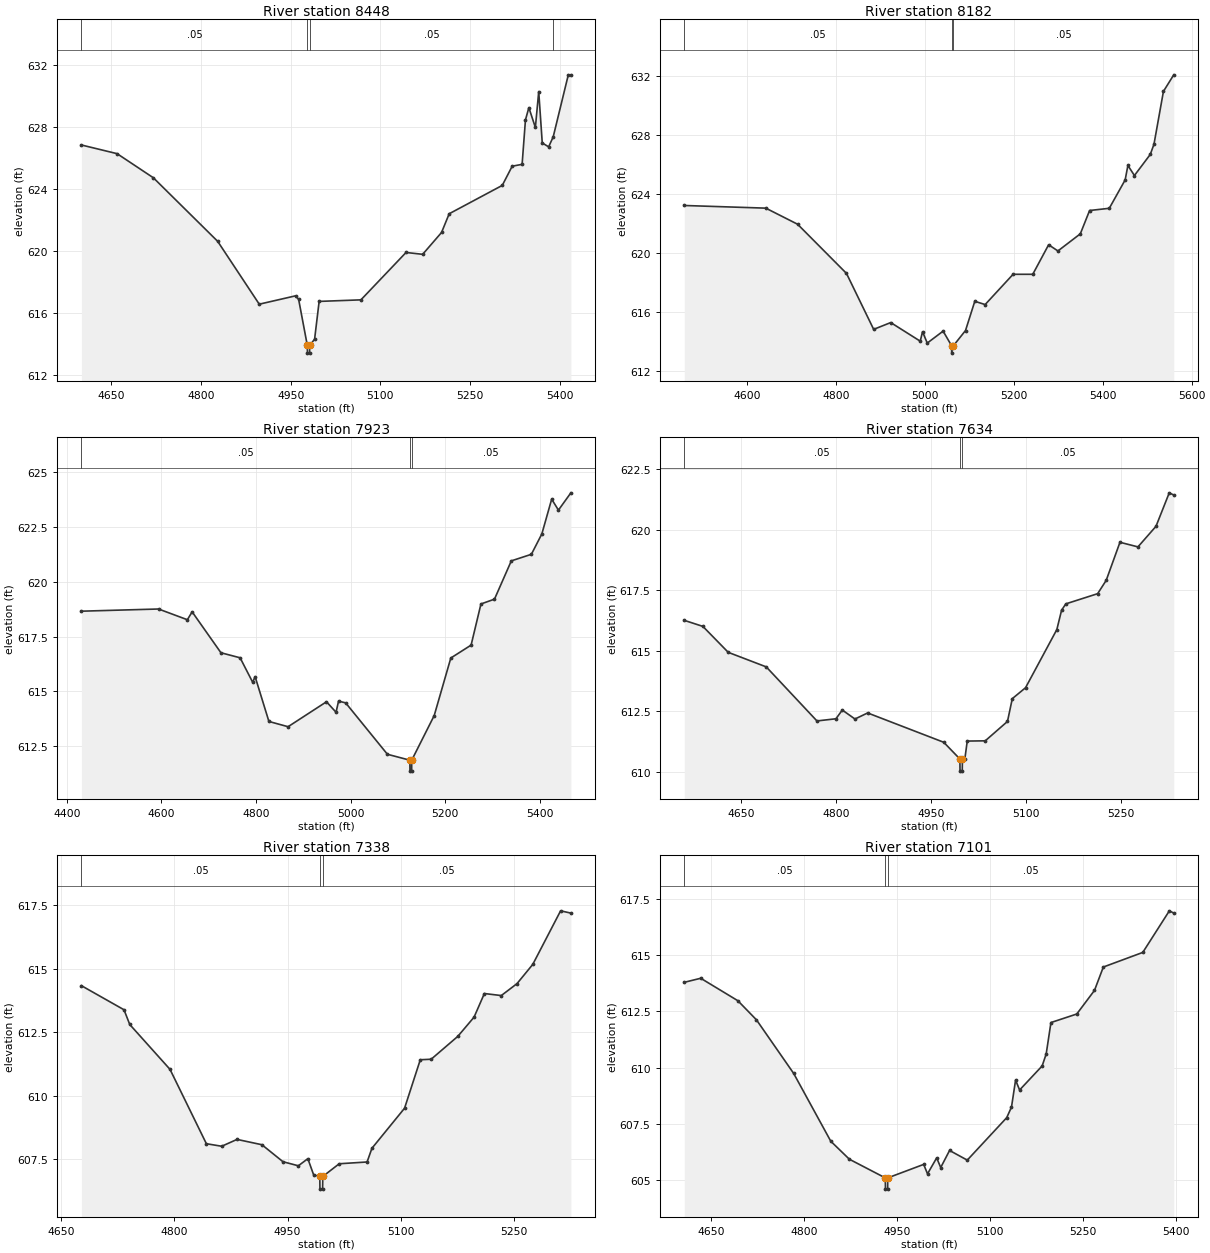
Type RM Length L Ch R = 1 ,8448    ,266,266,266
BEGIN DESCRIPTION:
Cleveland Branch 23.0
END DESCRIPTION:
XS GIS Cut Line= 3
      2354523.83      7072404.68      2354129.01      7072338.71
      2353756.41       7072529.7
#Sta/Elev= 30
  4599.7  626.83  4659.4  626.27  4720.2  624.71  4827.7  620.61  4897.3  616.55
  4958.1  617.09  4963.2  616.86  4977.7  613.89    4978  613.39  4981.5  613.39
  4981.7  613.89  4989.9  614.29  4997.5  616.73  5067.4  616.83  5142.9  619.89
  5170.7  619.77  5202.3  621.18  5215.1  622.39  5303.9  624.22  5320.5  625.46
  5337.1  625.58  5342.7  628.45  5348.4  629.24  5359.3  627.96  5364.9  630.28
  5370.8  626.96  5381.5  626.71  5389.1  627.35  5414.4  631.36  5418.7  631.36
#Mann= 4 ,-1 , 0
  4599.7     .05       0  4977.7    .033       0  4981.7     .05       0
  5389.1    .075       0
Bank Sta=4977.7,4981.7
XS Rating Curve= 0 ,0
Exp/Cntr=0.3,0.1

Type RM Length L Ch R = 1 ,8182    ,259,259,259
BEGIN DESCRIPTION:
Cleveland Branch 22.0
END DESCRIPTION:
XS GIS Cut Line= 3
      2354648.84       7072227.6      2354129.33      7072073.12
      2353672.71      7072396.79
#Sta/Elev= 30
    4458  623.23  4641.5  623.05  4713.1  621.96  4823.1  618.63  4884.3  614.84
  4922.7   615.3  4989.1  614.04  4994.3  614.68  5004.9  613.91  5040.6  614.72
  5059.7  613.73  5059.9  613.23  5063.7  613.73    5091  614.76  5111.9  616.74
  5135.2  616.52  5198.1  618.57  5242.4  618.57  5278.1  620.57    5299  620.15
  5349.4  621.31  5370.3  622.89  5414.6  623.04  5450.3  624.96  5456.5  625.94
  5471.2  625.26  5506.9  626.69  5515.2  627.38  5536.5  630.96  5559.7  632.08
#Mann= 3 ,-1 , 0
    4458     .05       0  5059.7    .033       0  5063.7     .05       0
Bank Sta=5059.7,5063.7
XS Rating Curve= 0 ,0
Exp/Cntr=0.3,0.1

Type RM Length L Ch R = 1 ,7923    ,289,289,289
BEGIN DESCRIPTION:
Cleveland Branch 21.0
END DESCRIPTION:
XS GIS Cut Line= 3
      2354549.85      7071965.44      2353988.68      7071870.78
      2353632.75      7072170.94
#Sta/Elev= 30
  4430.9  618.66    4594  618.76  4654.9  618.27    4665  618.63  4725.9  616.76
  4766.4  616.53    4793  615.41  4798.1  615.67  4827.3  613.62  4867.8  613.38
    4949  614.52  4969.2  614.04  4974.5  614.55  4989.5  614.47  5077.8  612.12
  5125.2  611.85  5125.5  611.35    5129  611.35  5129.2  611.85  5176.7  613.89
  5211.8  616.52  5254.7  617.11  5275.5  618.99  5304.1  619.21  5339.7  620.96
  5382.1  621.26  5404.2  622.19    5425  623.78  5439.3  623.28  5465.6  624.07
#Mann= 3 ,-1 , 0
  4430.9     .05       0  5125.2    .033       0  5129.2     .05       0
Bank Sta=5125.2,5129.2
XS Rating Curve= 0 ,0
Exp/Cntr=0.3,0.1

Type RM Length L Ch R = 1 ,7634    ,296,296,296
BEGIN DESCRIPTION:
Cleveland Branch 20.0
END DESCRIPTION:
XS GIS Cut Line= 3
      2354218.36      7071699.26      2353778.96      7071690.02
      2353528.98      7071910.02
#Sta/Elev= 30
  4560.5  616.26  4589.9  616.01  4629.9  614.94  4689.9  614.34  4769.9  612.11
  4799.9   612.2  4809.9  612.56  4829.9  612.19  4849.9  612.44    4970  611.23
  4995.5  610.54  4995.7  610.04  4999.2  610.04  4999.5  610.54  5003.3  610.54
  5007.1  611.28  5035.5  611.29  5070.6  612.09  5078.2  613.03  5099.1  613.48
  5148.5  615.88    5156  616.68  5162.7  616.94  5212.9  617.36  5226.4  617.91
  5248.1  619.48  5276.5  619.29    5305  620.14  5325.9  621.52    5333  621.43
#Mann= 3 ,-1 , 0
  4560.5     .05       0  4995.5     .04       0  4999.5     .05       0
Bank Sta=4995.5,4999.5
XS Rating Curve= 0 ,0
Exp/Cntr=0.3,0.1

Type RM Length L Ch R = 1 ,7338    ,237,237,237
BEGIN DESCRIPTION:
Cleveland Branch 19.0
END DESCRIPTION:
XS GIS Cut Line= 3
      2354052.17      7071356.14        2353729.        7071410.
      2353478.99      7071610.01
#Sta/Elev= 30
  4677.1  614.33  4733.5  613.38  4741.1   612.8  4794.4  611.03  4842.5   608.1
  4862.8     608  4883.1  608.27    4916  608.06  4943.9  607.39  4964.2  607.23
  4976.8  607.51  4984.5  606.87  4992.6  606.81  4992.8  606.31  4996.3  606.31
  4996.6  606.81  5018.3  607.31  5055.2  607.38  5061.6  607.92  5104.8   609.5
  5125.6  611.41    5140  611.43  5175.2  612.33  5196.8  613.09  5210.4  614.02
  5232.8  613.94  5253.6  614.41  5274.5  615.17  5311.3  617.28  5324.9  617.19
#Mann= 3 ,-1 , 0
  4677.1     .05       0  4992.6    .033       0  4996.6     .05       0
Bank Sta=4992.6,4996.6
XS Rating Curve= 0 ,0
Exp/Cntr=0.3,0.1

Type RM Length L Ch R = 1 ,7101    ,231,231,231
BEGIN DESCRIPTION:
Cleveland Branch 18.0
END DESCRIPTION:
XS GIS Cut Line= 3
      2354025.57        7071210.      2353631.71      7071203.88
      2353329.02      7071459.98
#Sta/Elev= 30
  4606.1  613.79  4632.7  613.97  4692.7  612.97  4722.7  612.12  4782.7  609.74
  4842.7  606.72  4872.7  605.92  4930.7  605.09    4931  604.59  4934.5  604.59
  4934.7  605.09  4992.7  605.69  4998.9  605.27  5013.7  605.98  5020.2  605.55
  5034.5  606.31  5063.1  605.88  5126.8  607.77  5134.5  608.24  5141.1  609.44
  5147.6     609    5184  610.07  5190.5   610.6  5198.2     612  5239.9  612.38
  5268.5  613.43  5282.8  614.47  5346.5  615.12  5389.4  616.97  5396.5  616.87
#Mann= 3 ,-1 , 0
  4606.1     .05       0  4930.7     .04       0  4934.7     .05       0
Bank Sta=4930.7,4934.7
XS Rating Curve= 0 ,0
Exp/Cntr=0.3,0.1

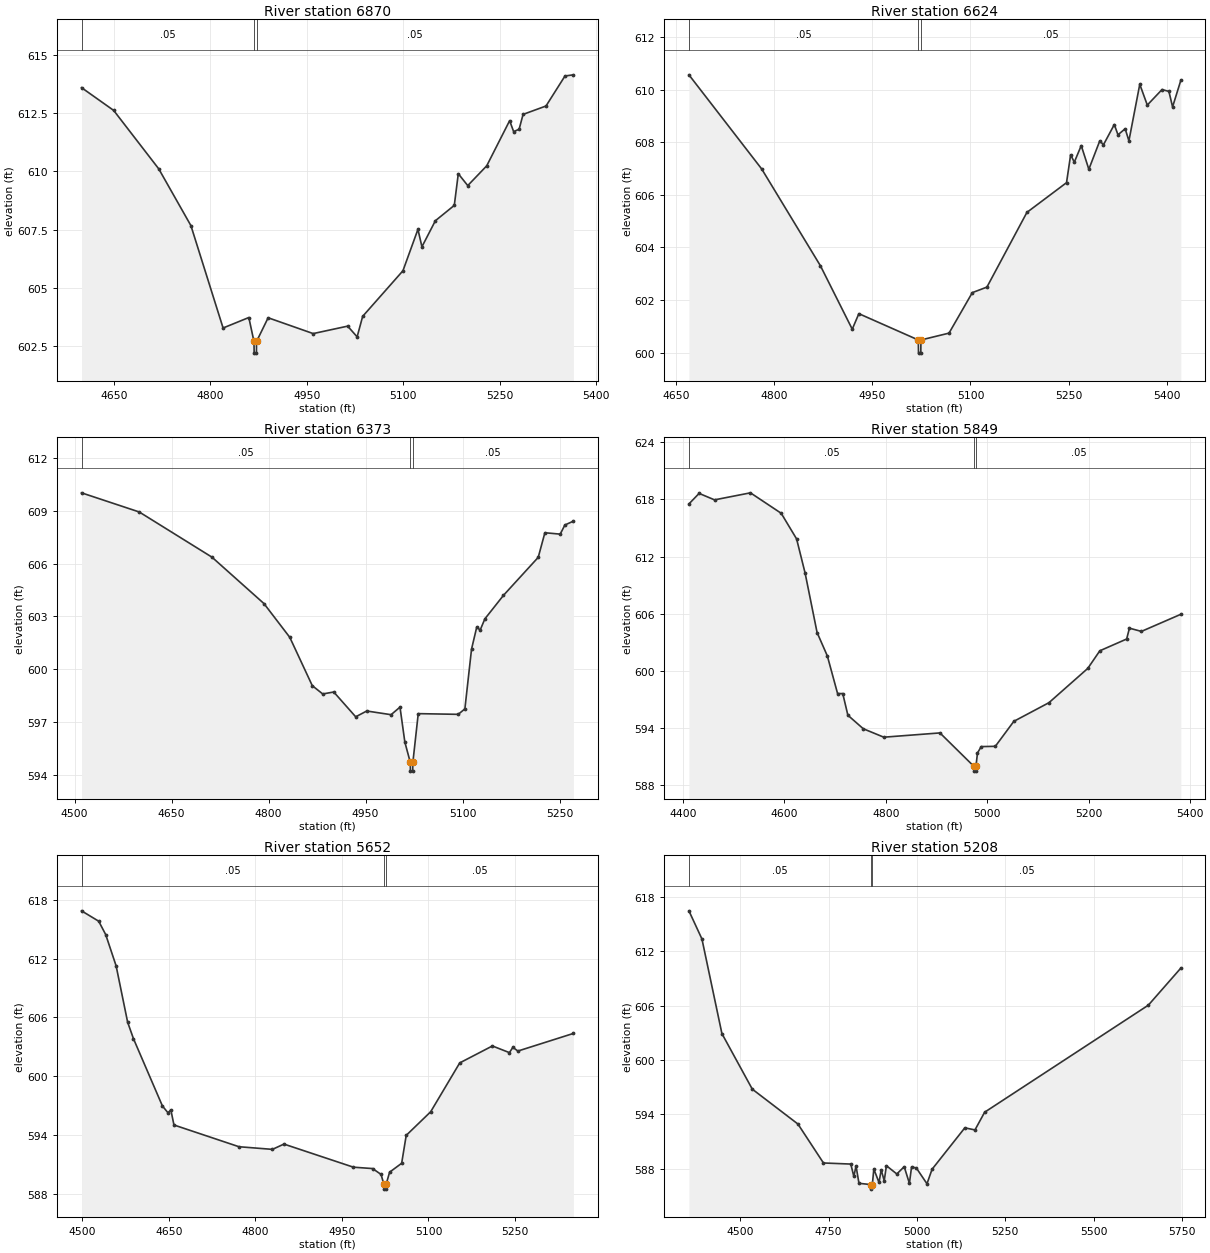
Type RM Length L Ch R = 1 ,6870    ,246,246,246
BEGIN DESCRIPTION:
Cleveland Branch 17.0
END DESCRIPTION:
XS GIS Cut Line= 3
      2353929.04        7071010.        2353529.        7071010.
       2353232.9      7071222.34
#Sta/Elev= 30
  4599.9   613.6  4649.9  612.62  4719.9  610.11  4769.9  607.67  4819.9  603.27
  4859.9  603.72  4867.9  602.69  4868.2  602.19  4871.7  602.19  4871.9  602.69
  4889.9  603.71  4959.9  603.03  5013.5  603.35  5028.2  602.89  5036.8  603.77
  5099.4  605.73  5122.7  607.51  5128.9  606.76  5149.8  607.88  5179.2  608.54
  5185.4   609.9  5200.1  609.39  5229.6  610.24  5265.2  612.18  5271.4  611.71
  5279.9  611.81  5286.1  612.45  5321.7  612.81  5351.2   614.1  5364.3  614.15
#Mann= 3 ,-1 , 0
  4599.9     .05       0  4867.9     .04       0  4871.9     .05       0
Bank Sta=4867.9,4871.9
XS Rating Curve= 0 ,0
Exp/Cntr=0.3,0.1

Type RM Length L Ch R = 1 ,6624    ,251,251,251
BEGIN DESCRIPTION:
Cleveland Branch 16.0
END DESCRIPTION:
XS GIS Cut Line= 3
       2353806.9      7070817.28      2353478.91      7070780.04
      2353103.38      7070971.03
#Sta/Elev= 30
  4669.9  610.56  4781.1  606.98  4870.8   603.3  4919.4  600.89  4929.5  601.48
  5020.3  600.48  5020.6  599.98  5024.1  599.98  5024.3  600.48  5067.2  600.74
  5102.8  602.28  5125.1  602.49  5186.2  605.33  5246.7  606.46    5253  607.52
  5258.6  607.24  5269.2  607.87  5280.8  606.97  5297.5  608.05  5303.1   607.9
  5319.7  608.67  5325.3  608.28  5336.3  608.51    5342  608.05  5358.6   610.2
  5370.1  609.41  5392.6     610  5403.1  609.93  5408.7  609.34  5421.3  610.35
#Mann= 3 ,-1 , 0
  4669.9     .05       0  5020.3    .033       0  5024.3     .05       0
Bank Sta=5020.3,5024.3
XS Rating Curve= 0 ,0
Exp/Cntr=0.3,0.1

Type RM Length L Ch R = 1 ,6373    ,524,524,524
BEGIN DESCRIPTION:
Cleveland Branch 15.0
END DESCRIPTION:
XS GIS Cut Line= 3
      2353871.14      7070755.07      2353429.43      7070544.82
      2353166.17       7070610.4
#Sta/Elev= 30
  4510.8  610.03  4600.1  608.94  4712.5  606.37  4792.9  603.73  4832.8  601.81
  4867.6  599.06  4883.7  598.59  4900.8   598.7  4934.7  597.29  4951.8  597.62
  4989.4  597.41  5003.2  597.84  5010.7  595.85  5019.1   594.7  5019.3   594.2
  5022.8   594.2  5023.1   594.7  5031.4  597.47  5093.2  597.43  5103.5  597.74
  5113.8  601.14  5121.9   602.4  5127.1  602.22  5134.4  602.86  5163.2   604.2
  5216.9  606.36  5227.2  607.76  5250.9  607.68  5258.1   608.2  5271.3  608.42
#Mann= 3 ,-1 , 0
  4510.8     .05       0  5019.1    .033       0  5023.1     .05       0
Bank Sta=5019.1,5023.1
XS Rating Curve= 0 ,0
Exp/Cntr=0.3,0.1

Type RM Length L Ch R = 1 ,5849    ,197,197,197
BEGIN DESCRIPTION:
Cleveland Branch 14.0
END DESCRIPTION:
XS GIS Cut Line= 3
       2354148.9      7070060.62      2353567.16      7070148.23
      2353215.68      7070296.58
#Sta/Elev= 30
  4411.7  617.53  4431.8  618.64  4462.2  617.96    4533   618.7  4593.6  616.55
    4624  613.85  4640.8  610.25  4664.4     604  4684.6  601.54  4704.8  597.58
    4715  597.58  4725.1   595.3  4755.4  593.88  4795.9  592.99  4906.6  593.44
  4973.6  589.92  4973.8  589.42  4977.3  589.42  4977.6  589.92  4980.6  591.33
    4988     592  5015.8  592.03  5052.3  594.66  5121.5  596.62  5198.1  600.23
  5221.8  602.08  5274.7  603.32  5280.2  604.46  5303.8  604.12  5381.5  605.92
#Mann= 3 ,-1 , 0
  4411.7     .05       0  4973.6    .033       0  4977.6     .05       0
Bank Sta=4973.6,4977.6
XS Rating Curve= 0 ,0
Exp/Cntr=0.3,0.1

Type RM Length L Ch R = 1 ,5652    ,444,444,444
BEGIN DESCRIPTION:
Cleveland Branch 13.0
END DESCRIPTION:
XS GIS Cut Line= 3
      2353978.73      7070028.36        2353479.        7069985.
      2353193.13      7070189.18
#Sta/Elev= 30
  4498.4  616.87  4528.2  615.81  4540.3  614.45  4558.4  611.25  4578.4  605.49
  4588.5  603.81  4638.7  596.94  4648.3  596.25  4653.3  596.54  4658.7     595
  4771.4  592.78  4829.4  592.51  4849.4  593.05  4969.9  590.69  5003.1  590.55
  5017.8  589.95  5022.6  588.95  5022.8  588.45  5026.3  588.45  5026.6  588.95
  5032.6  590.18  5053.5  591.09  5061.4  593.94  5103.8  596.35  5154.2  601.34
  5210.8  603.07  5240.3  602.39  5246.4  602.93    5255  602.55  5351.3  604.35
#Mann= 3 ,-1 , 0
  4498.4     .05       0  5022.6     .04       0  5026.6     .05       0
Bank Sta=5022.6,5026.6
XS Rating Curve= 0 ,0
Exp/Cntr=0.3,0.1

Type RM Length L Ch R = 1 ,5208    ,367,367,367
BEGIN DESCRIPTION:
Cleveland Branch 12.0
END DESCRIPTION:
XS GIS Cut Line= 3
      2353979.03      7070010.02      2353456.09      7069632.97
      2352879.03      7069160.03
#Sta/Elev= 30
  4355.3  616.43  4392.1  613.33  4448.6  602.91  4534.5  596.79  4663.5  592.95
  4735.7  588.66    4813  588.54  4821.6  587.18  4827.8  588.33  4836.1  586.42
  4869.9  586.28  4870.1  585.78  4873.9  586.28  4878.1  587.99  4892.8  586.51
  4898.9  587.91  4907.5   586.7  4913.7  588.36  4943.1  587.45    4964  588.25
  4978.7  586.42  4984.8  588.22  4998.3  588.11  5028.4  586.37  5042.8  587.97
  5135.4  592.53  5164.1   592.3  5191.4  594.25  5654.3  606.04  5746.1  610.12
#Mann= 3 ,-1 , 0
  4355.3     .05       0  4869.9    .033       0  4873.9     .05       0
Bank Sta=4869.9,4873.9
XS Rating Curve= 0 ,0
Exp/Cntr=0.3,0.1

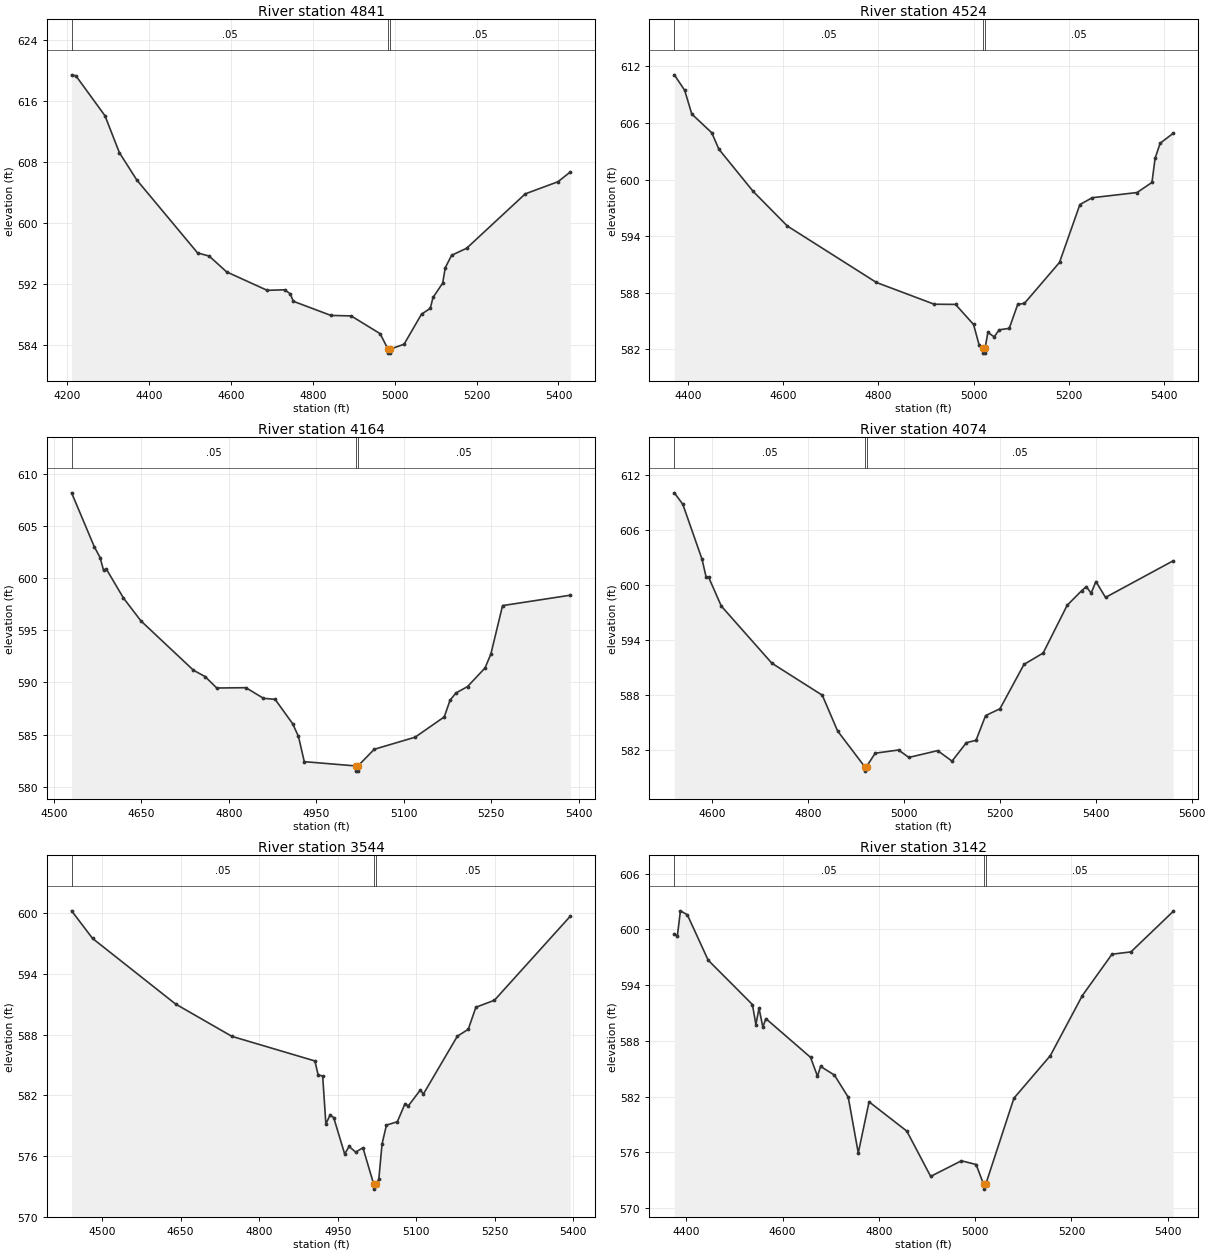
Type RM Length L Ch R = 1 ,4841    ,317,317,317
BEGIN DESCRIPTION:
Cleveland Branch 11.0
END DESCRIPTION:
XS GIS Cut Line= 3
      2354131.08      7069923.12      2353588.86      7069349.96
       2353223.3      7069125.43
#Sta/Elev= 30
    4211  619.43  4221.7  619.29  4292.5  614.07  4327.7  609.23  4370.2  605.65
  4518.7  596.09    4547  595.68  4589.5  593.61  4688.6  591.19  4731.1  591.26
  4745.2  590.73  4752.2  589.76  4844.3   587.9  4893.7  587.84  4964.5  585.51
  4983.9  583.46  4984.2  582.96  4987.7  582.96  4987.9  583.46    5023  584.13
  5065.6  588.07  5086.9  588.82  5093.7  590.26  5117.2  592.13  5123.6  594.15
    5139  595.78  5175.7   596.7  5318.9  603.83  5398.8  605.42    5429   606.7
#Mann= 3 ,-1 , 0
    4211     .05       0  4983.9    .033       0  4987.9     .05       0
Bank Sta=4983.9,4987.9
XS Rating Curve= 0 ,0
Exp/Cntr=0.3,0.1

Type RM Length L Ch R = 1 ,4524    ,360,360,360
BEGIN DESCRIPTION:
Cleveland Branch 10.0
END DESCRIPTION:
XS GIS Cut Line= 3
      2354300.33      7069478.22      2353779.96      7069125.58
      2353383.21      7068990.23
#Sta/Elev= 30
  4371.4  611.11    4393  609.47    4408  606.95    4450  604.96  4464.9  603.22
  4536.8  598.75  4608.7  595.07  4795.8  589.08  4917.3  586.77  4962.1  586.75
    5000  584.62  5011.6  582.46  5020.1  582.08  5020.4  581.58  5023.9  581.58
  5024.1  582.08  5030.1  583.78  5043.3  583.31  5053.8  584.05    5075  584.21
  5092.8  586.76  5106.7  586.85  5180.6  591.21  5223.4  597.35  5249.4  598.07
  5343.4  598.62  5374.8  599.69  5381.4  602.26    5392  603.85  5419.2   604.9
#Mann= 3 ,-1 , 0
  4371.4     .05       0  5020.1    .033       0  5024.1     .05       0
Bank Sta=5020.1,5024.1
XS Rating Curve= 0 ,0
Exp/Cntr=0.3,0.1

Type RM Length L Ch R = 1 ,4164    ,90,90,90
BEGIN DESCRIPTION:
Mapping XS a45e2757
END DESCRIPTION:
XS GIS Cut Line= 3
      2354347.85      7068876.42       2353880.2      7068864.48
      2353492.85      7068857.99
#Sta/Elev= 30
  4530.6  608.23  4569.5  603.05  4579.5     602  4585.3   600.8  4590.3  600.89
  4619.5  598.12  4649.5  595.92  4739.5  591.18  4759.5  590.57  4779.5  589.47
  4829.5   589.5  4859.6  588.48  4879.6  588.38  4909.6  586.04  4919.6  584.82
  4929.6  582.39  5017.6  581.98  5017.9  581.48  5021.4  581.48  5021.7  581.98
  5049.6  583.58  5119.6  584.74  5169.6  586.69  5179.6   588.3  5189.6  588.99
  5209.6  589.61  5239.6   591.4  5249.6  592.74  5269.6  597.39  5385.8  598.39
#Mann= 3 ,-1 , 0
  4530.6     .05       0  5017.6    .033       0  5021.7     .05       0
Bank Sta=5017.6,5021.7
XS Rating Curve= 0 ,0
Exp/Cntr=0.3,0.1

Type RM Length L Ch R = 1 ,4074    ,530,530,530
BEGIN DESCRIPTION:
Cleveland Branch 9.0
END DESCRIPTION:
XS GIS Cut Line= 3
      2354356.56      7068810.23       2353879.4      7068774.42
      2353318.11      7068772.25
#Sta/Elev= 30
  4521.5  610.01  4539.1  608.76  4579.2  602.78  4587.8  600.82  4592.8  600.84
  4619.3  597.69  4724.8  591.47  4829.9  587.99  4861.8   584.1  4918.1  580.23
  4918.4  579.73  4922.2  580.23  4940.2  581.68  4988.8  582.03  5010.4  581.22
  5070.4  581.96  5100.4  580.82  5130.4  582.83  5150.4  583.08  5170.4  585.77
  5200.4  586.52  5250.4  591.34  5290.4  592.58  5340.4  597.77  5370.4  599.35
  5380.4   599.8  5390.4  599.09  5400.4  600.36  5420.4  598.63  5561.3  602.61
#Mann= 3 ,-1 , 0
  4521.5     .05       0  4918.1    .033       0  4922.2     .05       0
Bank Sta=4918.1,4922.2
XS Rating Curve= 0 ,0
Exp/Cntr=0.3,0.1

Type RM Length L Ch R = 1 ,3544    ,402,402,402
BEGIN DESCRIPTION:
Cleveland Branch 8.0
END DESCRIPTION:
XS GIS Cut Line= 3
       2354306.8       7068707.8      2353845.59        7068393.
       2353529.9      7068156.59
#Sta/Elev= 30
  4441.6  600.23  4481.7   597.5  4640.2  591.02  4747.9  587.82  4906.4  585.39
  4912.5  584.03  4921.3  583.89  4927.4  579.16  4935.3  580.03  4942.3   579.8
  4963.3  576.19  4971.7  576.94  4984.3  576.38  4998.2  576.81  5018.7  573.22
    5019  572.72  5022.8  573.22  5028.5  573.68  5034.7  577.18  5043.1  579.05
  5063.9  579.38  5078.5  581.15  5084.8  580.95  5107.7   582.5  5113.9  582.14
  5178.5  587.83  5199.4  588.52    5214   590.7  5249.4  591.39  5394.4   599.7
#Mann= 3 ,-1 , 0
  4441.6     .05       0  5018.7    .033       0  5022.8     .05       0
Bank Sta=5018.7,5022.8
XS Rating Curve= 0 ,0
Exp/Cntr=0.3,0.1

Type RM Length L Ch R = 1 ,3142    ,501,501,501
BEGIN DESCRIPTION:
Cleveland Branch 7.0
END DESCRIPTION:
XS GIS Cut Line= 3
      2354465.27      7068451.76        2353979.        7068060.
      2353572.56      7067994.07
#Sta/Elev= 30
  4375.1  599.49  4381.3  599.31  4387.7     602  4402.1  601.57  4445.3  596.69
  4537.3  591.91  4544.5  589.74  4550.9  591.52  4558.9  589.49  4565.3  590.39
    4658  586.23  4672.4   584.2  4678.9  585.25  4707.6  584.32  4736.4  581.93
  4757.2  575.93  4779.6  581.44    4858  578.29  4907.6  573.41  4971.5  575.09
  5002.1  574.69  5017.7  572.54  5018.1  572.04  5021.9  572.54  5080.6  581.83
  5156.1   586.4  5222.8  592.88  5284.4  597.33  5323.7  597.58  5411.3  601.93
#Mann= 3 ,-1 , 0
  4375.1     .05       0  5017.7     .04       0  5021.9     .05       0
Bank Sta=5017.7,5021.9
XS Rating Curve= 0 ,0
Exp/Cntr=0.3,0.1

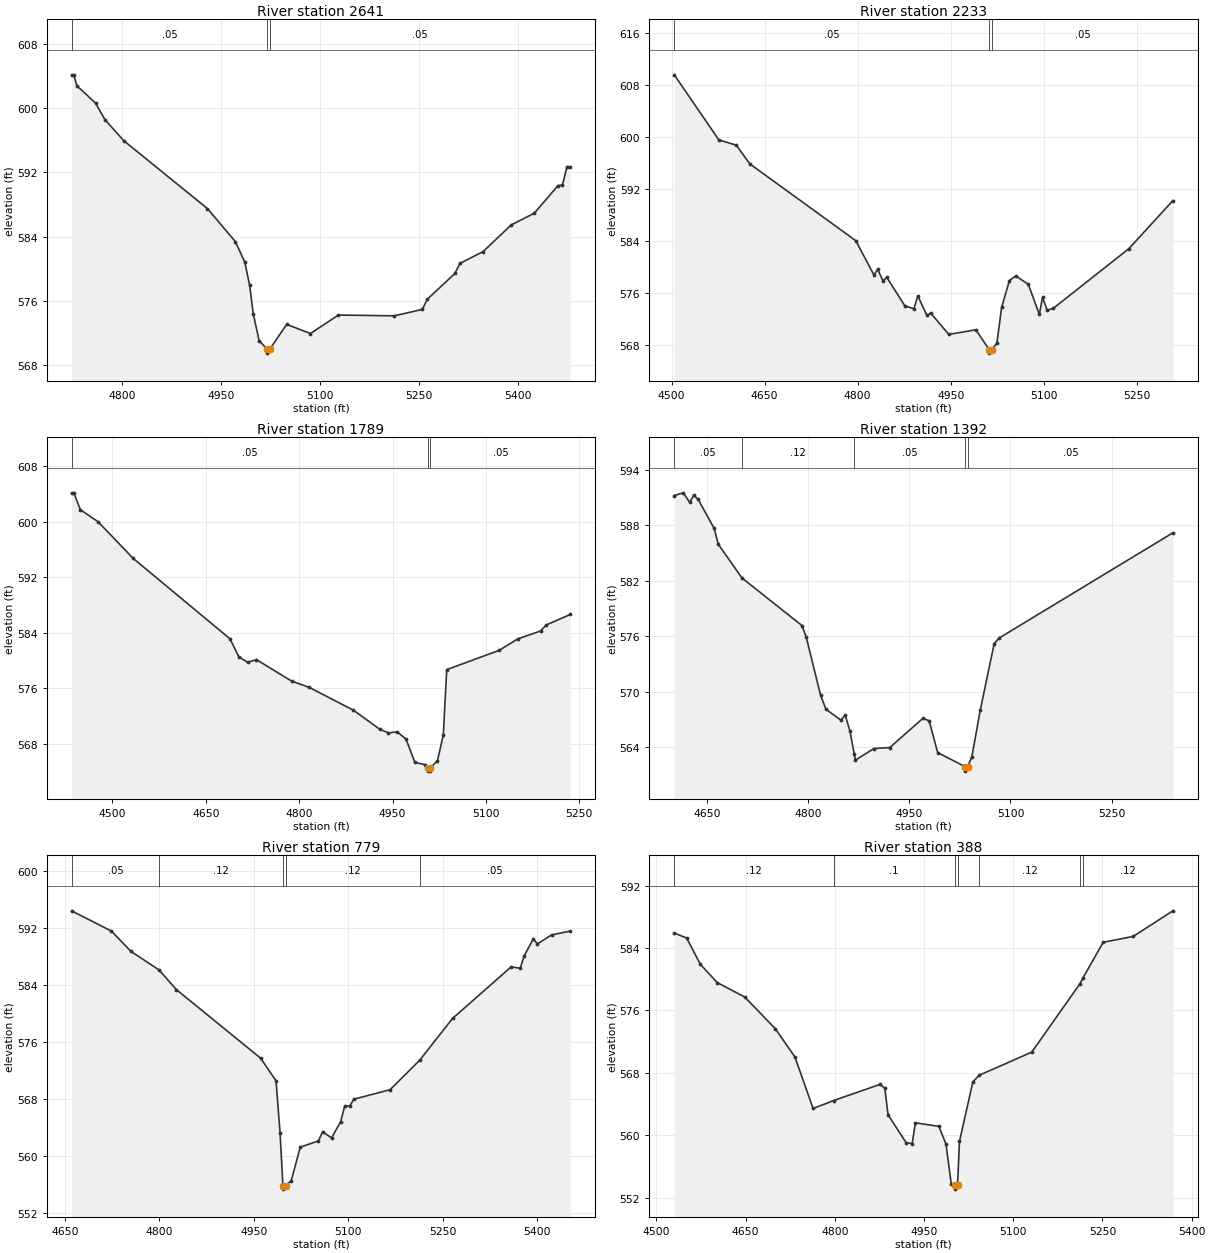
Type RM Length L Ch R = 1 ,2641    ,408,408,408
BEGIN DESCRIPTION:
Cleveland Branch 6.0
END DESCRIPTION:
XS GIS Cut Line= 3
      2354508.65      7068271.62      2354305.95      7068083.86
      2353946.57      7067765.96
#Sta/Elev= 30
  4723.7  604.13  4726.9  604.13  4731.7  602.78  4760.1   600.6  4774.3  598.55
  4802.6  595.95  4929.6  587.49  4972.1  583.37  4986.3  580.83  4993.7  577.93
  4999.2  574.37    5008  571.06  5020.1     570  5020.4   569.5  5024.4     570
  5049.8  573.08  5085.8  571.94  5128.4  574.24  5212.9  574.14  5255.6  574.94
  5262.9  576.19  5304.9  579.41  5312.5  580.66  5347.6  582.13  5390.2  585.44
  5425.4  586.92  5461.3  590.35    5468   590.4  5474.8  592.69  5479.8  592.69
#Mann= 3 ,-1 , 0
  4723.7     .05       0  5020.1     .04       0  5024.4     .05       0
Bank Sta=5020.1,5024.4
XS Rating Curve= 0 ,0
Exp/Cntr=0.3,0.1

Type RM Length L Ch R = 1 ,2233    ,444,444,444
BEGIN DESCRIPTION:
Cleveland Branch 5.0
END DESCRIPTION:
XS GIS Cut Line= 3
      2354678.99      7068059.99        2354279.        7067760.
      2353979.02        7067710.
#Sta/Elev= 30
  4504.3  609.59  4576.2  599.55  4604.3  598.74  4626.2  595.85    4797  584.01
  4826.2  578.73  4832.4  579.59  4840.7  577.82    4847  578.35  4876.2  573.95
  4890.7  573.52    4897  575.51  4911.6  572.49  4917.8  572.84    4947  569.56
  4990.7  570.27  5012.3  567.17  5012.6  566.67  5016.6  567.17  5024.6  568.24
  5032.2  573.73  5044.8  577.87    5055  578.57  5075.2  577.29    5093  572.63
  5098.1  575.28  5105.7  573.27  5115.8   573.6  5237.5  582.79  5308.4   590.2
#Mann= 3 ,-1 , 0
  4504.3     .05       0  5012.3     .04       0  5016.6     .05       0
Bank Sta=5012.3,5016.6
XS Rating Curve= 0 ,0
Exp/Cntr=0.3,0.1

Type RM Length L Ch R = 1 ,1789    ,397,397,397
BEGIN DESCRIPTION:
Cleveland Branch 4.0
END DESCRIPTION:
XS GIS Cut Line= 3
      2354778.99      7067809.99        2354379.        7067410.
      2354165.75      7067310.24
#Sta/Elev= 30
  4434.3  604.15  4437.8  604.15  4448.4  601.72  4476.7  599.99  4533.3   594.7
  4688.8  583.11    4703  580.51  4717.1  579.73  4731.3  580.11  4787.8  577.02
  4816.1  576.11  4886.8  572.85  4929.3  570.09  4943.4  569.56  4957.5  569.71
  4971.7  568.65  4985.8   565.3  5002.7  564.97  5006.5  564.55  5006.8  564.05
  5010.4  564.05  5010.8  564.55  5022.1  565.54  5031.5  569.27    5037  578.67
  5121.4  581.46  5151.2  583.11  5187.7  584.24  5196.9  585.11  5235.4  586.62
#Mann= 3 ,-1 , 0
  4434.3     .05       0  5006.5    .033       0  5010.8     .05       0
Bank Sta=5006.5,5010.8
XS Rating Curve= 0 ,0
Exp/Cntr=0.3,0.1

Type RM Length L Ch R = 1 ,1392    ,613,613,613
BEGIN DESCRIPTION:
Cleveland Branch 3.0
END DESCRIPTION:
XS GIS Cut Line= 3
      2354828.97      7066960.02      2354492.37      7067173.32
      2354162.68      7067260.02
#Sta/Elev= 30
  4601.5  591.22    4615  591.51  4624.4  590.47  4630.3  591.24    4637  590.79
  4660.7  587.66  4666.7  585.96  4701.8  582.31  4790.9  577.16  4797.2  575.91
  4818.4  569.64  4826.4  568.12  4848.9  566.92  4854.8  567.51  4861.9  565.78
  4868.4  563.28  4870.1  562.62  4897.4  563.87  4921.1  563.98  4970.1  567.13
  4979.4  566.88  4992.1  563.43  5032.3  561.93  5032.7  561.43  5036.7  561.93
  5042.8  562.99  5055.2  568.02  5075.9  575.21  5083.1  575.81  5340.9  587.19
#Mann= 5 ,-1 , 0
  4601.5     .05       0  4701.8     .12       0  4868.4     .05       0
  5032.3    .033       0  5036.7     .05       0
Bank Sta=5032.3,5036.7
XS Rating Curve= 0 ,0
Exp/Cntr=0.3,0.1

Type RM Length L Ch R = 1 ,779     ,391,391,391
BEGIN DESCRIPTION:
Cleveland Branch 2.0
END DESCRIPTION:
XS GIS Cut Line= 3
      2354710.46      7066617.99      2354380.92       7066698.8
      2354026.86      7066980.42
#Sta/Elev= 30
  4660.7  594.37    4724  591.53  4754.9  588.69  4799.7  586.08  4826.9  583.35
  4960.8  573.73  4985.3  570.56  4991.7  563.25  4996.2  555.89  4996.6  555.39
  5000.7  555.89  5009.4  556.57  5023.8  561.28  5052.7  562.14  5059.1  563.43
  5073.5  562.57  5087.9  564.85  5094.3  567.02  5102.3  567.02  5108.7  567.98
  5166.4  569.32  5213.2  573.43  5265.7  579.31  5358.6  586.52    5373  586.32
  5379.4  588.09  5393.8  590.44  5400.2  589.73  5422.7  590.99  5452.4  591.54
#Mann= 5 ,-1 , 0
  4660.7     .05       0  4799.7     .12       0  4996.2     .07       0
  5000.7     .12       0  5213.2     .05       0
Bank Sta=4996.2,5000.7
XS Rating Curve= 0 ,0
Exp/Cntr=0.3,0.1

Type RM Length L Ch R = 1 ,388     ,0,0,0
BEGIN DESCRIPTION:
Cleveland Branch 1.0
END DESCRIPTION:
XS GIS Cut Line= 3
      2354543.38      7066266.42      2354116.35      7066462.28
      2353953.55      7066792.87
#Sta/Elev= 30
  4530.2  585.93  4551.1  585.27  4574.1   581.9  4602.6  579.56  4648.6  577.72
  4700.1  573.65    4733  570.03  4763.6  563.42  4798.1  564.44  4876.1  566.51
  4884.1  566.03  4889.6  562.62  4920.1  559.02  4930.1  558.93  4935.6  561.58
  4975.1  561.13  4987.1  558.82  4995.8  553.77  5001.9  553.58  5002.4  553.08
  5006.4  553.58  5009.7  559.21  5032.2  566.84    5043  567.69  5131.2  570.65
  5212.5  579.45  5217.3  580.18  5251.3  584.73  5301.8  585.49  5368.5  588.77
#Mann= 7 ,-1 , 0
  4530.2     .12       0  4798.1      .1       0  5001.9     .07       0
  5006.4      .1       0    5043     .12       0  5212.5     .05       0
  5217.3     .12       0
Bank Sta=5001.9,5006.4
XS Rating Curve= 0 ,0
Exp/Cntr=0.3,0.1

Chan Stop Cuts=-1
Use User Specified Reach Order=0
Composite Channel Slope=5