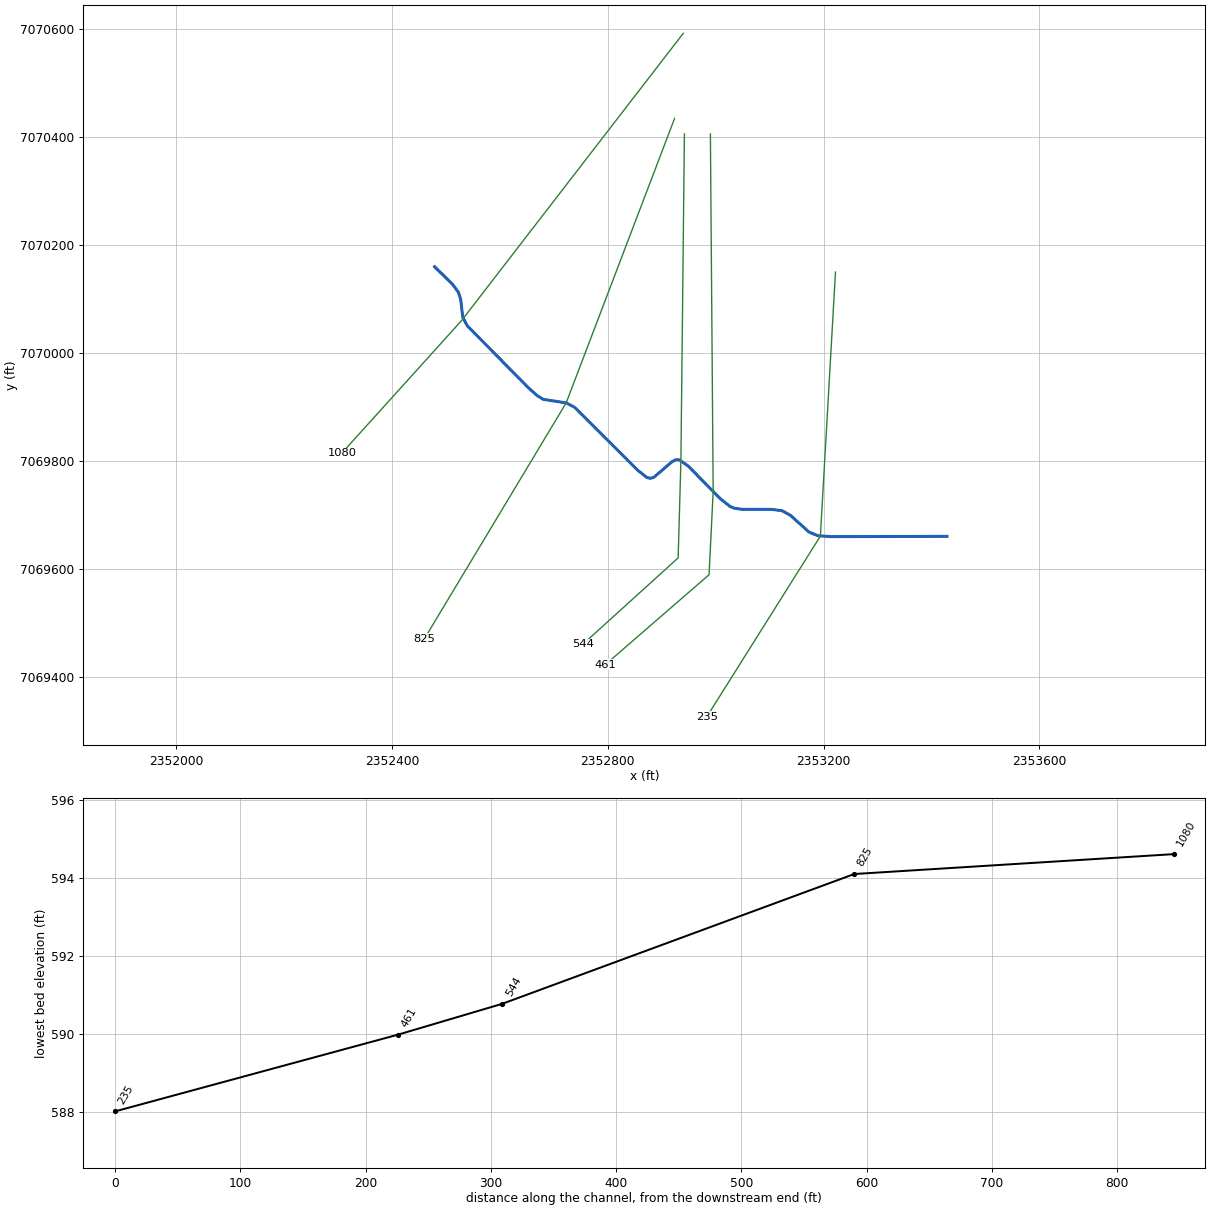
--- Cleveland Branch Tr 1.prj (project) ---

Proj Title=Cleveland Branch Tr 1 Base Level Engineering
Current Plan=p01
Default Exp/Contr=0.3,0.1
English Units
Geom File=g01
Flow File=f01
Plan File=p01
BEGIN DESCRIPTION:
Cleveland Branch Tr 1
END DESCRIPTION:

--- Cleveland Branch Tr 1.p01 (plan) ---

Plan Title=Multiple Run
Short Identifier=Multiple
Geom File=g01
Flow File=f01
Subcritical Flow
K Sum by GR= 0
Std Step Tol= 0.01
Critical Tol= 0.01
Num of Std Step Trials= 20
Max Error Tol= 0.3
Flow Tol Ratio= 0.001
Split Flow NTrial= 30
Split Flow Tol= 0.02
Split Flow Ratio= 0.02
Log Output Level= 0
Friction Slope Method= 1
Unsteady Friction Slope Method= 2
Unsteady Bridges Friction Slope Method= 1
Parabolic Critical Depth
Global Vel Dist=  1 , 1 , 1
Global Log Level= 0
CheckData=True
Encroach Param= -1, 0, 0, 0
BEGIN DESCRIPTION:
Multiple Run
END DESCRIPTION:

--- Cleveland Branch Tr 1.f01 (steady flow) ---

Flow Title=Multiple
Number of Profiles=7
Profile Names=10-year,25-year,50-year,1pct_min,100-year,1pct_plu,500-year
River Rch & RM= Cleveland Branch,Reach-1,1080
     107     130     146      82     163     326     204
Boundary for River Rch & Prof#=Cleveland Branch,Reach-1,1
Up Type=0
Dn Type=3
Dn Slope=0.005
Boundary for River Rch & Prof#=Cleveland Branch,Reach-1,2
Up Type=0
Dn Type=3
Dn Slope=0.005
Boundary for River Rch & Prof#=Cleveland Branch,Reach-1,3
Up Type=0
Dn Type=3
Dn Slope=0.005
Boundary for River Rch & Prof#=Cleveland Branch,Reach-1,4
Up Type=0
Dn Type=3
Dn Slope=0.005
Boundary for River Rch & Prof#=Cleveland Branch,Reach-1,5
Up Type=0
Dn Type=3
Dn Slope=0.005
Boundary for River Rch & Prof#=Cleveland Branch,Reach-1,6
Up Type=0
Dn Type=3
Dn Slope=0.005
Boundary for River Rch & Prof#=Cleveland Branch,Reach-1,7
Up Type=0
Dn Type=3
Dn Slope=0.005

--- Cleveland Branch Tr 1.g01 (geometry) ---

Geom Title=Existing Conditions

River Reach=Cleveland Branch,Reach-1
Reach XY= 30
      2352479.00      7070160.00      2352512.58      7070126.92
      2352523.29      7070112.35      2352527.34      7070099.31
      2352531.34      7070065.97      2352539.70      7070050.29
      2352652.18      7069936.30      2352669.32      7069920.78
      2352680.65      7069913.98      2352722.95      7069907.46
      2352738.68      7069899.22      2352855.67      7069782.52
      2352872.33      7069769.30      2352879.00      7069767.56
      2352885.67      7069769.62      2352919.00      7069798.29
      2352925.66      7069801.83      2352932.33      7069801.98
      2352948.98      7069790.58      2353008.84      7069729.71
      2353026.57      7069715.55      2353034.89      7069712.17
      2353049.05      7069710.13      2353104.00      7069709.99
      2353123.02      7069707.64      2353138.63      7069699.10
      2353172.94      7069668.14      2353189.50      7069661.22
      2353213.82      7069659.57      2353429.00      7069660.00

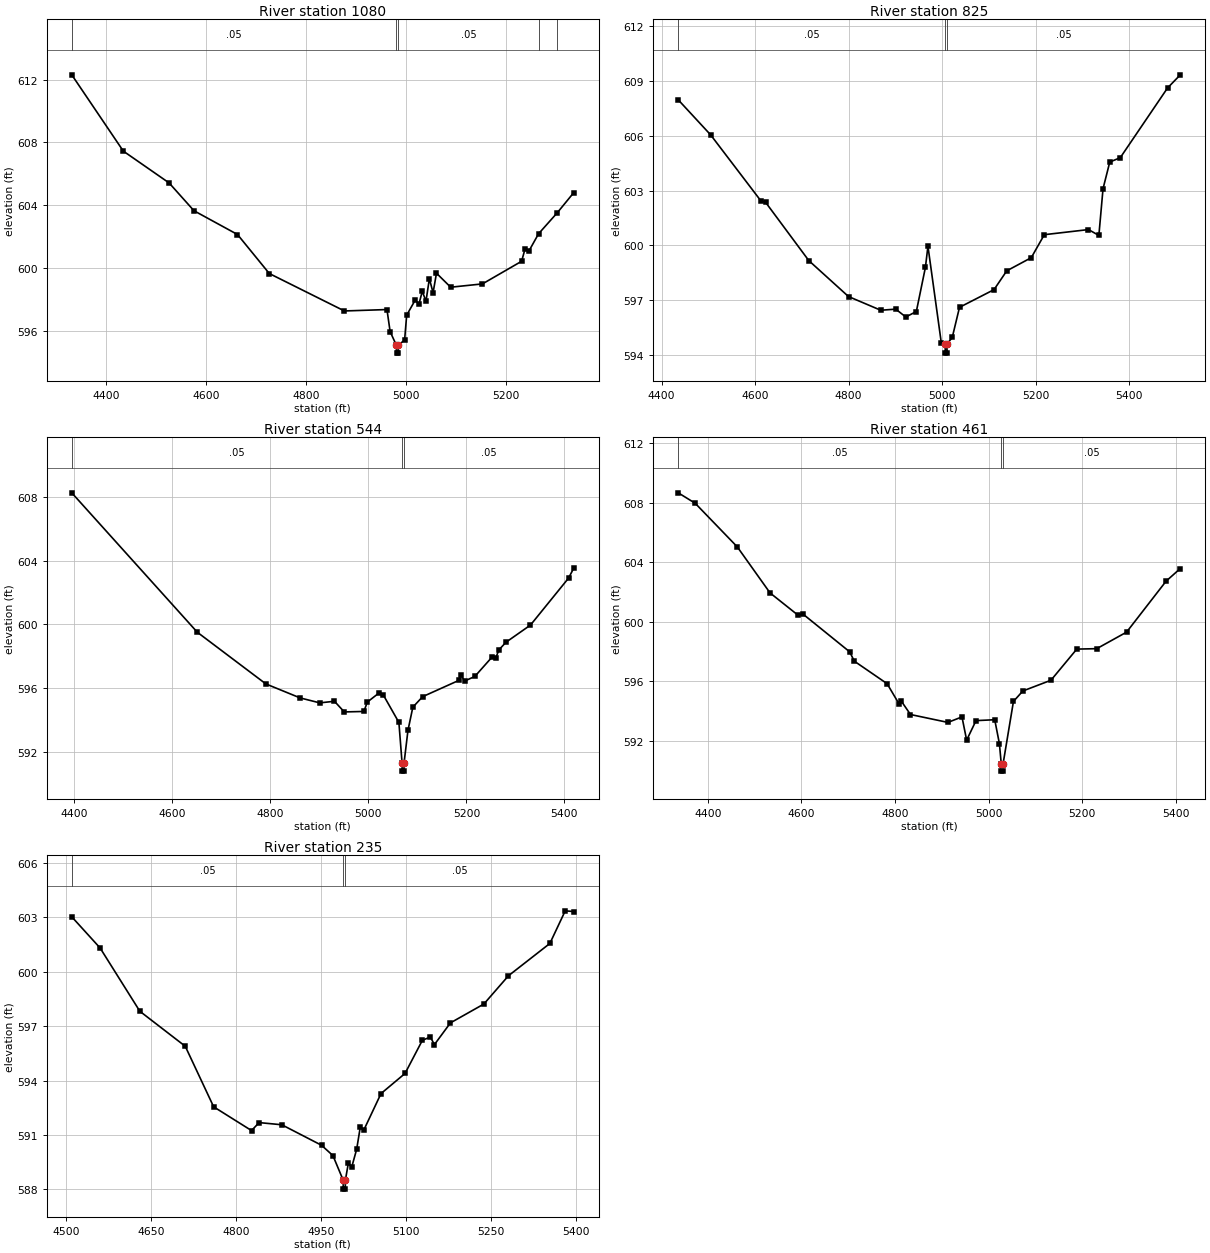
Type RM Length L Ch R = 1,1080,255,255,255
BEGIN DESCRIPTION:
Cleveland Branch Tr 1 4.0
END DESCRIPTION:
XS GIS Cut Line= 3
      2352940.09      7070592.67      2352529.00      7070060.00
      2352307.02      7069814.26
#Sta/Elev= 30
  4332.1  612.30  4435.2  607.45  4526.7  605.43  4576.5  603.66  4663.5  602.15
  4727.1  599.67  4877.3  597.29  4962.4  597.38  4968.7  595.98  4981.2  595.11
  4981.5  594.61  4985.0  594.61  4985.2  595.11  4997.7  595.45  5001.8  597.02
  5018.8  597.98  5026.2  597.71  5033.0  598.54  5040.4  597.91  5047.2  599.34
  5054.6  598.45  5061.4  599.69  5089.8  598.80  5153.3  599.01  5231.7  600.45
  5238.5  601.24  5245.9  601.08  5265.6  602.20  5302.9  603.53  5336.1  604.82
#Mann=5,-1,0
  4332.1    0.05       0  4981.2   0.033       0  4985.2    0.05       0
  5265.6   0.075       0  5302.9    0.05       0
Bank Sta=4981.2,4985.2
Exp/Cntr=0.3,0.1

Type RM Length L Ch R = 1,825,281,281,281
BEGIN DESCRIPTION:
Cleveland Branch Tr 1 3.0
END DESCRIPTION:
XS GIS Cut Line= 3
      2352923.91      7070434.77      2352722.95      7069907.46
      2352460.46      7069470.67
#Sta/Elev= 30
  4435.7  607.98  4505.0  606.06  4612.0  602.46  4622.7  602.36  4715.0  599.17
  4799.9  597.20  4868.9  596.45  4901.0  596.51  4922.4  596.08  4945.0  596.38
  4964.4  598.80  4969.8  599.96  4998.5  594.64  5006.7  594.60  5007.0  594.10
  5010.5  594.10  5010.7  594.60  5021.8  594.96  5037.3  596.61  5111.2  597.58
  5138.4  598.61  5190.8  599.33  5218.7  600.59  5313.2  600.87  5335.4  600.55
  5344.3  603.11  5358.7  604.57  5381.2  604.81  5482.3  608.63  5509.6  609.35
#Mann=3,-1,0
  4435.7    0.05       0  5006.7    0.04       0  5010.7    0.05       0
Bank Sta=5006.7,5010.7
Exp/Cntr=0.3,0.1

Type RM Length L Ch R = 1,544,83,83,83
BEGIN DESCRIPTION:
Mapping XS 74460307
END DESCRIPTION:
XS GIS Cut Line= 4
      2352942.15      7070406.14      2352935.66      7069800.68
      2352930.55      7069620.12      2352753.70      7069459.84
#Sta/Elev= 30
  4394.5  608.26  4650.7  599.50  4790.7  596.25  4860.7  595.37  4900.7  595.06
  4930.7  595.16  4950.7  594.49  4990.7  594.52  4997.8  595.11  5020.7  595.66
  5030.7  595.54  5062.2  593.83  5068.7  591.27  5069.0  590.77  5072.5  590.77
  5072.7  591.27  5080.7  593.33  5090.7  594.79  5110.7  595.45  5184.4  596.47
  5188.9  596.82  5196.2  596.43  5217.2  596.72  5252.4  597.94  5259.8  597.88
  5266.6  598.40  5280.8  598.87  5330.8  599.95  5408.5  602.90  5419.3  603.54
#Mann=3,-1,0
  4394.5    0.05       0  5068.7    0.04       0  5072.7    0.05       0
Bank Sta=5068.7,5072.7
Exp/Cntr=0.3,0.1

Type RM Length L Ch R = 1,461,226,226,226
BEGIN DESCRIPTION:
Cleveland Branch Tr 1 2.0
END DESCRIPTION:
XS GIS Cut Line= 4
      2352990.32      7070406.15      2352995.48      7069743.07
      2352987.84      7069588.87      2352794.97      7069421.73
#Sta/Elev= 30
  4336.9  608.66  4373.1  607.96  4463.1  605.03  4533.1  601.94  4593.1  600.44
  4603.1  600.53  4703.1  597.99  4713.1  597.36  4783.1  595.85  4808.9  594.48
  4813.9  594.66  4833.1  593.78  4913.1  593.25  4943.1  593.62  4953.1  592.06
  4973.1  593.37  5013.1  593.43  5023.1  591.82  5027.0  590.48  5027.2  589.98
  5030.7  589.98  5031.0  590.48  5053.1  594.66  5073.2  595.36  5133.2  596.08
  5188.4  598.17  5231.1  598.20  5294.8  599.31  5379.2  602.73  5409.6  603.58
#Mann=3,-1,0
  4336.9    0.05       0  5027.0    0.04       0  5031.0    0.05       0
Bank Sta=5027,5031
Exp/Cntr=0.3,0.1

Type RM Length L Ch R = 1,235,0,0,0
BEGIN DESCRIPTION:
Cleveland Branch Tr 1 1.0
END DESCRIPTION:
XS GIS Cut Line= 3
      2353222.20      7070149.92      2353194.22      7069660.52
      2352983.73      7069325.68
#Sta/Elev= 30
  4509.8  603.03  4559.8  601.31  4629.9  597.82  4710.0  595.89  4760.1  592.55
  4826.9  591.24  4840.3  591.68  4880.3  591.56  4950.4  590.43  4970.5  589.86
  4988.5  588.51  4988.8  588.01  4992.3  588.01  4992.5  588.51  4997.8  589.46
  5003.5  589.21  5012.4  590.21  5018.8  591.44  5024.7  591.25  5055.3  593.28
  5097.7  594.39  5128.3  596.22  5142.4  596.40  5149.5  595.98  5177.8  597.18
  5236.8  598.22  5280.2  599.78  5353.2  601.56  5380.3  603.36  5395.5  603.32
#Mann=3,-1,0
  4509.8    0.05       0  4988.5    0.04       0  4992.5    0.05       0
Bank Sta=4988.5,4992.5
Exp/Cntr=0.3,0.1

Chan Stop Cuts=-1