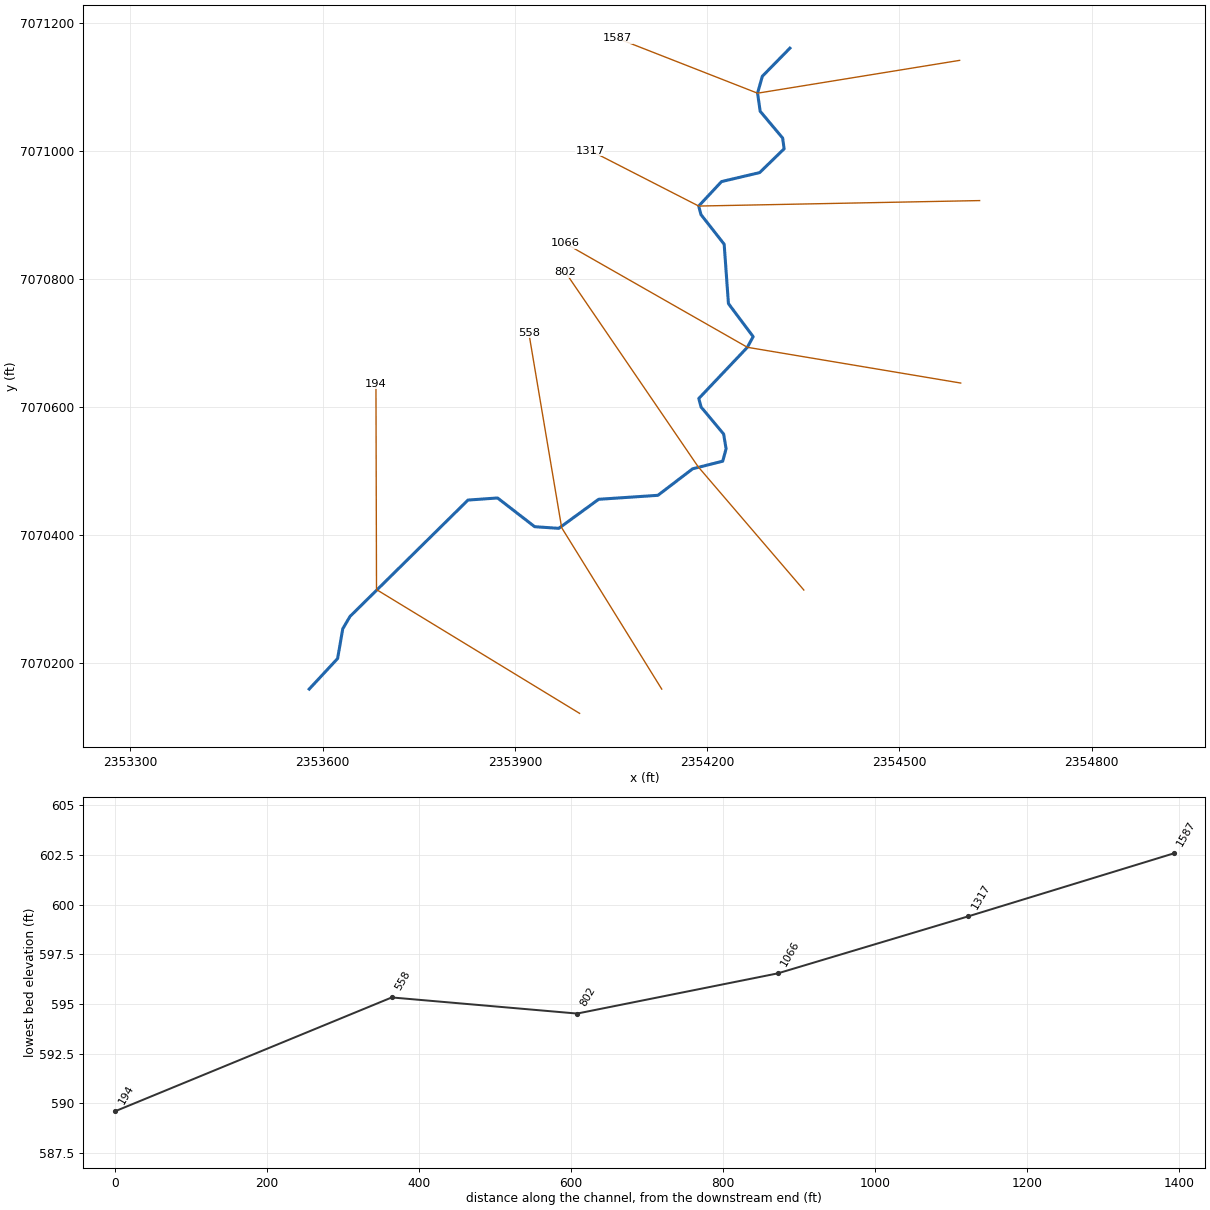
--- Cleveland Branch Tr 2.prj (project) ---

Proj Title=Cleveland Branch Tr 2 Base Level Engineering
Current Plan=p01
Default Exp/Contr=0.3,0.1
English Units
Geom File=g01
Flow File=f01
Plan File=p01
BEGIN DESCRIPTION:
Cleveland Branch Tr 2
END DESCRIPTION:

--- Cleveland Branch Tr 2.p01 (plan) ---

Plan Title=Multiple Run
Short Identifier=Multiple
Geom File=g01
Flow File=f01
Subcritical Flow
K Sum by GR= 0
Std Step Tol= 0.01
Critical Tol= 0.01
Num of Std Step Trials= 20
Max Error Tol= 0.3
Flow Tol Ratio= 0.001
Split Flow NTrial= 30
Split Flow Tol= 0.02
Split Flow Ratio= 0.02
Log Output Level= 0
Friction Slope Method= 1
Unsteady Friction Slope Method= 2
Unsteady Bridges Friction Slope Method= 1
Parabolic Critical Depth
Global Vel Dist=  1 , 1 , 1
Global Log Level= 0
CheckData=True
Encroach Param= -1, 0, 0, 0
BEGIN DESCRIPTION:
Multiple Run
END DESCRIPTION:

--- Cleveland Branch Tr 2.f01 (steady flow) ---

Flow Title=Multiple
Number of Profiles=7
Profile Names=10-year,25-year,50-year,1pct_min,100-year,1pct_plu,500-year
River Rch & RM= Cleveland Branch,Reach-1,1587
     296     387     460     272     542    1082     755
Boundary for River Rch & Prof#=Cleveland Branch,Reach-1,1
Up Type=0
Dn Type=3
Dn Slope=0.005
Boundary for River Rch & Prof#=Cleveland Branch,Reach-1,2
Up Type=0
Dn Type=3
Dn Slope=0.005
Boundary for River Rch & Prof#=Cleveland Branch,Reach-1,3
Up Type=0
Dn Type=3
Dn Slope=0.005
Boundary for River Rch & Prof#=Cleveland Branch,Reach-1,4
Up Type=0
Dn Type=3
Dn Slope=0.005
Boundary for River Rch & Prof#=Cleveland Branch,Reach-1,5
Up Type=0
Dn Type=3
Dn Slope=0.005
Boundary for River Rch & Prof#=Cleveland Branch,Reach-1,6
Up Type=0
Dn Type=3
Dn Slope=0.005
Boundary for River Rch & Prof#=Cleveland Branch,Reach-1,7
Up Type=0
Dn Type=3
Dn Slope=0.005

--- Cleveland Branch Tr 2.g01 (geometry) ---

Geom Title=Existing Conditions

River Reach=Cleveland Branch,Reach-1
Reach XY= 30
      2354329.00      7071160.00      2354285.98      7071116.14
      2354278.54      7071089.75      2354282.61      7071061.57
      2354317.71      7071019.74      2354319.98      7071002.99
      2354281.80      7070965.85      2354222.35      7070951.85
      2354186.69      7070913.67      2354190.27      7070900.28
      2354226.44      7070854.12      2354233.10      7070761.50
      2354271.66      7070709.90      2354262.64      7070693.29
      2354186.86      7070613.39      2354190.42      7070600.08
      2354225.57      7070557.99      2354229.44      7070534.91
      2354224.21      7070515.59      2354177.28      7070503.72
      2354123.06      7070462.32      2354030.59      7070456.11
      2353968.31      7070410.77      2353930.72      7070413.40
      2353872.87      7070458.19      2353826.70      7070454.91
      2353642.57      7070273.23      2353631.34      7070254.03
      2353623.29      7070207.65      2353579.00      7070160.00

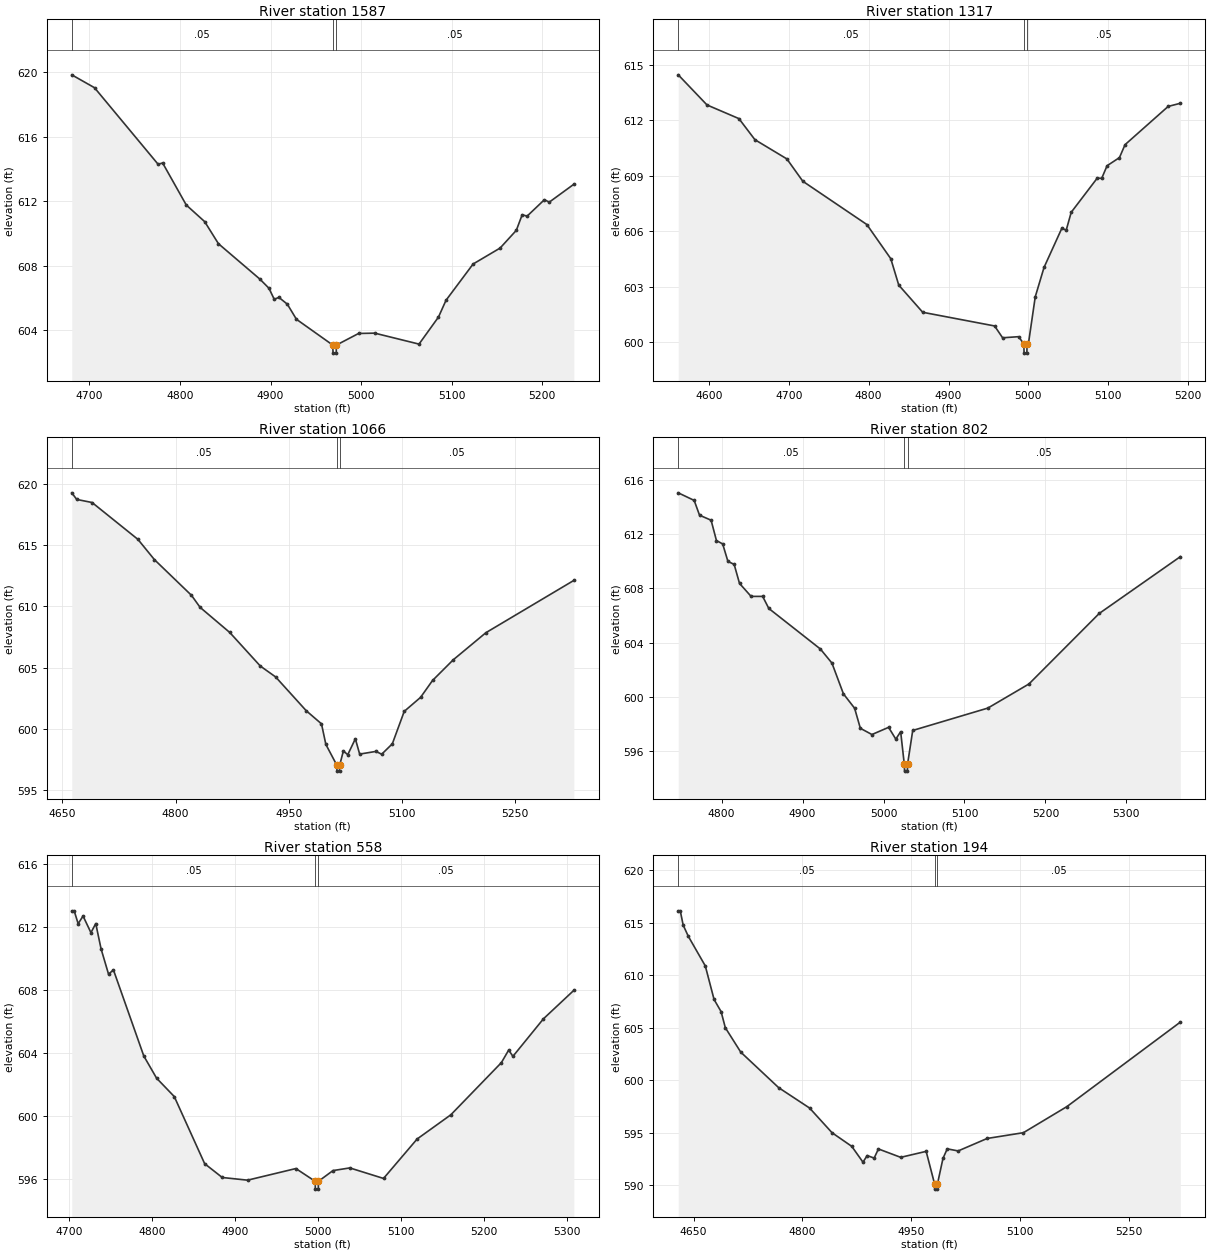
Type RM Length L Ch R = 1,1587,270,270,270
BEGIN DESCRIPTION:
Cleveland Branch Tr 2 6.0
END DESCRIPTION:
XS GIS Cut Line= 3
      2354593.81      7071140.97      2354278.54      7071089.75
      2354059.91      7071175.35
#Sta/Elev= 30
  4680.6  619.84  4705.7  619.04  4775.9  614.29  4780.9  614.37  4807.0  611.76
  4827.3  610.73  4842.5  609.36  4888.1  607.17  4898.2  606.60  4904.1  605.91
  4909.2  606.03  4918.5  605.61  4928.6  604.67  4968.7  603.07  4969.0  602.57
  4972.5  602.57  4972.7  603.07  4997.2  603.79  5015.0  603.81  5063.9  603.13
  5085.4  604.81  5093.7  605.85  5123.6  608.10  5153.4  609.09  5171.3  610.19
  5177.8  611.16  5183.2  611.07  5202.3  612.09  5207.7  611.94  5234.8  613.05
#Mann=3,-1,0
  4680.6    0.05       0  4968.7    0.04       0  4972.7    0.05       0
Bank Sta=4968.7,4972.7
Exp/Cntr=0.3,0.1

Type RM Length L Ch R = 1,1317,251,251,251
BEGIN DESCRIPTION:
Cleveland Branch Tr 2 5.0
END DESCRIPTION:
XS GIS Cut Line= 3
      2354625.01      7070922.21      2354186.69      7070913.67
      2354017.39      7071000.34
#Sta/Elev= 30
  4561.6  614.47  4597.6  612.84  4637.6  612.10  4657.6  610.96  4697.6  609.92
  4717.6  608.71  4797.7  606.37  4827.7  604.52  4837.7  603.09  4867.7  601.62
  4957.7  600.88  4967.7  600.24  4987.7  600.30  4994.3  599.91  4994.6  599.41
  4998.1  599.41  4998.3  599.91  5000.0  599.91  5008.6  602.46  5019.6  604.05
  5041.8  606.16  5047.4  606.07  5053.6  607.03  5086.2  608.88  5091.8  608.87
  5098.5  609.55  5114.0  609.99  5121.0  610.69  5175.0  612.76  5190.2  612.93
#Mann=3,-1,0
  4561.6    0.05       0  4994.3    0.04       0  4998.3    0.05       0
Bank Sta=4994.3,4998.3
Exp/Cntr=0.3,0.1

Type RM Length L Ch R = 1,1066,264,264,264
BEGIN DESCRIPTION:
Cleveland Branch Tr 2 4.0
END DESCRIPTION:
XS GIS Cut Line= 3
      2354595.49      7070637.50      2354262.64      7070693.29
      2353977.73      7070855.81
#Sta/Elev= 30
  4662.5  619.26  4669.1  618.72  4689.4  618.47  4750.2  615.46  4772.0  613.81
  4821.2  610.89  4832.6  609.91  4871.9  607.86  4912.4  605.12  4932.7  604.23
  4973.3  601.47  4993.5  600.40  4999.3  598.72  5013.7  597.04  5014.0  596.54
  5017.5  596.54  5017.7  597.04  5022.5  598.19  5028.3  597.88  5038.4  599.18
  5044.1  597.93  5065.7  598.15  5073.3  597.92  5087.4  598.77  5103.2  601.42
  5124.8  602.56  5140.7  603.94  5168.0  605.62  5211.4  607.84  5328.0  612.11
#Mann=3,-1,0
  4662.5    0.05       0  5013.7   0.033       0  5017.7    0.05       0
Bank Sta=5013.7,5017.7
Exp/Cntr=0.3,0.1

Type RM Length L Ch R = 1,802,244,244,244
BEGIN DESCRIPTION:
Cleveland Branch Tr 2 3.0
END DESCRIPTION:
XS GIS Cut Line= 3
      2354350.74      7070314.55      2354185.70      7070507.10
      2353979.00      7070810.00
#Sta/Elev= 30
  4746.4  615.05  4766.1  614.49  4772.7  613.40  4787.0  613.03  4793.6  611.53
  4801.3  611.28  4807.8  609.99  4815.5  609.77  4822.1  608.37  4836.4  607.41
  4850.7  607.41  4858.3  606.52  4922.0  603.53  4936.3  602.49  4950.5  600.22
  4964.3  599.16  4971.4  597.68  4985.7  597.22  5006.3  597.75  5015.2  596.88
  5021.2  597.43  5025.7  595.02  5026.0  594.52  5029.5  594.52  5029.7  595.02
  5036.1  597.52  5128.9  599.17  5179.7  600.95  5266.5  606.15  5366.7  610.34
#Mann=3,-1,0
  4746.4    0.05       0  5025.7   0.033       0  5029.7    0.05       0
Bank Sta=5025.7,5029.7
Exp/Cntr=0.3,0.1

Type RM Length L Ch R = 1,558,364,364,364
BEGIN DESCRIPTION:
Cleveland Branch Tr 2 2.0
END DESCRIPTION:
XS GIS Cut Line= 3
      2354129.00      7070159.99      2353972.88      7070411.82
      2353921.57      7070716.13
#Sta/Elev= 30
  4703.7  613.04  4706.6  613.04  4711.4  612.22  4717.3  612.71  4726.8  611.65
  4732.6  612.23  4739.0  610.62  4748.0  609.01  4753.9  609.28  4790.5  603.80
  4805.9  602.39  4827.2  601.22  4863.8  596.95  4885.0  596.07  4915.5  595.90
  4973.7  596.64  4996.9  595.83  4997.2  595.33  5000.7  595.33  5000.9  595.83
  5018.4  596.51  5038.7  596.68  5079.3  596.01  5119.8  598.52  5160.4  600.06
  5221.3  603.38  5230.1  604.18  5235.2  603.78  5272.0  606.17  5308.6  607.98
#Mann=3,-1,0
  4703.7    0.05       0  4996.9    0.04       0  5000.9    0.05       0
Bank Sta=4996.9,5000.9
Exp/Cntr=0.3,0.1

Type RM Length L Ch R = 1,194,0,0,0
BEGIN DESCRIPTION:
Cleveland Branch Tr 2 1.0
END DESCRIPTION:
XS GIS Cut Line= 3
      2354000.86      7070122.09      2353683.99      7070315.24
      2353683.12      7070636.34
#Sta/Elev= 30
  4628.9  616.14  4631.7  616.14  4635.7  614.78  4642.8  613.71  4666.2  610.89
  4678.3  607.69  4688.0  606.53  4693.8  605.00  4715.1  602.67  4767.4  599.28
  4810.0  597.34  4840.9  594.99  4868.1  593.69  4883.6  592.18  4889.4  592.81
  4899.0  592.57  4904.9  593.44  4935.6  592.64  4970.7  593.21  4982.3  590.11
  4982.5  589.61  4986.0  589.61  4986.3  590.11  4993.9  592.54  4999.8  593.45
  5014.8  593.25  5054.8  594.44  5104.8  594.99  5164.8  597.48  5321.1  605.53
#Mann=3,-1,0
  4628.9    0.05       0  4982.3   0.033       0  4986.3    0.05       0
Bank Sta=4982.3,4986.3
Exp/Cntr=0.3,0.1

Chan Stop Cuts=-1