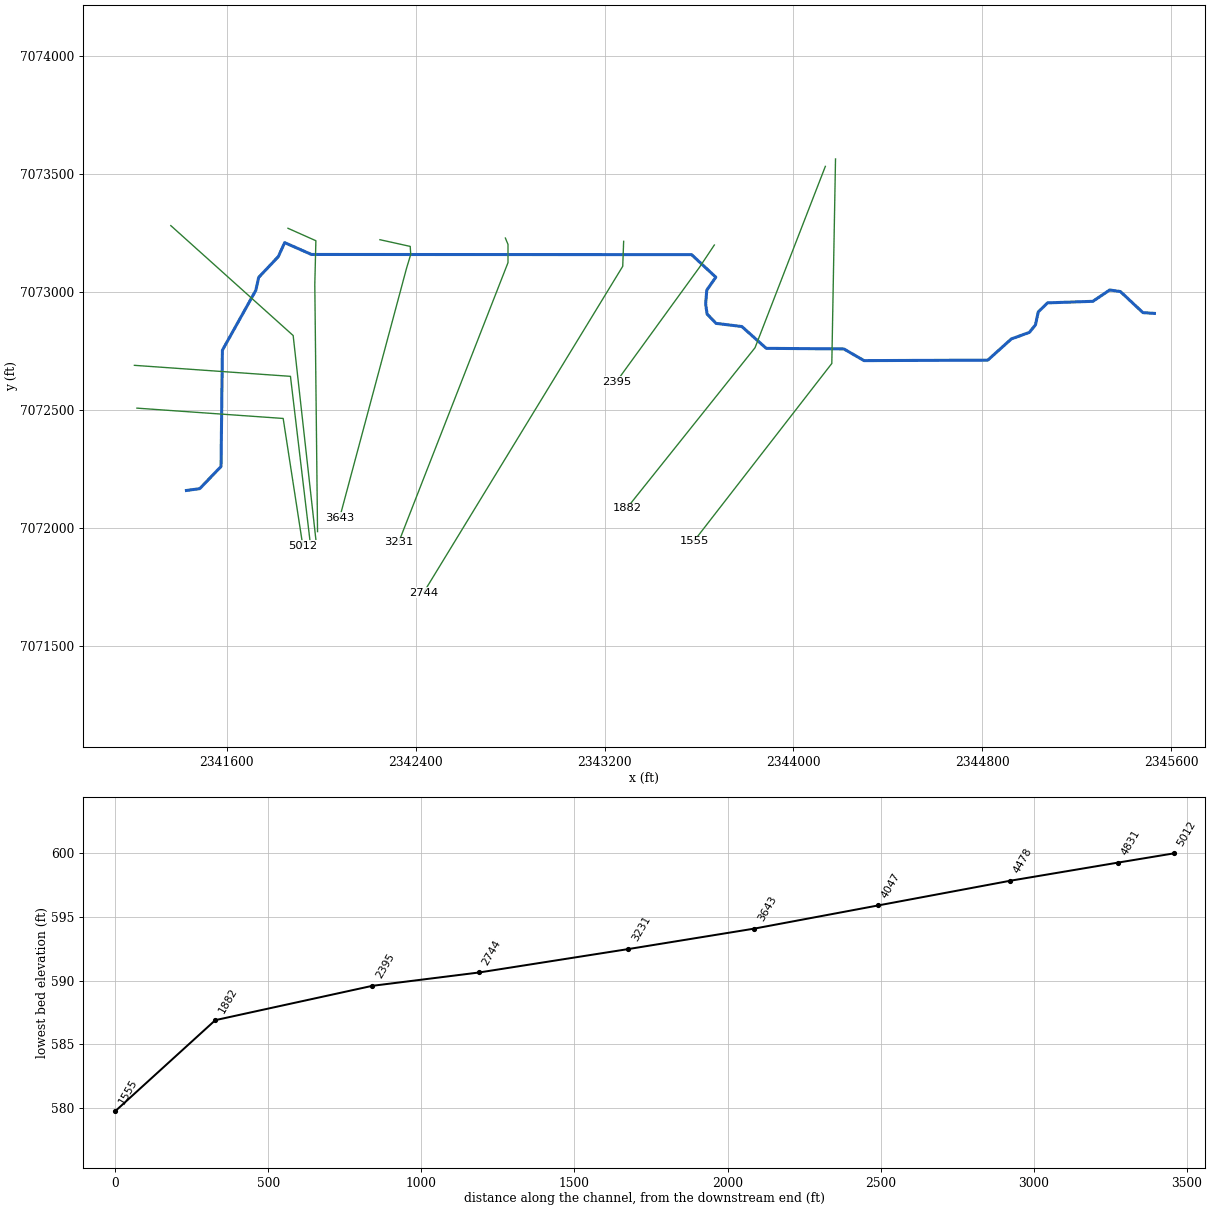
--- Denton Creek Tr 10.prj (project) ---

Proj Title=Denton Creek Tr 10 Base Level Engineering
Current Plan=p01
Default Exp/Contr=0.3,0.1
English Units
Geom File=g01
Flow File=f01
Plan File=p01
Y Axis Title=Elevation
X Axis Title(PF)=Main Channel Distance
X Axis Title(XS)=Station
BEGIN DESCRIPTION:
Denton Creek Tr 10
END DESCRIPTION:
DSS Export Rating Curves= 0
DSS Export Rating Curve Sorted= 0
DSS Export Volume Flow Curves= 0
DXF OffsetX= 0
DXF OffsetY= 0
DXF ScaleX= 1
DXF ScaleY= 10

--- Denton Creek Tr 10.p01 (plan) ---

Plan Title=Multiple Run
Program Version=4.10
Short Identifier=Multiple
Geom File=g01
Flow File=f01
Subcritical Flow
K Sum by GR= 0
Std Step Tol= 0.01
Critical Tol= 0.01
Num of Std Step Trials= 20
Max Error Tol= 0.3
Flow Tol Ratio= 0.001
Split Flow NTrial= 30
Split Flow Tol= 0.02
Split Flow Ratio= 0.02
Log Output Level= 0
Friction Slope Method= 1
Unsteady Friction Slope Method= 2
Unsteady Bridges Friction Slope Method= 1
Parabolic Critical Depth
Global Vel Dist= 1 , 1 , 1
Global Log Level= 0
CheckData=True
Encroach Param=-1 ,0,0, 0
BEGIN DESCRIPTION:
Multiple Run
END DESCRIPTION:
Computation Interval=1HOUR
Output Interval=1HOUR
Run HTab= 0
Run UNet= 0
Run PostProcess= 0
Run WQNet= 0
UNET Theta= 1
UNET Theta Warmup= 1
UNET ZTol= 0.02
UNET ZSATol= 0.05
UNET MxIter= 20
UNET MaxInSteps= 0
UNET DtIC= 0
UNET DtMin= 0
UNET MaxCRTS= 20
UNET WFStab= 2
UNET SFStab= 1
UNET WFX= 1
UNET SFX= 1
UNET DSS MLevel= 4
UNET DZMax Abort= 100
UNET Convert EG Bridges= 0
UNET Use Existing IB Tables=-1
UNET Froude Reduction=False
UNET Froude Limit= 1
UNET Froude Power= 10
UNET Time Slicing=0,0, 5
UNET Junction Losses=0
Instantaneous Interval=1HOUR
Write IC File= 0
Write IC File at Sim End=0
Echo Input=False
Echo Parameters=False
Echo Output=False
Write Detailed= 0
WQ AD Non Conservative
WQ ULTIMATE=-1
WQ Max Comp Step=1HOUR
WQ Output Interval=15MIN
WQ Output Selected Increments= 0
WQ Output face flow=0
WQ Output face velocity=0
WQ Output face area=0
WQ Output face dispersion=0
WQ Output cell volume=0
WQ Output cell surface area=0
WQ Output cell continuity=0
WQ Output cumulative cell continuity=0
WQ Output face conc=0
WQ Output face dconc_dx=0
WQ Output face courant=0
WQ Output face peclet=0
WQ Output face adv mass=0
WQ Output face disp mass=0
WQ Output cell mass=0
WQ Output cell source sink temp=0
WQ Output cell source sink nsm=0
WQ Output MaxMinRange=-1
WQ Daily Max Min Mean=-1
WQ Daily Range=0
WQ Daily Time=0
WQ Create Restart=0
WQ Fixed Restart=0
WQ System Summary=0
WQ Use Fixed Temperature=0
Sorting and Armoring Iterations= 10
XS Update Threshold= 0.02
Hydraulics Update Threshold= 0.02
Energy Slope Method= 1
Volume Change Method= 0
XS Weighting Method= 0
Number of US Weighted Cross Sections= 1
Number of DS Weighted Cross Sections= 1
Upstream XS Weight=0.25
Main XS Weight=0.5
Downstream XS Weight=0.25
Number of DS XS's Weighted with US Boundary= 1
Upstream Boundary Weight= 1
Weight of XSs Associated with US Boundary= 0
Number of US XS's Weighted with DS Boundary= 1
Downstream Boundary Weight= 0.5
Weight of XSs Associated with DS Boundary= 0.5
Sediment Output Level= 4
Mass or Volume Output= 0
Output Increment Type= 1
Profile and TS Output Increment= 10
XS Output Flag= 0
XS Output Increment= 10
Disregard all LS=0
Disregard all Conn=0
Disregard all Breaches=0
Disregard all Pumps=0

--- Denton Creek Tr 10.f01 (steady flow) ---

Flow Title=Multiple
Number of Profiles=7
Profile Names=10-year,25-year,50-year,1pct_min,100-year,1pct_plu,500-year
River Rch & RM= Denton Creek Tr ,Reach-1,5012
     387     516     620     370     739    1474    1050
River Rch & RM= Denton Creek Tr ,Reach-1,1882
     560     765     933     565    1128    2251    1653
Boundary for River Rch & Prof#=Denton Creek Tr ,Reach-1,1
Up Type=0
Dn Type=3
Dn Slope=0.005
Boundary for River Rch & Prof#=Denton Creek Tr ,Reach-1,2
Up Type=0
Dn Type=3
Dn Slope=0.005
Boundary for River Rch & Prof#=Denton Creek Tr ,Reach-1,3
Up Type=0
Dn Type=3
Dn Slope=0.005
Boundary for River Rch & Prof#=Denton Creek Tr ,Reach-1,4
Up Type=0
Dn Type=3
Dn Slope=0.005
Boundary for River Rch & Prof#=Denton Creek Tr ,Reach-1,5
Up Type=0
Dn Type=3
Dn Slope=0.005
Boundary for River Rch & Prof#=Denton Creek Tr ,Reach-1,6
Up Type=0
Dn Type=3
Dn Slope=0.005
Boundary for River Rch & Prof#=Denton Creek Tr ,Reach-1,7
Up Type=0
Dn Type=3
Dn Slope=0.005

--- Denton Creek Tr 10.g01 (geometry) ---

Geom Title=Existing Conditions

River Reach=Denton Creek Tr ,Reach-1
Reach XY= 30
      2341429.00      7072160.00      2341485.24      7072167.75
      2341575.48      7072261.45      2341581.24      7072754.07
      2341722.90      7073007.81      2341734.85      7073062.29
      2341818.09      7073150.68      2341845.01      7073209.77
      2341958.84      7073159.65      2343568.58      7073158.95
      2343671.21      7073063.43      2343632.95      7073008.50
      2343628.18      7072949.89      2343634.28      7072907.29
      2343672.49      7072867.73      2343781.42      7072854.46
      2343884.86      7072762.07      2344213.78      7072759.48
      2344299.03      7072710.07      2344823.14      7072712.06
      2344922.98      7072801.81      2344999.47      7072829.64
      2345025.10      7072861.47      2345037.03      7072916.36
      2345076.30      7072954.64      2345268.50      7072961.24
      2345339.71      7073009.28      2345385.06      7073002.52
      2345480.36      7072913.29      2345529.00      7072910.00

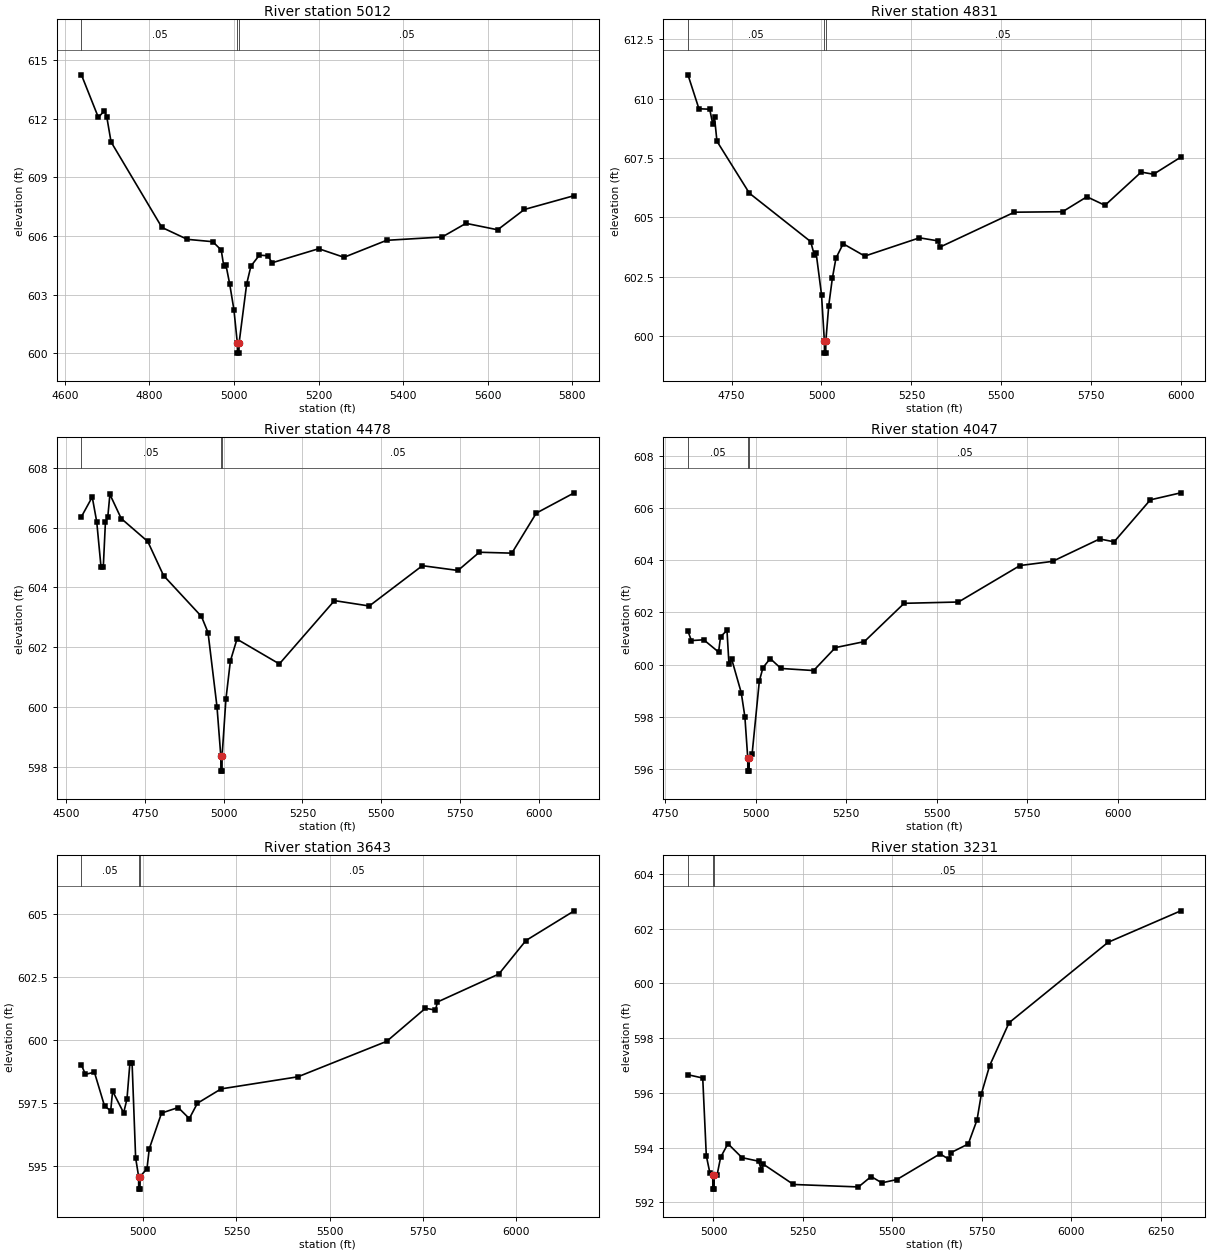
Type RM Length L Ch R = 1,5012,181,181,181
BEGIN DESCRIPTION:
Denton Creek Tr 10 13.0
END DESCRIPTION:
XS GIS Cut Line= 3
      2341219.11      7072508.78      2341838.69      7072465.07
      2341921.78      7071926.86
#Sta/Elev= 30
  4639.2  614.26  4679.2  612.08  4693.6  612.42  4699.2  612.10  4709.3  610.82
  4829.6  606.44  4889.7  605.83  4949.9  605.71  4969.9  605.28  4976.0  604.44
  4981.0  604.52  4990.0  603.53  5000.0  602.21  5008.0  600.50  5008.3  600.00
  5011.8  600.00  5012.0  600.50  5030.1  603.55  5040.1  604.46  5060.1  605.02
  5080.2  604.99  5090.2  604.63  5200.5  605.35  5260.3  604.91  5361.1  605.78
  5492.4  605.95  5548.8  606.65  5623.7  606.32  5686.9  607.36  5804.9  608.07
#Mann=3,-1,0
  4639.2    0.05       0  5008.0   0.035       0  5012.0    0.05       0
Bank Sta=5008,5012
Exp/Cntr=0.3,0.1

Type RM Length L Ch R = 1,4831,353,353,353
BEGIN DESCRIPTION:
Denton Creek Tr 10 12.0
END DESCRIPTION:
XS GIS Cut Line= 3
      2341208.62      7072690.07      2341869.54      7072643.44
      2341953.03      7071940.75
#Sta/Elev= 30
  4628.8  611.01  4659.3  609.58  4689.3  609.56  4697.6  608.94  4702.6  609.22
  4709.4  608.21  4799.6  606.02  4970.0  603.98  4980.0  603.42  4985.0  603.52
  5000.1  601.75  5008.1  599.78  5008.4  599.28  5011.9  599.28  5012.1  599.78
  5020.2  601.28  5030.2  602.43  5040.2  603.28  5060.3  603.89  5120.4  603.37
  5272.5  604.14  5324.6  604.01  5329.6  603.75  5536.5  605.22  5670.3  605.24
  5737.9  605.87  5788.3  605.51  5889.0  606.91  5923.3  606.82  5999.0  607.54
#Mann=3,-1,0
  4628.8    0.05       0  5008.1   0.035       0  5012.1    0.05       0
Bank Sta=5008.1,5012.1
Exp/Cntr=0.3,0.1

Type RM Length L Ch R = 1,4478,431,431,431
BEGIN DESCRIPTION:
Denton Creek Tr 10 11.0
END DESCRIPTION:
XS GIS Cut Line= 3
      2341362.81      7073281.87      2341880.98      7072816.32
      2341977.13      7071953.05
#Sta/Elev= 30
  4548.0  606.37  4582.3  607.03  4596.6  606.20  4610.1  604.70  4617.5  604.70
  4624.2  606.19  4631.7  606.36  4638.4  607.12  4674.3  606.31  4758.7  605.54
  4808.8  604.40  4929.2  603.03  4950.1  602.49  4978.5  600.01  4990.7  598.35
  4991.0  597.85  4994.5  597.85  4994.7  598.35  5006.9  600.26  5021.1  601.54
  5042.0  602.27  5176.6  601.44  5351.6  603.56  5462.2  603.38  5630.8  604.73
  5744.0  604.57  5811.7  605.18  5915.0  605.15  5992.6  606.49  6113.2  607.17
#Mann=3,-1,0
  4548.0    0.05       0  4990.7   0.035       0  4994.7    0.05       0
Bank Sta=4990.7,4994.7
Exp/Cntr=0.3,0.1

Type RM Length L Ch R = 1,4047,404,404,404
BEGIN DESCRIPTION:
Denton Creek Tr 10 10.0
END DESCRIPTION:
XS GIS Cut Line= 4
      2341859.14      7073270.52      2341977.23      7073217.87
      2341972.67      7073030.89      2341984.28      7071985.88
#Sta/Elev= 30
  4812.4  601.28  4821.8  600.92  4856.0  600.95  4897.0  600.48  4902.5  601.07
  4920.2  601.31  4925.7  600.01  4932.7  600.23  4959.6  598.92  4969.6  598.00
  4977.6  596.41  4977.8  595.91  4981.3  595.91  4981.6  596.41  4989.6  596.57
  5009.6  599.37  5019.6  599.88  5039.6  600.23  5069.3  599.85  5159.6  599.77
  5219.6  600.65  5299.6  600.88  5409.6  602.35  5559.6  602.40  5729.7  603.80
  5819.7  603.96  5949.7  604.82  5989.7  604.71  6089.7  606.32  6173.8  606.59
#Mann=3,-1,0
  4812.4    0.05       0  4977.6   0.035       0  4981.6    0.05       0
Bank Sta=4977.6,4981.6
Exp/Cntr=0.3,0.1

Type RM Length L Ch R = 1,3643,412,412,412
BEGIN DESCRIPTION:
Denton Creek Tr 10 9.0
END DESCRIPTION:
XS GIS Cut Line= 5
      2342248.61      7073222.20      2342376.83      7073193.80
      2342379.00      7073160.00      2342360.99      7073100.36
      2342078.03      7072044.93
#Sta/Elev= 30
  4834.8  599.02  4845.4  598.65  4869.6  598.73  4896.7  597.39  4913.2  597.20
  4918.3  597.98  4947.9  597.12  4956.8  597.67  4964.7  599.10  4970.5  599.10
  4980.0  595.33  4988.0  594.59  4988.2  594.09  4991.7  594.09  4992.0  594.59
  5010.4  594.90  5016.5  595.69  5049.4  597.11  5094.1  597.33  5123.8  596.89
  5145.5  597.50  5209.0  598.07  5414.7  598.55  5652.8  599.96  5756.3  601.27
  5783.3  601.20  5788.5  601.52  5953.0  602.63  6025.5  603.96  6155.0  605.14
#Mann=3,-1,0
  4834.8    0.05       0  4988.0    0.04       0  4992.0    0.05       0
Bank Sta=4988,4992
Exp/Cntr=0.3,0.1

Type RM Length L Ch R = 1,3231,487,487,487
BEGIN DESCRIPTION:
Denton Creek Tr 10 8.0
END DESCRIPTION:
XS GIS Cut Line= 4
      2342779.93      7073229.11      2342791.02      7073202.11
      2342791.02      7073125.17      2342328.04      7071940.78
#Sta/Elev= 30
  4928.7  596.66  4970.0  596.54  4980.0  593.70  4990.0  593.07  4998.0  592.98
  4998.3  592.48  5001.8  592.48  5002.0  592.98  5010.0  592.99  5020.0  593.64
  5040.4  594.14  5079.8  593.63  5126.3  593.50  5134.1  593.18  5139.5  593.39
  5223.6  592.65  5405.4  592.56  5440.8  592.94  5470.7  592.71  5512.8  592.83
  5633.6  593.77  5658.1  593.57  5663.4  593.81  5712.4  594.13  5736.9  595.01
  5749.0  595.96  5772.1  596.99  5826.4  598.56  6103.3  601.50  6306.5  602.65
#Mann=3,-1,0
  4928.7    0.05       0  4998.0    0.04       0  5002.0    0.05       0
Bank Sta=4998,5002
Exp/Cntr=0.3,0.1

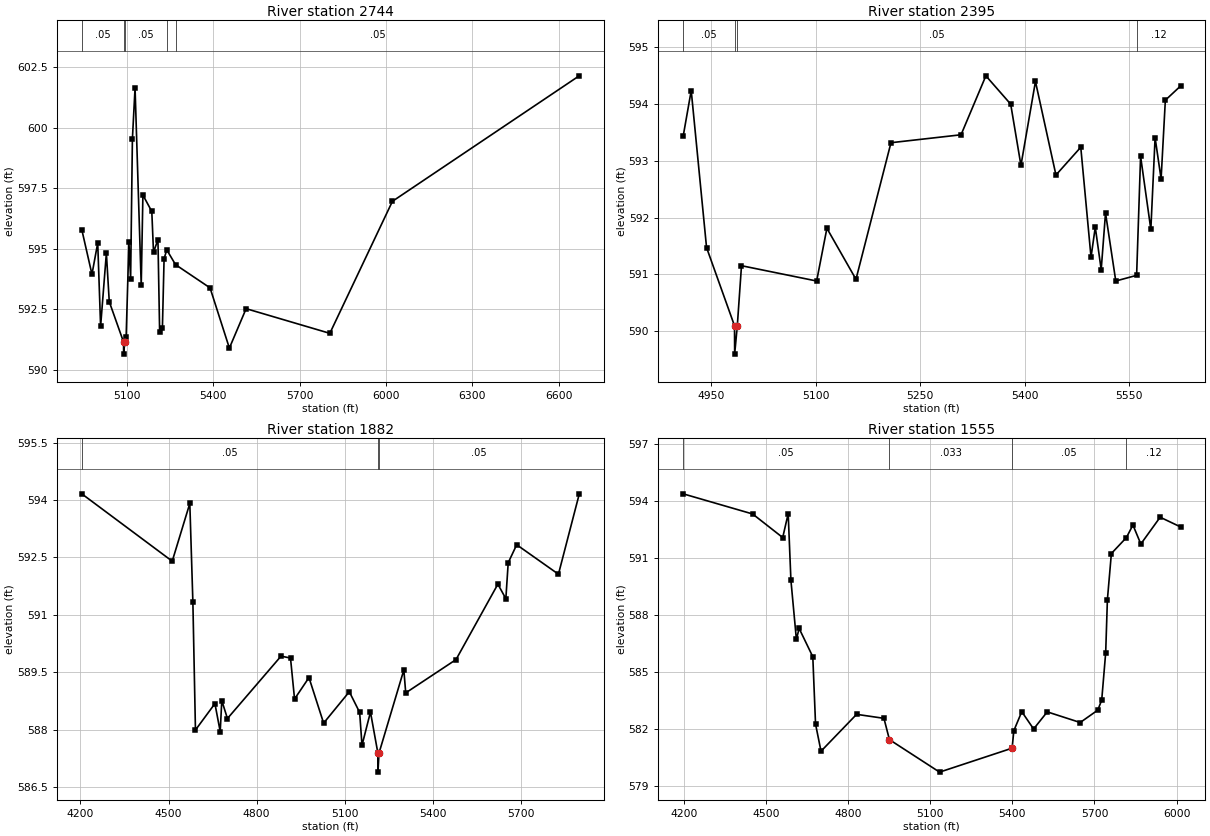
Type RM Length L Ch R = 1,2744,349,349,349
BEGIN DESCRIPTION:
Denton Creek Tr 10 7.0
END DESCRIPTION:
XS GIS Cut Line= 3
      2343280.86      7073215.27      2343276.94      7073109.50
      2342433.08      7071726.93
#Sta/Elev= 30
  4944.7  595.79  4980.0  593.94  5000.0  595.24  5010.0  591.79  5030.0  594.82
  5040.0  592.81  5089.6  591.14  5089.9  590.64  5093.6  591.14  5098.6  591.36
  5108.2  595.26  5114.1  593.76  5120.3  599.54  5129.5  601.65  5150.9  593.49
  5156.7  597.22  5187.6  596.54  5193.5  594.85  5208.9  595.38  5214.8  591.54
  5224.4  591.73  5230.2  594.59  5239.6  594.95  5270.0  594.34  5389.7  593.38
  5456.7  590.89  5514.8  592.52  5805.2  591.50  6022.3  596.96  6670.3  602.15
#Mann=5,-1,0
  4944.7    0.05       0  5089.6   0.033       0  5093.6    0.05       0
  5239.6    0.12       0  5270.0    0.05       0
Bank Sta=5089.6,5093.6
Exp/Cntr=0.3,0.1

Type RM Length L Ch R = 1,2395,513,513,513
BEGIN DESCRIPTION:
Denton Creek Tr 10 6.0
END DESCRIPTION:
XS GIS Cut Line= 3
      2343664.89      7073199.62      2343602.20      7073105.58
      2343249.54      7072619.69
#Sta/Elev= 30
  4910.1  593.43  4921.7  594.24  4943.7  591.47  4983.8  590.09  4984.0  589.59
  4987.8  590.09  4993.8  591.15  5101.6  590.88  5116.3  591.81  5158.0  590.91
  5208.2  593.32  5308.7  593.46  5344.3  594.50  5379.9  594.00  5394.6  592.92
  5415.4  594.40  5444.8  592.75  5480.4  593.24  5495.1  591.30  5501.2  591.83
  5509.7  591.08  5515.9  592.08  5530.6  590.88  5560.5  590.98  5566.2  593.08
  5580.9  591.79  5587.0  593.41  5595.6  592.68  5601.7  594.07  5623.5  594.32
#Mann=4,-1,0
  4910.1    0.05       0  4983.8   0.033       0  4987.8    0.05       0
  5560.5    0.12       0
Bank Sta=4983.8,4987.8
Exp/Cntr=0.3,0.1

Type RM Length L Ch R = 1,1882,327,327,327
BEGIN DESCRIPTION:
Denton Creek Tr 10 5.0
END DESCRIPTION:
XS GIS Cut Line= 3
      2344135.15      7073532.73      2343837.33      7072764.65
      2343294.19      7072084.75
#Sta/Elev= 30
  4204.4  594.16  4512.4  592.40  4572.3  593.91  4582.7  591.34  4591.5  587.99
  4657.8  588.68  4675.8  587.95  4681.2  588.76  4700.4  588.29  4883.0  589.92
  4915.2  589.87  4929.0  588.80  4978.1  589.36  5028.0  588.17  5115.5  588.99
  5150.7  588.45  5158.7  587.59  5187.5  588.46  5212.7  587.39  5213.0  586.89
  5216.7  587.39  5301.2  589.56  5307.6  588.96  5478.9  589.83  5621.4  591.80
  5648.6  591.42  5656.6  592.36  5685.5  592.83  5827.7  592.06  5898.4  594.15
#Mann=3,-1,0
  4204.4    0.05       0  5212.7   0.033       0  5216.7    0.05       0
Bank Sta=5212.7,5216.7
Exp/Cntr=0.3,0.1

Type RM Length L Ch R = 1,1555,0,0,0
BEGIN DESCRIPTION:
Denton Creek Tr 10 4.0
END DESCRIPTION:
XS GIS Cut Line= 3
      2344178.26      7073564.07      2344162.58      7072698.03
      2343578.66      7071945.60
#Sta/Elev= 30
  4196.1  594.37  4450.2  593.31  4560.2  592.07  4580.2  593.33  4590.2  589.82
  4610.2  586.71  4620.2  587.29  4670.2  585.80  4680.2  582.26  4700.2  580.83
  4830.3  582.77  4930.3  582.56  4950.3  581.44  5133.7  579.73  5398.9  580.99
  5405.2  581.91  5434.2  582.91  5477.5  582.00  5527.4  582.90  5647.8  582.34
  5712.0  582.99  5726.5  583.52  5741.0  586.01  5747.3  588.81  5761.8  591.23
  5816.8  592.07  5840.6  592.73  5869.5  591.73  5940.1  593.14  6014.7  592.63
#Mann=4,-1,0
  4196.1    0.05       0  4950.3   0.033       0  5398.9    0.05       0
  5816.8    0.12       0
Bank Sta=4950.3,5398.9
Exp/Cntr=0.3,0.1

Chan Stop Cuts=-1