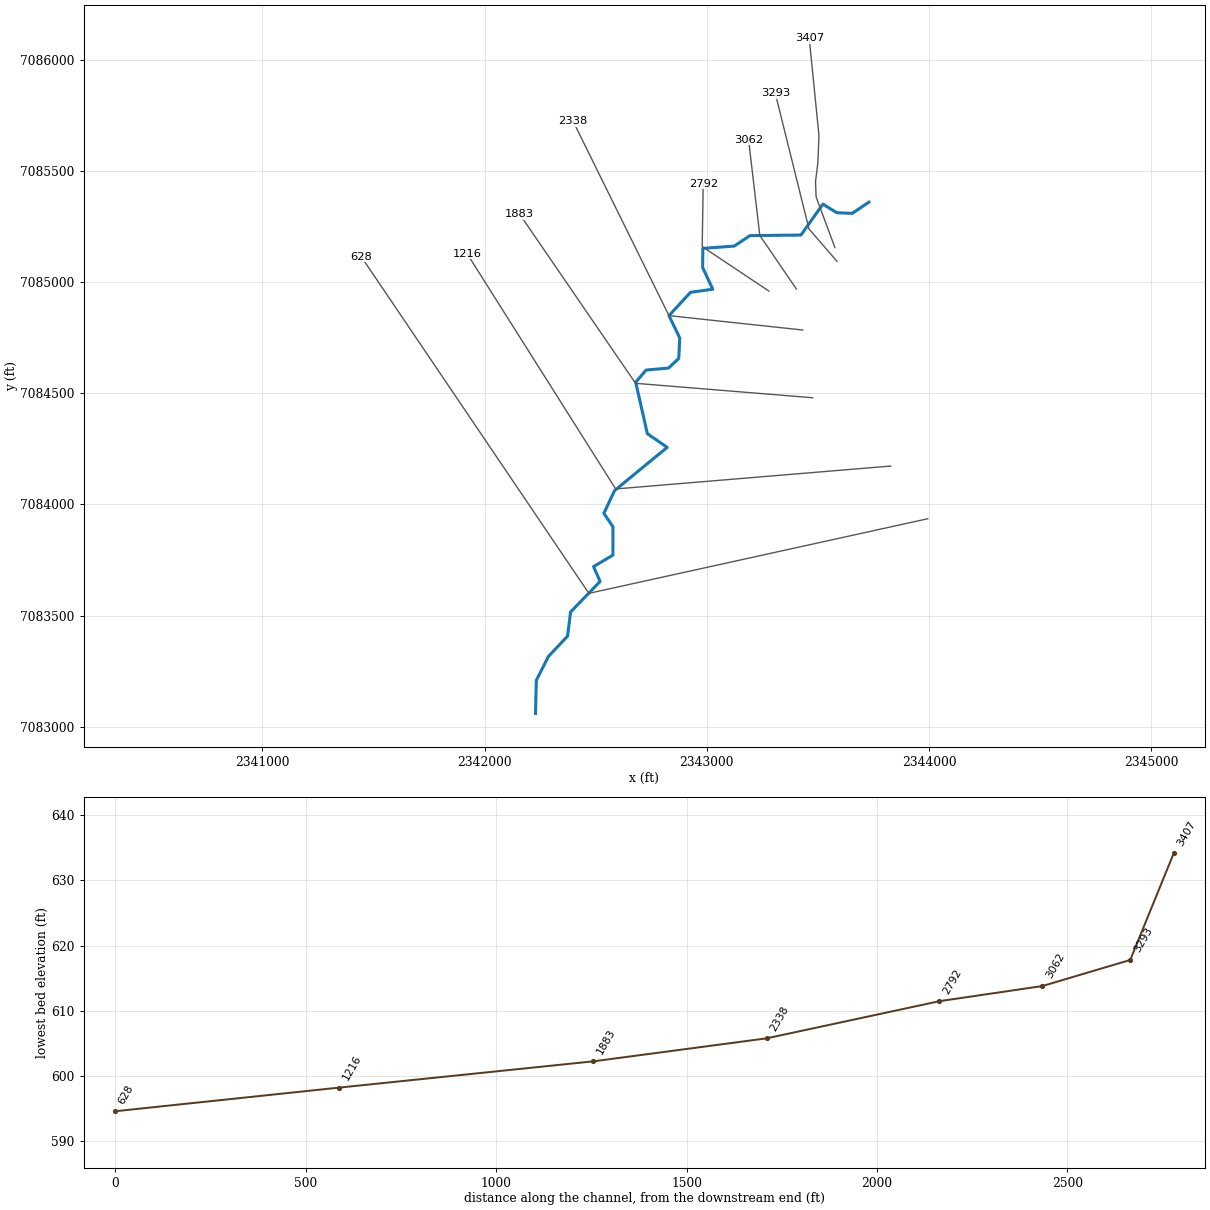
--- Denton Creek Tr 12.prj (project) ---

Proj Title=Denton Creek Tr 12 Base Level Engineering
Current Plan=p01
Default Exp/Contr=0.3,0.1
English Units
Geom File=g01
Flow File=f01
Plan File=p01
Y Axis Title=Elevation
X Axis Title(PF)=Main Channel Distance
X Axis Title(XS)=Station
BEGIN DESCRIPTION:
Denton Creek Tr 12
END DESCRIPTION:
DSS Export Rating Curves= 0
DSS Export Rating Curve Sorted= 0
DSS Export Volume Flow Curves= 0
DXF OffsetX= 0
DXF OffsetY= 0
DXF ScaleX= 1
DXF ScaleY= 10

--- Denton Creek Tr 12.p01 (plan) ---

Plan Title=Multiple Run
Short Identifier=Multiple
Geom File=g01
Flow File=f01
Subcritical Flow
K Sum by GR= 0
Std Step Tol= 0.01
Critical Tol= 0.01
Num of Std Step Trials= 20
Max Error Tol= 0.3
Flow Tol Ratio= 0.001
Split Flow NTrial= 30
Split Flow Tol= 0.02
Split Flow Ratio= 0.02
Log Output Level= 0
Friction Slope Method= 1
Unsteady Friction Slope Method= 2
Unsteady Bridges Friction Slope Method= 1
Parabolic Critical Depth
Global Vel Dist=  1 , 1 , 1
Global Log Level= 0
CheckData=True
Encroach Param= -1, 0, 0, 0
BEGIN DESCRIPTION:
Multiple Run
END DESCRIPTION:

--- Denton Creek Tr 12.f01 (steady flow) ---

Flow Title=Multiple
Number of Profiles=7
Profile Names=10-year,25-year,50-year,1pct_min,100-year,1pct_plu,500-year
River Rch & RM= Denton Creek Tr ,Reach-1,3407
     420     567     688     415     828    1651    1200
River Rch & RM= Denton Creek Tr ,Reach-1,2338
     519     709     865     526    1049    2092    1542
Boundary for River Rch & Prof#=Denton Creek Tr ,Reach-1,1
Up Type=0
Dn Type=3
Dn Slope=0.005
Boundary for River Rch & Prof#=Denton Creek Tr ,Reach-1,2
Up Type=0
Dn Type=3
Dn Slope=0.005
Boundary for River Rch & Prof#=Denton Creek Tr ,Reach-1,3
Up Type=0
Dn Type=3
Dn Slope=0.005
Boundary for River Rch & Prof#=Denton Creek Tr ,Reach-1,4
Up Type=0
Dn Type=3
Dn Slope=0.005
Boundary for River Rch & Prof#=Denton Creek Tr ,Reach-1,5
Up Type=0
Dn Type=3
Dn Slope=0.005
Boundary for River Rch & Prof#=Denton Creek Tr ,Reach-1,6
Up Type=0
Dn Type=3
Dn Slope=0.005
Boundary for River Rch & Prof#=Denton Creek Tr ,Reach-1,7
Up Type=0
Dn Type=3
Dn Slope=0.005

--- Denton Creek Tr 12.g01 (geometry) ---

Geom Title=Existing Conditions
Program Version=4.10

River Reach=Denton Creek Tr ,Reach-1
Reach XY= 30
        2343729.        7085360.        2343654.      7085309.53
      2343584.87      7085312.37      2343521.98      7085350.99
      2343423.33      7085211.98      2343194.22      7085209.48
      2343123.05      7085162.28      2342981.82      7085152.05
      2342981.16      7085066.04       2343026.5      7084968.15
      2342926.63      7084954.46      2342829.59      7084849.39
      2342877.88      7084749.45      2342873.72      7084657.29
      2342827.75      7084613.52      2342726.29      7084604.59
      2342679.86      7084549.69      2342732.21      7084318.34
      2342821.47      7084256.82       2342584.8       7084062.3
      2342536.53      7083960.01      2342577.63      7083899.55
      2342577.35      7083771.83      2342490.17      7083720.29
      2342519.69      7083653.34      2342386.86      7083516.17
      2342373.46      7083407.58      2342287.16      7083316.05
      2342232.72      7083208.46        2342229.        7083060.

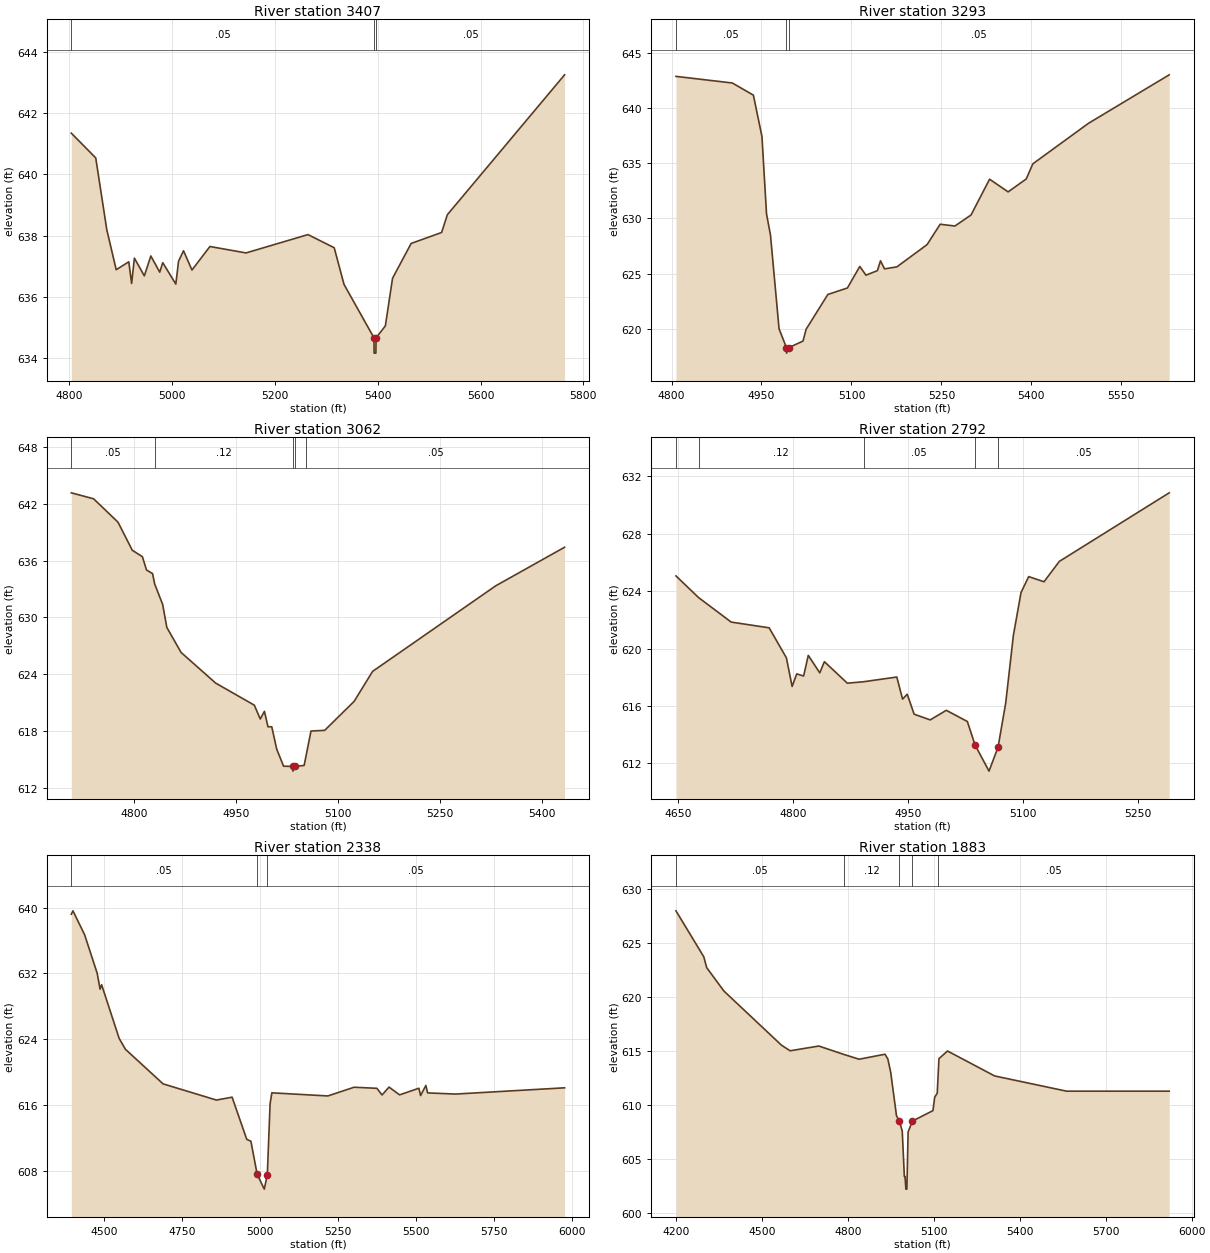
Type RM Length L Ch R = 1 ,3407    ,114,114,114
BEGIN DESCRIPTION:
Denton Creek Tr 12 10.0
END DESCRIPTION:
XS GIS Cut Line= 6
      2343576.11      7085155.62      2343491.46      7085383.53
      2343488.86      7085452.54      2343499.27      7085535.87
      2343504.48      7085658.27      2343460.56      7086096.97
#Sta/Elev= 30
  4803.9  641.35  4851.4  640.54  4872.9  638.19  4891.2  636.88  4915.7  637.14
  4921.2  636.43  4926.6  637.26  4945.9  636.68  4958.6  637.33  4975.9   636.8
  4981.8  637.11  5007.2  636.41  5012.5  637.16  5022.2   637.5  5038.6  636.87
  5073.5  637.64  5143.8  637.43  5264.3  638.03  5315.3   637.6  5334.4   636.4
  5392.7  634.65  5392.9  634.15  5396.4  634.15  5396.7  634.65  5414.8  635.04
  5428.8   636.6    5465  637.74  5524.3   638.1  5535.4  638.68  5763.5  643.26
#Mann= 3 ,-1 , 0
  4803.9     .05       0  5392.7    .033       0  5396.7     .05       0
Bank Sta=5392.7,5396.7
XS Rating Curve= 0 ,0
Exp/Cntr=0.3,0.1

Type RM Length L Ch R = 1 ,3293    ,231,231,231
BEGIN DESCRIPTION:
Denton Creek Tr 12 9.0
END DESCRIPTION:
XS GIS Cut Line= 3
      2343585.36      7085093.73      2343459.41      7085239.44
      2343307.59      7085850.66
#Sta/Elev= 30
  4807.4  642.85  4901.4  642.25  4936.5  641.15  4950.8   637.4  4958.4   630.4
    4965  628.48  4979.3  619.99  4991.6  618.29  4991.8  617.79  4995.6  618.29
  5019.2  618.88  5024.4  619.95  5060.6   623.1  5093.3  623.69  5113.9  625.64
  5124.2  624.85  5143.3  625.26  5148.4  626.15  5155.1  625.42  5175.7   625.6
    5226  627.61  5247.9  629.46  5272.5   629.3  5299.4   630.3  5330.3  633.54
  5361.2  632.39  5391.4  633.56  5402.4  634.93  5495.2   638.6  5629.8  642.99
#Mann= 3 ,-1 , 0
  4807.4     .05       0  4991.6    .033       0  4995.6     .05       0
Bank Sta=4991.6,4995.6
XS Rating Curve= 0 ,0
Exp/Cntr=0.3,0.1

Type RM Length L Ch R = 1 ,3062    ,270,270,270
BEGIN DESCRIPTION:
Denton Creek Tr 12 8.0
END DESCRIPTION:
XS GIS Cut Line= 3
      2343403.06      7084968.74      2343238.14      7085210.32
      2343187.79      7085640.58
#Sta/Elev= 30
  4707.5  643.14  4740.3  642.51  4776.2  640.04  4797.2  637.08  4812.1   636.4
  4818.1     635    4827  634.62  4830.2  633.51  4841.9  631.36    4848  628.94
    4869   626.3  4919.8  623.07  4976.7  620.74  4985.5  619.28  4991.6  620.09
  4996.8  618.46  5002.4  618.46  5009.7  616.09  5019.8   614.3  5033.3  614.28
  5033.5  613.78  5037.3  614.28    5050  614.38  5053.2  615.53  5060.1  618.01
  5080.2  618.08  5123.6  621.14  5150.7   624.3  5331.9  633.33  5433.2   637.4
#Mann= 5 ,-1 , 0
  4707.5     .05       0  4830.2     .12       0  5033.3     .07       0
  5037.3     .12       0  5053.2     .05       0
Bank Sta=5033.3,5037.3
XS Rating Curve= 0 ,0
Exp/Cntr=0.3,0.1

Type RM Length L Ch R = 1 ,2792    ,454,454,454
BEGIN DESCRIPTION:
Denton Creek Tr 12 7.0
END DESCRIPTION:
XS GIS Cut Line= 3
      2343278.99      7084960.01        2342979.        7085160.
      2342983.62      7085443.52
#Sta/Elev= 30
  4646.9  625.07  4676.4  623.56    4719  621.85  4768.6  621.45  4791.1  619.36
  4798.6  617.36  4804.6  618.24  4813.6  618.09  4819.7  619.53  4834.7  618.31
  4840.7  619.09  4870.7  617.59  4891.8  617.69  4935.3  618.02  4942.8  616.48
  4948.9  616.82  4957.9  615.43  4978.9  615.03  4999.9   615.7  5027.4  614.92
  5037.5  613.28  5055.7  611.46  5067.5  613.13  5077.5  616.21  5087.5  620.92
  5097.5  623.91  5107.5  625.02  5127.5  624.66  5147.5  626.08    5291  630.86
#Mann= 5 ,-1 , 0
  4646.9     .05       0  4676.4     .12       0  4891.8     .05       0
  5037.5    .033       0  5067.5     .05       0
Bank Sta=5037.5,5067.5
XS Rating Curve= 0 ,0
Exp/Cntr=0.3,0.1

Type RM Length L Ch R = 1 ,2338    ,455,455,455
BEGIN DESCRIPTION:
Denton Creek Tr 12 6.0
END DESCRIPTION:
XS GIS Cut Line= 3
      2343431.53       7084784.7      2342829.59      7084849.39
      2342397.67      7085724.83
#Sta/Elev= 30
  4394.6  639.21  4399.8  639.62  4437.4  636.69  4477.6  632.01  4486.8  630.09
  4491.8  630.62    4548  624.09  4568.1  622.77  4688.8  618.56  4859.8  616.59
  4910.1  616.94  4957.1  611.81  4970.4  611.58  4990.5  607.55  5013.3  605.75
    5023  607.48  5031.9  616.12  5037.5  617.47  5217.1  617.09  5301.3  618.15
  5374.3  618.02    5391  617.21  5413.3  618.17  5447.2  617.22    5509  618.03
  5514.5  617.14  5531.4  618.37    5537  617.46  5626.8  617.32  5976.2  618.08
#Mann= 3 ,-1 , 0
  4394.6     .05       0  4990.5    .033       0    5023     .05       0
Bank Sta=4990.5,5023
XS Rating Curve= 0 ,0
Exp/Cntr=0.3,0.1

Type RM Length L Ch R = 1 ,1883    ,667,667,667
BEGIN DESCRIPTION:
Denton Creek Tr 12 5.0
END DESCRIPTION:
XS GIS Cut Line= 3
      2343475.84      7084480.01      2342679.18      7084544.92
      2342158.26       7085305.3
#Sta/Elev= 30
  4200.7  627.99  4297.9  623.73  4307.9  622.73  4368.1  620.56  4568.8  615.55
  4598.9  615.03  4699.2  615.47  4787.9  614.68  4839.7  614.25    4930  614.71
    4940  614.27    4950  613.03  4970.1  609.02  4980.1  608.53  4990.2  607.61
  4997.6  603.39    5000  603.39  5002.9  602.22  5006.4  602.22  5010.7  607.51
  5025.6  608.52  5097.4  609.49  5103.4  610.73  5112.3   611.1  5114.1  612.06
  5118.3   614.3  5148.1  615.01  5312.6   612.7  5563.7  611.29  5921.7  611.29
#Mann= 5 ,-1 , 0
  4200.7     .05       0  4787.9     .12       0  4980.1     .07       0
  5025.6     .12       0  5114.1     .05       0
Bank Sta=4980.1,5025.6
XS Rating Curve= 0 ,0
Exp/Cntr=0.3,0.1

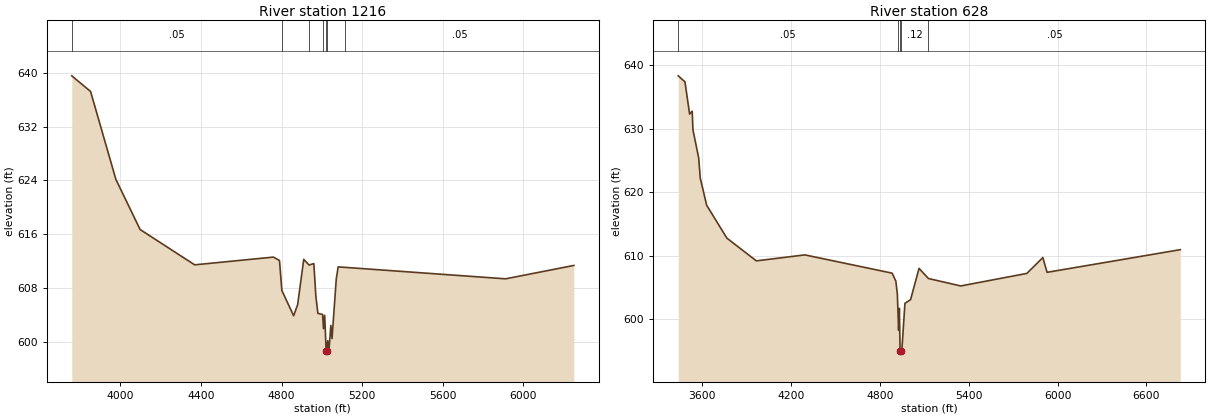
Type RM Length L Ch R = 1 ,1216    ,588,588,588
BEGIN DESCRIPTION:
Denton Creek Tr 12 4.0
END DESCRIPTION:
XS GIS Cut Line= 3
      2343827.36      7084172.72      2342589.74       7084069.7
      2341921.12      7085128.45
#Sta/Elev= 30
  3758.1  639.55  3851.5  637.23  3977.2  624.16  4097.6  616.71  4368.6  611.46
  4759.9  612.61    4790   612.1  4801.8  607.65  4860.3  603.89  4880.3  605.56
  4910.4  612.27    4937  611.43  4960.6  611.65  4970.6  606.81  4980.7  604.25
  5004.3  604.08  5008.5  601.97  5014.4  603.96  5021.8  598.69    5022  598.19
  5025.8  598.69  5029.7  600.18  5035.8  598.75    5045  602.46  5050.9   600.5
  5072.1  609.38  5081.4  611.15  5117.2  611.08  5913.3  609.38  6252.2  611.37
#Mann= 7 ,-1 , 0
  3758.1     .05       0  4801.8     .12       0    4937     .05       0
  5004.3     .12       0  5021.8    .033       0  5025.8     .12       0
  5117.2     .05       0
Bank Sta=5021.8,5025.8
XS Rating Curve= 0 ,0
Exp/Cntr=0.3,0.1

Type RM Length L Ch R = 1 ,628     ,0,0,0
BEGIN DESCRIPTION:
Denton Creek Tr 12 3.0
END DESCRIPTION:
XS GIS Cut Line= 3
      2343994.03      7083935.74      2342469.26      7083600.01
       2341444.7      7085115.23
#Sta/Elev= 30
  3438.7  638.28  3484.2  637.33  3515.5  632.27    3533  632.72  3538.1  629.79
  3576.8  625.39  3587.2  622.24  3630.7  617.95    3767  612.79  3966.1  609.21
  4293.7  610.15  4883.1  607.28  4908.1  606.04  4918.3  604.04  4925.1   599.5
  4926.9   598.3    4932  601.74  4936.8  595.06  4937.1  594.56  4940.8  595.06
  4949.1  595.29  4969.5  602.54  5007.7  603.12  5064.7  608.03  5128.1  606.44
  5346.3  605.27  5792.8  607.24  5900.7  609.73  5929.5  607.41  6829.1  610.97
#Mann= 5 ,-1 , 0
  3438.7     .05       0  4925.1     .12       0  4936.8     .07       0
  4940.8     .12       0  5128.1     .05       0
Bank Sta=4936.8,4940.8
XS Rating Curve= 0 ,0
Exp/Cntr=0.3,0.1

Chan Stop Cuts=-1
Use User Specified Reach Order=0
Composite Channel Slope=5