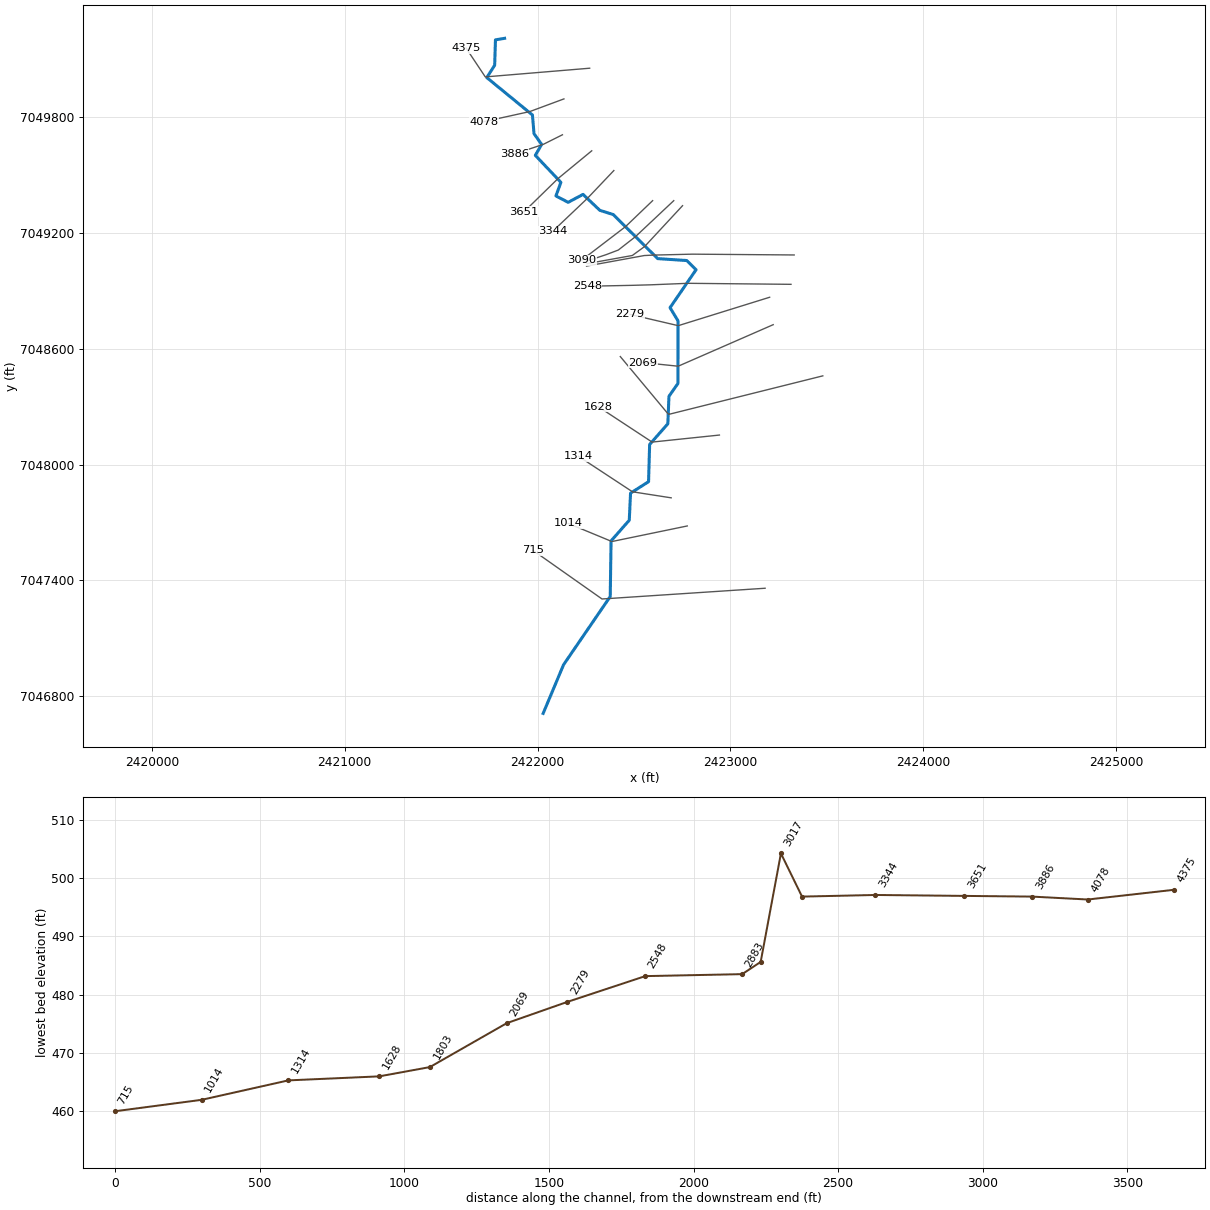
--- Denton Creek Tr 2.prj (project) ---

Proj Title=Denton Creek Tr 2 Base Level Engineering
Current Plan=p01
Default Exp/Contr=0.3,0.1
English Units
Geom File=g01
Flow File=f01
Plan File=p01
BEGIN DESCRIPTION:
Denton Creek Tr 2
END DESCRIPTION:

--- Denton Creek Tr 2.p01 (plan) ---

Plan Title=Multiple Run
Short Identifier=Multiple
Geom File=g01
Flow File=f01
Subcritical Flow
K Sum by GR= 0
Std Step Tol= 0.01
Critical Tol= 0.01
Num of Std Step Trials= 20
Max Error Tol= 0.3
Flow Tol Ratio= 0.001
Split Flow NTrial= 30
Split Flow Tol= 0.02
Split Flow Ratio= 0.02
Log Output Level= 0
Friction Slope Method= 1
Unsteady Friction Slope Method= 2
Unsteady Bridges Friction Slope Method= 1
Parabolic Critical Depth
Global Vel Dist=  1 , 1 , 1
Global Log Level= 0
CheckData=True
Encroach Param= -1, 0, 0, 0
BEGIN DESCRIPTION:
Multiple Run
END DESCRIPTION:

--- Denton Creek Tr 2.f01 (steady flow) ---

Flow Title=Multiple
Number of Profiles=7
Profile Names=10-year,25-year,50-year,1pct_min,100-year,1pct_plu,500-year
River Rch & RM= Denton Creek Tr ,Reach-1,4375
     384     514     619     371     741    1478    1060
River Rch & RM= Denton Creek Tr ,Reach-1,1314
     530     719     872     525    1048    2092    1514
Boundary for River Rch & Prof#=Denton Creek Tr ,Reach-1,1
Up Type=0
Dn Type=3
Dn Slope=0.005
Boundary for River Rch & Prof#=Denton Creek Tr ,Reach-1,2
Up Type=0
Dn Type=3
Dn Slope=0.005
Boundary for River Rch & Prof#=Denton Creek Tr ,Reach-1,3
Up Type=0
Dn Type=3
Dn Slope=0.005
Boundary for River Rch & Prof#=Denton Creek Tr ,Reach-1,4
Up Type=0
Dn Type=3
Dn Slope=0.005
Boundary for River Rch & Prof#=Denton Creek Tr ,Reach-1,5
Up Type=0
Dn Type=3
Dn Slope=0.005
Boundary for River Rch & Prof#=Denton Creek Tr ,Reach-1,6
Up Type=0
Dn Type=3
Dn Slope=0.005
Boundary for River Rch & Prof#=Denton Creek Tr ,Reach-1,7
Up Type=0
Dn Type=3
Dn Slope=0.005

--- Denton Creek Tr 2.g01 (geometry) ---

Geom Title=Existing Conditions

River Reach=Denton Creek Tr ,Reach-1
Reach XY= 30
      2421829.00      7050210.00      2421781.72      7050202.29
      2421777.60      7050070.44      2421736.79      7050006.57
      2421973.49      7049812.44      2421981.55      7049715.89
      2422021.20      7049659.90      2421988.30      7049603.33
      2422120.99      7049463.32      2422095.24      7049392.79
      2422158.69      7049359.76      2422235.72      7049400.83
      2422322.95      7049318.20      2422392.21      7049296.37
      2422622.81      7049067.82      2422773.55      7049057.94
      2422821.82      7049010.33      2422686.81      7048813.41
      2422728.34      7048744.84      2422727.78      7048420.50
      2422681.27      7048354.06      2422675.44      7048211.47
      2422581.07      7048104.14      2422575.52      7047911.26
      2422482.11      7047851.68      2422475.44      7047711.48
      2422381.07      7047604.14      2422376.76      7047315.93
      2422134.85      7046962.29      2422029.00      7046710.00

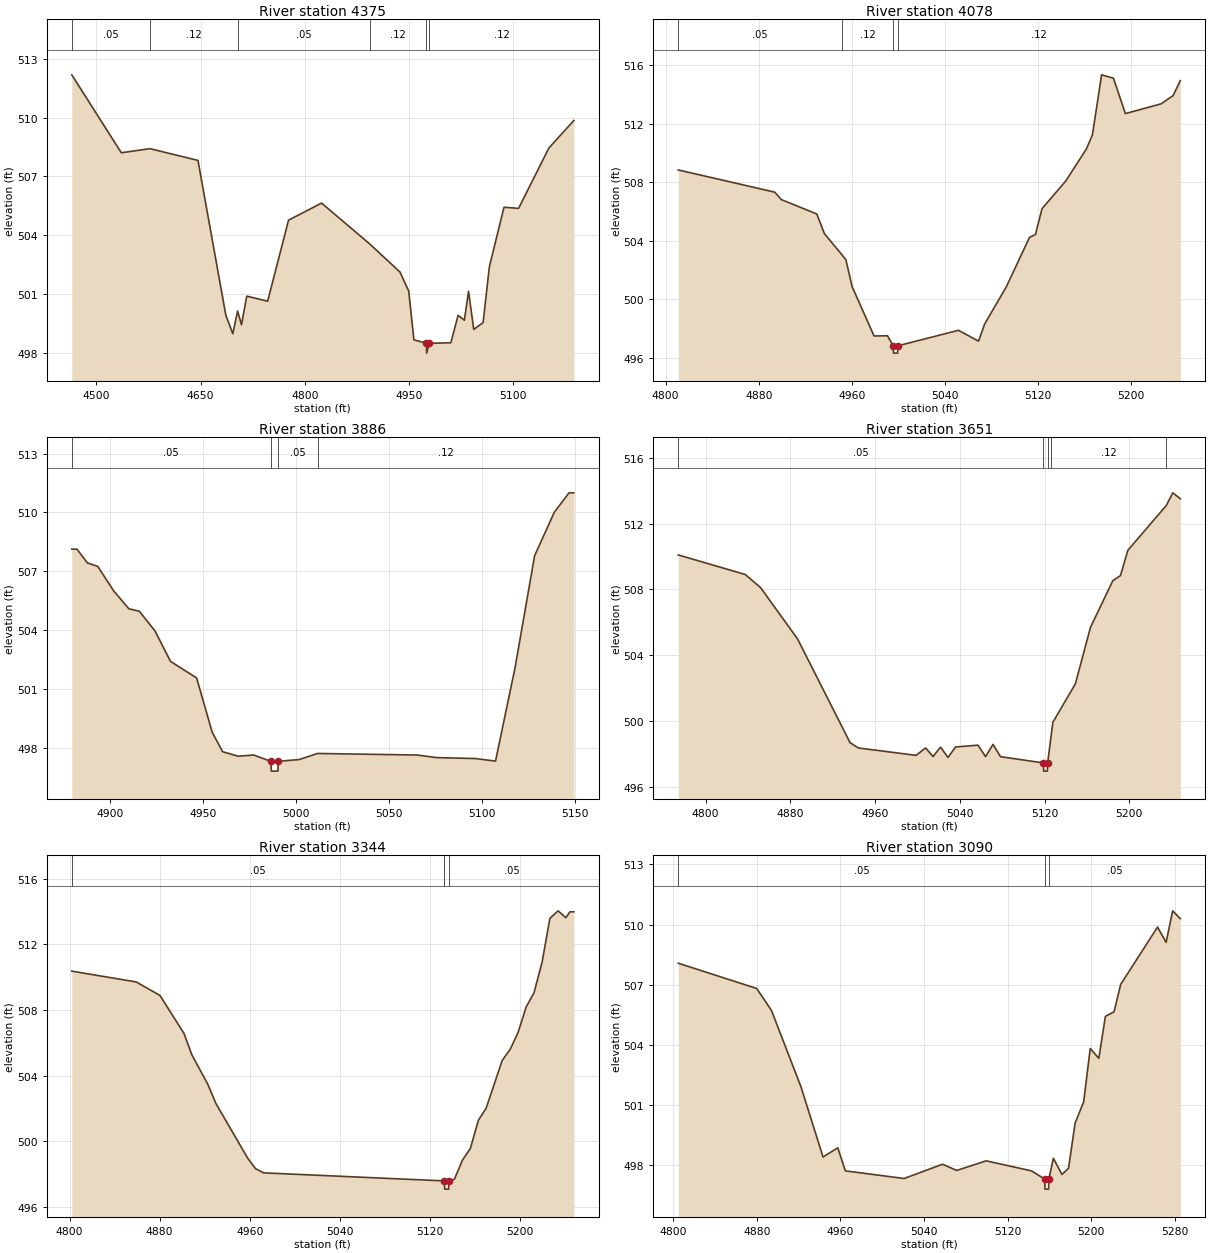
Type RM Length L Ch R = 1,4375,297,297,297
BEGIN DESCRIPTION:
Denton Creek Tr 2 15.0
END DESCRIPTION:
XS GIS Cut Line= 3
      2422270.18      7050055.10      2421729.00      7050010.00
      2421629.02      7050159.97
#Sta/Elev= 30
  4464.4  512.19  4535.8  508.21  4577.1  508.42  4646.2  507.82  4686.4  499.91
  4696.4  498.97  4703.3  500.13  4708.9  499.43  4716.5  500.89  4746.6  500.63
  4776.7  504.77  4824.3  505.64  4893.8  503.55  4937.2  502.12  4949.8  501.15
  4957.3  498.66  4975.4  498.48  4975.6  497.98  4979.4  498.48  5010.5  498.51
  5021.0  499.91  5030.0  499.66  5036.0  501.14  5043.5  499.19  5057.0  499.54
  5066.0  502.39  5087.1  505.43  5108.1  505.37  5151.7  508.45  5187.7  509.86
#Mann=6,-1,0
  4464.4    0.05       0  4577.1    0.12       0  4703.3    0.05       0
  4893.8    0.12       0  4975.4    0.07       0  4979.4    0.12       0
Bank Sta=4975.4,4979.4
Exp/Cntr=0.3,0.1

Type RM Length L Ch R = 1,4078,192,192,192
BEGIN DESCRIPTION:
Denton Creek Tr 2 14.0
END DESCRIPTION:
XS GIS Cut Line= 3
      2422136.69      7049895.96      2421959.39      7049830.20
      2421722.95      7049778.17
#Sta/Elev= 30
  4810.9  508.84  4893.8  507.32  4899.5  506.81  4929.9  505.83  4936.4  504.49
  4951.4  503.05  4954.9  502.70  4960.3  500.85  4979.1  497.49  4990.6  497.51
  4995.5  496.82  4995.8  496.32  4999.3  496.32  4999.5  496.82  5051.6  497.88
  5068.8  497.14  5074.0  498.30  5092.6  500.84  5112.6  504.23  5117.7  504.43
  5123.3  506.19  5143.7  508.08  5161.4  510.27  5166.6  511.23  5174.5  515.34
  5184.7  515.11  5194.9  512.69  5225.7  513.36  5235.9  513.92  5242.1  514.94
#Mann=4,-1,0
  4810.9    0.05       0  4951.4    0.12       0  4995.5    0.07       0
  4999.5    0.12       0
Bank Sta=4995.5,4999.5
Exp/Cntr=0.3,0.1

Type RM Length L Ch R = 1,3886,235,235,235
BEGIN DESCRIPTION:
Denton Creek Tr 2 13.0
END DESCRIPTION:
XS GIS Cut Line= 3
      2422129.00      7049710.00      2422029.00      7049660.00
      2421879.01      7049610.00
#Sta/Elev= 29
  4879.5  508.13  4882.3  508.13  4887.9  507.43  4893.5  507.25  4901.9  506.02
  4910.2  505.09  4915.8  504.97  4924.2  503.97  4932.6  502.41  4946.6  501.57
  4955.0  498.80  4960.6  497.81  4968.9  497.58  4977.3  497.64  4986.5  497.32
  4986.8  496.82  4990.3  496.82  4990.5  497.32  5001.8  497.41  5011.6  497.72
  5065.1  497.64  5075.6  497.51  5096.7  497.46  5107.3  497.33  5117.8  502.09
  5128.3  507.79  5138.9  510.01  5146.8  511.00  5149.4  511.00
#Mann=4,-1,0
  4879.5    0.05       0  4986.5   0.033       0  4990.5    0.05       0
  5011.6    0.12       0
Bank Sta=4986.5,4990.5
Exp/Cntr=0.3,0.1

Type RM Length L Ch R = 1,3651,307,307,307
BEGIN DESCRIPTION:
Denton Creek Tr 2 12.0
END DESCRIPTION:
XS GIS Cut Line= 3
      2422280.80      7049626.85      2422106.48      7049483.33
      2421928.98      7049309.98
#Sta/Elev= 30
  4774.2  510.10  4837.4  508.91  4851.8  508.12  4886.9  504.98  4936.4  498.67
  4944.3  498.35  4998.7  497.90  5007.7  498.35  5014.7  497.83  5021.8  498.40
  5028.8  497.77  5036.0  498.41  5057.1  498.52  5064.3  497.82  5071.3  498.57
  5078.4  497.82  5118.9  497.44  5119.1  496.94  5122.6  496.94  5122.9  497.44
  5126.2  499.10  5127.8  499.91  5149.1  502.26  5163.3  505.69  5184.4  508.53
  5191.6  508.84  5198.6  510.38  5234.9  513.11  5241.0  513.88  5248.1  513.52
#Mann=5,-1,0
  4774.2    0.05       0  5118.9   0.033       0  5122.9    0.05       0
  5126.2    0.12       0  5234.9    0.05       0
Bank Sta=5118.9,5122.9
Exp/Cntr=0.3,0.1

Type RM Length L Ch R = 1,3344,254,254,254
BEGIN DESCRIPTION:
Denton Creek Tr 2 11.0
END DESCRIPTION:
XS GIS Cut Line= 3
      2422395.44      7049524.47      2422258.99      7049380.86
      2422078.98      7049209.98
#Sta/Elev= 30
  4801.9  510.37  4859.2  509.71  4880.3  508.89  4901.7  506.57  4908.6  505.28
  4922.7  503.50  4930.0  502.32  4958.3  498.98  4965.2  498.35  4972.5  498.09
  5133.1  497.60  5133.4  497.10  5136.9  497.10  5137.1  497.60  5142.0  497.70
  5149.3  498.88  5156.2  499.57  5163.4  501.30  5170.3  502.03  5184.5  504.93
  5191.7  505.62  5198.6  506.63  5205.9  508.20  5212.8  509.05  5220.0  510.92
  5226.9  513.58  5234.2  514.04  5241.1  513.62  5244.7  513.98  5248.2  513.98
#Mann=3,-1,0
  4801.9    0.05       0  5133.1   0.033       0  5137.1    0.05       0
Bank Sta=5133.1,5137.1
Exp/Cntr=0.3,0.1

Type RM Length L Ch R = 1,3090,73,73,73
BEGIN DESCRIPTION:
Denton Creek Tr 2 10.0
END DESCRIPTION:
XS GIS Cut Line= 3
      2422596.62      7049368.44      2422455.69      7049233.38
      2422228.99      7049060.00
#Sta/Elev= 30
  4804.8  508.08  4879.9  506.82  4894.0  505.73  4922.3  501.92  4943.4  498.42
  4957.5  498.88  4964.8  497.73  5021.0  497.35  5057.8  498.06  5071.4  497.75
  5099.5  498.23  5143.0  497.73  5155.6  497.32  5155.8  496.82  5159.3  496.82
  5159.6  497.32  5163.9  498.36  5172.1  497.55  5178.4  497.86  5184.7  500.11
  5192.9  501.17  5199.2  503.83  5207.4  503.34  5213.7  505.43  5222.0  505.66
  5228.3  507.02  5263.6  509.88  5271.8  509.12  5278.1  510.69  5285.4  510.30
#Mann=3,-1,0
  4804.8    0.05       0  5155.6    0.05       0  5159.6    0.05       0
Bank Sta=5155.6,5159.6
Exp/Cntr=0.3,0.1

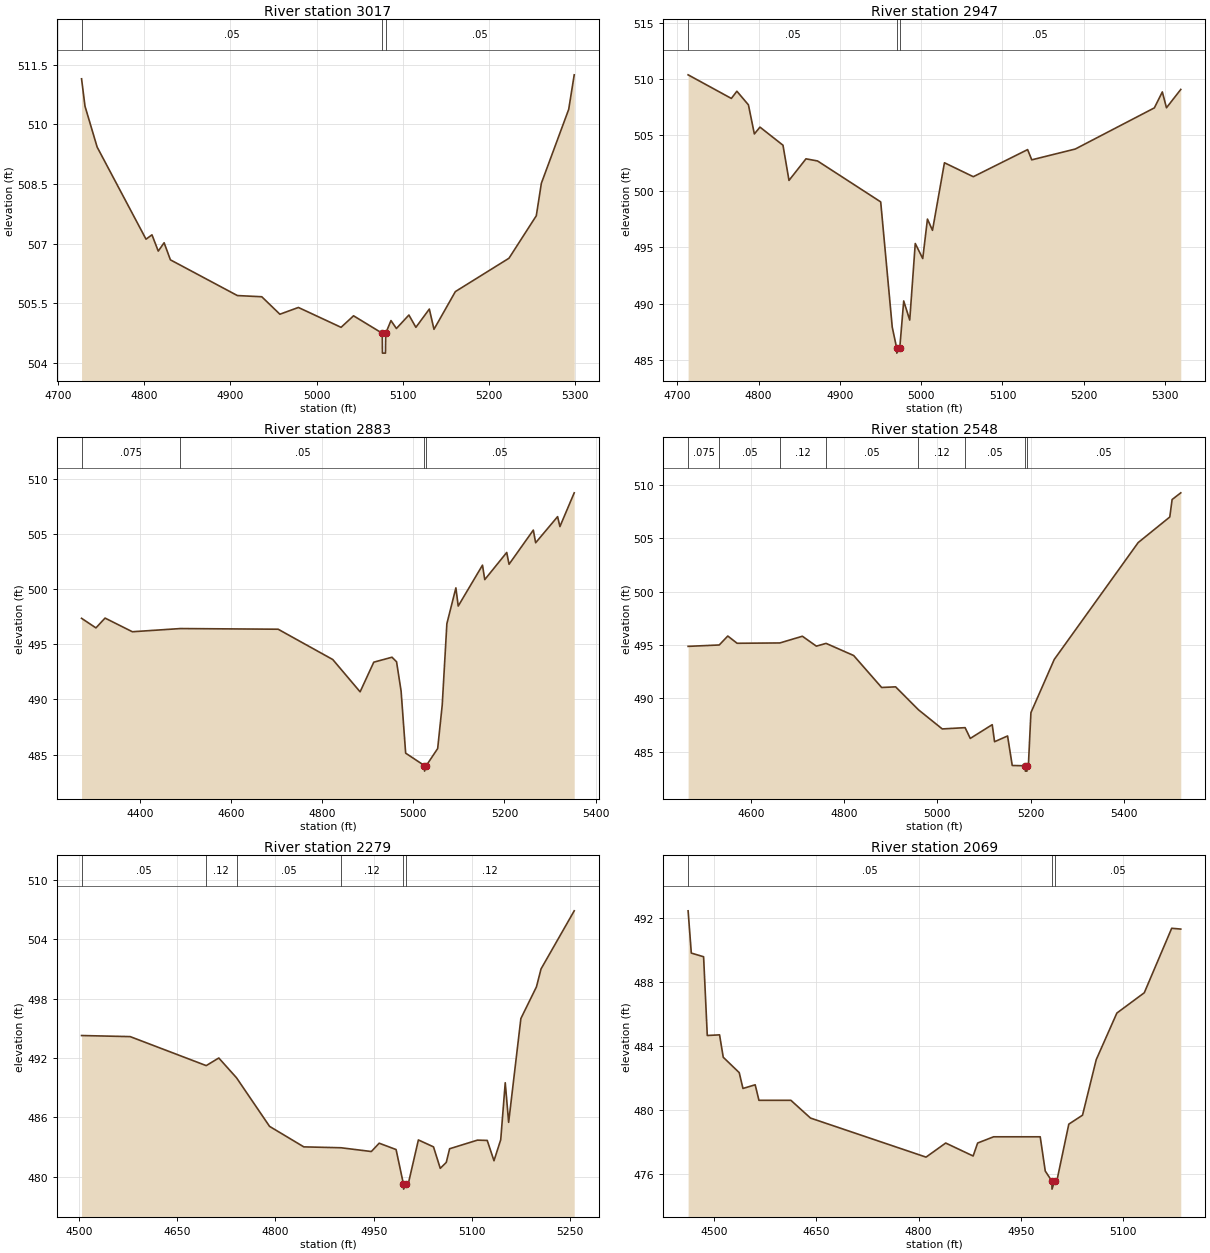
Type RM Length L Ch R = 1,3017,70,70,70
BEGIN DESCRIPTION:
Mapping XS 2ab8bc8c
END DESCRIPTION:
XS GIS Cut Line= 5
      2422706.18      7049368.41      2422507.61      7049181.78
      2422418.64      7049112.34      2422355.70      7049088.46
      2422242.89      7049050.86
#Sta/Elev= 30
  4727.2  511.15  4731.2  510.46  4745.3  509.43  4802.0  507.11  4808.9  507.22
  4816.2  506.81  4823.0  507.02  4830.3  506.59  4908.0  505.69  4936.3  505.66
  4957.3  505.22  4978.8  505.39  5028.3  504.89  5042.8  505.18  5076.1  504.74
  5076.3  504.24  5079.8  504.24  5080.1  504.74  5086.2  505.06  5092.5  504.86
  5107.0  505.20  5115.1  504.89  5130.7  505.35  5136.1  504.84  5160.9  505.79
  5223.1  506.63  5254.8  507.70  5260.7  508.52  5292.4  510.38  5298.8  511.25
#Mann=3,-1,0
  4727.2    0.05       0  5076.1    0.05       0  5080.1    0.05       0
Bank Sta=5076.1,5080.1
Exp/Cntr=0.3,0.1

Type RM Length L Ch R = 1,2947,64,64,64
BEGIN DESCRIPTION:
Mapping XS 3b41b213
END DESCRIPTION:
XS GIS Cut Line= 4
      2422751.72      7049342.34      2422555.35      7049130.78
      2422491.34      7049084.12      2422256.99      7049041.81
#Sta/Elev= 30
  4713.3  510.35  4766.5  508.25  4773.3  508.89  4787.5  507.68  4794.8  505.09
  4801.7  505.70  4830.0  504.09  4837.4  500.96  4858.3  502.88  4872.5  502.69
  4950.2  499.05  4964.4  487.91  4969.7  486.10  4970.0  485.60  4973.7  486.10
  4978.5  490.24  4985.9  488.54  4992.7  495.35  5001.9  494.01  5007.7  497.52
  5013.9  496.52  5028.6  502.53  5064.1  501.29  5130.9  503.70  5136.0  502.79
  5189.5  503.75  5286.8  507.41  5296.6  508.83  5301.7  507.42  5319.3  509.05
#Mann=3,-1,0
  4713.3    0.05       0  4969.7    0.05       0  4973.7    0.05       0
Bank Sta=4969.7,4973.7
Exp/Cntr=0.3,0.1

Type RM Length L Ch R = 1,2883,335,335,335
BEGIN DESCRIPTION:
Denton Creek Tr 2 9.0
END DESCRIPTION:
XS GIS Cut Line= 5
      2423330.55      7049086.82      2422802.60      7049090.97
      2422602.13      7049086.17      2422553.68      7049083.86
      2422253.92      7049029.22
#Sta/Elev= 30
  4271.5  497.36  4303.1  496.49  4323.1  497.38  4383.1  496.14  4488.5  496.43
  4703.1  496.37  4823.1  493.62  4883.1  490.69  4913.1  493.38  4953.1  493.83
  4963.1  493.42  4973.1  490.76  4983.1  485.13  5024.4  484.00  5024.6  483.50
  5028.4  484.00  5053.4  485.55  5063.4  489.50  5073.6  496.87  5093.4  500.12
  5098.5  498.47  5151.8  502.18  5156.8  500.87  5205.0  503.33  5210.1  502.26
  5263.4  505.36  5268.5  504.21  5316.7  506.58  5321.8  505.68  5353.2  508.74
#Mann=4,-1,0
  4271.5   0.075       0  4488.5    0.05       0  5024.4    0.05       0
  5028.4    0.05       0
Bank Sta=5024.4,5028.4
Exp/Cntr=0.3,0.1

Type RM Length L Ch R = 1,2548,269,269,269
BEGIN DESCRIPTION:
Denton Creek Tr 2 8.0
END DESCRIPTION:
XS GIS Cut Line= 5
      2423314.09      7048934.56      2422779.62      7048939.84
      2422584.49      7048931.95      2422491.61      7048929.35
      2422257.66      7048924.58
#Sta/Elev= 30
  4465.5  494.87  4532.3  495.00  4550.6  495.84  4570.6  495.16  4662.3  495.19
  4710.6  495.82  4740.6  494.89  4761.4  495.15  4820.6  494.01  4880.6  491.01
  4910.6  491.07  4959.5  488.92  5010.6  487.12  5059.6  487.24  5070.7  486.23
  5117.8  487.52  5122.8  485.92  5150.7  486.46  5160.7  483.69  5188.5  483.66
  5188.8  483.16  5192.3  483.16  5192.5  483.66  5195.3  483.66  5200.8  488.65
  5250.8  493.64  5430.8  504.61  5498.6  507.01  5503.6  508.65  5522.2  509.28
#Mann=8,-1,0
  4465.5   0.075       0  4532.3    0.05       0  4662.3    0.12       0
  4761.4    0.05       0  4959.5    0.12       0  5059.6    0.05       0
  5188.5    0.07       0  5192.5    0.05       0
Bank Sta=5188.5,5192.5
Exp/Cntr=0.3,0.1

Type RM Length L Ch R = 1,2279,210,210,210
BEGIN DESCRIPTION:
Denton Creek Tr 2 7.0
END DESCRIPTION:
XS GIS Cut Line= 3
      2423203.33      7048867.53      2422729.40      7048720.21
      2422479.63      7048778.57
#Sta/Elev= 30
  4503.7  494.26  4578.0  494.15  4694.2  491.22  4713.4  491.99  4740.5  489.99
  4791.0  485.08  4843.3  483.01  4900.1  482.92  4946.5  482.54  4958.5  483.38
  4984.3  482.74  4995.6  479.24  4995.8  478.74  4999.6  479.24  5002.8  479.24
  5018.4  483.71  5041.5  483.01  5051.8  480.84  5061.0  481.44  5066.1  482.82
  5108.6  483.69  5123.6  483.66  5133.9  481.61  5144.2  483.73  5151.1  489.49
  5156.3  485.49  5175.0  495.98  5198.8  499.18  5205.8  500.99  5256.5  506.86
#Mann=6,-1,0
  4503.7    0.05       0  4694.2    0.12       0  4740.5    0.05       0
  4900.1    0.12       0  4995.6    0.07       0  4999.6    0.12       0
Bank Sta=4995.6,4999.6
Exp/Cntr=0.3,0.1

Type RM Length L Ch R = 1,2069,266,266,266
BEGIN DESCRIPTION:
Denton Creek Tr 2 6.0
END DESCRIPTION:
XS GIS Cut Line= 3
      2423221.78      7048725.39      2422729.00      7048510.00
      2422545.78      7048529.00
#Sta/Elev= 30
  4462.3  492.47  4467.0  489.83  4485.0  489.60  4490.4  484.68  4508.4  484.72
  4513.8  483.32  4537.2  482.36  4542.7  481.37  4560.6  481.60  4566.1  480.63
  4612.9  480.63  4641.7  479.52  4811.0  477.08  4839.8  477.96  4880.0  477.15
  4886.6  477.96  4910.0  478.35  4978.3  478.35  4985.7  476.21  4995.4  475.58
  4995.6  475.08  4999.4  475.58  5002.6  475.58  5020.2  479.14  5040.3  479.70
  5060.4  483.17  5090.6  486.08  5130.8  487.35  5171.0  491.38  5184.3  491.33
#Mann=3,-1,0
  4462.3    0.05       0  4995.4   0.033       0  4999.4    0.05       0
Bank Sta=4995.4,4999.4
Exp/Cntr=0.3,0.1

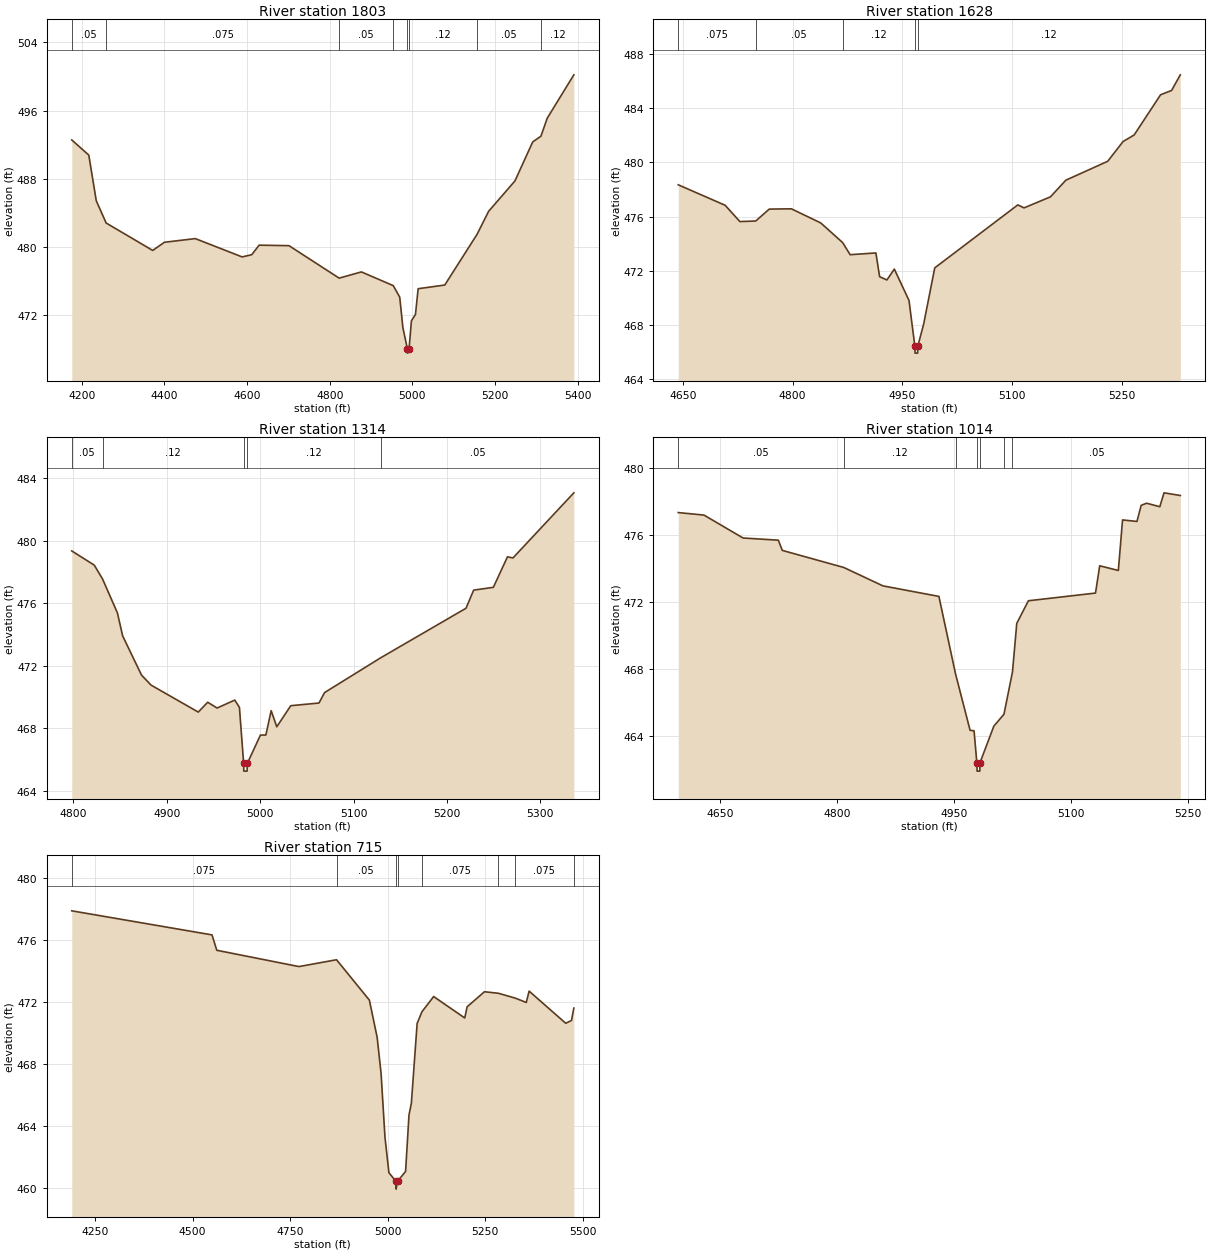
Type RM Length L Ch R = 1,1803,175,175,175
BEGIN DESCRIPTION:
Denton Creek Tr 2 5.0
END DESCRIPTION:
XS GIS Cut Line= 3
      2423479.01      7048460.00      2422679.00      7048260.00
      2422429.02      7048559.97
#Sta/Elev= 30
  4175.7  492.55  4216.9  490.77  4235.0  485.41  4258.9  482.80  4371.6  479.58
  4399.9  480.54  4474.6  480.97  4588.0  478.82  4611.2  479.08  4629.2  480.20
  4701.4  480.14  4822.8  476.33  4876.6  477.06  4953.8  475.45  4969.4  474.10
  4977.1  470.51  4988.0  468.03  4988.3  467.53  4992.0  468.03  4997.7  471.32
  5007.5  472.07  5014.0  475.09  5078.4  475.52  5156.8  481.49  5184.5  484.17
  5248.3  487.74  5291.3  492.32  5311.1  492.98  5326.4  495.10  5390.8  500.19
#Mann=8,-1,0
  4175.7    0.05       0  4258.9   0.075       0  4822.8    0.05       0
  4953.8    0.12       0  4988.0    0.07       0  4992.0    0.12       0
  5156.8    0.05       0  5311.1    0.12       0
Bank Sta=4988,4992
Exp/Cntr=0.3,0.1

Type RM Length L Ch R = 1,1628,314,314,314
BEGIN DESCRIPTION:
Mapping XS 9df6b81c
END DESCRIPTION:
XS GIS Cut Line= 3
      2422942.86      7048153.08      2422593.88      7048116.62
      2422313.35      7048301.04
#Sta/Elev= 30
  4643.7  478.34  4707.9  476.83  4728.0  475.63  4749.6  475.67  4768.2  476.55
  4798.4  476.57  4838.6  475.53  4868.6  474.08  4878.8  473.19  4914.0  473.32
  4919.1  471.57  4929.1  471.33  4939.2  472.13  4959.3  469.82  4967.3  466.44
  4967.6  465.94  4971.1  465.94  4971.3  466.44  4979.4  468.10  4994.5  472.22
  5108.1  476.86  5116.6  476.64  5152.7  477.45  5173.8  478.68  5231.0  480.07
  5252.1  481.53  5267.2  482.01  5303.3  484.97  5318.4  485.29  5330.3  486.44
#Mann=5,-1,0
  4643.7   0.075       0  4749.6    0.05       0  4868.6    0.12       0
  4967.3    0.07       0  4971.3    0.12       0
Bank Sta=4967.3,4971.3
Exp/Cntr=0.3,0.1

Type RM Length L Ch R = 1,1314,300,300,300
BEGIN DESCRIPTION:
Mapping XS 1aaa4e4e
END DESCRIPTION:
XS GIS Cut Line= 3
      2422692.85      7047827.55      2422492.32      7047858.80
      2422212.52      7048042.75
#Sta/Elev= 30
  4798.2  479.35  4822.3  478.44  4831.2  477.55  4847.1  475.38  4852.7  473.91
  4872.9  471.40  4883.1  470.76  4933.7  469.03  4943.8  469.66  4953.9  469.29
  4972.8  469.80  4977.8  469.33  4982.3  465.75  4982.5  465.25  4986.0  465.25
  4986.3  465.75  5000.3  467.56  5006.1  467.56  5011.8  469.12  5017.8  468.09
  5032.8  469.44  5063.0  469.61  5069.0  470.28  5129.2  472.51  5220.5  475.68
  5228.7  476.84  5249.8  477.02  5264.9  478.97  5270.8  478.90  5336.0  483.07
#Mann=5,-1,0
  4798.2    0.05       0  4831.2    0.12       0  4982.3    0.07       0
  4986.3    0.12       0  5129.2    0.05       0
Bank Sta=4982.3,4986.3
Exp/Cntr=0.3,0.1

Type RM Length L Ch R = 1,1014,299,299,299
BEGIN DESCRIPTION:
Mapping XS 39587541
END DESCRIPTION:
XS GIS Cut Line= 3
      2422776.16      7047681.72      2422385.55      7047600.99
      2422158.95      7047694.76
#Sta/Elev= 30
  4596.0  477.36  4629.0  477.21  4679.2  475.84  4724.4  475.71  4729.5  475.10
  4808.3  474.08  4858.6  472.98  4930.4  472.35  4951.7  467.73  4970.4  464.35
  4975.5  464.32  4979.1  462.41  4979.4  461.91  4982.9  461.91  4983.1  462.41
  5000.9  464.60  5013.9  465.31  5024.8  467.84  5030.3  470.74  5045.2  472.09
  5131.3  472.55  5136.7  474.18  5160.6  473.90  5166.0  476.92  5184.5  476.83
  5189.9  477.79  5196.8  477.92  5213.8  477.71  5219.2  478.54  5240.1  478.38
#Mann=7,-1,0
  4596.0    0.05       0  4808.3    0.12       0  4951.7    0.05       0
  4979.1    0.05       0  4983.1    0.05       0  5013.9    0.12       0
  5024.8    0.05       0
Bank Sta=4979.1,4983.1
Exp/Cntr=0.3,0.1

Type RM Length L Ch R = 1,715,0,0,0
BEGIN DESCRIPTION:
Denton Creek Tr 2 4.0
END DESCRIPTION:
XS GIS Cut Line= 3
      2423179.81      7047358.80      2422334.22      7047303.09
      2421975.32      7047555.85
#Sta/Elev= 30
  4190.4  477.87  4549.7  476.32  4562.0  475.33  4772.5  474.28  4868.8  474.72
  4952.9  472.12  4972.9  469.72  4982.9  467.40  4992.9  463.29  5003.0  461.01
  5021.0  460.45  5021.3  459.95  5025.0  460.45  5045.7  461.09  5054.4  464.72
  5060.5  465.48  5075.3  470.62  5087.6  471.37  5117.6  472.35  5197.3  470.97
  5203.4  471.69  5247.8  472.66  5283.7  472.56  5326.5  472.25  5354.9  471.97
  5362.2  472.70  5456.0  470.63  5470.8  470.81  5476.3  471.54  5476.8  471.61
#Mann=8,-1,0
  4190.4   0.075       0  4868.8    0.05       0  5021.0    0.05       0
  5025.0    0.05       0  5087.6   0.075       0  5283.7    0.05       0
  5326.5   0.075       0  5476.3    0.05       0
Bank Sta=5021,5025
Exp/Cntr=0.3,0.1

Chan Stop Cuts=-1