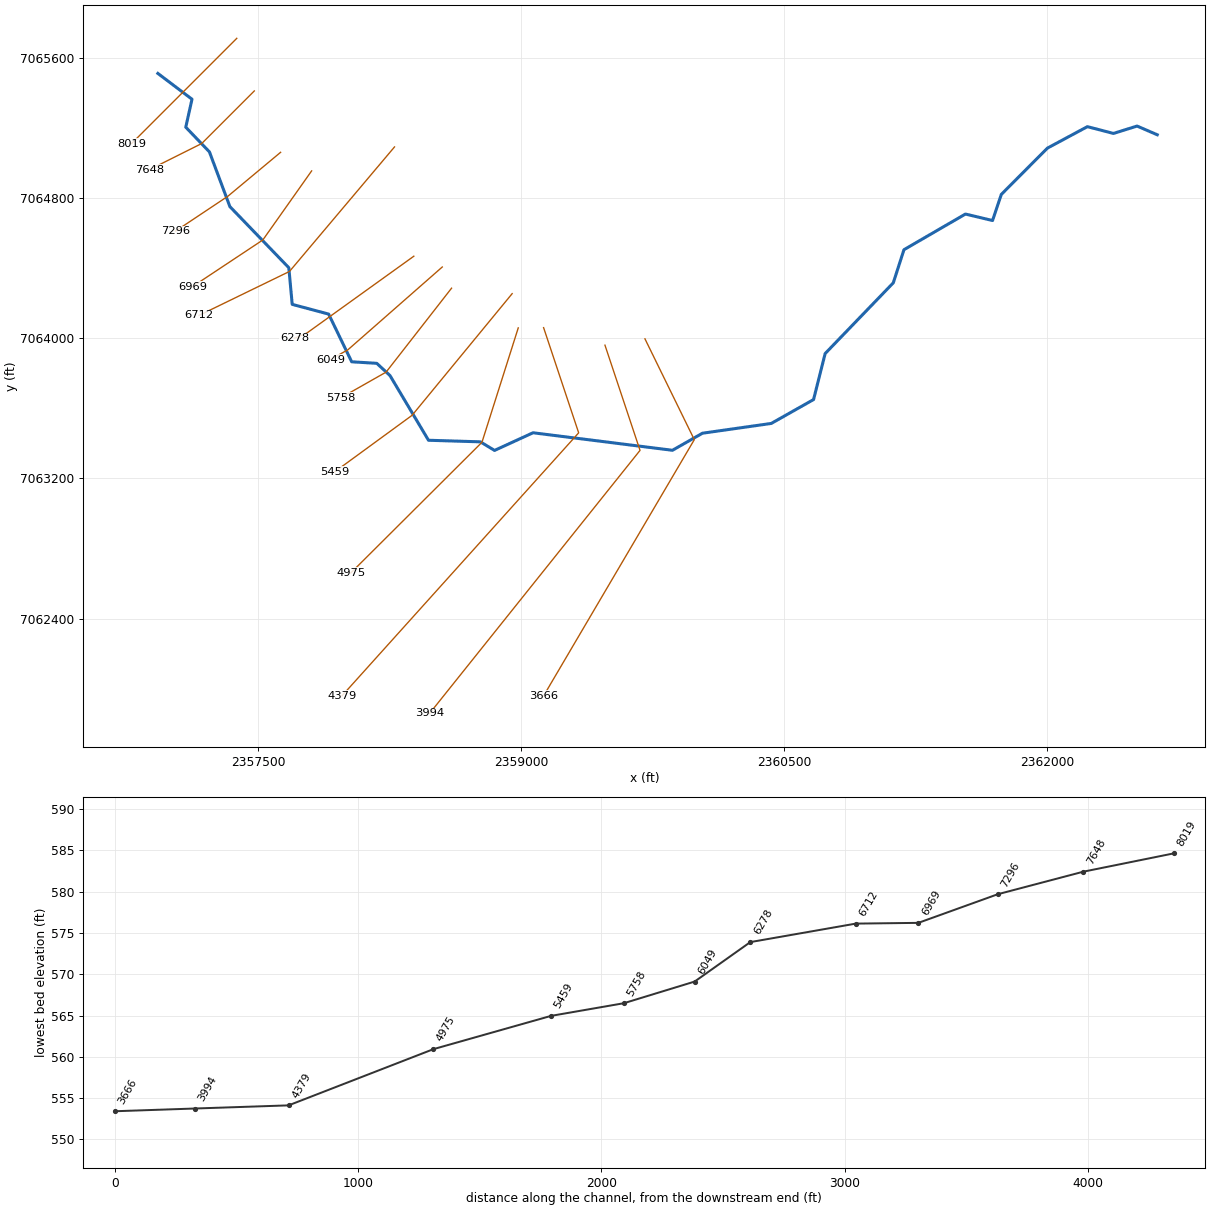
--- Denton Creek Tr 5.prj (project) ---

Proj Title=Denton Creek Tr 5 Base Level Engineering
Current Plan=p01
Default Exp/Contr=0.3,0.1
English Units
Geom File=g01
Flow File=f01
Plan File=p01
Y Axis Title=Elevation
X Axis Title(PF)=Main Channel Distance
X Axis Title(XS)=Station
BEGIN DESCRIPTION:
Denton Creek Tr 5
END DESCRIPTION:
DSS Export Rating Curves= 0
DSS Export Rating Curve Sorted= 0
DSS Export Volume Flow Curves= 0
DXF OffsetX= 0
DXF OffsetY= 0
DXF ScaleX= 1
DXF ScaleY= 10

--- Denton Creek Tr 5.p01 (plan) ---

Plan Title=Multiple Run
Short Identifier=Multiple
Geom File=g01
Flow File=f01
Subcritical Flow
K Sum by GR= 0
Std Step Tol= 0.01
Critical Tol= 0.01
Num of Std Step Trials= 20
Max Error Tol= 0.3
Flow Tol Ratio= 0.001
Split Flow NTrial= 30
Split Flow Tol= 0.02
Split Flow Ratio= 0.02
Log Output Level= 0
Friction Slope Method= 1
Unsteady Friction Slope Method= 2
Unsteady Bridges Friction Slope Method= 1
Parabolic Critical Depth
Global Vel Dist=  1 , 1 , 1
Global Log Level= 0
CheckData=True
Encroach Param= -1, 0, 0, 0
BEGIN DESCRIPTION:
Multiple Run
END DESCRIPTION:

--- Denton Creek Tr 5.f01 (steady flow) ---

Flow Title=Multiple
Number of Profiles=7
Profile Names=10-year,25-year,50-year,1pct_min,100-year,1pct_plu,500-year
River Rch & RM= Denton Creek Tr ,Reach-1,8019
     514     696     845     510    1017    2029    1476
River Rch & RM= Denton Creek Tr ,Reach-1,4975
     564     767     934     565    1127    2248    1643
Boundary for River Rch & Prof#=Denton Creek Tr ,Reach-1,1
Up Type=0
Dn Type=3
Dn Slope=0.005
Boundary for River Rch & Prof#=Denton Creek Tr ,Reach-1,2
Up Type=0
Dn Type=3
Dn Slope=0.005
Boundary for River Rch & Prof#=Denton Creek Tr ,Reach-1,3
Up Type=0
Dn Type=3
Dn Slope=0.005
Boundary for River Rch & Prof#=Denton Creek Tr ,Reach-1,4
Up Type=0
Dn Type=3
Dn Slope=0.005
Boundary for River Rch & Prof#=Denton Creek Tr ,Reach-1,5
Up Type=0
Dn Type=3
Dn Slope=0.005
Boundary for River Rch & Prof#=Denton Creek Tr ,Reach-1,6
Up Type=0
Dn Type=3
Dn Slope=0.005
Boundary for River Rch & Prof#=Denton Creek Tr ,Reach-1,7
Up Type=0
Dn Type=3
Dn Slope=0.005

--- Denton Creek Tr 5.g01 (geometry) ---

Geom Title=Existing Conditions
Program Version=4.10

River Reach=Denton Creek Tr ,Reach-1
Reach XY= 30
        2356929.        7065510.       2357123.7      7065362.67
      2357088.13      7065203.26      2357223.17       7065062.3
      2357339.76      7064750.32      2357675.91      7064401.69
      2357695.24      7064192.77      2357903.02      7064137.34
      2358034.44      7063865.19      2358177.54      7063856.46
      2358252.74      7063786.89      2358472.52      7063417.69
       2358768.5      7063408.76      2358849.18      7063359.71
      2359068.81      7063460.46      2359863.79      7063360.51
      2360034.93      7063457.76       2360427.5      7063513.62
      2360668.67      7063649.83      2360734.83       7063912.3
      2361123.41      7064315.61      2361184.26      7064504.53
      2361534.97      7064707.85      2361689.43      7064670.94
      2361739.52      7064819.78      2362002.18      7065083.71
      2362230.59      7065206.32        2362379.      7065167.57
      2362513.75      7065209.69        2362629.        7065160.

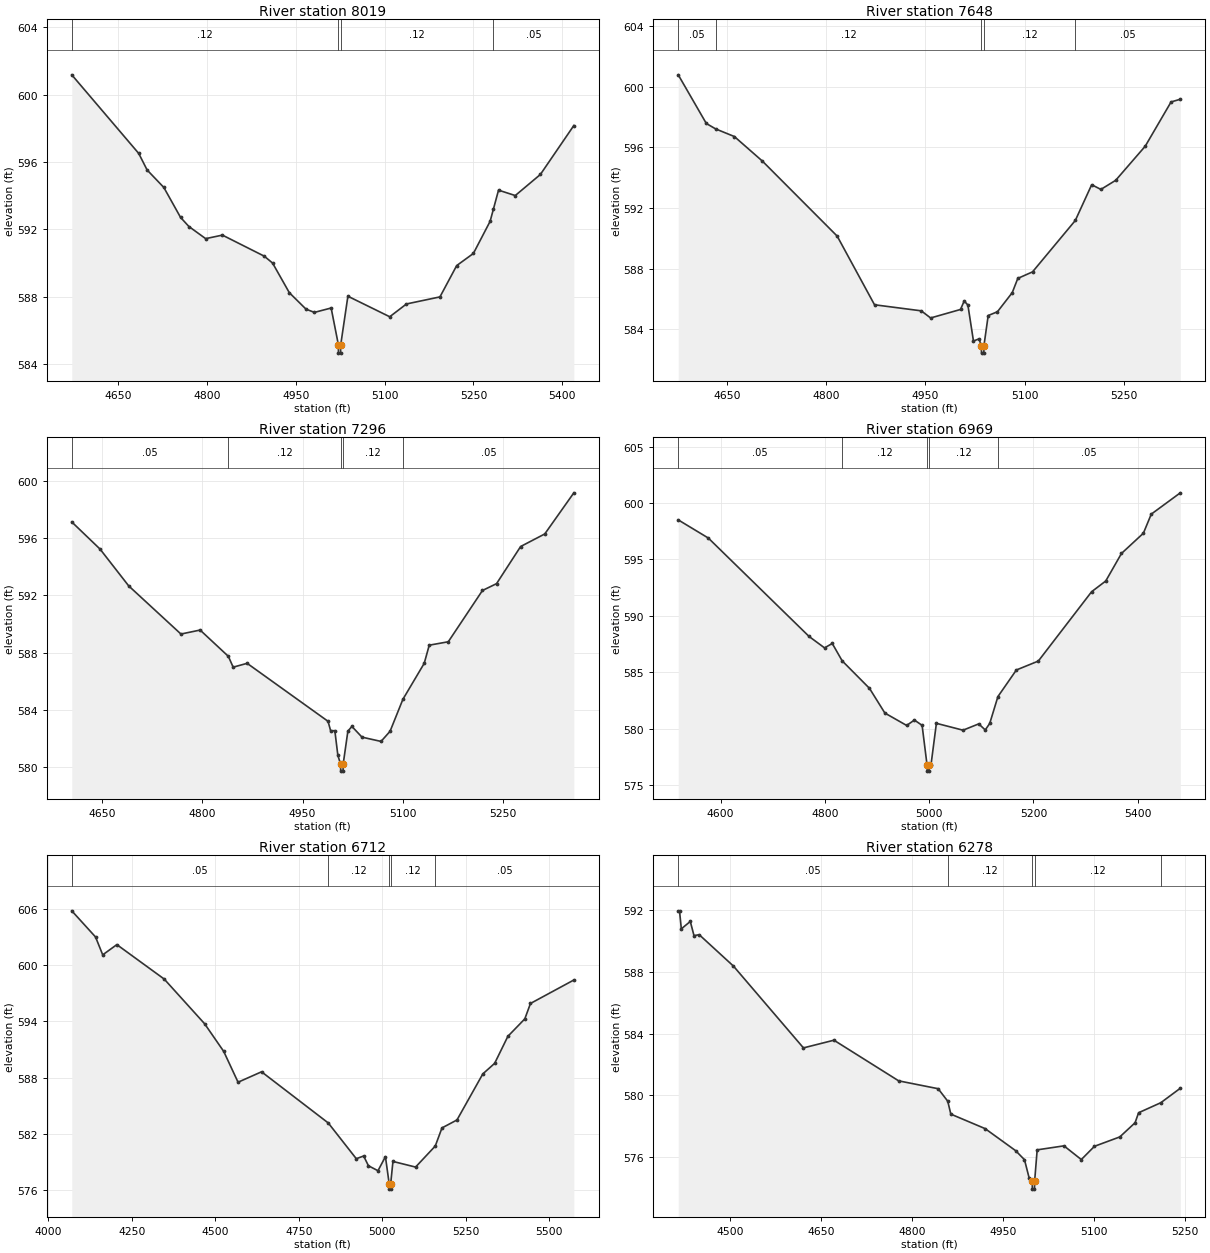
Type RM Length L Ch R = 1 ,8019    ,371,371,371
BEGIN DESCRIPTION:
Denton Creek Tr 5 19.0
END DESCRIPTION:
XS GIS Cut Line= 3
      2357379.02      7065710.02        2357079.        7065410.
      2356778.97      7065109.97
#Sta/Elev= 30
  4571.1  601.17  4684.3   596.5  4698.4  595.52  4726.7  594.48    4755   592.7
  4769.1  592.16  4797.4  591.44  4825.7  591.65  4896.4   590.4  4910.5  589.99
  4938.8  588.23  4967.1  587.25  4981.2  587.06  5009.5  587.32  5021.7  585.14
  5021.9  584.64  5025.4  584.64  5025.7  585.14  5037.8  588.02  5108.5   586.8
  5136.8  587.56  5193.4  587.98  5221.7  589.84  5249.9  590.56  5278.2  592.47
  5283.8   593.2  5292.4  594.32  5320.7     594  5363.1  595.25  5419.7  598.16
#Mann= 4 ,-1 , 0
  4571.1     .12       0  5021.7     .07       0  5025.7     .12       0
  5283.8     .05       0
Bank Sta=5021.7,5025.7
XS Rating Curve= 0 ,0
Exp/Cntr=0.3,0.1

Type RM Length L Ch R = 1 ,7648    ,352,352,352
BEGIN DESCRIPTION:
Denton Creek Tr 5 18.0
END DESCRIPTION:
XS GIS Cut Line= 3
      2357479.03      7065410.03        2357179.        7065110.
      2356879.02      7064960.01
#Sta/Elev= 30
  4575.9  600.79  4618.4  597.58  4632.6  597.22  4660.8  596.72  4703.2   595.1
  4816.4  590.15  4872.9  585.62  4943.6  585.22  4957.8  584.75    5003  585.31
  5008.6  585.87  5014.2   585.6  5022.6  583.23    5031  583.37  5034.5  582.93
  5034.8  582.43  5038.3  582.43  5038.5  582.93  5044.9  584.91  5058.9  585.16
  5081.3  586.42  5089.7  587.36    5112  587.79  5176.7  591.18  5201.5  593.54
  5215.4  593.23  5237.8  593.83  5282.5  596.08  5321.6     599  5335.6  599.18
#Mann= 5 ,-1 , 0
  4575.9     .05       0  4632.6     .12       0  5034.5     .07       0
  5038.5     .12       0  5176.7     .05       0
Bank Sta=5034.5,5038.5
XS Rating Curve= 0 ,0
Exp/Cntr=0.3,0.1

Type RM Length L Ch R = 1 ,7296    ,327,327,327
BEGIN DESCRIPTION:
Denton Creek Tr 5 17.0
END DESCRIPTION:
XS GIS Cut Line= 3
      2357628.98      7065059.98        2357329.        7064810.
      2357029.03      7064610.02
#Sta/Elev= 30
  4604.8  597.15  4647.1  595.25    4690  592.67  4768.1   589.3  4796.8  589.58
    4839  587.74  4846.2  586.98  4867.1  587.25  4988.1  583.19    4992  582.53
  4998.3  582.53  5002.8  580.81  5006.8   580.2  5007.1   579.7  5010.6   579.7
  5010.8   580.2  5017.8   582.5  5023.8  582.83  5038.9  582.08  5067.4  581.78
  5080.9  582.49  5100.1  584.73    5132  587.25  5139.5  588.52    5168  588.76
  5219.1  592.35  5240.2  592.83  5276.2  595.43  5312.3  596.31  5355.8  599.19
#Mann= 5 ,-1 , 0
  4604.8     .05       0    4839     .12       0  5006.8     .07       0
  5010.8     .12       0  5100.1     .05       0
Bank Sta=5006.8,5010.8
XS Rating Curve= 0 ,0
Exp/Cntr=0.3,0.1

Type RM Length L Ch R = 1 ,6969    ,257,257,257
BEGIN DESCRIPTION:
Denton Creek Tr 5 16.0
END DESCRIPTION:
XS GIS Cut Line= 3
      2357806.02      7064953.97       2357527.7        7064560.
      2357127.22      7064294.42
#Sta/Elev= 30
  4518.8  598.51  4576.5   596.9  4769.8  588.17  4799.4  587.16  4814.2  587.55
  4833.2  586.01  4885.6  583.57  4915.1  581.38  4956.9  580.28  4971.7  580.76
  4986.5  580.29  4996.1  576.73  4996.4  576.23  4999.9  576.23  5000.1  576.73
  5003.4  576.73  5013.9  580.47    5065  579.86  5095.1  580.42  5107.6  579.88
  5116.2  580.46  5131.9  582.84  5167.3   585.2  5209.4  585.99  5311.6  592.14
  5338.7  593.09  5368.8  595.53  5410.9  597.33    5426  599.02  5481.7  600.91
#Mann= 5 ,-1 , 0
  4518.8     .05       0  4833.2     .12       0  4996.1     .07       0
  5000.1     .12       0  5131.9     .05       0
Bank Sta=4996.1,5000.1
XS Rating Curve= 0 ,0
Exp/Cntr=0.3,0.1

Type RM Length L Ch R = 1 ,6712    ,434,434,434
BEGIN DESCRIPTION:
Denton Creek Tr 5 15.0
END DESCRIPTION:
XS GIS Cut Line= 3
      2358278.72      7065090.76      2357679.53      7064380.43
      2357164.14       7064129.8
#Sta/Elev= 30
  4070.7  605.79  4141.9     603  4163.3   601.1  4205.6  602.19  4347.3  598.52
  4468.2  593.76  4525.4  590.81  4568.3  587.53  4638.6  588.64  4838.2  583.19
  4922.1  579.38  4944.1  579.67  4958.4  578.63    4987   578.1  5009.3   579.6
  5020.8  576.64  5021.1  576.14  5024.6  576.14  5024.8  576.64  5031.8  579.09
  5099.5  578.49  5158.4  580.73  5178.5  582.66  5223.4  583.51  5300.8  588.42
  5336.1  589.54  5375.7  592.42  5426.4  594.28  5443.3  595.92  5573.1  598.42
#Mann= 5 ,-1 , 0
  4070.7     .05       0  4838.2     .12       0  5020.8     .07       0
  5024.8     .12       0  5158.4     .05       0
Bank Sta=5020.8,5024.8
XS Rating Curve= 0 ,0
Exp/Cntr=0.3,0.1

Type RM Length L Ch R = 1 ,6278    ,229,229,229
BEGIN DESCRIPTION:
Denton Creek Tr 5 14.0
END DESCRIPTION:
XS GIS Cut Line= 3
      2358388.93      7064467.44      2357779.27      7064029.45
      2357707.85      7063999.57
#Sta/Elev= 30
  4414.9  591.97    4417  591.97    4420   590.8  4434.8  591.28  4440.9  590.36
  4449.5  590.42    4506  588.38  4621.4  583.07  4671.7  583.57  4778.5  580.93
  4843.6  580.42  4859.4  579.61  4864.5  578.77    4921  577.83  4971.3   576.4
    4986  575.81  4993.5  574.65  4998.7   574.4    4999   573.9  5002.5   573.9
  5002.7   574.4  5006.9  576.45  5051.1  576.71  5079.7  575.82  5101.4  576.68
  5143.2  577.29  5168.4  578.21  5174.2  578.86  5210.8  579.51    5243  580.45
#Mann= 5 ,-1 , 0
  4414.9     .05       0  4859.4     .12       0  4998.7     .07       0
  5002.7     .12       0  5210.8     .05       0
Bank Sta=4998.7,5002.7
XS Rating Curve= 0 ,0
Exp/Cntr=0.3,0.1

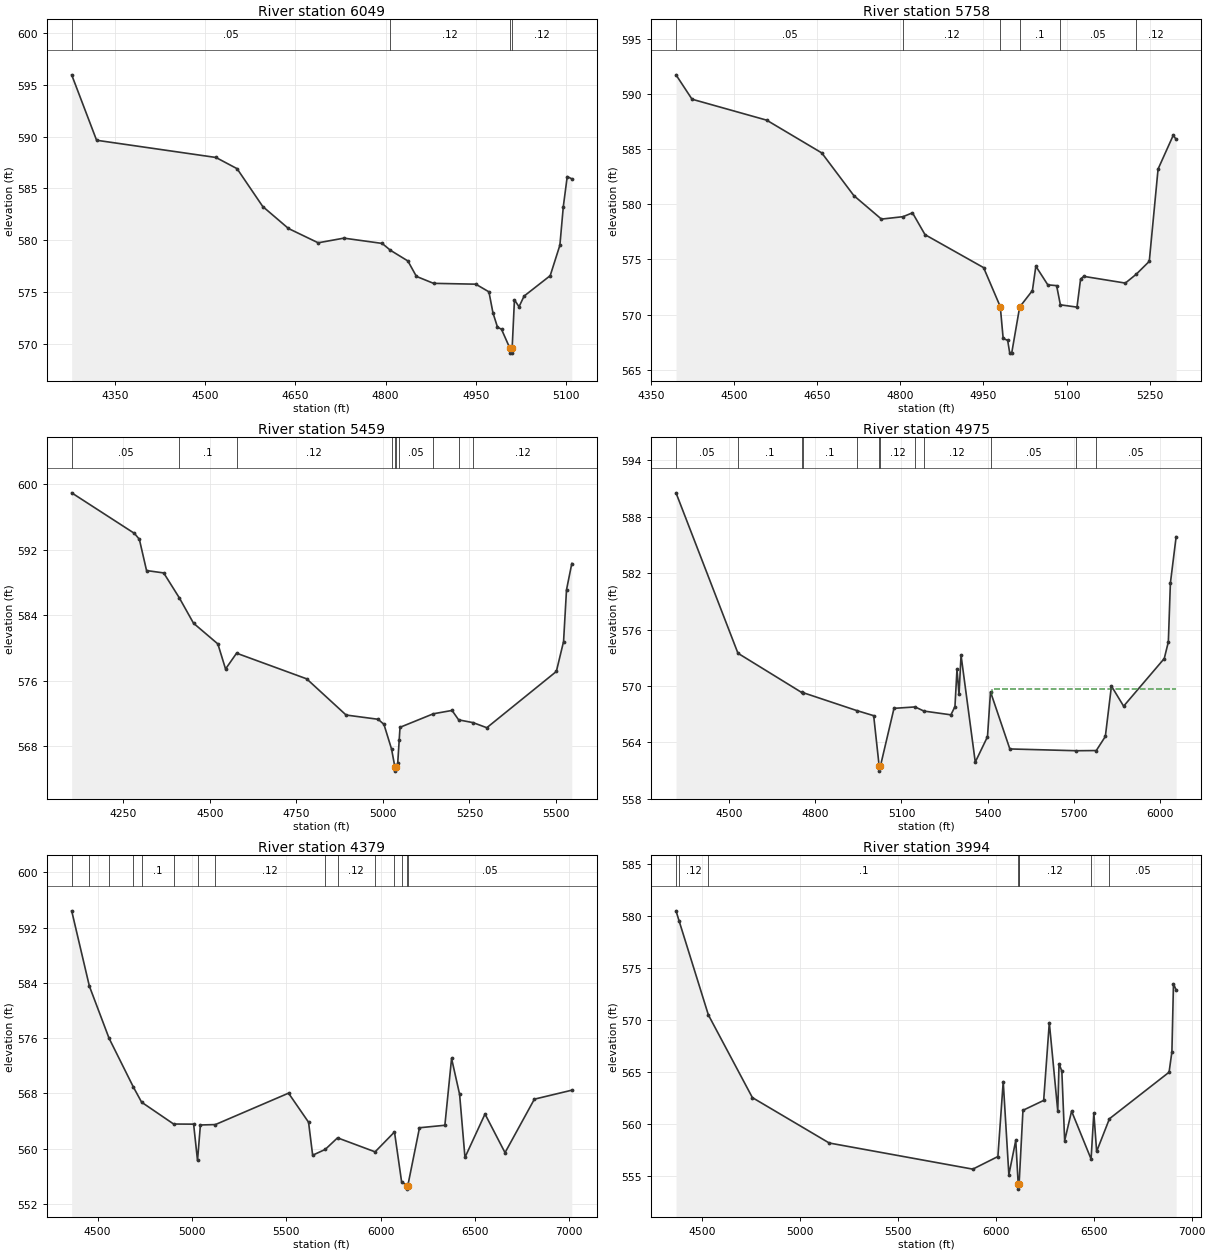
Type RM Length L Ch R = 1 ,6049    ,291,291,291
BEGIN DESCRIPTION:
Mapping XS abf9f125
END DESCRIPTION:
XS GIS Cut Line= 3
      2358551.04      7064405.85      2358012.81       7063933.6
      2357912.31      7063877.77
#Sta/Elev= 30
  4278.5  595.96  4319.9  589.65  4518.2  587.99  4553.3  586.91    4596  583.26
  4638.7  581.14  4688.1  579.76  4730.8  580.21  4794.4   579.7  4808.1  579.04
  4837.1  578.01  4851.3  576.52  4879.8  575.85    4950  575.77  4971.8  575.03
  4978.5     573    4986  571.63  4992.7  571.42  5006.4  569.62  5006.7  569.12
  5010.2  569.12  5010.4  569.62  5014.2  574.26  5021.8  573.59  5030.2  574.62
  5073.6  576.59  5089.7  579.53  5095.4  583.26  5101.9  586.15  5109.5  585.93
#Mann= 4 ,-1 , 0
  4278.5     .05       0  4808.1     .12       0  5006.4     .07       0
  5010.4     .12       0
Bank Sta=5006.4,5010.4
XS Rating Curve= 0 ,0
Exp/Cntr=0.3,0.1

Type RM Length L Ch R = 1 ,5758    ,299,299,299
BEGIN DESCRIPTION:
Denton Creek Tr 5 13.0
END DESCRIPTION:
XS GIS Cut Line= 3
      2358603.99      7064284.98      2358230.69      7063806.29
      2357973.26      7063660.26
#Sta/Elev= 30
  4394.9  591.73  4423.8  589.52  4558.6  587.62  4658.1  584.65    4716  580.78
  4765.8  578.65  4804.8  578.87  4821.9  579.22  4844.5  577.24  4950.3  574.25
  4980.4  570.71  4985.6  567.83  4993.7  567.66  4997.5   566.5    5001   566.5
  5015.4  570.68  5038.4  572.17  5044.6  574.38  5066.2  572.69  5082.1  572.62
  5088.9  570.88  5118.9  570.67  5125.4  573.22  5131.1  573.46  5206.2  572.85
  5225.6  573.64  5249.4  574.82  5265.3  583.19  5292.7  586.25  5297.9  585.88
#Mann= 6 ,-1 , 0
  4394.9     .05       0  4804.8     .12       0  4980.4     .07       0
  5015.4      .1       0  5088.9     .05       0  5225.6     .12       0
Bank Sta=4980.4,5015.4
XS Rating Curve= 0 ,0
Exp/Cntr=0.3,0.1

Type RM Length L Ch R = 1 ,5459    ,484,484,484
BEGIN DESCRIPTION:
Denton Creek Tr 5 12.0
END DESCRIPTION:
XS GIS Cut Line= 3
      2358949.73      7064253.96        2358379.        7063560.
      2357938.45      7063238.32
#Sta/Elev= 30
  4101.5  598.95  4282.6     594  4296.9  593.28  4317.7  589.46  4367.2  589.17
  4412.4  586.12  4453.3  583.03  4523.6   580.5  4545.8  577.44  4577.6  579.37
  4779.9  576.24  4893.8  571.82  4986.4   571.3  5003.1  570.68  5025.1  567.66
  5034.7  565.47  5034.9  564.97  5038.7  565.47  5042.9  565.95  5047.1  568.73
  5049.5  570.32  5145.6  571.97  5199.7  572.38  5218.8  571.23  5260.6  570.89
  5300.1  570.27  5500.9  577.14  5521.7  580.79  5530.2  587.11  5545.5  590.32
#Mann= 10 ,-1 , 0
  4101.5     .05       0  4412.4      .1       0  4577.6     .12       0
  5025.1      .1       0  5034.7     .07       0  5038.7      .1       0
  5047.1     .05       0  5145.6      .1       0  5218.8     .05       0
  5260.6     .12       0
Bank Sta=5034.7,5038.7
XS Rating Curve= 0 ,0
Exp/Cntr=0.3,0.1

Type RM Length L Ch R = 1 ,4975    ,596,596,596
BEGIN DESCRIPTION:
Denton Creek Tr 5 11.0
END DESCRIPTION:
XS GIS Cut Line= 3
      2358984.44      7064058.64      2358777.45      7063406.19
      2358029.59      7062661.06
#Sta/Elev= 30
  4315.5  590.55  4531.1  573.48  4752.2  569.32  4757.5  569.29  4943.8  567.39
  5003.3  566.84  5022.5  561.44  5022.8  560.94  5026.5  561.44    5074  567.62
  5147.3  567.77  5178.2  567.33    5272  566.93  5286.1   567.8  5293.2  571.77
  5300.3  569.11  5307.3  573.27  5356.8   561.9  5399.3   564.6  5409.8  569.38
  5477.1   563.3  5708.2  563.11  5777.9  563.13  5809.4  564.63  5830.6  569.99
    5873  567.85  6014.4  572.92  6028.6  574.69  6035.7  580.94  6055.7  585.88
#Mann= 12 ,-1 , 0
  4315.5     .05       0  4531.1      .1       0  4752.2     .12       0
  4757.5      .1       0  4943.8     .12       0  5022.5     .07       0
  5026.5     .12       0  5147.3     .05       0  5178.2     .12       0
  5409.8     .05       0  5708.2     .12       0  5777.9     .05       0
#XS Ineff= 2 , 0
       0                  5413.4       0  569.65
Permanent Ineff=
       F       F
Bank Sta=5022.5,5026.5
XS Rating Curve= 0 ,0
Exp/Cntr=0.3,0.1

Type RM Length L Ch R = 1 ,4379    ,385,385,385
BEGIN DESCRIPTION:
Denton Creek Tr 5 9.0
END DESCRIPTION:
XS GIS Cut Line= 3
        2359129.      7064060.01        2359329.        7063460.
      2357979.01      7061960.01
#Sta/Elev= 30
  4363.1  594.44  4456.8  583.54  4561.3  575.98  4689.8  568.93  4733.8  566.72
  4903.4  563.56  5009.4  563.54    5030  558.28  5045.3  563.42  5124.7  563.48
  5512.4  568.03  5618.5  563.82  5640.2  559.04  5706.8  559.88  5772.1  561.56
  5971.2  559.53  6073.9  562.41  6111.5  555.21  6140.5  554.63  6140.7  554.13
  6144.5  554.63  6206.4  563.02  6340.9  563.38  6376.4  573.06    6419  567.86
  6447.4  558.72  6553.6  565.01  6659.7  559.41  6815.2  567.16  7013.6  568.46
#Mann= 15 ,-1 , 0
  4363.1     .05       0  4456.8     .12       0  4561.3      .1       0
  4689.8     .12       0  4733.8      .1       0  4903.4     .12       0
    5030      .1       0  5124.7     .12       0  5706.8      .1       0
  5772.1     .12       0  5971.2      .1       0  6073.9     .12       0
  6111.5     .05       0  6140.5     .07       0  6144.5     .05       0
Bank Sta=6140.5,6144.5
XS Rating Curve= 0 ,0
Exp/Cntr=0.3,0.1

Type RM Length L Ch R = 1 ,3994    ,328,328,328
BEGIN DESCRIPTION:
Denton Creek Tr 5 8.0
END DESCRIPTION:
XS GIS Cut Line= 3
      2359478.99      7063960.03        2359679.        7063360.
      2358479.02      7061860.02
#Sta/Elev= 30
  4367.4  580.48  4383.4   579.5  4532.7  570.48  4757.4  562.54  5149.6  558.18
  5882.7  555.67  6010.8  556.88    6038  564.08  6066.8  555.13    6102  558.43
  6114.4  554.25  6114.7  553.75  6118.4  554.25  6119.1  554.26  6138.8  561.32
  6244.5  562.27  6273.3  569.74  6316.5  561.25  6322.9   565.8  6337.3  565.08
  6351.7   558.4    6387  561.24  6486.6  556.64  6500.6  561.06    6515  557.37
  6580.3  560.51  6884.8  564.98  6899.2  566.94  6907.2  573.48  6920.8  572.87
#Mann= 8 ,-1 , 0
  4367.4     .05       0  4383.4     .12       0  4532.7      .1       0
  6114.4     .07       0  6118.4      .1       0  6119.1     .12       0
  6486.6      .1       0  6580.3     .05       0
Bank Sta=6114.4,6118.4
XS Rating Curve= 0 ,0
Exp/Cntr=0.3,0.1

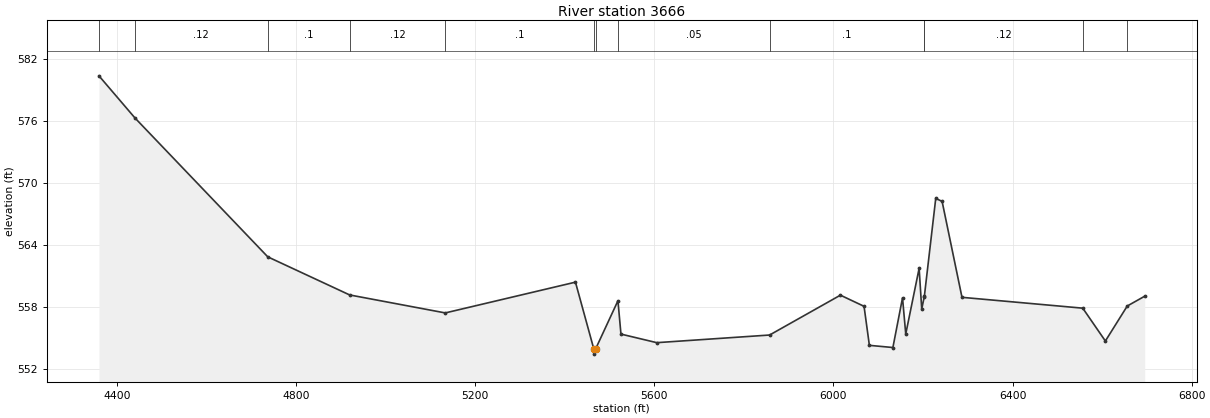
Type RM Length L Ch R = 1 ,3666    ,0,0,0
BEGIN DESCRIPTION:
Denton Creek Tr 5 7.0
END DESCRIPTION:
XS GIS Cut Line= 3
      2359707.06      7063996.15      2359988.53      7063421.14
        2359129.        7061960.
#Sta/Elev= 30
  4359.8  580.37  4440.2  576.29  4736.8  562.84  4919.7  559.15  5133.2  557.41
  5423.9  560.39  5464.9  553.92  5465.1  553.42  5468.9  553.92  5518.8  558.59
  5525.5  555.36  5605.5  554.53  5857.5  555.27  6015.6  559.13  6068.4  558.05
  6080.3  554.27  6132.8  554.06  6154.3  558.87  6161.5  555.37  6191.4  561.73
  6197.2  557.78  6202.8  558.97  6203.1  559.03  6228.5   568.5  6242.7  568.21
  6287.1  558.92  6556.8  557.87  6607.3  554.69  6656.2  558.08  6695.2  559.03
#Mann= 13 ,-1 , 0
  4359.8     .05       0  4440.2     .12       0  4736.8      .1       0
  4919.7     .12       0  5133.2      .1       0  5464.9     .07       0
  5468.9      .1       0  5518.8     .05       0  5857.5      .1       0
  6202.8     .05       0  6203.1     .12       0  6556.8      .1       0
  6656.2     .05       0
Bank Sta=5464.9,5468.9
XS Rating Curve= 0 ,0
Exp/Cntr=0.3,0.1

Chan Stop Cuts=-1
Use User Specified Reach Order=0
Composite Channel Slope=5