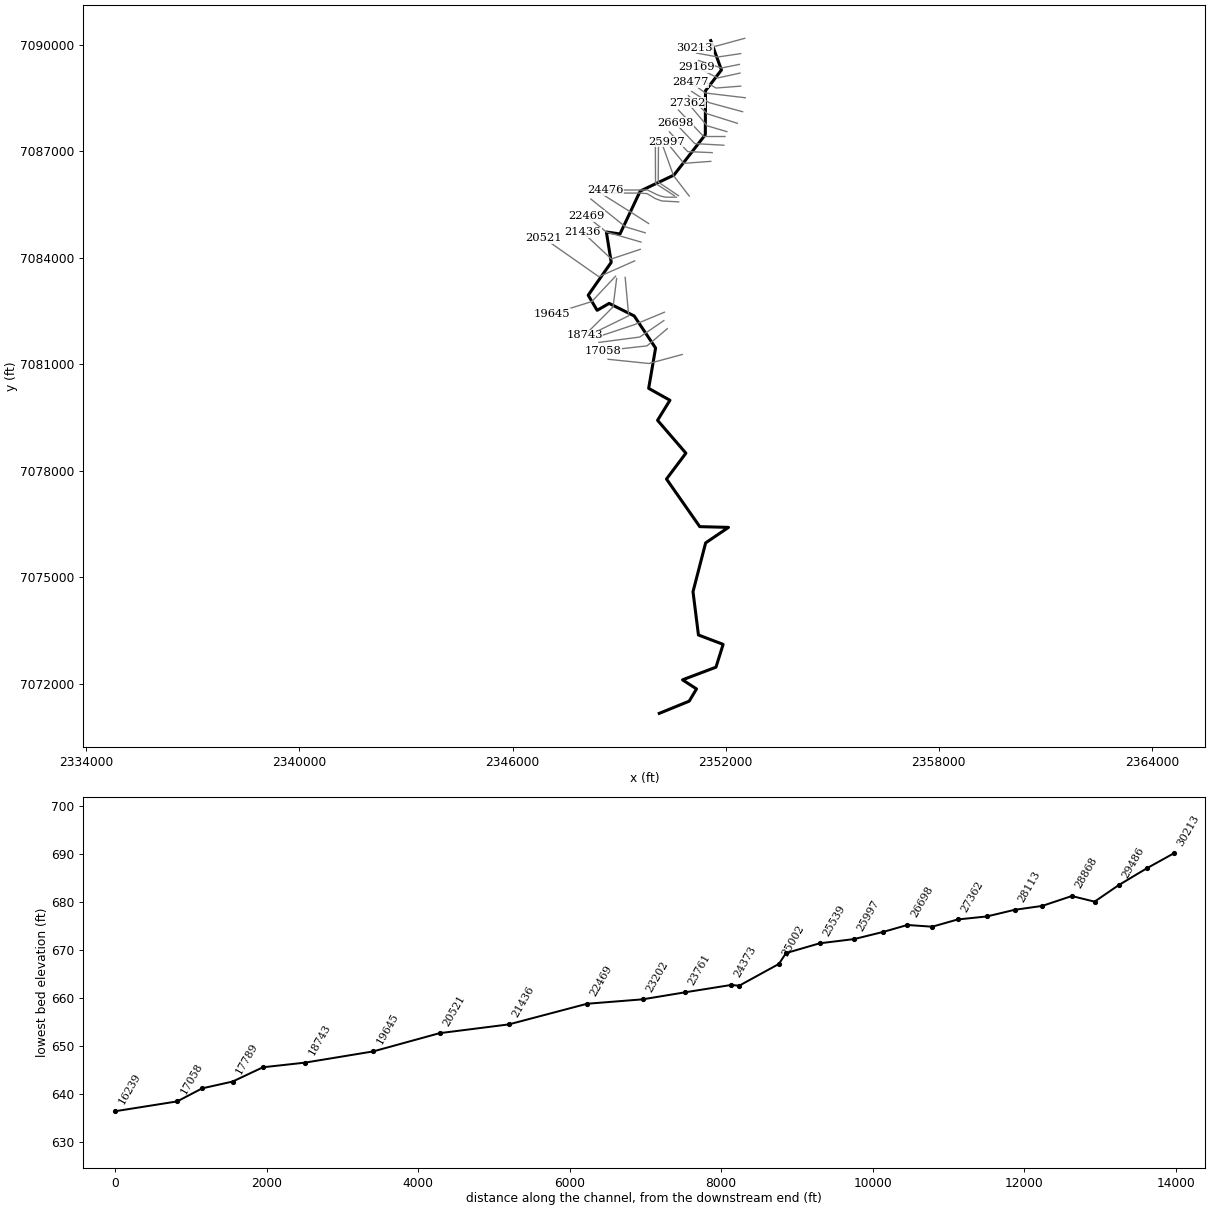
--- Denton Creek Tr 7.prj (project) ---

Proj Title=Denton Creek Tr 7 Base Level Engineering
Current Plan=p01
Default Exp/Contr=0.3,0.1
English Units
Geom File=g01
Flow File=f01
Plan File=p01
Y Axis Title=Elevation
X Axis Title(PF)=Main Channel Distance
X Axis Title(XS)=Station
BEGIN DESCRIPTION:
Denton Creek Tr 7
END DESCRIPTION:
DSS Export Rating Curves= 0
DSS Export Rating Curve Sorted= 0
DSS Export Volume Flow Curves= 0
DXF OffsetX= 0
DXF OffsetY= 0
DXF ScaleX= 1
DXF ScaleY= 10

--- Denton Creek Tr 7.p01 (plan) ---

Plan Title=Multiple Run
Short Identifier=Multiple
Geom File=g01
Flow File=f01
Subcritical Flow
K Sum by GR= 0
Std Step Tol= 0.01
Critical Tol= 0.01
Num of Std Step Trials= 20
Max Error Tol= 0.3
Flow Tol Ratio= 0.001
Split Flow NTrial= 30
Split Flow Tol= 0.02
Split Flow Ratio= 0.02
Log Output Level= 0
Friction Slope Method= 1
Unsteady Friction Slope Method= 2
Unsteady Bridges Friction Slope Method= 1
Parabolic Critical Depth
Global Vel Dist=  1 , 1 , 1
Global Log Level= 0
CheckData=True
Encroach Param= -1, 0, 0, 0
BEGIN DESCRIPTION:
Multiple Run
END DESCRIPTION:

--- Denton Creek Tr 7.f01 (steady flow) ---

Flow Title=Multiple
Program Version=4.10
Number of Profiles= 7
Profile Names=10-year,25-year,50-year,1pct_min,100-year,1pct_plu,500-year
River Rch & RM=Denton Creek Tr,Reach-1         ,30213
     554     753     916     553    1104    2203    1607
River Rch & RM=Denton Creek Tr,Reach-1         ,25539
     660     907    1111     675    1347    2688    1987
River Rch & RM=Denton Creek Tr,Reach-1         ,24476
     816    1132    1395     853    1702    3395    2538
River Rch & RM=Denton Creek Tr,Reach-1         ,21436
     891    1240    1530     936    1868    3726    2790
River Rch & RM=Denton Creek Tr,Reach-1         ,17789
    1037    1454    1805    1109    2213    4415    3338
River Rch & RM=Denton Creek Tr,Reach-1         ,14734
    1167    1645    2049    1263    2521    5029    3829
River Rch & RM=Denton Creek Tr,Reach-1         ,14125
    1295    1836    2294    1419    2832    5650    4329
River Rch & RM=Denton Creek Tr,Reach-1         ,10063
    1461    2075    2597    1609    3210    6404    4918
River Rch & RM=Denton Creek Tr,Reach-1         ,7972
    1518    2160    2708    1679    3350    6684    5144
River Rch & RM=Denton Creek Tr,Reach-1         ,6867
    1624    2317    2910    1808    3607    7197    5560
River Rch & RM=Denton Creek Tr,Reach-1         ,5068
    1728    2472    3110    1934    3860    7701    5965
River Rch & RM=Denton Creek Tr,Reach-1         ,669
    1797    2574    3242    2019    4028    8038    6239
Boundary for River Rch & Prof#=Denton Creek Tr,Reach-1         , 1
Up Type= 0
Dn Type= 3
Dn Slope=0.005
Boundary for River Rch & Prof#=Denton Creek Tr,Reach-1         , 2
Up Type= 0
Dn Type= 3
Dn Slope=0.005
Boundary for River Rch & Prof#=Denton Creek Tr,Reach-1         , 3
Up Type= 0
Dn Type= 3
Dn Slope=0.005
Boundary for River Rch & Prof#=Denton Creek Tr,Reach-1         , 4
Up Type= 0
Dn Type= 3
Dn Slope=0.005
Boundary for River Rch & Prof#=Denton Creek Tr,Reach-1         , 5
Up Type= 0
Dn Type= 3
Dn Slope=0.005
Boundary for River Rch & Prof#=Denton Creek Tr,Reach-1         , 6
Up Type= 0
Dn Type= 3
Dn Slope=0.005
Boundary for River Rch & Prof#=Denton Creek Tr,Reach-1         , 7
Up Type= 0
Dn Type= 3
Dn Slope=0.005
DSS Import GetInterval= 0
DSS Import GetPeak= 0
DSS Import FillOption= 0

--- Denton Creek Tr 7.g01 (geometry) ---

Geom Title=Existing Conditions
Program Version=4.10

River Reach=Denton Creek Tr ,Reach-1
Reach XY= 30
        2351579.        7090110.       2351879.5      7089284.97
      2351430.36      7088698.46      2351425.46      7087461.46
      2350542.32      7086323.37      2349592.62      7085873.22
      2349023.39      7084664.77      2348640.09      7084720.09
      2348777.03      7083865.64      2348128.63       7082939.8
       2348380.5      7082513.46      2348718.52      7082709.07
        2349424.        7082355.      2350025.65       7081451.9
      2349830.88      7080315.69      2350429.48      7079980.14
      2350080.96      7079415.65      2350878.95       7078489.8
      2350332.47       7077761.5      2351268.88      7076420.34
      2352078.07      7076399.52      2351434.71      7075962.59
      2351079.01      7074587.24      2351232.22      7073367.99
      2351926.84      7073104.02      2351725.47      7072461.45
      2350783.89       7072104.9      2351178.02      7071848.31
      2350971.19      7071503.81        2350129.        7071160.

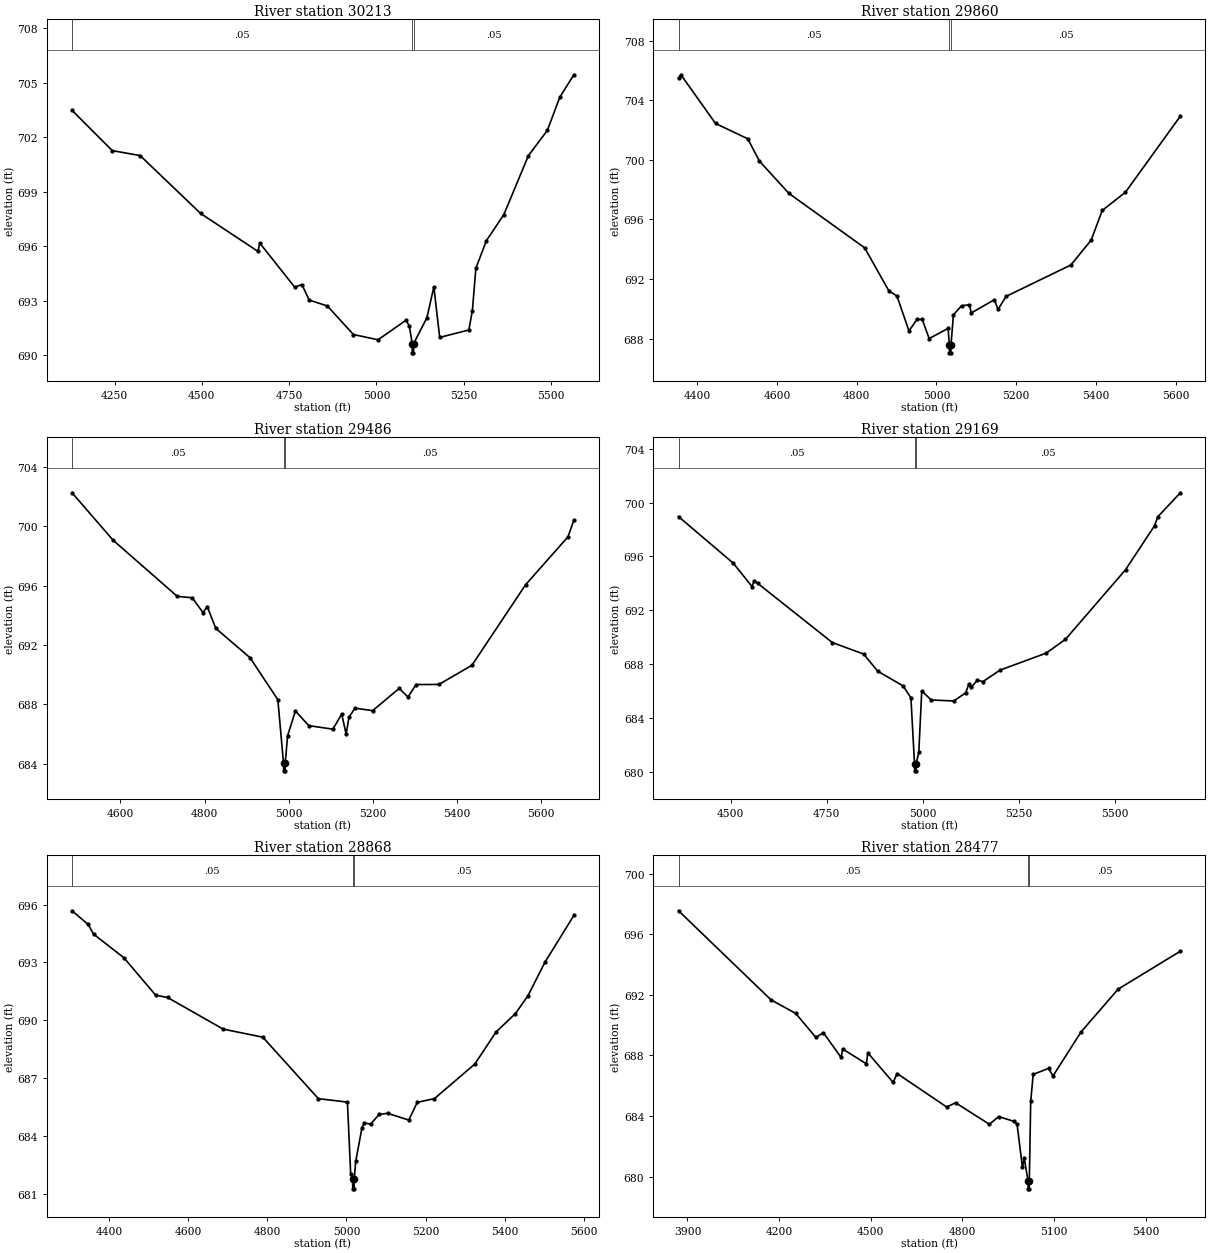
Type RM Length L Ch R = 1 ,30213   ,353,353,353
BEGIN DESCRIPTION:
Denton Creek Tr 7 56.0
END DESCRIPTION:
XS GIS Cut Line= 3
       2352534.2      7090175.44      2351692.98      7089946.94
      2351128.99        7089910.
#Sta/Elev= 30
  4128.3  703.49  4243.5  701.27  4323.1     701  4496.4  697.81  4660.5  695.72
  4665.7  696.18  4765.8  693.75  4786.5  693.89  4807.2  693.04  4859.5  692.71
  4933.9  691.14  5004.5  690.85  5084.2  691.92  5094.2  691.61  5102.2  690.63
  5102.5  690.13    5106  690.13  5106.2  690.63  5144.3  692.06  5164.3  693.76
    5181  690.98  5264.5  691.39  5274.6  692.46  5284.6  694.79  5314.7  696.31
  5364.8  697.75  5434.9  700.99  5489.4  702.39  5525.1  704.22  5565.2  705.45
#Mann= 3 ,-1 , 0
  4128.3     .05       0  5102.2     .04       0  5106.2     .05       0
Bank Sta=5102.2,5106.2
XS Rating Curve= 0 ,0
Exp/Cntr=0.3,0.1

Type RM Length L Ch R = 1 ,29860   ,374,374,374
BEGIN DESCRIPTION:
Denton Creek Tr 7 55.0
END DESCRIPTION:
XS GIS Cut Line= 3
      2352420.87      7089745.74      2351780.79      7089649.36
      2351178.97        7089760.
#Sta/Elev= 30
  4352.7  705.49  4358.7  705.71  4445.6  702.44  4526.5  701.41  4555.5  699.92
  4629.5  697.75  4819.8  694.09  4880.5   691.2  4900.7  690.86    4931  688.51
  4951.2  689.29  4964.3  689.28  4981.6     688  5029.2  688.68  5032.3  687.54
  5032.6  687.04  5036.1  687.04  5036.3  687.54  5042.5  689.59  5062.8   690.2
  5082.3  690.27  5087.4  689.72  5145.5  690.61  5154.3  689.95  5174.7  690.83
  5337.3  692.94  5388.2  694.61    5416   696.6  5474.1  697.82  5611.9  702.93
#Mann= 3 ,-1 , 0
  4352.7     .05       0  5032.3    .033       0  5036.3     .05       0
Bank Sta=5032.3,5036.3
XS Rating Curve= 0 ,0
Exp/Cntr=0.3,0.1

Type RM Length L Ch R = 1 ,29486   ,317,317,317
BEGIN DESCRIPTION:
Denton Creek Tr 7 54.0
END DESCRIPTION:
XS GIS Cut Line= 3
       2352384.4      7089441.05      2351879.21      7089339.94
      2351233.73      7089550.32
#Sta/Elev= 30
  4484.8  702.27  4582.1  699.08  4735.1  695.28  4770.6  695.19  4796.3  694.19
  4806.5  694.59  4826.8  693.12  4908.4  691.14  4974.5  688.31    4988  684.01
  4988.3  683.51  4991.8  683.51    4992  684.01  4997.6  685.87  5016.2  687.55
  5048.1  686.56  5105.4  686.32  5126.4  687.34    5137  685.99  5143.8  687.13
    5158  687.74  5200.1  687.57  5263.2  689.07  5284.2  688.49  5303.4  689.33
  5357.8  689.34  5436.3  690.63  5563.9  696.06  5664.9   699.3  5678.9  700.42
#Mann= 3 ,-1 , 0
  4484.8     .05       0    4988    .033       0    4992     .05       0
Bank Sta=4988,4992
XS Rating Curve= 0 ,0
Exp/Cntr=0.3,0.1

Type RM Length L Ch R = 1 ,29169   ,301,301,301
BEGIN DESCRIPTION:
Denton Creek Tr 7 53.0
END DESCRIPTION:
XS GIS Cut Line= 3
      2352400.04      7089196.26        2351779.        7089060.
      2351179.03      7089359.98
#Sta/Elev= 30
  4364.5  698.96  4507.1   695.5    4556  693.76  4561.1  694.18  4570.3  694.01
  4764.8  689.61  4846.7  688.75  4883.1  687.48  4949.1  686.39  4969.6   685.5
    4979  680.58  4979.2  680.08  4982.7  680.08    4983  680.58  4990.1  681.46
  4997.8  686.01  5022.7  685.34  5081.4  685.27  5112.1  685.87  5120.5  686.53
  5126.1  686.27  5142.9  686.82  5156.8   686.7  5201.6  687.56  5321.7  688.82
  5372.1  689.85  5528.6  695.02  5604.1  698.29  5612.4  698.95  5671.1  700.73
#Mann= 3 ,-1 , 0
  4364.5     .05       0    4979    .033       0    4983     .05       0
Bank Sta=4979,4983
XS Rating Curve= 0 ,0
Exp/Cntr=0.3,0.1

Type RM Length L Ch R = 1 ,28868   ,391,391,391
BEGIN DESCRIPTION:
Denton Creek Tr 7 52.0
END DESCRIPTION:
XS GIS Cut Line= 3
      2352419.58      7088829.08      2351728.44      7088775.58
      2351228.96      7089060.02
#Sta/Elev= 30
  4306.8  695.68  4347.5  694.97  4361.1  694.47  4437.8  693.24    4518   691.3
  4548.1  691.18  4688.5  689.54  4788.8  689.12  4929.2  685.93  5002.6  685.75
  5010.9  682.01  5015.8  681.75  5016.1  681.25  5019.6  681.25  5019.8  681.75
  5023.6  682.68  5039.4  684.42  5045.4  684.67  5061.1  684.61  5082.7  685.11
  5104.3  685.17  5157.6  684.82  5179.2  685.74  5222.4  685.93  5324.7  687.73
  5378.1  689.39    5427  690.34  5458.8  691.27    5502  693.02  5574.8  695.44
#Mann= 3 ,-1 , 0
  4306.8     .05       0  5015.8     .04       0  5019.8     .05       0
Bank Sta=5015.8,5019.8
XS Rating Curve= 0 ,0
Exp/Cntr=0.3,0.1

Type RM Length L Ch R = 1 ,28477   ,364,364,364
BEGIN DESCRIPTION:
Denton Creek Tr 7 51.0
END DESCRIPTION:
XS GIS Cut Line= 3
      2352549.78      7088501.82      2351428.37      7088635.09
      2351012.61      7088936.97
#Sta/Elev= 30
  3870.7  697.54  4173.6  691.66  4254.2  690.77  4320.5  689.18  4344.8   689.5
  4403.1  687.86  4408.1  688.42  4485.8  687.44  4490.8  688.16  4573.5  686.21
  4586.5   686.8  4748.8  684.59  4777.8  684.87  4888.6  683.45  4919.2  683.96
  4969.2  683.64  4979.2  683.46  4996.8   680.6  5002.7  681.21  5015.3  679.69
  5015.6  679.19  5019.1  679.19  5019.3  679.69  5023.9  684.96    5032  686.74
  5082.2  687.14  5096.9  686.64  5188.9  689.55  5310.3  692.37  5513.8  694.87
#Mann= 3 ,-1 , 0
  3870.7     .05       0  5015.3    .033       0  5019.3     .05       0
Bank Sta=5015.3,5019.3
XS Rating Curve= 0 ,0
Exp/Cntr=0.3,0.1

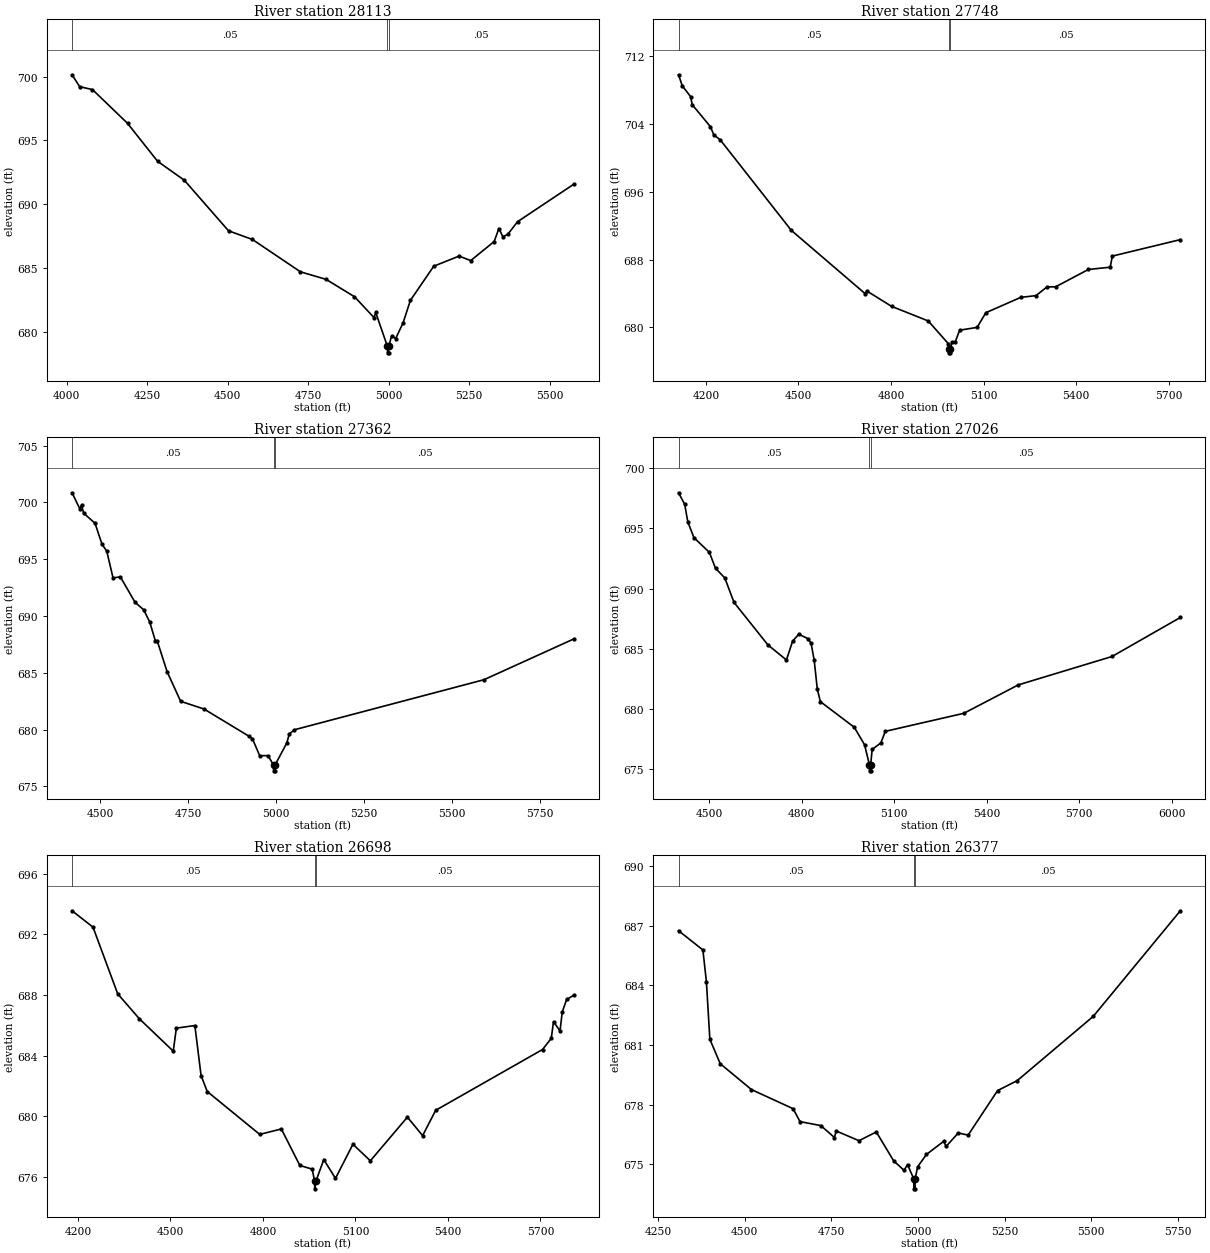
Type RM Length L Ch R = 1 ,28113   ,365,365,365
BEGIN DESCRIPTION:
Denton Creek Tr 7 50.0
END DESCRIPTION:
XS GIS Cut Line= 3
      2352475.18      7088108.41      2351526.62      7088365.97
      2351043.44      7088677.49
#Sta/Elev= 30
  4017.1  700.14  4040.6  699.21  4080.5  698.98  4189.3  696.34  4282.6  693.37
  4365.5  691.89  4502.8  687.93  4577.2  687.25  4726.1  684.72  4805.7  684.13
  4893.9  682.77  4954.5  681.14  4959.7  681.54  4996.2  678.88  4996.4  678.38
  4999.9  678.38  5000.2  678.88  5009.1  679.71  5021.8   679.5  5044.8  680.73
  5067.3  682.48  5139.9  685.16  5218.5  685.95  5254.8   685.6  5327.4  687.09
  5342.2  688.11  5354.5  687.47  5369.6  687.65    5400  688.64  5574.9  691.58
#Mann= 3 ,-1 , 0
  4017.1     .05       0  4996.2    .033       0  5000.2     .05       0
Bank Sta=4996.2,5000.2
XS Rating Curve= 0 ,0
Exp/Cntr=0.3,0.1

Type RM Length L Ch R = 1 ,27748   ,386,386,386
BEGIN DESCRIPTION:
Denton Creek Tr 7 49.0
END DESCRIPTION:
XS GIS Cut Line= 3
      2352327.61      7087782.02      2351480.11      7088049.45
      2350949.11      7088561.54
#Sta/Elev= 30
  4111.3  709.79  4123.4  708.49  4150.5  707.21  4155.7  706.26  4214.7  703.67
  4225.7   702.7  4246.2  702.13  4476.9  691.44  4716.1  683.98  4721.3   684.3
  4801.9  682.48  4920.6  680.76  4985.3   678.1  4988.7   677.5  4988.9     677
  4992.4     677  4992.7   677.5    4998  678.31  5008.2   678.3  5022.4  679.67
    5079     680  5107.3  681.73  5220.5  683.54  5269.9  683.75  5305.4  684.77
  5333.7  684.79  5439.7  686.83  5510.4   687.1  5517.4  688.41  5737.7  690.35
#Mann= 3 ,-1 , 0
  4111.3     .05       0  4988.7     .04       0  4992.7     .05       0
Bank Sta=4988.7,4992.7
XS Rating Curve= 0 ,0
Exp/Cntr=0.3,0.1

Type RM Length L Ch R = 1 ,27362   ,336,336,336
BEGIN DESCRIPTION:
Denton Creek Tr 7 48.0
END DESCRIPTION:
XS GIS Cut Line= 3
      2352030.71      7087547.65      2351474.71      7087712.08
      2350929.01      7088359.99
#Sta/Elev= 30
  4420.2  700.84  4441.9  699.45  4447.1  699.74  4453.3  699.04  4485.6  698.15
  4505.4   696.3  4518.8  695.71  4536.7  693.35  4557.5  693.44  4599.3   691.2
  4623.9  690.54    4641  689.47  4657.1   687.8  4662.4   687.8  4690.4   685.1
  4728.9  682.49  4795.5  681.81  4922.5  679.43    4933   679.2  4953.8   677.7
  4977.5  677.71  4993.2  676.87  4993.4  676.37  4996.9  676.37  4997.2  676.87
  5031.1  678.84  5037.6   679.6  5051.9  679.98  5591.6  684.39  5847.1  687.98
#Mann= 3 ,-1 , 0
  4420.2     .05       0  4993.2     .04       0  4997.2     .05       0
Bank Sta=4993.2,4997.2
XS Rating Curve= 0 ,0
Exp/Cntr=0.3,0.1

Type RM Length L Ch R = 1 ,27026   ,328,328,328
BEGIN DESCRIPTION:
Denton Creek Tr 7 47.0
END DESCRIPTION:
XS GIS Cut Line= 3
      2351978.99        7087410.        2351379.        7087410.
      2350669.57      7088153.58
#Sta/Elev= 30
  4400.4  697.96  4420.4     697  4430.4  695.55  4450.4  694.23  4500.4  693.01
  4520.4  691.68  4550.4  690.89  4580.4  688.85  4690.4  685.32  4750.4  684.07
  4770.4  685.63  4790.4  686.21  4820.4  685.84  4830.4  685.45  4840.4  684.06
  4850.4  681.68  4860.4  680.61  4970.4  678.48  5003.8  677.03  5019.6  675.36
  5019.9  674.86  5023.4  674.86  5023.6  675.36  5028.5  676.64  5056.8  677.18
    5071  678.14  5325.8  679.64  5502.5     682  5806.7  684.36  6028.1   687.6
#Mann= 3 ,-1 , 0
  4400.4     .05       0  5019.6     .04       0  5023.6     .05       0
Bank Sta=5019.6,5023.6
XS Rating Curve= 0 ,0
Exp/Cntr=0.3,0.1

Type RM Length L Ch R = 1 ,26698   ,321,321,321
BEGIN DESCRIPTION:
Denton Creek Tr 7 46.0
END DESCRIPTION:
XS GIS Cut Line= 3
      2351946.83      7087164.57        2351129.        7087210.
      2350571.88      7087796.34
#Sta/Elev= 30
  4180.7  693.56  4248.6  692.48  4328.8  688.08  4398.9  686.44    4509   684.3
    4519  685.82  4579.1  685.99  4599.2  682.69  4619.2  681.64  4789.5  678.81
  4859.6  679.17  4919.7  676.76  4959.7  676.52  4967.7  675.72    4968  675.22
  4971.7  675.72  4997.3  677.15  5035.2  675.91  5091.8  678.16  5148.4  677.07
  5268.6  679.95  5317.9  678.73  5360.4   680.4    5707  684.41  5735.4  685.15
  5742.6  686.25  5763.7  685.63  5770.9  686.88  5785.1  687.71  5808.6  687.99
#Mann= 3 ,-1 , 0
  4180.7     .05       0  4967.7    .033       0  4971.7     .05       0
Bank Sta=4967.7,4971.7
XS Rating Curve= 0 ,0
Exp/Cntr=0.3,0.1

Type RM Length L Ch R = 1 ,26377   ,380,380,380
BEGIN DESCRIPTION:
Denton Creek Tr 7 45.0
END DESCRIPTION:
XS GIS Cut Line= 3
      2351619.28      7086955.64      2350928.81      7086985.09
      2350414.38      7087540.71
#Sta/Elev= 30
  4308.9  686.75  4379.2  685.78  4389.3  684.19  4399.3  681.29  4429.3  680.06
  4519.4  678.76  4639.5   677.8  4659.5  677.15  4719.6  676.95  4758.9  676.35
  4763.9  676.68  4829.7  676.19  4879.7  676.63  4929.7  675.18  4959.8   674.7
  4969.8  674.99  4987.8  674.27  4988.1  673.77  4991.6  673.77  4991.8  674.27
    4999  674.88  5024.5   675.5  5074.3  676.16  5081.2   675.9  5116.3  676.58
  5144.7  676.47  5229.7  678.71  5286.4  679.21  5505.8  682.44  5757.2  687.75
#Mann= 3 ,-1 , 0
  4308.9     .05       0  4987.8    .033       0  4991.8     .05       0
Bank Sta=4987.8,4991.8
XS Rating Curve= 0 ,0
Exp/Cntr=0.3,0.1

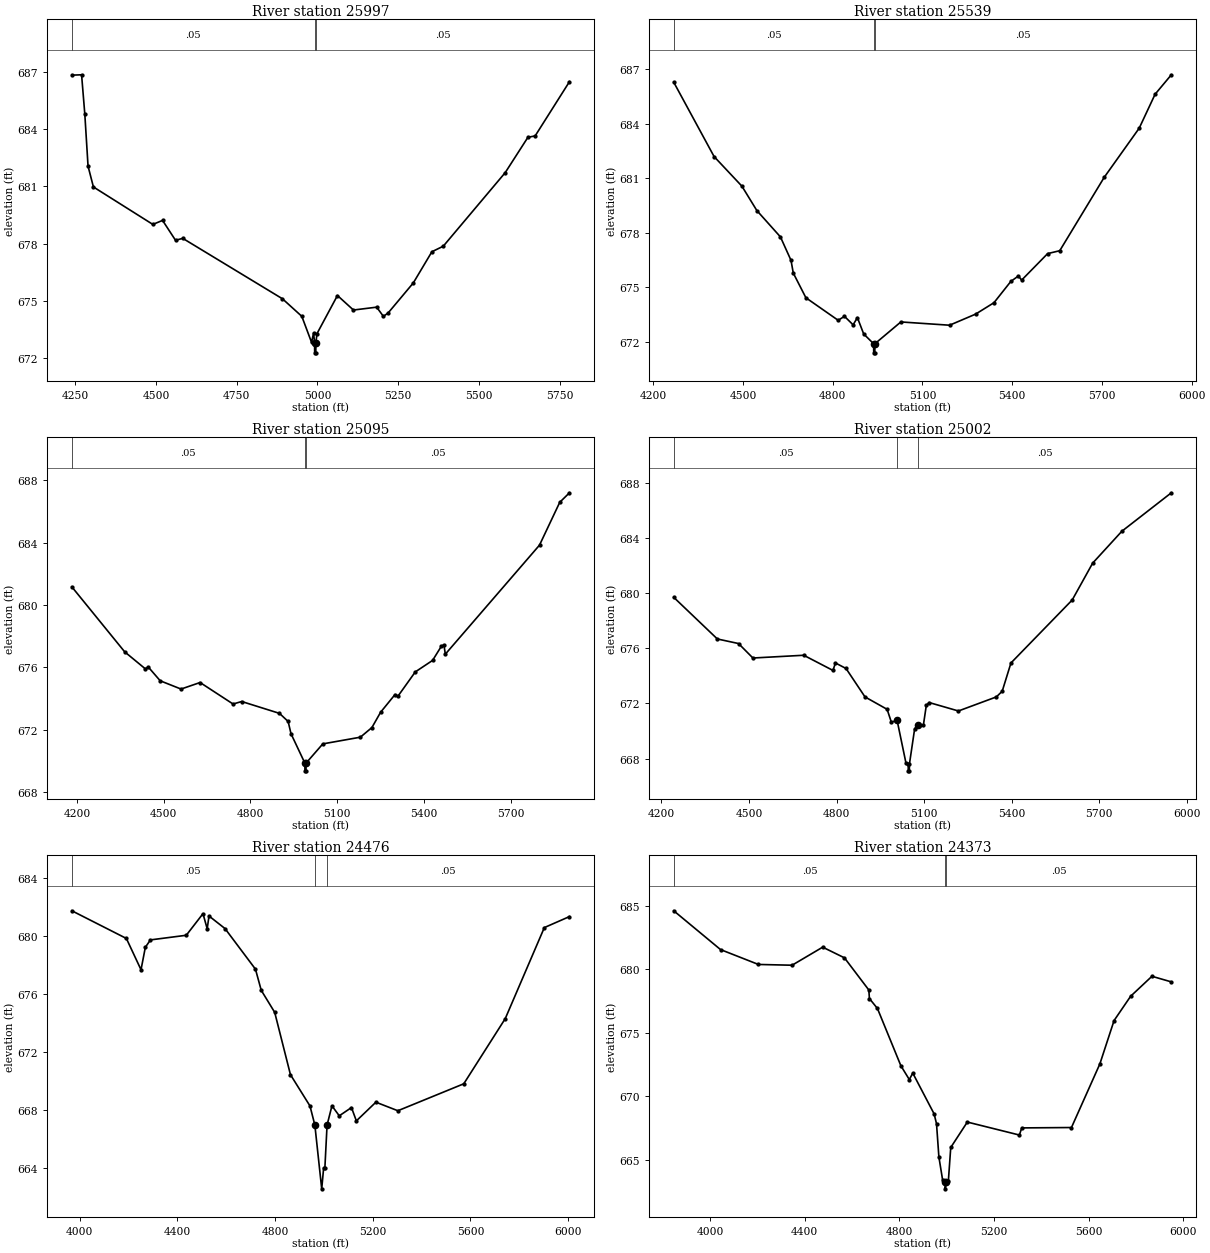
Type RM Length L Ch R = 1 ,25997   ,458,458,458
BEGIN DESCRIPTION:
Denton Creek Tr 7 44.0
END DESCRIPTION:
XS GIS Cut Line= 3
        2351579.        7086710.      2350820.75      7086654.23
      2350329.02      7087259.97
#Sta/Elev= 30
  4239.7  686.82  4269.8  686.84  4279.8  684.78  4289.8  682.06  4306.4  680.97
  4490.4  679.01  4520.5  679.22  4560.6  678.18  4583.1  678.28  4891.5  675.12
  4951.6   674.2  4981.7  672.84  4988.1  673.33  4991.1  672.79  4991.4  672.29
  4994.9  672.29  4995.1  672.79  4998.4  673.29  5061.9  675.29  5111.4  674.53
  5183.3  674.68  5204.1   674.2  5218.5  674.37  5296.8  675.95  5354.3  677.58
  5389.5  677.87  5581.3  681.72  5651.6  683.57  5673.9  683.64  5780.2  686.48
#Mann= 3 ,-1 , 0
  4239.7     .05       0  4991.1    .033       0  4995.1     .05       0
Bank Sta=4991.1,4995.1
XS Rating Curve= 0 ,0
Exp/Cntr=0.3,0.1

Type RM Length L Ch R = 1 ,25539   ,444,444,444
BEGIN DESCRIPTION:
Denton Creek Tr 7 43.0
END DESCRIPTION:
XS GIS Cut Line= 3
      2350971.85        7085733.        2350529.        7086310.
      2350213.51      7087191.17
#Sta/Elev= 30
  4268.8  686.29  4403.7   682.2  4496.7  680.57  4546.6  679.23  4625.4  677.78
  4660.8  676.49  4668.4  675.79  4710.6  674.43  4818.5  673.19  4839.4  673.41
  4868.4  672.94  4882.7  673.34  4903.7  672.44  4936.9   671.9  4937.3   671.4
  4940.9   671.4  4941.2   671.9    5028   673.1  5190.8  672.92  5277.8  673.53
  5339.3  674.16  5395.6  675.33    5421  675.63  5431.6   675.4  5518.6  676.86
  5559.1  677.02  5707.8  681.06  5824.6  683.76  5877.8  685.63  5932.1   686.7
#Mann= 3 ,-1 , 0
  4268.8     .05       0  4936.9    .033       0  4941.2     .05       0
Bank Sta=4936.9,4941.2
XS Rating Curve= 0 ,0
Exp/Cntr=0.3,0.1

Type RM Length L Ch R = 1 ,25095   ,93,93,93
BEGIN DESCRIPTION:
Denton Creek Tr 7 42.0
END DESCRIPTION:
XS GIS Cut Line= 4
        2350668.      7085744.58      2350099.43       7086126.3
      2350100.67      7086259.67      2350107.02      7087163.65
#Sta/Elev= 30
  4181.8  681.17  4364.6     677  4436.6   675.9  4445.6  676.04  4487.6  675.14
  4559.7  674.61  4625.6  675.03  4739.7  673.65  4769.7  673.81  4900.3  673.05
  4930.3  672.53  4940.3  671.74  4988.1  669.86  4988.5  669.36  4992.1  669.36
  4992.5  669.86  5050.3  671.09  5180.3  671.52  5220.3  672.14  5250.3  673.12
  5300.3  674.26  5310.3  674.15  5370.3  675.71  5430.3  676.45  5460.3  677.35
  5469.4  677.45  5474.4  676.85  5800.3  683.85  5870.4   686.6    5904  687.21
#Mann= 3 ,-1 , 0
  4181.8     .05       0  4988.1    .033       0  4992.5     .05       0
Bank Sta=4988.1,4992.5
XS Rating Curve= 0 ,0
Exp/Cntr=0.3,0.1

Type RM Length L Ch R = 1 ,25002   ,526,526,526
BEGIN DESCRIPTION:
Mapping XS cff7f0c4
END DESCRIPTION:
XS GIS Cut Line= 4
      2350556.55       7085741.7      2350027.81      7086085.07
      2350023.03      7086212.33      2350019.42      7087159.63
#Sta/Elev= 30
  4242.2  679.69  4391.7  676.67  4464.2  676.34  4513.5  675.29  4687.7  675.49
  4787.8  674.39  4796.4  674.93  4832.6  674.53  4897.6  672.47  4973.4  671.57
  4987.7  670.65  5007.7  670.76  5037.7   667.7  5045.5  667.61  5045.9  667.11
  5049.5  667.11  5049.9  667.61  5067.7  670.16  5077.7  670.42  5097.7  670.43
  5107.7  671.86  5117.7  672.06  5217.7  671.45  5347.7  672.47  5367.7  672.88
  5397.7  674.93  5607.7   679.5  5677.7  682.17  5777.7  684.48  5947.3  687.27
#Mann= 3 ,-1 , 0
  4242.2     .05       0  5007.7    .033       0  5077.7     .05       0
Bank Sta=5007.7,5077.7
XS Rating Curve= 0 ,0
Exp/Cntr=0.3,0.1

Type RM Length L Ch R = 1 ,24476   ,103,103,103
BEGIN DESCRIPTION:
Denton Creek Tr 7 41.0
END DESCRIPTION:
XS GIS Cut Line= 6
       2350612.3      7085700.74       2350308.7      7085700.43
      2350183.91      7085727.56      2350053.71      7085777.47
      2349797.63      7085903.34      2348616.03      7085901.17
#Sta/Elev= 30
  3967.5  681.75  4190.8  679.84  4250.8  677.68  4268.5  679.23  4289.4  679.74
  4436.2  680.06  4504.6  681.55  4521.9  680.51  4529.3  681.39    4595  680.52
  4719.6  677.72  4743.3  676.26  4798.4  674.74  4862.9  670.44  4942.9  668.28
  4962.9  666.96    4991  662.56    4999  664.02    5004  664.02  5012.9  666.96
  5032.9  668.29  5062.9   667.6  5112.9  668.17  5132.9  667.25  5212.9  668.54
  5302.9  667.95  5572.9  669.81  5742.9  674.31  5902.9  680.59  6005.9  681.35
#Mann= 3 ,-1 , 0
  3967.5     .05       0  4962.9    .033       0  5012.9     .05       0
Bank Sta=4962.9,5012.9
XS Rating Curve= 0 ,0
Exp/Cntr=0.3,0.1

Type RM Length L Ch R = 1 ,24373   ,612,612,612
BEGIN DESCRIPTION:
Denton Creek Tr 7 40.0
END DESCRIPTION:
XS GIS Cut Line= 6
      2350676.58      7085568.05      2350195.21      7085595.44
      2350020.07      7085660.29      2349784.61      7085801.34
      2349576.26      7085816.13      2348626.99      7085816.54
#Sta/Elev= 30
    3847  684.59  4044.7  681.54  4204.8  680.37    4347  680.31  4476.3  681.73
  4568.3  680.89  4671.3  678.36  4673.7  677.69  4707.6  676.91  4806.8   672.4
  4842.3  671.32  4856.9  671.83  4947.1  668.62  4957.2  667.85  4967.2  665.24
  4983.1  663.41  4993.6  663.23  4994.2  662.73  4998.7  663.23  5007.3  663.36
  5017.3  665.98  5087.3  667.98  5307.3  666.96  5317.3  667.52  5527.3  667.55
  5647.3  672.55  5707.3  675.96  5777.3  677.87  5867.3  679.44  5949.3     679
#Mann= 3 ,-1 , 0
    3847     .05       0  4993.6    .033       0  4998.7     .05       0
Bank Sta=4993.6,4998.7
XS Rating Curve= 0 ,0
Exp/Cntr=0.3,0.1

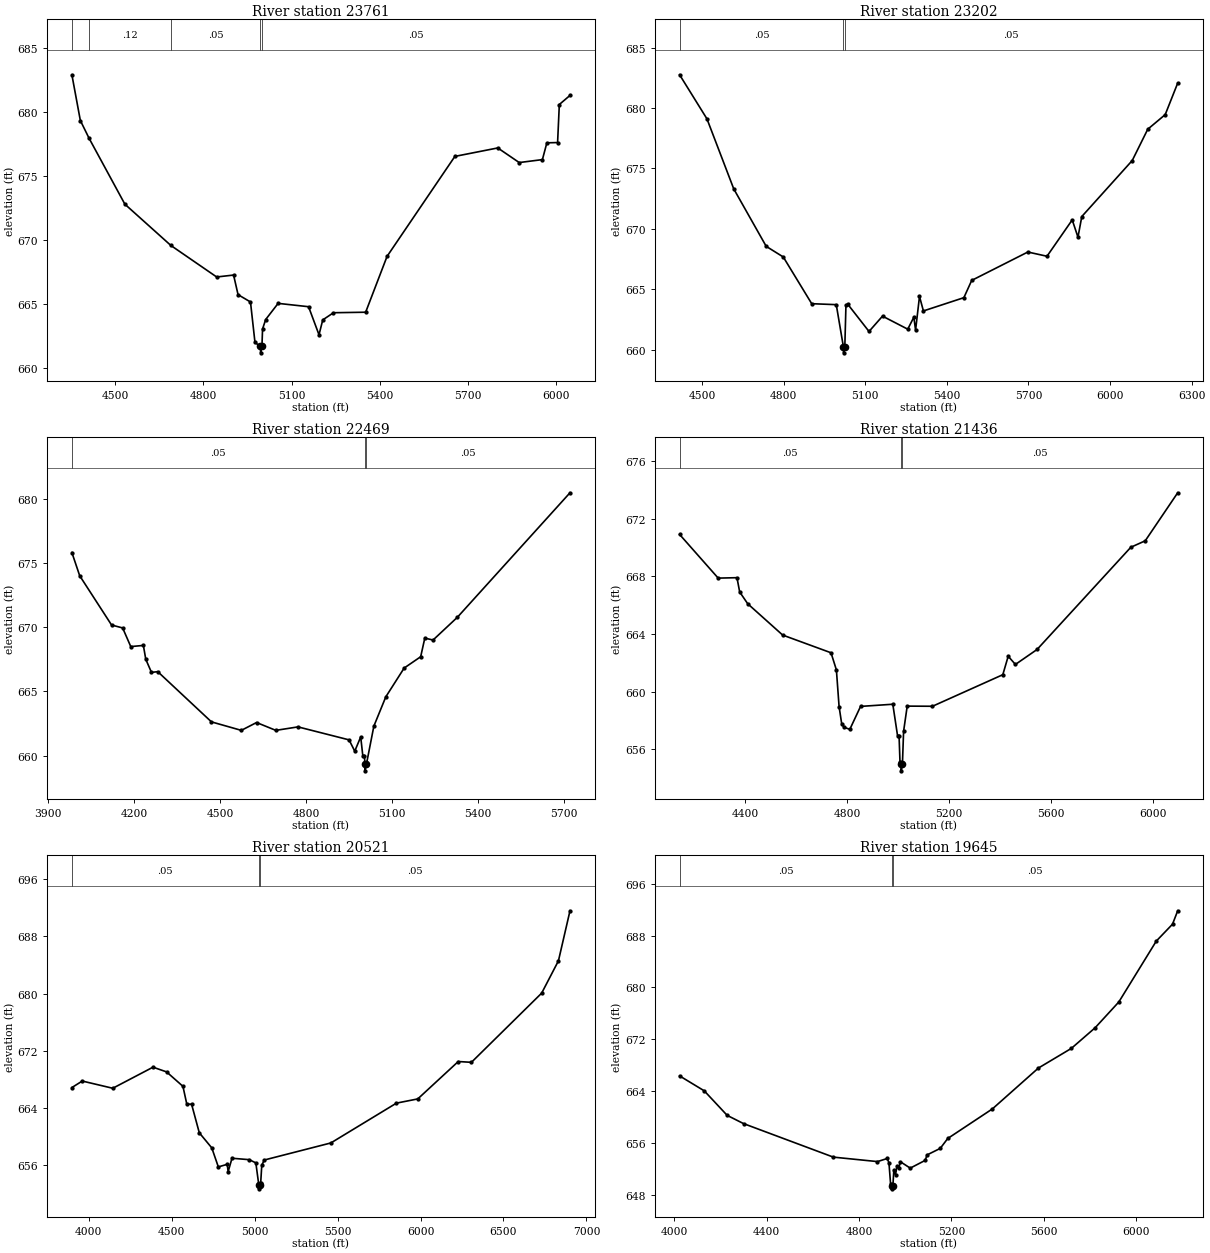
Type RM Length L Ch R = 1 ,23761   ,559,559,559
BEGIN DESCRIPTION:
Denton Creek Tr 7 39.0
END DESCRIPTION:
XS GIS Cut Line= 3
      2349829.04      7084959.98        2349279.        7085310.
      2348396.07      7085866.06
#Sta/Elev= 30
  4352.2  682.89    4381  679.32  4410.8  677.93  4532.6  672.79  4689.1  669.57
    4845  667.11  4902.6  667.26  4917.8  665.73  4960.1  665.16  4975.4     662
  4993.9  661.69  4994.6  661.19  4999.1  661.69  5001.2  663.05  5011.8  663.79
  5054.2  665.05  5157.8  664.79  5193.3   662.6  5206.1  663.76  5242.6  664.32
  5352.1  664.36    5425  668.72  5655.8  676.52  5801.8  677.18  5874.8  676.04
  5953.7  676.27  5968.9  677.58  6005.4   677.6  6011.3  680.57  6047.6  681.28
#Mann= 5 ,-1 , 0
  4352.2     .05       0  4410.8     .12       0  4689.1     .05       0
  4993.9    .033       0  4999.1     .05       0
Bank Sta=4993.9,4999.1
XS Rating Curve= 0 ,0
Exp/Cntr=0.3,0.1

Type RM Length L Ch R = 1 ,23202   ,733,733,733
BEGIN DESCRIPTION:
Denton Creek Tr 7 38.0
END DESCRIPTION:
XS GIS Cut Line= 3
      2349733.71      7084696.75      2349176.28      7084866.51
      2348203.24      7085649.26
#Sta/Elev= 30
  4417.3  682.76  4517.9  679.11  4616.4  673.31  4735.8  668.55  4798.5  667.67
  4903.1   663.8  4993.4  663.72  5019.6  660.23  5020.3  659.73  5024.8  660.23
    5029  663.68  5035.5  663.76  5113.8   661.5  5163.4  662.77  5256.2  661.69
  5278.6  662.68    5285  661.61  5299.4   664.4  5313.8   663.2  5462.6   664.3
  5491.4  665.73  5697.8  668.08  5768.2  667.73    5861  670.74  5882.1  669.31
  5896.2  671.02  6081.7  675.66  6138.7  678.25  6202.9  679.46  6248.8  682.07
#Mann= 3 ,-1 , 0
  4417.3     .05       0  5019.6    .033       0  5024.8     .05       0
Bank Sta=5019.6,5024.8
XS Rating Curve= 0 ,0
Exp/Cntr=0.3,0.1

Type RM Length L Ch R = 1 ,22469   ,1033,1033,1033
BEGIN DESCRIPTION:
Denton Creek Tr 7 37.0
END DESCRIPTION:
XS GIS Cut Line= 3
      2349616.59      7084436.32      2348640.09      7084720.09
       2348077.5      7085170.69
#Sta/Elev= 30
  3983.1   675.8  4010.4  673.99  4121.5  670.16  4160.2  669.93  4188.5  668.48
  4232.5  668.57  4240.9  667.49  4260.8  666.47  4282.6  666.53    4470  662.62
  4574.2  661.96  4627.4  662.57  4694.5  661.96    4772  662.23  4950.1  661.22
  4969.9  660.34  4990.7  661.45    4998  659.99  5003.9  659.99  5005.1  659.31
  5005.9  658.81  5010.5  659.31  5036.6  662.29  5078.3  664.57  5142.3  666.81
  5199.9  667.69  5214.3  669.14  5243.1  668.99  5327.9  670.76  5720.8  680.45
#Mann= 3 ,-1 , 0
  3983.1     .05       0  5005.1    .033       0  5010.5     .05       0
Bank Sta=5005.1,5010.5
XS Rating Curve= 0 ,0
Exp/Cntr=0.3,0.1

Type RM Length L Ch R = 1 ,21436   ,915,915,915
BEGIN DESCRIPTION:
Denton Creek Tr 7 36.0
END DESCRIPTION:
XS GIS Cut Line= 3
      2349592.59       7084231.2        2348779.        7083960.
      2347978.99      7084710.01
#Sta/Elev= 30
  4142.5  670.91  4293.9  667.88  4367.6  667.91  4378.2  666.92  4409.8   666.1
  4546.8  663.93  4736.6   662.7  4757.7  661.51  4768.2  658.97  4778.7  657.75
  4789.3  657.52  4810.4  657.39  4852.5  658.98    4979  659.13  4997.5  656.96
  5003.5  656.96  5007.2  655.11  5011.3  655.01  5012.1  654.51  5016.8  655.01
  5021.3  657.25  5035.5     659  5134.7  658.99  5410.6  661.18  5431.7  662.46
    5460  661.89    5545  662.93  5912.8  670.02  5969.4  670.47  6096.7   673.8
#Mann= 3 ,-1 , 0
  4142.5     .05       0  5011.3    .033       0  5016.8     .05       0
Bank Sta=5011.3,5016.8
XS Rating Curve= 0 ,0
Exp/Cntr=0.3,0.1

Type RM Length L Ch R = 1 ,20521   ,876,876,876
BEGIN DESCRIPTION:
Denton Creek Tr 7 35.0
END DESCRIPTION:
XS GIS Cut Line= 3
      2349436.19      7083906.15        2348429.        7083460.
      2346872.56      7084551.84
#Sta/Elev= 30
  3898.2  666.85  3960.8  667.76  4144.6  666.75  4387.3   669.7  4469.1  669.04
  4567.7  667.02    4591  664.53  4619.8  664.52  4666.3  660.52  4741.6  658.41
    4781  655.75  4834.8  656.11  4840.2  655.08  4863.5  656.96  4967.6  656.76
  5007.2  656.31  5025.3  653.18  5026.2  652.68  5030.9  653.18  5036.4  653.49
  5042.9  655.97  5057.7  656.71  5459.5   659.1  5854.8  664.67  5983.4  665.26
  6227.4  670.49  6306.8  670.38  6730.3  680.06  6831.4  684.58    6901  691.58
#Mann= 3 ,-1 , 0
  3898.2     .05       0  5025.3    .033       0  5030.9     .05       0
Bank Sta=5025.3,5030.9
XS Rating Curve= 0 ,0
Exp/Cntr=0.3,0.1

Type RM Length L Ch R = 1 ,19645   ,902,902,902
BEGIN DESCRIPTION:
Denton Creek Tr 7 34.0
END DESCRIPTION:
XS GIS Cut Line= 3
      2348896.95      7083473.02        2348229.        7082760.
      2347103.33      7082408.11
#Sta/Elev= 30
  4023.5  666.33  4130.3  664.02  4229.5  660.23  4300.3  658.96  4689.1  653.78
  4880.1  653.09  4922.6  653.57  4929.9  652.89  4936.8  649.69  4941.1  649.38
  4942.1  648.88    4947  649.38  4950.9  651.73  4958.2  651.07  4965.1  652.44
  4972.4  652.06  4979.3  653.07    5022  652.08  5086.9  653.28  5094.8  654.12
  5151.9  655.13  5184.4  656.66  5377.7  661.23  5576.8  667.54  5719.6  670.58
  5822.3  673.76    5925  677.75  6087.3  687.16  6157.5  689.77  6179.9  691.84
#Mann= 3 ,-1 , 0
  4023.5     .05       0  4941.1    .033       0    4947     .05       0
Bank Sta=4941.1,4947
XS Rating Curve= 0 ,0
Exp/Cntr=0.3,0.1

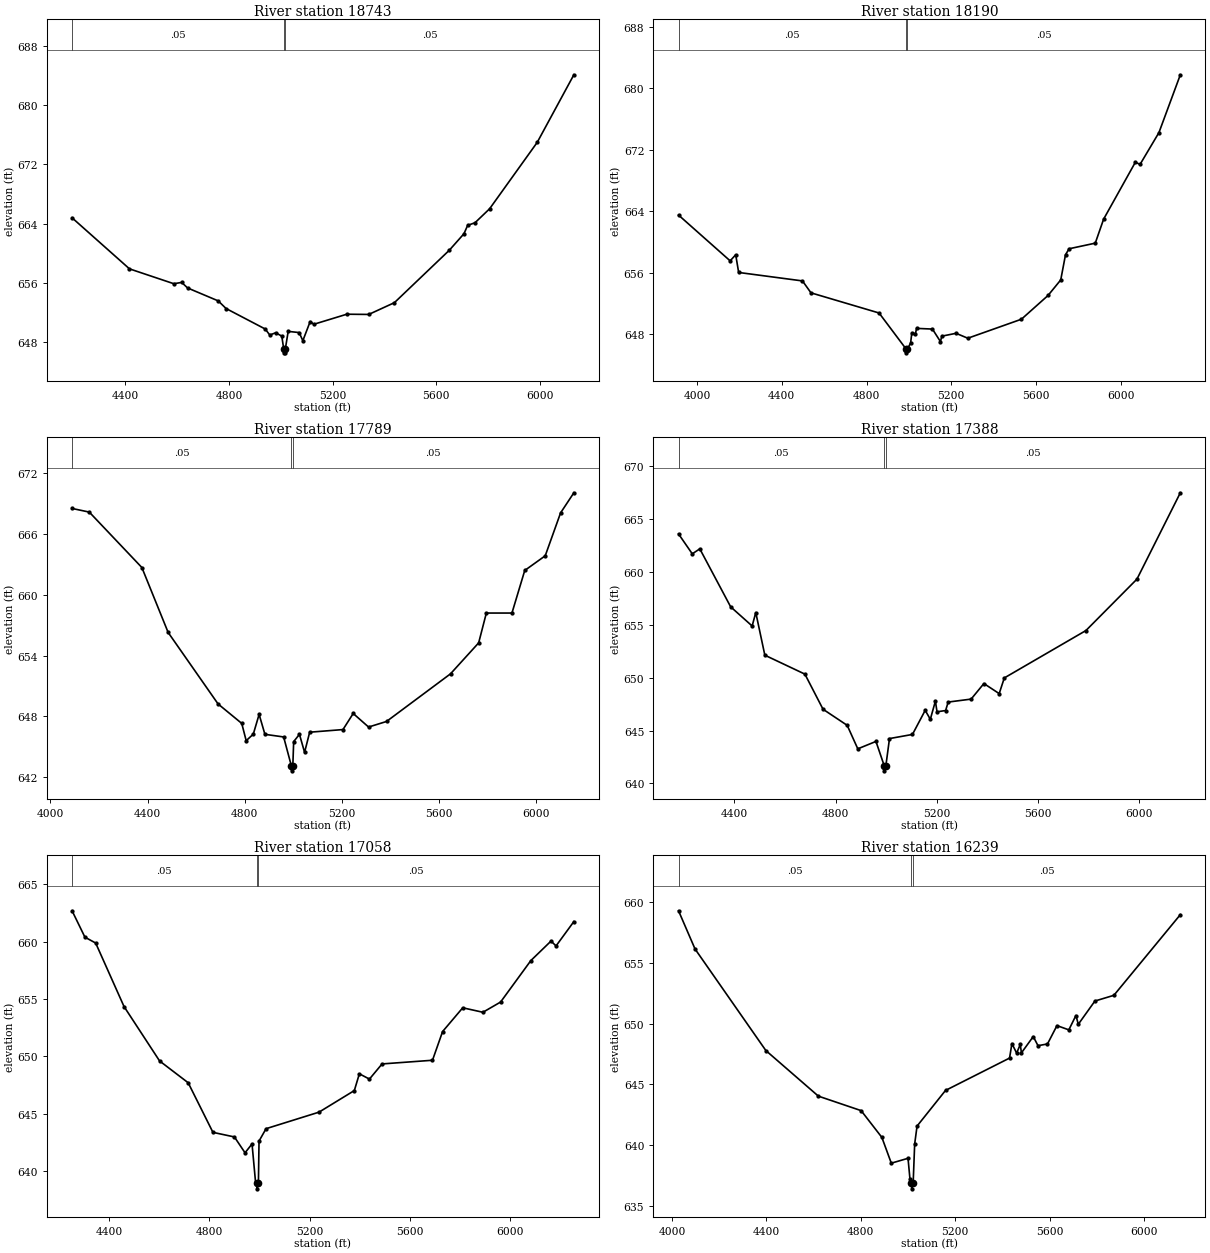
Type RM Length L Ch R = 1 ,18743   ,553,553,553
BEGIN DESCRIPTION:
Denton Creek Tr 7 33.0
END DESCRIPTION:
XS GIS Cut Line= 3
        2348929.      7083410.01        2348829.        7082610.
        2348029.        7081810.
#Sta/Elev= 30
  4193.8  664.79  4415.5  657.89  4586.8  655.88  4617.1  656.06  4639.8  655.31
  4758.2  653.56  4788.4  652.53  4939.6  649.76  4957.2  648.95  4979.9  649.25
  5003.6   648.8  5011.2  647.04  5012.2  646.54  5016.2  646.54  5017.2  647.04
  5028.3  649.44  5070.7  649.28  5084.9  648.18  5113.2  650.77  5127.3   650.4
  5254.6  651.76  5339.4  651.73  5438.4  653.32  5650.6  660.41  5707.1  662.64
  5721.3  663.77  5749.6  664.12  5806.1  666.01    5990  674.99  6131.4  684.12
#Mann= 3 ,-1 , 0
  4193.8     .05       0  5011.2    .033       0  5017.2     .05       0
Bank Sta=5011.2,5017.2
XS Rating Curve= 0 ,0
Exp/Cntr=0.3,0.1

Type RM Length L Ch R = 1 ,18190   ,401,401,401
BEGIN DESCRIPTION:
Denton Creek Tr 7 32.0
END DESCRIPTION:
XS GIS Cut Line= 3
      2349169.14      7083442.58      2349268.86      7082359.86
      2348118.33      7081795.94
#Sta/Elev= 30
  3912.7  663.49  4156.3  657.54  4182.6  658.33  4196.5  656.03  4497.7  654.93
  4537.9  653.38  4859.3  650.76  4986.8  646.08  4987.8  645.58  4992.9  646.08
  5008.2  646.85  5013.8  648.17  5030.7  648.03  5036.3  648.76  5111.2  648.67
  5148.8  647.05  5155.8  647.75  5222.6  648.12  5278.2  647.48  5531.2  649.95
  5656.9  653.04  5716.8  655.06  5739.3  658.33  5756.2  659.11  5879.8  659.84
  5919.2  662.96    6069  670.36  6091.2  670.08  6180.3  674.21  6281.3  681.73
#Mann= 3 ,-1 , 0
  3912.7     .05       0  4986.8    .033       0  4992.9     .05       0
Bank Sta=4986.8,4992.9
XS Rating Curve= 0 ,0
Exp/Cntr=0.3,0.1

Type RM Length L Ch R = 1 ,17789   ,401,401,401
BEGIN DESCRIPTION:
Denton Creek Tr 7 31.0
END DESCRIPTION:
XS GIS Cut Line= 3
      2350274.52      7082459.97        2349429.        7082110.
      2348337.15      7081746.05
#Sta/Elev= 30
    4089  668.54  4159.9  668.18  4376.4   662.7  4484.6  656.28  4690.2  649.21
  4787.6  647.29  4805.9  645.58  4835.2  646.23  4859.1  648.18    4883  646.21
  4960.1  645.95  4991.8   643.1  4992.8   642.6  4997.9   643.1  5001.4  645.49
  5025.2  646.21  5046.3  644.43  5067.3  646.42  5204.4  646.68  5246.5  648.27
  5309.8  646.93  5383.6  647.48  5647.1  652.19    5763  655.25  5794.7   658.2
  5900.1   658.2  5952.8  662.41  6037.1  663.86  6100.3   668.1    6155  670.09
#Mann= 3 ,-1 , 0
    4089     .05       0  4991.8    .033       0  4997.9     .05       0
Bank Sta=4991.8,4997.9
XS Rating Curve= 0 ,0
Exp/Cntr=0.3,0.1

Type RM Length L Ch R = 1 ,17388   ,330,330,330
BEGIN DESCRIPTION:
Denton Creek Tr 7 30.0
END DESCRIPTION:
XS GIS Cut Line= 3
      2350258.93      7082225.62      2349582.29      7081761.36
      2348428.98        7081610.
#Sta/Elev= 30
  4179.4  663.58  4233.7   661.7  4263.5  662.17  4385.5  656.69  4470.4  654.88
  4484.8  656.15  4520.6  652.12    4679  650.33  4750.7  647.01  4846.2  645.49
  4888.1  643.27  4959.9  643.97  4992.3  641.69  4993.4  641.19  4999.2  641.69
  5013.4  644.24  5104.2  644.63  5154.6  646.91  5174.8  646.06  5194.9  647.78
  5201.3  646.77  5235.3  646.89  5245.4  647.69  5336.1  647.97  5386.6  649.44
  5447.1  648.49  5467.3  649.97    5790  654.45  5991.7  659.31  6163.2  667.47
#Mann= 3 ,-1 , 0
  4179.4     .05       0  4992.3    .033       0  4999.2     .05       0
Bank Sta=4992.3,4999.2
XS Rating Curve= 0 ,0
Exp/Cntr=0.3,0.1

Type RM Length L Ch R = 1 ,17058   ,819,819,819
BEGIN DESCRIPTION:
Denton Creek Tr 7 29.0
END DESCRIPTION:
XS GIS Cut Line= 3
      2350355.25      7081996.43      2349785.02      7081512.49
       2348538.4      7081373.09
#Sta/Elev= 30
  4252.1  662.69  4303.4  660.39  4346.3  659.88  4459.4  654.35  4601.3  649.61
  4715.4  647.71  4814.2  643.39  4899.9  642.99  4942.3  641.61  4970.2  642.38
  4984.4  639.01  4988.7  638.97  4989.8  638.47  4995.7  638.97  4998.1  642.63
  5026.2  643.71  5237.5  645.15  5378.4  647.03  5398.5  648.49  5438.7  648.03
  5489.1  649.35  5690.3  649.67  5730.6  652.17    5811  654.24  5891.5  653.85
    5962  654.74  6082.7  658.35  6163.2  660.05  6183.4  659.63  6254.4  661.75
#Mann= 3 ,-1 , 0
  4252.1     .05       0  4988.7    .033       0  4995.7     .05       0
Bank Sta=4988.7,4995.7
XS Rating Curve= 0 ,0
Exp/Cntr=0.3,0.1

Type RM Length L Ch R = 1 ,16239   ,529,529,529
BEGIN DESCRIPTION:
Denton Creek Tr 7 28.0
END DESCRIPTION:
XS GIS Cut Line= 3
      2350776.48      7081269.22      2349837.08      7081016.12
      2348688.78      7081134.68
#Sta/Elev= 30
  4027.1  659.28    4097  656.14  4397.3  647.79    4620  644.04  4801.2  642.85
  4889.1  640.65  4929.1  638.53    5000  638.93  5008.1  637.25  5014.6  636.92
  5015.7  636.42  5021.8  636.92  5028.2  640.11  5038.3  641.58  5158.9  644.51
  5430.4  647.17  5440.4  648.36  5460.5  647.58  5475.8  648.29  5480.8   647.6
  5530.9  648.94    5551  648.19  5591.2  648.33  5631.4  649.84  5681.7  649.49
  5711.8  650.67  5721.9  649.95  5792.3  651.86  5872.7  652.33  6154.4  658.96
#Mann= 3 ,-1 , 0
  4027.1     .05       0  5014.6    .033       0  5021.8     .05       0
Bank Sta=5014.6,5021.8
XS Rating Curve= 0 ,0
Exp/Cntr=0.3,0.1