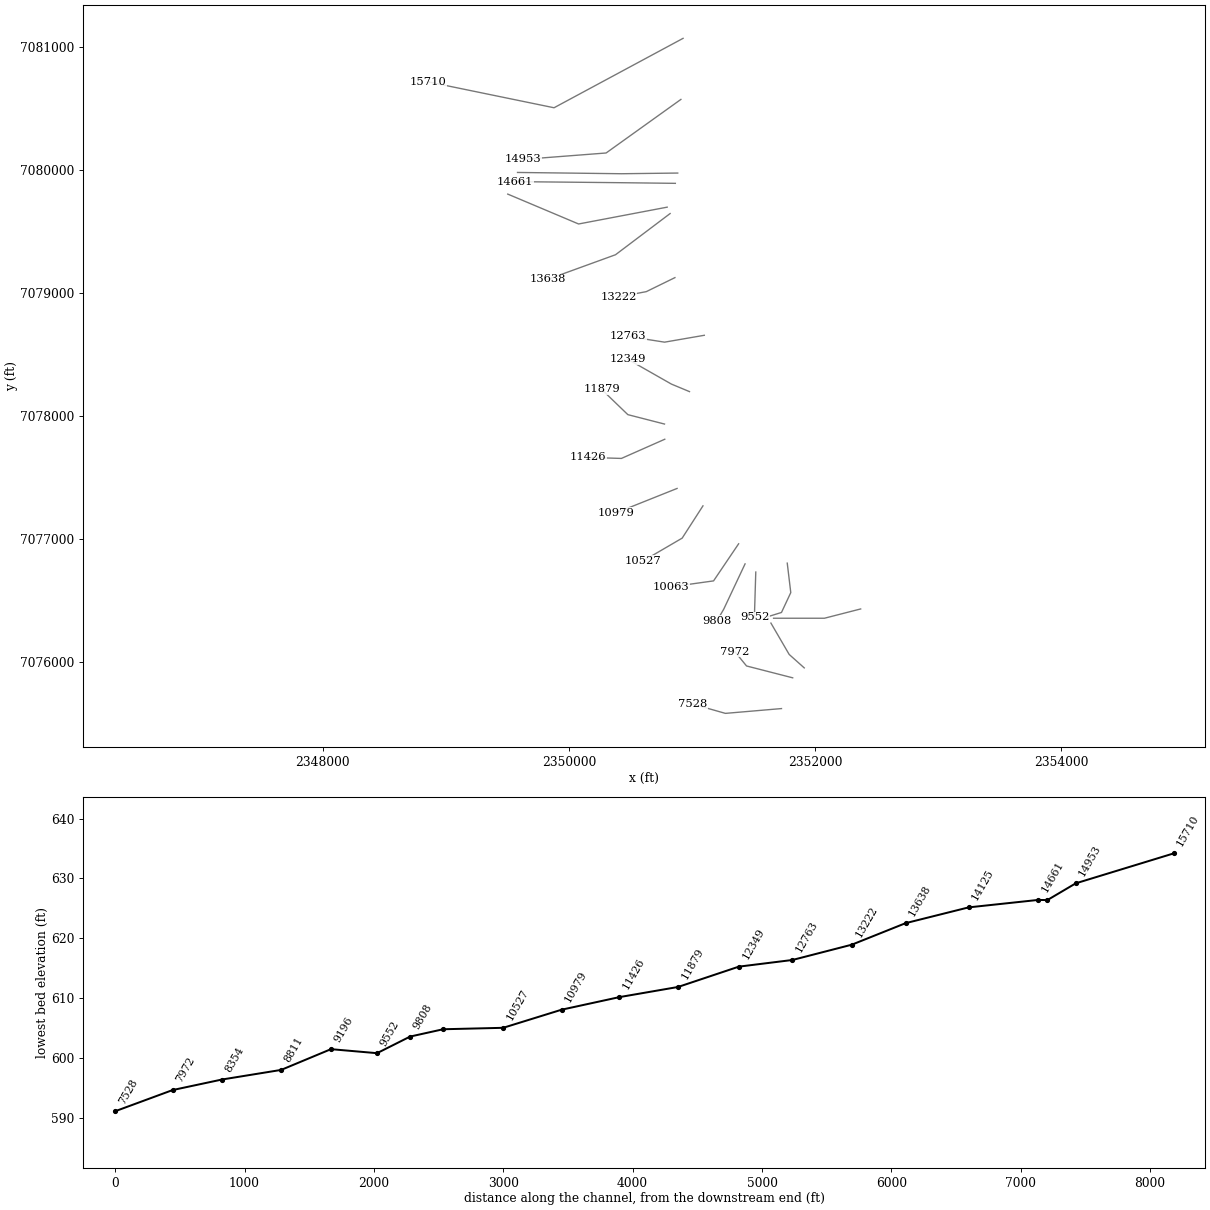
HEC-RAS study Denton Creek Tr 7.prj: Denton Creek Tr 7 Base Level Engineering

--- Denton Creek Tr 7.g01 (geometry) --- (continued)

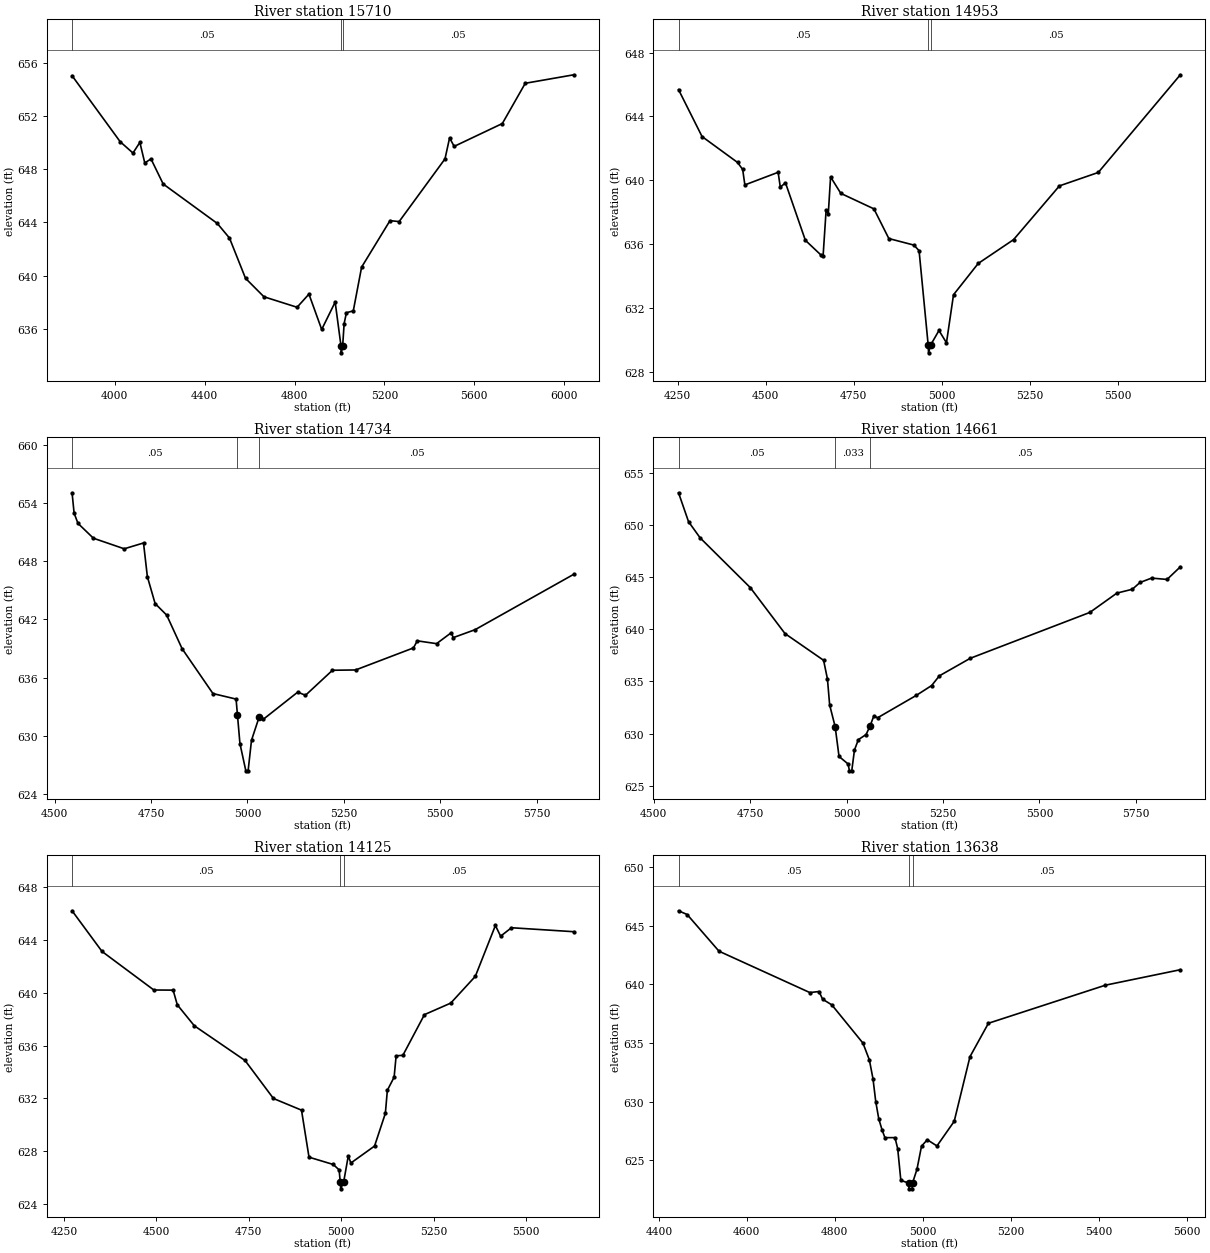
Type RM Length L Ch R = 1 ,15710   ,757,757,757
BEGIN DESCRIPTION:
Denton Creek Tr 7 27.0
END DESCRIPTION:
XS GIS Cut Line= 3
      2350927.79      7081069.18      2349879.44      7080504.82
        2348857.      7080715.39
#Sta/Elev= 30
  3809.4  655.04  4023.7  650.07  4080.6  649.22  4111.3  650.02  4133.2  648.47
  4160.8  648.78  4215.1  646.89  4456.1  643.92  4510.4  642.82  4581.8  639.79
  4663.8   638.4  4811.4  637.61  4864.2   638.6    4921  635.94    4981     638
  5007.1  634.68  5008.2  634.18  5014.3  634.68  5020.9  636.38  5031.1   637.2
  5061.7  637.34  5098.7  640.63  5225.1  644.13  5265.9  644.06  5470.1  648.78
  5490.5  650.36  5510.9  649.72  5725.4  651.44  5827.5  654.47  6043.9  655.11
#Mann= 3 ,-1 , 0
  3809.4     .05       0  5007.1    .033       0  5014.3     .05       0
Bank Sta=5007.1,5014.3
XS Rating Curve= 0 ,0
Exp/Cntr=0.3,0.1

Type RM Length L Ch R = 1 ,14953   ,219,219,219
BEGIN DESCRIPTION:
Denton Creek Tr 7 26.0
END DESCRIPTION:
XS GIS Cut Line= 3
      2350910.05      7080572.64      2350302.52      7080137.13
      2349626.64      7080084.89
#Sta/Elev= 30
  4252.5  645.68  4319.3  642.74    4420  641.12  4434.7  640.68  4440.9  639.71
  4535.4   640.5  4541.6  639.57  4556.3  639.84  4612.8  636.24    4657  635.32
  4663.2  635.28  4671.8  638.15  4677.9   637.9  4684.4  640.21  4713.5  639.18
  4807.5  638.21  4849.9  636.35  4921.1  635.94  4935.8  635.59  4961.6  629.69
  4962.7  629.19  4968.9  629.69  4992.3  630.59  5013.6  629.82  5033.6  632.83
  5103.8  634.79  5204.1  636.28  5334.5  639.65  5444.8  640.49  5677.9  646.61
#Mann= 3 ,-1 , 0
  4252.5     .05       0  4961.6    .033       0  4968.9     .05       0
Bank Sta=4961.6,4968.9
XS Rating Curve= 0 ,0
Exp/Cntr=0.3,0.1

Type RM Length L Ch R = 1 ,14734   ,73,73,73
BEGIN DESCRIPTION:
Mapping XS b6e78bf6
END DESCRIPTION:
XS GIS Cut Line= 3
      2350884.33      7079973.94      2350427.42      7079968.47
      2349582.93      7079978.88
#Sta/Elev= 30
  4545.2  655.04  4550.5  652.94  4560.5  651.89  4600.5  650.36  4680.5  649.27
  4730.5  649.87  4740.5   646.4  4760.6  643.63  4790.6  642.44  4830.6  638.98
  4910.6  634.36  4970.6  633.79  4974.1 632.187  4980.6  629.21  4995.9   626.4
  5001.8   626.4  5010.6  629.55  5030.6  631.96  5040.6  631.69  5130.6  634.51
  5150.6  634.18  5220.6  636.76  5280.6  636.79  5430.6  639.06  5440.6  639.79
  5490.6   639.5  5528.8  640.63  5533.8  640.12  5590.6  640.94  5846.7  646.65
#Mann= 3 ,-1 , 0
  4545.2     .05       0  4974.1    .033       0  5030.6     .05       0
Bank Sta=4974.1,5030.6
XS Rating Curve= 0 ,0
Exp/Cntr=0.3,0.1

Type RM Length L Ch R = 1 ,14661   ,536,536,536
BEGIN DESCRIPTION:
Mapping XS 1b71d9cd
END DESCRIPTION:
XS GIS Cut Line= 3
      2350864.92      7079890.35      2350425.68      7079895.56
      2349564.59      7079904.24
#Sta/Elev= 30
  4564.7  653.08  4590.6  650.31  4620.6  648.76  4750.6  643.99  4840.6  639.58
  4940.6  637.02  4950.6  635.23  4956.3  632.74  4970.6  630.65  4980.6   627.8
    5004  627.08  5007.7  626.42  5013.6  626.42  5020.6  628.41  5030.7  629.41
  5050.7   629.9  5060.7  630.69  5070.7  631.67  5080.7  631.51  5180.7  633.65
  5220.7   634.6  5240.7  635.53  5320.7  637.21  5630.7  641.61  5700.7  643.46
  5740.7  643.83  5760.7  644.48  5790.7   644.9  5830.7  644.77  5865.1  645.98
#Mann= 3 ,-1 , 0
  4564.7     .05       0  4970.6    .033       0  5060.7     .05       0
Bank Sta=4970.6,5060.7
XS Rating Curve= 0 ,0
Exp/Cntr=0.3,0.1

Type RM Length L Ch R = 1 ,14125   ,487,487,487
BEGIN DESCRIPTION:
Denton Creek Tr 7 25.0
END DESCRIPTION:
XS GIS Cut Line= 3
      2350798.55      7079696.78        2350079.        7079560.
      2349503.49      7079802.88
#Sta/Elev= 30
  4272.1  646.17  4353.1   643.1  4493.2  640.19  4545.4  640.18  4556.7  639.07
  4602.7  637.49  4739.9  634.87  4816.7     632  4892.6  631.12  4912.9  627.57
  4978.4  627.02  4994.4  626.61  4997.4  625.68  4998.7  625.18  5006.5  625.68
  5019.1  627.66  5026.2  627.13  5090.2  628.41  5119.4  630.88  5124.8  632.62
  5143.1  633.61  5148.5  635.22  5166.8  635.26  5225.1  638.33  5296.2   639.2
  5362.7  641.22    5417  645.06  5431.1  644.25  5460.4  644.89  5629.2  644.59
#Mann= 3 ,-1 , 0
  4272.1     .05       0  4997.4    .033       0  5006.5     .05       0
Bank Sta=4997.4,5006.5
XS Rating Curve= 0 ,0
Exp/Cntr=0.3,0.1

Type RM Length L Ch R = 1 ,13638   ,416,416,416
BEGIN DESCRIPTION:
Denton Creek Tr 7 24.0
END DESCRIPTION:
XS GIS Cut Line= 3
      2350822.41      7079644.71        2350379.        7079310.
      2349828.99        7079110.
#Sta/Elev= 30
  4444.7  646.28  4464.3  645.96  4536.7  642.83  4743.2   639.3    4764  639.39
  4772.3  638.73  4793.2  638.25  4863.9  634.99  4878.5  633.56  4886.8  631.94
  4893.1  629.98    4900  628.51  4907.6  627.56  4913.9  626.92  4936.8  626.92
    4943  625.97  4950.1  623.27  4967.6  623.05  4968.9  622.55  4975.4  622.55
  4976.7  623.05  4986.7  624.21  4997.1  626.19  5010.2  626.74  5032.2  626.21
  5071.4  628.31  5107.3  633.83  5149.2  636.68  5415.2  639.93  5585.5  641.25
#Mann= 3 ,-1 , 0
  4444.7     .05       0  4967.6    .033       0  4976.7     .05       0
Bank Sta=4967.6,4976.7
XS Rating Curve= 0 ,0
Exp/Cntr=0.3,0.1

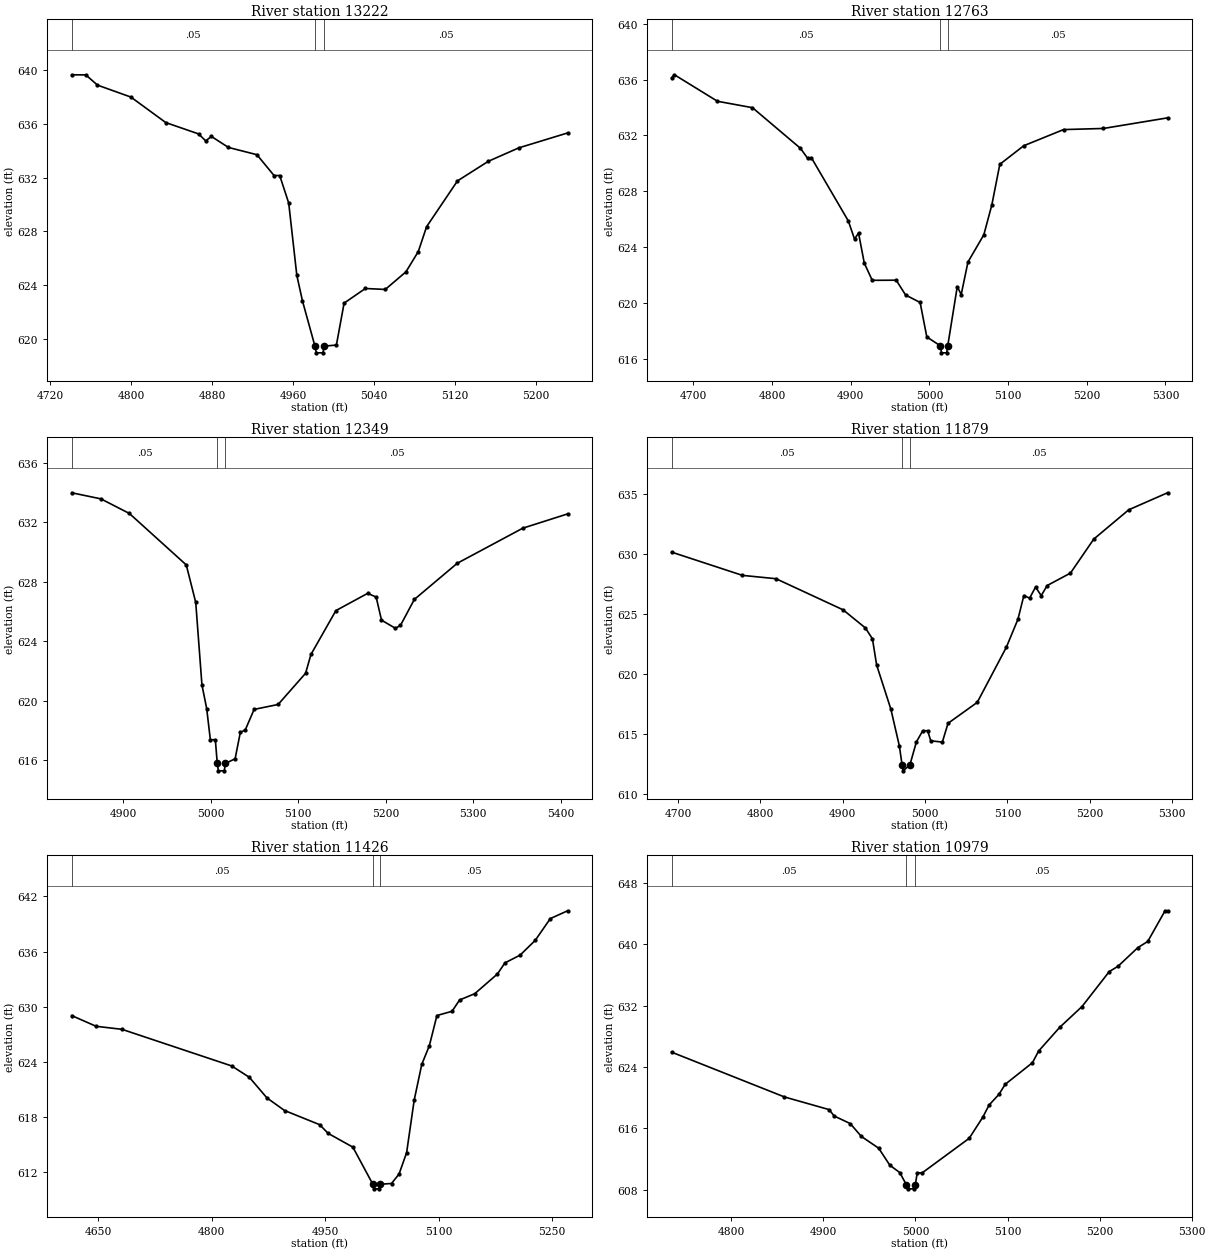
Type RM Length L Ch R = 1 ,13222   ,459,459,459
BEGIN DESCRIPTION:
Denton Creek Tr 7 23.0
END DESCRIPTION:
XS GIS Cut Line= 3
      2350861.45      7079123.86        2350629.        7079010.
      2350402.11      7078966.87
#Sta/Elev= 30
  4741.2  639.66  4755.1  639.65  4766.6  638.89  4799.6     638  4834.1   636.1
  4866.4  635.26  4873.5  634.74  4879.1  635.07    4896  634.25  4924.1  633.71
    4941  632.16  4946.6  632.16  4955.5  630.11  4963.5  624.73  4969.1  622.82
  4981.4  619.46  4982.8  618.96  4989.3  618.96  4990.6  619.46  5002.6  619.54
  5010.2  622.66  5031.2  623.75  5050.9  623.68  5071.3  624.99  5083.5   626.5
  5091.7  628.35  5122.2  631.76  5152.7  633.22  5182.8  634.22    5231  635.33
#Mann= 3 ,-1 , 0
  4741.2     .05       0  4981.4    .033       0  4990.6     .05       0
Bank Sta=4981.4,4990.6
XS Rating Curve= 0 ,0
Exp/Cntr=0.3,0.1

Type RM Length L Ch R = 1 ,12763   ,414,414,414
BEGIN DESCRIPTION:
Denton Creek Tr 7 22.0
END DESCRIPTION:
XS GIS Cut Line= 3
      2351100.19      7078655.11      2350777.29      7078599.25
      2350478.39      7078646.43
#Sta/Elev= 30
  4672.3  636.14  4675.8  636.35  4730.5  634.45    4775  633.99  4835.9  631.08
    4845  630.37    4850  630.39  4896.8  625.87  4904.7  624.57  4909.8     625
  4917.1  622.85  4927.2  621.61  4957.7  621.62  4969.6  620.56  4988.1  620.02
  4996.6  617.55  5013.9  616.91  5015.2  616.41  5021.8  616.41  5023.2  616.91
  5035.3  621.16  5040.3  620.59  5048.9  622.92  5069.1  624.88  5079.3  627.03
  5089.4  629.93  5119.8  631.26  5170.4  632.42    5221   632.5  5302.6  633.26
#Mann= 3 ,-1 , 0
  4672.3     .05       0  5013.9    .033       0  5023.2     .05       0
Bank Sta=5013.9,5023.2
XS Rating Curve= 0 ,0
Exp/Cntr=0.3,0.1

Type RM Length L Ch R = 1 ,12349   ,470,470,470
BEGIN DESCRIPTION:
Denton Creek Tr 7 21.0
END DESCRIPTION:
XS GIS Cut Line= 3
      2350979.73       7078197.2      2350833.23      7078258.22
      2350478.98      7078460.01
#Sta/Elev= 30
  4841.3  633.99  4874.6  633.58  4907.1   632.6  4972.1  629.14  4982.9  626.62
    4990  621.07  4995.4  619.49  4999.6  617.39  5005.3  617.39  5007.5   615.8
  5008.8   615.3  5015.5   615.3  5016.8   615.8  5027.9  616.11  5033.8  617.88
  5039.5  618.05  5049.6  619.43    5077  619.76  5108.4  621.86  5114.5  623.12
    5143  626.07  5179.3  627.23    5189  626.98  5195.1  625.43    5211  624.88
  5216.8  625.08  5232.6  626.82  5281.6  629.25  5356.5  631.61  5407.7  632.57
#Mann= 3 ,-1 , 0
  4841.3     .05       0  5007.5    .033       0  5016.8     .05       0
Bank Sta=5007.5,5016.8
XS Rating Curve= 0 ,0
Exp/Cntr=0.3,0.1

Type RM Length L Ch R = 1 ,11879   ,453,453,453
BEGIN DESCRIPTION:
Denton Creek Tr 7 20.0
END DESCRIPTION:
XS GIS Cut Line= 3
      2350776.82      7077933.53        2350479.        7078010.
      2350266.83      7078214.56
#Sta/Elev= 30
  4692.3  630.18  4778.2  628.24    4819  627.96  4900.5  625.36  4927.5  623.85
  4936.1  622.94  4941.2  620.75  4958.5  617.06  4968.8  613.99  4972.1  612.41
  4973.4  611.91  4981.6  612.41  4989.5  614.33  4997.2  615.26  5003.2  615.26
  5006.9  614.42    5021  614.31  5027.9  615.88  5063.4  617.63  5098.7  622.23
  5112.8  624.57    5120  626.55    5127  626.34  5134.2  627.26  5141.1  626.55
  5148.3  627.39  5176.6  628.43  5204.9  631.27  5247.4  633.72  5294.5  635.14
#Mann= 3 ,-1 , 0
  4692.3     .05       0  4972.1    .033       0  4981.6     .05       0
Bank Sta=4972.1,4981.6
XS Rating Curve= 0 ,0
Exp/Cntr=0.3,0.1

Type RM Length L Ch R = 1 ,11426   ,447,447,447
BEGIN DESCRIPTION:
Denton Creek Tr 7 19.0
END DESCRIPTION:
XS GIS Cut Line= 3
      2350779.01      7077810.01      2350426.81      7077654.02
      2350156.14      7077662.27
#Sta/Elev= 30
  4614.8  629.04    4647  627.88  4681.2  627.55  4826.4  623.57  4849.7  622.34
    4873   620.1  4896.3  618.73  4942.8  617.19  4953.9  616.25  4986.7  614.75
  5013.1  610.72  5014.4  610.22  5021.2  610.22  5022.6  610.72  5037.8   610.8
  5047.8  611.83  5057.8  614.15  5067.8  619.85  5077.8  623.73  5087.9  625.78
  5097.9  629.05  5117.9  629.51  5127.9  630.74  5147.9  631.42  5177.9  633.56
  5187.9  634.77  5207.9  635.61  5227.9  637.21  5247.9  639.58  5270.8  640.43
#Mann= 3 ,-1 , 0
  4614.8     .05       0  5013.1    .033       0  5022.6     .05       0
Bank Sta=5013.1,5022.6
XS Rating Curve= 0 ,0
Exp/Cntr=0.3,0.1

Type RM Length L Ch R = 1 ,10979   ,452,452,452
BEGIN DESCRIPTION:
Denton Creek Tr 7 18.0
END DESCRIPTION:
XS GIS Cut Line= 3
        2350879.        7077410.        2350629.        7077310.
      2350379.02      7077210.01
#Sta/Elev= 30
  4735.3  625.94  4857.8   620.1  4906.3  618.45  4911.7  617.62  4929.2  616.63
  4941.3  614.95  4960.1  613.42  4972.2   611.2    4983  610.24  4990.3  608.62
  4991.7  608.12  4998.5  608.12  4999.9  608.62  5001.9   610.2  5007.3   610.2
  5058.4  614.71  5073.2  617.47    5080  619.05  5090.7  620.44  5097.5  621.75
  5127.1  624.57  5133.8  626.09  5156.7  629.18  5180.9  631.89  5210.5  636.45
    5220  637.14  5241.5  639.57  5252.3  640.38  5271.1  644.38  5273.8  644.38
#Mann= 3 ,-1 , 0
  4735.3     .05       0  4990.3    .033       0  4999.9     .05       0
Bank Sta=4990.3,4999.9
XS Rating Curve= 0 ,0
Exp/Cntr=0.3,0.1

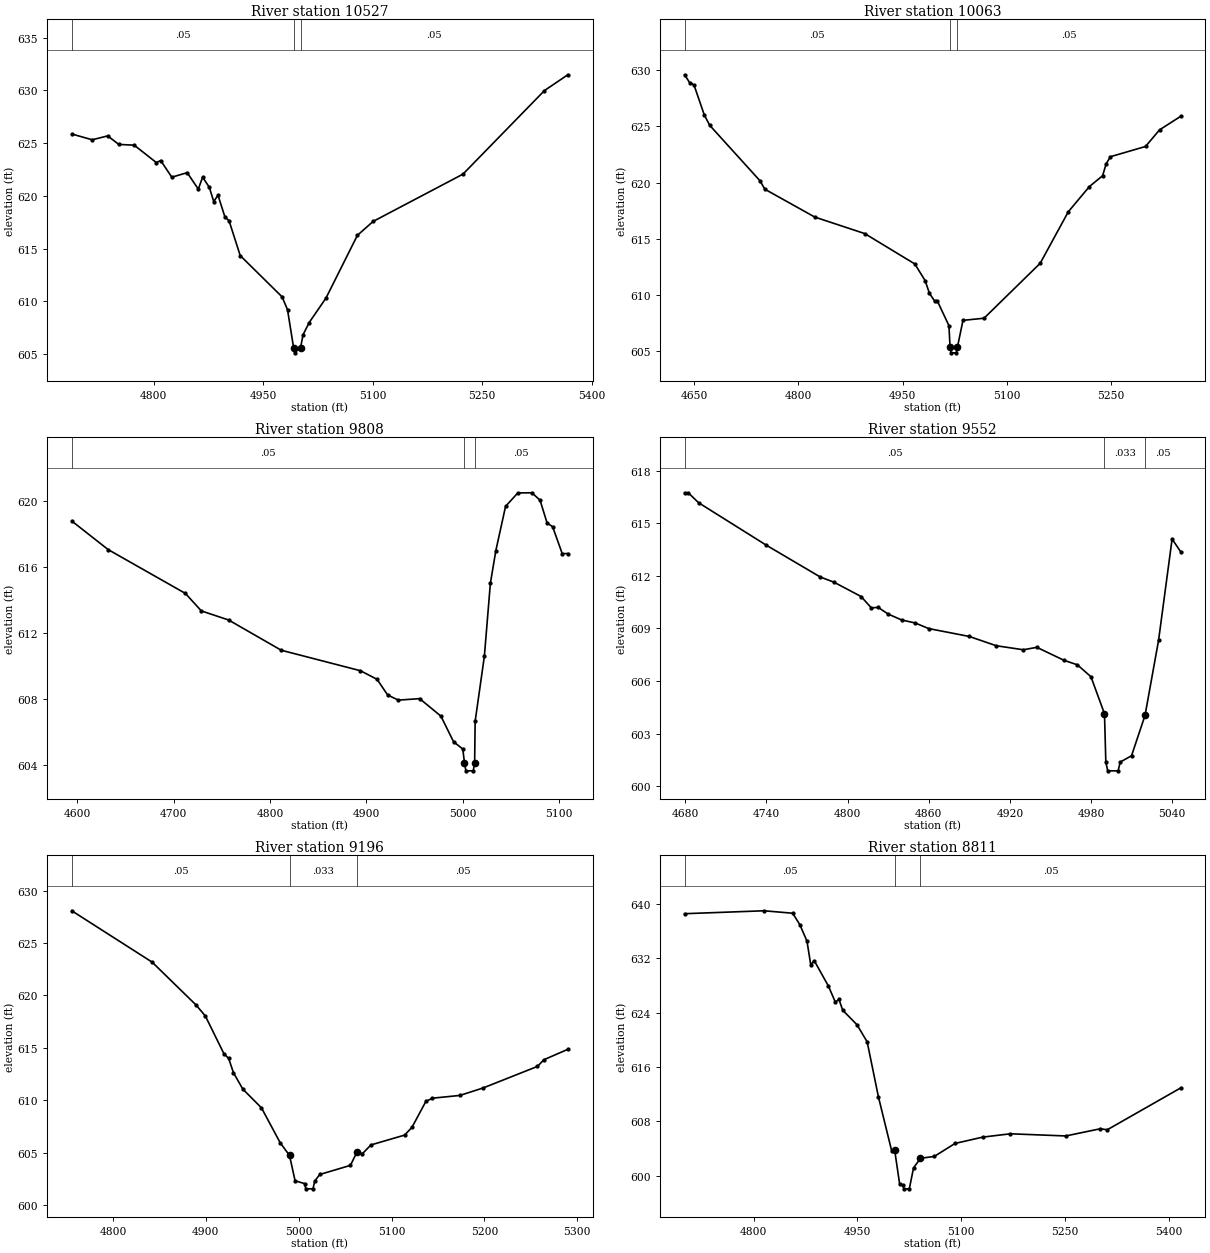
Type RM Length L Ch R = 1 ,10527   ,464,464,464
BEGIN DESCRIPTION:
Denton Creek Tr 7 17.0
END DESCRIPTION:
XS GIS Cut Line= 3
      2351089.31      7077268.39      2350920.33      7077006.11
      2350603.08      7076820.82
#Sta/Elev= 30
    4688  625.87    4716  625.32  4737.2  625.69  4752.4  624.88  4773.5  624.81
  4803.8  623.16  4809.8  623.35    4825  621.77  4846.1   622.2  4861.3  620.64
  4867.2  621.77  4876.4  620.81  4882.4  619.46  4888.3  620.05  4897.6  618.03
  4903.5  617.62  4918.7  614.33  4976.1  610.41  4983.5  609.19  4991.8   605.6
  4993.2   605.1  5001.4   605.6  5004.8  606.82  5013.1  607.97  5036.2   610.3
  5079.2  616.25  5100.7  617.57  5223.8  622.06  5335.4  629.99  5367.4  631.49
#Mann= 3 ,-1 , 0
    4688     .05       0  4991.8    .033       0  5001.4     .05       0
Bank Sta=4991.8,5001.4
XS Rating Curve= 0 ,0
Exp/Cntr=0.3,0.1

Type RM Length L Ch R = 1 ,10063   ,255,255,255
BEGIN DESCRIPTION:
Denton Creek Tr 7 16.0
END DESCRIPTION:
XS GIS Cut Line= 3
      2351378.99      7076959.98      2351175.38       7076658.5
      2350828.96      7076609.99
#Sta/Elev= 30
  4636.2   629.6  4643.7  628.88  4649.7   628.7  4664.7     626  4672.4   625.1
  4744.8  620.16  4751.6  619.42  4823.5  616.94  4895.4  615.47  4967.4  612.77
  4982.3  611.28  4988.4  610.16  4996.1  609.45    5000  609.45  5016.5  607.28
  5018.1  605.36  5019.6  604.86  5027.3  604.86  5028.7  605.36  5036.7  607.75
    5067  607.94  5147.8  612.83  5188.2  617.41  5218.5  619.65  5237.6  620.62
  5242.7  621.68  5248.8  622.31  5299.3  623.22  5319.5   624.7  5349.8   625.9
#Mann= 3 ,-1 , 0
  4636.2     .05       0  5018.1    .033       0  5028.7     .05       0
Bank Sta=5018.1,5028.7
XS Rating Curve= 0 ,0
Exp/Cntr=0.3,0.1

Type RM Length L Ch R = 1 ,9808    ,256,256,256
BEGIN DESCRIPTION:
Denton Creek Tr 7 15.0
END DESCRIPTION:
XS GIS Cut Line= 3
      2351431.29       7076796.7      2351258.45      7076429.44
      2351204.01      7076335.01
#Sta/Elev= 30
  4594.1  618.76  4631.9  617.03    4712  614.38  4728.6  613.32  4756.9  612.77
  4811.5  610.94  4893.7   609.7    4911  609.18    4922  608.23  4933.1  607.92
  4955.2  608.01  4977.3  606.95  4990.4   605.4    5000  604.96  5001.7  604.14
  5003.2  603.64  5010.9  603.64  5012.3  604.14  5012.8  606.63  5022.4  610.58
  5028.6  614.98  5034.3  616.97  5044.4  619.65  5057.1  620.46  5071.7  620.47
  5080.2  620.02  5087.5  618.64  5093.2  618.42  5103.2  616.79    5109  616.79
#Mann= 3 ,-1 , 0
  4594.1     .05       0  5001.7    .033       0  5012.3     .05       0
Bank Sta=5001.7,5012.3
XS Rating Curve= 0 ,0
Exp/Cntr=0.3,0.1

Type RM Length L Ch R = 1 ,9552    ,356,356,356
BEGIN DESCRIPTION:
Mapping XS fafbcb91
END DESCRIPTION:
XS GIS Cut Line= 3
      2351518.32      7076730.39      2351508.56      7076412.49
      2351509.62      7076363.75
#Sta/Elev= 30
  4679.5  616.74  4682.2  616.74  4689.9  616.17  4739.9  613.75  4779.9  611.93
  4789.9  611.64    4810  610.82  4817.6  610.17  4822.6   610.2    4830  609.82
    4840  609.48    4850  609.31    4860  608.99    4890  608.54    4910  608.01
    4930  607.78    4940  607.92    4960  607.18    4970  606.92    4980  606.24
    4990  604.13    4991  601.37  4992.4  600.87  5000.1  600.87  5001.6  601.37
    5010  601.73    5020  604.04    5030  608.32    5040   614.1  5046.3  613.38
#Mann= 3 ,-1 , 0
  4679.5     .05       0    4990    .033       0    5020     .05       0
Bank Sta=4990,5020
XS Rating Curve= 0 ,0
Exp/Cntr=0.3,0.1

Type RM Length L Ch R = 1 ,9196    ,385,385,385
BEGIN DESCRIPTION:
Mapping XS 18dbf2de
END DESCRIPTION:
XS GIS Cut Line= 4
      2351773.96      7076802.79      2351802.61      7076563.21
      2351727.09      7076401.75      2351617.74       7076367.9
#Sta/Elev= 30
  4755.7  628.07  4842.2  623.17  4889.4  619.09  4899.5  618.03  4919.5  614.43
  4924.6  613.98  4929.7  612.63  4939.8  611.06  4959.9  609.27  4980.1  605.93
  4990.1  604.73  4996.1  602.31  5006.3  602.04  5007.7  601.54  5015.4  601.54
  5017.2  602.27  5022.7  602.91  5055.7  603.78  5062.9  605.09  5068.4  604.88
  5077.8  605.73  5114.1  606.67    5122  607.42  5136.9  609.88    5144  610.19
  5173.4  610.45  5198.7  611.17    5257  613.22    5264  613.86  5289.7  614.85
#Mann= 3 ,-1 , 0
  4755.7     .05       0  4990.1    .033       0  5062.9     .05       0
Bank Sta=4990.1,5062.9
XS Rating Curve= 0 ,0
Exp/Cntr=0.3,0.1

Type RM Length L Ch R = 1 ,8811    ,457,457,457
BEGIN DESCRIPTION:
Mapping XS e352edd5
END DESCRIPTION:
XS GIS Cut Line= 3
      2352370.34       7076430.4      2352076.05      7076354.87
      2351662.98      7076354.87
#Sta/Elev= 30
  4700.1  638.56    4815  638.99  4856.3  638.63  4866.7  636.94    4877  634.52
  4882.4  631.06  4887.6  631.63    4908  627.91    4918  625.54  4923.2  625.97
  4928.6  624.36  4949.3  622.22    4964   619.7  4980.2  611.63  4999.6  603.58
  5003.7  603.78    5011  598.73  5015.6  598.58  5017.1  598.08  5024.9  598.08
    5031  601.16    5041  602.57    5061  602.85    5091  604.76    5131  605.69
    5171  606.18    5251  605.86    5301  606.92    5311  606.77    5417  612.92
#Mann= 3 ,-1 , 0
  4700.1     .05       0  5003.7    .033       0    5041     .05       0
Bank Sta=5003.7,5041
XS Rating Curve= 0 ,0
Exp/Cntr=0.3,0.1

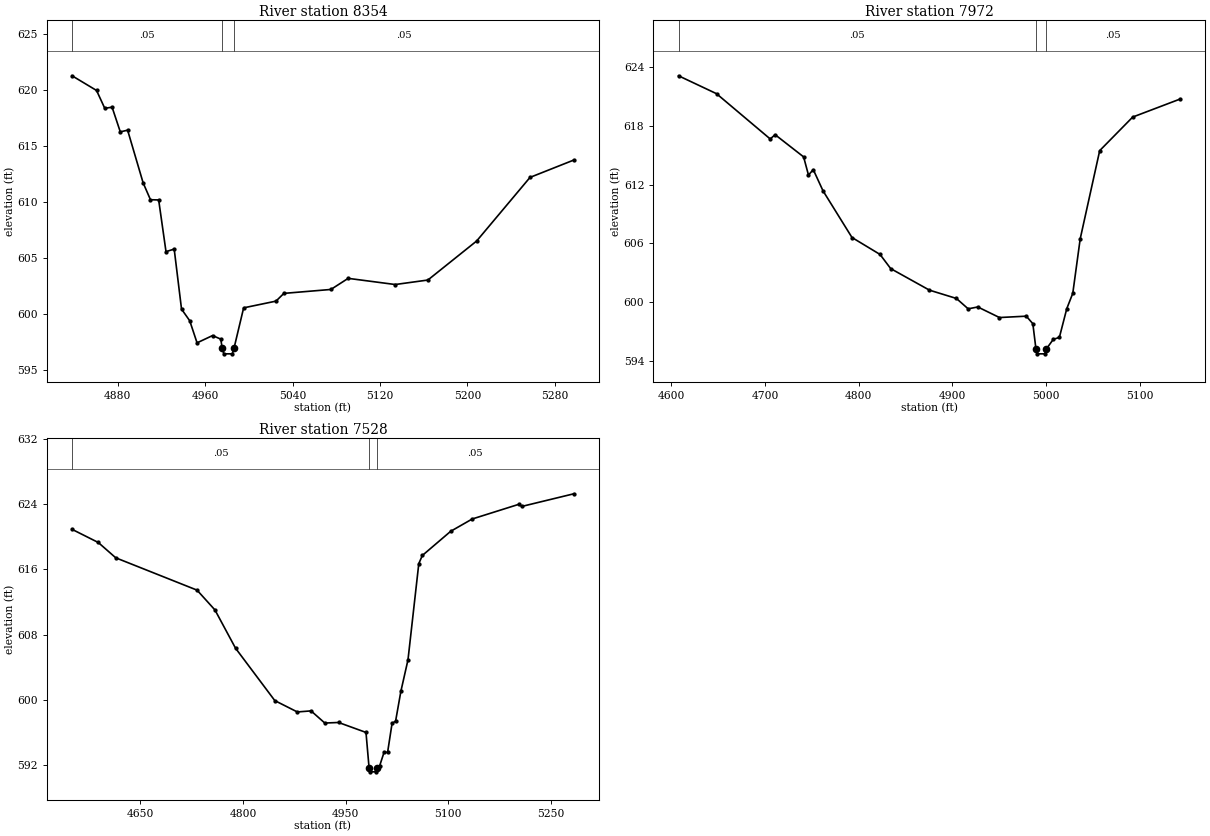
Type RM Length L Ch R = 1 ,8354    ,382,382,382
BEGIN DESCRIPTION:
Mapping XS b5a605ff
END DESCRIPTION:
XS GIS Cut Line= 3
      2351911.96      7075951.25      2351789.59       7076060.6
      2351641.37      7076315.43
#Sta/Elev= 30
  4838.4  621.27  4860.8  619.96  4868.3  618.37    4875  618.47  4882.5  616.27
  4889.2  616.42  4903.4  611.72  4910.1  610.22  4917.6   610.2  4924.3  605.59
  4931.8  605.82  4938.5  600.47    4946  599.43  4952.7  597.46  4966.9  598.11
  4974.4  597.79  4975.7  596.98  4977.2  596.48    4985  596.48  4986.5  596.98
  4995.3  600.58  5024.9  601.18  5032.1  601.87  5075.1  602.22  5090.9  603.21
  5133.9  602.66  5163.8  603.06  5208.4  606.54  5257.2  612.21  5297.3  613.76
#Mann= 3 ,-1 , 0
  4838.4     .05       0  4975.7    .033       0  4986.5     .05       0
Bank Sta=4975.7,4986.5
XS Rating Curve= 0 ,0
Exp/Cntr=0.3,0.1

Type RM Length L Ch R = 1 ,7972    ,444,444,444
BEGIN DESCRIPTION:
Mapping XS 29995720
END DESCRIPTION:
XS GIS Cut Line= 3
       2351818.2      7075870.51      2351443.23      7075966.85
      2351349.48      7076081.44
#Sta/Elev= 30
  4607.9  623.14  4648.4  621.31  4705.7  616.68  4710.9  617.12  4741.3  614.85
  4746.5  612.99  4751.6  613.55    4762  611.38  4792.9  606.61  4822.8  604.88
  4834.2  603.43  4875.5  601.23  4904.3  600.38  4916.8  599.32  4927.1  599.51
  4950.2  598.43  4978.8  598.57  4985.8   597.8  4989.1  595.22  4990.7  594.72
  4998.7  594.72  5000.2  595.22  5007.6   596.2  5014.1   596.4    5022  599.34
  5028.4  600.91  5036.3  606.47  5057.1  615.49  5092.3  618.92  5143.1  620.77
#Mann= 3 ,-1 , 0
  4607.9     .05       0  4989.1    .033       0  5000.2     .05       0
Bank Sta=4989.1,5000.2
XS Rating Curve= 0 ,0
Exp/Cntr=0.3,0.1

Type RM Length L Ch R = 1 ,7528    ,258,258,258
BEGIN DESCRIPTION:
Mapping XS 98140d4f
END DESCRIPTION:
XS GIS Cut Line= 3
      2351727.14       7075620.5      2351271.36      7075581.44
      2351005.74      7075656.96
#Sta/Elev= 30
    4550  620.91  4588.3   619.3  4613.9  617.42  4732.7  613.46  4758.9  611.03
    4789  606.34  4846.4  599.92  4879.3  598.53  4899.4  598.66  4919.5  597.17
  4939.6  597.24  4979.7  596.02  4984.2  591.69  4985.7  591.19  4993.7  591.19
  4995.3  591.69  4999.8  591.96  5006.1  593.58  5011.3  593.58  5017.8  597.12
    5023  597.41  5030.7  601.06  5041.1  604.92  5056.9  616.71  5062.1  617.71
  5103.5  620.67    5135  622.18  5202.8  623.97    5208  623.73  5283.6  625.27
#Mann= 3 ,-1 , 0
    4550     .05       0  4984.2    .033       0  4995.3     .05       0
Bank Sta=4984.2,4995.3
XS Rating Curve= 0 ,0
Exp/Cntr=0.3,0.1