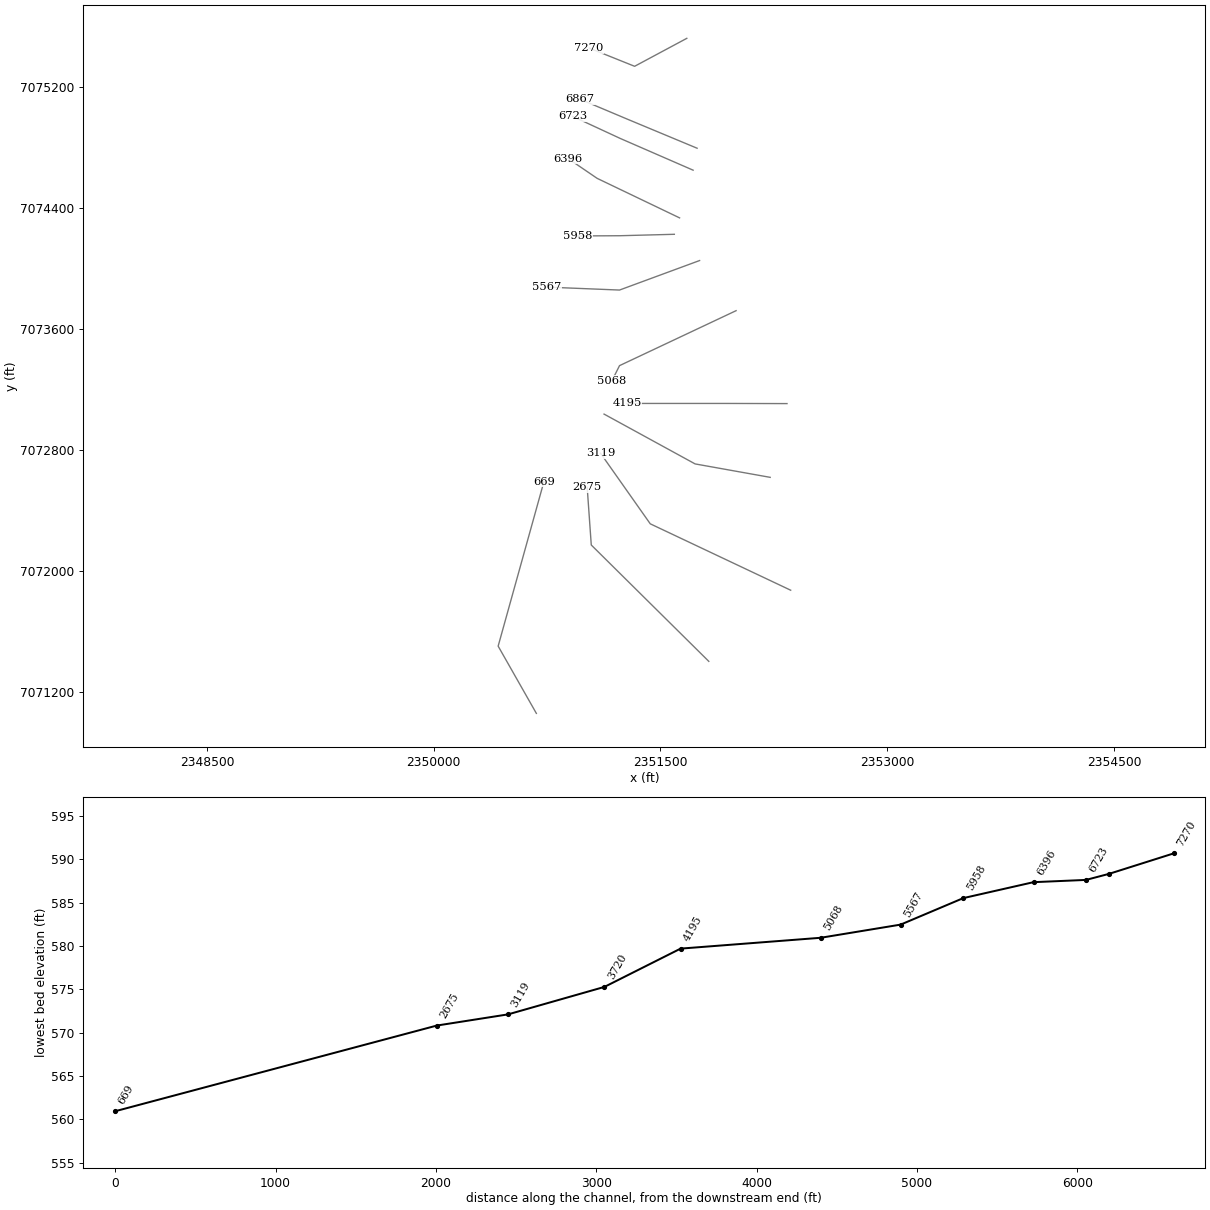
HEC-RAS study Denton Creek Tr 7.prj: Denton Creek Tr 7 Base Level Engineering

--- Denton Creek Tr 7.g01 (geometry) --- (continued)

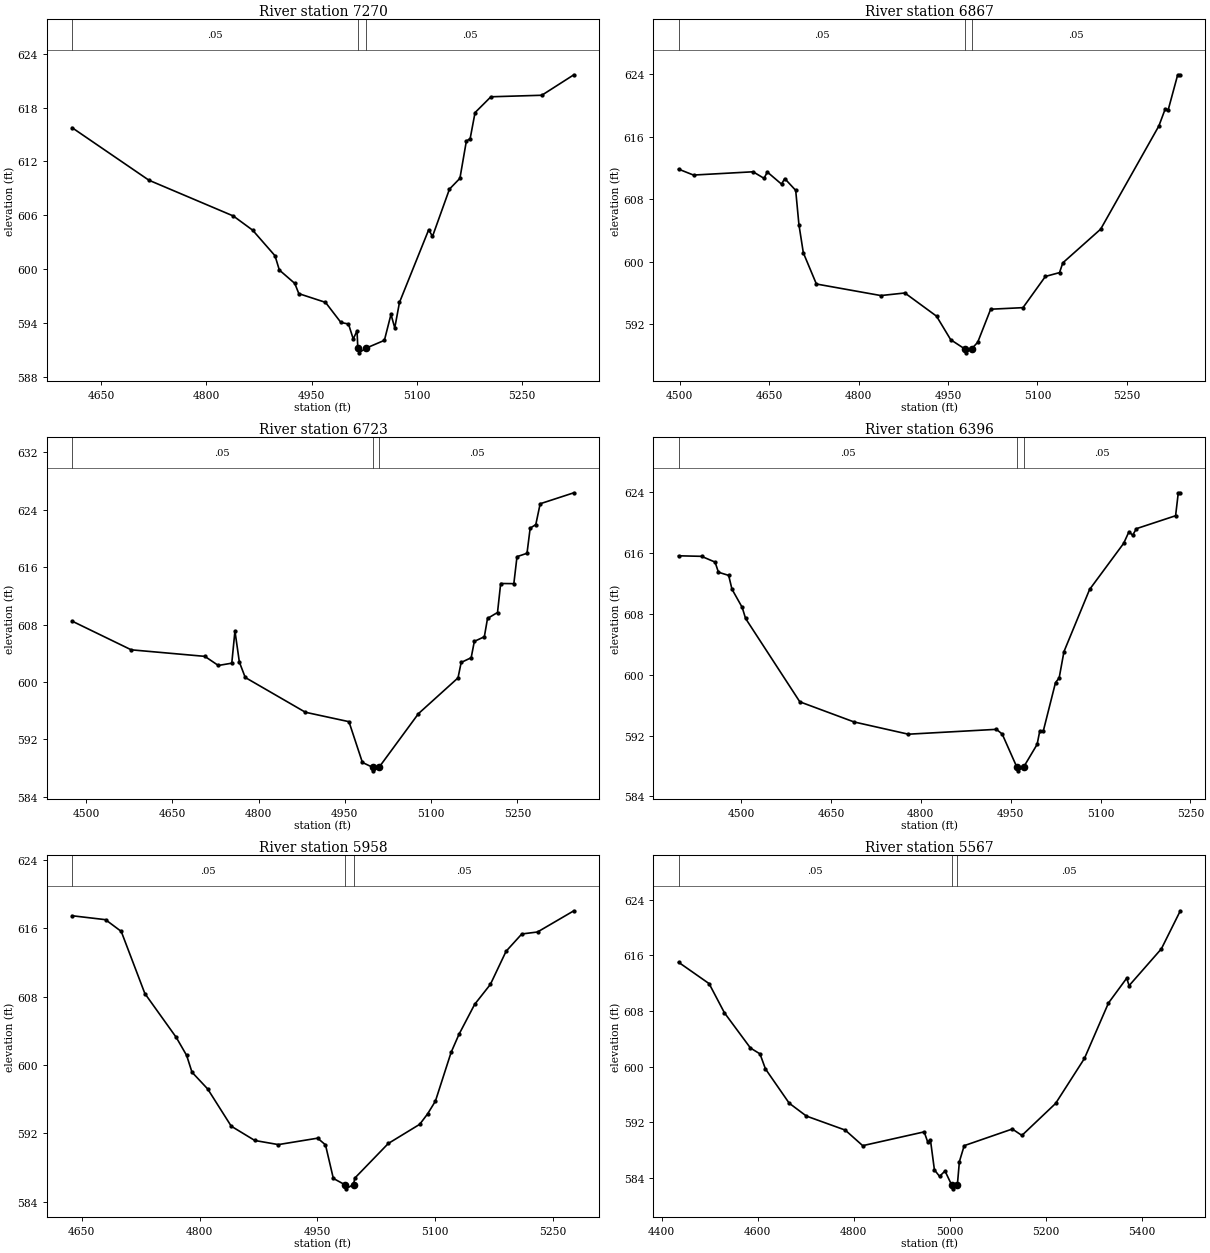
Type RM Length L Ch R = 1 ,7270    ,403,403,403
BEGIN DESCRIPTION:
Denton Creek Tr 7 11.0
END DESCRIPTION:
XS GIS Cut Line= 3
      2351674.09       7075524.9      2351328.91      7075339.96
      2351028.23      7075460.67
#Sta/Elev= 30
  4608.4  615.76    4718  609.91  4838.3  605.93  4865.9  604.35  4897.8   601.5
    4904  599.91    4926  598.42  4931.8  597.28  4969.8  596.31  4991.8  594.07
  5002.6   593.9  5009.4  592.23  5014.8  593.15  5015.9  591.19  5017.5  590.69
    5027  591.19  5053.8  592.08  5063.2  594.97  5068.6  593.47  5075.3   596.3
    5117   604.4  5122.4  603.65  5146.6  608.92  5161.5  610.12  5170.7  614.27
  5176.1  614.54  5183.1  617.44  5205.7   619.2  5278.3  619.37    5324  621.65
#Mann= 3 ,-1 , 0
  4608.4     .05       0  5015.9    .033       0    5027     .05       0
Bank Sta=5015.9,5027
XS Rating Curve= 0 ,0
Exp/Cntr=0.3,0.1

Type RM Length L Ch R = 1 ,6867    ,144,144,144
BEGIN DESCRIPTION:
Denton Creek Tr 7 10.0
END DESCRIPTION:
XS GIS Cut Line= 3
      2351742.18      7074798.06      2351284.01      7074988.97
      2350965.85      7075123.03
#Sta/Elev= 30
  4498.1  611.87  4523.2  611.11  4623.1  611.53  4641.5  610.69    4647   611.5
  4670.8  609.95  4676.2  610.66  4694.6  609.15    4700  604.77  4707.4  601.15
  4729.3  597.15  4837.4  595.67  4877.7     596  4930.8  593.03  4954.6  590.01
  4978.2  588.83  4979.8  588.33  4989.6  588.83  4999.9  589.69  5021.6  593.92
  5075.8  594.12  5113.4  598.12  5137.1  598.61  5142.6  599.86  5206.1  604.18
  5303.7   617.4  5314.1  619.53  5319.5   619.5  5335.3  623.96  5339.7  623.96
#Mann= 3 ,-1 , 0
  4498.1     .05       0  4978.2    .033       0  4989.6     .05       0
Bank Sta=4978.2,4989.6
XS Rating Curve= 0 ,0
Exp/Cntr=0.3,0.1

Type RM Length L Ch R = 1 ,6723    ,327,327,327
BEGIN DESCRIPTION:
Denton Creek Tr 7 9.5
END DESCRIPTION:
XS GIS Cut Line= 3
      2351715.83      7074652.84      2351234.95      7074862.25
      2350918.95      7075008.74
#Sta/Elev= 30
  4475.5  608.49  4578.4  604.49  4706.4  603.58  4729.9  602.31  4753.3  602.63
  4758.8  607.11  4766.5  602.78  4776.7  600.64  4881.4  595.79  4957.1  594.48
  4980.5   588.8  4998.1  588.13  4999.7  587.63  5009.5  588.13    5078   595.6
  5146.8  600.58  5152.3  602.73  5169.7  603.39  5175.2  605.67  5192.6  606.31
  5198.1  608.86  5215.5  609.69    5221  613.73  5243.9  613.71  5249.4  617.47
  5266.8  617.94  5272.3  621.44  5282.1  621.94  5289.7  624.84  5348.3  626.37
#Mann= 3 ,-1 , 0
  4475.5     .05       0  4998.1    .033       0  5009.5     .05       0
Bank Sta=4998.1,5009.5
XS Rating Curve= 0 ,0
Exp/Cntr=0.3,0.1

Type RM Length L Ch R = 1 ,6396    ,438,438,438
BEGIN DESCRIPTION:
Denton Creek Tr 7 9.0
END DESCRIPTION:
XS GIS Cut Line= 3
      2351626.31      7074337.31      2351081.15      7074598.73
      2350888.47       7074730.1
#Sta/Elev= 30
  4395.4  615.66  4433.8  615.59  4456.4  614.83    4462   613.5  4479.1  613.08
  4484.6  611.27  4501.7  608.87  4507.3  607.42  4597.9  596.45  4688.5   593.8
  4779.1  592.19  4926.1  592.83  4935.8  592.21  4960.2  587.87  4961.8  587.37
  4971.6  587.87  4994.1  590.85  4998.4  592.57  5004.3  592.57  5024.8  598.98
  5030.9  599.59  5038.9  603.05  5081.7  611.23  5138.6   617.3  5147.5  618.84
  5153.5  618.36  5159.9  619.23  5225.3  620.93  5229.8  623.95  5233.2  623.95
#Mann= 3 ,-1 , 0
  4395.4     .05       0  4960.2    .033       0  4971.6     .05       0
Bank Sta=4960.2,4971.6
XS Rating Curve= 0 ,0
Exp/Cntr=0.3,0.1

Type RM Length L Ch R = 1 ,5958    ,391,391,391
BEGIN DESCRIPTION:
Denton Creek Tr 7 8.0
END DESCRIPTION:
XS GIS Cut Line= 3
      2351591.62      7074228.78      2351229.45      7074219.28
      2350952.75      7074217.94
#Sta/Elev= 30
  4637.7  617.44  4680.3  616.98  4700.3  615.61  4730.4  608.35  4770.4  603.22
  4783.6  601.12  4790.4  599.16  4810.4   597.2  4840.4  592.85  4870.4  591.18
  4900.4   590.7  4950.4  591.45  4960.4  590.67  4970.4  586.75  4984.7  586.03
  4986.3  585.53  4996.1  586.03  4997.7  586.78  5040.4  590.83  5080.4  593.07
  5090.4  594.28  5100.4  595.78  5120.4  601.48  5130.4  603.58  5150.4  607.09
  5170.4  609.42  5190.4  613.29  5210.4  615.31  5230.4  615.54  5276.7  618.02
#Mann= 3 ,-1 , 0
  4637.7     .05       0  4984.7    .033       0  4996.1     .05       0
Bank Sta=4984.7,4996.1
XS Rating Curve= 0 ,0
Exp/Cntr=0.3,0.1

Type RM Length L Ch R = 1 ,5567    ,499,499,499
BEGIN DESCRIPTION:
Denton Creek Tr 7 7.0
END DESCRIPTION:
XS GIS Cut Line= 3
       2351758.7      7074055.17        2351229.        7073860.
      2350749.61      7073879.39
#Sta/Elev= 30
  4435.1  615.01  4498.7  611.94  4530.7  607.74  4584.8  602.69  4604.6  601.85
    4616  599.69  4665.4  594.77  4701.2  592.92  4781.9  590.91  4818.4  588.67
  4946.3  590.65  4953.9  589.15  4959.3  589.52  4967.6   585.2  4978.3  584.26
  4989.7  585.03  5003.9  582.97  5005.5  582.47  5015.3  582.97  5019.6  586.38
  5029.6  588.67  5129.7  591.06  5149.7  590.14  5219.8  594.73  5279.8  601.19
  5329.9  609.16  5367.8  612.72  5372.8  611.65    5440  616.94  5479.4   622.4
#Mann= 3 ,-1 , 0
  4435.1     .05       0  5003.9    .033       0  5015.3     .05       0
Bank Sta=5003.9,5015.3
XS Rating Curve= 0 ,0
Exp/Cntr=0.3,0.1

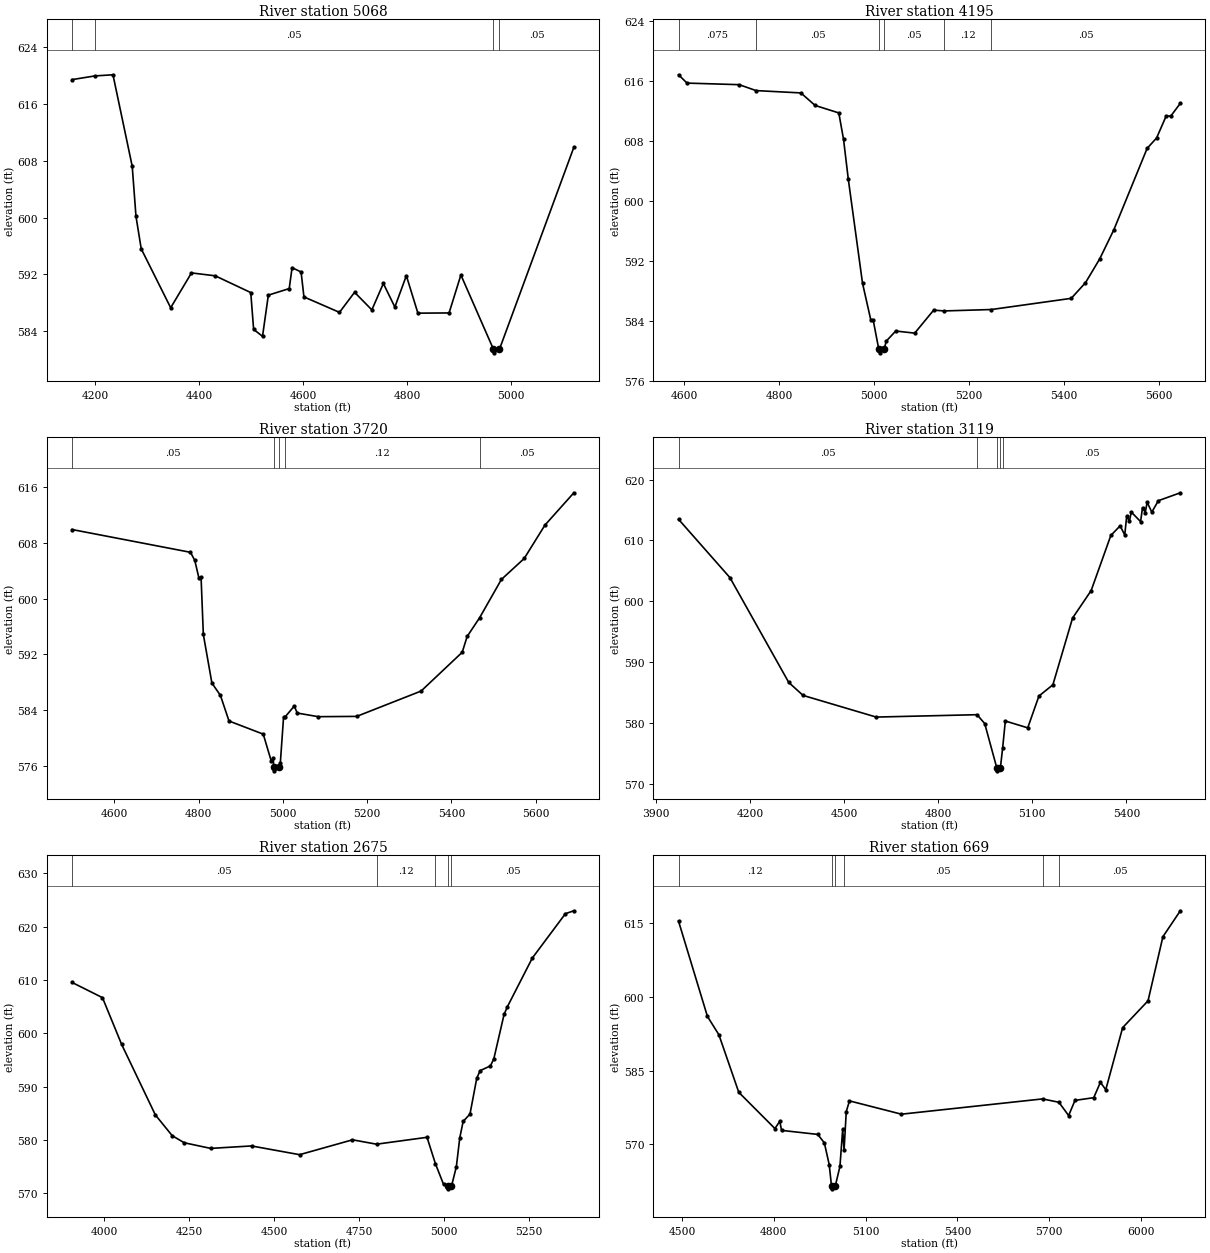
Type RM Length L Ch R = 1 ,5068    ,873,873,873
BEGIN DESCRIPTION:
Denton Creek Tr 7 6.0
END DESCRIPTION:
XS GIS Cut Line= 3
      2352000.08       7073723.6        2351229.        7073360.
      2351179.01      7073260.01
#Sta/Elev= 30
    4156  619.44    4200  619.96  4234.6  620.12  4271.6  607.23  4278.8  600.19
  4288.9   595.6  4345.5   587.3  4385.5  592.21  4431.1   591.8  4499.4  589.44
  4504.9  584.25    4522  583.28  4533.2  589.08  4573.3     590  4578.8  592.95
  4596.1  592.34  4601.6  588.83  4669.9  586.65  4698.9  589.48  4732.1     587
  4754.2  590.72  4776.3   587.4  4798.4  591.82  4820.6  586.54  4880.5  586.57
  4903.2  591.92  4965.8  581.45  4967.4  580.95  4977.3  581.45  5120.3  609.91
#Mann= 4 ,-1 , 0
    4156      .1       0    4200     .05       0  4965.8    .033       0
  4977.3     .05       0
Bank Sta=4965.8,4977.3
XS Rating Curve= 0 ,0
Exp/Cntr=0.3,0.1

Type RM Length L Ch R = 1 ,4195    ,475,475,475
BEGIN DESCRIPTION:
Denton Creek Tr 7 5.0
END DESCRIPTION:
XS GIS Cut Line= 3
      2352336.89      7073108.99        2351929.        7073110.
      2351278.99        7073110.
#Sta/Elev= 30
  4587.6   616.8  4605.5  615.69  4715.5  615.48  4751.1  614.69  4845.5  614.38
  4875.5  612.71  4925.5  611.71  4935.5  608.17  4945.5  602.87  4975.5  588.98
    4993  584.07    4998  584.07  5009.7   580.2  5011.3   579.7  5021.3   580.2
  5025.5  581.26  5045.5  582.61  5085.5  582.33  5125.5   585.4  5147.4  585.29
  5247.3  585.48  5415.5  586.97  5445.5  589.05  5475.5  592.23  5505.5  596.14
  5575.5  606.98  5595.5  608.37  5615.5  611.28  5625.5   611.3  5645.5  612.99
#Mann= 6 ,-1 , 0
  4587.6    .075       0  4751.1     .05       0  5009.7    .033       0
  5021.3     .05       0  5147.4     .12       0  5247.3     .05       0
Bank Sta=5009.7,5021.3
XS Rating Curve= 0 ,0
Exp/Cntr=0.3,0.1

Type RM Length L Ch R = 1 ,3720    ,601,601,601
BEGIN DESCRIPTION:
Denton Creek Tr 7 4.0
END DESCRIPTION:
XS GIS Cut Line= 3
       2352225.7      7072621.15        2351729.        7072710.
      2351126.76      7073039.55
#Sta/Elev= 30
  4499.4  609.94  4780.5  606.67  4790.7   605.5  4800.5  602.97  4805.6   603.1
    4811  594.87  4831.3  587.89  4851.6  586.11  4871.9  582.44  4953.2  580.55
    4972  576.73  4977.1  577.08  4977.9  575.78  4979.5  575.28  4989.5  575.78
  4993.8  576.46  5001.4  582.96  5004.1  582.96  5026.8  584.58  5033.9  583.58
  5083.8  583.06    5175   583.1  5327.9  586.74  5425.5  592.31  5437.2  594.58
  5466.8  597.27  5518.5  602.77  5572.6  605.78  5621.9  610.58  5690.5  615.22
#Mann= 5 ,-1 , 0
  4499.4     .05       0  4977.9    .033       0  4989.5     .05       0
  5004.1     .12       0  5466.8     .05       0
Bank Sta=4977.9,4989.5
XS Rating Curve= 0 ,0
Exp/Cntr=0.3,0.1

Type RM Length L Ch R = 1 ,3119    ,444,444,444
BEGIN DESCRIPTION:
Denton Creek Tr 7 3.0
END DESCRIPTION:
XS GIS Cut Line= 3
      2352361.15      7071874.62      2351432.34      7072313.79
      2351103.01      7072781.22
#Sta/Elev= 30
  3972.6  613.46  4136.3  603.88  4323.9  586.64  4369.4  584.51  4602.5  580.95
  4923.9  581.34  4948.4  579.88  4986.8  572.61  4988.4  572.11  4998.4  572.61
  5005.5  575.87  5014.1   580.3  5085.5  579.18  5121.2  584.41  5165.6  586.25
  5228.4  597.23  5287.6  601.74  5350.3   610.8  5379.9  612.38  5394.7  610.89
  5400.8  613.97  5409.5  613.17  5415.6  614.65  5445.2  613.08  5451.3  615.38
    5460  614.57  5466.1  616.26  5480.9  614.64  5501.8  616.52  5571.8  617.82
#Mann= 5 ,-1 , 0
  3972.6     .05       0  4923.9     .12       0  4986.8     .07       0
  4998.4     .12       0  5005.5     .05       0
Bank Sta=4986.8,4998.4
XS Rating Curve= 0 ,0
Exp/Cntr=0.3,0.1

Type RM Length L Ch R = 1 ,2675    ,2006,2006,2006
BEGIN DESCRIPTION:
Denton Creek Tr 7 2.0
END DESCRIPTION:
XS GIS Cut Line= 3
      2351819.52       7071404.1      2351042.21      7072173.64
      2351015.23      7072554.78
#Sta/Elev= 30
  3906.2  609.55  3995.6   606.7  4052.1  597.91  4151.1   584.7  4200.7   580.8
    4236  579.47  4313.8  578.41    4434  578.87  4575.4  577.23    4731  580.02
  4801.7   579.2  4950.2  580.49    4975  575.52  4998.7  571.68  5010.6  571.32
  5012.2  570.82  5022.2  571.32  5036.5  574.98  5046.5  580.39  5056.5  583.47
  5076.6  584.86  5096.6  591.61  5106.6  593.01  5136.7  593.89  5146.7  595.22
  5176.8  603.54  5186.8  605.02  5259.9  614.13  5357.3  622.46  5382.1     623
#Mann= 5 ,-1 , 0
  3906.2     .05       0  4801.7     .12       0    4975     .05       0
  5010.6    .033       0  5022.2     .05       0
Bank Sta=5010.6,5022.2
XS Rating Curve= 0 ,0
Exp/Cntr=0.3,0.1

Type RM Length L Ch R = 1 ,669     ,0,0,0
BEGIN DESCRIPTION:
Denton Creek Tr 7 1.0
END DESCRIPTION:
XS GIS Cut Line= 3
        2350679.      7071060.01      2350426.28      7071504.72
      2350728.77      7072591.61
#Sta/Elev= 30
  4488.5  615.46  4582.9  596.06  4620.4  592.32  4685.3   580.6  4803.5  573.21
  4819.4   574.7  4825.1  572.84  4943.4  572.02    4965  570.29  4980.8  565.88
  4988.5  561.43  4990.1  560.93  5000.4  561.43  5015.9  565.49  5024.9  573.06
  5029.4  568.82  5036.6  576.67    5047  578.85  5216.8  576.14  5677.9  579.25
  5731.4  578.57  5763.2  575.86    5784  578.95  5845.2   579.5    5867  582.62
  5884.6  581.13  5939.7  593.77  6022.7  599.24  6071.3   612.3  6128.2  617.58
#Mann= 6 ,-1 , 0
  4488.5     .12       0  4988.5     .07       0  5000.4     .12       0
  5029.4     .05       0  5677.9     .12       0  5731.4     .05       0
Bank Sta=4988.5,5000.4
XS Rating Curve= 0 ,0
Exp/Cntr=0.3,0.1

Chan Stop Cuts=-1
Use User Specified Reach Order=0
Composite Channel Slope=5