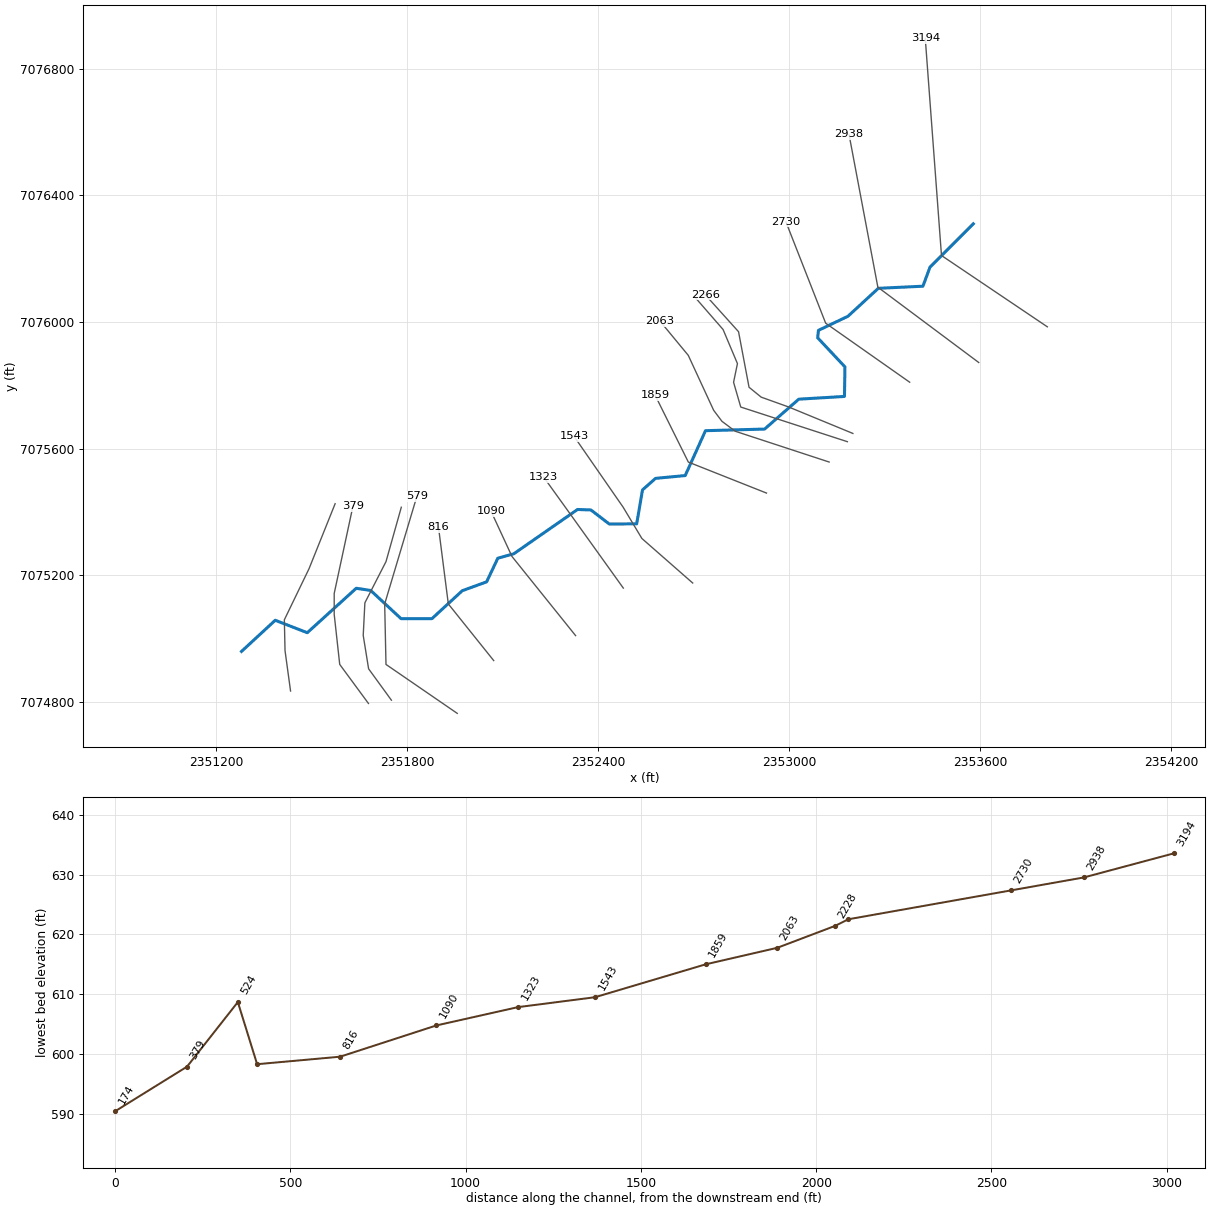
--- Denton Creek Tr 7_1.prj (project) ---

Proj Title=Denton Creek Tr 7_1 Base Level Engineering
Current Plan=p01
Default Exp/Contr=0.3,0.1
English Units
Geom File=g01
Flow File=f01
Plan File=p01
Y Axis Title=Elevation
X Axis Title(PF)=Main Channel Distance
X Axis Title(XS)=Station
BEGIN DESCRIPTION:
Denton Creek Tr 7_1
END DESCRIPTION:
DSS Export Rating Curves= 0
DSS Export Rating Curve Sorted= 0
DSS Export Volume Flow Curves= 0
DXF OffsetX= 0
DXF OffsetY= 0
DXF ScaleX= 1
DXF ScaleY= 10

--- Denton Creek Tr 7_1.p01 (plan) ---

Plan Title=Multiple Run
Short Identifier=Multiple
Geom File=g01
Flow File=f01
Subcritical Flow
K Sum by GR= 0
Std Step Tol= 0.01
Critical Tol= 0.01
Num of Std Step Trials= 20
Max Error Tol= 0.3
Flow Tol Ratio= 0.001
Split Flow NTrial= 30
Split Flow Tol= 0.02
Split Flow Ratio= 0.02
Log Output Level= 0
Friction Slope Method= 1
Unsteady Friction Slope Method= 2
Unsteady Bridges Friction Slope Method= 1
Parabolic Critical Depth
Global Vel Dist=  1 , 1 , 1
Global Log Level= 0
CheckData=True
Encroach Param= -1, 0, 0, 0
BEGIN DESCRIPTION:
Multiple Run
END DESCRIPTION:

--- Denton Creek Tr 7_1.f01 (steady flow) ---

Flow Title=Multiple
Number of Profiles=7
Profile Names=10-year,25-year,50-year,1pct_min,100-year,1pct_plu,500-year
River Rch & RM= Denton Creek Tr ,Reach-1,3194
     333     441     528     315     628    1252     888
Boundary for River Rch & Prof#=Denton Creek Tr ,Reach-1,1
Up Type=0
Dn Type=3
Dn Slope=0.005
Boundary for River Rch & Prof#=Denton Creek Tr ,Reach-1,2
Up Type=0
Dn Type=3
Dn Slope=0.005
Boundary for River Rch & Prof#=Denton Creek Tr ,Reach-1,3
Up Type=0
Dn Type=3
Dn Slope=0.005
Boundary for River Rch & Prof#=Denton Creek Tr ,Reach-1,4
Up Type=0
Dn Type=3
Dn Slope=0.005
Boundary for River Rch & Prof#=Denton Creek Tr ,Reach-1,5
Up Type=0
Dn Type=3
Dn Slope=0.005
Boundary for River Rch & Prof#=Denton Creek Tr ,Reach-1,6
Up Type=0
Dn Type=3
Dn Slope=0.005
Boundary for River Rch & Prof#=Denton Creek Tr ,Reach-1,7
Up Type=0
Dn Type=3
Dn Slope=0.005

--- Denton Creek Tr 7_1.g01 (geometry) ---

Geom Title=Existing Conditions
Program Version=4.10

River Reach=Denton Creek Tr ,Reach-1
Reach XY= 30
        2353579.        7076310.      2353442.73      7076172.95
       2353420.7      7076113.08      2353280.48      7076106.44
        2353185.      7076018.18      2353092.27      7075973.69
      2353089.92      7075950.14      2353175.55      7075858.42
      2353174.08      7075765.04      2353030.48      7075756.44
      2352923.14      7075662.07      2352737.28      7075656.94
      2352673.55      7075515.25      2352580.33      7075506.45
      2352539.39      7075470.11      2352520.99      7075362.84
      2352435.06      7075362.15      2352377.27      7075406.63
      2352335.11       7075408.2      2352134.74       7075268.3
      2352084.63      7075254.35      2352049.43      7075179.73
      2351972.98      7075151.81       2351877.5      7075063.47
       2351780.5      7075063.47      2351685.04      7075152.52
      2351639.64      7075159.45      2351485.73      7075019.15
      2351385.04       7075058.4        2351279.        7074960.

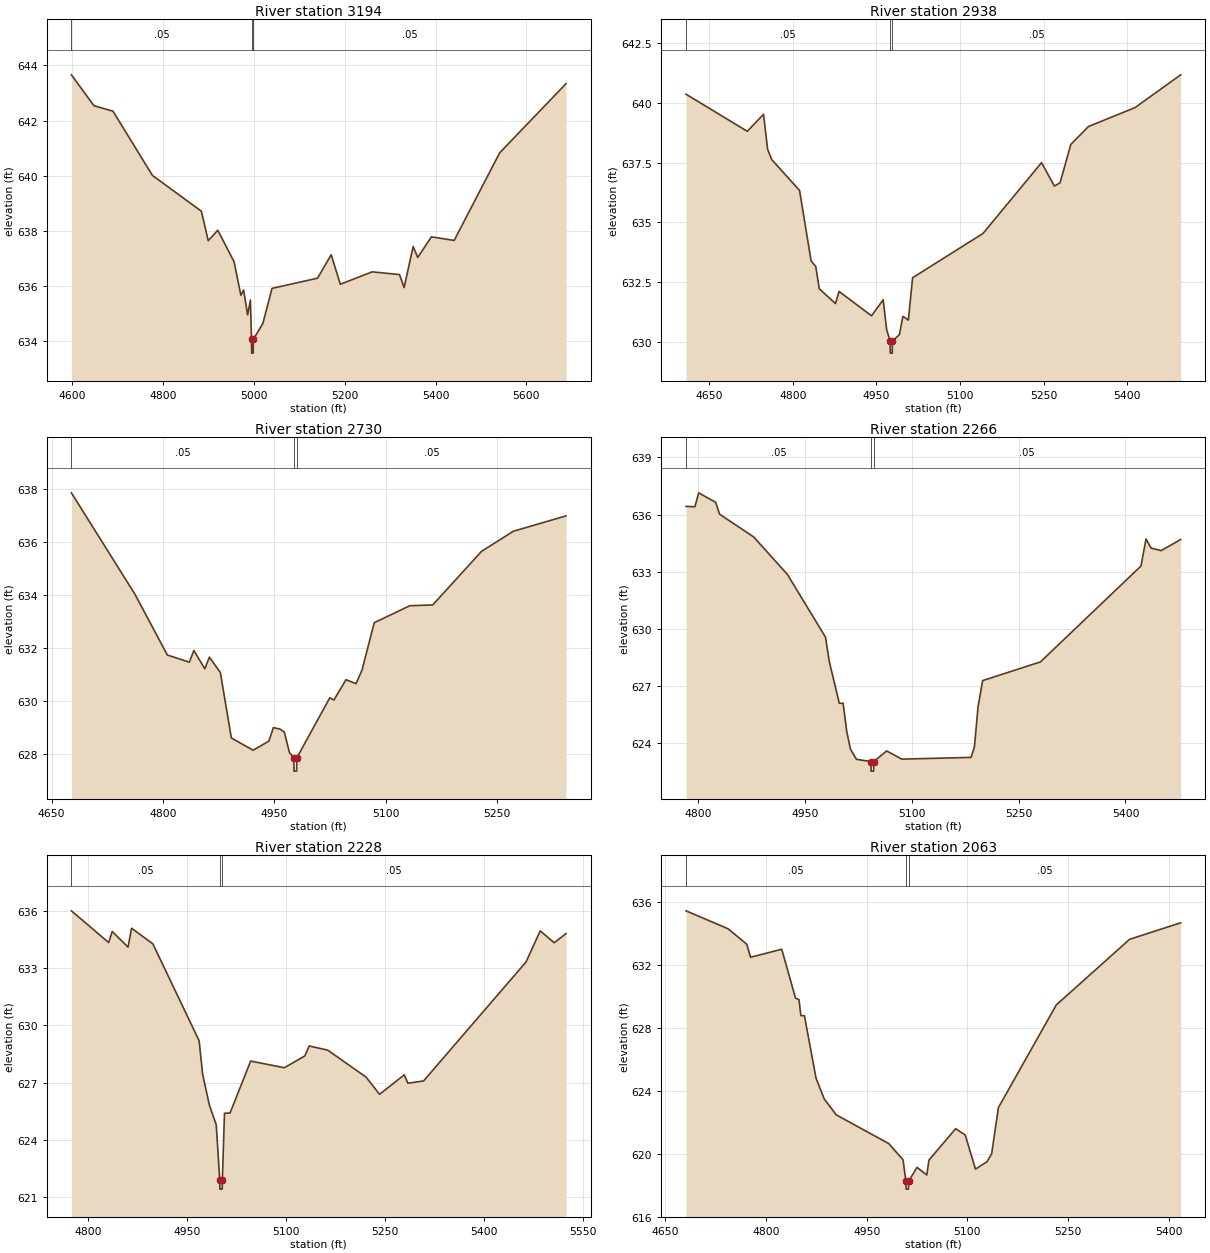
Type RM Length L Ch R = 1 ,3194    ,256,256,256
BEGIN DESCRIPTION:
Denton Creek Tr 7_1 12.0
END DESCRIPTION:
XS GIS Cut Line= 3
      2353811.65       7075984.9        2353479.        7076210.
      2353427.99      7076895.65
#Sta/Elev= 30
  4598.1  643.66  4647.7  642.54  4689.7  642.34  4776.5  640.01  4884.4  638.71
  4899.4  637.64  4920.4  638.02  4956.3  636.88  4971.3  635.66  4977.3  635.85
  4986.2  634.95  4992.3  635.49  4994.7  634.06    4995  633.56  4998.5  633.56
  4998.7  634.06  5019.8  634.64  5039.9  635.91  5140.1  636.28  5170.2  637.13
  5190.3  636.06  5260.5  636.51  5320.6  636.41  5330.7  635.94  5350.7  637.43
  5360.7  637.03  5390.8  637.78    5441  637.65  5541.2  640.83  5687.3  643.34
#Mann= 3 ,-1 , 0
  4598.1     .05       0  4994.7    .033       0  4998.7     .05       0
Bank Sta=4994.7,4998.7
XS Rating Curve= 0 ,0
Exp/Cntr=0.3,0.1

Type RM Length L Ch R = 1 ,2938    ,208,208,208
BEGIN DESCRIPTION:
Denton Creek Tr 7_1 11.0
END DESCRIPTION:
XS GIS Cut Line= 3
      2353596.01      7075872.24        2353279.        7076110.
      2353188.34      7076592.59
#Sta/Elev= 30
  4608.4  640.36  4718.2  638.81  4747.4  639.52  4754.7  638.06    4762  637.63
    4812  636.34  4832.8  633.39  4841.1  633.16  4847.4  632.23  4876.5  631.61
  4882.8  632.12  4941.1   631.1    4962  631.77  4968.2  630.53  4974.5  630.04
  4974.8  629.54  4978.3  629.54  4978.5  630.04  4991.1  630.31  4997.4  631.08
  5007.2  630.92  5014.8  632.69  5141.1  634.54  5246.1   637.5  5269.2  636.52
  5279.4  636.66  5298.6  638.26  5330.3  639.01  5413.8   639.8  5495.7  641.17
#Mann= 3 ,-1 , 0
  4608.4     .05       0  4974.5     .04       0  4978.5     .05       0
Bank Sta=4974.5,4978.5
XS Rating Curve= 0 ,0
Exp/Cntr=0.3,0.1

Type RM Length L Ch R = 1 ,2730    ,464,464,464
BEGIN DESCRIPTION:
Denton Creek Tr 7_1 10.0
END DESCRIPTION:
XS GIS Cut Line= 3
        2353379.        7075810.      2353114.94      7075996.37
      2352990.14      7076316.07
#Sta/Elev= 30
  4676.8  637.87  4762.5  634.04  4806.1  631.75  4835.7  631.48  4841.8  631.92
  4856.6  631.23  4862.7  631.67  4877.5  631.09  4892.3  628.62  4921.6  628.16
  4942.8   628.5  4948.9  629.01  4957.6  628.96  4963.7  628.84  4970.6  628.07
  4976.5  627.87  4976.7  627.37  4980.2  627.37  4980.5  627.87    5025  630.14
  5030.4  630.05  5046.8  630.82  5060.3  630.67  5068.3  631.18  5084.8  632.97
  5132.7  633.61  5163.6  633.64  5229.3  635.66  5272.2  636.42  5343.2     637
#Mann= 3 ,-1 , 0
  4676.8     .05       0  4976.5     .04       0  4980.5     .05       0
Bank Sta=4976.5,4980.5
XS Rating Curve= 0 ,0
Exp/Cntr=0.3,0.1

Type RM Length L Ch R = 1 ,2266    ,38,38,38
BEGIN DESCRIPTION:
Mapping XS 8dd5a6cd
END DESCRIPTION:
XS GIS Cut Line= 6
      2353200.55      7075648.25      2352999.15      7075731.59
      2352912.34      7075762.84      2352874.15      7075794.09
      2352841.16      7075969.44       2352736.4      7076086.22
#Sta/Elev= 30
  4782.7  636.43  4795.1  636.41  4800.5  637.14  4824.4  636.64  4829.8  636.02
  4877.6  634.83  4925.1  632.86  4978.6  629.57    4984  628.28    4998   626.1
  5003.4   626.1  5008.4  624.63  5013.7  623.69  5022.1  623.16  5042.4  623.04
  5042.7  622.54  5046.2  622.54  5046.4  623.04  5064.5   623.6  5085.9  623.17
  5183.1  623.26  5187.8   623.8  5192.9  625.91  5199.4  627.29  5280.6  628.27
  5421.8   633.3  5428.9  634.72    5436  634.24  5450.2  634.11  5477.6  634.69
#Mann= 3 ,-1 , 0
  4782.7     .05       0  5042.4    .033       0  5046.4     .05       0
Bank Sta=5042.4,5046.4
XS Rating Curve= 0 ,0
Exp/Cntr=0.3,0.1

Type RM Length L Ch R = 1 ,2228    ,165,165,165
BEGIN DESCRIPTION:
Mapping XS 369182a1
END DESCRIPTION:
XS GIS Cut Line= 6
      2353183.18      7075622.22      2352848.11      7075731.59
      2352825.54      7075809.72      2352837.69      7075868.75
      2352792.55      7075976.39      2352703.13      7076079.56
#Sta/Elev= 30
  4774.5  635.99    4831  634.33  4836.4  634.91  4860.3  634.09  4865.7  635.08
    4898  634.26  4968.1  629.19  4973.3  627.46  4983.6  625.83    4994   624.8
  4999.3  621.93  4999.5  621.43    5003  621.43  5003.3  621.93  5006.5   625.4
  5014.9  625.41  5046.2  628.13  5097.2  627.78  5128.4   628.4  5134.9  628.92
    5163   628.7  5221.1  627.29  5241.5  626.39    5279  627.41  5284.4  626.97
  5308.2  627.09  5463.4  633.31    5485  634.94  5506.2  634.32  5524.1   634.8
#Mann= 3 ,-1 , 0
  4774.5     .05       0  4999.3    .033       0  5003.3     .05       0
Bank Sta=4999.3,5003.3
XS Rating Curve= 0 ,0
Exp/Cntr=0.3,0.1

Type RM Length L Ch R = 1 ,2063    ,204,204,204
BEGIN DESCRIPTION:
Mapping XS 5c2a57b0
END DESCRIPTION:
XS GIS Cut Line= 6
      2353125.91      7075557.98      2352830.74      7075655.21
      2352789.08      7075686.46      2352763.04      7075721.18
      2352683.18      7075894.79       2352594.6      7076002.47
#Sta/Elev= 30
  4680.9  635.44  4743.5   634.3  4771.4  633.32    4777  632.49  4823.5     633
    4844   629.9  4849.2   629.8    4852  628.78  4857.3  628.78  4874.6  624.81
  4886.8  623.49  4904.7  622.48  4983.1  620.65  5004.3  619.62  5008.5  618.26
  5008.8  617.76  5012.3  617.76  5012.5  618.26  5025.1  619.14  5039.7  618.66
  5042.8   619.6  5082.7   621.6  5096.9   621.2  5112.2  619.03  5129.3   619.5
  5136.3     620  5146.4  622.94  5232.6  629.46  5341.9  633.63    5418  634.68
#Mann= 3 ,-1 , 0
  4680.9     .05       0  5008.5    .033       0  5012.5     .05       0
Bank Sta=5008.5,5012.5
XS Rating Curve= 0 ,0
Exp/Cntr=0.3,0.1

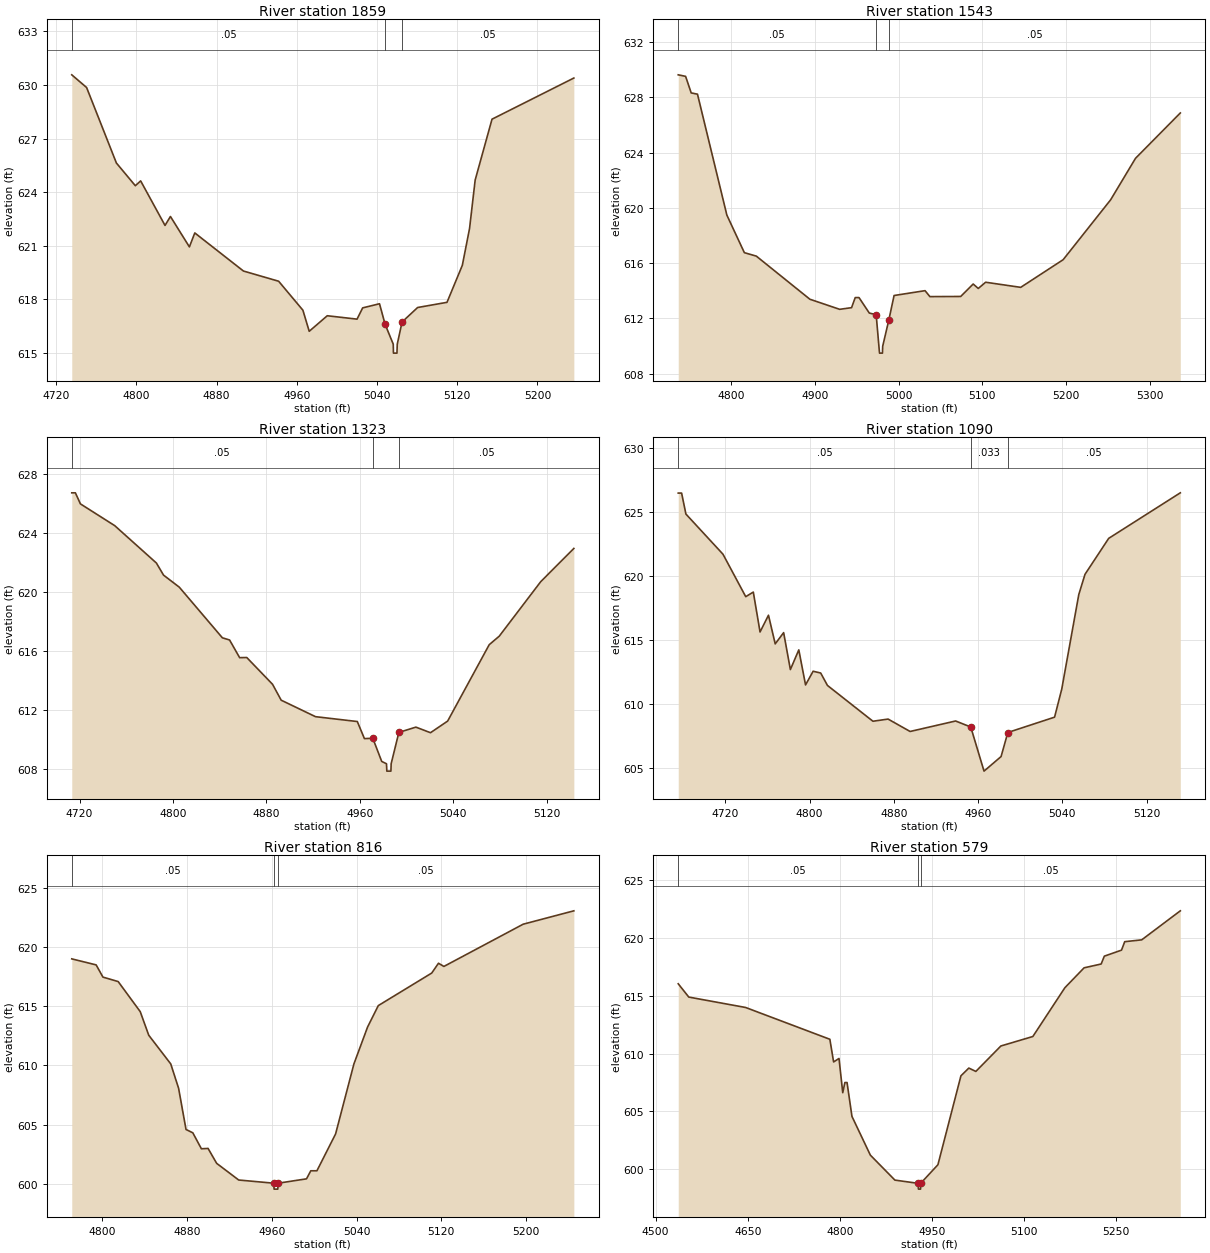
Type RM Length L Ch R = 1 ,1859    ,316,316,316
BEGIN DESCRIPTION:
Denton Creek Tr 7_1 7.0
END DESCRIPTION:
XS GIS Cut Line= 3
      2352928.98      7075460.01      2352683.35      7075557.86
       2352578.6      7075769.68
#Sta/Elev= 30
  4735.6  630.56  4750.4  629.85  4780.1  625.63    4799  624.36  4804.3  624.63
  4828.6  622.14    4834  622.64  4852.9  620.94  4858.3  621.72  4906.8  619.59
  4941.9  619.02  4966.1   617.4  4972.4  616.22  4990.4  617.09  5020.1   616.9
  5025.7  617.53  5042.5  617.76  5048.1  616.61  5056.2   615.5  5056.4     615
  5059.9     615  5060.2   615.5    5065  616.74  5080.5  617.55  5109.8  617.84
  5125.1  619.91  5132.3  621.97  5137.9  624.68  5154.7  628.08  5236.3  630.38
#Mann= 3 ,-1 , 0
  4735.6     .05       0  5048.1    .033       0    5065     .05       0
Bank Sta=5048.1,5065
XS Rating Curve= 0 ,0
Exp/Cntr=0.3,0.1

Type RM Length L Ch R = 1 ,1543    ,220,220,220
BEGIN DESCRIPTION:
Mapping XS 519cb647
END DESCRIPTION:
XS GIS Cut Line= 4
      2352697.04      7075176.06      2352537.34      7075316.66
      2352478.31      7075415.62      2352323.91      7075639.42
#Sta/Elev= 30
  4736.6  629.63  4745.4  629.52  4752.1  628.32  4759.6  628.23  4794.7  619.48
  4815.6  616.76  4829.9  616.51  4893.9  613.39  4929.5  612.66  4943.7  612.78
  4948.1  613.51  4952.6  613.51  4964.9  612.39  4973.1  612.27  4977.1  609.49
  4980.6  609.49  4980.9  609.99  4988.2  611.88  4994.5  613.66  5031.5  614.01
  5037.3  613.58  5074.1  613.59    5089  614.49  5095.1  614.17  5103.9  614.62
  5145.8  614.25  5196.5  616.25  5253.3  620.59    5283  623.59  5336.5  626.87
#Mann= 3 ,-1 , 0
  4736.6     .05       0  4973.1    .033       0  4988.2     .05       0
Bank Sta=4973.1,4988.2
XS Rating Curve= 0 ,0
Exp/Cntr=0.3,0.1

Type RM Length L Ch R = 1 ,1323    ,233,233,233
BEGIN DESCRIPTION:
Denton Creek Tr 7_1 5.0
END DESCRIPTION:
XS GIS Cut Line= 3
      2352478.99      7075160.02      2352312.48      7075393.41
        2352229.        7075510.
#Sta/Elev= 30
  4713.3  626.74  4716.4  626.74  4720.7  625.99  4750.1  624.51  4785.8  621.97
  4791.9  621.15  4805.4  620.33  4842.3  616.89  4848.5  616.74  4857.1  615.54
  4863.2  615.55  4885.3  613.73  4892.7  612.65  4922.1  611.53  4957.9   611.2
    4964  610.04  4971.2  610.06  4978.8  608.49  4982.9  608.33  4983.2  607.83
  4986.7  607.83  4986.9  608.33  4993.5  610.46  5008.1  610.82  5020.6  610.44
  5035.3  611.23  5070.9  616.42  5079.5     617  5115.1  620.71  5143.4  622.96
#Mann= 3 ,-1 , 0
  4713.3     .05       0  4971.2    .033       0  4993.5     .05       0
Bank Sta=4971.2,4993.5
XS Rating Curve= 0 ,0
Exp/Cntr=0.3,0.1

Type RM Length L Ch R = 1 ,1090    ,274,274,274
BEGIN DESCRIPTION:
Denton Creek Tr 7_1 4.0
END DESCRIPTION:
XS GIS Cut Line= 3
      2352329.03      7075009.96        2352129.        7075260.
      2352063.49      7075402.24
#Sta/Elev= 30
  4675.2   626.5  4678.4   626.5  4682.5  624.86  4717.7  621.72  4739.3   618.4
  4746.5  618.76  4752.9  615.64  4760.9  616.95  4767.3  614.71  4775.3  615.59
  4781.7   612.7  4789.7  614.24  4796.1   611.5  4803.3  612.57  4810.5  612.43
  4816.9  611.46  4860.1  608.66  4874.5  608.83  4895.4  607.86  4938.6  608.68
    4953  608.21  4965.6  604.76  4981.8   605.9  4988.2  607.78  5032.6  608.98
  5039.4  611.17  5055.6  618.57  5061.5  620.15    5084  622.96    5152  626.52
#Mann= 3 ,-1 , 0
  4675.2     .05       0    4953    .033       0  4988.2     .05       0
Bank Sta=4953,4988.2
XS Rating Curve= 0 ,0
Exp/Cntr=0.3,0.1

Type RM Length L Ch R = 1 ,816     ,237,237,237
BEGIN DESCRIPTION:
Denton Creek Tr 7_1 3.0
END DESCRIPTION:
XS GIS Cut Line= 3
      2352071.63      7074931.18        2351929.        7075110.
      2351898.04        7075353.
#Sta/Elev= 30
  4771.3     619  4794.3  618.49  4800.7  617.46  4815.1  617.08  4835.9  614.54
  4843.9  612.55  4864.7  610.12  4872.1  608.06  4879.1  604.58  4885.5   604.3
  4893.6  602.95  4899.9  602.98    4908  601.72  4928.8  600.31    4962  600.04
  4962.2  599.54  4965.7  599.54    4966  600.04  4992.8  600.41  4996.8  601.09
  5002.6  601.09  5020.2   604.2  5037.5  610.12  5050.4  613.24  5060.5  615.05
  5110.9   617.8  5117.3  618.63  5122.4  618.36  5197.2  621.93    5245  623.06
#Mann= 3 ,-1 , 0
  4771.3     .05       0    4962    .033       0    4966     .05       0
Bank Sta=4962,4966
XS Rating Curve= 0 ,0
Exp/Cntr=0.3,0.1

Type RM Length L Ch R = 1 ,579     ,55,55,55
BEGIN DESCRIPTION:
Denton Creek Tr 7_1 2.0
END DESCRIPTION:
XS GIS Cut Line= 4
      2351957.09      7074764.47      2351733.11        7074919.
        2351729.        7075110.      2351830.34      7075450.26
#Sta/Elev= 30
  4536.8  616.04    4554  614.89  4646.6  613.99  4783.9  611.24    4790  609.28
  4798.8  609.58  4804.9  606.62  4808.4   607.5  4811.9   607.5  4819.9  604.57
  4849.9  601.22  4889.9  599.06  4927.9  598.78  4928.2  598.28  4931.7  598.28
  4931.9  598.78    4960  600.39  4997.5  608.08  5010.4  608.75  5021.8  608.46
  5062.6  610.66  5114.7  611.48  5166.9   615.7  5198.2  617.42    5226  617.75
  5231.2  618.43  5259.2  618.95  5264.4  619.68  5292.1  619.84    5355  622.35
#Mann= 3 ,-1 , 0
  4536.8     .05       0  4927.9    .033       0  4931.9     .05       0
Bank Sta=4927.9,4931.9
XS Rating Curve= 0 ,0
Exp/Cntr=0.3,0.1

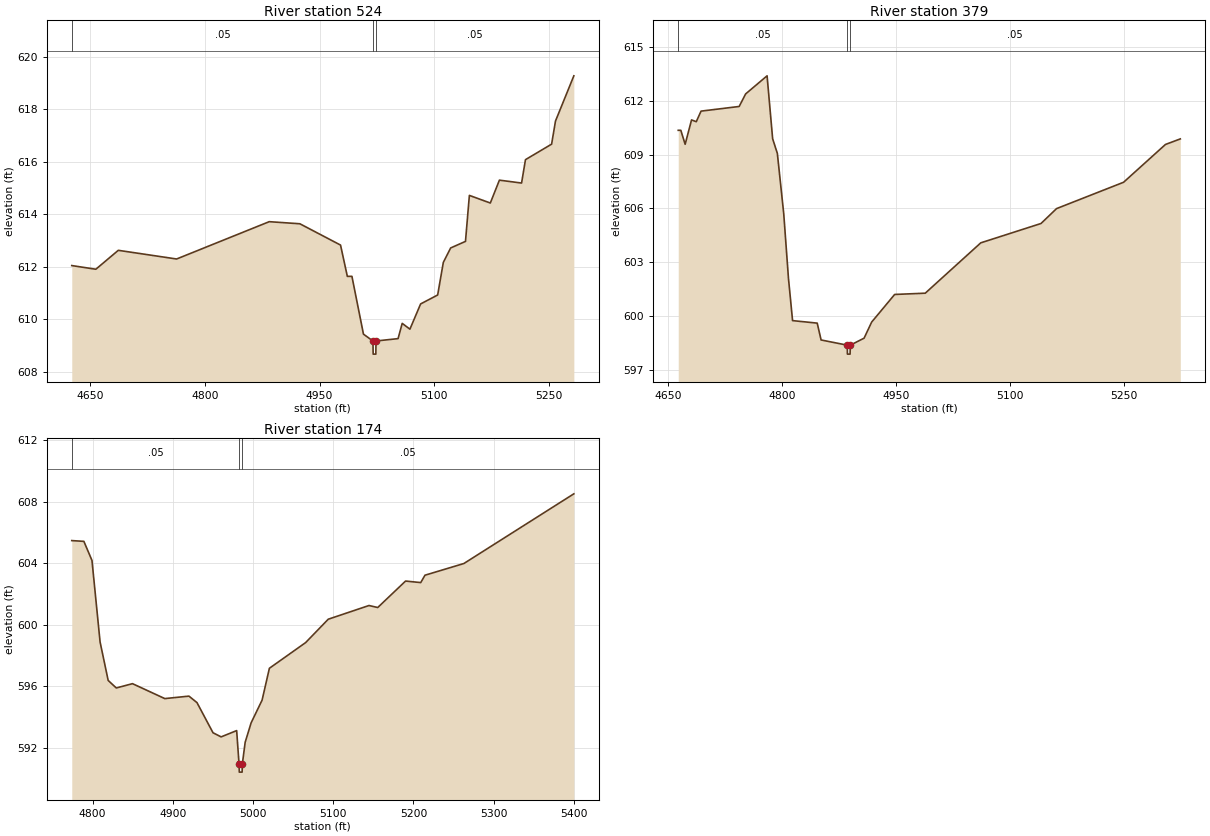
Type RM Length L Ch R = 1 ,524     ,145,145,145
BEGIN DESCRIPTION:
Mapping XS a3aaab03
END DESCRIPTION:
XS GIS Cut Line= 6
       2351750.1      7074806.18      2351678.48      7074905.15
      2351661.55      7075010.62      2351666.76      7075113.48
      2351733.17      7075243.69      2351781.25      7075415.25
#Sta/Elev= 30
  4625.8  612.05  4657.3  611.91  4686.7  612.63    4763   612.3  4884.2  613.72
  4924.3  613.64  4977.5  612.83  4986.4  611.64  4992.4  611.64  5007.5  609.44
  5019.9  609.18  5020.2  608.68  5023.7  608.68  5023.9  609.18  5052.8  609.27
  5058.2  609.85  5068.3  609.63  5082.3  610.59  5104.6  610.93    5112  612.17
  5121.6  612.72    5141  612.97  5146.1  614.72  5173.5  614.43  5185.4   615.3
  5214.4  615.19  5219.5  616.08  5253.7  616.67  5258.8  617.55  5282.8  619.27
#Mann= 3 ,-1 , 0
  4625.8     .05       0  5019.9    .033       0  5023.9     .05       0
Bank Sta=5019.9,5023.9
XS Rating Curve= 0 ,0
Exp/Cntr=0.3,0.1

Type RM Length L Ch R = 1 ,379     ,205,205,205
BEGIN DESCRIPTION:
Mapping XS 66938f8a
END DESCRIPTION:
XS GIS Cut Line= 5
      2351677.99       7074795.8      2351587.69      7074919.09
      2351570.33      7075077.08      2351570.33      7075143.05
      2351629.35      7075419.08
#Sta/Elev= 30
  4663.8  610.36  4667.2  610.36  4672.9  609.58  4681.3  610.94  4687.5  610.84
  4693.8  611.43  4743.9  611.69  4752.4  612.39  4780.6   613.4  4787.9  609.89
  4794.1  609.07  4802.5   605.7  4808.7   602.1  4814.1  599.74  4846.5   599.6
  4851.6  598.66    4886  598.37  4886.2  597.87  4889.7  597.87    4890  598.37
  4908.1  598.76  4918.1  599.66  4948.3   601.2  4988.5  601.27  5061.5  604.08
  5140.7  605.16  5161.1  605.99  5249.2  607.46  5304.3  609.57  5323.8  609.88
#Mann= 3 ,-1 , 0
  4663.8     .05       0    4886    .033       0    4890     .05       0
Bank Sta=4886,4890
XS Rating Curve= 0 ,0
Exp/Cntr=0.3,0.1

Type RM Length L Ch R = 1 ,174     ,0,0,0
BEGIN DESCRIPTION:
Denton Creek Tr 7_1 1.0
END DESCRIPTION:
XS GIS Cut Line= 5
      2351433.17      7074835.04      2351415.81       7074962.5
      2351413.65      7075059.84      2351491.25      7075221.23
      2351573.24      7075426.37
#Sta/Elev= 30
    4774  605.46  4789.1  605.41  4799.2  604.17  4809.3  598.87  4819.4  596.37
  4829.5  595.88  4849.7  596.16    4890  595.19  4920.1  595.35  4930.1  594.93
  4950.1  592.97  4960.2   592.7  4979.6  593.11  4982.6  590.91  4982.9  590.41
  4986.4  590.41  4986.6  590.91  4990.2  592.35  4997.6  593.61  5011.3  595.09
  5020.4  597.16  5065.6  598.83  5093.8  600.35  5144.6  601.24  5155.5  601.11
  5190.2  602.83  5209.1  602.73  5214.4  603.21  5262.9  603.97    5400   608.5
#Mann= 3 ,-1 , 0
    4774     .05       0  4982.6    .033       0  4986.6     .05       0
Bank Sta=4982.6,4986.6
XS Rating Curve= 0 ,0
Exp/Cntr=0.3,0.1

Chan Stop Cuts=-1
Use User Specified Reach Order=0
Composite Channel Slope=5