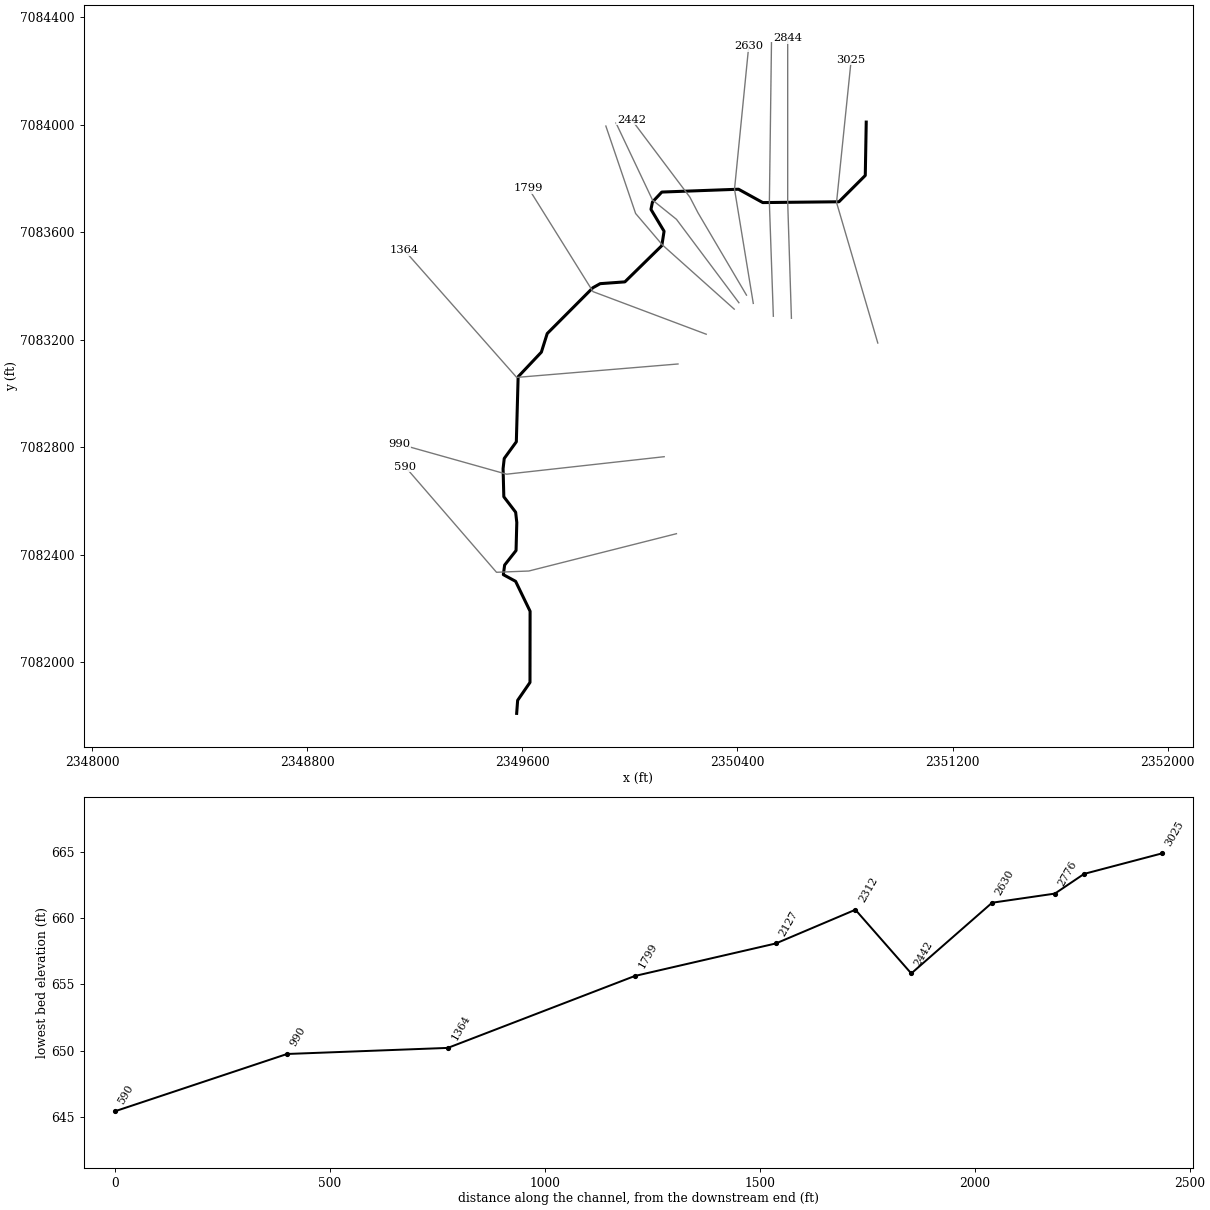
--- Denton Creek Tr 7_4.prj (project) ---

Proj Title=Denton Creek Tr 7_4 Base Level Engineering
Current Plan=p01
Default Exp/Contr=0.3,0.1
English Units
Geom File=g01
Flow File=f01
Plan File=p01
Y Axis Title=Elevation
X Axis Title(PF)=Main Channel Distance
X Axis Title(XS)=Station
BEGIN DESCRIPTION:
Denton Creek Tr 7_4
END DESCRIPTION:
DSS Export Rating Curves= 0
DSS Export Rating Curve Sorted= 0
DSS Export Volume Flow Curves= 0
DXF OffsetX= 0
DXF OffsetY= 0
DXF ScaleX= 1
DXF ScaleY= 10

--- Denton Creek Tr 7_4.p01 (plan) ---

Plan Title=Multiple Run
Short Identifier=Multiple
Geom File=g01
Flow File=f01
Subcritical Flow
K Sum by GR= 0
Std Step Tol= 0.01
Critical Tol= 0.01
Num of Std Step Trials= 20
Max Error Tol= 0.3
Flow Tol Ratio= 0.001
Split Flow NTrial= 30
Split Flow Tol= 0.02
Split Flow Ratio= 0.02
Log Output Level= 0
Friction Slope Method= 1
Unsteady Friction Slope Method= 2
Unsteady Bridges Friction Slope Method= 1
Parabolic Critical Depth
Global Vel Dist=  1 , 1 , 1
Global Log Level= 0
CheckData=True
Encroach Param= -1, 0, 0, 0
BEGIN DESCRIPTION:
Multiple Run
END DESCRIPTION:

--- Denton Creek Tr 7_4.f01 (steady flow) ---

Flow Title=Multiple
Program Version=4.10
Number of Profiles= 7
Profile Names=10-year,25-year,50-year,1pct_min,100-year,1pct_plu,500-year
River Rch & RM=Denton Creek Tr,Reach-1         ,3025
     255     331     391     230     459     916     634
Boundary for River Rch & Prof#=Denton Creek Tr,Reach-1         , 1
Up Type= 0
Dn Type= 3
Dn Slope=0.00831
Boundary for River Rch & Prof#=Denton Creek Tr,Reach-1         , 2
Up Type= 0
Dn Type= 3
Dn Slope=0.00831
Boundary for River Rch & Prof#=Denton Creek Tr,Reach-1         , 3
Up Type= 0
Dn Type= 3
Dn Slope=0.00831
Boundary for River Rch & Prof#=Denton Creek Tr,Reach-1         , 4
Up Type= 0
Dn Type= 3
Dn Slope=0.00831
Boundary for River Rch & Prof#=Denton Creek Tr,Reach-1         , 5
Up Type= 0
Dn Type= 3
Dn Slope=0.00831
Boundary for River Rch & Prof#=Denton Creek Tr,Reach-1         , 6
Up Type= 0
Dn Type= 3
Dn Slope=0.00831
Boundary for River Rch & Prof#=Denton Creek Tr,Reach-1         , 7
Up Type= 0
Dn Type= 3
Dn Slope=0.00831
DSS Import GetInterval= 0
DSS Import GetPeak= 0
DSS Import FillOption= 0

--- Denton Creek Tr 7_4.g01 (geometry) ---

Geom Title=Existing Conditions
Program Version=4.10

River Reach=Denton Creek Tr ,Reach-1
Reach XY= 30
        2350879.        7084010.      2350875.48      7083811.45
      2350777.55      7083713.53      2350494.22      7083710.52
      2350404.08       7083760.2      2350118.76      7083749.66
      2350083.97      7083712.58      2350078.47      7083685.13
      2350127.19      7083603.88      2350118.81      7083550.32
      2349981.43      7083415.52      2349889.48      7083408.83
      2349862.25      7083393.54      2349692.63      7083223.21
      2349670.82      7083153.96      2349584.47      7083062.45
      2349577.78       7082820.5      2349532.77      7082758.43
       2349528.5      7082720.17      2349531.25      7082615.94
      2349575.23      7082558.43       2349579.5      7082520.17
      2349576.72      7082415.91      2349534.27      7082361.86
      2349529.49      7082326.12      2349575.04      7082301.38
      2349628.94      7082189.99      2349628.55      7081925.19
      2349582.65      7081858.49        2349579.        7081810.

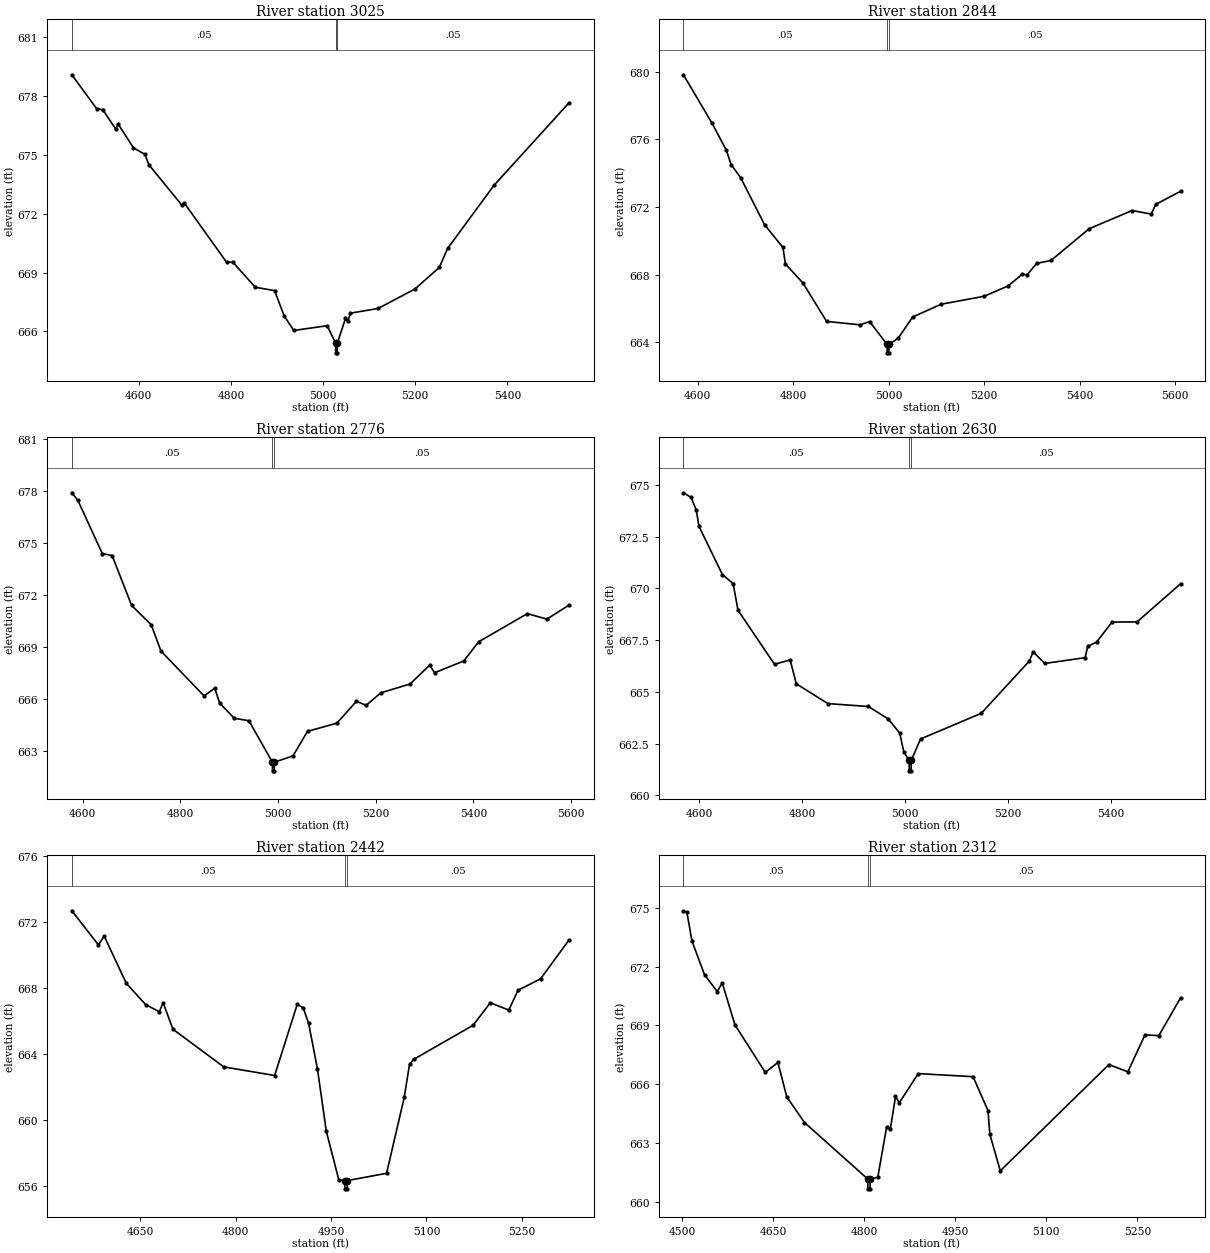
Type RM Length L Ch R = 1 ,3025    ,181,181,181
BEGIN DESCRIPTION:
Denton Creek Tr 7_4 7.0
END DESCRIPTION:
XS GIS Cut Line= 3
        2350922.      7083187.98      2350768.57      7083711.04
      2350823.04      7084241.86
#Sta/Elev= 30
  4454.9  679.07  4509.1  677.33  4521.8   677.3    4550  676.31  4555.2  676.57
  4588.6  675.35  4613.3  675.02    4622  674.49    4694  672.42  4699.2  672.53
  4790.5  669.53  4804.6  669.52    4853  668.25  4894.7  668.08  4915.5   666.8
  4936.4  666.05    5009  666.29  5027.1  665.41  5027.4  664.91  5030.9  664.91
  5031.1  665.41  5048.7  666.66  5053.7  666.51  5059.3  666.93  5119.6  667.17
    5200  668.17  5252.2  669.26  5270.4  670.23  5370.9  673.44  5533.6  677.64
#Mann= 3 ,-1 , 0
  4454.9     .05       0  5027.1     .04       0  5031.1     .05       0
Bank Sta=5027.1,5031.1
XS Rating Curve= 0 ,0
Exp/Cntr=0.3,0.1

Type RM Length L Ch R = 1 ,2844    ,68,68,68
BEGIN DESCRIPTION:
Mapping XS 0361063d
END DESCRIPTION:
XS GIS Cut Line= 3
      2350600.81      7083280.04      2350586.92       7083712.3
      2350586.92      7084321.62
#Sta/Elev= 30
  4569.9  679.83  4629.9  676.96  4659.9  675.36  4669.9  674.51  4689.9  673.73
  4739.9  670.95  4778.5   669.6  4783.5  668.63    4820  667.51    4870  665.22
    4940  665.02  4960.1  665.21  4996.7  663.86    4997  663.36  5000.5  663.36
  5000.7  663.86  5020.1  664.23  5050.1  665.48  5110.1  666.24  5200.1  666.71
  5250.1  667.32  5280.1  668.02  5290.1  667.98  5310.1  668.66  5340.1  668.83
  5420.1  670.71  5510.1  671.79  5550.1  671.58  5560.1  672.16  5611.7  672.93
#Mann= 3 ,-1 , 0
  4569.9     .05       0  4996.7     .04       0  5000.7     .05       0
Bank Sta=4996.7,5000.7
XS Rating Curve= 0 ,0
Exp/Cntr=0.3,0.1

Type RM Length L Ch R = 1 ,2776    ,146,146,146
BEGIN DESCRIPTION:
Mapping XS 0db601e3
END DESCRIPTION:
XS GIS Cut Line= 3
      2350533.59      7083287.61      2350518.81      7083709.55
      2350526.64       7084305.2
#Sta/Elev= 30
  4577.8  677.91  4590.2  677.47  4640.2   674.4  4660.2  674.29  4700.3  671.41
  4740.3   670.3  4760.3  668.78  4848.6  666.19  4870.4  666.64  4880.4  665.78
  4910.4   664.9  4940.4  664.76  4988.4  662.37  4988.7  661.87  4992.2  661.87
  4992.4  662.37  5030.5  662.73  5060.5  664.15  5120.5  664.62  5160.5  665.88
  5180.5  665.65  5210.5  666.37  5270.5  666.88  5310.5  667.97  5320.5  667.53
  5380.5  668.21  5410.5  669.31  5510.5  670.94  5550.5  670.62  5595.7  671.43
#Mann= 3 ,-1 , 0
  4577.8     .05       0  4988.4     .04       0  4992.4     .05       0
Bank Sta=4988.4,4992.4
XS Rating Curve= 0 ,0
Exp/Cntr=0.3,0.1

Type RM Length L Ch R = 1 ,2630    ,188,188,188
BEGIN DESCRIPTION:
Denton Creek Tr 7_4 6.0
END DESCRIPTION:
XS GIS Cut Line= 3
      2350458.93      7083335.43      2350389.19      7083760.45
      2350442.01      7084292.43
#Sta/Elev= 30
  4569.3  674.62  4584.1   674.4  4594.2  673.79  4599.5     673  4644.9  670.67
  4665.8  670.23  4675.3  668.94  4746.2  666.33  4776.6  666.54  4788.4  665.39
  4849.7  664.43  4928.6  664.29  4967.2  663.68  4989.4     663  4997.2  662.09
  5007.6  661.68  5007.8  661.18  5011.3  661.18  5011.6  661.68  5029.7  662.72
  5147.6  663.96  5240.7  666.48  5248.4  666.93  5270.9  666.37  5349.3  666.65
  5354.3   667.2  5371.4   667.4  5401.5  668.37  5450.1  668.38  5534.6  670.22
#Mann= 3 ,-1 , 0
  4569.3     .05       0  5007.6    .033       0  5011.6     .05       0
Bank Sta=5007.6,5011.6
XS Rating Curve= 0 ,0
Exp/Cntr=0.3,0.1

Type RM Length L Ch R = 1 ,2442    ,130,130,130
BEGIN DESCRIPTION:
Mapping XS 71bc13c2
END DESCRIPTION:
XS GIS Cut Line= 4
      2350433.65      7083366.16      2350253.53      7083672.14
      2350223.15      7083730.73      2350006.12      7084019.39
#Sta/Elev= 30
    4542  672.66  4583.9  670.59  4592.9  671.13  4627.7  668.27  4658.1  666.98
  4679.6  666.55  4685.7  667.09  4701.1  665.49  4781.1  663.21  4861.1  662.69
  4896.6  666.99  4905.9   666.8  4914.6  665.84  4928.4   663.1  4942.4  659.31
  4962.1  656.37  4971.3  656.33  4971.6  655.83  4975.1  655.83  4975.3  656.33
  5037.2  656.77    5065  661.36  5073.3  663.36  5079.6  663.66  5173.3  665.73
  5200.4  667.09  5229.5  666.65  5244.1  667.85  5279.5  668.54  5324.2  670.89
#Mann= 3 ,-1 , 0
    4542     .05       0  4971.3    .033       0  4975.3     .05       0
Bank Sta=4971.3,4975.3
XS Rating Curve= 0 ,0
Exp/Cntr=0.3,0.1

Type RM Length L Ch R = 1 ,2312    ,185,185,185
BEGIN DESCRIPTION:
Mapping XS 0f04a3e0
END DESCRIPTION:
XS GIS Cut Line= 4
      2350405.47       7083337.9      2350173.24      7083648.27
      2350084.26      7083719.88      2349948.37      7084006.77
#Sta/Elev= 30
  4501.9  674.86  4507.6  674.79  4515.9  673.32  4536.7  671.59  4557.6  670.73
  4565.9  671.17  4586.8  669.03  4636.8   666.6  4657.6  667.11  4672.2  665.35
  4701.4  664.04  4805.7  661.15  4805.9  660.65  4809.4  660.65  4809.7  661.15
  4822.2  661.24  4836.8  663.81  4843.1  663.73  4851.4  665.37  4857.7  665.05
  4888.9  666.54  4979.2  666.38  5003.8  664.65  5006.9  663.44  5024.1  661.57
  5203.1     667  5234.3  666.63  5262.6  668.52  5285.4  668.48  5321.2  670.41
#Mann= 3 ,-1 , 0
  4501.9     .05       0  4805.7    .033       0  4809.7     .05       0
Bank Sta=4805.7,4809.7
XS Rating Curve= 0 ,0
Exp/Cntr=0.3,0.1

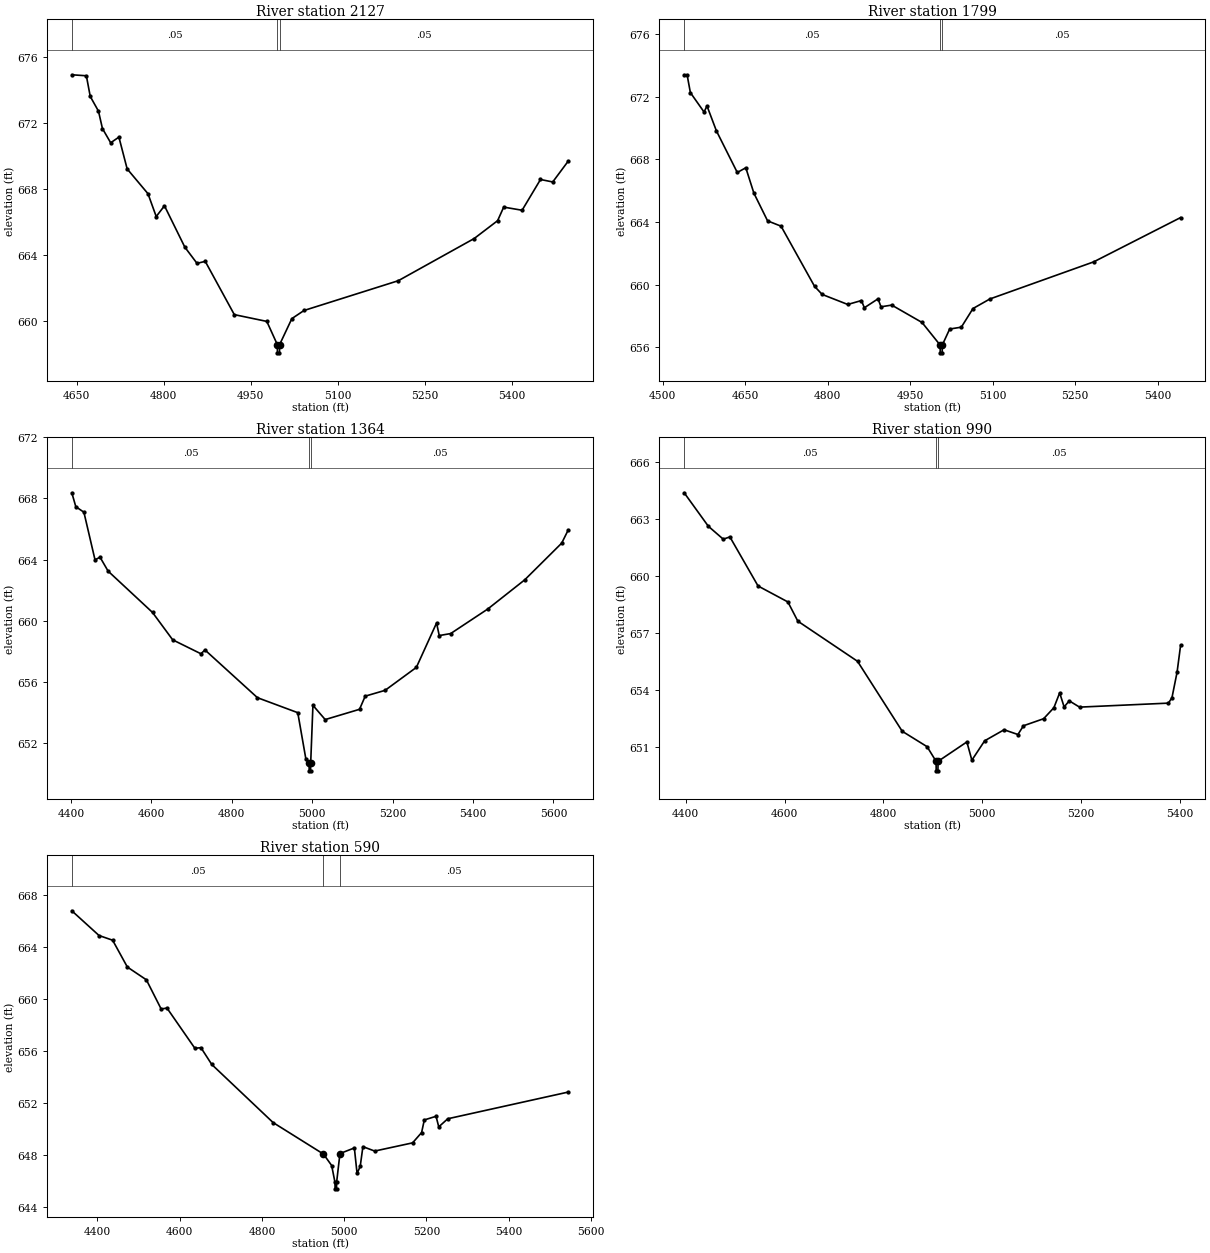
Type RM Length L Ch R = 1 ,2127    ,328,328,328
BEGIN DESCRIPTION:
Mapping XS 7cb3fca3
END DESCRIPTION:
XS GIS Cut Line= 4
      2350388.07      7083314.08      2350121.15      7083552.78
      2350021.33      7083669.97      2349910.73      7083995.25
#Sta/Elev= 30
  4641.5  674.91  4666.6  674.85  4673.3   673.6  4687.5  672.71  4694.3  671.66
  4708.5   670.8  4722.7  671.14  4736.9  669.22  4772.8  667.72    4787  666.34
  4801.2  666.99  4836.3  664.49  4857.3  663.51  4871.5  663.63  4921.6  660.41
  4977.6     660  4995.7   658.6  4995.9   658.1  4999.4   658.1  4999.7   658.6
  5020.8  660.17  5041.7  660.66  5204.2  662.46    5335  665.01  5375.4  666.09
  5385.9  666.91  5417.6  666.72  5449.3  668.58  5470.4  668.43  5497.1  669.69
#Mann= 3 ,-1 , 0
  4641.5     .05       0  4995.7    .033       0  4999.7     .05       0
Bank Sta=4995.7,4999.7
XS Rating Curve= 0 ,0
Exp/Cntr=0.3,0.1

Type RM Length L Ch R = 1 ,1799    ,435,435,435
BEGIN DESCRIPTION:
Mapping XS 2794cc97
END DESCRIPTION:
XS GIS Cut Line= 3
      2350283.88      7083220.76      2349862.91      7083379.17
      2349623.15      7083763.65
#Sta/Elev= 30
  4539.1   673.4  4544.4   673.4  4550.4  672.26  4575.3  671.02  4580.6  671.41
  4597.7  669.82  4635.7  667.16  4651.2  667.46  4665.9  665.84  4690.8  664.07
  4715.3  663.73  4776.2  659.89  4790.1  659.37  4836.6  658.73  4861.5  658.98
  4866.8  658.52  4891.7  659.09  4897.1  658.58  4916.6  658.69  4971.7  657.58
  5004.6  656.14  5004.9  655.64  5008.4  655.64  5008.6  656.14    5022  657.16
  5043.2  657.28  5064.4  658.47  5095.1  659.08  5283.9  661.45    5442  664.28
#Mann= 3 ,-1 , 0
  4539.1     .05       0  5004.6    .033       0  5008.6     .05       0
Bank Sta=5004.6,5008.6
XS Rating Curve= 0 ,0
Exp/Cntr=0.3,0.1

Type RM Length L Ch R = 1 ,1364    ,374,374,374
BEGIN DESCRIPTION:
Denton Creek Tr 7_4 2.0
END DESCRIPTION:
XS GIS Cut Line= 3
      2350178.99        7083110.        2349579.        7083060.
       2349160.5      7083534.03
#Sta/Elev= 30
  4402.4  668.37  4412.4  667.46  4432.5   667.1  4460.1  663.99  4472.6  664.16
  4492.7  663.25  4603.1  660.55  4653.3  658.76  4723.5  657.85  4733.5   658.1
    4864  654.98  4964.3     654  4984.4  650.98  4992.4   650.7  4992.7   650.2
  4996.2   650.2  4996.4   650.7    5002  654.48  5032.5  653.55  5117.8  654.22
    5132  655.08  5181.4  655.46  5259.2  656.96  5309.4  659.86  5316.1  659.04
  5344.5  659.17  5436.5  660.77  5528.6  662.68  5620.6  665.08  5636.8  665.94
#Mann= 3 ,-1 , 0
  4402.4     .05       0  4992.4    .033       0  4996.4     .05       0
Bank Sta=4992.4,4996.4
XS Rating Curve= 0 ,0
Exp/Cntr=0.3,0.1

Type RM Length L Ch R = 1 ,990     ,400,400,400
BEGIN DESCRIPTION:
Mapping XS 3a8c9585
END DESCRIPTION:
XS GIS Cut Line= 3
      2350127.63      7082765.02      2349541.73      7082699.92
      2349142.12      7082812.24
#Sta/Elev= 30
  4396.8  664.36  4445.7   662.6  4475.9  661.92  4489.3  662.04  4546.3  659.46
  4606.7  658.62  4626.8  657.61  4747.6   655.5  4838.1  651.82  4888.4  651.01
  4906.6  650.24  4906.8  649.74  4910.3  649.74  4910.6  650.24  4968.9  651.26
    4979   650.3  5004.9  651.32  5044.2   651.9  5072.2  651.65  5083.4  652.11
  5124.2  652.48    5145  653.06  5156.7  653.84  5165.7   653.1  5176.1  653.42
  5196.9  653.09  5376.7   653.3  5383.9  653.58  5394.3  654.93  5401.4  656.34
#Mann= 3 ,-1 , 0
  4396.8     .05       0  4906.6    .033       0  4910.6     .05       0
Bank Sta=4906.6,4910.6
XS Rating Curve= 0 ,0
Exp/Cntr=0.3,0.1

Type RM Length L Ch R = 1 ,590     ,0,0,0
BEGIN DESCRIPTION:
Denton Creek Tr 7_4 1.0
END DESCRIPTION:
XS GIS Cut Line= 4
       2350173.2      7082478.55      2349624.19      7082339.68
        2349504.        7082335.       2349164.1      7082728.16
#Sta/Elev= 30
  4338.1  666.76  4404.3  664.86  4437.3   664.5  4473.1  662.44  4519.3  661.46
  4555.2  659.22  4569.4  659.29  4637.2   656.2  4651.9  656.25  4678.2  654.96
  4827.2   650.5  4949.6  648.08  4969.6   647.2  4977.6  645.91  4977.9  645.41
  4981.4  645.41  4981.6  645.91  4989.7  648.12  5024.7  648.55  5031.3  646.59
  5038.9  647.13  5045.5  648.65  5074.1  648.31  5166.2  648.94  5188.1  649.73
  5194.7   650.7  5223.2  650.98  5229.8  650.17  5251.7  650.79  5544.4  652.84
#Mann= 3 ,-1 , 0
  4338.1     .05       0  4949.6    .033       0  4989.7     .05       0
Bank Sta=4949.6,4989.7
XS Rating Curve= 0 ,0
Exp/Cntr=0.3,0.1

Chan Stop Cuts=-1
Use User Specified Reach Order=0
Composite Channel Slope=5