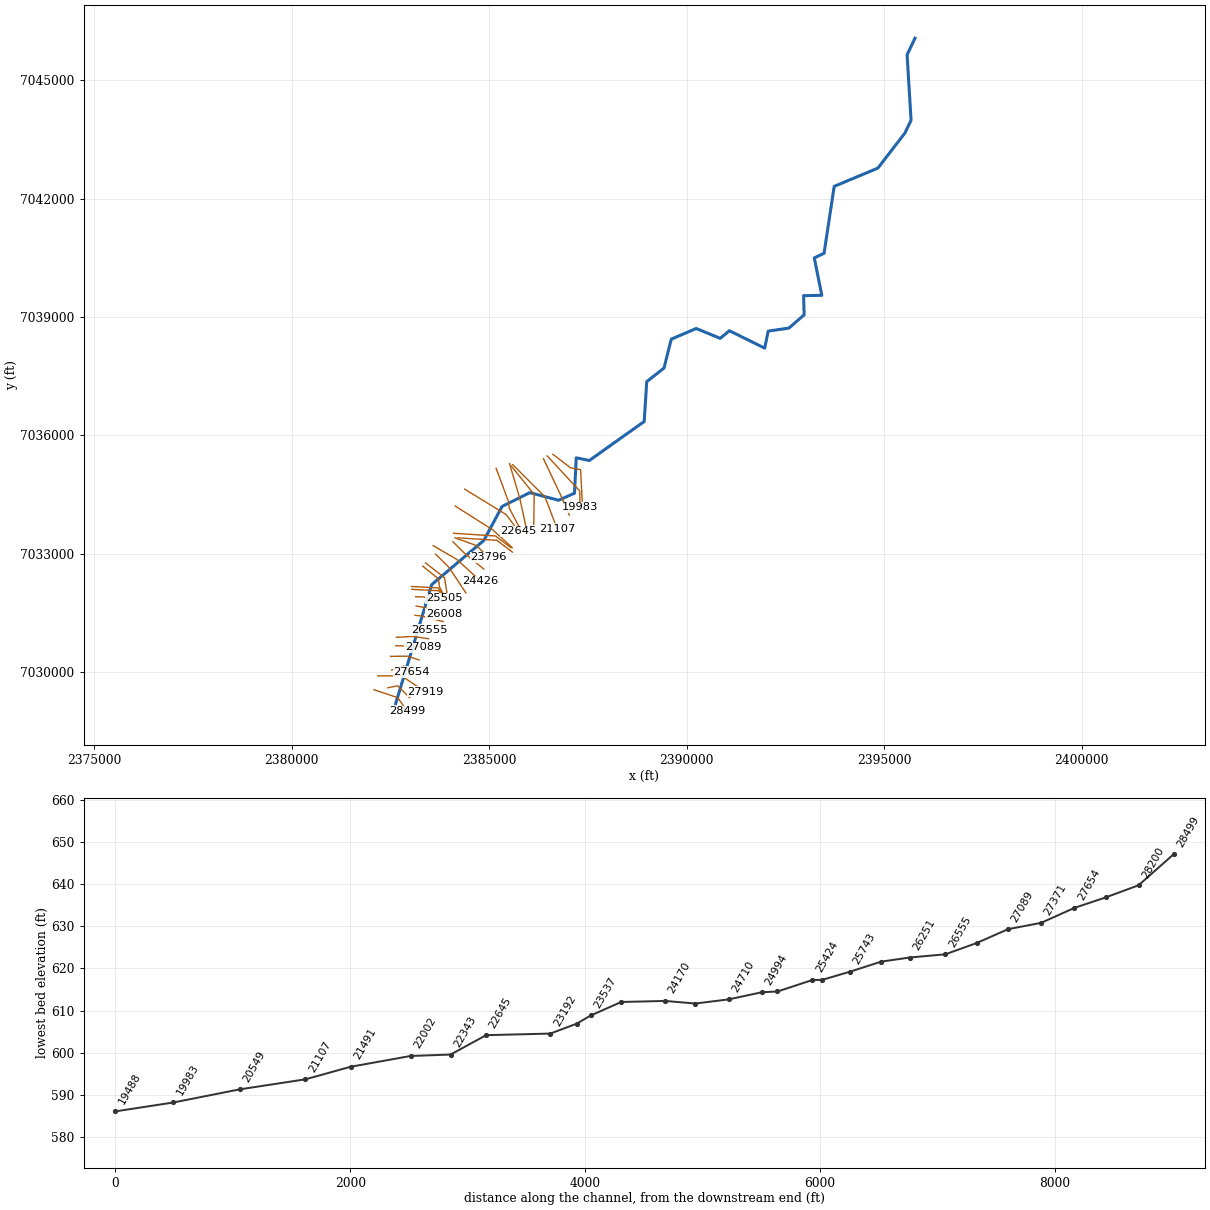
--- Dove Creek.prj (project) ---

Proj Title=Dove Creek Base Level Engineering
Current Plan=p01
Default Exp/Contr=0.3,0.1
English Units
Geom File=g01
Flow File=f01
Plan File=p01
Y Axis Title=Elevation
X Axis Title(PF)=Main Channel Distance
X Axis Title(XS)=Station
BEGIN DESCRIPTION:
Dove Creek
END DESCRIPTION:
DSS Export Rating Curves= 0
DSS Export Rating Curve Sorted= 0
DSS Export Volume Flow Curves= 0
DXF OffsetX= 0
DXF OffsetY= 0
DXF ScaleX= 1
DXF ScaleY= 10

--- Dove Creek.p01 (plan) ---

Plan Title=Multiple Run
Program Version=4.10
Short Identifier=Multiple
Geom File=g01
Flow File=f01
Subcritical Flow
K Sum by GR= 0
Std Step Tol= 0.01
Critical Tol= 0.01
Num of Std Step Trials= 20
Max Error Tol= 0.3
Flow Tol Ratio= 0.001
Split Flow NTrial= 30
Split Flow Tol= 0.02
Split Flow Ratio= 0.02
Log Output Level= 0
Friction Slope Method= 1
Unsteady Friction Slope Method= 2
Unsteady Bridges Friction Slope Method= 1
Parabolic Critical Depth
Global Vel Dist= 1 , 1 , 1
Global Log Level= 0
CheckData=True
Encroach Param=-1 ,0,0, 0
BEGIN DESCRIPTION:
Multiple Run
END DESCRIPTION:
Computation Interval=1HOUR
Output Interval=1HOUR
Run HTab= 0
Run UNet= 0
Run PostProcess= 0
Run WQNet= 0
UNET Theta= 1
UNET Theta Warmup= 1
UNET ZTol= 0.02
UNET ZSATol= 0.05
UNET MxIter= 20
UNET MaxInSteps= 0
UNET DtIC= 0
UNET DtMin= 0
UNET MaxCRTS= 20
UNET WFStab= 2
UNET SFStab= 1
UNET WFX= 1
UNET SFX= 1
UNET DSS MLevel= 4
UNET DZMax Abort= 100
UNET Convert EG Bridges= 0
UNET Use Existing IB Tables=-1
UNET Froude Reduction=False
UNET Froude Limit= 1
UNET Froude Power= 10
UNET Time Slicing=0,0, 5
UNET Junction Losses=0
Instantaneous Interval=1HOUR
Write IC File= 0
Write IC File at Sim End=0
Echo Input=False
Echo Parameters=False
Echo Output=False
Write Detailed= 0
WQ AD Non Conservative
WQ ULTIMATE=-1
WQ Max Comp Step=1HOUR
WQ Output Interval=15MIN
WQ Output Selected Increments= 0
WQ Output face flow=0
WQ Output face velocity=0
WQ Output face area=0
WQ Output face dispersion=0
WQ Output cell volume=0
WQ Output cell surface area=0
WQ Output cell continuity=0
WQ Output cumulative cell continuity=0
WQ Output face conc=0
WQ Output face dconc_dx=0
WQ Output face courant=0
WQ Output face peclet=0
WQ Output face adv mass=0
WQ Output face disp mass=0
WQ Output cell mass=0
WQ Output cell source sink temp=0
WQ Output cell source sink nsm=0
WQ Output MaxMinRange=-1
WQ Daily Max Min Mean=-1
WQ Daily Range=0
WQ Daily Time=0
WQ Create Restart=0
WQ Fixed Restart=0
WQ System Summary=0
WQ Use Fixed Temperature=0
Sorting and Armoring Iterations= 10
XS Update Threshold= 0.02
Hydraulics Update Threshold= 0.02
Energy Slope Method= 1
Volume Change Method= 0
XS Weighting Method= 0
Number of US Weighted Cross Sections= 1
Number of DS Weighted Cross Sections= 1
Upstream XS Weight=0.25
Main XS Weight=0.5
Downstream XS Weight=0.25
Number of DS XS's Weighted with US Boundary= 1
Upstream Boundary Weight= 1
Weight of XSs Associated with US Boundary= 0
Number of US XS's Weighted with DS Boundary= 1
Downstream Boundary Weight= 0.5
Weight of XSs Associated with DS Boundary= 0.5
Sediment Output Level= 4
Mass or Volume Output= 0
Output Increment Type= 1
Profile and TS Output Increment= 10
XS Output Flag= 0
XS Output Increment= 10
Disregard all LS=0
Disregard all Conn=0
Disregard all Breaches=0
Disregard all Pumps=0

--- Dove Creek.f01 (steady flow) ---

Flow Title=Multiple
Number of Profiles=7
Profile Names=10-year,25-year,50-year,1pct_min,100-year,1pct_plu,500-year
River Rch & RM= Dove Creek,Reach-1,28499
     369     488     582     345     689    1374     963
River Rch & RM= Dove Creek,Reach-1,23796
     538     727     881     529    1056    2108    1519
River Rch & RM= Dove Creek,Reach-1,21491
     829    1151    1419     867    1730    3452    2572
River Rch & RM= Dove Creek,Reach-1,20549
    1048    1473    1831    1126    2247    4484    3388
River Rch & RM= Dove Creek,Reach-1,19033
    1236    1748    2183    1348    2690    5366    4086
River Rch & RM= Dove Creek,Reach-1,15644
    1425    2029    2544    1576    3145    6276    4813
River Rch & RM= Dove Creek,Reach-1,12018
    1548    2210    2776    1723    3437    6858    5276
River Rch & RM= Dove Creek,Reach-1,9220
    1627    2326    2923    1815    3622    7227    5565
River Rch & RM= Dove Creek,Reach-1,7682
    1772    2543    3204    1994    3978    7937    6138
River Rch & RM= Dove Creek,Reach-1,5887
    1939    2781    3502    2177    4343    8665    6685
Boundary for River Rch & Prof#=Dove Creek,Reach-1,1
Up Type=0
Dn Type=3
Dn Slope=0.005
Boundary for River Rch & Prof#=Dove Creek,Reach-1,2
Up Type=0
Dn Type=3
Dn Slope=0.005
Boundary for River Rch & Prof#=Dove Creek,Reach-1,3
Up Type=0
Dn Type=3
Dn Slope=0.005
Boundary for River Rch & Prof#=Dove Creek,Reach-1,4
Up Type=0
Dn Type=3
Dn Slope=0.005
Boundary for River Rch & Prof#=Dove Creek,Reach-1,5
Up Type=0
Dn Type=3
Dn Slope=0.005
Boundary for River Rch & Prof#=Dove Creek,Reach-1,6
Up Type=0
Dn Type=3
Dn Slope=0.005
Boundary for River Rch & Prof#=Dove Creek,Reach-1,7
Up Type=0
Dn Type=3
Dn Slope=0.005

--- Dove Creek.g01 (geometry) ---

Geom Title=Existing Conditions
Program Version=4.10

River Reach=Dove Creek      ,Reach-1
Reach XY= 30
        2382629.        7029210.      2383539.52      7032219.79
      2384862.51      7033342.95      2385322.79       7034202.2
      2386025.38      7034552.13      2386751.97      7034359.37
      2387156.13      7034536.48       2387201.7      7035434.16
      2387531.43       7035365.4       2388921.2      7036353.79
      2388986.68       7037363.7      2389423.66      7037707.26
      2389608.42      7038440.77      2390239.44      7038708.96
      2390847.39       7038459.7       2391078.7       7038652.8
      2391973.31      7038211.87      2392061.78      7038643.77
      2392585.99      7038719.17      2392971.52      7039053.94
      2392958.42      7039540.42      2393418.98      7039549.94
      2393228.98      7040496.08      2393477.01      7040615.27
      2393732.76      7042308.44      2394838.79      7042770.52
      2395523.15      7043657.71      2395679.39       7043982.8
      2395579.21      7045641.73        2395779.        7046060.

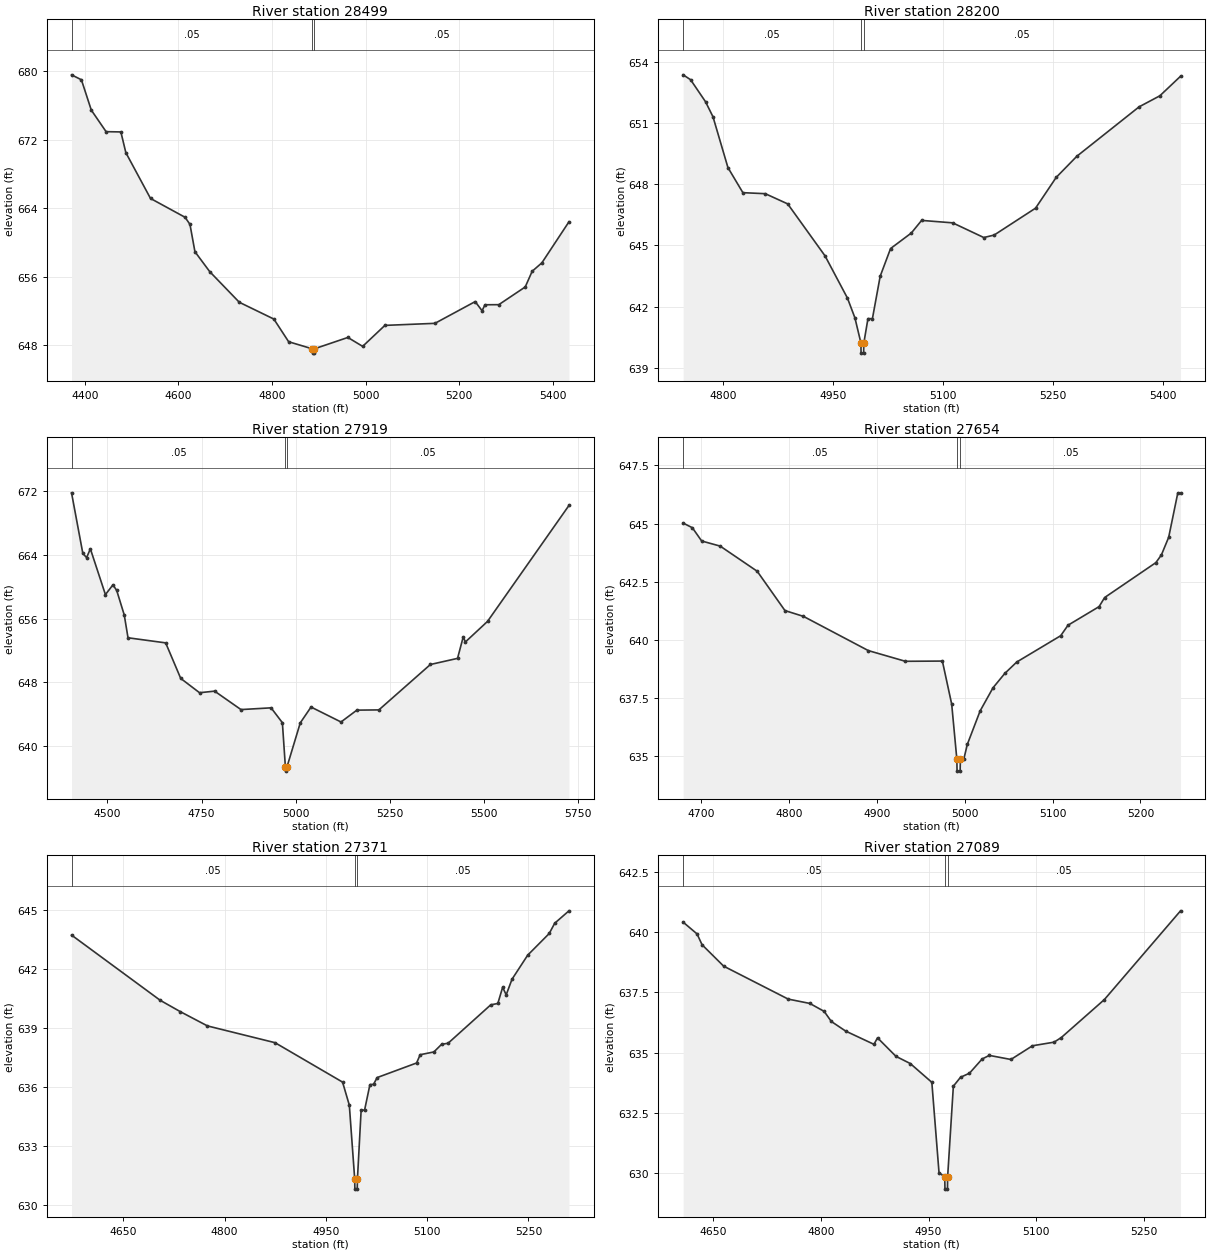
Type RM Length L Ch R = 1 ,28499   ,299,299,299
BEGIN DESCRIPTION:
Dove Creek 63.0
END DESCRIPTION:
XS GIS Cut Line= 3
      2382078.97      7029560.01        2382679.        7029360.
        2382929.        7029010.
#Sta/Elev= 30
  4371.6  679.58  4392.7     679  4413.8  675.46  4445.4  672.94    4477  672.91
  4487.6  670.49  4540.3  665.14  4614.1  662.94  4624.6  662.11  4635.2  658.92
  4666.8  656.59    4730  653.01  4803.8  651.05  4835.4   648.4  4886.1  647.57
  4886.4  647.07  4889.9  647.07  4890.1  647.57  4961.9   648.9  4993.5  647.86
    5041  650.31  5147.9  650.55  5233.9  653.09  5248.6  652.02  5254.8  652.72
  5284.3  652.73  5340.8   654.8  5355.6  656.63  5376.4  657.62  5434.2  662.41
#Mann= 3 ,-1 , 0
  4371.6     .05       0  4886.1     .05       0  4890.1     .05       0
Bank Sta=4886.1,4890.1
XS Rating Curve= 0 ,0
Exp/Cntr=0.3,0.1

Type RM Length L Ch R = 1 ,28200   ,281,281,281
BEGIN DESCRIPTION:
Dove Creek 62.0
END DESCRIPTION:
XS GIS Cut Line= 3
      2382428.96      7029609.99        2382679.        7029660.
      2382979.03      7029359.97
#Sta/Elev= 30
  4745.1  653.37  4755.3  653.13  4775.7  652.05  4785.9  651.31  4806.3  648.82
  4826.7  647.59  4857.3  647.54  4887.9  647.04  4938.9  644.49  4969.5  642.42
  4979.7  641.45  4987.9  640.22  4988.1  639.72  4991.6  639.72  4991.9  640.22
  4997.5  641.41  5003.6  641.41  5014.2  643.49  5028.4  644.85  5056.7  645.61
  5070.8  646.23  5113.2  646.11  5155.7  645.39  5169.8  645.51  5226.4  646.83
  5254.6  648.34  5282.9  649.38  5367.8   651.8  5396.1  652.34  5424.4   653.3
#Mann= 3 ,-1 , 0
  4745.1     .05       0  4987.9    .033       0  4991.9     .05       0
Bank Sta=4987.9,4991.9
XS Rating Curve= 0 ,0
Exp/Cntr=0.3,0.1

Type RM Length L Ch R = 1 ,27919   ,265,265,265
BEGIN DESCRIPTION:
Dove Creek 61.0
END DESCRIPTION:
XS GIS Cut Line= 3
      2382178.99        7029910.        2382779.        7029910.
      2383378.98      7029510.01
#Sta/Elev= 30
  4404.6  671.83  4434.6  664.21  4444.6  663.68  4454.6  664.79  4494.6  659.03
  4514.6  660.26  4524.6  659.55  4544.6  656.47  4554.6   653.6  4654.6  652.96
  4694.6  648.49  4744.6  646.69  4784.6  646.89  4854.6  644.57  4934.6  644.79
  4964.6  642.92  4972.6  637.33  4972.9  636.83  4976.6  637.33  5012.1   642.9
  5040.7  644.89  5120.3  643.01  5162.4   644.5  5220.9  644.53  5357.7  650.24
  5429.8  651.01  5444.8  653.69  5450.8  653.08  5509.4  655.66  5725.7  670.24
#Mann= 3 ,-1 , 0
  4404.6     .05       0  4972.6    .033       0  4976.6     .05       0
Bank Sta=4972.6,4976.6
XS Rating Curve= 0 ,0
Exp/Cntr=0.3,0.1

Type RM Length L Ch R = 1 ,27654   ,283,283,283
BEGIN DESCRIPTION:
Dove Creek 60.0
END DESCRIPTION:
XS GIS Cut Line= 3
        2382529.        7030060.        2382829.        7030160.
      2383028.98      7030010.02
#Sta/Elev= 30
  4679.4  645.02  4689.9  644.82  4700.5  644.25  4721.6  644.03  4763.7  642.95
  4795.3  641.26  4816.4  641.01  4890.2  639.54  4932.4  639.08  4974.5  639.09
  4985.1  637.24    4991  634.86  4991.2  634.36  4994.7  634.36    4995  634.86
  4998.8  634.86  5002.9  635.51  5017.5  636.95  5032.1  637.94  5045.6  638.56
  5059.2  639.05  5109.2  640.18  5117.5  640.63  5152.9  641.43  5159.2  641.82
  5217.5  643.32  5223.8  643.65  5232.1  644.41  5242.5  646.32  5245.6  646.32
#Mann= 3 ,-1 , 0
  4679.4     .05       0    4991    .033       0    4995     .05       0
Bank Sta=4991,4995
XS Rating Curve= 0 ,0
Exp/Cntr=0.3,0.1

Type RM Length L Ch R = 1 ,27371   ,282,282,282
BEGIN DESCRIPTION:
Dove Creek 59.0
END DESCRIPTION:
XS GIS Cut Line= 3
      2382497.74      7030405.98        2382929.        7030410.
      2383219.07      7030315.03
#Sta/Elev= 30
  4573.4  643.71  4704.7   640.4  4734.7  639.82  4774.7   639.1  4874.7  638.25
  4974.7  636.25  4984.7  635.08  4992.7  631.32  4992.9  630.82  4996.4  630.82
  4996.7  631.32  5002.2  634.83  5007.3  634.83  5015.2  636.12  5020.6  636.14
  5025.9  636.48  5084.3  637.22  5089.6  637.64  5109.9  637.78  5121.4  638.17
  5130.9  638.22  5194.1  640.17  5204.6  640.24  5211.7  641.06    5217  640.68
  5225.6  641.47  5248.8  642.69  5280.7  643.79  5288.8  644.31  5309.9  644.94
#Mann= 3 ,-1 , 0
  4573.4     .05       0  4992.7     .05       0  4996.7     .05       0
Bank Sta=4992.7,4996.7
XS Rating Curve= 0 ,0
Exp/Cntr=0.3,0.1

Type RM Length L Ch R = 1 ,27089   ,267,267,267
BEGIN DESCRIPTION:
Dove Creek 58.0
END DESCRIPTION:
XS GIS Cut Line= 3
      2382632.58      7030675.69        2383029.        7030660.
      2383324.86      7030638.12
#Sta/Elev= 30
  4607.8  640.42  4627.2  639.93  4634.2  639.48  4664.3  638.59  4754.3  637.22
  4784.4  637.04  4804.4  636.71  4814.4  636.29  4834.4  635.89  4873.8  635.34
  4878.8  635.61  4904.5  634.84  4924.5  634.54  4954.5  633.76  4964.5  630.01
  4972.5  629.82  4972.8  629.32  4976.3  629.32  4976.5  629.82  4984.5   633.6
  4994.5  633.97    5007  634.14  5024.6  634.73  5034.6  634.88  5064.7  634.71
  5094.8  635.28  5124.9  635.43  5134.9  635.62    5195   637.2  5301.2  640.89
#Mann= 3 ,-1 , 0
  4607.8     .05       0  4972.5    .033       0  4976.5     .05       0
Bank Sta=4972.5,4976.5
XS Rating Curve= 0 ,0
Exp/Cntr=0.3,0.1

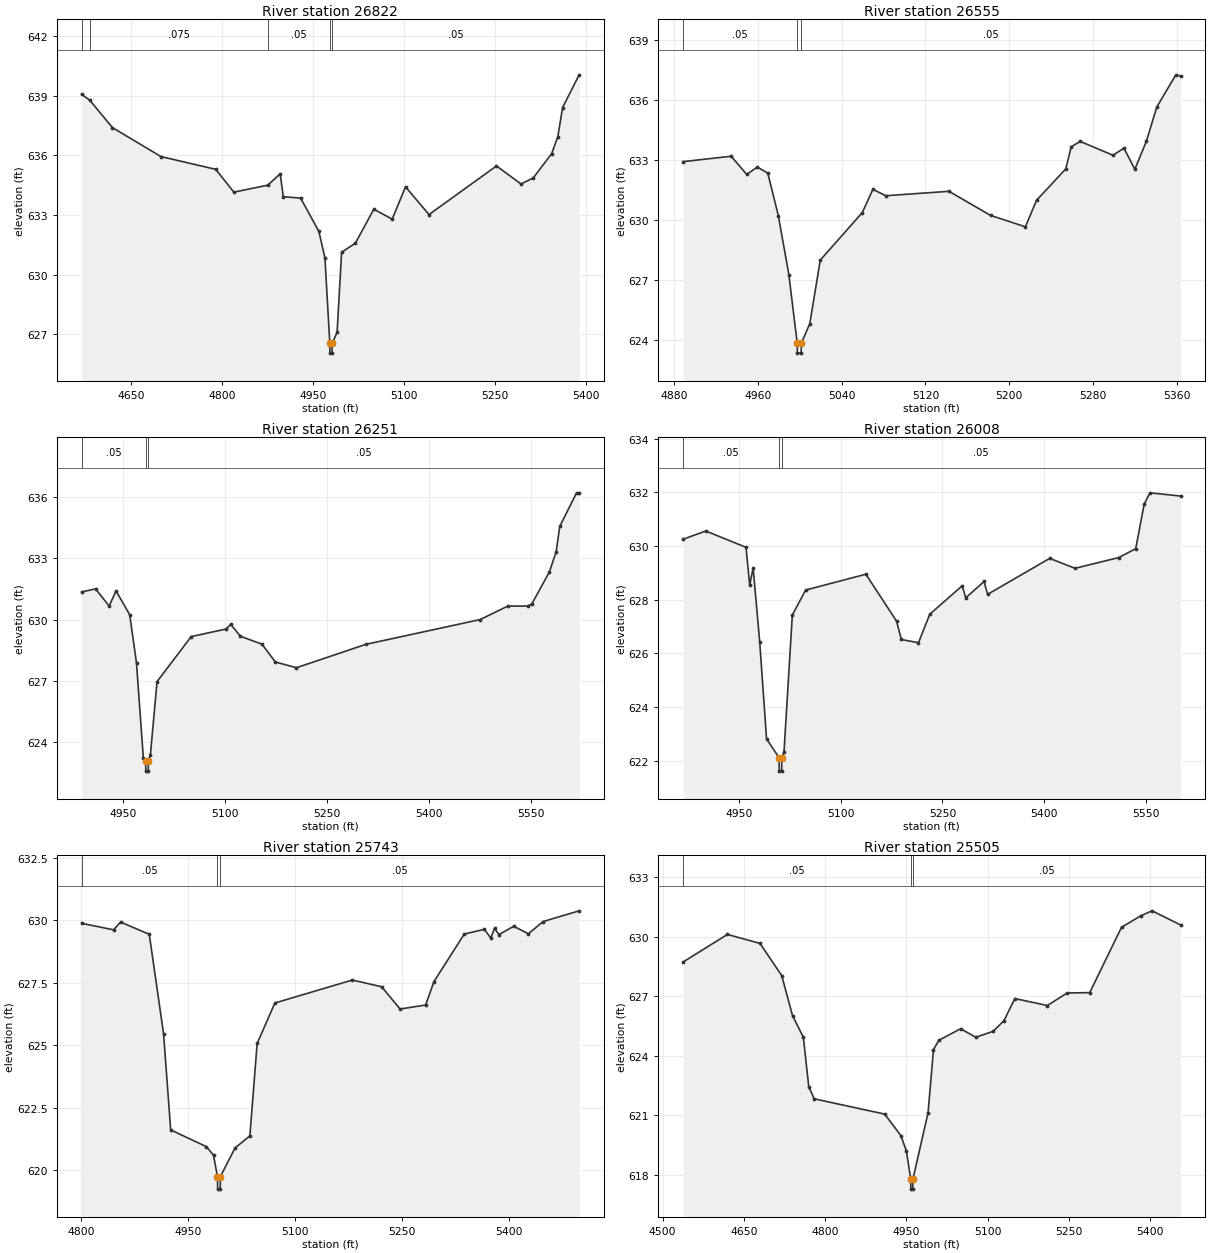
Type RM Length L Ch R = 1 ,26822   ,267,267,267
BEGIN DESCRIPTION:
Dove Creek 57.0
END DESCRIPTION:
XS GIS Cut Line= 3
       2382648.3      7030888.95        2383079.        7030910.
      2383463.73      7030851.31
#Sta/Elev= 30
  4568.7  639.08  4582.1  638.78  4619.5   637.4  4699.6  635.94  4789.7   635.3
  4819.7  634.15  4875.4   634.5  4896.1  635.07  4901.2  633.92  4929.8  633.85
  4959.9  632.17  4969.9  630.83  4977.9  626.54  4978.1  626.04  4981.6  626.04
  4981.9  626.54  4989.9  627.08  4997.4  631.12  5020.1  631.58  5050.5  633.29
  5080.8  632.79  5102.8  634.42  5141.5  633.02  5252.8  635.47  5293.3  634.56
  5313.5  634.87  5343.8  636.09    5354  636.95  5361.8  638.41  5389.1  640.06
#Mann= 5 ,-1 , 0
  4568.7     .05       0  4582.1    .075       0  4875.4     .05       0
  4977.9     .05       0  4981.9     .05       0
Bank Sta=4977.9,4981.9
XS Rating Curve= 0 ,0
Exp/Cntr=0.3,0.1

Type RM Length L Ch R = 1 ,26555   ,304,304,304
BEGIN DESCRIPTION:
Dove Creek 56.0
END DESCRIPTION:
XS GIS Cut Line= 3
      2383018.35      7031168.07      2383206.53      7031155.52
      2383480.81      7031074.48
#Sta/Elev= 30
  4888.8  632.91  4934.7  633.18  4949.6  632.27  4959.6  632.64  4969.6  632.34
  4979.7  630.21  4989.7  627.28  4997.7  623.86  4997.9  623.36  5001.4  623.36
  5001.7  623.86  5009.7  624.83  5019.7     628  5059.8  630.37  5069.9  631.53
  5082.2  631.21  5142.5  631.43  5182.1  630.23  5215.4  629.66    5226  630.98
  5253.9  632.55  5259.1  633.65  5267.7  633.92  5298.9  633.23  5309.4  633.58
  5319.8  632.53  5330.9  633.94  5340.7  635.63  5358.9  637.24  5363.4  637.18
#Mann= 3 ,-1 , 0
  4888.8     .05       0  4997.7     .05       0  5001.7     .05       0
Bank Sta=4997.7,5001.7
XS Rating Curve= 0 ,0
Exp/Cntr=0.3,0.1

Type RM Length L Ch R = 1 ,26251   ,243,243,243
BEGIN DESCRIPTION:
Dove Creek 55.0
END DESCRIPTION:
XS GIS Cut Line= 3
      2383118.73      7031444.05      2383284.93      7031428.37
      2383831.41      7031287.83
#Sta/Elev= 30
  4889.3  631.35  4909.7   631.5  4929.7  630.66  4939.8   631.4  4959.9  630.24
  4969.9  627.88    4980  623.22  4983.3   623.1  4983.6   622.6  4987.1   622.6
  4987.3   623.1  4990.3  623.38  5000.1  626.97  5050.3  629.17  5101.7  629.54
  5108.4  629.77  5122.4  629.19  5154.3   628.8    5174  627.93    5205  627.65
  5306.9  628.79  5474.9     630  5515.7  630.66  5545.7  630.66  5551.2  630.78
  5576.7  632.32  5586.8  633.32    5592  634.55  5616.7  636.19  5620.5  636.19
#Mann= 3 ,-1 , 0
  4889.3     .05       0  4983.3     .05       0  4987.3     .05       0
Bank Sta=4983.3,4987.3
XS Rating Curve= 0 ,0
Exp/Cntr=0.3,0.1

Type RM Length L Ch R = 1 ,26008   ,265,265,265
BEGIN DESCRIPTION:
Dove Creek 54.0
END DESCRIPTION:
XS GIS Cut Line= 4
      2383146.96      7031679.26        2383279.        7031660.
      2383307.02      7031650.48       2383852.1      7031477.83
#Sta/Elev= 30
  4866.9  630.25  4900.4  630.56  4959.9  629.95  4965.3  628.54  4970.4  629.19
  4980.1  626.43  4990.2  622.82  5008.7  622.12    5009  621.62  5012.5  621.62
  5012.7  622.12    5016  622.34  5028.3  627.43  5047.9  628.36  5136.9  628.95
  5182.3   627.2  5189.3  626.52  5214.6   626.4  5231.3  627.46  5279.2  628.52
  5284.4  628.07  5311.5  628.68  5316.7   628.2  5408.4  629.54  5445.9  629.17
  5510.5  629.57  5535.5   629.9    5548  631.56  5556.5  631.98  5601.7  631.86
#Mann= 3 ,-1 , 0
  4866.9     .05       0  5008.7     .05       0  5012.7     .05       0
Bank Sta=5008.7,5012.7
XS Rating Curve= 0 ,0
Exp/Cntr=0.3,0.1

Type RM Length L Ch R = 1 ,25743   ,238,238,238
BEGIN DESCRIPTION:
Dove Creek 53.0
END DESCRIPTION:
XS GIS Cut Line= 4
       2383134.4      7031917.61        2383329.        7031910.
      2383412.55      7031892.99      2383818.29      7031797.63
#Sta/Elev= 30
  4801.3  629.88  4845.9  629.62  4855.9  629.93    4896  629.44    4916  625.46
    4926  621.61    4976  620.94    4986   620.6  4991.5  619.74  4991.8  619.24
  4995.3  619.24  4995.5  619.74  5016.2  620.89  5036.9  621.37  5047.1  625.07
  5071.9  626.69  5180.4  627.61  5221.5  627.34  5247.3  626.45  5283.1  626.61
  5294.8  627.55  5337.2  629.45  5365.3  629.64  5374.4  629.29  5379.6  629.68
  5385.8  629.43  5406.4  629.76  5427.1  629.46  5447.5  629.95  5498.1  630.38
#Mann= 3 ,-1 , 0
  4801.3     .05       0  4991.5     .05       0  4995.5     .05       0
Bank Sta=4991.5,4995.5
XS Rating Curve= 0 ,0
Exp/Cntr=0.3,0.1

Type RM Length L Ch R = 1 ,25505   ,81,81,81
BEGIN DESCRIPTION:
Dove Creek 52.2
END DESCRIPTION:
XS GIS Cut Line= 3
      2383037.17      7032102.64      2383714.59      7032068.14
      2383855.74      7031873.67
#Sta/Elev= 30
  4537.8  628.73  4619.7  630.12  4679.8  629.67  4719.9  628.05  4739.9  626.03
  4759.9  624.94  4769.9  622.45  4779.9  621.84  4910.1  621.07  4940.2  619.98
  4950.2   619.2  4958.2  617.79  4958.4  617.29  4961.9  617.29  4962.2  617.79
  4990.2  621.14  5000.2  624.32  5010.2  624.79  5050.3  625.37  5078.3  624.94
  5110.4  625.24  5130.4  625.78  5150.4  626.89  5210.5  626.54  5246.9  627.17
  5288.7  627.19  5347.4  630.48    5383  631.06  5403.8  631.31  5456.4   630.6
#Mann= 3 ,-1 , 0
  4537.8     .05       0  4958.2     .05       0  4962.2     .05       0
Bank Sta=4958.2,4962.2
XS Rating Curve= 0 ,0
Exp/Cntr=0.3,0.1

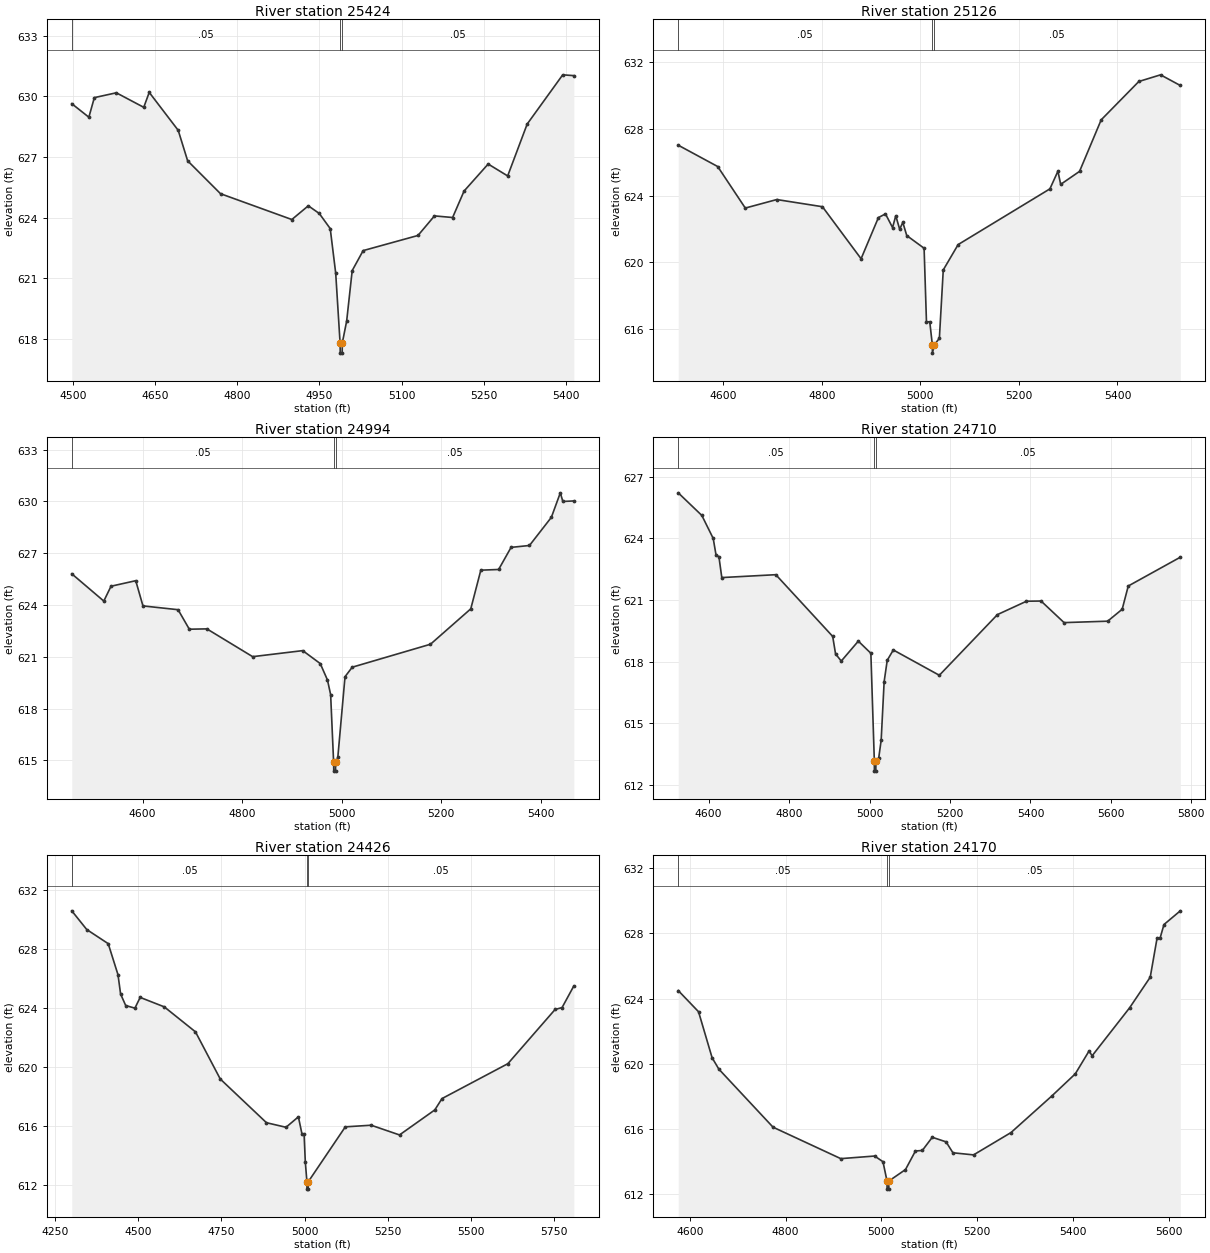
Type RM Length L Ch R = 1 ,25424   ,298,298,298
BEGIN DESCRIPTION:
Dove Creek 52.0
END DESCRIPTION:
XS GIS Cut Line= 3
       2383027.8      7032174.77      2383705.18      7032140.28
      2383845.12      7031947.46
#Sta/Elev= 30
    4498  629.64  4529.2  628.97  4539.2  629.94  4579.3  630.18  4629.4  629.46
  4639.4   630.2  4692.3  628.32  4709.5  626.81  4769.5  625.18  4899.7   623.9
  4929.8  624.58  4949.8   624.2  4969.8  623.45  4979.8  621.24  4987.8  617.78
  4988.1  617.28  4991.6  617.28  4991.8  617.78  4999.8  618.87  5009.9  621.37
  5029.9  622.36    5130  623.11  5160.1  624.08  5193.2     624  5214.1  625.31
  5258.1  626.65  5293.7  626.06  5329.3  628.63  5394.2  631.07  5414.5  631.03
#Mann= 3 ,-1 , 0
    4498     .05       0  4987.8     .05       0  4991.8     .05       0
Bank Sta=4987.8,4991.8
XS Rating Curve= 0 ,0
Exp/Cntr=0.3,0.1

Type RM Length L Ch R = 1 ,25126   ,132,132,132
BEGIN DESCRIPTION:
Dove Creek 51.0
END DESCRIPTION:
XS GIS Cut Line= 4
      2383316.33      7032689.08      2383711.45      7032369.22
      2383740.17      7032159.59       2383880.8      7031895.67
#Sta/Elev= 30
  4508.5  627.02  4588.6  625.74  4644.6  623.25  4708.5  623.76  4801.2  623.33
  4879.6  620.21  4914.8  622.68  4929.1   622.9  4943.5  622.08    4950  622.79
  4957.9  621.98  4964.3  622.39  4972.3   621.6  5007.5  620.84  5012.3  616.43
    5019  616.43  5024.2  615.05  5024.4  614.55  5028.2  615.05  5038.5  615.44
  5046.4  619.54  5076.6  621.06  5262.8   624.4  5279.1  625.46  5284.7  624.67
    5323  625.45  5366.9  628.54  5443.3  630.84  5487.4  631.24  5527.5   630.6
#Mann= 3 ,-1 , 0
  4508.5     .05       0  5024.2     .05       0  5028.2     .05       0
Bank Sta=5024.2,5028.2
XS Rating Curve= 0 ,0
Exp/Cntr=0.3,0.1

Type RM Length L Ch R = 1 ,24994   ,284,284,284
BEGIN DESCRIPTION:
Dove Creek 50.0
END DESCRIPTION:
XS GIS Cut Line= 3
      2383382.17      7032773.77      2383865.12      7032397.44
      2383927.85      7032005.39
#Sta/Elev= 30
  4457.7  625.81  4522.1  624.23  4536.6  625.09  4586.3  625.41  4600.8  623.95
  4671.4  623.73    4694   622.6  4729.3  622.62  4821.3  621.01    4922  621.36
  4957.2  620.61  4971.7  619.66  4978.1  618.81  4984.1  614.88  4984.4  614.38
  4987.9  614.38  4988.1  614.88  4992.5  615.17    5007  619.85  5021.5   620.4
  5178.8  621.73  5259.8  623.78    5280  626.02  5315.8  626.06  5340.8  627.34
  5377.8  627.45  5421.8  629.08  5439.8   630.5  5444.9     630    5467  630.03
#Mann= 3 ,-1 , 0
  4457.7     .05       0  4984.1     .05       0  4988.1     .05       0
Bank Sta=4984.1,4988.1
XS Rating Curve= 0 ,0
Exp/Cntr=0.3,0.1

Type RM Length L Ch R = 1 ,24710   ,284,284,284
BEGIN DESCRIPTION:
Dove Creek 49.0
END DESCRIPTION:
XS GIS Cut Line= 3
      2383639.29      7032993.34        2383979.        7032660.
      2384404.21      7032015.34
#Sta/Elev= 30
  4524.3  626.21    4583  625.11  4611.3  623.99  4618.4  623.17  4625.4  623.11
  4632.6  622.09  4766.9  622.23  4908.3  619.23  4915.4  618.38  4929.6  618.03
    4972     619  5003.2  618.41  5011.8  613.18    5012  612.68  5015.5  612.68
  5015.8  613.18  5022.8  613.33  5028.8  614.18  5036.2  617.03  5043.9  618.07
    5059  618.57  5173.4  617.34  5317.9  620.29  5390.1  620.94  5426.3  620.95
  5483.5   619.9  5591.9  619.97    5628  620.55  5643.1  621.68  5772.5  623.08
#Mann= 3 ,-1 , 0
  4524.3     .05       0  5011.8     .04       0  5015.8     .05       0
Bank Sta=5011.8,5015.8
XS Rating Curve= 0 ,0
Exp/Cntr=0.3,0.1

Type RM Length L Ch R = 1 ,24426   ,256,256,256
BEGIN DESCRIPTION:
Dove Creek 48.0
END DESCRIPTION:
XS GIS Cut Line= 3
      2383579.03      7033209.98        2384179.        7032860.
      2384778.98      7032310.02
#Sta/Elev= 30
  4300.5   630.6  4345.5  629.33    4410  628.37  4439.4  626.26  4447.2  624.95
  4462.5  624.17  4490.2  623.99    4506  624.72  4578.3  624.08  4672.2  622.38
  4746.6  619.18  4885.5  616.21  4944.2   615.9  4981.4  616.61  4992.2  615.44
  4998.5  615.44  5002.2  613.54    5007   612.2  5007.2   611.7  5010.7   611.7
    5011   612.2  5122.4  615.93  5200.1  616.04  5285.2  615.38  5391.3  617.08
  5412.9  617.85  5610.8  620.22  5752.6   623.9  5773.6  624.03    5809   625.5
#Mann= 3 ,-1 , 0
  4300.5     .05       0    5007    .033       0    5011     .05       0
Bank Sta=5007,5011
XS Rating Curve= 0 ,0
Exp/Cntr=0.3,0.1

Type RM Length L Ch R = 1 ,24170   ,374,374,374
BEGIN DESCRIPTION:
Dove Creek 47.0
END DESCRIPTION:
XS GIS Cut Line= 3
      2384079.03      7033309.97        2384379.        7033010.
       2384861.7      7032614.43
#Sta/Elev= 30
    4576  624.49  4618.4  623.19  4646.7  620.37  4660.8  619.67  4773.9  616.11
  4915.4  614.18  4986.1  614.34  5003.5  613.99  5011.9  612.81  5012.1  612.31
  5015.6  612.31  5015.9  612.81  5050.5  613.51  5071.3  614.65  5085.6  614.68
  5106.4  615.49  5135.2  615.21  5149.5  614.54  5192.6  614.41  5270.8  615.78
  5355.5  618.01    5405  619.38  5433.7  620.78  5440.2  620.49  5518.4  623.43
  5561.5  625.31  5575.8  627.71  5582.3  627.73  5590.2  628.54  5624.3  629.38
#Mann= 3 ,-1 , 0
    4576     .05       0  5011.9    .033       0  5015.9     .05       0
Bank Sta=5011.9,5015.9
XS Rating Curve= 0 ,0
Exp/Cntr=0.3,0.1

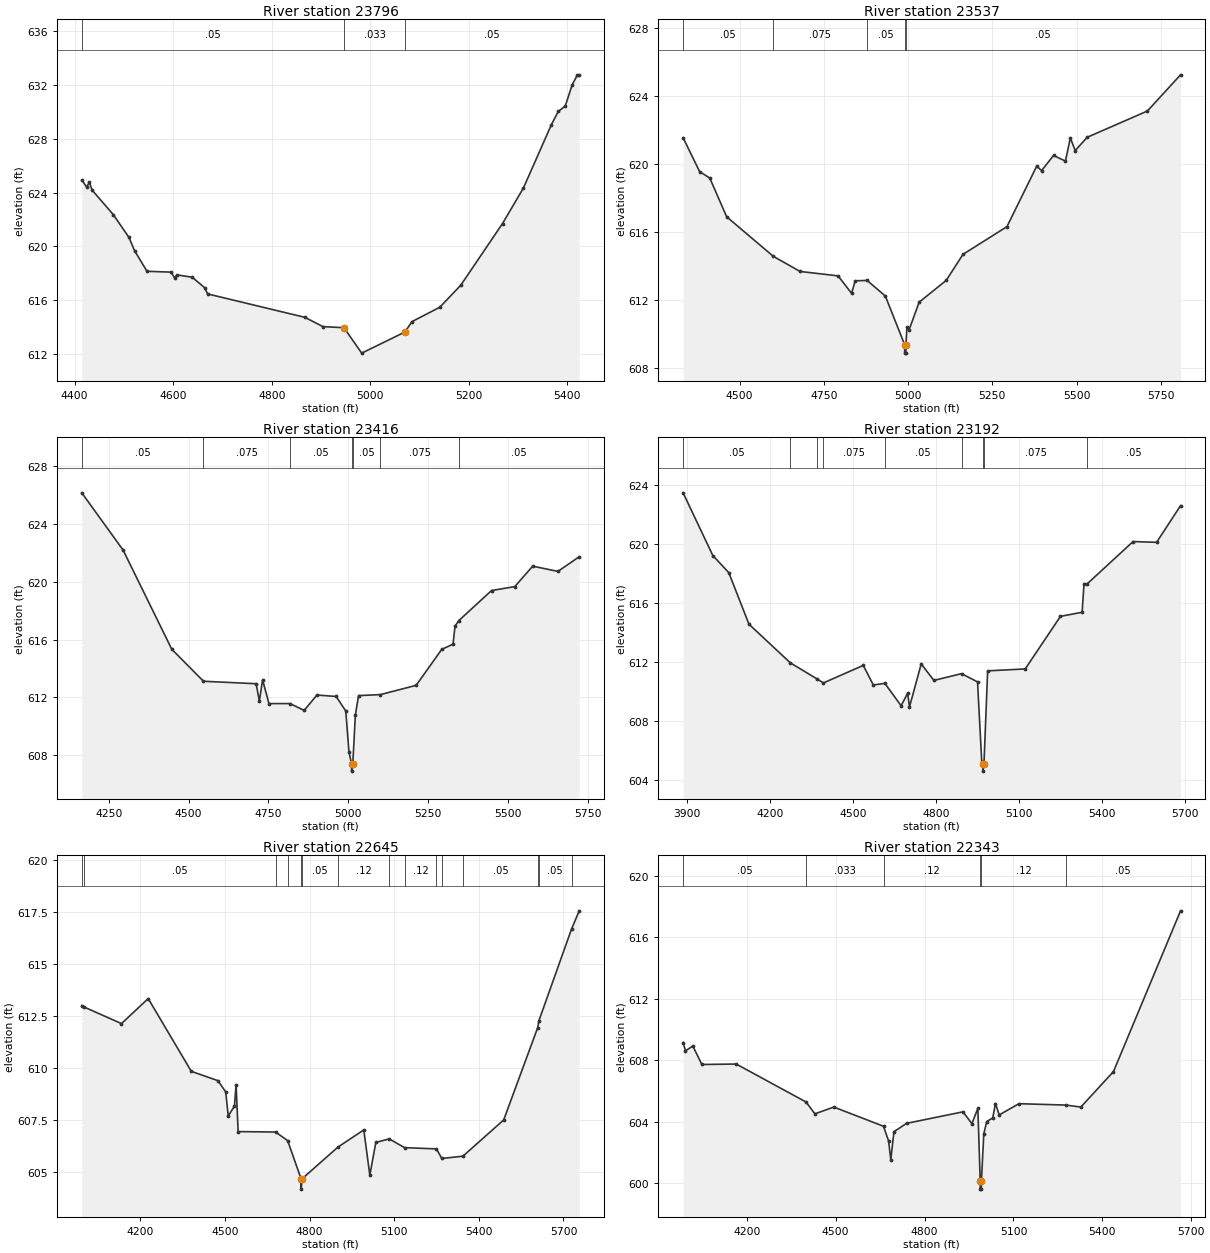
Type RM Length L Ch R = 1 ,23796   ,259,259,259
BEGIN DESCRIPTION:
Dove Creek 46.0
END DESCRIPTION:
XS GIS Cut Line= 3
      2384129.04      7033409.99        2384679.        7033210.
      2384979.03      7032909.97
#Sta/Elev= 30
  4414.6  624.92  4424.5  624.42  4429.9  624.76  4435.8  624.17  4478.4  622.37
  4510.3  620.67  4521.6  619.69  4546.9  618.15  4595.4  618.09  4602.8  617.68
  4608.1  617.88  4638.7  617.71  4663.9  616.93  4669.9  616.47  4867.4  614.73
    4904  614.04  4946.6  613.96  4982.7  612.07  5070.5  613.64  5084.6  614.41
  5141.2  615.48  5183.6  617.11  5268.5   621.7  5310.9  624.34  5367.5  629.03
  5381.6  630.03  5395.8  630.43  5409.9  632.01  5420.5  632.75  5424.1  632.75
#Mann= 3 ,-1 , 0
  4414.6     .05       0  4946.6    .033       0  5070.5     .05       0
Bank Sta=4946.6,5070.5
XS Rating Curve= 0 ,0
Exp/Cntr=0.3,0.1

Type RM Length L Ch R = 1 ,23537   ,121,121,121
BEGIN DESCRIPTION:
Dove Creek 45.3
END DESCRIPTION:
XS GIS Cut Line= 3
      2384210.09      7033407.29      2385191.72      7033344.56
      2385583.72      7033046.64
#Sta/Elev= 30
  4332.5  621.56  4381.5  619.57  4411.6  619.19  4461.7  616.91  4600.1  614.58
  4679.6  613.69  4792.3  613.43  4832.4   612.4  4843.1  613.14  4878.6  613.16
  4932.6  612.24  4989.7  609.38  4989.9  608.88  4993.4  608.88  4993.7  609.38
  4996.7  610.43  5002.8  610.24  5032.8  611.88    5113  613.16  5163.1   614.7
  5293.4  616.33  5381.7  619.89  5396.2  619.63  5431.6  620.52  5466.9  620.19
  5481.5  621.55    5496  620.81  5531.4  621.59  5710.2  623.14  5808.5  625.27
#Mann= 5 ,-1 , 0
  4332.5     .05       0  4600.1    .075       0  4878.6     .05       0
  4989.7    .033       0  4993.7     .05       0
Bank Sta=4989.7,4993.7
XS Rating Curve= 0 ,0
Exp/Cntr=0.3,0.1

Type RM Length L Ch R = 1 ,23416   ,224,224,224
BEGIN DESCRIPTION:
Dove Creek 45.0
END DESCRIPTION:
XS GIS Cut Line= 3
      2384094.03      7033523.33      2385157.22      7033454.33
      2385549.23       7033156.4
#Sta/Elev= 30
  4165.3  626.12  4294.7  622.17  4447.1  615.33  4546.4  613.12  4711.4  612.95
  4721.4  611.75  4731.5  613.22  4751.5  611.58  4817.5  611.58  4861.7  611.11
  4901.8  612.17  4961.9  612.07    4992  611.07    5002  608.27    5010  607.42
  5010.3  606.92    5014  607.42  5022.1   610.8  5032.1  612.13  5100.8   612.2
  5212.5  612.84  5292.6  615.32    5328  615.68  5334.2  616.92  5345.8   617.3
  5448.6  619.38  5521.3  619.65  5577.5  621.06  5656.5   620.7  5723.1  621.71
#Mann= 7 ,-1 , 0
  4165.3     .05       0  4546.4    .075       0  4817.5     .05       0
    5010     .05       0    5014     .05       0  5100.8    .075       0
  5345.8     .05       0
Bank Sta=5010,5014
XS Rating Curve= 0 ,0
Exp/Cntr=0.3,0.1

Type RM Length L Ch R = 1 ,23192   ,547,547,547
BEGIN DESCRIPTION:
Dove Creek 44.0
END DESCRIPTION:
XS GIS Cut Line= 3
      2384134.85      7034213.27      2385088.23        7033608.
      2385580.62      7033159.52
#Sta/Elev= 30
  3887.2  623.48  3994.4  619.22    4052  618.06  4124.8  614.56  4274.3  611.93
  4370.6  610.84  4393.5  610.57  4537.3  611.76  4573.7  610.43  4615.3  610.54
  4673.9  609.02  4697.6  609.87  4704.2  608.94  4746.5  611.86  4792.3  610.74
    4892   611.2  4949.8  610.64  4965.1  605.18    4969  605.08  4969.3  604.58
    4973  605.08  4986.3  611.39  5121.9  611.52    5249  615.09  5327.3  615.37
  5334.1  617.31    5345  617.29  5511.1  620.17  5596.2  620.12  5682.5  622.61
#Mann= 9 ,-1 , 0
  3887.2     .05       0  4274.3    .075       0  4370.6     .05       0
  4393.5    .075       0  4615.3     .05       0    4892    .075       0
    4969     .07       0    4973    .075       0    5345     .05       0
Bank Sta=4969,4973
XS Rating Curve= 0 ,0
Exp/Cntr=0.3,0.1

Type RM Length L Ch R = 1 ,22645   ,302,302,302
BEGIN DESCRIPTION:
Dove Creek 43.0
END DESCRIPTION:
XS GIS Cut Line= 3
      2384376.35      7034639.78      2385426.93      7033996.88
      2385743.71      7033570.33
#Sta/Elev= 30
  3992.8     613  4001.8  612.93  4133.4  612.14  4228.2  613.34    4381  609.85
  4475.8   609.4    4503  608.86  4511.8  607.71  4533.9  608.18  4539.7  609.21
  4546.9  606.96  4679.4  606.94  4722.3  606.53  4769.9   604.7  4770.2   604.2
  4773.9   604.7    4901  606.22  4992.4  607.04  5013.7  604.87    5035  606.44
  5082.6  606.61  5136.9  606.19  5249.9  606.13  5268.8  605.67  5343.6  605.78
  5488.2  607.52  5608.8  611.95  5612.7  612.27  5728.5  616.67  5755.8  617.55
#Mann= 15 ,-1 , 0
  3992.8    .075       0  4001.8     .05       0  4679.4     .12       0
  4722.3     .05       0  4769.9     .07       0  4773.9     .05       0
    4901     .12       0  5082.6     .05       0  5136.9     .12       0
  5249.9     .05       0  5268.8     .12       0  5343.6     .05       0
  5608.8    .075       0  5612.7     .05       0  5728.5    .075       0
Bank Sta=4769.9,4773.9
XS Rating Curve= 0 ,0
Exp/Cntr=0.3,0.1

Type RM Length L Ch R = 1 ,22343   ,341,341,341
BEGIN DESCRIPTION:
Dove Creek 42.0
END DESCRIPTION:
XS GIS Cut Line= 4
       2385172.9      7035166.68      2385492.79      7034307.36
       2385502.2      7034166.24      2385790.72      7033617.42
#Sta/Elev= 30
  3985.3  609.15  3993.1  608.61  4018.1  608.92  4048.4  607.72  4164.5  607.75
    4400  605.28  4429.9  604.51  4493.9  604.95  4661.4   603.7  4678.5  602.75
    4686  601.53  4696.7  603.35  4739.4  603.89  4929.6  604.64  4959.7  603.87
  4979.8  604.87  4987.8  600.11    4988  599.61  4991.5  599.61  4991.8  600.11
  4999.8  603.21  5009.8  604.01  5029.9  604.24  5039.3  605.18  5051.9  604.44
  5118.5  605.17  5276.6  605.08  5327.2  604.95  5437.4  607.26  5663.7  617.72
#Mann= 6 ,-1 , 0
  3985.3     .05       0    4400    .033       0  4661.4     .12       0
  4987.8     .07       0  4991.8     .12       0  5276.6     .05       0
Bank Sta=4987.8,4991.8
XS Rating Curve= 0 ,0
Exp/Cntr=0.3,0.1

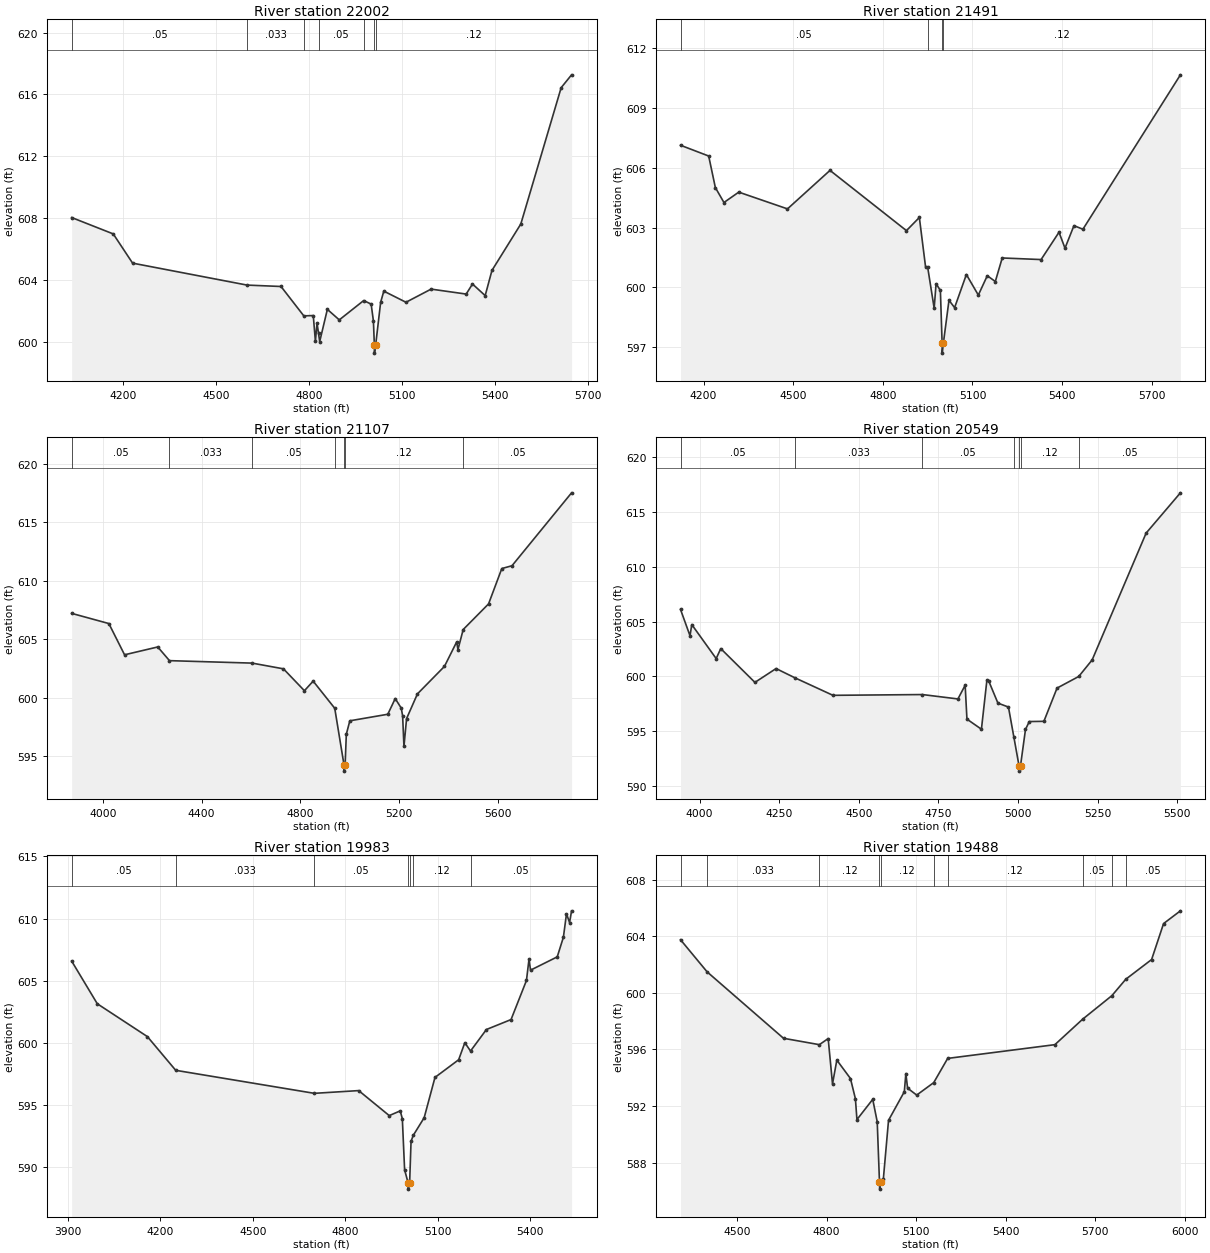
Type RM Length L Ch R = 1 ,22002   ,511,511,511
BEGIN DESCRIPTION:
Dove Creek 41.0
END DESCRIPTION:
XS GIS Cut Line= 3
      2385511.62      7035288.95      2385775.05      7034392.04
       2385919.3       7033727.2
#Sta/Elev= 30
  4033.2  608.04  4167.6  606.98  4230.1  605.09    4600  603.67  4709.6  603.58
  4783.2  601.68  4813.8   601.7  4820.7  600.04  4825.9  601.22  4830.8  600.54
  4834.6  600.02  4859.3   602.1  4897.8  601.42  4976.7  602.67  5000.8  602.44
  5008.1  601.35  5011.2  599.77  5011.4  599.27  5015.2  599.77  5031.5  602.56
  5041.7  603.28  5113.3  602.56  5194.5  603.41  5307.8  603.09  5328.2  603.74
  5369.2  602.99  5391.1  604.62  5484.3  607.62  5614.7  616.44  5648.3  617.27
#Mann= 7 ,-1 , 0
  4033.2     .05       0    4600    .033       0  4783.2     .12       0
  4830.8     .05       0  4976.7     .12       0  5011.2     .07       0
  5015.2     .12       0
Bank Sta=5011.2,5015.2
XS Rating Curve= 0 ,0
Exp/Cntr=0.3,0.1

Type RM Length L Ch R = 1 ,21491   ,384,384,384
BEGIN DESCRIPTION:
Dove Creek 40.0
END DESCRIPTION:
XS GIS Cut Line= 3
      2385558.65      7035223.13       2386135.7      7034508.08
      2386126.31      7033753.59
#Sta/Elev= 30
  4122.7  607.13    4217  606.59  4239.3  605.01  4268.1  604.26  4317.7  604.78
  4480.8  603.94  4623.1  605.87    4879  602.85  4922.2  603.51    4943  601.03
  4950.1  601.01  4971.8  598.96  4978.2  600.19  4992.6  599.85  4998.4  597.21
  4998.8  596.71  5002.6  597.21  5021.4  599.36  5040.2  598.99  5079.6  600.65
  5119.6  599.62  5149.6  600.59  5176.5   600.3  5199.6  601.48  5329.7   601.4
  5389.7  602.77  5409.7  601.97  5439.7   603.1  5469.7  602.92  5796.1  610.66
#Mann= 4 ,-1 , 0
  4122.7     .05       0  4950.1     .12       0  4998.4     .07       0
  5002.6     .12       0
Bank Sta=4998.4,5002.6
XS Rating Curve= 0 ,0
Exp/Cntr=0.3,0.1

Type RM Length L Ch R = 1 ,21107   ,558,558,558
BEGIN DESCRIPTION:
Dove Creek 39.0
END DESCRIPTION:
XS GIS Cut Line= 3
      2385589.99      7035263.92      2386408.55      7034445.36
      2386719.04       7033636.2
#Sta/Elev= 30
  3873.9  607.22  4024.5  606.35  4088.1  603.68  4222.5  604.35    4270  603.18
  4604.6  602.97  4731.6  602.48  4816.4  600.61  4851.8  601.43  4939.2  599.11
    4977  594.24  4977.3  593.74  4981.2  594.24  4986.1  596.89  5000.3  598.04
  5154.1   598.6  5184.1  599.94  5208.6  599.12  5214.1  598.46  5219.5  595.85
  5230.1  598.23  5274.1  600.34  5383.5  602.69  5432.9  604.78  5438.2  604.13
  5459.4  605.84  5562.1  608.03  5615.7  611.05    5657  611.29  5898.2  617.52
#Mann= 7 ,-1 , 0
  3873.9     .05       0    4270    .033       0  4604.6     .05       0
  4939.2     .12       0    4977     .07       0  4981.2     .12       0
  5459.4     .05       0
Bank Sta=4977,4981.2
XS Rating Curve= 0 ,0
Exp/Cntr=0.3,0.1

Type RM Length L Ch R = 1 ,20549   ,566,566,566
BEGIN DESCRIPTION:
Dove Creek 38.0
END DESCRIPTION:
XS GIS Cut Line= 3
      2386370.93      7035411.27      2386806.84      7034489.26
      2387026.24      7033984.66
#Sta/Elev= 30
  3940.2  606.11    3970  603.71  3975.6  604.73  4052.2  601.63  4066.6  602.54
  4173.9  599.46  4240.3  600.72    4300  599.87    4419  598.28    4700  598.35
  4811.5  597.95  4834.2   599.2  4839.8  596.11  4885.3  595.19  4902.5  599.66
    4908   599.6  4937.1  597.57  4970.2  597.21  4987.4  594.44  5003.3  591.87
  5003.9  591.37  5008.1  591.87  5023.7  595.17  5035.6  595.89  5081.5  595.91
  5122.8  598.94    5191     600  5233.1  601.51  5402.6  613.07  5510.3  616.74
#Mann= 7 ,-1 , 0
  3940.2     .05       0    4300    .033       0    4700     .05       0
  4987.4     .12       0  5003.3     .07       0  5008.1     .12       0
    5191     .05       0
Bank Sta=5003.3,5008.1
XS Rating Curve= 0 ,0
Exp/Cntr=0.3,0.1

Type RM Length L Ch R = 1 ,19983   ,495,495,495
BEGIN DESCRIPTION:
Dove Creek 37.0
END DESCRIPTION:
XS GIS Cut Line= 3
      2386465.03       7035483.4      2387289.81      7034592.75
      2387296.06      7034183.49
#Sta/Elev= 30
  3912.1  606.58  3995.3  603.15    4158  600.51    4250   597.8    4700  595.95
  4844.1  596.17  4943.3  594.16    4979  594.54  4985.8  593.91  4993.2   589.8
  5004.6  588.75  5005.2  588.25  5009.5  588.75  5014.1  592.09  5021.2  592.57
  5056.7  593.99  5091.8  597.23  5168.7  598.65  5188.7  600.02  5207.2  599.35
  5258.8  601.08  5338.8  601.88  5388.8  605.02  5397.1  606.73  5402.1  605.85
  5488.8  606.92  5508.8   608.5  5518.8  610.38  5528.8  609.68  5535.3  610.62
#Mann= 7 ,-1 , 0
  3912.1     .05       0    4250    .033       0    4700     .05       0
  5004.6    .033       0  5009.5     .05       0  5021.2     .12       0
  5207.2     .05       0
Bank Sta=5004.6,5009.5
XS Rating Curve= 0 ,0
Exp/Cntr=0.3,0.1

Type RM Length L Ch R = 1 ,19488   ,455,455,455
BEGIN DESCRIPTION:
Dove Creek 36.0
END DESCRIPTION:
XS GIS Cut Line= 4
      2386609.27      7035524.19      2387057.74      7035179.22
      2387311.76      7035132.17       2387355.6      7034283.65
#Sta/Elev= 30
  4310.9  603.75    4400  601.48  4655.8  596.79  4775.8  596.34  4805.3  596.77
  4819.8  593.57  4834.3  595.25  4879.9  593.95  4896.5  592.52  4901.6  591.05
  4954.5  592.48  4969.5   590.9  4977.1  586.64  4977.8  586.14  4982.2  586.64
  4989.9  586.82  5007.4     591  5060.3  593.02  5065.4   594.3  5071.2  593.27
  5101.7  592.78  5158.7  593.66  5205.4  595.37  5564.4  596.34  5657.4  598.14
  5755.2   599.8  5801.8  600.96  5888.2  602.35  5928.3  604.89  5984.7  605.79
#Mann= 10 ,-1 , 0
  4310.9     .05       0    4400    .033       0  4775.8     .12       0
  4977.1     .07       0  4982.2     .12       0  5158.7     .05       0
  5205.4     .12       0  5657.4     .05       0  5755.2    .075       0
  5801.8     .05       0
Bank Sta=4977.1,4982.2
XS Rating Curve= 0 ,0
Exp/Cntr=0.3,0.1