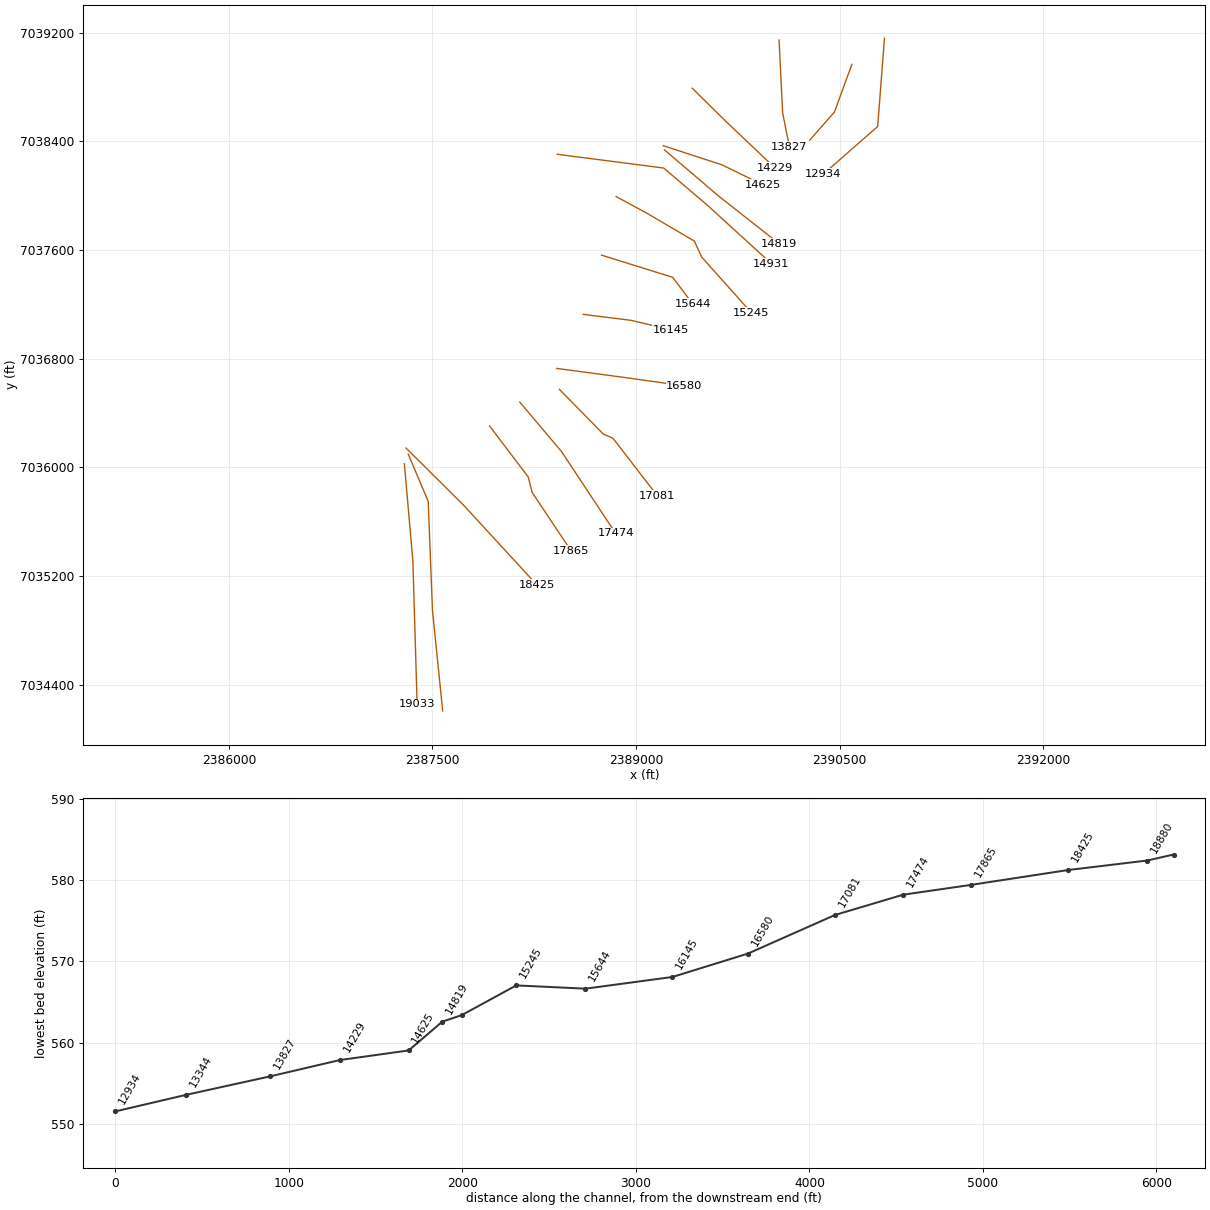
HEC-RAS study Dove Creek.prj: Dove Creek Base Level Engineering

--- Dove Creek.g01 (geometry) --- (continued)

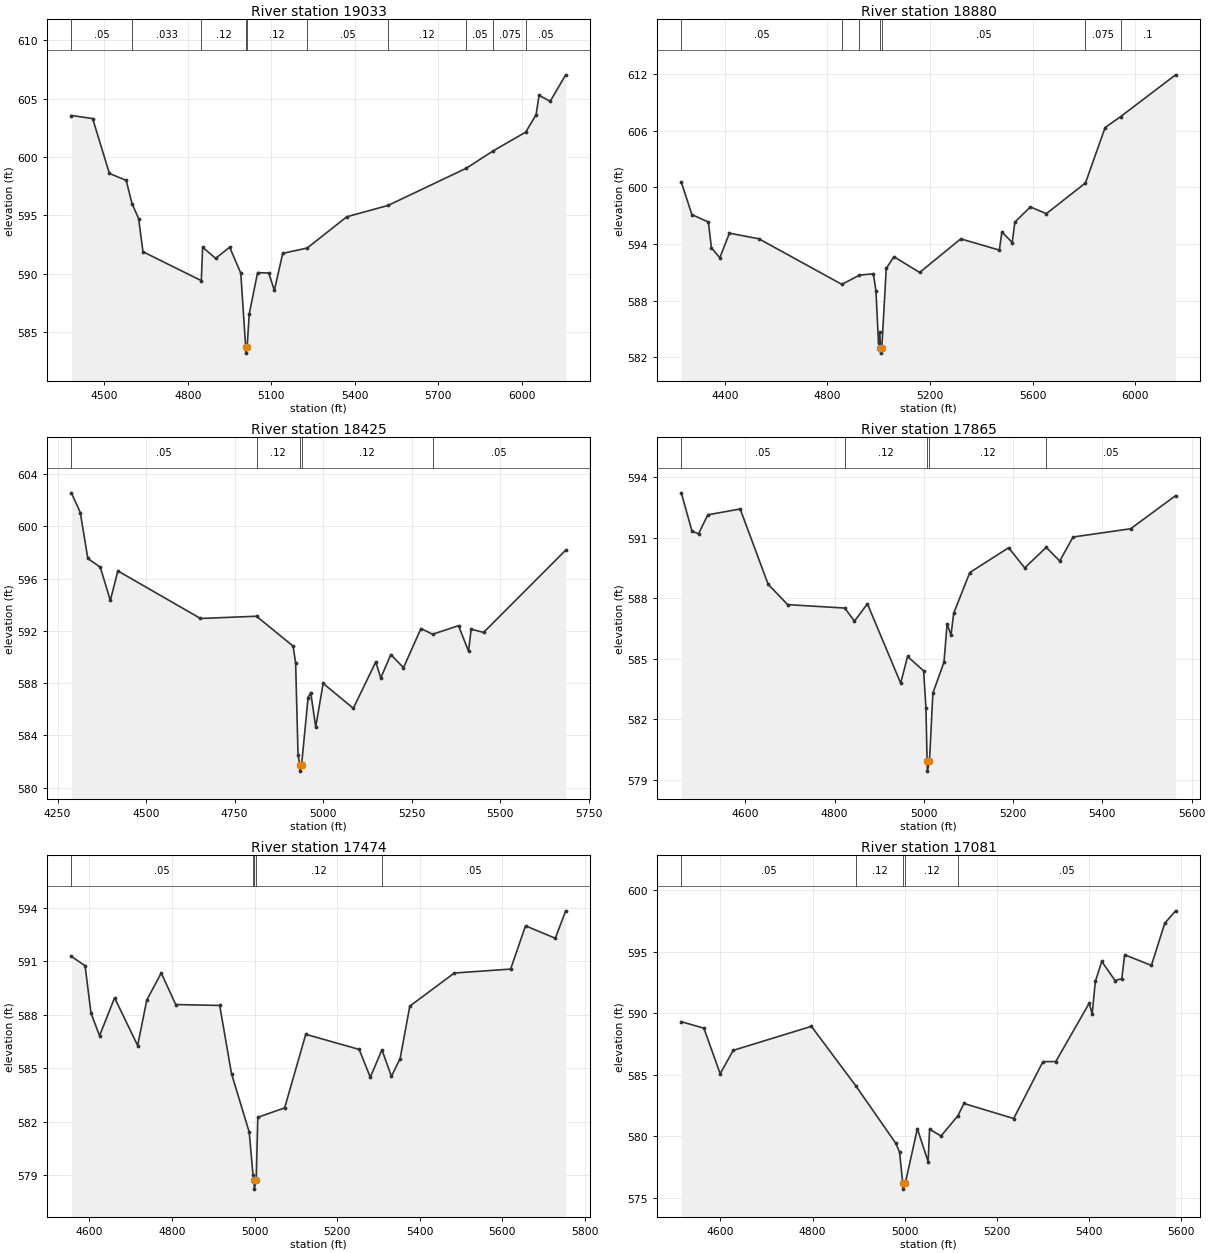
Type RM Length L Ch R = 1 ,19033   ,153,153,153
BEGIN DESCRIPTION:
Dove Creek 35.0
END DESCRIPTION:
XS GIS Cut Line= 3
      2387292.94      7036026.01      2387355.67      7035310.94
      2387387.02      7034254.53
#Sta/Elev= 30
  4382.3  603.56  4458.6   603.3  4518.8  598.59  4579.1  597.99    4600     596
  4623.7  594.72  4639.3  591.87  4848.8  589.39  4853.6  592.26  4900.3   591.3
  4950.5  592.26  4990.6  590.03  5008.1  583.67  5008.8  583.17  5013.3  583.67
  5020.8  586.53  5050.9  590.08    5091  590.04  5111.1  588.55  5141.1  591.73
  5229.1  592.19  5371.2  594.87  5518.9  595.84  5799.9  599.03  5897.7  600.54
  6013.5  602.13  6050.8  603.63  6061.5  605.29  6101.5  604.78    6157  607.05
#Mann= 10 ,-1 , 0
  4382.3     .05       0    4600    .033       0  4848.8     .12       0
  5008.1     .07       0  5013.3     .12       0  5229.1     .05       0
  5518.9     .12       0  5799.9     .05       0  5897.7    .075       0
  6013.5     .05       0
Bank Sta=5008.1,5013.3
XS Rating Curve= 0 ,0
Exp/Cntr=0.3,0.1

Type RM Length L Ch R = 1 ,18880   ,455,455,455
BEGIN DESCRIPTION:
Dove Creek 34.0
END DESCRIPTION:
XS GIS Cut Line= 4
      2387321.16      7036098.14      2387468.59      7035749.78
      2387499.93      7034947.14       2387575.2      7034206.98
#Sta/Elev= 30
  4230.8  600.53  4272.2   597.1  4336.3  596.31  4348.2  593.57  4380.8  592.53
  4418.3  595.13  4532.8  594.54  4856.4  589.71  4924.8  590.69  4979.1  590.83
  4989.1  589.01  4999.1  583.47  5004.1  584.63  5006.6  582.93  5007.3  582.43
  5011.8  582.93  5029.2   591.4  5059.2  592.64  5159.3  590.97  5319.4  594.53
  5469.8  593.34  5479.8  595.27    5520  594.14  5530.1   596.3  5590.4  597.91
    5653   597.2  5805.3  600.45  5881.9  606.32    5942  607.47  6156.3   611.9
#Mann= 7 ,-1 , 0
  4230.8     .05       0  4856.4     .12       0  4924.8     .05       0
  5006.6    .033       0  5011.8     .05       0  5805.3    .075       0
    5942      .1       0
Bank Sta=5006.6,5011.8
XS Rating Curve= 0 ,0
Exp/Cntr=0.3,0.1

Type RM Length L Ch R = 1 ,18425   ,560,560,560
BEGIN DESCRIPTION:
Dove Creek 33.0
END DESCRIPTION:
XS GIS Cut Line= 3
      2387305.47      7036142.05      2387728.87      7035721.77
      2388270.13      7035133.59
#Sta/Elev= 30
  4289.2  602.57  4314.4  601.06  4335.6  597.55  4370.9  596.87  4399.2  594.33
  4420.5  596.59  4653.8  592.95    4812  593.12  4915.4  590.83  4922.5  589.54
  4929.3  582.49  4934.1  581.76  4934.8  581.26  4939.4  581.76  4957.7  586.89
  4965.1  587.28  4979.2  584.64  5000.2  587.98  5085.3  586.07  5148.8  589.62
    5163  588.39  5191.3  590.19  5227.1  589.18  5276.4  592.18  5309.5  591.74
  5382.5   592.4  5410.8  590.44  5418.2  592.13  5453.3  591.88  5685.1  598.18
#Mann= 5 ,-1 , 0
  4289.2     .05       0    4812     .12       0  4934.1     .07       0
  4939.4     .12       0  5309.5     .05       0
Bank Sta=4934.1,4939.4
XS Rating Curve= 0 ,0
Exp/Cntr=0.3,0.1

Type RM Length L Ch R = 1 ,17865   ,391,391,391
BEGIN DESCRIPTION:
Dove Creek 32.5
END DESCRIPTION:
XS GIS Cut Line= 4
      2387920.19      7036305.08      2388205.57      7035928.76
       2388233.8      7035815.86       2388521.7        7035384.
#Sta/Elev= 30
  4456.3  593.22  4480.3  591.32  4494.9  591.19  4515.7  592.13  4588.2  592.42
  4650.9  588.69  4694.6  587.68  4822.7  587.51  4844.3  586.86  4873.4  587.72
  4947.9  583.79  4963.4  585.11  4999.4   584.4  5004.6  582.55  5007.1  579.93
  5007.9  579.43  5012.5  579.93  5020.1   583.3    5045  584.83    5052  586.73
  5060.7  586.17  5066.7  587.25  5102.8  589.27  5189.9   590.5  5225.9   589.5
  5274.1  590.52  5304.4  589.84  5334.1  591.03  5463.3  591.44    5564  593.08
#Mann= 5 ,-1 , 0
  4456.3     .05       0  4822.7     .12       0  5007.1     .07       0
  5012.5     .12       0  5274.1     .05       0
Bank Sta=5007.1,5012.5
XS Rating Curve= 0 ,0
Exp/Cntr=0.3,0.1

Type RM Length L Ch R = 1 ,17474   ,393,393,393
BEGIN DESCRIPTION:
Dove Creek 32.0
END DESCRIPTION:
XS GIS Cut Line= 3
      2388142.87       7036480.7      2388450.19      7036116.93
      2388848.39      7035514.93
#Sta/Elev= 30
  4556.1  591.28  4589.3  590.76  4603.6   588.1  4624.4  586.83  4660.8  588.96
  4716.7  586.28  4738.8  588.83  4773.9  590.35    4809  588.58  4915.6  588.53
  4944.2   584.7  4987.1  581.42  4996.3  579.02  4998.7  578.72  4999.4  578.22
  5004.1  578.72  5007.9  582.25    5073  582.78  5124.2  586.91  5253.6  586.06
  5280.6   584.5  5308.8  586.04  5331.8  584.55  5352.9  585.55  5376.3  588.49
  5484.2  590.35  5620.7  590.57  5656.8     593    5729   592.3  5754.1  593.84
#Mann= 5 ,-1 , 0
  4556.1     .05       0  4996.3     .12       0  4998.7     .07       0
  5004.1     .12       0  5308.8     .05       0
Bank Sta=4998.7,5004.1
XS Rating Curve= 0 ,0
Exp/Cntr=0.3,0.1

Type RM Length L Ch R = 1 ,17081   ,501,501,501
BEGIN DESCRIPTION:
Dove Creek 31.0
END DESCRIPTION:
XS GIS Cut Line= 4
      2388434.49      7036574.83      2388757.54      7036245.51
      2388829.67      7036214.15      2389154.91      7035791.97
#Sta/Elev= 30
    4515  589.33    4564   588.8  4599.4   585.1  4627.7     587  4797.4  588.95
  4894.3  584.09  4980.5  579.45  4988.8  578.73  4995.6  576.22  4996.5  575.72
  5001.3  576.22  5027.4  580.63  5050.8  577.95  5053.9  580.59  5078.8  580.04
  5115.3  581.68  5128.6  582.68  5236.5  581.46    5300  586.08  5327.9  586.09
  5400.4  590.83  5406.8  589.95  5413.7   592.6  5427.6  594.23  5456.6  592.67
  5471.1  592.83  5477.4  594.77  5535.4   593.9  5564.4  597.33  5587.9  598.34
#Mann= 5 ,-1 , 0
    4515     .05       0  4894.3     .12       0  4995.6     .07       0
  5001.3     .12       0  5115.3     .05       0
Bank Sta=4995.6,5001.3
XS Rating Curve= 0 ,0
Exp/Cntr=0.3,0.1

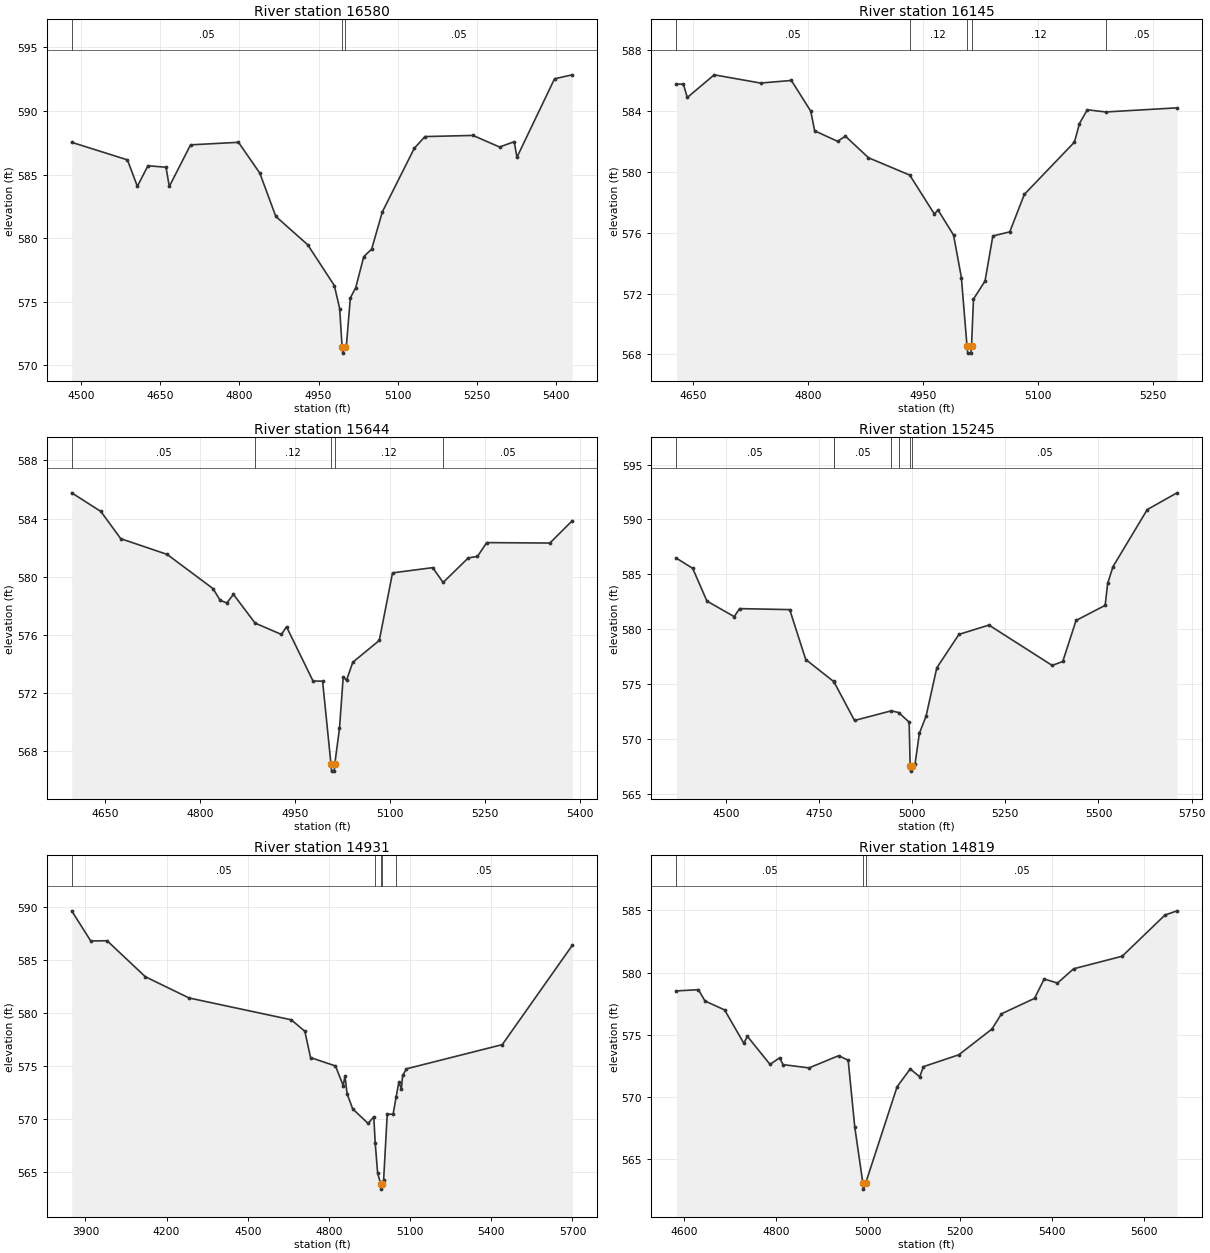
Type RM Length L Ch R = 1 ,16580   ,435,435,435
BEGIN DESCRIPTION:
Dove Creek 30.0
END DESCRIPTION:
XS GIS Cut Line= 3
      2388415.74      7036728.48        2388929.        7036660.
       2389355.3      7036600.07
#Sta/Elev= 30
  4482.2  587.53  4587.8  586.15  4606.6  584.07  4626.7  585.69  4660.9  585.57
  4667.1  584.06  4707.4  587.33  4798.2  587.53  4838.6  585.11  4868.9  581.71
  4929.4  579.48  4979.8  576.28  4989.9  574.47  4994.5  571.47  4995.5  570.97
  5000.4  571.47  5002.5  571.47  5010.1  575.31  5020.2  576.09  5035.6  578.55
  5050.5  579.14  5070.7  582.06  5131.3  587.06  5151.5  587.98  5242.4  588.07
  5292.9  587.16  5320.7  587.58  5325.7  586.35    5397  592.52  5430.5  592.83
#Mann= 3 ,-1 , 0
  4482.2     .05       0  4994.5    .033       0  5000.4     .05       0
Bank Sta=4994.5,5000.4
XS Rating Curve= 0 ,0
Exp/Cntr=0.3,0.1

Type RM Length L Ch R = 1 ,16145   ,501,501,501
BEGIN DESCRIPTION:
Dove Creek 29.0
END DESCRIPTION:
XS GIS Cut Line= 3
      2388610.09      7037126.78      2388961.39      7037082.87
      2389253.01      7037013.88
#Sta/Elev= 30
  4628.2  585.77  4637.2  585.77  4642.4  584.89  4677.5  586.38    4738  585.84
  4778.3  586.01  4803.6  583.99  4808.7   582.7  4838.7  582.01  4848.8  582.35
    4879  580.93  4932.9  579.79  4964.9  577.24  4969.9  577.49  4990.1  575.85
  5000.3  573.06  5007.6  568.59  5008.6  568.09  5012.6  568.09  5013.6  568.59
  5016.1  571.64  5031.2  572.83  5041.4  575.79  5063.5  576.06  5082.5  578.52
    5148  581.96  5154.5  583.18  5164.7  584.08    5189  583.94  5281.9  584.21
#Mann= 5 ,-1 , 0
  4628.2     .05       0  4932.9     .12       0  5007.6     .07       0
  5013.6     .12       0    5189     .05       0
Bank Sta=5007.6,5013.6
XS Rating Curve= 0 ,0
Exp/Cntr=0.3,0.1

Type RM Length L Ch R = 1 ,15644   ,399,399,399
BEGIN DESCRIPTION:
Dove Creek 28.0
END DESCRIPTION:
XS GIS Cut Line= 3
      2388744.99       7037562.7      2389268.73      7037399.62
      2389415.08      7037206.57
#Sta/Elev= 30
  4596.7  585.77  4642.8  584.49  4674.2  582.62  4747.5  581.54    4820  579.19
  4831.3  578.38  4841.8  578.21  4852.3  578.79  4886.5  576.82  4928.1  576.04
  4936.1  576.57    4978  572.84  4993.1  572.83  5006.3  567.15  5007.3  566.65
  5011.4  566.65  5012.4  567.15  5019.8  569.58  5025.7  573.13  5030.9  572.89
  5040.8  574.13  5082.7  575.63  5103.6  580.27  5167.1  580.63  5183.5  579.61
  5223.3   581.3  5237.8   581.4  5252.4  582.35  5352.2  582.32  5387.5  583.85
#Mann= 5 ,-1 , 0
  4596.7     .05       0  4886.5     .12       0  5006.3     .07       0
  5012.4     .12       0  5183.5     .05       0
Bank Sta=5006.3,5012.4
XS Rating Curve= 0 ,0
Exp/Cntr=0.3,0.1

Type RM Length L Ch R = 1 ,15245   ,314,314,314
BEGIN DESCRIPTION:
Dove Creek 27.0
END DESCRIPTION:
XS GIS Cut Line= 5
      2388852.68      7037994.13      2389077.07      7037872.69
      2389428.67      7037666.19      2389483.23        7037548.
      2389849.53       7037138.1
#Sta/Elev= 30
  4367.9  586.47  4411.5  585.54  4449.6  582.56  4522.9  581.14  4537.1  581.87
  4671.7  581.78  4714.7  577.23  4789.4  575.23  4790.6  575.18  4845.6  571.67
  4944.4  572.55    4964  572.39  4992.1  571.52  4994.9  567.55  4995.9  567.05
    5001  567.55  5007.8  567.67  5019.6   570.5  5037.6  572.07  5066.3  576.47
  5125.7  579.52  5206.2  580.37  5375.9  576.69  5404.3  577.05  5439.9  580.79
    5518  582.17  5524.7  584.17  5538.9  585.69  5630.9   590.9  5710.7  592.43
#Mann= 7 ,-1 , 0
  4367.9     .05       0  4789.4     .12       0  4790.6     .05       0
  4944.4     .12       0    4964     .05       0  4994.9    .033       0
    5001     .05       0
Bank Sta=4994.9,5001
XS Rating Curve= 0 ,0
Exp/Cntr=0.3,0.1

Type RM Length L Ch R = 1 ,14931   ,112,112,112
BEGIN DESCRIPTION:
Dove Creek 26.5
END DESCRIPTION:
XS GIS Cut Line= 4
      2388419.17      7038305.39      2389203.09      7038204.06
      2389529.03       7037926.5      2389995.19        7037501.
#Sta/Elev= 30
  3849.4  589.62  3919.8  586.78  3980.3   586.8  4121.5  583.41  4282.8  581.41
  4660.7  579.35  4711.1  578.27    4732  575.79  4824.2     575  4852.8  573.15
  4859.3  574.07    4867  572.39  4887.9  570.95    4945  569.58  4965.8  570.22
  4971.1  567.71  4980.1  564.88  4991.3  563.89  4992.3  563.39  4997.6  563.89
  5002.1  564.24  5015.4  570.44  5037.2  570.46  5048.1  572.03  5058.1  573.44
  5067.9  572.86  5072.4  574.11  5086.6  574.73  5440.6  577.01  5699.1  586.36
#Mann= 5 ,-1 , 0
  3849.4     .05       0  4971.1     .12       0  4991.3     .07       0
  4997.6     .12       0  5048.1     .05       0
Bank Sta=4991.3,4997.6
XS Rating Curve= 0 ,0
Exp/Cntr=0.3,0.1

Type RM Length L Ch R = 1 ,14819   ,194,194,194
BEGIN DESCRIPTION:
Dove Creek 26.3
END DESCRIPTION:
XS GIS Cut Line= 3
      2389209.13      7038337.34      2389610.57      7037995.49
      2390052.81      7037647.35
#Sta/Elev= 30
  4582.7  578.53  4630.5  578.63  4644.8  577.72  4687.6     577  4729.4  574.32
  4737.1  574.88  4786.5  572.62  4807.3  573.15    4815   572.6  4871.5  572.34
  4935.8  573.32  4956.7  572.96    4971  567.59  4988.6  563.09  4989.7  562.59
  4994.9  563.09  5063.2  570.82  5091.8  572.26  5112.5  571.62  5120.6  572.44
  5197.5  573.39  5269.7  575.46  5290.6  576.69  5362.5  577.93  5383.6  579.49
  5412.5  579.16  5447.7  580.31  5553.5  581.32  5646.6  584.63  5672.8  584.97
#Mann= 3 ,-1 , 0
  4582.7     .05       0  4988.6    .033       0  4994.9     .05       0
Bank Sta=4988.6,4994.9
XS Rating Curve= 0 ,0
Exp/Cntr=0.3,0.1

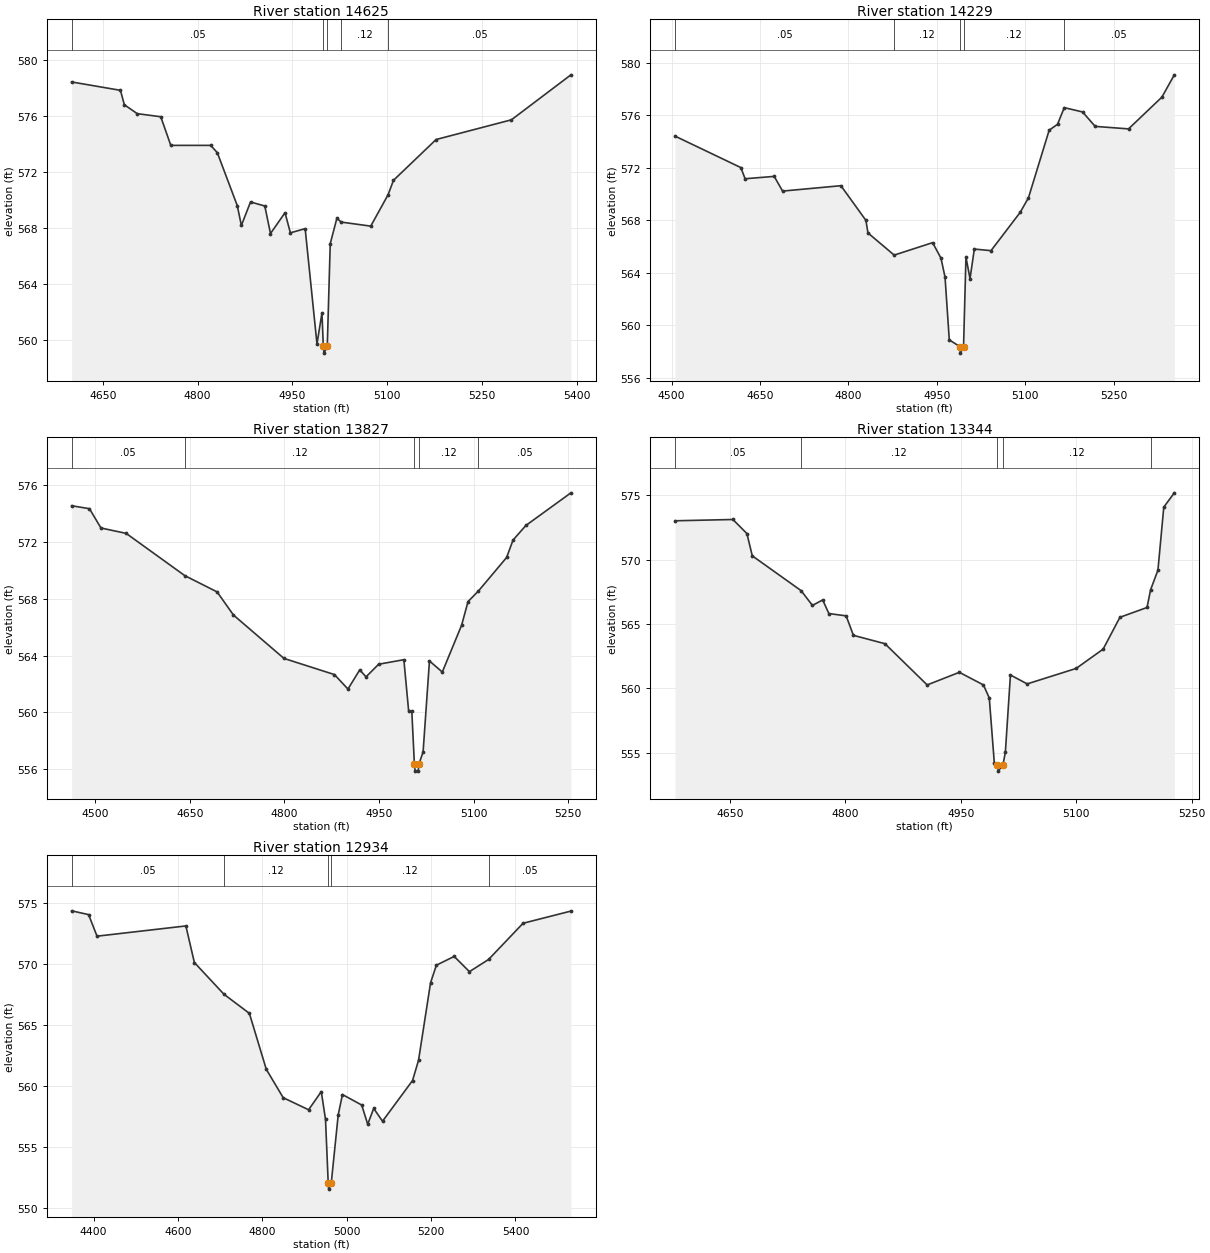
Type RM Length L Ch R = 1 ,14625   ,396,396,396
BEGIN DESCRIPTION:
Dove Creek 26.0
END DESCRIPTION:
XS GIS Cut Line= 3
      2389199.75      7038368.69      2389632.53      7038227.57
      2389933.58      7038080.17
#Sta/Elev= 30
  4600.7  578.45    4678  577.85  4684.1  576.82  4704.6  576.18  4741.8  575.96
  4757.7  573.91  4820.8  573.91  4831.3  573.39  4862.9   569.6  4869.4  568.18
  4883.9  569.86  4906.5  569.57  4915.5   567.6  4938.5  569.09    4947  567.65
  4970.4  567.95  4989.1   559.7    4997  561.92  4999.1  559.54  5000.2  559.04
  5005.4  559.54  5010.1  566.88  5020.6  568.69  5027.5  568.42  5074.2  568.13
  5101.7  570.38  5110.2  571.41  5177.7  574.33  5296.9  575.74  5391.1  578.96
#Mann= 5 ,-1 , 0
  4600.7     .05       0  4999.1    .033       0  5005.4     .05       0
  5027.5     .12       0  5101.7     .05       0
Bank Sta=4999.1,5005.4
XS Rating Curve= 0 ,0
Exp/Cntr=0.3,0.1

Type RM Length L Ch R = 1 ,14229   ,402,402,402
BEGIN DESCRIPTION:
Dove Creek 25.0
END DESCRIPTION:
XS GIS Cut Line= 3
      2389413.02      7038792.05      2389648.21        7038560.
      2390022.96      7038203.99
#Sta/Elev= 30
  4505.7   574.4  4617.4     572  4624.6  571.15    4674  571.33  4688.2  570.21
  4787.2  570.62  4829.6  567.98  4833.1  567.02  4877.6  565.33  4942.8  566.28
    4957   565.1  4963.9  563.65  4971.1  558.87    4989  558.36    4990  557.86
  4995.3  558.36  4999.4  565.17  5006.3  563.54  5013.6  565.79  5041.9  565.67
  5091.3  568.58  5105.4  569.69  5140.6  574.85  5154.8   575.3  5166.2  576.57
  5197.3  576.24  5218.7  575.14  5275.3  574.95  5331.9  577.37    5353  579.07
#Mann= 5 ,-1 , 0
  4505.7     .05       0  4877.6     .12       0    4989     .07       0
  4995.3     .12       0  5166.2     .05       0
Bank Sta=4989,4995.3
XS Rating Curve= 0 ,0
Exp/Cntr=0.3,0.1

Type RM Length L Ch R = 1 ,13827   ,483,483,483
BEGIN DESCRIPTION:
Dove Creek 24.0
END DESCRIPTION:
XS GIS Cut Line= 3
      2390052.77      7039146.41        2390079.        7038610.
        2390129.      7038360.01
#Sta/Elev= 30
  4462.5  574.57  4490.8  574.36    4509     573    4549  572.62    4642  569.64
  4693.3  568.49  4719.2  566.86  4799.3   563.8  4879.4  562.66  4900.8  561.64
  4919.5  562.99  4929.5   562.5  4949.5  563.39  4989.5  563.71  4997.1  560.09
  5002.1  560.09  5006.2  556.35  5007.3  555.85  5012.2  555.85  5013.4  556.35
    5020   557.2  5030.1  563.62  5050.5  562.84  5081.1  566.14  5091.3  567.81
  5107.7  568.55  5152.5  570.92  5162.7  572.15  5183.1  573.18  5254.5  575.48
#Mann= 5 ,-1 , 0
  4462.5     .05       0    4642     .12       0  5006.2     .07       0
  5013.4     .12       0  5107.7     .05       0
Bank Sta=5006.2,5013.4
XS Rating Curve= 0 ,0
Exp/Cntr=0.3,0.1

Type RM Length L Ch R = 1 ,13344   ,410,410,410
BEGIN DESCRIPTION:
Dove Creek 23.0
END DESCRIPTION:
XS GIS Cut Line= 3
      2390589.06      7038967.71      2390460.47      7038616.45
      2390279.02      7038410.02
#Sta/Elev= 30
  4578.5  573.01  4653.7  573.11  4671.9  572.02  4678.9  570.29  4742.3  567.59
  4757.1  566.44  4770.4  566.87  4778.4  565.81  4800.9  565.63  4810.3  564.12
  4851.3  563.47  4906.2  560.27    4948  561.25  4979.3  560.27  4986.9  559.26
  4993.5  554.18  4997.5  554.08  4998.6  553.58  5004.7  554.08  5007.8  555.04
  5014.4  561.04  5036.2  560.35  5099.8  561.55  5134.9  563.05  5156.7  565.52
  5191.9  566.28  5196.6  567.66  5206.1  569.18  5213.7  574.07  5227.4  575.18
#Mann= 5 ,-1 , 0
  4578.5     .05       0  4742.3     .12       0  4997.5     .07       0
  5004.7     .12       0  5196.6     .05       0
Bank Sta=4997.5,5004.7
XS Rating Curve= 0 ,0
Exp/Cntr=0.3,0.1

Type RM Length L Ch R = 1 ,12934   ,419,419,419
BEGIN DESCRIPTION:
Dove Creek 22.0
END DESCRIPTION:
XS GIS Cut Line= 3
        2390829.      7039160.05        2390779.        7038510.
      2390378.98      7038159.98
#Sta/Elev= 30
    4348  574.36  4388.2  574.05  4408.2  572.28  4618.8  573.12  4638.9  570.12
  4709.3  567.51  4769.3  565.95  4809.4  561.36  4849.5  559.03  4909.7  558.04
  4939.8  559.53  4949.8  557.25  4956.2  552.03  4957.3  551.53  4963.4  552.03
  4979.9  557.62  4989.9  559.29  5035.6  558.43  5049.8  556.85    5064  558.15
  5084.9   557.1  5156.1  560.44  5170.3   562.1  5198.8  568.46  5212.6   569.9
  5254.8  570.62  5290.9  569.37  5336.3  570.37  5418.1  573.34  5531.5  574.34
#Mann= 5 ,-1 , 0
    4348     .05       0  4709.3     .12       0  4956.2     .07       0
  4963.4     .12       0  5336.3     .05       0
Bank Sta=4956.2,4963.4
XS Rating Curve= 0 ,0
Exp/Cntr=0.3,0.1