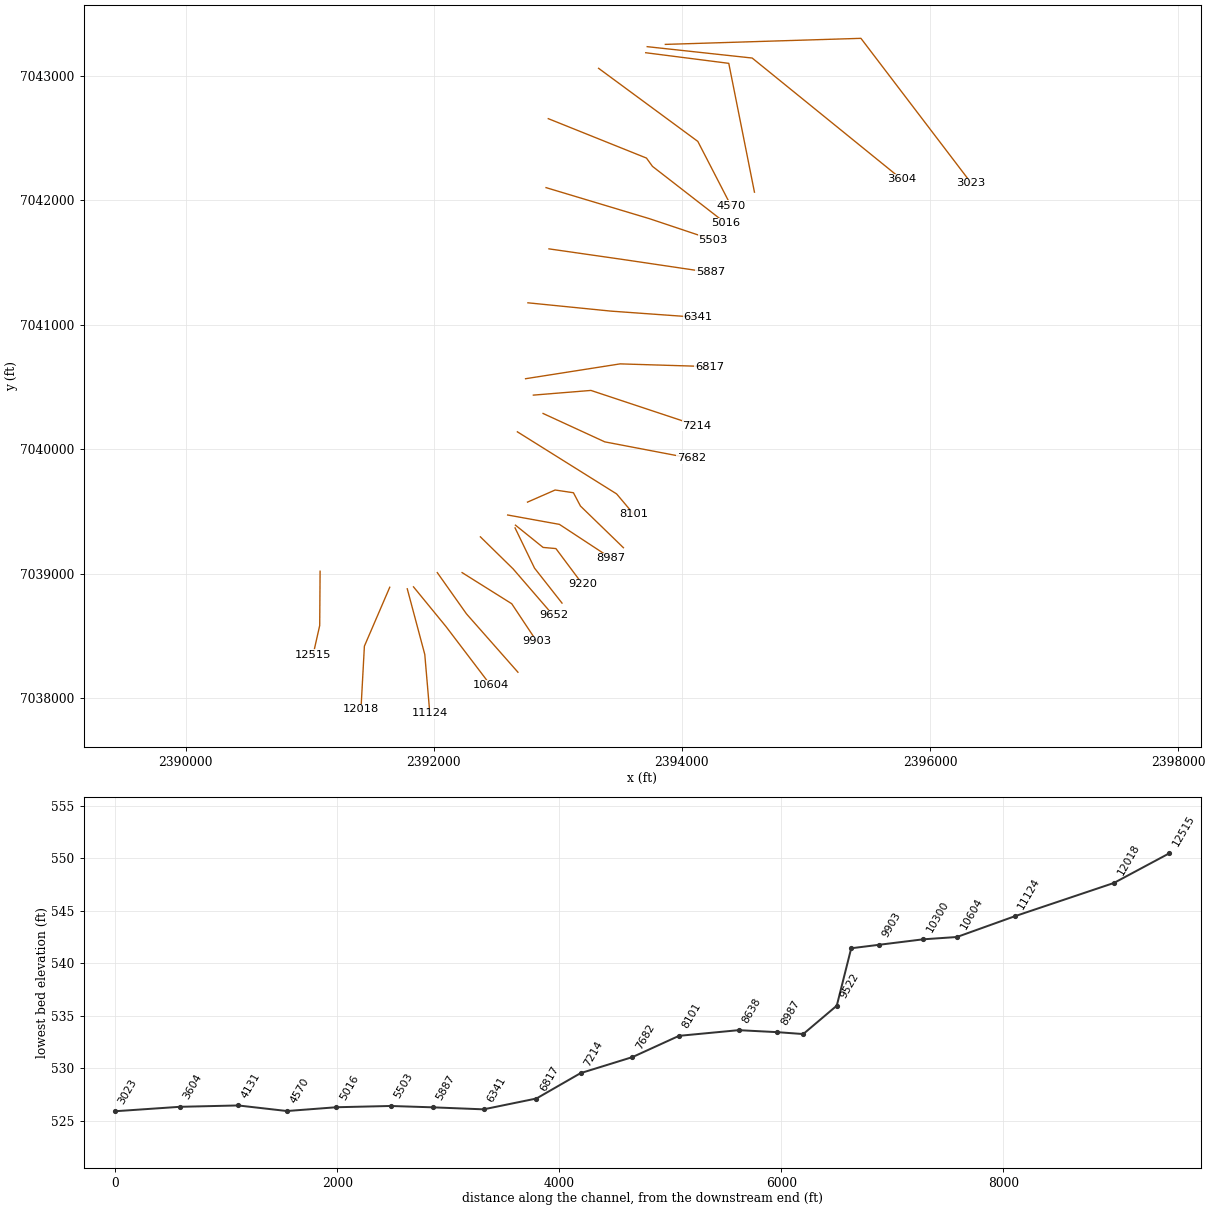
HEC-RAS study Dove Creek.prj: Dove Creek Base Level Engineering

--- Dove Creek.g01 (geometry) --- (continued)

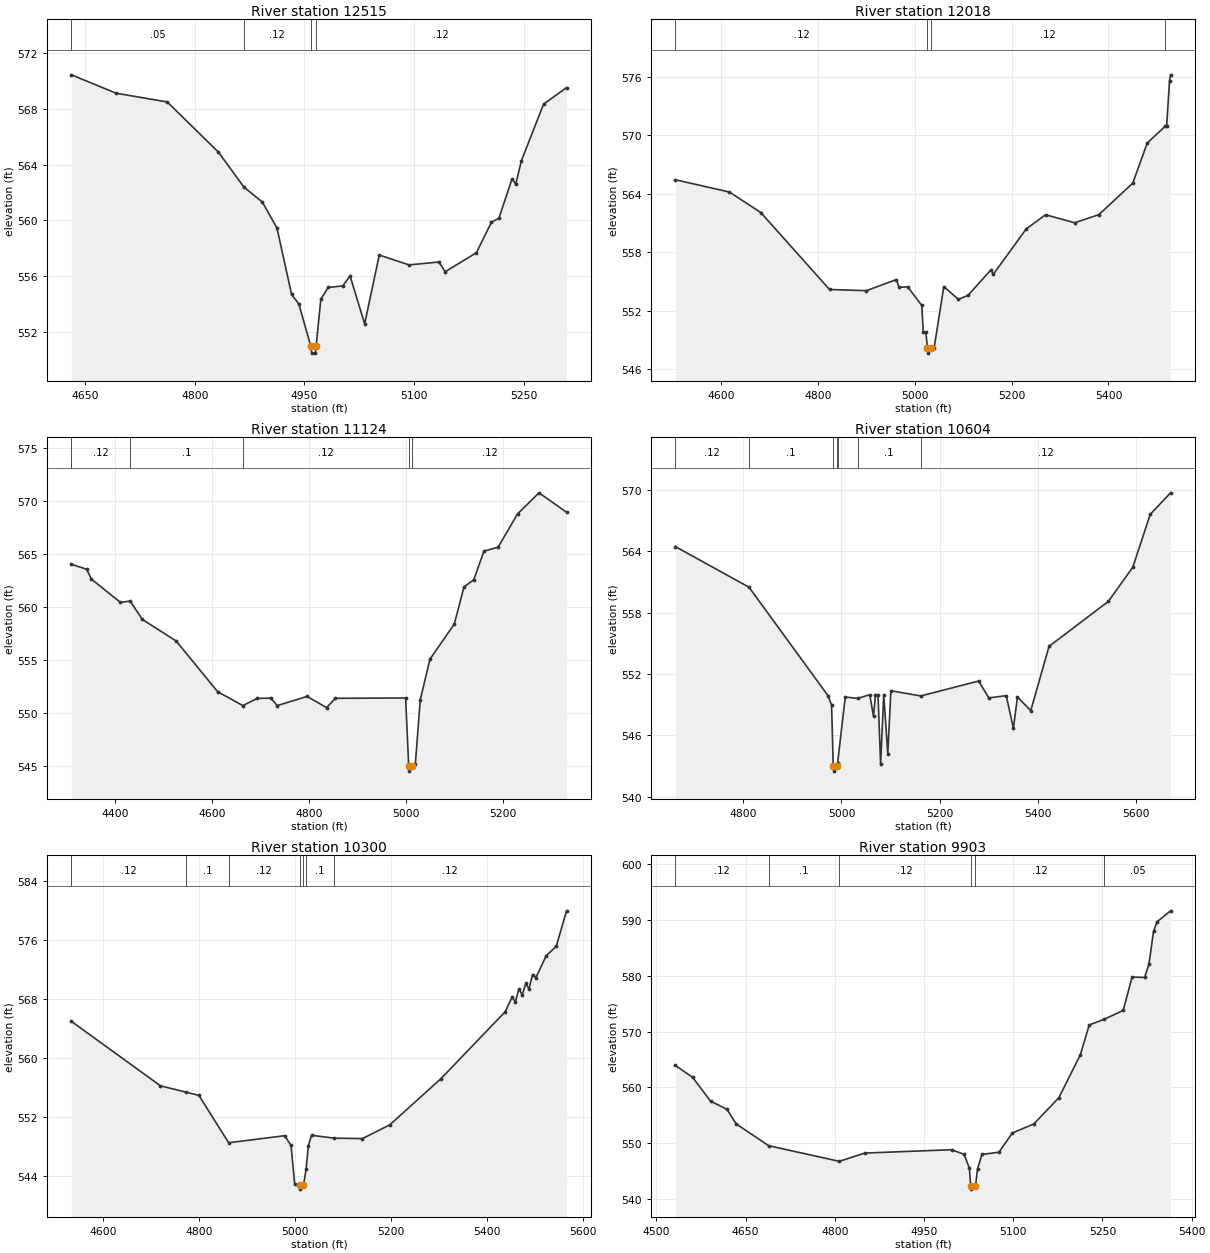
Type RM Length L Ch R = 1 ,12515   ,497,497,497
BEGIN DESCRIPTION:
Dove Creek 21.0
END DESCRIPTION:
XS GIS Cut Line= 3
      2391084.57      7039021.05      2391081.43      7038585.09
      2391028.11      7038349.83
#Sta/Elev= 30
  4631.2  570.45  4692.3  569.13  4762.3   568.5  4832.3  564.89  4867.2  562.38
  4892.3  561.31  4912.3  559.45  4932.3  554.68  4942.3  553.98  4958.6  550.95
  4959.8  550.45  4964.8  550.45  4965.9  550.95  4972.3  554.31  4982.3  555.17
  5002.3  555.28  5012.3     556  5032.3  552.56  5052.3   557.5  5092.9  556.79
  5133.9     557  5142.5   556.3  5185.2  557.67  5205.7  559.86  5215.9  560.14
  5233.9  562.98    5239   562.6  5246.7  564.28    5277  568.34  5308.4  569.53
#Mann= 4 ,-1 , 0
  4631.2     .05       0  4867.2     .12       0  4958.6     .07       0
  4965.9     .12       0
Bank Sta=4958.6,4965.9
XS Rating Curve= 0 ,0
Exp/Cntr=0.3,0.1

Type RM Length L Ch R = 1 ,12018   ,894,894,894
BEGIN DESCRIPTION:
Dove Creek 20.0
END DESCRIPTION:
XS GIS Cut Line= 3
      2391645.93      7038892.41      2391441.54      7038419.23
      2391413.93      7037912.02
#Sta/Elev= 30
  4504.9  565.43  4616.5  564.17  4681.3  562.07  4823.4  554.17  4899.7  554.05
  4961.6  555.19  4967.1  554.39  4985.2  554.44  5014.1  552.53  5017.2   549.8
  5022.5   549.8  5025.9  548.14    5027  547.64  5033.2  548.14  5039.6  548.15
  5059.6  554.47  5089.7  553.16  5109.7  553.57  5156.9  556.18    5162  555.73
  5229.9  560.38  5269.9  561.84    5330  561.02  5380.1  561.85  5450.2  565.08
  5480.2  569.21  5517.8  570.94  5520.3  570.96  5526.2   575.6  5528.3   576.2
#Mann= 4 ,-1 , 0
  4504.9     .12       0  5025.9     .07       0  5033.2     .12       0
  5517.8     .05       0
Bank Sta=5025.9,5033.2
XS Rating Curve= 0 ,0
Exp/Cntr=0.3,0.1

Type RM Length L Ch R = 1 ,11124   ,520,520,520
BEGIN DESCRIPTION:
Dove Creek 19.3
END DESCRIPTION:
XS GIS Cut Line= 3
      2391787.08      7038879.86       2391928.2      7038353.01
      2391968.96      7037879.49
#Sta/Elev= 30
  4310.2  564.04  4341.6  563.57  4351.5  562.63  4411.3  560.43  4431.3  560.56
  4456.5  558.82  4526.2  556.78  4611.5  551.99  4663.6  550.67  4693.1  551.35
  4721.2  551.38  4734.5  550.67  4796.1  551.54  4836.1  550.48  4854.6  551.36
  4999.2  551.39  5005.5  544.97  5006.6  544.47    5013  544.97  5019.2  545.11
  5029.3   551.2  5049.3  555.06  5099.5  558.38  5119.6   561.9  5139.7  562.57
  5160.6  565.28  5189.9  565.66    5230  568.81  5274.1   570.8  5330.9  568.97
#Mann= 5 ,-1 , 0
  4310.2     .12       0  4431.3      .1       0  4663.6     .12       0
  5005.5     .07       0    5013     .12       0
Bank Sta=5005.5,5013
XS Rating Curve= 0 ,0
Exp/Cntr=0.3,0.1

Type RM Length L Ch R = 1 ,10604   ,304,304,304
BEGIN DESCRIPTION:
Dove Creek 19.0
END DESCRIPTION:
XS GIS Cut Line= 3
      2391837.22       7038895.6      2392097.55      7038578.82
      2392460.26      7038103.54
#Sta/Elev= 30
    4662  564.45  4811.8  560.48  4972.7  549.87  4979.9  548.96  4983.2     543
  4984.4   542.5  4990.8     543  4992.2  543.34  5007.8  549.75  5032.8  549.61
  5057.6  549.97  5065.2  547.86  5069.2  549.93  5074.4  549.93  5079.7  543.17
    5086  549.96  5094.3   544.2  5100.6  550.36  5161.5  549.85  5279.3  551.31
  5300.1  549.66  5335.5  549.88    5350  546.67  5358.2  549.76  5385.3  548.41
  5422.6   554.7  5543.2  559.09  5593.1  562.44  5628.5   567.6  5669.9  569.71
#Mann= 7 ,-1 , 0
    4662     .12       0  4811.8      .1       0  4983.2     .07       0
  4990.8      .1       0  4992.2     .12       0  5032.8      .1       0
  5161.5     .12       0
Bank Sta=4983.2,4990.8
XS Rating Curve= 0 ,0
Exp/Cntr=0.3,0.1

Type RM Length L Ch R = 1 ,10300   ,397,397,397
BEGIN DESCRIPTION:
Dove Creek 18.0
END DESCRIPTION:
XS GIS Cut Line= 3
      2392029.03      7039009.96      2392263.77      7038679.17
      2392679.03      7038209.96
#Sta/Elev= 30
    4534  564.99  4719.7  556.26  4773.3   555.4  4799.7  554.97  4861.8  548.56
  4978.6  549.51  4991.9  548.19  4999.5  542.91  5009.6  542.78  5010.8  542.28
  5017.8  542.78  5023.3  544.99  5027.9  548.14  5034.6  549.57  5081.3  549.18
  5140.8  549.12  5197.7  550.98  5303.9   557.2  5438.6  566.31  5452.8  568.27
  5459.5  567.62    5467  569.39  5473.7  568.57  5481.3  570.13  5487.9  569.39
  5495.5  571.32  5502.2  570.89  5523.9  573.88  5544.8  575.14  5566.2  579.95
#Mann= 7 ,-1 , 0
    4534     .12       0  4773.3      .1       0  4861.8     .12       0
  5009.6     .07       0  5017.8     .12       0  5023.3      .1       0
  5081.3     .12       0
Bank Sta=5009.6,5017.8
XS Rating Curve= 0 ,0
Exp/Cntr=0.3,0.1

Type RM Length L Ch R = 1 ,9903    ,251,251,251
BEGIN DESCRIPTION:
Dove Creek 17.0
END DESCRIPTION:
XS GIS Cut Line= 3
      2392228.97      7039010.02        2392629.        7038760.
      2392829.01      7038459.99
#Sta/Elev= 30
  4532.2  563.92  4561.1  561.78  4591.2  557.53  4618.9  556.05  4634.2  553.46
  4688.9  549.54  4807.6  546.74  4850.6  548.22  4996.3  548.82  5017.4     548
  5026.5  545.47  5028.4  542.26  5029.6  541.76  5036.6  542.26    5040  545.39
  5047.5  547.98    5076  548.37  5098.6  551.82  5134.6  553.43  5176.7  558.13
  5212.8  565.81  5227.8  571.17  5252.8  572.19  5284.9  573.77  5299.9  579.76
  5320.9  579.68  5328.4  582.17  5335.9  587.97  5341.9  589.65  5364.5  591.62
#Mann= 6 ,-1 , 0
  4532.2     .12       0  4688.9      .1       0  4807.6     .12       0
  5028.4     .07       0  5036.6     .12       0  5252.8     .05       0
Bank Sta=5028.4,5036.6
XS Rating Curve= 0 ,0
Exp/Cntr=0.3,0.1

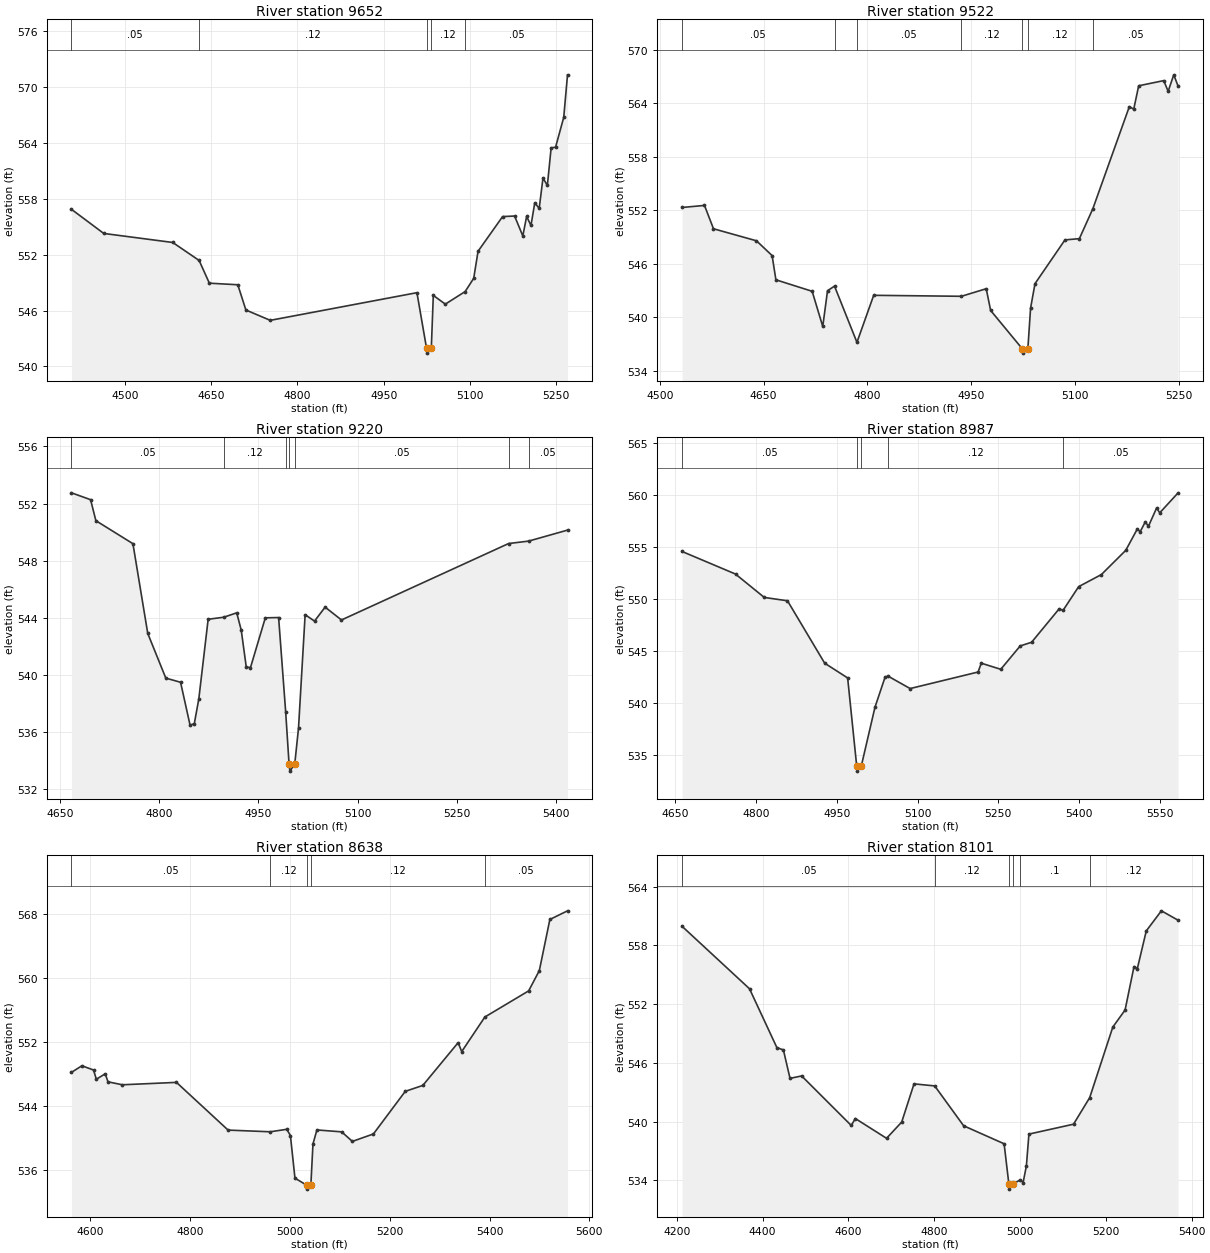
Type RM Length L Ch R = 1 ,9652    ,130,130,130
BEGIN DESCRIPTION:
Dove Creek 17.6
END DESCRIPTION:
XS GIS Cut Line= 3
      2392376.66        7039297.       2392640.1      7039039.83
      2392964.46      7038665.58
#Sta/Elev= 30
  4406.6  556.87  4462.8  554.28  4582.9  553.31  4628.8  551.38  4646.6  548.94
  4696.1  548.77  4710.2  546.06  4752.6  544.95  5007.9  547.92  5024.7  541.93
  5025.9  541.43  5032.9  541.93  5036.4  547.63  5057.3  546.69  5091.8  548.04
  5106.7  549.46  5114.3  552.37    5157  556.09  5177.9  556.15  5192.2  554.01
  5198.8   556.1  5206.4  555.14    5213  557.57  5220.7  556.97  5227.3  560.23
  5234.9  559.43  5241.5  563.47  5249.2  563.54  5263.4  566.74    5270  571.31
#Mann= 5 ,-1 , 0
  4406.6     .05       0  4628.8     .12       0  5024.7     .07       0
  5032.9     .12       0  5091.8     .05       0
Bank Sta=5024.7,5032.9
XS Rating Curve= 0 ,0
Exp/Cntr=0.3,0.1

Type RM Length L Ch R = 1 ,9522    ,302,302,302
BEGIN DESCRIPTION:
Dove Creek 17.4
END DESCRIPTION:
XS GIS Cut Line= 3
      2392655.78      7039369.13      2392812.59      7039046.11
      2393034.15      7038765.26
#Sta/Elev= 30
  4532.3  552.32  4564.7  552.55  4577.7  549.93  4639.8  548.58  4662.4  546.92
  4667.9   544.2  4720.3  542.91  4735.6  538.96  4742.5  542.98  4752.6  543.49
    4785  537.18  4809.2  542.46    4936  542.35  4971.8   543.2  4978.2  540.76
  5023.8  536.47    5025  535.97    5032  536.47  5035.9  541.02  5042.3  543.77
  5085.6  548.68  5106.4  548.82  5125.9  552.18  5178.6  563.64    5185  563.36
  5192.1  565.98  5228.3  566.56  5234.7  565.36  5242.8  567.21  5249.1  565.94
#Mann= 7 ,-1 , 0
  4532.3     .05       0  4752.6     .12       0    4785     .05       0
    4936     .12       0  5023.8     .07       0    5032     .12       0
  5125.9     .05       0
Bank Sta=5023.8,5032
XS Rating Curve= 0 ,0
Exp/Cntr=0.3,0.1

Type RM Length L Ch R = 1 ,9220    ,233,233,233
BEGIN DESCRIPTION:
Dove Creek 16.0
END DESCRIPTION:
XS GIS Cut Line= 4
      2392658.91      7039391.09      2392881.59      7039212.32
      2392985.08      7039202.91      2393201.28      7038914.66
#Sta/Elev= 30
  4667.6  552.75  4696.5  552.27  4704.5   550.8  4760.5  549.19  4782.9  542.91
  4810.2  539.78  4832.5  539.49  4846.9  536.48  4853.3   536.6  4860.1  538.33
  4874.2   543.9  4897.6  544.04  4917.4  544.35  4924.2  543.14  4931.8  540.56
  4938.2  540.52  4960.6     544  4980.7  544.02  4991.4   537.4  4996.5  533.77
  4997.8  533.27  5005.1  533.77  5010.8  536.29  5020.8  544.22    5035  543.77
    5051  544.75  5075.7  543.85  5328.3   549.2  5358.5  549.37  5417.4  550.14
#Mann= 7 ,-1 , 0
  4667.6     .05       0  4897.6     .12       0  4991.4     .05       0
  4996.5    .033       0  5005.1     .05       0  5328.3     .12       0
  5358.5     .05       0
Bank Sta=4996.5,5005.1
XS Rating Curve= 0 ,0
Exp/Cntr=0.3,0.1

Type RM Length L Ch R = 1 ,8987    ,349,349,349
BEGIN DESCRIPTION:
Dove Creek 15.0
END DESCRIPTION:
XS GIS Cut Line= 3
      2392596.23      7039472.62      2393013.31      7039397.36
      2393430.05      7039124.75
#Sta/Elev= 30
  4662.3  554.57  4761.6   552.4  4815.1  550.15  4858.2  549.83  4927.3  543.83
    4970  542.41  4986.8  533.95    4988  533.45  4995.4  533.95  5020.8   539.6
  5039.5  542.48  5044.9  542.59  5086.1  541.39  5212.4  542.98  5218.3  543.83
  5254.5  543.24  5290.7  545.49  5311.8  545.84  5363.1  549.06  5370.3  548.91
  5399.3  551.19  5441.5  552.35  5486.8  554.68  5507.9   556.7  5513.8  556.49
    5523  557.41    5529     557  5544.1  558.75    5550  558.29  5584.1  560.21
#Mann= 5 ,-1 , 0
  4662.3     .05       0  4986.8    .033       0  4995.4     .05       0
  5044.9     .12       0  5370.3     .05       0
Bank Sta=4986.8,4995.4
XS Rating Curve= 0 ,0
Exp/Cntr=0.3,0.1

Type RM Length L Ch R = 1 ,8638    ,537,537,537
BEGIN DESCRIPTION:
Dove Creek 14.0
END DESCRIPTION:
XS GIS Cut Line= 5
       2392756.1       7039576.1      2392978.81      7039673.34
      2393126.21      7039651.38      2393182.66      7039544.76
      2393529.03      7039209.98
#Sta/Elev= 30
  4561.9   548.2  4582.8  549.02  4606.2  548.49  4611.7  547.34  4629.6  548.02
  4635.1  547.02  4663.9  546.65  4772.4  546.95  4875.9     541  4960.4  540.79
  4993.5   541.1  5000.8  540.32  5009.9  535.01  5033.2  534.14  5034.5  533.64
  5041.8  534.14    5046  539.26  5053.9  541.02  5103.6  540.78    5125  539.59
  5167.2  540.52    5231  545.83  5266.2  546.57    5337   551.9  5344.2  550.79
  5390.6   555.1  5478.4  558.36  5499.8  560.89  5520.9  567.26  5556.3  568.34
#Mann= 5 ,-1 , 0
  4561.9     .05       0  4960.4     .12       0  5033.2     .07       0
  5041.8     .12       0  5390.6     .05       0
Bank Sta=5033.2,5041.8
XS Rating Curve= 0 ,0
Exp/Cntr=0.3,0.1

Type RM Length L Ch R = 1 ,8101    ,419,419,419
BEGIN DESCRIPTION:
Dove Creek 13.0
END DESCRIPTION:
XS GIS Cut Line= 3
       2392674.6      7040140.63      2393474.32      7039641.98
      2393612.33      7039478.88
#Sta/Elev= 30
  4212.4  559.94  4369.6  553.56  4433.3  547.56  4448.6  547.31    4464  544.41
  4491.1  544.66  4606.7   539.6  4616.2  540.31    4689  538.29  4724.3  539.95
    4753  543.85  4801.2  543.64  4868.6  539.57    4963  537.73  4974.1   533.6
  4975.3   533.1  4982.7   533.6  5000.8  534.05  5007.2  533.76  5014.9  535.48
  5020.8  538.72  5124.7  539.73  5162.4  542.44  5216.3  549.65  5244.9  551.39
  5265.7  555.83  5273.5  555.63  5294.3  559.47  5329.5  561.52  5368.5  560.56
#Mann= 6 ,-1 , 0
  4212.4     .05       0  4801.2     .12       0  4974.1     .07       0
  4982.7     .12       0  5000.8      .1       0  5162.4     .12       0
Bank Sta=4974.1,4982.7
XS Rating Curve= 0 ,0
Exp/Cntr=0.3,0.1

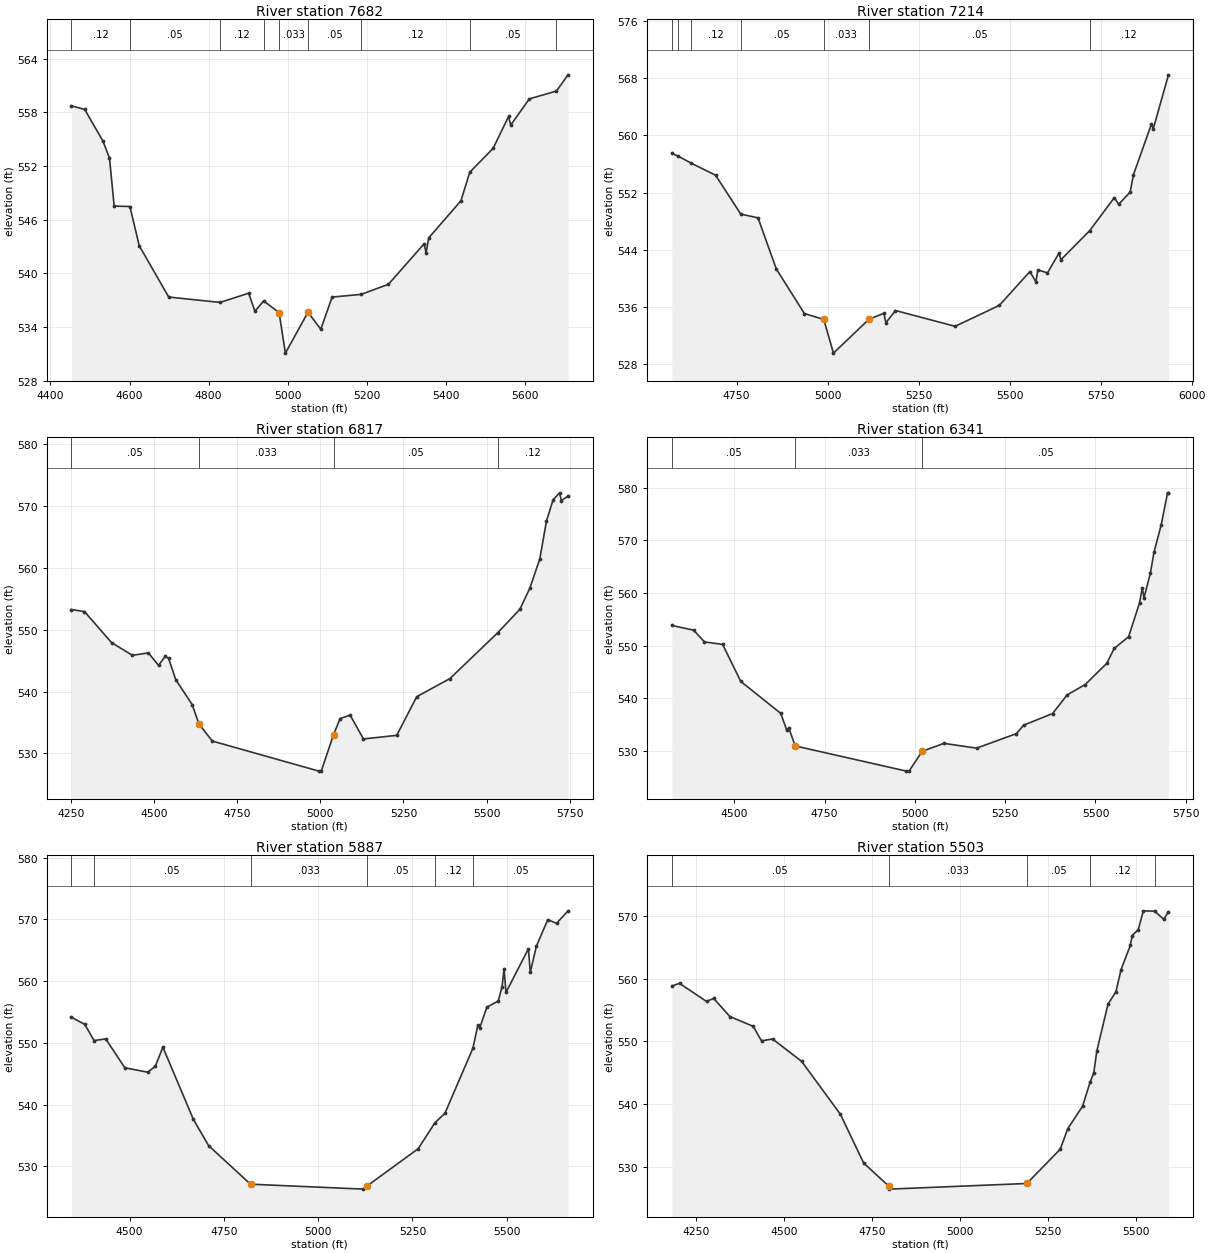
Type RM Length L Ch R = 1 ,7682    ,468,468,468
BEGIN DESCRIPTION:
Dove Creek 12.0
END DESCRIPTION:
XS GIS Cut Line= 3
      2392881.63      7040288.01        2393379.        7040060.
      2394075.18      7039927.61
#Sta/Elev= 30
  4453.3  558.73  4486.7  558.33  4532.7   554.8  4549.4   552.9  4561.2  547.53
    4601  547.47  4624.7  543.08  4699.2  537.35    4829  536.75  4901.4  537.78
  4917.2  535.76  4939.3  536.92  4978.4   535.6  4994.2  531.08  5051.3  535.65
  5083.8  533.75  5112.4  537.35    5186  537.65  5254.9  538.78  5344.9   543.3
    5350  542.31  5356.7  543.97  5438.1  548.11  5460.5  551.31  5519.6  553.98
  5558.8  557.56  5563.9  556.57  5611.1  559.51  5679.5  560.38  5709.1   562.2
#Mann= 9 ,-1 , 0
  4453.3     .12       0    4601     .05       0    4829     .12       0
  4939.3     .05       0  4978.4    .033       0  5051.3     .05       0
    5186     .12       0  5460.5     .05       0  5679.5     .12       0
Bank Sta=4978.4,5051.3
XS Rating Curve= 0 ,0
Exp/Cntr=0.3,0.1

Type RM Length L Ch R = 1 ,7214    ,397,397,397
BEGIN DESCRIPTION:
Dove Creek 11.0
END DESCRIPTION:
XS GIS Cut Line= 3
      2392803.16      7040435.42      2393267.34      7040473.06
      2394120.35      7040190.81
#Sta/Elev= 30
  4572.1  557.49  4588.3  557.12  4625.4  556.11    4692  554.43  4761.4  548.99
  4808.7  548.47  4858.9  541.32  4936.1  535.09  4989.3  534.26  5015.9  529.55
  5113.3  534.28  5154.6  535.12  5159.8  533.79  5186.3  535.51  5350.1   533.3
  5471.4  536.22  5555.7  540.96  5572.1  539.52  5577.4   541.2  5603.9  540.77
  5635.6  543.55  5640.8  542.61  5720.1  546.69  5787.4  551.29  5799.4  550.36
  5831.1  552.07  5840.1  554.51  5889.3  561.56  5894.6  560.94  5936.3  568.47
#Mann= 7 ,-1 , 0
  4572.1     .12       0  4588.3     .05       0  4625.4     .12       0
  4761.4     .05       0  4989.3    .033       0  5113.3     .05       0
  5720.1     .12       0
Bank Sta=4989.3,5113.3
XS Rating Curve= 0 ,0
Exp/Cntr=0.3,0.1

Type RM Length L Ch R = 1 ,6817    ,476,476,476
BEGIN DESCRIPTION:
Dove Creek 10.0
END DESCRIPTION:
XS GIS Cut Line= 3
      2392740.49      7040567.15      2393502.55      7040686.32
      2394223.89      7040664.36
#Sta/Elev= 30
    4252  553.28    4291  552.96  4372.3  547.94    4435  545.88  4483.3  546.27
  4513.7  544.24  4533.9  545.73    4544  545.38  4565.5  541.93  4614.9  537.91
  4635.1  534.76  4675.6     532    4996  527.14    5003  527.14  5039.8  533.04
  5059.8  535.65  5089.8   536.2  5129.8  532.35  5229.9  532.93  5289.9  539.18
  5389.9  542.12  5532.9   549.5    5600  553.32  5630.1  556.74  5660.1   561.5
  5680.1  567.62  5700.1  571.05  5719.6  572.17  5724.6  570.92    5745  571.64
#Mann= 4 ,-1 , 0
    4252     .05       0  4635.1    .033       0  5039.8     .05       0
  5532.9     .12       0
Bank Sta=4635.1,5039.8
XS Rating Curve= 0 ,0
Exp/Cntr=0.3,0.1

Type RM Length L Ch R = 1 ,6341    ,454,454,454
BEGIN DESCRIPTION:
Dove Creek 9.0
END DESCRIPTION:
XS GIS Cut Line= 3
      2392759.33      7041176.78        2393429.        7041110.
      2394129.02        7041060.
#Sta/Elev= 30
  4327.4  553.82  4387.4  552.92  4417.5  550.69  4467.8  550.21    4518  543.18
  4628.6   537.1  4645.6  533.87  4650.7  534.35  4668.8   530.9  4976.8  526.11
  4983.8  526.11  5020.4  529.88  5080.6  531.39  5170.8  530.48  5281.1  533.24
  5301.2  534.85  5381.4  537.06  5421.5   540.6  5471.6  542.58  5531.7  546.63
  5551.8  549.44  5591.9  551.68    5622   558.1  5629.5   560.9  5634.5  559.09
    5652  563.74  5662.1  567.73  5682.1  572.97  5699.7  579.04  5702.2  579.04
#Mann= 3 ,-1 , 0
  4327.4     .05       0  4668.8    .033       0  5020.4     .05       0
Bank Sta=4668.8,5020.4
XS Rating Curve= 0 ,0
Exp/Cntr=0.3,0.1

Type RM Length L Ch R = 1 ,5887    ,384,384,384
BEGIN DESCRIPTION:
Dove Creek 8.0
END DESCRIPTION:
XS GIS Cut Line= 3
      2392928.98        7041610.      2393532.23      7041523.67
      2394232.13      7041420.21
#Sta/Elev= 30
  4345.8  554.13  4381.1  552.97  4405.7  550.36  4436.7  550.63  4487.2  545.95
  4547.9  545.24  4568.1  546.18  4588.1   549.3  4669.1  537.58  4709.5  533.34
  4820.6   527.1  5119.7   526.3  5129.4   526.8  5265.3  532.85  5309.8  537.06
  5336.1  538.58  5410.3  549.11  5423.4  552.84  5428.5  552.41  5447.3  555.77
  5477.6  556.76  5487.7  559.09    5493  561.99    5498  558.15  5557.5  565.22
  5562.5  561.42  5578.7  565.65    5609  569.95  5632.1  569.34  5662.7  571.37
#Mann= 6 ,-1 , 0
  4345.8     .12       0  4405.7     .05       0  4820.6    .033       0
  5129.4     .05       0  5309.8     .12       0  5410.3     .05       0
Bank Sta=4820.6,5129.4
XS Rating Curve= 0 ,0
Exp/Cntr=0.3,0.1

Type RM Length L Ch R = 1 ,5503    ,487,487,487
BEGIN DESCRIPTION:
Dove Creek 7.0
END DESCRIPTION:
XS GIS Cut Line= 3
      2392905.42      7042101.82      2393739.15      7041852.31
      2394250.33      7041681.92
#Sta/Elev= 30
  4182.5  558.82  4204.1  559.25  4280.7  556.37  4301.1  556.85  4346.9  553.96
  4413.1   552.4  4436.8  550.08  4468.1  550.38  4550.7  546.81  4660.5  538.38
  4726.6  530.59  4797.6  526.93  4799.2  526.43  5189.6  527.33  5284.5   532.8
  5305.6  536.05  5347.8  539.66  5369.6  543.56  5379.4  544.91  5388.4  548.49
    5420  555.93  5442.6  557.93  5456.9  561.44  5483.3   565.3  5488.5  566.88
  5505.9  567.82  5520.1  570.82  5552.7  570.76  5578.1  569.46  5591.6  570.67
#Mann= 5 ,-1 , 0
  4182.5     .05       0  4797.6    .033       0  5189.6     .05       0
  5369.6     .12       0  5552.7     .05       0
Bank Sta=4797.6,5189.6
XS Rating Curve= 0 ,0
Exp/Cntr=0.3,0.1

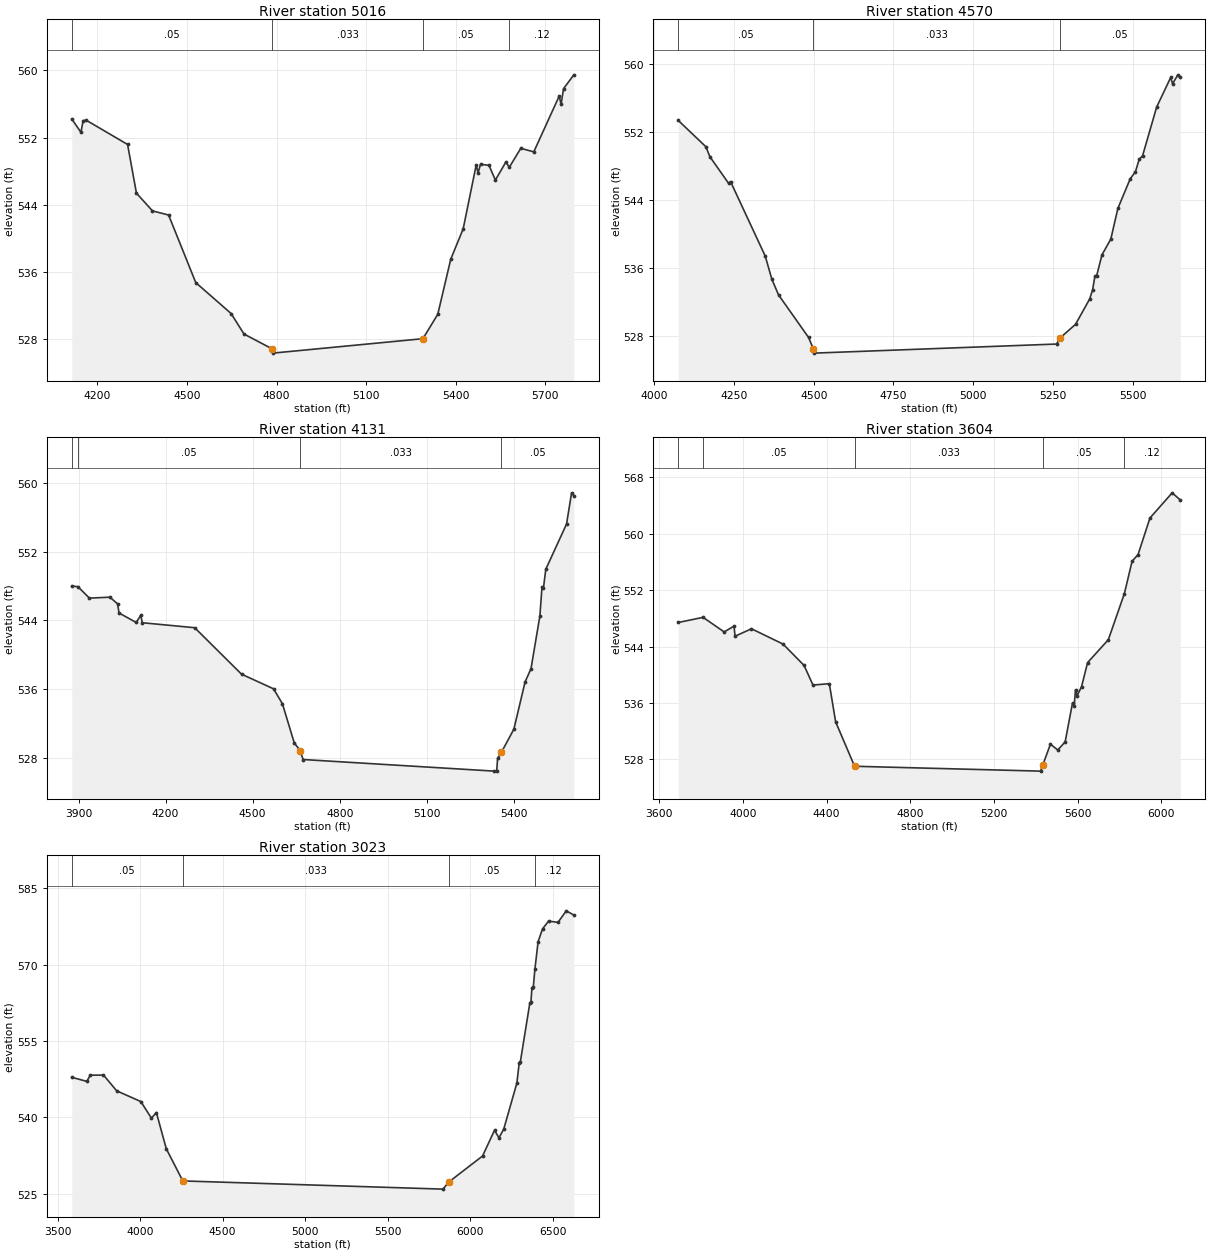
Type RM Length L Ch R = 1 ,5016    ,446,446,446
BEGIN DESCRIPTION:
Dove Creek 6.0
END DESCRIPTION:
XS GIS Cut Line= 4
      2392923.63      7042655.65      2393714.81      7042339.18
       2393763.5      7042272.24      2394353.82      7041815.81
#Sta/Elev= 30
  4114.3  554.22    4145  552.63  4152.4  554.02  4163.2  554.06  4301.2  551.18
  4330.8  545.38  4384.6  543.26  4438.5  542.77  4529.4  534.72  4647.8  531.03
  4690.9  528.59  4785.6  526.81  4787.1  526.31    5290  528.03  5339.8  530.94
  5383.3  537.51  5424.9  541.13  5468.4  548.72  5474.7   547.8  5482.9  548.82
  5511.2  548.69  5532.7  546.94    5568   549.1  5579.2  548.46  5617.8  550.72
  5661.3   550.3  5746.4  556.95  5752.7  555.97  5760.9  557.83  5795.4  559.48
#Mann= 4 ,-1 , 0
  4114.3     .05       0  4785.6    .033       0    5290     .05       0
  5579.2     .12       0
Bank Sta=4785.6,5290
XS Rating Curve= 0 ,0
Exp/Cntr=0.3,0.1

Type RM Length L Ch R = 1 ,4570    ,439,439,439
BEGIN DESCRIPTION:
Dove Creek 5.0
END DESCRIPTION:
XS GIS Cut Line= 3
      2393329.02      7043059.99      2394128.65      7042473.07
      2394396.43      7041955.77
#Sta/Elev= 30
  4075.2  553.35    4162  550.25  4174.4  549.08    4233  545.95  4239.2  546.15
    4348  537.38  4368.8  534.65  4389.7  532.81  4483.8   527.8    4499  526.45
  4500.5  525.95    5262  527.02  5271.1  527.69    5321  529.34  5365.2  532.31
  5374.6  533.41  5381.8  535.01  5387.4  535.07  5403.9  537.52  5431.7  539.38
  5453.8  542.99  5492.4  546.47  5508.9  547.31    5521   548.8  5531.1  549.17
  5575.4  554.92  5619.6  558.42  5625.3  557.66  5641.8  558.72  5649.6  558.45
#Mann= 3 ,-1 , 0
  4075.2     .05       0    4499    .033       0  5271.1     .05       0
Bank Sta=4499,5271.1
XS Rating Curve= 0 ,0
Exp/Cntr=0.3,0.1

Type RM Length L Ch R = 1 ,4131    ,527,527,527
BEGIN DESCRIPTION:
Dove Creek 4.0
END DESCRIPTION:
XS GIS Cut Line= 3
      2393708.77      7043185.11      2394378.17      7043099.92
      2394585.09      7042065.31
#Sta/Elev= 30
  3876.7     548  3897.9  547.92  3937.4  546.59    4008   546.7  4034.6  545.92
  4039.6  544.86  4098.7  543.76  4114.5   544.6  4119.6  543.73  4300.3  543.15
  4461.6  537.75  4571.8  536.05  4602.4  534.32  4643.2  529.77  4663.6  528.86
  4673.8  527.83  5332.6  526.48  5340.8  526.48  5343.9  527.95  5357.1  528.67
    5400  531.36  5438.6  536.85    5459  538.39  5489.6  544.52  5496.9  547.89
    5502   547.8    5510  549.95  5581.4   555.2  5598.9  558.83  5606.6  558.49
#Mann= 4 ,-1 , 0
  3876.7    .075       0  3897.9     .05       0  4663.6    .033       0
  5357.1     .05       0
Bank Sta=4663.6,5357.1
XS Rating Curve= 0 ,0
Exp/Cntr=0.3,0.1

Type RM Length L Ch R = 1 ,3604    ,581,581,581
BEGIN DESCRIPTION:
Dove Creek 3.0
END DESCRIPTION:
XS GIS Cut Line= 3
      2393720.91      7043233.81      2394566.83      7043142.52
      2395771.84      7042168.78
#Sta/Elev= 30
  3690.7  547.43  3809.6  548.16  3910.1  546.09  3957.3  546.91  3962.3  545.48
  4040.8  546.54  4191.7  544.37  4292.3  541.34  4334.8  538.56    4413  538.75
  4443.1  533.34  4533.7  527.04  5422.7  526.35  5433.2   527.2  5469.9  530.17
  5505.1  529.35  5540.3   530.5  5575.5  536.03  5583.5  535.65  5589.9   537.9
  5597.9  537.07  5618.7  538.33  5647.5  541.74  5746.6  544.98  5823.6  551.54
  5860.2  556.11  5888.9  557.07  5945.7  562.25    6052  565.82  6090.8   564.8
#Mann= 5 ,-1 , 0
  3690.7    .075       0  3809.6     .05       0  4533.7    .033       0
  5433.2     .05       0  5823.6     .12       0
Bank Sta=4533.7,5433.2
XS Rating Curve= 0 ,0
Exp/Cntr=0.3,0.1

Type RM Length L Ch R = 1 ,3023    ,0,0,0
BEGIN DESCRIPTION:
Dove Creek 2.0
END DESCRIPTION:
XS GIS Cut Line= 3
      2393866.99      7043252.07       2395443.2      7043300.75
      2396331.76      7042138.33
#Sta/Elev= 30
  3586.3  547.89  3677.3  547.09  3698.4   548.3  3778.4  548.33  3858.4  545.23
  4004.4  543.13  4068.5  539.86  4098.6  540.97  4158.6  533.86  4258.6  527.54
  5834.6  525.93  5867.7  527.29  6073.5  532.43    6146  537.48  6173.2  536.01
  6202.3  537.76  6281.2  546.73  6295.8  550.78    6302  550.83    6360  562.49
  6366.4  562.62  6372.7   565.5    6381  565.65  6390.4  569.07    6410  574.52
  6437.1  577.05  6473.3  578.56  6530.6  578.32  6580.5  580.58  6626.4  579.75
#Mann= 4 ,-1 , 0
  3586.3     .05       0  4258.6    .033       0  5867.7     .05       0
  6390.4     .12       0
Bank Sta=4258.6,5867.7
XS Rating Curve= 0 ,0
Exp/Cntr=0.3,0.1

Chan Stop Cuts=-1
Use User Specified Reach Order=0
Composite Channel Slope=5