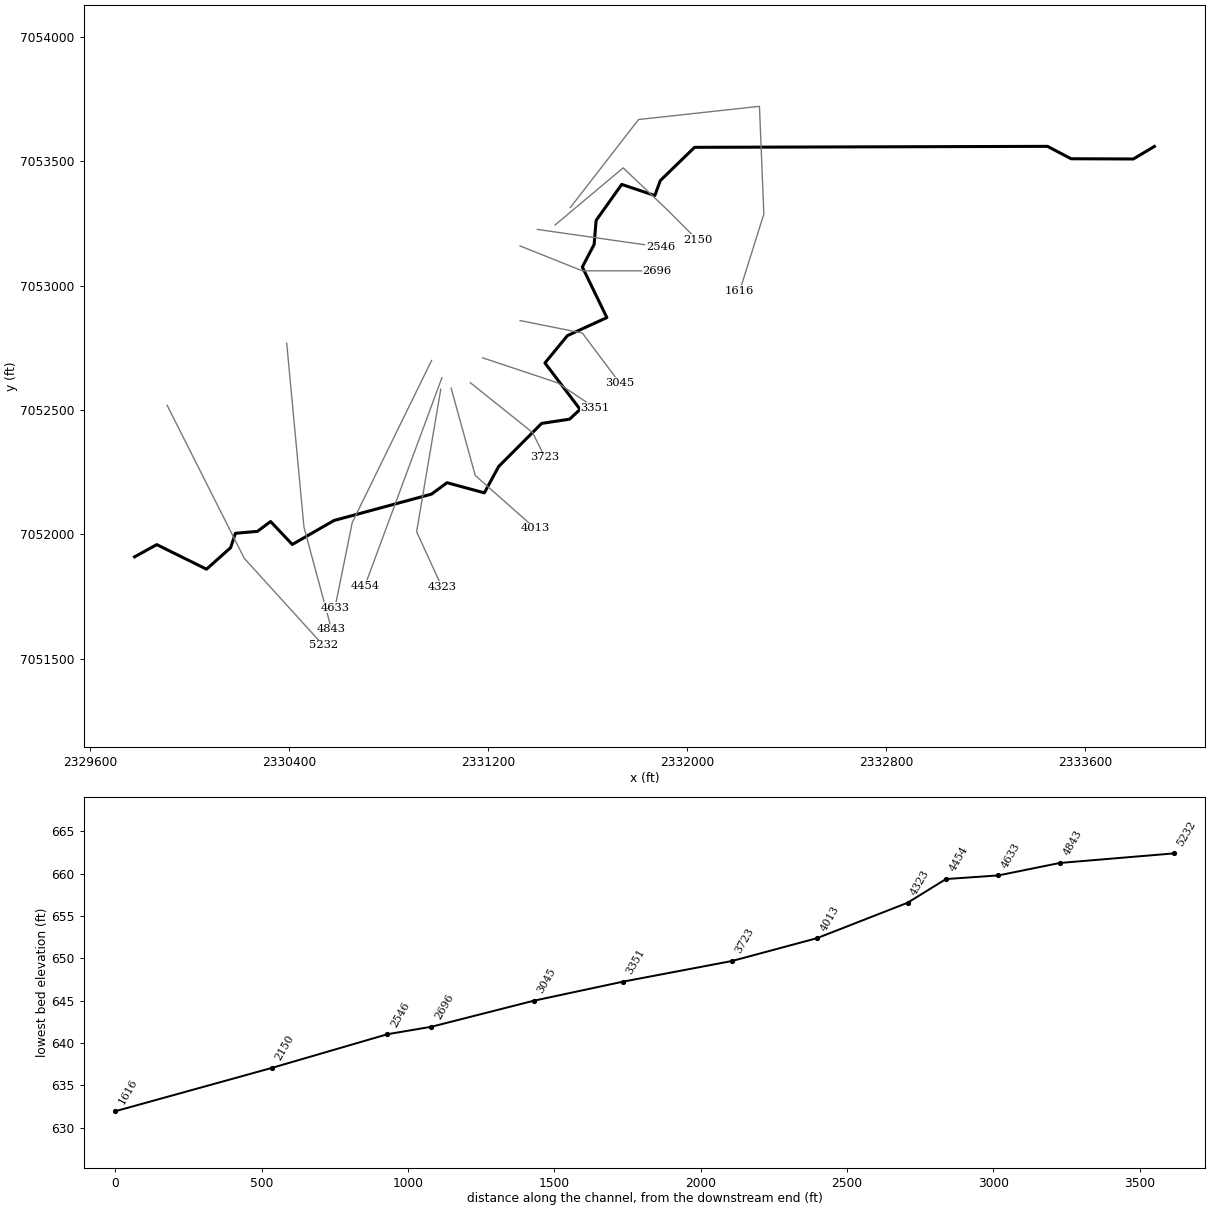
--- Elizabeth Cr Tr 11.prj (project) ---

Proj Title=Elizabeth Cr Tr 11 Base Level Engineering
Current Plan=p01
Default Exp/Contr=0.3,0.1
English Units
Geom File=g01
Flow File=f01
Plan File=p01
BEGIN DESCRIPTION:
Elizabeth Cr Tr 11
END DESCRIPTION:

--- Elizabeth Cr Tr 11.p01 (plan) ---

Plan Title=Multiple Run
Short Identifier=Multiple
Geom File=g01
Flow File=f01
Subcritical Flow
K Sum by GR= 0
Std Step Tol= 0.01
Critical Tol= 0.01
Num of Std Step Trials= 20
Max Error Tol= 0.3
Flow Tol Ratio= 0.001
Split Flow NTrial= 30
Split Flow Tol= 0.02
Split Flow Ratio= 0.02
Log Output Level= 0
Friction Slope Method= 1
Unsteady Friction Slope Method= 2
Unsteady Bridges Friction Slope Method= 1
Parabolic Critical Depth
Global Vel Dist=  1 , 1 , 1
Global Log Level= 0
CheckData=True
Encroach Param= -1, 0, 0, 0
BEGIN DESCRIPTION:
Multiple Run
END DESCRIPTION:

--- Elizabeth Cr Tr 11.f01 (steady flow) ---

Flow Title=Multiple
Number of Profiles=7
Profile Names=10-year,25-year,50-year,1pct_min,100-year,1pct_plu,500-year
River Rch & RM= Elizabeth Cr Tr ,Reach-1,5232
     364     481     575     341     681    1360     958
River Rch & RM= Elizabeth Cr Tr ,Reach-1,4454
     467     629     760     457     911    1820    1310
Boundary for River Rch & Prof#=Elizabeth Cr Tr ,Reach-1,1
Up Type=0
Dn Type=3
Dn Slope=0.005
Boundary for River Rch & Prof#=Elizabeth Cr Tr ,Reach-1,2
Up Type=0
Dn Type=3
Dn Slope=0.005
Boundary for River Rch & Prof#=Elizabeth Cr Tr ,Reach-1,3
Up Type=0
Dn Type=3
Dn Slope=0.005
Boundary for River Rch & Prof#=Elizabeth Cr Tr ,Reach-1,4
Up Type=0
Dn Type=3
Dn Slope=0.005
Boundary for River Rch & Prof#=Elizabeth Cr Tr ,Reach-1,5
Up Type=0
Dn Type=3
Dn Slope=0.005
Boundary for River Rch & Prof#=Elizabeth Cr Tr ,Reach-1,6
Up Type=0
Dn Type=3
Dn Slope=0.005
Boundary for River Rch & Prof#=Elizabeth Cr Tr ,Reach-1,7
Up Type=0
Dn Type=3
Dn Slope=0.005

--- Elizabeth Cr Tr 11.g01 (geometry) ---

Geom Title=Existing Conditions

River Reach=Elizabeth Cr Tr ,Reach-1
Reach XY= 30
      2329779.00      7051910.00      2329868.38      7051959.34
      2330068.38      7051860.59      2330165.27      7051947.02
      2330184.47      7052004.74      2330273.03      7052012.60
      2330325.95      7052052.18      2330413.24      7051959.88
      2330580.58      7052056.17      2330973.03      7052162.38
      2331035.12      7052208.18      2331185.34      7052167.37
      2331242.64      7052273.20      2331415.70      7052446.60
      2331527.99      7052463.61      2331570.18      7052503.01
      2331428.83      7052689.54      2331519.02      7052799.32
      2331677.84      7052872.00      2331579.08      7053075.39
      2331626.62      7053165.97      2331634.54      7053262.42
      2331737.49      7053407.36      2331870.51      7053362.64
      2331892.73      7053422.92      2332030.46      7053556.46
      2333449.15      7053560.36      2333544.22      7053510.52
      2333794.17      7053509.59      2333879.00      7053560.00

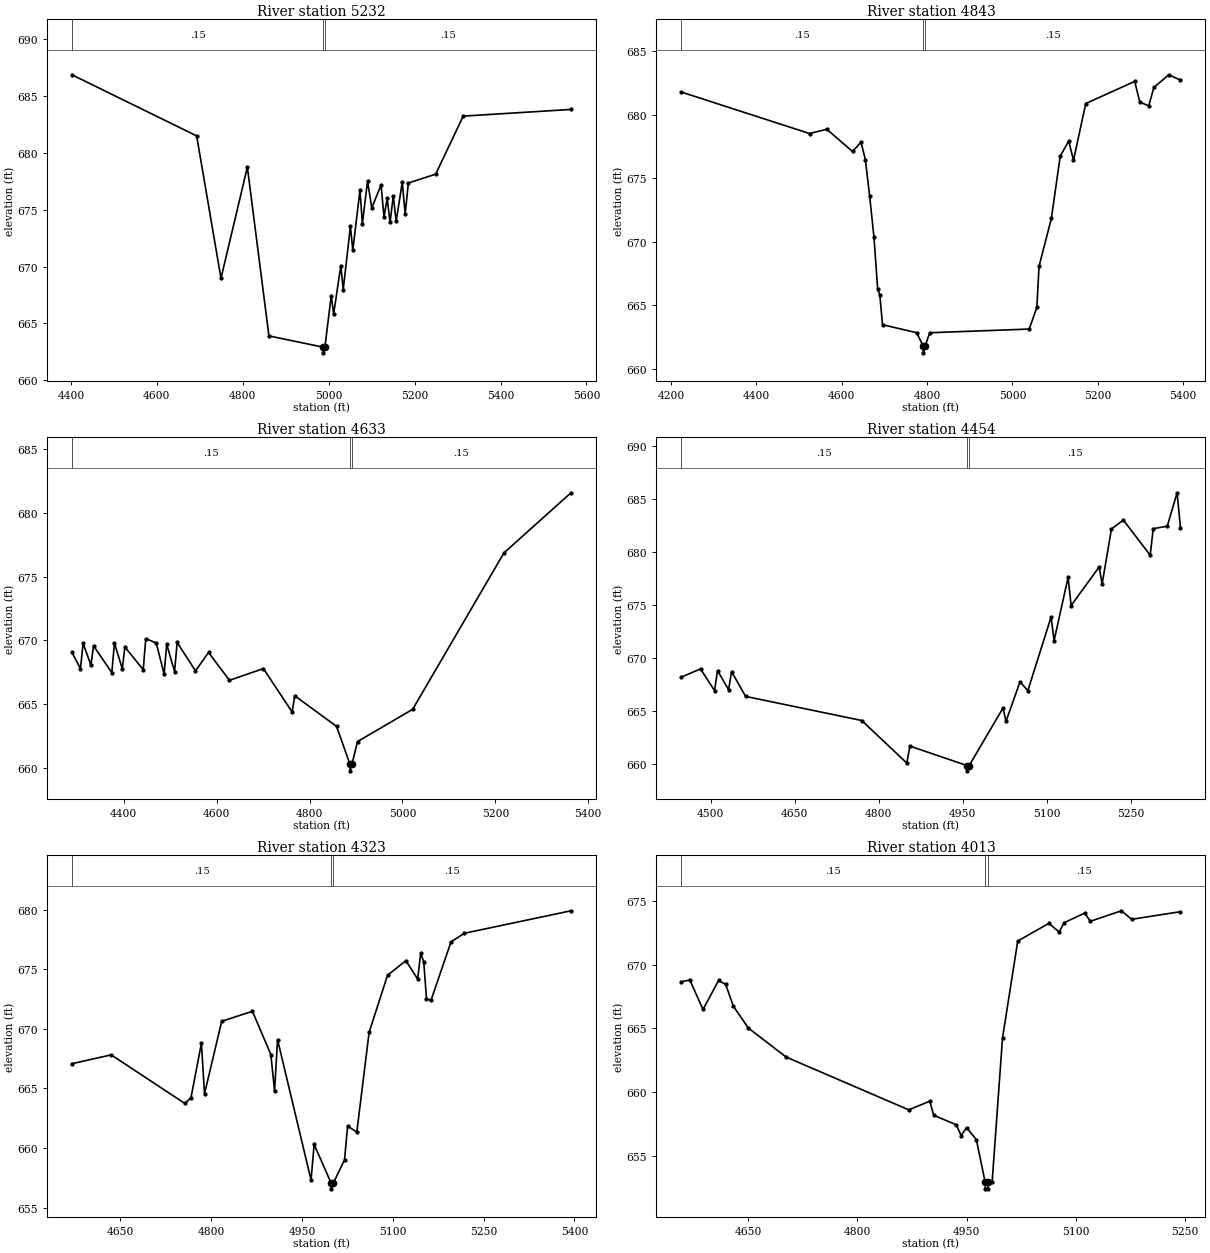
Type RM Length L Ch R = 1,5232,389,389,389
BEGIN DESCRIPTION:
1014
END DESCRIPTION:
XS GIS Cut Line= 3
      2329910.14      7052519.28      2330219.77      7051904.65
      2330537.90      7051554.24
#Sta/Elev= 30
  4402.5  686.88  4692.8  681.50  4749.4  668.96  4810.8  678.75  4861.0  663.89
  4987.3  662.90  4987.5  662.40  4991.3  662.90  5006.0  667.44  5011.6  665.81
  5028.3  670.08  5033.9  667.97  5050.6  673.53  5056.2  671.44  5072.9  676.72
  5078.5  673.78  5090.5  677.51  5100.4  675.16  5122.0  677.18  5128.8  674.35
  5136.2  676.01  5143.0  673.88  5150.4  676.22  5157.1  673.99  5171.3  677.40
  5178.1  674.63  5185.5  677.35  5249.1  678.13  5313.1  683.24  5564.0  683.83
#Mann=3,-1,0
  4402.5    0.15       0  4987.3    0.05       0  4991.3    0.15       0
Bank Sta=4987.3,4991.3
Exp/Cntr=0.3,0.1

Type RM Length L Ch R = 1,4843,210,210,210
BEGIN DESCRIPTION:
1013
END DESCRIPTION:
XS GIS Cut Line= 3
      2330390.76      7052768.91      2330460.09      7052029.43
      2330571.00      7051618.15
#Sta/Elev= 30
  4224.8  681.77  4525.0  678.51  4565.2  678.85  4625.5  677.10  4645.5  677.83
  4655.6  676.46  4665.6  673.61  4675.7  670.37  4684.4  666.29  4689.4  665.83
  4695.8  663.48  4776.1  662.85  4791.2  661.77  4791.4  661.27  4795.2  661.77
  4806.3  662.85  5039.4  663.14  5057.2  664.85  5062.3  668.07  5091.2  671.84
  5111.9  676.73  5131.8  677.92  5143.0  676.41  5171.7  680.87  5286.3  682.61
  5298.4  680.98  5319.1  680.69  5331.4  682.14  5366.2  683.13  5393.5  682.71
#Mann=3,-1,0
  4224.8    0.15       0  4791.2    0.05       0  4795.2    0.15       0
Bank Sta=4791.2,4795.2
Exp/Cntr=0.3,0.1

Type RM Length L Ch R = 1,4633,179,179,179
BEGIN DESCRIPTION:
1010
END DESCRIPTION:
XS GIS Cut Line= 3
      2330973.07      7052699.53      2330654.19      7052047.92
      2330584.87      7051705.93
#Sta/Elev= 30
  4288.4  669.07  4306.8  667.79  4312.4  669.77  4329.3  668.08  4334.9  669.58
  4374.3  667.48  4379.9  669.81  4396.8  667.78  4402.4  669.49  4441.9  667.71
  4447.4  670.15  4469.9  669.79  4486.9  667.37  4492.4  669.70  4509.4  667.57
  4514.9  669.84  4554.4  667.62  4582.5  669.06  4627.5  666.88  4700.6  667.80
  4762.5  664.40  4768.1  665.67  4858.1  663.28  4887.1  660.30  4887.3  659.80
  4891.1  660.30  4903.2  662.09  5021.9  664.61  5218.5  676.85  5362.8  681.55
#Mann=3,-1,0
  4288.4    0.15       0  4887.1    0.05       0  4891.1    0.15       0
Bank Sta=4887.1,4891.1
Exp/Cntr=0.3,0.1

Type RM Length L Ch R = 1,4454,131,131,131
BEGIN DESCRIPTION:
1009
END DESCRIPTION:
XS GIS Cut Line= 2
      2331014.67      7052630.20      2330705.25      7051794.33
#Sta/Elev= 30
  4447.8  668.20  4481.9  668.97  4507.0  666.93  4512.3  668.81  4532.1  667.01
  4537.4  668.71  4562.5  666.38  4769.9  664.11  4850.4  660.10  4855.8  661.70
  4957.8  659.87  4958.1  659.37  4961.8  659.87  5022.2  665.29  5027.5  664.03
  5052.6  667.76  5066.5  666.92  5108.0  673.85  5113.4  671.64  5138.4  677.59
  5143.8  674.94  5193.9  678.57  5199.2  676.97  5215.8  682.15  5237.1  682.99
  5285.1  679.68  5290.4  682.18  5315.5  682.41  5333.1  685.56  5339.1  682.25
#Mann=3,-1,0
  4447.8    0.15       0  4957.8    0.05       0  4961.8    0.15       0
Bank Sta=4957.8,4961.8
Exp/Cntr=0.3,0.1

Type RM Length L Ch R = 1,4323,310,310,310
BEGIN DESCRIPTION:
1012
END DESCRIPTION:
XS GIS Cut Line= 3
      2331010.05      7052583.98      2330913.00      7052010.94
      2331014.34      7051789.85
#Sta/Elev= 30
  4569.9  667.08  4634.8  667.82  4756.5  663.74  4766.6  664.23  4783.8  668.80
  4788.9  664.55  4817.3  670.64  4868.1  671.48  4898.5  667.85  4904.6  664.80
  4909.6  669.09  4964.9  657.31  4970.0  660.30  4997.9  657.07  4998.2  656.57
  5001.9  657.07  5020.2  659.01  5025.3  661.84  5040.5  661.33  5060.8  669.71
  5091.2  674.50  5121.6  675.73  5141.0  674.19  5146.0  676.34  5151.1  675.63
  5155.6  672.52  5163.1  672.40  5196.1  677.31  5218.1  678.03  5394.3  679.92
#Mann=3,-1,0
  4569.9    0.15       0  4997.9    0.05       0  5001.9    0.15       0
Bank Sta=4997.9,5001.9
Exp/Cntr=0.3,0.1

Type RM Length L Ch R = 1,4013,290,290,290
BEGIN DESCRIPTION:
1011
END DESCRIPTION:
XS GIS Cut Line= 3
      2331051.66      7052588.63      2331148.70      7052237.40
      2331388.92      7052024.90
#Sta/Elev= 30
  4558.5  668.66  4570.0  668.80  4588.2  666.48  4609.5  668.76  4619.3  668.45
  4629.7  666.75  4650.4  665.02  4702.3  662.74  4870.6  658.59  4899.4  659.27
  4904.9  658.16  4935.8  657.42  4942.5  656.57  4950.0  657.19  4963.4  656.25
  4975.6  652.88  4975.8  652.38  4979.3  652.38  4979.6  652.88  4985.1  652.94
  4999.3  664.23  5020.2  671.86  5062.9  673.25  5077.1  672.57  5083.8  673.30
  5112.2  674.06  5119.8  673.41  5162.5  674.24  5176.7  673.57  5243.6  674.17
#Mann=3,-1,0
  4558.5    0.15       0  4975.6    0.05       0  4979.6    0.15       0
Bank Sta=4975.6,4979.6
Exp/Cntr=0.3,0.1

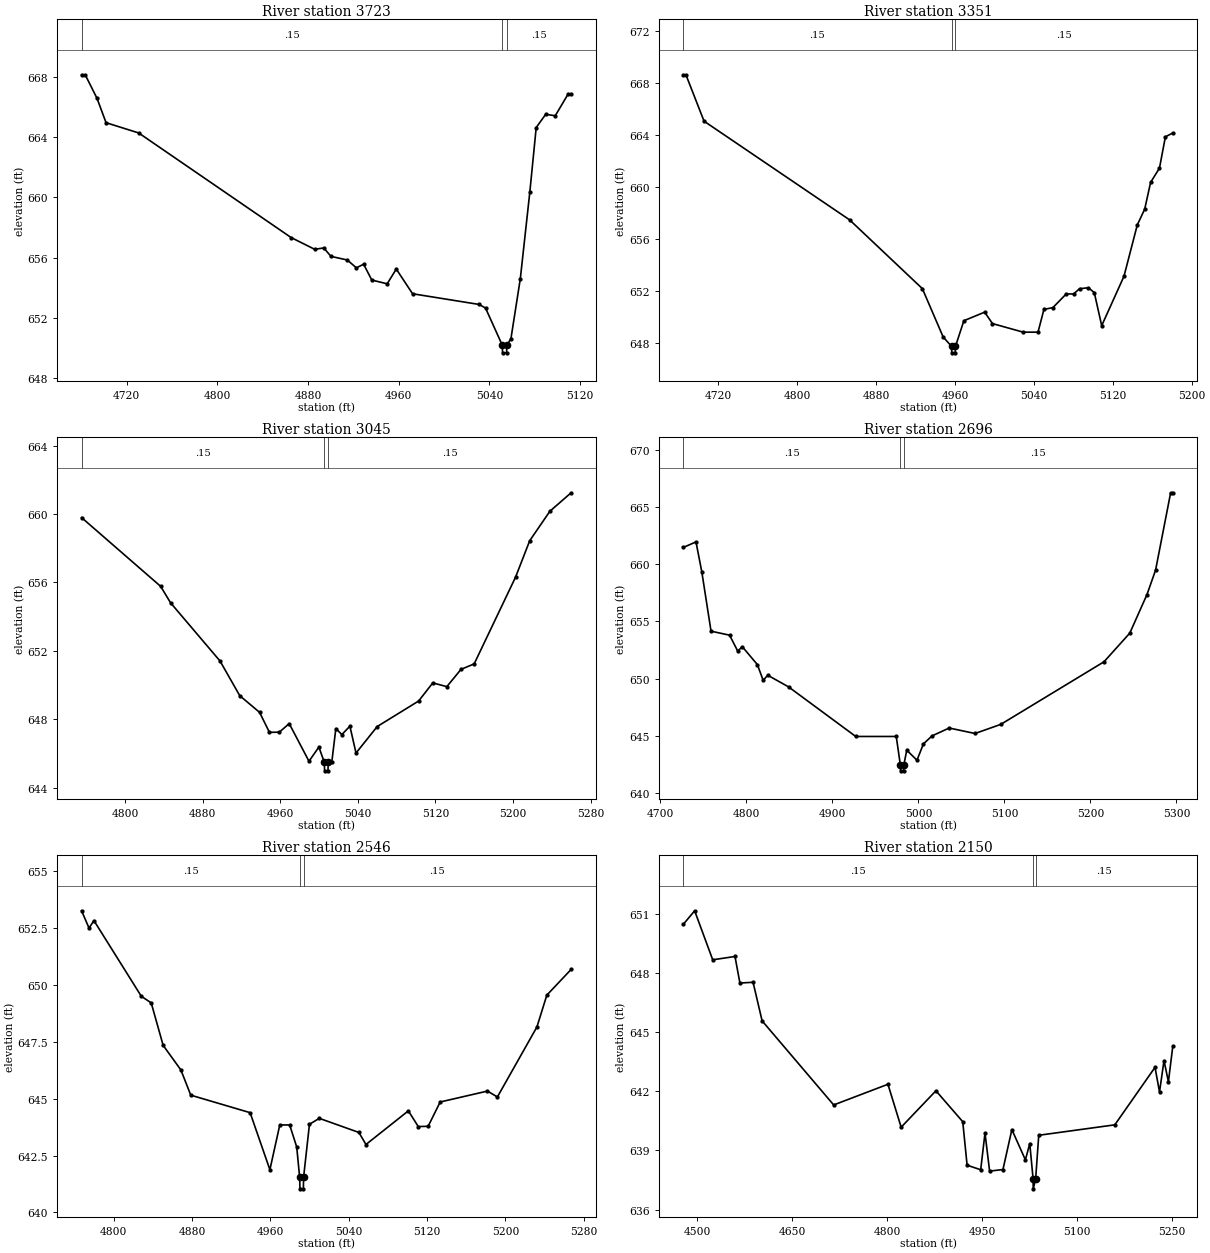
Type RM Length L Ch R = 1,3723,372,372,372
BEGIN DESCRIPTION:
Elizabeth Creek Tributary 11 4.0
END DESCRIPTION:
XS GIS Cut Line= 3
      2331129.00      7052610.00      2331379.00      7052410.00
      2331429.02      7052309.96
#Sta/Elev= 30
  4680.1  668.14  4683.3  668.14  4693.7  666.58  4701.7  664.96  4730.5  664.28
  4865.0  657.34  4885.8  656.56  4893.8  656.65  4900.2  656.09  4914.6  655.85
  4922.6  655.33  4929.0  655.57  4936.2  654.52  4949.8  654.27  4957.8  655.25
  4972.2  653.61  5031.0  652.90  5036.6  652.66  5051.4  650.19  5051.6  649.69
  5055.1  649.69  5055.4  650.19  5059.0  650.63  5067.3  654.62  5075.7  660.38
  5081.3  664.64  5089.7  665.52  5098.1  665.42  5109.3  666.84  5112.1  666.84
#Mann=3,-1,0
  4680.1    0.15       0  5051.4    0.05       0  5055.4    0.15       0
Bank Sta=5051.4,5055.4
Exp/Cntr=0.3,0.1

Type RM Length L Ch R = 1,3351,306,306,306
BEGIN DESCRIPTION:
Elizabeth Creek Tributary 11 3.0
END DESCRIPTION:
XS GIS Cut Line= 3
      2331178.97      7052710.01      2331479.00      7052610.00
      2331628.97      7052510.02
#Sta/Elev= 30
  4684.3  668.64  4687.0  668.64  4705.4  665.07  4853.0  657.48  4926.8  652.19
  4947.9  648.47  4956.4  647.75  4956.6  647.25  4960.1  647.25  4960.4  647.75
  4968.9  649.72  4990.0  650.38  4997.9  649.50  5029.1  648.84  5044.1  648.84
  5050.1  650.59  5059.2  650.73  5072.7  651.78  5080.2  651.78  5086.2  652.18
  5095.2  652.26  5101.2  651.88  5108.7  649.34  5131.3  653.14  5144.8  657.09
  5152.3  658.30  5158.3  660.36  5167.3  661.46  5173.3  663.87  5180.8  664.16
#Mann=3,-1,0
  4684.3    0.15       0  4956.4    0.05       0  4960.4    0.15       0
Bank Sta=4956.4,4960.4
Exp/Cntr=0.3,0.1

Type RM Length L Ch R = 1,3045,349,349,349
BEGIN DESCRIPTION:
Elizabeth Creek Tributary 11 2.0
END DESCRIPTION:
XS GIS Cut Line= 3
      2331328.98      7052860.00      2331579.00      7052810.00
      2331729.02      7052609.98
#Sta/Elev= 30
  4754.9  659.79  4836.5  655.77  4846.7  654.81  4897.7  651.41  4918.1  649.38
  4938.5  648.41  4948.7  647.24  4958.9  647.25  4969.1  647.75  4989.5  645.55
  4999.7  646.38  5005.3  645.49  5005.6  644.99  5009.1  644.99  5009.3  645.49
  5013.0  645.49  5017.2  647.46  5023.4  647.11  5031.7  647.60  5038.0  646.03
  5059.9  647.58  5102.6  649.07  5117.2  650.13  5131.7  649.91  5146.3  650.92
  5159.9  651.24  5202.6  656.31  5217.2  658.44  5238.0  660.16  5259.9  661.24
#Mann=3,-1,0
  4754.9    0.15       0  5005.3    0.05       0  5009.3    0.15       0
Bank Sta=5005.3,5009.3
Exp/Cntr=0.3,0.1

Type RM Length L Ch R = 1,2696,150,150,150
BEGIN DESCRIPTION:
Elizabeth Creek Tributary 11 1.0
END DESCRIPTION:
XS GIS Cut Line= 3
      2331328.98      7053160.01      2331579.00      7053060.00
      2331879.02      7053060.00
#Sta/Elev= 30
  4726.5  661.48  4741.3  661.97  4748.1  659.33  4758.8  654.15  4780.4  653.80
  4789.8  652.41  4795.2  652.79  4812.7  651.22  4819.4  649.85  4824.8  650.29
  4849.0  649.27  4927.1  644.93  4974.2  644.93  4979.0  642.42  4979.2  641.92
  4982.7  641.92  4983.0  642.42  4986.4  643.73  4998.3  642.85  5005.8  644.28
  5015.8  644.98  5035.8  645.67  5065.8  645.19  5095.8  645.99  5215.8  651.47
  5245.8  653.98  5265.8  657.36  5275.8  659.50  5293.3  666.27  5295.8  666.27
#Mann=3,-1,0
  4726.5    0.15       0  4979.0    0.05       0  4983.0    0.15       0
Bank Sta=4979,4983
Exp/Cntr=0.3,0.1

Type RM Length L Ch R = 1,2546,396,396,396
BEGIN DESCRIPTION:
1008
END DESCRIPTION:
XS GIS Cut Line= 2
      2331398.65      7053226.37      2331893.52      7053155.68
#Sta/Elev= 30
  4767.2  653.27  4774.8  652.51  4779.8  652.84  4828.2  649.51  4838.3  649.22
  4850.5  647.35  4868.6  646.27  4878.7  645.16  4939.3  644.39  4959.5  641.88
  4969.6  643.85  4979.7  643.85  4986.9  642.88  4989.9  641.54  4990.2  641.04
  4993.7  641.04  4993.9  641.54  4999.9  643.88  5010.0  644.14  5050.4  643.52
  5057.6  642.99  5100.9  644.47  5111.0  643.78  5121.1  643.79  5133.4  644.86
  5181.7  645.34  5191.8  645.08  5232.2  648.16  5242.3  649.56  5267.1  650.69
#Mann=3,-1,0
  4767.2    0.15       0  4989.9    0.05       0  4993.9    0.15       0
Bank Sta=4989.9,4993.9
Exp/Cntr=0.3,0.1

Type RM Length L Ch R = 1,2150,534,534,534
BEGIN DESCRIPTION:
1007
END DESCRIPTION:
XS GIS Cut Line= 4
      2331469.40      7053244.07      2331743.31      7053473.80
      2331920.05      7053305.90      2332042.33      7053183.62
#Sta/Elev= 30
  4477.6  650.48  4495.6  651.17  4524.2  648.68  4559.4  648.85  4567.2  647.50
  4588.0  647.54  4602.3  645.58  4715.5  641.31  4801.3  642.36  4822.2  640.18
  4877.2  642.03  4919.6  640.46  4926.5  638.25  4948.0  638.02  4954.8  639.88
  4962.1  637.95  4983.2  638.03  4997.3  640.06  5018.7  638.52  5025.6  639.35
  5030.9  637.55  5031.1  637.05  5034.9  637.55  5039.8  639.77  5160.1  640.30
  5223.7  643.22  5230.8  641.97  5237.9  643.56  5244.9  642.49  5251.8  644.29
#Mann=3,-1,0
  4477.6    0.15       0  5030.9    0.05       0  5034.9    0.15       0
Bank Sta=5030.9,5034.9
Exp/Cntr=0.3,0.1

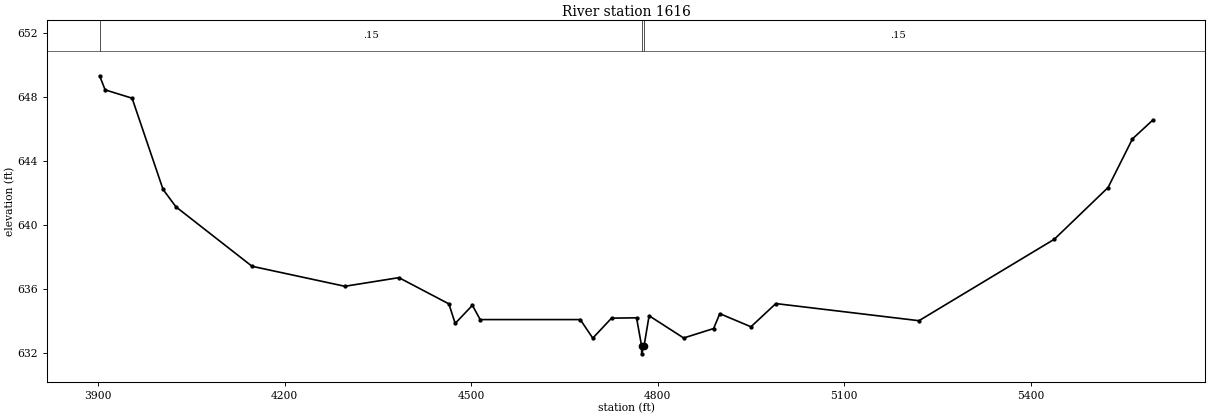
Type RM Length L Ch R = 1,1616,0,0,0
BEGIN DESCRIPTION:
1006
END DESCRIPTION:
XS GIS Cut Line= 5
      2331531.22      7053314.72      2331805.17      7053668.21
      2332291.20      7053721.23      2332308.87      7053288.23
      2332211.67      7052978.94
#Sta/Elev= 30
  3902.5  649.31  3911.3  648.43  3954.7  647.91  4004.5  642.21  4025.3  641.12
  4147.6  637.41  4296.9  636.16  4383.8  636.70  4464.2  635.06  4474.3  633.84
  4502.0  634.97  4514.5  634.08  4675.5  634.08  4695.6  632.92  4725.8  634.17
  4766.0  634.19  4774.1  632.44  4774.3  631.94  4778.1  632.44  4786.2  634.32
  4841.8  632.93  4889.9  633.52  4899.9  634.45  4950.0  633.63  4990.0  635.08
  5220.2  634.01  5437.9  639.10  5524.3  642.33  5563.6  645.37  5596.2  646.54
#Mann=3,-1,0
  3902.5    0.15       0  4774.1    0.05       0  4778.1    0.15       0
Bank Sta=4774.1,4778.1
Exp/Cntr=0.3,0.1

Chan Stop Cuts=-1