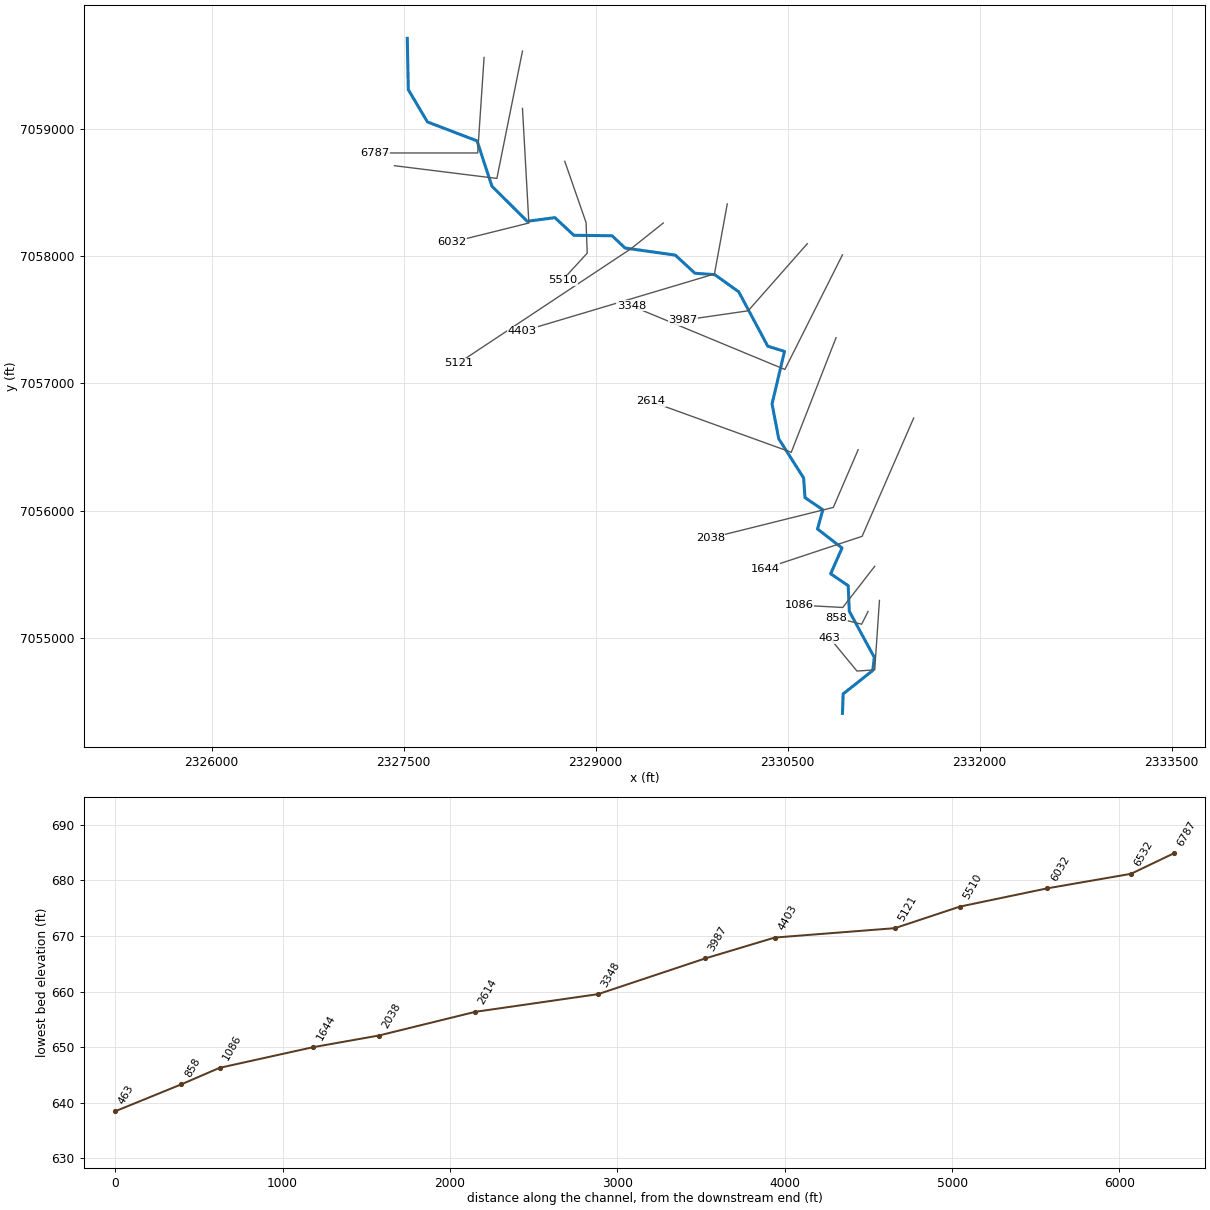
--- Elizabeth Cr Tr 12.prj (project) ---

Proj Title=Elizabeth Cr Tr 12 Base Level Engineering
Current Plan=p01
Default Exp/Contr=0.3,0.1
English Units
Geom File=g01
Flow File=f01
Plan File=p01
Y Axis Title=Elevation
X Axis Title(PF)=Main Channel Distance
X Axis Title(XS)=Station
BEGIN DESCRIPTION:
Elizabeth Cr Tr 12
END DESCRIPTION:
DSS Export Rating Curves= 0
DSS Export Rating Curve Sorted= 0
DSS Export Volume Flow Curves= 0
DXF OffsetX= 0
DXF OffsetY= 0
DXF ScaleX= 1
DXF ScaleY= 10

--- Elizabeth Cr Tr 12.p01 (plan) ---

Plan Title=Multiple Run
Program Version=4.10
Short Identifier=Multiple
Geom File=g01
Flow File=f01
Subcritical Flow
K Sum by GR= 0
Std Step Tol= 0.01
Critical Tol= 0.01
Num of Std Step Trials= 20
Max Error Tol= 0.3
Flow Tol Ratio= 0.001
Split Flow NTrial= 30
Split Flow Tol= 0.02
Split Flow Ratio= 0.02
Log Output Level= 0
Friction Slope Method= 0
Unsteady Friction Slope Method= 2
Unsteady Bridges Friction Slope Method= 1
Parabolic Critical Depth
Global Vel Dist= 1 , 1 , 1
Global Log Level= 0
CheckData=True
Encroach Param=-1 ,0,0, 0
BEGIN DESCRIPTION:
Multiple Run
END DESCRIPTION:
Computation Interval=1HOUR
Output Interval=1HOUR
Run HTab= 0
Run UNet= 0
Run PostProcess= 0
Run WQNet= 0
UNET Theta= 1
UNET Theta Warmup= 1
UNET ZTol= 0.02
UNET ZSATol= 0.05
UNET MxIter= 20
UNET MaxInSteps= 0
UNET DtIC= 0
UNET DtMin= 0
UNET MaxCRTS= 20
UNET WFStab= 2
UNET SFStab= 1
UNET WFX= 1
UNET SFX= 1
UNET DSS MLevel= 4
UNET DZMax Abort= 100
UNET Convert EG Bridges= 0
UNET Use Existing IB Tables=-1
UNET Froude Reduction=False
UNET Froude Limit= 1
UNET Froude Power= 10
UNET Time Slicing=0,0, 5
UNET Junction Losses=0
Instantaneous Interval=1HOUR
Write IC File= 0
Write IC File at Sim End=0
Echo Input=False
Echo Parameters=False
Echo Output=False
Write Detailed= 0
WQ AD Non Conservative
WQ ULTIMATE=-1
WQ Max Comp Step=1HOUR
WQ Output Interval=15MIN
WQ Output Selected Increments= 0
WQ Output face flow=0
WQ Output face velocity=0
WQ Output face area=0
WQ Output face dispersion=0
WQ Output cell volume=0
WQ Output cell surface area=0
WQ Output cell continuity=0
WQ Output cumulative cell continuity=0
WQ Output face conc=0
WQ Output face dconc_dx=0
WQ Output face courant=0
WQ Output face peclet=0
WQ Output face adv mass=0
WQ Output face disp mass=0
WQ Output cell mass=0
WQ Output cell source sink temp=0
WQ Output cell source sink nsm=0
WQ Output MaxMinRange=-1
WQ Daily Max Min Mean=-1
WQ Daily Range=0
WQ Daily Time=0
WQ Create Restart=0
WQ Fixed Restart=0
WQ System Summary=0
WQ Use Fixed Temperature=0
Sorting and Armoring Iterations= 10
XS Update Threshold= 0.02
Hydraulics Update Threshold= 0.02
Energy Slope Method= 1
Volume Change Method= 0
XS Weighting Method= 0
Number of US Weighted Cross Sections= 1
Number of DS Weighted Cross Sections= 1
Upstream XS Weight=0.25
Main XS Weight=0.5
Downstream XS Weight=0.25
Number of DS XS's Weighted with US Boundary= 1
Upstream Boundary Weight= 1
Weight of XSs Associated with US Boundary= 0
Number of US XS's Weighted with DS Boundary= 1
Downstream Boundary Weight= 0.5
Weight of XSs Associated with DS Boundary= 0.5
Sediment Output Level= 4
Mass or Volume Output= 0
Output Increment Type= 1
Profile and TS Output Increment= 10
XS Output Flag= 0
XS Output Increment= 10
Disregard all LS=0
Disregard all Conn=0
Disregard all Breaches=0
Disregard all Pumps=0

--- Elizabeth Cr Tr 12.f01 (steady flow) ---

Flow Title=Multiple
Number of Profiles=7
Profile Names=10-year,25-year,50-year,1pct_min,100-year,1pct_plu,500-year
River Rch & RM= Elizabeth Cr Tr ,Reach-1,6787
     174     219     253     146     291     580     383
River Rch & RM= Elizabeth Cr Tr ,Reach-1,5121
     541     733     890     536    1070    2130    1550
Boundary for River Rch & Prof#=Elizabeth Cr Tr ,Reach-1,1
Up Type=0
Dn Type=3
Dn Slope=0.005
Boundary for River Rch & Prof#=Elizabeth Cr Tr ,Reach-1,2
Up Type=0
Dn Type=3
Dn Slope=0.005
Boundary for River Rch & Prof#=Elizabeth Cr Tr ,Reach-1,3
Up Type=0
Dn Type=3
Dn Slope=0.005
Boundary for River Rch & Prof#=Elizabeth Cr Tr ,Reach-1,4
Up Type=0
Dn Type=3
Dn Slope=0.005
Boundary for River Rch & Prof#=Elizabeth Cr Tr ,Reach-1,5
Up Type=0
Dn Type=3
Dn Slope=0.005
Boundary for River Rch & Prof#=Elizabeth Cr Tr ,Reach-1,6
Up Type=0
Dn Type=3
Dn Slope=0.005
Boundary for River Rch & Prof#=Elizabeth Cr Tr ,Reach-1,7
Up Type=0
Dn Type=3
Dn Slope=0.005

--- Elizabeth Cr Tr 12.g01 (geometry) ---

Geom Title=Existing Conditions

River Reach=Elizabeth Cr Tr ,Reach-1
Reach XY= 30
      2327529.00      7059710.00      2327536.99      7059306.66
      2327686.75      7059053.54      2328073.96      7058904.92
      2328190.11      7058549.68      2328465.66      7058273.36
      2328682.42      7058302.20      2328830.46      7058163.54
      2329129.00      7058160.00      2329230.48      7058063.56
      2329623.15      7058007.94      2329776.55      7057865.47
      2329931.44      7057854.52      2330118.37      7057720.00
      2330345.46      7057292.87      2330476.07      7057252.02
      2330378.91      7056839.90      2330431.08      7056565.86
      2330625.44      7056258.53      2330636.70      7056103.53
      2330775.65      7056008.65      2330733.89      7055857.77
      2330925.88      7055708.38      2330836.67      7055506.34
      2330973.64      7055412.70      2330982.55      7055211.47
      2331177.92      7054849.45      2331165.66      7054746.69
      2330934.33      7054562.72      2330929.00      7054410.00

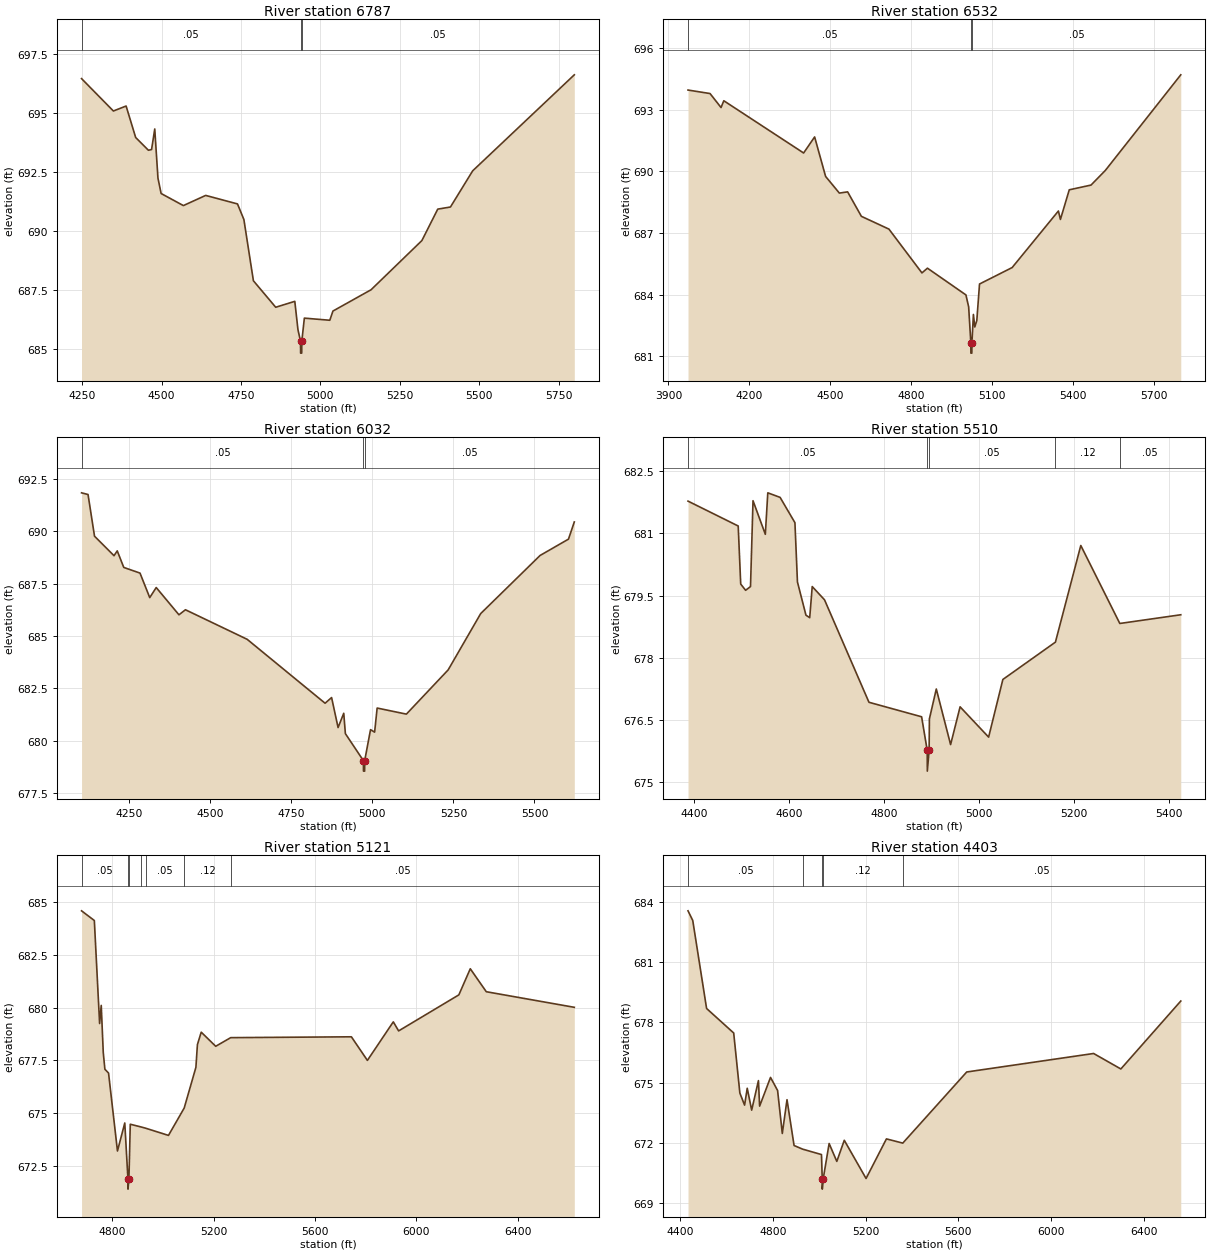
Type RM Length L Ch R = 1,6787,255,255,255
BEGIN DESCRIPTION:
Elizabeth Creek Tributary 12 9.0
END DESCRIPTION:
XS GIS Cut Line= 3
      2328129.00      7059560.03      2328079.00      7058810.00
      2327278.99      7058810.00
#Sta/Elev= 30
  4248.0  696.44  4348.2  695.07  4388.3  695.28  4418.4  693.95  4458.5  693.41
  4468.5  693.44  4478.5  694.31  4488.6  692.23  4498.6  691.58  4568.7  691.07
  4638.9  691.50  4739.1  691.14  4759.2  690.48  4789.2  687.89  4859.4  686.77
  4919.5  687.02  4929.5  685.82  4937.6  685.33  4937.8  684.83  4941.3  684.83
  4941.6  685.33  4949.6  686.31  5029.7  686.22  5039.7  686.61  5159.7  687.51
  5319.7  689.59  5369.7  690.92  5409.7  691.01  5479.7  692.54  5799.7  696.60
#Mann=3,-1,0
  4248.0    0.05       0  4937.6   0.033       0  4941.6    0.05       0
Bank Sta=4937.6,4941.6
Exp/Cntr=0.3,0.1

Type RM Length L Ch R = 1,6532,500,500,500
BEGIN DESCRIPTION:
Elizabeth Creek Tributary 12 8.0
END DESCRIPTION:
XS GIS Cut Line= 3
      2328429.01      7059610.04      2328229.00      7058610.00
      2327428.97      7058710.00
#Sta/Elev= 30
  3972.4  693.95  4054.0  693.78  4094.8  693.10  4105.0  693.43  4400.8  690.89
  4441.6  691.67  4482.3  689.75  4533.3  688.94  4563.9  689.00  4614.9  687.81
  4716.9  687.19  4839.3  685.06  4859.7  685.29  5002.3  683.99  5012.4  683.41
  5020.5  681.66  5020.7  681.16  5024.2  681.16  5024.5  681.66  5030.0  683.04
  5035.1  682.43  5042.6  682.74  5052.7  684.52  5173.6  685.32  5345.0  688.07
  5352.5  687.66  5385.3  689.10  5465.9  689.33  5518.8  690.04  5798.5  694.69
#Mann=3,-1,0
  3972.4    0.05       0  5020.5   0.033       0  5024.5    0.05       0
Bank Sta=5020.5,5024.5
Exp/Cntr=0.3,0.1

Type RM Length L Ch R = 1,6032,522,522,522
BEGIN DESCRIPTION:
Elizabeth Creek Tributary 12 7.0
END DESCRIPTION:
XS GIS Cut Line= 3
      2328429.00      7059159.98      2328479.00      7058260.00
      2327879.03      7058110.01
#Sta/Elev= 30
  4103.0  691.83  4123.0  691.75  4143.0  689.76  4203.1  688.83  4213.1  689.06
  4233.2  688.27  4283.3  688.00  4313.3  686.83  4333.3  687.31  4403.4  686.01
  4423.5  686.25  4613.8  684.84  4854.1  681.79  4874.2  682.06  4894.2  680.63
  4911.7  681.31  4916.7  680.34  4972.3  679.05  4972.6  678.55  4976.1  678.55
  4976.3  679.05  4994.3  680.53  5006.9  680.41  5014.7  681.56  5104.9  681.27
  5233.7  683.38  5334.2  686.07  5517.2  688.84  5604.8  689.62  5622.8  690.44
#Mann=3,-1,0
  4103.0    0.05       0  4972.3   0.033       0  4976.3    0.05       0
Bank Sta=4972.3,4976.3
Exp/Cntr=0.3,0.1

Type RM Length L Ch R = 1,5510,389,389,389
BEGIN DESCRIPTION:
1015
END DESCRIPTION:
XS GIS Cut Line= 4
      2328759.36      7058744.55      2328925.72      7058263.94
      2328934.97      7058023.62      2328740.84      7057811.00
#Sta/Elev= 30
  4387.3  681.78  4492.9  681.18  4498.2  679.78  4508.5  679.63  4518.8  679.72
  4524.1  681.79  4550.0  680.98  4555.2  681.98  4581.1  681.87  4612.3  681.26
  4617.6  679.83  4635.5  679.03  4643.4  678.97  4648.7  679.72  4674.6  679.40
  4768.1  676.93  4878.9  676.58  4890.7  675.77  4890.9  675.27  4894.7  675.77
  4895.3  676.53  4909.8  677.25  4939.9  675.91  4959.9  676.82  5019.9  676.09
  5049.9  677.48  5160.5  678.38  5213.9  680.71  5296.0  678.83  5424.3  679.04
#Mann=5,-1,0
  4387.3    0.05       0  4890.7   0.033       0  4894.7    0.05       0
  5160.5    0.12       0  5296.0    0.05       0
Bank Sta=4890.7,4894.7
Exp/Cntr=0.3,0.1

Type RM Length L Ch R = 1,5121,718,718,718
BEGIN DESCRIPTION:
Elizabeth Creek Tributary 12 5.0
END DESCRIPTION:
XS GIS Cut Line= 3
      2329528.97      7058259.97      2329279.00      7058060.00
      2327929.01      7057160.01
#Sta/Elev= 30
  4679.8  684.60  4730.2  684.14  4751.0  679.25  4757.4  680.11  4765.4  677.87
  4771.8  677.08  4786.2  676.90  4821.4  673.20  4850.2  674.53  4862.6  671.89
  4862.9  671.39  4866.6  671.89  4871.9  674.47  4914.7  674.34  4933.0  674.28
  5022.5  673.94  5084.5  675.24  5130.6  677.17  5136.6  678.25  5151.6  678.84
  5208.7  678.17  5267.7  678.58  5743.6  678.62  5806.7  677.50  5908.8  679.33
  5929.8  678.90  6167.2  680.61  6212.3  681.85  6275.4  680.76  6622.4  680.02
#Mann=7,-1,0
  4679.8    0.05       0  4862.6   0.033       0  4866.6    0.05       0
  4914.7    0.12       0  4933.0    0.05       0  5084.5    0.12       0
  5267.7    0.05       0
Bank Sta=4862.6,4866.6
Exp/Cntr=0.3,0.1

Type RM Length L Ch R = 1,4403,416,416,416
BEGIN DESCRIPTION:
Elizabeth Creek Tributary 12 4.0
END DESCRIPTION:
XS GIS Cut Line= 3
      2330029.01      7058410.03      2329929.00      7057860.00
      2328428.99      7057410.00
#Sta/Elev= 30
  4434.2  683.55  4454.6  683.07  4514.3  678.69  4631.2  677.47  4657.8  674.48
  4678.2  673.88  4689.6  674.72  4708.7  673.63  4737.9  675.10  4743.0  673.83
  4790.0  675.26  4820.5  674.61  4840.8  672.47  4861.1  674.15  4891.6  671.87
  4928.4  671.69  5009.8  671.42  5013.0  670.20  5013.2  669.70  5017.0  670.20
  5042.8  671.97  5075.9  671.08  5108.1  672.13  5202.1  670.23  5289.9  672.20
  5360.4  671.99  5636.2  675.53  6183.4  676.45  6300.9  675.68  6559.3  679.06
#Mann=5,-1,0
  4434.2    0.05       0  4928.4    0.12       0  5013.0    0.07       0
  5017.0    0.12       0  5360.4    0.05       0
Bank Sta=5013,5017
Exp/Cntr=0.3,0.1

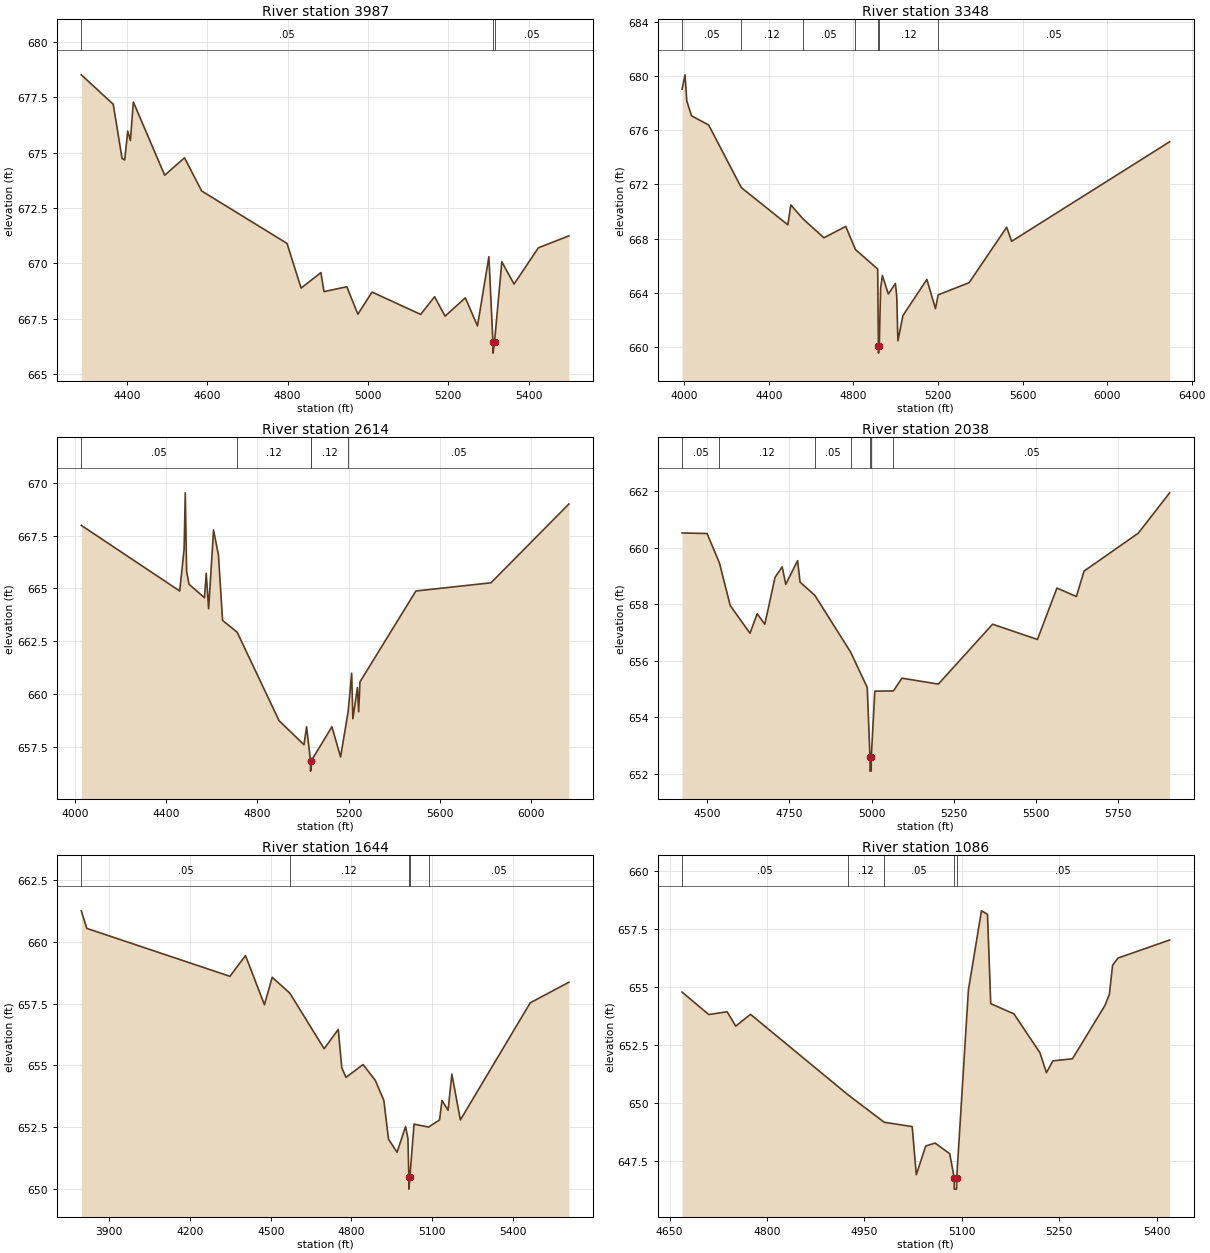
Type RM Length L Ch R = 1,3987,639,639,639
BEGIN DESCRIPTION:
71019
END DESCRIPTION:
XS GIS Cut Line= 3
      2330654.17      7058097.54      2330192.04      7057570.71
      2329683.79      7057496.78
#Sta/Elev= 30
  4286.0  678.52  4365.6  677.19  4387.5  674.74  4394.1  674.67  4401.7  675.98
  4408.3  675.55  4415.7  677.29  4493.7  673.98  4543.1  674.77  4585.8  673.27
  4798.4  670.90  4833.5  668.88  4882.8  669.58  4890.4  668.72  4947.3  668.94
  4974.9  667.70  5010.1  668.70  5131.3  667.69  5166.0  668.49  5192.0  667.61
  5242.5  668.44  5272.8  667.17  5301.2  670.30  5311.2  666.44  5311.5  665.94
  5315.2  666.44  5333.4  670.07  5363.8  669.06  5424.4  670.70  5500.4  671.24
#Mann=3,-1,0
  4286.0    0.05       0  5311.2   0.033       0  5315.2    0.05       0
Bank Sta=5311.2,5315.2
Exp/Cntr=0.3,0.1

Type RM Length L Ch R = 1,3348,734,734,734
BEGIN DESCRIPTION:
Elizabeth Creek Tributary 12 3.0
END DESCRIPTION:
XS GIS Cut Line= 3
      2330928.99      7058009.98      2330479.00      7057110.00
      2329279.01      7057609.99
#Sta/Elev= 30
  3989.7  679.05  4003.7  680.11  4012.0  678.18  4034.4  677.08  4115.5  676.40
  4269.9  671.77  4490.0  669.02  4504.0  670.49  4560.9  669.47  4660.5  668.06
  4763.9  668.90  4809.8  667.19  4914.9  665.75  4918.4  660.03  4918.7  659.53
  4922.4  660.03  4928.8  664.33  4937.2  665.27  4965.2  663.90  4998.6  664.68
  5005.1  663.75  5010.5  660.44  5034.4  662.31  5147.6  664.98  5188.2  662.82
  5200.9  663.84  5347.5  664.74  5525.1  668.84  5548.4  667.80  6295.9  675.16
#Mann=7,-1,0
  3989.7    0.05       0  4269.9    0.12       0  4560.9    0.05       0
  4809.8    0.12       0  4918.4    0.07       0  4922.4    0.12       0
  5200.9    0.05       0
Bank Sta=4918.4,4922.4
Exp/Cntr=0.3,0.1

Type RM Length L Ch R = 1,2614,576,576,576
BEGIN DESCRIPTION:
Elizabeth Creek Tributary 12 2.0
END DESCRIPTION:
XS GIS Cut Line= 3
      2330879.00      7057360.00      2330529.00      7056460.00
      2329429.03      7056859.99
#Sta/Elev= 30
  4028.7  667.99  4459.8  664.88  4479.0  666.84  4484.3  669.53  4490.1  665.80
  4500.8  665.20  4568.6  664.56  4575.9  665.72  4586.6  664.04  4608.1  667.77
  4629.6  666.58  4647.6  663.49  4711.5  662.93  4895.1  658.74  5004.3  657.60
  5015.6  658.45  5032.9  656.85  5033.2  656.35  5036.9  656.85  5126.7  658.45
  5164.6  657.02  5197.8  659.17  5213.2  660.99  5218.5  658.83  5238.4  660.31
  5243.8  659.16  5249.7  660.58  5494.5  664.88  5823.7  665.27  6164.8  669.00
#Mann=5,-1,0
  4028.7    0.05       0  4711.5    0.12       0  5032.9    0.07       0
  5036.9    0.12       0  5197.8    0.05       0
Bank Sta=5032.9,5036.9
Exp/Cntr=0.3,0.1

Type RM Length L Ch R = 1,2038,394,394,394
BEGIN DESCRIPTION:
1020
END DESCRIPTION:
XS GIS Cut Line= 3
      2331051.64      7056479.99      2330857.54      7056027.10
      2329896.26      7055786.78
#Sta/Elev= 30
  4423.5  660.52  4499.6  660.50  4537.2  659.46  4570.1  657.95  4630.2  656.97
  4652.0  657.66  4675.3  657.29  4706.4  658.95  4728.1  659.32  4739.0  658.70
  4775.0  659.54  4782.5  658.78  4827.6  658.31  4936.5  656.30  4986.9  655.05
  4995.2  652.59  4995.4  652.09  4998.9  652.09  4999.2  652.59  5010.0  654.92
  5066.6  654.93  5092.5  655.38  5203.3  655.17  5368.3  657.29  5504.8  656.75
  5564.1  658.57  5623.3  658.27  5646.6  659.17  5811.5  660.51  5907.1  661.94
#Mann=7,-1,0
  4423.5    0.05       0  4537.2    0.12       0  4827.6    0.05       0
  4936.5    0.12       0  4995.2    0.07       0  4999.2    0.12       0
  5066.6    0.05       0
Bank Sta=4995.2,4999.2
Exp/Cntr=0.3,0.1

Type RM Length L Ch R = 1,1644,558,558,558
BEGIN DESCRIPTION:
1023
END DESCRIPTION:
XS GIS Cut Line= 3
      2331485.41      7056728.83      2331082.59      7055800.17
      2330322.76      7055546.89
#Sta/Elev= 30
  3795.7  661.25  3816.2  660.54  4348.5  658.60  4406.3  659.44  4476.7  657.45
  4505.6  658.56  4571.1  657.92  4698.8  655.67  4751.2  656.45  4764.5  654.90
  4780.1  654.51  4843.4  655.03  4889.2  654.39  4920.8  653.58  4938.2  652.01
  4969.9  651.48  5001.5  652.52  5010.4  652.04  5013.7  650.49  5013.9  649.99
  5017.7  650.49  5033.1  652.62  5087.1  652.50  5128.0  652.79  5136.9  653.58
  5159.6  653.18  5173.8  654.64  5205.4  652.79  5465.3  657.53  5608.9  658.36
#Mann=5,-1,0
  3795.7    0.05       0  4571.1    0.12       0  5013.7    0.07       0
  5017.7    0.12       0  5087.1    0.05       0
Bank Sta=5013.7,5017.7
Exp/Cntr=0.3,0.1

Type RM Length L Ch R = 1,1086,228,228,228
BEGIN DESCRIPTION:
1022
END DESCRIPTION:
XS GIS Cut Line= 3
      2331181.05      7055564.94      2330931.49      7055241.43
      2330589.47      7055259.92
#Sta/Elev= 30
  4669.1  654.79  4710.2  653.82  4738.5  653.94  4751.8  653.32  4774.5  653.83
  4924.9  650.35  4980.4  649.17  5023.6  648.98  5029.9  646.90  5044.4  648.14
  5058.9  648.27  5081.4  647.81  5088.2  646.78  5088.4  646.28  5091.9  646.28
  5092.2  646.78  5110.2  654.88  5130.3  658.30  5139.6  658.15  5144.6  654.29
  5180.3  653.85  5220.4  652.17  5230.4  651.31  5240.4  651.82  5270.5  651.91
  5320.5  654.21  5327.3  654.69  5332.3  655.95  5340.6  656.26  5420.2  657.04
#Mann=5,-1,0
  4669.1    0.05       0  4924.9    0.12       0  4980.4    0.05       0
  5088.2    0.05       0  5092.2    0.05       0
Bank Sta=5088.2,5092.2
Exp/Cntr=0.3,0.1

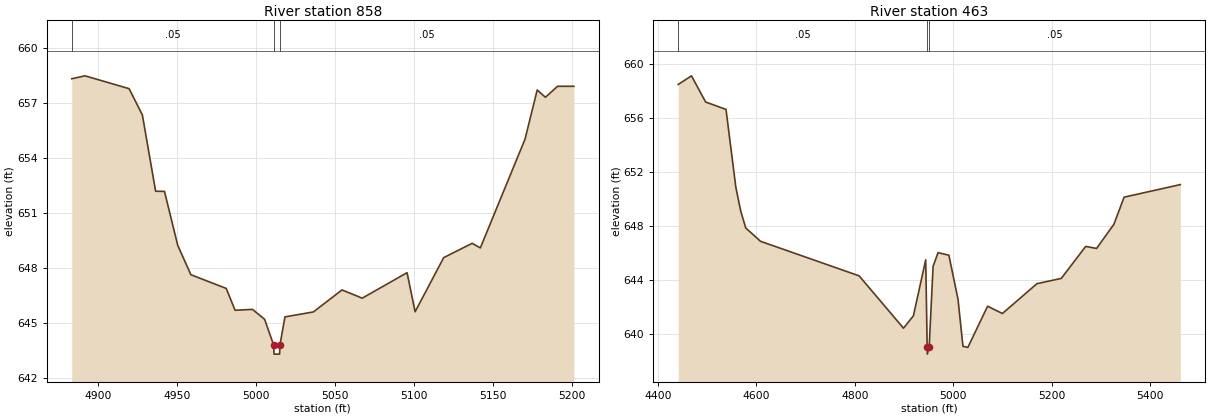
Type RM Length L Ch R = 1,858,395,395,395
BEGIN DESCRIPTION:
Elizabeth Creek Tributary 12 1.0
END DESCRIPTION:
XS GIS Cut Line= 3
      2331128.99      7055209.98      2331079.00      7055110.00
      2330879.04      7055159.99
#Sta/Elev= 30
  4883.1  658.33  4891.5  658.49  4919.4  657.79  4927.8  656.36  4936.2  652.20
  4941.8  652.19  4950.2  649.25  4958.5  647.65  4980.9  646.90  4986.5  645.71
  4997.5  645.76  5005.2  645.22  5010.9  643.82  5011.2  643.32  5014.7  643.32
  5014.9  643.82  5018.1  645.35  5036.1  645.62  5054.2  646.82  5067.0  646.37
  5095.4  647.76  5100.5  645.63  5118.6  648.58  5136.6  649.36  5141.8  649.11
  5170.1  655.04  5177.8  657.72  5183.0  657.32  5190.7  657.92  5201.0  657.92
#Mann=3,-1,0
  4883.1    0.05       0  5010.9   0.033       0  5014.9    0.05       0
Bank Sta=5010.9,5014.9
Exp/Cntr=0.3,0.1

Type RM Length L Ch R = 1,463,0,0,0
BEGIN DESCRIPTION:
1021
END DESCRIPTION:
XS GIS Cut Line= 4
      2331218.03      7055296.86      2331181.05      7054751.54
      2331042.41      7054742.30      2330829.79      7055001.14
#Sta/Elev= 30
  4441.3  658.46  4468.2  659.10  4497.0  657.16  4538.4  656.61  4558.4  650.84
  4568.4  649.07  4578.5  647.83  4608.5  646.84  4809.0  644.28  4899.2  640.40
  4919.3  641.32  4944.3  645.47  4947.3  638.98  4947.6  638.48  4951.3  638.98
  4959.3  644.98  4969.4  646.00  4991.4  645.81  5010.0  642.54  5020.0  639.06
  5030.0  638.98  5070.1  642.03  5100.2  641.49  5170.4  643.70  5219.9  644.09
  5269.4  646.46  5291.6  646.31  5326.8  648.10  5347.6  650.11  5461.8  651.04
#Mann=3,-1,0
  4441.3    0.05       0  4947.3   0.033       0  4951.3    0.05       0
Bank Sta=4947.3,4951.3
Exp/Cntr=0.3,0.1

Chan Stop Cuts=-1