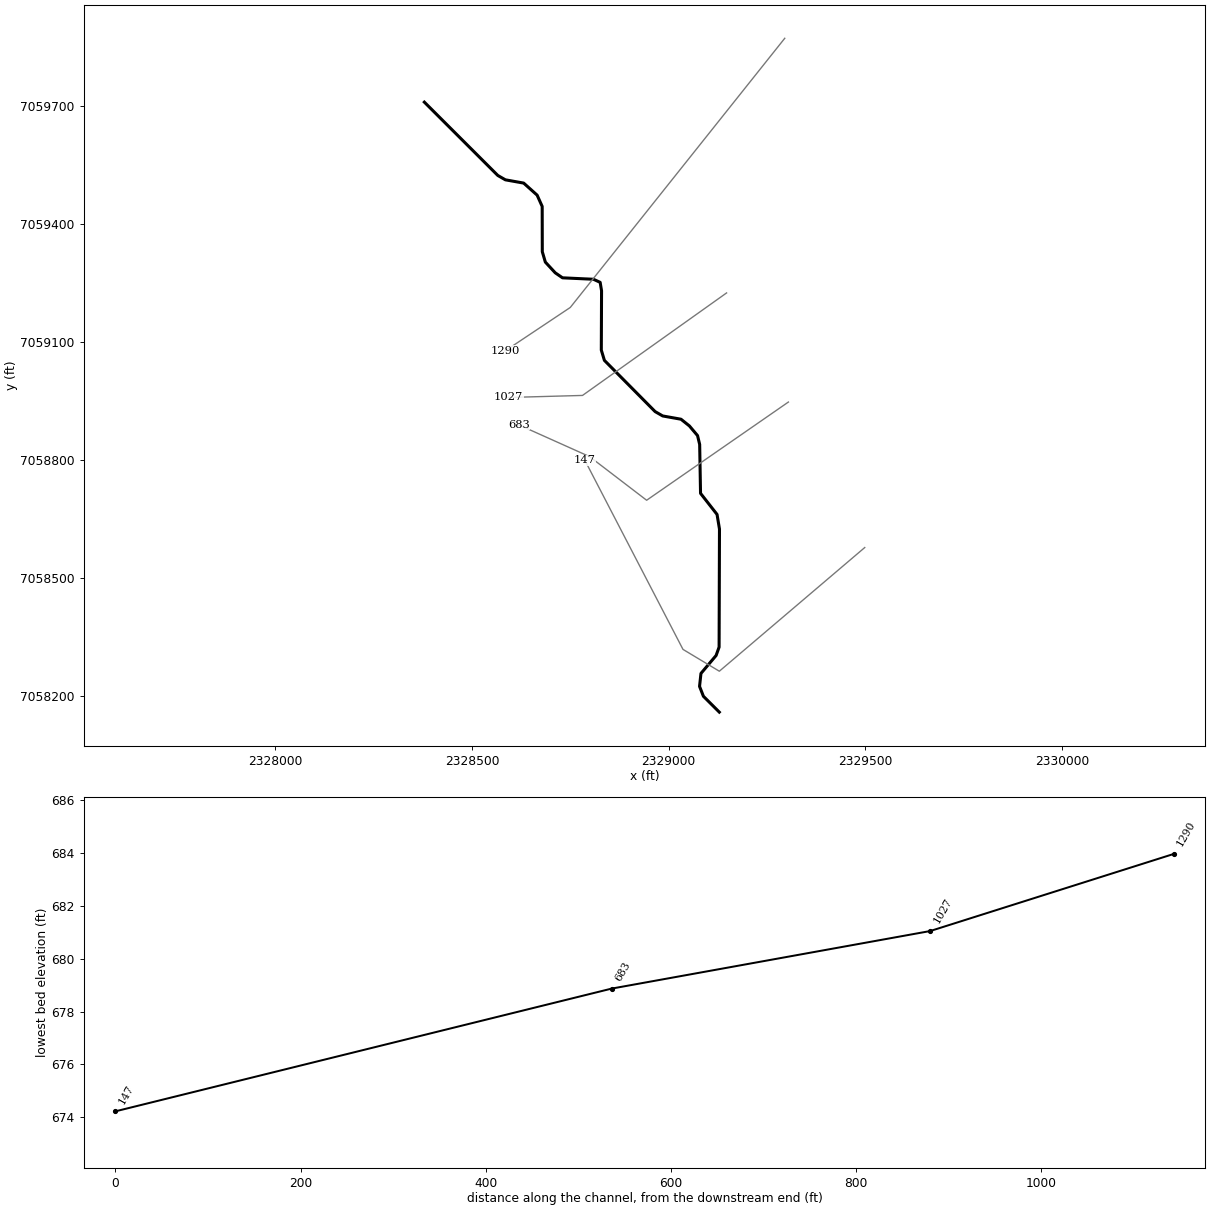
--- Elizabeth Cr Tr 12_1.prj (project) ---

Proj Title=Elizabeth Cr Tr 12_1 Base Level Engineering
Current Plan=p01
Default Exp/Contr=0.3,0.1
English Units
Geom File=g01
Flow File=f01
Plan File=p01
BEGIN DESCRIPTION:
Elizabeth Cr Tr 12_1
END DESCRIPTION:

--- Elizabeth Cr Tr 12_1.p01 (plan) ---

Plan Title=Multiple Run
Short Identifier=Multiple
Geom File=g01
Flow File=f01
Subcritical Flow
K Sum by GR= 0
Std Step Tol= 0.01
Critical Tol= 0.01
Num of Std Step Trials= 20
Max Error Tol= 0.3
Flow Tol Ratio= 0.001
Split Flow NTrial= 30
Split Flow Tol= 0.02
Split Flow Ratio= 0.02
Log Output Level= 0
Friction Slope Method= 1
Unsteady Friction Slope Method= 2
Unsteady Bridges Friction Slope Method= 1
Parabolic Critical Depth
Global Vel Dist=  1 , 1 , 1
Global Log Level= 0
CheckData=True
Encroach Param= -1, 0, 0, 0
BEGIN DESCRIPTION:
Multiple Run
END DESCRIPTION:

--- Elizabeth Cr Tr 12_1.f01 (steady flow) ---

Flow Title=Multiple
Number of Profiles=7
Profile Names=10-year,25-year,50-year,1pct_min,100-year,1pct_plu,500-year
River Rch & RM= Elizabeth Cr Tr ,Reach-1,1290
     188     237     275     158     316     630     417
Boundary for River Rch & Prof#=Elizabeth Cr Tr ,Reach-1,1
Up Type=0
Dn Type=3
Dn Slope=0.005
Boundary for River Rch & Prof#=Elizabeth Cr Tr ,Reach-1,2
Up Type=0
Dn Type=3
Dn Slope=0.005
Boundary for River Rch & Prof#=Elizabeth Cr Tr ,Reach-1,3
Up Type=0
Dn Type=3
Dn Slope=0.005
Boundary for River Rch & Prof#=Elizabeth Cr Tr ,Reach-1,4
Up Type=0
Dn Type=3
Dn Slope=0.005
Boundary for River Rch & Prof#=Elizabeth Cr Tr ,Reach-1,5
Up Type=0
Dn Type=3
Dn Slope=0.005
Boundary for River Rch & Prof#=Elizabeth Cr Tr ,Reach-1,6
Up Type=0
Dn Type=3
Dn Slope=0.005
Boundary for River Rch & Prof#=Elizabeth Cr Tr ,Reach-1,7
Up Type=0
Dn Type=3
Dn Slope=0.005

--- Elizabeth Cr Tr 12_1.g01 (geometry) ---

Geom Title=Existing Conditions

River Reach=Elizabeth Cr Tr ,Reach-1
Reach XY= 30
      2328379.00      7059710.00      2328565.80      7059523.64
      2328585.09      7059512.55      2328631.57      7059504.26
      2328665.77      7059473.67      2328678.65      7059444.96
      2328678.93      7059329.88      2328686.68      7059303.48
      2328711.81      7059276.28      2328730.33      7059263.55
      2328808.98      7059259.88      2328826.06      7059252.03
      2328829.60      7059230.59      2328828.96      7059079.98
      2328836.81      7059053.81      2328965.80      7058923.64
      2328985.09      7058912.55      2329031.57      7058904.26
      2329052.96      7058887.19      2329073.64      7058862.70
      2329079.07      7058840.11      2329081.27      7058715.94
      2329123.25      7058662.33      2329129.43      7058625.18
      2329128.47      7058325.21      2329120.84      7058303.92
      2329082.34      7058258.31      2329078.75      7058225.40
      2329088.62      7058200.20      2329129.00      7058160.00

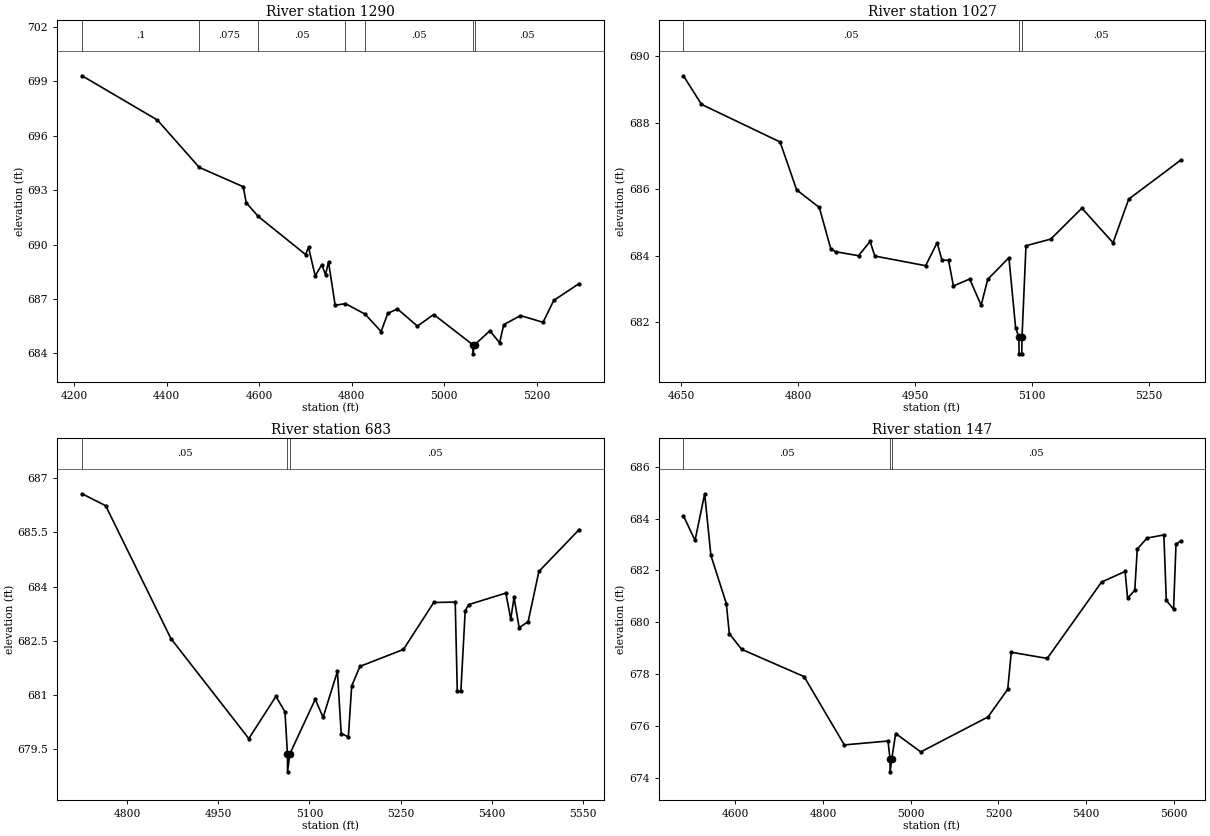
Type RM Length L Ch R = 1,1290,263,263,263
BEGIN DESCRIPTION:
71018
END DESCRIPTION:
XS GIS Cut Line= 3
      2329295.43      7059872.22      2328750.10      7059188.26
      2328583.90      7059077.46
#Sta/Elev= 30
  4217.0  699.31  4379.7  696.87  4470.1  694.26  4565.2  693.19  4571.9  692.30
  4597.8  691.55  4700.0  689.45  4706.4  689.85  4720.8  688.27  4735.2  688.89
  4743.2  688.33  4749.6  689.04  4764.0  686.65  4786.2  686.74  4828.7  686.16
  4863.3  685.20  4877.7  686.20  4898.5  686.45  4941.8  685.50  4977.0  686.14
  5061.5  684.47  5061.8  683.97  5065.5  684.47  5098.4  685.24  5119.4  684.58
  5128.4  685.58  5164.5  686.08  5213.3  685.71  5236.6  686.92  5291.5  687.85
#Mann=7,-1,0
  4217.0     0.1       0  4470.1   0.075       0  4597.8    0.05       0
  4786.2    0.12       0  4828.7    0.05       0  5061.5   0.033       0
  5065.5    0.05       0
Bank Sta=5061.5,5065.5
Exp/Cntr=0.3,0.1

Type RM Length L Ch R = 1,1027,344,344,344
BEGIN DESCRIPTION:
71017
END DESCRIPTION:
XS GIS Cut Line= 3
      2329147.52      7059225.20      2328781.18      7058964.70
      2328592.38      7058959.48
#Sta/Elev= 30
  4652.7  689.41  4675.9  688.55  4776.8  687.42  4798.1  685.98  4827.2  685.45
  4842.0  684.20  4848.1  684.12  4877.6  684.00  4892.4  684.43  4898.5  683.99
  4963.7  683.70  4978.5  684.39  4984.6  683.87  4993.2  683.86  4999.4  683.09
  5020.3  683.30  5035.0  682.51  5043.5  683.29  5070.7  683.94  5079.3  681.83
  5083.5  681.55  5083.7  681.05  5087.2  681.05  5087.5  681.55  5092.6  684.30
  5124.4  684.50  5164.4  685.43  5204.4  684.39  5224.5  685.70  5291.1  686.87
#Mann=3,-1,0
  4652.7    0.05       0  5083.5   0.033       0  5087.5    0.05       0
Bank Sta=5083.5,5087.5
Exp/Cntr=0.3,0.1

Type RM Length L Ch R = 1,683,536,536,536
BEGIN DESCRIPTION:
71016
END DESCRIPTION:
XS GIS Cut Line= 4
      2329304.70      7058947.94      2328944.21      7058698.37
      2328799.31      7058809.18      2328618.78      7058890.09
#Sta/Elev= 30
  4725.6  686.57  4764.4  686.24  4871.9  682.56  5000.2  679.79  5044.8  680.96
  5059.7  680.53  5063.8  679.37  5064.0  678.87  5067.8  679.37  5109.6  680.88
  5122.5  680.38  5146.1  681.65  5152.3  679.93  5164.1  679.84  5169.6  681.25
  5183.2  681.79  5254.9  682.26  5304.7  683.56  5340.1  683.57  5343.5  681.10
  5349.4  681.10  5356.5  683.32  5362.0  683.50  5423.5  683.82  5431.5  683.10
  5437.0  683.70  5445.4  682.86  5460.2  683.03  5477.9  684.42  5544.3  685.58
#Mann=3,-1,0
  4725.6    0.05       0  5063.8   0.033       0  5067.8    0.05       0
Bank Sta=5063.8,5067.8
Exp/Cntr=0.3,0.1

Type RM Length L Ch R = 1,147,0,0,0
BEGIN DESCRIPTION:
1016
END DESCRIPTION:
XS GIS Cut Line= 4
      2329498.79      7058578.20      2329129.07      7058263.94
      2329036.64      7058319.40      2328787.08      7058800.04
#Sta/Elev= 30
  4481.2  684.11  4507.7  683.16  4529.7  684.96  4543.9  682.58  4579.1  680.72
  4585.9  679.56  4614.2  678.95  4756.5  677.90  4848.4  675.26  4948.1  675.41
  4952.7  674.72  4952.9  674.22  4956.7  674.72  4965.6  675.70  5022.9  674.99
  5176.3  676.34  5221.4  677.41  5229.4  678.84  5311.5  678.60  5435.5  681.55
  5489.2  681.96  5494.9  680.93  5511.3  681.23  5517.0  682.82  5539.1  683.25
  5577.7  683.37  5583.3  680.84  5599.8  680.50  5605.4  683.01  5615.8  683.13
#Mann=3,-1,0
  4481.2    0.05       0  4952.7   0.033       0  4956.7    0.05       0
Bank Sta=4952.7,4956.7
Exp/Cntr=0.3,0.1

Chan Stop Cuts=-1