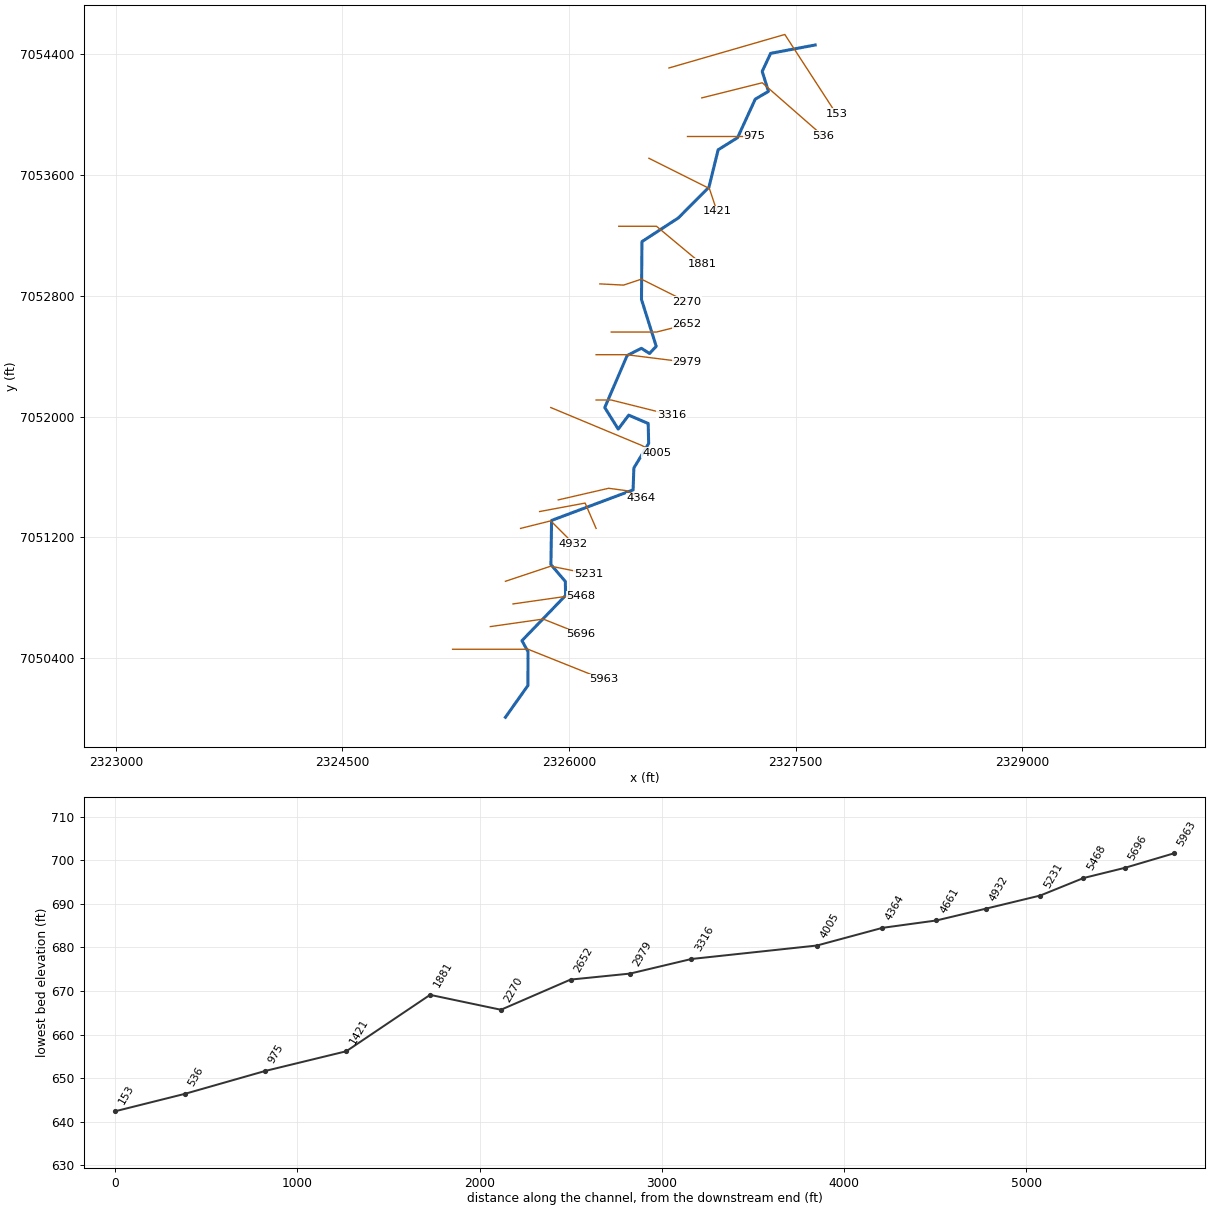
--- Elizabeth Cr Tr 13.prj (project) ---

Proj Title=Elizabeth Cr Tr 13 Base Level Engineering
Current Plan=p01
Default Exp/Contr=0.3,0.1
English Units
Geom File=g01
Flow File=f01
Plan File=p01
Y Axis Title=Elevation
X Axis Title(PF)=Main Channel Distance
X Axis Title(XS)=Station
BEGIN DESCRIPTION:
Elizabeth Cr Tr 13
END DESCRIPTION:
DSS Export Rating Curves= 0
DSS Export Rating Curve Sorted= 0
DSS Export Volume Flow Curves= 0
DXF OffsetX= 0
DXF OffsetY= 0
DXF ScaleX= 1
DXF ScaleY= 10

--- Elizabeth Cr Tr 13.p01 (plan) ---

Plan Title=Multiple Run
Program Version=4.10
Short Identifier=Multiple
Geom File=g01
Flow File=f01
Subcritical Flow
K Sum by GR= 0
Std Step Tol= 0.01
Critical Tol= 0.01
Num of Std Step Trials= 20
Max Error Tol= 0.3
Flow Tol Ratio= 0.001
Split Flow NTrial= 30
Split Flow Tol= 0.02
Split Flow Ratio= 0.02
Log Output Level= 0
Friction Slope Method= 0
Unsteady Friction Slope Method= 2
Unsteady Bridges Friction Slope Method= 1
Parabolic Critical Depth
Global Vel Dist= 1 , 1 , 1
Global Log Level= 0
CheckData=True
Encroach Param=-1 ,0,0, 0
BEGIN DESCRIPTION:
Multiple Run
END DESCRIPTION:
Computation Interval=1HOUR
Output Interval=1HOUR
Run HTab= 0
Run UNet= 0
Run PostProcess= 0
Run WQNet= 0
UNET Theta= 1
UNET Theta Warmup= 1
UNET ZTol= 0.02
UNET ZSATol= 0.05
UNET MxIter= 20
UNET MaxInSteps= 0
UNET DtIC= 0
UNET DtMin= 0
UNET MaxCRTS= 20
UNET WFStab= 2
UNET SFStab= 1
UNET WFX= 1
UNET SFX= 1
UNET DSS MLevel= 4
UNET DZMax Abort= 100
UNET Convert EG Bridges= 0
UNET Use Existing IB Tables=-1
UNET Froude Reduction=False
UNET Froude Limit= 1
UNET Froude Power= 10
UNET Time Slicing=0,0, 5
UNET Junction Losses=0
Instantaneous Interval=1HOUR
Write IC File= 0
Write IC File at Sim End=0
Echo Input=False
Echo Parameters=False
Echo Output=False
Write Detailed= 0
WQ AD Non Conservative
WQ ULTIMATE=-1
WQ Max Comp Step=1HOUR
WQ Output Interval=15MIN
WQ Output Selected Increments= 0
WQ Output face flow=0
WQ Output face velocity=0
WQ Output face area=0
WQ Output face dispersion=0
WQ Output cell volume=0
WQ Output cell surface area=0
WQ Output cell continuity=0
WQ Output cumulative cell continuity=0
WQ Output face conc=0
WQ Output face dconc_dx=0
WQ Output face courant=0
WQ Output face peclet=0
WQ Output face adv mass=0
WQ Output face disp mass=0
WQ Output cell mass=0
WQ Output cell source sink temp=0
WQ Output cell source sink nsm=0
WQ Output MaxMinRange=-1
WQ Daily Max Min Mean=-1
WQ Daily Range=0
WQ Daily Time=0
WQ Create Restart=0
WQ Fixed Restart=0
WQ System Summary=0
WQ Use Fixed Temperature=0
Sorting and Armoring Iterations= 10
XS Update Threshold= 0.02
Hydraulics Update Threshold= 0.02
Energy Slope Method= 1
Volume Change Method= 0
XS Weighting Method= 0
Number of US Weighted Cross Sections= 1
Number of DS Weighted Cross Sections= 1
Upstream XS Weight=0.25
Main XS Weight=0.5
Downstream XS Weight=0.25
Number of DS XS's Weighted with US Boundary= 1
Upstream Boundary Weight= 1
Weight of XSs Associated with US Boundary= 0
Number of US XS's Weighted with DS Boundary= 1
Downstream Boundary Weight= 0.5
Weight of XSs Associated with DS Boundary= 0.5
Sediment Output Level= 4
Mass or Volume Output= 0
Output Increment Type= 1
Profile and TS Output Increment= 10
XS Output Flag= 0
XS Output Increment= 10
Disregard all LS=0
Disregard all Conn=0
Disregard all Breaches=0
Disregard all Pumps=0

--- Elizabeth Cr Tr 13.f01 (steady flow) ---

Flow Title=Multiple
Number of Profiles=7
Profile Names=10-year,25-year,50-year,1pct_min,100-year,1pct_plu,500-year
River Rch & RM= Elizabeth Cr Tr ,Reach-1,5963
     251     325     382     224     447     893     612
River Rch & RM= Elizabeth Cr Tr ,Reach-1,4005
     664     913    1120     680    1360    2710    2000
River Rch & RM= Elizabeth Cr Tr ,Reach-1,153
     677     931    1140     695    1390    2770    2050
Boundary for River Rch & Prof#=Elizabeth Cr Tr ,Reach-1,1
Up Type=0
Dn Type=3
Dn Slope=0.005
Boundary for River Rch & Prof#=Elizabeth Cr Tr ,Reach-1,2
Up Type=0
Dn Type=3
Dn Slope=0.005
Boundary for River Rch & Prof#=Elizabeth Cr Tr ,Reach-1,3
Up Type=0
Dn Type=3
Dn Slope=0.005
Boundary for River Rch & Prof#=Elizabeth Cr Tr ,Reach-1,4
Up Type=0
Dn Type=3
Dn Slope=0.005
Boundary for River Rch & Prof#=Elizabeth Cr Tr ,Reach-1,5
Up Type=0
Dn Type=3
Dn Slope=0.005
Boundary for River Rch & Prof#=Elizabeth Cr Tr ,Reach-1,6
Up Type=0
Dn Type=3
Dn Slope=0.005
Boundary for River Rch & Prof#=Elizabeth Cr Tr ,Reach-1,7
Up Type=0
Dn Type=3
Dn Slope=0.005

--- Elizabeth Cr Tr 13.g01 (geometry) ---

Geom Title=Existing Conditions
Program Version=4.10

River Reach=Elizabeth Cr Tr ,Reach-1
Reach XY= 30
        2325579.        7050010.      2325727.95      7050220.44
      2325728.34      7050444.84      2325688.13      7050516.74
      2325977.04      7050815.88      2325975.53       7050908.5
      2325880.06      7051020.44      2325884.34      7051312.74
      2326424.02      7051515.02        2326429.        7051660.
      2326527.06      7051821.98      2326523.84      7051954.59
      2326395.02      7052009.74      2326325.59      7051917.44
       2326236.5        7052060.      2326384.59      7052404.45
      2326479.07      7052452.23      2326532.63      7052417.88
      2326577.04       7052465.5      2326479.52      7052775.22
      2326482.54      7053158.54      2326723.53      7053315.26
      2326925.92      7053518.31      2326987.02      7053766.34
      2327115.52      7053846.44      2327232.56      7054101.52
      2327319.94        7054153.      2327278.59      7054285.01
      2327334.44      7054404.75        2327629.        7054460.

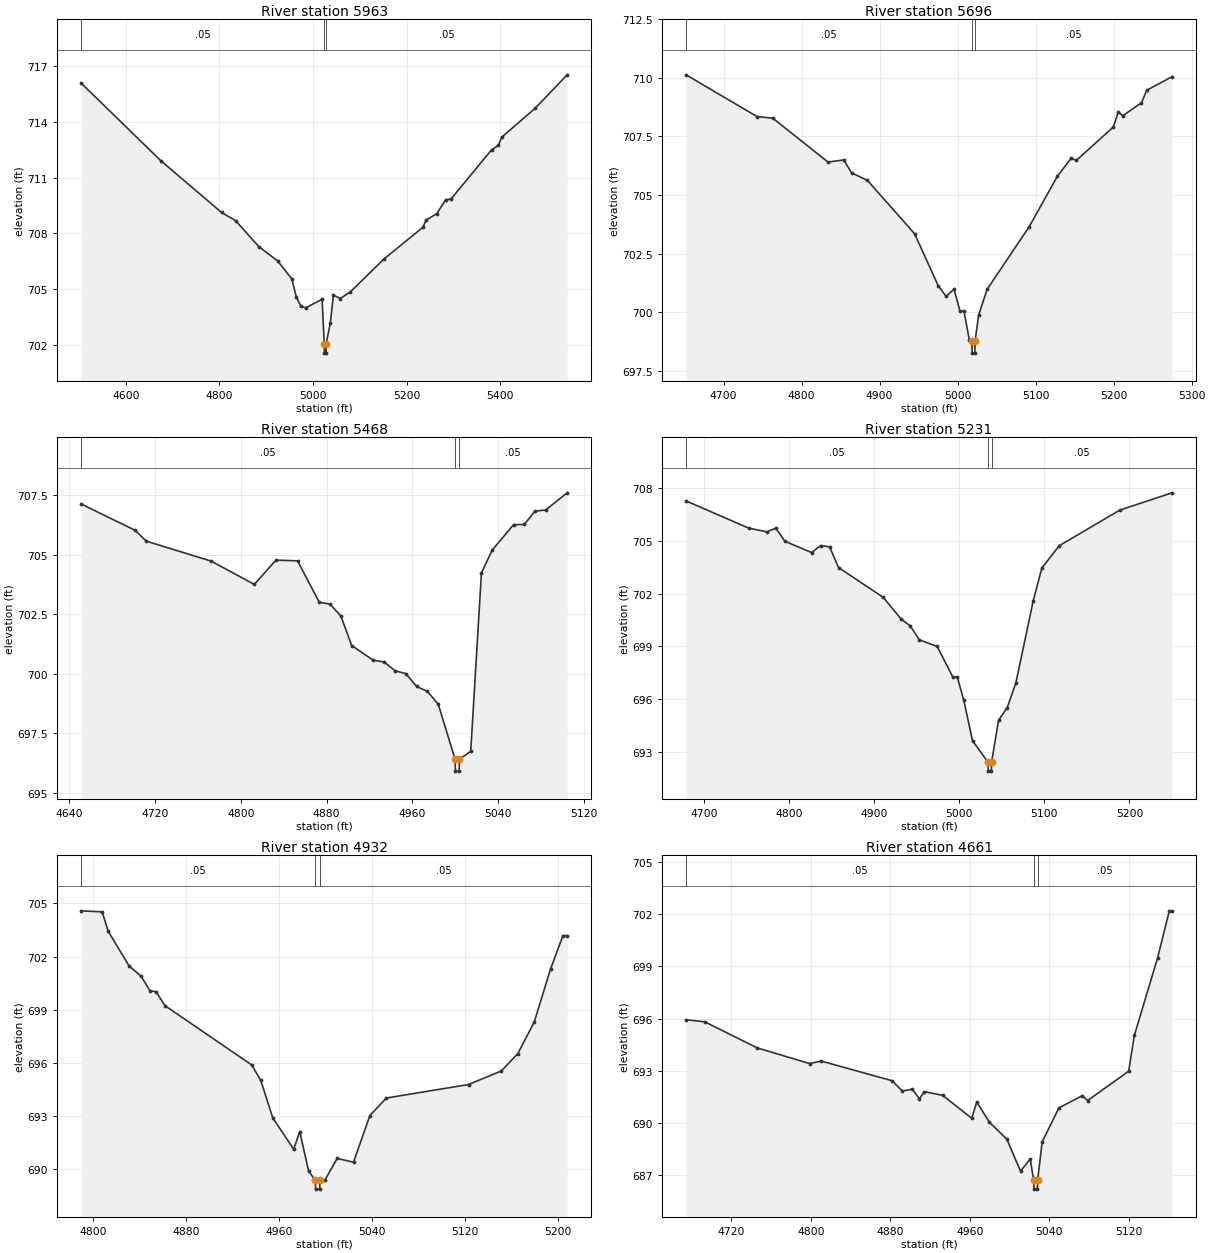
Type RM Length L Ch R = 1 ,5963    ,267,267,267
BEGIN DESCRIPTION:
Elizabeth Creek Tributary 13 16.0
END DESCRIPTION:
XS GIS Cut Line= 3
      2325229.02        7050460.        2325729.        7050460.
      2326229.01        7050260.
#Sta/Elev= 30
  4504.8  716.09  4674.8  711.92  4804.8  709.13  4834.8  708.69  4884.8  707.28
  4924.8  706.52  4954.8  705.56  4964.8  704.56  4974.8  704.07  4984.8     704
  5019.6  704.46  5024.3  702.06  5024.6  701.56  5028.1  701.56  5028.3  702.06
  5037.1  703.17  5043.8  704.68  5058.6   704.5  5080.2  704.86  5151.5  706.62
    5235  708.33  5241.7  708.71  5264.6  709.07  5283.5   709.8  5295.6  709.87
  5381.7   712.5  5396.5  712.74  5403.3  713.18  5474.6  714.73  5543.3  716.54
#Mann= 3 ,-1 , 0
  4504.8     .05       0  5024.3    .033       0  5028.3     .05       0
Bank Sta=5024.3,5028.3
XS Rating Curve= 0 ,0
Exp/Cntr=0.3,0.1

Type RM Length L Ch R = 1 ,5696    ,228,228,228
BEGIN DESCRIPTION:
Elizabeth Creek Tributary 13 15.0
END DESCRIPTION:
XS GIS Cut Line= 3
      2325478.96      7050609.99        2325829.        7050660.
      2326079.05      7050559.98
#Sta/Elev= 30
  4651.9  710.13  4742.9  708.35  4763.1  708.28  4833.8  706.41    4854   706.5
  4864.1  705.95  4884.3  705.63  4944.9  703.35  4975.2  701.13  4985.3  700.68
  4995.4  700.99    5003  700.05  5008.2  700.05  5014.9  698.84  5018.3  698.76
  5018.6  698.26  5022.1  698.26  5022.3  698.76    5027  699.89  5037.8  700.98
  5091.7  703.65    5128  705.81  5145.5  706.57  5152.2  706.48  5199.4   707.9
  5206.1  708.55  5211.5  708.38  5235.7  708.94  5242.4  709.47  5274.8  710.05
#Mann= 3 ,-1 , 0
  4651.9     .05       0  5018.3    .033       0  5022.3     .05       0
Bank Sta=5018.3,5022.3
XS Rating Curve= 0 ,0
Exp/Cntr=0.3,0.1

Type RM Length L Ch R = 1 ,5468    ,237,237,237
BEGIN DESCRIPTION:
Elizabeth Creek Tributary 13 14.0
END DESCRIPTION:
XS GIS Cut Line= 3
        2325629.        7050760.        2325979.        7050810.
      2326079.05        7050810.
#Sta/Elev= 30
    4651  707.14  4701.5  706.03  4711.6  705.58  4772.2  704.74  4812.6  703.76
  4832.8  704.78    4853  704.75  4873.2  703.01  4883.3  702.93  4893.4  702.43
  4903.5  701.19  4923.7  700.57  4933.8   700.5  4943.9  700.13    4954  700.01
  4964.1  699.47  4974.2  699.26  4984.3  698.72    5000  696.41  5000.3  695.91
  5003.8  695.91    5004  696.41  5014.6  696.74  5024.6  704.24  5034.6   705.2
  5054.6  706.27  5064.6  706.28  5074.6  706.84  5084.6  706.89  5104.6  707.61
#Mann= 3 ,-1 , 0
    4651     .05       0    5000    .033       0    5004     .05       0
Bank Sta=5000,5004
XS Rating Curve= 0 ,0
Exp/Cntr=0.3,0.1

Type RM Length L Ch R = 1 ,5231    ,299,299,299
BEGIN DESCRIPTION:
Elizabeth Creek Tributary 13 13.0
END DESCRIPTION:
XS GIS Cut Line= 3
      2325578.96      7050909.99        2325879.        7051010.
      2326128.98        7050960.
#Sta/Elev= 30
  4678.9  707.27  4752.7  705.72  4773.8  705.51  4784.4  705.72  4794.9  704.98
  4826.5  704.33  4837.1  704.73  4847.6  704.66  4858.1  703.48  4910.8  701.78
  4931.9  700.54  4942.5  700.16    4953  699.37  4974.1  698.99  4992.5  697.25
  4997.7  697.25  5005.4  695.92  5015.6  693.63    5034   692.4  5034.2   691.9
  5037.7   691.9    5038   692.4  5046.2  694.79  5056.4  695.51  5066.6  696.92
    5087  701.59  5097.1  703.45  5117.5  704.72  5188.9  706.75  5250.1  707.73
#Mann= 3 ,-1 , 0
  4678.9     .05       0    5034    .033       0    5038     .05       0
Bank Sta=5034,5038
XS Rating Curve= 0 ,0
Exp/Cntr=0.3,0.1

Type RM Length L Ch R = 1 ,4932    ,271,271,271
BEGIN DESCRIPTION:
Elizabeth Creek Tributary 13 12.0
END DESCRIPTION:
XS GIS Cut Line= 3
      2325679.03      7051260.01        2325879.        7051310.
      2326029.03      7051159.97
#Sta/Elev= 30
  4789.8  704.58  4807.8  704.52    4813  703.43    4831  701.47  4841.3   700.9
    4849  700.07  4854.2  700.02  4861.9  699.23  4936.7  695.88  4944.4  695.01
  4954.7   692.9  4972.7  691.13  4977.9  692.13  4985.6  689.89  4991.3  689.38
  4991.6  688.88  4995.1  688.88  4995.3  689.38  4999.5  689.38  5010.1  690.61
  5024.2   690.4  5038.3  693.03  5052.5  694.02  5123.2  694.78  5151.5  695.55
  5165.6  696.52  5179.8  698.31  5193.9  701.31  5204.5  703.18  5208.1  703.18
#Mann= 3 ,-1 , 0
  4789.8     .05       0  4991.3    .033       0  4995.3     .05       0
Bank Sta=4991.3,4995.3
XS Rating Curve= 0 ,0
Exp/Cntr=0.3,0.1

Type RM Length L Ch R = 1 ,4661    ,297,297,297
BEGIN DESCRIPTION:
Elizabeth Creek Tributary 13 11.0
END DESCRIPTION:
XS GIS Cut Line= 3
      2325805.09      7051371.62      2326106.34      7051427.74
      2326178.99      7051260.03
#Sta/Elev= 30
  4674.4  695.93  4693.3  695.81    4746  694.31  4798.7  693.41  4810.6  693.55
  4881.8  692.42    4892  691.83  4902.2  691.93  4909.3  691.38  4914.4  691.79
  4932.7  691.58    4962  690.26  4967.1   691.2  4979.6  690.04  4997.4  689.05
  5011.1  687.21  5020.9  687.92  5024.3  686.68  5024.6  686.18  5028.1  686.18
  5028.3  686.68  5032.9   688.9  5049.8  690.86  5073.3  691.56  5078.7  691.28
    5120  692.97  5125.7  695.03  5149.2  699.51  5160.9   702.2  5163.6   702.2
#Mann= 3 ,-1 , 0
  4674.4     .05       0  5024.3    .033       0  5028.3     .05       0
Bank Sta=5024.3,5028.3
XS Rating Curve= 0 ,0
Exp/Cntr=0.3,0.1

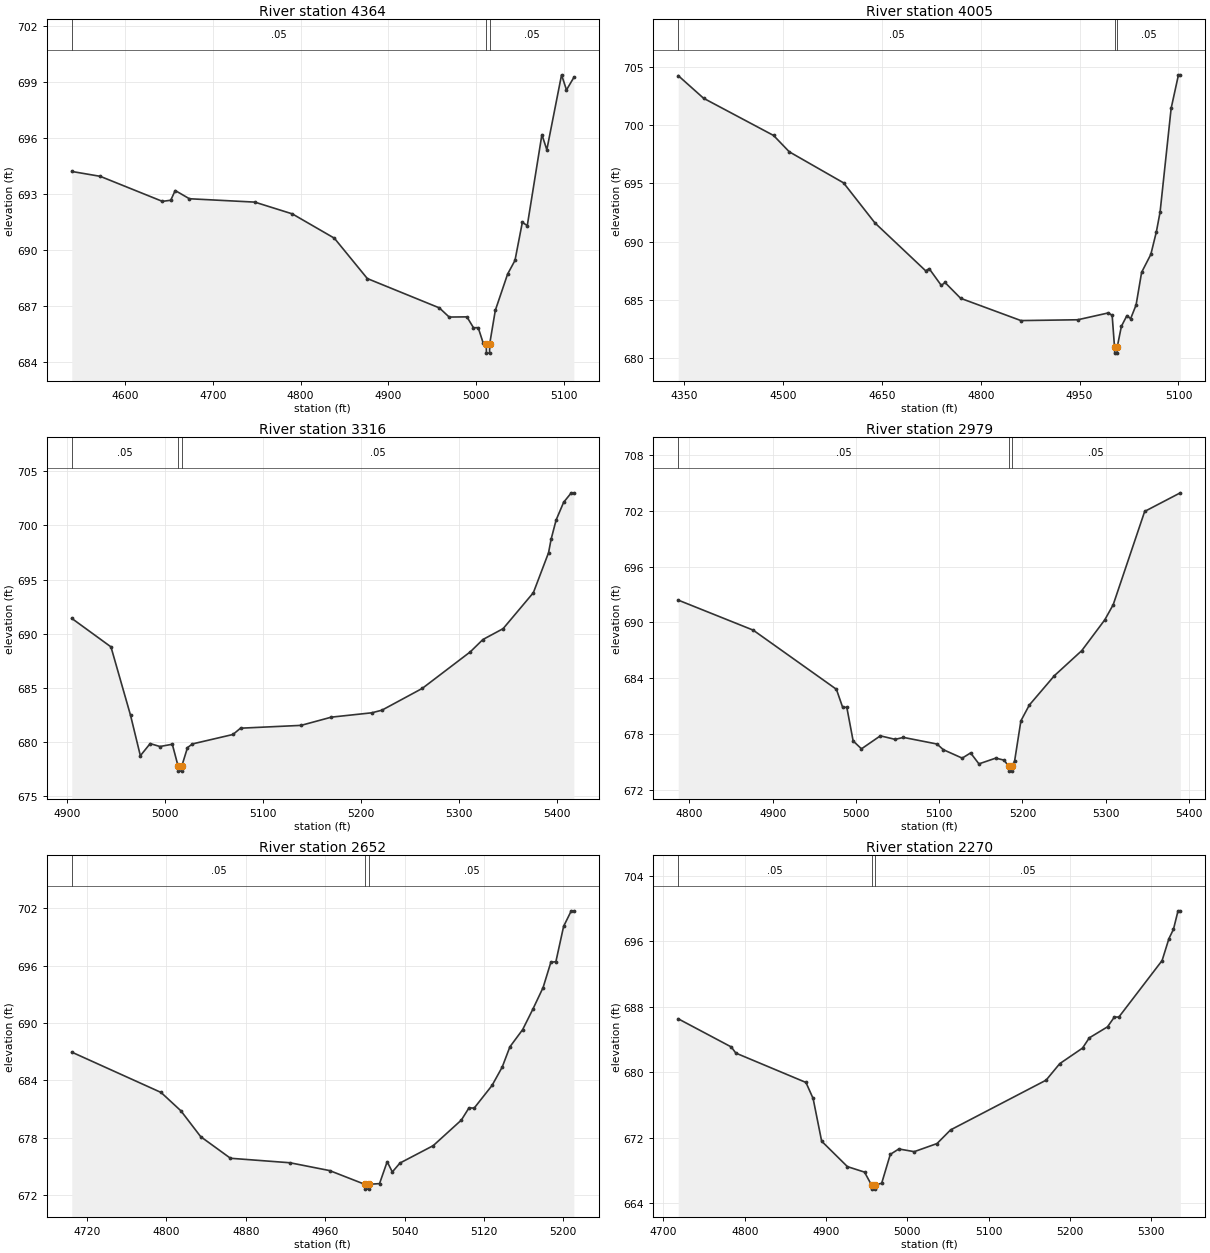
Type RM Length L Ch R = 1 ,4364    ,359,359,359
BEGIN DESCRIPTION:
Elizabeth Creek Tributary 13 10.0
END DESCRIPTION:
XS GIS Cut Line= 4
      2325928.35      7051448.65      2326262.15      7051525.68
        2326379.        7051510.      2326479.03      7051459.99
#Sta/Elev= 30
  4539.1   694.2  4571.5  693.94  4642.4   692.6  4651.9  692.66    4657  693.18
  4673.2  692.74  4747.7  692.56  4790.5  691.93  4838.4  690.63    4876  688.47
  4958.1   686.9  4969.3  686.41  4989.5  686.42    4997  685.84  5002.4  685.84
    5008  685.03  5011.5  684.98  5011.8  684.48  5015.3  684.48  5015.5  684.98
  5021.9  686.77  5035.9  688.71  5044.3  689.44  5052.7  691.48  5058.3   691.3
    5075  696.17  5080.6  695.36  5097.4  699.37    5103  698.56  5111.4  699.23
#Mann= 3 ,-1 , 0
  4539.1     .05       0  5011.5    .033       0  5015.5     .05       0
Bank Sta=5011.5,5015.5
XS Rating Curve= 0 ,0
Exp/Cntr=0.3,0.1

Type RM Length L Ch R = 1 ,4005    ,689,689,689
BEGIN DESCRIPTION:
Elizabeth Creek Tributary 13 9.0
END DESCRIPTION:
XS GIS Cut Line= 3
      2325878.98      7052060.01        2326479.        7051810.
      2326578.97      7051760.01
#Sta/Elev= 30
    4341  704.22  4379.5  702.28  4485.7  699.09  4509.5  697.69  4591.8  695.03
  4639.5  691.59  4716.4  687.49  4721.8  687.67  4740.2  686.23  4745.7  686.49
  4769.5  685.13    4861  683.22  4947.2  683.29  4993.8  683.88  4999.4  683.66
    5003  680.93  5003.3  680.43  5006.8  680.43    5007  680.93  5013.4  682.73
  5021.8  683.65  5027.4  683.38  5035.7  684.56  5044.1  687.36  5058.1   688.9
  5066.5  690.84  5072.1  692.52  5088.9  701.42    5100  704.29  5102.8  704.29
#Mann= 3 ,-1 , 0
    4341     .05       0    5003    .033       0    5007     .05       0
Bank Sta=5003,5007
XS Rating Curve= 0 ,0
Exp/Cntr=0.3,0.1

Type RM Length L Ch R = 1 ,3316    ,337,337,337
BEGIN DESCRIPTION:
Elizabeth Creek Tributary 13 8.0
END DESCRIPTION:
XS GIS Cut Line= 3
      2326178.96        7052110.        2326279.        7052110.
      2326679.05      7052009.99
#Sta/Elev= 30
  4905.2  691.43  4945.2   688.8  4965.2  682.48  4975.2  678.76  4985.2  679.88
  4995.2  679.61  5007.8  679.82  5013.6  677.84  5013.8  677.34  5017.3  677.34
  5017.6  677.84  5023.3  679.51  5028.4  679.85  5069.7  680.72  5077.4   681.3
  5139.2  681.56  5170.2  682.32  5211.4  682.72  5221.7  682.96  5262.9  684.97
  5311.9  688.34  5324.8  689.48  5345.4  690.48  5376.3   693.8  5391.8  697.49
  5394.4  698.73  5399.5   700.5  5407.2  702.14    5415  703.01  5417.6  703.01
#Mann= 3 ,-1 , 0
  4905.2     .05       0  5013.6    .033       0  5017.6     .05       0
Bank Sta=5013.6,5017.6
XS Rating Curve= 0 ,0
Exp/Cntr=0.3,0.1

Type RM Length L Ch R = 1 ,2979    ,327,327,327
BEGIN DESCRIPTION:
Elizabeth Creek Tributary 13 7.0
END DESCRIPTION:
XS GIS Cut Line= 3
      2326179.01        7052410.        2326379.        7052410.
        2326779.        7052360.
#Sta/Elev= 30
  4786.5   692.4  4876.5  689.17  4976.5   682.8    4984  680.86    4989  680.86
  4996.6  677.24  5006.6  676.39  5029.3  677.79    5047  677.41    5057  677.62
  5097.3  676.91  5104.9   676.3  5127.6  675.39  5137.7  675.95  5147.7  674.77
  5167.9  675.39    5178  675.17  5183.5  674.49  5183.8  673.99  5187.3  673.99
  5187.5  674.49  5190.6   675.1  5198.1   679.4  5208.2   681.1  5238.4  684.27
  5271.2  686.96  5298.9  690.28    5309  691.91  5346.8  701.95  5389.6  703.95
#Mann= 3 ,-1 , 0
  4786.5     .05       0  5183.5    .033       0  5187.5     .05       0
Bank Sta=5183.5,5187.5
XS Rating Curve= 0 ,0
Exp/Cntr=0.3,0.1

Type RM Length L Ch R = 1 ,2652    ,382,382,382
BEGIN DESCRIPTION:
Elizabeth Creek Tributary 13 6.0
END DESCRIPTION:
XS GIS Cut Line= 3
      2326278.99        7052560.        2326579.        7052560.
      2326779.03      7052610.01
#Sta/Elev= 30
  4704.5  686.95  4794.5  682.73  4814.5  680.81  4834.5   678.1  4864.5  675.84
  4924.5  675.37  4964.5  674.55    5000  673.11  5000.3  672.61  5003.8  672.61
    5004  673.11  5014.8  673.19  5022.5  675.48  5027.7  674.41  5035.4  675.34
  5068.9  677.16  5097.3  679.84    5105  681.12  5110.2  681.09  5128.2  683.46
  5138.5  685.39  5146.2   687.5  5159.1  689.31  5169.4  691.45  5179.7  693.71
  5187.5  696.35  5192.6  696.42  5200.4  700.12  5208.1  701.74  5210.7  701.74
#Mann= 3 ,-1 , 0
  4704.5     .05       0    5000    .033       0    5004     .05       0
Bank Sta=5000,5004
XS Rating Curve= 0 ,0
Exp/Cntr=0.3,0.1

Type RM Length L Ch R = 1 ,2270    ,389,389,389
BEGIN DESCRIPTION:
Elizabeth Creek Tributary 13 5.0
END DESCRIPTION:
XS GIS Cut Line= 4
      2326203.87       7052878.7       2326360.7      7052870.57
        2326479.        7052910.      2326779.04      7052759.98
#Sta/Elev= 30
  4718.3  686.51  4783.5  683.07  4789.1  682.32  4875.3  678.73  4884.1  676.77
  4894.6  671.55  4926.3  668.44  4947.3  667.77  4955.9  666.19  4956.1  665.69
  4959.6  665.69  4959.9  666.19  4968.4  666.41    4979  669.94  4989.5   670.6
  5008.4  670.27  5036.4  671.26  5053.1  672.93  5170.5  679.01  5187.3  681.03
  5215.3  682.93  5223.6  684.18    5246  685.53  5254.4  686.72    5260  686.73
  5313.1  693.63  5321.5  696.31  5327.1  697.46  5332.7  699.71  5335.5  699.71
#Mann= 3 ,-1 , 0
  4718.3     .05       0  4955.9    .033       0  4959.9     .05       0
Bank Sta=4955.9,4959.9
XS Rating Curve= 0 ,0
Exp/Cntr=0.3,0.1

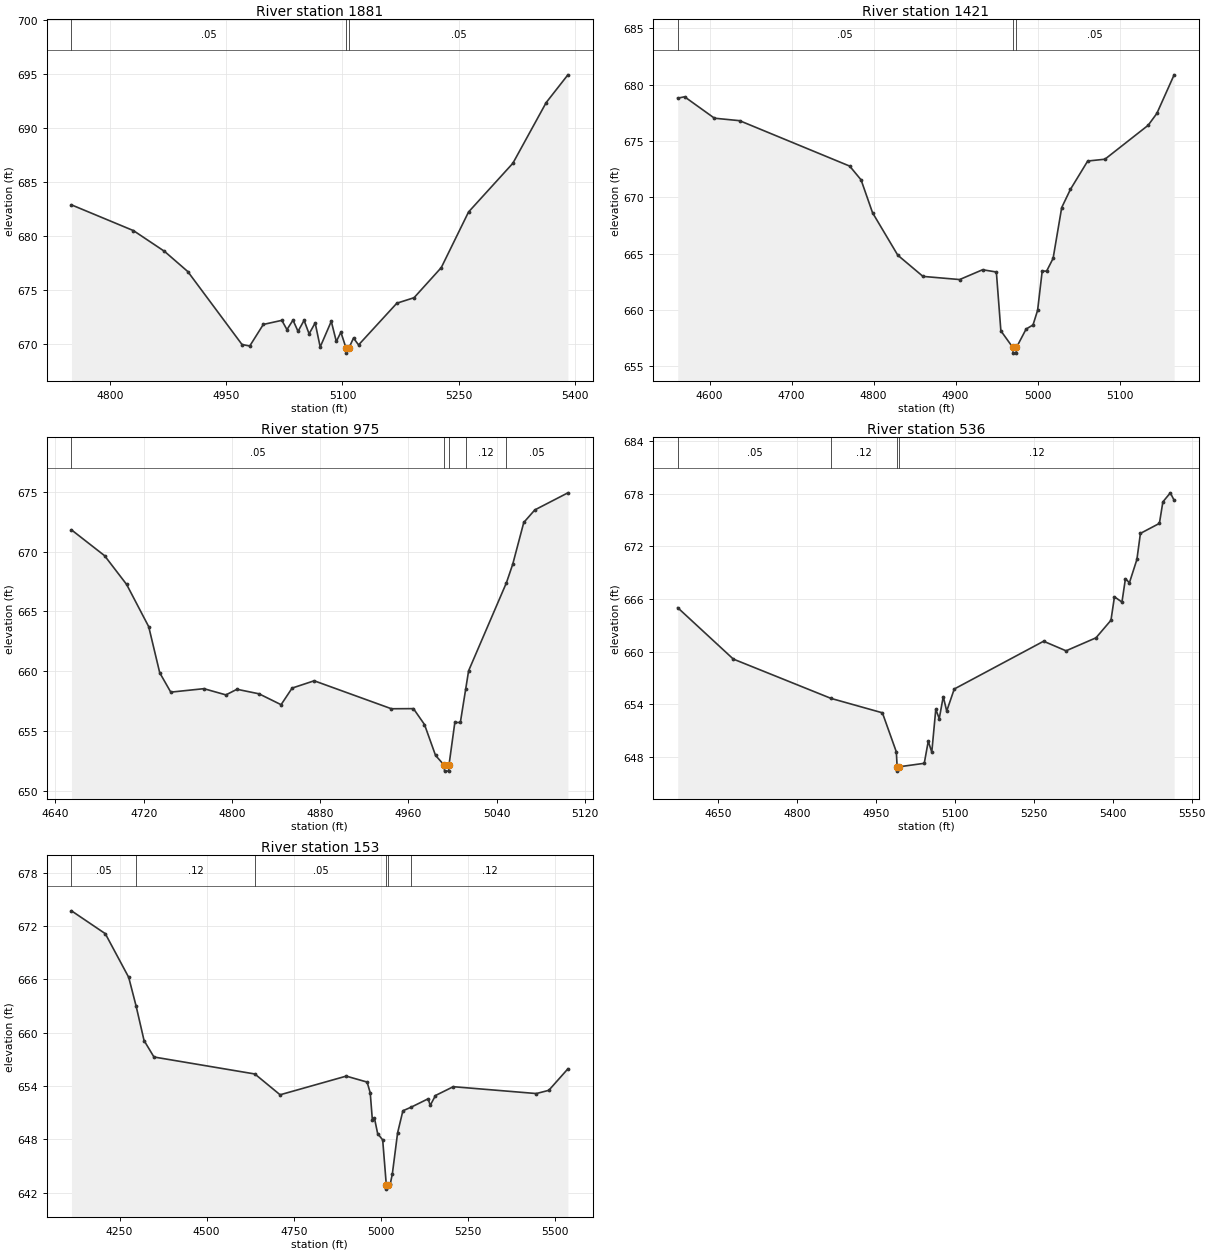
Type RM Length L Ch R = 1 ,1881    ,460,460,460
BEGIN DESCRIPTION:
Elizabeth Creek Tributary 13 4.0
END DESCRIPTION:
XS GIS Cut Line= 3
      2326329.03        7053260.        2326579.        7053260.
      2326879.02      7053009.99
#Sta/Elev= 30
  4750.4  682.86  4830.4  680.47  4870.4  678.55  4900.4  676.68  4970.4  669.91
  4980.4  669.77  4997.9  671.77  5021.8  672.15  5028.4  671.29  5036.2  672.17
  5042.7  671.13  5050.5  672.15    5057   670.9  5064.8  671.91  5071.3  669.68
  5085.6  672.06  5092.1  670.19    5098  671.05  5104.5  669.61  5104.7  669.11
  5108.5  669.61  5114.3  670.51  5120.8  669.87  5170.2  673.74  5192.4  674.25
  5227.5  677.04  5262.7   682.2  5319.9  686.72  5362.9  692.35  5390.9  694.92
#Mann= 3 ,-1 , 0
  4750.4     .05       0  5104.5     .05       0  5108.5     .05       0
Bank Sta=5104.5,5108.5
XS Rating Curve= 0 ,0
Exp/Cntr=0.3,0.1

Type RM Length L Ch R = 1 ,1421    ,446,446,446
BEGIN DESCRIPTION:
Elizabeth Creek Tributary 13 3.0
END DESCRIPTION:
XS GIS Cut Line= 3
      2326528.97      7053710.02        2326929.        7053510.
      2326979.01      7053359.97
#Sta/Elev= 30
  4561.2   678.8  4569.6  678.92    4606  677.02  4636.7   676.8  4770.9  672.77
  4784.8  671.55  4798.8  668.63  4829.6  664.86  4860.3  662.98    4905   662.7
    4933  663.57  4949.8  663.37  4955.3  658.15  4969.9  656.67  4970.3  656.17
  4973.9  656.17  4974.3  656.67  4986.1  658.31  4994.5  658.67  5000.1  659.97
  5005.7  663.45  5011.1  663.45    5019  664.58  5029.5  669.09  5040.1   670.7
  5061.2  673.22  5082.2  673.38  5134.9  676.39  5145.5  677.44  5166.6  680.87
#Mann= 3 ,-1 , 0
  4561.2     .05       0  4969.9    .033       0  4974.3     .05       0
Bank Sta=4969.9,4974.3
XS Rating Curve= 0 ,0
Exp/Cntr=0.3,0.1

Type RM Length L Ch R = 1 ,975     ,439,439,439
BEGIN DESCRIPTION:
Elizabeth Creek Tributary 13 2.0
END DESCRIPTION:
XS GIS Cut Line= 3
      2326778.97        7053860.        2327129.        7053860.
      2327228.97        7053860.
#Sta/Elev= 30
  4654.5  671.83  4684.5  669.67  4704.5  667.26  4724.5  663.73  4734.5  659.87
  4744.5  658.25  4774.5  658.54  4794.5  658.02  4804.5  658.49  4824.5  658.11
  4844.5   657.2  4854.5  658.59  4874.5   659.2  4944.5  656.86  4964.5  656.87
  4974.5  655.54  4984.5  652.96  4992.3  652.14  4992.7  651.64  4996.3  651.64
  4996.7  652.14    5002  655.71    5007  655.71  5011.8  658.48  5014.5  660.04
  5048.8  667.41  5054.5  668.96  5064.5  672.45  5074.5   673.5  5104.5  674.93
#Mann= 5 ,-1 , 0
  4654.5     .05       0  4992.3     .07       0  4996.7     .05       0
  5011.8     .12       0  5048.8     .05       0
Bank Sta=4992.3,4996.7
XS Rating Curve= 0 ,0
Exp/Cntr=0.3,0.1

Type RM Length L Ch R = 1 ,536     ,383,383,383
BEGIN DESCRIPTION:
Elizabeth Creek Tributary 13 1.0
END DESCRIPTION:
XS GIS Cut Line= 3
      2326878.96      7054109.99        2327279.        7054210.
      2327679.03      7053859.97
#Sta/Elev= 30
  4572.8  665.02  4678.5  659.17  4864.4  654.69    4962  653.05  4988.5   648.6
    4990  646.91  4990.5  646.41  4994.5  646.91  5041.6   647.3  5049.2  649.82
  5055.9  648.57  5063.5  653.45  5070.1  652.39  5077.7  654.89  5084.3  653.25
  5098.6  655.76  5268.5   661.2  5311.2  660.11  5368.1  661.59  5396.6  663.59
  5403.2  666.26  5417.5  665.66  5424.1  668.32  5431.7  667.86  5445.9  670.51
  5452.6  673.48  5488.7  674.62  5495.3  677.07  5509.5   678.1  5516.7  677.25
#Mann= 4 ,-1 , 0
  4572.8     .05       0  4864.4     .12       0    4990     .07       0
  4994.5     .12       0
Bank Sta=4990,4994.5
XS Rating Curve= 0 ,0
Exp/Cntr=0.3,0.1

Type RM Length L Ch R = 1 ,153     ,0,0,0
BEGIN DESCRIPTION:
1024
END DESCRIPTION:
XS GIS Cut Line= 3
      2326661.19      7054307.88      2327428.33      7054529.71
      2327769.62      7054003.93
#Sta/Elev= 30
  4111.8  673.71  4208.9  671.14  4276.1  666.23  4297.4  662.99  4320.2  659.12
  4348.6  657.27  4638.3  655.36  4710.8  653.02  4900.7  655.12  4960.6  654.45
  4969.6  653.24  4975.7  650.21  4981.7   650.4  4990.9  648.66  5005.4  647.94
  5015.7  642.91  5016.1  642.41  5020.2  642.91  5027.1  642.98  5033.1  644.12
  5048.2  648.74  5063.4  651.22  5087.8  651.64  5135.9  652.57  5141.8  651.83
    5157  652.94  5208.1  653.93  5446.5  653.16  5482.3  653.52  5537.2  655.94
#Mann= 6 ,-1 , 0
  4111.8     .05       0  4297.4     .12       0  4638.3     .05       0
  5015.7    .033       0  5020.2     .05       0  5087.8     .12       0
Bank Sta=5015.7,5020.2
XS Rating Curve= 0 ,0
Exp/Cntr=0.3,0.1

Chan Stop Cuts=-1
Use User Specified Reach Order=0
Composite Channel Slope=5