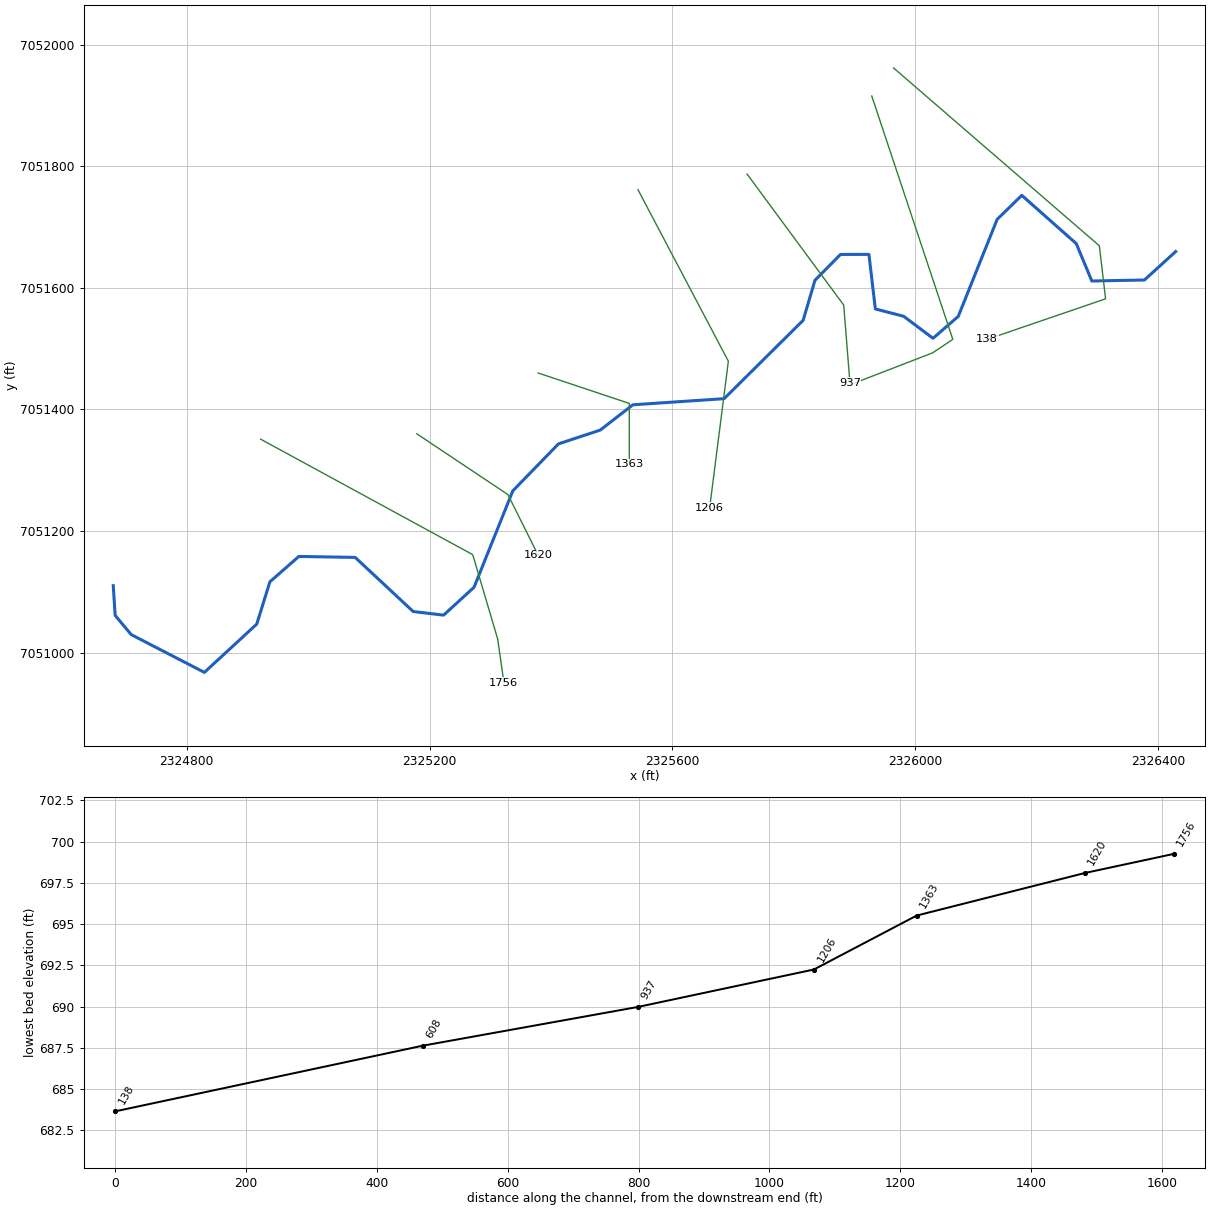
--- Elizabeth Cr Tr 13_1.prj (project) ---

Proj Title=Elizabeth Cr Tr 13_1 Base Level Engineering
Current Plan=p01
Default Exp/Contr=0.3,0.1
English Units
Geom File=g01
Flow File=f01
Plan File=p01
BEGIN DESCRIPTION:
Elizabeth Cr Tr 13_1
END DESCRIPTION:

--- Elizabeth Cr Tr 13_1.p01 (plan) ---

Plan Title=Multiple Run
Short Identifier=Multiple
Geom File=g01
Flow File=f01
Subcritical Flow
K Sum by GR= 0
Std Step Tol= 0.01
Critical Tol= 0.01
Num of Std Step Trials= 20
Max Error Tol= 0.3
Flow Tol Ratio= 0.001
Split Flow NTrial= 30
Split Flow Tol= 0.02
Split Flow Ratio= 0.02
Log Output Level= 0
Friction Slope Method= 1
Unsteady Friction Slope Method= 2
Unsteady Bridges Friction Slope Method= 1
Parabolic Critical Depth
Global Vel Dist=  1 , 1 , 1
Global Log Level= 0
CheckData=True
Encroach Param= -1, 0, 0, 0
BEGIN DESCRIPTION:
Multiple Run
END DESCRIPTION:

--- Elizabeth Cr Tr 13_1.f01 (steady flow) ---

Flow Title=Multiple
Number of Profiles=7
Profile Names=10-year,25-year,50-year,1pct_min,100-year,1pct_plu,500-year
River Rch & RM= Elizabeth Cr Tr ,Reach-1,1756
     268     347     408     239     478     953     653
Boundary for River Rch & Prof#=Elizabeth Cr Tr ,Reach-1,1
Up Type=0
Dn Type=3
Dn Slope=0.005
Boundary for River Rch & Prof#=Elizabeth Cr Tr ,Reach-1,2
Up Type=0
Dn Type=3
Dn Slope=0.005
Boundary for River Rch & Prof#=Elizabeth Cr Tr ,Reach-1,3
Up Type=0
Dn Type=3
Dn Slope=0.005
Boundary for River Rch & Prof#=Elizabeth Cr Tr ,Reach-1,4
Up Type=0
Dn Type=3
Dn Slope=0.005
Boundary for River Rch & Prof#=Elizabeth Cr Tr ,Reach-1,5
Up Type=0
Dn Type=3
Dn Slope=0.005
Boundary for River Rch & Prof#=Elizabeth Cr Tr ,Reach-1,6
Up Type=0
Dn Type=3
Dn Slope=0.005
Boundary for River Rch & Prof#=Elizabeth Cr Tr ,Reach-1,7
Up Type=0
Dn Type=3
Dn Slope=0.005

--- Elizabeth Cr Tr 13_1.g01 (geometry) ---

Geom Title=Existing Conditions

River Reach=Elizabeth Cr Tr ,Reach-1
Reach XY= 30
      2324679.00      7051110.00      2324682.14      7051061.03
      2324708.53      7051029.49      2324829.10      7050967.28
      2324915.36      7051046.75      2324937.02      7051116.38
      2324984.71      7051158.12      2325077.50      7051156.53
      2325172.98      7051067.47      2325223.13      7051061.50
      2325273.27      7051107.38      2325337.13      7051266.07
      2325412.29      7051343.37      2325481.17      7051366.14
      2325534.93      7051407.75      2325685.19      7051417.82
      2325815.37      7051546.80      2325834.79      7051612.63
      2325876.85      7051655.19      2325923.68      7051655.35
      2325934.29      7051565.50      2325980.92      7051553.41
      2326029.27      7051517.18      2326070.86      7051553.30
      2326134.83      7051712.87      2326175.43      7051752.52
      2326265.26      7051673.01      2326290.83      7051611.49
      2326377.50      7051613.14      2326429.00      7051660.00

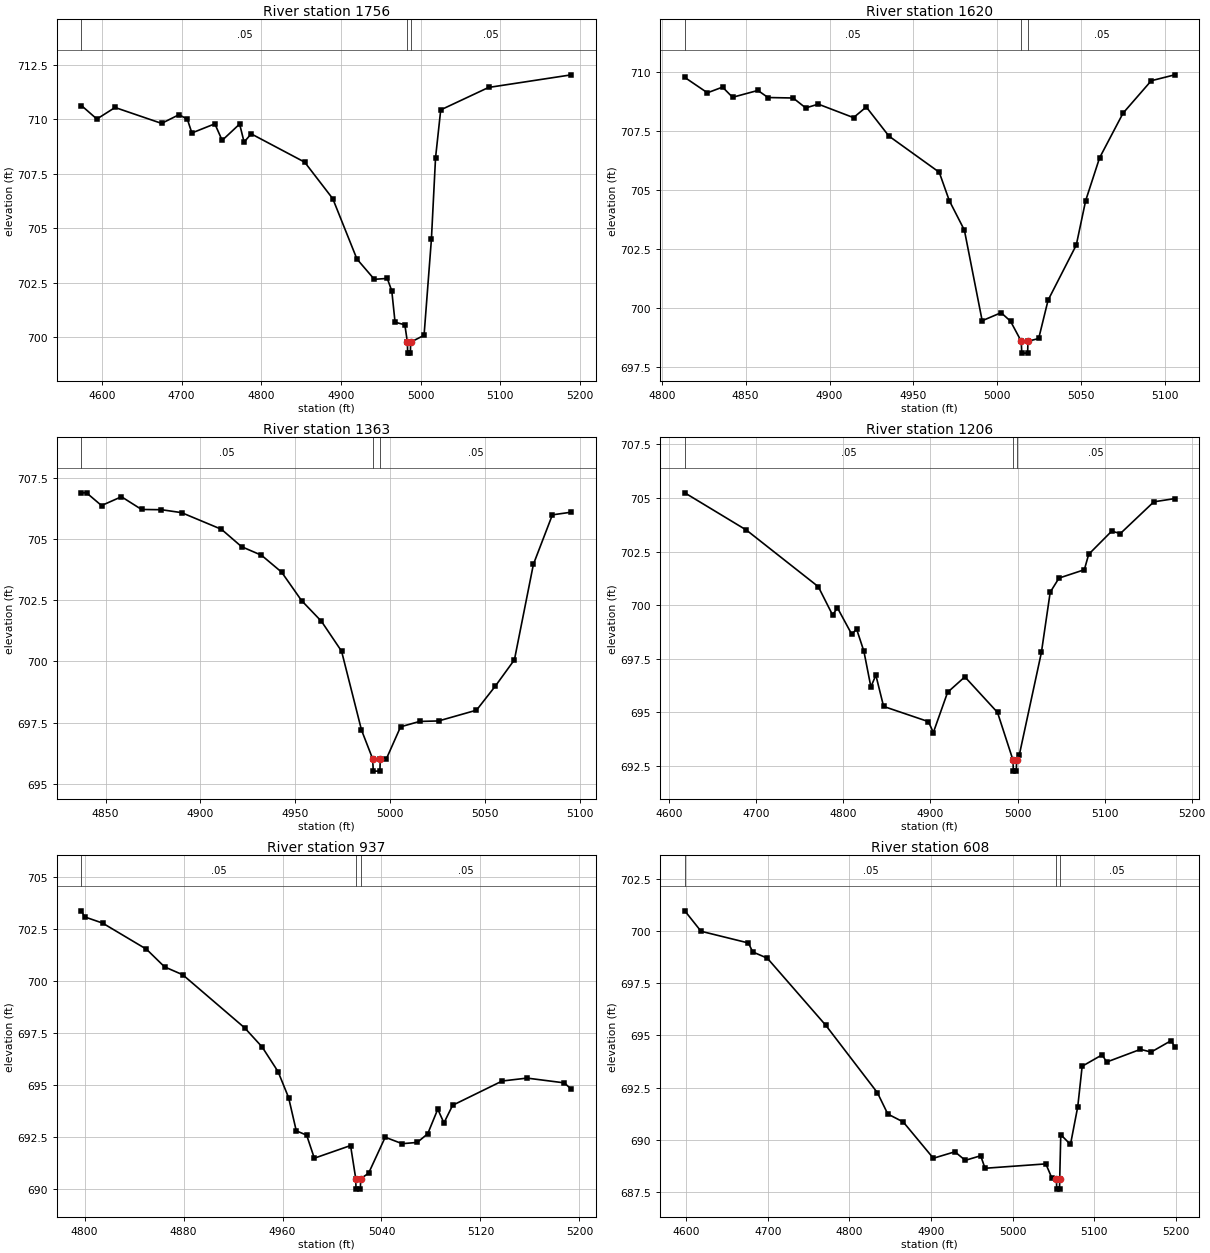
Type RM Length L Ch R = 1,1756,136,136,136
BEGIN DESCRIPTION:
1025
END DESCRIPTION:
XS GIS Cut Line= 4
      2324921.92      7051351.07      2325271.08      7051161.09
      2325312.16      7051022.44      2325322.43      7050950.58
#Sta/Elev= 30
  4574.4  710.63  4593.8  710.01  4616.6  710.54  4675.0  709.81  4696.9  710.21
  4707.3  710.00  4713.0  709.37  4741.8  709.79  4751.0  709.03  4772.9  709.78
  4778.5  708.95  4787.4  709.33  4854.5  708.03  4889.8  706.35  4920.1  703.58
  4941.9  702.65  4958.1  702.69  4963.8  702.12  4967.9  700.68  4980.2  700.56
  4983.4  699.76  4983.7  699.26  4987.2  699.26  4987.4  699.76  5004.3  700.08
  5013.5  704.48  5018.7  708.23  5025.2  710.43  5085.2  711.46  5189.1  712.04
#Mann=3,-1,0
  4574.4    0.05       0  4983.4   0.033       0  4987.4    0.05       0
Bank Sta=4983.4,4987.4
Exp/Cntr=0.3,0.1

Type RM Length L Ch R = 1,1620,257,257,257
BEGIN DESCRIPTION:
Elizabeth Creek Tributary 13_1 2.0
END DESCRIPTION:
XS GIS Cut Line= 3
      2325179.01      7051359.99      2325329.00      7051260.00
      2325379.02      7051159.97
#Sta/Elev= 30
  4813.7  709.76  4827.2  709.11  4836.2  709.35  4842.2  708.92  4857.3  709.21
  4863.3  708.91  4878.3  708.89  4885.8  708.47  4893.3  708.63  4914.3  708.06
  4921.9  708.51  4935.4  707.28  4965.4  705.75  4971.4  704.55  4980.4  703.30
  4991.0  699.47  5002.3  699.81  5007.9  699.45  5014.3  698.60  5014.6  698.10
  5018.1  698.10  5018.3  698.60  5024.7  698.72  5030.3  700.34  5047.1  702.67
  5052.7  704.55  5061.0  706.36  5075.0  708.25  5091.8  709.62  5105.8  709.87
#Mann=3,-1,0
  4813.7    0.05       0  5014.3   0.033       0  5018.3    0.05       0
Bank Sta=5014.3,5018.3
Exp/Cntr=0.3,0.1

Type RM Length L Ch R = 1,1363,157,157,157
BEGIN DESCRIPTION:
Elizabeth Creek Tributary 13_1 1.0
END DESCRIPTION:
XS GIS Cut Line= 3
      2325378.95      7051460.02      2325529.00      7051410.00
      2325529.00      7051309.96
#Sta/Elev= 29
  4837.3  706.89  4840.0  706.89  4847.9  706.37  4858.4  706.73  4869.0  706.21
  4879.5  706.20  4890.1  706.08  4911.1  705.40  4921.7  704.69  4932.2  704.34
  4942.8  703.65  4953.3  702.49  4963.8  701.64  4974.4  700.42  4984.9  697.20
  4990.8  696.02  4991.1  695.52  4994.6  695.52  4994.8  696.02  4998.0  696.02
  5005.5  697.33  5015.5  697.55  5025.5  697.57  5045.5  698.01  5055.5  699.00
  5065.5  700.07  5075.5  703.97  5085.5  705.99  5095.5  706.10
#Mann=3,-1,0
  4837.3    0.05       0  4990.8   0.033       0  4994.8    0.05       0
Bank Sta=4990.8,4994.8
Exp/Cntr=0.3,0.1

Type RM Length L Ch R = 1,1206,269,269,269
BEGIN DESCRIPTION:
1029
END DESCRIPTION:
XS GIS Cut Line= 3
      2325543.22      7051761.93      2325692.16      7051479.46
      2325661.35      7051238.15
#Sta/Elev= 30
  4617.9  705.24  4688.7  703.50  4771.2  700.86  4787.6  699.54  4793.2  699.87
  4809.6  698.64  4815.2  698.88  4823.6  697.84  4831.6  696.18  4837.3  696.73
  4846.2  695.27  4897.7  694.56  4903.3  694.05  4919.7  695.93  4939.5  696.65
  4977.0  694.99  4994.9  692.75  4995.1  692.25  4998.6  692.25  4998.9  692.75
  5001.9  692.98  5027.4  697.79  5037.5  700.60  5047.6  701.26  5076.7  701.65
  5081.7  702.37  5108.1  703.45  5118.1  703.34  5156.5  704.82  5180.5  704.97
#Mann=3,-1,0
  4617.9    0.05       0  4994.9   0.033       0  4998.9    0.05       0
Bank Sta=4994.9,4998.9
Exp/Cntr=0.3,0.1

Type RM Length L Ch R = 1,937,329,329,329
BEGIN DESCRIPTION:
1028
END DESCRIPTION:
XS GIS Cut Line= 3
      2325722.96      7051787.58      2325882.16      7051571.89
      2325892.37      7051444.27
#Sta/Elev= 30
  4797.4  703.39  4799.9  703.10  4814.5  702.80  4850.0  701.54  4864.6  700.69
  4879.3  700.31  4929.4  697.75  4943.5  696.83  4956.4  695.64  4964.9  694.39
  4971.1  692.79  4979.5  692.58  4985.7  691.47  5015.0  692.08  5019.2  690.48
  5019.4  689.98  5022.9  689.98  5023.2  690.48  5029.6  690.75  5043.0  692.48
  5056.7  692.17  5068.9  692.23  5077.4  692.65  5085.5  693.83  5090.5  693.17
  5097.5  694.02  5137.6  695.19  5157.7  695.33  5187.8  695.10  5193.5  694.79
#Mann=3,-1,0
  4797.4    0.05       0  5019.2   0.033       0  5023.2    0.05       0
Bank Sta=5019.2,5023.2
Exp/Cntr=0.3,0.1

Type RM Length L Ch R = 1,608,470,470,470
BEGIN DESCRIPTION:
1027
END DESCRIPTION:
XS GIS Cut Line= 4
      2325928.38      7051915.93      2326061.88      7051515.41
      2326028.61      7051493.22      2325899.86      7051443.49
#Sta/Elev= 30
  4598.4  700.97  4618.3  699.99  4676.3  699.43  4681.6  699.00  4699.5  698.70
  4771.2  695.48  4834.4  692.25  4847.1  691.23  4866.0  690.85  4902.9  689.11
  4929.3  689.42  4942.0  689.01  4960.9  689.23  4966.2  688.63  5040.7  688.84
  5048.1  688.16  5053.7  688.13  5054.0  687.63  5057.5  687.63  5057.7  688.13
  5059.0  690.24  5070.9  689.77  5079.8  691.58  5085.2  693.52  5109.8  694.07
  5115.1  693.72  5156.6  694.33  5169.7  694.20  5194.3  694.75  5198.6  694.44
#Mann=3,-1,0
  4598.4    0.05       0  5053.7   0.033       0  5057.7    0.05       0
Bank Sta=5053.7,5057.7
Exp/Cntr=0.3,0.1

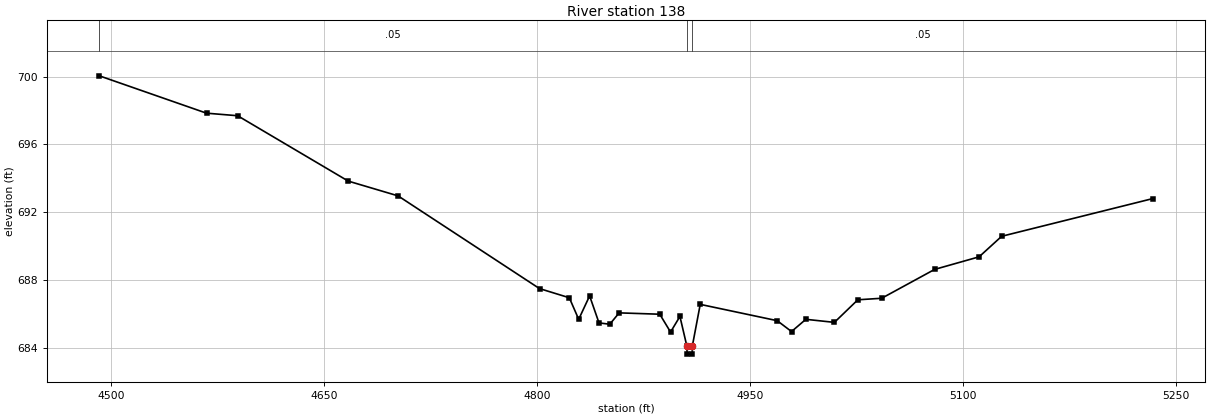
Type RM Length L Ch R = 1,138,0,0,0
BEGIN DESCRIPTION:
1026
END DESCRIPTION:
XS GIS Cut Line= 4
      2325964.35      7051962.13      2326303.23      7051669.46
      2326313.50      7051582.16      2326118.37      7051515.41
#Sta/Elev= 30
  4491.5  700.04  4567.0  697.84  4588.9  697.69  4666.8  693.84  4701.9  692.97
  4801.5  687.51  4822.5  686.97  4829.1  685.70  4836.8  687.08  4843.4  685.49
  4851.0  685.41  4857.6  686.08  4886.2  686.00  4893.8  684.95  4900.4  685.87
  4905.2  684.15  4905.5  683.65  4909.0  683.65  4909.2  684.15  4914.7  686.58
  4968.9  685.62  4979.0  684.98  4989.1  685.70  5009.2  685.52  5025.7  686.85
  5042.5  686.94  5079.8  688.64  5111.1  689.38  5127.0  690.59  5233.4  692.81
#Mann=3,-1,0
  4491.5    0.05       0  4905.2   0.033       0  4909.2    0.05       0
Bank Sta=4905.2,4909.2
Exp/Cntr=0.3,0.1

Chan Stop Cuts=-1