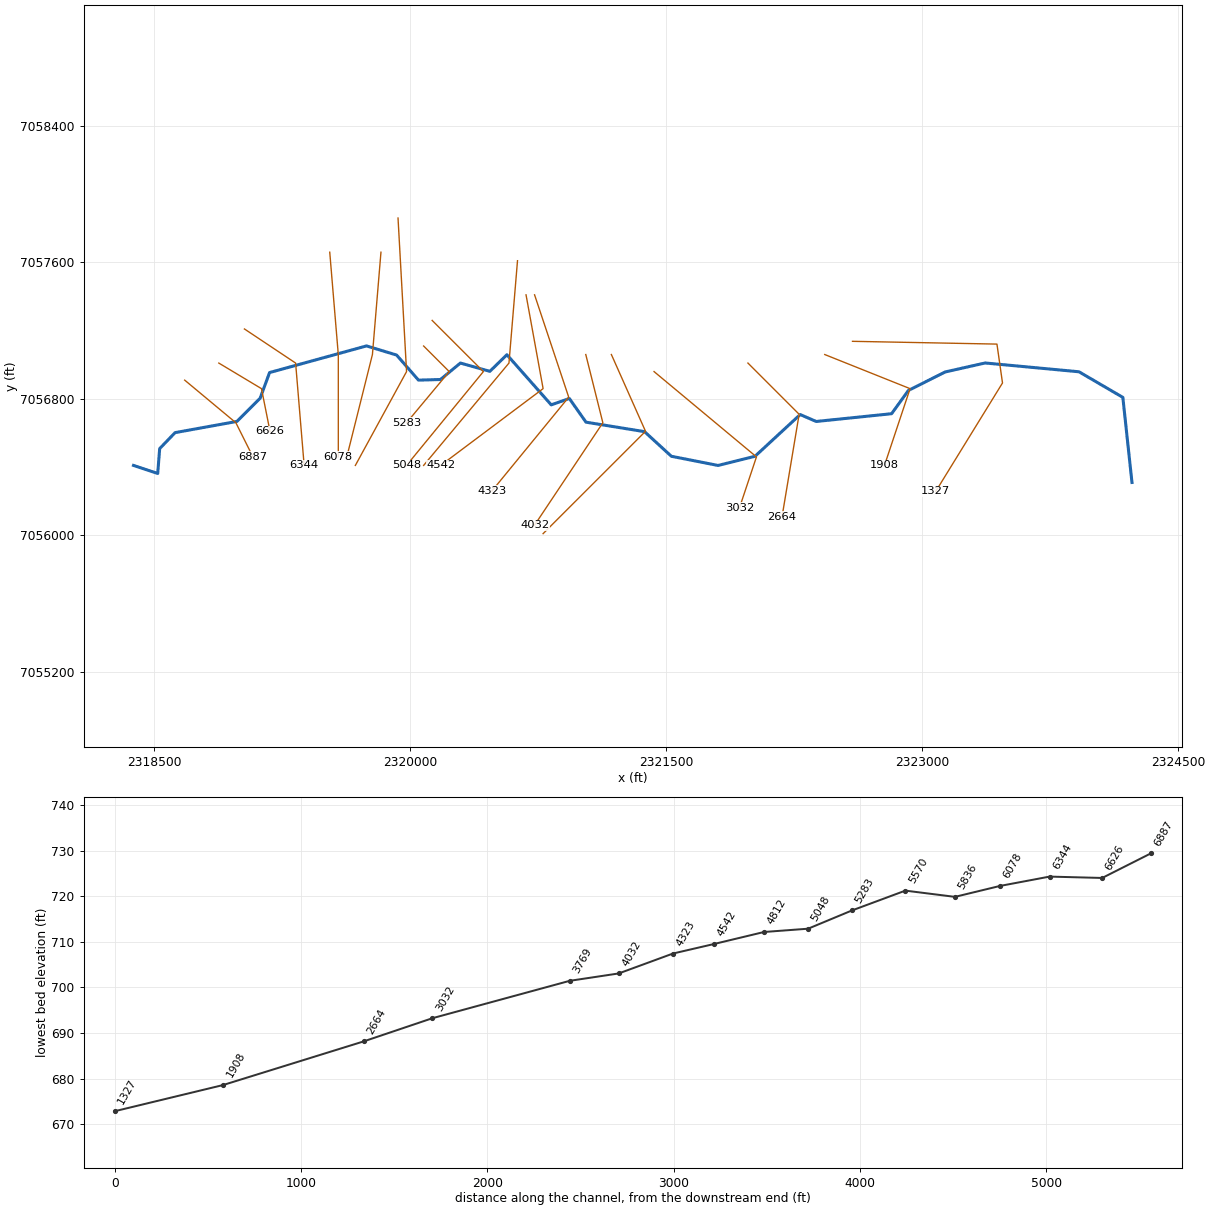
--- Elizabeth Cr Tr 14_1.prj (project) ---

Proj Title=Elizabeth Cr Tr 14_1 Base Level Engineering
Current Plan=p01
Default Exp/Contr=0.3,0.1
English Units
Geom File=g01
Flow File=f01
Plan File=p01
BEGIN DESCRIPTION:
Elizabeth Cr Tr 14_1
END DESCRIPTION:

--- Elizabeth Cr Tr 14_1.p01 (plan) ---

Plan Title=Multiple Run
Short Identifier=Multiple
Geom File=g01
Flow File=f01
Subcritical Flow
K Sum by GR= 0
Std Step Tol= 0.01
Critical Tol= 0.01
Num of Std Step Trials= 20
Max Error Tol= 0.3
Flow Tol Ratio= 0.001
Split Flow NTrial= 30
Split Flow Tol= 0.02
Split Flow Ratio= 0.02
Log Output Level= 0
Friction Slope Method= 1
Unsteady Friction Slope Method= 2
Unsteady Bridges Friction Slope Method= 1
Parabolic Critical Depth
Global Vel Dist=  1 , 1 , 1
Global Log Level= 0
CheckData=True
Encroach Param= -1, 0, 0, 0
BEGIN DESCRIPTION:
Multiple Run
END DESCRIPTION:

--- Elizabeth Cr Tr 14_1.f01 (steady flow) ---

Flow Title=Multiple
Number of Profiles=7
Profile Names=10-year,25-year,50-year,1pct_min,100-year,1pct_plu,500-year
River Rch & RM= Elizabeth Cr Tr ,Reach-1,6887
     370     493     592     353     705    1410    1000
River Rch & RM= Elizabeth Cr Tr ,Reach-1,3032
     426     572     690     415     827    1650    1190
Boundary for River Rch & Prof#=Elizabeth Cr Tr ,Reach-1,1
Up Type=0
Dn Type=3
Dn Slope=0.005
Boundary for River Rch & Prof#=Elizabeth Cr Tr ,Reach-1,2
Up Type=0
Dn Type=3
Dn Slope=0.005
Boundary for River Rch & Prof#=Elizabeth Cr Tr ,Reach-1,3
Up Type=0
Dn Type=3
Dn Slope=0.005
Boundary for River Rch & Prof#=Elizabeth Cr Tr ,Reach-1,4
Up Type=0
Dn Type=3
Dn Slope=0.005
Boundary for River Rch & Prof#=Elizabeth Cr Tr ,Reach-1,5
Up Type=0
Dn Type=3
Dn Slope=0.005
Boundary for River Rch & Prof#=Elizabeth Cr Tr ,Reach-1,6
Up Type=0
Dn Type=3
Dn Slope=0.005
Boundary for River Rch & Prof#=Elizabeth Cr Tr ,Reach-1,7
Up Type=0
Dn Type=3
Dn Slope=0.005

--- Elizabeth Cr Tr 14_1.g01 (geometry) ---

Geom Title=Existing Conditions

River Reach=Elizabeth Cr Tr ,Reach-1
Reach XY= 30
      2318379.00      7056410.00      2318521.09      7056362.79
      2318532.54      7056508.54      2318622.79      7056602.20
      2318985.17      7056667.86      2319121.14      7056803.83
      2319176.42      7056954.29      2319744.47      7057110.53
      2319920.69      7057056.92      2320048.99      7056909.94
      2320177.53      7056913.54      2320294.34      7057010.04
      2320467.12      7056961.53      2320566.92      7057058.89
      2320826.47      7056765.01      2320932.65      7056802.28
      2321030.25      7056663.46      2321373.14      7056607.93
      2321530.46      7056463.54      2321803.93      7056409.77
      2322020.52      7056463.51      2322285.12      7056708.16
      2322378.99      7056667.59      2322820.70      7056713.07
      2322919.19      7056849.49      2323134.86      7056957.92
      2323368.81      7057010.45      2323918.56      7056958.94
      2324175.55      7056808.77      2324229.00      7056310.00

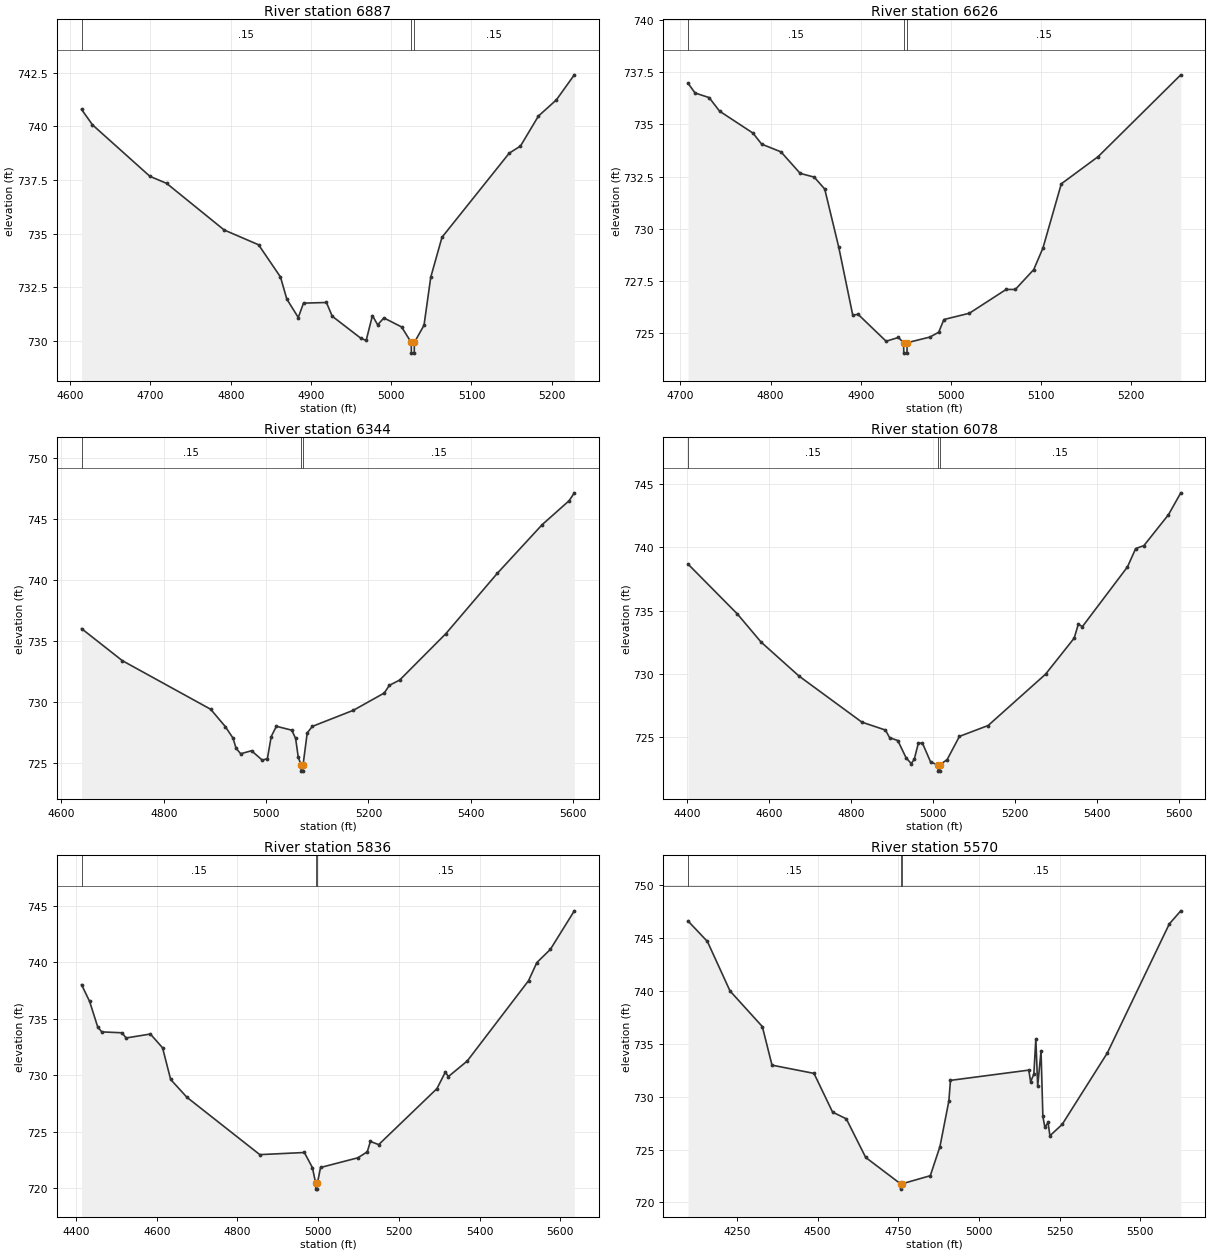
Type RM Length L Ch R = 1,6887,261,261,261
BEGIN DESCRIPTION:
Elizabeth Creek Tributary 14_1 16.0
END DESCRIPTION:
XS GIS Cut Line= 3
      2318679.02      7056909.98      2318979.00      7056660.00
      2319079.00      7056459.99
#Sta/Elev= 30
  4614.1  740.79  4627.7  740.07  4699.3  737.67  4720.2  737.34  4791.8  735.17
  4834.7  734.48  4862.0  732.98  4869.9  731.95  4884.2  731.09  4890.7  731.76
  4919.3  731.79  4926.5  731.15  4962.3  730.12  4968.8  730.02  4976.6  731.18
  4983.1  730.75  4990.9  731.07  5013.0  730.65  5024.9  729.93  5025.2  729.43
  5028.7  729.43  5028.9  729.93  5040.9  730.73  5049.3  732.97  5063.3  734.83
  5147.1  738.75  5161.1  739.08  5183.5  740.48  5205.8  741.23  5228.2  742.40
#Mann=3,-1,0
  4614.1    0.15       0  5024.9    0.05       0  5028.9    0.15       0
Bank Sta=5024.9,5028.9
Exp/Cntr=0.3,0.1

Type RM Length L Ch R = 1,6626,282,282,282
BEGIN DESCRIPTION:
Elizabeth Creek Tributary 14_1 15.0
END DESCRIPTION:
XS GIS Cut Line= 3
      2318878.97      7057010.02      2319129.00      7056860.00
      2319178.99      7056610.04
#Sta/Elev= 30
  4708.4  736.97  4716.2  736.50  4731.8  736.28  4743.4  735.63  4780.4  734.58
  4790.1  734.05  4811.5  733.68  4832.8  732.65  4848.4  732.47  4860.0  731.90
  4875.6  729.11  4891.1  725.86  4897.0  725.90  4928.1  724.61  4941.7  724.79
  4947.5  724.54  4947.7  724.04  4951.2  724.04  4951.5  724.54  4976.7  724.81
  4986.4  725.04  4992.2  725.65  5020.4  725.95  5061.2  727.09  5071.4  727.09
  5091.8  728.04  5102.0  729.07  5122.4  732.15  5163.2  733.45  5254.9  737.37
#Mann=3,-1,0
  4708.4    0.15       0  4947.5    0.05       0  4951.5    0.15       0
Bank Sta=4947.5,4951.5
Exp/Cntr=0.3,0.1

Type RM Length L Ch R = 1,6344,266,266,266
BEGIN DESCRIPTION:
Elizabeth Creek Tributary 14_1 14.0
END DESCRIPTION:
XS GIS Cut Line= 3
      2319029.04      7057209.97      2319329.00      7057010.00
      2319379.00      7056409.99
#Sta/Elev= 30
  4639.5  736.00  4719.1  733.38  4891.8  729.40  4920.4  727.98  4935.4  727.04
  4941.4  726.21  4950.4  725.76  4971.5  726.01  4992.5  725.24  5002.5  725.36
  5010.0  727.17  5020.1  728.01  5050.2  727.69  5057.7  727.01  5062.7  725.52
  5068.2  724.84  5068.5  724.34  5072.0  724.34  5072.2  724.84  5080.3  727.46
  5090.3  728.00  5170.6  729.32  5230.8  730.73  5240.8  731.36  5260.9  731.79
  5351.2  735.59  5451.6  740.52  5539.4  744.51  5592.1  746.47  5602.1  747.11
#Mann=3,-1,0
  4639.5    0.15       0  5068.2    0.05       0  5072.2    0.15       0
Bank Sta=5068.2,5072.2
Exp/Cntr=0.3,0.1

Type RM Length L Ch R = 1,6078,242,242,242
BEGIN DESCRIPTION:
Elizabeth Creek Tributary 14_1 13.0
END DESCRIPTION:
XS GIS Cut Line= 3
      2319529.00      7057660.03      2319579.00      7057060.00
      2319579.00      7056460.01
#Sta/Elev= 30
  4402.3  738.68  4522.7  734.73  4580.4  732.51  4673.3  729.81  4826.3  726.17
  4884.0  725.54  4894.0  724.94  4914.1  724.71  4934.2  723.35  4946.7  722.89
  4954.2  723.22  4964.3  724.52  4974.3  724.50  4994.4  722.99  5012.4  722.79
  5012.7  722.29  5016.2  722.29  5016.4  722.79  5034.4  723.20  5064.4  725.04
  5134.4  725.90  5274.4  729.96  5344.4  732.82  5354.4  733.92  5364.4  733.73
  5474.4  738.46  5494.4  739.91  5514.4  740.14  5574.4  742.59  5604.4  744.32
#Mann=3,-1,0
  4402.3    0.15       0  5012.4    0.05       0  5016.4    0.15       0
Bank Sta=5012.4,5016.4
Exp/Cntr=0.3,0.1

Type RM Length L Ch R = 1,5836,266,266,266
BEGIN DESCRIPTION:
Elizabeth Creek Tributary 14_1 12.0
END DESCRIPTION:
XS GIS Cut Line= 3
      2319829.00      7057659.96      2319779.00      7057060.00
      2319629.00      7056460.00
#Sta/Elev= 30
  4413.9  738.03  4433.9  736.54  4454.0  734.27  4464.0  733.84  4514.2  733.76
  4524.2  733.30  4584.4  733.65  4614.5  732.43  4634.6  729.62  4674.8  728.04
  4855.4  722.95  4965.8  723.14  4985.8  721.79  4993.9  720.39  4994.1  719.89
  4997.6  719.89  4997.9  720.39  5005.9  721.81  5098.4  722.67  5121.6  723.20
  5129.3  724.12  5149.9  723.84  5294.2  728.81  5314.9  730.27  5322.6  729.88
  5369.0  731.25  5521.0  738.38  5541.6  739.99  5575.1  741.16  5634.4  744.58
#Mann=3,-1,0
  4413.9    0.15       0  4993.9    0.05       0  4997.9    0.15       0
Bank Sta=4993.9,4997.9
Exp/Cntr=0.3,0.1

Type RM Length L Ch R = 1,5570,287,287,287
BEGIN DESCRIPTION:
Elizabeth Creek Tributary 14_1 11.0
END DESCRIPTION:
XS GIS Cut Line= 3
      2319929.00      7057860.04      2319979.00      7056960.00
      2319679.01      7056410.03
#Sta/Elev= 30
  4098.1  746.63  4158.2  744.69  4228.3  740.01  4328.5  736.64  4358.5  732.99
  4488.7  732.21  4546.3  728.55  4588.9  727.91  4649.0  724.26  4757.2  721.76
  4757.4  721.26  4761.2  721.76  4849.3  722.53  4879.3  725.29  4906.9  729.60
  4911.9  731.55  5154.7  732.52  5160.4  731.42  5170.4  732.14  5176.6  735.49
  5182.3  731.02  5192.7  734.32  5198.4  728.14  5204.6  727.11  5214.5  727.57
  5220.2  726.31  5258.2  727.38  5398.2  734.14  5590.4  746.35  5626.0  747.59
#Mann=3,-1,0
  4098.1    0.15       0  4757.2    0.05       0  4761.2    0.15       0
Bank Sta=4757.2,4761.2
Exp/Cntr=0.3,0.1

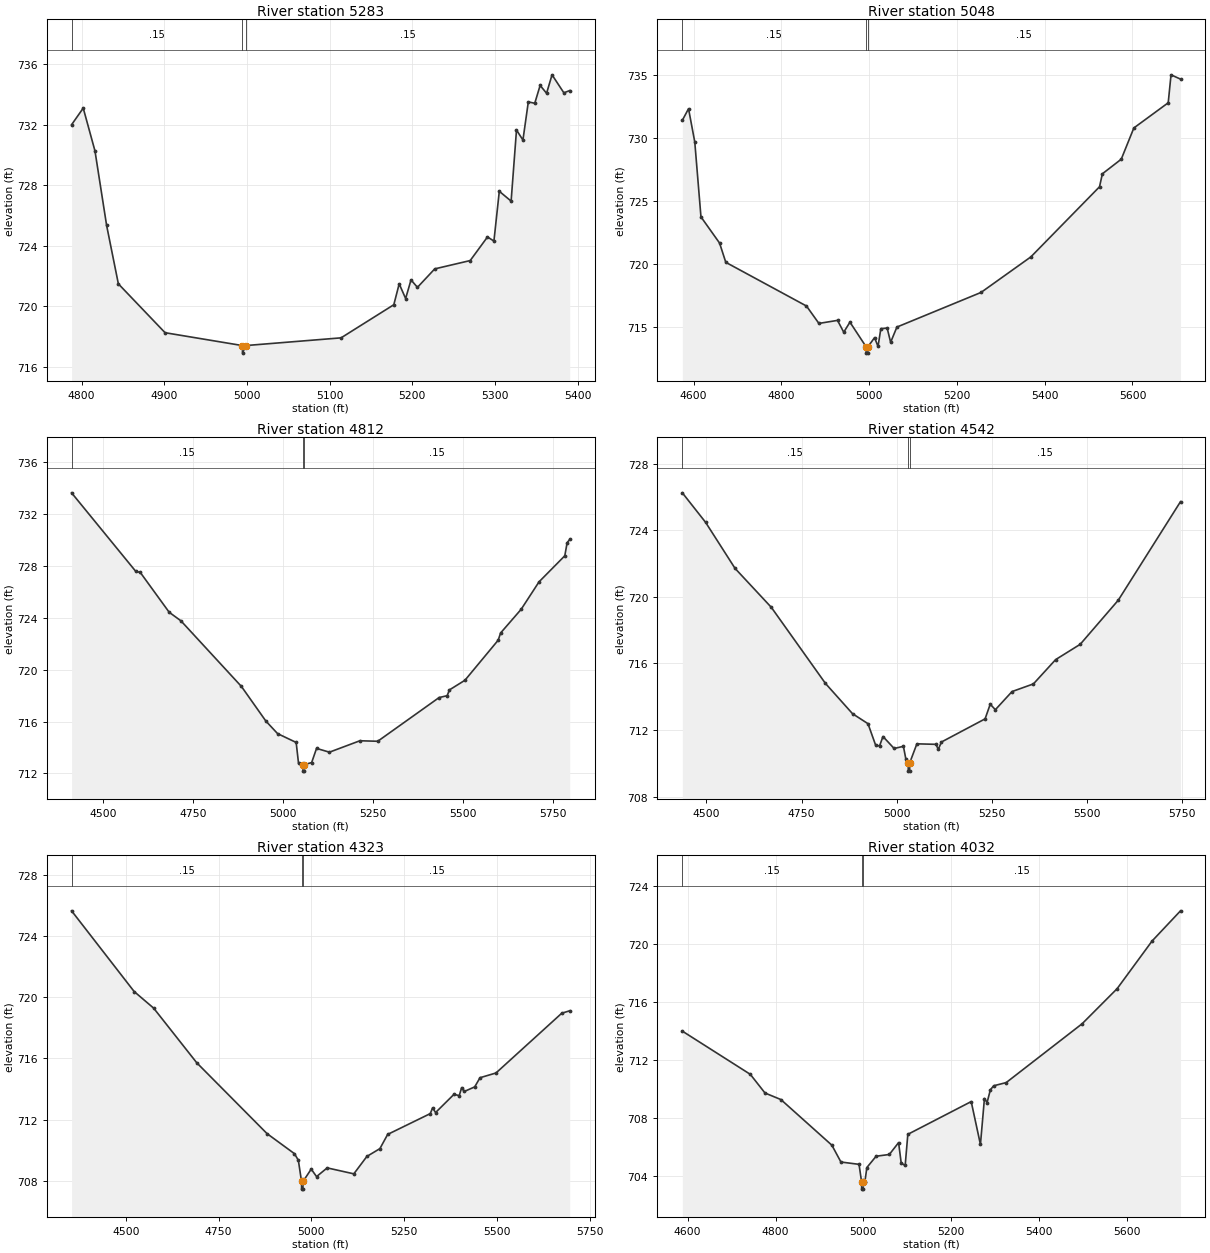
Type RM Length L Ch R = 1,5283,235,235,235
BEGIN DESCRIPTION:
Elizabeth Creek Tributary 14_1 10.0
END DESCRIPTION:
XS GIS Cut Line= 3
      2320079.01      7057109.99      2320229.00      7056960.00
      2319979.02      7056660.03
#Sta/Elev= 30
  4787.9  732.00  4802.0  733.10  4816.2  730.27  4830.3  725.34  4844.5  721.48
  4901.0  718.25  4994.5  717.40  4994.7  716.90  4998.5  717.40  5113.9  717.91
  5177.7  720.10  5184.2  721.48  5192.0  720.51  5198.5  721.74  5206.3  721.25
  5227.2  722.47  5270.1  723.02  5291.0  724.58  5298.8  724.31  5305.3  727.60
  5319.6  726.95  5326.1  731.65  5333.9  730.99  5340.4  733.51  5348.2  733.42
  5354.7  734.60  5362.5  734.08  5369.1  735.30  5383.4  734.11  5390.5  734.26
#Mann=3,-1,0
  4787.9    0.15       0  4994.5    0.05       0  4998.5    0.15       0
Bank Sta=4994.5,4998.5
Exp/Cntr=0.3,0.1

Type RM Length L Ch R = 1,5048,236,236,236
BEGIN DESCRIPTION:
Elizabeth Creek Tributary 14_1 9.0
END DESCRIPTION:
XS GIS Cut Line= 3
      2320129.02      7057259.98      2320429.00      7056960.00
      2319978.98      7056409.98
#Sta/Elev= 30
  4574.5  731.39  4588.6  732.31  4602.8  729.67  4616.9  723.72  4659.3  721.64
  4673.5  720.11  4857.3  716.64  4885.6  715.26  4928.0  715.50  4942.2  714.56
  4956.3  715.36  4993.2  713.40  4993.5  712.90  4997.0  712.90  4997.2  713.40
  5012.4  714.13  5020.3  713.43  5026.7  714.84  5041.1  714.89  5049.0  713.76
  5063.3  714.97  5255.0  717.72  5368.4  720.54  5524.9  726.11  5531.4  727.14
  5574.4  728.30  5603.1  730.78  5681.4  732.78  5687.8  735.00  5709.4  734.66
#Mann=3,-1,0
  4574.5    0.15       0  4993.2    0.05       0  4997.2    0.15       0
Bank Sta=4993.2,4997.2
Exp/Cntr=0.3,0.1

Type RM Length L Ch R = 1,4812,270,270,270
BEGIN DESCRIPTION:
Elizabeth Creek Tributary 14_1 8.0
END DESCRIPTION:
XS GIS Cut Line= 3
      2320629.00      7057610.05      2320579.00      7057010.00
      2320078.97      7056409.96
#Sta/Elev= 30
  4412.5  733.62  4590.7  727.57  4603.2  727.49  4683.5  724.42  4716.1  723.76
  4884.2  718.70  4951.9  716.04  4984.5  715.07  5036.1  714.39  5042.6  712.80
  5054.9  712.68  5055.2  712.18  5058.7  712.18  5058.9  712.68  5079.1  712.84
  5092.7  713.93  5128.5  713.64  5213.1  714.52  5262.6  714.48  5433.1  717.85
  5455.3  717.99  5461.8  718.44  5504.7  719.18  5597.1  722.27  5603.7  722.82
  5660.9  724.65  5710.4  726.76  5782.0  728.77  5788.5  729.78  5795.7  730.03
#Mann=3,-1,0
  4412.5    0.15       0  5054.9    0.05       0  5058.9    0.15       0
Bank Sta=5054.9,5058.9
Exp/Cntr=0.3,0.1

Type RM Length L Ch R = 1,4542,219,219,219
BEGIN DESCRIPTION:
Elizabeth Creek Tributary 14_1 7.0
END DESCRIPTION:
XS GIS Cut Line= 3
      2320679.00      7057409.98      2320779.00      7056860.00
      2320179.00      7056410.00
#Sta/Elev= 30
  4436.6  726.25  4497.6  724.48  4575.1  721.71  4670.4  719.37  4812.6  714.80
  4883.8  712.98  4924.4  712.38  4944.8  711.07  4954.9  711.05  4963.8  711.61
  4993.1  710.89  5017.5  711.02  5023.7  710.28  5030.1  710.03  5030.3  709.53
  5033.8  709.53  5034.1  710.03  5052.9  711.17  5102.9  711.14  5109.1  710.84
  5117.5  711.28  5232.1  712.67  5245.6  713.55  5259.1  713.22  5302.9  714.31
  5359.1  714.77  5417.5  716.23  5482.1  717.15  5582.1  719.80  5745.6  725.72
#Mann=3,-1,0
  4436.6    0.15       0  5030.1    0.05       0  5034.1    0.15       0
Bank Sta=5030.1,5034.1
Exp/Cntr=0.3,0.1

Type RM Length L Ch R = 1,4323,291,291,291
BEGIN DESCRIPTION:
Elizabeth Creek Tributary 14_1 6.0
END DESCRIPTION:
XS GIS Cut Line= 3
      2320728.98      7057410.05      2320929.00      7056810.00
      2320479.02      7056260.03
#Sta/Elev= 30
  4353.6  725.66  4522.3  720.38  4575.0  719.29  4691.0  715.72  4880.7  711.08
  4954.5  709.77  4965.0  709.34  4973.6  707.95  4973.8  707.45  4977.3  707.45
  4977.6  707.95  4999.7  708.76  5014.1  708.27  5042.8  708.84  5114.6  708.45
  5149.8  709.59  5184.9  710.10  5205.8  711.03  5320.6  712.39  5327.1  712.77
  5335.0  712.46  5384.5  713.65  5398.8  713.57  5405.3  714.09  5412.5  713.84
  5440.5  714.14  5454.8  714.74  5497.9  715.05  5675.2  718.96  5696.7  719.12
#Mann=3,-1,0
  4353.6    0.15       0  4973.6    0.05       0  4977.6    0.15       0
Bank Sta=4973.6,4977.6
Exp/Cntr=0.3,0.1

Type RM Length L Ch R = 1,4032,263,263,263
BEGIN DESCRIPTION:
Elizabeth Creek Tributary 14_1 5.0
END DESCRIPTION:
XS GIS Cut Line= 3
      2321028.99      7057060.02      2321129.00      7056660.00
      2320729.03      7056060.04
#Sta/Elev= 30
  4588.0  713.98  4742.6  711.00  4776.1  709.71  4812.2  709.26  4928.2  706.11
  4948.8  704.95  4990.0  704.79  4995.8  703.58  4996.0  703.08  4999.5  703.08
  4999.8  703.58  5003.3  703.58  5007.8  704.57  5028.9  705.35  5058.9  705.47
  5080.0  706.29  5086.0  704.86  5095.0  704.72  5101.0  706.86  5245.2  709.12
  5266.2  706.16  5275.3  709.33  5281.3  709.05  5288.8  709.93  5296.3  710.21
  5324.8  710.43  5497.6  714.49  5577.2  716.91  5656.8  720.20  5721.4  722.28
#Mann=3,-1,0
  4588.0    0.15       0  4995.8    0.05       0  4999.8    0.15       0
Bank Sta=4995.8,4999.8
Exp/Cntr=0.3,0.1

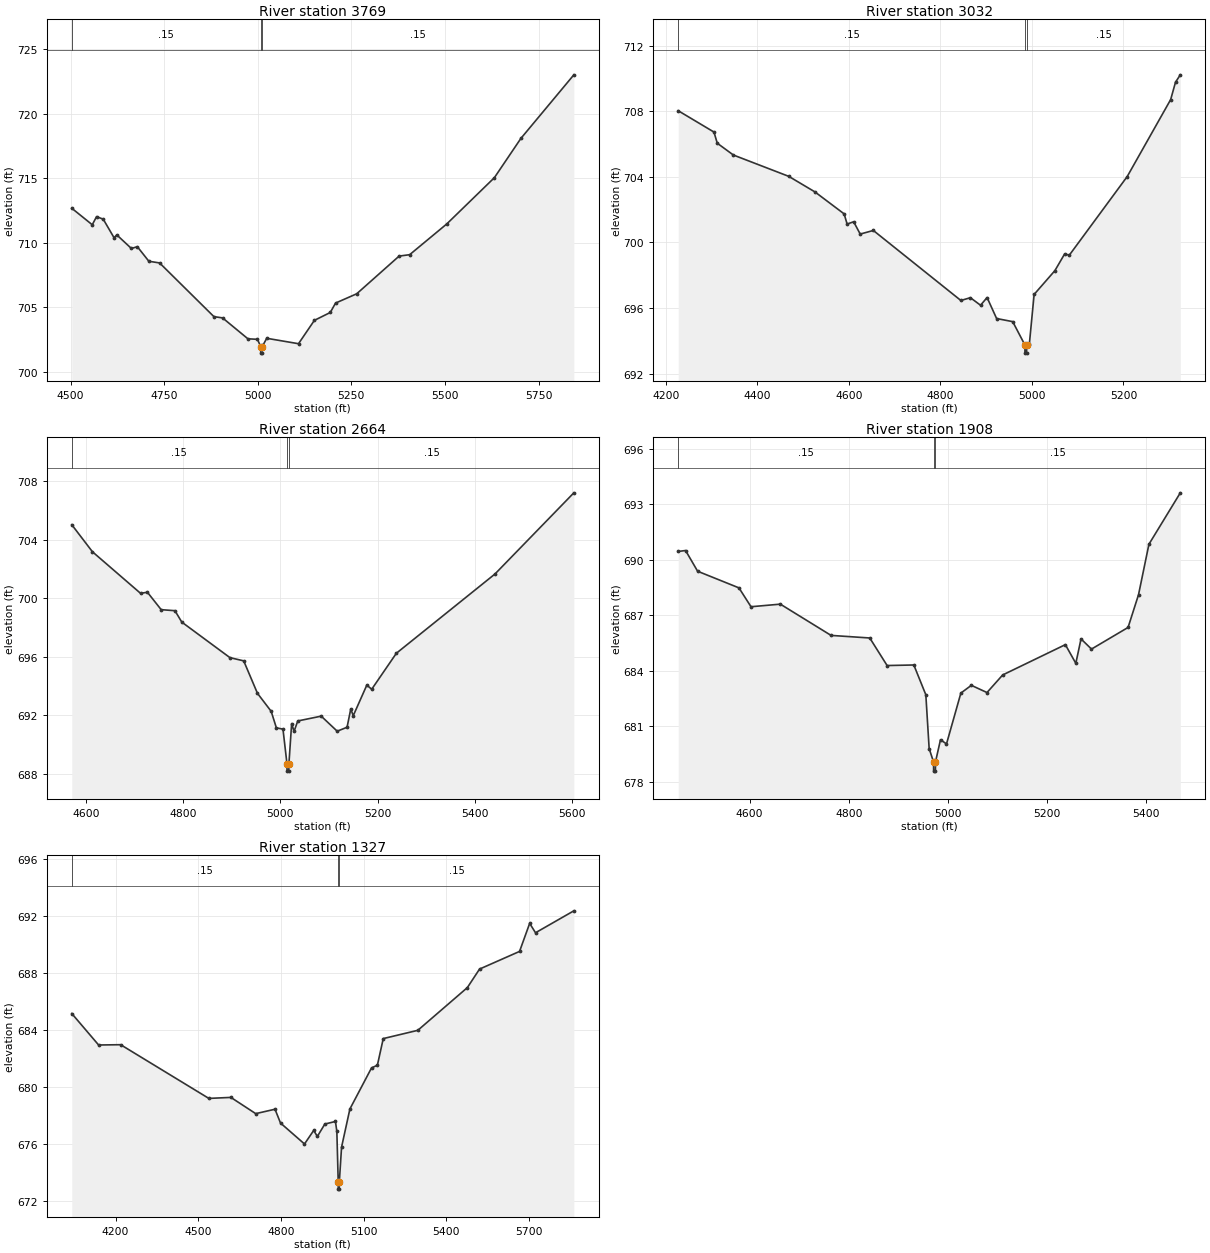
Type RM Length L Ch R = 1,3769,737,737,737
BEGIN DESCRIPTION:
Elizabeth Creek Tributary 14_1 4.0
END DESCRIPTION:
XS GIS Cut Line= 3
      2321179.01      7057059.99      2321379.00      7056610.00
      2320778.97      7056009.97
#Sta/Elev= 30
  4503.3  712.69  4558.0  711.41  4569.6  712.04  4587.4  711.84  4616.1  710.41
  4623.7  710.62  4662.6  709.57  4678.4  709.71  4709.2  708.58  4737.9  708.45
  4882.9  704.29  4906.1  704.19  4973.8  702.57  4999.3  702.53  5007.9  701.96
  5008.1  701.46  5011.6  701.46  5011.9  701.96  5024.0  702.61  5108.9  702.19
  5151.3  704.00  5193.7  704.61  5207.9  705.34  5264.4  706.06  5377.6  708.98
  5405.8  709.09  5504.8  711.47  5632.1  715.06  5702.8  718.10  5844.3  723.03
#Mann=3,-1,0
  4503.3    0.15       0  5007.9    0.05       0  5011.9    0.15       0
Bank Sta=5007.9,5011.9
Exp/Cntr=0.3,0.1

Type RM Length L Ch R = 1,3032,368,368,368
BEGIN DESCRIPTION:
Elizabeth Creek Tributary 14_1 3.0
END DESCRIPTION:
XS GIS Cut Line= 3
      2321428.97      7056960.03      2322029.00      7056460.00
      2321929.00      7056160.00
#Sta/Elev= 30
  4227.0  708.03  4305.1  706.73  4312.3  706.05  4347.5  705.33  4468.5  704.03
  4525.8  703.08  4589.6  701.74  4596.1  701.12  4610.4  701.26  4624.7  700.51
  4653.4  700.73  4844.7  696.46  4865.5  696.63  4887.7  696.17  4902.0  696.64
  4922.8  695.36  4958.0  695.17  4984.6  693.75  4984.8  693.25  4988.3  693.25
  4988.6  693.75  4994.4  693.81  5004.8  696.83  5050.2  698.28  5071.3  699.29
  5081.9  699.23  5208.3  704.02  5303.2  708.71  5313.8  709.77  5324.3  710.22
#Mann=3,-1,0
  4227.0    0.15       0  4984.6    0.05       0  4988.6    0.15       0
Bank Sta=4984.6,4988.6
Exp/Cntr=0.3,0.1

Type RM Length L Ch R = 1,2664,756,756,756
BEGIN DESCRIPTION:
Elizabeth Creek Tributary 14_1 2.0
END DESCRIPTION:
XS GIS Cut Line= 3
      2321978.98      7057010.02      2322279.00      7056710.00
      2322178.99      7056109.97
#Sta/Elev= 30
  4571.0  705.02  4613.5  703.17  4712.4  700.33  4726.6  700.40  4754.9  699.21
  4783.2  699.14  4797.3  698.36  4896.3  695.93  4924.6  695.71  4952.9  693.49
  4981.1  692.26  4991.8  691.13  5005.4  691.04  5013.6  688.67  5013.8  688.17
  5017.3  688.17  5017.6  688.67  5023.2  691.42  5028.2  690.89  5035.8  691.60
  5084.0  691.93  5116.9  690.90  5137.2  691.17  5144.8  692.42  5149.9  691.96
  5177.8  694.05  5187.9  693.77  5238.6  696.23  5441.4  701.65  5603.6  707.20
#Mann=3,-1,0
  4571.0    0.15       0  5013.6    0.05       0  5017.6    0.15       0
Bank Sta=5013.6,5017.6
Exp/Cntr=0.3,0.1

Type RM Length L Ch R = 1,1908,581,581,581
BEGIN DESCRIPTION:
Elizabeth Creek Tributary 14_1 1.0
END DESCRIPTION:
XS GIS Cut Line= 3
      2322428.97      7057060.01      2322929.00      7056860.00
      2322779.00      7056409.99
#Sta/Elev= 30
  4456.0  690.45  4470.8  690.50  4495.1  689.38  4578.5  688.48  4602.8  687.46
  4662.0  687.60  4764.3  685.91  4842.4  685.77  4877.4  684.28  4931.3  684.31
  4955.5  682.70  4962.2  679.79  4971.0  679.07  4971.3  678.57  4974.8  678.57
  4975.0  679.07  4985.1  680.27  4997.2  680.04  5026.2  682.79  5047.3  683.21
  5078.9  682.82  5110.5  683.77  5237.0  685.41  5258.1  684.40  5268.6  685.72
  5289.7  685.17  5363.5  686.34  5384.6  688.11  5405.6  690.84  5468.9  693.62
#Mann=3,-1,0
  4456.0    0.15       0  4971.0    0.05       0  4975.0    0.15       0
Bank Sta=4971,4975
Exp/Cntr=0.3,0.1

Type RM Length L Ch R = 1,1327,0,0,0
BEGIN DESCRIPTION:
1032
END DESCRIPTION:
XS GIS Cut Line= 4
      2322591.67      7057137.47      2323437.94      7057121.19
      2323470.49      7056893.34      2323079.88      7056258.60
#Sta/Elev= 30
  4041.3  685.16  4138.7  682.95  4218.7  682.97  4538.7  679.20  4618.7  679.27
  4708.8  678.13  4778.8  678.44  4798.8  677.47  4885.8  676.00  4919.2  676.95
  4932.5  676.53  4959.6  677.40  4998.1  677.58  5003.2  676.88  5008.2  673.33
  5008.4  672.83  5011.9  672.83  5012.2  673.33  5020.3  675.78  5050.6  678.46
  5129.0  681.34  5150.3  681.53  5171.6  683.40  5297.0  683.98  5476.8  686.98
  5521.0  688.28  5666.2  689.52  5702.9  691.49  5724.1  690.83  5863.2  692.37
#Mann=3,-1,0
  4041.3    0.15       0  5008.2    0.05       0  5012.2    0.15       0
Bank Sta=5008.2,5012.2
Exp/Cntr=0.3,0.1

Chan Stop Cuts=-1