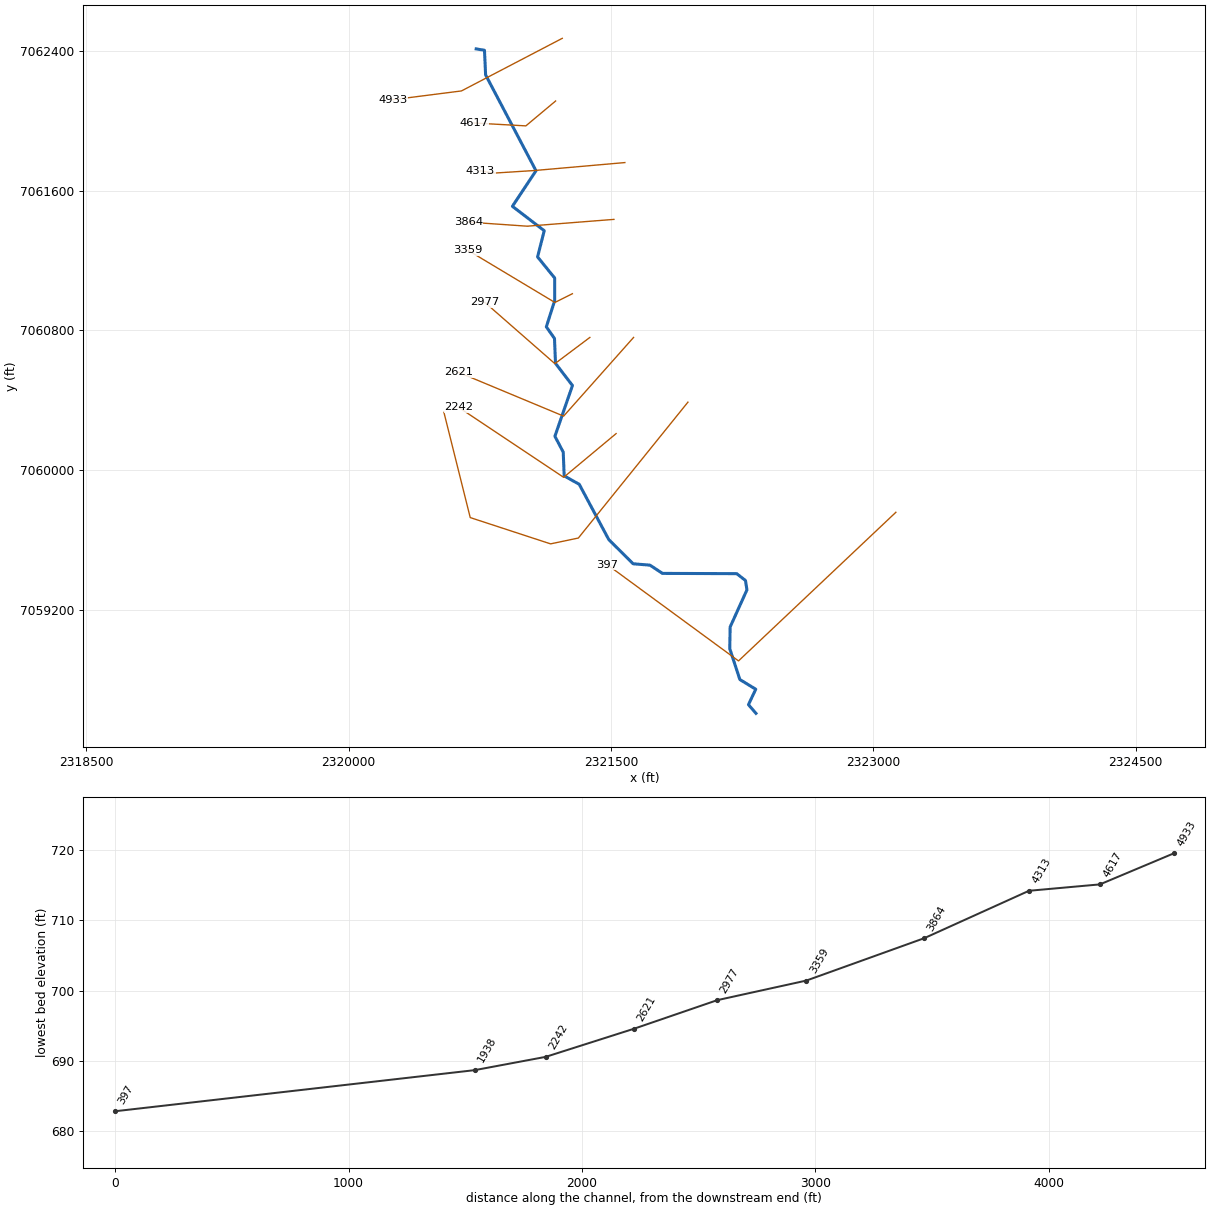
--- Elizabeth Cr Tr 16.prj (project) ---

Proj Title=Elizabeth Cr Tr 16 Base Level Engineering
Current Plan=p01
Default Exp/Contr=0.3,0.1
English Units
Geom File=g01
Flow File=f01
Plan File=p01
BEGIN DESCRIPTION:
Elizabeth Cr Tr 16
END DESCRIPTION:

--- Elizabeth Cr Tr 16.p01 (plan) ---

Plan Title=Multiple Run
Short Identifier=Multiple
Geom File=g01
Flow File=f01
Subcritical Flow
K Sum by GR= 0
Std Step Tol= 0.01
Critical Tol= 0.01
Num of Std Step Trials= 20
Max Error Tol= 0.3
Flow Tol Ratio= 0.001
Split Flow NTrial= 30
Split Flow Tol= 0.02
Split Flow Ratio= 0.02
Log Output Level= 0
Friction Slope Method= 1
Unsteady Friction Slope Method= 2
Unsteady Bridges Friction Slope Method= 1
Parabolic Critical Depth
Global Vel Dist=  1 , 1 , 1
Global Log Level= 0
CheckData=True
Encroach Param= -1, 0, 0, 0
BEGIN DESCRIPTION:
Multiple Run
END DESCRIPTION:

--- Elizabeth Cr Tr 16.f01 (steady flow) ---

Flow Title=Multiple
Number of Profiles=7
Profile Names=10-year,25-year,50-year,1pct_min,100-year,1pct_plu,500-year
River Rch & RM= Elizabeth Cr Tr ,Reach-1,4933
     368     490     588     351     701    1400     997
River Rch & RM= Elizabeth Cr Tr ,Reach-1,3359
     465     627     760     457     912    1820    1320
Boundary for River Rch & Prof#=Elizabeth Cr Tr ,Reach-1,1
Up Type=0
Dn Type=3
Dn Slope=0.005
Boundary for River Rch & Prof#=Elizabeth Cr Tr ,Reach-1,2
Up Type=0
Dn Type=3
Dn Slope=0.005
Boundary for River Rch & Prof#=Elizabeth Cr Tr ,Reach-1,3
Up Type=0
Dn Type=3
Dn Slope=0.005
Boundary for River Rch & Prof#=Elizabeth Cr Tr ,Reach-1,4
Up Type=0
Dn Type=3
Dn Slope=0.005
Boundary for River Rch & Prof#=Elizabeth Cr Tr ,Reach-1,5
Up Type=0
Dn Type=3
Dn Slope=0.005
Boundary for River Rch & Prof#=Elizabeth Cr Tr ,Reach-1,6
Up Type=0
Dn Type=3
Dn Slope=0.005
Boundary for River Rch & Prof#=Elizabeth Cr Tr ,Reach-1,7
Up Type=0
Dn Type=3
Dn Slope=0.005

--- Elizabeth Cr Tr 16.g01 (geometry) ---

Geom Title=Existing Conditions

River Reach=Elizabeth Cr Tr ,Reach-1
Reach XY= 30
      2320729.00      7062410.00      2320776.28      7062402.29
      2320782.75      7062261.56      2321070.98      7061713.31
      2320936.08      7061509.98      2321118.03      7061370.38
      2321079.95      7061220.49      2321177.96      7061099.56
      2321177.79      7060970.51      2321130.10      7060820.55
      2321176.73      7060754.06      2321182.56      7060611.47
      2321279.49      7060485.04      2321179.09      7060194.61
      2321226.70      7060104.06      2321232.10      7059968.31
      2321318.29      7059919.97      2321487.14      7059603.94
      2321626.57      7059465.52      2321723.02      7059457.64
      2321794.22      7059410.52      2322218.76      7059409.02
      2322268.97      7059370.06      2322277.24      7059316.17
      2322181.25      7059104.06      2322179.05      7058980.04
      2322236.80      7058803.56      2322327.79      7058747.98
      2322285.97      7058659.92      2322329.00      7058610.00

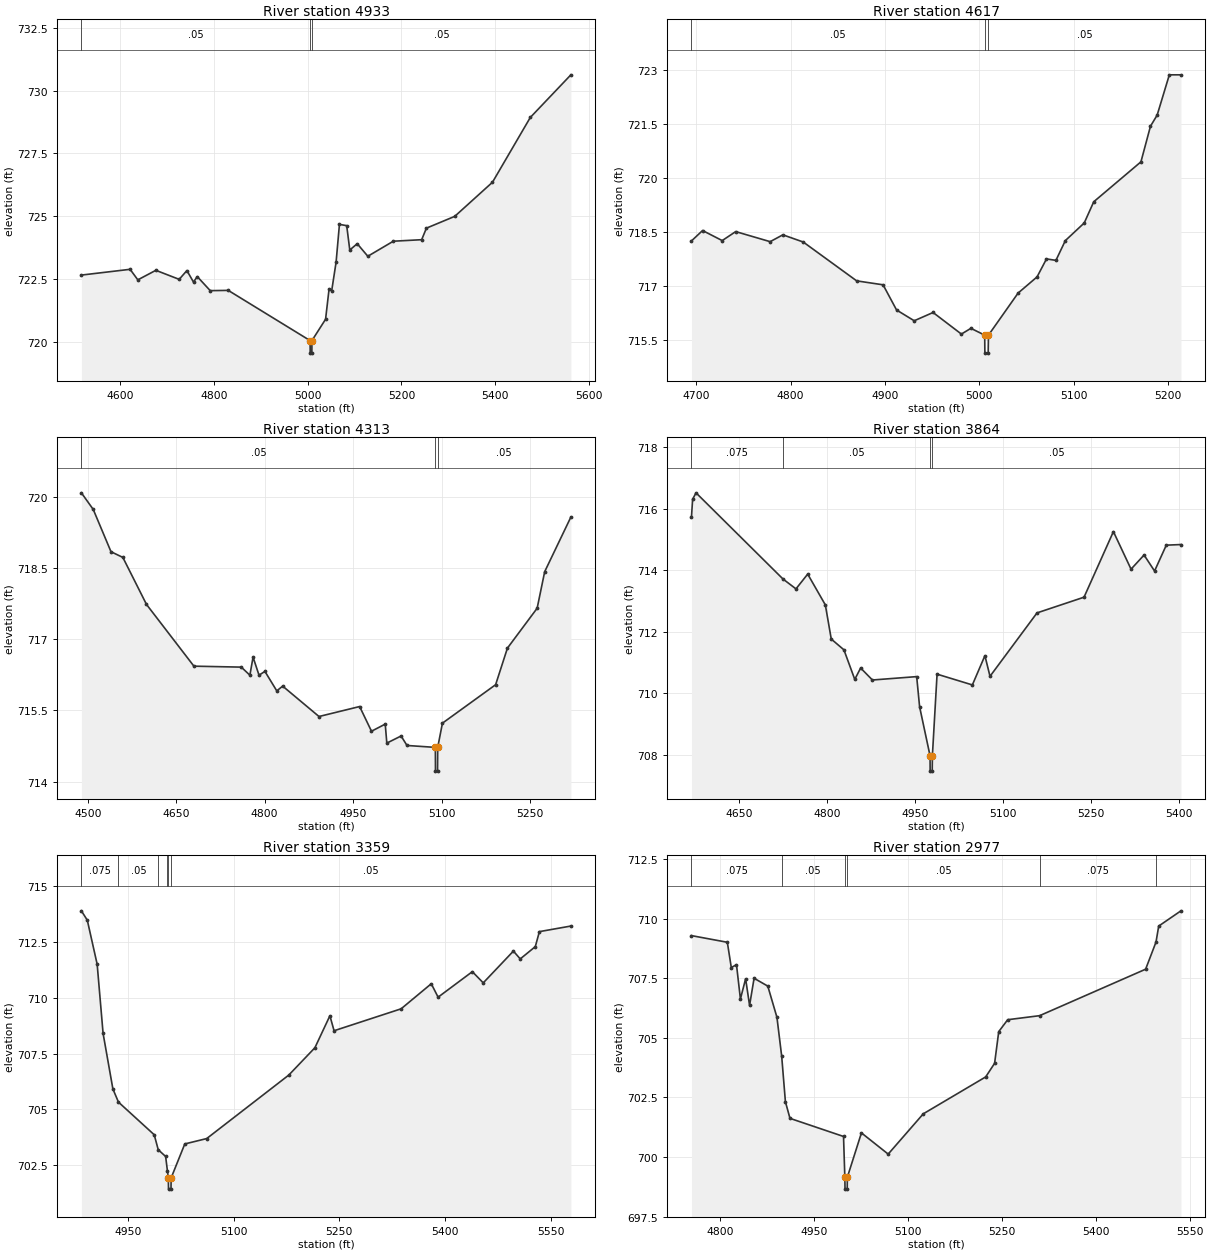
Type RM Length L Ch R = 1,4933,316,316,316
BEGIN DESCRIPTION:
1036
END DESCRIPTION:
XS GIS Cut Line= 3
      2321221.24      7062470.51      2320644.68      7062169.70
      2320252.97      7062119.69
#Sta/Elev= 30
  4516.6  722.65  4620.6  722.88  4637.1  722.46  4675.6  722.84  4725.4  722.48
  4741.9  722.83  4756.0  722.37  4764.0  722.59  4791.7  722.03  4830.2  722.04
  5004.9  720.04  5005.2  719.54  5008.7  719.54  5008.9  720.04  5038.0  720.89
  5045.5  722.10  5051.1  722.03  5060.5  723.17  5067.6  724.67  5083.1  724.62
  5089.7  723.65  5105.6  723.90  5128.2  723.40  5182.7  724.00  5243.2  724.06
  5253.3  724.52  5313.8  724.99  5394.4  726.35  5475.1  728.93  5561.8  730.63
#Mann=3,-1,0
  4516.6    0.05       0  5004.9   0.033       0  5008.9    0.05       0
Bank Sta=5004.9,5008.9
Exp/Cntr=0.3,0.1

Type RM Length L Ch R = 1,4617,304,304,304
BEGIN DESCRIPTION:
Elizabeth Creek Tributary 16 9.0
END DESCRIPTION:
XS GIS Cut Line= 3
      2321183.33      7062112.35      2321013.05      7061969.90
      2320716.70      7061986.28
#Sta/Elev= 30
  4694.9  718.25  4706.7  718.54  4727.5  718.26  4741.8  718.51  4778.3  718.23
  4791.8  718.42  4813.4  718.22  4870.0  717.14  4898.0  717.03  4912.3  716.33
  4931.0  716.03  4951.0  716.26  4981.0  715.66  4991.1  715.82  5005.7  715.63
  5005.9  715.13  5009.4  715.13  5009.7  715.63  5041.1  716.80  5061.2  717.25
  5071.2  717.75  5081.2  717.71  5091.2  718.26  5111.2  718.75  5121.3  719.34
  5171.3  720.45  5181.4  721.44  5188.5  721.75  5201.4  722.87  5213.7  722.87
#Mann=3,-1,0
  4694.9    0.05       0  5005.7   0.033       0  5009.7    0.05       0
Bank Sta=5005.7,5009.7
Exp/Cntr=0.3,0.1

Type RM Length L Ch R = 1,4313,449,449,449
BEGIN DESCRIPTION:
Elizabeth Creek Tributary 16 8.0
END DESCRIPTION:
XS GIS Cut Line= 4
      2321579.02      7061760.00      2321062.16      7061714.52
      2320830.20      7061699.76      2320752.55      7061712.64
#Sta/Elev= 30
  4489.2  720.08  4509.3  719.73  4539.4  718.84  4559.5  718.72  4599.6  717.73
  4680.0  716.43  4760.3  716.41  4774.9  716.24  4780.3  716.62  4790.4  716.24
  4800.4  716.32  4820.5  715.91  4830.5  716.01  4892.1  715.37  4961.0  715.58
  4981.1  715.06  5004.4  715.21  5007.1  714.81  5031.3  714.96  5041.3  714.76
  5089.4  714.72  5089.6  714.22  5093.1  714.22  5093.4  714.72  5101.4  715.23
  5191.6  716.04  5211.6  716.81  5262.0  717.65  5274.8  718.42  5319.2  719.57
#Mann=3,-1,0
  4489.2    0.05       0  5089.4   0.033       0  5093.4    0.05       0
Bank Sta=5089.4,5093.4
Exp/Cntr=0.3,0.1

Type RM Length L Ch R = 1,3864,505,505,505
BEGIN DESCRIPTION:
1034
END DESCRIPTION:
XS GIS Cut Line= 3
      2321516.73      7061435.10      2321021.28      7061396.19
      2320684.06      7061419.54
#Sta/Elev= 30
  4568.4  715.71  4570.4  716.30  4576.2  716.51  4724.6  713.71  4746.7  713.39
  4766.7  713.87  4796.8  712.87  4806.9  711.76  4828.5  711.41  4847.0  710.45
  4857.0  710.82  4877.1  710.43  4952.6  710.54  4957.6  709.56  4975.4  707.97
  4975.6  707.47  4979.1  707.47  4979.4  707.97  4987.4  710.62  5047.6  710.27
  5069.0  711.22  5077.7  710.55  5157.9  712.61  5238.1  713.12  5288.2  715.25
  5318.3  714.03  5340.5  714.49  5358.4  713.97  5378.4  714.81  5403.4  714.83
#Mann=4,-1,0
  4568.4   0.075       0  4724.6    0.05       0  4975.4   0.033       0
  4979.4    0.05       0
Bank Sta=4975.4,4979.4
Exp/Cntr=0.3,0.1

Type RM Length L Ch R = 1,3359,382,382,382
BEGIN DESCRIPTION:
Elizabeth Creek Tributary 16 5.0
END DESCRIPTION:
XS GIS Cut Line= 3
      2321279.02      7061010.01      2321179.00      7060960.00
      2320679.02      7061259.99
#Sta/Elev= 30
  4884.0  713.88  4892.4  713.46  4906.4  711.49  4914.8  708.40  4928.7  705.92
  4936.6  705.33  4987.4  703.87  4993.1  703.20  5003.6  702.90  5006.2  702.24
  5007.4  701.94  5007.7  701.44  5011.2  701.44  5011.4  701.94  5030.8  703.46
  5061.9  703.70  5178.5  706.54  5215.5  707.76  5236.8  709.19  5242.7  708.52
  5337.9  709.50  5380.7  710.62  5390.4  710.02  5439.0  711.16  5454.5  710.66
  5497.3  712.08  5507.0  711.73  5528.4  712.28  5534.2  712.95  5578.9  713.20
#Mann=6,-1,0
  4884.0   0.075       0  4936.6    0.05       0  4993.1   0.075       0
  5006.2    0.05       0  5007.4    0.07       0  5011.4    0.05       0
Bank Sta=5007.4,5011.4
Exp/Cntr=0.3,0.1

Type RM Length L Ch R = 1,2977,356,356,356
BEGIN DESCRIPTION:
Elizabeth Creek Tributary 16 4.0
END DESCRIPTION:
XS GIS Cut Line= 3
      2321379.03      7060760.03      2321179.00      7060610.00
      2320779.04      7060959.97
#Sta/Elev= 30
  4754.0  709.29  4811.3  709.01  4817.6  707.95  4825.9  708.07  4832.2  706.63
  4840.5  707.48  4846.8  706.36  4854.0  707.50  4875.9  707.17  4890.5  705.86
  4898.1  704.22  4904.0  702.32  4911.3  701.62  4996.8  700.86  4998.9  699.15
  4999.2  698.65  5002.7  698.65  5002.9  699.15  5025.4  701.01  5068.1  700.12
  5124.1  701.81  5223.8  703.36  5238.0  703.93  5244.6  705.26  5258.9  705.76
  5309.9  705.93  5479.1  707.88  5495.7  709.02  5500.0  709.69  5535.5  710.33
#Mann=6,-1,0
  4754.0   0.075       0  4898.1    0.05       0  4998.9   0.033       0
  5002.9    0.05       0  5309.9   0.075       0  5495.7    0.05       0
Bank Sta=4998.9,5002.9
Exp/Cntr=0.3,0.1

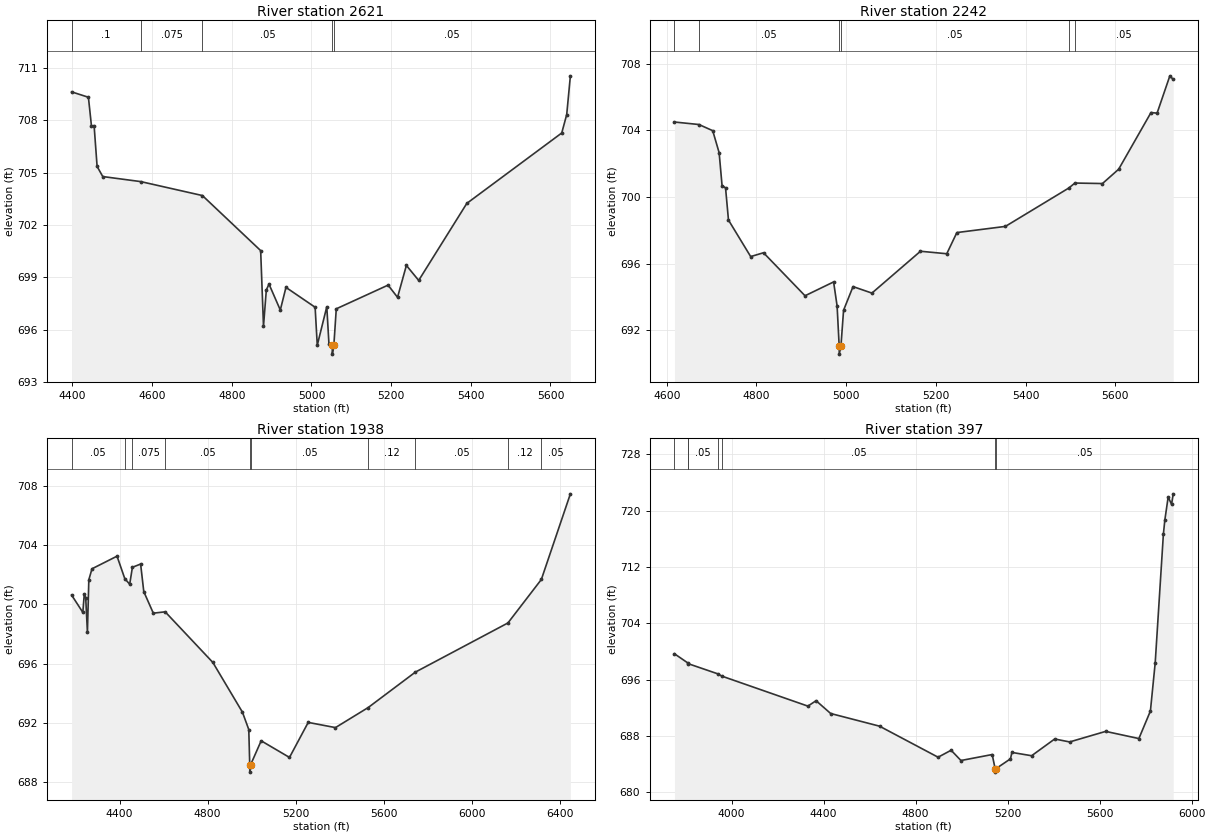
Type RM Length L Ch R = 1,2621,379,379,379
BEGIN DESCRIPTION:
Elizabeth Creek Tributary 16 3.0
END DESCRIPTION:
XS GIS Cut Line= 3
      2321629.01      7060760.01      2321229.00      7060310.00
      2320629.00      7060560.00
#Sta/Elev= 30
  4397.9  709.64  4440.1  709.33  4447.7  707.69  4454.4  707.70  4461.9  705.36
  4476.1  704.78  4571.5  704.49  4726.2  703.69  4872.5  700.53  4879.6  696.19
  4886.7  698.27  4893.4  698.61  4921.8  697.12  4936.0  698.42  5009.2  697.28
  5014.6  695.10  5038.5  697.31  5043.9  695.18  5052.2  695.09  5052.4  694.59
  5056.2  695.09  5062.3  697.19  5192.3  698.55  5216.1  697.85  5238.3  699.68
  5269.2  698.82  5390.0  703.24  5628.3  707.28  5640.8  708.34  5650.0  710.56
#Mann=5,-1,0
  4397.9     0.1       0  4571.5   0.075       0  4726.2    0.05       0
  5052.2   0.033       0  5056.2    0.05       0
Bank Sta=5052.2,5056.2
Exp/Cntr=0.3,0.1

Type RM Length L Ch R = 1,2242,304,304,304
BEGIN DESCRIPTION:
Elizabeth Creek Tributary 16 2.0
END DESCRIPTION:
XS GIS Cut Line= 3
      2321529.02      7060210.01      2321229.00      7059960.00
      2320629.04      7060359.98
#Sta/Elev= 30
  4617.2  704.50  4671.8  704.35  4702.5  703.98  4716.8  702.66  4723.3  700.69
  4731.1  700.55  4737.6  698.62  4787.1  696.43  4815.7  696.66  4908.2  694.08
  4971.9  694.91  4979.7  693.47  4984.3  691.08  4984.5  690.58  4988.3  691.08
  4994.1  693.21  5015.2  694.63  5057.3  694.24  5165.5  696.75  5224.1  696.60
  5246.6  697.87  5354.8  698.24  5496.0  700.54  5509.7  700.84  5571.1  700.81
  5607.2  701.67  5679.3  705.07  5692.8  705.03  5721.3  707.27  5728.8  707.05
#Mann=6,-1,0
  4617.2   0.075       0  4671.8    0.05       0  4984.3   0.033       0
  4988.3    0.05       0  5496.0    0.12       0  5509.7    0.05       0
Bank Sta=4984.3,4988.3
Exp/Cntr=0.3,0.1

Type RM Length L Ch R = 1,1938,1541,1541,1541
BEGIN DESCRIPTION:
1033
END DESCRIPTION:
XS GIS Cut Line= 5
      2321939.85      7060389.91      2321313.15      7059612.80
      2321154.39      7059579.38      2320694.81      7059729.78
      2320544.40      7060331.44
#Sta/Elev= 30
  4182.4  700.62  4233.4  699.45  4239.8  700.67  4246.5  700.42  4254.2  698.12
  4260.6  701.65  4275.0  702.39  4388.6  703.24  4424.0  701.72  4446.1  701.35
  4458.4  702.49  4495.7  702.71  4510.1  700.85  4553.3  699.40  4607.2  699.49
  4823.6  696.08  4957.9  692.73  4986.7  691.56  4991.1  689.19  4991.4  688.69
  4995.1  689.19  5043.0  690.80  5171.5  689.68  5256.5  692.04  5380.2  691.69
  5528.7  693.04  5743.2  695.43  6163.2  698.74  6314.9  701.67  6446.7  707.44
#Mann=10,-1,0
  4182.4    0.05       0  4424.0     0.1       0  4458.4   0.075       0
  4607.2    0.05       0  4991.1   0.033       0  4995.1    0.05       0
  5528.7    0.12       0  5743.2    0.05       0  6163.2    0.12       0
  6314.9    0.05       0
Bank Sta=4991.1,4995.1
Exp/Cntr=0.3,0.1

Type RM Length L Ch R = 1,397,0,0,0
BEGIN DESCRIPTION:
Elizabeth Creek Tributary 16 1.0
END DESCRIPTION:
XS GIS Cut Line= 3
      2323129.02      7059760.02      2322229.00      7058910.00
      2321479.02      7059459.99
#Sta/Elev= 30
  3751.9  699.66  3809.0  698.38  3811.8  698.25  3941.1  696.80  3958.2  696.48
  4331.9  692.22  4367.5  692.99  4431.0  691.17  4643.4  689.37  4897.8  684.96
  4954.5  685.95  4997.2  684.49  5133.0  685.34  5145.7  683.34  5145.9  682.84
  5149.7  683.34  5212.5  684.73  5218.7  685.64  5304.4  685.17  5404.7  687.55
  5469.6  687.13  5626.3  688.63  5770.6  687.61  5820.7  691.52  5841.6  698.39
  5877.1  716.65  5883.3  718.63  5897.9  721.94  5912.6  720.90  5919.9  722.39
#Mann=7,-1,0
  3751.9    0.05       0  3809.0    0.12       0  3811.8    0.05       0
  3941.1    0.12       0  3958.2    0.05       0  5145.7   0.033       0
  5149.7    0.05       0
Bank Sta=5145.7,5149.7
Exp/Cntr=0.3,0.1

Chan Stop Cuts=-1