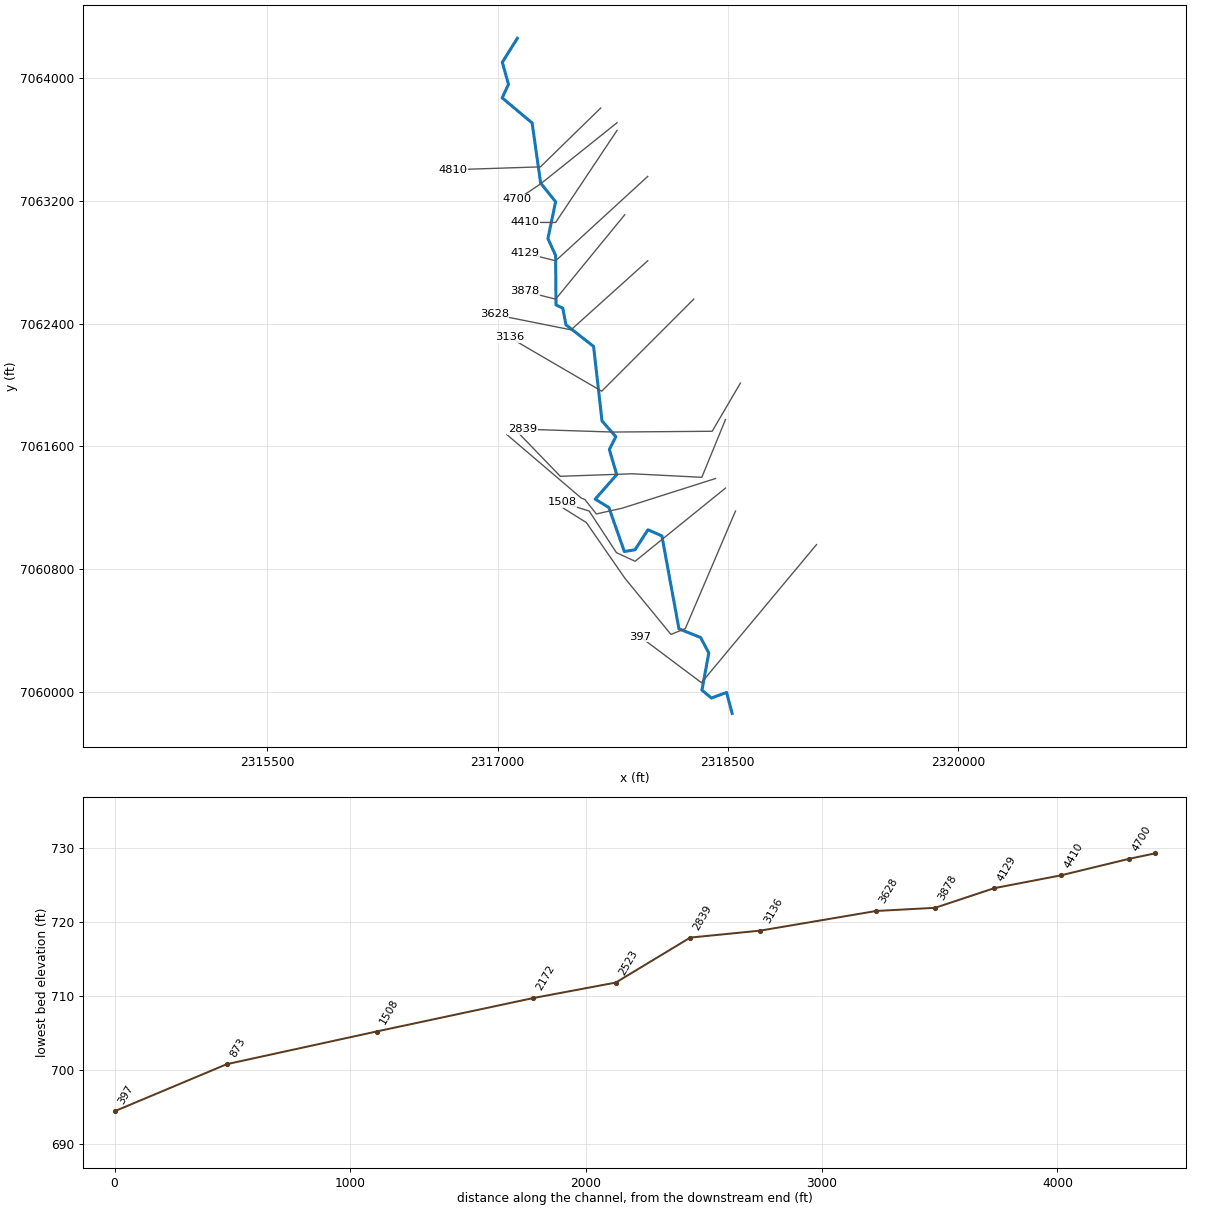
--- Elizabeth Cr Tr 19.prj (project) ---

Proj Title=Elizabeth Cr Tr 19 Base Level Engineering
Current Plan=p01
Default Exp/Contr=0.3,0.1
English Units
Geom File=g01
Flow File=f01
Plan File=p01
BEGIN DESCRIPTION:
Elizabeth Cr Tr 19
END DESCRIPTION:

--- Elizabeth Cr Tr 19.p01 (plan) ---

Plan Title=Multiple Run
Short Identifier=Multiple
Geom File=g01
Flow File=f01
Subcritical Flow
K Sum by GR= 0
Std Step Tol= 0.01
Critical Tol= 0.01
Num of Std Step Trials= 20
Max Error Tol= 0.3
Flow Tol Ratio= 0.001
Split Flow NTrial= 30
Split Flow Tol= 0.02
Split Flow Ratio= 0.02
Log Output Level= 0
Friction Slope Method= 1
Unsteady Friction Slope Method= 2
Unsteady Bridges Friction Slope Method= 1
Parabolic Critical Depth
Global Vel Dist=  1 , 1 , 1
Global Log Level= 0
CheckData=True
Encroach Param= -1, 0, 0, 0
BEGIN DESCRIPTION:
Multiple Run
END DESCRIPTION:

--- Elizabeth Cr Tr 19.f01 (steady flow) ---

Flow Title=Multiple
Number of Profiles=7
Profile Names=10-year,25-year,50-year,1pct_min,100-year,1pct_plu,500-year
River Rch & RM= Elizabeth Cr Tr ,Reach-1,4810
     357     473     566     337     673    1340     951
River Rch & RM= Elizabeth Cr Tr ,Reach-1,397
     370     493     591     353     704    1400     999
Boundary for River Rch & Prof#=Elizabeth Cr Tr ,Reach-1,1
Up Type=0
Dn Type=3
Dn Slope=0.005
Boundary for River Rch & Prof#=Elizabeth Cr Tr ,Reach-1,2
Up Type=0
Dn Type=3
Dn Slope=0.005
Boundary for River Rch & Prof#=Elizabeth Cr Tr ,Reach-1,3
Up Type=0
Dn Type=3
Dn Slope=0.005
Boundary for River Rch & Prof#=Elizabeth Cr Tr ,Reach-1,4
Up Type=0
Dn Type=3
Dn Slope=0.005
Boundary for River Rch & Prof#=Elizabeth Cr Tr ,Reach-1,5
Up Type=0
Dn Type=3
Dn Slope=0.005
Boundary for River Rch & Prof#=Elizabeth Cr Tr ,Reach-1,6
Up Type=0
Dn Type=3
Dn Slope=0.005
Boundary for River Rch & Prof#=Elizabeth Cr Tr ,Reach-1,7
Up Type=0
Dn Type=3
Dn Slope=0.005

--- Elizabeth Cr Tr 19.g01 (geometry) ---

Geom Title=Existing Conditions

River Reach=Elizabeth Cr Tr ,Reach-1
Reach XY= 30
      2317129.00      7064260.00      2317031.14      7064104.04
      2317071.39      7063959.96      2317030.22      7063872.03
      2317225.46      7063708.53      2317281.07      7063315.86
      2317378.63      7063194.83      2317328.19      7062954.97
      2317378.48      7062844.78      2317380.96      7062521.97
      2317425.44      7062501.50      2317445.46      7062393.27
      2317625.93      7062251.70      2317681.08      7061765.85
      2317771.17      7061663.40      2317728.79      7061580.21
      2317777.04      7061415.89      2317636.52      7061256.44
      2317725.79      7061201.66      2317826.45      7060914.94
      2317896.04      7060926.05      2317980.47      7061057.01
      2318071.30      7061016.57      2318182.44      7060411.22
      2318323.56      7060354.75      2318376.87      7060254.06
      2318332.37      7060011.22      2318394.22      7059959.96
      2318492.78      7059996.69      2318529.00      7059860.00

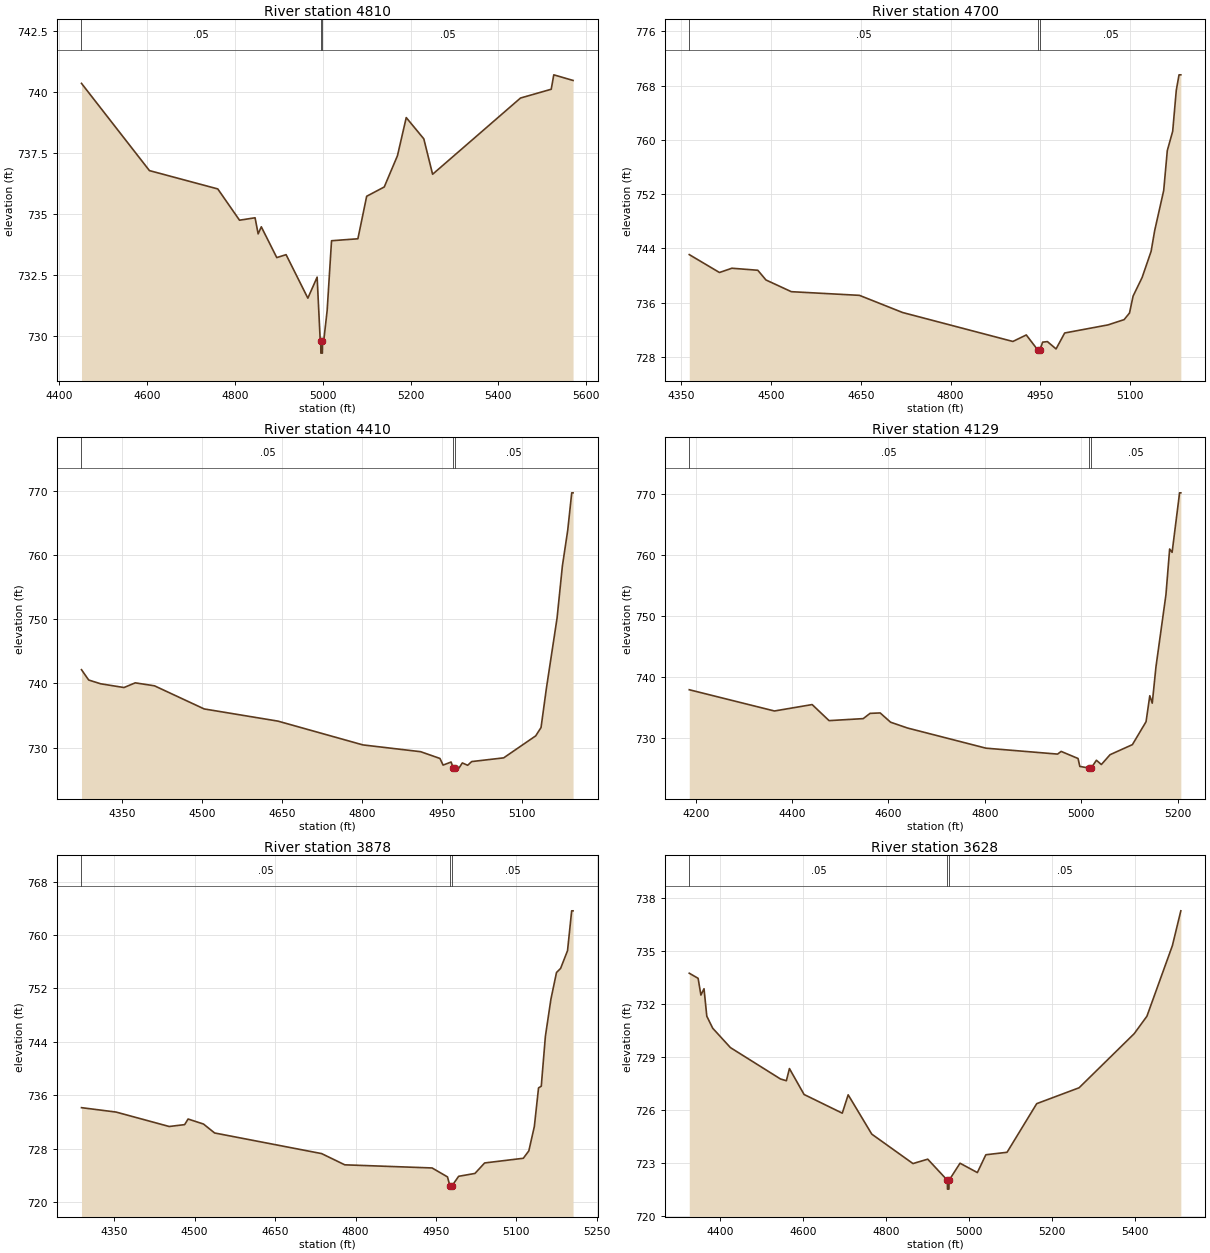
Type RM Length L Ch R = 1,4810,110,110,110
BEGIN DESCRIPTION:
1042
END DESCRIPTION:
XS GIS Cut Line= 3
      2317672.21      7063805.54      2317279.60      7063422.28
      2316709.37      7063403.58
#Sta/Elev= 30
  4450.8  740.34  4605.5  736.77  4761.1  736.02  4810.6  734.74  4846.0  734.84
  4853.0  734.18  4860.2  734.47  4895.4  733.21  4916.6  733.33  4966.2  731.55
  4987.3  732.41  4994.4  729.80  4995.5  729.80  4995.8  729.30  4999.3  729.30
  4999.5  729.80  5002.3  729.80  5010.1  731.04  5020.1  733.90  5080.1  733.98
  5100.1  735.72  5140.1  736.10  5170.2  737.38  5190.2  738.94  5230.2  738.07
  5250.2  736.62  5450.3  739.74  5520.3  740.10  5526.1  740.69  5570.0  740.46
#Mann=3,-1,0
  4450.8    0.05       0  4995.5   0.033       0  4999.5    0.05       0
Bank Sta=4995.5,4999.5
Exp/Cntr=0.3,0.1

Type RM Length L Ch R = 1,4700,290,290,290
BEGIN DESCRIPTION:
Elizabeth Creek Tributary 19 9.0
END DESCRIPTION:
XS GIS Cut Line= 3
      2317778.97      7063709.98      2317279.00      7063310.00
      2317128.96      7063209.98
#Sta/Elev= 30
  4363.8  743.09  4414.2  740.45  4435.0  741.08  4478.2  740.78  4491.8  739.35
  4534.2  737.62  4647.9  737.08  4719.9  734.55  4904.0  730.28  4926.4  731.24
  4945.3  729.06  4945.5  728.56  4949.3  729.06  4953.7  730.18  4961.7  730.26
  4976.1  729.18  4990.5  731.53  5062.7  732.72  5089.7  733.50  5098.7  734.47
  5104.7  736.97  5119.8  739.72  5134.8  743.58  5140.8  746.66  5155.8  752.54
  5161.8  758.43  5170.8  761.27  5176.8  767.33  5181.4  769.60  5184.4  769.60
#Mann=3,-1,0
  4363.8    0.05       0  4945.3   0.033       0  4949.3    0.05       0
Bank Sta=4945.3,4949.3
Exp/Cntr=0.3,0.1

Type RM Length L Ch R = 1,4410,281,281,281
BEGIN DESCRIPTION:
Elizabeth Creek Tributary 19 8.0
END DESCRIPTION:
XS GIS Cut Line= 3
      2317779.01      7063660.02      2317379.00      7063060.00
      2317179.03      7063060.00
#Sta/Elev= 30
  4274.3  742.14  4287.8  740.53  4310.4  739.94  4353.9  739.36  4375.0  740.09
  4411.0  739.63  4504.2  736.02  4642.4  734.12  4801.6  730.41  4909.8  729.35
  4945.9  728.30  4951.9  727.26  4966.9  727.74  4970.9  726.82  4971.1  726.32
  4974.6  726.32  4974.9  726.82  4981.9  726.83  4987.9  727.60  4997.9  727.23
  5005.4  727.81  5065.4  728.39  5125.4  731.82  5135.4  733.12  5145.4  739.22
  5165.4  750.18  5175.4  758.33  5185.4  763.89  5192.9  769.73  5195.4  769.73
#Mann=3,-1,0
  4274.3    0.05       0  4970.9   0.033       0  4974.9    0.05       0
Bank Sta=4970.9,4974.9
Exp/Cntr=0.3,0.1

Type RM Length L Ch R = 1,4129,251,251,251
BEGIN DESCRIPTION:
Elizabeth Creek Tributary 19 7.0
END DESCRIPTION:
XS GIS Cut Line= 3
      2317978.99      7063359.99      2317379.00      7062810.00
      2317178.99      7062860.00
#Sta/Elev= 30
  4186.6  737.93  4363.3  734.45  4441.6  735.50  4476.7  732.87  4547.6  733.20
  4561.8  734.06  4582.8  734.13  4604.4  732.61  4639.5  731.66  4802.3  728.36
  4950.9  727.39  4958.3  727.83  4993.4  726.67  4997.1  725.37  5016.6  725.10
  5016.8  724.60  5020.6  725.10  5031.5  726.38  5041.8  725.68  5059.8  727.29
  5106.2  728.94  5134.5  732.69  5142.3  736.95  5147.4  735.73  5155.1  741.69
  5175.8  753.50  5183.5  760.98  5188.6  760.43  5204.1  770.18  5206.7  770.18
#Mann=3,-1,0
  4186.6    0.05       0  5016.6   0.033       0  5020.6    0.05       0
Bank Sta=5016.6,5020.6
Exp/Cntr=0.3,0.1

Type RM Length L Ch R = 1,3878,250,250,250
BEGIN DESCRIPTION:
Elizabeth Creek Tributary 19 6.0
END DESCRIPTION:
XS GIS Cut Line= 3
      2317828.99      7063109.99      2317379.00      7062560.00
      2317178.98      7062610.01
#Sta/Elev= 30
  4288.9  734.14  4353.5  733.48  4452.5  731.32  4481.3  731.60  4487.7  732.44
  4516.4  731.69  4537.2  730.35  4736.8  727.26  4779.9  725.58  4942.8  725.11
  4971.5  723.77  4976.0  722.44  4976.2  721.94  4979.7  721.94  4980.0  722.44
  4992.3  723.86  5022.7  724.29  5040.8  725.86  5112.9  726.56  5123.2  727.67
  5133.5  731.32  5141.3  737.10  5146.4  737.35  5154.1  744.84  5164.4  750.39
  5174.8  754.38  5182.5  755.00  5195.4  757.66  5203.1  763.62  5205.7  763.62
#Mann=3,-1,0
  4288.9    0.05       0  4976.0   0.033       0  4980.0    0.05       0
Bank Sta=4976,4980
Exp/Cntr=0.3,0.1

Type RM Length L Ch R = 1,3628,492,492,492
BEGIN DESCRIPTION:
Elizabeth Creek Tributary 19 5.0
END DESCRIPTION:
XS GIS Cut Line= 3
      2317979.00      7062810.00      2317479.00      7062360.00
      2316978.99      7062460.00
#Sta/Elev= 30
  4326.8  733.76  4348.1  733.47  4354.8  732.52  4362.3  732.88  4369.0  731.32
  4383.2  730.64  4425.8  729.54  4546.2  727.76  4560.4  727.66  4567.8  728.35
  4603.0  726.88  4694.9  725.82  4709.1  726.86  4765.9  724.63  4865.0  722.96
  4900.5  723.21  4947.8  722.01  4948.0  721.51  4951.5  721.51  4951.8  722.01
  4978.2  722.98  5019.9  722.45  5040.3  723.46  5091.3  723.60  5162.7  726.36
  5264.6  727.26  5397.2  730.33  5427.8  731.32  5489.0  735.32  5509.4  737.30
#Mann=3,-1,0
  4326.8    0.05       0  4947.8   0.033       0  4951.8    0.05       0
Bank Sta=4947.8,4951.8
Exp/Cntr=0.3,0.1

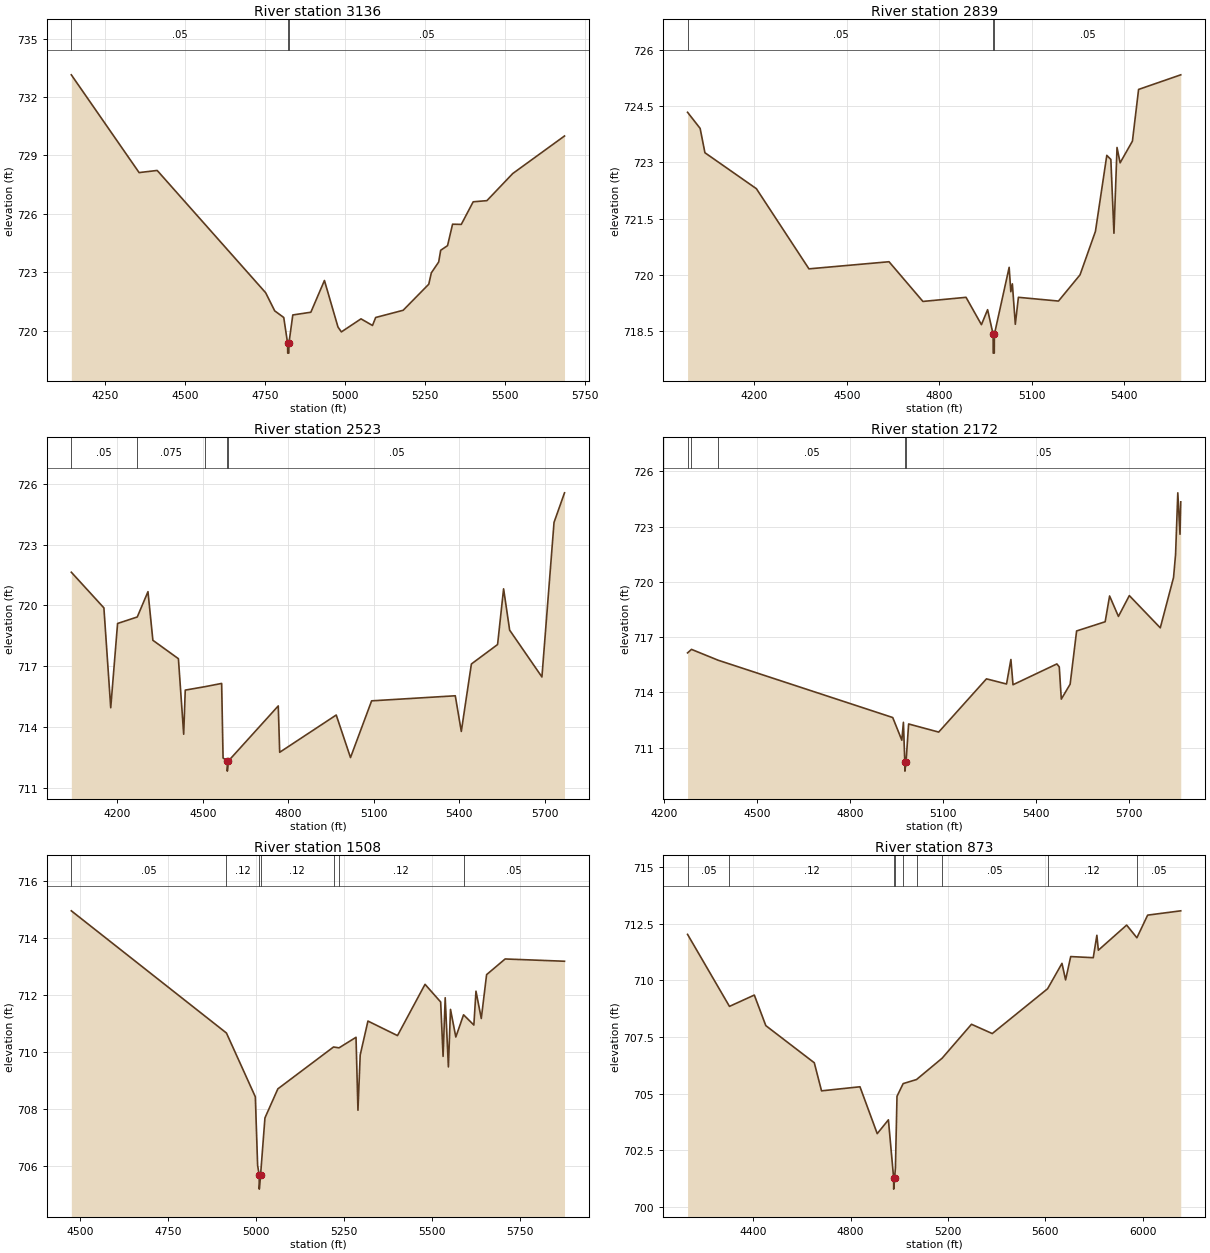
Type RM Length L Ch R = 1,3136,297,297,297
BEGIN DESCRIPTION:
Elizabeth Creek Tributary 19 4.0
END DESCRIPTION:
XS GIS Cut Line= 3
      2318279.00      7062560.00      2317679.00      7061960.00
      2317078.96      7062310.02
#Sta/Elev= 30
  4143.6  733.14  4355.7  728.12  4412.3  728.23  4751.7  721.95  4780.0  721.02
  4808.3  720.68  4820.4  719.35  4820.7  718.85  4824.2  718.85  4824.4  719.35
  4836.6  720.81  4893.1  720.95  4935.6  722.58  4978.0  720.19  4988.6  719.94
  5050.0  720.61  5086.0  720.27  5095.9  720.68  5181.9  721.05  5262.1  722.39
  5270.0  722.97  5293.1  723.53  5299.3  724.13  5320.8  724.37  5336.5  725.47
  5363.8  725.46  5401.0  726.62  5444.0  726.68  5524.7  728.07  5686.8  730.00
#Mann=3,-1,0
  4143.6    0.05       0  4820.4   0.033       0  4824.4    0.05       0
Bank Sta=4820.4,4824.4
Exp/Cntr=0.3,0.1

Type RM Length L Ch R = 1,2839,316,316,316
BEGIN DESCRIPTION:
1041
END DESCRIPTION:
XS GIS Cut Line= 4
      2318583.01      7062012.87      2318399.15      7061698.83
      2317752.69      7061693.74      2317162.18      7061712.61
#Sta/Elev= 30
  3982.7  724.34  4023.5  723.91  4039.1  723.26  4206.2  722.30  4376.8  720.16
  4636.8  720.35  4746.8  719.29  4886.8  719.40  4936.8  718.67  4956.8  719.07
  4974.8  718.41  4975.0  717.91  4978.5  717.91  4978.8  718.41  5026.8  720.20
  5032.2  719.55  5037.2  719.76  5046.8  718.68  5056.8  719.40  5186.9  719.30
  5256.9  720.00  5306.9  721.16  5343.8  723.19  5357.0  723.08  5367.0  721.11
  5377.0  723.40  5387.0  722.99  5427.0  723.57  5447.0  724.95  5583.9  725.34
#Mann=3,-1,0
  3982.7    0.05       0  4974.8   0.033       0  4978.8    0.05       0
Bank Sta=4974.8,4978.8
Exp/Cntr=0.3,0.1

Type RM Length L Ch R = 1,2523,351,351,351
BEGIN DESCRIPTION:
1040
END DESCRIPTION:
XS GIS Cut Line= 5
      2318485.65      7061774.86      2318331.48      7061398.69
      2317877.89      7061421.74      2317409.26      7061405.29
      2317130.60      7061693.75
#Sta/Elev= 30
  4038.9  721.64  4153.2  719.88  4177.2  714.95  4201.2  719.11  4270.3  719.43
  4307.9  720.68  4325.1  718.28  4414.7  717.37  4433.2  713.64  4438.7  715.82
  4508.0  715.99  4566.4  716.15  4571.4  712.47  4586.1  712.32  4586.3  711.82
  4590.1  712.32  4765.1  715.04  4770.1  712.75  4968.5  714.59  5018.6  712.49
  5092.7  715.29  5386.3  715.54  5407.4  713.78  5442.8  717.11  5534.7  718.07
  5555.8  720.82  5577.1  718.78  5690.3  716.47  5732.8  724.10  5769.6  725.56
#Mann=5,-1,0
  4038.9    0.05       0  4270.3   0.075       0  4508.0    0.05       0
  4586.1   0.033       0  4590.1    0.05       0
Bank Sta=4586.1,4590.1
Exp/Cntr=0.3,0.1

Type RM Length L Ch R = 1,2172,664,664,664
BEGIN DESCRIPTION:
1039
END DESCRIPTION:
XS GIS Cut Line= 6
      2318420.76      7061390.82      2317812.45      7061197.38
      2317644.18      7061159.98      2317569.40      7061253.47
      2317544.75      7061264.42      2317061.77      7061676.24
#Sta/Elev= 30
  4276.5  716.14  4289.2  716.33  4375.5  715.74  4938.8  712.63  4968.2  711.40
  4973.3  712.37  4977.8  710.22  4978.1  709.72  4981.8  710.22  4990.1  712.28
  5087.2  711.84  5241.4  714.73  5306.2  714.45  5320.3  715.78  5327.1  714.41
  5468.7  715.54  5476.4  715.38  5483.0  713.63  5511.5  714.44  5532.4  717.33
  5624.6  717.83  5638.9  719.23  5667.4  718.12  5702.6  719.25  5802.5  717.50
  5845.3  720.23  5851.9  721.49  5859.1  724.83  5866.2  722.58  5868.6  724.34
#Mann=5,-1,0
  4276.5    0.05       0  4289.2   0.075       0  4375.5    0.05       0
  4977.8   0.033       0  4981.8    0.05       0
Bank Sta=4977.8,4981.8
Exp/Cntr=0.3,0.1

Type RM Length L Ch R = 1,1508,635,635,635
BEGIN DESCRIPTION:
1038
END DESCRIPTION:
XS GIS Cut Line= 5
      2318485.54      7061328.26      2317896.59      7060851.49
      2317775.06      7060907.58      2317597.44      7061178.68
      2317419.79      7061234.78
#Sta/Elev= 30
  4475.9  714.97  4916.9  710.68  4999.0  708.44  5005.5  706.03  5009.9  705.70
  5010.2  705.20  5013.9  705.70  5026.3  707.70  5063.0  708.72  5221.3  710.19
  5236.9  710.16  5285.2  710.53  5290.7  707.97  5297.1  709.91  5319.1  711.10
  5403.1  710.59  5481.4  712.39  5525.8  711.77  5532.7  709.86  5538.7  711.92
  5547.8  709.49  5553.8  711.51  5568.9  710.54  5590.9  711.32  5620.2  710.96
  5626.2  712.15  5641.3  711.19  5656.4  712.73  5709.1  713.28  5877.9  713.20
#Mann=7,-1,0
  4475.9    0.05       0  4916.9    0.12       0  5009.9    0.07       0
  5013.9    0.12       0  5221.3    0.05       0  5236.9    0.12       0
  5590.9    0.05       0
Bank Sta=5009.9,5013.9
Exp/Cntr=0.3,0.1

Type RM Length L Ch R = 1,873,476,476,476
BEGIN DESCRIPTION:
1037
END DESCRIPTION:
XS GIS Cut Line= 6
      2318550.97      7061178.68      2318223.78      7060412.12
      2318130.30      7060374.72      2317831.15      7060739.31
      2317578.74      7061103.89      2317429.15      7061197.39
#Sta/Elev= 30
  4130.4  712.03  4302.5  708.85  4404.6  709.35  4451.8  708.00  4650.9  706.36
  4680.6  705.12  4838.5  705.30  4909.4  703.23  4955.3  703.84  4976.7  701.28
  4977.0  700.78  4980.7  701.28  4984.1  701.71  4990.6  704.88  5015.9  705.44
  5070.8  705.62  5175.8  706.56  5296.5  708.06  5381.8  707.65  5609.2  709.63
  5668.2  710.75  5683.0  710.02  5704.0  711.05  5796.6  711.00  5811.5  711.99
  5817.5  711.33  5933.8  712.44  5975.9  711.88  6020.0  712.88  6156.0  713.07
#Mann=9,-1,0
  4130.4    0.05       0  4302.5    0.12       0  4976.7    0.07       0
  4980.7    0.12       0  5015.9    0.05       0  5070.8    0.12       0
  5175.8    0.05       0  5609.2    0.12       0  5975.9    0.05       0
Bank Sta=4976.7,4980.7
Exp/Cntr=0.3,0.1

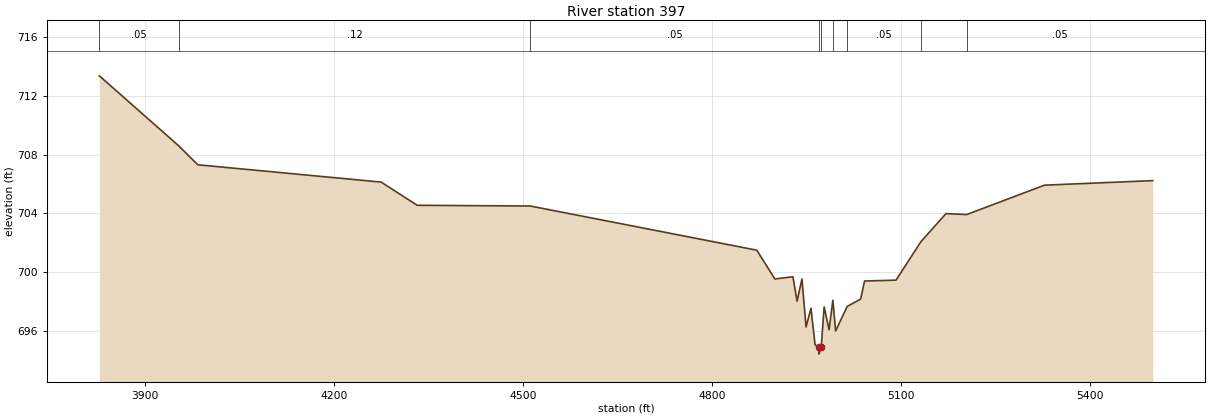
Type RM Length L Ch R = 1,397,0,0,0
BEGIN DESCRIPTION:
Elizabeth Creek Tributary 19 1.0
END DESCRIPTION:
XS GIS Cut Line= 3
      2319079.00      7060959.99      2318329.00      7060060.00
      2317929.02      7060359.98
#Sta/Elev= 30
  3827.4  713.37  3953.4  708.60  3983.6  707.31  4274.5  706.13  4331.8  704.55
  4511.3  704.50  4870.7  701.49  4899.3  699.53  4928.0  699.68  4934.5  698.02
  4942.3  699.53  4948.8  696.26  4956.6  697.54  4963.1  695.04  4968.9  694.91
  4969.2  694.41  4972.9  694.91  4977.5  697.63  4985.3  696.07  4991.3  698.08
  4995.7  695.99  5014.1  697.66  5035.4  698.16  5041.6  699.39  5091.6  699.45
  5131.0  702.07  5170.8  703.98  5203.8  703.92  5327.1  705.92  5498.9  706.23
#Mann=9,-1,0
  3827.4    0.05       0  3953.4    0.12       0  4511.3    0.05       0
  4968.9    0.07       0  4972.9    0.05       0  4991.3    0.12       0
  5014.1    0.05       0  5131.0    0.12       0  5203.8    0.05       0
Bank Sta=4968.9,4972.9
Exp/Cntr=0.3,0.1

Chan Stop Cuts=-1