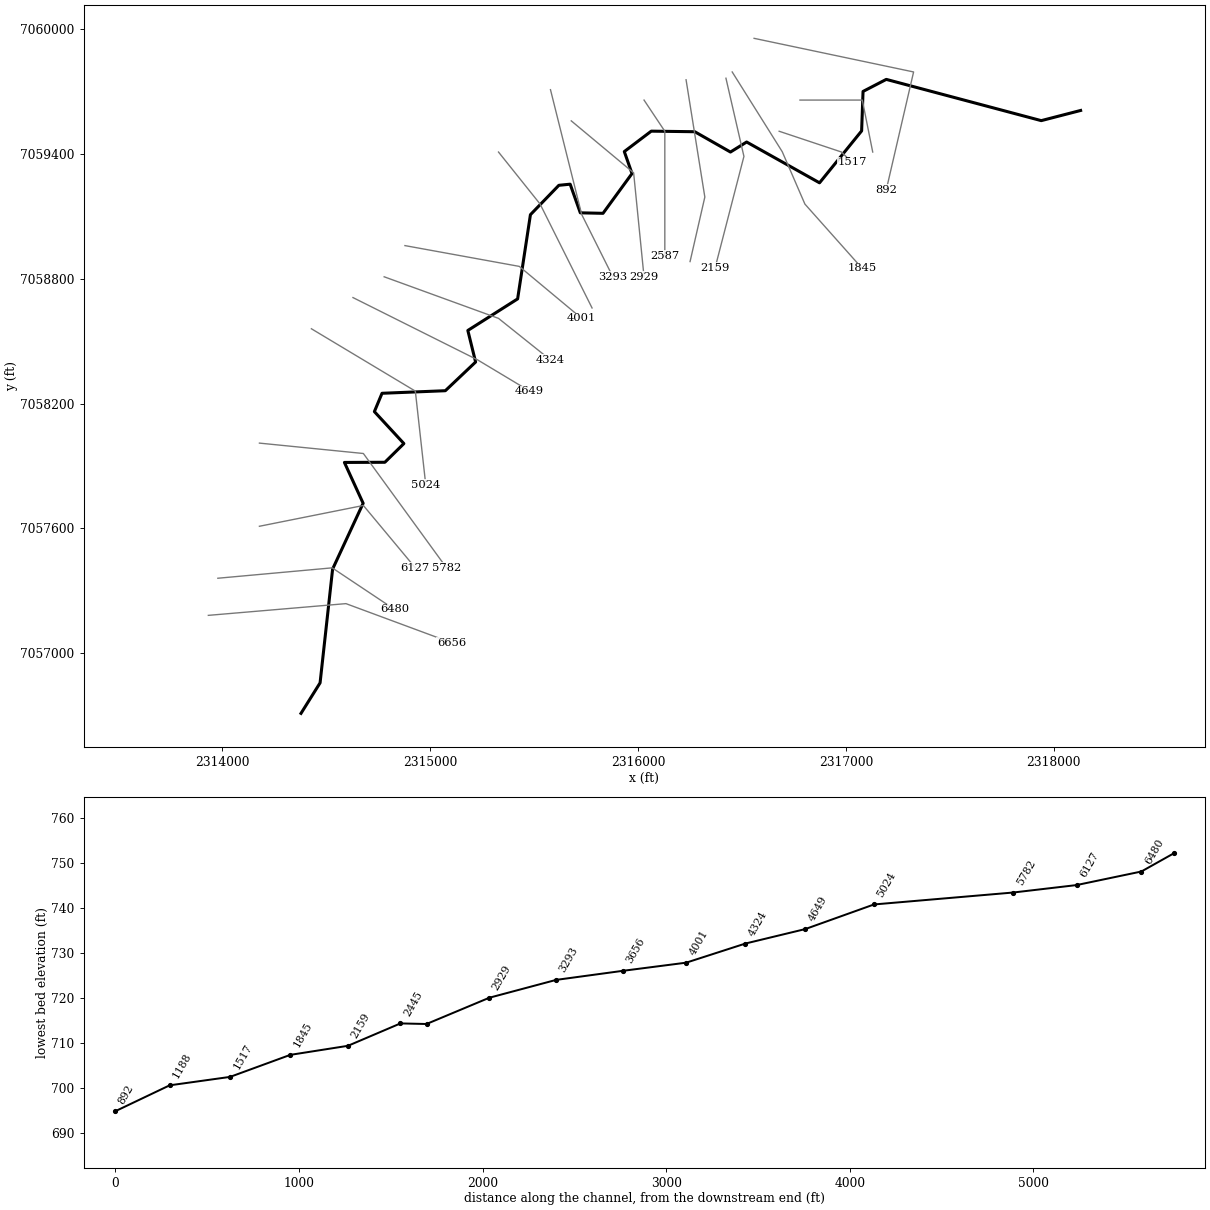
--- Elizabeth Cr Tr 20.prj (project) ---

Proj Title=Elizabeth Cr Tr 20 Base Level Engineering
Current Plan=p01
Default Exp/Contr=0.3,0.1
English Units
Geom File=g01
Flow File=f01
Plan File=p01
BEGIN DESCRIPTION:
Elizabeth Cr Tr 20
END DESCRIPTION:

--- Elizabeth Cr Tr 20.p01 (plan) ---

Plan Title=Multiple Run
Short Identifier=Multiple
Geom File=g01
Flow File=f01
Subcritical Flow
K Sum by GR= 0
Std Step Tol= 0.01
Critical Tol= 0.01
Num of Std Step Trials= 20
Max Error Tol= 0.3
Flow Tol Ratio= 0.001
Split Flow NTrial= 30
Split Flow Tol= 0.02
Split Flow Ratio= 0.02
Log Output Level= 0
Friction Slope Method= 1
Unsteady Friction Slope Method= 2
Unsteady Bridges Friction Slope Method= 1
Parabolic Critical Depth
Global Vel Dist=  1 , 1 , 1
Global Log Level= 0
CheckData=True
Encroach Param= -1, 0, 0, 0
BEGIN DESCRIPTION:
Multiple Run
END DESCRIPTION:

--- Elizabeth Cr Tr 20.f01 (steady flow) ---

Flow Title=Multiple
Number of Profiles=7
Profile Names=10-year,25-year,50-year,1pct_min,100-year,1pct_plu,500-year
River Rch & RM= Elizabeth Cr Tr ,Reach-1,6656
     594     814     995     604    1210    2410    1770
Boundary for River Rch & Prof#=Elizabeth Cr Tr ,Reach-1,1
Up Type=0
Dn Type=3
Dn Slope=0.005
Boundary for River Rch & Prof#=Elizabeth Cr Tr ,Reach-1,2
Up Type=0
Dn Type=3
Dn Slope=0.005
Boundary for River Rch & Prof#=Elizabeth Cr Tr ,Reach-1,3
Up Type=0
Dn Type=3
Dn Slope=0.005
Boundary for River Rch & Prof#=Elizabeth Cr Tr ,Reach-1,4
Up Type=0
Dn Type=3
Dn Slope=0.005
Boundary for River Rch & Prof#=Elizabeth Cr Tr ,Reach-1,5
Up Type=0
Dn Type=3
Dn Slope=0.005
Boundary for River Rch & Prof#=Elizabeth Cr Tr ,Reach-1,6
Up Type=0
Dn Type=3
Dn Slope=0.005
Boundary for River Rch & Prof#=Elizabeth Cr Tr ,Reach-1,7
Up Type=0
Dn Type=3
Dn Slope=0.005

--- Elizabeth Cr Tr 20.g01 (geometry) ---

Geom Title=Existing Conditions

River Reach=Elizabeth Cr Tr ,Reach-1
Reach XY= 30
      2314379.00      7056710.00      2314470.78      7056856.76
      2314531.07      7057404.14      2314677.90      7057720.55
      2314587.83      7057917.01      2314782.43      7057917.79
      2314873.95      7058007.70      2314731.99      7058161.47
      2314768.76      7058249.65      2315073.32      7058262.00
      2315218.89      7058400.02      2315181.50      7058551.84
      2315420.95      7058703.69      2315482.55      7059108.71
      2315619.33      7059250.03      2315673.71      7059255.41
      2315722.51      7059117.63      2315831.67      7059115.29
      2315971.17      7059306.60      2315934.11      7059412.30
      2316063.79      7059510.49      2316273.07      7059507.76
      2316444.71      7059410.03      2316522.53      7059458.29
      2316873.12      7059261.96      2317075.64      7059511.71
      2317082.46      7059701.53      2317194.20      7059759.50
      2317939.55      7059561.10      2318129.00      7059610.00

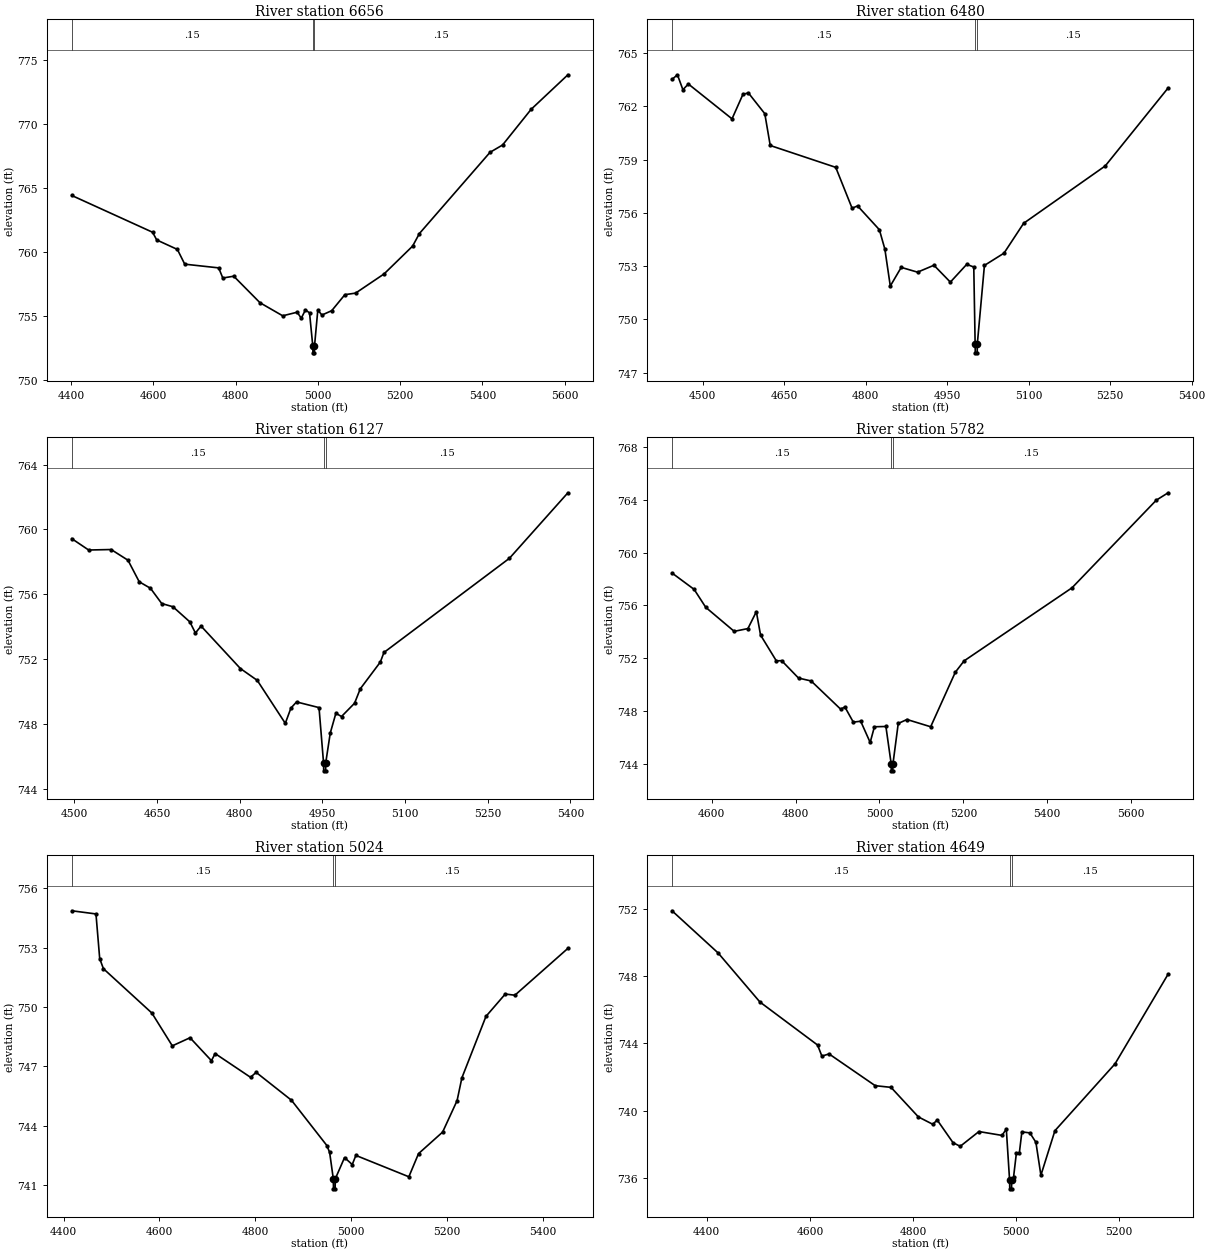
Type RM Length L Ch R = 1,6656,176,176,176
BEGIN DESCRIPTION:
1047
END DESCRIPTION:
XS GIS Cut Line= 3
      2313933.30      7057181.46      2314595.23      7057237.87
      2315102.90      7057049.85
#Sta/Elev= 30
  4402.1  764.42  4598.5  761.55  4608.5  760.95  4658.7  760.21  4676.6  759.06
  4759.1  758.77  4769.1  757.98  4795.7  758.12  4859.5  756.05  4914.7  755.03
  4949.8  755.31  4959.8  754.84  4969.9  755.49  4979.9  755.26  4987.9  752.64
  4988.2  752.14  4991.7  752.14  4991.9  752.64  5000.0  755.48  5010.0  755.09
  5033.8  755.43  5065.8  756.68  5091.8  756.80  5161.1  758.30  5230.4  760.47
  5246.9  761.45  5418.6  767.79  5449.0  768.36  5518.3  771.14  5607.8  773.84
#Mann=3,-1,0
  4402.1    0.15       0  4987.9    0.05       0  4991.9    0.15       0
Bank Sta=4987.9,4991.9
Exp/Cntr=0.3,0.1

Type RM Length L Ch R = 1,6480,353,353,353
BEGIN DESCRIPTION:
Elizabeth Creek Tributary 20 13.0
END DESCRIPTION:
XS GIS Cut Line= 3
      2313979.03      7057360.00      2314529.00      7057410.00
      2314829.01      7057209.99
#Sta/Elev= 30
  4443.8  763.51  4453.8  763.77  4463.8  762.93  4473.9  763.25  4554.2  761.29
  4574.3  762.67  4584.3  762.75  4614.5  761.58  4624.5  759.79  4745.0  758.56
  4775.1  756.26  4785.2  756.39  4825.3  755.05  4835.4  753.96  4845.4  751.88
  4865.5  752.93  4895.6  752.66  4925.7  753.05  4955.9  752.10  4986.0  753.10
  4999.0  752.95  5001.5  748.62  5001.8  748.12  5005.3  748.12  5005.5  748.62
  5018.6  753.04  5054.6  753.73  5090.7  755.41  5240.9  758.64  5356.6  763.03
#Mann=3,-1,0
  4443.8    0.15       0  5001.5    0.05       0  5005.5    0.15       0
Bank Sta=5001.5,5005.5
Exp/Cntr=0.3,0.1

Type RM Length L Ch R = 1,6127,345,345,345
BEGIN DESCRIPTION:
Elizabeth Creek Tributary 20 12.0
END DESCRIPTION:
XS GIS Cut Line= 3
      2314178.98      7057610.00      2314679.00      7057710.00
      2314928.98      7057410.03
#Sta/Elev= 30
  4495.2  759.43  4525.8  758.73  4566.6  758.76  4597.2  758.10  4617.6  756.77
  4638.0  756.37  4658.4  755.43  4678.8  755.23  4709.4  754.30  4719.6  753.61
  4729.8  754.04  4801.2  751.42  4831.8  750.69  4882.7  748.04  4892.9  748.98
  4903.1  749.36  4943.9  749.01  4952.1  745.61  4952.4  745.11  4955.9  745.11
  4956.1  745.61  4964.3  747.44  4974.5  748.66  4984.7  748.46  5008.4  749.28
  5018.8  750.17  5055.2  751.82  5061.7  752.41  5289.5  758.22  5395.6  762.26
#Mann=3,-1,0
  4495.2    0.15       0  4952.1    0.05       0  4956.1    0.15       0
Bank Sta=4952.1,4956.1
Exp/Cntr=0.3,0.1

Type RM Length L Ch R = 1,5782,758,758,758
BEGIN DESCRIPTION:
Elizabeth Creek Tributary 20 11.0
END DESCRIPTION:
XS GIS Cut Line= 3
      2314179.03      7058010.00      2314679.00      7057960.00
      2315078.98      7057410.03
#Sta/Elev= 30
  4505.6  758.45  4558.3  757.21  4586.0  755.85  4653.8  754.03  4686.5  754.24
  4706.6  755.52  4716.6  753.75  4754.3  751.79  4766.9  751.81  4807.1  750.49
  4837.2  750.27  4907.6  748.13  4917.6  748.30  4937.7  747.15  4955.3  747.22
  4977.9  745.61  4988.0  746.80  5015.4  746.82  5028.1  743.96  5028.3  743.46
  5031.8  743.46  5032.1  743.96  5044.8  747.05  5065.6  747.35  5122.1  746.80
  5180.8  750.93  5201.7  751.79  5459.0  757.33  5659.9  763.97  5688.1  764.53
#Mann=3,-1,0
  4505.6    0.15       0  5028.1    0.05       0  5032.1    0.15       0
Bank Sta=5028.1,5032.1
Exp/Cntr=0.3,0.1

Type RM Length L Ch R = 1,5024,375,375,375
BEGIN DESCRIPTION:
Elizabeth Creek Tributary 20 10.0
END DESCRIPTION:
XS GIS Cut Line= 3
      2314428.99      7058560.01      2314929.00      7058260.00
      2314979.00      7057809.98
#Sta/Elev= 30
  4416.9  754.87  4467.4  754.71  4475.2  752.45  4483.0  751.94  4584.1  749.70
  4626.8  748.04  4663.8  748.45  4708.5  747.29  4716.2  747.65  4790.1  746.45
  4801.8  746.70  4875.6  745.29  4949.5  743.00  4955.3  742.65  4963.0  741.31
  4963.3  740.81  4966.8  740.81  4967.0  741.31  4986.4  742.39  5002.5  742.04
  5010.1  742.50  5120.7  741.42  5140.9  742.59  5191.2  743.68  5221.4  745.27
  5231.4  746.42  5281.7  749.53  5322.0  750.66  5342.1  750.60  5452.8  752.97
#Mann=3,-1,0
  4416.9    0.15       0  4963.0    0.05       0  4967.0    0.15       0
Bank Sta=4963,4967
Exp/Cntr=0.3,0.1

Type RM Length L Ch R = 1,4649,325,325,325
BEGIN DESCRIPTION:
Elizabeth Creek Tributary 20 9.0
END DESCRIPTION:
XS GIS Cut Line= 3
      2314629.02      7058709.99      2315229.00      7058410.00
      2315478.96      7058260.03
#Sta/Elev= 30
  4332.6  751.89  4422.0  749.38  4503.1  746.46  4614.9  743.90  4623.3  743.24
  4637.2  743.37  4726.7  741.48  4757.4  741.38  4810.5  739.62  4838.5  739.18
  4846.9  739.44  4877.6  738.09  4891.6  737.87  4927.9  738.75  4972.7  738.52
  4981.0  738.90  4987.4  735.84  4987.7  735.34  4991.2  735.34  4991.4  735.84
  4995.0  736.02  5000.6  737.48  5006.3  737.48  5011.2  738.73  5026.7  738.67
  5038.4  738.11  5048.1  736.15  5075.3  738.80  5191.9  742.78  5294.9  748.12
#Mann=3,-1,0
  4332.6    0.15       0  4987.4    0.05       0  4991.4    0.15       0
Bank Sta=4987.4,4991.4
Exp/Cntr=0.3,0.1

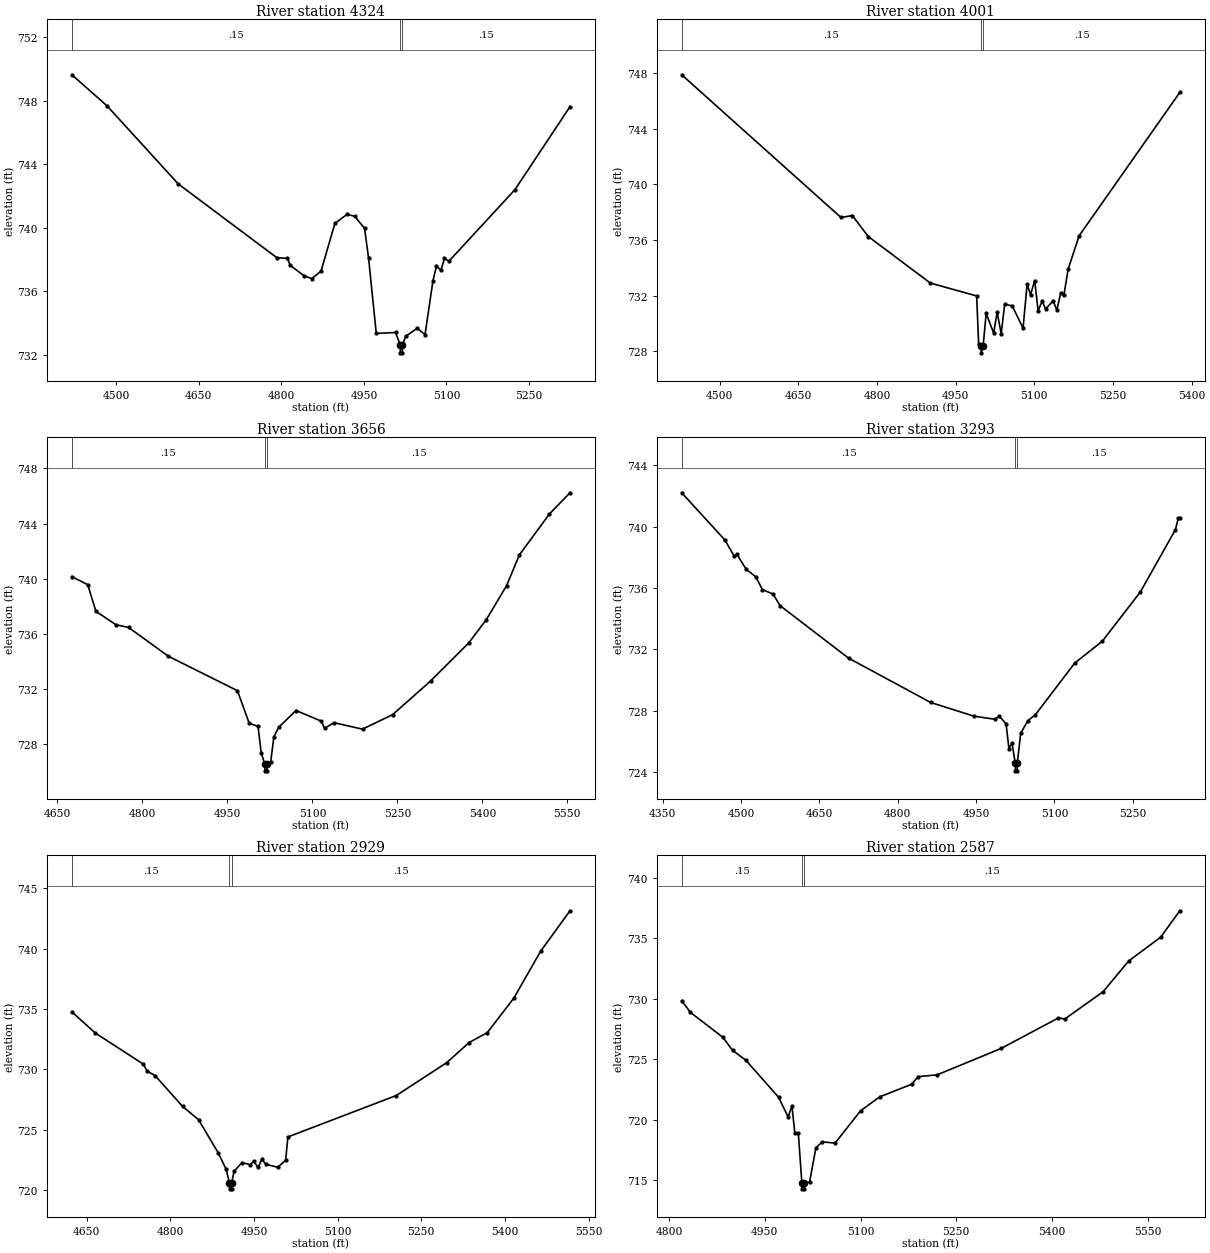
Type RM Length L Ch R = 1,4324,323,323,323
BEGIN DESCRIPTION:
Elizabeth Creek Tributary 20 8.0
END DESCRIPTION:
XS GIS Cut Line= 3
      2314779.02      7058809.99      2315329.00      7058610.00
      2315579.03      7058409.98
#Sta/Elev= 30
  4419.2  749.63  4483.0  747.68  4612.7  742.76  4791.6  738.13  4810.9  738.08
  4816.2  737.64  4841.5  736.98  4855.4  736.81  4872.1  737.28  4897.3  740.28
  4919.3  740.85  4933.3  740.73  4951.2  739.97  4958.5  738.11  4972.5  733.36
  5007.6  733.42  5016.0  732.64  5016.3  732.14  5019.8  732.14  5020.0  732.64
  5026.0  733.18  5046.8  733.68  5061.2  733.29  5075.6  736.68  5082.0  737.60
  5090.1  737.33  5096.5  738.09  5104.5  737.90  5224.5  742.40  5324.6  747.62
#Mann=3,-1,0
  4419.2    0.15       0  5016.0    0.05       0  5020.0    0.15       0
Bank Sta=5016,5020
Exp/Cntr=0.3,0.1

Type RM Length L Ch R = 1,4001,345,345,345
BEGIN DESCRIPTION:
Elizabeth Creek Tributary 20 7.0
END DESCRIPTION:
XS GIS Cut Line= 3
      2314878.96      7058960.01      2315429.00      7058860.00
      2315729.03      7058609.98
#Sta/Elev= 30
  4427.7  747.88  4731.4  737.62  4753.0  737.76  4783.5  736.25  4901.6  732.91
  4990.0  731.98  4993.9  728.52  4998.4  728.39  4998.7  727.89  5002.4  728.39
  5008.2  730.72  5022.5  729.31  5029.1  730.81  5036.9  729.26  5043.4  731.38
  5057.7  731.27  5078.5  729.67  5086.3  732.83  5092.8  732.06  5100.7  733.09
  5107.2  730.93  5115.0  731.60  5121.5  731.05  5135.8  731.62  5143.0  730.96
  5150.1  732.17  5156.6  732.08  5164.4  733.89  5185.3  736.30  5377.3  746.61
#Mann=3,-1,0
  4427.7    0.15       0  4998.4    0.05       0  5002.4    0.15       0
Bank Sta=4998.4,5002.4
Exp/Cntr=0.3,0.1

Type RM Length L Ch R = 1,3656,363,363,363
BEGIN DESCRIPTION:
Elizabeth Creek Tributary 20 6.0
END DESCRIPTION:
XS GIS Cut Line= 3
      2315328.99      7059410.02      2315529.00      7059160.00
      2315779.00      7058660.00
#Sta/Elev= 30
  4675.4  740.15  4703.4  739.57  4717.8  737.64  4753.1  736.67  4775.5  736.47
  4845.9  734.38  4967.6  731.89  4988.4  729.53  5004.0  729.30  5009.6  727.37
  5015.9  726.58  5016.2  726.08  5019.7  726.08  5019.9  726.58  5026.3  726.71
  5031.9  728.53  5040.3  729.23  5071.0  730.45  5115.8  729.68  5121.4  729.16
  5138.1  729.57  5188.4  729.10  5241.5  730.15  5308.6  732.59  5375.7  735.34
  5406.5  737.01  5442.8  739.50  5465.2  741.72  5518.3  744.69  5554.6  746.23
#Mann=3,-1,0
  4675.4    0.15       0  5015.9    0.05       0  5019.9    0.15       0
Bank Sta=5015.9,5019.9
Exp/Cntr=0.3,0.1

Type RM Length L Ch R = 1,3293,364,364,364
BEGIN DESCRIPTION:
Elizabeth Creek Tributary 20 5.0
END DESCRIPTION:
XS GIS Cut Line= 3
      2315579.00      7059709.99      2315729.00      7059110.00
      2315879.02      7058809.97
#Sta/Elev= 30
  4386.2  742.20  4468.7  739.13  4486.7  738.07  4491.8  738.20  4509.9  737.20
  4527.9  736.73  4540.8  735.89  4561.4  735.59  4574.3  734.85  4705.7  731.42
  4862.9  728.53  4945.4  727.64  4986.6  727.43  4994.3  727.65  5007.5  727.13
  5013.0  725.48  5018.6  725.91  5025.0  724.57  5025.3  724.07  5028.8  724.07
  5029.0  724.57  5035.4  726.52  5049.4  727.35  5063.4  727.72  5138.8  731.09
  5191.9  732.53  5264.6  735.73  5331.7  739.79  5337.3  740.54  5340.1  740.54
#Mann=3,-1,0
  4386.2    0.15       0  5025.0    0.05       0  5029.0    0.15       0
Bank Sta=5025,5029
Exp/Cntr=0.3,0.1

Type RM Length L Ch R = 1,2929,342,342,342
BEGIN DESCRIPTION:
Elizabeth Creek Tributary 20 4.0
END DESCRIPTION:
XS GIS Cut Line= 3
      2315679.00      7059560.00      2315979.00      7059310.00
      2316029.00      7058810.00
#Sta/Elev= 30
  4623.7  734.77  4666.0  733.01  4751.9  730.44  4758.4  729.87  4772.7  729.50
  4822.2  726.94  4850.8  725.84  4886.0  723.10  4900.3  721.73  4906.1  720.61
  4906.4  720.11  4909.9  720.11  4910.1  720.61  4914.6  721.58  4928.9  722.29
  4943.3  722.11  4949.8  722.38  4957.6  721.88  4964.1  722.55  4971.9  722.14
  4992.7  721.90  5007.0  722.48  5011.0  724.41  5205.2  727.84  5295.6  730.56
  5335.8  732.23  5368.5  733.05  5416.2  735.92  5463.9  739.78  5516.7  743.15
#Mann=3,-1,0
  4623.7    0.15       0  4906.1    0.05       0  4910.1    0.15       0
Bank Sta=4906.1,4910.1
Exp/Cntr=0.3,0.1

Type RM Length L Ch R = 1,2587,142,142,142
BEGIN DESCRIPTION:
Elizabeth Creek Tributary 20 3.0
END DESCRIPTION:
XS GIS Cut Line= 3
      2316029.03      7059659.96      2316129.00      7059510.00
      2316129.00      7058910.03
#Sta/Elev= 30
  4819.9  729.85  4833.4  728.88  4884.5  726.81  4899.5  725.74  4920.5  724.91
  4971.6  721.86  4986.6  720.23  4992.6  721.14  4997.1  718.89  5002.6  718.89
  5008.1  714.78  5008.4  714.28  5011.9  714.28  5012.1  714.78  5020.1  714.82
  5030.1  717.67  5040.1  718.17  5060.1  718.06  5100.1  720.74  5130.1  721.89
  5180.1  722.93  5190.1  723.56  5220.1  723.71  5320.1  725.89  5410.1  728.42
  5420.1  728.33  5480.1  730.59  5520.1  733.13  5570.1  735.09  5600.1  737.28
#Mann=3,-1,0
  4819.9    0.15       0  5008.1    0.05       0  5012.1    0.15       0
Bank Sta=5008.1,5012.1
Exp/Cntr=0.3,0.1

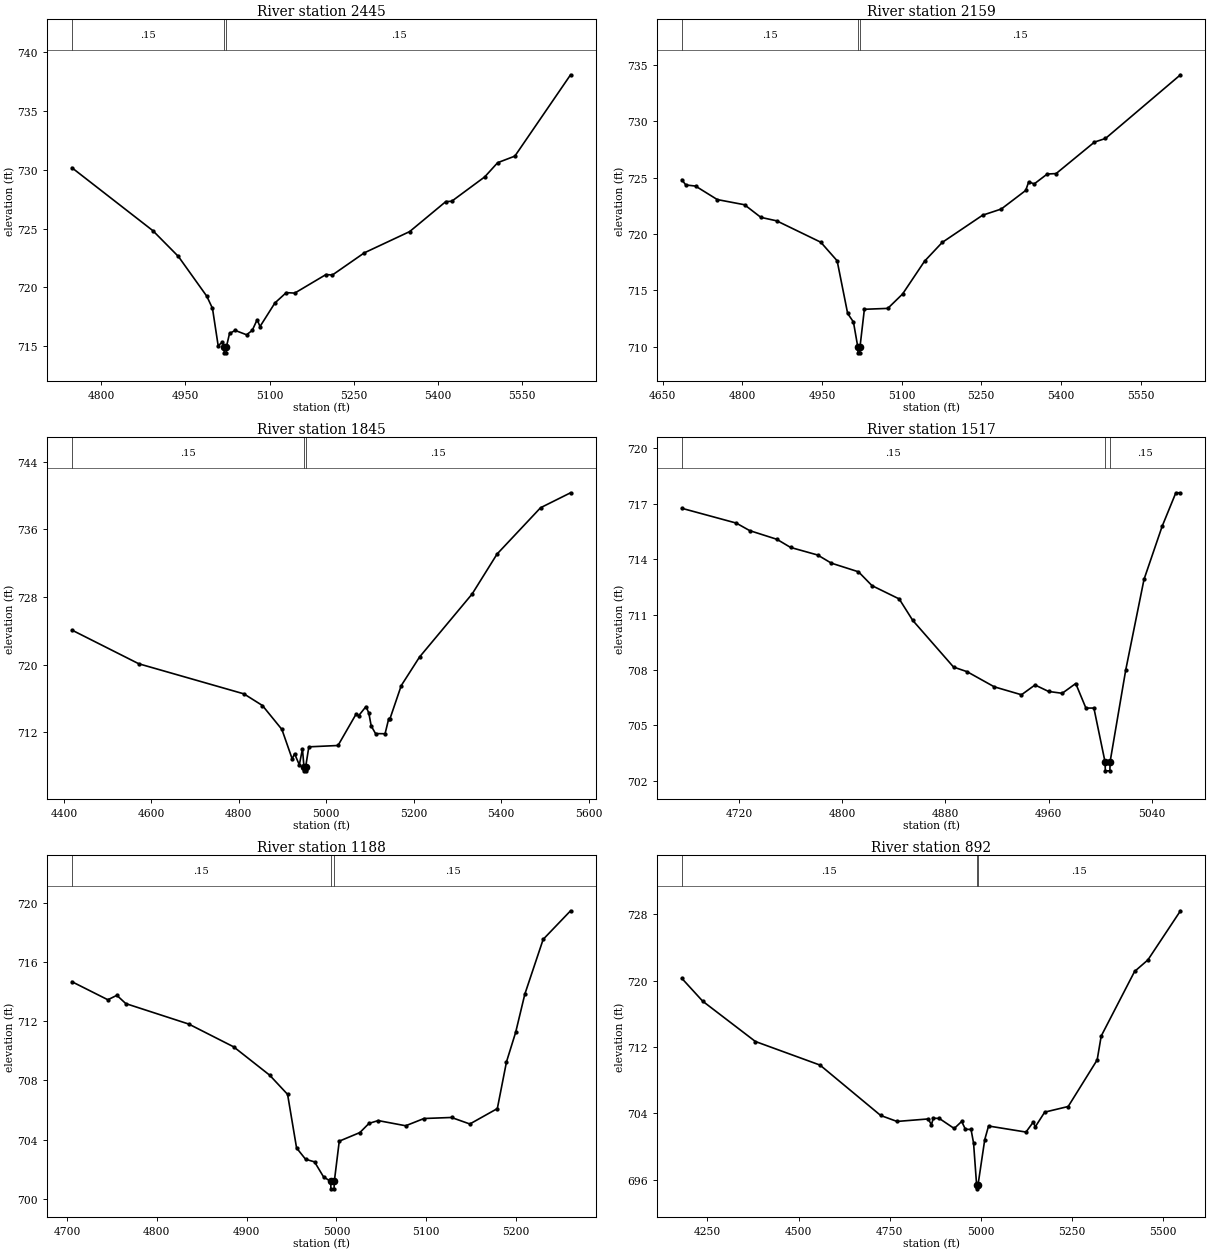
Type RM Length L Ch R = 1,2445,286,286,286
BEGIN DESCRIPTION:
1046
END DESCRIPTION:
XS GIS Cut Line= 3
      2316231.19      7059757.64      2316321.45      7059193.50
      2316250.40      7058883.14
#Sta/Elev= 30
  4747.4  730.18  4891.8  724.82  4937.4  722.62  4988.1  719.23  4998.2  718.20
  5008.3  715.03  5015.9  715.31  5019.0  714.91  5019.2  714.41  5022.7  714.41
  5023.0  714.91  5028.6  716.06  5038.7  716.32  5059.0  715.95  5069.1  716.32
  5077.9  717.23  5083.0  716.65  5109.6  718.66  5129.8  719.54  5145.0  719.50
  5200.7  721.08  5212.1  721.04  5269.1  722.93  5350.0  724.74  5414.6  727.30
  5424.9  727.32  5483.9  729.40  5507.0  730.61  5537.7  731.17  5637.1  738.10
#Mann=3,-1,0
  4747.4    0.15       0  5019.0    0.05       0  5023.0    0.15       0
Bank Sta=5019,5023
Exp/Cntr=0.3,0.1

Type RM Length L Ch R = 1,2159,314,314,314
BEGIN DESCRIPTION:
1045
END DESCRIPTION:
XS GIS Cut Line= 3
      2316423.00      7059765.11      2316509.49      7059389.06
      2316370.83      7058853.18
#Sta/Elev= 30
  4685.9  724.83  4693.3  724.36  4711.7  724.26  4752.7  723.06  4804.0  722.60
  4834.8  721.48  4864.6  721.17  4947.7  719.27  4978.5  717.62  4998.3  712.94
  5009.2  712.18  5017.5  709.94  5017.8  709.44  5021.3  709.44  5021.5  709.94
  5029.8  713.31  5073.9  713.39  5101.8  714.67  5143.1  717.58  5176.4  719.25
  5252.5  721.67  5287.7  722.22  5333.7  723.87  5339.4  724.64  5349.7  724.45
  5374.3  725.33  5391.0  725.37  5463.3  728.17  5484.0  728.49  5625.3  734.15
#Mann=3,-1,0
  4685.9    0.15       0  5017.5    0.05       0  5021.5    0.15       0
Bank Sta=5017.5,5021.5
Exp/Cntr=0.3,0.1

Type RM Length L Ch R = 1,1845,328,328,328
BEGIN DESCRIPTION:
1044
END DESCRIPTION:
XS GIS Cut Line= 4
      2316453.10      7059795.20      2316693.77      7059411.63
      2316802.83      7059159.65      2317077.39      7058851.25
#Sta/Elev= 30
  4418.4  724.09  4571.4  720.10  4811.7  716.54  4854.1  715.16  4898.6  712.33
  4922.1  708.84  4927.5  709.46  4938.4  708.14  4945.6  710.01  4949.0  707.93
  4949.3  707.43  4952.8  707.43  4953.0  707.93  4960.2  710.27  5026.9  710.43
  5068.4  714.16  5073.9  713.94  5090.9  715.04  5097.4  714.26  5102.8  712.74
  5112.7  711.84  5134.5  711.82  5142.9  713.61  5145.8  713.61  5171.5  717.52
  5213.3  720.90  5333.7  728.37  5390.6  733.09  5490.1  738.57  5558.7  740.34
#Mann=3,-1,0
  4418.4    0.15       0  4949.0    0.05       0  4953.0    0.15       0
Bank Sta=4949,4953
Exp/Cntr=0.3,0.1

Type RM Length L Ch R = 1,1517,329,329,329
BEGIN DESCRIPTION:
Elizabeth Creek Tributary 20 2.0
END DESCRIPTION:
XS GIS Cut Line= 3
      2316678.97      7059510.01      2316979.00      7059410.00
      2317029.02      7059359.98
#Sta/Elev= 30
  4675.4  716.76  4717.6  715.96  4728.1  715.55  4749.2  715.08  4759.8  714.64
  4780.8  714.23  4791.4  713.79  4812.5  713.32  4823.0  712.57  4844.1  711.85
  4854.6  710.69  4886.3  708.16  4896.8  707.91  4917.9  707.09  4939.0  706.66
  4949.5  707.19  4960.0  706.84  4970.6  706.74  4981.1  707.27  4989.0  705.94
  4995.2  705.94  5003.8  703.04  5004.1  702.54  5007.6  702.54  5007.8  703.04
  5019.9  708.00  5034.1  712.91  5048.2  715.79  5058.8  717.60  5062.4  717.60
#Mann=3,-1,0
  4675.4    0.15       0  5003.8    0.05       0  5007.8    0.15       0
Bank Sta=5003.8,5007.8
Exp/Cntr=0.3,0.1

Type RM Length L Ch R = 1,1188,296,296,296
BEGIN DESCRIPTION:
Elizabeth Creek Tributary 20 1.0
END DESCRIPTION:
XS GIS Cut Line= 3
      2316779.01      7059660.00      2317079.00      7059660.00
      2317128.99      7059410.04
#Sta/Elev= 30
  4705.6  714.66  4745.6  713.44  4755.6  713.74  4765.6  713.18  4835.6  711.80
  4885.6  710.26  4925.6  708.35  4945.6  707.05  4955.6  703.43  4965.6  702.67
  4975.6  702.49  4985.6  701.48  4993.6  701.17  4993.8  700.67  4997.3  700.67
  4997.6  701.17  5003.1  703.89  5026.0  704.47  5036.2  705.09  5046.4  705.28
  5077.0  704.93  5097.4  705.42  5128.0  705.49  5148.4  705.05  5179.0  706.09
  5189.2  709.25  5199.4  711.24  5209.6  713.82  5230.0  717.52  5260.5  719.45
#Mann=3,-1,0
  4705.6    0.15       0  4993.6    0.05       0  4997.6    0.15       0
Bank Sta=4993.6,4997.6
Exp/Cntr=0.3,0.1

Type RM Length L Ch R = 1,892,0,0,0
BEGIN DESCRIPTION:
1043
END DESCRIPTION:
XS GIS Cut Line= 3
      2316558.38      7059956.95      2317325.59      7059795.23
      2317193.98      7059227.46
#Sta/Elev= 30
  4180.1  720.28  4237.5  717.52  4381.8  712.67  4558.9  709.83  4725.2  703.76
  4769.9  703.04  4855.2  703.34  4864.3  702.65  4869.5  703.43  4885.9  703.40
  4926.8  702.19  4947.2  703.04  4957.4  702.10  4972.9  702.07  4979.8  700.44
  4988.1  695.42  4988.3  694.92  4992.1  695.42  5010.5  700.86  5020.9  702.49
  5123.5  701.76  5143.6  702.97  5148.8  702.38  5174.8  704.16  5239.2  704.84
  5318.6  710.45  5329.7  713.33  5421.2  721.11  5457.7  722.50  5547.0  728.42
#Mann=3,-1,0
  4180.1    0.15       0  4988.1    0.05       0  4992.1    0.15       0
Bank Sta=4988.1,4992.1
Exp/Cntr=0.3,0.1

Chan Stop Cuts=-1