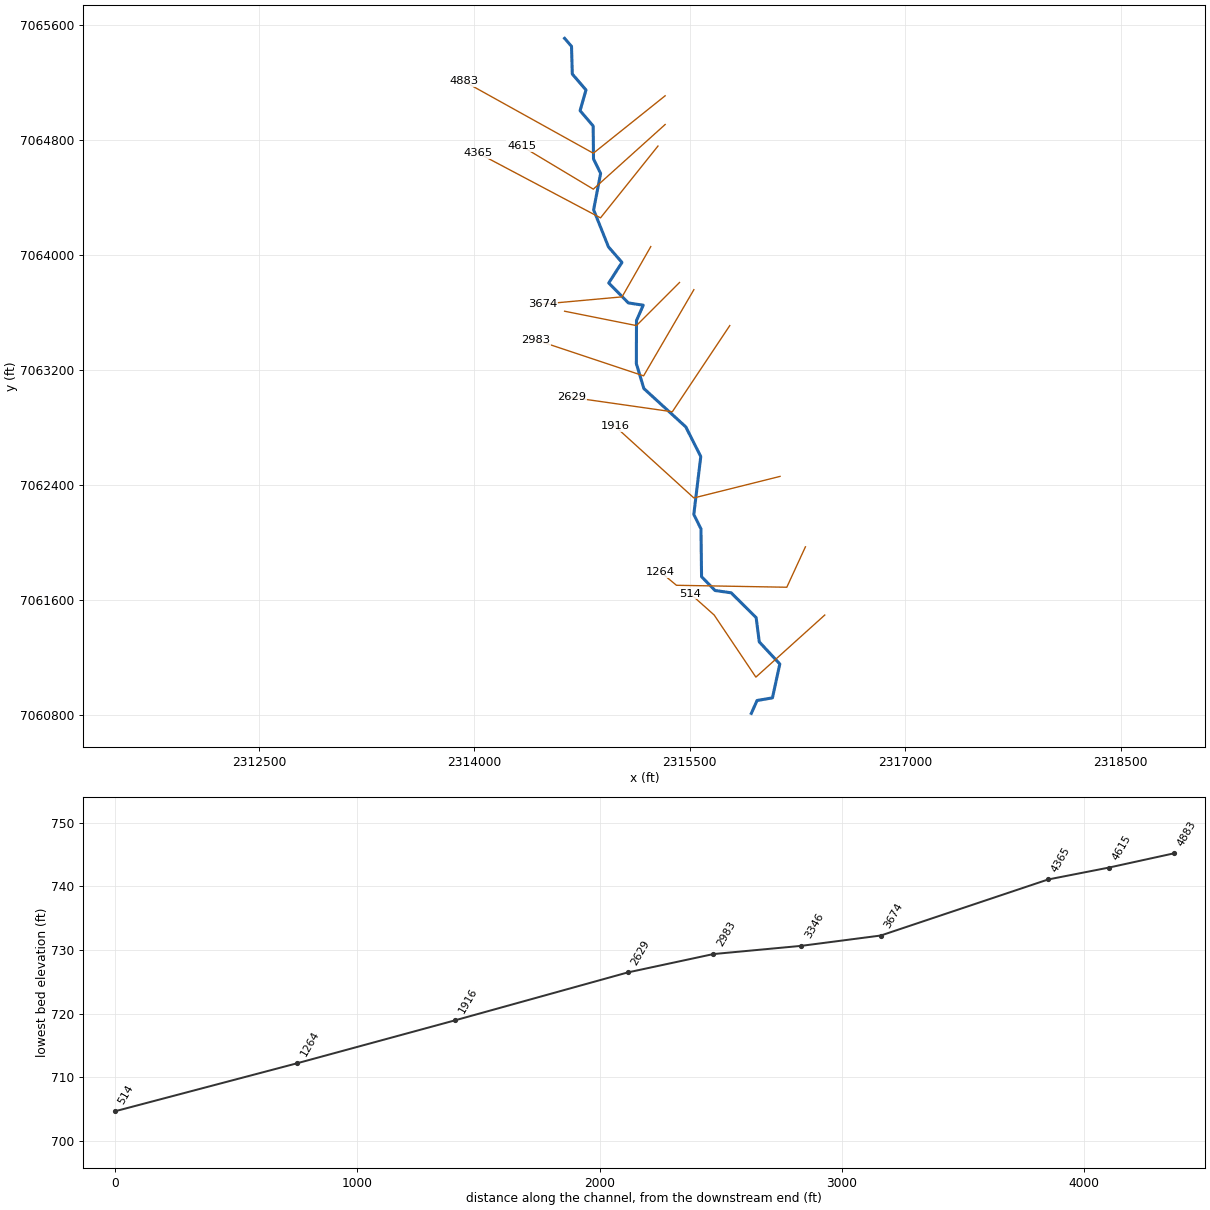
--- Elizabeth Cr Tr 21.prj (project) ---

Proj Title=Elizabeth Cr Tr 21 Base Level Engineering
Current Plan=p01
Default Exp/Contr=0.3,0.1
English Units
Geom File=g01
Flow File=f01
Plan File=p01
BEGIN DESCRIPTION:
Elizabeth Cr Tr 21
END DESCRIPTION:

--- Elizabeth Cr Tr 21.p01 (plan) ---

Plan Title=Multiple Run
Short Identifier=Multiple
Geom File=g01
Flow File=f01
Subcritical Flow
K Sum by GR= 0
Std Step Tol= 0.01
Critical Tol= 0.01
Num of Std Step Trials= 20
Max Error Tol= 0.3
Flow Tol Ratio= 0.001
Split Flow NTrial= 30
Split Flow Tol= 0.02
Split Flow Ratio= 0.02
Log Output Level= 0
Friction Slope Method= 1
Unsteady Friction Slope Method= 2
Unsteady Bridges Friction Slope Method= 1
Parabolic Critical Depth
Global Vel Dist=  1 , 1 , 1
Global Log Level= 0
CheckData=True
Encroach Param= -1, 0, 0, 0
BEGIN DESCRIPTION:
Multiple Run
END DESCRIPTION:

--- Elizabeth Cr Tr 21.f01 (steady flow) ---

Flow Title=Multiple
Number of Profiles=7
Profile Names=10-year,25-year,50-year,1pct_min,100-year,1pct_plu,500-year
River Rch & RM= Elizabeth Cr Tr ,Reach-1,4883
     240     309     364     213     425     849     582
River Rch & RM= Elizabeth Cr Tr ,Reach-1,3674
     520     708     863     522    1040    2080    1520
Boundary for River Rch & Prof#=Elizabeth Cr Tr ,Reach-1,1
Up Type=0
Dn Type=3
Dn Slope=0.005
Boundary for River Rch & Prof#=Elizabeth Cr Tr ,Reach-1,2
Up Type=0
Dn Type=3
Dn Slope=0.005
Boundary for River Rch & Prof#=Elizabeth Cr Tr ,Reach-1,3
Up Type=0
Dn Type=3
Dn Slope=0.005
Boundary for River Rch & Prof#=Elizabeth Cr Tr ,Reach-1,4
Up Type=0
Dn Type=3
Dn Slope=0.005
Boundary for River Rch & Prof#=Elizabeth Cr Tr ,Reach-1,5
Up Type=0
Dn Type=3
Dn Slope=0.005
Boundary for River Rch & Prof#=Elizabeth Cr Tr ,Reach-1,6
Up Type=0
Dn Type=3
Dn Slope=0.005
Boundary for River Rch & Prof#=Elizabeth Cr Tr ,Reach-1,7
Up Type=0
Dn Type=3
Dn Slope=0.005

--- Elizabeth Cr Tr 21.g01 (geometry) ---

Geom Title=Existing Conditions

River Reach=Elizabeth Cr Tr ,Reach-1
Reach XY= 30
      2314629.00      7065510.00      2314677.11      7065454.22
      2314682.55      7065261.47      2314777.90      7065150.36
      2314736.81      7065006.59      2314827.94      7064899.57
      2314830.22      7064670.50      2314879.76      7064569.13
      2314830.95      7064315.72      2314934.54      7064057.58
      2315028.34      7063949.86      2314936.19      7063806.59
      2315072.86      7063667.81      2315176.51      7063651.85
      2315129.54      7063544.81      2315128.57      7063244.82
      2315180.74      7063071.87      2315473.05      7062804.24
      2315577.04      7062598.03      2315528.57      7062194.82
      2315578.48      7062094.78      2315582.53      7061761.45
      2315676.56      7061665.52      2315788.79      7061649.48
      2315962.57      7061476.76      2315984.47      7061307.55
      2316127.38      7061153.97      2316076.06      7060917.97
      2315968.95      7060899.72      2315929.00      7060810.00

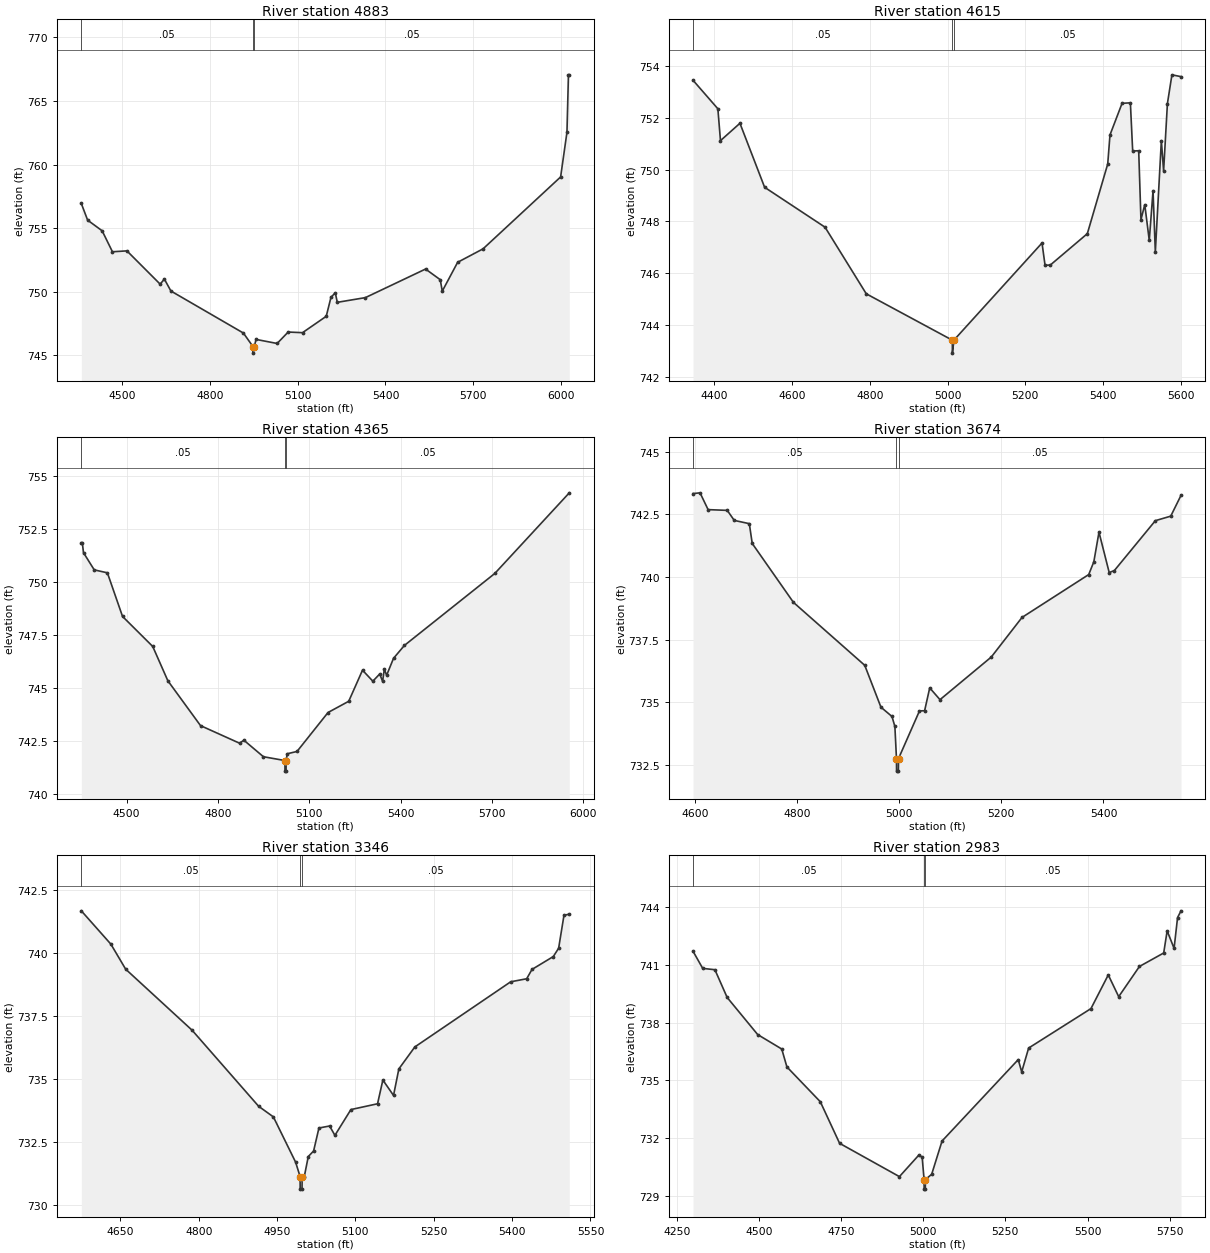
Type RM Length L Ch R = 1,4883,268,268,268
BEGIN DESCRIPTION:
Elizabeth Creek Tributary 21_1 3.0
END DESCRIPTION:
XS GIS Cut Line= 3
      2315329.02      7065110.02      2314829.00      7064710.00
      2313929.00      7065210.00
#Sta/Elev= 30
  4359.2  756.93  4380.8  755.62  4430.5  754.78  4465.7  753.13  4515.3  753.20
  4629.0  750.58  4643.4  750.98  4665.8  750.04  4913.9  746.73  4947.1  745.65
  4947.4  745.15  4951.1  745.65  4957.1  746.23  5029.3  745.91  5067.0  746.81
  5116.2  746.76  5197.4  748.05  5213.5  749.54  5228.3  749.90  5235.2  749.15
  5331.3  749.52  5537.2  751.77  5587.5  750.93  5594.4  750.03  5647.0  752.30
  5734.0  753.36  5999.4  759.02  6021.1  762.54  6026.2  767.06  6029.1  767.06
#Mann=3,-1,0
  4359.2    0.05       0  4947.1   0.033       0  4951.1    0.05       0
Bank Sta=4947.1,4951.1
Exp/Cntr=0.3,0.1

Type RM Length L Ch R = 1,4615,250,250,250
BEGIN DESCRIPTION:
Elizabeth Creek Tributary 21_1 2.0
END DESCRIPTION:
XS GIS Cut Line= 3
      2315328.98      7064909.98      2314829.00      7064460.00
      2314328.96      7064760.03
#Sta/Elev= 30
  4344.8  753.45  4408.7  752.35  4415.4  751.12  4465.5  751.79  4529.0  749.32
  4684.5  747.78  4790.6  745.21  5012.1  743.42  5012.3  742.92  5016.1  743.42
  5242.9  747.17  5250.7  746.31  5264.3  746.32  5359.5  747.53  5412.0  750.22
  5417.8  751.34  5448.9  752.56  5470.3  752.58  5476.2  750.72  5491.7  750.73
  5497.5  748.07  5507.3  748.65  5518.9  747.27  5528.6  749.19  5534.5  746.82
  5550.0  751.12  5555.8  749.95  5565.6  752.55  5577.2  753.66  5600.6  753.59
#Mann=3,-1,0
  4344.8    0.05       0  5012.1    0.04       0  5016.1    0.05       0
Bank Sta=5012.1,5016.1
Exp/Cntr=0.3,0.1

Type RM Length L Ch R = 1,4365,691,691,691
BEGIN DESCRIPTION:
Elizabeth Creek Tributary 21_1 1.0
END DESCRIPTION:
XS GIS Cut Line= 3
      2315278.99      7064759.99      2314879.00      7064260.00
      2314028.97      7064710.01
#Sta/Elev= 30
  4351.6  751.85  4354.8  751.85  4358.8  751.38  4394.0  750.57  4437.2  750.43
  4486.9  748.37  4586.1  746.95  4635.7  745.33  4743.0  743.21  4871.0  742.38
  4885.4  742.52  4949.5  741.74  5020.1  741.56  5020.3  741.06  5023.8  741.06
  5024.1  741.56  5027.7  741.88  5059.8  741.99  5161.6  743.83  5229.5  744.36
  5274.8  745.83  5308.7  745.31  5331.3  745.65  5340.8  745.30  5346.4  745.88
  5354.0  745.59  5376.6  746.39  5412.4  747.00  5709.1  750.40  5953.7  754.21
#Mann=3,-1,0
  4351.6    0.05       0  5020.1    0.04       0  5024.1    0.05       0
Bank Sta=5020.1,5024.1
Exp/Cntr=0.3,0.1

Type RM Length L Ch R = 1,3674,328,328,328
BEGIN DESCRIPTION:
Elizabeth Creek Tributary 21 6.0
END DESCRIPTION:
XS GIS Cut Line= 3
      2315229.02      7064060.03      2315029.00      7063710.00
      2314479.02      7063660.00
#Sta/Elev= 30
  4596.4  743.33  4610.1  743.36  4625.9  742.69  4663.4  742.66  4677.1  742.26
  4706.6  742.13  4712.3  741.34  4793.0  738.99  4932.6  736.48  4964.3  734.81
  4985.9  734.44  4991.6  734.04  4994.7  732.76  4994.9  732.26  4998.4  732.26
  4998.7  732.76  5039.7  734.66  5049.8  734.67  5059.8  735.58  5079.9  735.11
  5180.3  736.81  5240.5  738.39  5371.1  740.10  5381.1  740.61  5391.2  741.79
  5411.2  740.18  5421.3  740.26  5501.6  742.25  5531.7  742.43  5551.8  743.26
#Mann=3,-1,0
  4596.4    0.05       0  4994.7    0.04       0  4998.7    0.05       0
Bank Sta=4994.7,4998.7
Exp/Cntr=0.3,0.1

Type RM Length L Ch R = 1,3346,363,363,363
BEGIN DESCRIPTION:
Elizabeth Creek Tributary 21 5.0
END DESCRIPTION:
XS GIS Cut Line= 3
      2315429.03      7063810.03      2315129.00      7063510.00
      2314629.01      7063610.00
#Sta/Elev= 30
  4575.3  741.66  4631.9  740.34  4660.2  739.35  4787.5  736.93  4914.8  733.92
  4943.0  733.50  4985.5  731.71  4994.1  731.14  4994.3  730.64  4997.8  730.64
  4998.1  731.14  5002.2  731.14  5009.8  731.93  5020.0  732.15  5030.2  733.06
  5050.6  733.14  5060.8  732.77  5091.4  733.79  5142.4  734.02  5152.6  734.96
  5173.0  734.35  5183.2  735.40  5213.8  736.27  5397.3  738.85  5427.9  738.97
  5438.1  739.34  5478.9  739.85  5489.1  740.18  5499.3  741.48  5509.5  741.53
#Mann=3,-1,0
  4575.3    0.05       0  4994.1    0.04       0  4998.1    0.05       0
Bank Sta=4994.1,4998.1
Exp/Cntr=0.3,0.1

Type RM Length L Ch R = 1,2983,354,354,354
BEGIN DESCRIPTION:
Elizabeth Creek Tributary 21 4.0
END DESCRIPTION:
XS GIS Cut Line= 3
      2315529.01      7063760.02      2315179.00      7063160.00
      2314429.01      7063410.00
#Sta/Elev= 30
  4299.4  741.71  4328.8  740.82  4366.0  740.75  4403.2  739.31  4496.2  737.38
  4569.4  736.63  4585.1  735.70  4686.8  733.89  4745.5  731.73  4927.5  730.00
  4986.2  731.11  4996.7  731.02  5002.6  729.85  5002.8  729.35  5006.3  729.35
  5006.6  729.85  5025.7  730.12  5057.3  731.85  5289.2  736.08  5299.7  735.44
  5320.8  736.68  5510.5  738.73  5563.2  740.48  5594.9  739.35  5658.1  740.92
  5731.9  741.62  5742.4  742.77  5763.5  741.86  5774.1  743.46  5784.6  743.81
#Mann=3,-1,0
  4299.4    0.05       0  5002.6   0.033       0  5006.6    0.05       0
Bank Sta=5002.6,5006.6
Exp/Cntr=0.3,0.1

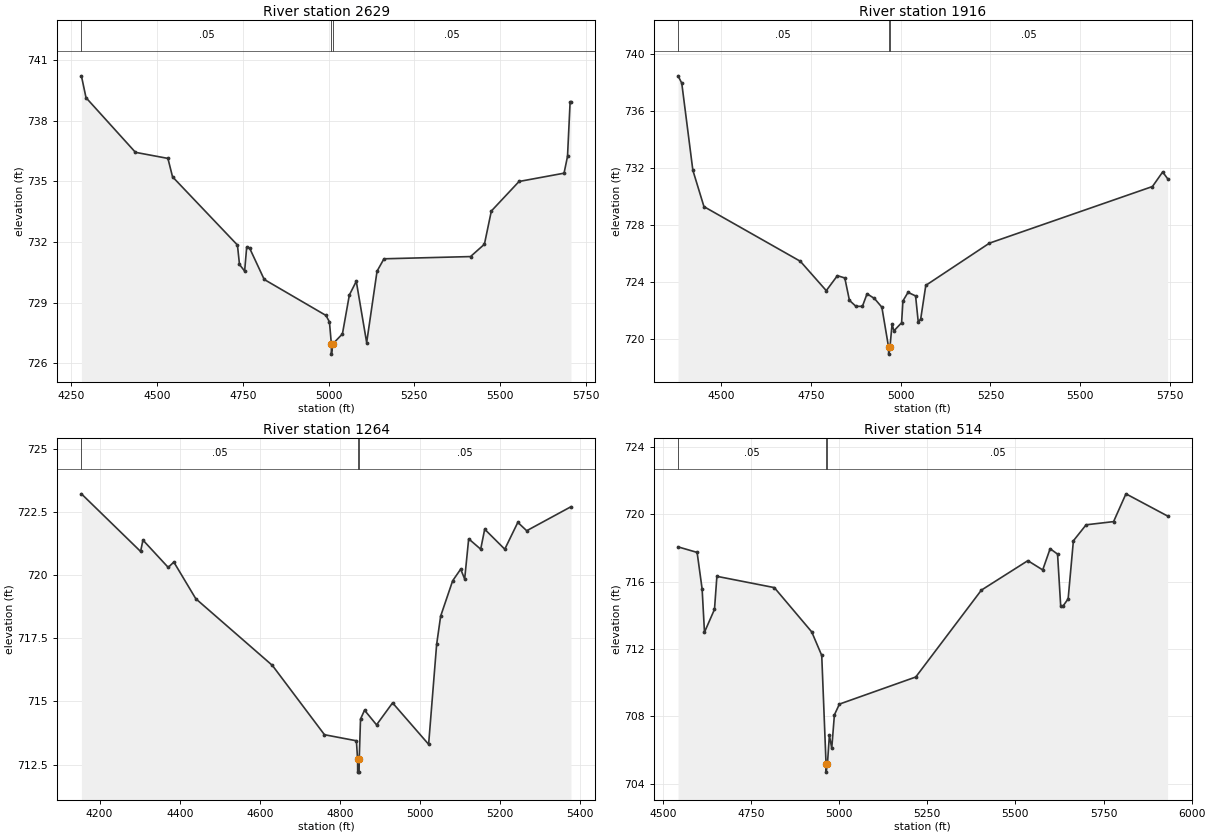
Type RM Length L Ch R = 1,2629,713,713,713
BEGIN DESCRIPTION:
Elizabeth Creek Tributary 21 3.0
END DESCRIPTION:
XS GIS Cut Line= 3
      2315778.99      7063509.98      2315379.00      7062910.00
      2314678.99      7063010.00
#Sta/Elev= 30
  4279.1  740.21  4292.6  739.13  4436.8  736.43  4531.5  736.13  4545.0  735.22
  4734.3  731.85  4740.3  730.89  4755.3  730.56  4761.3  731.75  4770.3  731.68
  4812.4  730.15  4992.7  728.37  5002.7  728.05  5008.3  726.96  5008.5  726.46
  5012.3  726.96  5040.6  727.46  5060.8  729.38  5081.0  730.06  5111.3  727.03
  5141.6  730.56  5161.8  731.17  5414.3  731.28  5454.8  731.89  5475.0  733.53
  5555.8  734.99  5687.1  735.40  5697.2  736.23  5704.8  738.92  5707.3  738.92
#Mann=3,-1,0
  4279.1    0.05       0  5008.3   0.033       0  5012.3    0.05       0
Bank Sta=5008.3,5012.3
Exp/Cntr=0.3,0.1

Type RM Length L Ch R = 1,1916,652,652,652
BEGIN DESCRIPTION:
Elizabeth Creek Tributary 21 2.0
END DESCRIPTION:
XS GIS Cut Line= 3
      2316128.98      7062459.99      2315529.00      7062310.00
      2314979.03      7062809.97
#Sta/Elev= 30
  4381.0  738.45  4391.3  737.94  4422.2  731.83  4453.1  729.28  4721.1  725.45
  4793.3  723.39  4824.2  724.44  4844.8  724.28  4857.7  722.71  4875.8  722.29
  4893.8  722.29  4906.7  723.17  4927.3  722.84  4947.9  722.23  4966.5  719.44
  4966.8  718.94  4970.5  719.44  4976.3  721.05  4981.4  720.57  5002.8  721.14
  5006.5  722.67  5020.7  723.27  5041.7  723.02  5049.1  721.19  5055.9  721.40
  5070.1  723.76  5247.1  726.72  5700.5  730.69  5728.9  731.71  5742.7  731.24
#Mann=3,-1,0
  4381.0    0.05       0  4966.5   0.033       0  4970.5    0.05       0
Bank Sta=4966.5,4970.5
Exp/Cntr=0.3,0.1

Type RM Length L Ch R = 1,1264,750,750,750
BEGIN DESCRIPTION:
Elizabeth Creek Tributary 21 1.0
END DESCRIPTION:
XS GIS Cut Line= 4
      2316305.69      7061969.61      2316176.04      7061688.25
      2315407.73      7061701.85      2315296.83      7061793.82
#Sta/Elev= 30
  4154.6  723.21  4302.4  720.93  4308.3  721.38  4371.3  720.30  4385.4  720.51
  4440.2  719.06  4631.5  716.42  4761.5  713.68  4841.2  713.44  4844.2  712.70
  4844.4  712.20  4847.9  712.20  4848.2  712.70  4851.5  714.30  4861.5  714.65
  4891.5  714.07  4931.5  714.94  5021.5  713.30  5041.5  717.25  5051.5  718.37
  5081.5  719.77  5101.5  720.23  5111.5  719.84  5121.5  721.43  5151.5  721.02
  5161.5  721.81  5211.6  721.02  5244.2  722.08  5266.4  721.75  5376.9  722.70
#Mann=3,-1,0
  4154.6    0.05       0  4844.2   0.033       0  4848.2    0.05       0
Bank Sta=4844.2,4848.2
Exp/Cntr=0.3,0.1

Type RM Length L Ch R = 1,514,0,0,0
BEGIN DESCRIPTION:
1048
END DESCRIPTION:
XS GIS Cut Line= 4
      2316440.36      7061494.67      2315960.67      7061062.36
      2315670.50      7061494.66      2315504.68      7061642.71
#Sta/Elev= 30
  4543.1  718.06  4597.2  717.73  4611.4  715.56  4618.1  712.99  4646.5  714.35
  4653.3  716.31  4816.2  715.64  4922.3  713.01  4950.7  711.61  4962.9  705.18
  4963.2  704.68  4966.9  705.18  4972.4  706.87  4979.1  706.10  4986.6  708.08
  5000.8  708.72  5217.4  710.33  5403.5  715.49  5535.3  717.24  5577.5  716.69
  5598.5  717.95  5619.6  717.63  5628.5  714.55  5634.6  714.53  5649.6  714.97
  5664.5  718.42  5700.6  719.37  5778.5  719.56  5813.6  721.21  5931.8  719.89
#Mann=3,-1,0
  4543.1    0.05       0  4962.9   0.033       0  4966.9    0.05       0
Bank Sta=4962.9,4966.9
Exp/Cntr=0.3,0.1

Chan Stop Cuts=-1