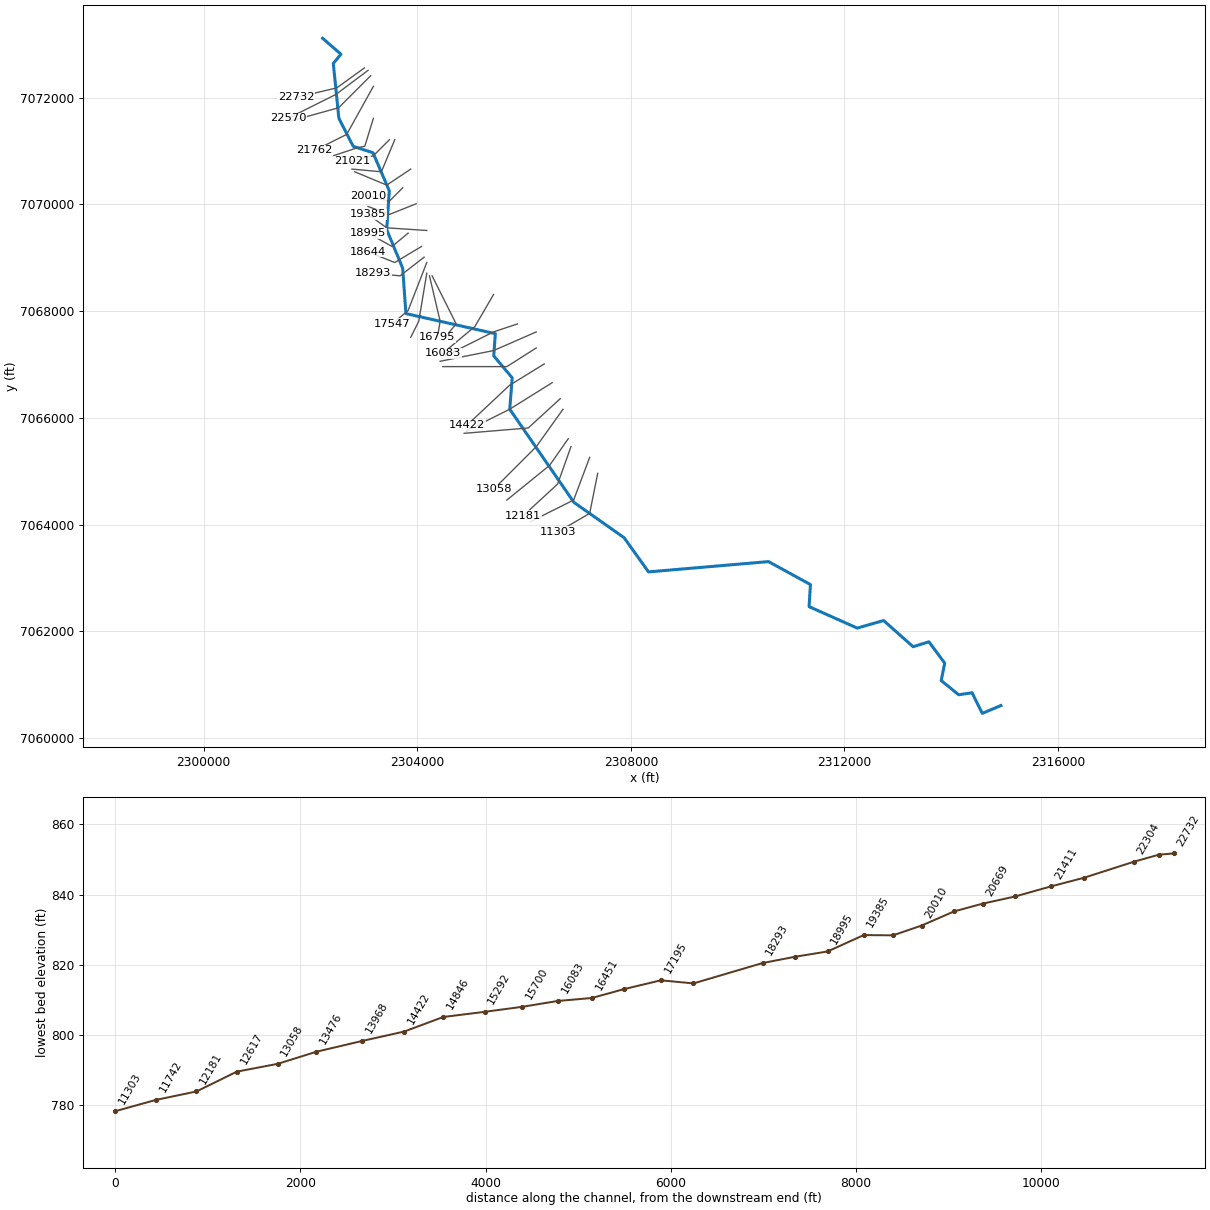
--- Elizabeth Cr Tr 22.prj (project) ---

Proj Title=Elizabeth Cr Tr 22 Base Level Engineering
Current Plan=p01
Default Exp/Contr=0.3,0.1
English Units
Geom File=g01
Flow File=f01
Plan File=p01
BEGIN DESCRIPTION:
Elizabeth Cr Tr 22
END DESCRIPTION:

--- Elizabeth Cr Tr 22.p01 (plan) ---

Plan Title=Multiple Run
Short Identifier=Multiple
Geom File=g01
Flow File=f01
Subcritical Flow
K Sum by GR= 0
Std Step Tol= 0.01
Critical Tol= 0.01
Num of Std Step Trials= 20
Max Error Tol= 0.3
Flow Tol Ratio= 0.001
Split Flow NTrial= 30
Split Flow Tol= 0.02
Split Flow Ratio= 0.02
Log Output Level= 0
Friction Slope Method= 0
Unsteady Friction Slope Method= 2
Unsteady Bridges Friction Slope Method= 1
Parabolic Critical Depth
Global Vel Dist=  1 , 1 , 1
Global Log Level= 0
CheckData=True
Encroach Param= -1, 0, 0, 0
BEGIN DESCRIPTION:
Multiple Run
END DESCRIPTION:

--- Elizabeth Cr Tr 22.f01 (steady flow) ---

Flow Title=Multiple
Number of Profiles=7
Profile Names=10-year,25-year,50-year,1pct_min,100-year,1pct_plu,500-year
River Rch & RM= Elizabeth Cr Tr ,Reach-1,22732
     311     407     482     284     567    1130     785
River Rch & RM= Elizabeth Cr Tr ,Reach-1,21411
     508     684     827     497     991    1980    1430
River Rch & RM= Elizabeth Cr Tr ,Reach-1,15292
     700     961    1180     714    1430    2840    2100
River Rch & RM= Elizabeth Cr Tr ,Reach-1,9687
     881    1230    1520     928    1850    3690    2770
River Rch & RM= Elizabeth Cr Tr ,Reach-1,3258
    1150    1620    2020    1250    2490    4960    3790
Boundary for River Rch & Prof#=Elizabeth Cr Tr ,Reach-1,1
Up Type=0
Dn Type=3
Dn Slope=0.005
Boundary for River Rch & Prof#=Elizabeth Cr Tr ,Reach-1,2
Up Type=0
Dn Type=3
Dn Slope=0.005
Boundary for River Rch & Prof#=Elizabeth Cr Tr ,Reach-1,3
Up Type=0
Dn Type=3
Dn Slope=0.005
Boundary for River Rch & Prof#=Elizabeth Cr Tr ,Reach-1,4
Up Type=0
Dn Type=3
Dn Slope=0.005
Boundary for River Rch & Prof#=Elizabeth Cr Tr ,Reach-1,5
Up Type=0
Dn Type=3
Dn Slope=0.005
Boundary for River Rch & Prof#=Elizabeth Cr Tr ,Reach-1,6
Up Type=0
Dn Type=3
Dn Slope=0.005
Boundary for River Rch & Prof#=Elizabeth Cr Tr ,Reach-1,7
Up Type=0
Dn Type=3
Dn Slope=0.005

--- Elizabeth Cr Tr 22.g01 (geometry) ---

Geom Title=Existing Conditions

River Reach=Elizabeth Cr Tr ,Reach-1
Reach XY= 30
      2302229.00      7073110.00      2302571.53      7072813.62
      2302428.60      7072639.87      2302532.75      7071611.55
      2302801.72      7071086.10      2303171.28      7070966.50
      2303477.20      7070253.89      2303428.88      7069525.76
      2303727.45      7068804.15      2303788.30      7067953.32
      2305462.56      7067576.79      2305432.37      7067161.28
      2305778.05      7066749.52      2305732.54      7066161.46
      2306934.61      7064415.59      2307873.44      7063754.38
      2308330.58      7063113.67      2310577.27      7063306.69
      2311362.60      7062876.82      2311336.95      7062463.00
      2312239.55      7062061.08      2312732.58      7062202.52
      2313285.05      7061711.59      2313581.30      7061804.17
      2313876.77      7061404.07      2313811.68      7061076.27
      2314140.49      7060811.47      2314389.06      7060849.97
      2314580.63      7060463.13      2314929.00      7060610.00

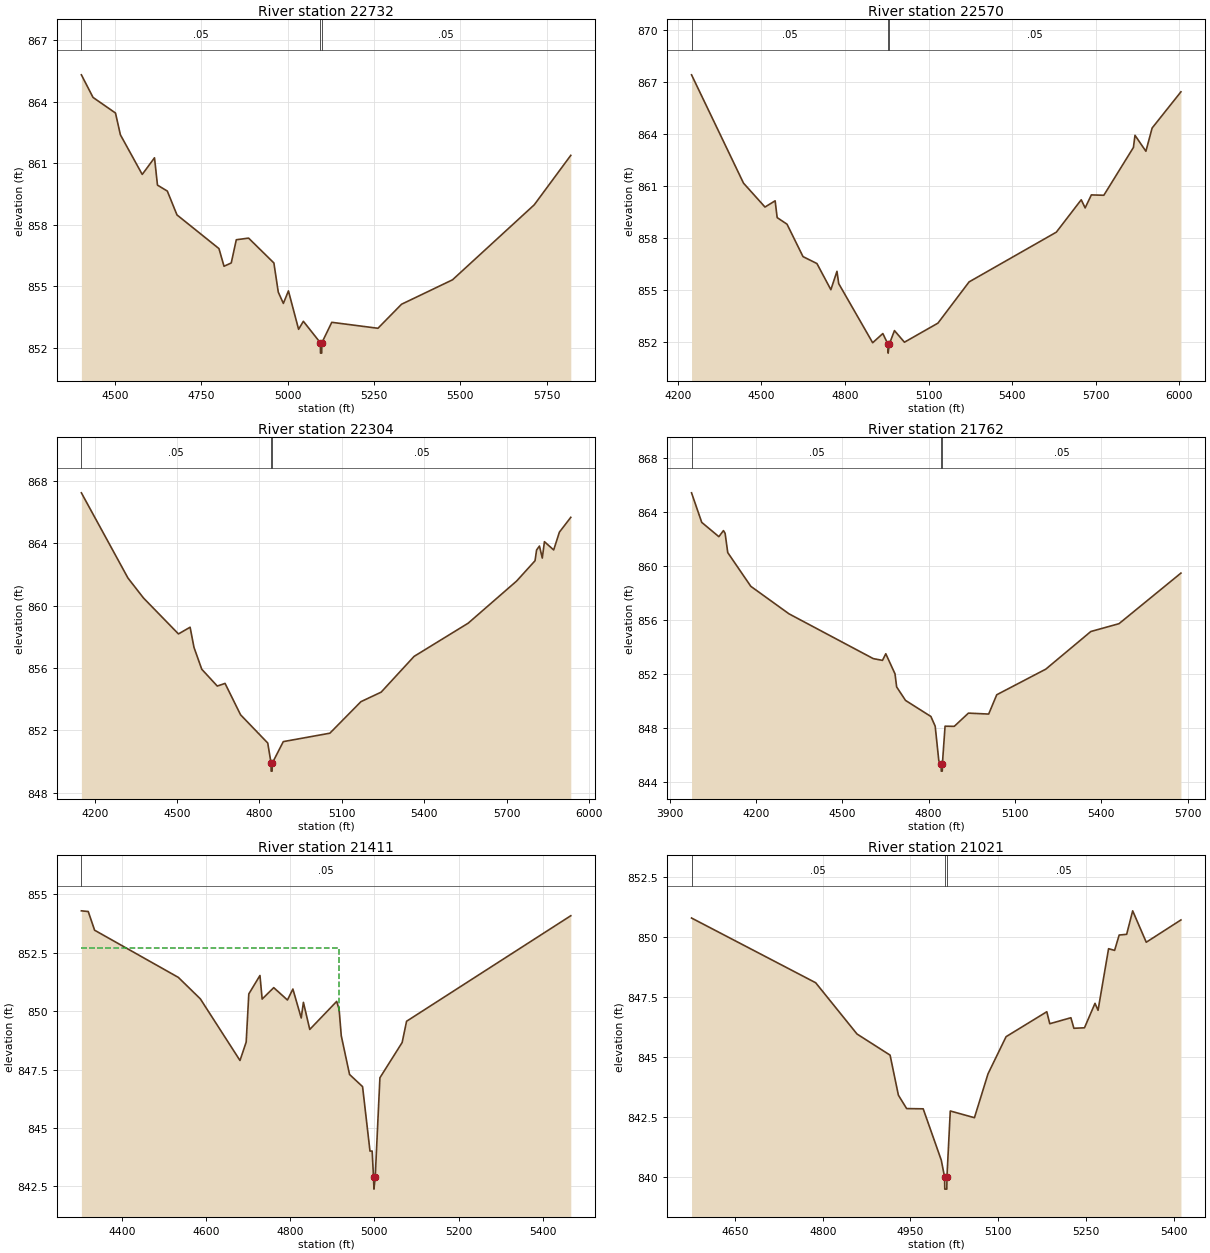
Type RM Length L Ch R = 1,22732,162,162,162
BEGIN DESCRIPTION:
1060
END DESCRIPTION:
XS GIS Cut Line= 3
      2303010.52      7072555.36      2302494.55      7072182.37
      2301736.05      7072002.07
#Sta/Elev= 30
  4403.1  865.30  4436.8  864.20  4501.8  863.44  4516.0  862.38  4579.2  860.45
  4614.7  861.26  4623.3  859.93  4651.8  859.64  4679.7  858.48  4801.2  856.84
  4815.9  855.98  4836.8  856.14  4851.4  857.27  4887.0  857.35  4960.2  856.14
  4972.9  854.72  4987.6  854.17  5002.3  854.78  5031.7  852.91  5045.5  853.30
  5094.9  852.25  5095.1  851.75  5098.6  851.75  5098.9  852.25  5127.7  853.25
  5261.3  852.96  5329.6  854.13  5477.2  855.32  5713.6  858.97  5819.4  861.38
#Mann=3,-1,0
  4403.1    0.05       0  5094.9   0.033       0  5098.9    0.05       0
Bank Sta=5094.9,5098.9
Exp/Cntr=0.3,0.1

Type RM Length L Ch R = 1,22570,266,266,266
BEGIN DESCRIPTION:
Elizabeth Creek Tributary 22 45.0
END DESCRIPTION:
XS GIS Cut Line= 3
      2303079.03      7072510.02      2302479.00      7072060.00
      2301578.97      7071609.99
#Sta/Elev= 30
  4249.1  867.43  4435.6  861.18  4512.7  859.80  4549.1  860.16  4556.4  859.19
  4591.8  858.81  4649.1  856.94  4699.1  856.54  4749.1  855.03  4771.0  856.09
  4777.3  855.38  4899.1  851.97  4935.6  852.50  4954.4  851.87  4954.7  851.37
  4958.4  851.87  4977.3  852.67  5013.1  852.00  5133.3  853.10  5245.1  855.48
  5558.2  858.35  5647.6  860.22  5661.6  859.75  5683.9  860.50  5728.7  860.48
  5834.9  863.24  5840.5  863.94  5879.6  863.02  5902.0  864.36  6005.4  866.45
#Mann=3,-1,0
  4249.1    0.05       0  4954.4   0.033       0  4958.4    0.05       0
Bank Sta=4954.4,4958.4
Exp/Cntr=0.3,0.1

Type RM Length L Ch R = 1,22304,542,542,542
BEGIN DESCRIPTION:
Elizabeth Creek Tributary 22 44.0
END DESCRIPTION:
XS GIS Cut Line= 3
      2303129.01      7072410.01      2302529.00      7071810.00
      2301629.02      7071560.01
#Sta/Elev= 30
  4151.5  867.22  4321.2  861.76  4377.8  860.48  4505.1  858.18  4547.5  858.61
  4561.6  857.32  4589.9  855.92  4646.5  854.84  4674.8  855.01  4731.3  853.00
  4830.3  851.19  4842.5  849.89  4842.7  849.39  4846.2  849.39  4846.5  849.89
  4886.9  851.28  5056.6  851.82  5169.7  853.84  5243.4  854.45  5363.3  856.74
  5560.5  858.87  5736.9  861.57  5803.9  862.87  5809.6  863.56  5820.0  863.81
  5830.3  863.04  5838.1  864.09  5871.8  863.56  5892.6  864.70  5934.1  865.65
#Mann=3,-1,0
  4151.5    0.05       0  4842.5   0.033       0  4846.5    0.05       0
Bank Sta=4842.5,4846.5
Exp/Cntr=0.3,0.1

Type RM Length L Ch R = 1,21762,351,351,351
BEGIN DESCRIPTION:
Elizabeth Creek Tributary 22 42.0
END DESCRIPTION:
XS GIS Cut Line= 3
      2303178.98      7072209.96      2302679.00      7071310.00
      2302079.03      7071010.02
#Sta/Elev= 30
  3976.3  865.43  4011.7  863.24  4071.2  862.18  4087.2  862.63  4092.9  862.43
  4102.1  861.00  4182.2  858.50  4314.9  856.46  4607.7  853.14  4639.7  853.01
  4651.2  853.50  4683.2  852.01  4688.9  851.04  4719.8  850.04  4807.9  848.85
  4822.8  848.13  4835.4  845.57  4843.7  845.30  4843.9  844.80  4847.4  844.80
  4847.7  845.30  4857.1  848.13  4889.1  848.12  4938.3  849.10  5008.6  849.03
  5036.6  850.46  5207.1  852.36  5363.6  855.15  5461.4  855.73  5676.6  859.48
#Mann=3,-1,0
  3976.3    0.05       0  4843.7   0.033       0  4847.7    0.05       0
Bank Sta=4843.7,4847.7
Exp/Cntr=0.3,0.1

Type RM Length L Ch R = 1,21411,390,390,390
BEGIN DESCRIPTION:
Elizabeth Creek Tributary 22 41.0
END DESCRIPTION:
XS GIS Cut Line= 4
      2303179.00      7071609.99      2303018.22      7071088.30
      2302879.00      7071060.00      2302429.01      7070910.00
#Sta/Elev= 30
  4304.2  854.30  4320.5  854.27  4335.6  853.47  4534.4  851.45  4586.7  850.53
  4680.9  847.89  4695.6  848.68  4701.8  850.74  4728.3  851.53  4733.5  850.52
  4761.0  851.01  4793.6  850.48  4806.5  850.95  4826.3  849.71  4831.5  850.38
  4846.6  849.22  4910.5  850.42  4916.3  850.08  4921.4  848.95  4941.1  847.29
  4972.0  846.77  4989.6  844.01  4994.8  844.01  4998.0  842.88  4999.0  842.38
  5002.0  842.88  5013.2  847.15  5066.0  848.66  5076.5  849.57  5466.5  854.09
#Mann=1,-1,0
  4304.2    0.05       0
#XS Ineff=2,0
    0.00 4917.10  852.69               0
Permanent Ineff=
       F       F
Bank Sta=4998,5002
Exp/Cntr=0.3,0.1

Type RM Length L Ch R = 1,21021,352,352,352
BEGIN DESCRIPTION:
Elizabeth Creek Tributary 22 40.0
END DESCRIPTION:
XS GIS Cut Line= 3
      2303479.02      7071210.02      2303179.00      7070910.00
      2302779.01      7070810.00
#Sta/Elev= 30
  4575.8  850.80  4788.0  848.10  4858.7  845.96  4915.2  845.08  4929.4  843.41
  4943.5  842.85  4971.8  842.84  5002.7  840.70  5008.4  839.99  5008.7  839.49
  5012.2  839.49  5012.4  839.99  5018.1  842.75  5059.4  842.47  5082.6  844.30
  5113.5  845.85  5183.1  846.89  5188.2  846.39  5224.3  846.64  5229.4  846.20
  5247.5  846.22  5265.5  847.24  5270.7  846.95  5288.7  849.52  5299.0  849.45
  5306.8  850.09  5319.6  850.12  5329.9  851.10  5353.1  849.79  5412.4  850.72
#Mann=3,-1,0
  4575.8    0.05       0  5008.4   0.033       0  5012.4    0.05       0
Bank Sta=5008.4,5012.4
Exp/Cntr=0.3,0.1

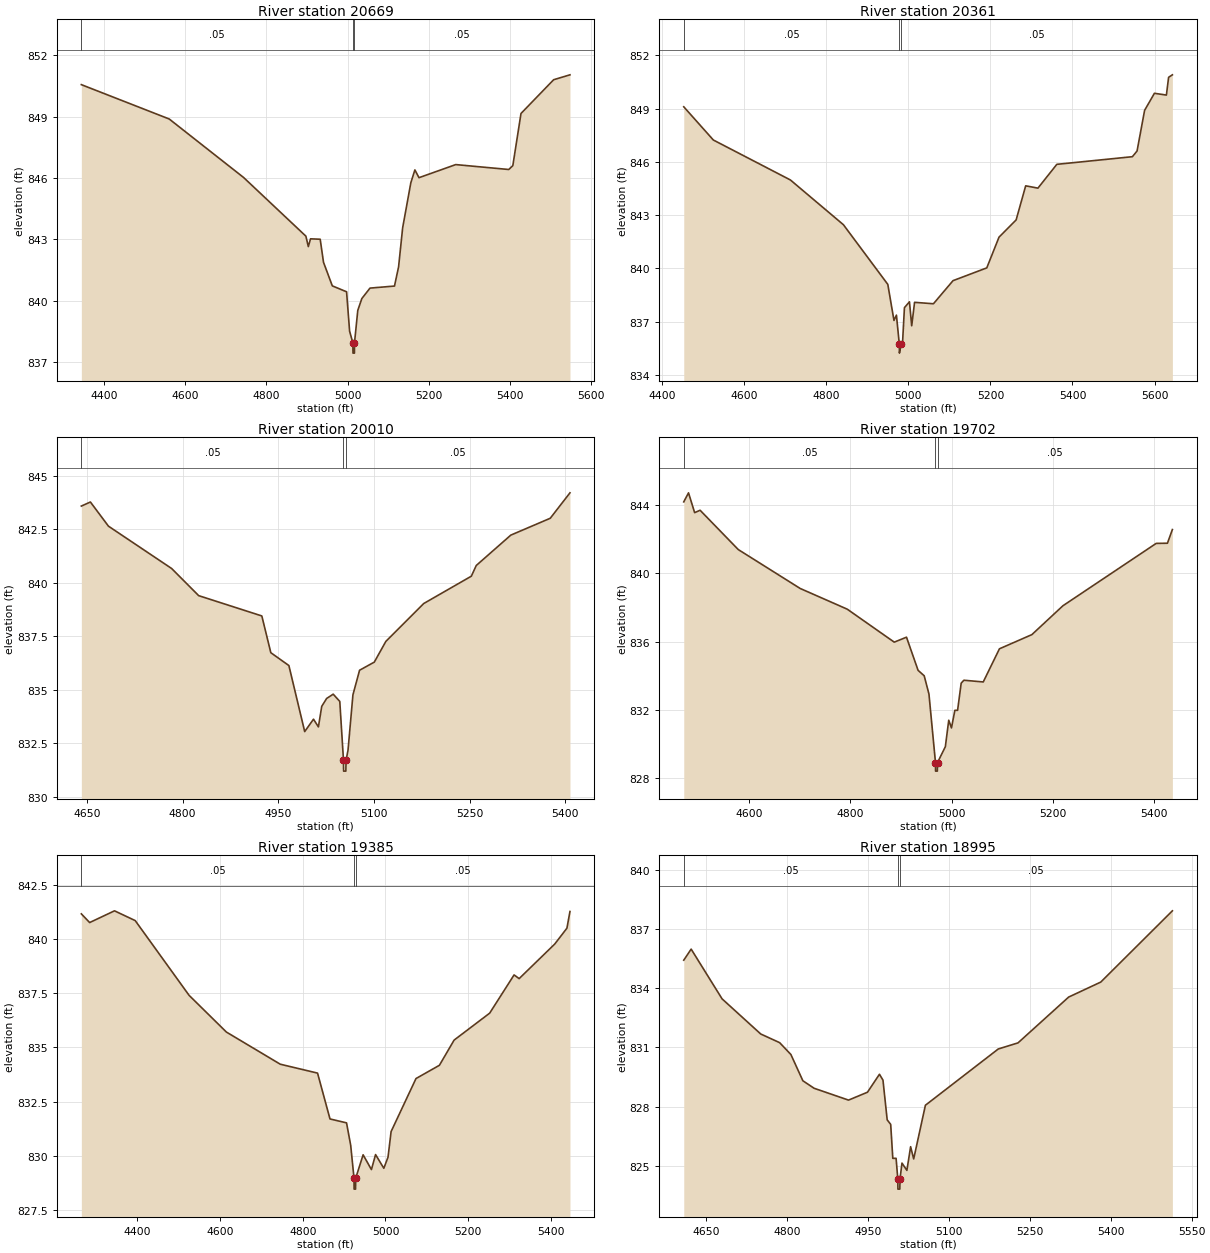
Type RM Length L Ch R = 1,20669,308,308,308
BEGIN DESCRIPTION:
Elizabeth Creek Tributary 22 39.0
END DESCRIPTION:
XS GIS Cut Line= 3
      2303579.02      7071210.04      2303329.00      7070610.00
      2302779.01      7070660.00
#Sta/Elev= 30
  4345.0  850.56  4561.2  848.88  4744.2  846.02  4897.5  843.15  4903.5  842.64
  4908.9  843.02  4932.7  843.00  4940.9  841.87  4962.5  840.72  4997.6  840.43
  5005.1  838.50  5013.1  837.93  5013.4  837.43  5016.9  837.43  5017.1  837.93
  5025.2  839.52  5035.2  840.10  5055.3  840.61  5115.5  840.71  5125.6  841.65
  5135.6  843.56  5155.7  845.76  5165.7  846.39  5175.8  846.01  5266.2  846.65
  5396.7  846.41  5406.7  846.60  5426.8  849.15  5507.1  850.80  5547.3  851.04
#Mann=3,-1,0
  4345.0    0.05       0  5013.1   0.033       0  5017.1    0.05       0
Bank Sta=5013.1,5017.1
Exp/Cntr=0.3,0.1

Type RM Length L Ch R = 1,20361,351,351,351
BEGIN DESCRIPTION:
Elizabeth Creek Tributary 22 38.0
END DESCRIPTION:
XS GIS Cut Line= 3
      2303878.99      7070660.00      2303429.00      7070360.00
      2302829.02      7070609.99
#Sta/Elev= 30
  4452.7  849.10  4524.8  847.23  4712.6  844.98  4841.8  842.46  4950.0  839.10
  4965.0  837.07  4971.0  837.37  4978.0  835.73  4978.3  835.23  4982.0  835.73
  4986.0  835.86  4990.5  837.79  5002.7  838.12  5008.2  836.77  5015.2  838.09
  5061.2  838.01  5108.9  839.31  5191.2  840.03  5221.0  841.76  5262.7  842.73
  5286.0  844.65  5315.8  844.52  5361.9  845.86  5546.0  846.29  5557.4  846.61
  5575.8  848.90  5599.7  849.86  5628.9  849.76  5634.3  850.76  5643.5  850.90
#Mann=3,-1,0
  4452.7    0.05       0  4978.0   0.033       0  4982.0    0.05       0
Bank Sta=4978,4982
Exp/Cntr=0.3,0.1

Type RM Length L Ch R = 1,20010,308,308,308
BEGIN DESCRIPTION:
Elizabeth Creek Tributary 22 37.0
END DESCRIPTION:
XS GIS Cut Line= 3
      2303729.03      7070310.03      2303479.00      7070060.00
      2303079.00      7070160.00
#Sta/Elev= 30
  4641.3  843.59  4655.5  843.78  4683.8  842.65  4782.8  840.67  4825.2  839.40
  4924.2  838.45  4938.3  836.73  4966.6  836.13  4991.4  833.04  5005.2  833.62
  5012.9  833.26  5018.1  834.22  5025.8  834.59  5036.1  834.79  5046.4  834.45
  5052.2  831.69  5052.4  831.19  5055.9  831.19  5056.2  831.69  5059.3  832.17
  5067.0  834.76  5077.4  835.91  5100.5  836.29  5118.6  837.26  5177.9  839.03
  5252.6  840.31  5260.3  840.81  5314.4  842.23  5376.3  843.02  5407.2  844.21
#Mann=3,-1,0
  4641.3    0.05       0  5052.2   0.033       0  5056.2    0.05       0
Bank Sta=5052.2,5056.2
Exp/Cntr=0.3,0.1

Type RM Length L Ch R = 1,19702,317,317,317
BEGIN DESCRIPTION:
Elizabeth Creek Tributary 22 36.0
END DESCRIPTION:
XS GIS Cut Line= 3
      2303978.98      7070009.99      2303479.00      7069810.00
      2303079.00      7069960.00
#Sta/Elev= 30
  4470.5  844.18  4479.9  844.71  4492.0  843.55  4502.8  843.69  4578.2  841.39
  4700.7  839.11  4793.6  837.90  4886.5  835.97  4910.7  836.26  4933.6  834.32
  4945.7  834.00  4955.1  832.93  4968.0  828.92  4968.2  828.42  4971.7  828.42
  4972.0  828.92  4987.5  829.85  4994.2  831.40  4999.6  830.95  5006.3  831.98
  5011.7  831.98  5018.8  833.57  5024.1  833.74  5062.4  833.64  5094.4  835.58
  5158.5  836.41  5219.9  838.10  5404.2  841.75  5426.4  841.76  5436.2  842.56
#Mann=3,-1,0
  4470.5    0.05       0  4968.0   0.033       0  4972.0    0.05       0
Bank Sta=4968,4972
Exp/Cntr=0.3,0.1

Type RM Length L Ch R = 1,19385,390,390,390
BEGIN DESCRIPTION:
Elizabeth Creek Tributary 22 35.0
END DESCRIPTION:
XS GIS Cut Line= 3
      2304179.03      7069510.00      2303429.00      7069560.00
      2303079.01      7069810.00
#Sta/Elev= 30
  4264.5  841.15  4284.6  840.75  4344.7  841.29  4394.8  840.84  4525.1  837.40
  4615.3  835.71  4745.6  834.23  4835.8  833.82  4865.9  831.71  4905.9  831.53
  4916.0  830.49  4924.0  828.98  4924.2  828.48  4927.7  828.48  4928.0  828.98
  4946.0  830.06  4966.1  829.38  4976.1  830.07  4996.1  829.44  5006.2  829.95
  5013.7  831.13  5073.9  833.57  5130.5  834.18  5166.1  835.34  5252.1  836.58
  5311.1  838.34  5323.4  838.17  5409.4  839.76  5438.9  840.49  5446.3  841.26
#Mann=3,-1,0
  4264.5    0.05       0  4924.0   0.033       0  4928.0    0.05       0
Bank Sta=4924,4928
Exp/Cntr=0.3,0.1

Type RM Length L Ch R = 1,18995,351,351,351
BEGIN DESCRIPTION:
Elizabeth Creek Tributary 22 34.0
END DESCRIPTION:
XS GIS Cut Line= 3
      2303829.03      7069460.02      2303529.00      7069210.00
      2303079.03      7069459.99
#Sta/Elev= 30
  4609.0  835.42  4622.7  835.98  4680.0  833.46  4751.6  831.68  4786.7  831.24
  4807.5  830.64  4829.7  829.31  4850.5  828.93  4914.3  828.33  4949.4  828.73
  4971.6  829.64  4978.1  829.34  4985.9  827.33  4992.4  827.10  4996.3  825.38
  5002.4  825.38  5005.6  824.32  5005.8  823.82  5009.3  823.82  5009.6  824.32
  5013.3  825.14  5022.4  824.77  5029.3  825.97  5035.0  825.35  5056.7  828.07
  5191.7  830.92  5228.3  831.23  5322.1  833.55  5381.6  834.31  5514.3  837.92
#Mann=3,-1,0
  4609.0    0.05       0  5005.6   0.033       0  5009.6    0.05       0
Bank Sta=5005.6,5009.6
Exp/Cntr=0.3,0.1

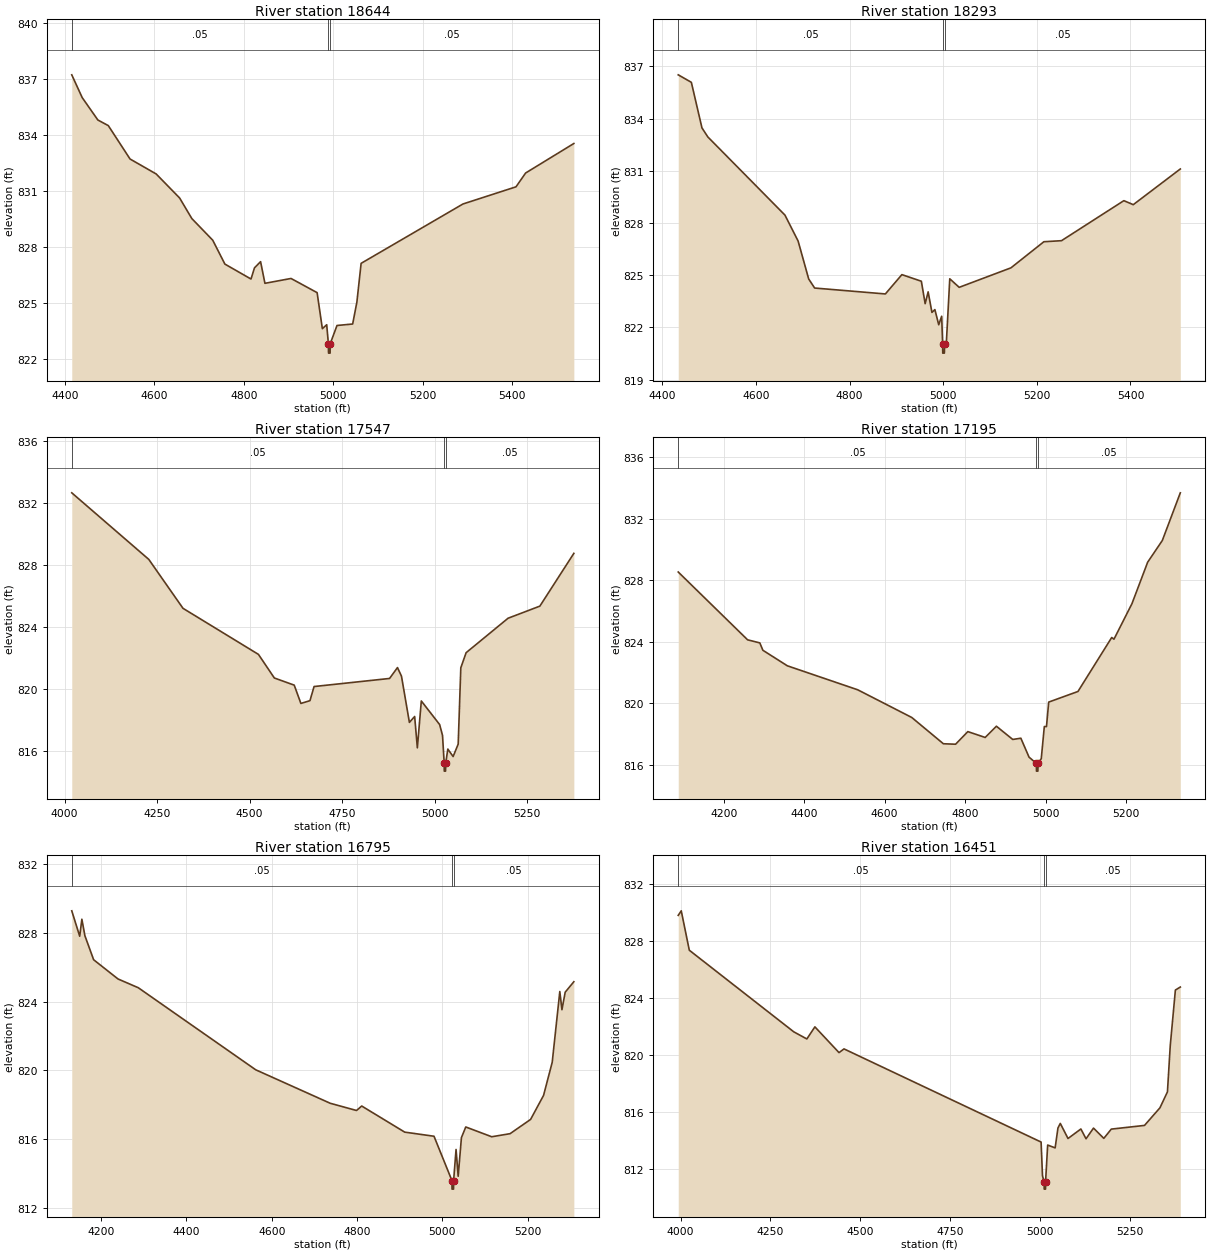
Type RM Length L Ch R = 1,18644,351,351,351
BEGIN DESCRIPTION:
Elizabeth Creek Tributary 22 33.0
END DESCRIPTION:
XS GIS Cut Line= 3
      2304078.99      7069209.99      2303579.00      7068910.00
      2303079.00      7069110.00
#Sta/Elev= 30
  4415.7  837.22  4439.0  836.00  4474.0  834.80  4497.3  834.50  4545.9  832.71
  4604.2  831.91  4656.7  830.62  4683.9  829.52  4730.6  828.36  4757.8  827.08
  4816.1  826.28  4823.9  826.88  4837.5  827.21  4847.2  826.05  4905.5  826.31
  4963.8  825.55  4975.5  823.62  4985.2  823.83  4989.0  822.81  4989.3  822.31
  4992.8  822.31  4993.0  822.81  5008.2  823.79  5043.2  823.87  5052.6  825.04
  5062.1  827.12  5289.6  830.30  5408.1  831.22  5429.6  831.96  5537.3  833.54
#Mann=3,-1,0
  4415.7    0.05       0  4989.0   0.033       0  4993.0    0.05       0
Bank Sta=4989,4993
Exp/Cntr=0.3,0.1

Type RM Length L Ch R = 1,18293,746,746,746
BEGIN DESCRIPTION:
Elizabeth Creek Tributary 22 32.0
END DESCRIPTION:
XS GIS Cut Line= 3
      2304128.98      7069009.99      2303679.00      7068660.00
      2303178.96      7068710.00
#Sta/Elev= 30
  4433.9  836.51  4461.9  836.08  4484.6  833.46  4497.2  832.94  4661.9  828.45
  4690.0  826.96  4712.6  824.78  4725.3  824.26  4876.4  823.92  4911.7  825.03
  4953.3  824.65  4961.4  823.36  4967.8  824.04  4975.9  822.86  4982.2  823.02
  4990.4  822.15  4996.7  822.64  4998.8  821.02  4999.0  820.52  5002.5  820.52
  5002.8  821.02  5006.5  821.02  5014.0  824.79  5034.1  824.30  5144.7  825.42
  5215.0  826.92  5252.7  826.98  5385.9  829.28  5406.0  829.05  5506.5  831.10
#Mann=3,-1,0
  4433.9    0.05       0  4998.8   0.033       0  5002.8    0.05       0
Bank Sta=4998.8,5002.8
Exp/Cntr=0.3,0.1

Type RM Length L Ch R = 1,17547,352,352,352
BEGIN DESCRIPTION:
Elizabeth Creek Tributary 22 31.0
END DESCRIPTION:
XS GIS Cut Line= 3
      2304179.00      7068910.01      2303829.00      7068010.00
      2303528.98      7067759.99
#Sta/Elev= 30
  4019.5  832.65  4227.6  828.36  4319.9  825.21  4523.8  822.24  4566.7  820.72
  4620.4  820.26  4638.4  819.08  4662.9  819.26  4674.0  820.17  4877.9  820.69
  4899.3  821.39  4910.1  820.84  4931.5  817.86  4945.7  818.24  4953.0  816.22
  4963.7  819.24  5013.2  817.72  5021.0  817.02  5025.5  815.22  5025.7  814.72
  5029.2  814.72  5029.5  815.22  5035.3  816.14  5049.6  815.66  5063.3  816.46
  5070.4  821.38  5084.7  822.35  5198.0  824.57  5283.9  825.35  5375.7  828.75
#Mann=3,-1,0
  4019.5    0.05       0  5025.5   0.033       0  5029.5    0.05       0
Bank Sta=5025.5,5029.5
Exp/Cntr=0.3,0.1

Type RM Length L Ch R = 1,17195,400,400,400
BEGIN DESCRIPTION:
Elizabeth Creek Tributary 22 30.0
END DESCRIPTION:
XS GIS Cut Line= 3
      2304179.01      7068710.05      2304029.00      7067810.00
      2303878.99      7067509.97
#Sta/Elev= 30
  4087.1  828.55  4259.5  824.14  4289.9  823.94  4297.5  823.46  4358.3  822.45
  4533.2  820.89  4667.5  819.09  4746.1  817.38  4776.5  817.35  4806.9  818.17
  4850.0  817.79  4877.9  818.52  4918.5  817.66  4938.7  817.74  4959.0  816.51
  4977.3  816.10  4977.5  815.60  4981.0  815.60  4981.3  816.10  4989.4  816.41
  4997.0  818.50  5002.4  818.50  5007.9  820.09  5080.6  820.78  5164.5  824.29
  5170.1  824.18  5214.8  826.49  5253.9  829.19  5290.3  830.60  5335.0  833.70
#Mann=3,-1,0
  4087.1    0.05       0  4977.3   0.033       0  4981.3    0.05       0
Bank Sta=4977.3,4981.3
Exp/Cntr=0.3,0.1

Type RM Length L Ch R = 1,16795,344,344,344
BEGIN DESCRIPTION:
Elizabeth Creek Tributary 22 29.0
END DESCRIPTION:
XS GIS Cut Line= 3
      2304229.01      7068659.96      2304429.00      7067810.00
      2304379.00      7067510.01
#Sta/Elev= 30
  4131.2  829.29  4149.8  827.81  4154.9  828.80  4162.0  827.84  4182.5  826.44
  4239.7  825.32  4287.2  824.81  4562.6  820.03  4737.3  818.08  4798.9  817.66
  4811.1  817.92  4911.9  816.40  4980.6  816.16  5022.6  813.58  5022.9  813.08
  5026.4  813.08  5026.6  813.58  5032.3  815.39  5037.3  813.83  5044.9  816.08
  5055.1  816.70  5115.9  816.13  5159.0  816.31  5207.1  817.14  5237.5  818.54
  5257.8  820.47  5275.6  824.59  5280.6  823.53  5288.2  824.55  5308.5  825.16
#Mann=3,-1,0
  4131.2    0.05       0  5022.6   0.033       0  5026.6    0.05       0
Bank Sta=5022.6,5026.6
Exp/Cntr=0.3,0.1

Type RM Length L Ch R = 1,16451,368,368,368
BEGIN DESCRIPTION:
Elizabeth Creek Tributary 22 28.0
END DESCRIPTION:
XS GIS Cut Line= 3
      2304278.98      7068660.04      2304729.00      7067760.00
      2304479.00      7067459.99
#Sta/Elev= 30
  3993.6  829.82  4002.0  830.14  4024.4  827.37  4315.1  821.63  4351.4  821.13
  4373.8  821.98  4440.9  820.17  4454.8  820.43  5003.1  813.88  5007.0  811.51
  5011.5  811.07  5011.8  810.57  5015.3  810.57  5015.5  811.07  5021.4  813.67
  5042.2  813.47  5050.0  814.87  5056.5  815.19  5078.0  814.13  5113.8  814.80
  5128.1  814.11  5148.9  814.86  5177.6  814.14  5198.4  814.79  5290.8  815.05
  5333.8  816.29  5354.6  817.41  5362.4  820.65  5376.7  824.57  5390.4  824.78
#Mann=3,-1,0
  3993.6    0.05       0  5011.5   0.033       0  5015.5    0.05       0
Bank Sta=5011.5,5015.5
Exp/Cntr=0.3,0.1

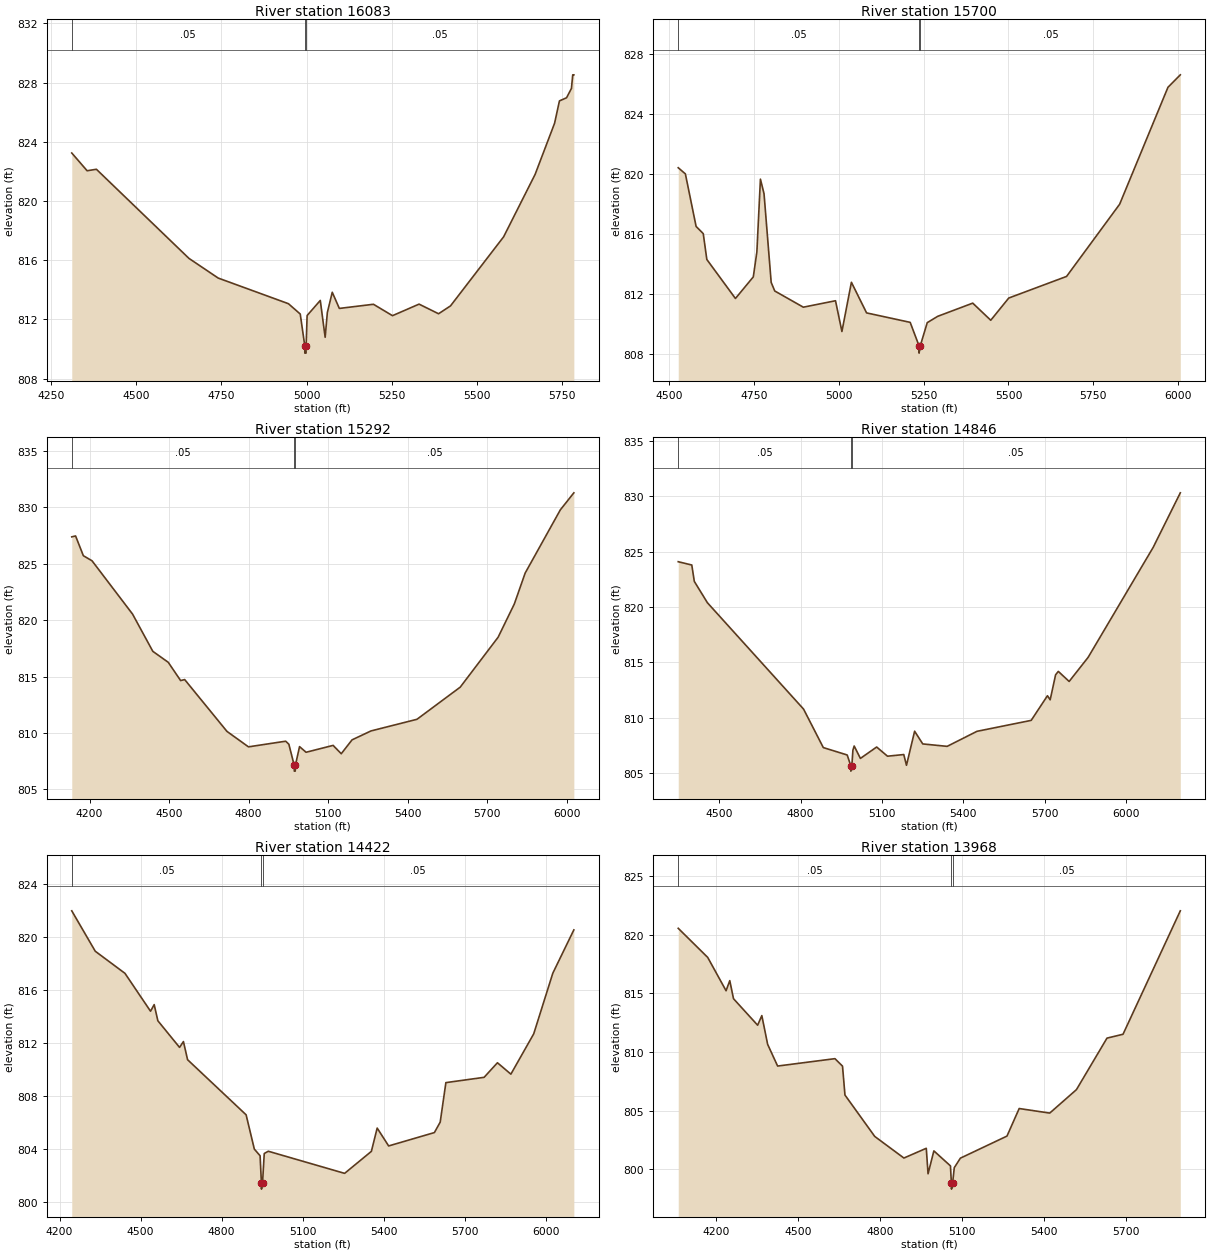
Type RM Length L Ch R = 1,16083,383,383,383
BEGIN DESCRIPTION:
Elizabeth Creek Tributary 22 27.0
END DESCRIPTION:
XS GIS Cut Line= 3
      2305429.00      7068310.00      2305079.00      7067710.00
      2304479.03      7067210.03
#Sta/Elev= 30
  4310.0  823.24  4355.1  822.04  4382.4  822.14  4654.4  816.12  4740.4  814.79
  4946.7  813.06  4981.5  812.36  4994.8  810.22  4995.0  809.72  4998.5  809.72
  4998.8  810.22  5001.7  812.26  5040.4  813.28  5054.7  810.79  5061.2  812.47
  5075.6  813.83  5096.4  812.74  5196.6  813.02  5252.6  812.25  5330.7  813.03
  5388.0  812.38  5423.1  812.91  5579.3  817.58  5671.7  821.79  5729.0  825.25
  5743.3  826.76  5764.2  826.97  5778.5  827.60  5782.4  828.52  5785.6  828.52
#Mann=3,-1,0
  4310.0    0.05       0  4994.8   0.033       0  4998.8    0.05       0
Bank Sta=4994.8,4998.8
Exp/Cntr=0.3,0.1

Type RM Length L Ch R = 1,15700,408,408,408
BEGIN DESCRIPTION:
Elizabeth Creek Tributary 22 26.0
END DESCRIPTION:
XS GIS Cut Line= 3
      2305879.00      7067760.00      2305429.00      7067610.00
      2304528.98      7067159.99
#Sta/Elev= 30
  4526.2  820.41  4547.3  820.00  4578.9  816.50  4600.0  816.02  4610.5  814.30
  4694.9  811.70  4747.6  813.14  4758.1  814.80  4768.6  819.65  4779.2  818.68
  4800.3  812.77  4810.8  812.20  4895.1  811.12  4990.0  811.55  5008.9  809.50
  5036.9  812.78  5081.6  810.74  5210.2  810.11  5236.1  808.56  5236.4  808.06
  5240.1  808.56  5260.5  810.09  5291.2  810.51  5394.7  811.39  5447.8  810.25
  5500.9  811.73  5671.4  813.17  5827.9  817.98  5970.4  825.77  6006.8  826.60
#Mann=3,-1,0
  4526.2    0.05       0  5236.1   0.033       0  5240.1    0.05       0
Bank Sta=5236.1,5240.1
Exp/Cntr=0.3,0.1

Type RM Length L Ch R = 1,15292,446,446,446
BEGIN DESCRIPTION:
Elizabeth Creek Tributary 22 25.0
END DESCRIPTION:
XS GIS Cut Line= 3
      2306228.99      7067610.00      2305429.00      7067260.00
      2304429.01      7067060.00
#Sta/Elev= 30
  4133.1  827.37  4147.5  827.45  4176.8  825.70  4209.5  825.25  4362.3  820.53
  4438.7  817.23  4496.8  816.26  4543.6  814.64  4558.8  814.73  4718.2  810.14
  4799.3  808.77  4939.6  809.27  4951.7  809.00  4971.9  807.12  4972.2  806.62
  4975.7  806.62  4976.1  807.12  4991.9  808.79  5016.5  808.29  5118.5  808.90
  5149.1  808.16  5189.9  809.39  5261.3  810.18  5434.6  811.21  5597.8  814.06
  5740.6  818.48  5801.8  821.43  5842.5  824.16  5975.1  829.76  6026.1  831.27
#Mann=3,-1,0
  4133.1    0.05       0  4971.9   0.033       0  4976.1    0.05       0
Bank Sta=4971.9,4976.1
Exp/Cntr=0.3,0.1

Type RM Length L Ch R = 1,14846,424,424,424
BEGIN DESCRIPTION:
Elizabeth Creek Tributary 22 24.0
END DESCRIPTION:
XS GIS Cut Line= 3
      2306229.02      7067310.02      2305679.00      7066960.00
      2304479.05      7066960.00
#Sta/Elev= 30
  4348.6  824.10  4398.6  823.80  4407.9  822.32  4456.2  820.39  4810.9  810.77
  4883.7  807.29  4971.8  806.62  4984.9  805.66  4985.2  805.16  4989.1  805.66
  4992.9  807.06  4997.6  807.43  5020.5  806.31  5080.5  807.34  5120.5  806.51
  5180.5  806.66  5190.5  805.69  5220.5  808.77  5250.5  807.62  5340.5  807.40
  5450.5  808.76  5650.5  809.75  5710.5  811.98  5720.5  811.61  5740.5  813.87
  5750.5  814.18  5790.5  813.27  5860.5  815.45  6100.5  825.40  6200.5  830.33
#Mann=3,-1,0
  4348.6    0.05       0  4984.9   0.033       0  4989.1    0.05       0
Bank Sta=4984.9,4989.1
Exp/Cntr=0.3,0.1

Type RM Length L Ch R = 1,14422,454,454,454
BEGIN DESCRIPTION:
Elizabeth Creek Tributary 22 23.0
END DESCRIPTION:
XS GIS Cut Line= 3
      2306379.04      7067010.02      2305729.00      7066610.00
      2304929.03      7065860.03
#Sta/Elev= 30
  4245.0  822.00  4332.0  818.95  4442.1  817.28  4536.8  814.42  4550.3  814.92
  4563.9  813.70  4644.3  811.69  4658.6  812.13  4674.0  810.76  4890.8  806.60
  4921.3  804.01  4942.6  803.51  4947.4  801.49  4947.7  800.99  4951.7  801.49
  4958.0  803.68  4973.0  803.85  5255.7  802.18  5354.8  803.84  5376.3  805.60
  5418.8  804.25  5588.3  805.26  5609.8  806.05  5630.8  809.03  5772.4  809.43
  5821.8  810.53  5871.6  809.67  5956.1  812.71  6026.9  817.29  6104.8  820.56
#Mann=3,-1,0
  4245.0    0.05       0  4947.4   0.033       0  4951.7    0.05       0
Bank Sta=4947.4,4951.7
Exp/Cntr=0.3,0.1

Type RM Length L Ch R = 1,13968,492,492,492
BEGIN DESCRIPTION:
Elizabeth Creek Tributary 22 22.0
END DESCRIPTION:
XS GIS Cut Line= 3
      2306529.02      7066660.01      2305729.00      7066160.00
      2304928.96      7065759.98
#Sta/Elev= 30
  4060.5  820.55  4168.4  818.07  4235.6  815.23  4249.2  816.09  4262.8  814.55
  4351.2  812.29  4366.5  813.11  4387.8  810.66  4424.3  808.81  4634.2  809.44
  4661.9  808.80  4670.8  806.34  4779.9  802.81  4886.6  800.97  4968.5  801.80
  4975.0  799.63  4996.3  801.58  5057.0  800.30  5060.4  798.82  5060.8  798.32
  5064.8  798.82  5071.0  800.15  5093.4  800.96  5263.9  802.84  5308.6  805.19
  5420.4  804.80  5518.2  806.80  5630.0  811.19  5688.7  811.52  5898.4  822.04
#Mann=3,-1,0
  4060.5    0.05       0  5060.4   0.033       0  5064.8    0.05       0
Bank Sta=5060.4,5064.8
Exp/Cntr=0.3,0.1

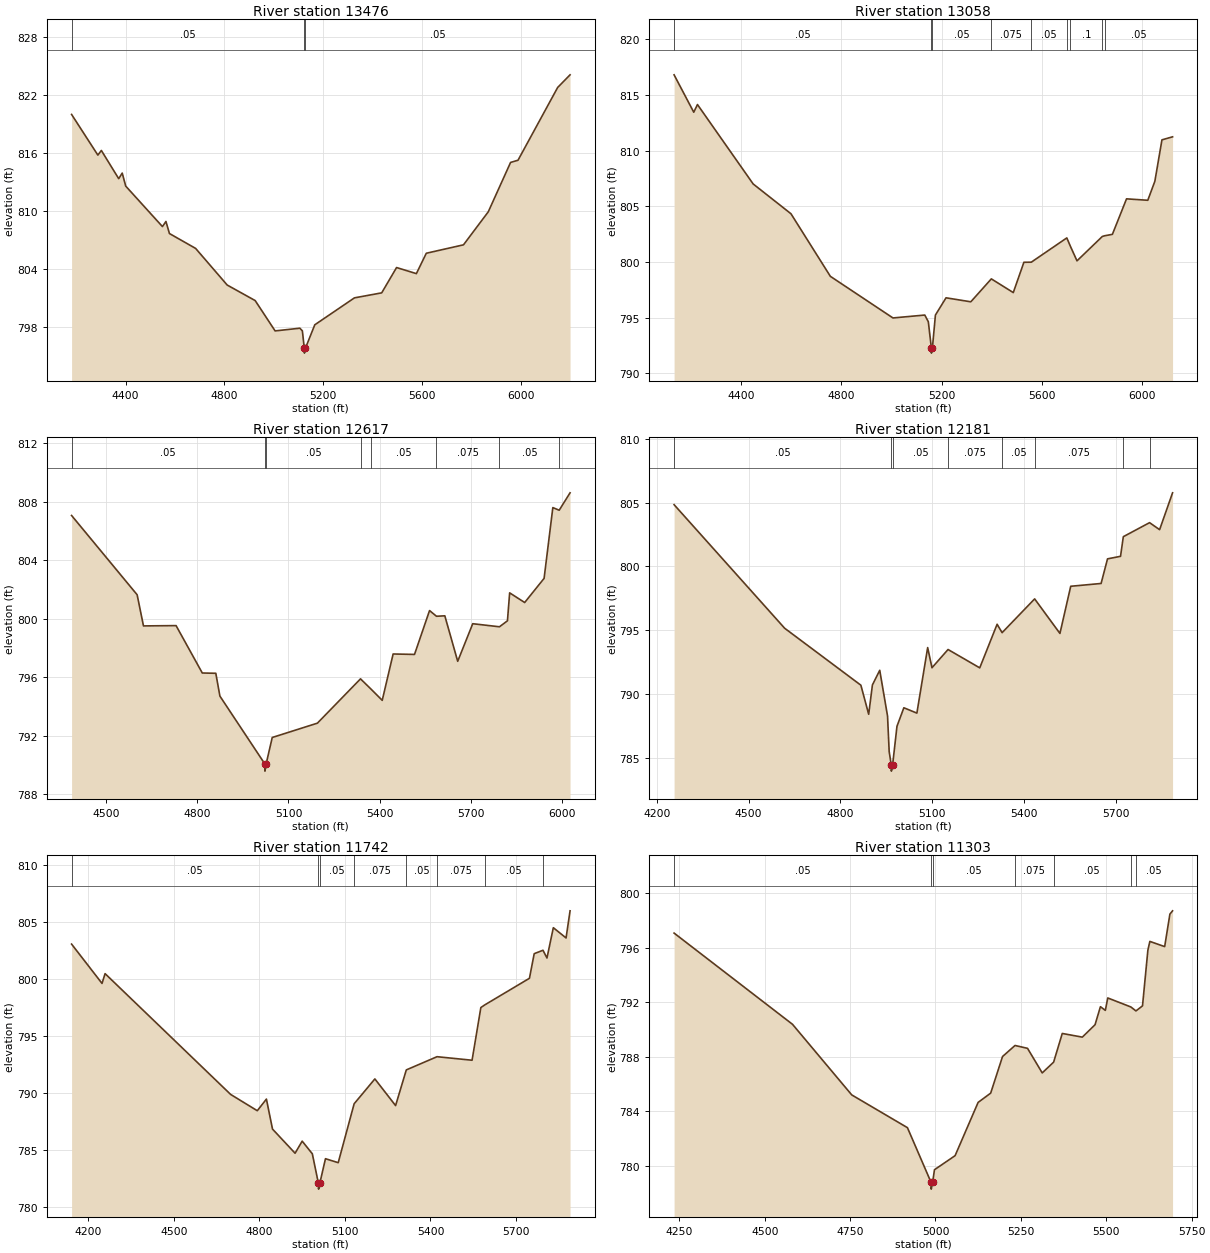
Type RM Length L Ch R = 1,13476,418,418,418
BEGIN DESCRIPTION:
Elizabeth Creek Tributary 22 21.0
END DESCRIPTION:
XS GIS Cut Line= 3
      2306679.00      7066360.00      2306079.00      7065810.00
      2304879.00      7065710.00
#Sta/Elev= 30
  4181.5  819.97  4287.9  815.76  4302.0  816.24  4372.3  813.32  4386.5  813.90
  4400.7  812.55  4549.3  808.36  4563.5  808.89  4577.7  807.64  4683.7  806.10
  4811.4  802.31  4924.8  800.70  5005.5  797.56  5105.8  797.84  5115.9  797.56
  5123.6  795.76  5124.1  795.26  5128.1  795.76  5166.0  798.19  5326.6  800.98
  5437.0  801.50  5497.2  804.12  5577.4  803.49  5617.6  805.60  5768.1  806.47
  5868.5  809.89  5958.8  815.00  5988.9  815.23  6149.4  822.76  6199.6  824.07
#Mann=3,-1,0
  4181.5    0.05       0  5123.6   0.033       0  5128.1    0.05       0
Bank Sta=5123.6,5128.1
Exp/Cntr=0.3,0.1

Type RM Length L Ch R = 1,13058,441,441,441
BEGIN DESCRIPTION:
Elizabeth Creek Tributary 22 20.0
END DESCRIPTION:
XS GIS Cut Line= 3
      2306728.99      7066159.99      2306229.00      7065460.00
      2305428.99      7064659.99
#Sta/Elev= 30
  4131.4  816.81  4210.0  813.45  4224.8  814.14  4447.2  807.01  4598.4  804.33
  4755.7  798.71  5005.8  794.97  5133.0  795.23  5147.2  794.63  5159.1  792.31
  5159.5  791.81  5163.6  792.31  5175.5  795.23  5217.9  796.78  5316.9  796.42
  5398.9  798.48  5486.6  797.25  5529.0  799.97  5558.6  799.98  5700.5  802.16
  5714.6  801.42  5741.2  800.10  5842.4  802.29  5851.2  802.35  5882.6  802.48
  5939.1  805.67  6024.0  805.54  6052.3  807.25  6080.6  810.97  6123.0  811.24
#Mann=9,-1,0
  4131.4    0.05       0  5159.1   0.033       0  5163.6    0.05       0
  5398.9   0.075       0  5558.6    0.05       0  5700.5   0.075       0
  5714.6     0.1       0  5842.4   0.075       0  5851.2    0.05       0
Bank Sta=5159.1,5163.6
Exp/Cntr=0.3,0.1

Type RM Length L Ch R = 1,12617,436,436,436
BEGIN DESCRIPTION:
Elizabeth Creek Tributary 22 19.0
END DESCRIPTION:
XS GIS Cut Line= 3
      2306829.01      7065610.02      2306479.00      7065110.00
      2305679.02      7064460.02
#Sta/Elev= 30
  4385.9  807.07  4601.7  801.65  4622.6  799.52  4729.9  799.54  4816.2  796.30
  4860.7  796.28  4874.2  794.72  5021.9  790.09  5022.4  789.59  5026.5  790.09
  5046.5  791.89  5195.2  792.87  5337.1  795.90  5373.1  795.17  5408.6  794.43
  5444.5  797.60  5514.9  797.57  5564.4  800.57  5587.2  800.18  5614.7  800.21
  5657.1  797.10  5706.6  799.67  5794.6  799.46  5820.9  799.87  5828.1  801.78
  5877.6  801.12  5941.5  802.77  5970.3  807.61  5991.2  807.43  6027.0  808.62
#Mann=8,-1,0
  4385.9    0.05       0  5021.9   0.033       0  5026.5    0.05       0
  5337.1   0.075       0  5373.1    0.05       0  5587.2   0.075       0
  5794.6    0.05       0  5991.2   0.075       0
Bank Sta=5021.9,5026.5
Exp/Cntr=0.3,0.1

Type RM Length L Ch R = 1,12181,439,439,439
BEGIN DESCRIPTION:
Elizabeth Creek Tributary 22 18.0
END DESCRIPTION:
XS GIS Cut Line= 3
      2306878.99      7065459.98      2306629.00      7064760.00
      2305978.98      7064159.98
#Sta/Elev= 30
  4256.7  804.84  4617.7  795.15  4866.7  790.68  4892.2  788.40  4904.4  790.70
  4928.3  791.85  4953.8  788.26  4959.1  785.48  4965.8  784.44  4966.3  783.94
  4970.4  784.44  4984.6  787.46  5007.1  788.91  5049.6  788.49  5084.8  793.63
  5098.9  792.05  5151.4  793.48  5254.9  792.04  5311.6  795.46  5327.9  794.80
  5434.2  797.45  5516.8  794.74  5552.0  798.44  5651.2  798.66  5672.2  800.59
  5714.7  800.79  5723.8  802.33  5809.5  803.43  5842.3  802.88  5884.6  805.77
#Mann=8,-1,0
  4256.7    0.05       0  4965.8   0.033       0  4970.4    0.05       0
  5151.4   0.075       0  5327.9    0.05       0  5434.2   0.075       0
  5723.8    0.05       0  5809.5   0.075       0
Bank Sta=4965.8,4970.4
Exp/Cntr=0.3,0.1

Type RM Length L Ch R = 1,11742,439,439,439
BEGIN DESCRIPTION:
Elizabeth Creek Tributary 22 17.0
END DESCRIPTION:
XS GIS Cut Line= 3
      2307229.00      7065259.99      2306929.00      7064460.00
      2306129.02      7064060.01
#Sta/Elev= 30
  4141.0  803.03  4247.8  799.58  4258.5  800.44  4699.0  789.84  4792.5  788.41
  4824.5  789.43  4845.9  786.80  4925.1  784.68  4950.0  785.74  4985.6  784.63
  5007.0  782.03  5007.5  781.53  5011.7  782.03  5031.7  784.20  5076.4  783.85
  5132.3  789.02  5205.0  791.20  5277.7  788.86  5315.3  791.99  5423.0  793.15
  5546.0  792.84  5576.8  797.46  5590.2  797.69  5747.3  800.03  5764.0  802.19
  5794.8  802.49  5808.8  801.81  5831.1  804.47  5875.8  803.57  5889.8  805.95
#Mann=8,-1,0
  4141.0    0.05       0  5007.0   0.033       0  5011.7    0.05       0
  5132.3   0.075       0  5315.3    0.05       0  5423.0   0.075       0
  5590.2    0.05       0  5794.8   0.075       0
Bank Sta=5007,5011.7
Exp/Cntr=0.3,0.1

Type RM Length L Ch R = 1,11303,472,472,472
BEGIN DESCRIPTION:
Elizabeth Creek Tributary 22 16.0
END DESCRIPTION:
XS GIS Cut Line= 3
      2307378.99      7064959.97      2307229.00      7064210.00
      2306629.04      7063860.02
#Sta/Elev= 30
  4234.7  797.06  4581.4  790.38  4754.8  785.21  4917.9  782.81  4987.0  778.81
  4987.5  778.31  4991.7  778.81  4997.0  779.73  5057.4  780.76  5124.8  784.66
  5161.6  785.34  5196.3  788.02  5232.9  788.83  5269.5  788.62  5312.5  786.82
  5345.9  787.61  5371.2  789.71  5429.9  789.44  5467.2  790.35  5482.9  791.67
  5497.3  791.40  5504.4  792.31  5572.0  791.65  5586.9  791.36  5606.1  791.73
  5621.8  795.80  5627.6  796.45  5671.0  796.07  5686.3  798.45  5694.1  798.69
#Mann=7,-1,0
  4234.7    0.05       0  4987.0   0.033       0  4991.7    0.05       0
  5232.9   0.075       0  5345.9    0.05       0  5572.0   0.075       0
  5586.9    0.05       0
Bank Sta=4987,4991.7
Exp/Cntr=0.3,0.1