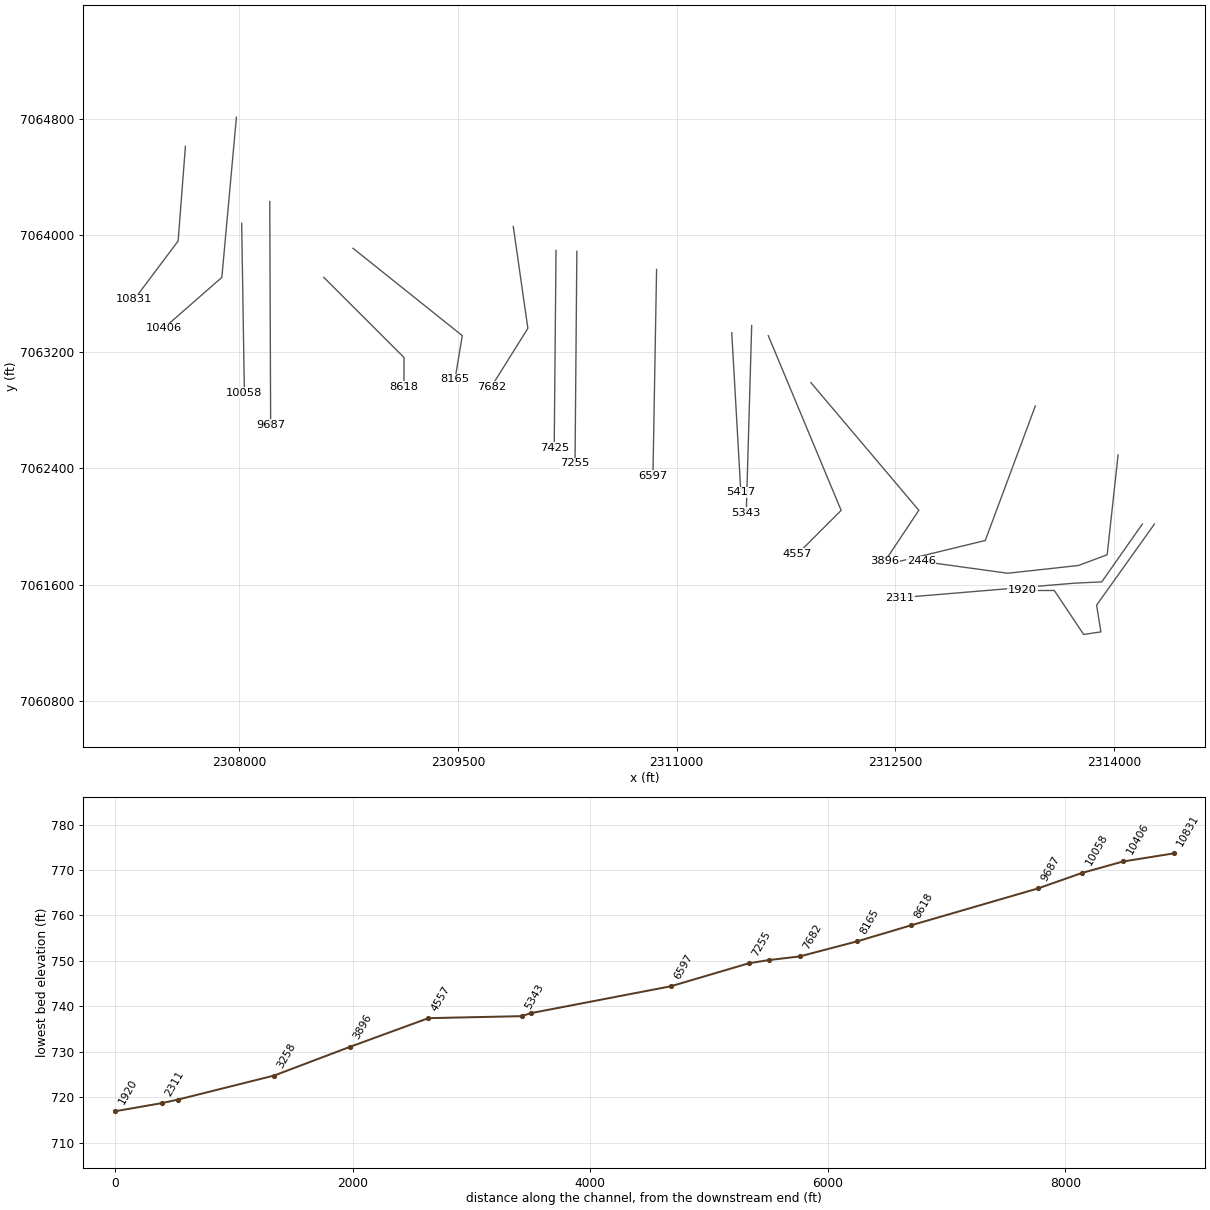
HEC-RAS study Elizabeth Cr Tr 22.prj: Elizabeth Cr Tr 22 Base Level Engineering

--- Elizabeth Cr Tr 22.g01 (geometry) --- (continued)

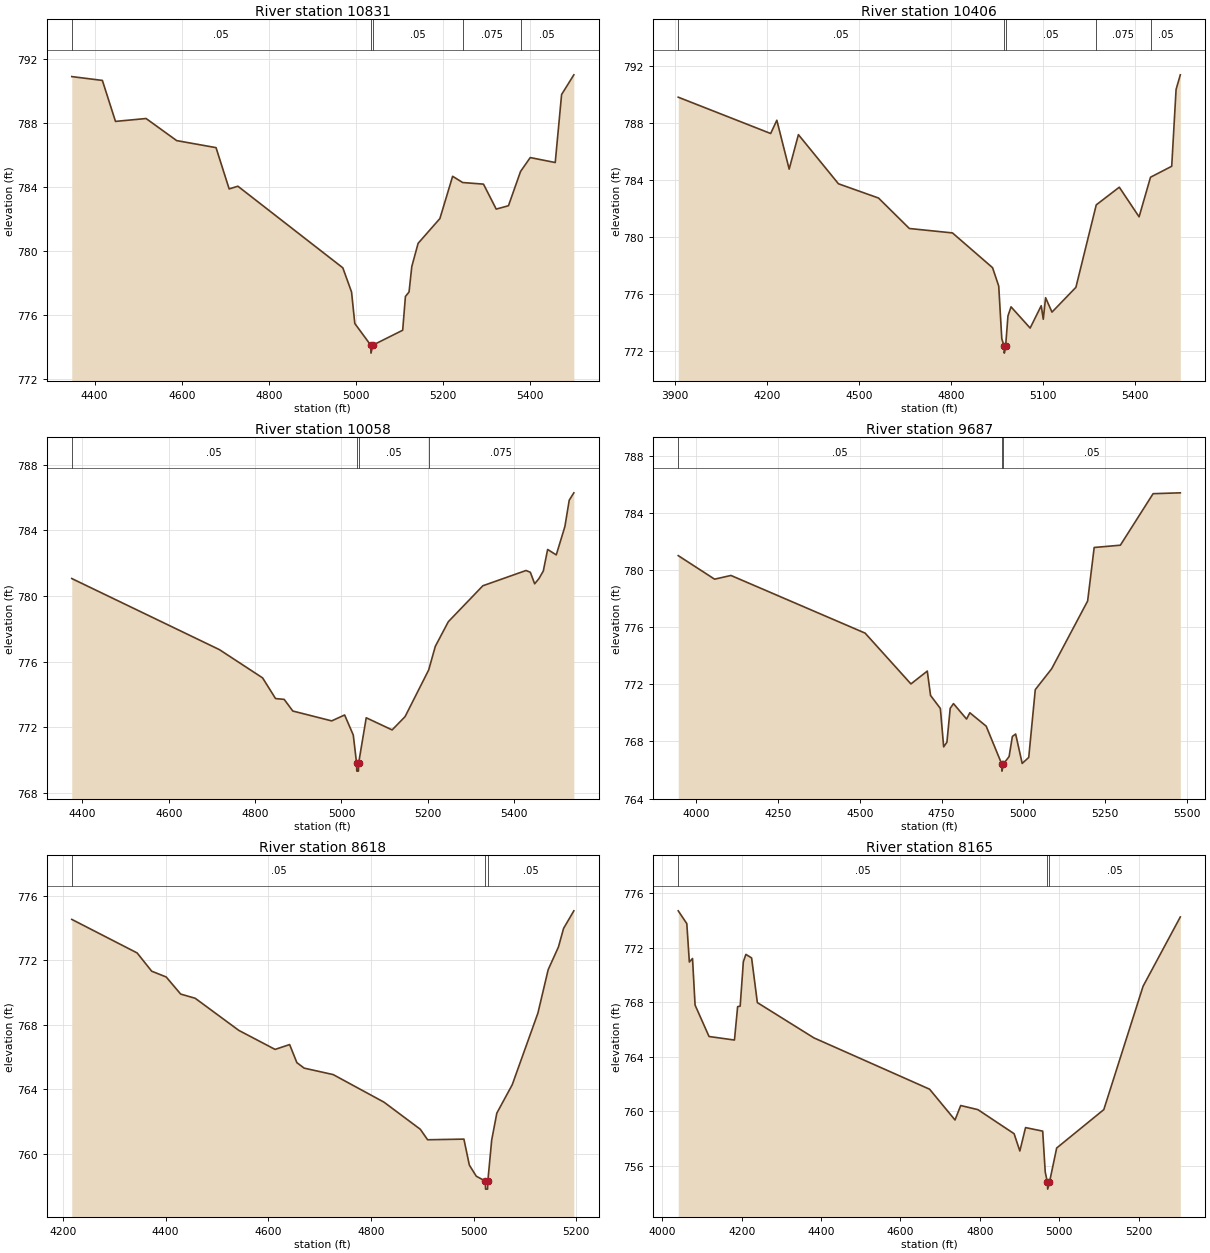
Type RM Length L Ch R = 1,10831,425,425,425
BEGIN DESCRIPTION:
Elizabeth Creek Tributary 22 15.0
END DESCRIPTION:
XS GIS Cut Line= 3
      2307629.00      7064610.02      2307579.00      7063960.00
      2307279.02      7063560.03
#Sta/Elev= 30
  4347.8  790.92  4418.0  790.68  4448.1  788.12  4518.3  788.30  4588.5  786.92
  4678.8  786.48  4708.9  783.90  4728.9  784.07  4969.7  778.97  4989.7  777.46
  4997.2  775.49  5033.7  774.14  5034.3  773.64  5038.6  774.14  5107.0  775.07
  5113.3  777.18  5121.6  777.46  5127.9  779.05  5142.4  780.50  5192.4  782.05
  5221.6  784.69  5244.7  784.30  5292.4  784.20  5321.6  782.64  5349.7  782.85
  5377.4  784.99  5399.7  785.86  5457.0  785.55  5471.6  789.80  5499.7  791.03
#Mann=5,-1,0
  4347.8    0.05       0  5033.7   0.033       0  5038.6    0.05       0
  5244.7   0.075       0  5377.4    0.05       0
Bank Sta=5033.7,5038.6
Exp/Cntr=0.3,0.1

Type RM Length L Ch R = 1,10406,348,348,348
BEGIN DESCRIPTION:
Elizabeth Creek Tributary 22 14.0
END DESCRIPTION:
XS GIS Cut Line= 3
      2307979.00      7064809.97      2307879.00      7063710.00
      2307479.01      7063360.01
#Sta/Elev= 30
  3910.7  789.84  4211.9  787.29  4232.0  788.22  4272.2  784.79  4302.3  787.21
  4432.8  783.76  4563.3  782.76  4663.8  780.62  4804.3  780.31  4934.9  777.87
  4955.0  776.58  4965.0  772.88  4972.6  772.37  4973.2  771.87  4977.5  772.37
  4985.1  774.48  4995.1  775.12  5057.4  773.63  5093.5  775.20  5100.2  774.25
  5107.7  775.76  5128.6  774.75  5206.5  776.49  5272.8  782.28  5347.9  783.52
  5412.4  781.44  5449.6  784.22  5518.7  784.99  5532.9  790.38  5546.7  791.41
#Mann=5,-1,0
  3910.7    0.05       0  4972.6   0.033       0  4977.5    0.05       0
  5272.8   0.075       0  5449.6    0.05       0
Bank Sta=4972.6,4977.5
Exp/Cntr=0.3,0.1

Type RM Length L Ch R = 1,10058,371,371,371
BEGIN DESCRIPTION:
1058
END DESCRIPTION:
XS GIS Cut Line= 2
      2308015.07      7064081.84      2308033.72      7062919.29
#Sta/Elev= 30
  4375.4  781.06  4717.3  776.73  4817.3  775.01  4847.3  773.75  4867.3  773.70
  4887.3  772.99  4977.3  772.39  5007.3  772.75  5027.3  771.53  5034.9  769.83
  5035.5  769.33  5039.2  769.33  5039.8  769.83  5057.3  772.58  5117.3  771.84
  5147.3  772.65  5201.9  775.49  5217.3  776.93  5247.4  778.43  5327.4  780.62
  5427.4  781.55  5437.4  781.44  5447.4  780.74  5457.4  781.06  5467.4  781.52
  5477.4  782.83  5497.4  782.50  5517.4  784.23  5527.4  785.83  5538.1  786.28
#Mann=4,-1,0
  4375.4    0.05       0  5034.9   0.033       0  5039.8    0.05       0
  5201.9   0.075       0
Bank Sta=5034.9,5039.8
Exp/Cntr=0.3,0.1

Type RM Length L Ch R = 1,9687,1069,1069,1069
BEGIN DESCRIPTION:
1059
END DESCRIPTION:
XS GIS Cut Line= 2
      2308207.79      7064231.08      2308214.00      7062696.79
#Sta/Elev= 30
  3945.2  781.02  4056.3  779.37  4106.3  779.63  4516.3  775.59  4656.3  772.03
  4706.3  772.93  4716.3  771.22  4746.3  770.31  4756.3  767.62  4766.3  767.95
  4776.3  770.32  4786.3  770.65  4826.3  769.57  4836.3  770.01  4886.3  769.07
  4933.8  766.42  4934.4  765.92  4938.8  766.42  4956.3  766.94  4966.3  768.35
  4976.3  768.52  4996.3  766.46  5016.3  766.88  5036.3  771.63  5086.3  773.09
  5196.3  777.84  5216.3  781.59  5296.3  781.75  5396.3  785.36  5479.5  785.42
#Mann=3,-1,0
  3945.2    0.05       0  4933.8   0.033       0  4938.8    0.05       0
Bank Sta=4933.8,4938.8
Exp/Cntr=0.3,0.1

Type RM Length L Ch R = 1,8618,453,453,453
BEGIN DESCRIPTION:
Elizabeth Creek Tributary 22 12.0
END DESCRIPTION:
XS GIS Cut Line= 3
      2308579.00      7063710.00      2309129.00      7063160.00
      2309129.00      7062960.02
#Sta/Elev= 30
  4217.4  774.52  4344.7  772.44  4373.0  771.31  4401.3  770.95  4429.5  769.89
  4457.8  769.63  4542.7  767.64  4613.4  766.46  4641.7  766.76  4655.8  765.64
  4670.0  765.30  4726.5  764.90  4825.5  763.19  4896.2  761.51  4910.4  760.86
  4981.1  760.90  4991.7  759.29  5005.2  758.60  5022.7  758.30  5023.3  757.80
  5027.1  757.80  5027.7  758.30  5035.2  760.84  5045.2  762.51  5075.2  764.27
  5125.2  768.71  5145.2  771.40  5165.2  772.81  5175.2  773.96  5195.2  775.05
#Mann=3,-1,0
  4217.4    0.05       0  5022.7   0.033       0  5027.7    0.05       0
Bank Sta=5022.7,5027.7
Exp/Cntr=0.3,0.1

Type RM Length L Ch R = 1,8165,483,483,483
BEGIN DESCRIPTION:
Elizabeth Creek Tributary 22 11.0
END DESCRIPTION:
XS GIS Cut Line= 3
      2308779.03      7063909.97      2309529.00      7063310.00
      2309478.99      7063009.96
#Sta/Elev= 30
  4040.2  774.72  4061.8  773.78  4068.2  770.96  4076.2  771.22  4082.6  767.80
  4117.8  765.49  4181.8  765.23  4189.8  767.68  4196.2  767.72  4204.2  770.98
  4210.6  771.52  4225.0  771.26  4239.5  767.98  4381.9  765.39  4673.3  761.62
  4737.3  759.36  4751.7  760.42  4794.9  760.12  4886.2  758.35  4900.6  757.08
  4915.0  758.80  4958.2  758.54  4964.6  755.53  4970.1  754.78  4970.7  754.28
  4975.2  754.78  4993.4  757.30  5112.1  760.12  5211.0  769.18  5304.8  774.27
#Mann=3,-1,0
  4040.2    0.05       0  4970.1   0.033       0  4975.2    0.05       0
Bank Sta=4970.1,4975.2
Exp/Cntr=0.3,0.1

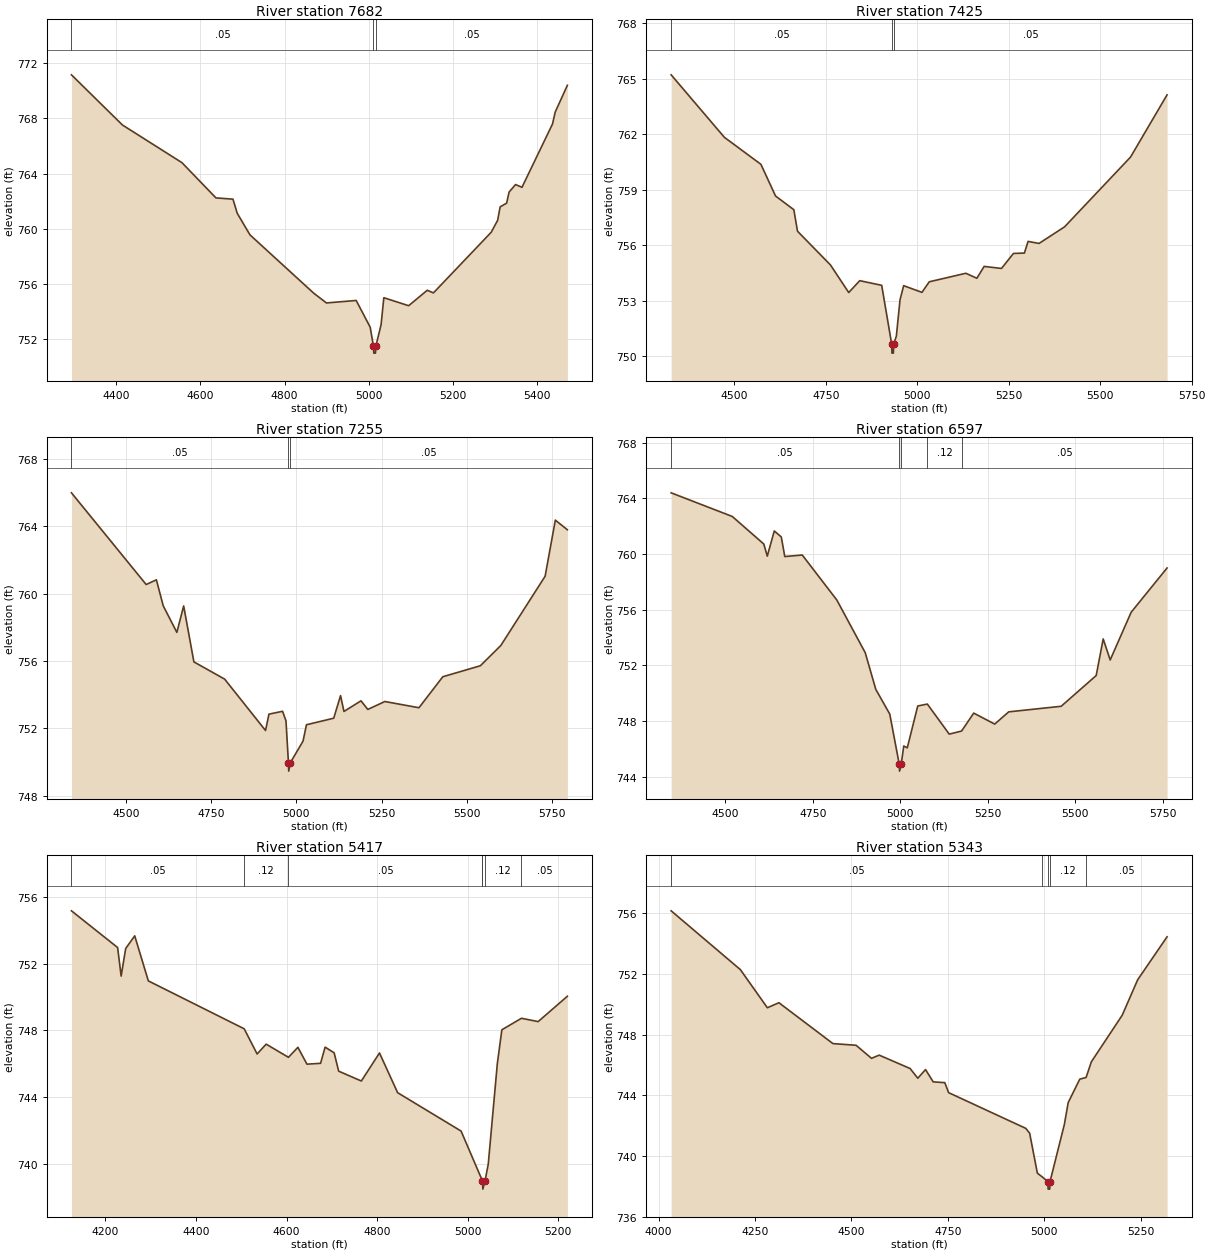
Type RM Length L Ch R = 1,7682,257,257,257
BEGIN DESCRIPTION:
Elizabeth Creek Tributary 22 10.0
END DESCRIPTION:
XS GIS Cut Line= 3
      2309879.00      7064060.00      2309979.00      7063360.00
      2309729.01      7062960.01
#Sta/Elev= 30
  4293.3  771.16  4414.5  767.52  4555.9  764.79  4636.8  762.23  4677.2  762.14
  4687.3  761.12  4717.6  759.55  4869.1  755.32  4899.4  754.61  4970.1  754.79
  5003.4  752.85  5011.2  751.47  5012.0  750.97  5015.9  750.97  5016.8  751.47
  5029.3  753.04  5035.8  754.99  5094.8  754.41  5139.0  755.53  5153.7  755.34
  5291.1  759.74  5306.4  760.61  5312.3  761.58  5327.7  761.85  5333.5  762.65
  5348.9  763.20  5364.2  763.00  5436.7  767.59  5443.2  768.46  5472.1  770.40
#Mann=3,-1,0
  4293.3    0.05       0  5011.2   0.033       0  5016.8    0.05       0
Bank Sta=5011.2,5016.8
Exp/Cntr=0.3,0.1

Type RM Length L Ch R = 1,7425,170,170,170
BEGIN DESCRIPTION:
1052
END DESCRIPTION:
XS GIS Cut Line= 2
      2310172.30      7063895.33      2310159.87      7062540.09
#Sta/Elev= 30
  4327.5  765.20  4472.8  761.83  4572.8  760.37  4612.8  758.66  4662.8  757.92
  4672.8  756.76  4762.8  754.94  4812.8  753.45  4842.9  754.09  4902.9  753.84
  4930.1  750.68  4930.9  750.18  4934.8  750.18  4935.7  750.68  4942.9  751.09
  4952.9  753.05  4962.9  753.82  5012.9  753.46  5032.9  754.03  5132.9  754.49
  5162.9  754.22  5182.9  754.86  5230.3  754.75  5262.9  755.56  5292.9  755.58
  5302.9  756.21  5332.9  756.10  5402.9  757.00  5582.9  760.76  5682.8  764.12
#Mann=3,-1,0
  4327.5    0.05       0  4930.1    0.05       0  4935.7    0.05       0
Bank Sta=4930.1,4935.7
Exp/Cntr=0.3,0.1

Type RM Length L Ch R = 1,7255,658,658,658
BEGIN DESCRIPTION:
1053
END DESCRIPTION:
XS GIS Cut Line= 2
      2310315.29      7063889.13      2310302.86      7062434.69
#Sta/Elev= 30
  4340.4  765.98  4559.5  760.54  4589.5  760.82  4609.5  759.28  4649.5  757.70
  4669.5  759.27  4699.5  755.95  4789.6  754.93  4909.6  751.88  4919.6  752.85
  4959.6  753.02  4969.6  752.45  4976.8  749.97  4977.6  749.47  4982.4  749.97
  5019.6  751.25  5029.6  752.22  5109.6  752.61  5129.6  753.95  5139.6  753.01
  5189.6  753.64  5209.6  753.13  5259.6  753.60  5359.6  753.23  5429.6  755.07
  5539.6  755.72  5599.6  756.92  5729.6  761.03  5759.6  764.36  5794.9  763.79
#Mann=3,-1,0
  4340.4    0.05       0  4976.8    0.05       0  4982.4    0.05       0
Bank Sta=4976.8,4982.4
Exp/Cntr=0.3,0.1

Type RM Length L Ch R = 1,6597,1180,1180,1180
BEGIN DESCRIPTION:
1056
END DESCRIPTION:
XS GIS Cut Line= 2
      2310862.37      7063764.76      2310837.50      7062347.38
#Sta/Elev= 30
  4345.3  764.40  4520.1  762.70  4610.1  760.72  4620.1  759.85  4640.1  761.66
  4660.1  761.23  4670.1  759.82  4720.1  759.93  4818.8  756.70  4900.1  752.91
  4930.2  750.28  4970.2  748.50  4997.3  744.90  4998.2  744.40  5003.0  744.90
  5010.2  746.21  5020.2  746.07  5050.2  749.08  5077.6  749.22  5140.2  747.06
  5175.5  747.28  5210.2  748.57  5270.2  747.78  5310.2  748.66  5460.2  749.06
  5560.3  751.27  5580.3  753.90  5600.3  752.39  5660.3  755.82  5762.9  759.00
#Mann=5,-1,0
  4345.3    0.05       0  4997.3   0.033       0  5003.0    0.05       0
  5077.6    0.12       0  5175.5    0.05       0
Bank Sta=4997.3,5003
Exp/Cntr=0.3,0.1

Type RM Length L Ch R = 1,5417,74,74,74
BEGIN DESCRIPTION:
1055
END DESCRIPTION:
XS GIS Cut Line= 2
      2311378.37      7063329.59      2311440.53      7062235.46
#Sta/Elev= 30
  4124.8  755.16  4226.8  752.96  4234.6  751.25  4244.6  752.90  4264.6  753.66
  4294.7  750.96  4506.5  748.09  4535.1  746.58  4555.1  747.17  4604.3  746.38
  4625.2  746.98  4645.2  745.97  4675.3  746.02  4685.3  746.99  4705.3  746.65
  4715.3  745.55  4765.4  744.96  4805.5  746.64  4845.6  744.26  4985.8  741.96
  5032.6  739.00  5033.0  738.98  5033.9  738.48  5038.8  738.98  5045.9  739.99
  5065.9  746.00  5075.9  748.03  5119.3  748.72  5156.1  748.52  5220.7  750.04
#Mann=7,-1,0
  4124.8    0.05       0  4506.5    0.12       0  4604.3    0.05       0
  5032.6    0.12       0  5033.0   0.033       0  5038.8    0.12       0
  5119.3    0.05       0
Bank Sta=5033,5038.8
Exp/Cntr=0.3,0.1

Type RM Length L Ch R = 1,5343,786,786,786
BEGIN DESCRIPTION:
1054
END DESCRIPTION:
XS GIS Cut Line= 2
      2311515.14      7063379.39      2311477.87      7062093.73
#Sta/Elev= 30
  4032.5  756.15  4212.0  752.28  4282.0  749.77  4312.0  750.10  4452.1  747.41
  4512.1  747.30  4552.1  746.44  4572.1  746.65  4652.2  745.77  4672.2  745.13
  4692.2  745.70  4712.2  744.89  4742.2  744.84  4752.2  744.18  4952.3  741.83
  4962.3  741.51  4982.3  738.88  4994.6  738.64  5009.4  738.33  5010.3  737.83
  5014.3  737.83  5015.2  738.33  5052.3  742.09  5062.3  743.53  5092.3  745.07
  5108.7  745.18  5122.3  746.21  5202.4  749.28  5242.4  751.61  5318.7  754.44
#Mann=5,-1,0
  4032.5    0.05       0  4994.6    0.12       0  5009.4    0.07       0
  5015.2    0.12       0  5108.7    0.05       0
Bank Sta=5009.4,5015.2
Exp/Cntr=0.3,0.1

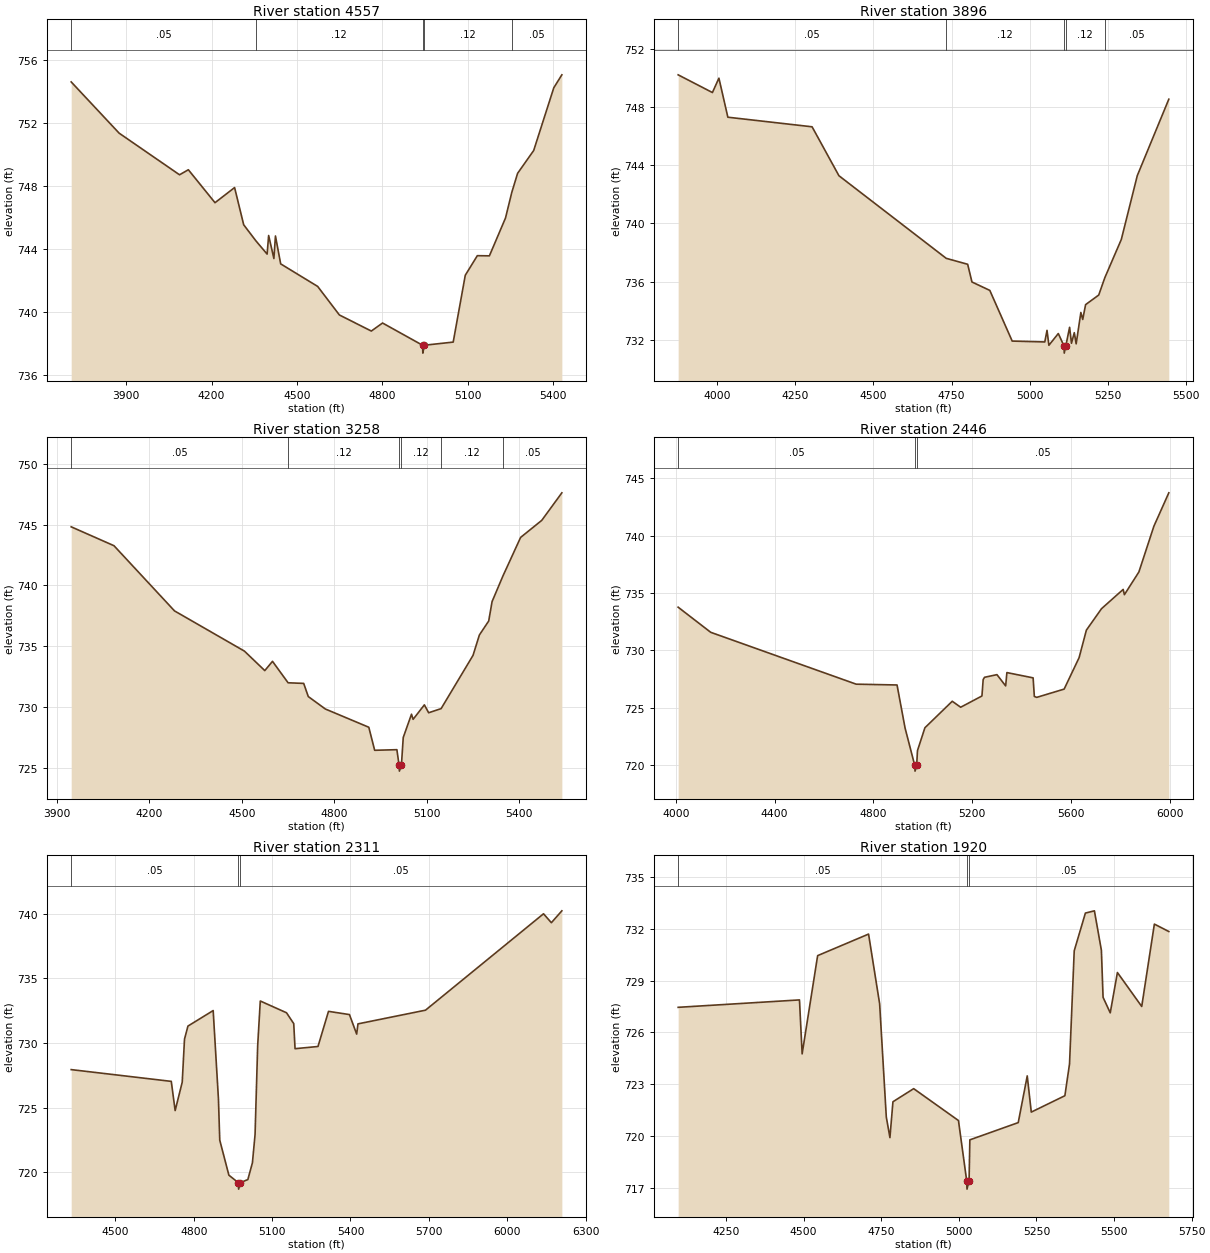
Type RM Length L Ch R = 1,4557,661,661,661
BEGIN DESCRIPTION:
Elizabeth Creek Tributary 22 5.0
END DESCRIPTION:
XS GIS Cut Line= 3
      2311628.98      7063310.04      2312129.00      7062110.00
      2311829.00      7061810.00
#Sta/Elev= 30
  3706.8  754.59  3875.3  751.34  4087.6  748.70  4118.5  749.02  4212.2  746.93
  4281.0  747.89  4313.0  745.53  4355.5  744.52  4395.3  743.67  4400.7  744.85
  4419.1  743.39  4424.6  744.82  4443.0  743.05  4573.0  741.62  4649.3  739.81
  4761.5  738.79  4801.0  739.30  4941.6  737.89  4942.6  737.39  4947.5  737.89
  5049.3  738.09  5091.7  742.33  5134.1  743.57  5176.5  743.56  5233.1  745.96
  5255.1  747.58  5275.5  748.79  5332.1  750.24  5402.8  754.22  5431.1  755.04
#Mann=5,-1,0
  3706.8    0.05       0  4355.5    0.12       0  4941.6    0.07       0
  4947.5    0.12       0  5255.1    0.05       0
Bank Sta=4941.6,4947.5
Exp/Cntr=0.3,0.1

Type RM Length L Ch R = 1,3896,638,638,638
BEGIN DESCRIPTION:
Elizabeth Creek Tributary 22 4.0
END DESCRIPTION:
XS GIS Cut Line= 3
      2311921.94      7062987.00      2312662.20      7062110.53
      2312428.98      7061759.97
#Sta/Elev= 30
  3875.9  750.24  3985.4  749.02  4006.2  750.01  4034.8  747.32  4304.0  746.66
  4389.8  743.29  4732.7  737.60  4801.3  737.19  4815.0  735.97  4872.1  735.39
  4943.6  731.90  5047.8  731.84  5054.9  732.64  5060.9  731.61  5091.0  732.42
  5109.1  731.57  5110.0  731.07  5115.0  731.57  5127.1  732.85  5133.1  731.75
  5142.1  732.48  5148.1  731.71  5163.1  733.87  5169.1  733.39  5178.2  734.41
  5220.2  735.07  5239.6  736.26  5292.4  738.90  5343.5  743.30  5444.2  748.56
#Mann=5,-1,0
  3875.9    0.05       0  4732.7    0.12       0  5109.1    0.07       0
  5115.0    0.12       0  5239.6    0.05       0
Bank Sta=5109.1,5115
Exp/Cntr=0.3,0.1

Type RM Length L Ch R = 1,3258,812,812,812
BEGIN DESCRIPTION:
Elizabeth Creek Tributary 22 3.0
END DESCRIPTION:
XS GIS Cut Line= 3
      2313461.64      7062827.03      2313118.19      7061903.26
      2312529.00      7061760.00
#Sta/Elev= 30
  3946.1  744.81  4084.9  743.26  4281.3  737.91  4508.1  734.61  4574.2  733.01
  4599.2  733.77  4649.8  732.01  4700.4  731.96  4715.3  730.88  4770.6  729.86
  4911.7  728.36  4930.7  726.47  5002.8  726.52  5009.8  725.26  5010.9  724.76
  5017.5  725.26  5023.4  727.52  5050.2  729.43  5055.4  729.01  5092.0  730.20
  5105.8  729.55  5146.3  729.89  5249.8  734.26  5270.4  735.93  5300.7  737.08
  5311.6  738.67  5346.9  740.78  5404.2  743.94  5472.8  745.34  5538.0  747.60
#Mann=6,-1,0
  3946.1    0.05       0  4649.8    0.12       0  5009.8    0.07       0
  5017.5    0.12       0  5146.3    0.12       0  5346.9    0.05       0
Bank Sta=5009.8,5017.5
Exp/Cntr=0.3,0.1

Type RM Length L Ch R = 1,2446,135,135,135
BEGIN DESCRIPTION:
Elizabeth Creek Tributary 22 2.0
END DESCRIPTION:
XS GIS Cut Line= 5
      2314029.59      7062491.26      2313954.73      7061805.40
      2313757.75      7061731.53      2313272.15      7061678.23
      2312678.98      7061760.00
#Sta/Elev= 30
  4009.0  733.75  4141.0  731.56  4730.1  727.04  4895.7  726.97  4928.2  723.22
  4967.4  719.96  4968.6  719.46  4975.2  719.96  4978.5  721.25  5008.6  723.24
  5119.3  725.55  5153.5  725.03  5239.6  726.01  5244.6  727.44  5250.1  727.64
  5300.4  727.87  5335.7  726.89  5340.7  728.05  5446.9  727.59  5451.9  725.97
  5461.6  725.89  5572.6  726.61  5633.2  729.35  5662.7  731.75  5724.0  733.62
  5811.7  735.30  5816.7  734.84  5875.4  736.82  5936.0  740.80  5996.6  743.72
#Mann=3,-1,0
  4009.0    0.05       0  4967.4   0.033       0  4975.2    0.05       0
Bank Sta=4967.4,4975.2
Exp/Cntr=0.3,0.1

Type RM Length L Ch R = 1,2311,391,391,391
BEGIN DESCRIPTION:
Elizabeth Creek Tributary 22 1.0
END DESCRIPTION:
XS GIS Cut Line= 4
      2314195.95      7062015.76      2313917.64      7061619.01
      2313729.00      7061610.00      2312529.04      7061510.00
#Sta/Elev= 30
  4331.2  727.94  4714.2  727.03  4729.0  724.77  4756.1  726.97  4764.8  730.30
  4778.0  731.31  4874.5  732.51  4894.6  725.69  4899.7  722.48  4934.6  719.77
  4970.7  719.19  4971.9  718.69  4978.5  719.19  5007.2  719.43  5024.7  720.73
  5034.8  722.91  5044.8  729.79  5054.8  733.25  5155.2  732.34  5182.8  731.50
  5187.8  729.56  5275.6  729.73  5315.8  732.45  5396.0  732.20  5423.6  730.69
  5428.6  731.48  5687.0  732.54  6138.6  740.00  6168.7  739.31  6208.8  740.23
#Mann=3,-1,0
  4331.2    0.05       0  4970.7   0.033       0  4978.5    0.05       0
Bank Sta=4970.7,4978.5
Exp/Cntr=0.3,0.1

Type RM Length L Ch R = 1,1920,0,0,0
BEGIN DESCRIPTION:
1049
END DESCRIPTION:
XS GIS Cut Line= 6
      2314278.89      7062015.81      2313882.10      7061459.12
      2313911.71      7061275.55      2313793.28      7061257.78
      2313591.93      7061559.80      2313373.37      7061559.90
#Sta/Elev= 30
  4096.3  727.46  4487.0  727.89  4495.6  724.76  4545.5  730.46  4709.5  731.71
  4745.2  727.66  4766.6  721.10  4778.3  719.90  4788.0  721.98  4854.8  722.74
  4999.0  720.89  5025.4  717.41  5026.5  716.91  5033.2  717.41  5035.7  719.77
  5191.5  720.77  5220.5  723.48  5233.5  721.38  5341.7  722.33  5356.7  724.18
  5371.8  730.74  5407.8  732.93  5436.8  733.06  5459.3  730.77  5464.7  728.04
  5487.8  727.14  5510.9  729.48  5589.2  727.51  5629.9  732.29  5676.4  731.86
#Mann=3,-1,0
  4096.3    0.05       0  5025.4   0.033       0  5033.2    0.05       0
Bank Sta=5025.4,5033.2
Exp/Cntr=0.3,0.1

Chan Stop Cuts=-1