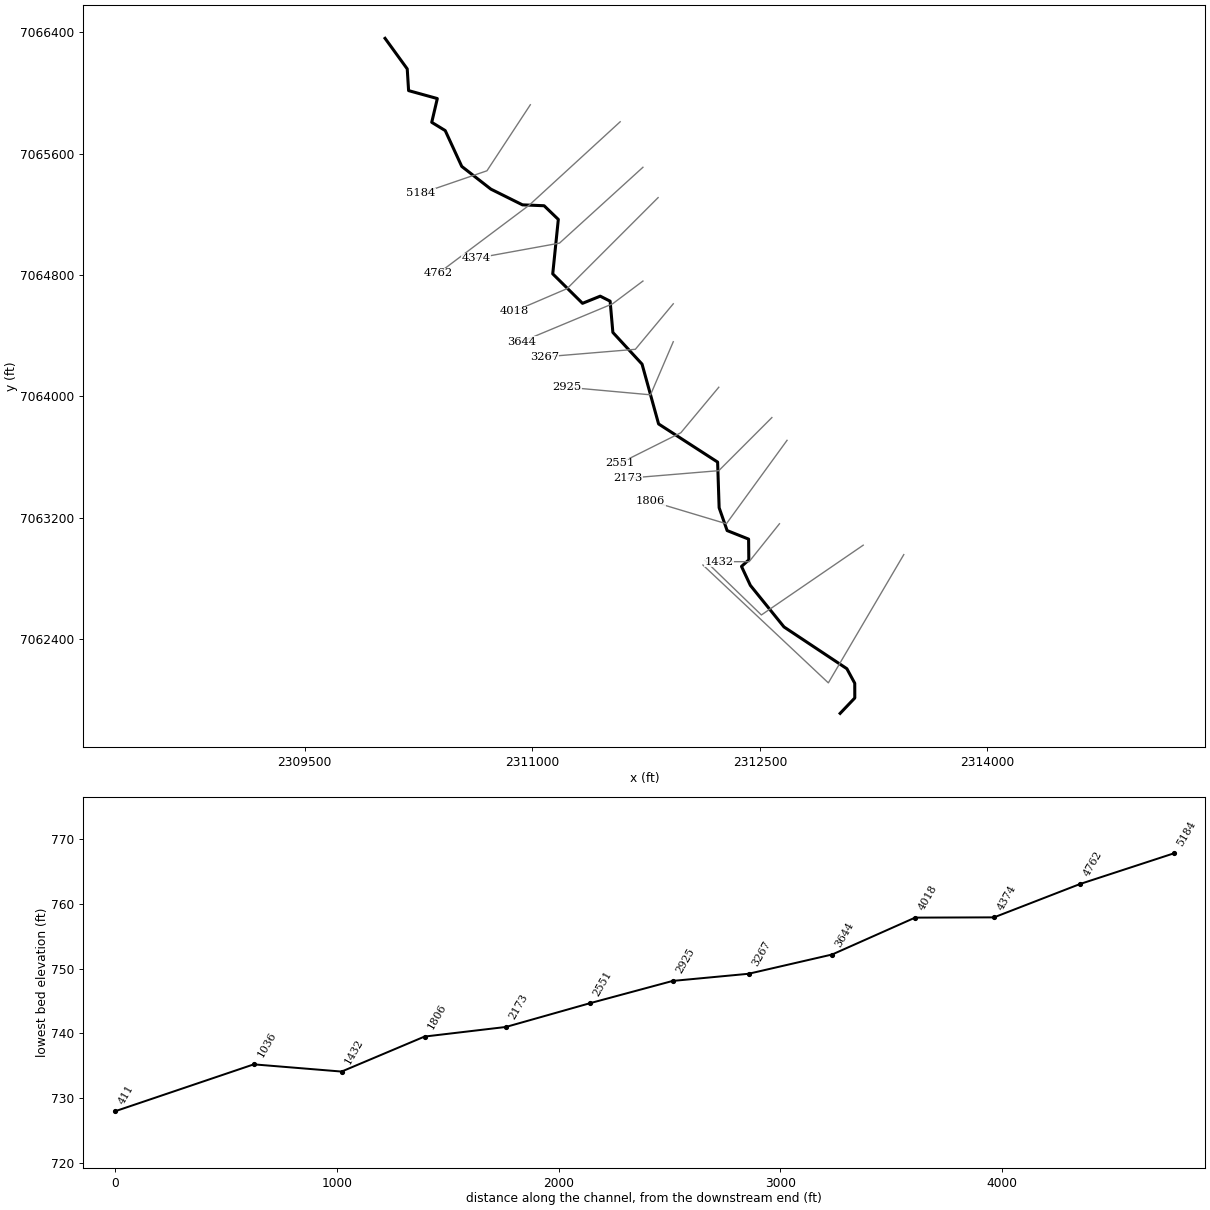
--- Elizabeth Cr Tr 22_1.prj (project) ---

Proj Title=Elizabeth Cr Tr 22_1 Base Level Engineering
Current Plan=p01
Default Exp/Contr=0.3,0.1
English Units
Geom File=g01
Flow File=f01
Plan File=p01
Y Axis Title=Elevation
X Axis Title(PF)=Main Channel Distance
X Axis Title(XS)=Station
BEGIN DESCRIPTION:
Elizabeth Cr Tr 22_1
END DESCRIPTION:
DSS Export Rating Curves= 0
DSS Export Rating Curve Sorted= 0
DSS Export Volume Flow Curves= 0
DXF OffsetX= 0
DXF OffsetY= 0
DXF ScaleX= 1
DXF ScaleY= 10

--- Elizabeth Cr Tr 22_1.p01 (plan) ---

Plan Title=Multiple Run
Program Version=4.10
Short Identifier=Multiple
Geom File=g01
Flow File=f01
Subcritical Flow
K Sum by GR= 0
Std Step Tol= 0.01
Critical Tol= 0.01
Num of Std Step Trials= 20
Max Error Tol= 0.3
Flow Tol Ratio= 0.001
Split Flow NTrial= 30
Split Flow Tol= 0.02
Split Flow Ratio= 0.02
Log Output Level= 0
Friction Slope Method= 0
Unsteady Friction Slope Method= 2
Unsteady Bridges Friction Slope Method= 1
Parabolic Critical Depth
Global Vel Dist= 1 , 1 , 1
Global Log Level= 0
CheckData=True
Encroach Param=-1 ,0,0, 0
BEGIN DESCRIPTION:
Multiple Run
END DESCRIPTION:
Computation Interval=1HOUR
Output Interval=1HOUR
Run HTab= 0
Run UNet= 0
Run PostProcess= 0
Run WQNet= 0
UNET Theta= 1
UNET Theta Warmup= 1
UNET ZTol= 0.02
UNET ZSATol= 0.05
UNET MxIter= 20
UNET MaxInSteps= 0
UNET DtIC= 0
UNET DtMin= 0
UNET MaxCRTS= 20
UNET WFStab= 2
UNET SFStab= 1
UNET WFX= 1
UNET SFX= 1
UNET DSS MLevel= 4
UNET DZMax Abort= 100
UNET Convert EG Bridges= 0
UNET Use Existing IB Tables=-1
UNET Froude Reduction=False
UNET Froude Limit= 1
UNET Froude Power= 10
UNET Time Slicing=0,0, 5
UNET Junction Losses=0
Instantaneous Interval=1HOUR
Write IC File= 0
Write IC File at Sim End=0
Echo Input=False
Echo Parameters=False
Echo Output=False
Write Detailed= 0
WQ AD Non Conservative
WQ ULTIMATE=-1
WQ Max Comp Step=1HOUR
WQ Output Interval=15MIN
WQ Output Selected Increments= 0
WQ Output face flow=0
WQ Output face velocity=0
WQ Output face area=0
WQ Output face dispersion=0
WQ Output cell volume=0
WQ Output cell surface area=0
WQ Output cell continuity=0
WQ Output cumulative cell continuity=0
WQ Output face conc=0
WQ Output face dconc_dx=0
WQ Output face courant=0
WQ Output face peclet=0
WQ Output face adv mass=0
WQ Output face disp mass=0
WQ Output cell mass=0
WQ Output cell source sink temp=0
WQ Output cell source sink nsm=0
WQ Output MaxMinRange=-1
WQ Daily Max Min Mean=-1
WQ Daily Range=0
WQ Daily Time=0
WQ Create Restart=0
WQ Fixed Restart=0
WQ System Summary=0
WQ Use Fixed Temperature=0
Sorting and Armoring Iterations= 10
XS Update Threshold= 0.02
Hydraulics Update Threshold= 0.02
Energy Slope Method= 1
Volume Change Method= 0
XS Weighting Method= 0
Number of US Weighted Cross Sections= 1
Number of DS Weighted Cross Sections= 1
Upstream XS Weight=0.25
Main XS Weight=0.5
Downstream XS Weight=0.25
Number of DS XS's Weighted with US Boundary= 1
Upstream Boundary Weight= 1
Weight of XSs Associated with US Boundary= 0
Number of US XS's Weighted with DS Boundary= 1
Downstream Boundary Weight= 0.5
Weight of XSs Associated with DS Boundary= 0.5
Sediment Output Level= 4
Mass or Volume Output= 0
Output Increment Type= 1
Profile and TS Output Increment= 10
XS Output Flag= 0
XS Output Increment= 10
Disregard all LS=0
Disregard all Conn=0
Disregard all Breaches=0
Disregard all Pumps=0

--- Elizabeth Cr Tr 22_1.f01 (steady flow) ---

Flow Title=Multiple
Number of Profiles=7
Profile Names=10-year,25-year,50-year,1pct_min,100-year,1pct_plu,500-year
River Rch & RM= Elizabeth Cr Tr ,Reach-1,5184
     374     498     598     357     712    1420    1010
River Rch & RM= Elizabeth Cr Tr ,Reach-1,4374
     456     614     742     446     890    1770    1280
Boundary for River Rch & Prof#=Elizabeth Cr Tr ,Reach-1,1
Up Type=0
Dn Type=3
Dn Slope=0.005
Boundary for River Rch & Prof#=Elizabeth Cr Tr ,Reach-1,2
Up Type=0
Dn Type=3
Dn Slope=0.005
Boundary for River Rch & Prof#=Elizabeth Cr Tr ,Reach-1,3
Up Type=0
Dn Type=3
Dn Slope=0.005
Boundary for River Rch & Prof#=Elizabeth Cr Tr ,Reach-1,4
Up Type=0
Dn Type=3
Dn Slope=0.005
Boundary for River Rch & Prof#=Elizabeth Cr Tr ,Reach-1,5
Up Type=0
Dn Type=3
Dn Slope=0.005
Boundary for River Rch & Prof#=Elizabeth Cr Tr ,Reach-1,6
Up Type=0
Dn Type=3
Dn Slope=0.005
Boundary for River Rch & Prof#=Elizabeth Cr Tr ,Reach-1,7
Up Type=0
Dn Type=3
Dn Slope=0.005

--- Elizabeth Cr Tr 22_1.g01 (geometry) ---

Geom Title=Existing Conditions

River Reach=Elizabeth Cr Tr ,Reach-1
Reach XY= 30
      2310029.00      7066360.00      2310175.24      7066158.44
      2310184.19      7066015.38      2310373.60      7065962.97
      2310336.73      7065806.35      2310425.62      7065751.95
      2310534.62      7065515.62      2310726.70      7065365.83
      2310934.93      7065262.25      2311077.54      7065256.46
      2311171.20      7065166.21      2311134.40      7064807.57
      2311330.63      7064613.13      2311447.53      7064660.26
      2311512.73      7064627.31      2311530.85      7064421.14
      2311723.21      7064212.27      2311832.23      7063817.99
      2312221.31      7063566.48      2312231.37      7063265.53
      2312284.11      7063115.11      2312425.57      7063058.77
      2312427.00      7062921.95      2312378.78      7062878.68
      2312437.14      7062753.95      2312658.87      7062479.77
      2313073.42      7062204.42      2313125.34      7062108.44
      2313125.60      7062011.48      2313029.00      7061910.00

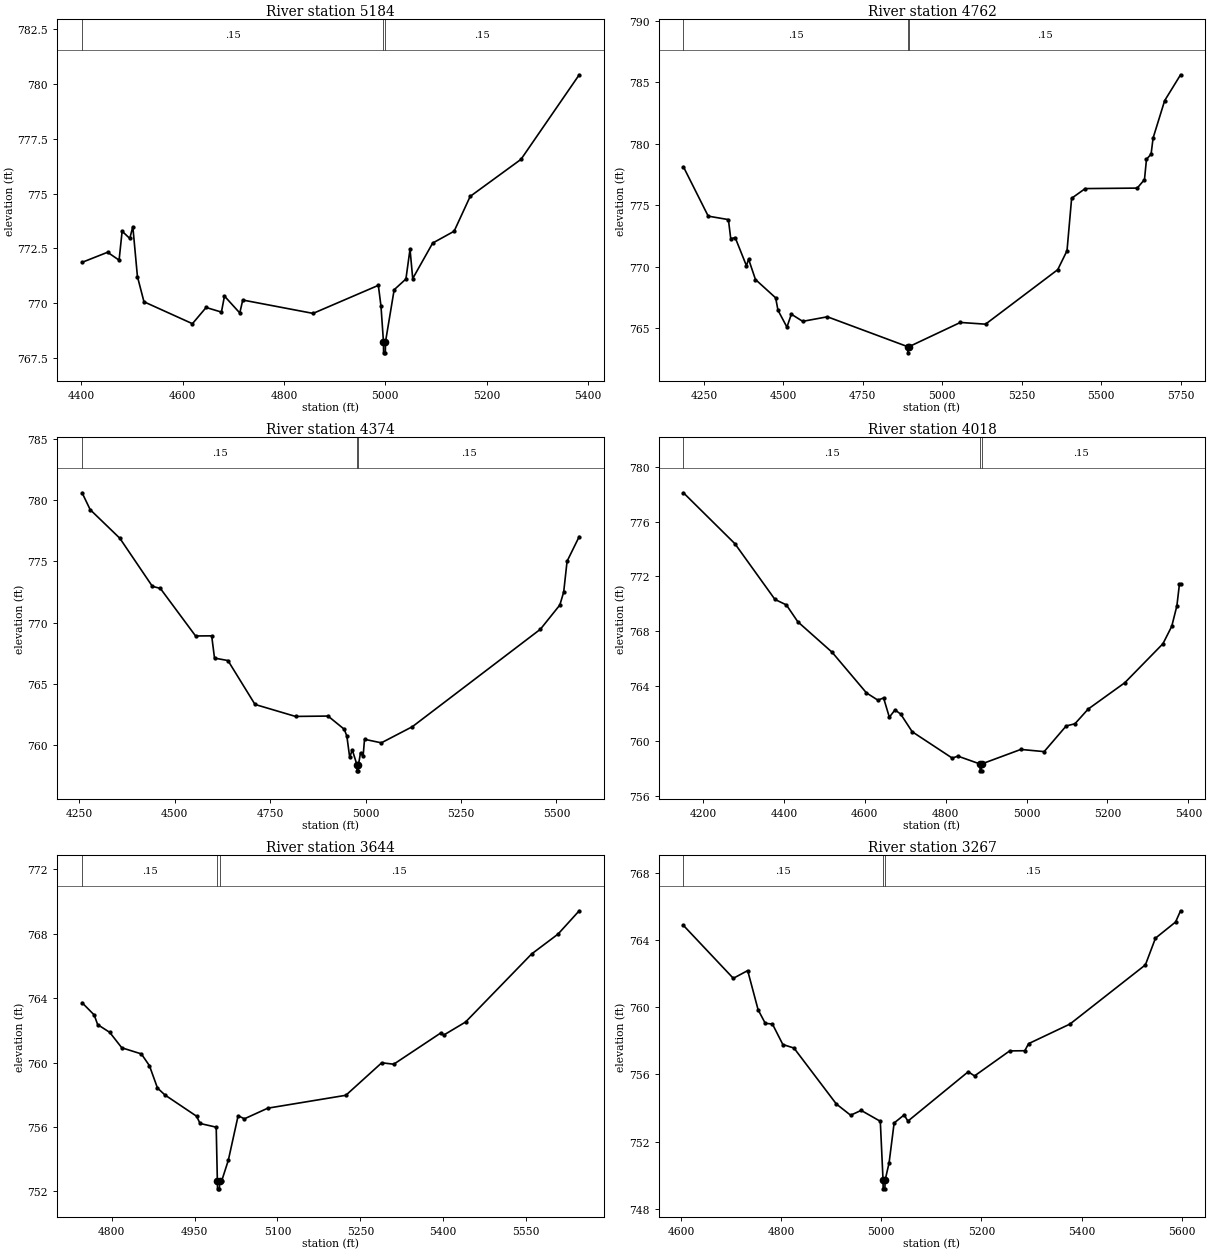
Type RM Length L Ch R = 1,5184,422,422,422
BEGIN DESCRIPTION:
1057
END DESCRIPTION:
XS GIS Cut Line= 3
      2310986.72      7065922.07      2310700.73      7065486.87
      2310265.56      7065337.67
#Sta/Elev= 30
  4401.8  771.86  4452.1  772.32  4474.8  771.96  4480.8  773.28  4495.9  772.95
  4501.9  773.49  4511.0  771.21  4523.9  770.06  4619.5  769.06  4646.5  769.80
  4676.7  769.59  4682.7  770.32  4712.9  769.55  4718.8  770.14  4857.5  769.53
  4986.3  770.81  4991.5  769.86  4996.4  768.23  4996.6  767.73  5000.1  767.73
  5000.4  768.23  5017.5  770.61  5040.7  771.10  5048.8  772.46  5054.1  771.12
  5093.5  772.74  5135.8  773.28  5167.5  774.87  5267.7  776.56  5382.6  780.42
#Mann=3,-1,0
  4401.8    0.15       0  4996.4    0.05       0  5000.4    0.15       0
Bank Sta=4996.4,5000.4
Exp/Cntr=0.3,0.1

Type RM Length L Ch R = 1,4762,388,388,388
BEGIN DESCRIPTION:
Elizabeth Creek Tributary 22_1 10.0
END DESCRIPTION:
XS GIS Cut Line= 3
      2311579.00      7065810.00      2310979.00      7065260.00
      2310379.03      7064810.03
#Sta/Elev= 30
  4185.5  778.14  4263.5  774.13  4327.0  773.85  4334.4  772.29  4348.3  772.39
  4383.7  770.10  4390.5  770.63  4412.1  768.98  4475.6  767.49  4483.0  766.48
  4511.1  765.11  4525.0  766.16  4560.7  765.58  4638.4  765.95  4891.1  763.52
  4891.3  763.02  4895.1  763.52  5056.7  765.49  5135.9  765.35  5363.0  769.78
  5392.2  771.32  5406.7  775.58  5449.4  776.37  5613.0  776.41  5635.9  777.10
  5642.2  778.75  5656.7  779.17  5663.0  780.48  5699.4  783.52  5749.4  785.62
#Mann=3,-1,0
  4185.5    0.15       0  4891.1    0.05       0  4895.1    0.15       0
Bank Sta=4891.1,4895.1
Exp/Cntr=0.3,0.1

Type RM Length L Ch R = 1,4374,356,356,356
BEGIN DESCRIPTION:
Elizabeth Creek Tributary 22_1 9.0
END DESCRIPTION:
XS GIS Cut Line= 3
      2311728.97      7065509.97      2311179.00      7065010.00
      2310628.98      7064910.00
#Sta/Elev= 30
  4257.3  780.62  4278.5  779.24  4356.2  776.90  4441.4  772.97  4462.3  772.80
  4554.6  768.91  4596.8  768.92  4604.2  767.10  4639.4  766.90  4710.3  763.31
  4816.4  762.33  4901.6  762.36  4944.1  761.28  4950.9  760.72  4958.3  758.99
  4965.1  759.59  4977.3  758.38  4977.5  757.88  4981.0  757.88  4981.3  758.38
  4986.7  759.36  4993.5  759.09  4997.2  760.46  5041.2  760.17  5122.5  761.49
  5457.9  769.46  5508.8  771.44  5518.9  772.50  5527.8  775.02  5559.6  777.04
#Mann=3,-1,0
  4257.3    0.15       0  4977.3    0.05       0  4981.3    0.15       0
Bank Sta=4977.3,4981.3
Exp/Cntr=0.3,0.1

Type RM Length L Ch R = 1,4018,374,374,374
BEGIN DESCRIPTION:
Elizabeth Creek Tributary 22_1 8.0
END DESCRIPTION:
XS GIS Cut Line= 3
      2311829.03      7065310.03      2311229.00      7064710.00
      2310878.96      7064559.98
#Sta/Elev= 30
  4151.4  778.10  4278.7  774.39  4377.7  770.33  4406.0  769.93  4434.3  768.70
  4519.1  766.48  4604.0  763.52  4632.3  762.99  4646.4  763.15  4660.6  761.75
  4674.7  762.28  4688.8  761.97  4717.1  760.69  4816.1  758.77  4830.3  758.91
  4884.8  758.34  4885.1  757.84  4888.6  757.84  4888.8  758.34  4985.8  759.40
  5043.5  759.24  5097.9  761.11  5119.6  761.27  5152.3  762.34  5242.9  764.26
  5337.2  767.10  5359.0  768.37  5371.7  769.86  5378.0  771.44  5380.8  771.44
#Mann=3,-1,0
  4151.4    0.15       0  4884.8    0.05       0  4888.8    0.15       0
Bank Sta=4884.8,4888.8
Exp/Cntr=0.3,0.1

Type RM Length L Ch R = 1,3644,377,377,377
BEGIN DESCRIPTION:
Elizabeth Creek Tributary 22_1 7.0
END DESCRIPTION:
XS GIS Cut Line= 3
      2311729.04      7064760.03      2311529.00      7064610.00
      2310929.04      7064360.02
#Sta/Elev= 30
  4746.3  763.72  4768.2  762.96  4774.5  762.36  4796.3  761.88  4818.2  760.92
  4853.6  760.54  4868.2  759.81  4882.8  758.42  4896.3  757.99  4953.6  756.67
  4959.9  756.22  4989.1  755.99  4991.2  752.66  4991.5  752.16  4995.0  752.16
  4995.2  752.66  4999.1  752.66  5011.0  753.93  5028.8  756.70  5040.2  756.51
  5082.5  757.17  5223.8  757.97  5288.8  759.99  5310.5  759.90  5395.6  761.84
  5401.0  761.71  5440.5  762.52  5560.2  766.75  5607.9  767.98  5646.3  769.43
#Mann=3,-1,0
  4746.3    0.15       0  4991.2    0.05       0  4995.2    0.15       0
Bank Sta=4991.2,4995.2
Exp/Cntr=0.3,0.1

Type RM Length L Ch R = 1,3267,342,342,342
BEGIN DESCRIPTION:
Elizabeth Creek Tributary 22_1 6.0
END DESCRIPTION:
XS GIS Cut Line= 3
      2311929.02      7064610.03      2311679.00      7064310.00
      2311079.03      7064260.00
#Sta/Elev= 30
  4604.9  764.87  4704.5  761.72  4733.2  762.18  4754.0  759.85  4768.3  759.04
  4782.6  759.00  4803.4  757.78  4825.6  757.57  4910.2  754.24  4938.8  753.57
  4959.7  753.86  4998.0  753.21  5003.5  749.69  5003.7  749.19  5007.2  749.19
  5007.5  749.69  5015.5  750.73  5025.6  753.11  5045.6  753.59  5053.1  753.22
  5173.6  756.16  5186.1  755.91  5256.3  757.40  5286.5  757.41  5294.0  757.83
  5376.8  759.00  5527.3  762.52  5547.4  764.11  5587.5  765.07  5597.5  765.74
#Mann=3,-1,0
  4604.9    0.15       0  5003.5    0.05       0  5007.5    0.15       0
Bank Sta=5003.5,5007.5
Exp/Cntr=0.3,0.1

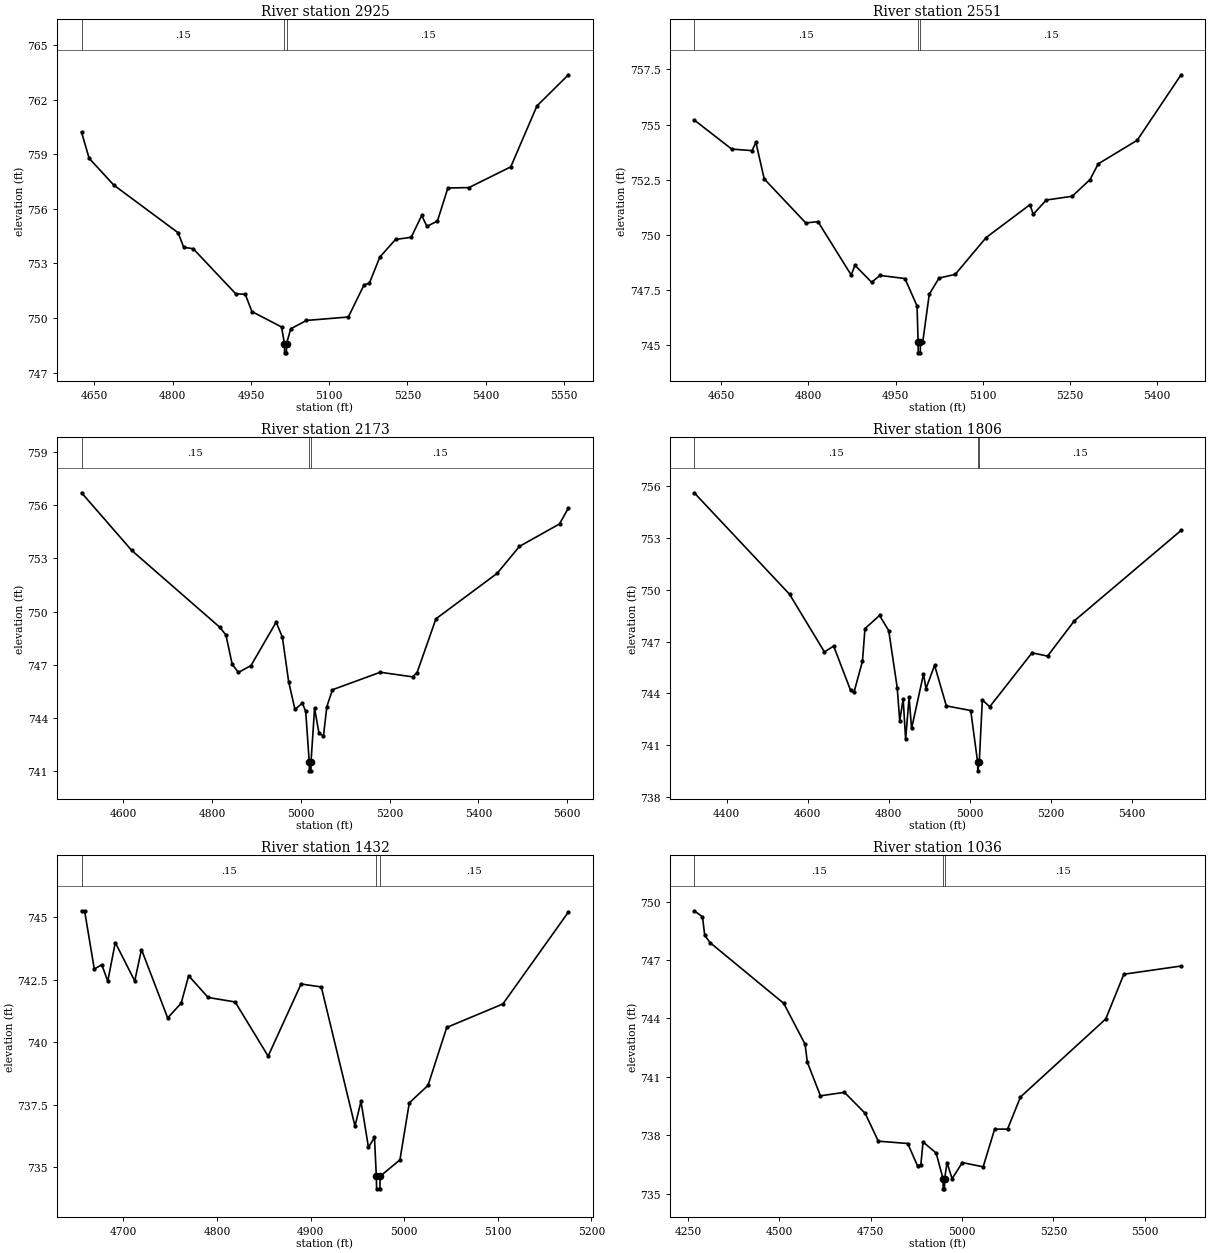
Type RM Length L Ch R = 1,2925,374,374,374
BEGIN DESCRIPTION:
Elizabeth Creek Tributary 22_1 5.0
END DESCRIPTION:
XS GIS Cut Line= 3
      2311929.00      7064360.00      2311779.00      7064010.00
      2311228.96      7064060.00
#Sta/Elev= 30
  4625.5  760.21  4640.0  758.78  4687.2  757.31  4810.5  754.69  4821.3  753.89
  4839.5  753.81  4921.1  751.33  4939.2  751.31  4951.9  750.36  5008.8  749.51
  5014.3  748.59  5014.6  748.09  5018.1  748.09  5018.3  748.59  5026.4  749.41
  5056.5  749.87  5136.8  750.06  5167.0  751.83  5177.0  751.91  5197.1  753.35
  5227.2  754.32  5257.3  754.44  5277.4  755.64  5287.4  755.04  5307.5  755.33
  5327.6  757.15  5367.8  757.17  5448.1  758.31  5498.3  761.66  5558.6  763.37
#Mann=3,-1,0
  4625.5    0.15       0  5014.3    0.05       0  5018.3    0.15       0
Bank Sta=5014.3,5018.3
Exp/Cntr=0.3,0.1

Type RM Length L Ch R = 1,2551,378,378,378
BEGIN DESCRIPTION:
Elizabeth Creek Tributary 22_1 4.0
END DESCRIPTION:
XS GIS Cut Line= 3
      2312229.02      7064060.03      2311979.00      7063760.00
      2311578.97      7063559.98
#Sta/Elev= 30
  4603.4  755.21  4667.9  753.89  4703.0  753.82  4709.5  754.20  4723.8  752.54
  4795.4  750.54  4816.3  750.60  4873.5  748.18  4880.0  748.62  4908.7  747.85
  4923.0  748.16  4966.0  748.02  4986.8  746.78  4988.7  745.15  4988.9  744.65
  4992.4  744.65  4992.7  745.15  4996.7  745.15  5007.9  747.31  5024.7  748.04
  5052.6  748.21  5105.8  749.88  5181.2  751.37  5186.8  750.93  5209.2  751.58
  5253.9  751.75  5284.6  752.51  5298.6  753.22  5365.7  754.29  5441.2  757.26
#Mann=3,-1,0
  4603.4    0.15       0  4988.7    0.05       0  4992.7    0.15       0
Bank Sta=4988.7,4992.7
Exp/Cntr=0.3,0.1

Type RM Length L Ch R = 1,2173,367,367,367
BEGIN DESCRIPTION:
Elizabeth Creek Tributary 22_1 3.0
END DESCRIPTION:
XS GIS Cut Line= 3
      2312578.97      7063859.97      2312229.00      7063510.00
      2311629.01      7063460.00
#Sta/Elev= 30
  4505.7  756.71  4618.8  753.45  4816.8  749.12  4830.9  748.68  4845.1  747.02
  4859.2  746.56  4887.5  746.95  4944.1  749.40  4958.2  748.55  4972.3  746.04
  4986.5  744.47  5003.1  744.82  5010.7  744.37  5018.7  741.50  5019.0  741.00
  5022.5  741.00  5022.7  741.50  5030.7  744.53  5040.8  743.11  5050.8  742.98
  5058.3  744.62  5070.9  745.58  5178.7  746.57  5251.5  746.31  5261.5  746.54
  5304.2  749.59  5442.2  752.16  5492.3  753.68  5582.6  754.95  5602.7  755.85
#Mann=3,-1,0
  4505.7    0.15       0  5018.7    0.05       0  5022.7    0.15       0
Bank Sta=5018.7,5022.7
Exp/Cntr=0.3,0.1

Type RM Length L Ch R = 1,1806,374,374,374
BEGIN DESCRIPTION:
Elizabeth Creek Tributary 22_1 2.0
END DESCRIPTION:
XS GIS Cut Line= 3
      2312679.00      7063710.00      2312279.00      7063160.00
      2311778.99      7063310.00
#Sta/Elev= 30
  4319.7  755.61  4555.0  749.74  4641.2  746.40  4664.0  746.74  4705.7  744.18
  4714.2  744.07  4735.1  745.86  4741.3  747.75  4777.2  748.51  4800.0  747.63
  4820.9  744.33  4827.1  742.42  4835.6  743.68  4841.7  741.34  4850.2  743.77
  4856.4  741.97  4885.8  745.12  4892.0  744.28  4913.2  745.63  4942.2  743.28
  5002.4  743.01  5019.5  740.02  5019.8  739.52  5023.5  740.02  5031.1  743.62
  5049.4  743.23  5153.8  746.35  5192.1  746.16  5258.2  748.20  5521.8  753.43
#Mann=3,-1,0
  4319.7    0.15       0  5019.5    0.05       0  5023.5    0.15       0
Bank Sta=5019.5,5023.5
Exp/Cntr=0.3,0.1

Type RM Length L Ch R = 1,1432,396,396,396
BEGIN DESCRIPTION:
Elizabeth Creek Tributary 22_1 1.0
END DESCRIPTION:
XS GIS Cut Line= 3
      2312628.99      7063159.99      2312429.00      7062910.00
      2312229.04      7062910.00
#Sta/Elev= 30
  4655.3  745.26  4658.5  745.26  4668.9  742.93  4676.9  743.10  4683.3  742.44
  4691.3  743.99  4712.1  742.45  4719.3  743.71  4747.3  740.97  4761.7  741.56
  4769.7  742.66  4790.5  741.79  4819.4  741.61  4854.6  739.44  4889.8  742.33
  4911.4  742.21  4947.4  736.64  4953.8  737.63  4961.8  735.79  4968.2  736.19
  4970.2  734.63  4970.5  734.13  4974.0  734.13  4974.2  734.63  4995.4  735.29
  5005.4  737.57  5025.4  738.27  5045.4  740.59  5105.4  741.53  5175.4  745.21
#Mann=3,-1,0
  4655.3    0.15       0  4970.2    0.05       0  4974.2    0.15       0
Bank Sta=4970.2,4974.2
Exp/Cntr=0.3,0.1

Type RM Length L Ch R = 1,1036,625,625,625
BEGIN DESCRIPTION:
1051
END DESCRIPTION:
XS GIS Cut Line= 3
      2313181.20      7063018.77      2312509.82      7062558.75
      2312136.78      7062919.36
#Sta/Elev= 30
  4266.8  749.53  4289.4  749.22  4295.5  748.27  4310.4  747.89  4511.9  744.77
  4570.3  742.67  4576.4  741.75  4612.3  740.02  4678.0  740.20  4734.8  739.12
  4770.7  737.69  4851.3  737.57  4878.3  736.41  4887.2  736.49  4893.2  737.65
  4929.1  737.08  4948.1  735.74  4948.3  735.24  4951.8  735.24  4952.1  735.74
  4958.9  736.59  4972.6  735.76  5000.8  736.59  5057.7  736.37  5089.2  738.31
  5124.5  738.31  5159.9  739.96  5393.3  743.97  5442.9  746.27  5599.5  746.69
#Mann=3,-1,0
  4266.8    0.15       0  4948.1    0.05       0  4952.1    0.15       0
Bank Sta=4948.1,4952.1
Exp/Cntr=0.3,0.1

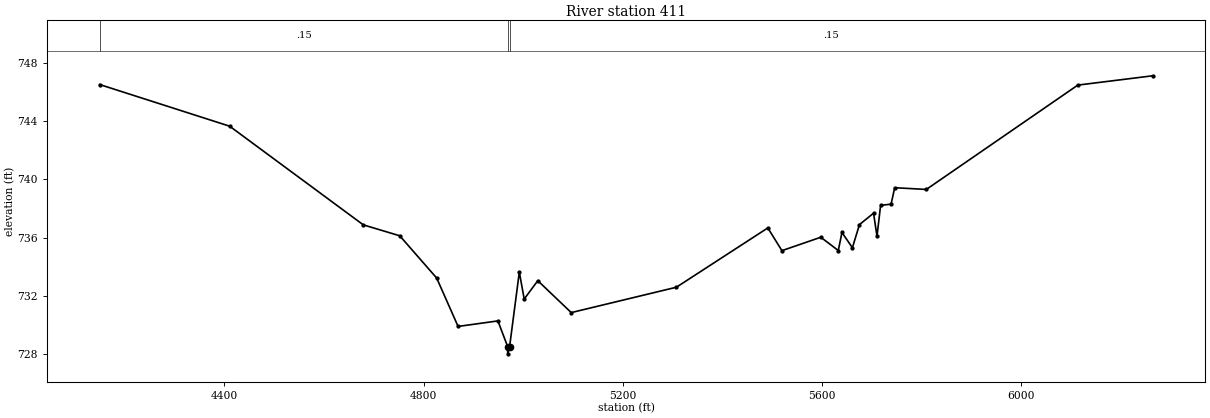
Type RM Length L Ch R = 1,411,0,0,0
BEGIN DESCRIPTION:
1050
END DESCRIPTION:
XS GIS Cut Line= 3
      2313448.54      7062956.59      2312951.22      7062111.14
      2312124.37      7062888.26
#Sta/Elev= 30
  4149.2  746.50  4410.4  743.64  4678.9  736.87  4752.1  736.12  4826.3  733.22
  4869.3  729.90  4949.3  730.28  4968.8  728.52  4969.0  728.02  4972.8  728.52
  4992.3  733.63  5002.1  731.78  5029.4  733.04  5096.6  730.85  5307.8  732.59
  5491.5  736.66  5519.8  735.10  5597.9  736.02  5633.1  735.11  5640.4  736.35
  5661.4  735.30  5675.6  736.89  5703.9  737.67  5710.8  736.09  5718.1  738.21
  5739.1  738.29  5746.4  739.42  5809.9  739.30  6114.2  746.46  6264.8  747.10
#Mann=3,-1,0
  4149.2    0.15       0  4968.8    0.05       0  4972.8    0.15       0
Bank Sta=4968.8,4972.8
Exp/Cntr=0.3,0.1

Chan Stop Cuts=-1