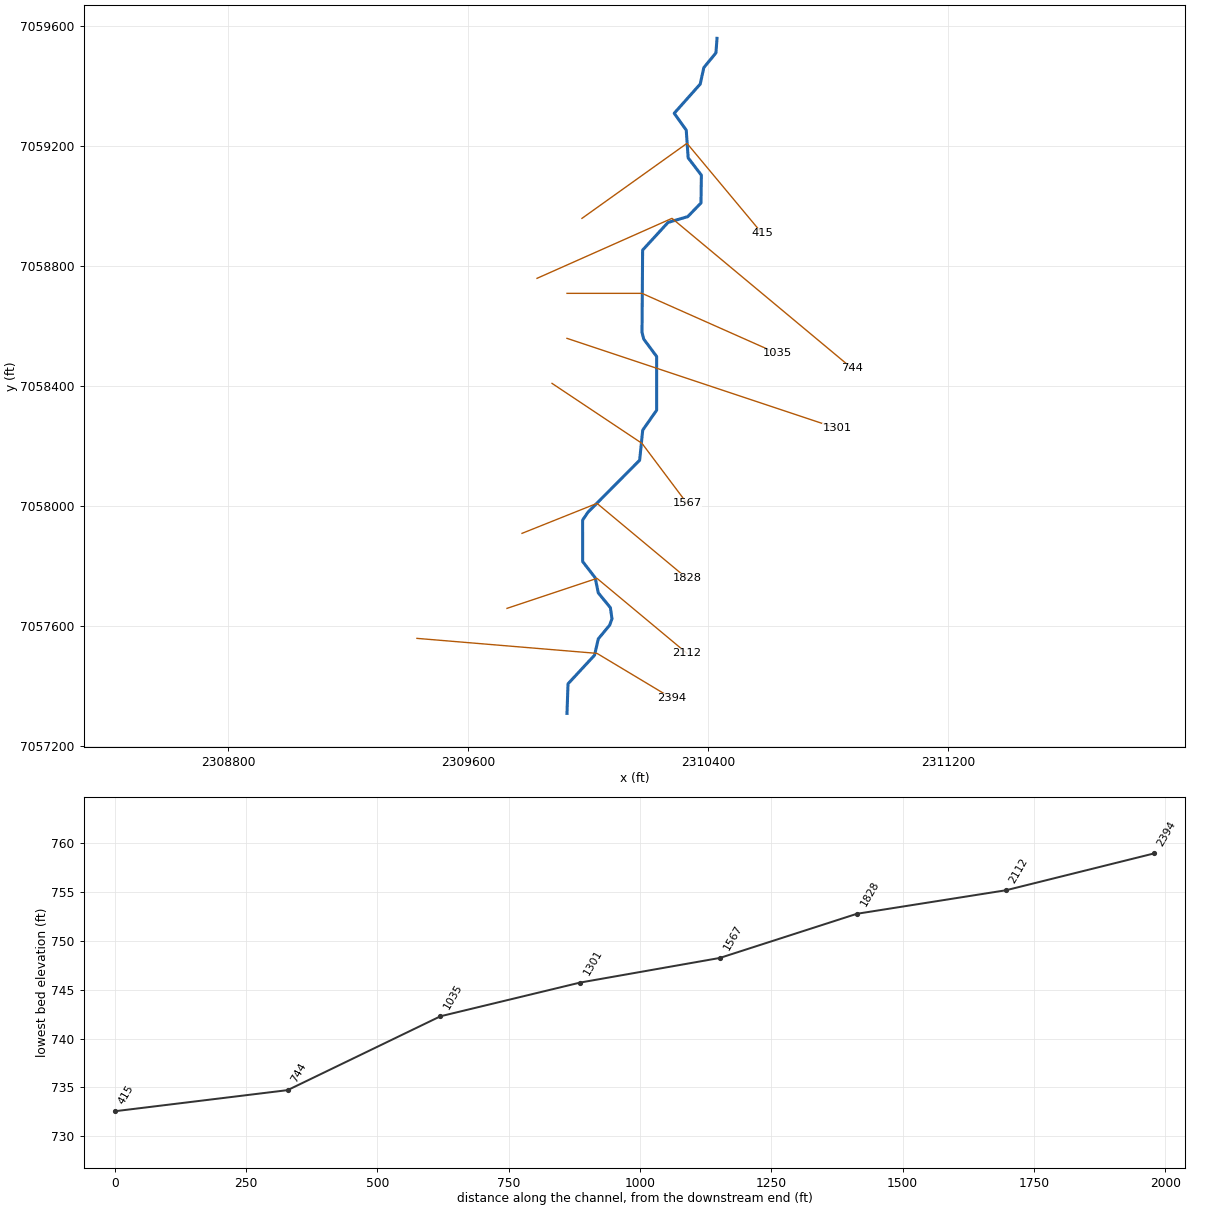
--- Elizabeth Cr Tr 23.prj (project) ---

Proj Title=Elizabeth Cr Tr 23 Base Level Engineering
Current Plan=p01
Default Exp/Contr=0.3,0.1
English Units
Geom File=g01
Flow File=f01
Plan File=p01
BEGIN DESCRIPTION:
Elizabeth Cr Tr 23
END DESCRIPTION:

--- Elizabeth Cr Tr 23.p01 (plan) ---

Plan Title=Multiple Run
Short Identifier=Multiple
Geom File=g01
Flow File=f01
Subcritical Flow
K Sum by GR= 0
Std Step Tol= 0.01
Critical Tol= 0.01
Num of Std Step Trials= 20
Max Error Tol= 0.3
Flow Tol Ratio= 0.001
Split Flow NTrial= 30
Split Flow Tol= 0.02
Split Flow Ratio= 0.02
Log Output Level= 0
Friction Slope Method= 1
Unsteady Friction Slope Method= 2
Unsteady Bridges Friction Slope Method= 1
Parabolic Critical Depth
Global Vel Dist=  1 , 1 , 1
Global Log Level= 0
CheckData=True
Encroach Param= -1, 0, 0, 0
BEGIN DESCRIPTION:
Multiple Run
END DESCRIPTION:

--- Elizabeth Cr Tr 23.f01 (steady flow) ---

Flow Title=Multiple
Number of Profiles=7
Profile Names=10-year,25-year,50-year,1pct_min,100-year,1pct_plu,500-year
River Rch & RM= Elizabeth Cr Tr ,Reach-1,2394
     412     553     668     402     801    1600    1150
River Rch & RM= Elizabeth Cr Tr ,Reach-1,415
     424     572     692     416     831    1660    1200
Boundary for River Rch & Prof#=Elizabeth Cr Tr ,Reach-1,1
Up Type=0
Dn Type=3
Dn Slope=0.005
Boundary for River Rch & Prof#=Elizabeth Cr Tr ,Reach-1,2
Up Type=0
Dn Type=3
Dn Slope=0.005
Boundary for River Rch & Prof#=Elizabeth Cr Tr ,Reach-1,3
Up Type=0
Dn Type=3
Dn Slope=0.005
Boundary for River Rch & Prof#=Elizabeth Cr Tr ,Reach-1,4
Up Type=0
Dn Type=3
Dn Slope=0.005
Boundary for River Rch & Prof#=Elizabeth Cr Tr ,Reach-1,5
Up Type=0
Dn Type=3
Dn Slope=0.005
Boundary for River Rch & Prof#=Elizabeth Cr Tr ,Reach-1,6
Up Type=0
Dn Type=3
Dn Slope=0.005
Boundary for River Rch & Prof#=Elizabeth Cr Tr ,Reach-1,7
Up Type=0
Dn Type=3
Dn Slope=0.005

--- Elizabeth Cr Tr 23.g01 (geometry) ---

Geom Title=Existing Conditions

River Reach=Elizabeth Cr Tr ,Reach-1
Reach XY= 30
      2309929.00      7057310.00      2309932.39      7057408.59
      2310020.85      7057503.95      2310033.25      7057558.26
      2310071.24      7057604.06      2310078.93      7057625.39
      2310073.66      7057662.20      2310033.22      7057711.72
      2310022.89      7057762.18      2309981.23      7057815.93
      2309981.05      7057954.14      2309998.60      7057980.16
      2310171.14      7058153.83      2310181.36      7058254.02
      2310227.78      7058320.50      2310227.78      7058499.49
      2310184.75      7058557.67      2310179.07      7058580.03
      2310181.05      7058854.16      2310265.77      7058946.38
      2310331.58      7058965.74      2310375.63      7059011.28
      2310376.84      7059104.02      2310332.86      7059161.60
      2310326.44      7059254.11      2310286.32      7059310.10
      2310373.15      7059407.69      2310384.97      7059462.24
      2310425.40      7059511.49      2310429.00      7059560.00

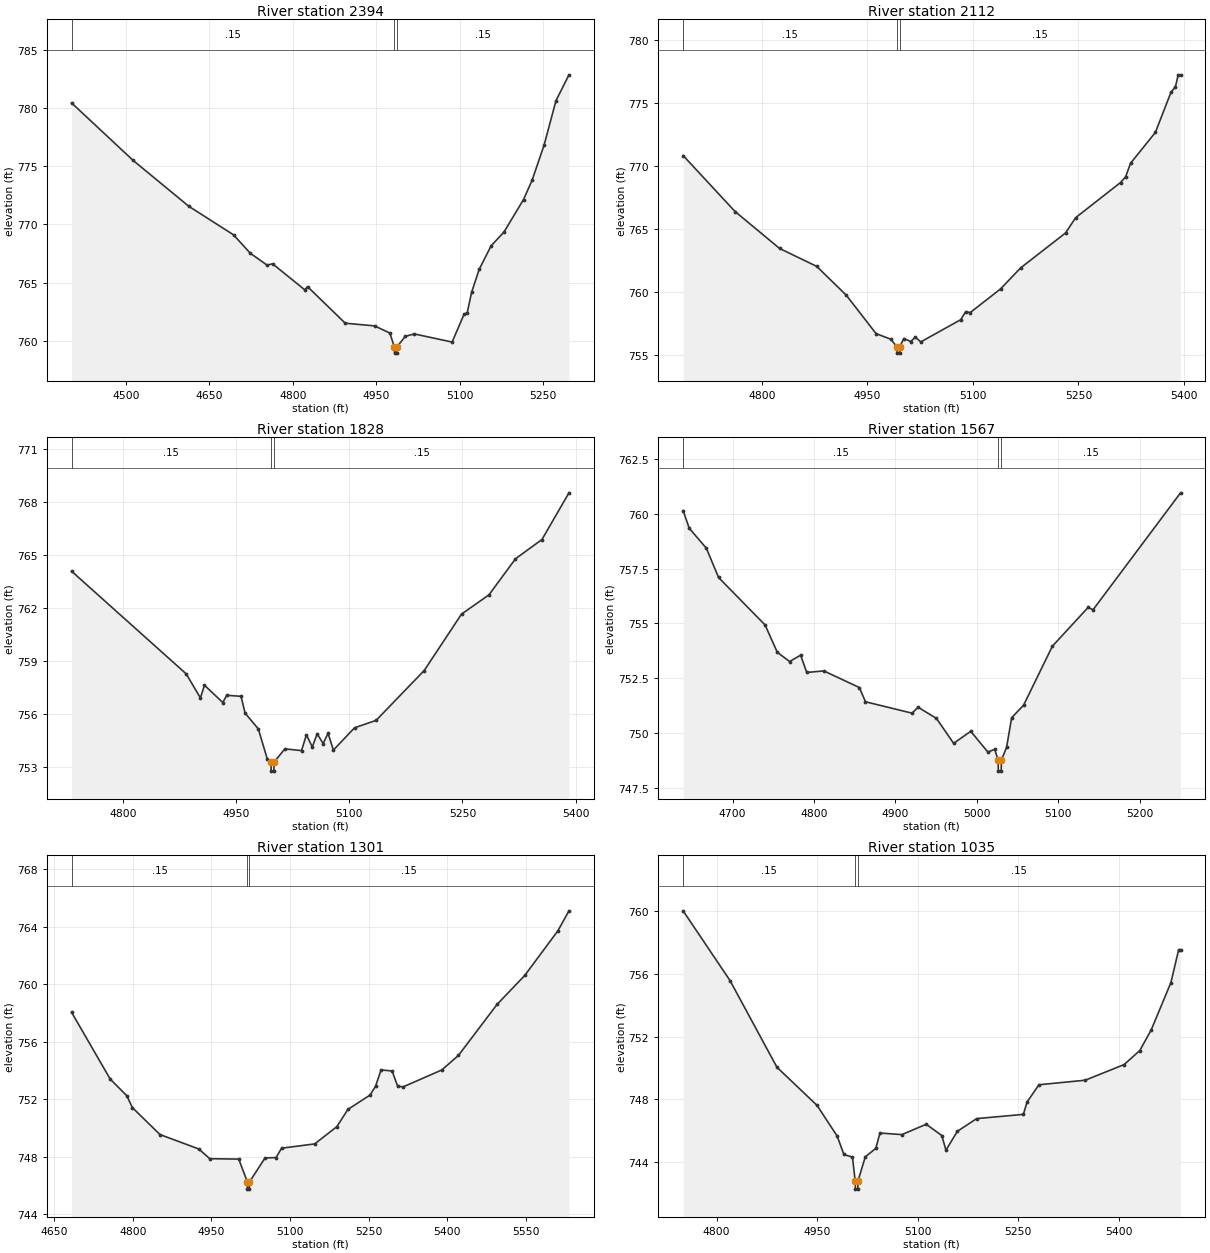
Type RM Length L Ch R = 1,2394,282,282,282
BEGIN DESCRIPTION:
Elizabeth Creek Tributary 23 8.0
END DESCRIPTION:
XS GIS Cut Line= 3
      2309429.01      7057560.00      2310029.00      7057510.00
      2310278.98      7057360.01
#Sta/Elev= 30
  4402.5  780.44  4512.9  775.51  4613.2  771.56  4693.5  769.11  4723.6  767.53
  4753.7  766.51  4763.7  766.62  4821.4  764.39  4826.5  764.66  4894.2  761.52
  4946.9  761.29  4974.5  760.67  4982.5  759.45  4982.8  758.95  4986.3  758.95
  4986.5  759.45  5002.1  760.39  5018.2  760.60  5086.2  759.90  5107.6  762.28
  5113.4  762.43  5121.2  764.17  5134.8  766.14  5156.2  768.16  5179.5  769.36
  5214.5  772.14  5230.0  773.81  5251.4  776.81  5272.8  780.63  5296.1  782.85
#Mann=3,-1,0
  4402.5    0.15       0  4982.5    0.05       0  4986.5    0.15       0
Bank Sta=4982.5,4986.5
Exp/Cntr=0.3,0.1

Type RM Length L Ch R = 1,2112,284,284,284
BEGIN DESCRIPTION:
Elizabeth Creek Tributary 23 7.0
END DESCRIPTION:
XS GIS Cut Line= 3
      2309728.96      7057659.99      2310029.00      7057760.00
      2310329.02      7057509.99
#Sta/Elev= 30
  4688.3  770.85  4762.1  766.41  4825.4  763.48  4878.1  762.06  4920.2  759.77
  4962.4  756.73  4983.5  756.28  4992.0  755.68  4992.3  755.18  4995.8  755.18
  4996.0  755.68  5001.9  756.34  5011.7  756.10  5018.2  756.45  5026.0  756.07
  5082.7  757.83  5089.8  758.47  5096.3  758.40  5139.3  760.27  5167.9  761.94
  5231.7  764.71  5246.0  765.92  5309.8  768.71  5317.0  769.16  5324.1  770.24
  5359.3  772.68  5381.4  775.85  5387.9  776.32  5391.8  777.25  5395.1  777.25
#Mann=3,-1,0
  4688.3    0.15       0  4992.0    0.05       0  4996.0    0.15       0
Bank Sta=4992,4996
Exp/Cntr=0.3,0.1

Type RM Length L Ch R = 1,1828,261,261,261
BEGIN DESCRIPTION:
Elizabeth Creek Tributary 23 6.0
END DESCRIPTION:
XS GIS Cut Line= 3
      2309779.04      7057910.02      2310029.00      7058010.00
      2310328.98      7057760.02
#Sta/Elev= 30
  4731.5  764.08  4883.6  758.27  4902.4  756.91  4907.8  757.63  4932.1  756.65
  4937.4  757.06  4956.3  757.00  4961.7  756.05  4979.2  755.16  4991.3  753.43
  4996.0  753.27  4996.3  752.77  4999.8  752.77  5000.0  753.27  5014.4  754.03
  5036.5  753.93  5043.0  754.82  5050.8  754.14  5057.3  754.88  5065.2  754.33
  5071.7  754.91  5078.8  753.96  5106.8  755.22  5135.4  755.64  5199.2  758.46
  5248.7  761.65  5285.1  762.74  5320.3  764.78  5355.4  765.87  5391.2  768.51
#Mann=3,-1,0
  4731.5    0.15       0  4996.0    0.05       0  5000.0    0.15       0
Bank Sta=4996,5000
Exp/Cntr=0.3,0.1

Type RM Length L Ch R = 1,1567,266,266,266
BEGIN DESCRIPTION:
Elizabeth Creek Tributary 23 5.0
END DESCRIPTION:
XS GIS Cut Line= 3
      2309879.04      7058409.98      2310179.00      7058210.00
      2310328.99      7058010.01
#Sta/Elev= 30
  4639.4  760.16  4646.9  759.35  4667.9  758.44  4682.9  757.10  4740.0  754.93
  4755.0  753.68  4770.1  753.26  4783.6  753.55  4791.1  752.76  4812.1  752.83
  4855.7  752.07  4863.2  751.42  4920.3  750.90  4927.8  751.17  4950.3  750.66
  4971.4  749.52  4992.4  750.07  5013.5  749.12  5021.8  749.25  5026.0  748.75
  5026.3  748.25  5029.8  748.25  5030.0  748.75  5036.4  749.34  5042.6  750.69
  5057.2  751.26  5092.6  753.96  5136.4  755.73  5142.6  755.63  5249.9  760.97
#Mann=3,-1,0
  4639.4    0.15       0  5026.0    0.05       0  5030.0    0.15       0
Bank Sta=5026,5030
Exp/Cntr=0.3,0.1

Type RM Length L Ch R = 1,1301,266,266,266
BEGIN DESCRIPTION:
Elizabeth Creek Tributary 23 4.0
END DESCRIPTION:
XS GIS Cut Line= 3
      2309928.96      7058560.01      2310229.00      7058460.00
      2310828.98      7058260.01
#Sta/Elev= 30
  4683.3  758.05  4757.1  753.39  4788.8  752.23  4799.3  751.41  4852.0  749.53
  4925.8  748.53  4946.9  747.85  5002.2  747.82  5018.7  746.23  5018.9  745.73
  5022.4  745.73  5022.7  746.23  5052.3  747.90  5073.4  747.93  5083.9  748.58
  5147.1  748.88  5189.3  750.08  5210.4  751.28  5252.6  752.28  5263.1  752.89
  5273.6  754.03  5294.7  753.96  5305.3  752.90  5315.8  752.85  5389.6  754.03
  5421.2  755.04  5495.0  758.60  5547.7  760.61  5610.9  763.72  5632.0  765.11
#Mann=3,-1,0
  4683.3    0.15       0  5018.7    0.05       0  5022.7    0.15       0
Bank Sta=5018.7,5022.7
Exp/Cntr=0.3,0.1

Type RM Length L Ch R = 1,1035,291,291,291
BEGIN DESCRIPTION:
Elizabeth Creek Tributary 23 3.0
END DESCRIPTION:
XS GIS Cut Line= 3
      2309928.98      7058710.00      2310179.00      7058710.00
      2310629.03      7058509.99
#Sta/Elev= 30
  4750.0  760.04  4820.0  755.59  4890.0  750.06  4950.0  747.62  4980.0  745.66
  4990.0  744.49  5002.8  744.32  5006.9  742.78  5007.2  742.28  5010.7  742.28
  5010.9  742.78  5021.9  744.34  5037.6  744.88  5043.8  745.86  5076.6  745.76
  5112.9  746.42  5136.1  745.70  5142.3  744.77  5159.4  745.97  5188.1  746.78
  5257.9  747.05  5263.3  747.83  5281.1  748.94  5350.2  749.23  5408.3  750.23
  5431.6  751.12  5448.7  752.44  5478.1  755.46  5489.7  757.56  5492.5  757.56
#Mann=3,-1,0
  4750.0    0.15       0  5006.9    0.05       0  5010.9    0.15       0
Bank Sta=5006.9,5010.9
Exp/Cntr=0.3,0.1

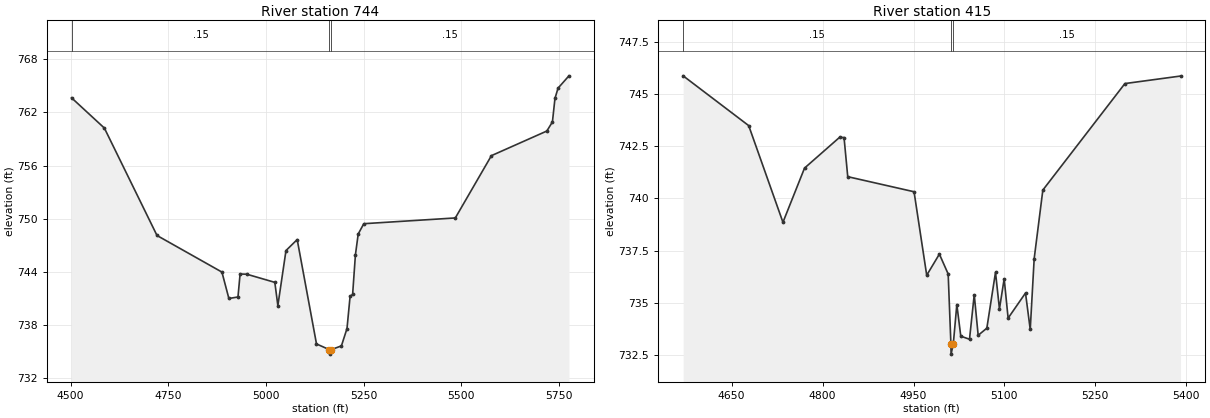
Type RM Length L Ch R = 1,744,329,329,329
BEGIN DESCRIPTION:
Elizabeth Creek Tributary 23 2.0
END DESCRIPTION:
XS GIS Cut Line= 3
      2309829.02      7058760.01      2310279.00      7058960.00
      2310878.97      7058460.03
#Sta/Elev= 30
  4502.5  763.65  4586.6  760.23  4721.3  748.11  4887.5  743.98  4905.3  741.00
  4928.6  741.17  4934.0  743.76  4951.1  743.74  5022.9  742.82  5030.7  740.20
  5051.5  746.41  5080.2  747.65  5129.6  735.87  5162.8  735.22  5163.0  734.72
  5166.8  735.22  5193.4  735.65  5207.7  737.61  5215.6  741.24  5222.1  741.45
  5229.2  745.91  5236.4  748.28  5250.7  749.44  5485.0  750.09  5577.4  757.12
  5719.3  759.90  5733.6  760.93  5740.1  763.58  5748.0  764.74  5775.9  766.13
#Mann=3,-1,0
  4502.5    0.15       0  5162.8    0.05       0  5166.8    0.15       0
Bank Sta=5162.8,5166.8
Exp/Cntr=0.3,0.1

Type RM Length L Ch R = 1,415,0,0,0
BEGIN DESCRIPTION:
Elizabeth Creek Tributary 23 1.0
END DESCRIPTION:
XS GIS Cut Line= 3
      2309978.97      7058959.98      2310329.00      7059210.00
      2310579.03      7058909.97
#Sta/Elev= 30
  4569.9  745.86  4678.1  743.48  4734.6  738.86  4770.2  741.45  4828.0  742.92
  4835.4  742.91  4841.5  741.04  4950.9  740.32  4971.8  736.33  4992.7  737.34
  5007.2  736.39  5011.7  733.06  5012.0  732.56  5015.7  733.06  5021.5  734.93
  5028.0  733.42  5042.4  733.27  5050.2  735.40  5056.7  733.46  5071.0  733.80
  5085.3  736.47  5091.8  734.72  5099.6  736.16  5106.1  734.28  5134.8  735.48
  5142.6  733.74  5149.1  737.12  5163.4  740.40  5298.8  745.49  5390.6  745.85
#Mann=3,-1,0
  4569.9    0.15       0  5011.7    0.05       0  5015.7    0.15       0
Bank Sta=5011.7,5015.7
Exp/Cntr=0.3,0.1

Chan Stop Cuts=-1