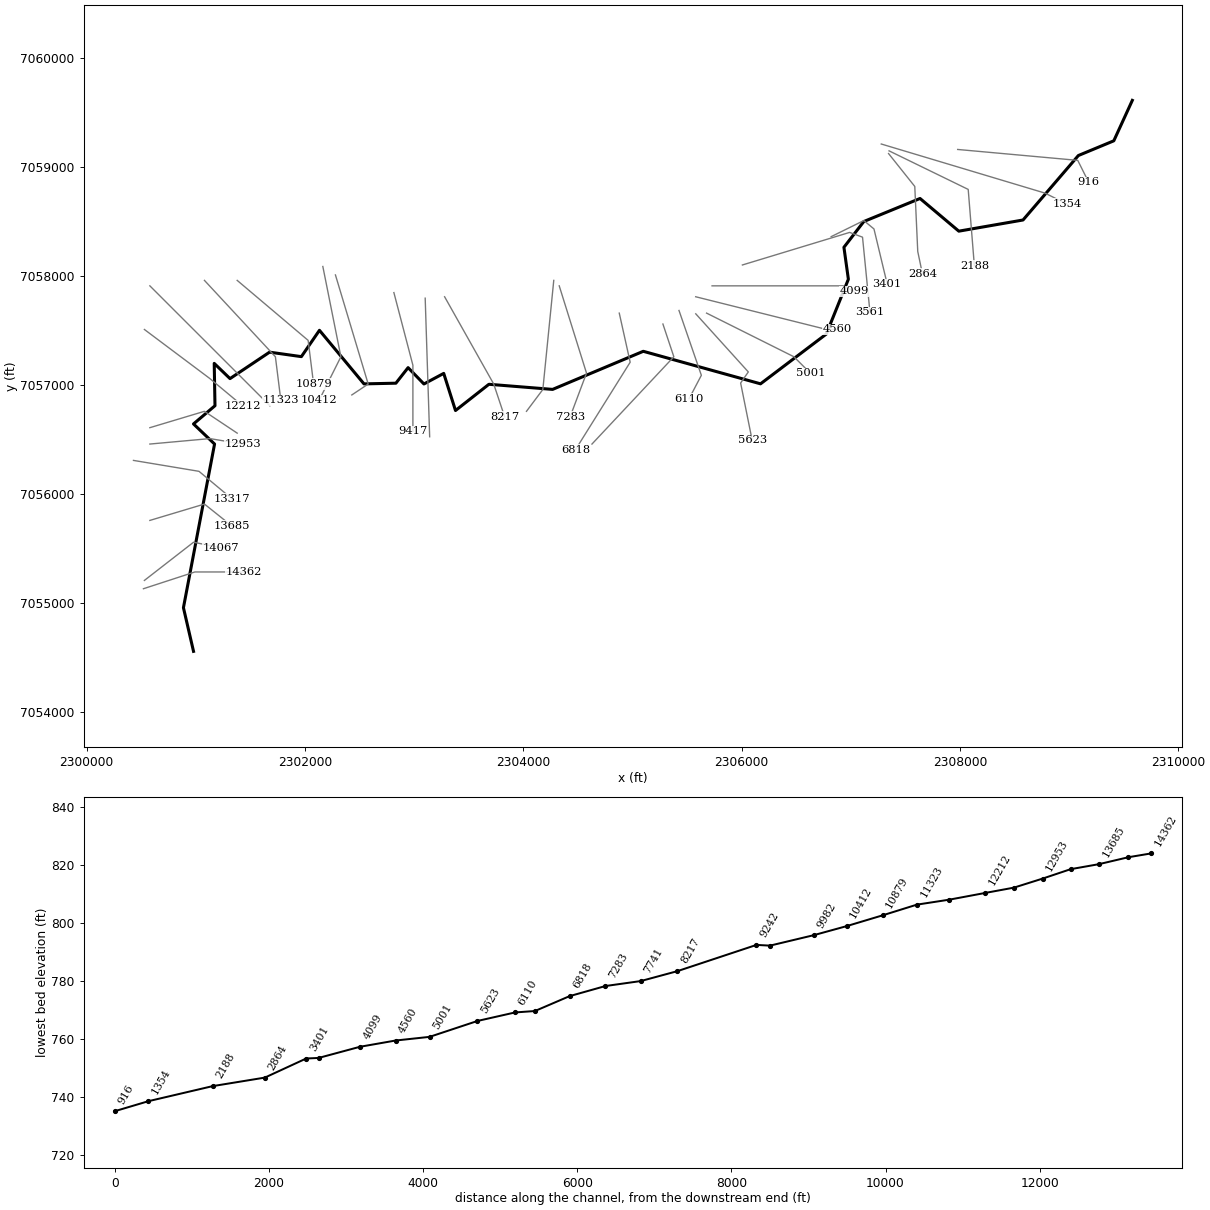
--- Elizabeth Cr Tr 24.prj (project) ---

Proj Title=Elizabeth Cr Tr 24 Base Level Engineering
Current Plan=p01
Default Exp/Contr=0.3,0.1
English Units
Geom File=g01
Flow File=f01
Plan File=p01
Y Axis Title=Elevation
X Axis Title(PF)=Main Channel Distance
X Axis Title(XS)=Station
BEGIN DESCRIPTION:
Elizabeth Cr Tr 24
END DESCRIPTION:
DSS Export Rating Curves= 0
DSS Export Rating Curve Sorted= 0
DSS Export Volume Flow Curves= 0
DXF OffsetX= 0
DXF OffsetY= 0
DXF ScaleX= 1
DXF ScaleY= 10

--- Elizabeth Cr Tr 24.p01 (plan) ---

Plan Title=Multiple Run
Short Identifier=Multiple
Geom File=g01
Flow File=f01
Subcritical Flow
K Sum by GR= 0
Std Step Tol= 0.01
Critical Tol= 0.01
Num of Std Step Trials= 20
Max Error Tol= 0.3
Flow Tol Ratio= 0.001
Split Flow NTrial= 30
Split Flow Tol= 0.02
Split Flow Ratio= 0.02
Log Output Level= 0
Friction Slope Method= 1
Unsteady Friction Slope Method= 2
Unsteady Bridges Friction Slope Method= 1
Parabolic Critical Depth
Global Vel Dist=  1 , 1 , 1
Global Log Level= 0
CheckData=True
Encroach Param= -1, 0, 0, 0
BEGIN DESCRIPTION:
Multiple Run
END DESCRIPTION:

--- Elizabeth Cr Tr 24.f01 (steady flow) ---

Flow Title=Multiple
Number of Profiles=7
Profile Names=10-year,25-year,50-year,1pct_min,100-year,1pct_plu,500-year
River Rch & RM= Elizabeth Cr Tr ,Reach-1,14362
     611     841    1030     628    1250    2500    1850
River Rch & RM= Elizabeth Cr Tr ,Reach-1,9417
     767    1060    1310     803    1600    3200    2390
River Rch & RM= Elizabeth Cr Tr ,Reach-1,5001
    1260    1800    2260    1400    2800    5580    4320
River Rch & RM= Elizabeth Cr Tr ,Reach-1,2864
    1950    2820    3580    2250    4480    8940    7050
Boundary for River Rch & Prof#=Elizabeth Cr Tr ,Reach-1,1
Up Type=0
Dn Type=3
Dn Slope=0.005
Boundary for River Rch & Prof#=Elizabeth Cr Tr ,Reach-1,2
Up Type=0
Dn Type=3
Dn Slope=0.005
Boundary for River Rch & Prof#=Elizabeth Cr Tr ,Reach-1,3
Up Type=0
Dn Type=3
Dn Slope=0.005
Boundary for River Rch & Prof#=Elizabeth Cr Tr ,Reach-1,4
Up Type=0
Dn Type=3
Dn Slope=0.005
Boundary for River Rch & Prof#=Elizabeth Cr Tr ,Reach-1,5
Up Type=0
Dn Type=3
Dn Slope=0.005
Boundary for River Rch & Prof#=Elizabeth Cr Tr ,Reach-1,6
Up Type=0
Dn Type=3
Dn Slope=0.005
Boundary for River Rch & Prof#=Elizabeth Cr Tr ,Reach-1,7
Up Type=0
Dn Type=3
Dn Slope=0.005

--- Elizabeth Cr Tr 24.g01 (geometry) ---

Geom Title=Existing Conditions

River Reach=Elizabeth Cr Tr ,Reach-1
Reach XY= 30
      2300979.00      7054560.00      2300886.56      7054960.00
      2301171.71      7056460.09      2300978.74      7056644.30
      2301175.55      7056811.25      2301168.62      7057199.20
      2301313.29      7057059.75      2301675.60      7057302.17
      2301967.00      7057261.17      2302132.57      7057502.52
      2302540.49      7057011.47      2302832.66      7057017.72
      2302944.58      7057160.30      2303089.63      7057010.55
      2303270.89      7057107.57      2303378.90      7056767.28
      2303684.90      7057007.77      2304268.41      7056960.90
      2305098.99      7057310.06      2306173.11      7057011.96
      2306775.62      7057468.15      2306977.78      7057970.50
      2306937.04      7058263.32      2307119.20      7058499.52
      2307634.29      7058710.70      2307989.48      7058411.18
      2308577.72      7058513.52      2309084.61      7059104.41
      2309409.28      7059239.28      2309579.00      7059610.00

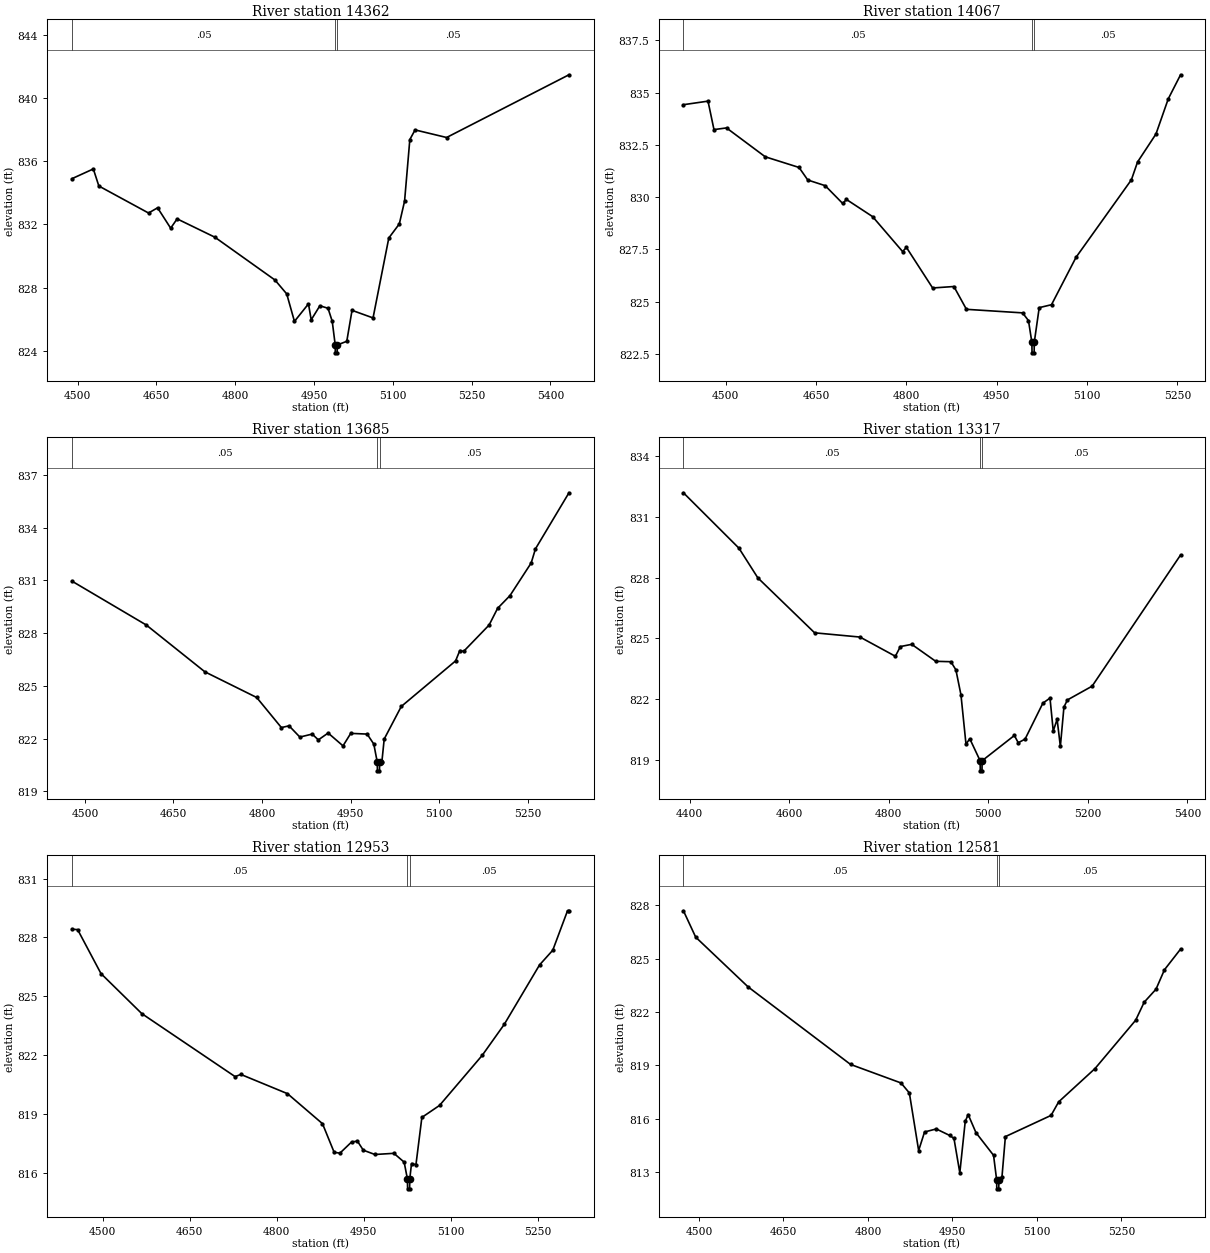
Type RM Length L Ch R = 1,14362,295,295,295
BEGIN DESCRIPTION:
1070
END DESCRIPTION:
XS GIS Cut Line= 3
      2300520.16      7055133.95      2300991.32      7055287.59
      2301441.95      7055287.59
#Sta/Elev= 30
  4489.2  834.89  4530.1  835.51  4540.6  834.43  4635.2  832.72  4652.4  833.05
  4677.3  831.76  4689.6  832.35  4761.4  831.19  4875.8  828.48  4898.2  827.60
  4912.9  825.86  4939.6  826.97  4944.8  825.96  4961.3  826.85  4976.8  826.69
  4984.8  825.87  4990.5  824.37  4990.7  823.87  4994.2  823.87  4994.5  824.37
  5012.5  824.60  5022.5  826.56  5062.5  826.08  5092.5  831.14  5112.5  832.03
  5122.5  833.47  5132.5  837.37  5142.5  837.98  5202.5  837.50  5435.4  841.47
#Mann=3,-1,0
  4489.2    0.05       0  4990.5   0.033       0  4994.5    0.05       0
Bank Sta=4990.5,4994.5
Exp/Cntr=0.3,0.1

Type RM Length L Ch R = 1,14067,382,382,382
BEGIN DESCRIPTION:
Elizabeth Creek Tributary 24 25.0
END DESCRIPTION:
XS GIS Cut Line= 3
      2300528.97      7055209.98      2300979.00      7055560.00
      2301229.02      7055510.00
#Sta/Elev= 30
  4430.0  834.42  4470.8  834.59  4480.7  833.23  4501.5  833.31  4565.8  831.93
  4621.9  831.42  4636.4  830.82  4665.3  830.55  4694.3  829.70  4700.6  829.89
  4744.0  829.07  4793.8  827.40  4800.1  827.60  4843.6  825.66  4878.9  825.73
  4899.7  824.64  4992.9  824.47  5002.7  824.10  5008.3  823.06  5008.6  822.56
  5012.1  822.56  5012.3  823.06  5020.5  824.72  5040.9  824.86  5081.7  827.13
  5173.5  830.83  5183.7  831.68  5214.3  833.02  5234.7  834.70  5255.1  835.85
#Mann=3,-1,0
  4430.0    0.05       0  5008.3   0.033       0  5012.3    0.05       0
Bank Sta=5008.3,5012.3
Exp/Cntr=0.3,0.1

Type RM Length L Ch R = 1,13685,368,368,368
BEGIN DESCRIPTION:
Elizabeth Creek Tributary 24 24.0
END DESCRIPTION:
XS GIS Cut Line= 3
      2300578.97      7055759.99      2301079.00      7055910.00
      2301329.00      7055710.00
#Sta/Elev= 30
  4477.9  830.96  4604.1  828.46  4703.3  825.80  4791.1  824.34  4832.9  822.63
  4845.9  822.73  4864.2  822.09  4885.1  822.26  4895.5  821.93  4912.1  822.32
  4937.3  821.59  4950.4  822.30  4978.2  822.26  4989.5  821.69  4995.3  820.67
  4995.6  820.17  4999.1  820.17  4999.3  820.67  5003.1  820.67  5007.1  821.98
  5036.0  823.83  5128.0  826.42  5135.2  827.01  5141.6  826.96  5184.8  828.46
  5199.2  829.41  5220.1  830.13  5256.1  831.99  5263.3  832.79  5320.1  835.98
#Mann=3,-1,0
  4477.9    0.05       0  4995.3   0.033       0  4999.3    0.05       0
Bank Sta=4995.3,4999.3
Exp/Cntr=0.3,0.1

Type RM Length L Ch R = 1,13317,364,364,364
BEGIN DESCRIPTION:
Elizabeth Creek Tributary 24 23.0
END DESCRIPTION:
XS GIS Cut Line= 3
      2300429.00      7056310.00      2301029.00      7056210.00
      2301329.01      7055959.99
#Sta/Elev= 30
  4387.4  832.20  4498.9  829.46  4536.9  827.99  4651.0  825.27  4742.2  825.06
  4813.2  824.11  4823.3  824.59  4846.1  824.70  4894.3  823.86  4924.7  823.84
  4934.8  823.44  4945.0  822.20  4955.1  819.76  4962.7  820.03  4983.5  818.94
  4983.8  818.44  4987.3  818.44  4987.5  818.94  5052.3  820.19  5060.1  819.83
  5073.8  820.01  5109.6  821.79  5123.9  822.04  5130.4  820.41  5138.2  820.99
  5144.7  819.65  5151.9  821.60  5159.0  821.95  5208.5  822.63  5386.2  829.12
#Mann=3,-1,0
  4387.4    0.05       0  4983.5   0.033       0  4987.5    0.05       0
Bank Sta=4983.5,4987.5
Exp/Cntr=0.3,0.1

Type RM Length L Ch R = 1,12953,372,372,372
BEGIN DESCRIPTION:
Elizabeth Creek Tributary 24 22.0
END DESCRIPTION:
XS GIS Cut Line= 3
      2300579.00      7056460.00      2301129.00      7056510.00
      2301428.99      7056460.00
#Sta/Elev= 30
  4447.1  828.42  4457.1  828.40  4497.3  826.16  4567.6  824.12  4728.3  820.91
  4738.3  821.02  4818.6  820.04  4878.9  818.51  4899.0  817.05  4909.0  817.01
  4929.1  817.58  4939.1  817.62  4949.2  817.16  4969.2  816.94  5001.9  817.00
  5019.6  816.55  5025.2  815.69  5025.5  815.19  5029.0  815.19  5029.2  815.69
  5032.3  816.48  5039.9  816.42  5050.1  818.83  5080.5  819.44  5154.0  821.99
  5192.0  823.57  5252.8  826.60  5275.6  827.35  5301.0  829.36  5303.5  829.36
#Mann=3,-1,0
  4447.1    0.05       0  5025.2   0.033       0  5029.2    0.05       0
Bank Sta=5025.2,5029.2
Exp/Cntr=0.3,0.1

Type RM Length L Ch R = 1,12581,369,369,369
BEGIN DESCRIPTION:
Elizabeth Creek Tributary 24 21.0
END DESCRIPTION:
XS GIS Cut Line= 3
      2300579.00      7056610.00      2301079.00      7056760.00
      2301379.02      7056559.98
#Sta/Elev= 30
  4472.5  827.68  4494.3  826.20  4587.3  823.41  4769.2  819.06  4858.8  818.02
  4873.6  817.46  4890.1  814.23  4900.6  815.27  4921.4  815.44  4944.9  815.08
  4952.8  814.91  4963.2  812.98  4972.8  815.86  4978.0  816.25  4991.9  815.23
  5023.1  813.96  5028.6  812.58  5028.8  812.08  5032.3  812.08  5032.6  812.58
  5038.1  812.77  5044.1  815.01  5125.2  816.20  5138.7  816.96  5203.3  818.83
  5275.4  821.54  5290.5  822.55  5311.5  823.28  5326.5  824.37  5355.1  825.53
#Mann=3,-1,0
  4472.5    0.05       0  5028.6   0.033       0  5032.6    0.05       0
Bank Sta=5028.6,5032.6
Exp/Cntr=0.3,0.1

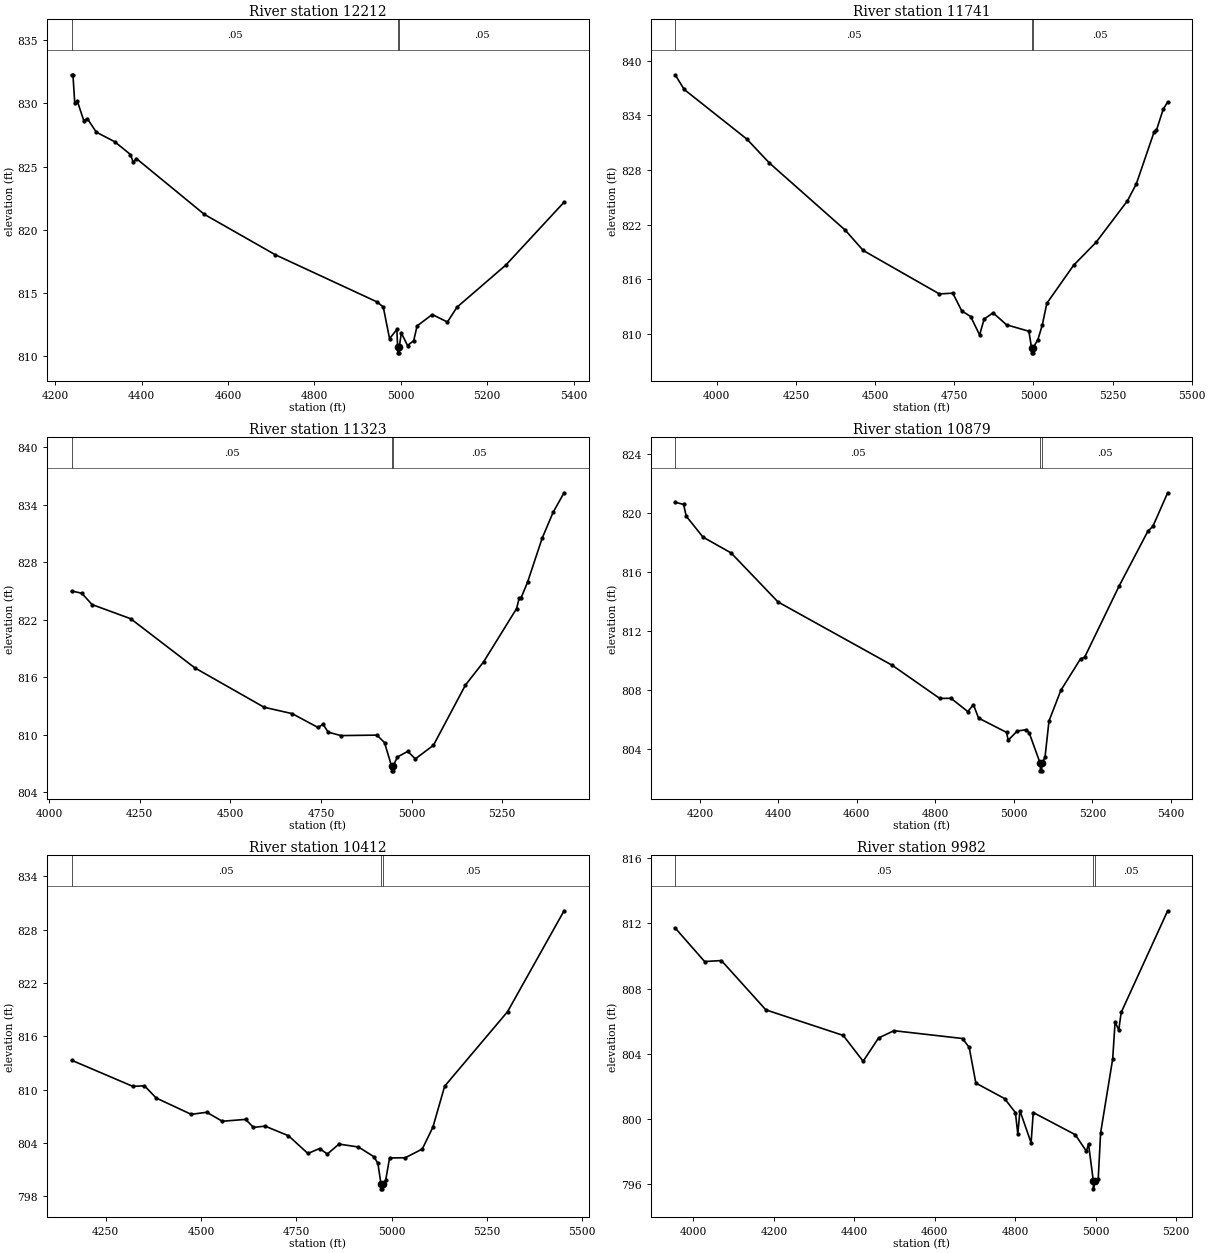
Type RM Length L Ch R = 1,12212,471,471,471
BEGIN DESCRIPTION:
Elizabeth Creek Tributary 24 20.0
END DESCRIPTION:
XS GIS Cut Line= 3
      2300529.02      7057509.98      2301129.00      7057060.00
      2301429.01      7056809.99
#Sta/Elev= 30
  4237.6  832.27  4240.7  832.27  4244.9  830.03  4251.1  830.16  4265.7  828.65
  4274.0  828.80  4294.9  827.73  4337.6  826.97  4374.0  825.96  4380.3  825.34
  4387.6  825.64  4544.9  821.23  4709.4  818.03  4944.9  814.30  4959.4  813.90
  4974.0  811.39  4990.8  812.12  4992.7  810.77  4993.0  810.27  4996.5  810.27
  4996.7  810.77  5001.2  811.84  5015.6  810.85  5029.9  811.23  5037.7  812.40
  5072.8  813.30  5108.0  812.71  5130.1  813.88  5243.4  817.22  5378.1  822.19
#Mann=3,-1,0
  4237.6    0.05       0  4992.7   0.033       0  4996.7    0.05       0
Bank Sta=4992.7,4996.7
Exp/Cntr=0.3,0.1

Type RM Length L Ch R = 1,11741,418,418,418
BEGIN DESCRIPTION:
Elizabeth Creek Tributary 24 19.0
END DESCRIPTION:
XS GIS Cut Line= 3
      2300579.02      7057909.98      2301379.00      7057110.00
      2301678.99      7056810.01
#Sta/Elev= 30
  3868.6  838.46  3896.9  836.85  4094.9  831.40  4165.6  828.79  4406.0  821.39
  4462.5  819.17  4703.0  814.40  4745.4  814.48  4773.7  812.54  4802.0  811.91
  4830.2  809.89  4844.4  811.64  4872.7  812.32  4915.1  811.01  4985.8  810.30
  4994.4  808.43  4994.7  807.93  4998.2  807.93  4998.4  808.43  5014.1  809.36
  5028.2  810.99  5042.4  813.36  5127.2  817.55  5197.9  820.06  5296.9  824.61
  5325.2  826.48  5381.8  832.23  5388.9  832.38  5410.1  834.68  5424.2  835.47
#Mann=3,-1,0
  3868.6    0.05       0  4994.4   0.033       0  4998.4    0.05       0
Bank Sta=4994.4,4998.4
Exp/Cntr=0.3,0.1

Type RM Length L Ch R = 1,11323,444,444,444
BEGIN DESCRIPTION:
Elizabeth Creek Tributary 24 18.0
END DESCRIPTION:
XS GIS Cut Line= 3
      2301078.98      7057960.02      2301729.00      7057260.00
      2301779.00      7056859.99
#Sta/Elev= 30
  4062.4  825.01  4090.5  824.77  4118.8  823.59  4225.4  822.11  4402.3  816.98
  4593.3  812.87  4671.0  812.20  4741.9  810.76  4756.0  811.09  4770.2  810.27
  4805.4  809.91  4904.6  809.96  4925.6  809.17  4945.0  806.73  4945.3  806.23
  4948.8  806.23  4949.1  806.73  4961.3  807.68  4989.6  808.26  5010.6  807.48
  5060.5  808.90  5148.7  815.18  5199.1  817.62  5289.8  823.17  5297.3  824.29
  5302.4  824.31  5320.0  825.91  5360.3  830.51  5390.6  833.22  5420.8  835.26
#Mann=3,-1,0
  4062.4    0.05       0  4945.0    0.04       0  4949.1    0.05       0
Bank Sta=4945,4949.1
Exp/Cntr=0.3,0.1

Type RM Length L Ch R = 1,10879,467,467,467
BEGIN DESCRIPTION:
Elizabeth Creek Tributary 24 17.0
END DESCRIPTION:
XS GIS Cut Line= 3
      2301379.02      7057959.98      2302029.00      7057410.00
      2302079.01      7057009.95
#Sta/Elev= 30
  4137.2  820.73  4158.6  820.58  4165.2  819.79  4208.0  818.37  4279.5  817.30
  4399.2  813.98  4690.3  809.69  4811.2  807.45  4839.8  807.46  4882.7  806.56
  4896.9  807.03  4910.0  806.12  4981.5  805.15  4985.4  804.62  5008.8  805.25
  5031.5  805.33  5039.0  805.12  5067.2  803.05  5067.5  802.55  5071.0  802.55
  5071.3  803.05  5079.3  803.46  5089.4  805.92  5119.7  808.00  5170.0  810.14
  5180.1  810.23  5268.3  815.07  5341.4  818.77  5354.0  819.09  5391.8  821.37
#Mann=3,-1,0
  4137.2    0.05       0  5067.2   0.033       0  5071.3    0.05       0
Bank Sta=5067.2,5071.3
Exp/Cntr=0.3,0.1

Type RM Length L Ch R = 1,10412,430,430,430
BEGIN DESCRIPTION:
Elizabeth Creek Tributary 24 16.0
END DESCRIPTION:
XS GIS Cut Line= 3
      2302163.52      7058087.42      2302329.00      7057260.00
      2302129.01      7056860.02
#Sta/Elev= 30
  4161.1  813.31  4321.6  810.37  4352.2  810.43  4382.8  809.06  4474.6  807.22
  4515.4  807.45  4556.2  806.44  4617.4  806.65  4637.8  805.75  4668.4  805.89
  4729.6  804.81  4780.6  802.81  4811.1  803.37  4831.5  802.75  4862.1  803.87
  4913.1  803.54  4953.9  802.44  4964.1  801.69  4972.3  799.33  4972.6  798.83
  4976.1  798.83  4976.4  799.33  4984.5  799.81  4994.7  802.31  5035.7  802.33
  5080.4  803.31  5108.3  805.78  5139.1  810.39  5304.0  818.78  5452.1  830.14
#Mann=3,-1,0
  4161.1    0.05       0  4972.3   0.033       0  4976.4    0.05       0
Bank Sta=4972.3,4976.4
Exp/Cntr=0.3,0.1

Type RM Length L Ch R = 1,9982,565,565,565
BEGIN DESCRIPTION:
Elizabeth Creek Tributary 24 15.0
END DESCRIPTION:
XS GIS Cut Line= 3
      2302278.99      7058010.03      2302579.00      7057010.00
      2302429.03      7056910.02
#Sta/Elev= 30
  3954.7  811.72  4027.8  809.66  4069.6  809.72  4180.1  806.69  4372.3  805.12
  4421.9  803.53  4460.2  804.96  4498.5  805.41  4669.0  804.93  4685.6  804.38
  4702.1  802.19  4773.4  801.24  4800.4  800.38  4806.5  799.06  4811.7  800.49
  4839.5  798.52  4844.8  800.38  4949.2  799.02  4977.0  798.00  4982.2  798.45
  4994.1  796.19  4994.4  795.69  4998.3  796.19  5006.3  796.28  5012.3  799.13
  5042.3  803.67  5048.3  805.95  5057.4  805.45  5063.4  806.53  5179.0  812.78
#Mann=3,-1,0
  3954.7    0.05       0  4994.1   0.033       0  4998.3    0.05       0
Bank Sta=4994.1,4998.3
Exp/Cntr=0.3,0.1

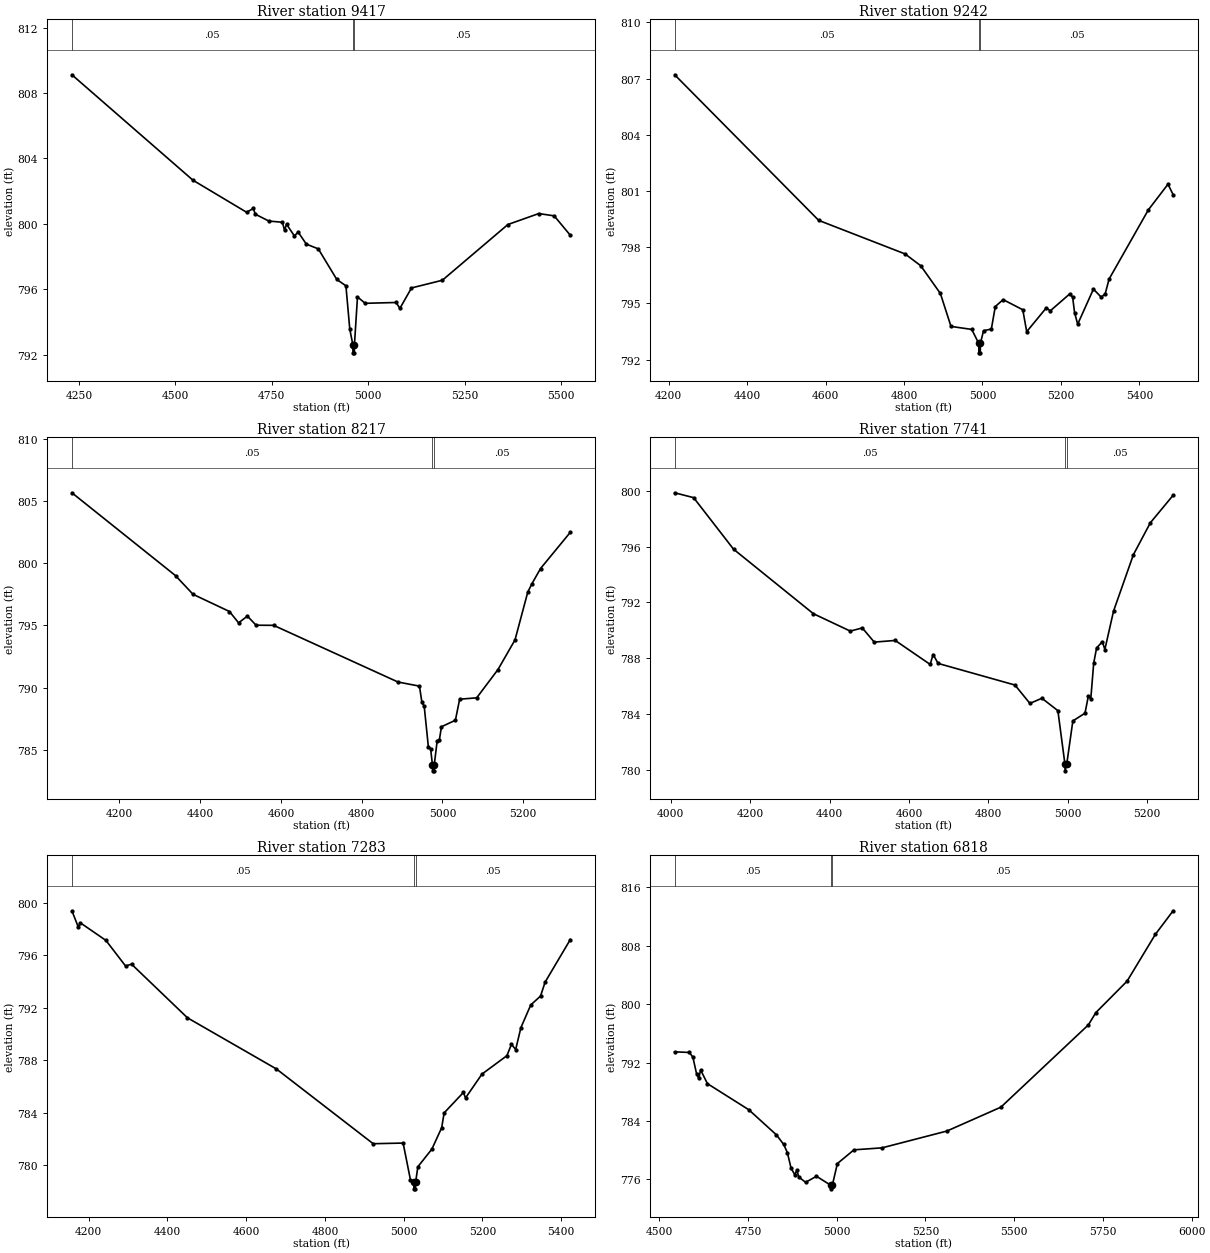
Type RM Length L Ch R = 1,9417,175,175,175
BEGIN DESCRIPTION:
1071
END DESCRIPTION:
XS GIS Cut Line= 3
      2302814.45      7057848.12      2302988.56      7057182.40
      2302988.56      7056578.12
#Sta/Elev= 30
  4232.0  809.12  4545.9  802.67  4684.9  800.71  4702.4  800.94  4707.6  800.59
  4742.9  800.17  4777.9  800.10  4783.3  799.60  4788.5  799.98  4808.9  799.26
  4818.6  799.50  4839.9  798.76  4870.9  798.47  4918.8  796.60  4942.5  796.21
  4952.5  793.56  4960.4  792.61  4960.8  792.11  4964.3  792.11  4964.6  792.61
  4972.5  795.53  4992.5  795.14  5072.5  795.19  5082.5  794.83  5112.5  796.08
  5192.5  796.55  5362.5  799.96  5442.5  800.63  5482.5  800.49  5524.4  799.30
#Mann=3,-1,0
  4232.0    0.05       0  4960.4   0.033       0  4964.6    0.05       0
Bank Sta=4960.4,4964.6
Exp/Cntr=0.3,0.1

Type RM Length L Ch R = 1,9242,1025,1025,1025
BEGIN DESCRIPTION:
1072
END DESCRIPTION:
XS GIS Cut Line= 2
      2303101.22      7057796.91      2303142.19      7056526.87
#Sta/Elev= 30
  4215.5  807.20  4582.6  799.43  4802.7  797.64  4842.7  797.01  4892.8  795.53
  4919.9  793.77  4972.8  793.61  4990.7  792.86  4991.0  792.36  4994.6  792.36
  4994.9  792.86  5002.8  793.54  5022.8  793.63  5032.8  794.83  5052.8  795.20
  5102.9  794.66  5112.9  793.49  5162.9  794.76  5172.9  794.60  5222.9  795.51
  5230.0  795.33  5235.0  794.50  5242.9  793.89  5283.0  795.76  5303.0  795.33
  5313.0  795.51  5323.0  796.30  5423.0  799.99  5473.1  801.36  5486.2  800.80
#Mann=3,-1,0
  4215.5    0.05       0  4990.7   0.033       0  4994.9    0.05       0
Bank Sta=4990.7,4994.9
Exp/Cntr=0.3,0.1

Type RM Length L Ch R = 1,8217,476,476,476
BEGIN DESCRIPTION:
Elizabeth Creek Tributary 24 12.0
END DESCRIPTION:
XS GIS Cut Line= 3
      2303279.00      7057809.99      2303729.00      7057010.00
      2303829.00      7056710.00
#Sta/Elev= 30
  4082.6  805.65  4339.1  799.00  4382.5  797.50  4472.7  796.12  4495.3  795.21
  4517.0  795.75  4538.7  795.02  4582.0  795.01  4889.9  790.46  4943.1  790.13
  4949.2  788.83  4954.9  788.51  4965.1  785.28  4970.8  785.09  4975.2  783.83
  4975.7  783.33  4979.4  783.33  4979.8  783.83  4986.8  785.69  4992.5  785.83
  4997.6  786.87  5032.1  787.39  5042.6  789.08  5084.8  789.19  5137.5  791.46
  5179.7  793.84  5211.3  797.68  5221.8  798.36  5242.9  799.57  5316.7  802.48
#Mann=3,-1,0
  4082.6    0.05       0  4975.2   0.033       0  4979.8    0.05       0
Bank Sta=4975.2,4979.8
Exp/Cntr=0.3,0.1

Type RM Length L Ch R = 1,7741,458,458,458
BEGIN DESCRIPTION:
Elizabeth Creek Tributary 24 11.0
END DESCRIPTION:
XS GIS Cut Line= 3
      2304279.00      7057959.99      2304179.00      7056960.00
      2304028.98      7056759.98
#Sta/Elev= 30
  4010.2  799.87  4057.9  799.52  4158.4  795.82  4359.4  791.19  4452.4  789.94
  4482.5  790.17  4512.7  789.15  4565.4  789.27  4653.4  787.55  4660.9  788.26
  4673.5  787.62  4866.9  786.07  4904.6  784.75  4934.8  785.12  4975.0  784.23
  4992.7  780.41  4993.2  779.91  4997.4  780.41  5012.7  783.49  5043.3  784.05
  5051.6  785.26  5057.9  785.09  5065.2  787.64  5072.5  788.73  5087.0  789.18
  5093.3  788.62  5115.2  791.38  5165.2  795.43  5207.9  797.72  5265.2  799.69
#Mann=3,-1,0
  4010.2    0.05       0  4992.7   0.033       0  4997.4    0.05       0
Bank Sta=4992.7,4997.4
Exp/Cntr=0.3,0.1

Type RM Length L Ch R = 1,7283,465,465,465
BEGIN DESCRIPTION:
Elizabeth Creek Tributary 24 10.0
END DESCRIPTION:
XS GIS Cut Line= 3
      2304329.01      7057909.98      2304579.00      7057110.00
      2304429.01      7056710.03
#Sta/Elev= 30
  4157.8  799.40  4174.0  798.16  4179.3  798.48  4244.2  797.14  4294.0  795.19
  4309.2  795.33  4451.1  791.24  4676.9  787.34  4922.6  781.64  4998.6  781.69
  5017.3  778.87  5025.6  778.70  5026.1  778.20  5029.8  778.20  5030.3  778.70
  5036.0  779.88  5071.6  781.23  5096.5  782.86  5102.7  783.99  5151.7  785.55
  5157.0  785.13  5198.8  786.95  5262.0  788.35  5273.6  789.22  5284.3  788.82
  5297.6  790.49  5322.6  792.22  5347.5  792.90  5359.0  793.96  5423.1  797.21
#Mann=3,-1,0
  4157.8    0.05       0  5025.6   0.033       0  5030.3    0.05       0
Bank Sta=5025.6,5030.3
Exp/Cntr=0.3,0.1

Type RM Length L Ch R = 1,6818,450,450,450
BEGIN DESCRIPTION:
Elizabeth Creek Tributary 24 9.0
END DESCRIPTION:
XS GIS Cut Line= 3
      2304879.00      7057660.02      2304979.00      7057210.00
      2304479.00      7056409.99
#Sta/Elev= 30
  4543.4  793.47  4584.4  793.39  4594.6  792.76  4604.9  790.50  4611.3  789.83
  4616.4  791.00  4635.6  789.12  4752.1  785.55  4830.2  782.10  4850.7  780.79
  4861.0  779.66  4871.2  777.57  4881.5  776.67  4887.9  777.26  4893.0  776.35
  4912.2  775.61  4942.9  776.44  4982.8  775.22  4983.3  774.72  4987.6  775.22
  5001.8  778.18  5048.6  780.06  5127.6  780.33  5310.4  782.63  5462.5  785.90
  5709.0  797.16  5730.2  798.85  5818.1  803.15  5897.7  809.55  5947.8  812.78
#Mann=3,-1,0
  4543.4    0.05       0  4982.8   0.033       0  4987.6    0.05       0
Bank Sta=4982.8,4987.6
Exp/Cntr=0.3,0.1

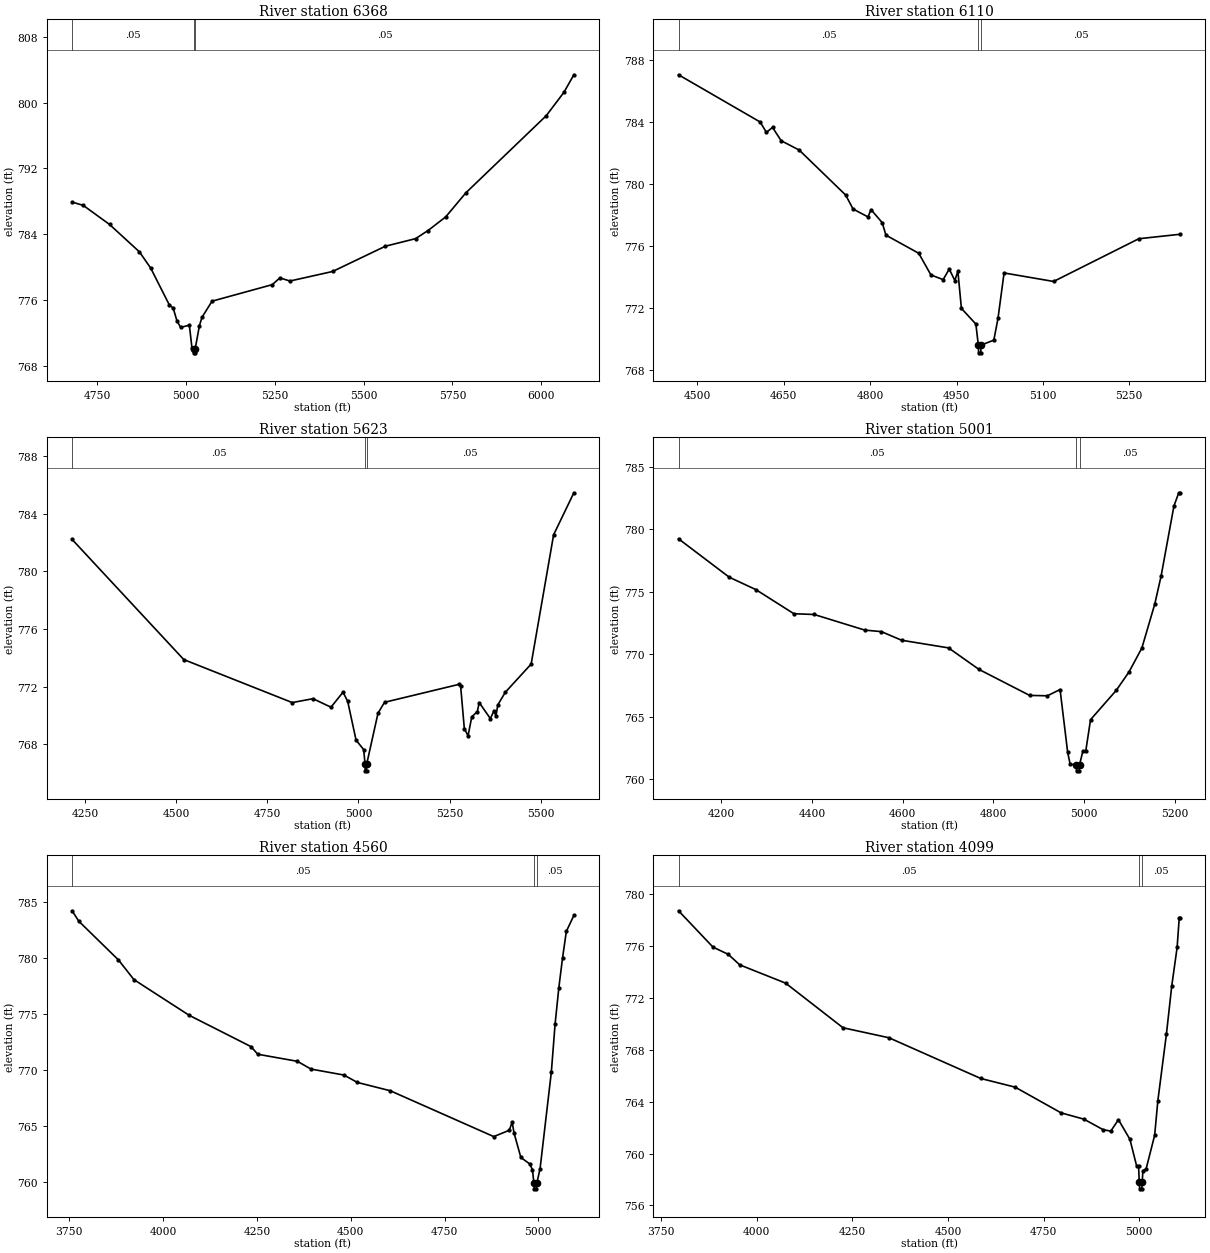
Type RM Length L Ch R = 1,6368,258,258,258
BEGIN DESCRIPTION:
Elizabeth Creek Tributary 24 8.0
END DESCRIPTION:
XS GIS Cut Line= 3
      2305279.00      7057560.01      2305379.00      7057260.00
      2304629.01      7056460.01
#Sta/Elev= 30
  4679.2  787.92  4710.8  787.51  4784.6  785.20  4868.9  781.86  4900.6  779.89
  4953.3  775.39  4963.8  775.04  4974.4  773.49  4984.9  772.68  5009.4  772.95
  5016.7  770.22  5021.1  770.09  5021.7  769.59  5025.4  769.59  5025.9  770.09
  5037.7  772.88  5045.0  773.91  5073.3  775.87  5242.9  777.88  5264.3  778.70
  5292.7  778.32  5412.8  779.48  5561.3  782.55  5646.3  783.47  5681.5  784.46
  5731.3  786.12  5787.9  789.04  6014.1  798.41  6063.9  801.25  6092.0  803.39
#Mann=3,-1,0
  4679.2    0.05       0  5021.1   0.033       0  5025.9    0.05       0
Bank Sta=5021.1,5025.9
Exp/Cntr=0.3,0.1

Type RM Length L Ch R = 1,6110,487,487,487
BEGIN DESCRIPTION:
1074
END DESCRIPTION:
XS GIS Cut Line= 3
      2305426.20      7057684.31      2305631.06      7057090.22
      2305518.40      7056875.16
#Sta/Elev= 30
  4467.4  787.06  4609.1  784.01  4620.0  783.34  4630.6  783.66  4645.6  782.80
  4676.8  782.20  4757.6  779.29  4770.4  778.39  4796.3  777.88  4801.6  778.35
  4821.0  777.51  4827.5  776.70  4884.5  775.53  4905.6  774.13  4926.8  773.83
  4937.4  774.51  4947.1  773.77  4952.4  774.37  4958.5  771.97  4983.6  770.96
  4987.9  769.60  4988.4  769.10  4992.1  769.10  4992.7  769.60  5014.8  769.92
  5022.0  771.32  5032.6  774.26  5118.6  773.71  5266.5  776.47  5338.6  776.76
#Mann=3,-1,0
  4467.4    0.05       0  4987.9   0.033       0  4992.7    0.05       0
Bank Sta=4987.9,4992.7
Exp/Cntr=0.3,0.1

Type RM Length L Ch R = 1,5623,622,622,622
BEGIN DESCRIPTION:
1073
END DESCRIPTION:
XS GIS Cut Line= 4
      2305579.84      7057653.55      2306061.23      7057120.95
      2305990.90      7057019.35      2306096.13      7056495.60
#Sta/Elev= 30
  4214.9  782.21  4521.2  773.88  4818.6  770.90  4875.4  771.17  4924.7  770.58
  4957.7  771.62  4970.5  770.99  4993.5  768.30  5014.4  767.64  5018.0  766.67
  5018.6  766.17  5022.3  766.17  5022.9  766.67  5053.7  770.17  5071.6  770.92
  5275.1  772.16  5280.2  772.04  5290.3  769.10  5300.5  768.60  5310.7  769.91
  5326.0  770.28  5331.1  770.90  5361.7  769.79  5371.8  770.34  5376.9  769.95
  5382.1  770.74  5402.5  771.61  5473.5  773.57  5535.1  782.53  5590.6  785.44
#Mann=3,-1,0
  4214.9    0.05       0  5018.0   0.033       0  5022.9    0.05       0
Bank Sta=5018,5022.9
Exp/Cntr=0.3,0.1

Type RM Length L Ch R = 1,5001,441,441,441
BEGIN DESCRIPTION:
Elizabeth Creek Tributary 24 6.0
END DESCRIPTION:
XS GIS Cut Line= 3
      2305678.96      7057660.02      2306479.00      7057260.00
      2306629.00      7057110.00
#Sta/Elev= 30
  4105.7  779.24  4217.5  776.17  4276.2  775.18  4360.1  773.25  4404.8  773.19
  4516.6  771.94  4553.0  771.82  4597.7  771.13  4701.1  770.52  4768.2  768.80
  4880.0  766.72  4919.1  766.69  4947.1  767.19  4963.8  762.18  4969.4  761.20
  4982.3  761.19  4983.5  760.69  4988.9  760.69  4990.1  761.19  4997.4  762.26
  5003.7  762.26  5014.3  764.78  5070.9  767.12  5099.2  768.60  5127.5  770.51
  5155.7  773.99  5169.9  776.26  5198.2  781.86  5208.8  782.92  5212.3  782.92
#Mann=3,-1,0
  4105.7    0.05       0  4982.3   0.033       0  4990.1    0.05       0
Bank Sta=4982.3,4990.1
Exp/Cntr=0.3,0.1

Type RM Length L Ch R = 1,4560,461,461,461
BEGIN DESCRIPTION:
Elizabeth Creek Tributary 24 5.0
END DESCRIPTION:
XS GIS Cut Line= 3
      2305579.04      7057809.99      2306779.00      7057510.00
      2306879.01      7057510.00
#Sta/Elev= 30
  3757.7  784.18  3775.7  783.25  3881.4  779.80  3922.6  778.05  4069.5  774.88
  4234.4  772.09  4252.4  771.41  4358.1  770.78  4394.2  770.09  4481.8  769.56
  4517.9  768.90  4605.5  768.16  4881.2  764.08  4922.4  764.64  4930.2  765.36
  4935.3  764.39  4953.4  762.22  4976.6  761.66  4984.3  761.14  4988.1  759.93
  4989.3  759.43  4994.7  759.43  4995.9  759.93  5004.6  761.23  5034.6  769.82
  5044.6  774.10  5054.6  777.34  5064.6  780.02  5074.6  782.35  5094.6  783.76
#Mann=3,-1,0
  3757.7    0.05       0  4988.1   0.033       0  4995.9    0.05       0
Bank Sta=4988.1,4995.9
Exp/Cntr=0.3,0.1

Type RM Length L Ch R = 1,4099,538,538,538
BEGIN DESCRIPTION:
Elizabeth Creek Tributary 24 4.0
END DESCRIPTION:
XS GIS Cut Line= 3
      2305729.05      7057910.00      2306929.00      7057910.00
      2307029.04      7057859.98
#Sta/Elev= 30
  3795.8  778.72  3885.8  775.92  3925.8  775.36  3955.8  774.55  4075.8  773.14
  4225.8  769.70  4345.8  768.93  4585.8  765.79  4675.8  765.12  4795.8  763.14
  4855.8  762.65  4905.8  761.84  4925.8  761.73  4945.8  762.61  4975.8  761.10
  4993.3  759.05  4998.5  759.05  5000.2  757.78  5001.4  757.28  5006.9  757.28
  5008.0  757.78  5009.7  758.68  5018.1  758.81  5040.5  761.41  5048.9  764.09
  5071.2  769.20  5085.2  772.93  5099.2  775.89  5104.8  778.19  5107.6  778.19
#Mann=3,-1,0
  3795.8    0.05       0  5000.2   0.033       0  5008.0    0.05       0
Bank Sta=5000.2,5008
Exp/Cntr=0.3,0.1

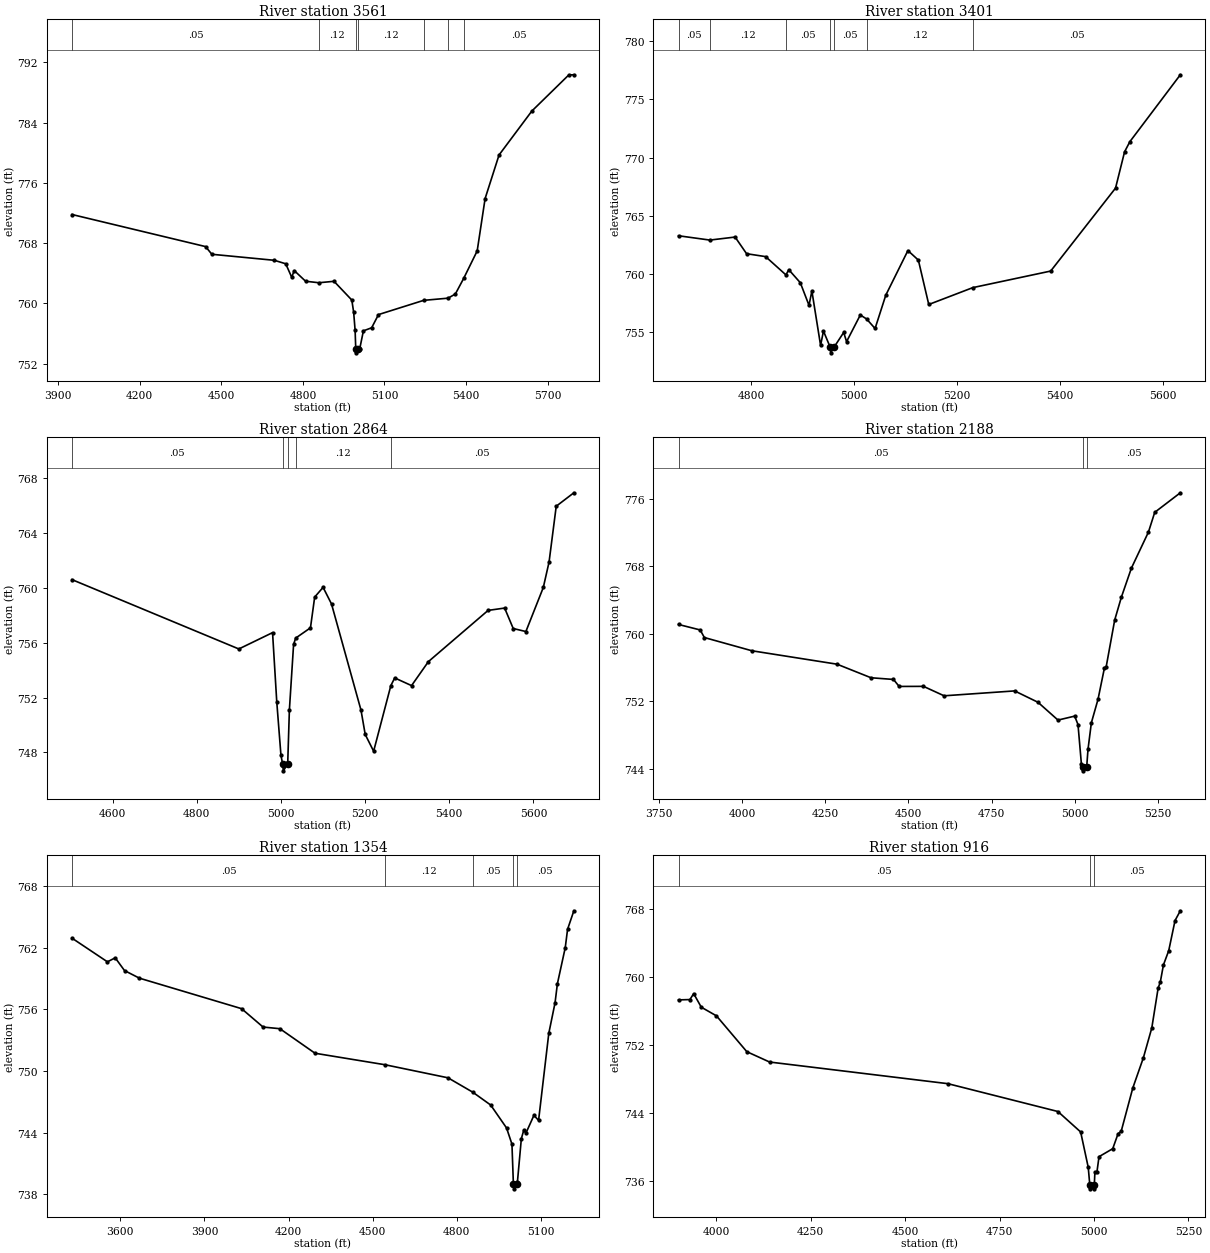
Type RM Length L Ch R = 1,3561,160,160,160
BEGIN DESCRIPTION:
1062
END DESCRIPTION:
XS GIS Cut Line= 4
      2306007.05      7058101.30      2306989.30      7058399.71
      2307107.42      7058356.19      2307175.80      7057666.13
#Sta/Elev= 30
  3950.9  771.80  4442.1  767.54  4465.1  766.52  4695.0  765.72  4736.8  765.26
  4758.9  763.47  4768.1  764.36  4809.9  762.94  4858.7  762.74  4914.5  762.93
  4980.0  760.44  4986.8  758.81  4992.1  756.42  4994.5  753.93  4995.7  753.43
  5002.4  753.93  5009.1  753.97  5022.6  756.35  5053.0  756.76  5078.1  758.51
  5244.2  760.40  5333.9  760.69  5360.8  761.24  5391.4  763.31  5441.2  766.97
  5470.3  773.92  5521.6  779.71  5642.2  785.54  5778.2  790.34  5796.8  790.36
#Mann=7,-1,0
  3950.9    0.05       0  4858.7    0.12       0  4994.5    0.07       0
  5002.4    0.12       0  5244.2    0.05       0  5333.9    0.12       0
  5391.4    0.05       0
Bank Sta=4994.5,5002.4
Exp/Cntr=0.3,0.1

Type RM Length L Ch R = 1,3401,537,537,537
BEGIN DESCRIPTION:
1668
END DESCRIPTION:
XS GIS Cut Line= 4
      2306820.40      7058361.11      2307119.42      7058508.35
      2307212.31      7058431.32      2307333.90      7057924.69
#Sta/Elev= 30
  4659.3  763.29  4720.2  762.92  4769.2  763.18  4791.5  761.75  4828.5  761.50
  4868.0  759.93  4873.5  760.38  4895.9  759.26  4912.8  757.32  4918.4  758.55
  4935.3  753.88  4940.9  755.11  4953.8  753.74  4955.0  753.24  4961.7  753.74
  4980.2  754.99  4985.8  754.20  5012.5  756.49  5024.6  756.15  5041.2  755.33
  5062.0  758.19  5105.0  762.02  5125.3  761.20  5145.5  757.39  5231.2  758.84
  5382.4  760.26  5508.4  767.38  5526.0  770.50  5536.3  771.37  5634.3  777.11
#Mann=7,-1,0
  4659.3    0.05       0  4720.2    0.12       0  4868.0    0.05       0
  4953.8    0.04       0  4961.7    0.05       0  5024.6    0.12       0
  5231.2    0.05       0
Bank Sta=4953.8,4961.7
Exp/Cntr=0.3,0.1

Type RM Length L Ch R = 1,2864,676,676,676
BEGIN DESCRIPTION:
1667
END DESCRIPTION:
XS GIS Cut Line= 4
      2307346.01      7059122.30      2307586.14      7058821.01
      2307613.32      7058225.15      2307656.38      7058018.95
#Sta/Elev= 30
  4503.7  760.59  4900.0  755.54  4980.1  756.73  4990.1  751.69  5000.1  747.78
  5004.1  747.16  5005.8  746.66  5016.1  747.16  5020.1  751.09  5030.1  755.87
  5035.0  756.33  5070.2  757.08  5080.2  759.32  5100.2  760.03  5120.2  758.82
  5190.3  751.08  5200.3  749.31  5220.3  748.09  5261.2  752.87  5270.4  753.43
  5310.4  752.87  5350.5  754.62  5492.3  758.35  5531.6  758.52  5552.0  757.03
  5582.1  756.81  5623.5  760.02  5637.2  761.88  5654.2  765.94  5696.1  766.92
#Mann=5,-1,0
  4503.7    0.05       0  5004.1   0.033       0  5016.1    0.05       0
  5035.0    0.12       0  5261.2    0.05       0
Bank Sta=5004.1,5016.1
Exp/Cntr=0.3,0.1

Type RM Length L Ch R = 1,2188,834,834,834
BEGIN DESCRIPTION:
Elizabeth Creek Tributary 24 3.0
END DESCRIPTION:
XS GIS Cut Line= 3
      2307350.53      7059147.25      2308075.51      7058793.82
      2308132.01      7058093.24
#Sta/Elev= 30
  3808.3  761.09  3873.4  760.44  3886.0  759.54  4029.1  757.97  4285.0  756.38
  4387.3  754.77  4454.9  754.57  4471.9  753.74  4545.1  753.75  4607.1  752.63
  4819.3  753.21  4889.6  751.86  4949.7  749.75  4999.9  750.22  5009.9  749.22
  5020.0  744.59  5024.0  744.23  5025.7  743.73  5036.1  744.23  5040.0  746.28
  5050.1  749.43  5070.1  752.21  5089.4  755.93  5094.4  756.01  5120.3  761.62
  5140.4  764.33  5170.5  767.77  5221.8  772.05  5240.7  774.39  5317.7  776.71
#Mann=3,-1,0
  3808.3    0.05       0  5024.0   0.033       0  5036.1    0.05       0
Bank Sta=5024,5036.1
Exp/Cntr=0.3,0.1

Type RM Length L Ch R = 1,1354,438,438,438
BEGIN DESCRIPTION:
Elizabeth Creek Tributary 24 2.0
END DESCRIPTION:
XS GIS Cut Line= 3
      2307279.05      7059209.99      2308779.00      7058760.00
      2308979.00      7058660.00
#Sta/Elev= 30
  3427.9  762.94  3554.0  760.64  3581.8  761.03  3614.9  759.79  3668.0  759.05
  4032.5  756.08  4109.1  754.29  4169.1  754.13  4294.4  751.74  4544.3  750.62
  4768.6  749.35  4856.9  747.95  4920.8  746.70  4977.4  744.47  4996.7  742.89
  5001.8  739.04  5003.5  738.54  5013.9  739.04  5016.3  739.23  5030.2  743.42
  5038.6  744.23  5047.0  743.99  5075.0  745.69  5091.7  745.21  5128.1  753.68
  5150.4  756.65  5158.8  758.51  5186.8  762.02  5195.1  763.81  5217.5  765.61
#Mann=5,-1,0
  3427.9    0.05       0  4544.3    0.12       0  4856.9    0.05       0
  5001.8   0.033       0  5013.9    0.05       0
Bank Sta=5001.8,5013.9
Exp/Cntr=0.3,0.1

Type RM Length L Ch R = 1,916,0,0,0
BEGIN DESCRIPTION:
Elizabeth Creek Tributary 24 1.0
END DESCRIPTION:
XS GIS Cut Line= 3
      2307979.04      7059160.00      2309079.00      7059060.00
      2309179.00      7058860.01
#Sta/Elev= 30
  3900.4  757.34  3930.5  757.38  3940.5  758.08  3960.6  756.48  4000.8  755.46
  4081.1  751.24  4141.4  750.02  4613.3  747.47  4904.5  744.19  4964.7  741.78
  4984.8  737.61  4988.8  735.58  4990.5  735.08  4999.2  735.08  5000.9  735.58
  5002.4  737.04  5007.7  737.04  5013.3  738.87  5049.6  739.81  5063.6  741.56
  5072.0  741.86  5102.7  746.96  5130.7  750.52  5153.0  754.04  5169.8  758.74
  5175.4  759.42  5183.8  761.46  5197.8  763.14  5214.5  766.69  5228.5  767.84
#Mann=3,-1,0
  3900.4    0.05       0  4988.8   0.033       0  5000.9    0.05       0
Bank Sta=4988.8,5000.9
Exp/Cntr=0.3,0.1

Chan Stop Cuts=-1