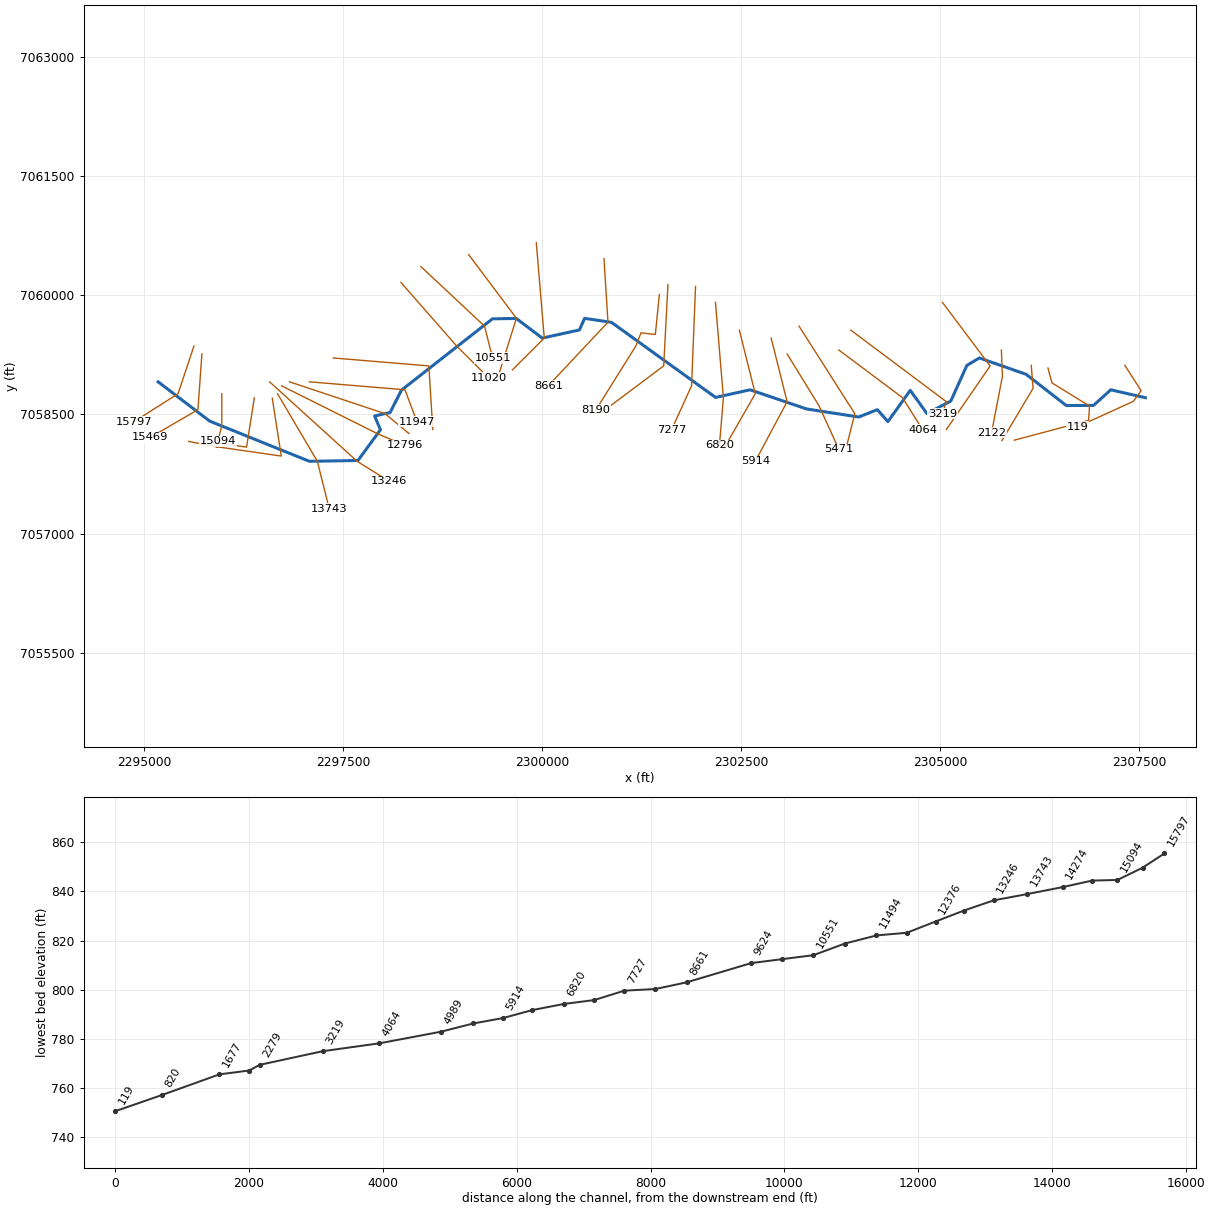
--- Elizabeth Cr Tr 24_1.prj (project) ---

Proj Title=Elizabeth Cr Tr 24_1 Base Level Engineering
Current Plan=p01
Default Exp/Contr=0.3,0.1
English Units
Geom File=g01
Flow File=f01
Plan File=p01
Y Axis Title=Elevation
X Axis Title(PF)=Main Channel Distance
X Axis Title(XS)=Station
BEGIN DESCRIPTION:
Elizabeth Cr Tr 24_1
END DESCRIPTION:
DSS Export Rating Curves= 0
DSS Export Rating Curve Sorted= 0
DSS Export Volume Flow Curves= 0
DXF OffsetX= 0
DXF OffsetY= 0
DXF ScaleX= 1
DXF ScaleY= 10

--- Elizabeth Cr Tr 24_1.p01 (plan) ---

Plan Title=Multiple Run
Program Version=4.10
Short Identifier=Multiple
Geom File=g01
Flow File=f01
Subcritical Flow
K Sum by GR= 0
Std Step Tol= 0.01
Critical Tol= 0.01
Num of Std Step Trials= 20
Max Error Tol= 0.3
Flow Tol Ratio= 0.001
Split Flow NTrial= 30
Split Flow Tol= 0.02
Split Flow Ratio= 0.02
Log Output Level= 0
Friction Slope Method= 0
Unsteady Friction Slope Method= 2
Unsteady Bridges Friction Slope Method= 1
Parabolic Critical Depth
Global Vel Dist= 1 , 1 , 1
Global Log Level= 0
CheckData=True
Encroach Param=-1 ,0,0, 0
BEGIN DESCRIPTION:
Multiple Run
END DESCRIPTION:
Computation Interval=1HOUR
Output Interval=1HOUR
Run HTab= 0
Run UNet= 0
Run PostProcess= 0
Run WQNet= 0
UNET Theta= 1
UNET Theta Warmup= 1
UNET ZTol= 0.02
UNET ZSATol= 0.05
UNET MxIter= 20
UNET MaxInSteps= 0
UNET DtIC= 0
UNET DtMin= 0
UNET MaxCRTS= 20
UNET WFStab= 2
UNET SFStab= 1
UNET WFX= 1
UNET SFX= 1
UNET DSS MLevel= 4
UNET DZMax Abort= 100
UNET Convert EG Bridges= 0
UNET Use Existing IB Tables=-1
UNET Froude Reduction=False
UNET Froude Limit= 1
UNET Froude Power= 10
UNET Time Slicing=0,0, 5
UNET Junction Losses=0
Instantaneous Interval=1HOUR
Write IC File= 0
Write IC File at Sim End=0
Echo Input=False
Echo Parameters=False
Echo Output=False
Write Detailed= 0
WQ AD Non Conservative
WQ ULTIMATE=-1
WQ Max Comp Step=1HOUR
WQ Output Interval=15MIN
WQ Output Selected Increments= 0
WQ Output face flow=0
WQ Output face velocity=0
WQ Output face area=0
WQ Output face dispersion=0
WQ Output cell volume=0
WQ Output cell surface area=0
WQ Output cell continuity=0
WQ Output cumulative cell continuity=0
WQ Output face conc=0
WQ Output face dconc_dx=0
WQ Output face courant=0
WQ Output face peclet=0
WQ Output face adv mass=0
WQ Output face disp mass=0
WQ Output cell mass=0
WQ Output cell source sink temp=0
WQ Output cell source sink nsm=0
WQ Output MaxMinRange=-1
WQ Daily Max Min Mean=-1
WQ Daily Range=0
WQ Daily Time=0
WQ Create Restart=0
WQ Fixed Restart=0
WQ System Summary=0
WQ Use Fixed Temperature=0
Sorting and Armoring Iterations= 10
XS Update Threshold= 0.02
Hydraulics Update Threshold= 0.02
Energy Slope Method= 1
Volume Change Method= 0
XS Weighting Method= 0
Number of US Weighted Cross Sections= 1
Number of DS Weighted Cross Sections= 1
Upstream XS Weight=0.25
Main XS Weight=0.5
Downstream XS Weight=0.25
Number of DS XS's Weighted with US Boundary= 1
Upstream Boundary Weight= 1
Weight of XSs Associated with US Boundary= 0
Number of US XS's Weighted with DS Boundary= 1
Downstream Boundary Weight= 0.5
Weight of XSs Associated with DS Boundary= 0.5
Sediment Output Level= 4
Mass or Volume Output= 0
Output Increment Type= 1
Profile and TS Output Increment= 10
XS Output Flag= 0
XS Output Increment= 10
Disregard all LS=0
Disregard all Conn=0
Disregard all Breaches=0
Disregard all Pumps=0

--- Elizabeth Cr Tr 24_1.f01 (steady flow) ---

Flow Title=Multiple
Number of Profiles=7
Profile Names=10-year,25-year,50-year,1pct_min,100-year,1pct_plu,500-year
River Rch & RM= Elizabeth Cr Tr ,Reach-1,15797
     336     443     527     312     623    1240     871
River Rch & RM= Elizabeth Cr Tr ,Reach-1,13743
     639     878    1070     652    1300    2600    1910
River Rch & RM= Elizabeth Cr Tr ,Reach-1,11020
     839    1170    1440     879    1750    3500    2620
River Rch & RM= Elizabeth Cr Tr ,Reach-1,10084
     978    1370    1700    1040    2080    4150    3130
River Rch & RM= Elizabeth Cr Tr ,Reach-1,4064
    1080    1520    1890    1170    2330    4640    3530
Boundary for River Rch & Prof#=Elizabeth Cr Tr ,Reach-1,1
Up Type=0
Dn Type=3
Dn Slope=0.005
Boundary for River Rch & Prof#=Elizabeth Cr Tr ,Reach-1,2
Up Type=0
Dn Type=3
Dn Slope=0.005
Boundary for River Rch & Prof#=Elizabeth Cr Tr ,Reach-1,3
Up Type=0
Dn Type=3
Dn Slope=0.005
Boundary for River Rch & Prof#=Elizabeth Cr Tr ,Reach-1,4
Up Type=0
Dn Type=3
Dn Slope=0.005
Boundary for River Rch & Prof#=Elizabeth Cr Tr ,Reach-1,5
Up Type=0
Dn Type=3
Dn Slope=0.005
Boundary for River Rch & Prof#=Elizabeth Cr Tr ,Reach-1,6
Up Type=0
Dn Type=3
Dn Slope=0.005
Boundary for River Rch & Prof#=Elizabeth Cr Tr ,Reach-1,7
Up Type=0
Dn Type=3
Dn Slope=0.005

--- Elizabeth Cr Tr 24_1.g01 (geometry) ---

Geom Title=Existing Conditions

River Reach=Elizabeth Cr Tr ,Reach-1
Reach XY= 30
      2295179.00      7058910.00      2295826.70      7058415.83
      2297079.00      7057910.00      2297688.80      7057920.48
      2297971.39      7058306.67      2297898.21      7058480.58
      2298092.35      7058523.36      2298234.59      7058804.39
      2299378.90      7059702.68      2299677.42      7059706.33
      2300003.80      7059459.68      2300471.02      7059562.95
      2300534.83      7059708.46      2300873.15      7059657.94
      2302180.55      7058713.75      2302613.72      7058809.63
      2303325.68      7058568.04      2303979.00      7058467.56
      2304212.99      7058559.77      2304344.42      7058409.86
      2304625.59      7058802.23      2304834.83      7058511.53
      2305135.07      7058668.13      2305336.70      7059116.48
      2305494.41      7059209.98      2306081.29      7059004.16
      2306585.12      7058611.84      2306927.54      7058613.53
      2307144.16      7058809.64      2307579.00      7058710.00

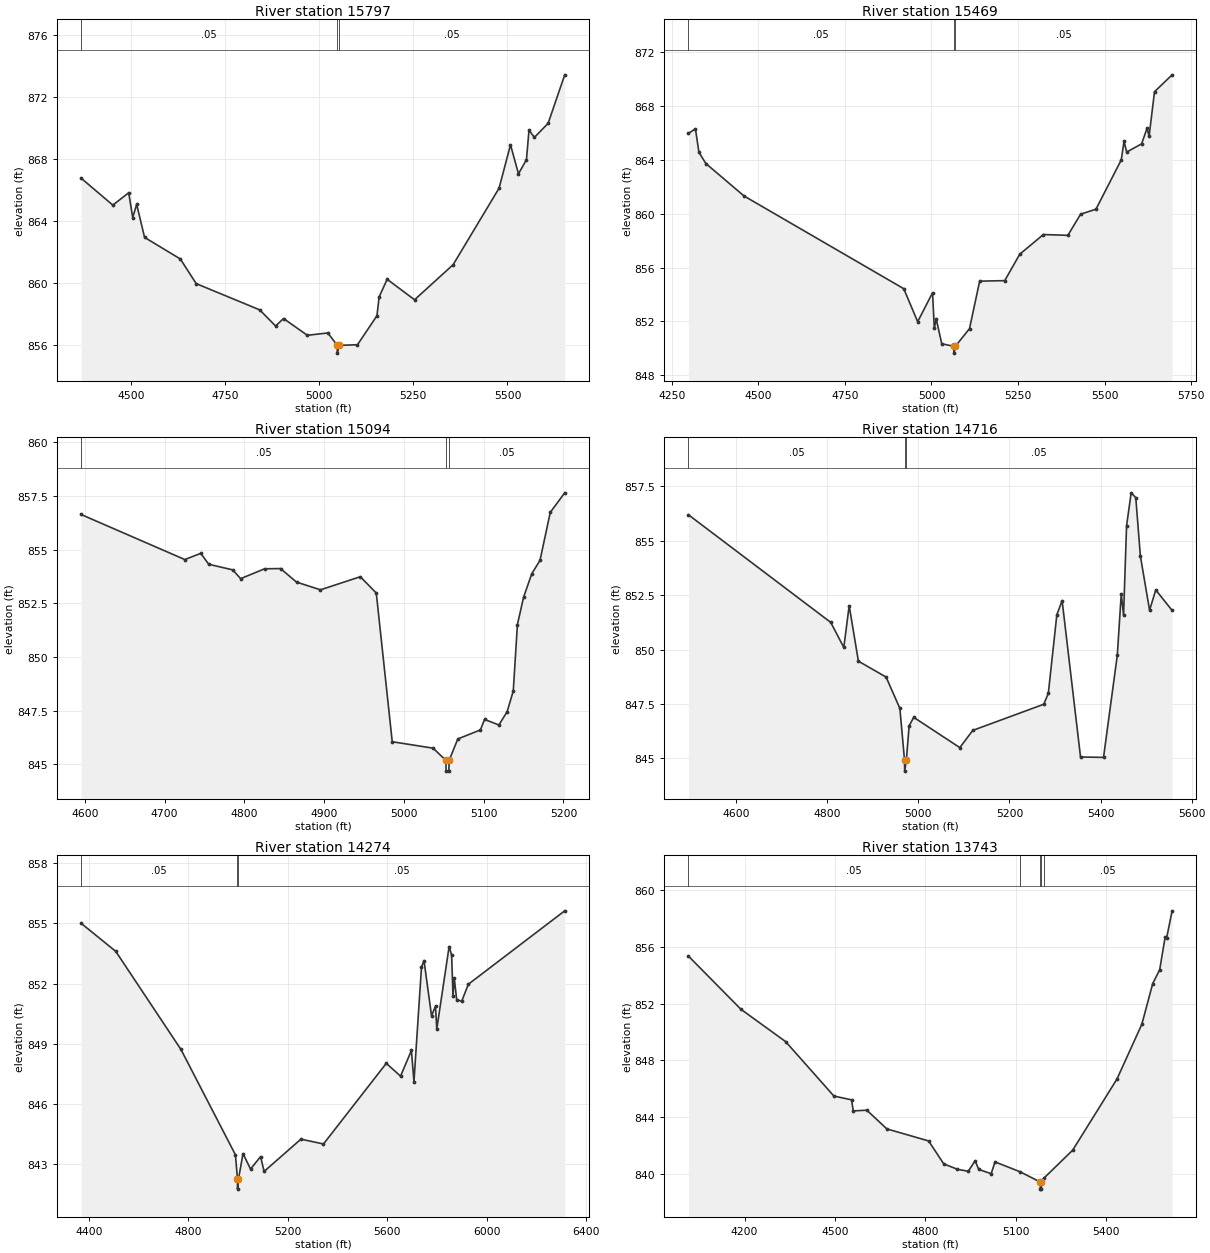
Type RM Length L Ch R = 1,15797,328,328,328
BEGIN DESCRIPTION:
Elizabeth Creek Tributary 24_1 28.0
END DESCRIPTION:
XS GIS Cut Line= 3
      2295629.00      7059359.99      2295429.00      7058760.00
      2294878.97      7058409.98
#Sta/Elev= 30
  4367.6  866.77  4451.9  865.03  4494.1  865.83  4504.6  864.23  4515.2  865.08
  4536.2  862.95  4631.1  861.56  4673.3  859.97  4841.9  858.28  4884.1  857.24
  4905.2  857.72  4968.4  856.64  5022.9  856.79  5048.0  855.99  5048.2  855.49
  5052.0  855.99  5101.6  856.03  5153.3  857.90  5159.2  859.12  5180.4  860.25
  5253.2  858.93  5355.6  861.19  5477.6  866.12  5508.0  868.92  5529.2  867.05
  5550.4  867.96  5557.1  869.86  5571.5  869.40  5607.9  870.30  5652.0  873.43
#Mann=3,-1,0
  4367.6    0.05       0  5048.0   0.033       0  5052.0    0.05       0
Bank Sta=5048,5052
Exp/Cntr=0.3,0.1

Type RM Length L Ch R = 1,15469,375,375,375
BEGIN DESCRIPTION:
Elizabeth Creek Tributary 24_1 27.0
END DESCRIPTION:
XS GIS Cut Line= 3
      2295729.00      7059260.01      2295679.00      7058560.00
      2295079.02      7058210.01
#Sta/Elev= 30
  4298.5  865.96  4318.6  866.29  4328.6  864.55  4348.6  863.72  4458.9  861.31
  4920.1  854.43  4960.2  851.98  5003.2  854.13  5008.2  851.50  5013.9  852.17
  5029.7  850.35  5064.9  850.15  5065.1  849.65  5068.9  850.15  5109.9  851.47
  5139.2  854.99  5211.6  855.03  5255.0  856.99  5323.2  858.45  5393.9  858.39
  5430.7  859.96  5475.0  860.33  5548.1  863.99  5556.0  865.36  5563.8  864.57
  5606.8  865.18  5622.6  866.34  5628.4  865.74  5644.1  869.05  5694.9  870.30
#Mann=3,-1,0
  4298.5    0.05       0  5064.9   0.033       0  5068.9    0.05       0
Bank Sta=5064.9,5068.9
Exp/Cntr=0.3,0.1

Type RM Length L Ch R = 1,15094,378,378,378
BEGIN DESCRIPTION:
Elizabeth Creek Tributary 24_1 26.0
END DESCRIPTION:
XS GIS Cut Line= 3
      2295979.00      7058760.00      2295979.00      7058360.00
      2295928.99      7058159.96
#Sta/Elev= 30
  4595.4  856.64  4725.4  854.54  4745.4  854.83  4755.4  854.32  4785.4  854.06
  4795.4  853.65  4825.4  854.11  4845.4  854.12  4865.4  853.49  4895.4  853.13
  4945.4  853.74  4965.4  852.98  4985.4  846.05  5036.6  845.75  5052.7  845.18
  5052.9  844.68  5056.4  844.68  5056.7  845.18  5067.6  846.18  5095.9  846.60
  5101.1  847.09  5119.1  846.83  5129.4  847.45  5137.1  848.41  5142.3  851.51
  5150.0  852.78  5160.3  853.88  5170.6  854.50  5183.5  856.74  5201.6  857.65
#Mann=3,-1,0
  4595.4    0.05       0  5052.7   0.033       0  5056.7    0.05       0
Bank Sta=5052.7,5056.7
Exp/Cntr=0.3,0.1

Type RM Length L Ch R = 1,14716,442,442,442
BEGIN DESCRIPTION:
1067
END DESCRIPTION:
XS GIS Cut Line= 3
      2296387.43      7058708.51      2296290.13      7058088.84
      2295859.96      7058150.30
#Sta/Elev= 30
  4495.3  856.19  4807.6  851.25  4836.3  850.10  4848.1  852.02  4868.3  849.47
  4929.1  848.74  4959.4  847.30  4969.6  844.92  4969.9  844.42  4973.6  844.92
  4979.7  846.50  4989.8  846.89  5091.0  845.50  5119.4  846.29  5275.2  847.49
  5285.3  847.99  5304.0  851.60  5315.6  852.25  5356.0  845.07  5406.5  845.05
  5436.8  849.75  5445.4  852.56  5450.5  851.58  5457.1  855.69  5467.2  857.20
  5477.3  856.98  5487.4  854.30  5507.6  851.81  5521.2  852.74  5557.1  851.80
#Mann=3,-1,0
  4495.3    0.05       0  4969.6   0.033       0  4973.6    0.05       0
Bank Sta=4969.6,4973.6
Exp/Cntr=0.3,0.1

Type RM Length L Ch R = 1,14274,531,531,531
BEGIN DESCRIPTION:
1066
END DESCRIPTION:
XS GIS Cut Line= 5
      2296612.75      7058703.42      2296725.42      7057976.18
      2295911.16      7058093.96      2295926.53      7058088.84
      2295563.47      7058160.43
#Sta/Elev= 30
  4369.0  855.01  4508.4  853.61  4770.6  848.72  4989.7  843.47  4997.9  842.26
  4998.1  841.76  5001.9  842.26  5020.1  843.53  5050.5  842.76  5090.8  843.38
  5104.9  842.64  5252.9  844.25  5343.8  844.01  5596.4  848.03  5653.7  847.39
  5697.4  848.67  5707.6  847.12  5737.9  852.83  5748.0  853.15  5778.3  850.40
  5794.3  850.88  5799.4  849.74  5849.0  853.85  5859.1  853.43  5864.6  851.38
  5869.7  852.28  5879.3  851.21  5899.5  851.12  5926.2  851.97  6313.9  855.63
#Mann=3,-1,0
  4369.0    0.05       0  4997.9   0.033       0  5001.9    0.05       0
Bank Sta=4997.9,5001.9
Exp/Cntr=0.3,0.1

Type RM Length L Ch R = 1,13743,497,497,497
BEGIN DESCRIPTION:
Elizabeth Creek Tributary 24_1 22.0
END DESCRIPTION:
XS GIS Cut Line= 3
      2296678.98      7058760.04      2297179.00      7057910.00
      2297329.01      7057309.96
#Sta/Elev= 30
  4013.8  855.35  4187.9  851.60  4336.1  849.32  4496.2  845.48  4554.8  845.21
  4560.6  844.43  4605.5  844.48  4672.0  843.16  4810.6  842.31  4860.8  840.69
  4906.3  840.31  4942.0  840.17  4964.9  840.91  4976.8  840.30  5018.0  840.00
  5030.9  840.83  5113.5  840.14  5181.0  839.41  5181.2  838.91  5184.7  838.91
  5185.0  839.41  5192.8  839.68  5288.6  841.66  5435.5  846.68  5518.0  850.54
  5554.0  853.41  5577.2  854.39  5595.3  856.69  5600.4  856.65  5618.5  858.55
#Mann=5,-1,0
  4013.8    0.05       0  5113.5    0.12       0  5181.0   0.033       0
  5185.0    0.12       0  5192.8    0.05       0
Bank Sta=5181,5185
Exp/Cntr=0.3,0.1

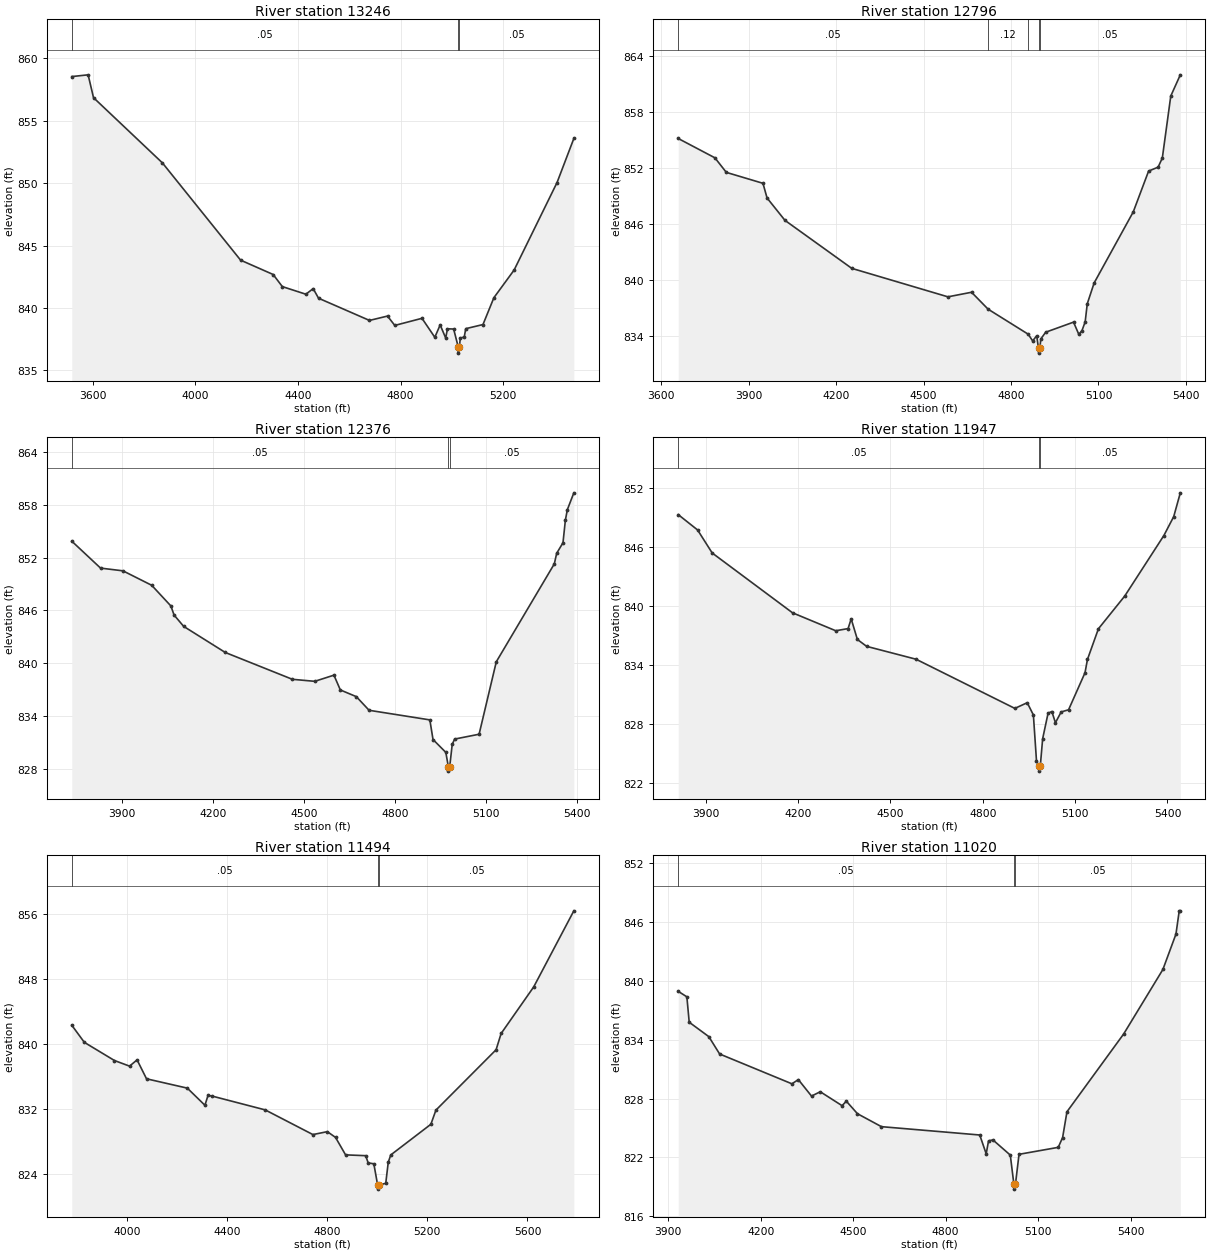
Type RM Length L Ch R = 1,13246,450,450,450
BEGIN DESCRIPTION:
Elizabeth Creek Tributary 24_1 21.0
END DESCRIPTION:
XS GIS Cut Line= 3
      2296579.03      7058909.97      2297679.00      7057910.00
      2298079.03      7057659.98
#Sta/Elev= 30
  3517.8  858.54  3581.6  858.68  3602.6  856.85  3871.5  851.62  4176.3  843.83
  4303.3  842.68  4339.1  841.71  4431.0  841.10  4459.4  841.55  4480.3  840.78
  4679.0  839.00  4749.3  839.35  4777.7  838.60  4883.8  839.17  4933.8  837.65
  4954.7  838.64  4976.3  837.59  4983.1  838.33  5007.3  838.31  5025.1  836.88
  5025.6  836.38  5029.6  836.88  5033.3  837.59  5048.6  837.67  5054.5  838.34
  5121.7  838.67  5164.2  840.82  5243.2  843.04  5410.6  850.05  5476.1  853.58
#Mann=3,-1,0
  3517.8    0.05       0  5025.1   0.033       0  5029.6    0.05       0
Bank Sta=5025.1,5029.6
Exp/Cntr=0.3,0.1

Type RM Length L Ch R = 1,12796,420,420,420
BEGIN DESCRIPTION:
Elizabeth Creek Tributary 24_1 20.0
END DESCRIPTION:
XS GIS Cut Line= 3
      2296728.96      7058860.02      2297929.00      7058260.00
      2298279.02      7058109.99
#Sta/Elev= 30
  3658.2  855.16  3784.0  853.09  3823.2  851.53  3948.9  850.36  3962.9  848.79
  4024.4  846.39  4253.6  841.25  4583.4  838.20  4664.5  838.69  4721.2  836.88
  4858.7  834.20  4874.1  833.48  4888.1  834.03  4894.2  832.67  4894.7  832.17
  4898.7  832.67  4902.1  833.69  4918.8  834.41  5014.4  835.49  5032.5  834.18
  5043.4  834.59  5054.3  835.52  5061.5  837.46  5085.1  839.69  5219.3  847.30
  5271.9  851.67  5304.5  852.09  5319.0  853.07  5348.0  859.71  5380.7  861.98
#Mann=5,-1,0
  3658.2    0.05       0  4721.2    0.12       0  4858.7    0.05       0
  4894.2    0.04       0  4898.7    0.05       0
Bank Sta=4894.2,4898.7
Exp/Cntr=0.3,0.1

Type RM Length L Ch R = 1,12376,429,429,429
BEGIN DESCRIPTION:
Elizabeth Creek Tributary 24_1 19.0
END DESCRIPTION:
XS GIS Cut Line= 3
      2296828.98      7058910.01      2298029.00      7058510.00
      2298328.96      7058260.03
#Sta/Elev= 30
  3734.5  853.87  3829.4  850.81  3903.2  850.50  3998.0  848.86  4061.3  846.51
  4071.8  845.48  4103.5  844.19  4240.5  841.23  4461.8  838.18  4535.6  837.95
  4598.9  838.65  4620.0  836.97  4672.7  836.21  4714.8  834.66  4915.1  833.57
  4925.6  831.34  4967.8  829.88  4976.1  828.25  4976.6  827.75  4980.6  828.25
  4988.9  830.79  4996.8  831.39  5077.5  831.94  5134.2  840.17  5325.5  851.29
  5333.3  852.49  5354.1  853.69  5362.0  856.26  5368.5  857.45  5389.9  859.36
#Mann=3,-1,0
  3734.5    0.05       0  4976.1   0.033       0  4980.6    0.05       0
Bank Sta=4976.1,4980.6
Exp/Cntr=0.3,0.1

Type RM Length L Ch R = 1,11947,453,453,453
BEGIN DESCRIPTION:
Elizabeth Creek Tributary 24_1 18.0
END DESCRIPTION:
XS GIS Cut Line= 3
      2297078.96      7058910.00      2298279.00      7058810.00
      2298429.00      7058410.00
#Sta/Elev= 30
  3810.3  849.30  3873.1  847.74  3920.7  845.39  4181.6  839.30  4322.1  837.47
  4362.2  837.69  4372.3  838.68  4392.4  836.58  4422.5  835.88  4583.0  834.57
  4904.1  829.56  4944.3  830.14  4964.3  828.89  4974.4  824.21  4982.1  823.67
  4982.6  823.17  4986.7  823.67  4994.4  826.47  5012.0  829.07  5024.3  829.24
  5035.9  828.10  5054.6  829.20  5078.6  829.42  5132.0  833.19  5140.0  834.55
  5175.6  837.67  5261.0  841.00  5388.3  847.17  5420.3  849.10  5441.7  851.52
#Mann=3,-1,0
  3810.3    0.05       0  4982.1    0.04       0  4986.7    0.05       0
Bank Sta=4982.1,4986.7
Exp/Cntr=0.3,0.1

Type RM Length L Ch R = 1,11494,474,474,474
BEGIN DESCRIPTION:
Elizabeth Creek Tributary 24_1 17.0
END DESCRIPTION:
XS GIS Cut Line= 3
      2297378.98      7059210.00      2298579.00      7059110.00
      2298629.00      7058310.04
#Sta/Elev= 30
  3779.6  842.28  3829.8  840.17  3950.2  837.93  4010.4  837.24  4040.5  838.01
  4078.2  835.68  4241.2  834.53  4311.5  832.42  4324.0  833.64  4341.6  833.54
  4552.3  831.85  4742.9  828.81  4800.6  829.17  4833.3  828.46  4873.4  826.31
  4953.7  826.21  4963.7  825.32  4986.3  825.21  5001.5  822.59  5002.0  822.09
  5006.1  822.59  5033.9  822.81  5043.9  825.40  5053.9  826.30  5214.2  830.08
  5234.3  831.82  5474.7  839.26  5494.8  841.26  5625.0  847.00  5785.3  856.37
#Mann=3,-1,0
  3779.6    0.05       0  5001.5   0.033       0  5006.1    0.05       0
Bank Sta=5001.5,5006.1
Exp/Cntr=0.3,0.1

Type RM Length L Ch R = 1,11020,469,469,469
BEGIN DESCRIPTION:
Elizabeth Creek Tributary 24_1 16.0
END DESCRIPTION:
XS GIS Cut Line= 3
      2298228.98      7060160.02      2298929.00      7059360.00
      2299328.98      7058960.02
#Sta/Elev= 30
  3932.6  838.94  3960.6  838.38  3968.2  835.79  4031.8  834.32  4066.9  832.55
  4301.4  829.51  4322.2  829.94  4364.9  828.26  4393.4  828.70  4464.1  827.28
  4477.9  827.74  4514.0  826.46  4591.8  825.14  4910.7  824.29  4931.6  822.37
  4939.2  823.69  4953.4  823.79  5009.8  822.24  5021.4  819.27  5022.0  818.77
  5026.5  819.27  5038.1  822.32  5165.3  823.03  5179.5  824.03  5193.6  826.66
  5377.5  834.59  5504.8  841.17  5547.2  844.78  5557.8  847.15  5561.3  847.15
#Mann=3,-1,0
  3932.6    0.05       0  5021.4   0.033       0  5026.5    0.05       0
Bank Sta=5021.4,5026.5
Exp/Cntr=0.3,0.1

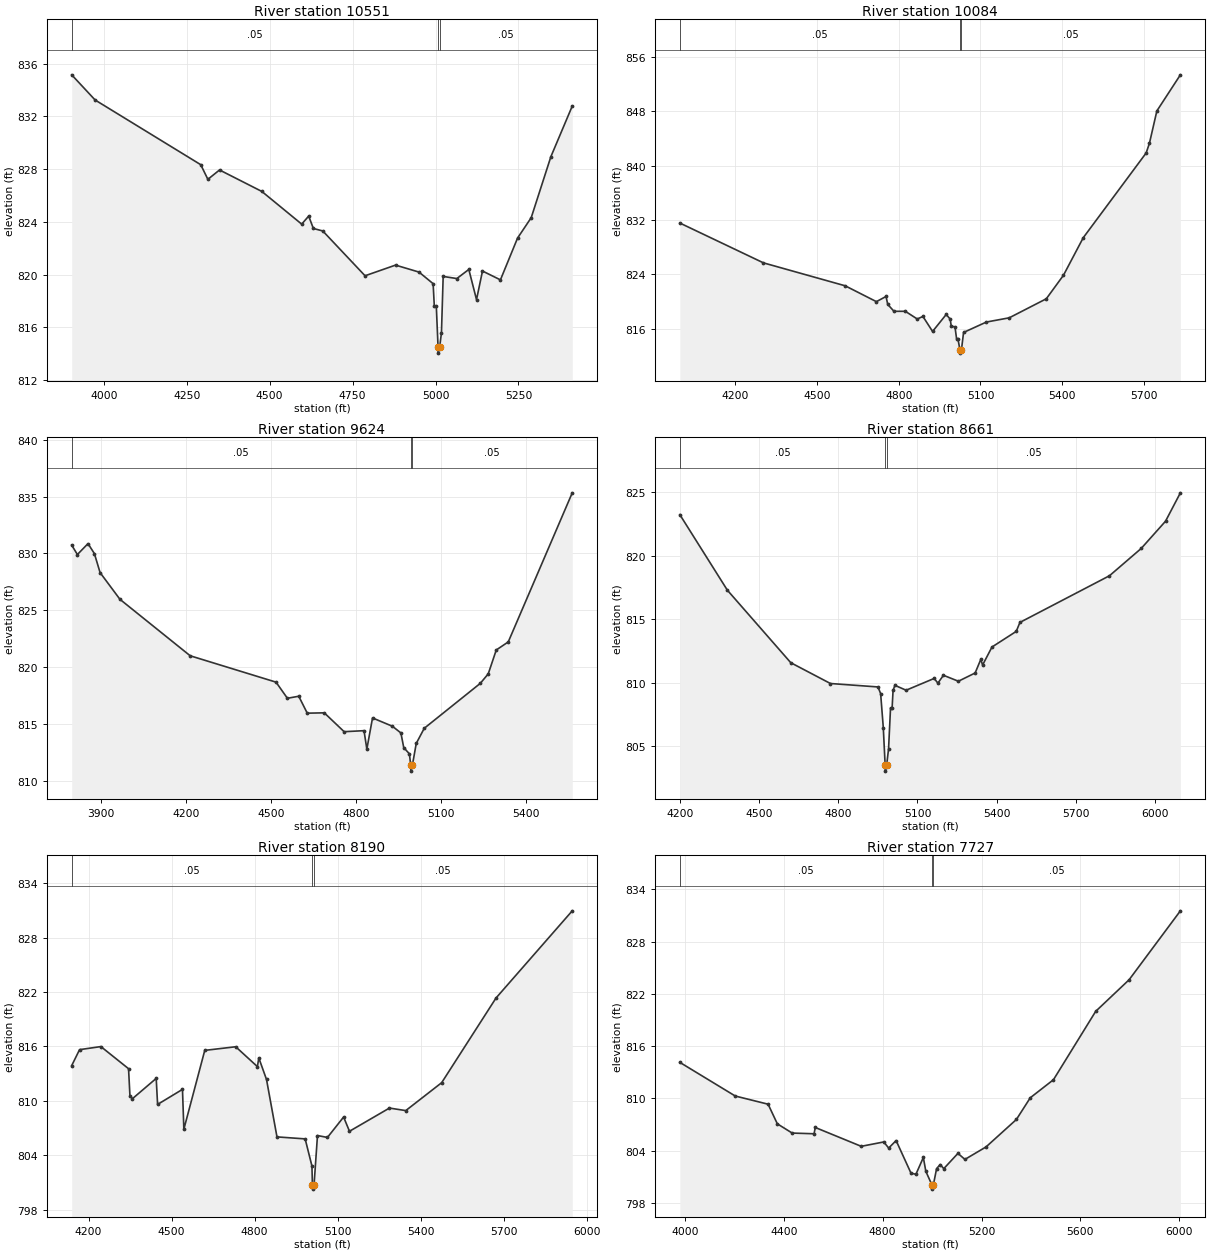
Type RM Length L Ch R = 1,10551,467,467,467
BEGIN DESCRIPTION:
Elizabeth Creek Tributary 24_1 15.0
END DESCRIPTION:
XS GIS Cut Line= 3
      2298479.01      7060359.99      2299279.00      7059610.00
      2299379.00      7059209.98
#Sta/Elev= 30
  3903.2  835.16  3973.8  833.25  4292.2  828.34  4313.7  827.23  4348.9  827.94
  4476.4  826.31  4596.5  823.83  4617.6  824.44  4631.7  823.50  4660.1  823.31
  4787.5  819.91  4879.4  820.72  4950.2  820.19  4992.7  819.31  4996.3  817.60
  5002.3  817.60  5007.5  814.54  5008.2  814.04  5012.6  814.54  5017.8  815.58
  5023.0  819.86  5064.2  819.70  5100.3  820.39  5123.5  818.10  5141.5  820.27
  5195.6  819.60  5247.2  822.77  5288.4  824.32  5347.7  828.95  5412.1  832.79
#Mann=3,-1,0
  3903.2    0.05       0  5007.5   0.033       0  5012.6    0.05       0
Bank Sta=5007.5,5012.6
Exp/Cntr=0.3,0.1

Type RM Length L Ch R = 1,10084,460,460,460
BEGIN DESCRIPTION:
Elizabeth Creek Tributary 24_1 14.0
END DESCRIPTION:
XS GIS Cut Line= 3
      2299079.03      7060509.96      2299679.00      7059710.00
      2299429.00      7058910.00
#Sta/Elev= 30
  3996.0  831.55  4303.2  825.69  4603.2  822.32  4717.8  819.99  4753.2  820.75
  4759.5  819.58  4782.4  818.57  4824.1  818.57  4867.8  817.44  4888.7  817.81
  4924.1  815.61  4974.1  818.10  4988.7  817.43  4992.8  816.36  5006.4  816.29
  5012.2  814.54  5017.4  814.49  5024.5  812.92  5025.4  812.42  5030.2  812.92
  5037.9  815.46  5121.7  816.99  5205.5  817.61  5341.7  820.41  5404.6  823.86
  5477.4  829.39  5708.4  841.85  5720.4  843.27  5747.7  848.03  5834.1  853.34
#Mann=3,-1,0
  3996.0    0.05       0  5024.5   0.033       0  5030.2    0.05       0
Bank Sta=5024.5,5030.2
Exp/Cntr=0.3,0.1

Type RM Length L Ch R = 1,9624,963,963,963
BEGIN DESCRIPTION:
Elizabeth Creek Tributary 24_1 13.0
END DESCRIPTION:
XS GIS Cut Line= 3
      2299929.00      7060660.02      2300029.00      7059460.00
      2299628.98      7059059.98
#Sta/Elev= 30
  3795.2  830.73  3815.3  829.90  3852.9  830.86  3875.5  829.98  3895.6  828.31
  3965.8  825.96  4214.2  820.99  4517.7  818.67  4557.9  817.25  4598.0  817.43
  4628.1  815.94  4688.3  815.97  4758.5  814.31  4828.8  814.40  4838.8  812.78
  4858.9  815.52  4929.1  814.79  4959.2  814.20  4969.3  812.91  4989.3  812.36
  4994.0  811.34  4994.9  810.84  4999.7  811.34  5013.5  813.28  5041.8  814.61
  5239.8  818.56  5268.1  819.40  5296.4  821.50  5338.8  822.21  5565.1  835.33
#Mann=3,-1,0
  3795.2    0.05       0  4994.0   0.033       0  4999.7    0.05       0
Bank Sta=4994,4999.7
Exp/Cntr=0.3,0.1

Type RM Length L Ch R = 1,8661,471,471,471
BEGIN DESCRIPTION:
Elizabeth Creek Tributary 24_1 12.0
END DESCRIPTION:
XS GIS Cut Line= 3
      2300779.00      7060459.97      2300829.00      7059660.00
      2300079.01      7058860.02
#Sta/Elev= 30
  4198.9  823.24  4379.2  817.28  4619.7  811.56  4770.0  809.92  4950.3  809.65
  4960.4  809.12  4970.4  806.45  4977.4  803.51  4978.4  803.01  4983.3  803.51
  4990.4  804.76  4997.9  808.00  5003.9  808.00  5007.5  809.37  5014.4  809.78
  5056.9  809.39  5163.3  810.32  5177.5  809.95  5198.5  810.57  5255.2  810.10
  5318.7  810.75  5340.1  811.82  5347.0  811.38  5382.6  812.80  5474.5  814.03
  5488.6  814.74  5828.1  818.42  5948.3  820.57  6040.6  822.72  6097.0  824.96
#Mann=3,-1,0
  4198.9    0.05       0  4977.4    0.04       0  4983.3    0.05       0
Bank Sta=4977.4,4983.3
Exp/Cntr=0.3,0.1

Type RM Length L Ch R = 1,8190,463,463,463
BEGIN DESCRIPTION:
Elizabeth Creek Tributary 24_1 11.0
END DESCRIPTION:
XS GIS Cut Line= 5
      2301474.79      7060008.22      2301423.90      7059505.33
      2301244.31      7059526.28      2301179.00      7059360.00
      2300679.01      7058560.01
#Sta/Elev= 30
  4139.0  813.89  4167.4  815.65  4244.4  815.99  4344.4  813.55  4349.4  810.58
  4358.3  810.24  4444.3  812.48  4449.3  809.61  4539.2  811.27  4544.2  806.88
  4619.7  815.57  4731.5  815.97  4809.9  813.78  4814.9  814.74  4842.8  812.36
  4880.6  806.03  4982.4  805.81  5006.9  802.82  5008.6  800.77  5009.6  800.27
  5014.6  800.77  5026.9  806.18  5062.9  805.97  5121.3  808.22  5142.5  806.65
  5286.9  809.21  5345.9  808.93  5475.6  812.01  5672.0  821.35  5947.3  830.96
#Mann=3,-1,0
  4139.0    0.05       0  5008.6    0.04       0  5014.6    0.05       0
Bank Sta=5008.6,5014.6
Exp/Cntr=0.3,0.1

Type RM Length L Ch R = 1,7727,450,450,450
BEGIN DESCRIPTION:
Elizabeth Creek Tributary 24_1 10.0
END DESCRIPTION:
XS GIS Cut Line= 3
      2301582.54      7060133.94      2301529.00      7059110.00
      2300729.03      7058510.02
#Sta/Elev= 30
  3979.3  814.14  4203.5  810.28  4336.5  809.34  4373.8  807.09  4433.9  806.03
  4522.4  805.95  4527.4  806.67  4713.3  804.51  4804.4  805.01  4824.4  804.31
  4854.4  805.17  4914.5  801.44  4934.5  801.30  4964.6  803.23  4974.6  801.65
  4999.0  800.10  5000.1  799.60  5005.2  800.10  5018.2  801.95  5032.8  802.42
  5047.3  801.95  5104.6  803.70  5132.8  803.01  5218.2  804.44  5341.1  807.59
  5397.3  810.08  5491.1  812.15  5661.9  819.99  5797.3  823.62  6004.6  831.52
#Mann=3,-1,0
  3979.3    0.05       0  4999.0   0.033       0  5005.2    0.05       0
Bank Sta=4999,5005.2
Exp/Cntr=0.3,0.1

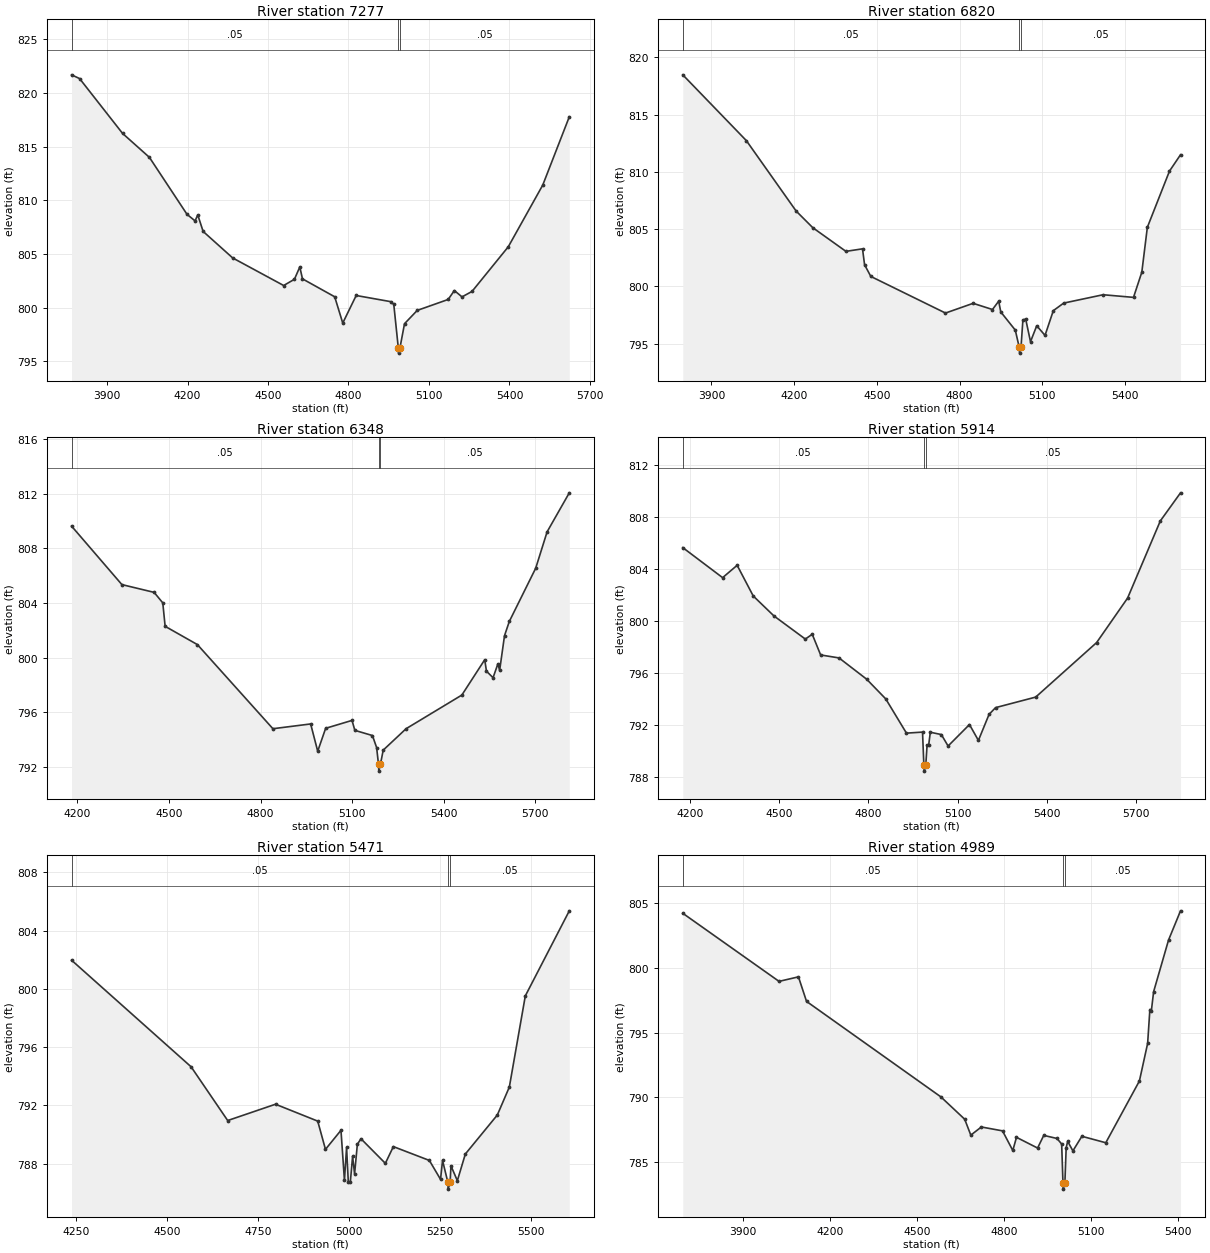
Type RM Length L Ch R = 1,7277,457,457,457
BEGIN DESCRIPTION:
Elizabeth Creek Tributary 24_1 9.0
END DESCRIPTION:
XS GIS Cut Line= 3
      2301929.00      7060110.01      2301879.00      7058860.00
      2301628.98      7058309.96
#Sta/Elev= 30
  3767.8  821.70  3797.8  821.35  3958.0  816.24  4058.0  814.01  4198.2  808.70
  4228.2  808.09  4238.2  808.65  4258.2  807.11  4368.3  804.64  4558.4  802.07
  4598.5  802.65  4618.5  803.80  4628.5  802.69  4748.6  801.02  4778.6  798.57
  4828.7  801.14  4958.8  800.56  4968.8  800.31  4985.6  796.27  4986.7  795.77
  4991.9  796.27  5008.8  798.51  5056.2  799.75  5171.5  800.77  5194.6  801.60
  5223.1  801.01  5260.5  801.52  5395.6  805.68  5524.1  811.43  5623.0  817.79
#Mann=3,-1,0
  3767.8    0.05       0  4985.6   0.033       0  4991.9    0.05       0
Bank Sta=4985.6,4991.9
Exp/Cntr=0.3,0.1

Type RM Length L Ch R = 1,6820,472,472,472
BEGIN DESCRIPTION:
Elizabeth Creek Tributary 24_1 8.0
END DESCRIPTION:
XS GIS Cut Line= 3
      2302179.00      7059909.96      2302279.00      7058710.00
      2302229.00      7058110.00
#Sta/Elev= 30
  3795.8  818.48  4026.6  812.73  4207.2  806.58  4267.4  805.13  4387.8  803.06
  4448.0  803.28  4455.5  801.89  4478.1  800.87  4749.1  797.67  4849.4  798.52
  4919.6  797.98  4942.2  798.71  4949.7  797.77  5002.4  796.18  5016.8  794.67
  5017.9  794.17  5023.1  794.67  5030.0  797.06  5040.1  797.15  5057.6  795.17
  5080.2  796.56  5110.3  795.72  5140.4  797.88  5178.0  798.54  5321.0  799.27
  5431.4  799.04  5461.5  801.24  5481.6  805.16  5561.9  810.07  5602.0  811.50
#Mann=3,-1,0
  3795.8    0.05       0  5016.8   0.033       0  5023.1    0.05       0
Bank Sta=5016.8,5023.1
Exp/Cntr=0.3,0.1

Type RM Length L Ch R = 1,6348,434,434,434
BEGIN DESCRIPTION:
Elizabeth Creek Tributary 24_1 7.0
END DESCRIPTION:
XS GIS Cut Line= 3
      2302479.01      7059559.97      2302679.00      7058760.00
      2302279.01      7058060.01
#Sta/Elev= 30
  4180.9  809.64  4345.8  805.35  4451.4  804.78  4479.8  804.01  4487.5  802.29
  4593.2  800.95  4840.6  794.78  4964.3  795.13  4987.4  793.13  5013.4  794.81
  5099.8  795.39  5109.1  794.66  5166.7  794.28  5180.4  793.40  5186.6  792.17
  5187.7  791.67  5192.9  792.17  5202.0  793.21  5276.9  794.78  5459.7  797.25
  5534.6  799.84  5540.3  799.00  5561.9  798.52  5577.8  799.54  5583.5  799.06
  5599.4  801.60  5615.2  802.65  5701.6  806.55  5739.0  809.22  5811.7  812.08
#Mann=3,-1,0
  4180.9    0.05       0  5186.6   0.033       0  5192.9    0.05       0
Bank Sta=5186.6,5192.9
Exp/Cntr=0.3,0.1

Type RM Length L Ch R = 1,5914,443,443,443
BEGIN DESCRIPTION:
Elizabeth Creek Tributary 24_1 6.0
END DESCRIPTION:
XS GIS Cut Line= 3
      2302879.00      7059459.98      2303079.00      7058660.00
      2302679.00      7057910.00
#Sta/Elev= 30
  4175.4  805.62  4309.4  803.31  4358.3  804.26  4412.5  801.90  4482.0  800.37
  4587.7  798.59  4610.9  798.96  4639.2  797.37  4701.1  797.14  4793.8  795.51
  4858.3  793.99  4927.9  791.36  4982.0  791.44  4986.4  788.94  4987.4  788.44
  4993.0  788.94  4997.4  790.46  5002.8  790.46  5008.2  791.43  5045.3  791.25
  5068.0  790.37  5139.9  792.02  5170.0  790.80  5205.8  792.80  5227.7  793.32
  5362.7  794.13  5567.7  798.32  5671.9  801.74  5782.0  807.67  5850.0  809.83
#Mann=3,-1,0
  4175.4    0.05       0  4986.4   0.033       0  4993.0    0.05       0
Bank Sta=4986.4,4993
Exp/Cntr=0.3,0.1

Type RM Length L Ch R = 1,5471,482,482,482
BEGIN DESCRIPTION:
Elizabeth Creek Tributary 24_1 5.0
END DESCRIPTION:
XS GIS Cut Line= 3
      2303079.02      7059259.96      2303479.00      7058610.00
      2303728.99      7058060.03
#Sta/Elev= 30
  4237.0  801.97  4565.4  794.65  4665.9  790.96  4797.3  792.08  4913.2  790.92
  4934.5  788.98  4977.1  790.29  4986.6  786.86  4992.5  789.11  4997.2  786.76
  5002.9  786.76  5009.0  788.50  5014.5  787.30  5022.1  789.33  5032.0  789.71
  5099.0  788.02  5121.0  789.17  5219.9  788.22  5250.6  786.92  5256.1  788.22
  5270.4  786.75  5271.4  786.25  5277.0  786.75  5279.2  787.85  5296.8  786.83
  5318.7  788.66  5406.6  791.34  5439.6  793.26  5483.5  799.52  5604.3  805.36
#Mann=3,-1,0
  4237.0    0.05       0  5270.4    0.04       0  5277.0    0.05       0
Bank Sta=5270.4,5277
Exp/Cntr=0.3,0.1

Type RM Length L Ch R = 1,4989,925,925,925
BEGIN DESCRIPTION:
Elizabeth Creek Tributary 24_1 4.0
END DESCRIPTION:
XS GIS Cut Line= 3
      2303228.99      7059610.02      2303929.00      7058510.00
      2303828.99      7058109.97
#Sta/Elev= 30
  3691.7  804.24  4023.6  798.97  4090.5  799.32  4118.4  797.42  4581.6  790.03
  4663.7  788.30  4684.8  787.07  4721.2  787.70  4794.1  787.40  4829.6  785.88
  4842.3  786.90  4915.1  786.07  4936.3  787.05  4982.0  786.81  4998.1  786.38
  5002.5  783.39  5003.6  782.89  5009.2  783.39  5013.6  786.09  5018.8  786.59
  5036.8  785.85  5067.7  786.98  5150.2  786.48  5266.1  791.26  5294.5  794.17
  5302.2  796.79  5307.4  796.70  5315.1  798.17  5366.6  802.17  5407.9  804.43
#Mann=3,-1,0
  3691.7    0.05       0  5002.5   0.033       0  5009.2    0.05       0
Bank Sta=5002.5,5009.2
Exp/Cntr=0.3,0.1

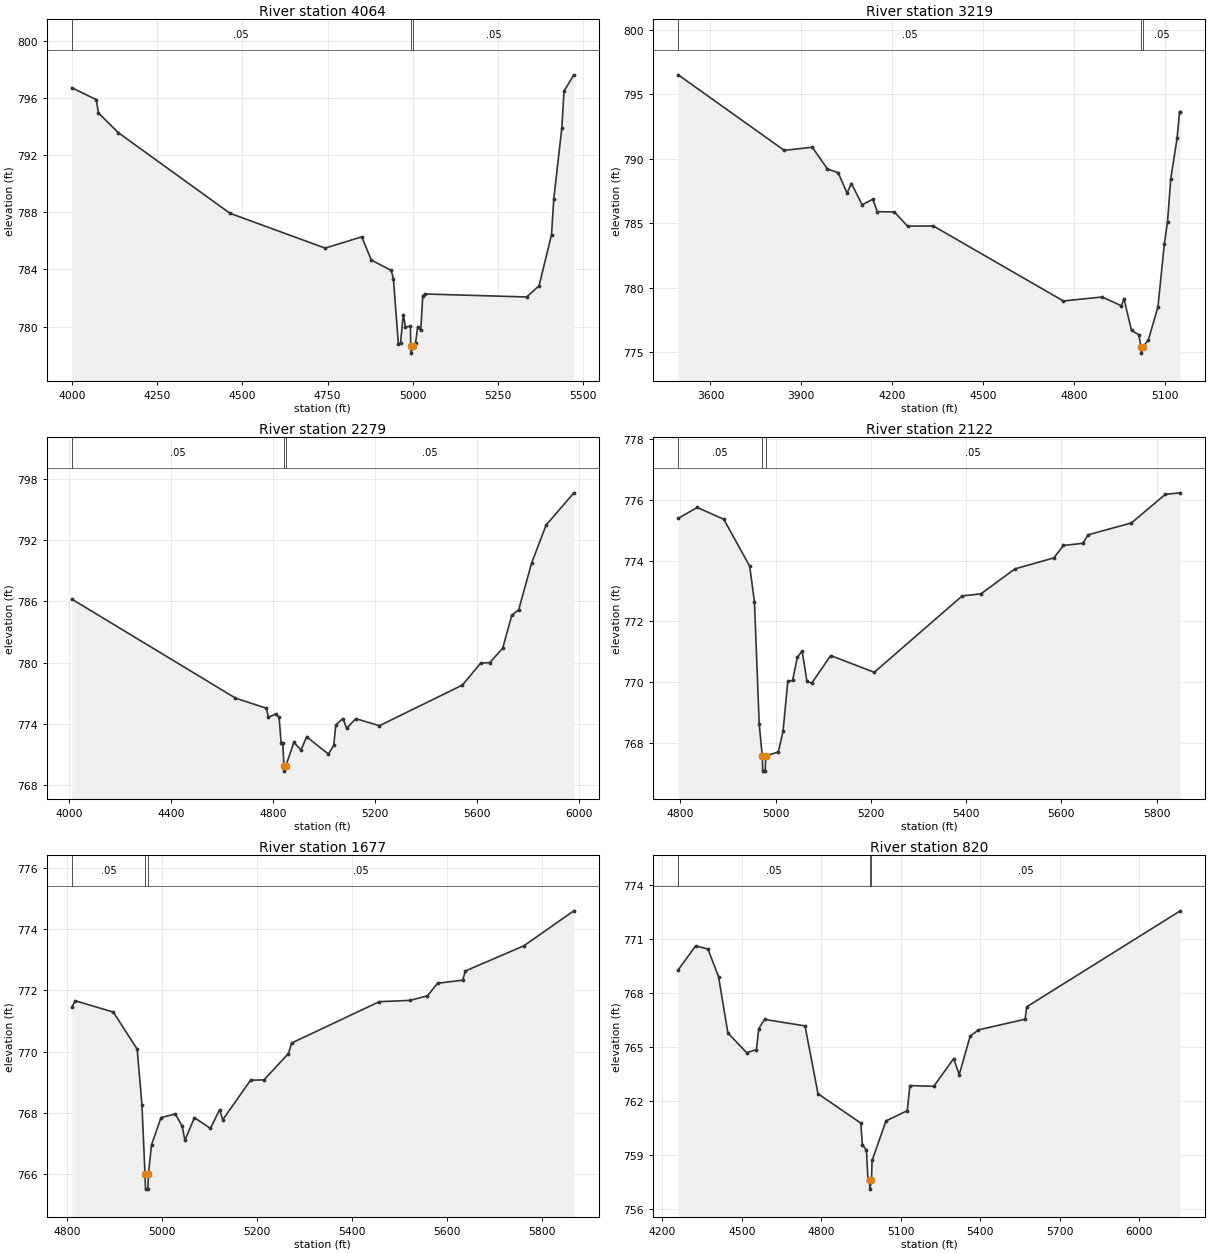
Type RM Length L Ch R = 1,4064,845,845,845
BEGIN DESCRIPTION:
Elizabeth Creek Tributary 24_1 3.0
END DESCRIPTION:
XS GIS Cut Line= 3
      2303728.96      7059310.03      2304529.00      7058710.00
      2304778.98      7058310.04
#Sta/Elev= 30
  4000.2  796.72  4072.1  795.88  4078.4  794.95  4136.7  793.57  4463.8  787.93
  4743.0  785.49  4850.2  786.28  4878.4  784.65  4936.7  783.93  4943.0  783.35
  4957.5  778.80  4963.8  778.84  4972.1  780.84  4978.4  779.97  4993.0  780.03
  4993.7  778.64  4994.8  778.14  5000.6  778.64  5007.9  778.84  5013.8  779.95
  5023.2  779.74  5029.1  782.16  5035.6  782.28  5333.4  782.07  5369.9  782.85
  5406.5  786.43  5413.0  788.93  5436.6  793.88  5443.1  796.48  5471.9  797.62
#Mann=3,-1,0
  4000.2    0.05       0  4993.7   0.033       0  5000.6    0.05       0
Bank Sta=4993.7,5000.6
Exp/Cntr=0.3,0.1

Type RM Length L Ch R = 1,3219,940,940,940
BEGIN DESCRIPTION:
Elizabeth Creek Tributary 24_1 2.0
END DESCRIPTION:
XS GIS Cut Line= 3
      2303879.01      7059560.00      2305079.00      7058660.00
      2305029.00      7058510.01
#Sta/Elev= 30
  3493.7  796.50  3843.7  790.65  3936.4  790.89  3986.4  789.21  4021.8  788.92
  4051.0  787.35  4065.6  788.08  4101.0  786.44  4136.4  786.86  4151.0  785.90
  4207.2  785.88  4251.0  784.78  4336.4  784.79  4765.6  778.98  4893.7  779.29
  4957.2  778.61  4965.6  779.16  4990.6  776.70  5014.8  776.37  5021.9  775.44
  5023.0  774.94  5028.8  775.44  5046.4  775.97  5078.0  778.53  5099.1  783.41
  5109.6  785.12  5120.2  788.45  5141.3  791.61  5149.2  793.62  5151.8  793.62
#Mann=3,-1,0
  3493.7    0.05       0  5021.9    0.04       0  5028.8    0.05       0
Bank Sta=5021.9,5028.8
Exp/Cntr=0.3,0.1

Type RM Length L Ch R = 1,2279,157,157,157
BEGIN DESCRIPTION:
Elizabeth Creek Tributary 24_1 1.0
END DESCRIPTION:
XS GIS Cut Line= 3
      2305028.98      7059910.03      2305629.00      7059110.00
      2305078.98      7058309.97
#Sta/Elev= 30
  4009.3  786.21  4652.0  776.53  4772.9  775.54  4781.2  774.67  4809.3  774.96
  4822.9  774.67  4831.2  772.16  4837.5  772.17  4842.2  769.89  4843.3  769.39
  4849.4  769.89  4881.2  772.21  4909.3  771.45  4931.2  772.75  5016.8  771.06
  5037.7  771.90  5045.7  773.90  5073.6  774.53  5088.5  773.57  5124.3  774.52
  5217.0  773.83  5542.5  777.80  5614.2  779.94  5650.0  780.00  5700.8  781.40
  5736.6  784.63  5763.7  785.17  5814.4  789.73  5871.2  793.44  5980.2  796.60
#Mann=3,-1,0
  4009.3    0.05       0  4842.2   0.033       0  4849.4    0.05       0
Bank Sta=4842.2,4849.4
Exp/Cntr=0.3,0.1

Type RM Length L Ch R = 1,2122,445,445,445
BEGIN DESCRIPTION:
1064
END DESCRIPTION:
XS GIS Cut Line= 3
      2305770.23      7059309.86      2305783.24      7058977.87
      2305646.47      7058269.19
#Sta/Elev= 30
  4795.8  775.39  4835.7  775.75  4891.4  775.36  4945.8  773.82  4955.8  772.65
  4965.8  768.62  4972.2  767.58  4973.3  767.08  4978.3  767.08  4979.4  767.58
  5005.8  767.71  5015.8  768.39  5025.8  770.03  5035.8  770.06  5045.8  770.82
  5055.9  771.03  5065.9  770.04  5075.9  769.97  5115.9  770.88  5207.3  770.33
  5391.8  772.84  5431.4  772.91  5502.7  773.73  5584.2  774.09  5604.5  774.50
  5645.3  774.57  5656.2  774.85  5747.1  775.24  5818.4  776.18  5849.8  776.23
#Mann=3,-1,0
  4795.8    0.05       0  4972.2    0.04       0  4979.4    0.05       0
Bank Sta=4972.2,4979.4
Exp/Cntr=0.3,0.1

Type RM Length L Ch R = 1,1677,857,857,857
BEGIN DESCRIPTION:
1063
END DESCRIPTION:
XS GIS Cut Line= 3
      2306145.23      7059117.12      2306168.68      7058828.67
      2305777.02      7058169.68
#Sta/Elev= 30
  4810.6  771.44  4817.7  771.66  4898.0  771.29  4948.2  770.08  4958.2  768.27
  4964.6  766.02  4965.7  765.52  4970.7  765.52  4971.9  766.02  4978.3  766.96
  4998.3  767.85  5028.4  767.97  5042.9  767.57  5048.5  767.11  5068.6  767.85
  5102.1  767.50  5121.7  768.11  5128.1  767.78  5186.6  769.07  5214.8  769.08
  5266.4  769.94  5272.9  770.28  5457.4  771.63  5521.6  771.67  5558.6  771.82
  5580.1  772.23  5632.7  772.33  5638.5  772.63  5761.5  773.45  5866.6  774.59
#Mann=3,-1,0
  4810.6    0.05       0  4964.6    0.04       0  4971.9    0.05       0
Bank Sta=4964.6,4971.9
Exp/Cntr=0.3,0.1

Type RM Length L Ch R = 1,820,701,701,701
BEGIN DESCRIPTION:
1061
END DESCRIPTION:
XS GIS Cut Line= 5
      2306355.17      7059083.60      2306404.92      7058897.05
      2306877.40      7058604.86      2306864.96      7058424.57
      2305933.23      7058176.11
#Sta/Elev= 30
  4260.5  769.28  4326.3  770.61  4372.6  770.43  4412.7  768.89  4447.7  765.78
  4518.8  764.68  4555.4  764.86  4564.2  766.02  4586.2  766.53  4738.7  766.17
  4787.6  762.41  4949.0  760.78  4954.9  759.59  4970.3  759.28  4976.2  757.65
  4982.0  757.62  4983.1  757.12  4989.3  757.62  4991.6  758.71  5044.0  760.90
  5124.2  761.47  5134.2  762.86  5224.4  762.82  5299.4  764.36  5320.2  763.47
  5361.6  765.60  5392.6  765.95  5568.6  766.54  5575.0  767.23  6154.1  772.55
#Mann=3,-1,0
  4260.5    0.05       0  4982.0    0.04       0  4989.3    0.05       0
Bank Sta=4982,4989.3
Exp/Cntr=0.3,0.1

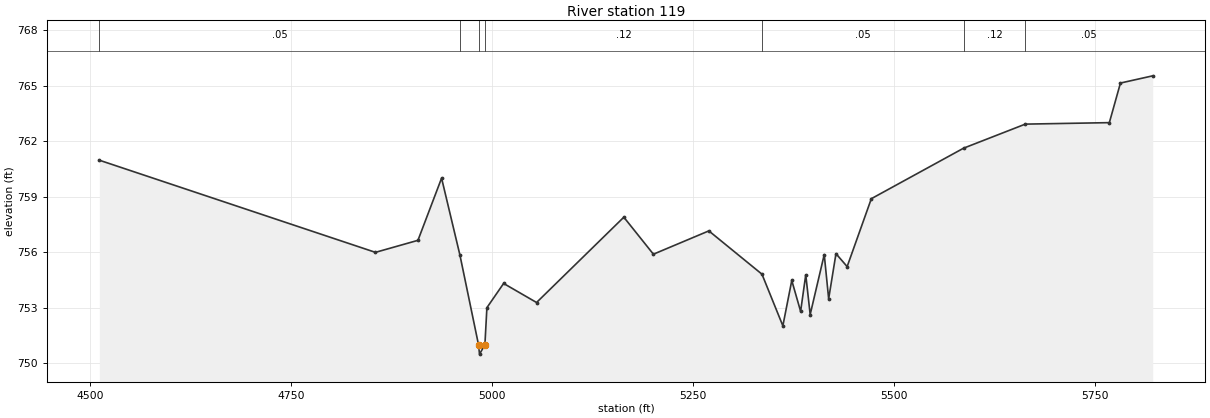
Type RM Length L Ch R = 1,119,0,0,0
BEGIN DESCRIPTION:
1666
END DESCRIPTION:
XS GIS Cut Line= 5
      2307321.08      7059117.77      2307524.97      7058798.35
      2307427.54      7058664.68      2306972.15      7058456.24
      2306729.70      7058347.48
#Sta/Elev= 30
  4511.2  760.98  4854.8  756.00  4907.7  756.65  4937.1  760.01  4959.9  755.86
  4983.1  751.00  4984.3  750.50  4991.0  751.00  4993.5  753.01  5014.3  754.32
  5055.3  753.29  5163.9  757.90  5200.7  755.90  5269.7  757.16  5335.8  754.82
  5361.8  752.03  5372.9  754.48  5383.9  752.81  5390.3  754.79  5395.8  752.64
  5413.3  755.88  5418.8  753.49  5427.9  755.93  5441.8  755.23  5471.9  758.90
  5586.7  761.63  5663.5  762.93  5768.1  763.01  5781.9  765.15  5822.1  765.54
#Mann=7,-1,0
  4511.2    0.05       0  4959.9    0.12       0  4983.1    0.07       0
  4991.0    0.12       0  5335.8    0.05       0  5586.7    0.12       0
  5663.5    0.05       0
Bank Sta=4983.1,4991
Exp/Cntr=0.3,0.1

Chan Stop Cuts=-1