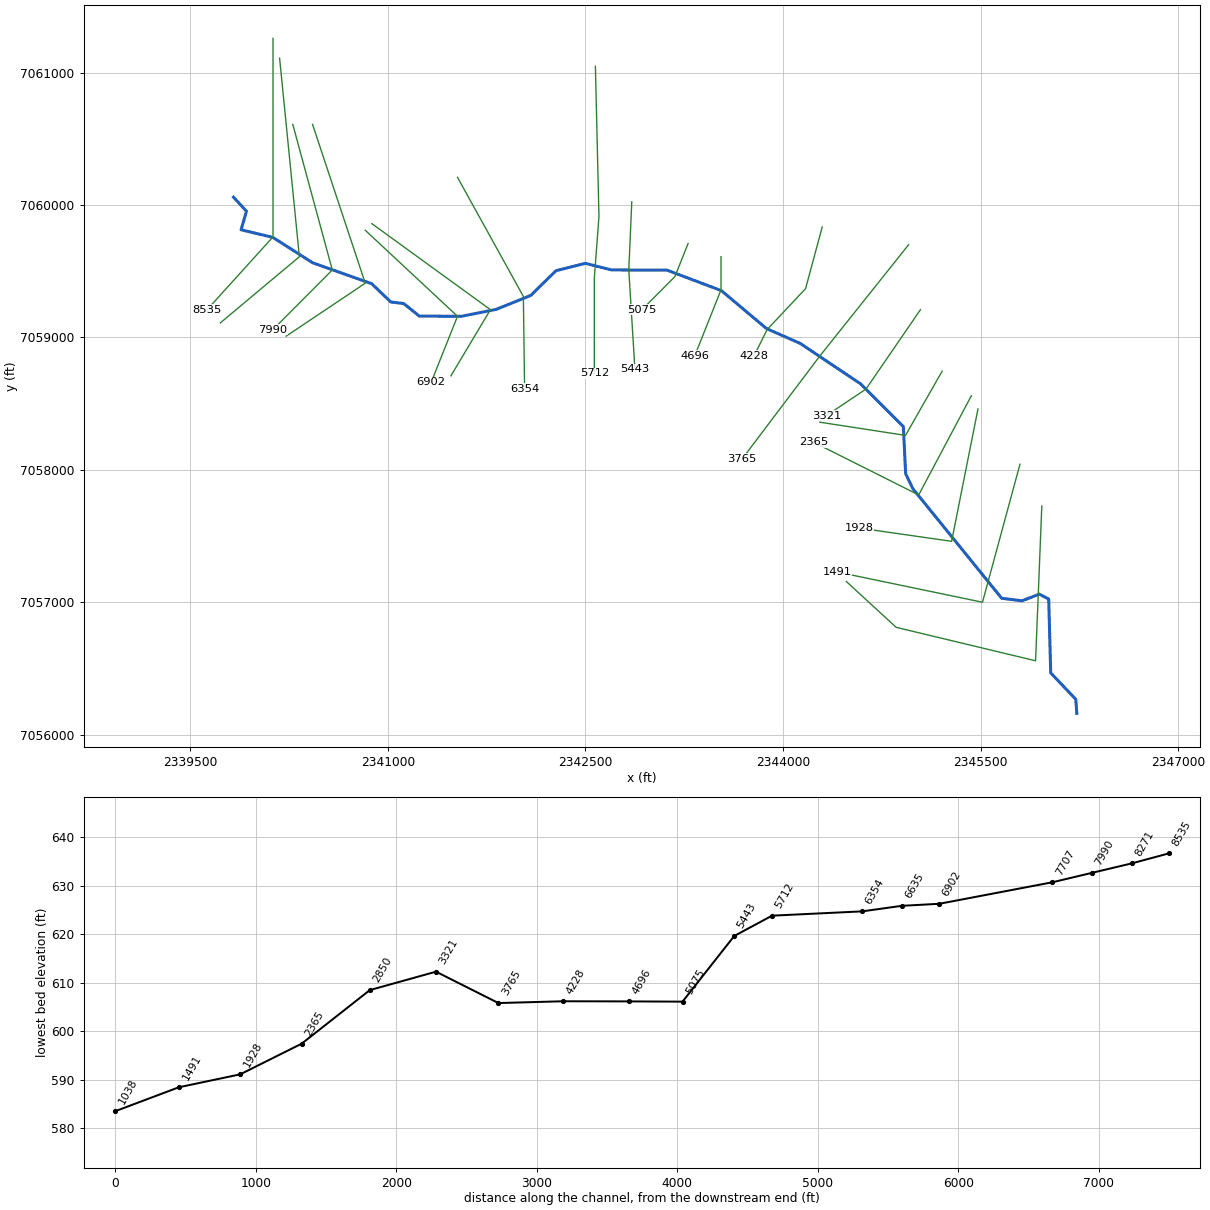
--- Elizabeth Cr Tr 4.prj (project) ---

Proj Title=Elizabeth Cr Tr 4 Base Level Engineering
Current Plan=p01
Default Exp/Contr=0.3,0.1
English Units
Geom File=g01
Flow File=f01
Plan File=p01
BEGIN DESCRIPTION:
Elizabeth Cr Tr 4
END DESCRIPTION:

--- Elizabeth Cr Tr 4.p01 (plan) ---

Plan Title=Multiple Run
Short Identifier=Multiple
Geom File=g01
Flow File=f01
Subcritical Flow
K Sum by GR= 0
Std Step Tol= 0.01
Critical Tol= 0.01
Num of Std Step Trials= 20
Max Error Tol= 0.3
Flow Tol Ratio= 0.001
Split Flow NTrial= 30
Split Flow Tol= 0.02
Split Flow Ratio= 0.02
Log Output Level= 0
Friction Slope Method= 1
Unsteady Friction Slope Method= 2
Unsteady Bridges Friction Slope Method= 1
Parabolic Critical Depth
Global Vel Dist=  1 , 1 , 1
Global Log Level= 0
CheckData=True
Encroach Param= -1, 0, 0, 0
BEGIN DESCRIPTION:
Multiple Run
END DESCRIPTION:

--- Elizabeth Cr Tr 4.f01 (steady flow) ---

Flow Title=Multiple
Number of Profiles=7
Profile Names=10-year,25-year,50-year,1pct_min,100-year,1pct_plu,500-year
River Rch & RM= Elizabeth Cr Tr ,Reach-1,8535
     330     434     517     306     611    1220     853
River Rch & RM= Elizabeth Cr Tr ,Reach-1,5712
     586     798     972     588    1170    2340    1710
River Rch & RM= Elizabeth Cr Tr ,Reach-1,4228
     731    1010    1240     754    1500    3000    2230
Boundary for River Rch & Prof#=Elizabeth Cr Tr ,Reach-1,1
Up Type=0
Dn Type=3
Dn Slope=0.005
Boundary for River Rch & Prof#=Elizabeth Cr Tr ,Reach-1,2
Up Type=0
Dn Type=3
Dn Slope=0.005
Boundary for River Rch & Prof#=Elizabeth Cr Tr ,Reach-1,3
Up Type=0
Dn Type=3
Dn Slope=0.005
Boundary for River Rch & Prof#=Elizabeth Cr Tr ,Reach-1,4
Up Type=0
Dn Type=3
Dn Slope=0.005
Boundary for River Rch & Prof#=Elizabeth Cr Tr ,Reach-1,5
Up Type=0
Dn Type=3
Dn Slope=0.005
Boundary for River Rch & Prof#=Elizabeth Cr Tr ,Reach-1,6
Up Type=0
Dn Type=3
Dn Slope=0.005
Boundary for River Rch & Prof#=Elizabeth Cr Tr ,Reach-1,7
Up Type=0
Dn Type=3
Dn Slope=0.005

--- Elizabeth Cr Tr 4.g01 (geometry) ---

Geom Title=Existing Conditions

River Reach=Elizabeth Cr Tr ,Reach-1
Reach XY= 30
      2339829.00      7060060.00      2339927.44      7059953.97
      2339886.72      7059813.50      2340127.47      7059756.25
      2340430.58      7059563.83      2340877.50      7059406.39
      2341022.87      7059267.88      2341120.52      7059256.50
      2341239.48      7059161.19      2341558.97      7059160.07
      2341823.07      7059212.24      2342085.17      7059317.86
      2342276.55      7059504.53      2342499.04      7059559.95
      2342699.03      7059510.07      2343118.50      7059508.78
      2343531.29      7059354.15      2343872.94      7059068.14
      2344131.29      7058954.15      2344588.68      7058649.22
      2344912.57      7058326.76      2344930.20      7057970.50
      2344984.83      7057857.70      2345658.84      7057029.60
      2345813.78      7057010.51      2345944.15      7057060.80
      2346015.80      7057023.75      2346031.06      7056465.85
      2346221.26      7056266.22      2346229.00      7056160.00

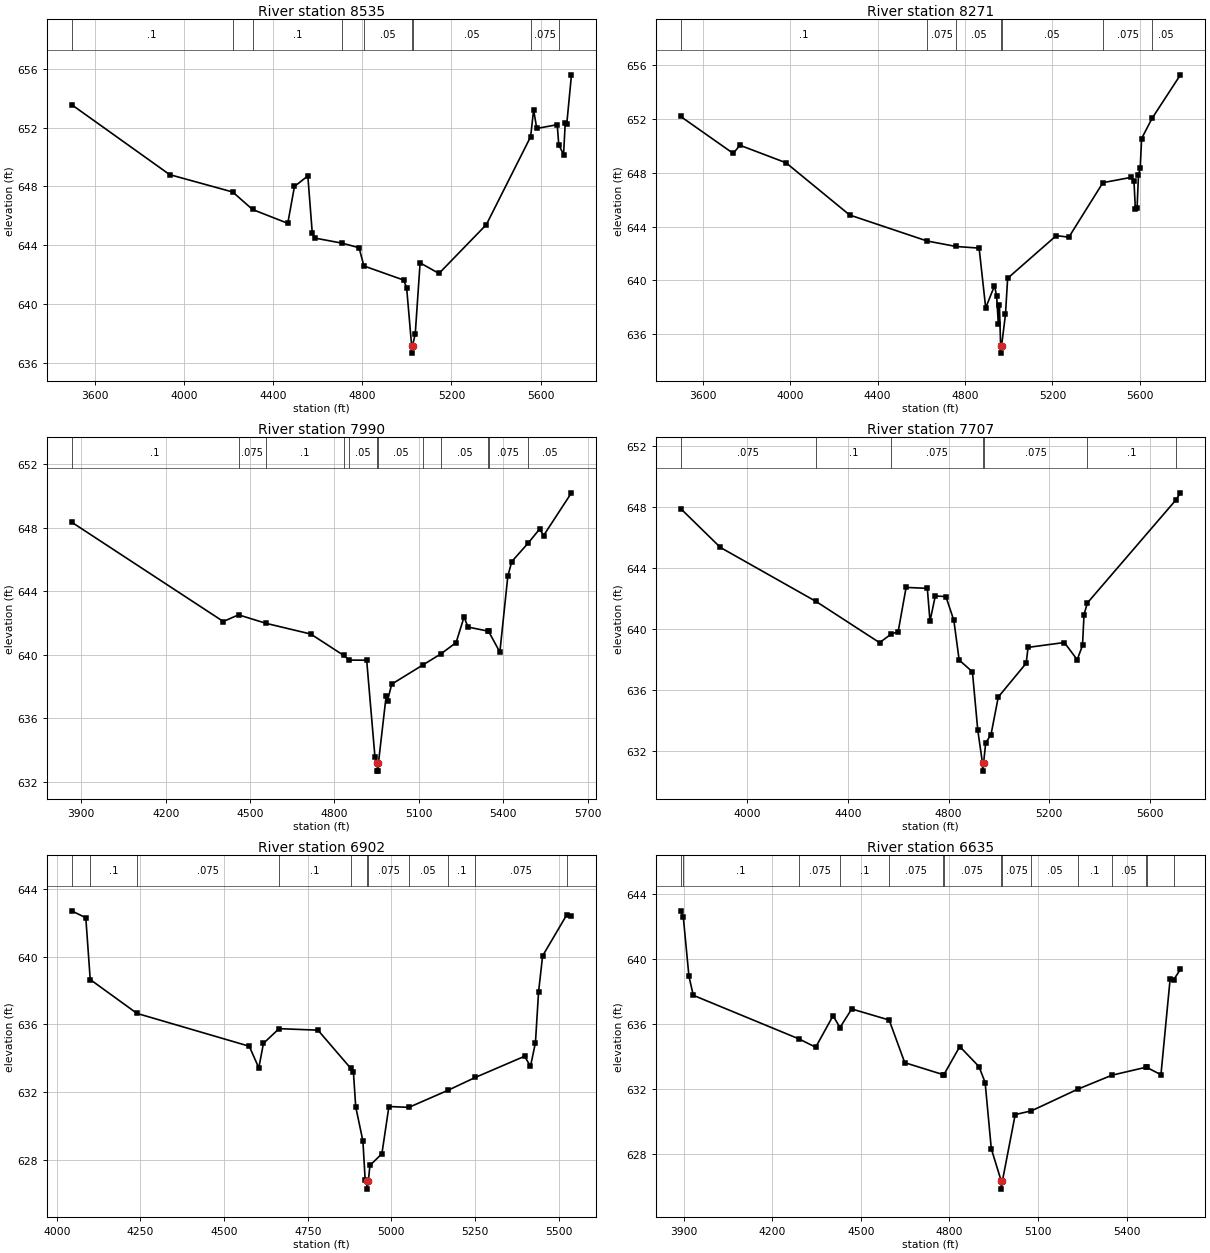
Type RM Length L Ch R = 1,8535,264,264,264
BEGIN DESCRIPTION:
Elizabeth Creek Tributary 4 17.0
END DESCRIPTION:
XS GIS Cut Line= 3
      2340129.00      7061260.00      2340129.00      7059760.00
      2339629.00      7059210.00
#Sta/Elev= 30
  3495.6  653.56  3935.6  648.80  4218.4  647.62  4307.4  646.43  4465.6  645.49
  4495.6  648.00  4555.6  648.71  4575.6  644.82  4585.6  644.49  4709.3  644.14
  4785.6  643.83  4807.2  642.59  4985.6  641.63  4999.0  641.12  5021.6  637.16
  5021.9  636.66  5025.6  637.16  5037.8  637.98  5059.5  642.80  5144.3  642.08
  5356.8  645.40  5555.6  651.38  5569.0  653.21  5583.1  651.94  5675.0  652.20
  5681.9  650.83  5703.4  650.17  5710.9  652.30  5717.6  652.22  5738.9  655.59
#Mann=9,-1,0
  3495.6     0.1       0  4218.4   0.075       0  4307.4     0.1       0
  4709.3   0.075       0  4807.2    0.05       0  5021.6   0.033       0
  5025.6    0.05       0  5555.6   0.075       0  5681.9    0.05       0
Bank Sta=5021.6,5025.6
Exp/Cntr=0.3,0.1

Type RM Length L Ch R = 1,8271,281,281,281
BEGIN DESCRIPTION:
Elizabeth Creek Tributary 4 16.0
END DESCRIPTION:
XS GIS Cut Line= 3
      2340179.00      7061109.98      2340329.00      7059610.00
      2339728.99      7059109.99
#Sta/Elev= 30
  3497.8  652.18  3739.0  649.43  3769.1  650.04  3980.2  648.74  4271.6  644.86
  4625.9  642.93  4759.0  642.52  4864.6  642.40  4894.7  637.96  4934.9  639.60
  4945.0  638.83  4952.5  636.76  4957.5  638.21  4963.1  635.10  4963.3  634.60
  4967.1  635.10  4985.2  637.47  4995.2  640.16  5218.1  643.33  5275.4  643.21
  5431.3  647.26  5559.1  647.65  5573.5  647.40  5580.0  645.31  5587.8  645.39
  5594.3  647.84  5602.1  648.32  5608.6  650.54  5656.2  652.03  5786.3  655.27
#Mann=7,-1,0
  3497.8     0.1       0  4625.9   0.075       0  4759.0    0.05       0
  4963.1    0.05       0  4967.1    0.05       0  5431.3   0.075       0
  5656.2    0.05       0
Bank Sta=4963.1,4967.1
Exp/Cntr=0.3,0.1

Type RM Length L Ch R = 1,7990,283,283,283
BEGIN DESCRIPTION:
Elizabeth Creek Tributary 4 15.0
END DESCRIPTION:
XS GIS Cut Line= 3
      2340279.01      7060609.96      2340579.00      7059510.00
      2340129.02      7059060.02
#Sta/Elev= 30
  3865.9  648.35  4404.9  642.09  4459.0  642.51  4557.7  641.97  4715.8  641.30
  4833.0  639.95  4851.8  639.66  4914.5  639.65  4943.8  633.58  4952.2  633.16
  4952.5  632.66  4956.0  632.66  4956.2  633.16  4983.6  637.38  4988.8  637.11
  5003.4  638.14  5114.1  639.35  5178.4  640.05  5232.3  640.76  5260.6  642.37
  5274.7  641.74  5347.0  641.48  5347.8  641.47  5387.9  640.16  5416.2  644.95
  5430.3  645.87  5488.0  647.02  5529.3  647.92  5543.4  647.51  5642.4  650.20
#Mann=12,-1,0
  3865.9     0.1       0  4459.0   0.075       0  4557.7     0.1       0
  4833.0   0.075       0  4851.8    0.05       0  4952.2    0.05       0
  4956.2    0.05       0  5114.1   0.075       0  5178.4    0.05       0
  5347.0     0.1       0  5347.8   0.075       0  5488.0    0.05       0
Bank Sta=4952.2,4956.2
Exp/Cntr=0.3,0.1

Type RM Length L Ch R = 1,7707,805,805,805
BEGIN DESCRIPTION:
Elizabeth Creek Tributary 4 14.0
END DESCRIPTION:
XS GIS Cut Line= 3
      2340429.00      7060610.01      2340829.00      7059410.00
      2340229.02      7059010.02
#Sta/Elev= 30
  3735.1  647.92  3893.2  645.37  4273.2  641.83  4525.7  639.13  4571.5  639.69
  4599.5  639.85  4631.1  642.75  4715.4  642.69  4726.0  640.53  4747.0  642.19
  4789.2  642.15  4820.8  640.59  4841.9  637.99  4894.6  637.22  4915.7  633.42
  4934.8  631.21  4935.0  630.71  4938.8  631.21  4947.3  632.56  4968.4  633.10
  4997.4  635.57  5108.2  637.78  5115.7  638.82  5259.9  639.14  5311.0  638.01
  5332.0  638.95  5338.0  640.96  5351.2  641.73  5702.5  648.47  5721.1  648.95
#Mann=7,-1,0
  3735.1   0.075       0  4273.2     0.1       0  4571.5   0.075       0
  4934.8    0.07       0  4938.8   0.075       0  5351.2     0.1       0
  5702.5    0.05       0
Bank Sta=4934.8,4938.8
Exp/Cntr=0.3,0.1

Type RM Length L Ch R = 1,6902,267,267,267
BEGIN DESCRIPTION:
Elizabeth Creek Tributary 4 13.0
END DESCRIPTION:
XS GIS Cut Line= 3
      2340828.97      7059810.02      2341529.00      7059160.00
      2341329.00      7058660.00
#Sta/Elev= 30
  4044.3  642.71  4086.6  642.30  4099.8  638.65  4239.6  636.65  4575.2  634.71
  4603.6  633.43  4617.5  634.88  4664.2  635.75  4780.5  635.66  4877.8  633.42
  4886.5  633.16  4893.3  631.13  4914.8  629.11  4921.6  626.78  4927.0  626.77
  4927.2  626.27  4931.0  626.77  4935.8  627.67  4971.5  628.36  4992.5  631.15
  5052.1  631.10  5168.1  632.10  5250.9  632.87  5398.1  634.12  5415.6  633.52
  5430.4  634.92  5439.8  637.93  5451.9  640.05  5524.5  642.49  5538.1  642.43
#Mann=11,-1,0
  4044.3   0.075       0  4099.8     0.1       0  4239.6   0.075       0
  4664.2     0.1       0  4877.8   0.075       0  4927.0    0.07       0
  4931.0   0.075       0  5052.1    0.05       0  5168.1     0.1       0
  5250.9   0.075       0  5524.5     0.1       0
Bank Sta=4927,4931
Exp/Cntr=0.3,0.1

Type RM Length L Ch R = 1,6635,281,281,281
BEGIN DESCRIPTION:
Elizabeth Creek Tributary 4 12.0
END DESCRIPTION:
XS GIS Cut Line= 3
      2340879.03      7059859.98      2341779.00      7059210.00
      2341479.02      7058710.03
#Sta/Elev= 30
  3889.4  642.95  3898.3  642.60  3917.6  638.93  3932.3  637.76  4290.3  635.08
  4347.0  634.57  4405.8  636.50  4429.3  635.78  4469.1  636.92  4595.9  636.24
  4648.7  633.62  4777.8  632.89  4780.5  632.86  4835.1  634.61  4900.1  633.38
  4921.0  632.40  4941.9  628.33  4975.5  626.35  4975.7  625.85  4979.5  626.35
  5022.9  630.43  5077.9  630.66  5234.7  631.99  5350.6  632.85  5466.4  633.34
  5468.5  633.33  5516.6  632.88  5547.7  638.76  5559.8  638.72  5582.6  639.35
#Mann=15,-1,0
  3889.4   0.075       0  3898.3     0.1       0  4290.3   0.075       0
  4429.3     0.1       0  4595.9   0.075       0  4777.8     0.1       0
  4780.5   0.075       0  4975.5    0.07       0  4979.5   0.075       0
  5077.9    0.05       0  5234.7     0.1       0  5350.6    0.05       0
  5466.4   0.075       0  5468.5    0.05       0  5559.8   0.075       0
Bank Sta=4975.5,4979.5
Exp/Cntr=0.3,0.1

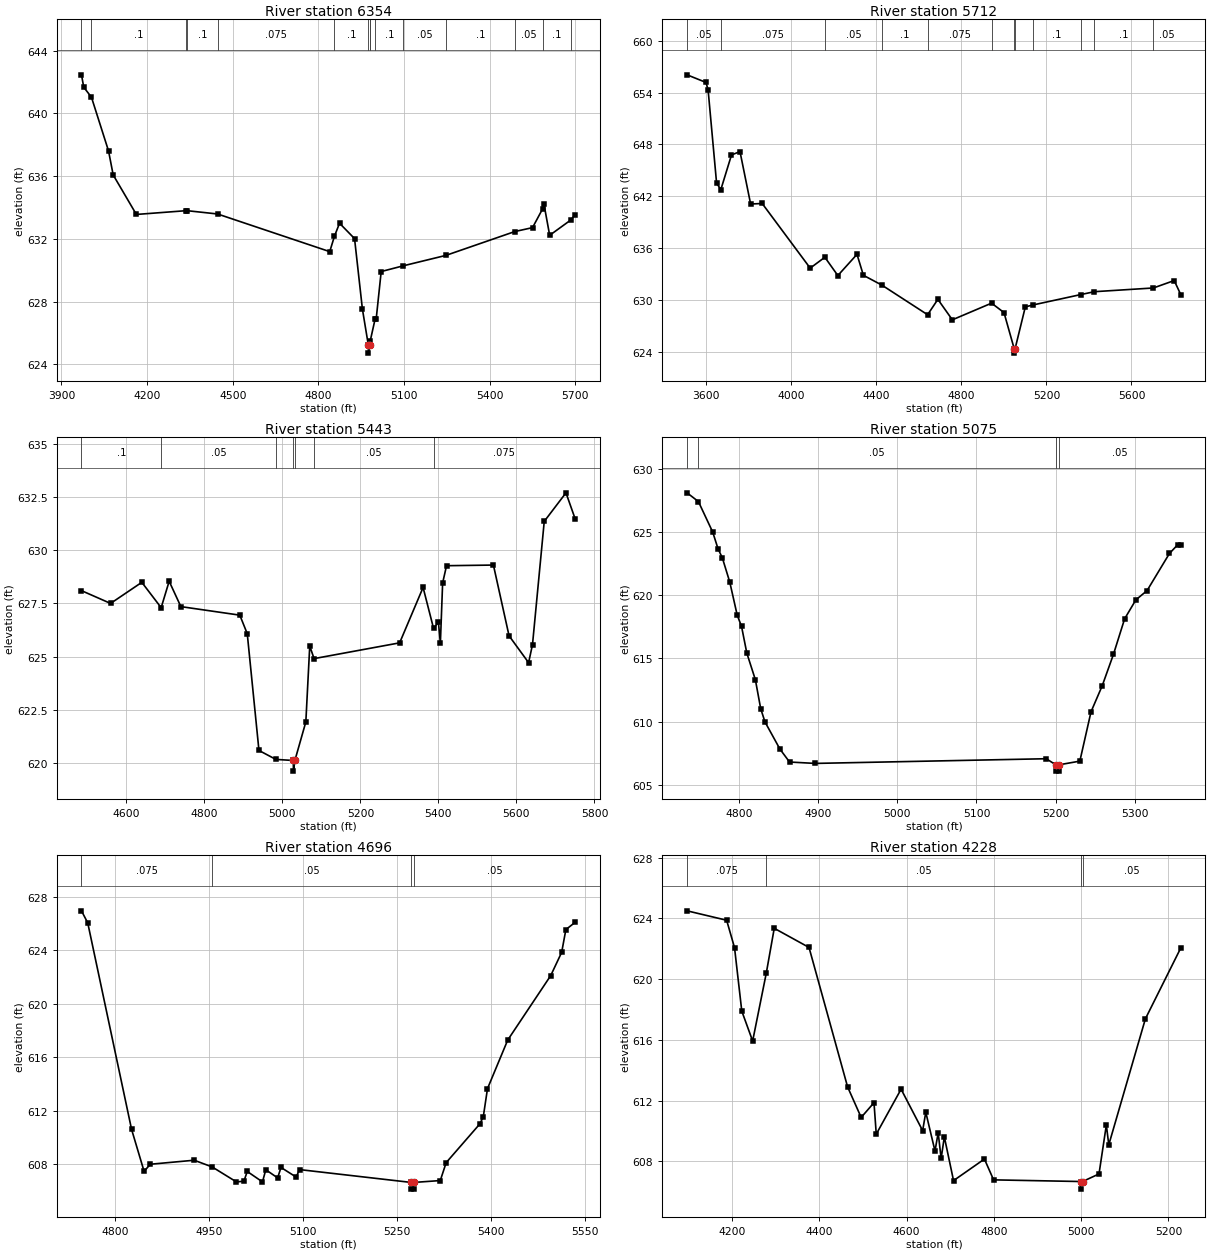
Type RM Length L Ch R = 1,6354,642,642,642
BEGIN DESCRIPTION:
Elizabeth Creek Tributary 4 11.0
END DESCRIPTION:
XS GIS Cut Line= 3
      2341529.01      7060209.99      2342029.00      7059310.00
      2342038.23      7058610.81
#Sta/Elev= 30
  3970.4  642.45  3978.4  641.66  4005.4  641.02  4065.3  637.59  4081.4  636.07
  4162.6  633.55  4337.0  633.79  4340.3  633.79  4446.9  633.58  4839.8  631.18
  4856.3  632.16  4874.1  632.99  4926.7  632.01  4954.2  627.52  4975.1  625.21
  4975.3  624.71  4979.1  625.21  4981.4  625.47  4998.8  626.89  5002.5  626.89
  5020.0  629.91  5098.1  630.28  5246.6  630.94  5487.9  632.46  5550.0  632.71
  5585.7  633.92  5590.0  634.21  5610.0  632.22  5683.5  633.19  5699.2  633.53
#Mann=15,-1,0
  3970.4    0.05       0  4005.4     0.1       0  4337.0   0.075       0
  4340.3     0.1       0  4446.9   0.075       0  4856.3     0.1       0
  4975.1    0.07       0  4979.1     0.1       0  4981.4   0.075       0
  4998.8     0.1       0  5098.1    0.05       0  5246.6     0.1       0
  5487.9    0.05       0  5585.7     0.1       0  5683.5   0.075       0
Bank Sta=4975.1,4979.1
Exp/Cntr=0.3,0.1

Type RM Length L Ch R = 1,5712,269,269,269
BEGIN DESCRIPTION:
Elizabeth Creek Tributary 4 10.0
END DESCRIPTION:
XS GIS Cut Line= 4
      2342575.63      7061048.73      2342602.60      7059912.66
      2342567.40      7059448.01      2342567.40      7058729.29
#Sta/Elev= 30
  3510.4  656.07  3599.2  655.19  3609.2  654.35  3649.2  643.52  3669.2  642.77
  3719.2  646.78  3759.2  647.18  3809.2  641.10  3863.6  641.16  4089.3  633.67
  4158.2  634.93  4219.3  632.81  4309.4  635.27  4339.4  632.84  4426.5  631.70
  4641.3  628.27  4689.6  630.05  4757.7  627.68  4942.1  629.61  5000.5  628.52
  5048.6  624.32  5048.9  623.82  5052.6  624.32  5100.8  629.18  5138.5  629.41
  5362.4  630.61  5426.0  630.94  5702.8  631.37  5800.8  632.23  5831.5  630.61
#Mann=12,-1,0
  3510.4    0.05       0  3669.2   0.075       0  4158.2    0.05       0
  4426.5     0.1       0  4641.3   0.075       0  4942.1    0.05       0
  5048.6   0.033       0  5052.6    0.05       0  5138.5     0.1       0
  5362.4    0.05       0  5426.0     0.1       0  5702.8    0.05       0
Bank Sta=5048.6,5052.6
Exp/Cntr=0.3,0.1

Type RM Length L Ch R = 1,5443,368,368,368
BEGIN DESCRIPTION:
Elizabeth Creek Tributary 4 9.0
END DESCRIPTION:
XS GIS Cut Line= 3
      2342851.72      7060024.57      2342829.00      7059510.00
      2342875.42      7058760.91
#Sta/Elev= 30
  4484.9  628.10  4559.5  627.50  4639.6  628.49  4689.2  627.30  4709.7  628.54
  4739.7  627.35  4890.8  626.95  4909.9  626.08  4939.9  620.60  4983.3  620.18
  5028.0  620.13  5028.3  619.63  5032.0  620.13  5060.1  621.94  5070.1  625.50
  5081.2  624.91  5300.6  625.65  5360.7  628.25  5387.5  626.33  5400.0  626.62
  5405.0  625.63  5410.8  628.46  5420.8  629.27  5541.0  629.30  5581.1  625.98
  5631.2  624.72  5641.2  625.57  5671.3  631.35  5727.0  632.69  5750.5  631.47
#Mann=7,-1,0
  4484.9     0.1       0  4689.2    0.05       0  4983.3   0.075       0
  5028.0    0.07       0  5032.0   0.075       0  5081.2    0.05       0
  5387.5   0.075       0
Bank Sta=5028,5032
Exp/Cntr=0.3,0.1

Type RM Length L Ch R = 1,5075,379,379,379
BEGIN DESCRIPTION:
Elizabeth Creek Tributary 4 8.0
END DESCRIPTION:
XS GIS Cut Line= 3
      2343279.02      7059710.04      2343179.00      7059460.00
      2342928.97      7059209.97
#Sta/Elev= 30
  4734.8  628.09  4749.1  627.40  4767.2  624.98  4773.9  623.66  4779.3  622.95
  4788.7  621.03  4798.1  618.41  4803.5  617.54  4810.2  615.42  4821.0  613.31
  4827.7  611.03  4833.1  609.98  4852.0  607.83  4864.1  606.81  4896.4  606.70
  5188.0  607.07  5200.1  606.59  5200.3  606.09  5203.8  606.09  5204.1  606.59
  5230.4  606.88  5244.5  610.78  5258.7  612.85  5272.8  615.32  5286.9  618.13
  5301.1  619.63  5315.2  620.36  5343.5  623.30  5354.1  624.00  5357.7  624.00
#Mann=4,-1,0
  4734.8   0.075       0  4749.1    0.05       0  5200.1    0.05       0
  5204.1    0.05       0
Bank Sta=5200.1,5204.1
Exp/Cntr=0.3,0.1

Type RM Length L Ch R = 1,4696,468,468,468
BEGIN DESCRIPTION:
Elizabeth Creek Tributary 4 7.0
END DESCRIPTION:
XS GIS Cut Line= 3
      2343529.00      7059610.01      2343529.00      7059360.00
      2343329.01      7058860.03
#Sta/Elev= 30
  4745.7  626.94  4755.7  626.04  4825.7  610.61  4845.7  607.47  4855.7  608.00
  4925.7  608.30  4954.4  607.80  4993.2  606.68  5005.1  606.73  5010.5  607.46
  5034.8  606.68  5040.1  607.59  5059.0  606.98  5064.4  607.76  5088.6  607.04
  5094.0  607.60  5272.4  606.64  5272.6  606.14  5276.1  606.14  5276.4  606.64
  5318.8  606.78  5328.2  608.12  5382.1  611.02  5387.5  611.55  5394.2  613.65
  5426.5  617.28  5495.2  622.10  5512.7  623.84  5519.4  625.54  5534.2  626.08
#Mann=4,-1,0
  4745.7   0.075       0  4954.4    0.05       0  5272.4   0.033       0
  5276.4    0.05       0
Bank Sta=5272.4,5276.4
Exp/Cntr=0.3,0.1

Type RM Length L Ch R = 1,4228,463,463,463
BEGIN DESCRIPTION:
Elizabeth Creek Tributary 4 6.0
END DESCRIPTION:
XS GIS Cut Line= 4
      2344297.07      7059835.05      2344170.69      7059369.03
      2343879.00      7059060.00      2343779.01      7058860.01
#Sta/Elev= 30
  4096.9  624.49  4187.6  623.87  4205.7  622.06  4222.3  617.89  4247.2  615.92
  4278.4  620.38  4296.7  623.34  4376.4  622.08  4464.8  612.90  4495.9  610.89
  4525.3  611.86  4530.5  609.79  4587.4  612.75  4636.8  610.02  4644.0  611.23
  4665.1  608.68  4672.4  609.88  4679.2  608.19  4686.5  609.61  4707.6  606.73
  4778.4  608.15  4799.4  606.78  4999.2  606.67  4999.5  606.17  5003.3  606.67
  5041.0  607.17  5057.8  610.39  5063.4  609.09  5147.3  617.38  5228.3  622.04
#Mann=4,-1,0
  4096.9   0.075       0  4278.4    0.05       0  4999.2    0.05       0
  5003.3    0.05       0
Bank Sta=4999.2,5003.3
Exp/Cntr=0.3,0.1

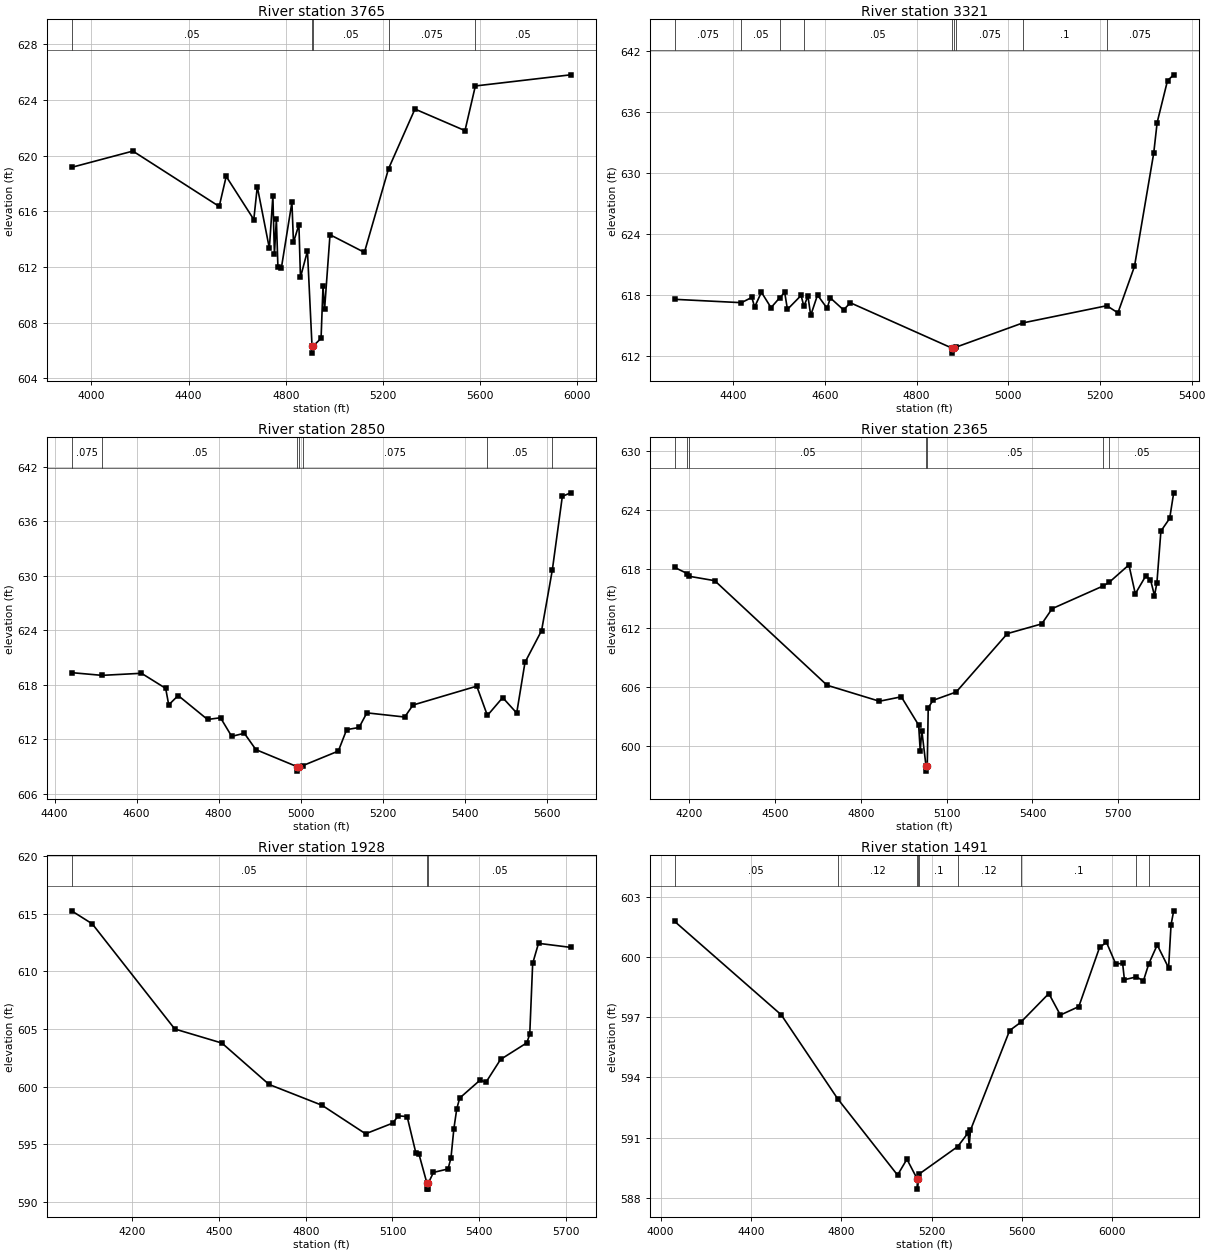
Type RM Length L Ch R = 1,3765,444,444,444
BEGIN DESCRIPTION:
Elizabeth Creek Tributary 4 5.0
END DESCRIPTION:
XS GIS Cut Line= 3
      2344952.56      7059700.71      2344279.00      7058860.00
      2343688.90      7058081.65
#Sta/Elev= 30
  3918.2  619.15  4170.4  620.32  4525.7  616.34  4554.5  618.50  4668.1  615.40
  4682.5  617.76  4732.2  613.33  4746.6  617.09  4753.0  612.91  4761.0  615.44
  4767.4  611.99  4781.8  611.94  4825.0  616.64  4831.4  613.76  4853.8  615.03
  4860.2  611.25  4889.0  613.14  4907.8  606.30  4908.1  605.80  4911.9  606.30
  4945.0  606.86  4953.0  610.61  4959.4  608.94  4981.8  614.31  5123.4  613.04
  5222.7  619.05  5331.4  623.34  5537.4  621.79  5580.1  625.00  5972.2  625.80
#Mann=5,-1,0
  3918.2    0.05       0  4907.8   0.033       0  4911.9    0.05       0
  5222.7   0.075       0  5580.1    0.05       0
Bank Sta=4907.8,4911.9
Exp/Cntr=0.3,0.1

Type RM Length L Ch R = 1,3321,471,471,471
BEGIN DESCRIPTION:
Elizabeth Creek Tributary 4 4.0
END DESCRIPTION:
XS GIS Cut Line= 3
      2345042.17      7059209.67      2344629.00      7058610.00
      2344328.99      7058409.99
#Sta/Elev= 30
  4272.0  617.56  4417.6  617.23  4440.3  617.75  4446.4  616.80  4461.2  618.26
  4482.2  616.74  4500.8  617.70  4512.0  618.24  4518.0  616.57  4547.8  617.94
  4553.9  616.87  4562.7  617.88  4568.8  615.98  4583.6  617.98  4604.6  616.68
  4611.6  617.70  4640.4  616.52  4655.3  617.22  4876.7  612.77  4877.0  612.27
  4880.9  612.77  4886.0  612.86  5031.6  615.24  5214.9  616.93  5239.1  616.23
  5275.2  620.79  5317.2  631.92  5324.7  634.94  5347.3  639.06  5360.8  639.63
#Mann=9,-1,0
  4272.0   0.075       0  4417.6    0.05       0  4500.8   0.075       0
  4553.9    0.05       0  4876.7    0.07       0  4880.9    0.05       0
  4886.0   0.075       0  5031.6     0.1       0  5214.9   0.075       0
Bank Sta=4876.7,4880.9
Exp/Cntr=0.3,0.1

Type RM Length L Ch R = 1,2850,485,485,485
BEGIN DESCRIPTION:
Elizabeth Creek Tributary 4 3.0
END DESCRIPTION:
XS GIS Cut Line= 3
      2345207.16      7058745.54      2344929.00      7058260.00
      2344279.02      7058360.00
#Sta/Elev= 30
  4441.3  619.32  4515.4  619.02  4611.7  619.25  4670.7  617.59  4678.2  615.77
  4701.2  616.80  4772.8  614.16  4804.5  614.35  4831.8  612.30  4862.6  612.64
  4890.8  610.84  4990.8  608.97  4991.2  608.47  4995.1  608.97  5005.0  609.07
  5091.9  610.68  5112.2  613.04  5142.5  613.28  5161.5  614.89  5253.8  614.43
  5274.0  615.75  5429.6  617.83  5455.5  614.60  5492.8  616.57  5527.0  614.87
  5547.2  620.45  5587.7  623.95  5613.9  630.63  5638.3  638.74  5658.5  639.13
#Mann=7,-1,0
  4441.3   0.075       0  4515.4    0.05       0  4990.8    0.05       0
  4995.1    0.05       0  5005.0   0.075       0  5455.5    0.05       0
  5613.9   0.075       0
Bank Sta=4990.8,4995.1
Exp/Cntr=0.3,0.1

Type RM Length L Ch R = 1,2365,437,437,437
BEGIN DESCRIPTION:
Elizabeth Creek Tributary 4 2.0
END DESCRIPTION:
XS GIS Cut Line= 3
      2345428.98      7058559.97      2345029.00      7057810.00
      2344228.99      7058210.00
#Sta/Elev= 30
  4149.3  618.17  4192.7  617.55  4199.7  617.27  4289.2  616.82  4681.9  606.17
  4865.0  604.54  4941.5  604.99  5002.1  602.11  5007.6  599.49  5013.2  601.55
  5027.9  597.92  5028.2  597.42  5032.2  597.92  5035.6  603.88  5052.4  604.63
  5133.4  605.48  5312.3  611.43  5432.5  612.42  5468.8  613.97  5646.9  616.28
  5668.1  616.65  5737.2  618.43  5759.5  615.48  5795.9  617.30  5812.6  616.93
  5826.6  615.29  5835.0  616.60  5849.0  621.87  5879.7  623.17  5893.7  625.77
#Mann=7,-1,0
  4149.3    0.05       0  4192.7   0.075       0  4199.7    0.05       0
  5027.9    0.05       0  5032.2    0.05       0  5646.9   0.075       0
  5668.1    0.05       0
Bank Sta=5027.9,5032.2
Exp/Cntr=0.3,0.1

Type RM Length L Ch R = 1,1928,437,437,437
BEGIN DESCRIPTION:
Elizabeth Creek Tributary 4 1.0
END DESCRIPTION:
XS GIS Cut Line= 3
      2345479.00      7058460.02      2345279.00      7057460.00
      2344579.03      7057560.00
#Sta/Elev= 30
  3989.6  615.24  4061.0  614.11  4346.6  604.99  4509.7  603.77  4672.9  600.18
  4856.5  598.37  5006.9  595.90  5100.3  596.82  5120.5  597.46  5150.8  597.39
  5181.2  594.21  5191.3  594.17  5219.4  591.60  5219.8  591.10  5223.4  591.10
  5223.7  591.60  5241.8  592.55  5292.3  592.85  5302.4  593.80  5312.5  596.34
  5322.6  598.08  5332.7  599.00  5403.4  600.56  5423.6  600.37  5474.1  602.35
  5565.0  603.79  5575.1  604.54  5585.2  610.68  5605.4  612.42  5716.5  612.07
#Mann=3,-1,0
  3989.6    0.05       0  5219.4   0.033       0  5223.7    0.05       0
Bank Sta=5219.4,5223.7
Exp/Cntr=0.3,0.1

Type RM Length L Ch R = 1,1491,453,453,453
BEGIN DESCRIPTION:
Elizabeth Creek Tributary 4 0.7
END DESCRIPTION:
XS GIS Cut Line= 3
      2345797.66      7058042.12      2345513.34      7056999.63
      2344407.58      7057228.69
#Sta/Elev= 30
  4062.7  601.76  4534.6  597.11  4784.4  592.93  5049.6  589.13  5091.1  589.92
  5137.1  588.93  5137.4  588.43  5141.4  588.93  5143.8  589.17  5316.1  590.55
  5362.0  591.23  5367.1  590.58  5372.4  591.36  5546.0  596.33  5594.4  596.73
  5719.6  598.17  5770.6  597.10  5852.3  597.52  5944.3  600.47  5974.9  600.72
  6015.7  599.65  6046.4  599.67  6054.3  598.86  6107.3  599.00  6138.3  598.80
  6162.5  599.66  6199.6  600.59  6249.9  599.45  6260.8  601.60  6272.5  602.29
#Mann=9,-1,0
  4062.7    0.05       0  4784.4    0.12       0  5137.1    0.07       0
  5141.4    0.12       0  5143.8     0.1       0  5316.1    0.12       0
  5594.4     0.1       0  6107.3   0.075       0  6162.5    0.05       0
Bank Sta=5137.1,5141.4
Exp/Cntr=0.3,0.1

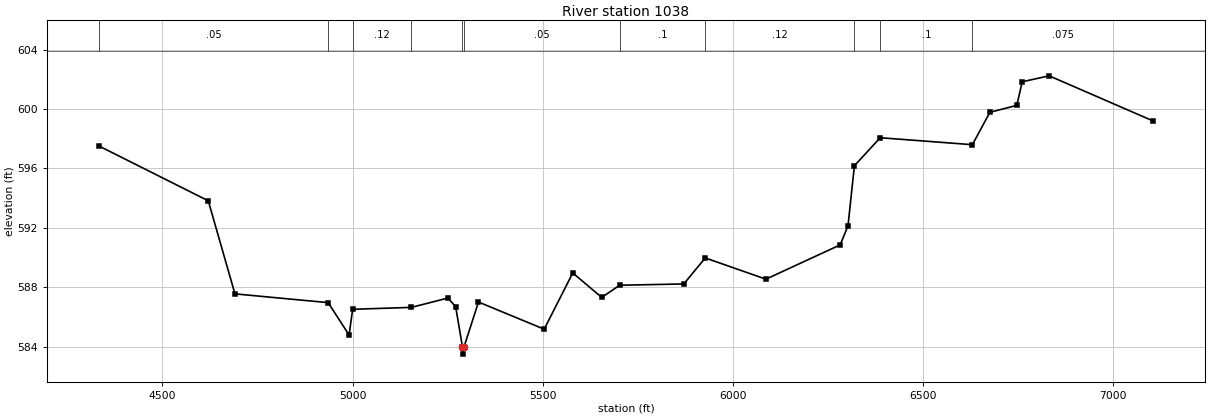
Type RM Length L Ch R = 1,1038,0,0,0
BEGIN DESCRIPTION:
Elizabeth Creek Tributary 4 0.5
END DESCRIPTION:
XS GIS Cut Line= 4
      2345963.53      7057726.28      2345916.14      7056557.35
      2344857.81      7056810.08      2344480.16      7057156.27
#Sta/Elev= 30
  4334.0  597.50  4620.5  593.82  4690.6  587.55  4935.7  586.96  4990.8  584.78
  5000.2  586.51  5154.6  586.64  5251.0  587.27  5271.1  586.68  5288.9  583.99
  5289.3  583.49  5293.2  583.99  5331.1  587.00  5503.9  585.17  5579.0  588.96
  5655.2  587.31  5702.3  588.13  5871.1  588.22  5927.5  589.97  6087.0  588.54
  6282.3  590.85  6302.9  592.14  6319.7  596.18  6387.5  598.07  6630.0  597.60
  6675.9  599.78  6746.8  600.25  6761.0  601.84  6831.9  602.24  7104.3  599.21
#Mann=11,-1,0
  4334.0    0.05       0  4935.7     0.1       0  5000.2    0.12       0
  5154.6    0.05       0  5288.9    0.07       0  5293.2    0.05       0
  5702.3     0.1       0  5927.5    0.12       0  6319.7   0.075       0
  6387.5     0.1       0  6630.0   0.075       0
Bank Sta=5288.9,5293.2
Exp/Cntr=0.3,0.1

Chan Stop Cuts=-1