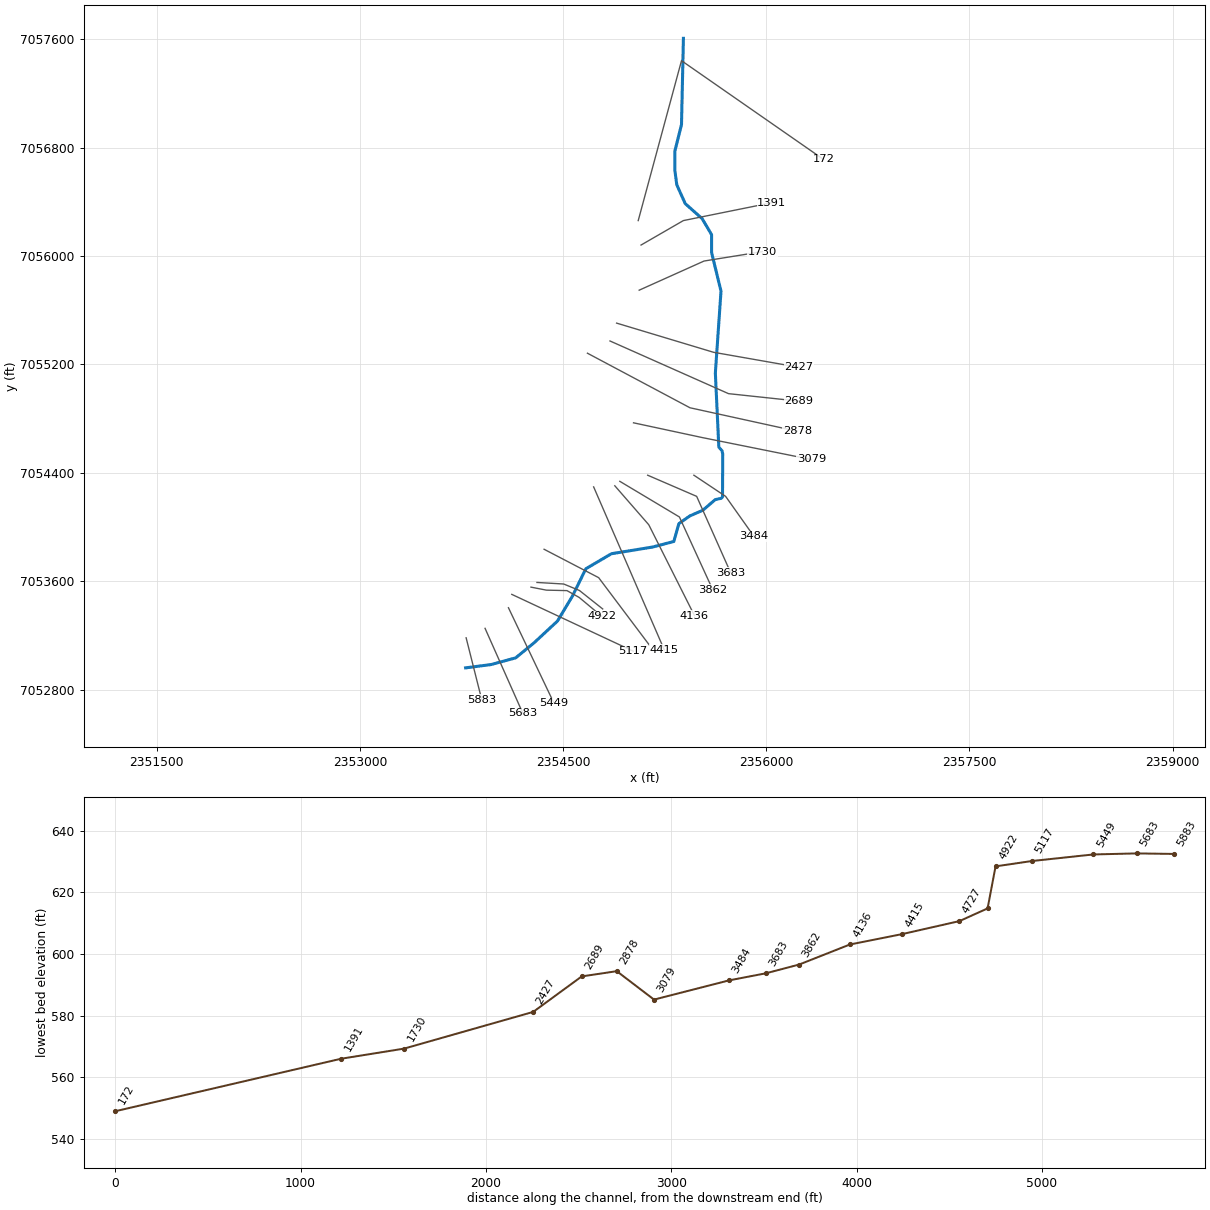
--- Elizabeth Cr Tr 4A.prj (project) ---

Proj Title=Elizabeth Cr Tr 4A Base Level Engineering
Current Plan=p01
Default Exp/Contr=0.3,0.1
English Units
Geom File=g01
Flow File=f01
Plan File=p01
Y Axis Title=Elevation
X Axis Title(PF)=Main Channel Distance
X Axis Title(XS)=Station
BEGIN DESCRIPTION:
Elizabeth Cr Tr 4A
END DESCRIPTION:
DSS Export Rating Curves= 0
DSS Export Rating Curve Sorted= 0
DSS Export Volume Flow Curves= 0
DXF OffsetX= 0
DXF OffsetY= 0
DXF ScaleX= 1
DXF ScaleY= 10

--- Elizabeth Cr Tr 4A.p01 (plan) ---

Plan Title=Multiple Run
Program Version=4.10
Short Identifier=Multiple
Geom File=g01
Flow File=f01
Subcritical Flow
K Sum by GR= 0
Std Step Tol= 0.01
Critical Tol= 0.01
Num of Std Step Trials= 20
Max Error Tol= 0.3
Flow Tol Ratio= 0.001
Split Flow NTrial= 30
Split Flow Tol= 0.02
Split Flow Ratio= 0.02
Log Output Level= 0
Friction Slope Method= 0
Unsteady Friction Slope Method= 2
Unsteady Bridges Friction Slope Method= 1
Parabolic Critical Depth
Global Vel Dist= 1 , 1 , 1
Global Log Level= 0
CheckData=True
Encroach Param=-1 ,0,0, 0
BEGIN DESCRIPTION:
Multiple Run
END DESCRIPTION:
Computation Interval=1HOUR
Output Interval=1HOUR
Run HTab= 0
Run UNet= 0
Run PostProcess= 0
Run WQNet= 0
UNET Theta= 1
UNET Theta Warmup= 1
UNET ZTol= 0.02
UNET ZSATol= 0.05
UNET MxIter= 20
UNET MaxInSteps= 0
UNET DtIC= 0
UNET DtMin= 0
UNET MaxCRTS= 20
UNET WFStab= 2
UNET SFStab= 1
UNET WFX= 1
UNET SFX= 1
UNET DSS MLevel= 4
UNET DZMax Abort= 100
UNET Convert EG Bridges= 0
UNET Use Existing IB Tables=-1
UNET Froude Reduction=False
UNET Froude Limit= 1
UNET Froude Power= 10
UNET Time Slicing=0,0, 5
UNET Junction Losses=0
Instantaneous Interval=1HOUR
Write IC File= 0
Write IC File at Sim End=0
Echo Input=False
Echo Parameters=False
Echo Output=False
Write Detailed= 0
WQ AD Non Conservative
WQ ULTIMATE=-1
WQ Max Comp Step=1HOUR
WQ Output Interval=15MIN
WQ Output Selected Increments= 0
WQ Output face flow=0
WQ Output face velocity=0
WQ Output face area=0
WQ Output face dispersion=0
WQ Output cell volume=0
WQ Output cell surface area=0
WQ Output cell continuity=0
WQ Output cumulative cell continuity=0
WQ Output face conc=0
WQ Output face dconc_dx=0
WQ Output face courant=0
WQ Output face peclet=0
WQ Output face adv mass=0
WQ Output face disp mass=0
WQ Output cell mass=0
WQ Output cell source sink temp=0
WQ Output cell source sink nsm=0
WQ Output MaxMinRange=-1
WQ Daily Max Min Mean=-1
WQ Daily Range=0
WQ Daily Time=0
WQ Create Restart=0
WQ Fixed Restart=0
WQ System Summary=0
WQ Use Fixed Temperature=0
Sorting and Armoring Iterations= 10
XS Update Threshold= 0.02
Hydraulics Update Threshold= 0.02
Energy Slope Method= 1
Volume Change Method= 0
XS Weighting Method= 0
Number of US Weighted Cross Sections= 1
Number of DS Weighted Cross Sections= 1
Upstream XS Weight=0.25
Main XS Weight=0.5
Downstream XS Weight=0.25
Number of DS XS's Weighted with US Boundary= 1
Upstream Boundary Weight= 1
Weight of XSs Associated with US Boundary= 0
Number of US XS's Weighted with DS Boundary= 1
Downstream Boundary Weight= 0.5
Weight of XSs Associated with DS Boundary= 0.5
Sediment Output Level= 4
Mass or Volume Output= 0
Output Increment Type= 1
Profile and TS Output Increment= 10
XS Output Flag= 0
XS Output Increment= 10
Disregard all LS=0
Disregard all Conn=0
Disregard all Breaches=0
Disregard all Pumps=0

--- Elizabeth Cr Tr 4A.f01 (steady flow) ---

Flow Title=Multiple
Number of Profiles=7
Profile Names=10-year,25-year,50-year,1pct_min,100-year,1pct_plu,500-year
River Rch & RM= Elizabeth Cr Tr ,Reach-1,5883
     430     578     699     420     838    1670    1210
River Rch & RM= Elizabeth Cr Tr ,Reach-1,3484
     528     716     871     526    1050    2100    1530
River Rch & RM= Elizabeth Cr Tr ,Reach-1,2878
     626     862    1060     646    1290    2570    1910
Boundary for River Rch & Prof#=Elizabeth Cr Tr ,Reach-1,1
Up Type=0
Dn Type=3
Dn Slope=0.005
Boundary for River Rch & Prof#=Elizabeth Cr Tr ,Reach-1,2
Up Type=0
Dn Type=3
Dn Slope=0.005
Boundary for River Rch & Prof#=Elizabeth Cr Tr ,Reach-1,3
Up Type=0
Dn Type=3
Dn Slope=0.005
Boundary for River Rch & Prof#=Elizabeth Cr Tr ,Reach-1,4
Up Type=0
Dn Type=3
Dn Slope=0.005
Boundary for River Rch & Prof#=Elizabeth Cr Tr ,Reach-1,5
Up Type=0
Dn Type=3
Dn Slope=0.005
Boundary for River Rch & Prof#=Elizabeth Cr Tr ,Reach-1,6
Up Type=0
Dn Type=3
Dn Slope=0.005
Boundary for River Rch & Prof#=Elizabeth Cr Tr ,Reach-1,7
Up Type=0
Dn Type=3
Dn Slope=0.005

--- Elizabeth Cr Tr 4A.g01 (geometry) ---

Geom Title=Existing Conditions
Program Version=4.10

River Reach=Elizabeth Cr Tr ,Reach-1
Reach XY= 30
      2353780.44      7052959.85      2353969.56      7052984.51
      2354150.45      7053033.85      2354286.12      7053144.85
      2354458.79      7053305.19      2354569.79      7053490.19
      2354668.46      7053691.64      2354857.58      7053802.64
      2355161.81      7053851.98      2355318.03      7053893.09
      2355355.03      7054024.65      2355437.26      7054082.21
      2355531.81      7054123.32      2355623.37      7054201.85
      2355668.23      7054211.92      2355677.46      7054221.71
      2355679.09      7054540.12      2355673.64       7054562.7
      2355650.26      7054589.77      2355624.59       7055137.2
      2355666.26      7055741.36      2355596.82      7056026.08
      2355596.82      7056158.03      2355527.37      7056276.08
      2355402.37       7056387.2      2355339.87      7056526.08
      2355325.98      7056630.25      2355325.98      7056776.08
      2355374.59      7056970.53      2355388.71      7057607.75

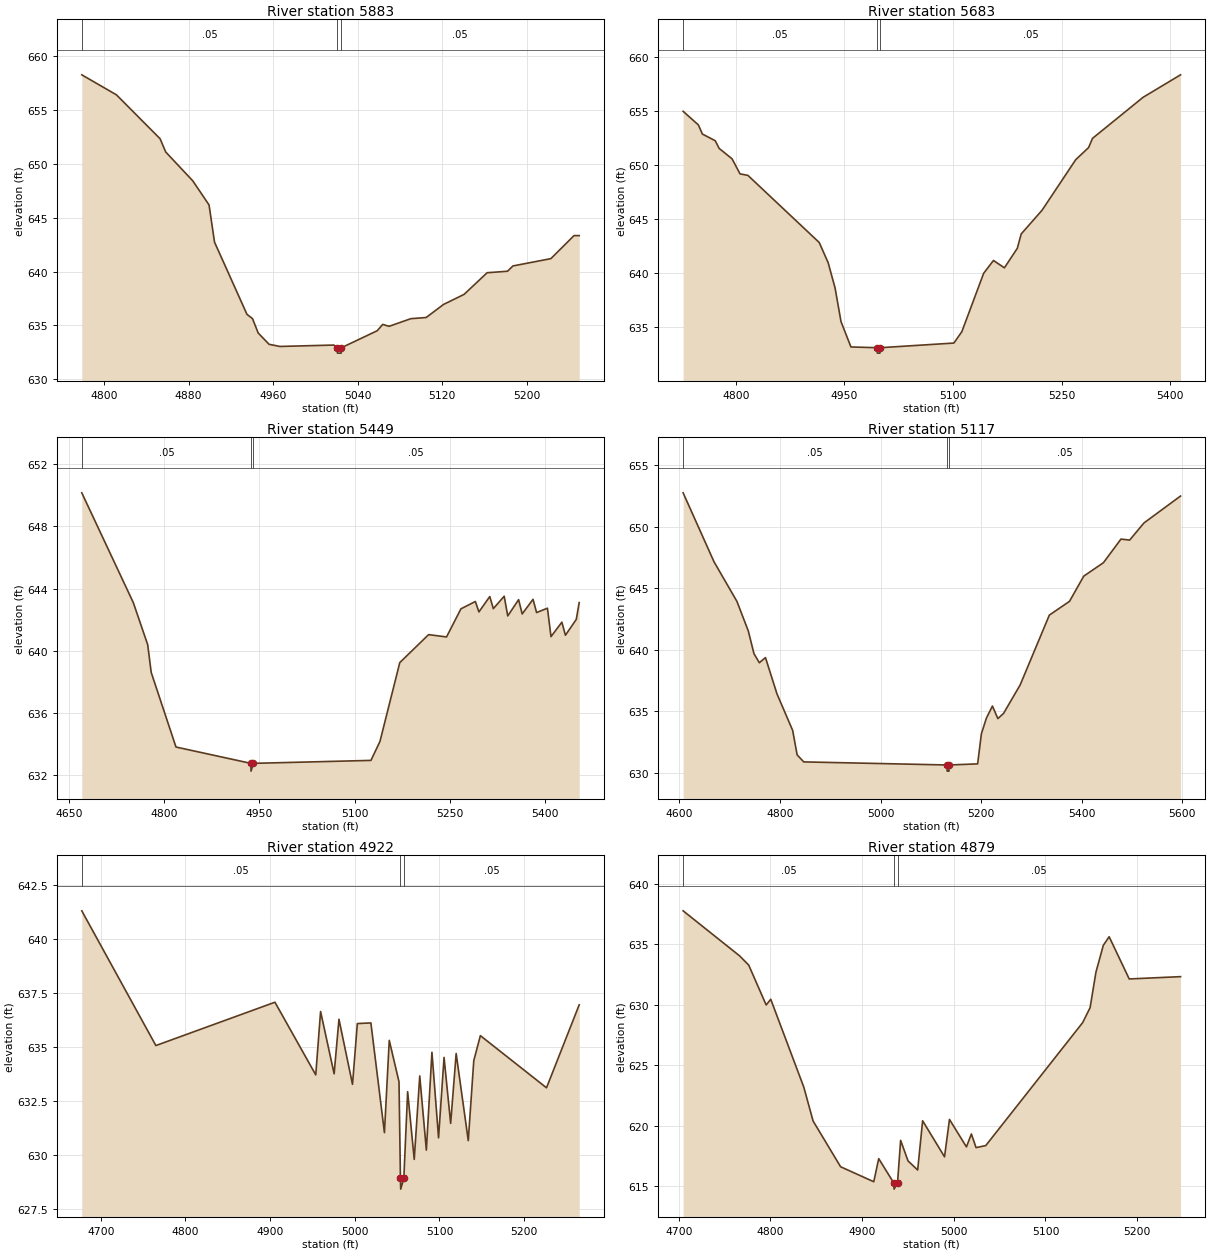
Type RM Length L Ch R = 1 ,5883    ,200,200,200
BEGIN DESCRIPTION:
Elizabeth Creek Tributary 4A 15.0
END DESCRIPTION:
XS GIS Cut Line= 2
      2353784.56      7053181.82      2353899.66      7052725.52
#Sta/Elev= 30
  4778.9  658.29  4811.7  656.43    4853  652.35  4858.3  651.12  4883.9  648.44
  4899.3   646.2  4904.5  642.74  4935.2  636.03  4940.4  635.64  4945.8   634.3
  4956.1  633.25  4966.4  633.05  5017.4  633.18  5020.5  632.93  5020.8  632.43
  5024.3  632.43  5024.5  632.93  5058.4  634.51  5063.6   635.1  5069.6  634.92
  5090.2  635.63  5104.7  635.74  5121.1  636.95  5140.6  637.89  5162.4   639.9
  5181.7  640.04  5186.8  640.53  5222.7  641.21  5244.6  643.35  5249.5  643.35
#Mann= 3 ,-1 , 0
  4778.9     .05       0  5020.5    .033       0  5024.5     .05       0
Bank Sta=5020.5,5024.5
XS Rating Curve= 0 ,0
Exp/Cntr=0.3,0.1

Type RM Length L Ch R = 1 ,5683    ,234,234,234
BEGIN DESCRIPTION:
Elizabeth Creek Tributary 4A 14.0
END DESCRIPTION:
XS GIS Cut Line= 2
      2353924.31      7053251.78      2354203.37       7052623.9
#Sta/Elev= 30
  4727.1  654.94  4748.2  653.68  4753.7  652.84  4771.5  652.22  4776.9  651.51
  4794.7  650.55  4805.7  649.16  4816.6  649.02  4915.1  642.82  4927.4  640.96
    4937  638.62  4945.2  635.51  4958.9  633.17  4995.2   633.1  4995.4   632.6
  4998.9   632.6  4999.2   633.1  5101.1  633.53  5112.1  634.58  5142.2  639.97
  5155.8  641.16  5170.9  640.48  5188.7  642.28  5194.1  643.61  5222.9   645.8
  5269.4  650.47  5287.2  651.59  5292.6  652.44  5362.4  656.23  5414.2  658.31
#Mann= 3 ,-1 , 0
  4727.1     .05       0  4995.2    .033       0  4999.2     .05       0
Bank Sta=4995.2,4999.2
XS Rating Curve= 0 ,0
Exp/Cntr=0.3,0.1

Type RM Length L Ch R = 1 ,5449    ,332,332,332
BEGIN DESCRIPTION:
Elizabeth Creek Tributary 4A 13.0
END DESCRIPTION:
XS GIS Cut Line= 2
      2354097.02      7053403.83      2354434.06      7052696.86
#Sta/Elev= 30
  4670.3  650.16  4751.4   643.1  4774.1  640.39  4779.6  638.61  4818.6  633.81
  4936.5  632.76  4936.8  632.26  4940.5  632.76  5125.6  632.95  5139.8  634.17
    5171  639.24  5216.4  641.04  5244.6  640.89  5267.3   642.7    5290  643.17
  5295.6   642.5  5312.7  643.49  5318.3  642.71  5335.4  643.51    5341  642.24
  5358.1  643.29  5363.7  642.37  5380.8  643.31  5386.4  642.46  5403.5  642.74
  5409.1  640.91  5426.2  641.84  5431.8     641  5448.9  642.02  5453.5   643.1
#Mann= 3 ,-1 , 0
  4670.3     .05       0  4936.5    .033       0  4940.5     .05       0
Bank Sta=4936.5,4940.5
XS Rating Curve= 0 ,0
Exp/Cntr=0.3,0.1

Type RM Length L Ch R = 1 ,5117    ,195,195,195
BEGIN DESCRIPTION:
Elizabeth Creek Tributary 4A 12.0
END DESCRIPTION:
XS GIS Cut Line= 2
      2354121.65      7053502.53       2355017.9      7053083.19
#Sta/Elev= 30
  4607.3  652.74  4668.7  647.14  4714.4  643.91  4736.9  641.52  4748.2  639.67
  4758.9  638.93  4771.1  639.35  4793.9  636.41  4825.2  633.43  4834.1  631.44
  4847.3  630.87  5132.3  630.62  5132.6  630.12  5136.1  630.12  5136.3  630.62
  5193.2  630.71  5200.6  633.15  5210.5  634.42  5222.6  635.41  5233.4  634.39
  5244.7  634.81  5277.8  637.13  5335.8   642.8  5375.9  643.92  5404.3  645.97
  5443.4  647.06  5478.3  648.98  5495.6   648.9    5524  650.29  5596.8  652.48
#Mann= 3 ,-1 , 0
  4607.3     .05       0  5132.3    .033       0  5136.3     .05       0
Bank Sta=5132.3,5136.3
XS Rating Curve= 0 ,0
Exp/Cntr=0.3,0.1

Type RM Length L Ch R = 1 ,4922    ,43,43,43
BEGIN DESCRIPTION:
Elizabeth Creek Tributary 4A 11.3
END DESCRIPTION:
XS GIS Cut Line= 5
      2354263.12      7053555.95      2354376.58      7053533.79
      2354529.01      7053530.24      2354619.41      7053479.73
      2354785.02      7053341.42
#Sta/Elev= 30
  4677.6  641.31  4765.1  635.06  4905.7  637.07  4953.9   633.7  4959.6  636.64
  4975.6  633.75  4981.3  636.28  4997.3  633.26    5003  636.08    5019  636.11
    5035  631.02  5040.7   635.3  5052.2  633.38  5053.9   628.9  5054.2   628.4
  5057.9   628.9  5062.4  632.92  5070.2  629.78  5076.7  633.65  5084.5  630.21
  5091.1  634.75  5098.9  630.78  5105.4  634.51  5113.2  631.45  5119.7  634.69
    5134  630.65  5140.5  634.36  5148.3  635.52  5226.4   633.1    5265  636.95
#Mann= 3 ,-1 , 0
  4677.6     .05       0  5053.9    .033       0  5057.9     .05       0
Bank Sta=5053.9,5057.9
XS Rating Curve= 0 ,0
Exp/Cntr=0.3,0.1

Type RM Length L Ch R = 1 ,4879    ,152,152,152
BEGIN DESCRIPTION:
Elizabeth Creek Tributary 4A 11.5
END DESCRIPTION:
XS GIS Cut Line= 4
      2354307.49       7053590.5      2354505.09      7053578.98
      2354621.18      7053531.13      2354792.86      7053394.85
#Sta/Elev= 30
  4704.7  637.78  4766.3  634.06  4776.3  633.29  4795.3     630  4800.3  630.47
  4836.4   623.2  4846.5  620.41  4876.5  616.63  4912.7  615.39  4918.1   617.3
  4934.6  615.28  4934.9  614.78  4938.6  615.28    4942  618.81  4950.1  617.11
  4960.6  616.36    4966  620.43  4989.9  617.45  4995.3  620.54  5013.8  618.27
  5019.2  619.34  5024.3  618.21  5034.9  618.38  5140.6  628.54  5148.7  629.77
  5155.1  632.71  5163.1  634.92  5169.5  635.64  5191.4  632.15  5247.4  632.34
#Mann= 3 ,-1 , 0
  4704.7     .05       0  4934.6    .033       0  4938.6     .05       0
Bank Sta=4934.6,4938.6
XS Rating Curve= 0 ,0
Exp/Cntr=0.3,0.1

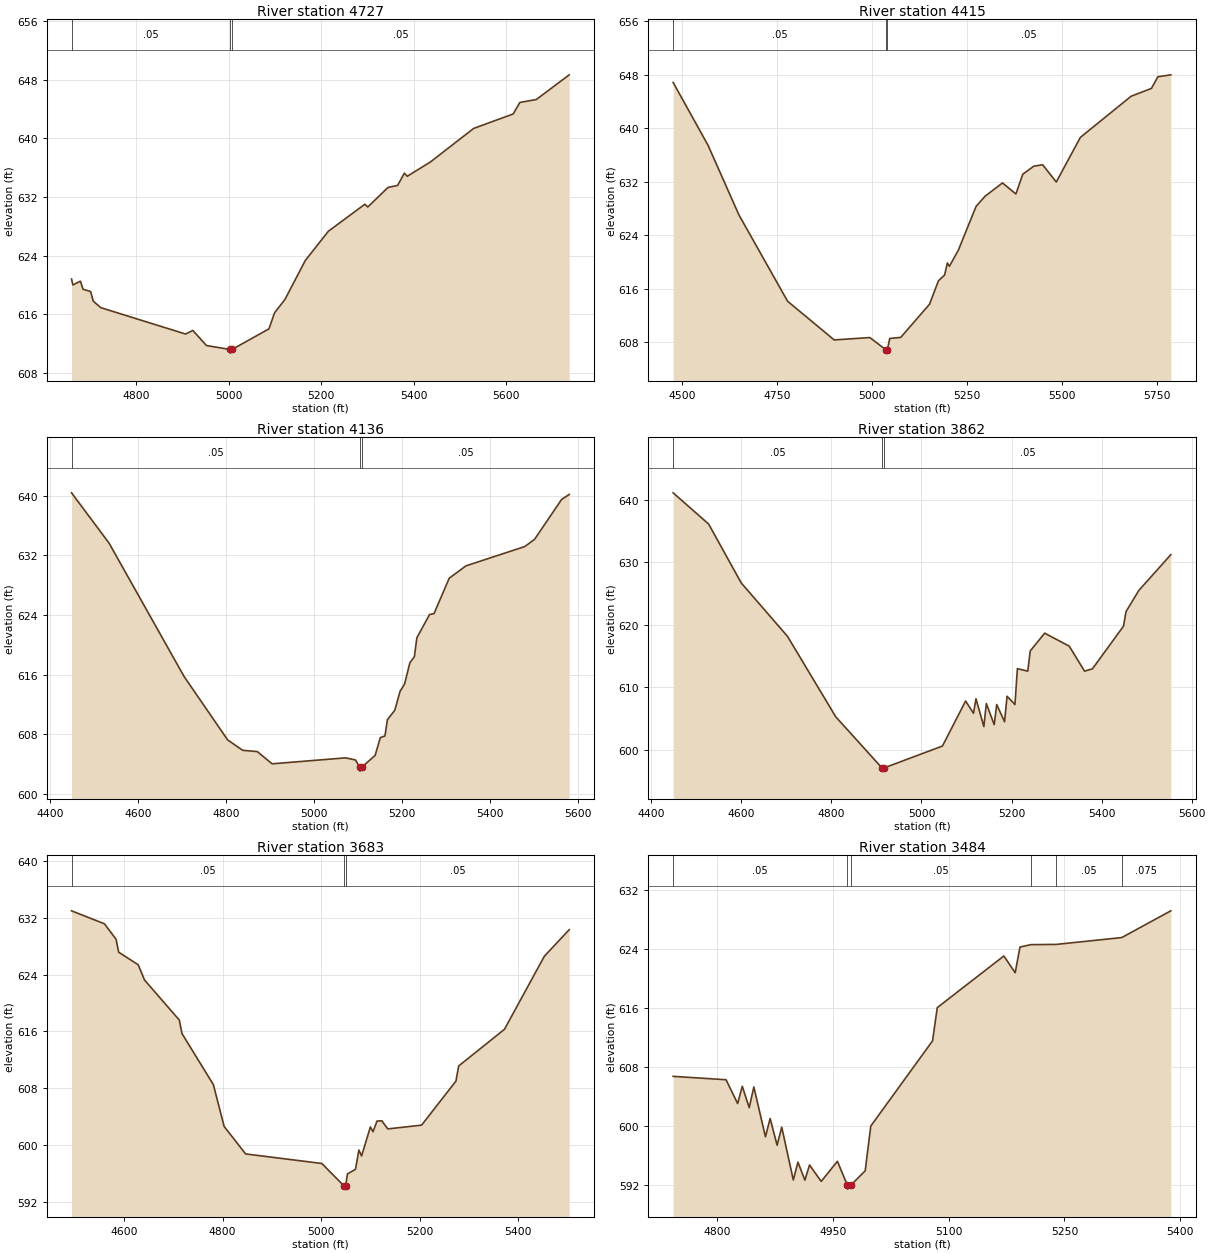
Type RM Length L Ch R = 1 ,4727    ,312,312,312
BEGIN DESCRIPTION:
Elizabeth Creek Tributary 4A 11.0
END DESCRIPTION:
XS GIS Cut Line= 3
      2354360.12      7053835.53      2354763.02      7053625.86
      2355137.12      7053128.43
#Sta/Elev= 30
  4659.7  620.78  4662.5  619.98  4678.9  620.49  4684.6  619.39    4701  619.07
  4706.7  617.76  4723.1  616.87  4906.4  613.27  4922.1  613.76  4951.5   611.7
  5002.9  611.16  5003.1  610.66  5006.9  611.16  5086.8  613.98  5098.9  616.17
  5121.5  618.01  5165.2   623.3  5215.2  627.31  5294.3  631.01  5300.6  630.63
  5344.3   633.3  5365.1  633.58  5379.7  635.25    5386  634.83    5436  636.78
  5529.7  641.37  5615.1  643.34  5629.6  644.92    5665  645.31  5736.3  648.69
#Mann= 3 ,-1 , 0
  4659.7     .05       0  5002.9    .033       0  5006.9     .05       0
Bank Sta=5002.9,5006.9
XS Rating Curve= 0 ,0
Exp/Cntr=0.3,0.1

Type RM Length L Ch R = 1 ,4415    ,279,279,279
BEGIN DESCRIPTION:
Elizabeth Creek Tributary 4A 10.0
END DESCRIPTION:
XS GIS Cut Line= 2
      2354726.02      7054295.98      2355247.36      7053093.21
#Sta/Elev= 30
  4475.9  646.87  4567.8  637.48  4649.1  627.08  4777.3  614.17  4900.2  608.38
    4994  608.74  5036.3  606.91  5036.5  606.41  5040.3  606.91  5046.4   608.6
  5075.4  608.76  5151.2  613.72  5174.7  617.22  5190.9  618.08  5198.2  619.89
  5203.6  619.39  5227.1  621.79    5274  628.36  5297.5  629.86  5343.4  631.85
  5378.8   630.2  5396.8  633.15  5425.8  634.35  5449.2  634.57  5485.1  631.99
  5548.6  638.66  5682.3  644.81  5735.8  645.98  5752.7  647.72  5786.8  648.01
#Mann= 3 ,-1 , 0
  4475.9     .05       0  5036.3    .033       0  5040.3     .05       0
Bank Sta=5036.3,5040.3
XS Rating Curve= 0 ,0
Exp/Cntr=0.3,0.1

Type RM Length L Ch R = 1 ,4136    ,274,274,274
BEGIN DESCRIPTION:
Elizabeth Creek Tributary 4A 9.0
END DESCRIPTION:
XS GIS Cut Line= 3
      2354882.23      7054304.23      2355133.03      7054016.43
      2355470.15       7053346.3
#Sta/Elev= 30
  4448.2  640.38  4533.5  633.64  4704.4  615.74  4803.2  607.27  4837.4  605.87
  4870.7   605.7  4904.4  604.06  5071.8  604.86  5094.1  604.57  5103.8  603.58
  5104.1  603.08  5107.8  603.58  5138.7  605.19  5150.6  607.58    5161  607.79
  5166.6  609.97  5183.4  611.24  5195.4  613.77  5205.7  614.76  5217.7   617.6
    5228  618.43  5233.6  620.95  5262.5  624.07  5272.6  624.19  5307.3  628.94
  5345.2  630.59  5479.1  633.18  5501.4  634.15  5562.8  639.49  5580.1  640.16
#Mann= 3 ,-1 , 0
  4448.2     .05       0  5103.8    .033       0  5107.8     .05       0
Bank Sta=5103.8,5107.8
XS Rating Curve= 0 ,0
Exp/Cntr=0.3,0.1

Type RM Length L Ch R = 1 ,3862    ,179,179,179
BEGIN DESCRIPTION:
Elizabeth Creek Tributary 4A 8.0
END DESCRIPTION:
XS GIS Cut Line= 3
      2354919.22      7054337.11      2355359.14      7054073.98
      2355605.83       7053535.4
#Sta/Elev= 30
  4448.7  641.08  4527.5  636.09  4599.9  626.67  4702.5  618.14  4809.7  605.27
  4912.5  597.08  4912.8  596.58  4916.5  597.08  5046.6  600.59  5098.1  607.79
  5115.6  605.83  5121.1  608.15  5138.6  603.71  5144.1  607.39  5161.6  604.01
  5167.1  607.23  5184.6  604.48  5190.1  608.55  5207.6  607.23  5213.1  612.97
  5236.1  612.57  5241.6   615.8  5273.7  618.64  5328.2  616.56  5362.2  612.57
  5379.7  612.94  5448.7  619.76  5454.2  622.08  5482.7  625.47  5553.7  631.19
#Mann= 3 ,-1 , 0
  4448.7     .05       0  4912.5    .033       0  4916.5     .05       0
Bank Sta=4912.5,4916.5
XS Rating Curve= 0 ,0
Exp/Cntr=0.3,0.1

Type RM Length L Ch R = 1 ,3683    ,199,199,199
BEGIN DESCRIPTION:
Elizabeth Creek Tributary 4A 7.0
END DESCRIPTION:
XS GIS Cut Line= 3
      2355124.84      7054382.31      2355486.59       7054226.1
       2355736.9      7053663.94
#Sta/Elev= 30
  4493.8  633.03  4560.5   631.2    4584  629.03  4589.4  627.19    4629  625.42
  4641.9  623.26  4712.4  617.61  4717.8  615.71  4781.5  608.49  4803.3   602.6
  4846.9  598.72  5001.4  597.37  5045.8  594.25    5046  593.75  5049.8  594.25
  5053.4   595.9  5069.7  596.54  5076.6  599.26  5082.1  598.43  5099.9  602.53
  5105.3  601.85  5113.4  603.36  5123.1  603.39  5135.3  602.25  5203.8  602.78
  5273.5     609    5279  611.13  5371.9  616.31  5452.8  626.62  5503.2  630.37
#Mann= 3 ,-1 , 0
  4493.8     .05       0  5045.8    .033       0  5049.8     .05       0
Bank Sta=5045.8,5049.8
XS Rating Curve= 0 ,0
Exp/Cntr=0.5,0.3

Type RM Length L Ch R = 1 ,3484    ,405,405,405
BEGIN DESCRIPTION:
Elizabeth Creek Tributary 4A 6.0
END DESCRIPTION:
XS GIS Cut Line= 3
      2355466.05      7054382.32      2355700.37       7054226.1
      2355910.06      7053930.07
#Sta/Elev= 30
  4743.4  606.76  4811.9   606.3  4826.9  603.07  4832.9  605.41  4841.9  602.51
  4847.9  605.32  4862.9  598.56    4869  601.04    4878  597.41    4884  599.86
    4899  592.69    4905  595.11    4914  592.67    4920  594.73  4935.1   592.5
  4956.1  595.23  4969.1  591.95  4969.4  591.45  4973.1  591.95  4992.1  593.94
  4999.3  600.01  5079.3  611.58  5085.4  616.09  5171.6   623.1  5186.3  620.83
  5192.5  624.31  5206.5  624.64  5239.2  624.67  5324.3   625.6  5387.8  629.23
#Mann= 6 ,-1 , 0
  4743.4     .05       0  4969.1     .05       0  4973.1     .05       0
  5206.5    .075       0  5239.2     .05       0  5324.3    .075       0
Bank Sta=4969.1,4973.1
XS Rating Curve= 0 ,0
Exp/Cntr=0.5,0.3

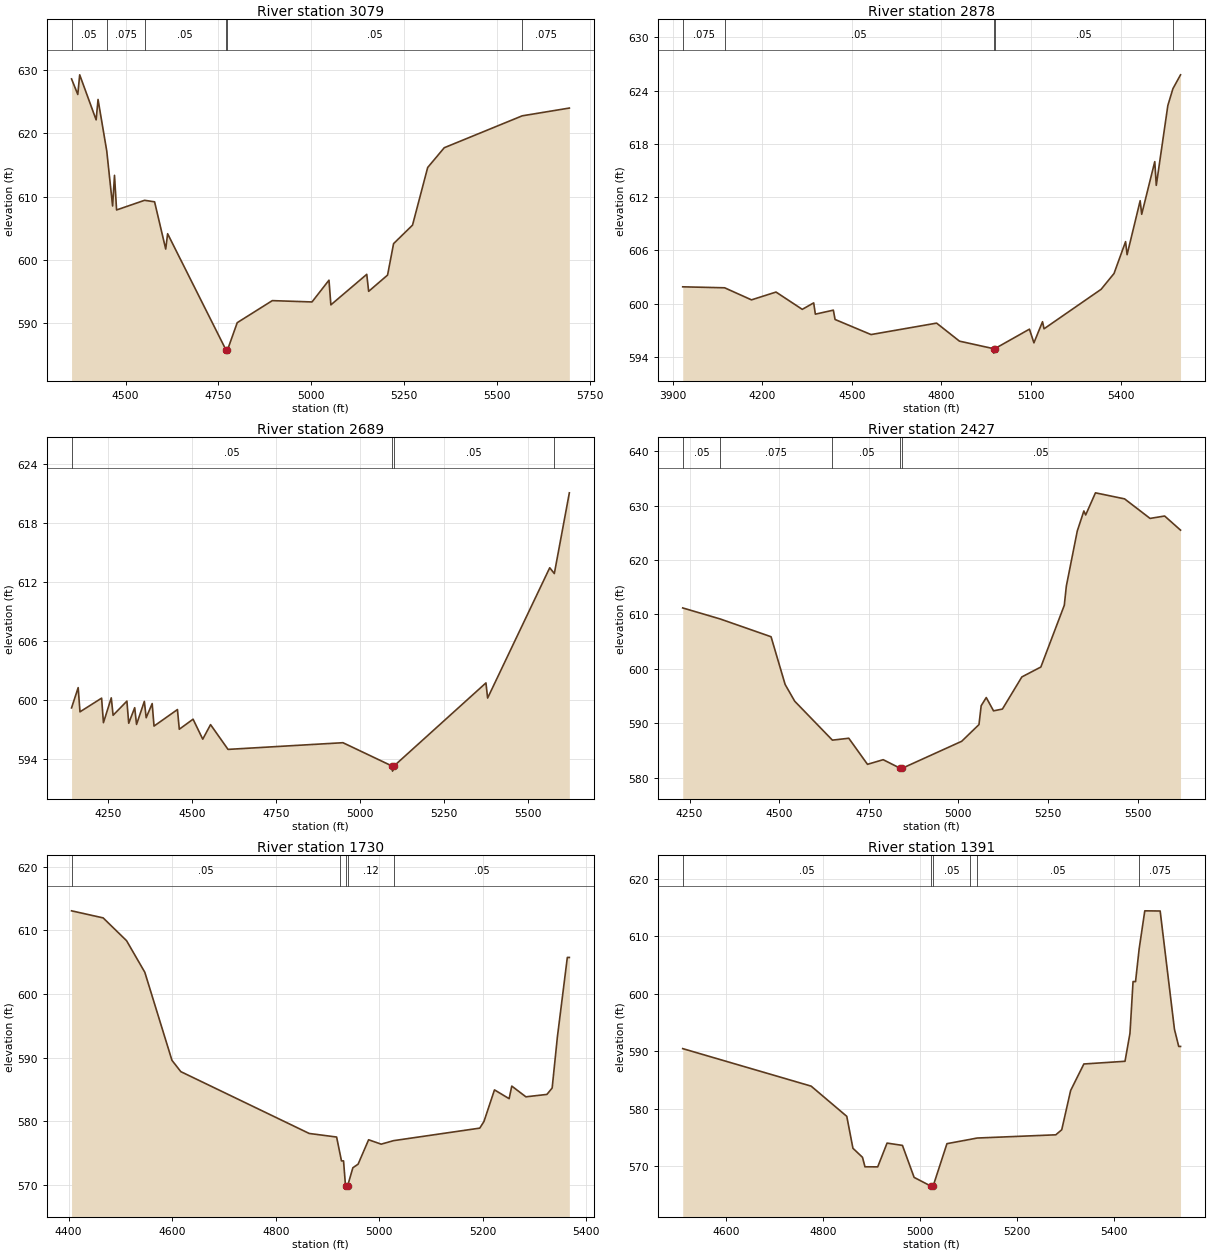
Type RM Length L Ch R = 1 ,3079    ,201,201,201
BEGIN DESCRIPTION:
Elizabeth Creek Tributary 4A 5.0
END DESCRIPTION:
XS GIS Cut Line= 3
      2355020.46      7054769.13        2355529.        7054660.
      2356332.89      7054498.31
#Sta/Elev= 30
  4354.6  628.62  4371.4  626.16  4376.5  629.27  4420.8  622.14  4425.9  625.37
  4449.4   617.2  4465.1  608.51  4470.2  613.36  4475.8  607.88  4551.2  609.41
  4578.1  609.17  4608.1  601.69  4613.2  604.12  4770.4  585.72  4770.7  585.22
  4774.4  585.72  4800.6  590.04    4895  593.53  5001.9  593.32  5047.6  596.77
  5052.7  592.86  5149.3  597.69  5154.4     595  5205.3  597.57  5221.5  602.55
  5272.5  605.48  5313.3   614.6  5357.9  617.73  5567.8  622.78  5694.7  624.01
#Mann= 6 ,-1 , 0
  4354.6     .05       0  4449.4    .075       0  4551.2     .05       0
  4770.4    .033       0  4774.4     .05       0  5567.8    .075       0
Bank Sta=4770.4,4774.4
XS Rating Curve= 0 ,0
Exp/Cntr=0.3,0.1

Type RM Length L Ch R = 1 ,2878    ,189,189,189
BEGIN DESCRIPTION:
Elizabeth Creek Tributary 4A 4.4
END DESCRIPTION:
XS GIS Cut Line= 3
      2354680.19      7055283.01      2355437.09      7054880.25
      2356228.79      7054706.63
#Sta/Elev= 30
    3933   601.9  4073.4  601.79  4163.4  600.43  4245.6  601.31  4333.5  599.36
  4371.8  600.09  4377.4  598.82  4437.7  599.27  4443.4  598.22  4563.9  596.52
  4783.6  597.81  4860.2  595.78  4974.6  594.93  4974.9  594.43  4978.6  594.93
  5094.7  597.13  5109.7  595.59  5138.5  597.97  5143.6  597.17  5334.9  601.62
  5378.1   603.4  5416.8  606.99  5421.9  605.52  5465.7   611.6  5470.8  610.07
  5514.6     616  5519.7  613.33  5558.4  622.32  5575.3  624.21  5600.9  625.78
#Mann= 5 ,-1 , 0
    3933    .075       0  4073.4     .05       0  4974.6    .033       0
  4978.6     .05       0  5575.3    .075       0
Bank Sta=4974.6,4978.6
XS Rating Curve= 0 ,0
Exp/Cntr=0.3,0.1

Type RM Length L Ch R = 1 ,2689    ,262,262,262
BEGIN DESCRIPTION:
Elizabeth Creek Tributary 4A 4.2
END DESCRIPTION:
XS GIS Cut Line= 3
      2354846.78      7055373.32      2355721.82      7054984.42
       2356242.6      7054928.87
#Sta/Elev= 30
  4141.8  599.17  4161.5  601.23  4166.9  598.77  4231.2  600.16  4236.7  597.67
    4260  600.19  4265.4  598.42  4306.5  599.86  4311.9  597.61  4329.7  599.19
  4335.2  597.49  4358.4  599.83  4363.9  598.17  4381.7  599.61  4387.2  597.32
  4456.9     599  4462.4     597  4503.4  598.02  4532.2  595.99  4555.4  597.47
  4607.4  594.95  4949.4  595.63  5096.6  593.24  5096.9  592.74  5100.6  593.24
  5374.9  601.71  5379.9  600.17  5564.7  613.42  5578.4  612.83  5623.1  621.04
#Mann= 4 ,-1 , 0
  4141.8     .05       0  5096.6    .033       0  5100.6     .05       0
  5578.4    .075       0
Bank Sta=5096.6,5100.6
XS Rating Curve= 0 ,0
Exp/Cntr=0.3,0.1

Type RM Length L Ch R = 1 ,2427    ,697,697,697
BEGIN DESCRIPTION:
Elizabeth Creek Tributary 4A 4.0
END DESCRIPTION:
XS GIS Cut Line= 3
      2354895.46      7055505.24       2355610.7      7055289.97
      2356242.67      7055178.86
#Sta/Elev= 30
    4231   611.2  4335.7  609.17  4477.4  605.91  4516.7  597.14  4543.4  594.07
  4648.5  586.92  4694.2  587.27  4746.4  582.48  4790.2  583.33  4838.4  581.73
  4838.6  581.23  4842.4  581.73  5009.2  586.71  5057.4  589.78  5063.5  593.24
  5077.7  594.74    5098   592.3  5122.8  592.63    5177  598.53    5230  600.35
  5295.4  611.69  5301.1  615.22  5331.6  625.33    5350  629.01    5355  628.27
  5382.3  632.34  5463.6  631.23  5534.6  627.64  5575.3  628.08  5619.6  625.49
#Mann= 5 ,-1 , 0
    4231     .05       0  4335.7    .075       0  4648.5     .05       0
  4838.4    .033       0  4842.4     .05       0
Bank Sta=4838.4,4842.4
XS Rating Curve= 0 ,0
Exp/Cntr=0.3,0.1

Type RM Length L Ch R = 1 ,1730    ,339,339,339
BEGIN DESCRIPTION:
Elizabeth Creek Tributary 4A 3.0
END DESCRIPTION:
XS GIS Cut Line= 3
       2355062.1      7055748.31      2355541.26      7055963.58
       2355971.8      7056033.03
#Sta/Elev= 30
  4405.7  613.08  4466.7  611.97  4511.9  608.39  4547.2  603.42  4599.6  589.58
  4616.7   587.8  4864.7  578.08  4917.6  577.52  4924.2  574.89    4927  573.77
    4931  573.77  4934.8  569.83  4935.1  569.33  4938.8  569.83    4949  572.69
  4959.1  573.25  4979.4  577.09  5003.7   576.4  5027.6  576.95  5194.1  578.92
  5202.2  579.97  5222.5  584.93  5250.8  583.55  5255.9  585.53  5283.2  583.84
  5323.8  584.22  5333.9  585.23    5344  593.26  5363.2  605.75  5367.1  605.75
#Mann= 5 ,-1 , 0
  4405.7     .05       0  4924.2     .12       0  4934.8     .07       0
  4938.8     .12       0  5027.6     .05       0
Bank Sta=4934.8,4938.8
XS Rating Curve= 0 ,0
Exp/Cntr=0.3,0.1

Type RM Length L Ch R = 1 ,1391    ,1219,1219,1219
BEGIN DESCRIPTION:
Elizabeth Creek Tributary 4A 2.0
END DESCRIPTION:
XS GIS Cut Line= 3
      2355076.02      7056081.66      2355388.48       7056262.2
      2356041.22      7056394.13
#Sta/Elev= 30
  4510.7  590.48  4775.6  583.96  4849.1  578.71  4861.8  573.16  4881.5  571.59
  4886.6  569.94  4912.9  569.93  4932.2  574.06  4963.9  573.66    4988   568.1
  5023.1  566.56  5023.4  566.06  5027.1  566.56  5055.7  573.96  5103.7  574.71
    5118  574.94  5280.2   575.5  5292.5  576.38  5310.8  583.19  5338.1  587.81
    5423  588.28  5433.2  593.13  5439.6  602.14  5444.7  602.12  5452.2  607.84
  5463.8  614.43  5495.5   614.4    5525  593.83  5533.8  590.86  5537.5  590.86
#Mann= 6 ,-1 , 0
  4510.7     .05       0  5023.1    .033       0  5027.1     .05       0
  5103.7     .12       0    5118     .05       0  5452.2    .075       0
Bank Sta=5023.1,5027.1
XS Rating Curve= 0 ,0
Exp/Cntr=0.3,0.1

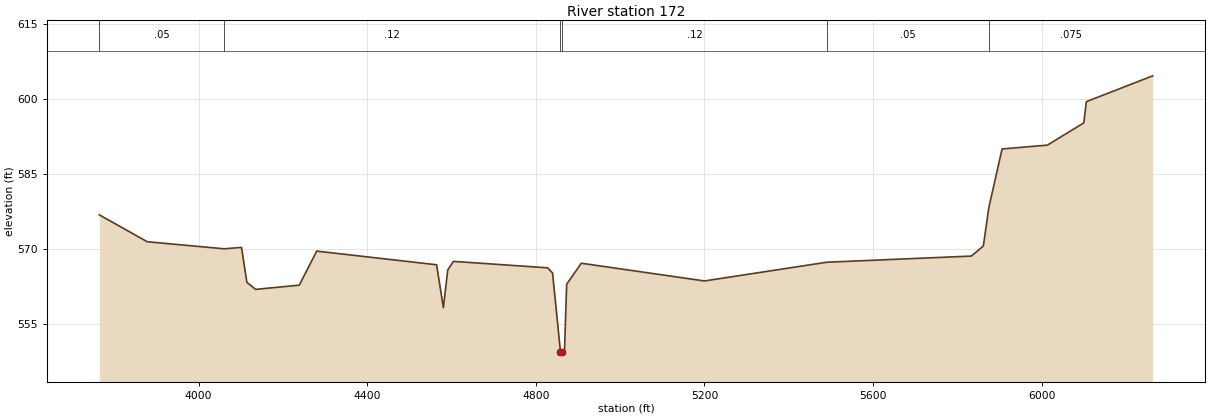
Type RM Length L Ch R = 1 ,172     ,0,0,0
BEGIN DESCRIPTION:
Elizabeth Creek Tributary 4A 1.0
END DESCRIPTION:
XS GIS Cut Line= 3
      2355055.14      7056262.16      2355374.59      7057442.75
      2356422.17       7056714.3
#Sta/Elev= 30
  3764.4  576.85  3878.1  571.48  4060.4  570.07  4101.7  570.35  4114.4  563.37
  4135.1  561.97  4238.7  562.81  4280.1  569.61  4564.5  566.88  4580.6  558.31
  4590.9  565.83  4604.4  567.56    4828  566.27  4839.6  565.23  4858.3  549.54
  4858.5  549.04  4862.3  549.54  4867.9  549.73  4873.1     563  4907.8  567.19
  5199.9  563.65  5490.2  567.39  5833.2  568.62  5861.5  570.63  5874.7  578.35
    5906  590.01  6013.4  590.77  6099.8  595.21  6105.9  599.45  6263.4  604.61
#Mann= 6 ,-1 , 0
  3764.4     .05       0  4060.4     .12       0  4858.3     .07       0
  4862.3     .12       0  5490.2     .05       0  5874.7    .075       0
Bank Sta=4858.3,4862.3
XS Rating Curve= 0 ,0
Exp/Cntr=0.3,0.1

Chan Stop Cuts=-1
Use User Specified Reach Order=0
Composite Channel Slope=5