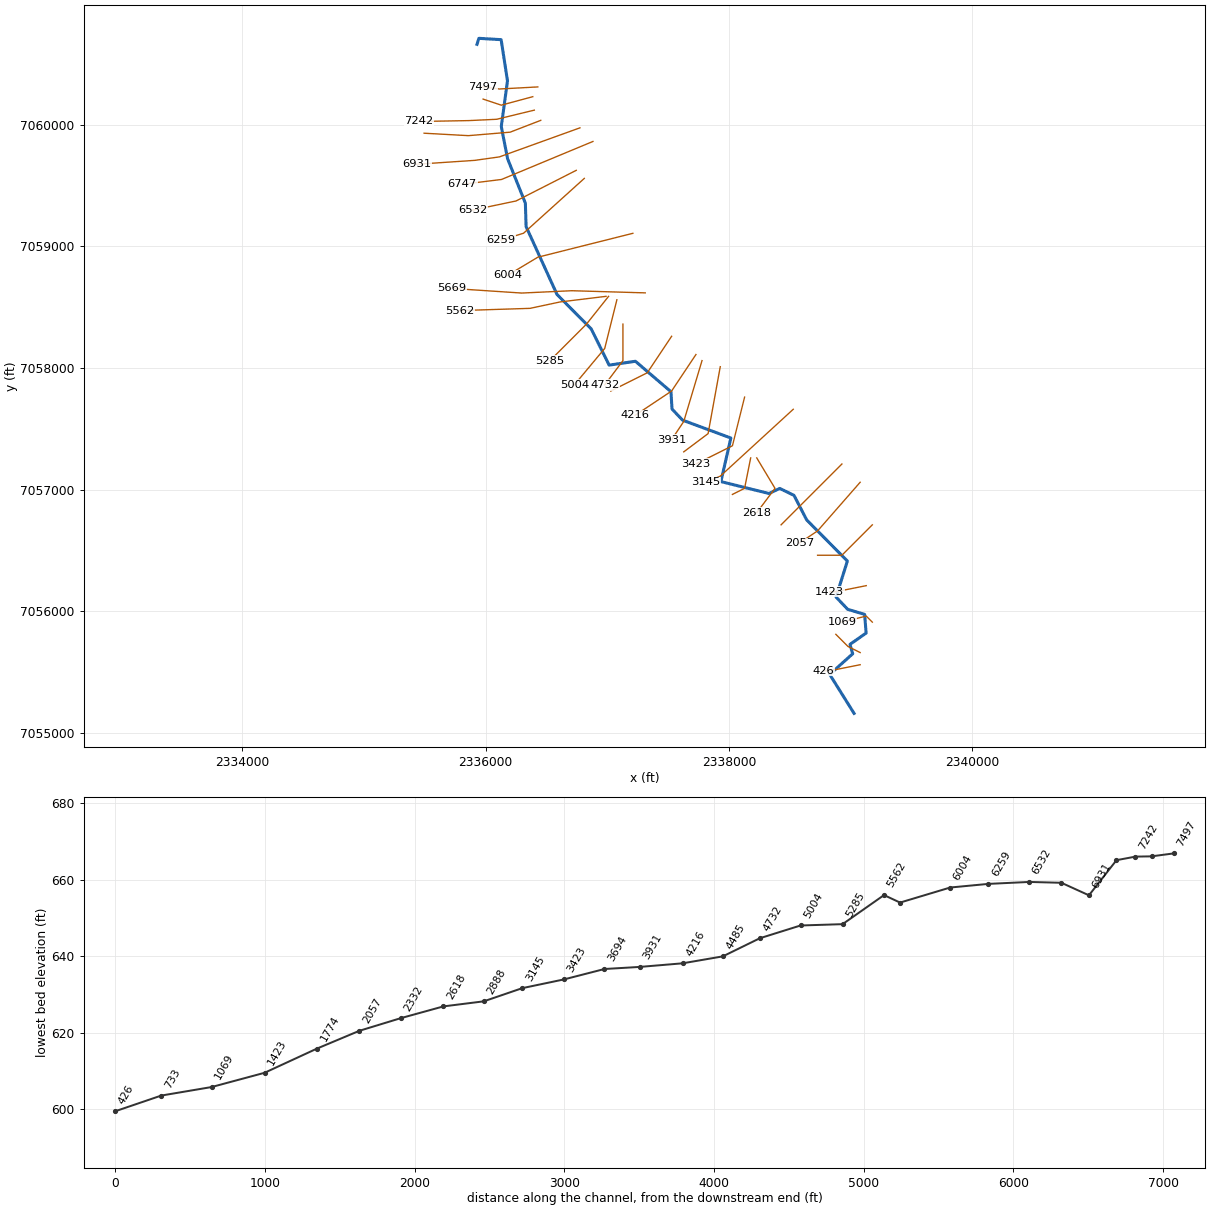
--- Elizabeth Cr Tr 7.prj (project) ---

Proj Title=Elizabeth Cr Tr 7 Base Level Engineering
Current Plan=p01
Default Exp/Contr=0.3,0.1
English Units
Geom File=g01
Flow File=f01
Plan File=p01
BEGIN DESCRIPTION:
Elizabeth Cr Tr 7
END DESCRIPTION:

--- Elizabeth Cr Tr 7.p01 (plan) ---

Plan Title=Multiple Run
Short Identifier=Multiple
Geom File=g01
Flow File=f01
Subcritical Flow
K Sum by GR= 0
Std Step Tol= 0.01
Critical Tol= 0.01
Num of Std Step Trials= 20
Max Error Tol= 0.3
Flow Tol Ratio= 0.001
Split Flow NTrial= 30
Split Flow Tol= 0.02
Split Flow Ratio= 0.02
Log Output Level= 0
Friction Slope Method= 1
Unsteady Friction Slope Method= 2
Unsteady Bridges Friction Slope Method= 1
Parabolic Critical Depth
Global Vel Dist=  1 , 1 , 1
Global Log Level= 0
CheckData=True
Encroach Param= -1, 0, 0, 0
BEGIN DESCRIPTION:
Multiple Run
END DESCRIPTION:

--- Elizabeth Cr Tr 7.f01 (steady flow) ---

Flow Title=Multiple
Number of Profiles=7
Profile Names=10-year,25-year,50-year,1pct_min,100-year,1pct_plu,500-year
River Rch & RM= Elizabeth Cr Tr ,Reach-1,7497
     343     452     540     320     639    1270     897
River Rch & RM= Elizabeth Cr Tr ,Reach-1,1423
     357     472     565     336     670    1340     944
Boundary for River Rch & Prof#=Elizabeth Cr Tr ,Reach-1,1
Up Type=0
Dn Type=3
Dn Slope=0.005
Boundary for River Rch & Prof#=Elizabeth Cr Tr ,Reach-1,2
Up Type=0
Dn Type=3
Dn Slope=0.005
Boundary for River Rch & Prof#=Elizabeth Cr Tr ,Reach-1,3
Up Type=0
Dn Type=3
Dn Slope=0.005
Boundary for River Rch & Prof#=Elizabeth Cr Tr ,Reach-1,4
Up Type=0
Dn Type=3
Dn Slope=0.005
Boundary for River Rch & Prof#=Elizabeth Cr Tr ,Reach-1,5
Up Type=0
Dn Type=3
Dn Slope=0.005
Boundary for River Rch & Prof#=Elizabeth Cr Tr ,Reach-1,6
Up Type=0
Dn Type=3
Dn Slope=0.005
Boundary for River Rch & Prof#=Elizabeth Cr Tr ,Reach-1,7
Up Type=0
Dn Type=3
Dn Slope=0.005

--- Elizabeth Cr Tr 7.g01 (geometry) ---

Geom Title=Existing Conditions

River Reach=Elizabeth Cr Tr ,Reach-1
Reach XY= 30
      2335929.00      7060660.00      2335944.62      7060709.39
      2336127.52      7060698.52      2336179.82      7060360.00
      2336128.80      7059984.92      2336180.22      7059720.50
      2336326.74      7059354.06      2336332.75      7059161.55
      2336586.86      7058603.83      2336868.54      7058320.04
      2337015.37      7058022.95      2337231.43      7058054.60
      2337523.45      7057804.41      2337532.54      7057661.46
      2337619.19      7057570.51      2338016.05      7057423.64
      2337934.16      7057065.41      2338329.01      7056967.59
      2338418.30      7057009.20      2338535.33      7056951.94
      2338639.53      7056750.25      2338973.91      7056412.30
      2338880.96      7056115.88      2338976.56      7056015.52
      2339115.81      7055973.73      2339128.03      7055820.29
      2338995.24      7055727.04      2339017.76      7055649.98
      2338828.50      7055480.23      2339029.00      7055160.00

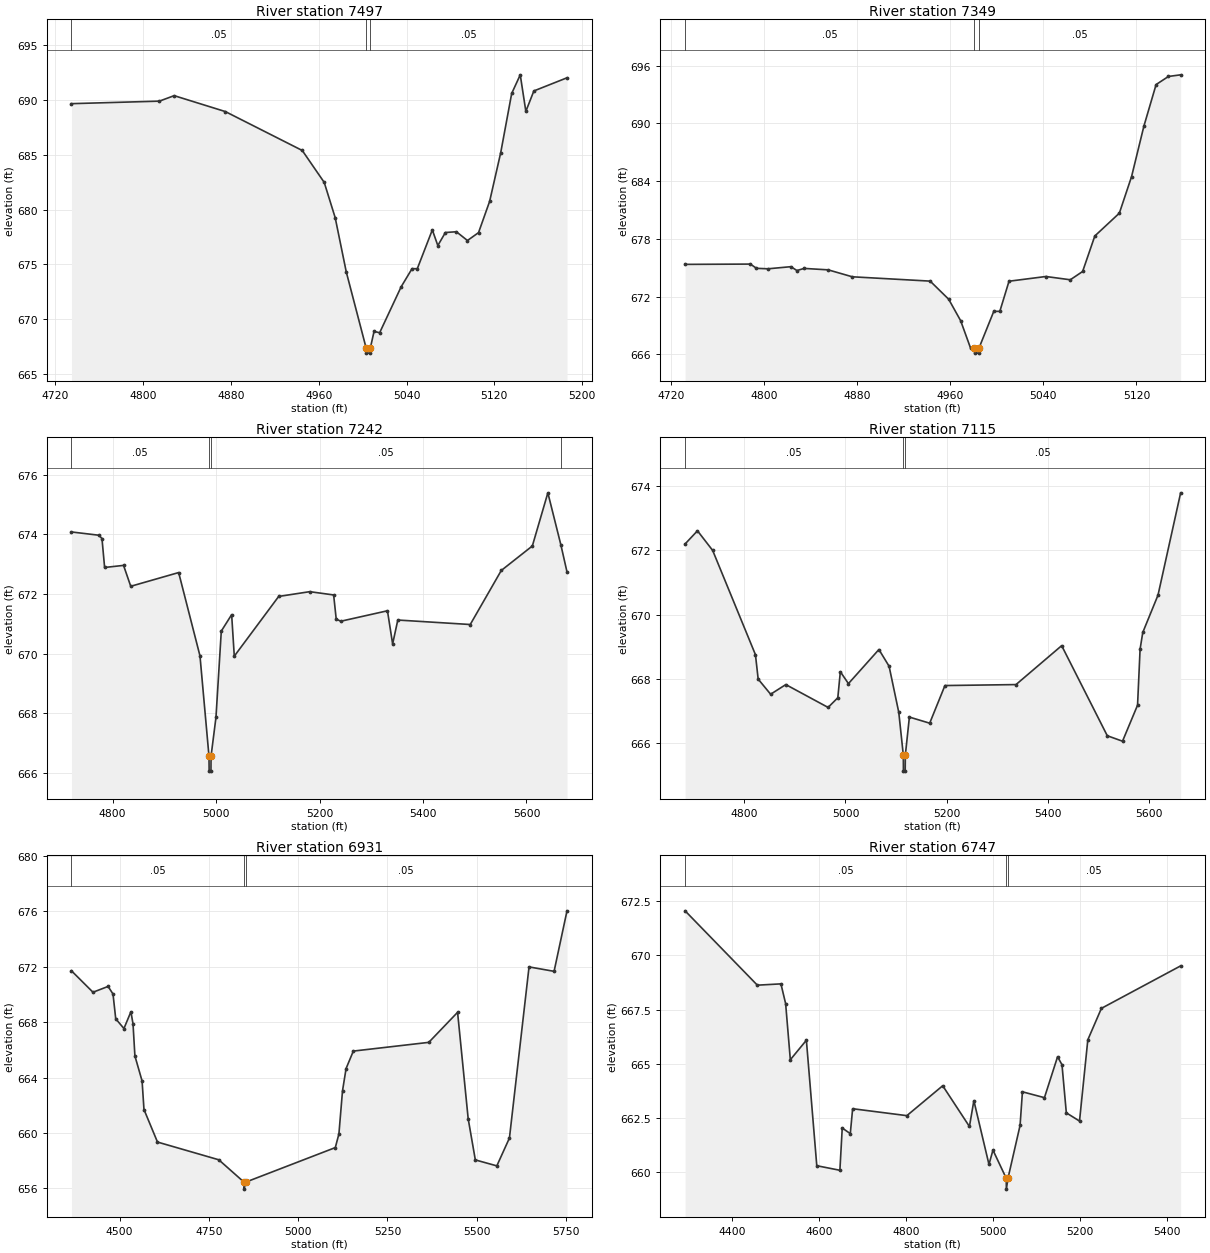
Type RM Length L Ch R = 1,7497,148,148,148
BEGIN DESCRIPTION:
Elizabeth Creek Tributary 7 23.0
END DESCRIPTION:
XS GIS Cut Line= 3
      2336428.99      7060310.00      2336114.32      7060292.88
      2335979.03      7060310.00
#Sta/Elev= 30
  4734.7  689.66  4814.8  689.89  4828.3  690.39  4874.9  688.94  4945.0  685.39
  4965.0  682.48  4975.0  679.26  4985.1  674.31  5003.1  667.41  5003.3  666.91
  5006.8  666.91  5007.1  667.41  5010.4  668.89  5015.5  668.77  5035.1  672.96
  5045.0  674.61  5049.8  674.61  5063.5  678.15  5068.5  676.72  5075.4  677.91
  5085.4  677.98  5095.5  677.18  5105.6  677.90  5115.7  680.75  5125.8  685.19
  5135.8  690.59  5143.6  692.29  5148.7  688.96  5156.0  690.82  5186.2  692.02
#Mann=3,-1,0
  4734.7    0.05       0  5003.1   0.033       0  5007.1    0.05       0
Bank Sta=5003.1,5007.1
Exp/Cntr=0.3,0.1

Type RM Length L Ch R = 1,7349,107,107,107
BEGIN DESCRIPTION:
Elizabeth Creek Tributary 7 22.0
END DESCRIPTION:
XS GIS Cut Line= 3
      2336387.87      7060229.74      2336129.00      7060160.00
      2335979.01      7060210.00
#Sta/Elev= 30
  4731.8  675.36  4788.0  675.39  4793.2  674.95  4803.1  674.90  4822.8  675.12
  4828.0  674.72  4834.2  674.94  4854.9  674.79  4875.6  674.07  4942.6  673.62
  4958.5  671.74  4968.8  669.51  4977.3  666.67  4980.5  666.64  4980.8  666.14
  4984.3  666.14  4984.5  666.64  4997.3  670.48  5002.5  670.48  5010.4  673.61
  5042.1  674.10  5063.1  673.76  5073.7  674.62  5084.2  678.31  5105.3  680.68
  5115.8  684.48  5126.4  689.72  5136.9  694.04  5147.5  694.88  5158.0  695.05
#Mann=3,-1,0
  4731.8    0.05       0  4980.5   0.033       0  4984.5    0.05       0
Bank Sta=4980.5,4984.5
Exp/Cntr=0.3,0.1

Type RM Length L Ch R = 1,7242,127,127,127
BEGIN DESCRIPTION:
1005
END DESCRIPTION:
XS GIS Cut Line= 4
      2336400.39      7060119.14      2336091.05      7060044.01
      2335861.58      7060033.09      2335452.01      7060025.79
#Sta/Elev= 30
  4720.6  674.08  4773.5  673.97  4779.6  673.86  4784.7  672.89  4821.3  672.96
  4835.2  672.26  4927.8  672.72  4969.0  669.93  4986.4  666.57  4986.7  666.07
  4990.2  666.07  4990.4  666.57  4999.9  667.87  5010.2  670.76  5030.2  671.31
  5035.3  669.92  5121.1  671.92  5181.1  672.08  5227.3  671.97  5232.3  671.16
  5241.2  671.09  5331.3  671.44  5341.3  670.33  5351.3  671.13  5491.3  670.98
  5551.3  672.79  5611.3  673.61  5641.3  675.39  5666.4  673.65  5678.3  672.74
#Mann=4,-1,0
  4720.6    0.05       0  4986.4   0.033       0  4990.4    0.05       0
  5666.4   0.075       0
Bank Sta=4986.4,4990.4
Exp/Cntr=0.3,0.1

Type RM Length L Ch R = 1,7115,184,184,184
BEGIN DESCRIPTION:
1004
END DESCRIPTION:
XS GIS Cut Line= 4
      2336453.38      7060035.18      2336201.51      7059937.97
      2335858.67      7059909.40      2335494.33      7059929.41
#Sta/Elev= 30
  4683.2  672.20  4707.7  672.61  4737.7  672.00  4822.2  668.76  4827.6  668.00
  4852.2  667.53  4882.2  667.83  4965.7  667.12  4984.9  667.42  4989.9  668.23
  5005.9  667.86  5066.1  668.92  5086.2  668.40  5105.3  666.97  5114.3  665.64
  5114.5  665.14  5118.0  665.14  5118.3  665.64  5126.3  666.82  5166.4  666.63
  5196.5  667.80  5336.9  667.83  5427.1  669.04  5517.2  666.24  5547.3  666.07
  5577.0  667.19  5582.0  668.93  5587.3  669.45  5617.4  670.61  5662.1  673.79
#Mann=3,-1,0
  4683.2    0.05       0  5114.3   0.033       0  5118.3    0.05       0
Bank Sta=5114.3,5118.3
Exp/Cntr=0.3,0.1

Type RM Length L Ch R = 1,6931,184,184,184
BEGIN DESCRIPTION:
1003
END DESCRIPTION:
XS GIS Cut Line= 4
      2336775.64      7059973.69      2336113.14      7059734.72
      2335910.57      7059706.19      2335432.89      7059674.27
#Sta/Elev= 30
  4365.3  671.71  4425.6  670.16  4468.0  670.58  4481.7  670.03  4489.3  668.24
  4512.3  667.54  4531.8  668.75  4537.7  667.88  4543.0  665.56  4563.1  663.75
  4568.4  661.69  4606.2  659.34  4777.8  658.06  4848.7  656.44  4849.0  655.94
  4852.7  656.44  5104.1  658.94  5114.2  659.92  5124.3  663.04  5134.3  664.65
  5154.6  665.91  5365.9  666.54  5446.5  668.71  5476.2  661.02  5496.2  658.05
  5556.4  657.62  5591.7  659.63  5646.6  671.99  5716.7  671.67  5752.9  676.04
#Mann=3,-1,0
  4365.3    0.05       0  4848.7   0.033       0  4852.7    0.05       0
Bank Sta=4848.7,4852.7
Exp/Cntr=0.3,0.1

Type RM Length L Ch R = 1,6747,215,215,215
BEGIN DESCRIPTION:
1002
END DESCRIPTION:
XS GIS Cut Line= 3
      2336882.37      7059861.69      2336130.82      7059549.15
      2335808.31      7059509.39
#Sta/Elev= 30
  4292.3  672.06  4458.4  668.63  4512.6  668.69  4523.4  667.78  4534.2  665.19
  4571.1  666.09  4595.0  660.30  4648.1  660.09  4653.5  662.04  4672.0  661.78
  4677.4  662.93  4802.0  662.61  4884.4  663.99  4945.8  662.11  4956.0  663.30
  4990.7  660.36  4999.9  661.02  5030.4  659.72  5030.7  659.22  5034.4  659.72
  5062.2  662.16  5067.6  663.71  5118.2  663.44  5148.4  665.33  5158.5  664.96
  5168.5  662.74  5198.8  662.36  5217.9  666.11  5249.1  667.56  5431.2  669.52
#Mann=3,-1,0
  4292.3    0.05       0  5030.4   0.033       0  5034.4    0.05       0
Bank Sta=5030.4,5034.4
Exp/Cntr=0.3,0.1

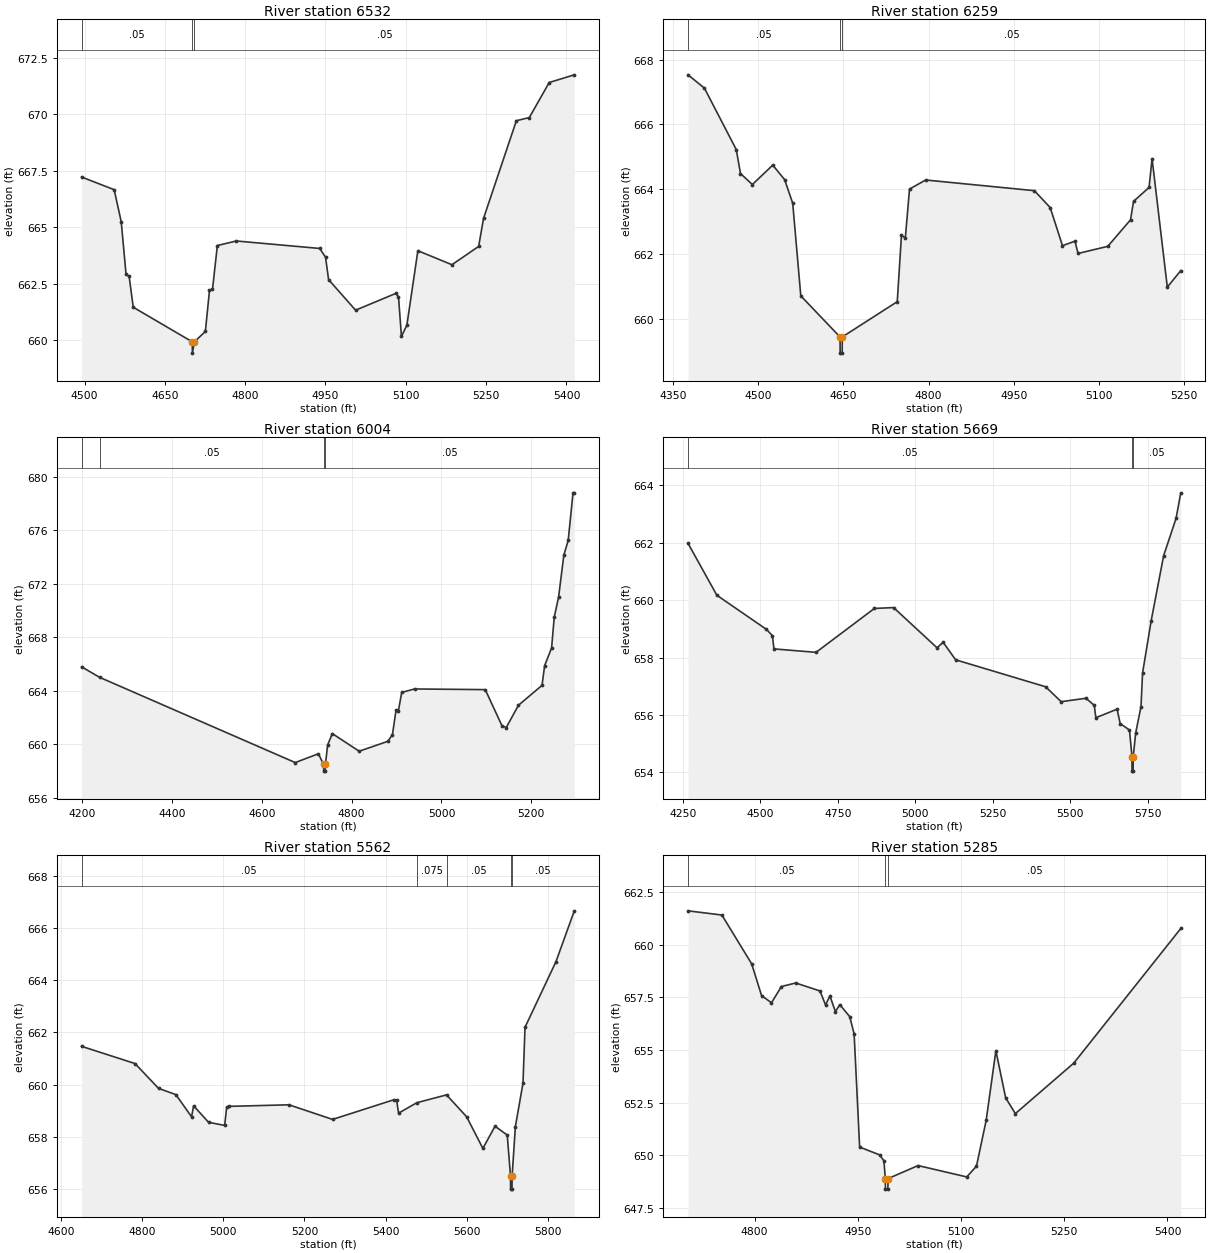
Type RM Length L Ch R = 1,6532,273,273,273
BEGIN DESCRIPTION:
1001
END DESCRIPTION:
XS GIS Cut Line= 3
      2336745.02      7059624.28      2336250.12      7059372.41
      2335893.11      7059297.48
#Sta/Elev= 30
  4494.5  667.23  4555.4  666.67  4568.6  665.25  4577.6  662.92  4583.3  662.84
  4591.0  661.47  4701.2  659.94  4701.5  659.44  4705.2  659.94  4725.7  660.40
  4733.4  662.22  4739.0  662.26  4748.1  664.20  4783.5  664.40  4939.2  664.07
  4950.1  663.68  4955.8  662.69  5006.2  661.34  5081.2  662.08  5086.3  661.94
  5091.8  660.18  5102.0  660.68  5122.5  663.97  5186.1  663.35  5236.0  664.16
  5245.1  665.40  5306.4  669.72  5330.6  669.86  5367.7  671.41  5414.6  671.75
#Mann=3,-1,0
  4494.5    0.05       0  4701.2   0.033       0  4705.2    0.05       0
Bank Sta=4701.2,4705.2
Exp/Cntr=0.3,0.1

Type RM Length L Ch R = 1,6259,255,255,255
BEGIN DESCRIPTION:
1000
END DESCRIPTION:
XS GIS Cut Line= 3
      2336811.26      7059557.99      2336311.97      7059107.30
      2336126.38      7059049.86
#Sta/Elev= 30
  4376.8  667.53  4405.6  667.12  4461.7  665.22  4469.1  664.48  4490.0  664.14
  4525.9  664.74  4546.8  664.29  4561.0  663.56  4575.2  660.70  4644.2  659.43
  4644.5  658.93  4648.0  658.93  4648.2  659.43  4744.9  660.52  4752.3  662.57
  4759.1  662.49  4766.5  664.00  4794.9  664.28  4986.1  663.95  5013.9  663.43
  5035.6  662.25  5057.5  662.39  5063.0  662.01  5115.3  662.23  5155.3  663.05
  5160.6  663.62  5187.9  664.05  5193.2  664.94  5220.0  660.97  5243.7  661.48
#Mann=3,-1,0
  4376.8    0.05       0  4644.2   0.033       0  4648.2    0.05       0
Bank Sta=4644.2,4648.2
Exp/Cntr=0.3,0.1

Type RM Length L Ch R = 1,6004,335,335,335
BEGIN DESCRIPTION:
Elizabeth Creek Tributary 7 21.0
END DESCRIPTION:
XS GIS Cut Line= 3
      2337210.51      7059106.49      2336429.00      7058910.00
      2336178.98      7058759.99
#Sta/Elev= 30
  4198.4  665.79  4238.6  665.00  4674.3  658.62  4725.8  659.28  4737.5  658.48
  4737.7  657.98  4741.2  657.98  4741.5  658.48  4746.4  659.93  4756.8  660.79
  4816.6  659.47  4880.5  660.21  4890.8  660.72  4898.8  662.54  4904.0  662.48
  4911.4  663.87  4940.0  664.13  5097.5  664.08  5134.5  661.39  5144.2  661.24
  5171.4  662.91  5223.9  664.40  5229.7  665.87  5245.2  667.20  5251.1  669.50
  5260.8  671.01  5272.5  674.15  5282.2  675.25  5292.9  678.81  5295.8  678.81
#Mann=4,-1,0
  4198.4   0.075       0  4238.6    0.05       0  4737.5   0.033       0
  4741.5    0.05       0
Bank Sta=4737.5,4741.5
Exp/Cntr=0.3,0.1

Type RM Length L Ch R = 1,5669,107,107,107
BEGIN DESCRIPTION:
Elizabeth Creek Tributary 7 20.0
END DESCRIPTION:
XS GIS Cut Line= 4
      2337312.05      7058616.91      2336707.76      7058634.61
      2336296.52      7058615.40      2335723.82      7058653.35
#Sta/Elev= 30
  4266.8  661.98  4359.9  660.17  4520.0  658.98  4539.1  658.76  4544.1  658.30
  4680.0  658.18  4868.2  659.71  4930.2  659.74  5070.3  658.34  5090.3  658.53
  5130.4  657.92  5420.9  656.98  5471.0  656.46  5551.1  656.58  5577.9  656.33
  5582.9  655.90  5651.4  656.20  5661.4  655.70  5691.5  655.47  5699.5  654.54
  5699.7  654.04  5703.2  654.04  5703.5  654.54  5711.5  655.37  5728.6  656.29
  5733.7  657.46  5761.6  659.29  5801.7  661.55  5841.8  662.85  5857.0  663.74
#Mann=3,-1,0
  4266.8    0.05       0  5699.5    0.05       0  5703.5    0.05       0
Bank Sta=5699.5,5703.5
Exp/Cntr=0.3,0.1

Type RM Length L Ch R = 1,5562,277,277,277
BEGIN DESCRIPTION:
Elizabeth Creek Tributary 7 19.0
END DESCRIPTION:
XS GIS Cut Line= 4
      2336989.80      7058588.32      2336610.96      7058542.02
      2336365.58      7058489.67      2335783.74      7058471.08
#Sta/Elev= 30
  4650.5  661.47  4782.3  660.81  4840.2  659.86  4883.0  659.62  4921.7  658.77
  4926.8  659.19  4963.6  658.56  5003.2  658.44  5008.3  659.14  5014.0  659.17
  5161.8  659.23  5269.3  658.67  5419.7  659.42  5427.0  659.42  5432.0  658.91
  5477.0  659.31  5550.2  659.61  5599.8  658.77  5639.8  657.56  5669.8  658.41
  5699.9  658.07  5707.9  656.50  5708.1  656.00  5711.6  656.00  5711.9  656.50
  5719.9  658.39  5738.7  660.06  5743.7  662.20  5819.9  664.71  5865.2  666.66
#Mann=5,-1,0
  4650.5    0.05       0  5477.0   0.075       0  5550.2    0.05       0
  5707.9    0.05       0  5711.9    0.05       0
Bank Sta=5707.9,5711.9
Exp/Cntr=0.3,0.1

Type RM Length L Ch R = 1,5285,281,281,281
BEGIN DESCRIPTION:
Elizabeth Creek Tributary 7 18.0
END DESCRIPTION:
XS GIS Cut Line= 3
      2337010.81      7058588.33      2336829.00      7058360.00
      2336529.03      7058060.03
#Sta/Elev= 30
  4703.2  661.62  4752.4  661.42  4795.7  659.10  4810.1  657.59  4824.5  657.25
  4838.9  658.02  4859.7  658.19  4895.0  657.81  4903.0  657.15  4909.4  657.57
  4917.4  656.83  4923.8  657.16  4938.2  656.59  4944.6  655.77  4952.6  650.39
  4981.5  650.02  4987.9  649.74  4989.9  648.89  4990.1  648.39  4993.6  648.39
  4993.9  648.89  5037.5  649.51  5108.2  648.97  5122.4  649.48  5136.5  651.66
  5150.6  654.97  5164.8  652.73  5178.9  651.98  5263.8  654.38  5419.3  660.78
#Mann=3,-1,0
  4703.2    0.05       0  4989.9   0.033       0  4993.9    0.05       0
Bank Sta=4989.9,4993.9
Exp/Cntr=0.3,0.1

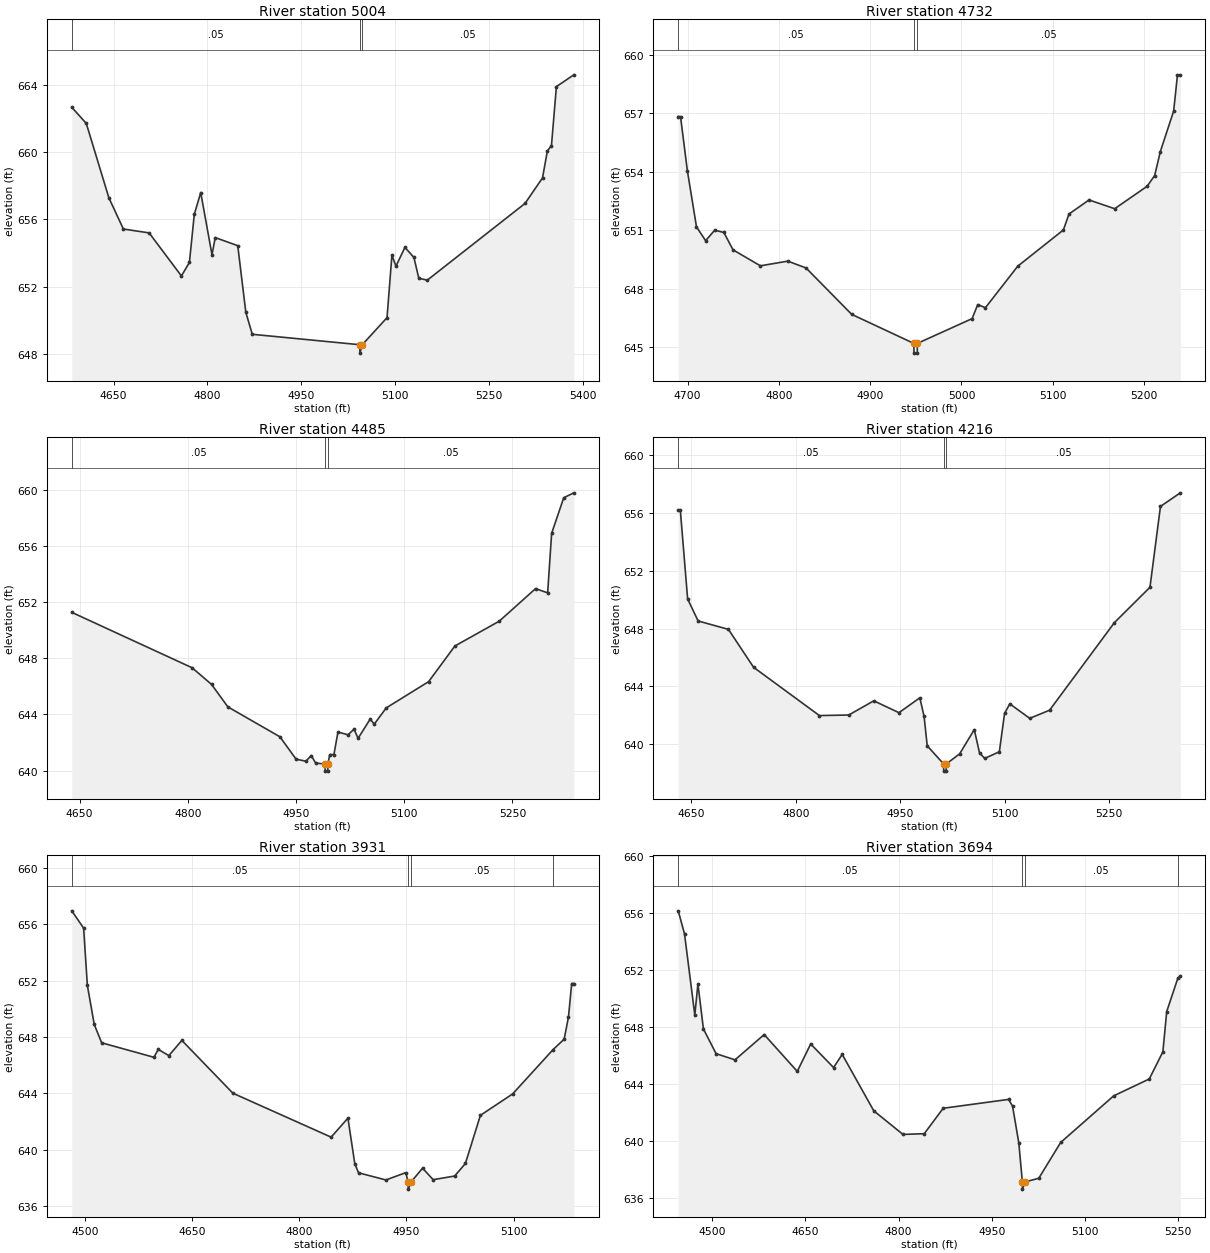
Type RM Length L Ch R = 1,5004,272,272,272
BEGIN DESCRIPTION:
Elizabeth Creek Tributary 7 17.0
END DESCRIPTION:
XS GIS Cut Line= 3
      2337079.01      7058560.02      2336979.00      7058160.00
      2336729.03      7057860.04
#Sta/Elev= 30
  4583.2  662.66  4606.4  661.70  4642.5  657.28  4665.7  655.42  4706.9  655.19
  4758.5  652.63  4771.3  653.43  4779.1  656.29  4789.4  657.59  4807.4  653.89
  4812.6  654.91  4848.6  654.43  4861.5  650.47  4871.8  649.16  5043.7  648.54
  5043.9  648.04  5047.7  648.54  5087.3  650.15  5095.1  653.86  5101.6  653.21
  5115.9  654.33  5130.3  653.73  5138.1  652.49  5151.7  652.38  5307.9  656.94
  5335.9  658.46  5343.7  660.07  5350.2  660.38  5358.1  663.89  5386.0  664.59
#Mann=3,-1,0
  4583.2    0.05       0  5043.7   0.033       0  5047.7    0.05       0
Bank Sta=5043.7,5047.7
Exp/Cntr=0.3,0.1

Type RM Length L Ch R = 1,4732,247,247,247
BEGIN DESCRIPTION:
Elizabeth Creek Tributary 7 16.0
END DESCRIPTION:
XS GIS Cut Line= 3
      2337129.00      7058360.02      2337129.00      7058060.00
      2336979.01      7057860.02
#Sta/Elev= 30
  4689.7  656.84  4692.2  656.84  4699.7  654.06  4709.7  651.18  4719.7  650.47
  4729.7  651.01  4739.7  650.89  4749.7  650.00  4779.7  649.18  4809.7  649.42
  4829.7  649.07  4879.7  646.69  4947.7  645.20  4948.0  644.70  4951.5  644.70
  4951.7  645.20  5011.6  646.47  5017.8  647.19  5026.2  647.03  5061.6  649.16
  5111.6  651.02  5117.8  651.84  5139.7  652.56  5167.8  652.11  5203.3  653.26
  5211.6  653.81  5217.8  655.04  5232.4  657.12  5236.6  658.98  5239.7  658.98
#Mann=3,-1,0
  4689.7    0.05       0  4947.7   0.033       0  4951.7    0.05       0
Bank Sta=4947.7,4951.7
Exp/Cntr=0.3,0.1

Type RM Length L Ch R = 1,4485,269,269,269
BEGIN DESCRIPTION:
Elizabeth Creek Tributary 7 15.0
END DESCRIPTION:
XS GIS Cut Line= 3
      2337529.01      7058260.02      2337329.00      7057960.00
      2337028.99      7057810.00
#Sta/Elev= 30
  4639.2  651.28  4806.0  647.33  4833.0  646.14  4855.6  644.54  4927.7  642.41
  4950.2  640.81  4963.7  640.67  4971.2  641.07  4977.2  640.54  4990.3  640.46
  4990.5  639.96  4994.0  639.96  4994.3  640.46  4996.8  641.14  5002.6  641.14
  5008.2  642.75  5022.1  642.55  5030.5  642.95  5036.1  642.30  5052.9  643.67
  5058.5  643.31  5075.2  644.47  5133.9  646.34  5170.3  648.88  5231.8  650.65
  5282.1  652.97  5298.9  652.67  5304.4  656.91  5321.2  659.45  5335.2  659.80
#Mann=3,-1,0
  4639.2    0.05       0  4990.3   0.033       0  4994.3    0.05       0
Bank Sta=4990.3,4994.3
Exp/Cntr=0.3,0.1

Type RM Length L Ch R = 1,4216,285,285,285
BEGIN DESCRIPTION:
Elizabeth Creek Tributary 7 14.0
END DESCRIPTION:
XS GIS Cut Line= 3
      2337729.00      7058110.01      2337529.00      7057810.00
      2337229.01      7057610.01
#Sta/Elev= 30
  4631.1  656.19  4634.1  656.19  4644.6  650.04  4659.7  648.52  4703.2  647.94
  4739.3  645.32  4833.9  641.98  4876.0  642.02  4912.0  643.00  4948.1  642.18
  4978.1  643.21  4984.2  641.92  4988.7  639.89  5012.2  638.64  5012.4  638.14
  5015.9  638.14  5016.2  638.64  5035.2  639.33  5056.3  641.01  5063.8  639.40
  5071.3  639.02  5092.3  639.48  5099.8  642.13  5107.3  642.79  5135.9  641.79
  5164.4  642.35  5257.6  648.41  5308.6  650.85  5323.7  656.44  5352.2  657.38
#Mann=3,-1,0
  4631.1    0.05       0  5012.2   0.033       0  5016.2    0.05       0
Bank Sta=5012.2,5016.2
Exp/Cntr=0.3,0.1

Type RM Length L Ch R = 1,3931,237,237,237
BEGIN DESCRIPTION:
Elizabeth Creek Tributary 7 13.0
END DESCRIPTION:
XS GIS Cut Line= 3
      2337779.01      7058060.03      2337629.00      7057560.00
      2337529.01      7057410.02
#Sta/Elev= 30
  4481.9  656.96  4498.5  655.73  4503.7  651.67  4513.3  648.90  4523.7  647.59
  4596.8  646.56  4602.9  647.12  4617.7  646.68  4635.9  647.76  4707.3  644.01
  4844.7  640.89  4868.2  642.24  4877.8  639.00  4883.0  638.36  4921.3  637.85
  4949.1  638.37  4952.4  637.70  4952.6  637.20  4956.4  637.70  4972.6  638.69
  4987.4  637.87  5017.5  638.13  5032.5  639.02  5053.5  642.44  5098.6  643.96
  5155.2  647.11  5170.7  647.85  5176.7  649.43  5181.2  651.80  5184.2  651.80
#Mann=4,-1,0
  4481.9    0.05       0  4952.4   0.033       0  4956.4    0.05       0
  5155.2   0.075       0
Bank Sta=4952.4,4956.4
Exp/Cntr=0.3,0.1

Type RM Length L Ch R = 1,3694,271,271,271
BEGIN DESCRIPTION:
Elizabeth Creek Tributary 7 12.0
END DESCRIPTION:
XS GIS Cut Line= 3
      2337929.00      7058009.98      2337829.00      7057460.00
      2337628.99      7057310.00
#Sta/Elev= 30
  4445.0  656.13  4455.1  654.52  4471.7  648.84  4476.7  651.01  4485.6  647.86
  4506.0  646.13  4536.5  645.70  4583.5  647.47  4636.8  644.89  4658.4  646.81
  4695.3  645.16  4709.2  646.08  4760.1  642.13  4807.1  640.48  4841.4  640.53
  4871.9  642.31  4977.3  642.93  4983.7  642.46  4993.8  639.87  4999.5  637.15
  4999.7  636.65  5003.5  637.15  5025.9  637.41  5061.3  639.92  5146.7  643.18
  5204.0  644.36  5225.9  646.26  5232.1  649.08  5249.9  651.40  5254.0  651.58
#Mann=4,-1,0
  4445.0    0.05       0  4999.5   0.033       0  5003.5    0.05       0
  5249.9   0.075       0
Bank Sta=4999.5,5003.5
Exp/Cntr=0.3,0.1

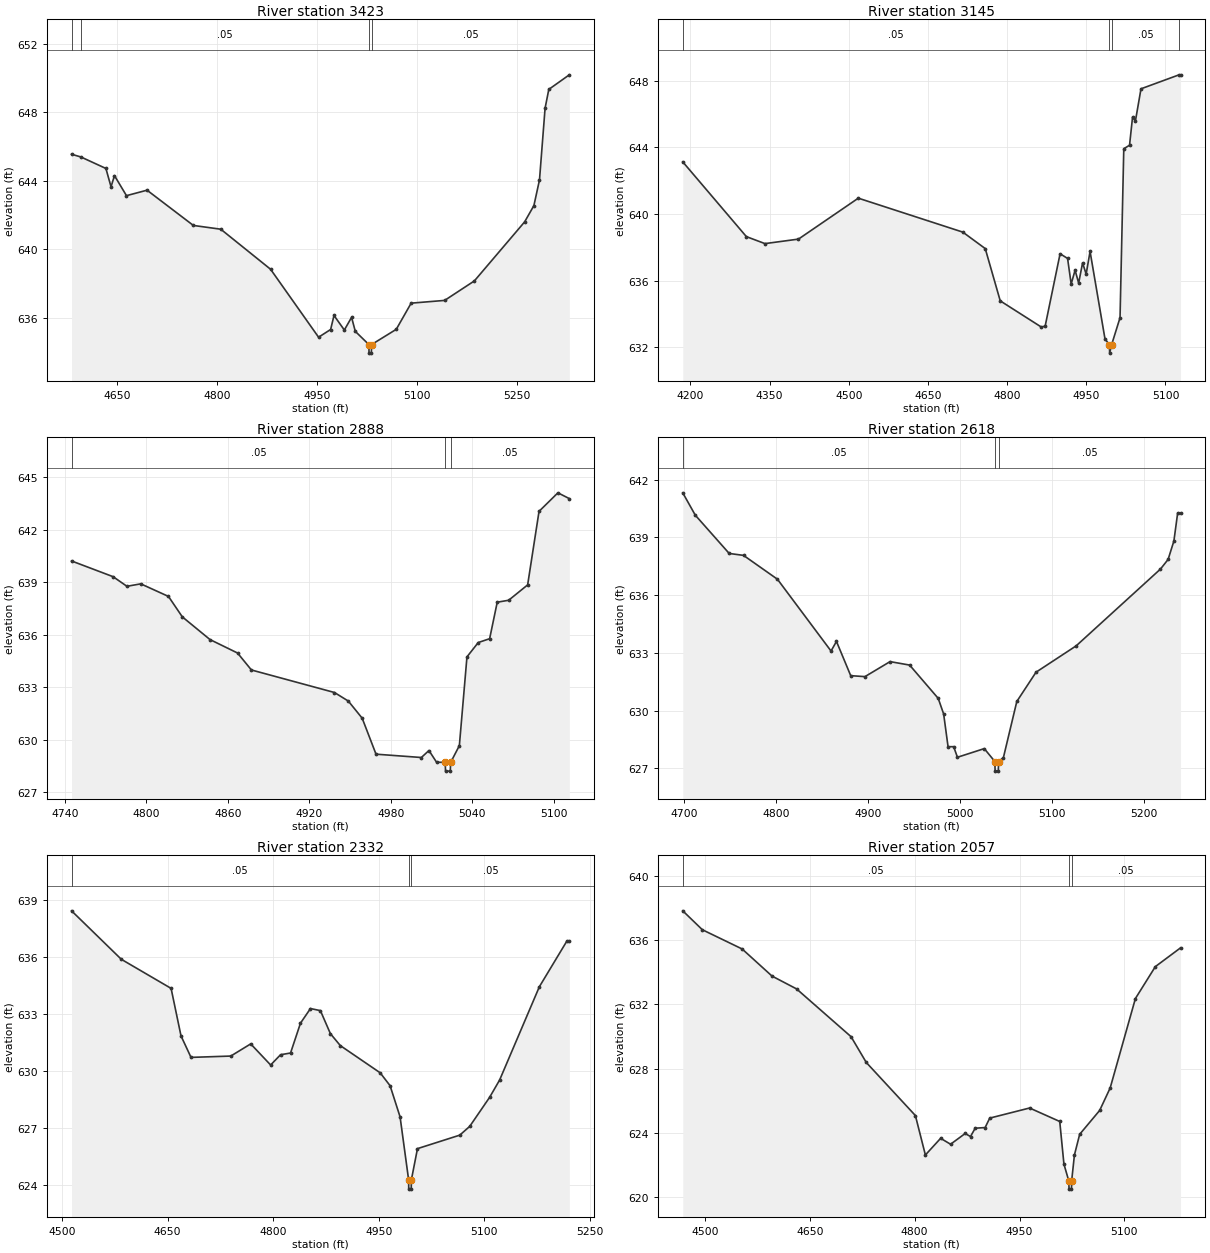
Type RM Length L Ch R = 1,3423,278,278,278
BEGIN DESCRIPTION:
Elizabeth Creek Tributary 7 11.0
END DESCRIPTION:
XS GIS Cut Line= 3
      2338129.01      7057760.03      2338029.00      7057360.00
      2337728.96      7057209.98
#Sta/Elev= 30
  4581.2  645.54  4595.3  645.38  4632.8  644.71  4640.5  643.64  4645.7  644.29
  4663.7  643.12  4694.6  643.44  4764.2  641.38  4805.4  641.16  4880.2  638.82
  4952.3  634.85  4970.4  635.30  4975.5  636.12  4991.0  635.27  5001.9  636.01
  5007.5  635.19  5027.9  634.42  5028.1  633.92  5031.6  633.92  5031.9  634.42
  5069.0  635.31  5091.4  636.84  5141.7  637.00  5186.4  638.14  5261.9  641.59
  5275.8  642.54  5284.2  644.04  5292.6  648.23  5298.2  649.33  5329.0  650.18
#Mann=4,-1,0
  4581.2   0.075       0  4595.3    0.05       0  5027.9   0.033       0
  5031.9    0.05       0
Bank Sta=5027.9,5031.9
Exp/Cntr=0.3,0.1

Type RM Length L Ch R = 1,3145,257,257,257
BEGIN DESCRIPTION:
Elizabeth Creek Tributary 7 10.0
END DESCRIPTION:
XS GIS Cut Line= 3
      2338528.97      7057659.97      2337929.00      7057110.00
      2337809.95      7057059.79
#Sta/Elev= 30
  4185.4  643.13  4305.9  638.64  4341.1  638.22  4404.6  638.49  4518.0  640.95
  4716.0  638.91  4758.5  637.92  4786.9  634.78  4864.6  633.21  4872.0  633.26
  4900.3  637.61  4914.5  637.33  4921.3  635.79  4928.7  636.62  4935.5  635.85
  4942.9  637.06  4949.7  636.39  4957.1  637.75  4985.4  632.49  4993.9  632.14
  4994.2  631.64  4997.9  632.14  5013.9  633.77  5021.0  643.92  5031.9  644.13
  5037.6  645.82  5043.0  645.58  5053.6  647.52  5125.7  648.36  5128.5  648.36
#Mann=4,-1,0
  4185.4    0.05       0  4993.9   0.033       0  4997.9    0.05       0
  5125.7   0.075       0
Bank Sta=4993.9,4997.9
Exp/Cntr=0.3,0.1

Type RM Length L Ch R = 1,2888,270,270,270
BEGIN DESCRIPTION:
Elizabeth Creek Tributary 7 9.0
END DESCRIPTION:
XS GIS Cut Line= 3
      2338178.99      7057259.97      2338129.00      7057010.00
      2338029.02      7056960.01
#Sta/Elev= 30
  4744.9  640.22  4775.5  639.32  4785.7  638.77  4795.9  638.91  4816.3  638.19
  4826.5  637.02  4846.9  635.72  4867.2  634.95  4877.4  633.98  4938.6  632.69
  4948.8  632.20  4959.0  631.22  4969.2  629.16  5002.6  628.97  5008.2  629.37
  5013.8  628.70  5020.2  628.69  5020.4  628.19  5023.9  628.19  5024.2  628.69
  5030.6  629.65  5036.2  634.73  5044.5  635.55  5052.9  635.77  5058.5  637.86
  5066.9  637.97  5080.9  638.85  5089.3  643.06  5103.2  644.12  5111.6  643.79
#Mann=3,-1,0
  4744.9    0.05       0  5020.2   0.033       0  5024.2    0.05       0
Bank Sta=5020.2,5024.2
Exp/Cntr=0.3,0.1

Type RM Length L Ch R = 1,2618,286,286,286
BEGIN DESCRIPTION:
Elizabeth Creek Tributary 7 8.0
END DESCRIPTION:
XS GIS Cut Line= 3
      2338229.00      7057260.00      2338379.00      7057010.00
      2338229.03      7056810.04
#Sta/Elev= 30
  4698.2  641.32  4711.8  640.16  4748.7  638.17  4764.3  638.07  4801.2  636.83
  4859.5  633.10  4865.4  633.60  4880.9  631.82  4896.4  631.77  4923.7  632.55
  4945.0  632.37  4976.1  630.64  4982.0  629.83  4986.8  628.13  4992.9  628.13
  4997.0  627.58  5026.2  628.03  5037.7  627.36  5038.0  626.86  5041.5  626.86
  5041.7  627.36  5047.0  627.56  5061.6  630.48  5082.5  632.00  5126.2  633.37
  5217.9  637.36  5226.2  637.86  5232.5  638.82  5236.6  640.28  5239.7  640.28
#Mann=3,-1,0
  4698.2    0.05       0  5037.7   0.033       0  5041.7    0.05       0
Bank Sta=5037.7,5041.7
Exp/Cntr=0.3,0.1

Type RM Length L Ch R = 1,2332,275,275,275
BEGIN DESCRIPTION:
Elizabeth Creek Tributary 7 7.0
END DESCRIPTION:
XS GIS Cut Line= 3
      2338928.97      7057209.97      2338579.00      7056860.00
      2338428.98      7056709.98
#Sta/Elev= 30
  4513.5  638.41  4584.2  635.86  4654.9  634.33  4669.0  631.83  4683.2  630.70
  4739.7  630.77  4768.0  631.41  4796.3  630.30  4810.4  630.84  4824.6  630.93
  4838.7  632.50  4852.9  633.27  4867.0  633.16  4881.2  631.95  4895.3  631.32
  4951.9  629.89  4966.0  629.21  4980.2  627.57  4992.3  624.27  4992.5  623.77
  4996.0  623.77  4996.3  624.27  5004.9  625.90  5065.0  626.61  5079.1  627.07
  5107.4  628.60  5121.6  629.51  5178.1  634.42  5217.0  636.81  5220.6  636.81
#Mann=3,-1,0
  4513.5    0.05       0  4992.3   0.033       0  4996.3    0.05       0
Bank Sta=4992.3,4996.3
Exp/Cntr=0.3,0.1

Type RM Length L Ch R = 1,2057,283,283,283
BEGIN DESCRIPTION:
Elizabeth Creek Tributary 7 6.0
END DESCRIPTION:
XS GIS Cut Line= 3
      2339078.98      7057059.97      2338729.00      7056660.00
      2338579.04      7056560.03
#Sta/Elev= 30
  4468.5  637.84  4496.5  636.66  4553.4  635.46  4596.1  633.77  4631.2  632.97
  4709.1  629.99  4730.9  628.38  4801.1  625.07  4815.4  622.61  4837.2  623.65
  4851.4  623.28  4872.3  623.95  4879.9  623.76  4886.6  624.28  4900.8  624.32
  4907.4  624.91  4964.4  625.54  5007.5  624.70  5013.5  622.04  5020.5  620.98
  5020.8  620.48  5024.3  620.48  5024.5  620.98  5028.5  622.61  5036.0  623.90
  5064.6  625.39  5079.6  626.79  5115.7  632.37  5144.2  634.36  5180.2  635.53
#Mann=3,-1,0
  4468.5    0.05       0  5020.5   0.033       0  5024.5    0.05       0
Bank Sta=5020.5,5024.5
Exp/Cntr=0.3,0.1

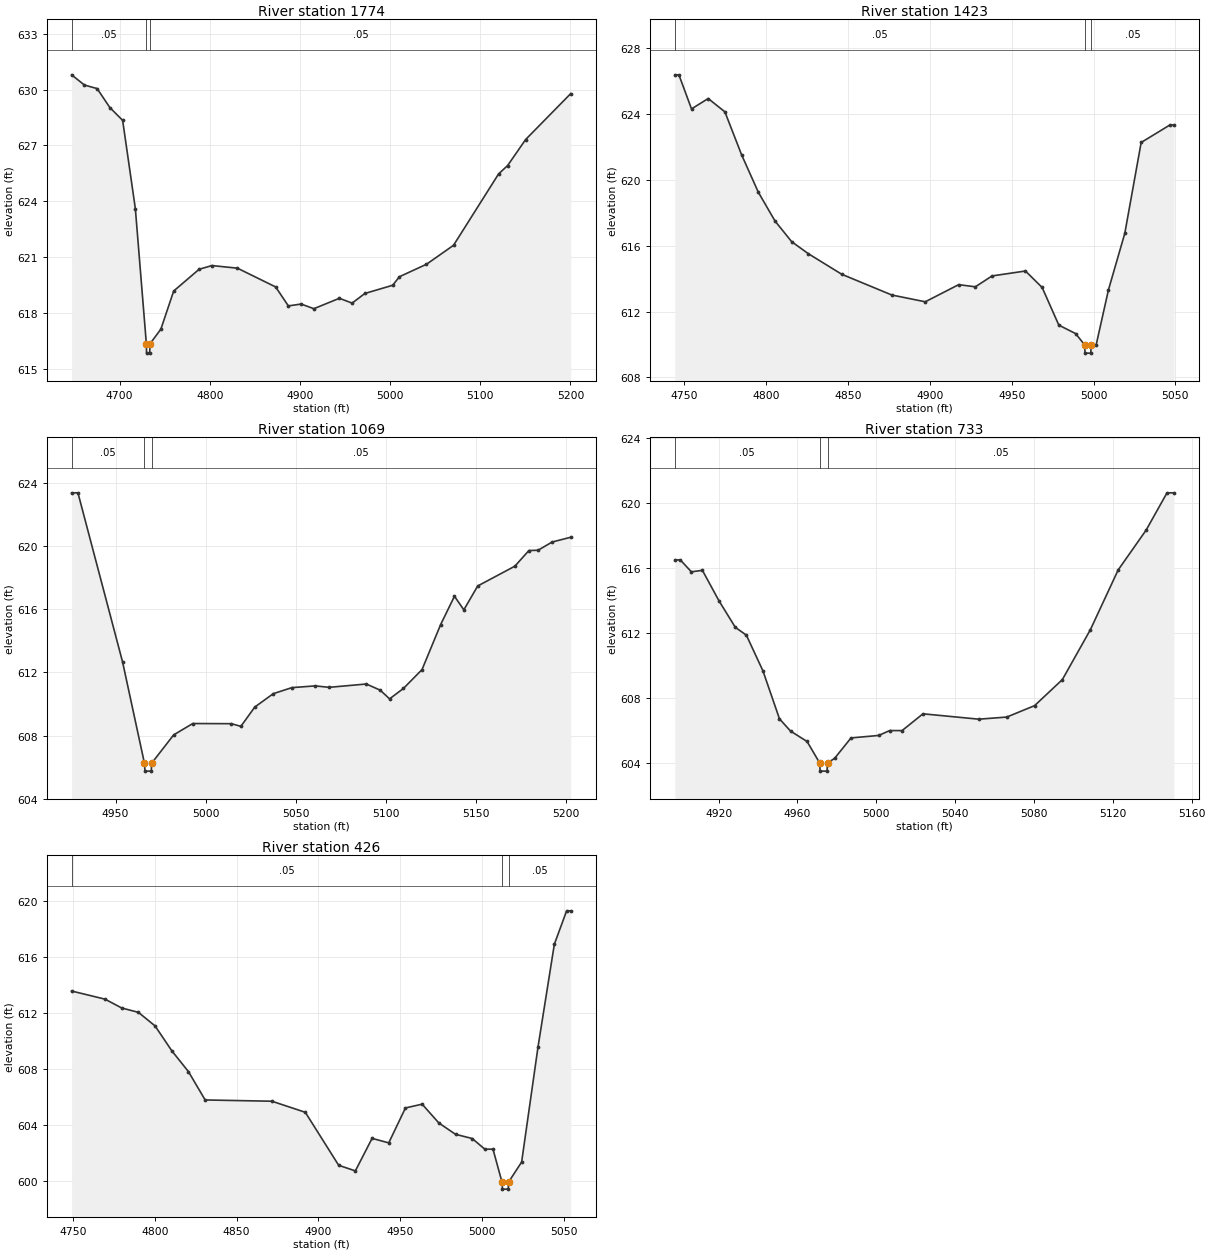
Type RM Length L Ch R = 1,1774,351,351,351
BEGIN DESCRIPTION:
Elizabeth Creek Tributary 7 5.0
END DESCRIPTION:
XS GIS Cut Line= 3
      2339179.01      7056710.01      2338929.00      7056460.00
      2338728.97      7056460.00
#Sta/Elev= 30
  4646.7  630.80  4660.9  630.25  4675.0  630.06  4689.1  629.04  4703.3  628.35
  4717.4  623.60  4729.6  616.33  4729.8  615.83  4733.3  615.83  4733.6  616.33
  4745.7  617.12  4759.9  619.17  4788.1  620.34  4802.3  620.54  4830.6  620.40
  4873.0  619.39  4887.1  618.37  4901.3  618.47  4915.4  618.22  4943.7  618.78
  4957.8  618.52  4972.0  619.04  5002.8  619.48  5010.3  619.94  5040.3  620.61
  5070.3  621.63  5120.3  625.47  5130.3  625.92  5150.3  627.32  5200.3  629.79
#Mann=3,-1,0
  4646.7    0.05       0  4729.6   0.033       0  4733.6    0.05       0
Bank Sta=4729.6,4733.6
Exp/Cntr=0.3,0.1

Type RM Length L Ch R = 1,1423,354,354,354
BEGIN DESCRIPTION:
Elizabeth Creek Tributary 7 4.0
END DESCRIPTION:
XS GIS Cut Line= 3
      2339129.00      7056210.00      2338879.00      7056160.00
      2338829.05      7056160.00
#Sta/Elev= 30
  4744.2  626.39  4746.7  626.39  4754.4  624.32  4764.6  624.95  4774.8  624.14
  4785.0  621.53  4795.2  619.26  4805.4  617.51  4815.6  616.25  4825.8  615.52
  4846.2  614.27  4876.8  613.01  4897.2  612.60  4917.6  613.64  4927.8  613.51
  4938.0  614.17  4958.4  614.47  4968.6  613.47  4978.8  611.18  4989.0  610.67
  4994.6  609.98  4994.8  609.48  4998.3  609.48  4998.6  609.98  5001.6  609.98
  5009.1  613.32  5019.1  616.76  5029.1  622.28  5046.6  623.34  5049.1  623.34
#Mann=3,-1,0
  4744.2    0.05       0  4994.6   0.033       0  4998.6    0.05       0
Bank Sta=4994.6,4998.6
Exp/Cntr=0.3,0.1

Type RM Length L Ch R = 1,1069,336,336,336
BEGIN DESCRIPTION:
Elizabeth Creek Tributary 7 3.0
END DESCRIPTION:
XS GIS Cut Line= 3
      2339179.00      7055910.00      2339129.00      7055960.00
      2338928.96      7055909.99
#Sta/Elev= 30
  4925.6  623.35  4929.1  623.35  4953.9  612.64  4966.0  606.25  4966.3  605.75
  4969.8  605.75  4970.0  606.25  4982.2  608.04  4992.8  608.76  5014.3  608.75
  5019.5  608.58  5027.2  609.80  5037.5  610.65  5047.8  611.03  5060.7  611.14
  5068.5  611.05  5089.1  611.26  5096.8  610.87  5102.0  610.32  5109.7  610.98
  5120.0  612.17  5130.3  615.01  5138.0  616.81  5143.2  615.95  5150.9  617.46
  5171.5  618.71  5179.3  619.70  5184.4  619.72  5192.2  620.24  5202.5  620.54
#Mann=3,-1,0
  4925.6    0.05       0  4966.0   0.033       0  4970.0    0.05       0
Bank Sta=4966,4970
Exp/Cntr=0.3,0.1

Type RM Length L Ch R = 1,733,307,307,307
BEGIN DESCRIPTION:
Elizabeth Creek Tributary 7 2.0
END DESCRIPTION:
XS GIS Cut Line= 3
      2339078.99      7055660.00      2338979.00      7055710.00
      2338879.01      7055809.99
#Sta/Elev= 30
  4897.8  616.49  4900.6  616.49  4906.2  615.76  4911.8  615.85  4920.2  613.98
  4928.5  612.35  4934.1  611.87  4942.5  609.68  4950.9  606.73  4956.5  605.98
  4964.9  605.34  4971.3  604.02  4971.5  603.52  4975.0  603.52  4975.3  604.02
  4978.9  604.31  4987.2  605.56  5001.2  605.71  5006.8  606.01  5013.1  606.01
  5023.7  607.04  5052.0  606.71  5066.2  606.84  5080.3  607.54  5094.4  609.14
  5108.6  612.20  5122.7  615.87  5136.9  618.32  5147.5  620.61  5151.0  620.61
#Mann=3,-1,0
  4897.8    0.05       0  4971.3   0.033       0  4975.3    0.05       0
Bank Sta=4971.3,4975.3
Exp/Cntr=0.3,0.1

Type RM Length L Ch R = 1,426,0,0,0
BEGIN DESCRIPTION:
Elizabeth Creek Tributary 7 1.0
END DESCRIPTION:
XS GIS Cut Line= 3
      2339079.05      7055560.01      2338829.00      7055510.00
      2338779.00      7055510.00
#Sta/Elev= 30
  4749.2  613.55  4769.6  612.97  4779.8  612.34  4790.0  612.03  4800.2  611.06
  4810.4  609.29  4820.6  607.80  4830.8  605.78  4871.6  605.69  4892.0  604.90
  4912.4  601.12  4922.6  600.72  4932.8  603.04  4943.0  602.72  4953.2  605.21
  4963.4  605.48  4973.6  604.14  4983.8  603.33  4994.0  603.03  5001.7  602.27
  5006.7  602.27  5012.2  599.92  5012.5  599.42  5016.0  599.42  5016.2  599.92
  5024.2  601.35  5034.2  609.55  5044.2  616.89  5051.7  619.27  5054.2  619.27
#Mann=3,-1,0
  4749.2    0.05       0  5012.2    0.04       0  5016.2    0.05       0
Bank Sta=5012.2,5016.2
Exp/Cntr=0.3,0.1

Chan Stop Cuts=-1