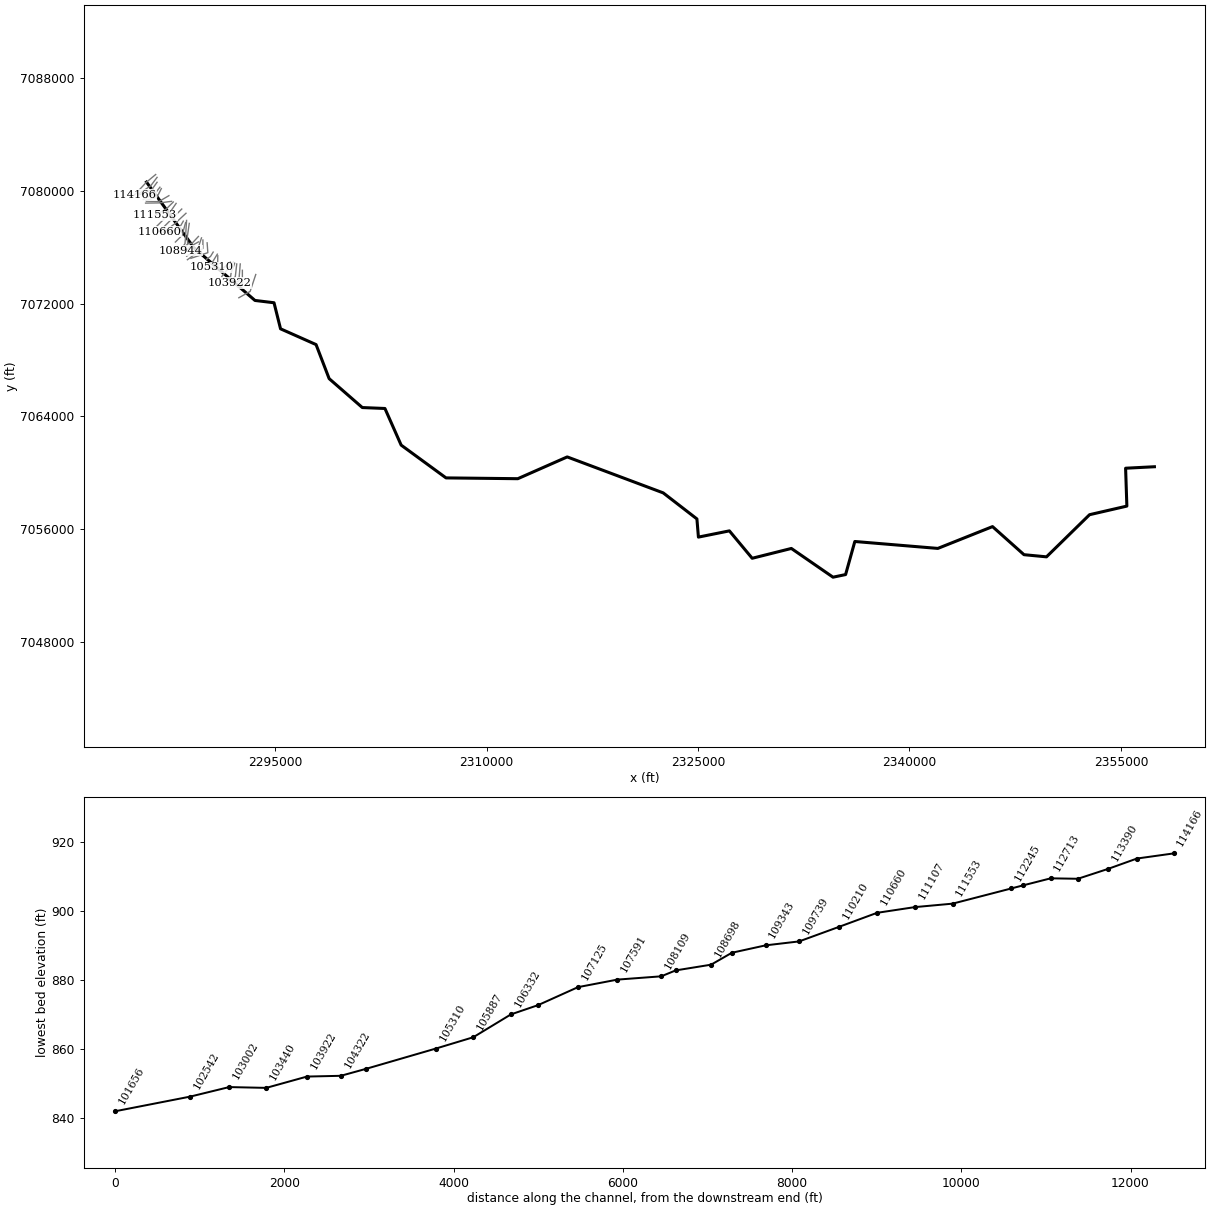
--- Elizabeth Creek.prj (project) ---

Proj Title=Elizabeth Creek Base Level Engineering
Current Plan=p01
Default Exp/Contr=0.3,0.1
English Units
Geom File=g01
Flow File=f01
Plan File=p01
BEGIN DESCRIPTION:
Elizabeth Creek
END DESCRIPTION:

--- Elizabeth Creek.p01 (plan) ---

Plan Title=Multiple Run
Short Identifier=Multiple
Geom File=g01
Flow File=f01
Subcritical Flow
K Sum by GR= 0
Std Step Tol= 0.01
Critical Tol= 0.01
Num of Std Step Trials= 20
Max Error Tol= 0.3
Flow Tol Ratio= 0.001
Split Flow NTrial= 30
Split Flow Tol= 0.02
Split Flow Ratio= 0.02
Log Output Level= 0
Friction Slope Method= 0
Unsteady Friction Slope Method= 2
Unsteady Bridges Friction Slope Method= 1
Parabolic Critical Depth
Global Vel Dist=  1 , 1 , 1
Global Log Level= 0
CheckData=True
Encroach Param= -1, 0, 0, 0
BEGIN DESCRIPTION:
Multiple Run
END DESCRIPTION:

--- Elizabeth Creek.f01 (steady flow) ---

Flow Title=Multiple
Number of Profiles=7
Profile Names=10-year,25-year,50-year,1pct_min,100-year,1pct_plu,500-year
River Rch & RM= Elizabeth Creek,Reach-1,114166
     549     744     904     545    1090    2170    1580
River Rch & RM= Elizabeth Creek,Reach-1,110210
     738    1020    1250     764    1520    3040    2260
River Rch & RM= Elizabeth Creek,Reach-1,104322
    1510    2160    2730    1700    3390    6770    5260
River Rch & RM= Elizabeth Creek,Reach-1,101656
    1710    2470    3120    1950    3890    7760    6070
River Rch & RM= Elizabeth Creek,Reach-1,99428
    1820    2630    3330    2080    4160    8300    6510
River Rch & RM= Elizabeth Creek,Reach-1,98089
    1870    2690    3400    2130    4250    8480    6640
River Rch & RM= Elizabeth Creek,Reach-1,94594
    1970    2860    3620    2270    4520    9020    7090
River Rch & RM= Elizabeth Creek,Reach-1,90025
    2930    4310    5520    3500    6980   13900   11200
River Rch & RM= Elizabeth Creek,Reach-1,89607
    3040    4480    5750    3640    7260   14500   11700
River Rch & RM= Elizabeth Creek,Reach-1,89164
    3050    4490    5750    3640    7260   14500   11600
River Rch & RM= Elizabeth Creek,Reach-1,84048
    3110    4580    5870    3720    7420   14800   11900
River Rch & RM= Elizabeth Creek,Reach-1,82929
    3190    4690    6020    3810    7610   15200   12200
River Rch & RM= Elizabeth Creek,Reach-1,81194
    3250    4780    6140    3890    7750   15500   12400
River Rch & RM= Elizabeth Creek,Reach-1,78498
    3280    4820    6180    3910    7810   15600   12500
River Rch & RM= Elizabeth Creek,Reach-1,72365
    4250    6320    8160    5190   10400   20700   16800
River Rch & RM= Elizabeth Creek,Reach-1,71793
    4400    6550    8460    5390   10700   21400   17400
River Rch & RM= Elizabeth Creek,Reach-1,68487
    4420    6570    8480    5400   10800   21500   17500
River Rch & RM= Elizabeth Creek,Reach-1,65706
    4860    7250    9380    5980   11900   23800   19400
River Rch & RM= Elizabeth Creek,Reach-1,63538
    4980    7430    9610    6130   12200   24400   19900
River Rch & RM= Elizabeth Creek,Reach-1,61330
    5140    7670    9930    6340   12700   25300   20600
River Rch & RM= Elizabeth Creek,Reach-1,60690
    5210    7770   10100    6420   12800   25600   20800
River Rch & RM= Elizabeth Creek,Reach-1,55810
    5360    7990   10400    6610   13200   26300   21500
River Rch & RM= Elizabeth Creek,Reach-1,50732
    5680    8500   11000    7030   14000   28000   22900
River Rch & RM= Elizabeth Creek,Reach-1,45346
    5890    8800   11400    7290   14600   29000   23700
River Rch & RM= Elizabeth Creek,Reach-1,42054
    6010    8990   11700    7450   14900   29700   24300
River Rch & RM= Elizabeth Creek,Reach-1,38961
    6130    9170   11900    7600   15200   30200   24700
River Rch & RM= Elizabeth Creek,Reach-1,35399
    6150    9190   11900    7610   15200   30300   24700
River Rch & RM= Elizabeth Creek,Reach-1,31176
    7980   12000   15700   10100   20100   40000   33000
River Rch & RM= Elizabeth Creek,Reach-1,28731
    8320   12500   16300   10400   20800   41500   34200
River Rch & RM= Elizabeth Creek,Reach-1,25794
    8110   12200   15900   10200   20400   40600   33500
River Rch & RM= Elizabeth Creek,Reach-1,24402
    8190   12300   16000   10300   20500   41000   33700
River Rch & RM= Elizabeth Creek,Reach-1,19585
    8630   13000   16900   10800   21600   43100   35400
River Rch & RM= Elizabeth Creek,Reach-1,14689
   12300   18700   24400   15700   31400   62600   52000
River Rch & RM= Elizabeth Creek,Reach-1,11453
   12200   18500   24200   15600   31100   62000   51400
River Rch & RM= Elizabeth Creek,Reach-1,6925
   12200   18400   24100   15500   30900   61700   51100
Boundary for River Rch & Prof#=Elizabeth Creek,Reach-1,1
Up Type=0
Dn Type=3
Dn Slope=0.005
Boundary for River Rch & Prof#=Elizabeth Creek,Reach-1,2
Up Type=0
Dn Type=3
Dn Slope=0.005
Boundary for River Rch & Prof#=Elizabeth Creek,Reach-1,3
Up Type=0
Dn Type=3
Dn Slope=0.005
Boundary for River Rch & Prof#=Elizabeth Creek,Reach-1,4
Up Type=0
Dn Type=3
Dn Slope=0.005
Boundary for River Rch & Prof#=Elizabeth Creek,Reach-1,5
Up Type=0
Dn Type=3
Dn Slope=0.005
Boundary for River Rch & Prof#=Elizabeth Creek,Reach-1,6
Up Type=0
Dn Type=3
Dn Slope=0.005
Boundary for River Rch & Prof#=Elizabeth Creek,Reach-1,7
Up Type=0
Dn Type=3
Dn Slope=0.005

--- Elizabeth Creek.g01 (geometry) ---

Geom Title=Existing Conditions

River Reach=Elizabeth Creek,Reach-1
Reach XY= 30
      2285877.81      7080622.91      2289234.61      7075965.59
      2293572.81      7072217.81      2294923.83      7072054.59
      2295386.80      7070203.81      2297906.33      7069084.02
      2298834.59      7066665.58      2301187.28      7064613.06
      2302792.22      7064546.88      2303942.40      7061946.70
      2307125.67      7059617.60      2312218.50      7059561.20
      2315723.15      7061107.94      2322531.43      7058554.48
      2324923.56      7056704.75      2325030.50      7055413.61
      2327227.50      7055856.54      2328844.22      7053910.52
      2331623.14      7054607.94      2334579.10      7052567.32
      2335470.99      7052753.62      2336125.77      7055102.17
      2342015.09      7054610.67      2345894.21      7056159.49
      2348126.70      7054165.06      2349723.10      7054012.23
      2352776.70      7057004.91      2355423.76      7057615.44
      2355334.23      7060304.98      2357379.00      7060410.00

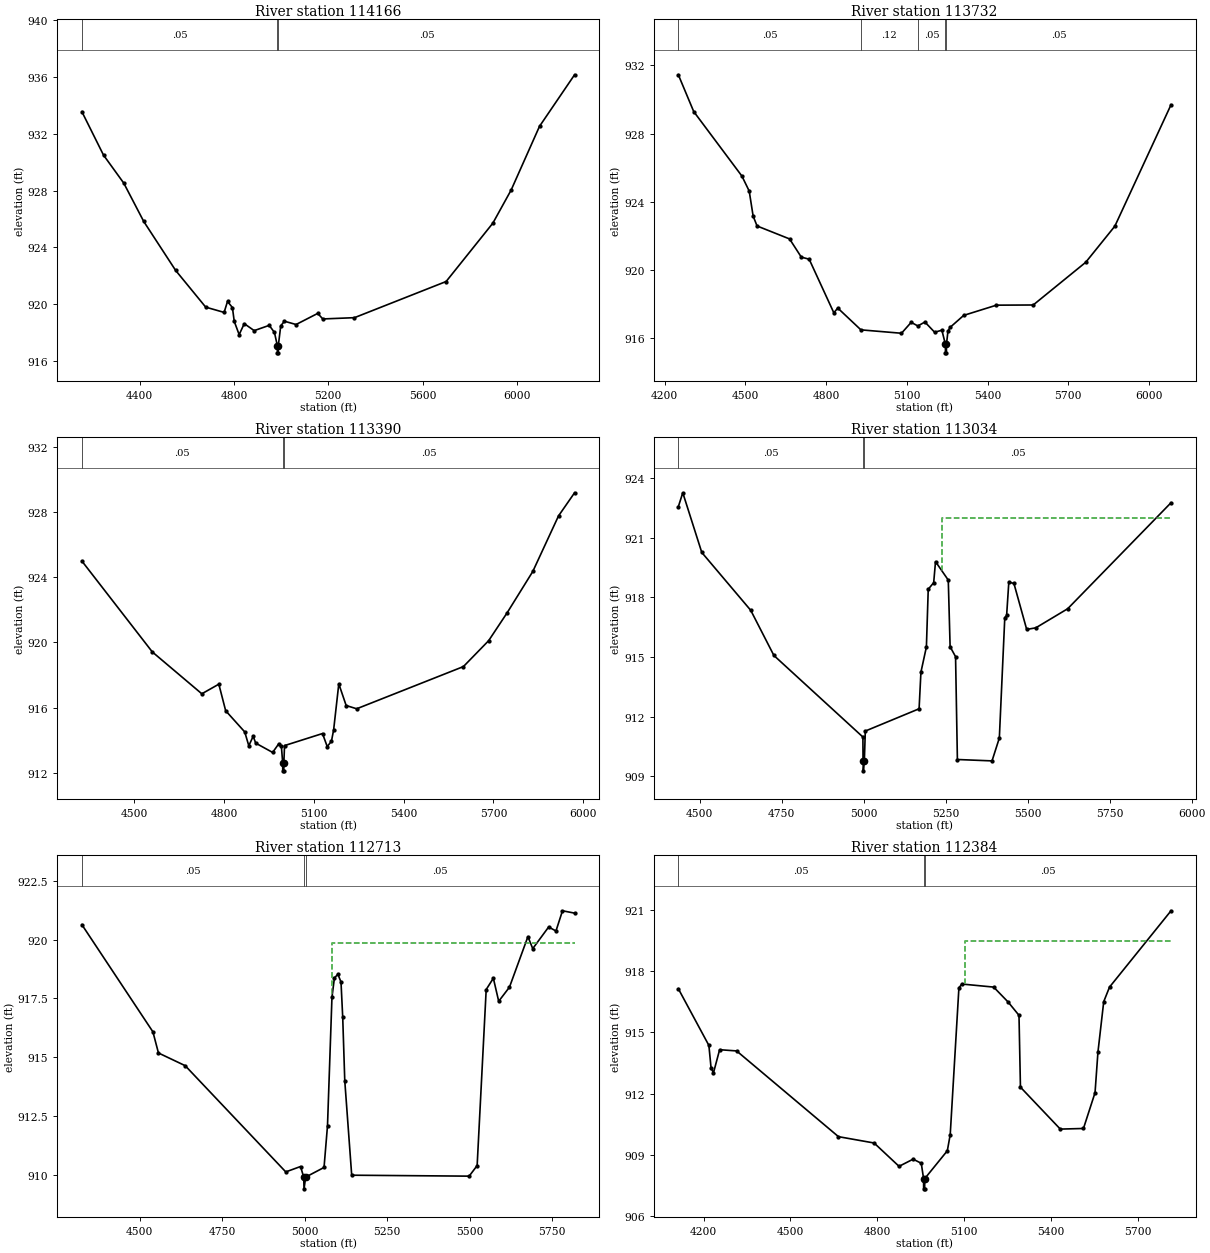
Type RM Length L Ch R = 1,114166,434,434,434
BEGIN DESCRIPTION:
Elizabeth Creek 146.0
END DESCRIPTION:
XS GIS Cut Line= 3
      2286529.01      7081160.01      2285875.72      7080617.45
      2285029.02      7079710.02
#Sta/Elev= 30
  4154.6  933.54  4246.4  930.49  4332.4  928.52  4417.0  925.83  4552.4  922.39
  4680.0  919.81  4758.1  919.44  4772.5  920.21  4793.3  919.78  4801.1  918.81
  4821.9  917.88  4843.6  918.65  4885.7  918.16  4949.5  918.53  4971.7  918.03
  4984.0  917.10  4984.3  916.60  4987.8  916.60  4988.0  917.10  4998.4  918.50
  5014.0  918.82  5063.4  918.59  5155.3  919.37  5176.8  918.98  5311.1  919.07
  5700.0  921.61  5898.3  925.71  5976.0  928.04  6096.2  932.51  6244.9  936.13
#Mann=3,-1,0
  4154.6    0.05       0  4984.0   0.033       0  4988.0    0.05       0
Bank Sta=4984,4988
Exp/Cntr=0.3,0.1

Type RM Length L Ch R = 1,113732,342,342,342
BEGIN DESCRIPTION:
Elizabeth Creek 145.0
END DESCRIPTION:
XS GIS Cut Line= 3
      2286628.97      7080959.96      2286179.00      7080360.00
      2285279.02      7079760.01
#Sta/Elev= 30
  4250.4  931.45  4307.6  929.29  4486.8  925.50  4513.9  924.62  4528.5  923.15
  4543.1  922.57  4663.9  921.81  4707.6  920.74  4736.8  920.62  4828.5  917.47
  4843.1  917.75  4929.1  916.47  5080.0  916.27  5116.0  916.91  5140.8  916.70
  5167.1  916.93  5203.2  916.33  5230.2  916.45  5243.2  915.62  5243.5  915.12
  5247.0  915.12  5247.2  915.62  5252.7  916.39  5260.3  916.61  5311.3  917.32
  5433.0  917.92  5569.7  917.93  5765.0  920.44  5873.2  922.56  6082.0  929.69
#Mann=5,-1,0
  4250.4    0.05       0  4929.1    0.12       0  5140.8    0.05       0
  5243.2    0.07       0  5247.2    0.05       0
Bank Sta=5243.2,5247.2
Exp/Cntr=0.3,0.1

Type RM Length L Ch R = 1,113390,356,356,356
BEGIN DESCRIPTION:
Elizabeth Creek 144.0
END DESCRIPTION:
XS GIS Cut Line= 3
      2286628.98      7080609.98      2286229.00      7080060.00
      2285329.00      7079710.00
#Sta/Elev= 30
  4325.2  925.00  4560.5  919.42  4725.9  916.85  4782.7  917.44  4805.5  915.81
  4869.2  914.51  4882.8  913.66  4897.4  914.24  4905.9  913.82  4962.4  913.25
  4983.2  913.79  4991.7  913.62  4995.9  912.62  4996.2  912.12  4999.7  912.12
  4999.9  912.62  5002.2  913.67  5129.0  914.41  5144.7  913.61  5158.9  913.94
  5166.2  914.64  5183.4  917.46  5208.0  916.13  5243.2  915.93  5599.6  918.52
  5683.9  920.11  5745.6  921.82  5831.4  924.36  5917.3  927.77  5970.9  929.19
#Mann=3,-1,0
  4325.2    0.05       0  4995.9   0.033       0  4999.9    0.05       0
Bank Sta=4995.9,4999.9
Exp/Cntr=0.3,0.1

Type RM Length L Ch R = 1,113034,321,321,321
BEGIN DESCRIPTION:
Elizabeth Creek 143.0
END DESCRIPTION:
XS GIS Cut Line= 3
      2286829.00      7080260.00      2286479.00      7079810.00
      2285648.21      7079387.14
#Sta/Elev= 30
  4434.8  922.55  4448.4  923.25  4506.3  920.25  4655.6  917.34  4726.2  915.07
  4997.6  910.97  4998.0  909.77  4999.0  909.27  5002.0  909.77  5004.9  911.27
  5168.9  912.39  5174.5  914.23  5191.2  915.50  5196.8  918.40  5213.4  918.73
  5219.0  919.79  5257.9  918.86  5263.5  915.51  5280.1  915.01  5285.7  909.84
  5391.3  909.77  5413.6  910.92  5430.2  916.97  5435.8  917.08  5442.5  918.76
  5458.1  918.69  5497.0  916.38  5524.8  916.46  5622.0  917.42  5937.1  922.75
#Mann=3,-1,0
  4434.8    0.05       0  4998.0    0.04       0  5002.0    0.05       0
#XS Ineff=2,0
       0                 5239.10    0.00  921.96
Permanent Ineff=
       F       F
Bank Sta=4998,5002
Exp/Cntr=0.3,0.1

Type RM Length L Ch R = 1,112713,329,329,329
BEGIN DESCRIPTION:
Elizabeth Creek 142.0
END DESCRIPTION:
XS GIS Cut Line= 3
      2286929.00      7080159.99      2286629.00      7079560.00
      2285844.00      7079317.21
#Sta/Elev= 30
  4325.0  920.64  4540.2  916.08  4557.0  915.18  4638.0  914.64  4942.7  910.12
  4987.4  910.35  4997.0  909.90  4998.0  909.40  5003.0  909.90  5058.6  910.31
  5069.1  912.09  5082.6  917.55  5090.0  918.37  5100.5  918.53  5110.0  918.20
  5115.2  916.69  5121.4  914.00  5142.4  909.98  5498.2  909.94  5522.4  910.39
  5549.8  917.88  5571.5  918.36  5587.7  917.38  5620.3  917.98  5676.2  920.13
  5690.8  919.62  5739.0  920.54  5761.2  920.37  5780.9  921.23  5817.5  921.13
#Mann=3,-1,0
  4325.0    0.05       0  4997.0    0.04       0  5003.0    0.05       0
#XS Ineff=2,0
       0                 5084.00    0.00  919.84
Permanent Ineff=
       F       F
Bank Sta=4997,5003
Exp/Cntr=0.3,0.1

Type RM Length L Ch R = 1,112384,139,139,139
BEGIN DESCRIPTION:
Elizabeth Creek 141.0
END DESCRIPTION:
XS GIS Cut Line= 3
      2287466.41      7079657.55      2286767.11      7079247.29
      2285876.66      7079265.94
#Sta/Elev= 30
  4112.7  917.13  4218.2  914.36  4225.6  913.28  4233.9  913.01  4255.3  914.15
  4314.0  914.09  4665.7  909.90  4788.8  909.59  4874.9  908.45  4923.5  908.80
  4951.6  908.60  4959.6  907.85  4959.8  907.35  4963.3  907.35  4963.6  907.85
  5041.6  909.21  5051.6  910.00  5081.6  917.17  5091.6  917.36  5201.6  917.21
  5251.6  916.48  5289.1  915.83  5294.1  912.32  5431.7  910.27  5511.7  910.30
  5551.7  912.05  5561.7  914.03  5581.7  916.50  5601.7  917.21  5814.1  920.94
#Mann=3,-1,0
  4112.7    0.05       0  4959.6    0.04       0  4963.6    0.05       0
#XS Ineff=2,0
       0                 5102.90    0.00  919.44
Permanent Ineff=
       F       F
Bank Sta=4959.6,4963.6
Exp/Cntr=0.3,0.1

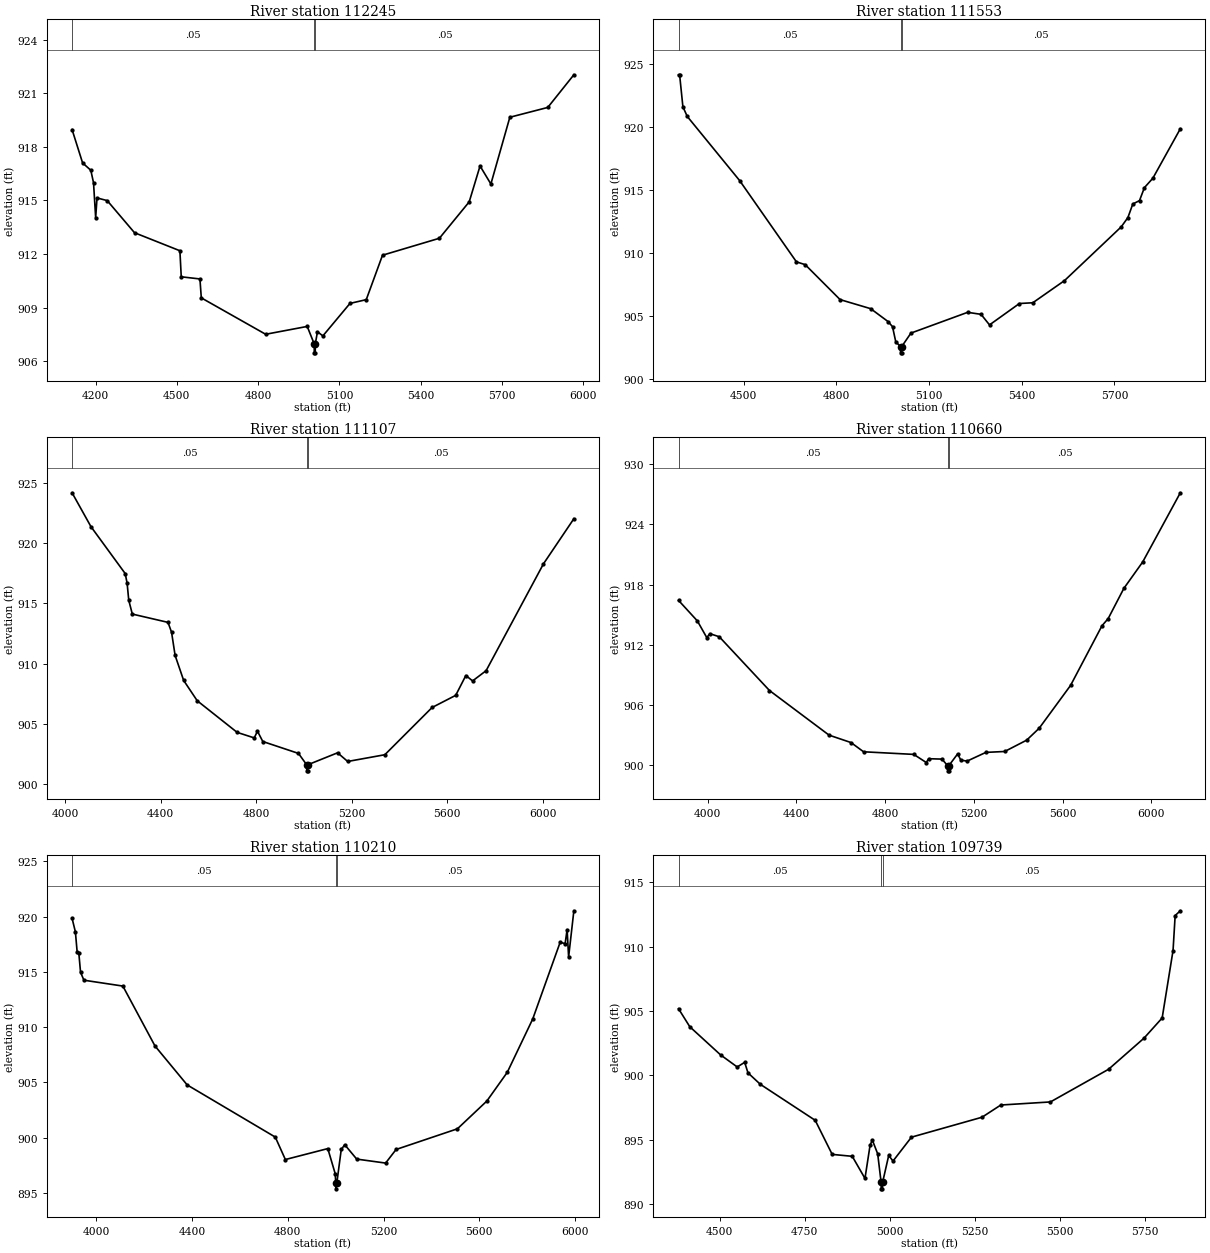
Type RM Length L Ch R = 1,112245,692,692,692
BEGIN DESCRIPTION:
Elizabeth Creek 140.0
END DESCRIPTION:
XS GIS Cut Line= 3
      2287657.57      7079256.62      2286799.75      7079144.73
      2285812.74      7079130.76
#Sta/Elev= 30
  4113.3  918.97  4152.2  917.10  4182.5  916.69  4192.5  915.99  4200.4  914.03
  4205.4  915.14  4243.0  914.99  4343.8  913.19  4511.3  912.18  4516.3  910.72
  4585.3  910.60  4590.3  909.54  4827.9  907.50  4981.3  907.94  5007.1  906.96
  5007.4  906.46  5010.9  906.46  5011.1  906.96  5019.1  907.64  5039.1  907.41
  5139.2  909.23  5199.2  909.44  5259.2  911.93  5469.2  912.88  5579.2  914.92
  5619.2  916.93  5659.2  915.92  5729.2  919.66  5869.2  920.21  5965.5  922.04
#Mann=3,-1,0
  4113.3    0.05       0  5007.1    0.04       0  5011.1    0.05       0
Bank Sta=5007.1,5011.1
Exp/Cntr=0.3,0.1

Type RM Length L Ch R = 1,111553,446,446,446
BEGIN DESCRIPTION:
Elizabeth Creek 139.0
END DESCRIPTION:
XS GIS Cut Line= 3
      2287778.97      7079209.97      2287279.00      7078710.00
      2286479.03      7078260.02
#Sta/Elev= 30
  4288.6  924.18  4292.1  924.18  4302.7  921.64  4316.8  920.87  4486.5  915.77
  4670.4  909.31  4698.7  909.09  4811.8  906.31  4910.8  905.59  4967.4  904.56
  4981.5  904.16  4992.1  902.95  5007.4  902.58  5007.6  902.08  5011.1  902.08
  5011.4  902.58  5041.2  903.65  5224.8  905.30  5268.2  905.14  5295.6  904.30
  5392.4  906.00  5435.8  906.06  5538.4  907.82  5722.0  912.09  5743.7  912.83
  5759.6  913.91  5781.3  914.18  5797.2  915.21  5824.6  915.96  5913.5  919.89
#Mann=3,-1,0
  4288.6    0.05       0  5007.4    0.04       0  5011.4    0.05       0
Bank Sta=5007.4,5011.4
Exp/Cntr=0.3,0.1

Type RM Length L Ch R = 1,111107,447,447,447
BEGIN DESCRIPTION:
Elizabeth Creek 138.0
END DESCRIPTION:
XS GIS Cut Line= 3
      2287979.01      7079110.02      2287429.00      7078310.00
      2286629.01      7077510.01
#Sta/Elev= 30
  4028.7  924.21  4107.9  921.39  4251.3  917.49  4259.3  916.69  4266.2  915.27
  4281.1  914.12  4430.6  913.43  4445.5  912.61  4460.4  910.68  4496.2  908.60
  4553.0  906.91  4720.2  904.28  4791.9  903.82  4805.4  904.38  4827.7  903.52
  4977.2  902.53  5011.7  901.58  5011.9  901.08  5015.4  901.08  5015.7  901.58
  5141.0  902.58  5183.4  901.86  5339.0  902.42  5537.0  906.35  5635.9  907.36
  5678.4  909.01  5706.7  908.56  5763.2  909.41  6003.6  918.30  6130.9  922.05
#Mann=3,-1,0
  4028.7    0.05       0  5011.7   0.033       0  5015.7    0.05       0
Bank Sta=5011.7,5015.7
Exp/Cntr=0.3,0.1

Type RM Length L Ch R = 1,110660,450,450,450
BEGIN DESCRIPTION:
Elizabeth Creek 137.0
END DESCRIPTION:
XS GIS Cut Line= 3
      2288379.00      7078710.00      2287579.00      7077910.00
      2286779.03      7077110.03
#Sta/Elev= 30
  3868.6  916.43  3953.5  914.38  3995.9  912.72  4010.0  913.11  4052.4  912.80
  4278.7  907.44  4547.4  902.99  4646.4  902.25  4703.0  901.33  4929.3  901.07
  4985.8  900.26  4996.4  900.64  5056.5  900.60  5082.7  899.93  5083.0  899.43
  5086.6  899.43  5086.9  899.93  5127.2  901.12  5141.4  900.50  5169.7  900.40
  5254.5  901.27  5339.4  901.36  5438.4  902.49  5494.9  903.68  5636.4  907.95
  5777.8  913.89  5806.1  914.62  5876.8  917.63  5961.6  920.26  6131.3  927.16
#Mann=3,-1,0
  3868.6    0.05       0  5082.7   0.033       0  5086.9    0.05       0
Bank Sta=5082.7,5086.9
Exp/Cntr=0.3,0.1

Type RM Length L Ch R = 1,110210,471,471,471
BEGIN DESCRIPTION:
Elizabeth Creek 136.0
END DESCRIPTION:
XS GIS Cut Line= 3
      2288678.98      7078409.98      2287879.00      7077660.00
      2287078.96      7077059.97
#Sta/Elev= 30
  3898.7  919.84  3912.6  918.61  3919.9  916.80  3926.8  916.72  3934.1  914.96
  3948.2  914.24  4110.9  913.71  4245.2  908.29  4379.6  904.77  4747.8  900.05
  4789.9  898.02  4967.2  899.01  4998.4  896.72  5000.4  895.87  5000.7  895.37
  5004.7  895.87  5023.4  898.93  5038.0  899.36  5088.0  898.06  5208.8  897.70
  5252.5  898.93  5508.8  900.80  5631.7  903.31  5717.1  905.91  5823.4  910.73
  5938.0  917.67  5958.8  917.55  5967.1  918.82  5973.4  916.34  5995.3  920.52
#Mann=3,-1,0
  3898.7    0.05       0  5000.4    0.04       0  5004.7    0.05       0
Bank Sta=5000.4,5004.7
Exp/Cntr=0.3,0.1

Type RM Length L Ch R = 1,109739,396,396,396
BEGIN DESCRIPTION:
Elizabeth Creek 135.0
END DESCRIPTION:
XS GIS Cut Line= 3
      2288487.41      7077848.72      2288179.00      7077310.00
      2287378.96      7077009.98
#Sta/Elev= 30
  4379.0  905.18  4412.1  903.78  4502.6  901.59  4551.5  900.65  4573.4  901.01
  4583.2  900.19  4619.5  899.30  4780.8  896.50  4830.7  893.85  4889.7  893.70
  4927.1  891.98  4942.1  894.56  4948.7  894.97  4964.5  893.89  4974.6  891.67
  4974.9  891.17  4978.5  891.17  4978.9  891.67  4996.9  893.77  5009.5  893.33
  5063.8  895.19  5271.2  896.74  5326.4  897.69  5472.3  897.93  5643.2  900.47
  5747.4  902.89  5800.8  904.46  5832.8  909.71  5839.0  912.43  5854.2  912.80
#Mann=3,-1,0
  4379.0    0.05       0  4974.6   0.033       0  4978.9    0.05       0
Bank Sta=4974.6,4978.9
Exp/Cntr=0.3,0.1

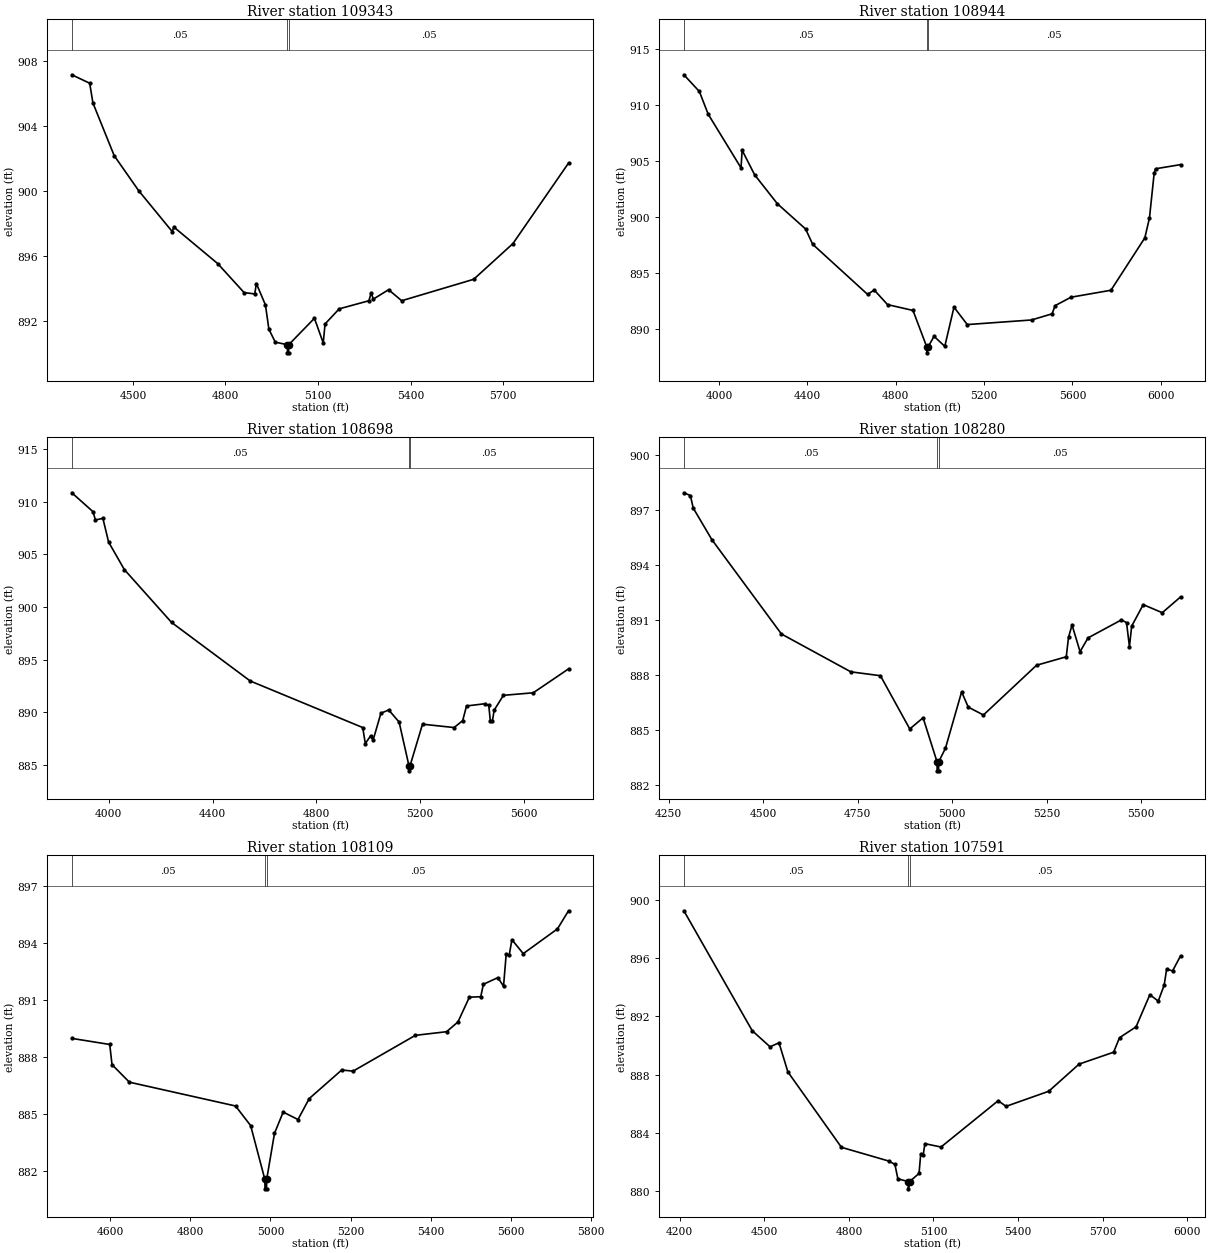
Type RM Length L Ch R = 1,109343,399,399,399
BEGIN DESCRIPTION:
Elizabeth Creek 134.5
END DESCRIPTION:
XS GIS Cut Line= 3
      2288650.56      7077746.10      2288403.48      7076841.70
      2287927.98      7076366.20
#Sta/Elev= 30
  4301.9  907.16  4359.8  906.64  4370.4  905.42  4439.2  902.18  4518.6  900.02
  4627.4  897.50  4632.6  897.78  4774.7  895.53  4860.4  893.74  4894.9  893.66
  4900.1  894.30  4929.5  892.98  4940.6  891.49  4961.3  890.69  5000.6  890.53
  5001.0  890.03  5004.6  890.03  5005.0  890.53  5088.3  892.16  5116.8  890.64
  5122.8  891.81  5168.6  892.74  5265.0  893.24  5272.1  893.73  5279.2  893.34
  5328.7  893.92  5371.1  893.24  5604.4  894.56  5731.7  896.76  5911.9  901.72
#Mann=3,-1,0
  4301.9    0.05       0  5000.6   0.033       0  5005.0    0.05       0
Bank Sta=5000.6,5005
Exp/Cntr=0.3,0.1

Type RM Length L Ch R = 1,108944,246,246,246
BEGIN DESCRIPTION:
Elizabeth Creek 134.0
END DESCRIPTION:
XS GIS Cut Line= 4
      2288720.49      7077899.93      2288655.22      7076865.01
      2288608.60      7076254.29      2288277.62      7075755.49
#Sta/Elev= 30
  3841.1  912.68  3911.2  911.19  3951.3  909.16  4099.8  904.38  4104.8  905.95
  4161.7  903.75  4264.4  901.18  4392.1  898.93  4424.0  897.57  4672.7  893.10
  4702.7  893.49  4762.9  892.19  4878.1  891.67  4941.0  888.39  4941.5  887.89
  4945.5  888.39  4973.4  889.36  5022.0  888.47  5063.6  891.96  5123.8  890.41
  5414.6  890.82  5507.7  891.37  5521.4  892.10  5593.5  892.85  5774.0  893.47
  5927.4  898.14  5948.4  899.92  5969.5  903.88  5975.8  904.30  6089.2  904.67
#Mann=3,-1,0
  3841.1    0.05       0  4941.0   0.033       0  4945.5    0.05       0
Bank Sta=4941,4945.5
Exp/Cntr=0.3,0.1

Type RM Length L Ch R = 1,108698,418,418,418
BEGIN DESCRIPTION:
Elizabeth Creek 133.0
END DESCRIPTION:
XS GIS Cut Line= 4
      2288911.64      7077690.19      2288771.77      7076725.15
      2288797.20      7076231.09      2288535.11      7075873.50
#Sta/Elev= 30
  3857.9  910.84  3938.9  909.06  3949.0  908.26  3977.6  908.41  3999.6  906.16
  4060.2  903.55  4242.1  898.53  4545.2  892.97  4978.4  888.55  4988.4  887.03
  5008.4  887.75  5018.4  887.36  5048.5  889.91  5078.5  890.22  5118.6  889.07
  5156.3  884.94  5156.8  884.44  5160.9  884.94  5208.7  888.87  5330.5  888.55
  5363.5  889.21  5378.2  890.60  5449.2  890.81  5463.9  890.65  5470.1  889.15
  5477.9  889.17  5484.7  890.20  5520.3  891.61  5635.3  891.85  5771.1  894.12
#Mann=3,-1,0
  3857.9    0.05       0  5156.3   0.033       0  5160.9    0.05       0
Bank Sta=5156.3,5160.9
Exp/Cntr=0.3,0.1

Type RM Length L Ch R = 1,108280,171,171,171
BEGIN DESCRIPTION:
Elizabeth Creek 132.0
END DESCRIPTION:
XS GIS Cut Line= 4
      2289562.21      7076761.53      2289116.76      7076282.26
      2288832.03      7076255.70      2288632.96      7075938.94
#Sta/Elev= 30
  4290.2  897.93  4307.5  897.78  4314.9  897.10  4364.2  895.38  4548.4  890.24
  4732.1  888.18  4810.3  887.97  4888.0  885.07  4923.2  885.68  4960.0  883.29
  4960.5  882.79  4964.2  882.79  4964.7  883.29  4982.4  884.02  5025.2  887.09
  5042.7  886.26  5082.9  885.83  5223.5  888.54  5302.1  889.00  5308.1  890.07
  5317.4  890.73  5338.6  889.28  5359.8  890.03  5448.1  891.01  5461.6  890.86
  5469.3  889.55  5475.2  890.67  5505.8  891.84  5556.1  891.40  5604.6  892.26
#Mann=3,-1,0
  4290.2    0.05       0  4960.0   0.033       0  4964.7    0.05       0
Bank Sta=4960,4964.7
Exp/Cntr=0.3,0.1

Type RM Length L Ch R = 1,108109,518,518,518
BEGIN DESCRIPTION:
Elizabeth Creek 131.0
END DESCRIPTION:
XS GIS Cut Line= 3
      2289562.21      7076373.63      2288972.24      7076044.50
      2288599.30      7075620.28
#Sta/Elev= 30
  4504.0  888.98  4598.7  888.66  4604.4  887.60  4647.8  886.68  4912.9  885.43
  4950.6  884.40  4986.0  881.58  4986.5  881.08  4990.2  881.08  4990.7  881.58
  5010.1  883.99  5031.8  885.11  5068.8  884.72  5096.9  885.82  5178.0  887.32
  5206.4  887.26  5362.0  889.14  5439.8  889.33  5468.2  889.84  5496.7  891.14
  5525.2  891.17  5531.8  891.82  5567.9  892.17  5582.1  891.72  5588.7  893.39
  5596.3  893.35  5603.0  894.16  5631.4  893.43  5716.8  894.73  5744.4  895.68
#Mann=3,-1,0
  4504.0    0.05       0  4986.0   0.033       0  4990.7    0.05       0
Bank Sta=4986,4990.7
Exp/Cntr=0.3,0.1

Type RM Length L Ch R = 1,107591,466,466,466
BEGIN DESCRIPTION:
Elizabeth Creek 130.0
END DESCRIPTION:
XS GIS Cut Line= 3
      2289779.00      7076659.99      2289529.00      7075910.00
      2288728.99      7075359.99
#Sta/Elev= 30
  4214.8  899.28  4457.2  891.02  4520.5  889.91  4552.1  890.19  4583.7  888.18
  4773.5  882.99  4942.1  882.04  4963.2  881.81  4973.7  880.82  5010.5  880.63
  5011.0  880.13  5015.2  880.63  5048.7  881.19  5054.7  882.52  5063.6  882.49
  5069.6  883.24  5126.7  883.01  5329.4  886.20  5357.3  885.81  5508.7  886.85
  5616.3  888.72  5738.7  889.54  5759.7  890.54  5818.4  891.29  5867.2  893.50
  5897.0  893.06  5918.0  894.16  5926.8  895.26  5947.8  895.14  5976.2  896.18
#Mann=3,-1,0
  4214.8    0.05       0  5010.5   0.033       0  5015.2    0.05       0
Bank Sta=5010.5,5015.2
Exp/Cntr=0.3,0.1

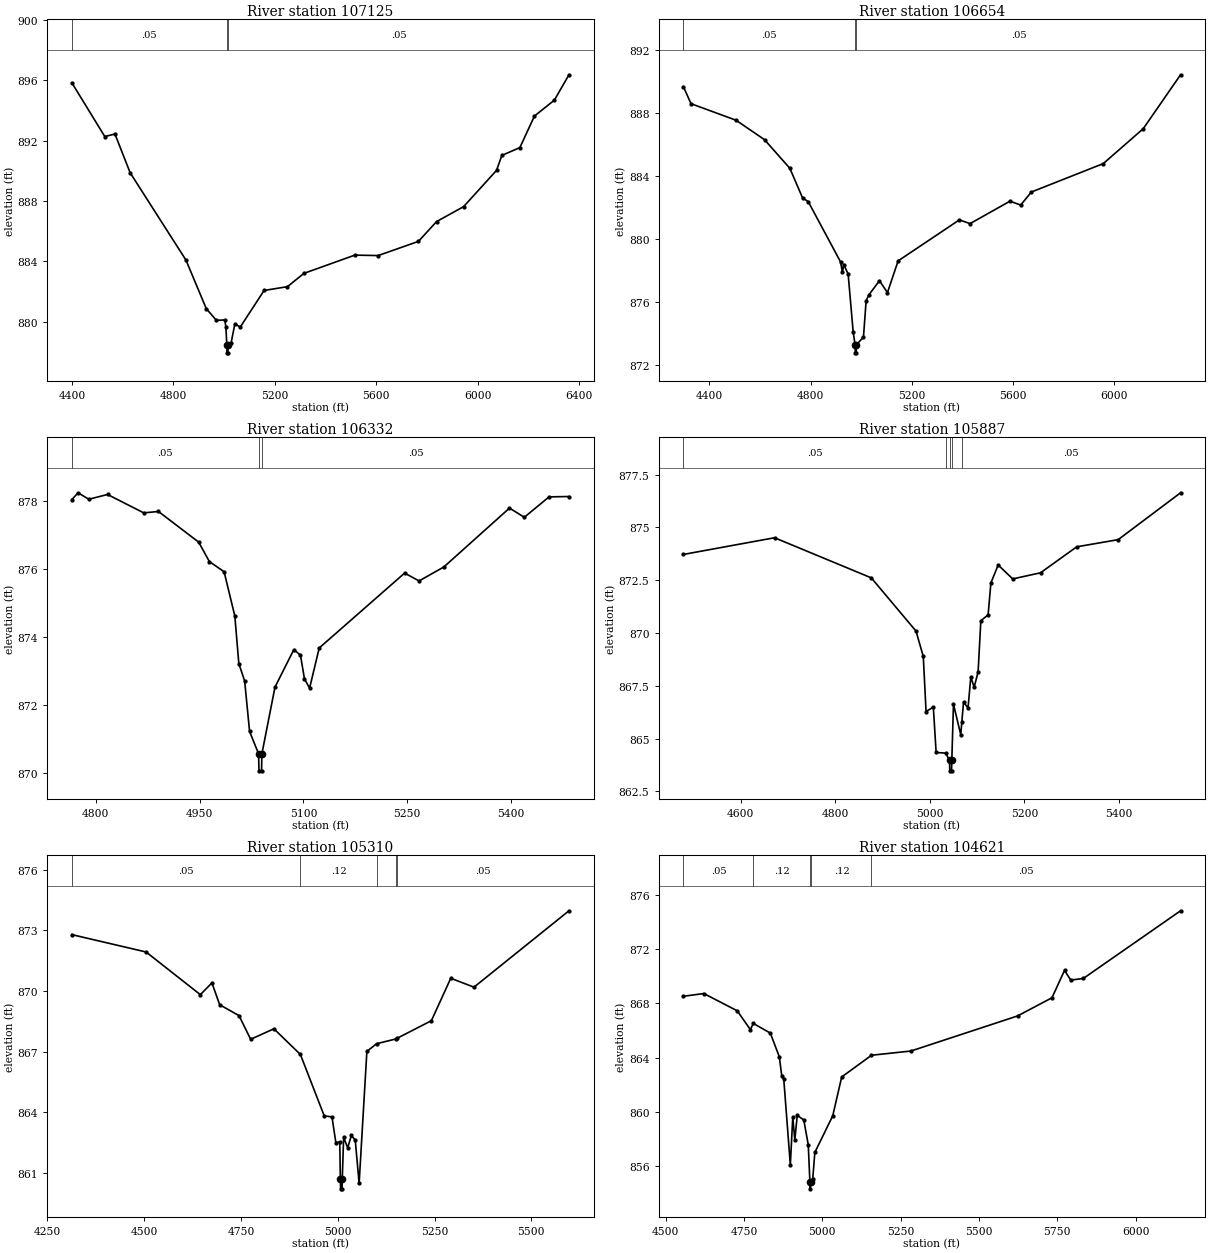
Type RM Length L Ch R = 1,107125,471,471,471
BEGIN DESCRIPTION:
Elizabeth Creek 129.0
END DESCRIPTION:
XS GIS Cut Line= 3
      2289879.00      7076510.03      2289879.00      7075910.00
      2288778.98      7075109.99
#Sta/Elev= 30
  4400.0  895.83  4530.0  892.27  4570.0  892.44  4630.0  889.87  4850.0  884.09
  4930.0  880.88  4970.0  880.10  5003.1  880.13  5007.4  879.68  5011.2  878.45
  5011.7  877.95  5015.4  877.95  5016.0  878.45  5028.2  878.62  5042.9  879.88
  5063.8  879.65  5158.1  882.08  5250.0  882.33  5315.0  883.21  5515.9  884.42
  5607.8  884.39  5766.7  885.33  5838.1  886.64  5944.8  887.63  6074.6  890.03
  6095.5  891.02  6166.6  891.54  6224.2  893.63  6302.6  894.68  6360.2  896.36
#Mann=3,-1,0
  4400.0    0.05       0  5011.2   0.033       0  5016.0    0.05       0
Bank Sta=5011.2,5016
Exp/Cntr=0.3,0.1

Type RM Length L Ch R = 1,106654,322,322,322
BEGIN DESCRIPTION:
Elizabeth Creek 128.0
END DESCRIPTION:
XS GIS Cut Line= 3
      2290179.00      7076309.96      2290229.00      7075610.00
      2289028.95      7075209.98
#Sta/Elev= 30
  4297.1  889.69  4327.1  888.61  4505.1  887.56  4617.9  886.32  4718.1  884.50
  4768.3  882.62  4790.8  882.38  4918.6  878.55  4926.2  877.88  4931.2  878.38
  4948.7  877.78  4968.8  874.06  4976.4  873.26  4976.9  872.76  4980.6  872.76
  4981.2  873.26  5009.4  873.77  5019.9  876.08  5030.5  876.44  5072.6  877.35
  5104.2  876.59  5146.4  878.61  5388.9  881.22  5431.0  880.98  5589.1  882.41
  5631.3  882.16  5673.5  882.99  5958.1  884.80  6116.2  887.02  6263.8  890.45
#Mann=3,-1,0
  4297.1    0.05       0  4976.4   0.033       0  4981.2    0.05       0
Bank Sta=4976.4,4981.2
Exp/Cntr=0.3,0.1

Type RM Length L Ch R = 1,106332,445,445,445
BEGIN DESCRIPTION:
Elizabeth Creek 127.5
END DESCRIPTION:
XS GIS Cut Line= 3
      2290608.60      7075652.89      2290417.46      7075340.53
      2290128.38      7075140.04
#Sta/Elev= 30
  4765.5  878.04  4774.5  878.24  4790.0  878.05  4817.1  878.19  4869.3  877.65
  4890.6  877.69  4948.7  876.79  4964.1  876.22  4985.4  875.92  5000.9  874.62
  5006.7  873.22  5015.1  872.71  5022.2  871.23  5035.2  870.57  5035.8  870.07
  5039.5  870.07  5040.0  870.57  5058.9  872.53  5086.1  873.63  5095.7  873.47
  5101.5  872.77  5108.9  872.50  5122.8  873.68  5246.1  875.88  5267.0  875.65
  5302.8  876.06  5397.6  877.79  5419.0  877.52  5454.8  878.12  5483.5  878.13
#Mann=3,-1,0
  4765.5    0.05       0  5035.2   0.033       0  5040.0    0.05       0
Bank Sta=5035.2,5040
Exp/Cntr=0.3,0.1

Type RM Length L Ch R = 1,105887,441,441,441
BEGIN DESCRIPTION:
Elizabeth Creek 127.3
END DESCRIPTION:
XS GIS Cut Line= 3
      2290902.30      7075503.69      2290506.04      7074860.35
      2290226.36      7074762.46
#Sta/Elev= 30
  4478.7  873.72  4671.5  874.51  4876.2  872.61  4970.8  870.09  4986.2  868.89
  4992.1  866.28  5007.5  866.49  5013.4  864.34  5033.5  864.31  5041.7  863.97
  5042.3  863.47  5046.0  863.47  5046.6  863.97  5050.1  866.63  5065.5  865.18
  5067.8  865.78  5071.4  866.73  5080.9  866.45  5086.8  867.92  5093.8  867.43
  5102.2  868.15  5108.0  870.58  5123.4  870.86  5129.3  872.37  5144.7  873.22
  5175.5  872.56  5234.3  872.85  5310.8  874.08  5398.6  874.42  5530.6  876.64
#Mann=5,-1,0
  4478.7    0.05       0  5033.5    0.12       0  5041.7   0.033       0
  5046.6    0.12       0  5067.8    0.05       0
Bank Sta=5041.7,5046.6
Exp/Cntr=0.3,0.1

Type RM Length L Ch R = 1,105310,825,825,825
BEGIN DESCRIPTION:
Elizabeth Creek 127.0
END DESCRIPTION:
XS GIS Cut Line= 3
      2290934.94      7075391.77      2290922.18      7074566.59
      2290463.69      7074560.68
#Sta/Elev= 30
  4313.3  872.79  4505.1  871.93  4645.1  869.82  4675.1  870.40  4695.1  869.32
  4745.1  868.78  4775.1  867.61  4835.1  868.13  4903.5  866.86  4965.1  863.82
  4985.1  863.77  4995.1  862.50  5005.2  862.53  5006.7  860.71  5007.4  860.21
  5011.1  860.21  5011.7  860.71  5015.2  862.76  5025.6  862.24  5035.2  862.85
  5045.2  862.62  5055.2  860.48  5075.2  867.01  5100.2  867.39  5150.6  867.63
  5152.2  867.65  5241.8  868.53  5291.8  870.63  5351.8  870.19  5597.1  873.97
#Mann=5,-1,0
  4313.3    0.05       0  4903.5    0.12       0  5100.2    0.05       0
  5150.6    0.12       0  5152.2    0.05       0
Bank Sta=5006.7,5011.7
Exp/Cntr=0.3,0.1

Type RM Length L Ch R = 1,104621,299,299,299
BEGIN DESCRIPTION:
Elizabeth Creek 126.5
END DESCRIPTION:
XS GIS Cut Line= 3
      2291820.69      7074939.57      2291279.93      7074487.39
      2290398.85      7074510.70
#Sta/Elev= 30
  4556.8  868.52  4622.0  868.72  4728.5  867.45  4770.3  866.07  4779.9  866.52
  4834.1  865.81  4862.7  864.07  4870.5  862.68  4877.0  862.41  4897.9  856.12
  4905.7  859.62  4912.2  857.95  4920.0  859.75  4940.8  859.42  4955.1  857.60
  4960.4  854.85  4961.1  854.35  4965.4  854.85  4969.4  855.07  4976.1  857.03
  5033.2  859.72  5061.8  862.58  5156.9  864.18  5282.6  864.49  5622.8  867.07
  5732.8  868.41  5772.8  870.42  5792.8  869.71  5832.8  869.83  6143.1  874.81
#Mann=5,-1,0
  4556.8    0.05       0  4779.9    0.12       0  4960.4    0.07       0
  4965.4    0.12       0  5156.9    0.05       0
Bank Sta=4960.4,4965.4
Exp/Cntr=0.3,0.1

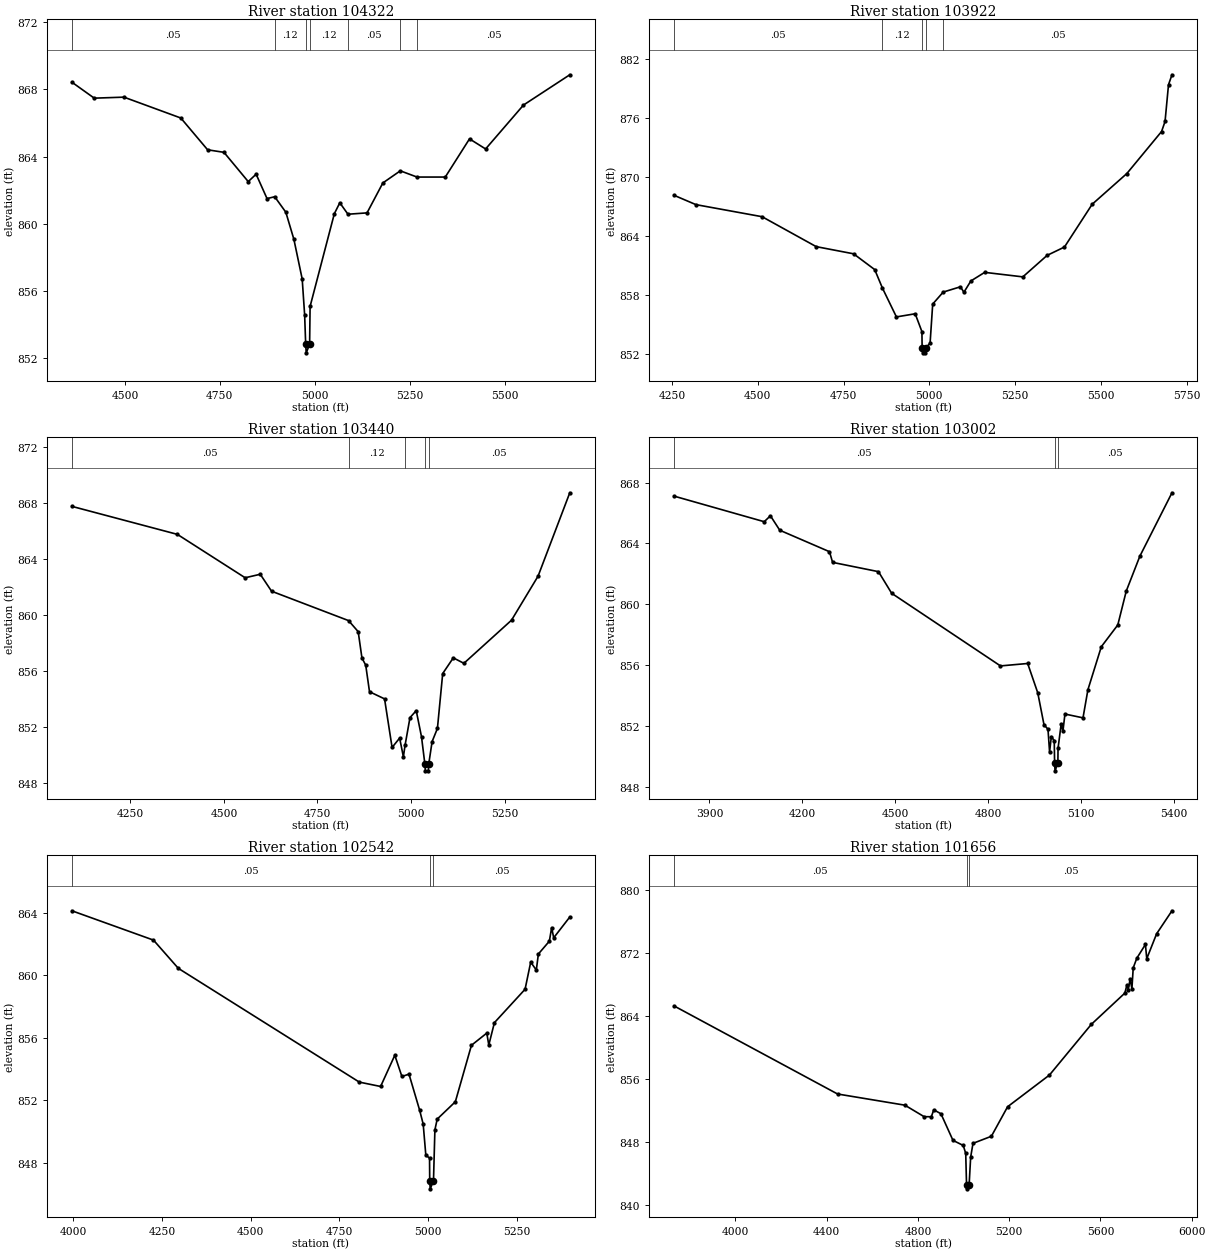
Type RM Length L Ch R = 1,104322,400,400,400
BEGIN DESCRIPTION:
Elizabeth Creek 126.2
END DESCRIPTION:
XS GIS Cut Line= 3
      2292030.51      7074911.62      2291256.62      7073969.90
      2291209.98      7073890.61
#Sta/Elev= 30
  4360.4  868.42  4419.3  867.47  4497.5  867.53  4647.2  866.29  4717.8  864.40
  4760.8  864.25  4824.7  862.51  4845.5  862.95  4874.2  861.50  4894.4  861.61
  4923.7  860.69  4944.9  859.08  4966.8  856.72  4973.2  854.60  4976.0  852.83
  4977.4  852.33  4986.3  852.83  4987.6  855.09  5051.4  860.60  5065.8  861.25
  5087.3  860.57  5137.5  860.65  5179.2  862.43  5225.1  863.15  5269.1  862.78
  5343.5  862.78  5407.3  865.05  5449.7  864.45  5549.4  867.06  5671.3  868.86
#Mann=7,-1,0
  4360.4    0.05       0  4894.4    0.12       0  4976.0    0.07       0
  4986.3    0.12       0  5087.3    0.05       0  5225.1    0.12       0
  5269.1    0.05       0
Bank Sta=4976,4986.3
Exp/Cntr=0.3,0.1

Type RM Length L Ch R = 1,103922,482,482,482
BEGIN DESCRIPTION:
Elizabeth Creek 126.0
END DESCRIPTION:
XS GIS Cut Line= 3
      2292128.99      7074859.96      2291879.00      7074160.00
      2291779.00      7073459.97
#Sta/Elev= 30
  4256.3  868.16  4320.0  867.21  4512.7  865.98  4670.4  862.93  4779.2  862.20
  4840.8  860.59  4863.1  858.72  4904.0  855.77  4958.7  856.09  4978.3  854.27
  4978.9  852.61  4980.4  852.11  4988.0  852.11  4989.4  852.61  5002.1  853.10
  5009.7  857.08  5040.3  858.30  5090.5  858.84  5100.6  858.28  5120.8  859.43
  5161.2  860.31  5272.3  859.85  5343.0  862.04  5393.5  862.89  5474.3  867.25
  5575.3  870.38  5676.4  874.66  5686.5  875.68  5696.6  879.43  5706.7  880.44
#Mann=5,-1,0
  4256.3    0.05       0  4863.1    0.12       0  4978.9    0.07       0
  4989.4    0.12       0  5040.3    0.05       0
Bank Sta=4978.9,4989.4
Exp/Cntr=0.3,0.1

Type RM Length L Ch R = 1,103440,438,438,438
BEGIN DESCRIPTION:
Elizabeth Creek 125.0
END DESCRIPTION:
XS GIS Cut Line= 3
      2292279.00      7074810.01      2292179.00      7073910.00
      2291879.01      7073610.01
#Sta/Elev= 30
  4094.0  867.73  4375.7  865.73  4556.8  862.63  4597.1  862.88  4627.3  861.67
  4833.0  859.57  4858.7  858.78  4868.7  856.90  4878.8  856.39  4888.9  854.49
  4929.1  853.98  4949.2  850.51  4969.4  851.18  4979.4  849.84  4983.9  850.67
  4997.0  852.64  5013.7  853.14  5027.8  851.27  5036.7  849.34  5038.2  848.84
  5045.8  848.84  5047.2  849.34  5056.1  850.93  5070.3  851.87  5084.4  855.79
  5112.7  856.91  5141.0  856.52  5268.2  859.60  5339.0  862.74  5423.8  868.70
#Mann=5,-1,0
  4094.0    0.05       0  4833.0    0.12       0  4983.9    0.05       0
  5036.7   0.033       0  5047.2    0.05       0
Bank Sta=5036.7,5047.2
Exp/Cntr=0.3,0.1

Type RM Length L Ch R = 1,103002,460,460,460
BEGIN DESCRIPTION:
Elizabeth Creek 124.0
END DESCRIPTION:
XS GIS Cut Line= 3
      2292529.00      7074809.97      2292429.00      7073610.00
      2292079.04      7073410.02
#Sta/Elev= 30
  3785.7  867.11  4076.7  865.43  4096.7  865.82  4126.9  864.87  4287.4  863.46
  4297.4  862.76  4445.5  862.15  4488.1  860.73  4839.3  855.96  4927.1  856.12
  4959.7  854.19  4979.8  852.10  4992.7  851.80  4997.8  850.31  5003.5  851.32
  5012.9  851.05  5014.0  849.57  5015.5  849.07  5024.6  849.57  5025.1  850.54
  5035.2  852.14  5040.9  851.67  5047.4  852.80  5105.7  852.55  5121.6  854.40
  5164.8  857.22  5218.0  858.65  5245.4  860.88  5289.3  863.17  5392.9  867.33
#Mann=3,-1,0
  3785.7    0.05       0  5014.0   0.033       0  5024.6    0.05       0
Bank Sta=5014,5024.6
Exp/Cntr=0.3,0.1

Type RM Length L Ch R = 1,102542,886,886,886
BEGIN DESCRIPTION:
Elizabeth Creek 123.0
END DESCRIPTION:
XS GIS Cut Line= 3
      2292679.00      7074359.99      2292679.00      7073360.00
      2292329.00      7073160.00
#Sta/Elev= 30
  3996.2  864.14  4226.2  862.26  4296.2  860.45  4806.2  853.16  4866.2  852.88
  4906.2  854.88  4926.2  853.52  4946.2  853.67  4976.2  851.36  4986.2  850.47
  4993.7  848.46  5004.1  848.30  5004.6  846.82  5006.0  846.32  5015.2  846.82
  5019.2  850.10  5025.7  850.79  5076.8  851.90  5122.2  855.52  5165.4  856.30
  5171.1  855.54  5186.9  856.97  5273.3  859.11  5289.2  860.85  5305.0  860.34
  5310.8  861.37  5341.7  862.19  5348.2  863.06  5354.0  862.41  5399.3  863.74
#Mann=3,-1,0
  3996.2    0.05       0  5004.6   0.033       0  5015.2    0.05       0
Bank Sta=5004.6,5015.2
Exp/Cntr=0.3,0.1

Type RM Length L Ch R = 1,101656,734,734,734
BEGIN DESCRIPTION:
Elizabeth Creek 122.0
END DESCRIPTION:
XS GIS Cut Line= 3
      2293628.99      7074059.98      2293229.00      7072860.00
      2292428.97      7072409.99
#Sta/Elev= 30
  3730.9  865.33  4447.7  854.14  4742.8  852.72  4827.1  851.26  4858.8  851.25
  4869.3  852.13  4900.9  851.63  4953.6  848.25  4998.7  847.60  5009.5  846.59
  5013.1  842.59  5014.6  842.09  5024.4  842.59  5031.2  846.13  5041.4  847.87
  5122.0  848.77  5193.1  852.52  5376.6  856.55  5560.2  862.99  5707.1  866.96
  5716.4  868.02  5722.1  867.39  5730.1  868.74  5738.1  867.53  5743.8  870.17
  5759.7  871.40  5797.3  873.14  5803.1  871.33  5846.4  874.50  5913.7  877.42
#Mann=3,-1,0
  3730.9    0.05       0  5013.1   0.033       0  5024.4    0.05       0
Bank Sta=5013.1,5024.4
Exp/Cntr=0.3,0.1