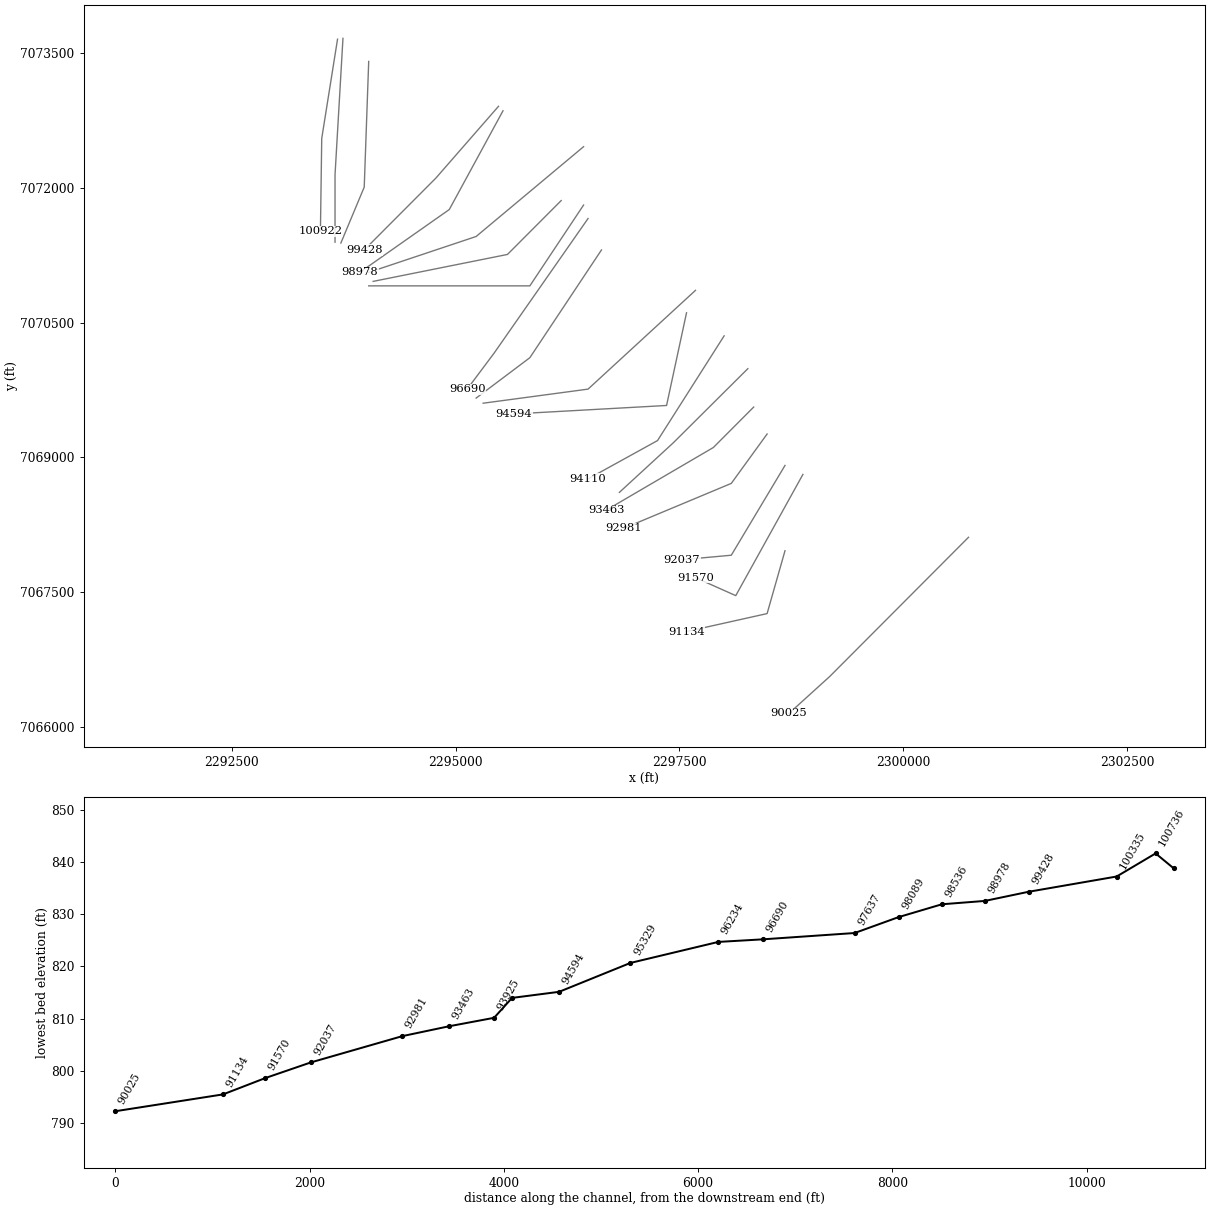
HEC-RAS study Elizabeth Creek.prj: Elizabeth Creek Base Level Engineering

--- Elizabeth Creek.g01 (geometry) --- (continued)

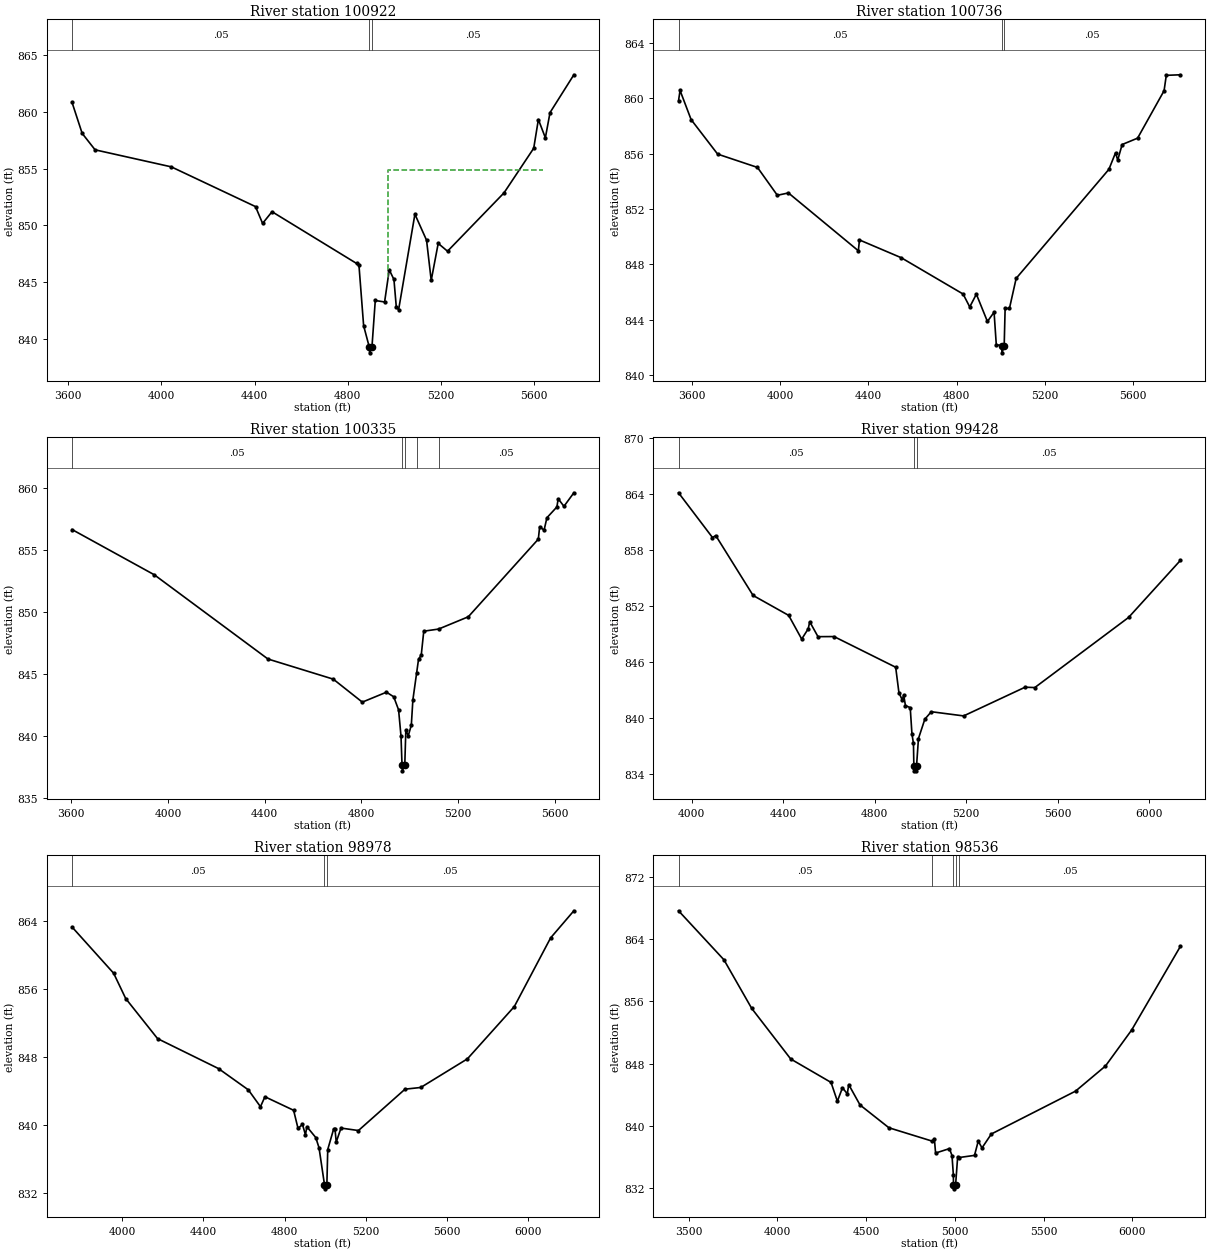
Type RM Length L Ch R = 1,100922,186,186,186
BEGIN DESCRIPTION:
Elizabeth Creek 121.0
END DESCRIPTION:
XS GIS Cut Line= 3
      2293680.86      7073657.52      2293504.36      7072552.05
      2293489.72      7071517.73
#Sta/Elev= 30
  3616.6  860.83  3659.9  858.11  3715.4  856.66  4042.6  855.16  4404.0  851.66
  4434.4  850.18  4474.9  851.21  4838.1  846.65  4848.1  846.48  4868.1  841.17
  4892.5  839.28  4894.0  838.78  4903.8  839.28  4918.1  843.39  4958.1  843.26
  4978.1  846.09  4998.2  845.24  5008.2  842.85  5018.2  842.57  5088.2  850.99
  5138.2  848.70  5158.2  845.16  5188.2  848.42  5228.2  847.73  5470.7  852.87
  5598.2  856.80  5618.2  859.33  5648.2  857.72  5668.2  859.94  5770.5  863.27
#Mann=3,-1,0
  3616.6    0.05       0  4892.5    0.04       0  4903.8    0.05       0
#XS Ineff=1,-1
 4973.20 5639.10  854.86
Permanent Ineff=
       F
Bank Sta=4892.5,4903.8
Exp/Cntr=0.3,0.1

Type RM Length L Ch R = 1,100736,401,401,401
BEGIN DESCRIPTION:
Elizabeth Creek 120.0
END DESCRIPTION:
XS GIS Cut Line= 3
      2293741.47      7073666.85      2293652.89      7072147.06
      2293652.89      7071396.43
#Sta/Elev= 30
  3540.5  859.81  3547.4  860.55  3597.4  858.45  3717.6  855.96  3898.0  855.00
  3988.1  852.99  4038.2  853.16  4355.0  848.99  4360.1  849.77  4549.1  848.49
  4829.5  845.87  4859.6  844.94  4889.6  845.86  4939.7  843.89  4969.8  844.56
  4979.8  842.23  5004.1  842.13  5005.7  841.63  5015.6  842.13  5019.9  844.83
  5039.4  844.83  5069.9  847.00  5489.9  854.86  5519.9  856.05  5529.9  855.53
  5549.9  856.65  5619.9  857.11  5739.9  860.53  5749.9  861.64  5813.5  861.68
#Mann=3,-1,0
  3540.5    0.05       0  5004.1   0.033       0  5015.6    0.05       0
Bank Sta=5004.1,5015.6
Exp/Cntr=0.3,0.1

Type RM Length L Ch R = 1,100335,907,907,907
BEGIN DESCRIPTION:
Elizabeth Creek 119.0
END DESCRIPTION:
XS GIS Cut Line= 3
      2294029.00      7073409.99      2293979.00      7072010.00
      2293718.18      7071387.19
#Sta/Elev= 30
  3603.3  856.63  3943.5  852.99  4413.8  846.21  4684.0  844.59  4804.1  842.74
  4904.1  843.54  4934.1  843.17  4954.2  842.12  4964.2  840.01  4968.4  837.71
  4970.0  837.21  4979.9  837.71  4984.2  840.49  4994.2  840.03  5006.9  840.88
  5013.4  842.93  5028.6  845.05  5036.7  846.18  5048.0  846.53  5058.4  848.45
  5119.6  848.62  5242.7  849.61  5532.4  855.86  5537.9  856.86  5556.2  856.58
  5567.9  857.58  5609.2  858.45  5614.6  859.11  5638.4  858.50  5679.4  859.59
#Mann=5,-1,0
  3603.3    0.05       0  4968.4   0.033       0  4979.9    0.05       0
  5028.6    0.12       0  5119.6    0.05       0
Bank Sta=4968.4,4979.9
Exp/Cntr=0.3,0.1

Type RM Length L Ch R = 1,99428,450,450,450
BEGIN DESCRIPTION:
Elizabeth Creek 118.0
END DESCRIPTION:
XS GIS Cut Line= 3
      2295478.99      7072909.98      2294779.00      7072110.00
      2293978.98      7071309.98
#Sta/Elev= 30
  3942.1  864.11  4090.6  859.31  4104.9  859.52  4268.1  853.10  4423.8  850.96
  4480.7  848.42  4509.2  849.52  4515.8  850.28  4551.9  848.68  4622.1  848.69
  4891.7  845.40  4905.9  842.67  4920.1  841.91  4926.8  842.40  4934.4  841.29
  4955.3  841.07  4962.9  838.23  4969.5  837.23  4971.2  834.79  4972.8  834.29
  4981.3  834.29  4982.9  834.79  4991.3  837.75  5019.2  839.83  5047.5  840.63
  5188.9  840.18  5457.6  843.26  5500.1  843.22  5910.2  850.74  6136.5  856.85
#Mann=3,-1,0
  3942.1    0.05       0  4971.2   0.033       0  4982.9    0.05       0
Bank Sta=4971.2,4982.9
Exp/Cntr=0.3,0.1

Type RM Length L Ch R = 1,98978,442,442,442
BEGIN DESCRIPTION:
Elizabeth Creek 117.0
END DESCRIPTION:
XS GIS Cut Line= 3
      2295529.00      7072860.00      2294929.00      7071760.00
      2293928.96      7071059.97
#Sta/Elev= 30
  3752.2  863.30  3957.2  857.87  4016.6  854.90  4173.7  850.19  4474.1  846.67
  4621.2  844.17  4681.0  842.19  4702.9  843.36  4844.3  841.77  4866.1  839.64
  4888.0  840.11  4902.7  838.89  4909.8  839.84  4953.5  838.57  4969.6  837.37
  4996.5  833.04  4998.1  832.54  5008.3  833.04  5012.6  837.16  5041.8  839.58
  5048.4  839.53  5054.5  838.04  5078.0  839.68  5163.9  839.39  5393.6  844.25
  5471.2  844.45  5701.0  847.81  5932.5  853.96  6111.2  862.02  6225.9  865.21
#Mann=3,-1,0
  3752.2    0.05       0  4996.5   0.033       0  5008.3    0.05       0
Bank Sta=4996.5,5008.3
Exp/Cntr=0.3,0.1

Type RM Length L Ch R = 1,98536,447,447,447
BEGIN DESCRIPTION:
Elizabeth Creek 116.0
END DESCRIPTION:
XS GIS Cut Line= 3
      2296428.99      7072459.99      2295229.00      7071460.00
      2294029.04      7071060.01
#Sta/Elev= 30
  3443.1  867.64  3698.9  861.34  3855.1  855.10  4075.1  848.59  4302.2  845.58
  4338.0  843.16  4366.6  844.89  4394.0  844.11  4401.8  845.30  4465.6  842.68
  4628.3  839.75  4870.9  838.04  4884.7  838.26  4891.2  836.50  4969.3  837.07
  4983.7  836.18  4991.5  833.64  4992.0  832.40  4993.7  831.90  5003.9  832.40
  5015.7  836.04  5022.2  835.92  5110.5  836.20  5131.6  838.04  5152.7  837.16
  5205.4  838.95  5679.8  844.46  5848.4  847.69  5996.0  852.32  6270.0  863.05
#Mann=5,-1,0
  3443.1    0.05       0  4870.9    0.12       0  4992.0    0.07       0
  5003.9    0.12       0  5022.2    0.05       0
Bank Sta=4992,5003.9
Exp/Cntr=0.3,0.1

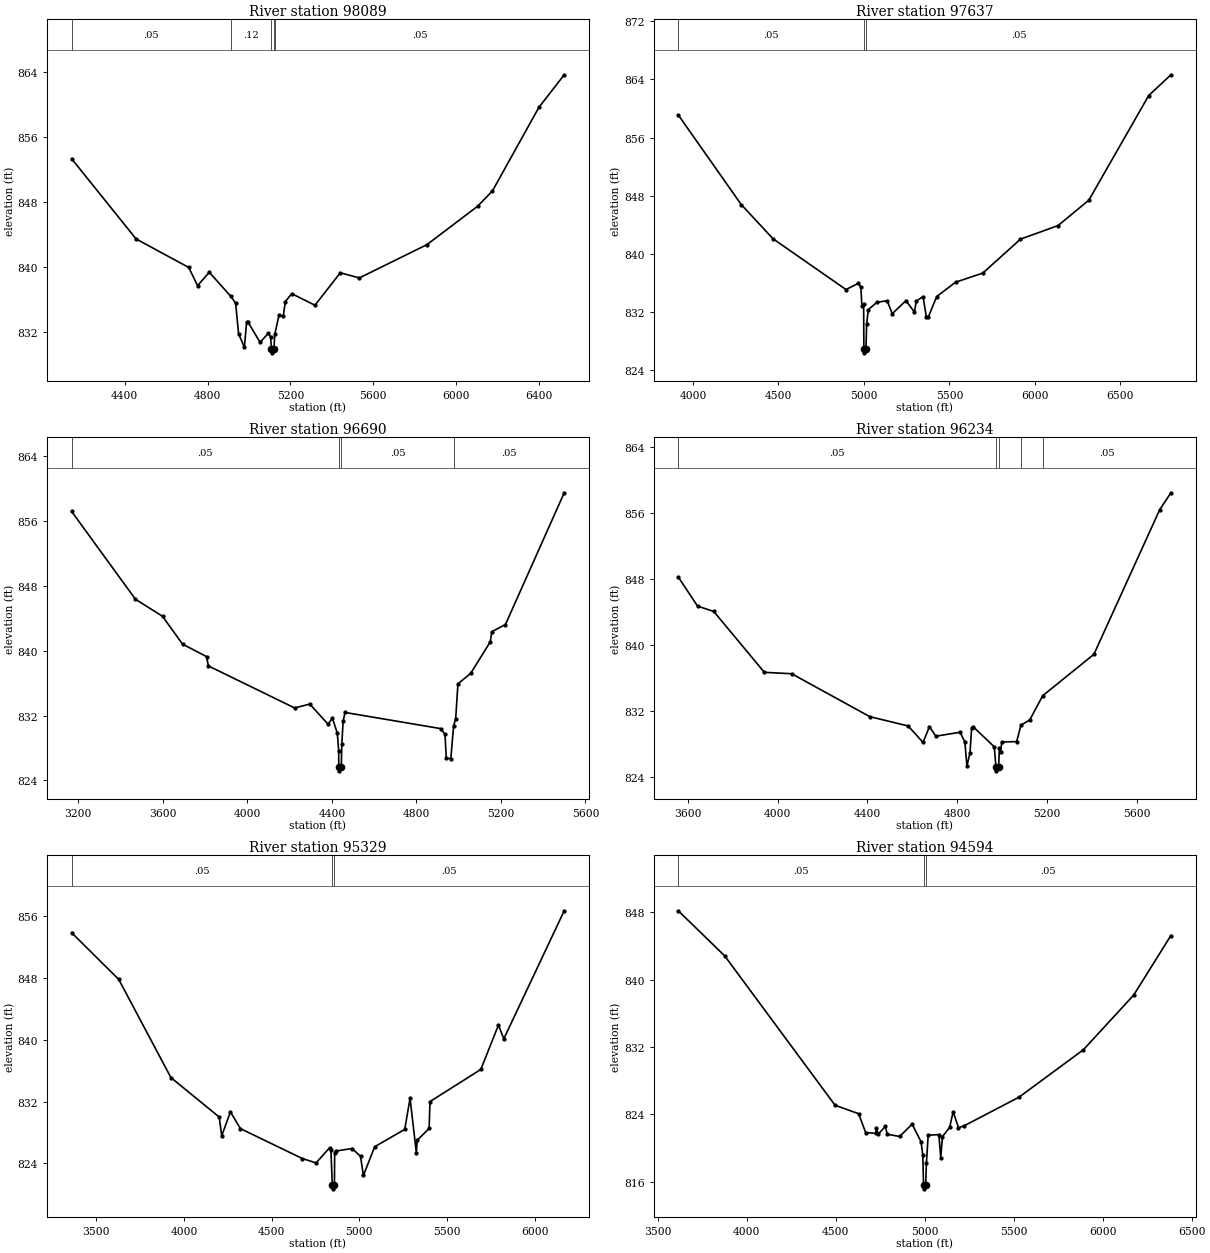
Type RM Length L Ch R = 1,98089,452,452,452
BEGIN DESCRIPTION:
Elizabeth Creek 115.0
END DESCRIPTION:
XS GIS Cut Line= 3
      2296178.97      7071859.97      2295579.00      7071260.00
      2294078.99      7070960.00
#Sta/Elev= 30
  4143.4  853.34  4454.5  843.47  4709.0  839.95  4751.5  837.71  4808.0  839.36
  4912.2  836.39  4935.3  835.55  4949.5  831.78  4977.7  830.12  4988.3  833.25
  4994.4  833.25  5053.1  830.74  5093.9  831.86  5104.1  831.40  5108.3  829.94
  5110.0  829.44  5120.2  829.94  5124.1  831.70  5144.8  834.12  5165.2  833.96
  5175.4  835.76  5206.0  836.73  5318.2  835.30  5440.6  839.30  5532.4  838.66
  5858.7  842.76  6103.5  847.49  6174.9  849.37  6399.2  859.66  6521.6  863.68
#Mann=5,-1,0
  4143.4    0.05       0  4912.2    0.12       0  5108.3    0.07       0
  5120.2    0.12       0  5124.1    0.05       0
Bank Sta=5108.3,5120.2
Exp/Cntr=0.3,0.1

Type RM Length L Ch R = 1,97637,947,947,947
BEGIN DESCRIPTION:
Elizabeth Creek 114.0
END DESCRIPTION:
XS GIS Cut Line= 3
      2296429.00      7071810.00      2295829.00      7070910.00
      2294028.97      7070910.00
#Sta/Elev= 30
  3914.1  859.10  4282.2  846.79  4468.5  842.08  4895.1  835.10  4967.2  835.96
  4982.2  835.39  4988.3  832.79  4998.3  833.05  4999.8  826.90  5001.5  826.40
  5011.8  826.90  5015.8  830.33  5025.8  832.35  5075.8  833.34  5135.8  833.57
  5165.8  831.78  5245.8  833.58  5295.8  831.99  5305.8  833.50  5345.8  834.14
  5365.8  831.27  5375.8  831.27  5425.8  834.14  5535.8  836.11  5695.8  837.37
  5915.8  842.03  6135.8  843.90  6315.8  847.39  6665.8  861.77  6795.8  864.63
#Mann=3,-1,0
  3914.1    0.05       0  4999.8   0.033       0  5011.8    0.05       0
Bank Sta=4999.8,5011.8
Exp/Cntr=0.3,0.1

Type RM Length L Ch R = 1,96690,456,456,456
BEGIN DESCRIPTION:
Elizabeth Creek 113.0
END DESCRIPTION:
XS GIS Cut Line= 3
      2296479.03      7071660.04      2295429.00      7070160.00
      2295129.02      7069760.02
#Sta/Elev= 30
  3168.7  857.17  3470.9  846.34  3599.0  844.24  3693.6  840.81  3807.4  839.27
  3815.7  838.13  4224.2  832.94  4295.7  833.42  4382.0  830.95  4402.9  831.68
  4426.0  829.83  4432.6  827.64  4432.7  825.69  4434.3  825.19  4444.7  825.69
  4447.4  828.52  4453.5  831.28  4462.2  832.39  4914.3  830.40  4935.6  829.69
  4941.7  826.74  4963.1  826.70  4976.3  830.73  4986.2  831.61  4996.7  835.92
  5057.0  837.20  5149.7  841.09  5157.0  842.34  5221.6  843.23  5499.7  859.47
#Mann=4,-1,0
  3168.7    0.05       0  4432.7   0.033       0  4444.7    0.05       0
  4976.3    0.05       0
Bank Sta=4432.7,4444.7
Exp/Cntr=0.3,0.1

Type RM Length L Ch R = 1,96234,905,905,905
BEGIN DESCRIPTION:
Elizabeth Creek 112.0
END DESCRIPTION:
XS GIS Cut Line= 3
      2296628.98      7071309.97      2295829.00      7070110.00
      2295228.99      7069659.99
#Sta/Elev= 30
  3558.3  848.25  3643.9  844.72  3716.0  844.07  3941.4  836.67  4063.0  836.50
  4410.1  831.29  4581.3  830.15  4647.4  828.16  4676.0  830.07  4704.5  828.91
  4812.7  829.39  4833.7  828.18  4842.7  825.29  4856.3  826.85  4863.8  829.94
  4869.8  830.08  4964.4  827.62  4971.9  825.20  4973.6  824.70  4984.0  825.20
  4987.0  827.45  4993.0  826.98  4997.5  828.21  5064.0  828.25  5083.3  830.25
  5122.4  830.89  5180.1  833.83  5407.8  838.86  5700.5  856.42  5750.5  858.49
#Mann=5,-1,0
  3558.3    0.05       0  4971.9   0.033       0  4984.0    0.05       0
  5083.3    0.12       0  5180.1    0.05       0
Bank Sta=4971.9,4984
Exp/Cntr=0.3,0.1

Type RM Length L Ch R = 1,95329,735,735,735
BEGIN DESCRIPTION:
Elizabeth Creek 111.0
END DESCRIPTION:
XS GIS Cut Line= 3
      2297678.99      7070859.99      2296479.00      7069760.00
      2295307.33      7069603.07
#Sta/Elev= 30
  3359.2  853.90  3628.3  847.83  3925.6  835.11  4201.2  829.99  4215.4  827.56
  4265.3  830.66  4322.0  828.49  4675.4  824.61  4753.7  824.04  4831.4  826.02
  4838.2  825.78  4846.3  821.18  4848.0  820.68  4858.4  821.18  4859.7  825.28
  4866.5  825.58  4959.0  825.91  5007.2  824.90  5023.6  822.42  5088.0  826.14
  5259.5  828.39  5289.8  832.43  5325.6  825.38  5330.6  826.98  5398.5  828.51
  5403.6  832.00  5693.3  836.16  5794.2  841.92  5824.5  840.13  6169.2  856.74
#Mann=3,-1,0
  3359.2    0.05       0  4846.3   0.033       0  4858.4    0.05       0
Bank Sta=4846.3,4858.4
Exp/Cntr=0.3,0.1

Type RM Length L Ch R = 1,94594,484,484,484
BEGIN DESCRIPTION:
Elizabeth Creek 110.0
END DESCRIPTION:
XS GIS Cut Line= 3
      2297579.01      7070610.05      2297356.04      7069577.86
      2295647.75      7069483.30
#Sta/Elev= 30
  3616.5  848.19  3877.2  842.83  4497.1  825.08  4629.4  824.08  4668.8  821.84
  4724.4  821.74  4729.6  822.33  4739.6  821.65  4779.7  822.57  4789.7  821.64
  4859.8  821.37  4929.9  822.84  4980.0  820.74  4990.0  819.13  4993.9  815.65
  4995.6  815.15  5006.2  815.65  5010.1  818.18  5020.1  821.53  5080.2  821.59
  5090.6  818.85  5100.2  821.35  5140.3  822.44  5160.3  824.31  5190.3  822.42
  5220.4  822.62  5530.9  826.05  5891.4  831.67  6174.3  838.17  6383.4  845.25
#Mann=3,-1,0
  3616.5    0.05       0  4993.9   0.033       0  5006.2    0.05       0
Bank Sta=4993.9,5006.2
Exp/Cntr=0.3,0.1

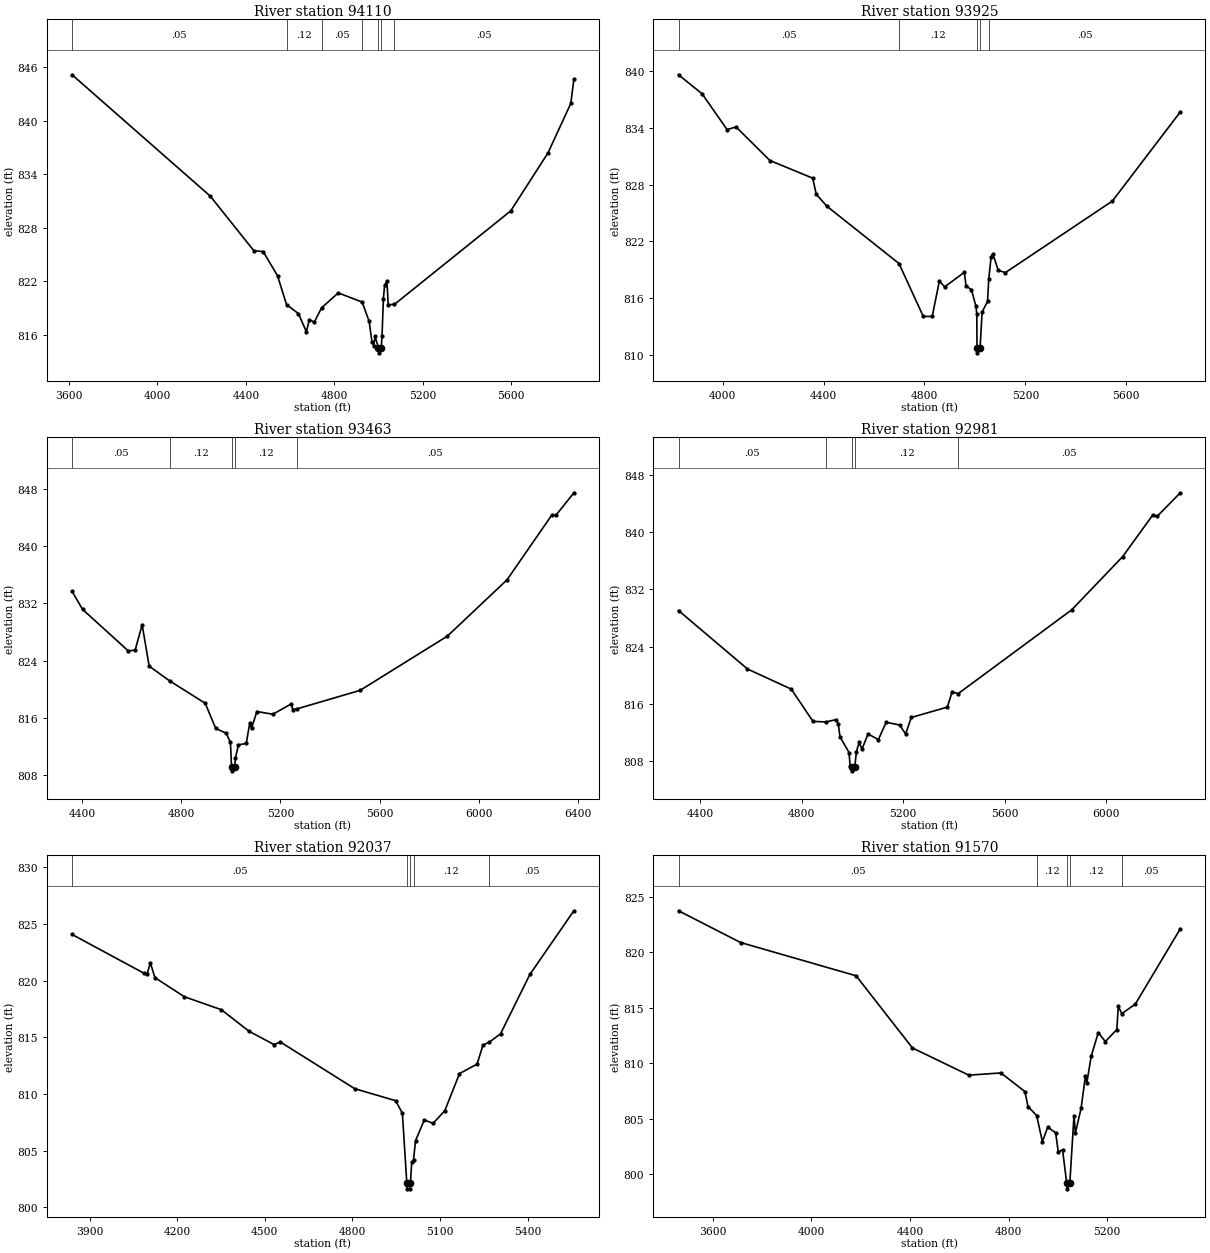
Type RM Length L Ch R = 1,94110,185,185,185
BEGIN DESCRIPTION:
Elizabeth Creek 109.0
END DESCRIPTION:
XS GIS Cut Line= 3
      2297999.05      7070353.26      2297255.18      7069187.02
      2296478.97      7068759.99
#Sta/Elev= 30
  3614.2  845.16  4239.0  831.56  4436.2  825.44  4478.5  825.34  4543.2  822.64
  4584.1  819.40  4638.1  818.38  4673.7  816.35  4687.5  817.72  4709.3  817.42
  4742.5  819.03  4817.8  820.71  4925.9  819.68  4957.5  817.54  4970.2  815.24
  4978.6  814.76  4984.5  815.87  4999.8  814.49  5001.5  813.99  5012.1  814.49
  5015.9  815.84  5022.0  820.08  5027.7  821.56  5038.1  822.01  5043.8  819.39
  5071.8  819.42  5597.8  829.90  5766.4  836.40  5869.6  841.95  5883.4  844.64
#Mann=7,-1,0
  3614.2    0.05       0  4584.1    0.12       0  4742.5    0.05       0
  4925.9    0.12       0  4999.8    0.07       0  5012.1    0.12       0
  5071.8    0.05       0
Bank Sta=4999.8,5012.1
Exp/Cntr=0.3,0.1

Type RM Length L Ch R = 1,93925,462,462,462
BEGIN DESCRIPTION:
Elizabeth Creek 108.0
END DESCRIPTION:
XS GIS Cut Line= 3
      2298263.76      7069987.58      2297429.00      7069160.00
      2296829.00      7068610.00
#Sta/Elev= 30
  3825.1  839.63  3918.7  837.61  4017.7  833.82  4053.0  834.11  4187.4  830.55
  4357.1  828.68  4371.2  826.97  4413.6  825.70  4699.1  819.64  4795.5  814.03
  4830.9  814.04  4859.2  817.79  4880.3  817.17  4958.2  818.71  4965.2  817.23
  4986.4  816.88  5004.0  815.13  5007.7  814.26  5008.3  810.68  5010.0  810.18
  5020.6  810.68  5028.6  814.49  5050.2  815.63  5055.0  817.99  5064.4  820.37
  5071.2  820.67  5092.7  818.91  5121.1  818.68  5545.3  826.26  5814.5  835.70
#Mann=5,-1,0
  3825.1    0.05       0  4699.1    0.12       0  5008.3    0.07       0
  5020.6    0.12       0  5055.0    0.05       0
Bank Sta=5008.3,5020.6
Exp/Cntr=0.3,0.1

Type RM Length L Ch R = 1,93463,482,482,482
BEGIN DESCRIPTION:
Elizabeth Creek 107.0
END DESCRIPTION:
XS GIS Cut Line= 3
      2298329.03      7069560.03      2297879.00      7069110.00
      2296678.98      7068409.99
#Sta/Elev= 30
  4358.7  833.67  4401.2  831.16  4585.0  825.37  4613.3  825.45  4641.6  829.02
  4669.9  823.22  4752.5  821.16  4896.1  818.03  4938.6  814.51  4981.0  813.82
  4998.0  812.57  5002.6  809.07  5004.3  808.57  5015.0  809.07  5018.3  810.37
  5030.3  812.21  5061.7  812.40  5076.2  815.27  5083.2  814.52  5104.7  816.87
  5169.2  816.49  5243.6  817.94  5249.8  817.15  5265.3  817.23  5521.5  819.83
  5873.8  827.42  6114.4  835.29  6296.3  844.41  6312.0  844.33  6384.4  847.48
#Mann=5,-1,0
  4358.7    0.05       0  4752.5    0.12       0  5002.6    0.07       0
  5015.0    0.12       0  5265.3    0.05       0
Bank Sta=5002.6,5015
Exp/Cntr=0.3,0.1

Type RM Length L Ch R = 1,92981,944,944,944
BEGIN DESCRIPTION:
Elizabeth Creek 106.0
END DESCRIPTION:
XS GIS Cut Line= 3
      2298479.01      7069260.02      2298079.00      7068710.00
      2296878.99      7068210.00
#Sta/Elev= 30
  4313.7  829.06  4585.7  820.90  4758.5  818.09  4844.3  813.58  4895.8  813.51
  4936.2  813.84  4944.3  813.16  4950.9  811.42  4986.5  809.24  4990.7  807.41
  4996.8  807.18  4998.6  806.68  5009.2  807.18  5015.5  809.33  5026.3  810.66
  5037.7  809.71  5061.5  811.84  5102.1  811.03  5133.0  813.46  5186.1  813.08
  5209.9  811.83  5232.1  814.13  5374.6  815.58  5393.0  817.70  5417.2  817.46
  5865.3  829.16  6066.3  836.59  6185.5  842.42  6202.3  842.21  6293.8  845.50
#Mann=5,-1,0
  4313.7    0.05       0  4895.8    0.12       0  4996.8    0.07       0
  5009.2    0.12       0  5417.2    0.05       0
Bank Sta=4996.8,5009.2
Exp/Cntr=0.3,0.1

Type RM Length L Ch R = 1,92037,467,467,467
BEGIN DESCRIPTION:
Elizabeth Creek 105.0
END DESCRIPTION:
XS GIS Cut Line= 3
      2298679.00      7068910.00      2298079.00      7067910.00
      2297528.95      7067860.00
#Sta/Elev= 30
  3839.8  824.09  4086.6  820.66  4096.4  820.57  4108.0  821.58  4123.6  820.28
  4224.6  818.59  4351.0  817.45  4446.2  815.54  4531.7  814.37  4553.1  814.60
  4807.7  810.48  4947.7  809.42  4971.0  808.32  4986.2  802.14  4987.9  801.64
  4996.9  801.64  4998.6  802.14  5003.1  804.02  5009.2  804.19  5016.0  805.89
  5046.1  807.72  5076.3  807.42  5116.4  808.54  5166.6  811.81  5226.9  812.65
  5247.0  814.33  5268.4  814.58  5307.2  815.32  5407.6  820.56  5558.3  826.18
#Mann=5,-1,0
  3839.8    0.05       0  4986.2   0.033       0  4998.6    0.05       0
  5009.2    0.12       0  5268.4    0.05       0
Bank Sta=4986.2,4998.6
Exp/Cntr=0.3,0.1

Type RM Length L Ch R = 1,91570,436,436,436
BEGIN DESCRIPTION:
Elizabeth Creek 104.0
END DESCRIPTION:
XS GIS Cut Line= 3
      2298879.01      7068810.01      2298129.00      7067460.00
      2297679.00      7067660.00
#Sta/Elev= 30
  3460.6  823.73  3712.3  820.87  4181.3  817.87  4410.1  811.36  4638.9  808.91
  4769.3  809.11  4866.5  807.43  4879.1  806.08  4914.3  805.27  4937.5  802.91
  4959.2  804.22  4991.2  803.72  5002.1  801.97  5019.3  802.19  5036.3  799.16
  5038.1  798.66  5048.8  799.16  5065.8  805.27  5071.3  803.69  5094.6  805.92
  5112.3  808.86  5117.8  808.21  5135.6  810.61  5164.3  812.75  5193.0  811.94
  5239.6  813.02  5245.7  815.13  5259.8  814.45  5314.8  815.32  5497.4  822.11
#Mann=5,-1,0
  3460.6    0.05       0  4914.3    0.12       0  5036.3    0.07       0
  5048.8    0.12       0  5259.8    0.05       0
Bank Sta=5036.3,5048.8
Exp/Cntr=0.3,0.1

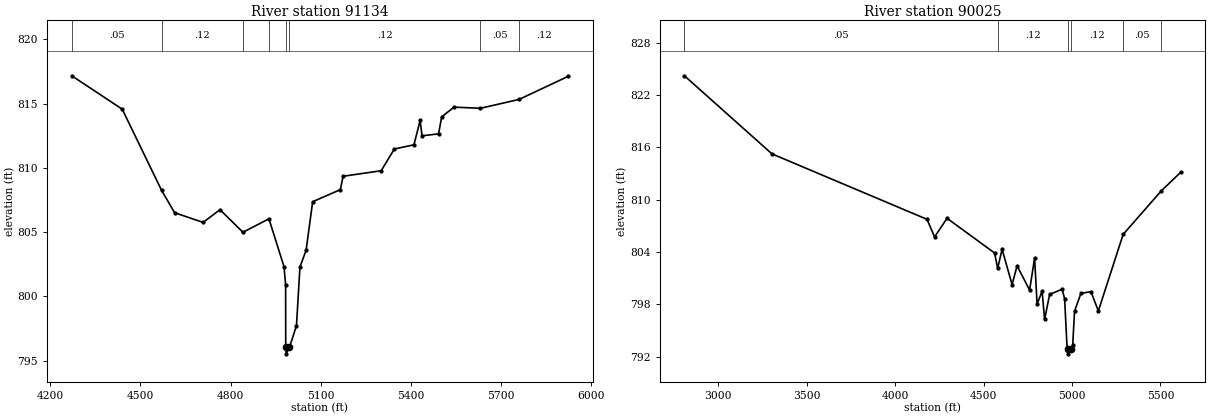
Type RM Length L Ch R = 1,91134,1109,1109,1109
BEGIN DESCRIPTION:
Elizabeth Creek 103.0
END DESCRIPTION:
XS GIS Cut Line= 3
      2298679.00      7067960.00      2298479.00      7067260.00
      2297578.97      7067059.99
#Sta/Elev= 30
  4272.2  817.17  4439.9  814.57  4570.9  808.25  4614.1  806.51  4709.0  805.76
  4764.9  806.75  4841.5  804.99  4927.8  806.04  4978.1  802.30  4983.3  800.89
  4983.6  796.03  4985.3  795.53  4996.1  796.03  5019.4  797.73  5030.9  802.29
  5051.4  803.59  5073.2  807.37  5165.4  808.31  5174.4  809.35  5301.1  809.78
  5344.7  811.47  5410.0  811.80  5430.5  813.69  5436.9  812.50  5491.9  812.65
  5502.2  813.97  5543.1  814.73  5631.0  814.64  5759.6  815.33  5922.2  817.12
#Mann=8,-1,0
  4272.2    0.05       0  4570.9    0.12       0  4841.5    0.05       0
  4927.8    0.12       0  4983.6    0.07       0  4996.1    0.12       0
  5631.0    0.05       0  5759.6    0.12       0
Bank Sta=4983.6,4996.1
Exp/Cntr=0.3,0.1

Type RM Length L Ch R = 1,90025,418,418,418
BEGIN DESCRIPTION:
Elizabeth Creek 102.0
END DESCRIPTION:
XS GIS Cut Line= 3
      2300728.98      7068109.98      2299179.00      7066560.00
      2298724.00      7066148.62
#Sta/Elev= 30
  2808.7  824.21  3303.6  815.25  4180.5  807.74  4222.9  805.72  4293.6  807.86
  4562.3  803.88  4579.7  802.11  4604.7  804.30  4661.3  800.26  4689.6  802.41
  4760.3  799.62  4788.6  803.28  4802.7  798.00  4831.0  799.51  4845.1  796.25
  4873.4  799.12  4944.1  799.73  4958.3  798.64  4972.4  792.94  4977.9  792.81
  4979.9  792.31  4995.3  792.81  5004.1  793.36  5014.5  797.21  5050.4  799.25
  5107.2  799.44  5149.0  797.23  5289.2  806.01  5503.6  810.98  5614.1  813.13
#Mann=6,-1,0
  2808.7    0.05       0  4579.7    0.12       0  4977.9    0.07       0
  4995.3    0.12       0  5289.2    0.05       0  5503.6    0.12       0
Bank Sta=4977.9,4995.3
Exp/Cntr=0.3,0.1