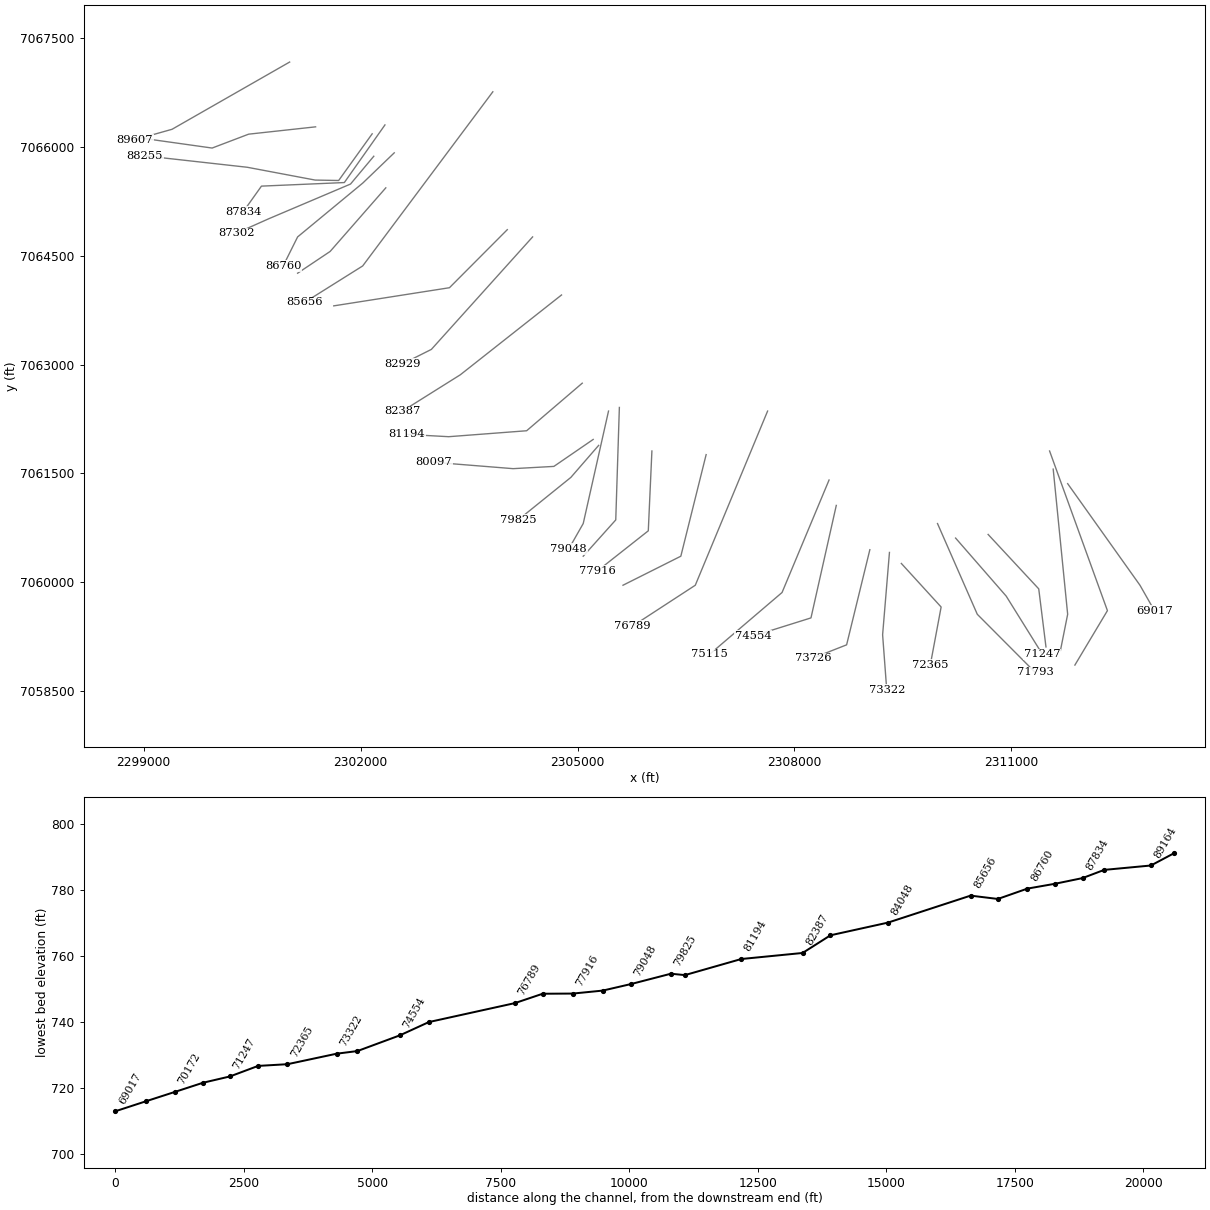
HEC-RAS study Elizabeth Creek.prj: Elizabeth Creek Base Level Engineering

--- Elizabeth Creek.g01 (geometry) --- (continued)

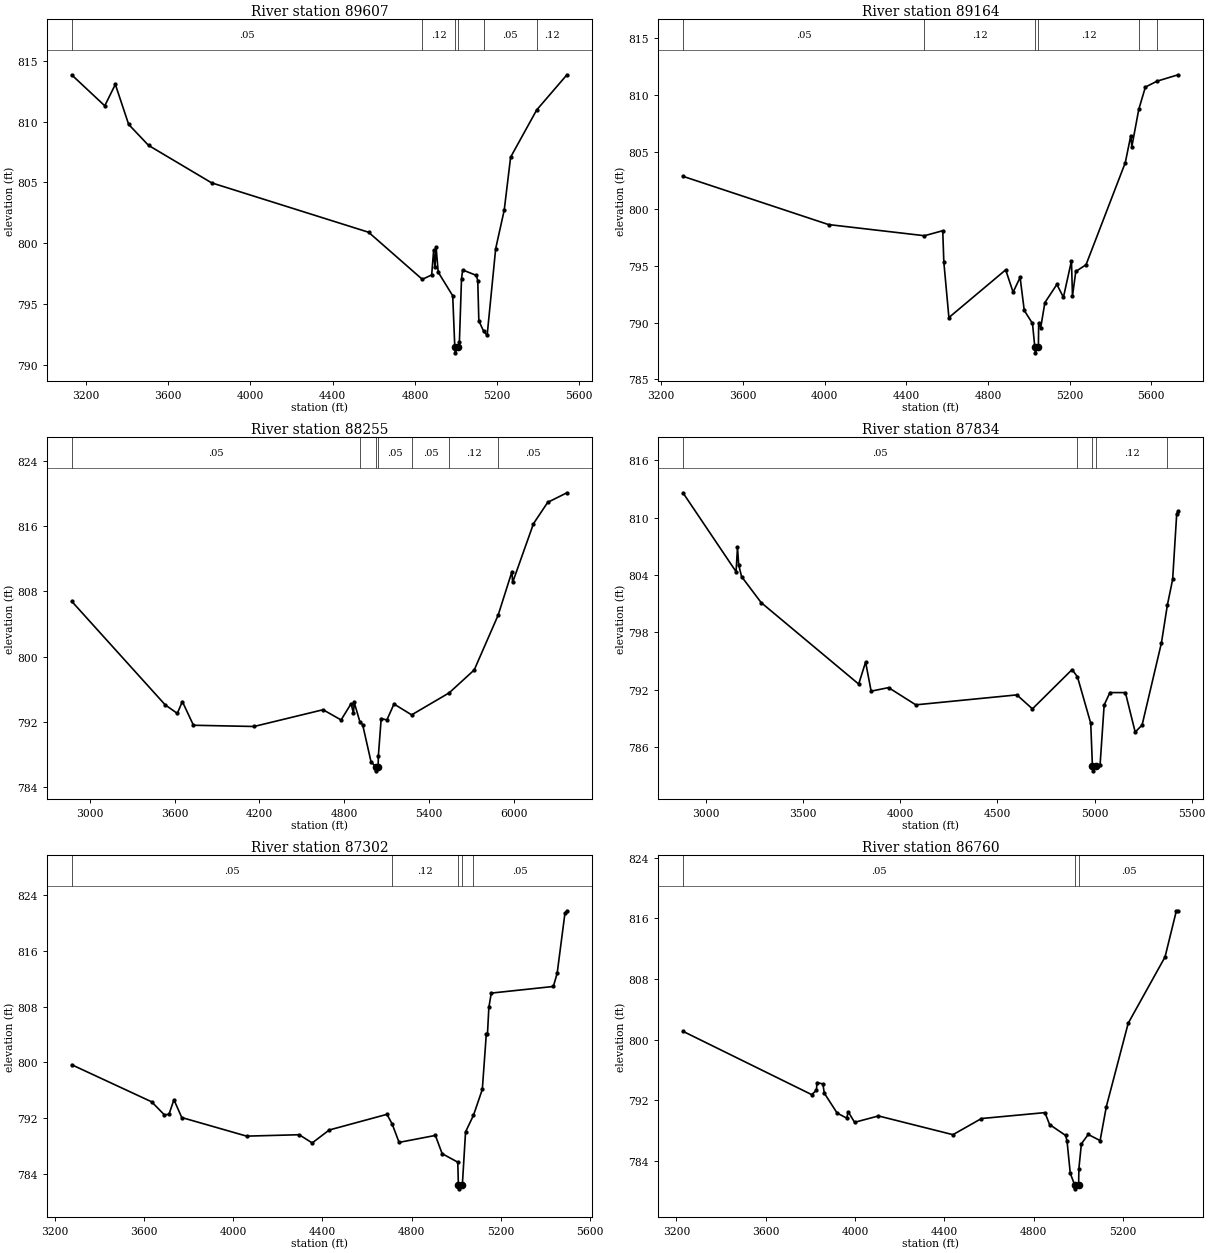
Type RM Length L Ch R = 1,89607,443,443,443
BEGIN DESCRIPTION:
Elizabeth Creek 101.0
END DESCRIPTION:
XS GIS Cut Line= 3
      2301018.58      7067169.83      2299392.17      7066243.15
      2298875.29      7066098.17
#Sta/Elev= 30
  3130.8  813.84  3291.4  811.30  3342.9  813.06  3407.7  809.77  3504.3  808.05
  3811.1  804.97  4574.7  800.91  4836.0  797.04  4881.6  797.40  4891.2  799.43
  4897.5  798.02  4903.2  799.67  4913.3  797.63  4983.9  795.69  4994.0  791.50
  4996.0  791.00  5011.4  791.50  5016.4  791.87  5026.7  797.08  5032.4  797.81
  5099.4  797.36  5105.8  796.90  5111.0  793.63  5134.2  792.78  5151.4  792.44
  5192.9  799.56  5234.5  802.73  5265.6  807.08  5392.4  810.96  5539.5  813.85
#Mann=6,-1,0
  3130.8    0.05       0  4836.0    0.12       0  4994.0    0.07       0
  5011.4    0.12       0  5134.2    0.05       0  5392.4    0.12       0
Bank Sta=4994,5011.4
Exp/Cntr=0.3,0.1

Type RM Length L Ch R = 1,89164,909,909,909
BEGIN DESCRIPTION:
Elizabeth Creek 100.0
END DESCRIPTION:
XS GIS Cut Line= 4
      2301377.75      7066276.91      2300451.87      7066176.06
      2299946.90      7065984.69      2299002.68      7066116.88
#Sta/Elev= 30
  3306.7  802.85  4019.6  798.61  4489.4  797.63  4578.8  798.07  4584.2  795.31
  4609.0  790.44  4887.0  794.63  4923.4  792.67  4957.7  793.97  4977.9  791.07
  5018.3  789.92  5029.7  787.84  5031.7  787.34  5047.2  787.84  5048.6  789.95
  5058.7  789.56  5078.9  791.75  5137.7  793.35  5169.8  792.22  5209.1  795.42
  5214.1  792.34  5230.3  794.49  5280.5  795.08  5472.7  804.05  5499.7  806.43
  5504.8  805.46  5538.7  808.73  5571.1  810.69  5628.5  811.21  5731.5  811.77
#Mann=6,-1,0
  3306.7    0.05       0  4489.4    0.12       0  5029.7    0.07       0
  5047.2    0.12       0  5538.7    0.05       0  5628.5    0.12       0
Bank Sta=5029.7,5047.2
Exp/Cntr=0.3,0.1

Type RM Length L Ch R = 1,88255,421,421,421
BEGIN DESCRIPTION:
Elizabeth Creek 99.0
END DESCRIPTION:
XS GIS Cut Line= 5
      2302160.27      7066180.73      2301696.77      7065537.62
      2301371.56      7065543.43      2300432.29      7065719.93
      2299013.92      7065877.53
#Sta/Elev= 30
  2872.8  806.76  3533.3  794.09  3619.2  793.04  3654.8  794.49  3733.3  791.59
  4161.5  791.44  4649.4  793.49  4776.9  792.24  4848.1  794.24  4864.5  793.03
  4869.6  794.40  4909.4  792.04  4929.5  791.65  4988.7  787.12  5021.6  786.51
  5023.6  786.01  5039.1  786.51  5040.4  787.82  5060.5  792.41  5100.7  792.24
  5151.0  794.19  5275.7  792.86  5541.3  795.56  5718.2  798.36  5887.3  805.07
  5984.8  810.39  5989.8  809.08  6137.1  816.27  6237.7  818.88  6373.6  820.05
#Mann=7,-1,0
  2872.8    0.05       0  4909.4    0.12       0  5021.6    0.07       0
  5039.1    0.05       0  5275.7    0.05       0  5541.3    0.12       0
  5887.3    0.05       0
Bank Sta=5021.6,5039.1
Exp/Cntr=0.3,0.1

Type RM Length L Ch R = 1,87834,532,532,532
BEGIN DESCRIPTION:
Elizabeth Creek 98.0
END DESCRIPTION:
XS GIS Cut Line= 4
      2302336.86      7066303.38      2301775.24      7065509.21
      2300629.00      7065460.00      2300379.00      7065110.00
#Sta/Elev= 30
  2880.4  812.60  3154.0  804.35  3161.3  806.89  3167.4  805.07  3182.2  803.84
  3283.1  801.12  3785.4  792.60  3821.0  794.90  3849.5  791.86  3939.4  792.23
  4079.5  790.43  4600.0  791.47  4680.1  790.01  4884.5  794.12  4912.1  793.35
  4980.4  788.50  4989.1  784.03  4991.1  783.53  5006.6  784.03  5028.6  784.18
  5049.5  790.41  5079.0  791.71  5158.9  791.71  5209.3  787.58  5244.9  788.32
  5344.5  796.91  5375.1  800.87  5402.2  803.54  5423.1  810.39  5430.5  810.70
#Mann=5,-1,0
  2880.4    0.05       0  4912.1    0.12       0  4989.1    0.07       0
  5006.6    0.12       0  5375.1    0.05       0
Bank Sta=4989.1,5006.6
Exp/Cntr=0.3,0.1

Type RM Length L Ch R = 1,87302,542,542,542
BEGIN DESCRIPTION:
Elizabeth Creek 97.0
END DESCRIPTION:
XS GIS Cut Line= 4
      2302182.36      7065871.75      2301860.71      7065488.54
      2300729.00      7065010.00      2300278.98      7064809.99
#Sta/Elev= 30
  3275.3  799.64  3633.6  794.32  3690.8  792.45  3711.6  792.52  3733.7  794.62
  3768.8  792.06  4059.8  789.39  4295.7  789.59  4354.0  788.41  4430.5  790.27
  4689.5  792.52  4713.0  791.11  4743.8  788.49  4906.6  789.49  4937.0  786.87
  5007.1  785.65  5009.9  782.32  5011.9  781.82  5027.5  782.32  5042.0  790.00
  5077.4  792.37  5117.2  796.10  5135.0  804.00  5140.4  804.10  5146.6  807.89
  5157.5  809.93  5435.9  810.88  5453.0  812.78  5487.9  821.40  5496.8  821.75
#Mann=5,-1,0
  3275.3    0.05       0  4713.0    0.12       0  5009.9    0.07       0
  5027.5    0.12       0  5077.4    0.05       0
Bank Sta=5009.9,5027.5
Exp/Cntr=0.3,0.1

Type RM Length L Ch R = 1,86760,573,573,573
BEGIN DESCRIPTION:
Elizabeth Creek 96.0
END DESCRIPTION:
XS GIS Cut Line= 4
      2302465.43      7065918.73      2302030.82      7065502.70
      2301129.00      7064760.00      2300929.01      7064360.03
#Sta/Elev= 30
  3229.4  801.11  3805.9  792.76  3827.2  793.34  3829.4  794.35  3855.9  794.17
  3862.3  792.95  3919.7  790.33  3962.7  789.66  3969.2  790.50  3997.9  789.11
  4104.8  789.95  4438.3  787.48  4566.0  789.61  4850.1  790.39  4870.9  788.82
  4942.6  787.38  4949.1  786.63  4963.5  782.40  4983.3  780.84  4985.3  780.34
  5000.9  780.84  5002.1  783.00  5013.3  786.28  5044.0  787.51  5097.1  786.70
  5125.1  791.19  5222.9  802.17  5387.8  810.91  5438.1  816.94  5446.5  817.00
#Mann=3,-1,0
  3229.4    0.05       0  4983.3   0.033       0  5000.9    0.05       0
Bank Sta=4983.3,5000.9
Exp/Cntr=0.3,0.1

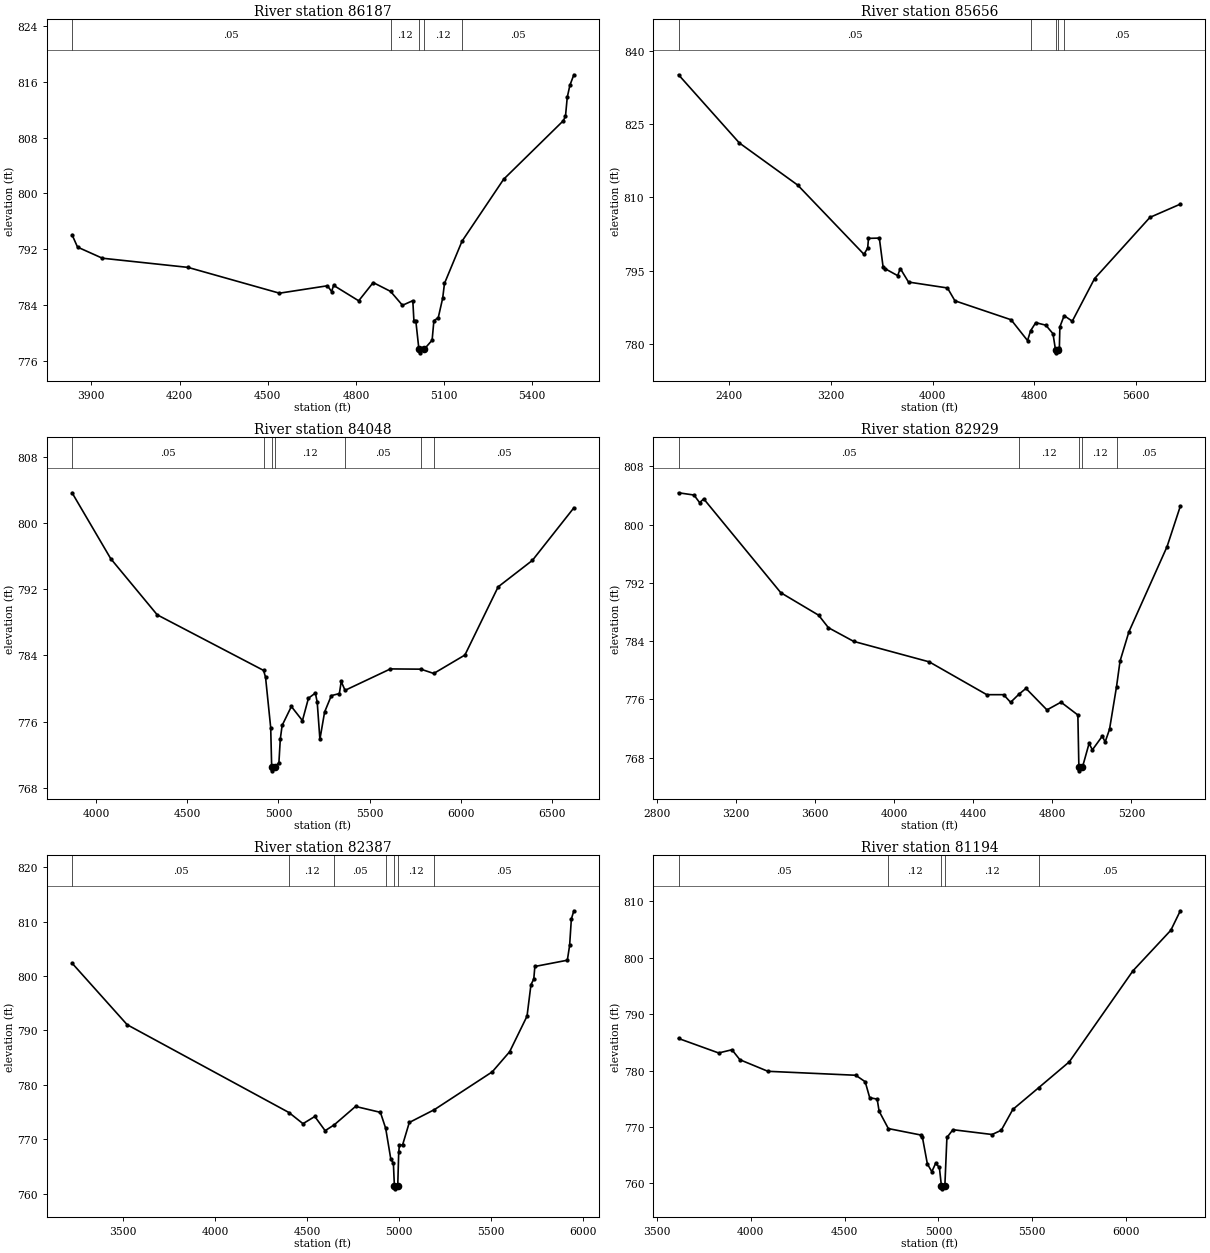
Type RM Length L Ch R = 1,86187,531,531,531
BEGIN DESCRIPTION:
Elizabeth Creek 95.0
END DESCRIPTION:
XS GIS Cut Line= 3
      2302348.64      7065436.26      2301579.00      7064560.00
      2301129.00      7064260.00
#Sta/Elev= 30
  3834.4  794.09  3853.0  792.33  3937.5  790.74  4228.7  789.43  4540.0  785.74
  4703.2  786.80  4717.4  785.97  4724.1  786.86  4809.5  784.65  4858.8  787.26
  4917.8  786.00  4958.4  784.01  4993.6  784.67  4997.3  781.83  5003.7  781.83
  5014.4  777.71  5016.4  777.21  5032.0  777.71  5059.3  779.02  5065.3  781.79
  5080.3  782.26  5095.3  785.04  5101.3  787.13  5161.0  793.17  5302.6  802.03
  5505.4  810.39  5513.0  811.03  5519.0  813.74  5528.0  815.47  5541.5  816.97
#Mann=5,-1,0
  3834.4    0.05       0  4917.8    0.12       0  5014.4    0.07       0
  5032.0    0.12       0  5161.0    0.05       0
Bank Sta=5014.4,5032
Exp/Cntr=0.3,0.1

Type RM Length L Ch R = 1,85656,1608,1608,1608
BEGIN DESCRIPTION:
Elizabeth Creek 94.0
END DESCRIPTION:
XS GIS Cut Line= 3
      2303829.00      7066760.00      2302029.00      7064360.00
      2301229.00      7063860.00
#Sta/Elev= 30
  2003.9  835.06  2482.0  821.12  2940.4  812.51  3461.2  798.36  3490.4  799.65
  3496.6  801.62  3582.0  801.68  3611.2  795.82  3625.8  795.44  3725.8  794.00
  3746.6  795.45  3811.2  792.69  4117.4  791.48  4175.8  788.86  4617.4  784.98
  4746.6  780.73  4770.6  782.73  4811.2  784.39  4890.4  783.87  4946.6  782.13
  4967.0  778.72  4969.0  778.22  4984.6  778.72  4996.6  779.16  5000.8  783.55
  5034.4  785.82  5098.2  784.69  5273.4  793.40  5708.5  805.91  5947.3  808.62
#Mann=5,-1,0
  2003.9    0.05       0  4770.6    0.12       0  4967.0    0.07       0
  4984.6    0.12       0  5034.4    0.05       0
Bank Sta=4967,4984.6
Exp/Cntr=0.3,0.1

Type RM Length L Ch R = 1,84048,1119,1119,1119
BEGIN DESCRIPTION:
Elizabeth Creek 93.0
END DESCRIPTION:
XS GIS Cut Line= 3
      2304028.98      7064859.98      2303229.00      7064060.00
      2301628.95      7063809.99
#Sta/Elev= 30
  3868.9  803.66  4081.0  795.69  4335.6  788.91  4918.6  782.19  4929.5  781.37
  4957.8  775.27  4963.1  770.55  4965.1  770.05  4980.9  770.55  5002.8  771.03
  5010.4  773.90  5020.5  775.54  5071.1  777.83  5131.8  776.12  5164.7  778.83
  5202.7  779.45  5212.8  778.34  5227.5  773.86  5253.3  777.16  5290.2  779.14
  5334.2  779.39  5344.4  780.85  5365.3  779.78  5614.1  782.37  5780.6  782.34
  5851.6  781.82  6022.5  784.05  6204.7  792.29  6392.4  795.49  6619.7  801.84
#Mann=7,-1,0
  3868.9    0.05       0  4918.6    0.12       0  4963.1    0.07       0
  4980.9    0.12       0  5365.3    0.05       0  5780.6    0.12       0
  5851.6    0.05       0
Bank Sta=4963.1,4980.9
Exp/Cntr=0.3,0.1

Type RM Length L Ch R = 1,82929,542,542,542
BEGIN DESCRIPTION:
Elizabeth Creek 92.0
END DESCRIPTION:
XS GIS Cut Line= 3
      2304379.02      7064760.02      2302979.00      7063210.00
      2302579.00      7063010.00
#Sta/Elev= 30
  2911.3  804.36  2989.4  804.05  3017.8  803.01  3038.7  803.52  3428.1  790.65
  3619.4  787.56  3668.7  785.85  3796.5  783.97  4178.4  781.16  4469.0  776.66
  4554.2  776.66  4589.4  775.61  4631.5  776.72  4667.1  777.52  4773.2  774.57
  4844.2  775.63  4929.4  773.87  4934.5  766.71  4936.5  766.21  4952.6  766.71
  4986.1  769.97  5002.8  769.09  5053.1  770.98  5067.1  770.16  5089.4  771.91
  5124.9  777.78  5142.5  781.26  5187.3  785.28  5380.1  796.97  5447.2  802.52
#Mann=5,-1,0
  2911.3    0.05       0  4631.5    0.12       0  4934.5    0.07       0
  4952.6    0.12       0  5124.9    0.05       0
Bank Sta=4934.5,4952.6
Exp/Cntr=0.3,0.1

Type RM Length L Ch R = 1,82387,1193,1193,1193
BEGIN DESCRIPTION:
Elizabeth Creek 91.0
END DESCRIPTION:
XS GIS Cut Line= 3
      2304779.01      7063960.00      2303379.00      7062860.00
      2302578.96      7062359.98
#Sta/Elev= 30
  3224.7  802.35  3523.9  791.03  4401.9  774.89  4478.2  772.84  4542.4  774.16
  4598.5  771.55  4648.3  772.64  4763.5  776.01  4898.5  774.92  4927.2  771.97
  4954.6  766.40  4969.0  765.53  4974.4  761.36  4976.4  760.86  4992.5  761.36
  4997.9  767.64  5002.0  768.93  5018.7  768.91  5055.3  773.06  5192.0  775.43
  5505.7  782.37  5600.1  786.07  5694.4  792.61  5715.7  798.38  5731.0  799.43
  5736.9  801.74  5913.2  802.89  5925.6  805.61  5935.0  810.48  5948.6  811.98
#Mann=7,-1,0
  3224.7    0.05       0  4401.9    0.12       0  4648.3    0.05       0
  4927.2    0.12       0  4974.4    0.07       0  4992.5    0.12       0
  5192.0    0.05       0
Bank Sta=4974.4,4992.5
Exp/Cntr=0.3,0.1

Type RM Length L Ch R = 1,81194,1097,1097,1097
BEGIN DESCRIPTION:
Elizabeth Creek 90.0
END DESCRIPTION:
XS GIS Cut Line= 4
      2305065.55      7062744.52      2304296.52      7062088.95
      2303218.57      7062007.00      2302638.61      7062038.52
#Sta/Elev= 30
  3615.7  785.68  3829.4  783.11  3900.2  783.68  3942.5  781.91  4091.8  779.86
  4559.5  779.16  4609.8  778.01  4633.8  775.18  4673.6  774.93  4683.9  772.79
  4733.1  769.71  4904.5  768.58  4914.6  768.16  4940.9  763.45  4964.7  762.07
  4984.8  763.54  5004.8  762.84  5015.8  759.53  5017.8  759.03  5034.0  759.53
  5045.0  768.13  5077.1  769.51  5285.6  768.66  5334.4  769.41  5396.0  773.10
  5533.6  776.95  5696.8  781.54  6035.6  797.66  6237.6  804.86  6288.1  808.31
#Mann=5,-1,0
  3615.7    0.05       0  4733.1    0.12       0  5015.8    0.07       0
  5034.0    0.12       0  5533.6    0.05       0
Bank Sta=5015.8,5034
Exp/Cntr=0.3,0.1

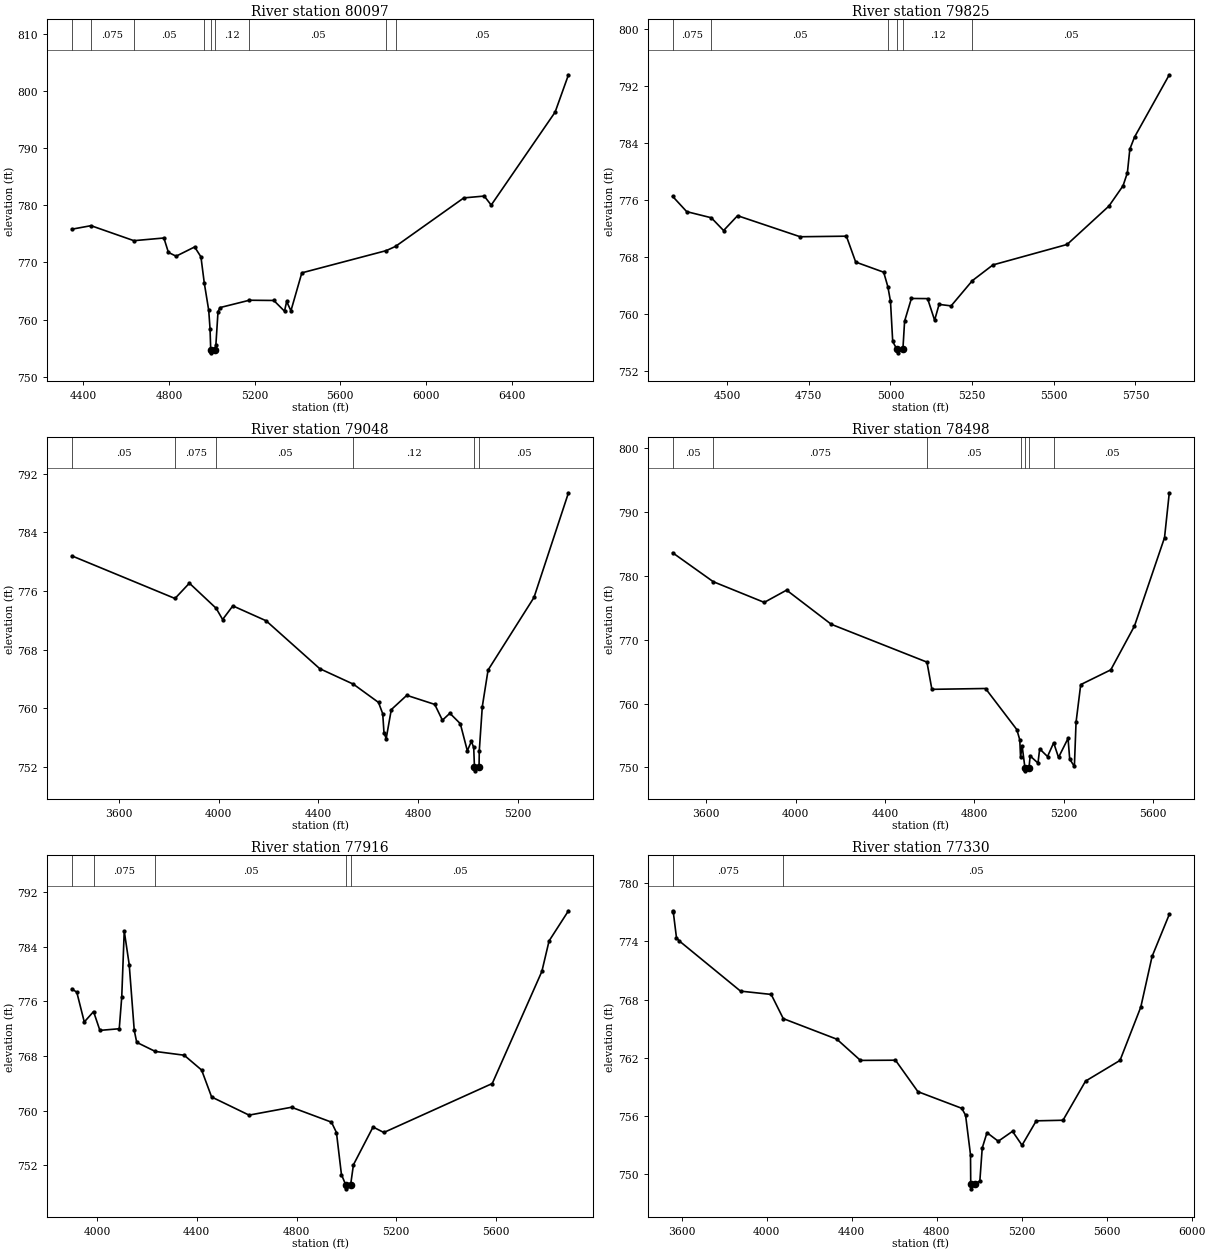
Type RM Length L Ch R = 1,80097,272,272,272
BEGIN DESCRIPTION:
Elizabeth Creek 89.0
END DESCRIPTION:
XS GIS Cut Line= 4
      2305216.83      7061969.15      2304673.33      7061597.62
      2304109.09      7061566.56      2303016.83      7061653.99
#Sta/Elev= 30
  4346.4  775.83  4436.1  776.45  4636.3  773.82  4776.4  774.29  4797.4  771.77
  4833.3  771.10  4920.0  772.72  4949.4  770.98  4964.9  766.42  4985.7  761.62
  4991.8  758.42  4995.1  754.66  4997.1  754.16  5013.5  754.66  5019.1  755.51
  5029.1  761.38  5039.1  762.10  5175.5  763.38  5289.5  763.34  5339.6  761.46
  5349.6  763.16  5369.6  761.53  5420.5  768.18  5815.0  772.08  5858.1  772.82
  6176.9  781.32  6272.2  781.64  6304.8  780.06  6603.2  796.35  6665.6  802.90
#Mann=9,-1,0
  4346.4    0.05       0  4436.1   0.075       0  4636.3    0.05       0
  4964.9    0.12       0  4995.1    0.07       0  5013.5    0.12       0
  5175.5    0.05       0  5815.0    0.12       0  5858.1    0.05       0
Bank Sta=4995.1,5013.5
Exp/Cntr=0.3,0.1

Type RM Length L Ch R = 1,79825,777,777,777
BEGIN DESCRIPTION:
Elizabeth Creek 88.0
END DESCRIPTION:
XS GIS Cut Line= 3
      2305292.51      7061887.22      2304907.98      7061445.96
      2304178.99      7060859.99
#Sta/Elev= 30
  4333.0  776.51  4376.1  774.37  4451.4  773.51  4489.0  771.72  4531.8  773.80
  4723.5  770.85  4865.0  770.93  4893.5  767.30  4979.2  765.88  4992.1  763.82
  5000.0  761.79  5006.8  756.17  5019.6  755.08  5021.6  754.58  5038.0  755.08
  5043.2  759.02  5064.0  762.20  5113.6  762.18  5135.1  759.15  5148.8  761.37
  5185.6  761.16  5250.7  764.70  5313.6  766.90  5540.8  769.77  5668.8  775.15
  5712.0  777.99  5725.3  779.82  5732.8  783.13  5747.2  784.82  5853.6  793.55
#Mann=6,-1,0
  4333.0   0.075       0  4451.4    0.05       0  4992.1    0.12       0
  5019.6    0.07       0  5038.0    0.12       0  5250.7    0.05       0
Bank Sta=5019.6,5038
Exp/Cntr=0.3,0.1

Type RM Length L Ch R = 1,79048,550,550,550
BEGIN DESCRIPTION:
Elizabeth Creek 87.0
END DESCRIPTION:
XS GIS Cut Line= 3
      2305429.00      7062360.02      2305079.00      7060810.00
      2304878.98      7060459.96
#Sta/Elev= 30
  3410.7  780.80  3824.6  774.98  3882.3  777.07  3989.7  773.64  4015.6  772.11
  4056.6  773.97  4189.9  771.94  4405.1  765.40  4540.2  763.28  4640.9  760.79
  4657.8  759.25  4662.9  756.64  4671.7  755.85  4692.2  759.81  4754.4  761.76
  4866.5  760.52  4897.2  758.36  4927.2  759.31  4969.0  757.89  4997.2  754.19
  5013.4  755.47  5022.8  754.64  5025.8  751.95  5027.8  751.45  5044.2  751.95
  5045.1  754.16  5057.3  760.23  5080.4  765.21  5264.6  775.12  5402.9  789.41
#Mann=6,-1,0
  3410.7    0.05       0  3824.6   0.075       0  3989.7    0.05       0
  4540.2    0.12       0  5025.8    0.07       0  5044.2    0.05       0
Bank Sta=5025.8,5044.2
Exp/Cntr=0.3,0.1

Type RM Length L Ch R = 1,78498,582,582,582
BEGIN DESCRIPTION:
Elizabeth Creek 86.0
END DESCRIPTION:
XS GIS Cut Line= 3
      2305579.00      7062409.96      2305529.00      7060860.00
      2305079.03      7060360.04
#Sta/Elev= 30
  3449.3  783.61  3631.2  779.08  3859.5  775.84  3959.5  777.76  4159.6  772.41
  4587.8  766.49  4609.9  762.23  4850.0  762.36  4990.1  755.93  5003.4  754.32
  5006.8  751.63  5013.9  753.38  5026.4  749.97  5028.4  749.47  5044.8  749.97
  5049.8  751.81  5084.9  750.68  5092.4  752.91  5127.5  751.71  5155.1  753.86
  5176.8  751.57  5219.4  754.55  5226.9  751.31  5247.8  750.15  5255.3  757.08
  5276.2  762.97  5410.8  765.28  5516.9  772.15  5651.4  785.98  5672.7  793.00
#Mann=7,-1,0
  3449.3    0.05       0  3631.2   0.075       0  4587.8    0.05       0
  5006.8    0.12       0  5026.4   0.033       0  5044.8    0.12       0
  5155.1    0.05       0
Bank Sta=5026.4,5044.8
Exp/Cntr=0.3,0.1

Type RM Length L Ch R = 1,77916,586,586,586
BEGIN DESCRIPTION:
Elizabeth Creek 85.0
END DESCRIPTION:
XS GIS Cut Line= 3
      2306029.00      7061810.00      2305979.00      7060710.00
      2305278.97      7060159.97
#Sta/Elev= 30
  3898.9  777.81  3918.9  777.32  3948.9  772.97  3986.1  774.49  4011.5  771.74
  4089.1  771.98  4099.1  776.61  4109.1  786.28  4129.1  781.34  4149.2  771.76
  4159.2  769.99  4233.7  768.66  4349.4  768.11  4419.4  765.94  4459.5  762.00
  4609.6  759.35  4779.8  760.50  4940.0  758.32  4960.0  756.80  4980.0  750.66
  4998.1  749.07  5000.1  748.57  5016.5  749.07  5028.1  752.09  5106.7  757.61
  5150.0  756.81  5584.7  763.97  5783.6  780.36  5812.5  784.82  5890.3  789.23
#Mann=5,-1,0
  3898.9    0.05       0  3986.1   0.075       0  4233.7    0.05       0
  4998.1   0.033       0  5016.5    0.05       0
Bank Sta=4998.1,5016.5
Exp/Cntr=0.3,0.1

Type RM Length L Ch R = 1,77330,541,541,541
BEGIN DESCRIPTION:
Elizabeth Creek 84.0
END DESCRIPTION:
XS GIS Cut Line= 3
      2306779.01      7061760.03      2306429.00      7060360.00
      2305629.04      7059960.02
#Sta/Elev= 30
  3557.2  777.14  3560.5  776.97  3575.3  774.36  3588.2  774.04  3876.8  768.87
  4021.1  768.53  4077.9  766.04  4330.3  763.92  4441.1  761.74  4606.0  761.76
  4711.7  758.52  4917.9  756.81  4935.9  756.10  4959.1  752.03  4960.2  749.02
  4962.2  748.52  4978.6  749.02  5003.1  749.33  5014.3  752.72  5036.7  754.30
  5089.8  753.42  5156.8  754.44  5201.6  753.01  5268.6  755.52  5394.4  755.58
  5500.6  759.61  5662.8  761.74  5760.6  767.23  5813.7  772.44  5894.7  776.77
#Mann=3,-1,0
  3557.2     0.1       0  3560.5   0.075       0  4077.9    0.05       0
Bank Sta=4960.2,4978.6
Exp/Cntr=0.3,0.1

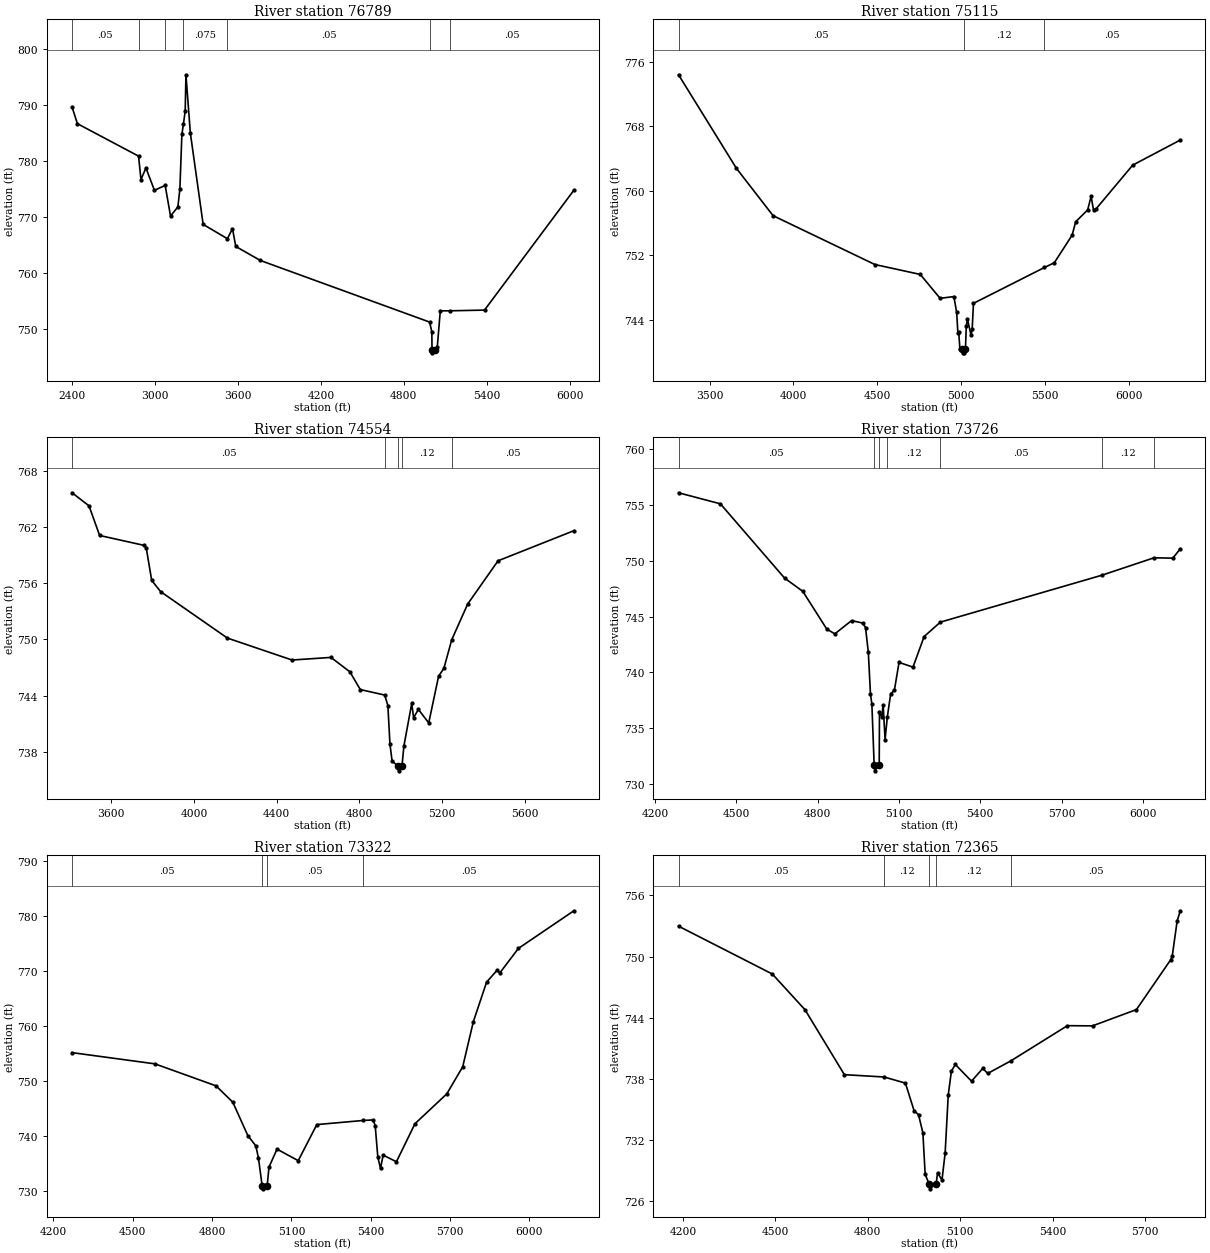
Type RM Length L Ch R = 1,76789,1674,1674,1674
BEGIN DESCRIPTION:
Elizabeth Creek 83.0
END DESCRIPTION:
XS GIS Cut Line= 3
      2307629.01      7062360.02      2306629.00      7059960.00
      2305764.51      7059398.62
#Sta/Elev= 30
  2400.0  789.61  2438.5  786.64  2881.1  780.84  2898.4  776.66  2934.6  778.72
  2995.9  774.73  3073.7  775.60  3112.3  770.14  3165.4  771.75  3180.0  774.93
  3194.6  784.72  3205.7  786.57  3218.5  788.86  3223.9  795.38  3255.9  784.95
  3348.5  768.64  3523.7  766.08  3560.8  767.87  3584.6  764.69  3762.3  762.19
  4986.9  751.18  5003.2  749.42  5004.5  746.18  5006.5  745.68  5022.9  746.18
  5042.4  746.67  5064.4  753.19  5131.1  753.19  5384.3  753.32  6030.8  774.74
#Mann=7,-1,0
  2400.0    0.05       0  2881.1   0.075       0  3073.7    0.05       0
  3205.7   0.075       0  3523.7    0.05       0  4986.9    0.12       0
  5131.1    0.05       0
Bank Sta=5004.5,5022.9
Exp/Cntr=0.3,0.1

Type RM Length L Ch R = 1,75115,561,561,561
BEGIN DESCRIPTION:
Elizabeth Creek 82.0
END DESCRIPTION:
XS GIS Cut Line= 3
      2308479.01      7061410.02      2307829.00      7059860.00
      2306829.03      7059010.02
#Sta/Elev= 30
  3314.5  774.38  3659.9  762.79  3878.4  756.93  4485.6  750.88  4756.7  749.65
  4874.8  746.69  4956.9  746.91  4973.6  744.94  4980.7  742.44  4986.1  742.47
  4992.6  740.46  5007.5  740.44  5009.5  739.94  5018.1  739.94  5026.0  740.44
  5031.0  743.21  5037.6  744.15  5059.6  742.10  5066.1  742.86  5073.8  746.07
  5497.0  750.51  5556.0  751.10  5662.5  754.52  5683.4  756.17  5754.8  757.64
  5775.6  759.31  5789.9  757.63  5804.2  757.75  6023.8  763.19  6307.7  766.30
#Mann=3,-1,0
  3314.5    0.05       0  5018.1    0.12       0  5497.0    0.05       0
Bank Sta=5007.5,5026
Exp/Cntr=0.3,0.1

Type RM Length L Ch R = 1,74554,828,828,828
BEGIN DESCRIPTION:
Elizabeth Creek 81.0
END DESCRIPTION:
XS GIS Cut Line= 3
      2308579.00      7061059.98      2308229.00      7059510.00
      2307428.96      7059259.99
#Sta/Elev= 30
  3410.7  765.70  3492.7  764.30  3544.0  761.13  3759.2  760.07  3769.5  759.80
  3795.9  756.32  3839.1  755.12  4162.0  750.15  4474.7  747.80  4662.9  748.08
  4754.4  746.54  4804.9  744.64  4923.0  744.05  4938.2  742.93  4948.4  738.80
  4958.7  736.98  4987.8  736.44  4989.8  735.94  5006.4  736.44  5015.9  738.61
  5053.7  743.15  5062.6  741.64  5086.1  742.51  5135.9  741.07  5183.6  746.07
  5209.2  746.91  5247.2  749.97  5324.5  753.80  5471.2  758.42  5837.9  761.64
#Mann=5,-1,0
  3410.7    0.05       0  4923.0    0.12       0  4987.8    0.07       0
  5006.4    0.12       0  5247.2    0.05       0
Bank Sta=4987.8,5006.4
Exp/Cntr=0.3,0.1

Type RM Length L Ch R = 1,73726,404,404,404
BEGIN DESCRIPTION:
Elizabeth Creek 80.5
END DESCRIPTION:
XS GIS Cut Line= 3
      2309043.28      7060449.98      2308721.78      7059138.78
      2308255.27      7058955.95
#Sta/Elev= 30
  4287.1  756.10  4441.5  755.11  4678.3  748.45  4745.6  747.26  4833.9  743.88
  4863.7  743.45  4925.4  744.64  4966.6  744.42  4976.9  744.02  4987.2  741.80
  4995.2  738.03  5000.3  737.18  5008.8  731.67  5010.8  731.17  5027.4  731.67
  5028.4  736.46  5036.7  736.01  5041.9  737.09  5049.0  733.97  5057.4  736.00
  5069.6  738.07  5083.5  738.41  5100.5  740.89  5152.0  740.47  5193.1  743.21
  5252.8  744.50  5849.0  748.71  6041.0  750.27  6110.4  750.24  6138.2  751.08
#Mann=7,-1,0
  4287.1    0.05       0  5008.8    0.05       0  5027.4    0.05       0
  5057.4    0.12       0  5252.8    0.05       0  5849.0    0.12       0
  6041.0    0.05       0
Bank Sta=5008.8,5027.4
Exp/Cntr=0.3,0.1

Type RM Length L Ch R = 1,73322,957,957,957
BEGIN DESCRIPTION:
Elizabeth Creek 80.2
END DESCRIPTION:
XS GIS Cut Line= 3
      2309314.34      7060412.17      2309219.78      7059277.46
      2309276.51      7058521.02
#Sta/Elev= 30
  4270.7  755.17  4583.9  753.13  4814.7  749.13  4878.4  746.15  4935.2  740.07
  4965.3  738.21  4975.3  736.01  4989.5  730.87  4991.5  730.37  5008.1  730.87
  5015.4  734.35  5045.5  737.60  5125.8  735.50  5196.1  742.07  5371.7  742.82
  5409.3  742.92  5416.8  741.87  5426.8  736.10  5436.9  734.12  5446.9  736.51
  5497.0  735.30  5567.2  742.23  5687.6  747.67  5747.7  752.60  5787.9  760.82
  5838.0  768.01  5878.1  770.20  5888.1  769.69  5958.3  774.15  6167.9  781.00
#Mann=4,-1,0
  4270.7    0.05       0  4989.5   0.033       0  5008.1    0.05       0
  5371.7    0.05       0
Bank Sta=4989.5,5008.1
Exp/Cntr=0.3,0.1

Type RM Length L Ch R = 1,72365,572,572,572
BEGIN DESCRIPTION:
Elizabeth Creek 80.0
END DESCRIPTION:
XS GIS Cut Line= 3
      2309478.97      7060260.03      2310029.00      7059660.00
      2309879.00      7058860.02
#Sta/Elev= 30
  4186.1  752.98  4490.4  748.28  4596.5  744.77  4724.1  738.40  4853.1  738.17
  4922.1  737.57  4950.4  734.85  4964.6  734.48  4978.8  732.69  4986.2  728.62
  4998.6  727.69  5001.0  727.19  5021.9  727.69  5026.4  728.76  5040.8  728.06
  5051.0  730.70  5061.1  736.40  5071.3  738.74  5084.0  739.40  5136.6  737.76
  5173.0  739.01  5189.2  738.52  5265.1  739.77  5447.7  743.21  5529.1  743.19
  5671.6  744.79  5782.7  749.68  5787.7  750.03  5803.8  753.51  5814.0  754.49
#Mann=5,-1,0
  4186.1    0.05       0  4853.1    0.12       0  4998.6    0.07       0
  5021.9    0.12       0  5265.1    0.05       0
Bank Sta=4998.6,5021.9
Exp/Cntr=0.3,0.1

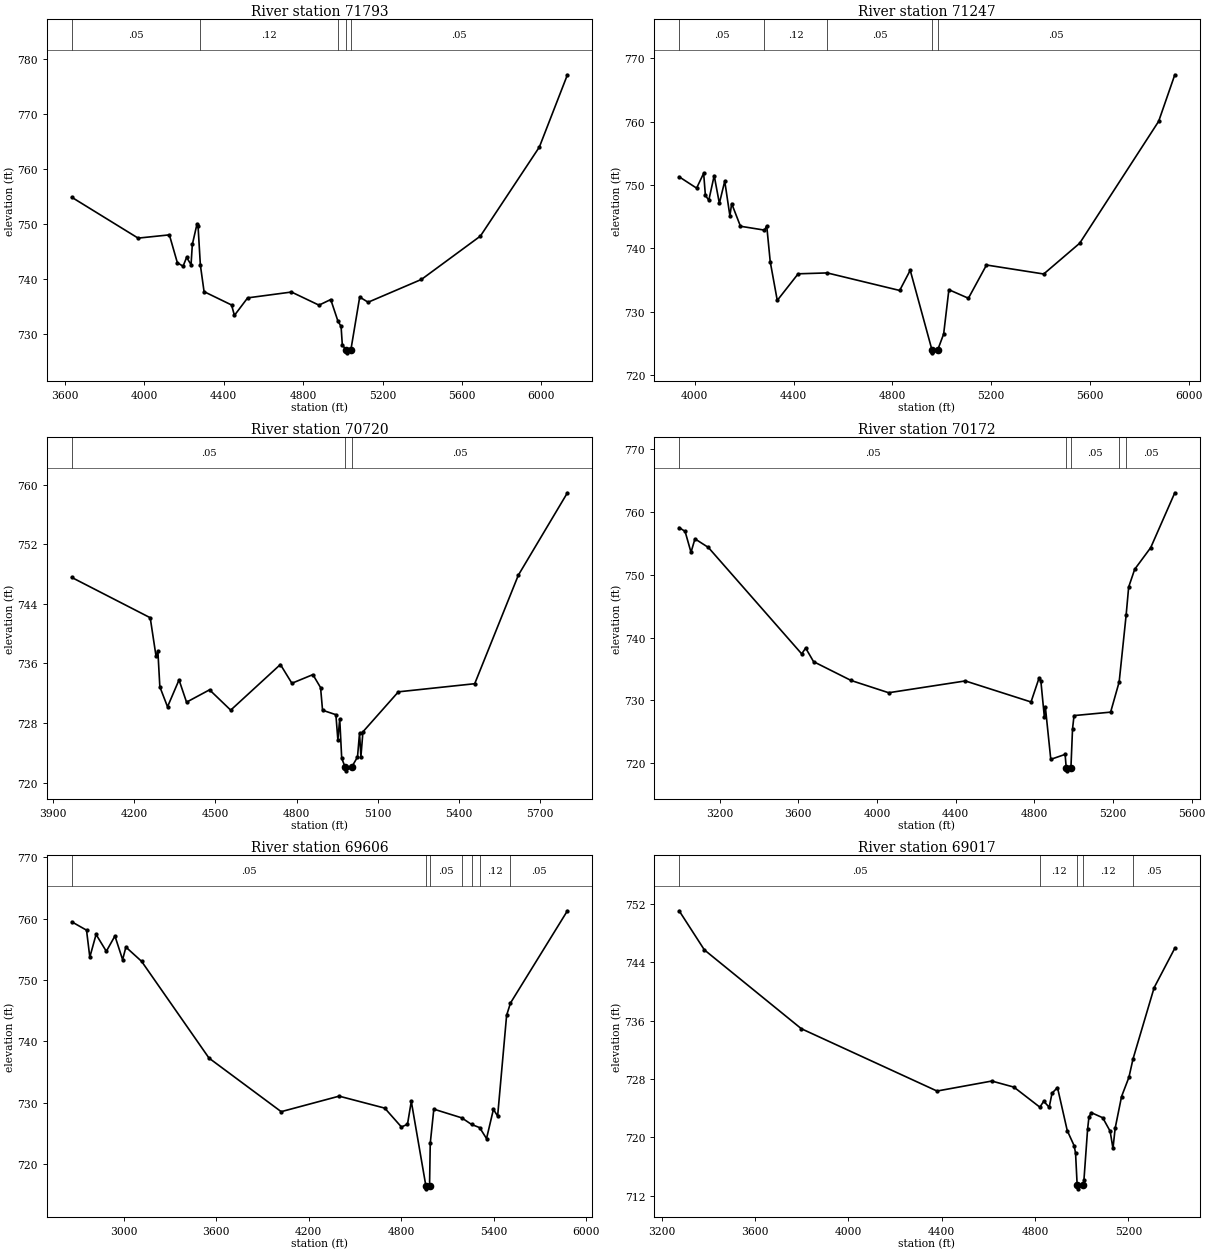
Type RM Length L Ch R = 1,71793,546,546,546
BEGIN DESCRIPTION:
Elizabeth Creek 79.0
END DESCRIPTION:
XS GIS Cut Line= 3
      2309978.99      7060810.02      2310529.00      7059560.00
      2311328.97      7058760.03
#Sta/Elev= 30
  3634.3  754.89  3968.5  747.48  4126.0  748.07  4166.2  743.02  4195.0  742.38
  4212.9  743.99  4235.2  742.66  4241.7  746.33  4265.0  750.00  4270.5  749.65
  4282.2  742.59  4300.8  737.77  4439.3  735.35  4453.7  733.46  4520.3  736.64
  4741.2  737.70  4879.8  735.32  4938.9  736.34  4975.4  732.40  4991.0  731.47
  4997.2  728.14  5016.3  727.17  5018.7  726.67  5040.2  727.17  5084.8  736.79
  5127.3  735.85  5396.0  739.99  5692.9  747.85  5989.9  764.00  6131.3  777.11
#Mann=5,-1,0
  3634.3    0.05       0  4282.2    0.12       0  4975.4    0.05       0
  5016.3    0.07       0  5040.2    0.05       0
Bank Sta=5016.3,5040.2
Exp/Cntr=0.3,0.1

Type RM Length L Ch R = 1,71247,527,527,527
BEGIN DESCRIPTION:
Elizabeth Creek 78.0
END DESCRIPTION:
XS GIS Cut Line= 3
      2310228.98      7060610.02      2310929.00      7059810.00
      2311428.98      7059010.03
#Sta/Elev= 30
  3937.0  751.29  4007.7  749.50  4036.2  751.84  4043.3  748.34  4057.1  747.59
  4078.9  751.48  4099.8  747.10  4121.6  750.60  4142.5  745.11  4149.6  747.06
  4185.2  743.48  4282.4  742.87  4291.5  743.55  4305.8  737.86  4334.2  731.77
  4418.7  735.97  4536.3  736.11  4829.7  733.34  4872.4  736.53  4960.1  723.99
  4962.5  723.49  4984.0  723.99  5007.7  726.46  5028.9  733.46  5107.9  732.11
  5181.1  737.36  5412.8  735.94  5558.4  740.80  5878.0  760.05  5943.4  767.40
#Mann=5,-1,0
  3937.0    0.05       0  4282.4    0.12       0  4536.3    0.05       0
  4960.1    0.05       0  4984.0    0.05       0
Bank Sta=4960.1,4984
Exp/Cntr=0.3,0.1

Type RM Length L Ch R = 1,70720,548,548,548
BEGIN DESCRIPTION:
Elizabeth Creek 77.0
END DESCRIPTION:
XS GIS Cut Line= 3
      2310678.99      7060660.01      2311379.00      7059910.00
      2311479.01      7059109.96
#Sta/Elev= 30
  3968.7  747.54  4258.7  742.13  4280.2  736.97  4287.0  737.65  4294.3  732.85
  4322.7  730.17  4365.2  733.78  4393.0  730.79  4478.0  732.45  4556.2  729.72
  4739.9  735.85  4782.4  733.33  4860.0  734.49  4888.4  732.75  4895.7  729.71
  4945.0  729.11  4952.4  725.72  4959.2  728.55  4966.5  723.27  4979.2  722.07
  4981.6  721.57  5003.2  722.07  5024.9  723.42  5032.4  726.62  5037.5  723.46
  5045.0  726.81  5176.0  732.18  5458.2  733.27  5619.5  747.85  5800.9  758.91
#Mann=3,-1,0
  3968.7    0.05       0  4979.2   0.033       0  5003.2    0.05       0
Bank Sta=4979.2,5003.2
Exp/Cntr=0.3,0.1

Type RM Length L Ch R = 1,70172,566,566,566
BEGIN DESCRIPTION:
Elizabeth Creek 76.0
END DESCRIPTION:
XS GIS Cut Line= 3
      2311579.00      7061560.02      2311779.00      7059560.00
      2311679.00      7059060.00
#Sta/Elev= 30
  2994.5  757.54  3024.7  756.93  3054.8  753.60  3074.9  755.74  3142.8  754.38
  3617.6  737.42  3637.7  738.35  3677.9  736.18  3868.9  733.18  4059.8  731.23
  4449.2  733.11  4783.4  729.76  4823.6  733.51  4833.6  733.06  4851.2  727.36
  4856.3  728.96  4883.9  720.62  4956.8  721.41  4962.3  719.29  4964.7  718.79
  4986.3  719.29  4994.4  725.44  5002.0  727.59  5188.1  728.14  5231.5  732.95
  5266.8  743.54  5279.8  748.06  5310.4  750.89  5392.0  754.35  5514.4  763.08
#Mann=5,-1,0
  2994.5    0.05       0  4962.3   0.033       0  4986.3    0.05       0
  5231.5    0.12       0  5266.8    0.05       0
Bank Sta=4962.3,4986.3
Exp/Cntr=0.3,0.1

Type RM Length L Ch R = 1,69606,589,589,589
BEGIN DESCRIPTION:
Elizabeth Creek 75.0
END DESCRIPTION:
XS GIS Cut Line= 3
      2311528.99      7061810.04      2312329.00      7059610.00
      2311879.01      7058860.02
#Sta/Elev= 30
  2663.3  759.47  2759.1  758.11  2780.4  753.71  2821.0  757.41  2887.5  754.66
  2943.3  757.16  2993.2  753.30  3014.5  755.35  3116.2  753.03  3553.8  737.25
  4022.0  728.52  4397.8  731.05  4693.7  729.10  4802.1  726.02  4841.3  726.47
  4866.0  730.20  4960.4  716.44  4962.8  715.94  4984.4  716.44  4989.0  723.36
  5012.1  728.93  5193.6  727.51  5256.7  726.44  5309.4  725.92  5354.1  724.13
  5398.8  728.90  5426.1  727.80  5484.4  744.23  5509.4  746.23  5878.9  761.27
#Mann=7,-1,0
  2663.3    0.05       0  4960.4   0.033       0  4984.4    0.05       0
  5193.6    0.12       0  5256.7    0.05       0  5309.4    0.12       0
  5509.4    0.05       0
Bank Sta=4960.4,4984.4
Exp/Cntr=0.3,0.1

Type RM Length L Ch R = 1,69017,530,530,530
BEGIN DESCRIPTION:
Elizabeth Creek 74.0
END DESCRIPTION:
XS GIS Cut Line= 3
      2311779.02      7061359.98      2312779.00      7059960.00
      2312978.98      7059610.04
#Sta/Elev= 30
  3274.9  751.05  3383.0  745.69  3798.4  734.89  4379.7  726.35  4614.4  727.72
  4709.0  726.89  4820.3  724.14  4836.8  724.95  4860.2  724.13  4872.4  726.05
  4895.8  726.83  4937.6  720.93  4967.1  718.86  4973.2  717.85  4980.1  713.45
  4982.6  712.95  5004.4  713.45  5009.0  714.10  5024.8  721.13  5030.6  722.79
  5040.7  723.39  5089.6  722.69  5121.3  720.85  5133.5  718.48  5142.9  721.26
  5170.3  725.60  5201.9  728.24  5219.3  730.74  5309.9  740.52  5398.4  745.92
#Mann=5,-1,0
  3274.9    0.05       0  4820.3    0.12       0  4980.1    0.07       0
  5004.4    0.12       0  5219.3    0.05       0
Bank Sta=4980.1,5004.4
Exp/Cntr=0.3,0.1