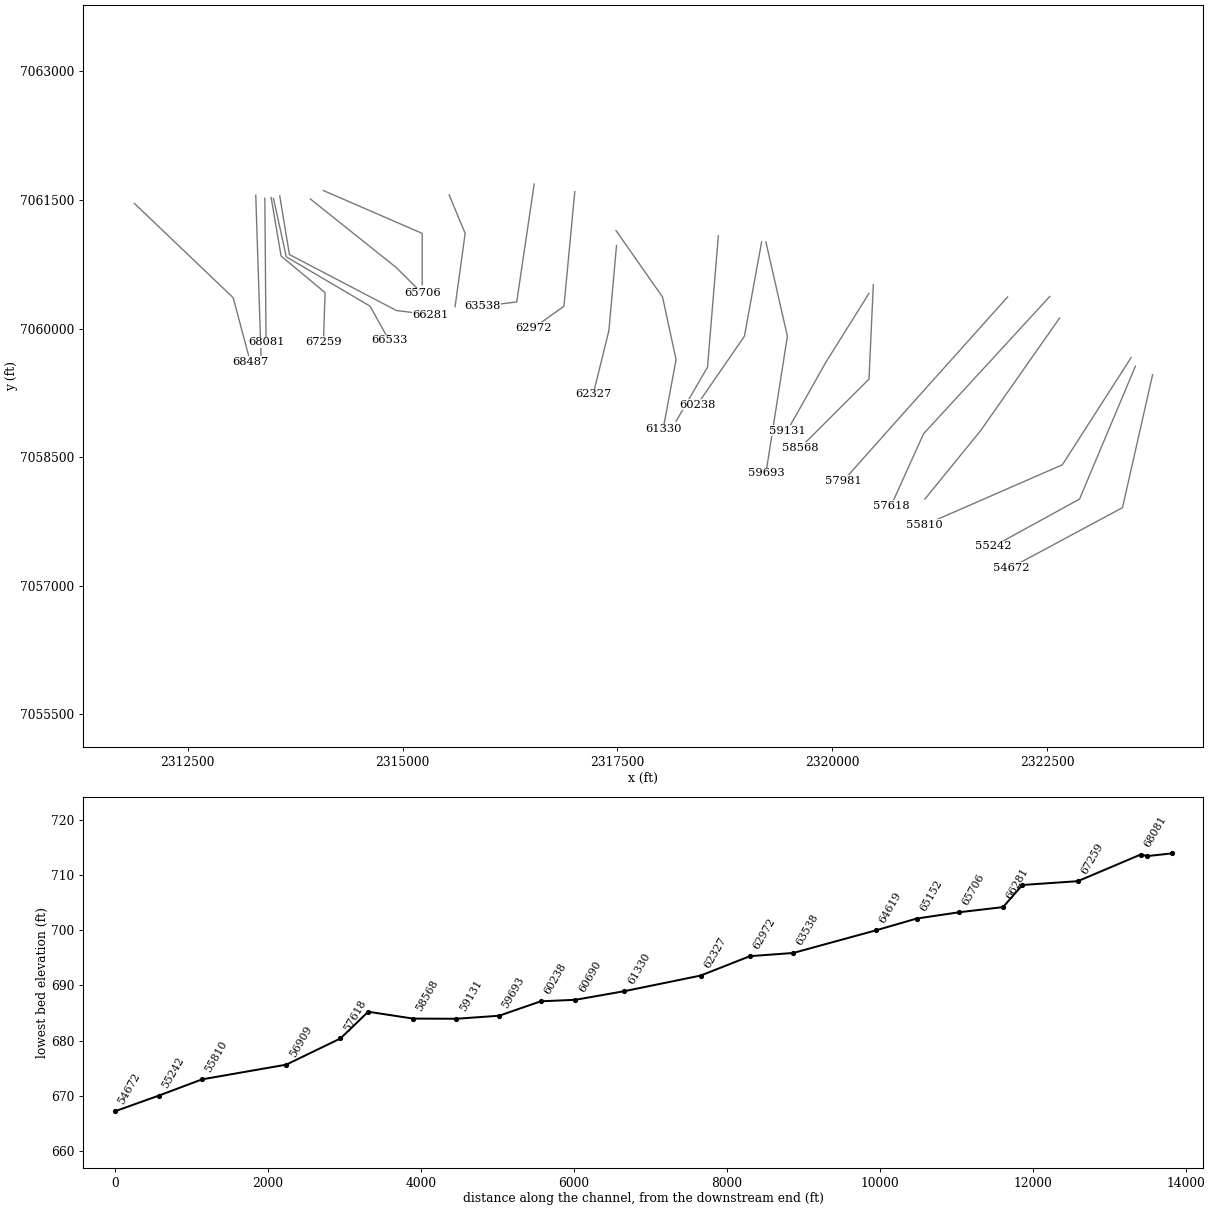
HEC-RAS study Elizabeth Creek.prj: Elizabeth Creek Base Level Engineering

--- Elizabeth Creek.g01 (geometry) --- (continued)

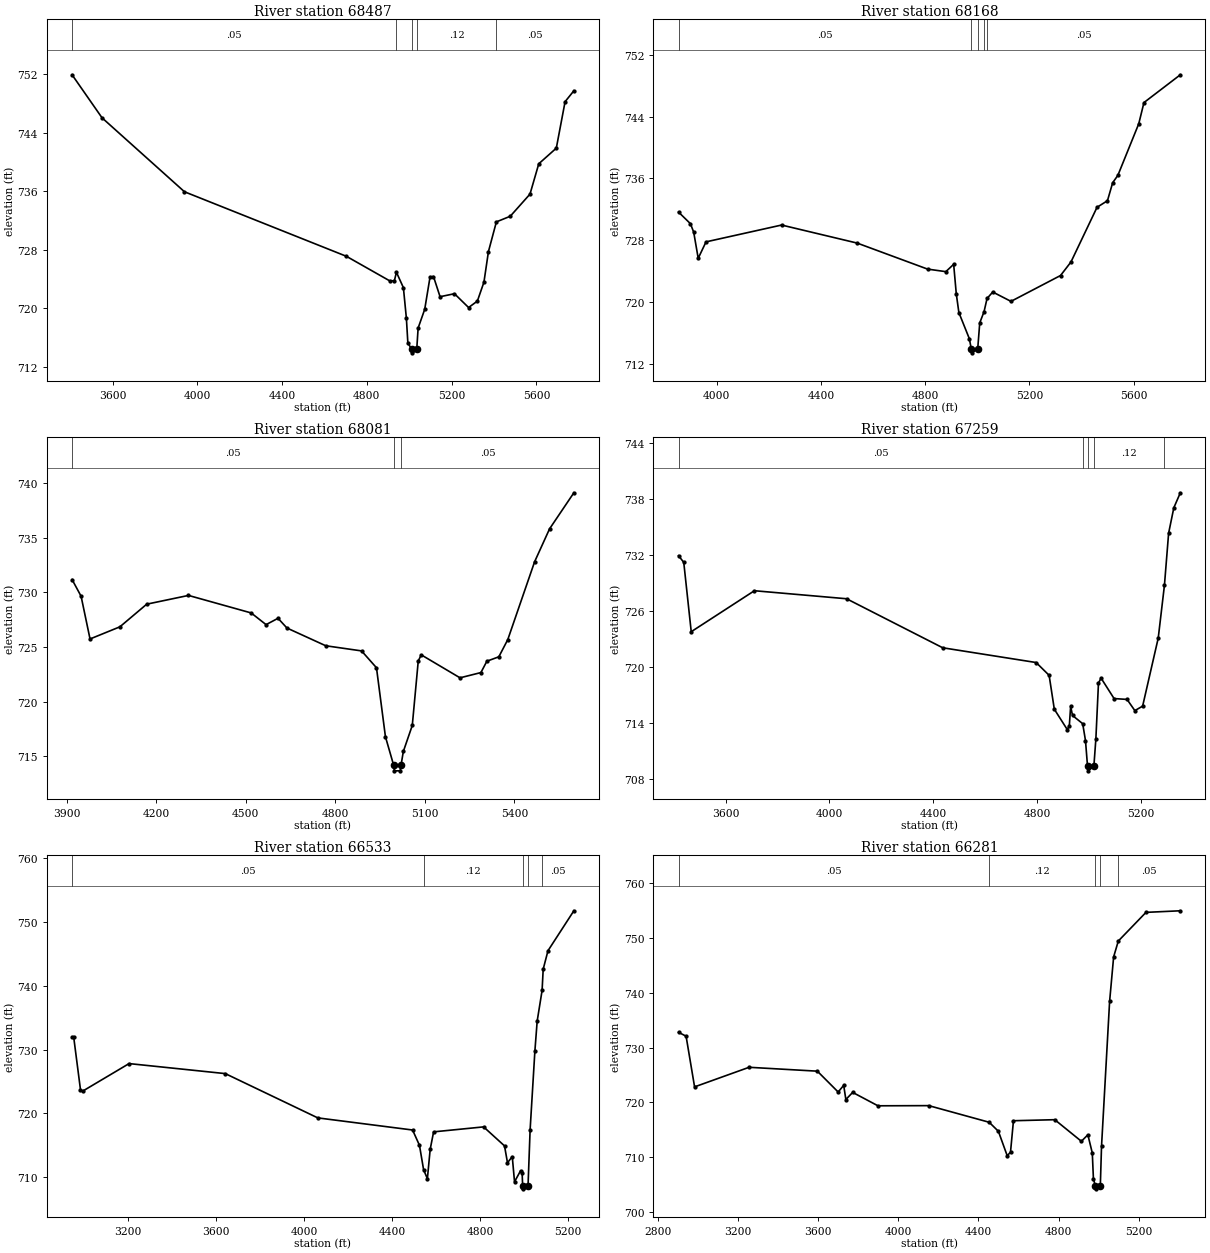
Type RM Length L Ch R = 1,68487,319,319,319
BEGIN DESCRIPTION:
Elizabeth Creek 73.0
END DESCRIPTION:
XS GIS Cut Line= 3
      2311878.97      7061460.03      2313029.00      7060360.00
      2313228.99      7059610.03
#Sta/Elev= 30
  3409.1  751.93  3550.5  746.04  3939.5  735.92  4703.5  727.09  4908.5  723.72
  4929.9  723.75  4939.5  724.91  4972.4  722.80  4986.5  718.61  4993.4  715.26
  5010.9  714.38  5013.4  713.88  5035.4  714.38  5041.9  717.27  5073.0  719.84
  5098.2  724.27  5114.4  724.32  5145.4  721.56  5213.3  721.97  5280.0  720.08
  5321.4  720.96  5352.4  723.55  5373.7  727.74  5411.1  731.80  5476.6  732.57
  5569.7  735.60  5611.1  739.75  5693.9  741.89  5735.3  748.25  5776.7  749.74
#Mann=5,-1,0
  3409.1    0.05       0  4939.5    0.12       0  5010.9    0.07       0
  5035.4    0.12       0  5411.1    0.05       0
Bank Sta=5010.9,5035.4
Exp/Cntr=0.3,0.1

Type RM Length L Ch R = 1,68168,87,87,87
BEGIN DESCRIPTION:
Elizabeth Creek 72.2
END DESCRIPTION:
XS GIS Cut Line= 2
      2313292.17      7061555.44      2313355.07      7059630.47
#Sta/Elev= 30
  3853.6  731.64  3899.1  730.14  3911.8  729.04  3929.1  725.65  3959.1  727.78
  4249.2  729.96  4539.4  727.62  4809.5  724.25  4879.6  723.92  4909.6  724.87
  4919.6  721.07  4929.6  718.62  4969.6  715.25  4977.4  713.90  4979.8  713.40
  5001.9  713.90  5009.7  717.28  5026.2  718.73  5037.8  720.45  5059.7  721.28
  5129.6  720.07  5319.8  723.42  5359.8  725.17  5459.9  732.26  5499.9  733.11
  5519.9  735.44  5539.9  736.40  5620.0  743.08  5640.0  745.83  5779.6  749.43
#Mann=5,-1,0
  3853.6    0.05       0  4977.4   0.033       0  5001.9    0.05       0
  5026.2    0.12       0  5037.8    0.05       0
Bank Sta=4977.4,5001.9
Exp/Cntr=0.3,0.1

Type RM Length L Ch R = 1,68081,822,822,822
BEGIN DESCRIPTION:
Elizabeth Creek 72.3
END DESCRIPTION:
XS GIS Cut Line= 2
      2313397.96      7061520.16      2313411.80      7059838.51
#Sta/Elev= 30
  3917.8  731.16  3948.0  729.64  3978.0  725.73  4078.0  726.84  4168.0  728.91
  4308.0  729.71  4518.0  728.11  4568.0  727.04  4608.0  727.62  4638.0  726.73
  4768.0  725.11  4888.0  724.64  4938.0  723.10  4968.0  716.80  4995.7  714.18
  4998.2  713.68  5017.8  713.68  5020.2  714.18  5028.0  715.45  5058.0  717.83
  5078.0  723.72  5088.0  724.28  5218.0  722.18  5288.0  722.66  5308.0  723.70
  5348.0  724.10  5378.0  725.67  5468.0  732.79  5518.0  735.79  5599.5  739.09
#Mann=3,-1,0
  3917.8    0.05       0  4995.7   0.033       0  5020.2    0.05       0
Bank Sta=4995.7,5020.2
Exp/Cntr=0.3,0.1

Type RM Length L Ch R = 1,67259,726,726,726
BEGIN DESCRIPTION:
Elizabeth Creek 72.4
END DESCRIPTION:
XS GIS Cut Line= 4
      2313471.21      7061528.23      2313586.77      7060846.17
      2314098.91      7060418.45      2314080.01      7059844.90
#Sta/Elev= 30
  3418.7  731.90  3438.8  731.19  3467.6  723.76  3711.0  728.15  4066.0  727.29
  4436.3  722.04  4796.2  720.46  4846.2  719.09  4866.2  715.46  4916.3  713.27
  4924.1  713.71  4929.1  715.77  4936.3  714.79  4975.5  713.91  4986.3  712.10
  4994.1  709.36  4996.5  708.86  5018.6  709.36  5026.3  712.29  5036.3  718.26
  5046.3  718.79  5096.4  716.60  5146.4  716.51  5176.4  715.31  5206.4  715.79
  5266.5  723.08  5290.4  728.73  5306.5  734.31  5326.5  737.03  5351.6  738.64
#Mann=5,-1,0
  3418.7    0.05       0  4975.5    0.12       0  4994.1    0.07       0
  5018.6    0.12       0  5290.4    0.05       0
Bank Sta=4994.1,5018.6
Exp/Cntr=0.3,0.1

Type RM Length L Ch R = 1,66533,252,252,252
BEGIN DESCRIPTION:
Elizabeth Creek 72.5
END DESCRIPTION:
XS GIS Cut Line= 4
      2313498.32      7061517.45      2313647.51      7060836.59
      2314622.13      7060260.85      2314842.42      7059864.32
#Sta/Elev= 30
  2944.5  731.98  2952.1  731.90  2982.8  723.70  2993.1  723.49  3203.8  727.80
  3641.5  726.23  4062.3  719.29  4493.5  717.39  4524.8  714.99  4543.6  711.16
  4560.8  709.76  4573.5  714.36  4589.1  717.10  4816.5  717.88  4911.7  714.90
  4925.2  712.26  4946.9  713.22  4957.2  709.27  4984.7  711.01  4991.8  710.64
  4994.1  708.67  4996.6  708.17  5018.7  708.67  5028.1  717.42  5049.9  729.81
  5060.2  734.45  5082.6  739.27  5087.6  742.60  5109.4  745.49  5227.1  751.75
#Mann=5,-1,0
  2944.5    0.05       0  4543.6    0.12       0  4994.1    0.07       0
  5018.7    0.12       0  5082.6    0.05       0
Bank Sta=4994.1,5018.7
Exp/Cntr=0.3,0.1

Type RM Length L Ch R = 1,66281,575,575,575
BEGIN DESCRIPTION:
Elizabeth Creek 72.0
END DESCRIPTION:
XS GIS Cut Line= 4
      2313571.57      7061547.25      2313683.89      7060863.12
      2314929.00      7060210.00      2315328.99      7060160.00
#Sta/Elev= 30
  2904.9  732.79  2942.6  732.07  2984.9  722.81  3256.8  726.39  3597.2  725.68
  3700.9  721.87  3728.6  723.09  3739.3  720.50  3773.3  721.80  3899.4  719.35
  4152.7  719.38  4454.1  716.34  4500.0  714.69  4544.1  710.21  4560.5  710.90
  4575.1  716.62  4781.1  716.81  4913.9  712.86  4946.2  714.05  4968.3  710.73
  4973.9  706.01  4983.7  704.67  4986.1  704.17  5008.3  704.67  5014.3  711.91
  5054.6  738.42  5074.7  746.57  5098.0  749.47  5236.0  754.71  5407.3  755.00
#Mann=5,-1,0
  2904.9    0.05       0  4454.1    0.12       0  4983.7    0.07       0
  5008.3    0.12       0  5098.0    0.05       0
Bank Sta=4983.7,5008.3
Exp/Cntr=0.3,0.1

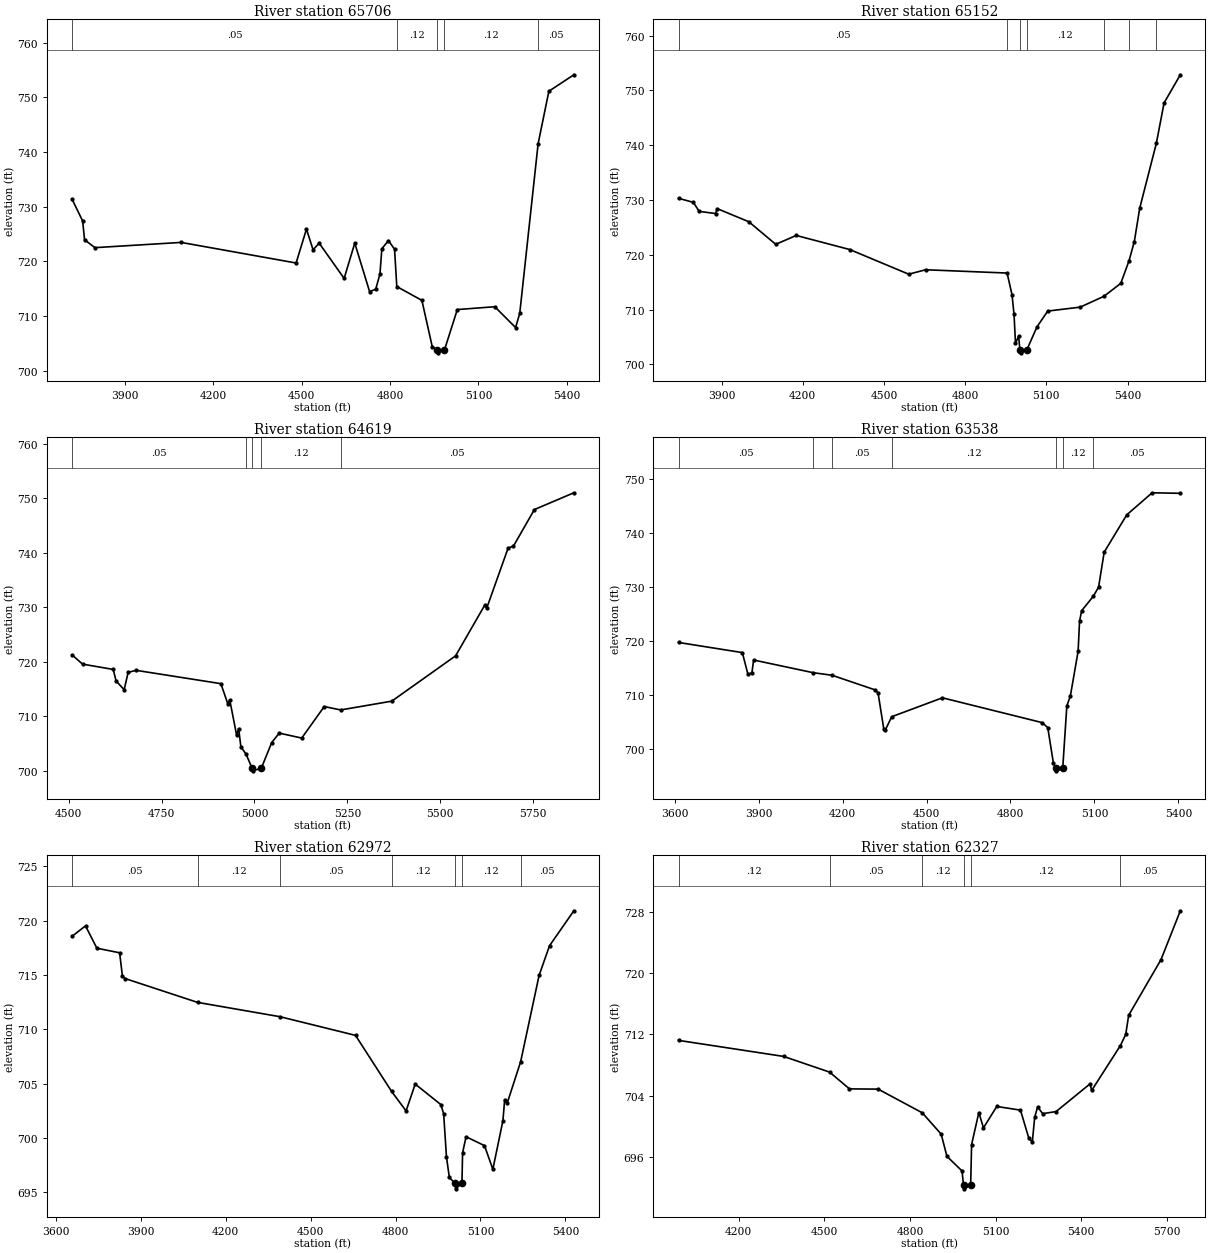
Type RM Length L Ch R = 1,65706,554,554,554
BEGIN DESCRIPTION:
Elizabeth Creek 71.0
END DESCRIPTION:
XS GIS Cut Line= 3
      2313929.00      7061510.00      2314929.00      7060710.00
      2315229.01      7060409.99
#Sta/Elev= 30
  3719.5  731.35  3755.5  727.37  3761.9  723.94  3797.1  722.49  4090.1  723.45
  4480.7  719.68  4515.9  725.89  4538.3  722.10  4559.1  723.31  4643.9  716.86
  4680.0  723.32  4730.4  714.44  4751.2  714.89  4765.6  717.69  4772.0  722.28
  4794.4  723.79  4815.2  722.20  4822.8  715.37  4908.1  712.84  4943.3  704.35
  4959.6  703.74  4962.1  703.24  4984.6  703.74  5028.4  711.16  5155.7  711.68
  5226.4  707.87  5240.5  710.46  5303.0  741.52  5339.5  751.12  5424.4  754.13
#Mann=5,-1,0
  3719.5    0.05       0  4822.8    0.12       0  4959.6    0.07       0
  4984.6    0.12       0  5303.0    0.05       0
Bank Sta=4959.6,4984.6
Exp/Cntr=0.3,0.1

Type RM Length L Ch R = 1,65152,533,533,533
BEGIN DESCRIPTION:
Elizabeth Creek 70.0
END DESCRIPTION:
XS GIS Cut Line= 3
      2314078.97      7061610.01      2315229.00      7061110.00
      2315229.00      7060510.03
#Sta/Elev= 30
  3741.0  730.30  3795.6  729.56  3817.4  727.91  3878.2  727.52  3883.6  728.42
  4000.8  726.02  4100.1  721.90  4175.8  723.52  4373.5  720.95  4591.6  716.45
  4654.0  717.26  4955.0  716.66  4973.2  712.68  4980.6  709.10  4986.0  703.81
  4997.5  705.15  5002.5  702.60  5005.0  702.10  5027.5  702.60  5065.0  706.80
  5105.0  709.72  5225.0  710.44  5312.9  712.42  5375.0  714.78  5405.4  718.89
  5425.0  722.40  5445.0  728.50  5506.4  740.34  5535.0  747.71  5595.0  752.84
#Mann=7,-1,0
  3741.0    0.05       0  4955.0    0.12       0  5002.5    0.07       0
  5027.5    0.12       0  5312.9    0.05       0  5405.4    0.12       0
  5506.4    0.05       0
Bank Sta=5002.5,5027.5
Exp/Cntr=0.3,0.1

Type RM Length L Ch R = 1,64619,1081,1081,1081
BEGIN DESCRIPTION:
Elizabeth Creek 69.0
END DESCRIPTION:
XS GIS Cut Line= 3
      2315542.49      7061559.40      2315729.00      7061110.00
      2315611.85      7060254.75
#Sta/Elev= 30
  4509.4  721.24  4537.6  719.54  4620.1  718.57  4627.8  716.45  4649.5  714.85
  4660.3  718.04  4682.0  718.40  4909.7  715.96  4928.2  712.29  4933.6  712.96
  4952.0  706.52  4957.5  707.71  4963.5  704.38  4977.3  703.04  4993.6  700.47
  4996.1  699.97  5018.6  700.47  5046.4  705.15  5066.6  706.89  5127.2  705.98
  5187.7  711.76  5232.1  711.14  5369.4  712.75  5541.0  721.06  5619.5  730.36
  5624.6  729.77  5682.3  740.82  5696.7  741.19  5753.0  747.89  5859.2  750.97
#Mann=5,-1,0
  4509.4    0.05       0  4977.3    0.12       0  4993.6    0.07       0
  5018.6    0.12       0  5232.1    0.05       0
Bank Sta=4993.6,5018.6
Exp/Cntr=0.3,0.1

Type RM Length L Ch R = 1,63538,566,566,566
BEGIN DESCRIPTION:
Elizabeth Creek 68.0
END DESCRIPTION:
XS GIS Cut Line= 3
      2316532.18      7061685.51      2316329.00      7060310.00
      2315929.04      7060260.01
#Sta/Elev= 30
  3613.6  719.70  3841.6  717.82  3861.8  713.76  3875.9  714.09  3882.0  716.44
  4094.9  714.09  4162.5  713.61  4316.7  710.89  4326.8  710.32  4347.0  703.71
  4353.0  703.48  4375.5  705.92  4556.7  709.43  4913.1  704.83  4933.3  703.90
  4953.5  697.29  4961.8  696.38  4964.3  695.88  4986.8  696.38  5001.5  707.95
  5014.1  709.77  5041.8  718.07  5046.9  723.64  5054.4  725.59  5095.8  728.25
  5114.9  729.96  5135.0  736.46  5215.7  743.38  5306.4  747.47  5407.1  747.37
#Mann=7,-1,0
  3613.6    0.05       0  4094.9    0.12       0  4162.5    0.05       0
  4375.5    0.12       0  4961.8    0.07       0  4986.8    0.12       0
  5095.8    0.05       0
Bank Sta=4961.8,4986.8
Exp/Cntr=0.3,0.1

Type RM Length L Ch R = 1,62972,645,645,645
BEGIN DESCRIPTION:
Elizabeth Creek 67.0
END DESCRIPTION:
XS GIS Cut Line= 3
      2317004.96      7061597.29      2316879.00      7060260.00
      2316529.02      7060010.02
#Sta/Elev= 30
  3656.9  718.57  3704.4  719.53  3744.6  717.47  3824.9  717.05  3835.0  714.88
  3845.0  714.67  4100.3  712.48  4391.8  711.16  4658.6  709.44  4786.2  704.27
  4837.3  702.48  4869.5  704.95  4959.9  703.07  4970.0  702.23  4980.0  698.24
  4990.1  696.36  5009.7  695.80  5012.2  695.30  5034.7  695.80  5037.0  698.63
  5049.3  700.10  5114.4  699.28  5143.9  697.10  5179.5  701.58  5185.7  703.52
  5194.3  703.17  5242.1  707.01  5307.3  714.96  5344.2  717.70  5430.2  720.92
#Mann=7,-1,0
  3656.9    0.05       0  4100.3    0.12       0  4391.8    0.05       0
  4786.2    0.12       0  5009.7    0.07       0  5034.7    0.12       0
  5242.1    0.05       0
Bank Sta=5009.7,5034.7
Exp/Cntr=0.3,0.1

Type RM Length L Ch R = 1,62327,997,997,997
BEGIN DESCRIPTION:
Elizabeth Creek 66.0
END DESCRIPTION:
XS GIS Cut Line= 3
      2317490.35      7060966.88      2317402.10      7059977.18
      2317219.51      7059234.21
#Sta/Elev= 30
  3988.9  711.22  4357.2  709.12  4518.1  707.07  4588.1  704.87  4688.5  704.84
  4843.2  701.74  4909.4  698.95  4929.5  696.05  4982.5  694.13  4987.7  692.29
  4990.2  691.79  5012.7  692.29  5016.1  697.59  5041.4  701.78  5057.6  699.77
  5104.3  702.57  5187.4  702.09  5216.5  698.43  5228.9  697.91  5237.1  701.15
  5247.4  702.51  5265.3  701.63  5312.0  701.90  5431.5  705.54  5436.7  704.66
  5537.5  710.53  5556.2  712.00  5566.6  714.51  5679.9  721.79  5747.6  728.18
#Mann=6,-1,0
  3988.9    0.12       0  4518.1    0.05       0  4843.2    0.12       0
  4987.7    0.07       0  5012.7    0.12       0  5537.5    0.05       0
Bank Sta=4987.7,5012.7
Exp/Cntr=0.3,0.1

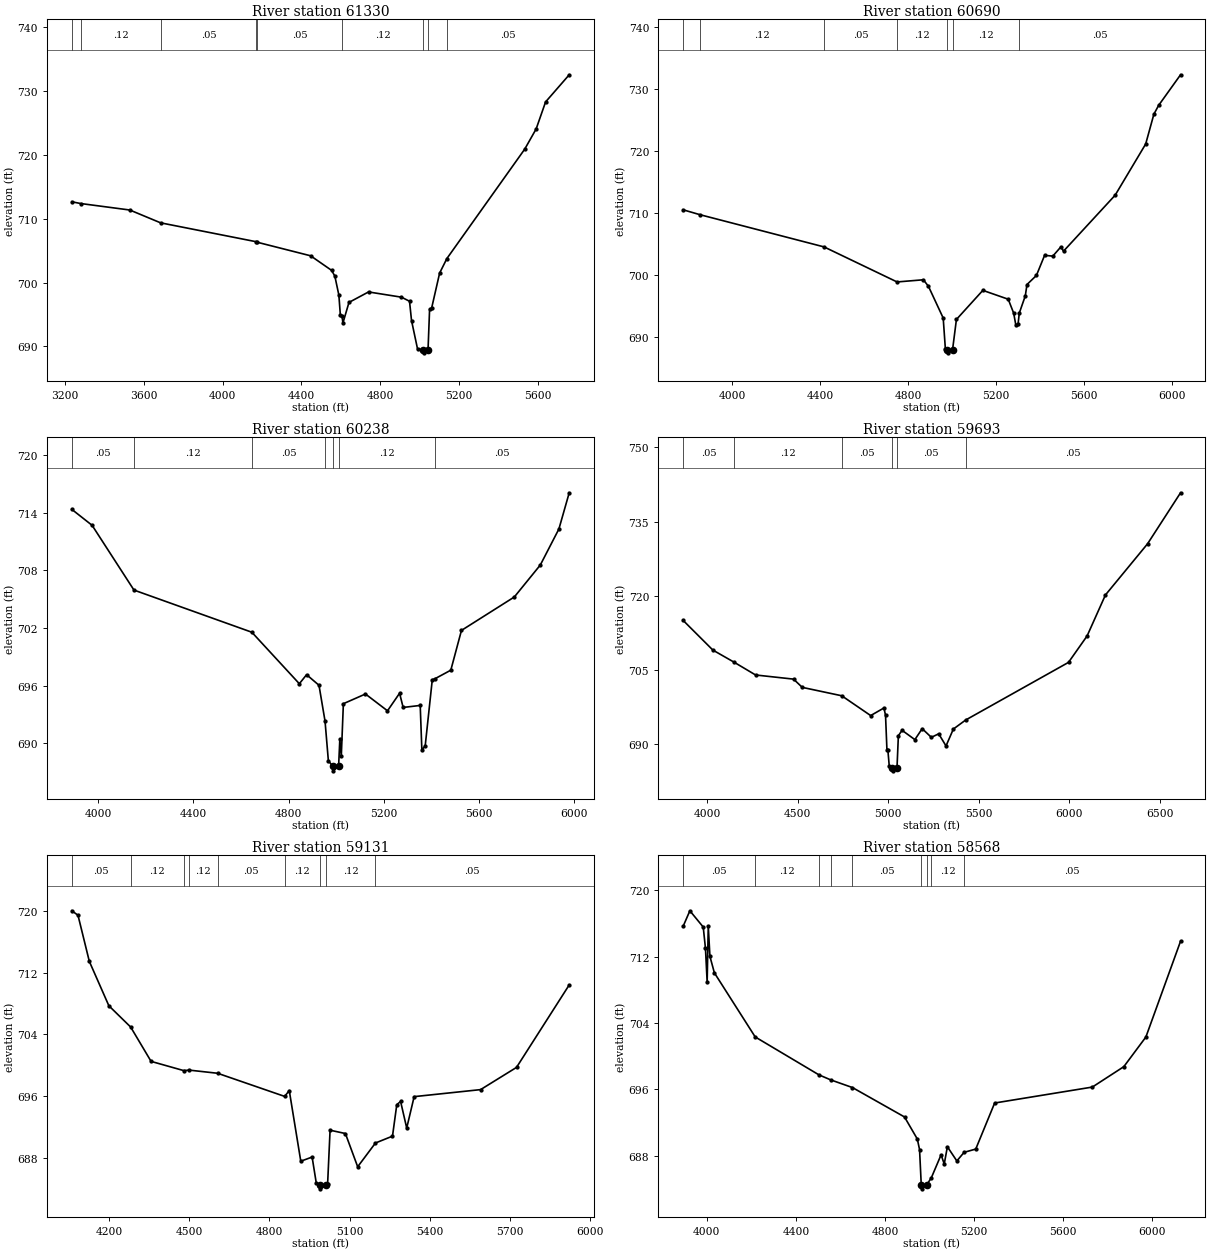
Type RM Length L Ch R = 1,61330,640,640,640
BEGIN DESCRIPTION:
Elizabeth Creek 65.5
END DESCRIPTION:
XS GIS Cut Line= 4
      2317484.05      7061143.38      2318026.18      7060368.01
      2318183.77      7059636.77      2318032.62      7058824.33
#Sta/Elev= 30
  3236.5  712.66  3280.7  712.39  3530.2  711.37  3686.2  709.36  4171.9  706.39
  4174.1  706.33  4446.5  704.19  4553.0  701.90  4569.3  701.00  4589.7  698.02
  4597.2  694.88  4605.5  694.80  4610.2  693.64  4640.9  696.88  4740.0  698.52
  4906.9  697.70  4947.7  697.06  4957.9  694.03  4988.7  689.53  5016.6  689.47
  5019.1  688.97  5041.6  689.47  5049.4  695.78  5059.6  695.96  5100.3  701.48
  5137.1  703.76  5531.6  720.92  5589.5  724.09  5637.2  728.32  5757.0  732.58
#Mann=9,-1,0
  3236.5    0.05       0  3280.7    0.12       0  3686.2    0.05       0
  4171.9    0.12       0  4174.1    0.05       0  4605.5    0.12       0
  5016.6    0.07       0  5041.6    0.12       0  5137.1    0.05       0
Bank Sta=5016.6,5041.6
Exp/Cntr=0.3,0.1

Type RM Length L Ch R = 1,60690,452,452,452
BEGIN DESCRIPTION:
Elizabeth Creek 65.2
END DESCRIPTION:
XS GIS Cut Line= 3
      2318675.47      7061080.37      2318549.39      7059548.52
      2318183.90      7058918.37
#Sta/Elev= 30
  3775.4  710.51  3852.1  709.72  4417.0  704.52  4749.6  698.86  4869.5  699.21
  4892.5  698.16  4959.8  693.03  4969.8  687.98  4977.4  687.91  4979.9  687.41
  5002.4  687.91  5020.0  692.80  5140.4  697.50  5256.0  696.07  5280.8  693.82
  5290.9  691.85  5300.9  692.09  5306.4  693.83  5333.8  696.62  5341.4  698.44
  5384.4  699.91  5421.7  703.16  5459.0  703.03  5495.7  704.52  5507.8  703.83
  5743.0  712.87  5882.1  721.14  5919.4  725.95  5940.9  727.37  6040.9  732.32
#Mann=7,-1,0
  3775.4    0.05       0  3852.1    0.12       0  4417.0    0.05       0
  4749.6    0.12       0  4977.4    0.07       0  5002.4    0.12       0
  5306.4    0.05       0
Bank Sta=4977.4,5002.4
Exp/Cntr=0.3,0.1

Type RM Length L Ch R = 1,60238,545,545,545
BEGIN DESCRIPTION:
Elizabeth Creek 65.0
END DESCRIPTION:
XS GIS Cut Line= 3
      2319179.00      7061010.01      2318979.00      7059910.00
      2318428.98      7059109.98
#Sta/Elev= 30
  3889.9  714.36  3975.0  712.70  4150.8  705.96  4645.9  701.57  4845.3  696.21
  4875.8  697.15  4927.9  696.05  4953.3  692.31  4967.3  688.18  4985.3  687.64
  4987.8  687.14  5010.3  687.64  5015.4  690.42  5021.5  688.64  5030.3  694.13
  5123.0  695.14  5215.6  693.39  5266.4  695.22  5281.3  693.74  5353.0  693.95
  5359.9  689.32  5373.9  689.73  5403.7  696.63  5415.0  696.73  5481.5  697.62
  5526.2  701.76  5748.2  705.24  5857.4  708.57  5935.5  712.32  5978.8  716.09
#Mann=7,-1,0
  3889.9    0.05       0  4150.8    0.12       0  4645.9    0.05       0
  4953.3    0.12       0  4985.3    0.07       0  5010.3    0.12       0
  5415.0    0.05       0
Bank Sta=4985.3,5010.3
Exp/Cntr=0.3,0.1

Type RM Length L Ch R = 1,59693,562,562,562
BEGIN DESCRIPTION:
Elizabeth Creek 64.0
END DESCRIPTION:
XS GIS Cut Line= 3
      2319229.01      7061009.97      2319479.00      7059910.00
      2319229.00      7058310.03
#Sta/Elev= 30
  3867.7  714.98  4031.7  708.98  4146.9  706.57  4267.6  703.94  4477.3  703.10
  4525.5  701.43  4743.5  699.73  4903.4  695.72  4976.7  697.26  4985.5  695.77
  4993.2  688.82  4998.2  688.82  5005.8  685.59  5023.7  685.03  5026.2  684.53
  5048.7  685.03  5056.4  691.63  5076.7  692.74  5147.5  690.85  5188.0  693.07
  5238.6  691.31  5279.1  692.03  5319.6  689.57  5360.1  692.99  5428.1  694.82
  5996.2  706.49  6098.9  711.84  6200.2  720.14  6432.9  730.50  6615.1  740.83
#Mann=6,-1,0
  3867.7    0.05       0  4146.9    0.12       0  4743.5    0.05       0
  5023.7   0.033       0  5048.7    0.05       0  5428.1    0.05       0
Bank Sta=5023.7,5048.7
Exp/Cntr=0.3,0.1

Type RM Length L Ch R = 1,59131,563,563,563
BEGIN DESCRIPTION:
Elizabeth Creek 63.0
END DESCRIPTION:
XS GIS Cut Line= 3
      2320428.98      7060409.97      2319929.00      7059610.00
      2319479.02      7058810.04
#Sta/Elev= 30
  4060.8  720.02  4083.8  719.44  4126.2  713.46  4199.3  707.71  4280.9  704.95
  4357.3  700.50  4480.0  699.30  4499.4  699.37  4606.2  698.96  4857.2  695.96
  4874.4  696.72  4917.5  687.56  4959.9  688.10  4975.3  684.77  4988.7  684.48
  4991.2  683.98  5013.7  684.48  5017.9  684.61  5027.1  691.58  5084.5  691.15
  5130.4  686.84  5196.9  689.92  5260.7  690.81  5276.7  694.88  5291.0  695.31
  5313.9  691.86  5341.7  695.93  5590.3  696.84  5724.8  699.72  5922.0  710.41
#Mann=9,-1,0
  4060.8    0.05       0  4280.9    0.12       0  4480.0   0.075       0
  4499.4    0.12       0  4606.2    0.05       0  4857.2    0.12       0
  4988.7    0.07       0  5013.7    0.12       0  5196.9    0.05       0
Bank Sta=4988.7,5013.7
Exp/Cntr=0.3,0.1

Type RM Length L Ch R = 1,58568,587,587,587
BEGIN DESCRIPTION:
Elizabeth Creek 62.0
END DESCRIPTION:
XS GIS Cut Line= 3
      2320479.00      7060509.96      2320429.00      7059410.00
      2319628.97      7058609.97
#Sta/Elev= 30
  3894.1  715.65  3924.1  717.51  3984.1  715.55  3994.2  712.97  4001.7  708.92
  4006.7  715.67  4014.2  712.01  4034.2  710.03  4217.4  702.31  4503.6  697.74
  4556.1  697.14  4654.1  696.21  4887.6  692.67  4945.1  690.01  4955.1  688.74
  4962.7  684.51  4965.2  684.01  4987.7  684.51  5008.1  685.35  5051.8  688.11
  5065.9  687.00  5080.0  689.08  5122.5  687.37  5155.1  688.41  5207.3  688.80
  5292.2  694.35  5730.6  696.27  5872.0  698.73  5971.0  702.30  6126.6  713.84
#Mann=9,-1,0
  3894.1    0.05       0  4217.4    0.12       0  4503.6    0.05       0
  4556.1    0.12       0  4654.1    0.05       0  4962.7   0.033       0
  4987.7    0.05       0  5008.1    0.12       0  5155.1    0.05       0
Bank Sta=4962.7,4987.7
Exp/Cntr=0.3,0.1

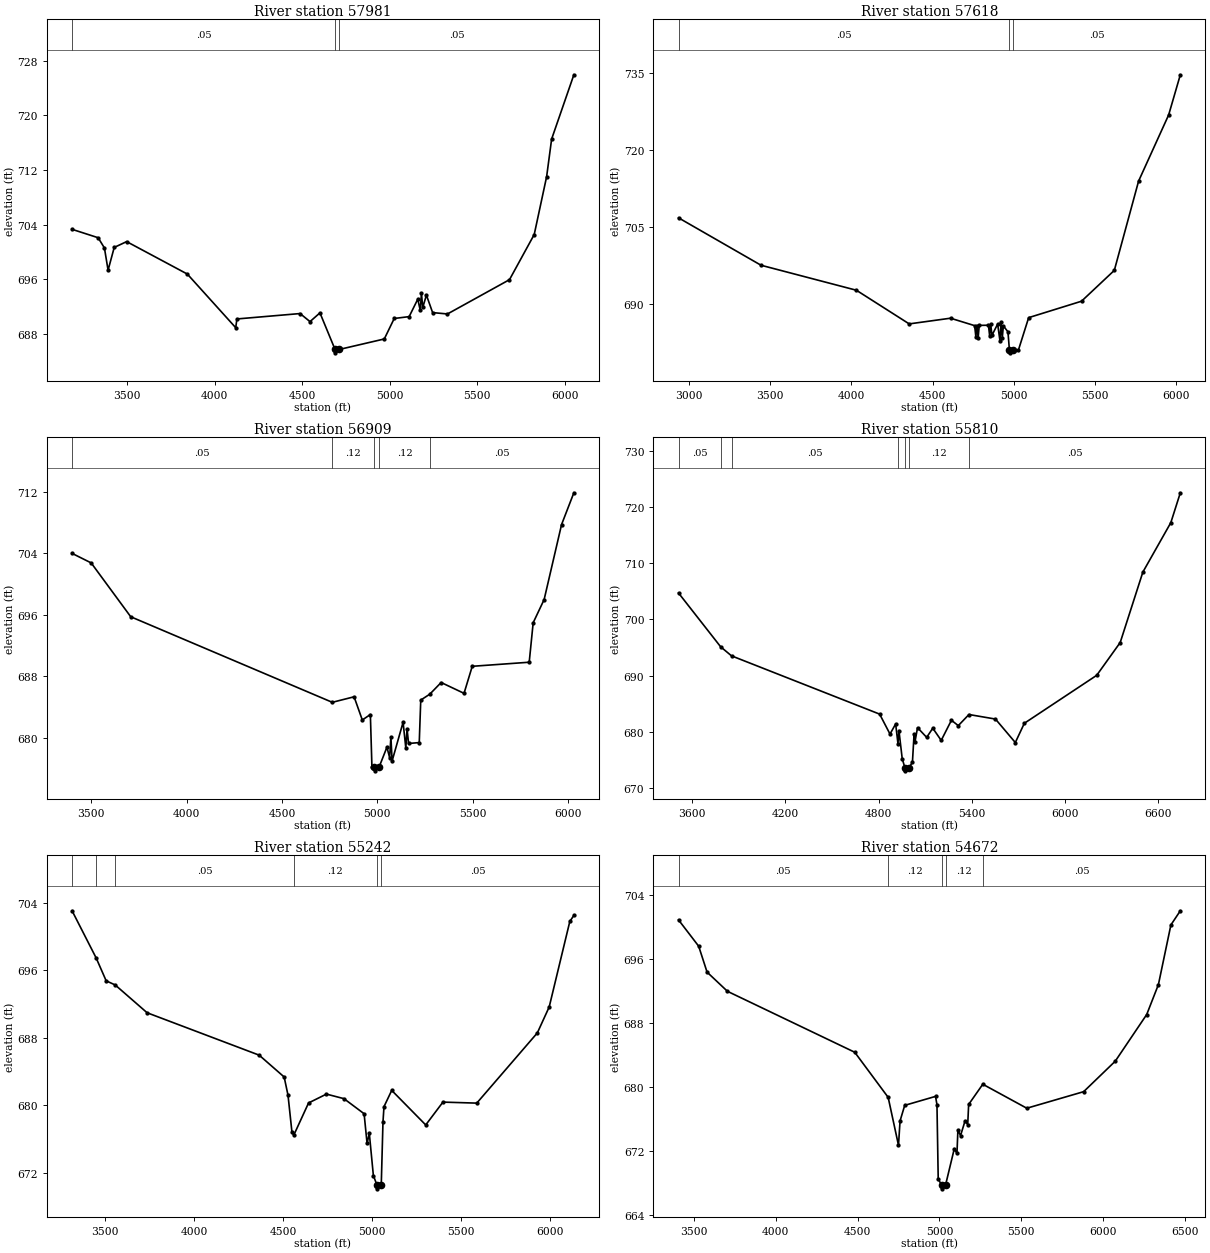
Type RM Length L Ch R = 1,57981,363,363,363
BEGIN DESCRIPTION:
Elizabeth Creek 61.0
END DESCRIPTION:
XS GIS Cut Line= 3
      2322041.66      7060367.98      2320829.00      7059010.00
      2320132.93      7058226.18
#Sta/Elev= 30
  3184.3  703.33  3333.3  702.10  3369.3  700.60  3390.2  697.35  3425.3  700.68
  3496.4  701.53  3843.3  696.78  4120.0  688.93  4126.7  690.21  4487.9  691.00
  4544.7  689.82  4601.5  691.10  4687.7  685.75  4690.2  685.25  4712.7  685.75
  4969.4  687.28  5026.2  690.28  5111.5  690.55  5160.9  693.11  5175.1  691.46
  5181.8  693.94  5189.3  691.89  5210.2  693.70  5245.7  691.14  5330.6  690.94
  5685.2  695.96  5826.6  702.57  5897.6  711.05  5926.1  716.54  6053.2  725.95
#Mann=3,-1,0
  3184.3    0.05       0  4687.7   0.033       0  4712.7    0.05       0
Bank Sta=4687.7,4712.7
Exp/Cntr=0.3,0.1

Type RM Length L Ch R = 1,57618,709,709,709
BEGIN DESCRIPTION:
Elizabeth Creek 60.0
END DESCRIPTION:
XS GIS Cut Line= 3
      2322533.41      7060374.34      2321064.60      7058773.16
      2320686.42      7057934.84
#Sta/Elev= 30
  2934.4  706.73  3442.8  697.49  4030.4  692.62  4356.0  686.06  4610.7  687.17
  4759.3  685.72  4766.7  683.58  4773.5  685.64  4780.9  683.36  4787.6  685.77
  4844.4  685.80  4851.8  683.73  4858.5  685.96  4865.9  683.83  4901.1  686.03
  4915.3  682.76  4922.1  686.36  4929.5  683.30  4936.2  685.67  4964.6  684.52
  4973.7  680.92  4976.2  680.42  4998.7  680.92  5028.7  680.92  5092.2  687.28
  5417.9  690.48  5620.1  696.49  5769.8  713.90  5954.9  726.78  6026.9  734.61
#Mann=3,-1,0
  2934.4    0.05       0  4973.7   0.033       0  4998.7    0.05       0
Bank Sta=4973.7,4998.7
Exp/Cntr=0.3,0.1

Type RM Length L Ch R = 1,56909,1099,1099,1099
BEGIN DESCRIPTION:
Elizabeth Creek 59.0
END DESCRIPTION:
XS GIS Cut Line= 3
      2322646.83      7060122.14      2321729.00      7058810.00
      2321078.98      7058009.97
#Sta/Elev= 30
  3399.2  703.99  3499.4  702.75  3706.9  695.74  4764.2  684.60  4878.5  685.32
  4921.6  682.30  4963.9  683.01  4972.1  676.21  4984.9  676.18  4987.4  675.68
  5009.9  676.18  5050.8  678.76  5064.9  677.40  5071.6  680.09  5078.0  676.97
  5135.5  682.00  5149.9  678.64  5156.3  681.16  5164.3  679.24  5220.3  679.36
  5228.2  684.89  5275.6  685.66  5335.2  687.18  5455.2  685.77  5498.3  689.29
  5797.1  689.82  5817.9  694.96  5875.4  697.98  5966.8  707.74  6031.3  711.88
#Mann=5,-1,0
  3399.2    0.05       0  4764.2    0.12       0  4984.9    0.07       0
  5009.9    0.12       0  5275.6    0.05       0
Bank Sta=4984.9,5009.9
Exp/Cntr=0.3,0.1

Type RM Length L Ch R = 1,55810,568,568,568
BEGIN DESCRIPTION:
Elizabeth Creek 58.0
END DESCRIPTION:
XS GIS Cut Line= 3
      2323478.99      7059659.99      2322679.00      7058410.00
      2321078.99      7057710.00
#Sta/Elev= 30
  3512.4  704.70  3783.6  695.12  3853.4  693.51  4807.1  683.13  4873.8  679.58
  4910.2  681.38  4925.0  677.89  4931.4  680.20  4952.5  675.18  4970.4  673.53
  4972.9  673.03  4995.4  673.53  5018.3  674.58  5028.8  679.58  5034.3  678.14
  5051.0  680.72  5109.9  678.99  5149.3  680.62  5203.5  678.45  5269.3  682.04
  5313.4  681.08  5382.1  683.06  5552.8  682.25  5680.6  678.07  5738.7  681.50
  6204.5  690.04  6355.8  695.88  6501.6  708.42  6681.7  717.23  6742.9  722.55
#Mann=7,-1,0
  3512.4    0.05       0  3783.6    0.12       0  3853.4    0.05       0
  4925.0    0.12       0  4970.4    0.07       0  4995.4    0.12       0
  5382.1    0.05       0
Bank Sta=4970.4,4995.4
Exp/Cntr=0.3,0.1

Type RM Length L Ch R = 1,55242,570,570,570
BEGIN DESCRIPTION:
Elizabeth Creek 57.0
END DESCRIPTION:
XS GIS Cut Line= 3
      2323529.00      7059559.99      2322879.00      7058010.00
      2321879.03      7057460.02
#Sta/Elev= 30
  3313.9  703.07  3449.2  697.48  3505.7  694.76  3556.4  694.27  3736.0  690.97
  4366.2  685.94  4506.7  683.35  4528.4  681.18  4550.1  676.88  4560.8  676.45
  4643.9  680.27  4744.4  681.32  4842.9  680.78  4956.3  678.99  4973.0  675.46
  4985.5  676.67  5008.4  671.65  5027.8  670.58  5030.3  670.08  5052.8  670.58
  5062.4  678.01  5068.1  679.83  5111.6  681.76  5302.8  677.66  5399.6  680.37
  5589.9  680.25  5930.5  688.58  5997.2  691.66  6113.1  701.80  6135.9  702.52
#Mann=6,-1,0
  3313.9    0.05       0  3449.2    0.12       0  3556.4    0.05       0
  4560.8    0.12       0  5027.8    0.07       0  5052.8    0.05       0
Bank Sta=5027.8,5052.8
Exp/Cntr=0.3,0.1

Type RM Length L Ch R = 1,54672,544,544,544
BEGIN DESCRIPTION:
Elizabeth Creek 56.0
END DESCRIPTION:
XS GIS Cut Line= 3
      2323729.01      7059460.05      2323379.00      7057910.00
      2322078.96      7057209.98
#Sta/Elev= 30
  3405.8  700.89  3528.9  697.60  3580.1  694.36  3704.6  691.96  4482.3  684.34
  4686.5  678.70  4749.6  672.71  4759.1  675.75  4787.6  677.70  4975.8  678.82
  4984.6  677.79  4992.3  668.48  5012.4  667.76  5014.9  667.26  5037.4  667.76
  5090.6  672.29  5106.8  671.68  5112.5  674.60  5128.7  673.92  5156.3  675.76
  5172.5  675.29  5178.2  677.81  5264.6  680.34  5533.5  677.34  5880.8  679.41
  6073.8  683.22  6266.1  689.06  6337.5  692.80  6413.8  700.26  6471.4  702.03
#Mann=5,-1,0
  3405.8    0.05       0  4686.5    0.12       0  5012.4    0.07       0
  5037.4    0.12       0  5264.6    0.05       0
Bank Sta=5012.4,5037.4
Exp/Cntr=0.3,0.1