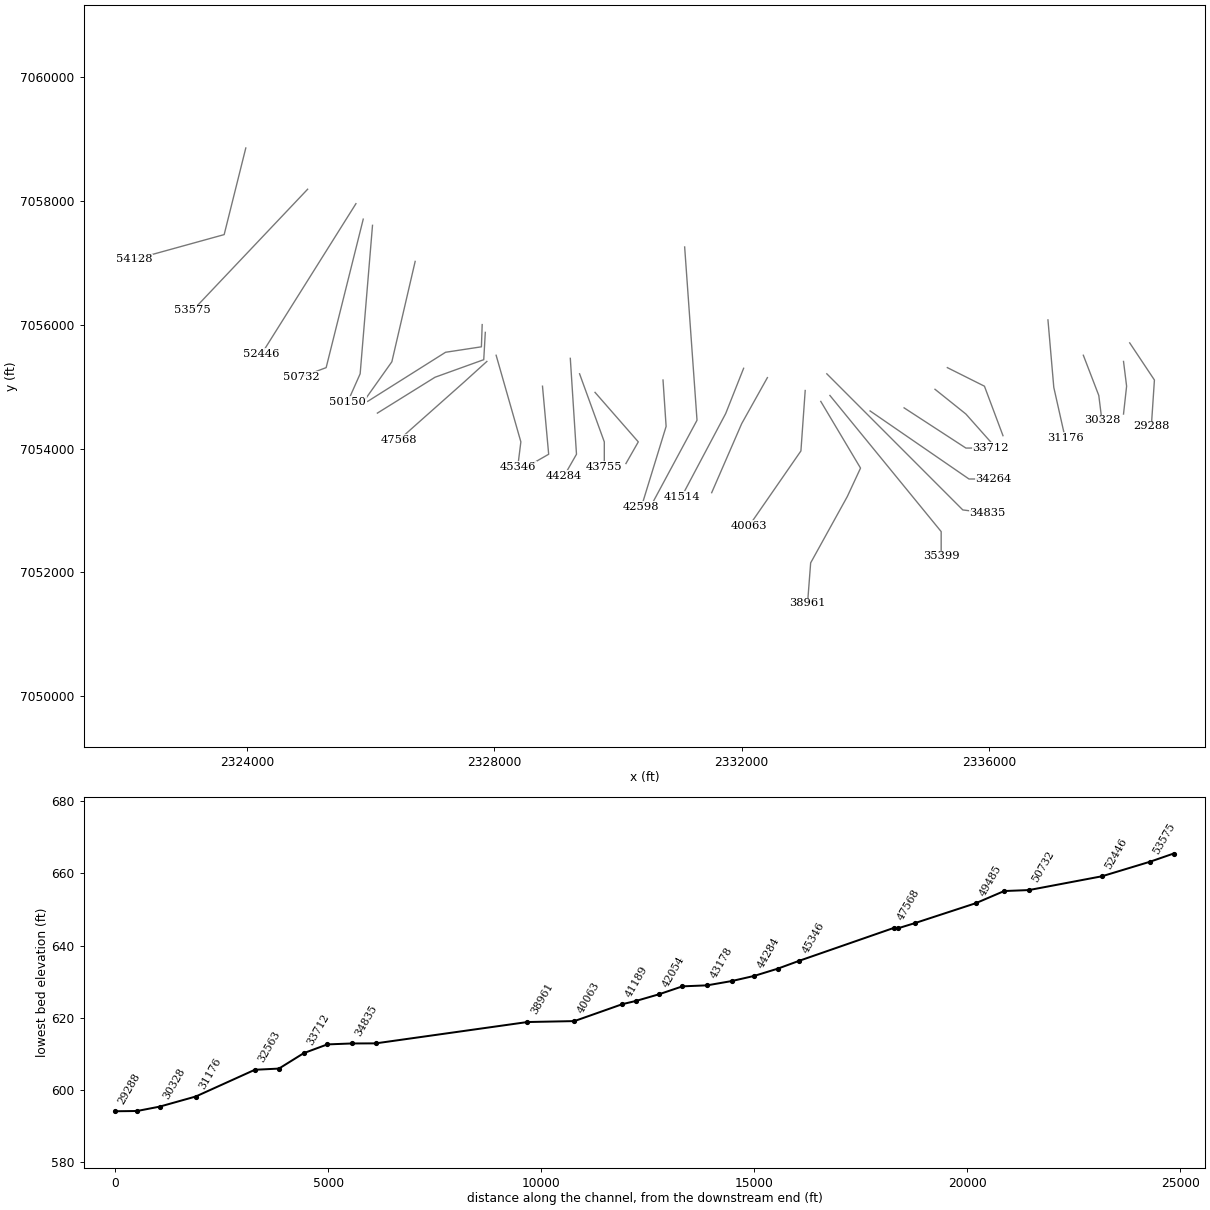
HEC-RAS study Elizabeth Creek.prj: Elizabeth Creek Base Level Engineering

--- Elizabeth Creek.g01 (geometry) --- (continued)

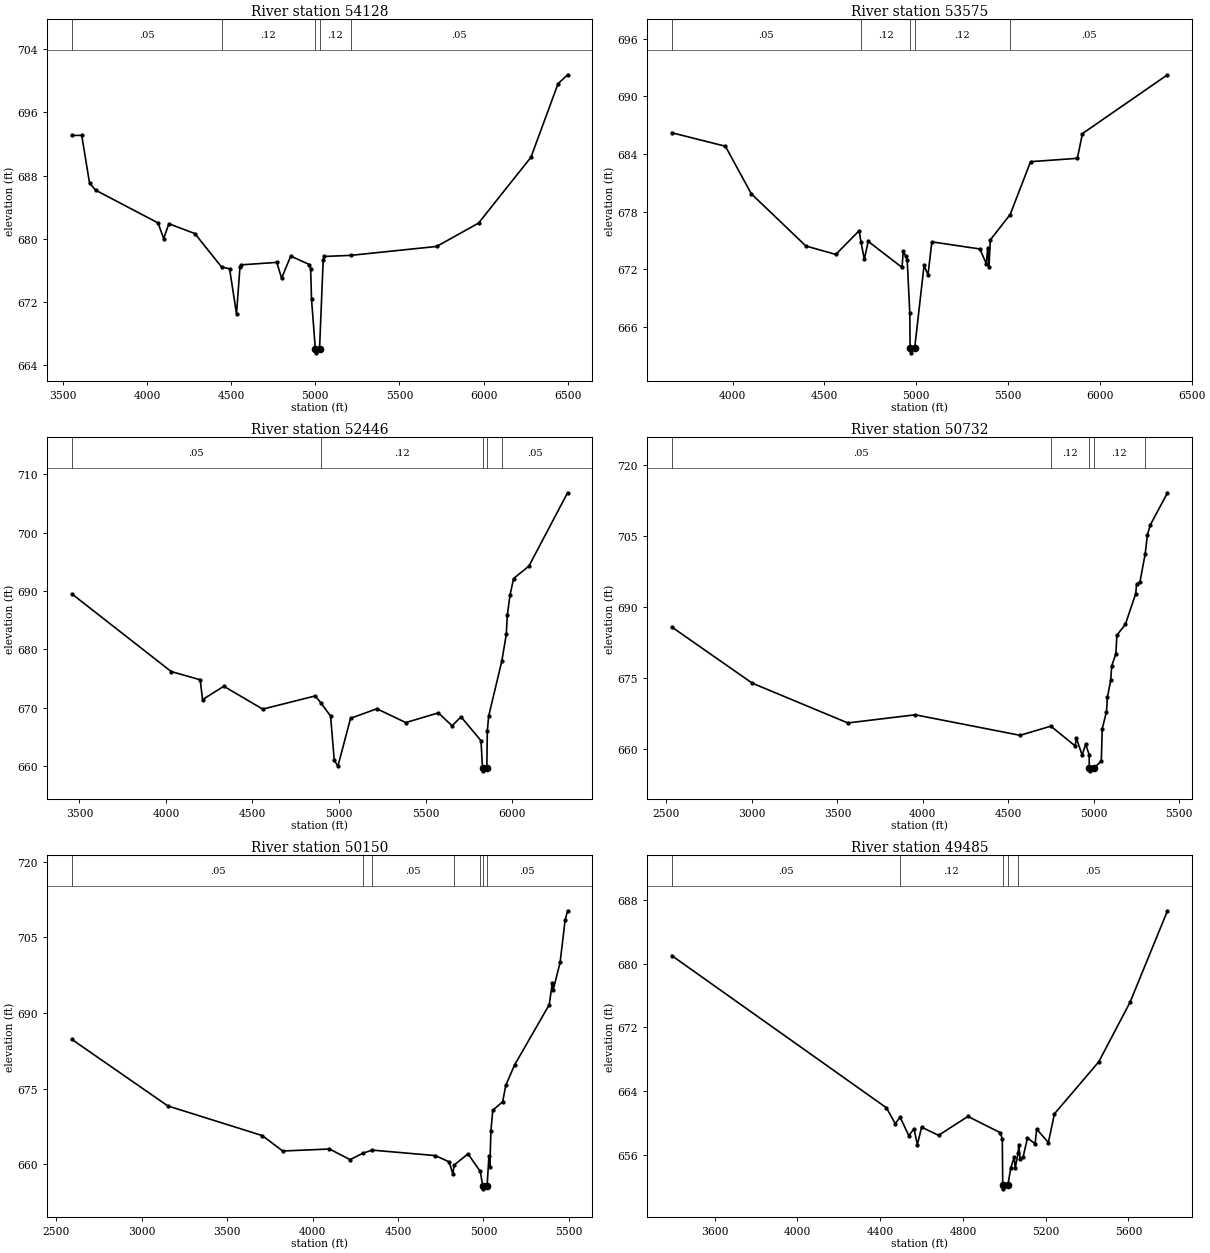
Type RM Length L Ch R = 1,54128,553,553,553
BEGIN DESCRIPTION:
Elizabeth Creek 55.0
END DESCRIPTION:
XS GIS Cut Line= 3
      2323978.99      7058859.95      2323629.00      7057460.00
      2322179.00      7057060.00
#Sta/Elev= 30
  3552.3  693.09  3611.5  693.09  3657.9  687.05  3694.0  686.15  4065.1  682.00
  4098.6  680.02  4129.5  681.90  4284.1  680.65  4442.6  676.42  4490.3  676.19
  4531.5  670.48  4552.1  676.40  4559.8  676.69  4771.1  677.00  4799.5  674.99
  4853.6  677.80  4964.4  676.73  4972.1  676.22  4977.3  672.38  5000.0  666.04
  5002.5  665.54  5025.0  666.04  5046.9  677.36  5052.1  677.75  5210.5  677.89
  5721.5  679.02  5970.4  681.98  6281.7  690.32  6442.8  699.64  6499.5  700.77
#Mann=5,-1,0
  3552.3    0.05       0  4442.6    0.12       0  5000.0    0.07       0
  5025.0    0.12       0  5210.5    0.05       0
Bank Sta=5000,5025
Exp/Cntr=0.3,0.1

Type RM Length L Ch R = 1,53575,1129,1129,1129
BEGIN DESCRIPTION:
Elizabeth Creek 54.5
END DESCRIPTION:
XS GIS Cut Line= 2
      2324979.28      7058193.23      2323120.74      7056233.88
#Sta/Elev= 30
  3667.7  686.22  3960.4  684.81  4101.5  679.85  4398.8  674.41  4561.5  673.53
  4688.9  676.00  4698.9  674.80  4717.2  673.03  4738.2  674.89  4922.3  672.18
  4929.2  673.87  4943.3  673.32  4950.6  672.95  4964.7  667.42  4966.4  663.77
  4968.9  663.27  4991.4  663.77  5042.4  672.39  5063.8  671.39  5084.9  674.84
  5346.6  674.10  5381.8  672.54  5389.1  674.25  5396.0  672.22  5403.2  675.04
  5511.4  677.69  5622.5  683.20  5877.3  683.55  5905.2  686.13  6368.3  692.26
#Mann=5,-1,0
  3667.7    0.05       0  4698.9    0.12       0  4966.4    0.07       0
  4991.4    0.12       0  5511.4    0.05       0
Bank Sta=4966.4,4991.4
Exp/Cntr=0.3,0.1

Type RM Length L Ch R = 1,52446,1714,1714,1714
BEGIN DESCRIPTION:
Elizabeth Creek 54.2
END DESCRIPTION:
XS GIS Cut Line= 2
      2325760.95      7057960.00      2324236.01      7055533.97
#Sta/Elev= 30
  3455.6  689.52  4030.4  676.22  4197.7  674.81  4211.5  671.42  4334.3  673.70
  4559.3  669.79  4863.1  672.05  4895.1  670.86  4951.4  668.60  4972.7  661.01
  4993.9  660.06  5066.9  668.22  5218.8  669.85  5386.1  667.49  5574.5  669.15
  5653.4  666.94  5705.2  668.47  5820.7  664.39  5829.4  659.73  5831.9  659.23
  5854.4  659.73  5857.2  666.01  5865.1  668.62  5941.3  678.05  5966.7  682.56
  5972.6  685.82  5987.9  689.24  6009.1  692.14  6097.4  694.26  6321.1  706.81
#Mann=5,-1,0
  3455.6    0.05       0  4895.1    0.12       0  5829.4    0.07       0
  5854.4    0.12       0  5941.3    0.05       0
Bank Sta=5829.4,5854.4
Exp/Cntr=0.3,0.1

Type RM Length L Ch R = 1,50732,582,582,582
BEGIN DESCRIPTION:
Elizabeth Creek 54.0
END DESCRIPTION:
XS GIS Cut Line= 3
      2325878.99      7057709.97      2325279.00      7055310.00
      2324879.03      7055160.01
#Sta/Elev= 30
  2530.4  685.78  3001.9  673.91  3561.1  665.51  3955.4  667.23  4568.7  662.90
  4749.0  664.83  4890.8  660.66  4898.6  662.25  4932.1  658.74  4952.7  661.02
  4973.3  658.80  4973.7  655.90  4976.2  655.40  4998.7  655.90  5044.3  657.48
  5049.6  664.31  5074.5  667.88  5079.9  670.91  5099.5  674.59  5104.8  677.49
  5129.7  680.17  5135.1  684.03  5184.9  686.31  5245.4  692.78  5250.8  694.81
  5270.3  695.28  5301.0  701.22  5314.0  705.23  5330.9  707.31  5431.4  714.10
#Mann=5,-1,0
  2530.4    0.05       0  4749.0    0.12       0  4973.7    0.07       0
  4998.7    0.12       0  5301.0    0.05       0
Bank Sta=4973.7,4998.7
Exp/Cntr=0.3,0.1

Type RM Length L Ch R = 1,50150,665,665,665
BEGIN DESCRIPTION:
Elizabeth Creek 53.0
END DESCRIPTION:
XS GIS Cut Line= 3
      2326029.00      7057610.04      2325829.00      7055210.00
      2325629.00      7054760.01
#Sta/Elev= 30
  2591.6  684.78  3153.6  671.57  3705.5  665.70  3825.9  662.63  4099.4  663.03
  4219.8  660.92  4295.9  662.21  4348.9  662.81  4719.0  661.72  4799.3  660.48
  4821.8  658.00  4827.6  659.81  4909.7  662.07  4981.6  658.57  4996.4  655.63
  4998.9  655.13  5021.4  655.63  5032.1  661.55  5037.6  659.54  5043.7  666.56
  5054.7  670.72  5112.8  672.41  5130.6  675.64  5182.6  679.71  5385.0  691.64
  5402.8  695.90  5408.3  694.60  5448.6  700.03  5478.0  708.44  5492.4  710.27
#Mann=7,-1,0
  2591.6    0.05       0  4295.9    0.12       0  4348.9    0.05       0
  4827.6    0.12       0  4981.6    0.05       0  4996.4   0.033       0
  5021.4    0.05       0
Bank Sta=4996.4,5021.4
Exp/Cntr=0.3,0.1

Type RM Length L Ch R = 1,49485,1438,1438,1438
BEGIN DESCRIPTION:
Elizabeth Creek 52.0
END DESCRIPTION:
XS GIS Cut Line= 3
      2326719.11      7057027.01      2326341.86      7055404.29
      2325918.54      7054808.09
#Sta/Elev= 30
  3391.7  681.02  4430.3  661.92  4473.0  659.93  4496.0  660.75  4538.5  658.42
  4563.3  659.30  4579.6  657.30  4600.1  659.49  4682.2  658.47  4824.1  660.84
  4980.0  658.81  4990.2  658.00  4992.4  652.26  4994.9  651.76  5017.4  652.26
  5031.3  654.40  5047.5  655.70  5052.6  654.35  5066.5  656.21  5070.2  657.32
  5076.3  655.50  5091.1  655.79  5112.0  658.14  5148.8  657.41  5156.3  659.25
  5212.9  657.57  5242.4  661.17  5456.4  667.68  5607.7  675.15  5788.9  686.63
#Mann=5,-1,0
  3391.7    0.05       0  4496.0    0.12       0  4992.4    0.07       0
  5017.4    0.12       0  5066.5    0.05       0
Bank Sta=4992.4,5017.4
Exp/Cntr=0.3,0.1

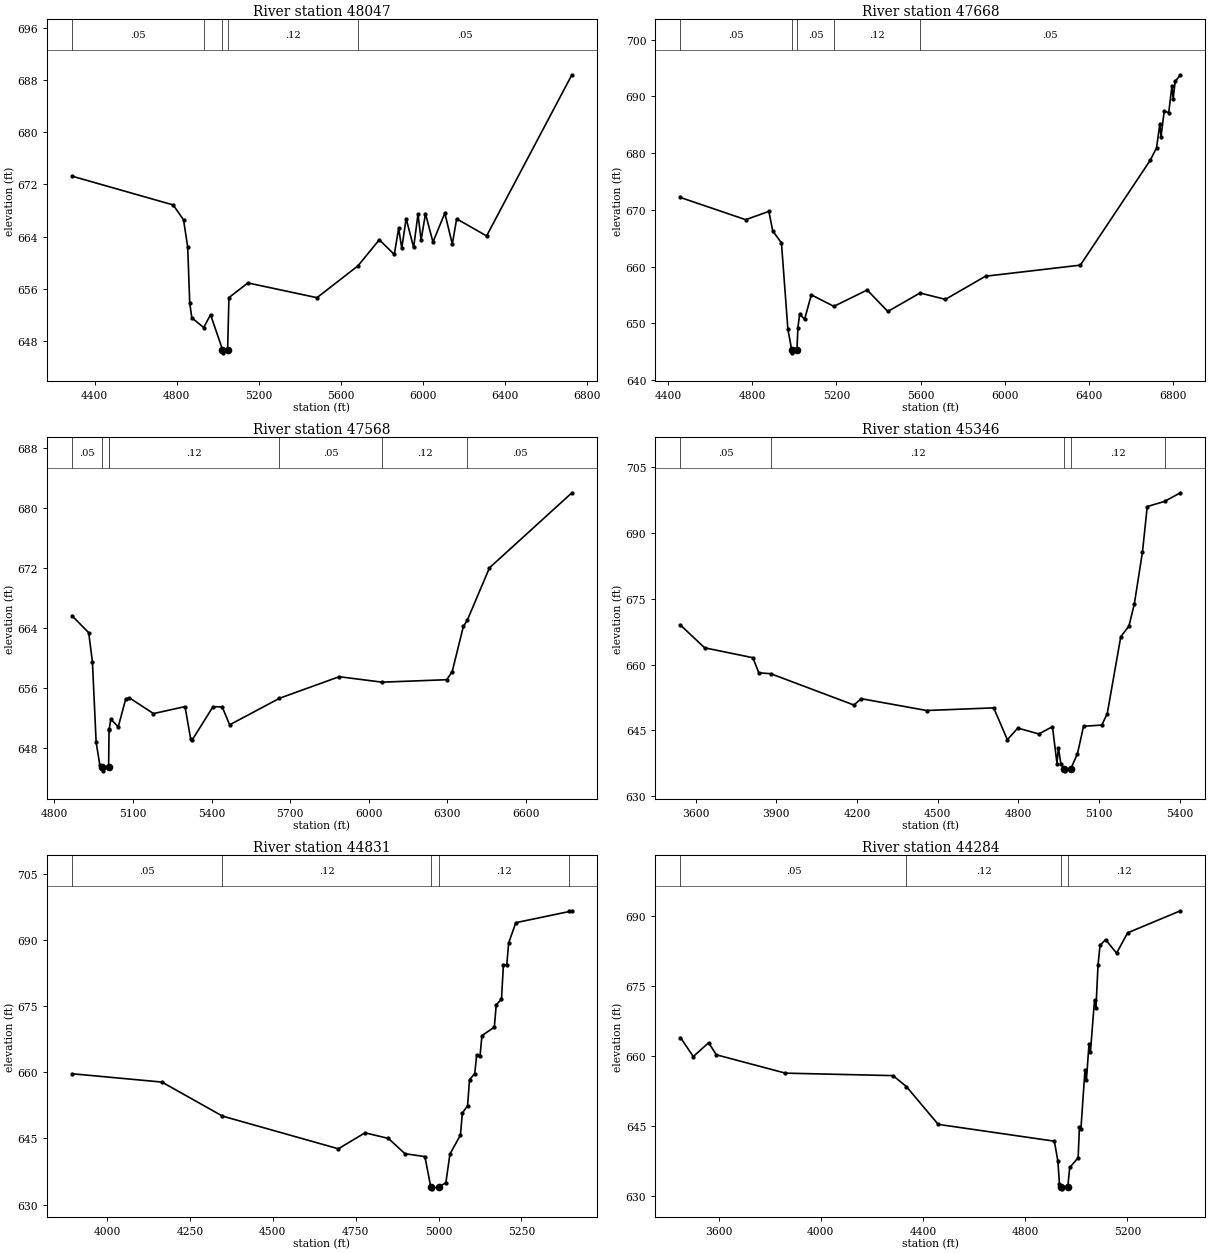
Type RM Length L Ch R = 1,48047,379,379,379
BEGIN DESCRIPTION:
Elizabeth Creek 51.0
END DESCRIPTION:
XS GIS Cut Line= 4
      2327803.36      7056005.77      2327790.75      7055646.47
      2327210.80      7055558.22      2325950.92      7054764.50
#Sta/Elev= 30
  4290.2  673.27  4783.0  668.86  4833.6  666.58  4853.8  662.45  4863.9  653.78
  4874.0  651.57  4932.0  650.07  4965.1  652.05  5023.4  646.70  5025.9  646.20
  5048.4  646.70  5054.7  654.66  5147.1  656.91  5483.5  654.65  5683.4  659.53
  5787.2  663.53  5860.2  661.27  5881.4  665.27  5896.7  662.21  5917.9  666.78
  5954.4  662.34  5975.6  667.44  5990.9  663.51  6012.1  667.51  6048.6  663.17
  6106.3  667.60  6142.8  662.87  6164.0  666.73  6309.9  664.11  6725.4  688.80
#Mann=5,-1,0
  4290.2    0.05       0  4932.0    0.12       0  5023.4    0.07       0
  5048.4    0.12       0  5683.4    0.05       0
Bank Sta=5023.4,5048.4
Exp/Cntr=0.5,0.3

Type RM Length L Ch R = 1,47668,100,100,100
BEGIN DESCRIPTION:
Elizabeth Creek 50.0
END DESCRIPTION:
XS GIS Cut Line= 4
      2327853.79      7055879.70      2327828.57      7055438.45
      2327040.60      7055154.78      2326107.78      7054574.92
#Sta/Elev= 30
  4458.1  672.20  4768.3  668.29  4878.5  669.75  4896.8  666.31  4938.3  664.20
  4969.0  648.97  4987.2  645.33  4989.7  644.83  5012.2  645.33  5016.5  649.27
  5025.1  651.65  5048.4  650.74  5080.3  655.05  5187.6  653.02  5346.0  655.90
  5444.3  652.12  5597.3  655.37  5718.0  654.25  5908.9  658.33  6359.9  660.28
  6693.2  678.81  6722.4  680.95  6737.7  685.09  6743.6  682.91  6759.0  687.46
  6780.2  687.15  6795.6  691.83  6801.4  689.56  6810.9  692.64  6835.9  693.82
#Mann=5,-1,0
  4458.1    0.05       0  4987.2   0.033       0  5012.2    0.05       0
  5187.6    0.12       0  5597.3    0.05       0
Bank Sta=4987.2,5012.2
Exp/Cntr=0.3,0.3

Type RM Length L Ch R = 1,47568,2222,2222,2222
BEGIN DESCRIPTION:
Elizabeth Creek 49.0
END DESCRIPTION:
XS GIS Cut Line= 3
      2327878.99      7055409.99      2327513.38      7055079.13
      2326454.37      7054139.89
#Sta/Elev= 30
  4867.2  665.63  4931.1  663.36  4945.3  659.45  4959.4  648.77  4973.6  645.69
  4982.1  645.43  4984.6  644.93  5007.1  645.43  5008.8  650.38  5009.4  650.51
  5015.5  651.82  5043.9  650.80  5072.3  654.51  5086.5  654.67  5178.4  652.57
  5298.8  653.50  5320.4  649.17  5327.1  649.10  5405.6  653.49  5440.8  653.46
  5469.2  651.07  5659.4  654.61  5887.4  657.49  6051.1  656.76  6298.0  657.09
  6318.9  658.18  6361.6  664.22  6376.4  665.03  6461.1  672.02  6775.8  682.03
#Mann=7,-1,0
  4867.2    0.05       0  4982.1   0.033       0  5007.1    0.05       0
  5009.4    0.12       0  5659.4    0.05       0  6051.1    0.12       0
  6376.4    0.05       0
Bank Sta=4982.1,5007.1
Exp/Cntr=0.3,0.1

Type RM Length L Ch R = 1,45346,515,515,515
BEGIN DESCRIPTION:
Elizabeth Creek 48.0
END DESCRIPTION:
XS GIS Cut Line= 3
      2328029.00      7055510.00      2328429.00      7054110.00
      2328379.00      7053710.03
#Sta/Elev= 30
  3543.7  668.99  3633.4  663.82  3812.8  661.56  3834.9  658.13  3879.8  657.91
  4188.5  650.79  4215.8  652.23  4458.9  649.54  4708.5  650.14  4759.2  642.89
  4798.2  645.54  4876.2  644.20  4926.9  645.86  4943.8  637.47  4949.0  641.08
  4958.1  637.45  4970.2  636.30  4972.7  635.80  4995.5  636.30  5019.9  639.71
  5042.5  645.94  5110.6  646.23  5130.7  648.85  5181.1  666.36  5211.4  668.77
  5231.5  673.85  5261.7  685.65  5279.4  695.98  5343.9  697.16  5402.8  699.12
#Mann=5,-1,0
  3543.7    0.05       0  3879.8    0.12       0  4970.2    0.07       0
  4995.5    0.12       0  5343.9    0.05       0
Bank Sta=4970.2,4995.5
Exp/Cntr=0.3,0.1

Type RM Length L Ch R = 1,44831,547,547,547
BEGIN DESCRIPTION:
Elizabeth Creek 47.0
END DESCRIPTION:
XS GIS Cut Line= 3
      2328779.00      7055010.04      2328879.00      7053910.00
      2328528.99      7053710.00
#Sta/Elev= 30
  3894.6  659.69  4165.8  657.80  4348.4  650.08  4697.9  642.66  4778.3  646.28
  4848.6  645.02  4898.8  641.55  4959.0  640.88  4976.5  634.07  4979.0  633.57
  5001.8  634.07  5022.2  634.94  5034.4  641.46  5066.1  645.78  5071.9  650.76
  5087.7  652.44  5093.5  658.33  5109.3  659.73  5115.1  663.96  5125.2  663.65
  5130.9  668.34  5168.3  670.25  5174.1  675.35  5189.9  676.60  5195.7  684.34
  5205.8  684.33  5211.5  689.35  5233.1  693.97  5395.0  696.51  5402.3  696.67
#Mann=5,-1,0
  3894.6    0.05       0  4348.4    0.12       0  4976.5    0.07       0
  5001.8    0.12       0  5395.0    0.05       0
Bank Sta=4976.5,5001.8
Exp/Cntr=0.3,0.1

Type RM Length L Ch R = 1,44284,529,529,529
BEGIN DESCRIPTION:
Elizabeth Creek 46.0
END DESCRIPTION:
XS GIS Cut Line= 3
      2329229.00      7055460.02      2329329.00      7053910.00
      2329128.98      7053559.96
#Sta/Elev= 30
  3450.9  663.96  3501.0  659.89  3561.1  662.85  3591.2  660.27  3861.8  656.34
  4282.6  655.81  4335.3  653.45  4459.3  645.38  4914.0  641.78  4927.7  637.52
  4934.0  632.58  4941.4  632.08  4943.9  631.58  4966.7  632.08  4974.1  636.15
  5007.0  638.22  5012.1  644.74  5017.8  644.30  5033.7  656.96  5039.4  654.84
  5049.5  662.48  5055.2  660.90  5071.1  672.02  5076.8  670.25  5084.8  679.45
  5092.7  683.68  5114.3  684.92  5157.5  682.02  5200.7  686.37  5407.3  691.09
#Mann=4,-1,0
  3450.9    0.05       0  4335.3    0.12       0  4941.4    0.07       0
  4966.7    0.12       0
Bank Sta=4941.4,4966.7
Exp/Cntr=0.3,0.1

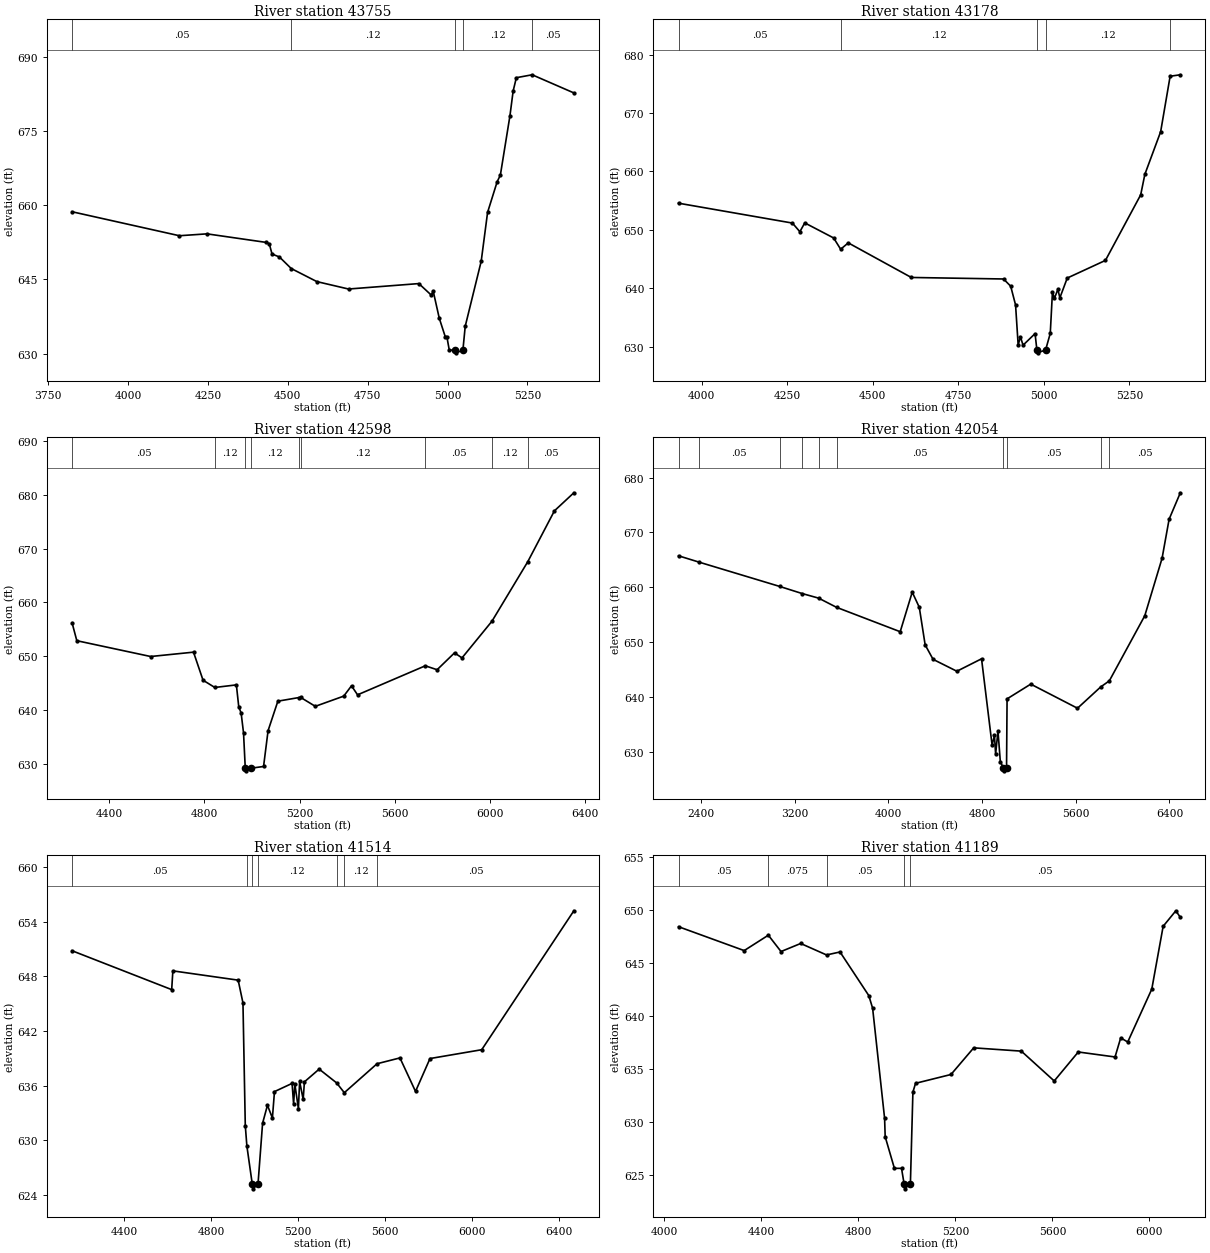
Type RM Length L Ch R = 1,43755,577,577,577
BEGIN DESCRIPTION:
Elizabeth Creek 45.0
END DESCRIPTION:
XS GIS Cut Line= 3
      2329379.01      7055209.97      2329779.00      7054110.00
      2329779.00      7053710.03
#Sta/Elev= 30
  3825.0  658.69  4160.8  653.84  4247.3  654.22  4431.5  652.50  4442.1  652.23
  4450.8  650.14  4474.0  649.54  4510.8  647.21  4591.1  644.56  4690.2  643.06
  4910.3  644.16  4949.5  641.81  4954.9  642.72  4974.2  637.15  4992.8  633.43
  4997.9  633.43  5005.4  630.74  5022.8  630.65  5025.3  630.15  5048.1  630.65
  5055.4  635.52  5105.4  648.67  5125.4  658.57  5155.4  664.77  5165.4  666.11
  5195.4  678.12  5205.4  683.12  5215.4  685.81  5264.9  686.40  5395.4  682.73
#Mann=5,-1,0
  3825.0    0.05       0  4510.8    0.12       0  5022.8    0.07       0
  5048.1    0.12       0  5264.9    0.05       0
Bank Sta=5022.8,5048.1
Exp/Cntr=0.3,0.1

Type RM Length L Ch R = 1,43178,580,580,580
BEGIN DESCRIPTION:
Elizabeth Creek 44.0
END DESCRIPTION:
XS GIS Cut Line= 3
      2329628.99      7054910.02      2330329.00      7054110.00
      2330129.02      7053760.04
#Sta/Elev= 30
  3932.7  654.57  4265.4  651.17  4287.2  649.69  4301.5  651.20  4385.9  648.62
  4406.4  646.69  4428.6  647.78  4612.8  641.86  4882.3  641.60  4903.2  640.36
  4917.4  637.16  4925.0  630.31  4931.7  631.69  4939.3  630.27  4974.4  632.25
  4979.7  629.46  4982.2  628.96  5005.2  629.46  5018.8  632.29  5025.2  639.39
  5031.0  638.29  5041.1  639.84  5046.8  638.37  5068.4  641.76  5180.0  644.78
  5283.0  656.00  5295.2  659.52  5341.3  666.80  5369.0  676.30  5398.8  676.55
#Mann=5,-1,0
  3932.7    0.05       0  4406.4    0.12       0  4979.7    0.07       0
  5005.2    0.12       0  5369.0    0.05       0
Bank Sta=4979.7,5005.2
Exp/Cntr=0.3,0.1

Type RM Length L Ch R = 1,42598,544,544,544
BEGIN DESCRIPTION:
Elizabeth Creek 43.0
END DESCRIPTION:
XS GIS Cut Line= 3
      2330729.00      7055109.97      2330779.00      7054360.00
      2330378.99      7053059.98
#Sta/Elev= 30
  4242.7  656.22  4262.7  652.89  4573.4  649.95  4753.8  650.76  4793.9  645.54
  4843.4  644.19  4934.2  644.67  4944.2  640.59  4954.2  639.44  4964.3  635.74
  4971.6  629.18  4974.1  628.68  4997.1  629.18  5048.6  629.49  5067.6  636.15
  5108.8  641.64  5198.2  642.32  5204.7  642.34  5266.4  640.68  5386.0  642.58
  5418.7  644.50  5444.2  642.82  5729.2  648.22  5779.0  647.49  5852.3  650.63
  5883.7  649.69  6009.9  656.52  6160.3  667.57  6272.7  677.05  6354.5  680.41
#Mann=9,-1,0
  4242.7    0.05       0  4843.4    0.12       0  4971.6    0.07       0
  4997.1    0.12       0  5198.2    0.05       0  5204.7    0.12       0
  5729.2    0.05       0  6009.9    0.12       0  6160.3    0.05       0
Bank Sta=4971.6,4997.1
Exp/Cntr=0.3,0.1

Type RM Length L Ch R = 1,42054,540,540,540
BEGIN DESCRIPTION:
Elizabeth Creek 42.0
END DESCRIPTION:
XS GIS Cut Line= 3
      2331079.00      7057259.98      2331279.00      7054460.00
      2330579.00      7053159.99
#Sta/Elev= 30
  2209.1  665.73  2382.2  664.59  3073.0  660.14  3263.7  658.85  3404.8  658.01
  3558.0  656.33  4101.4  651.88  4204.1  659.10  4264.3  656.34  4314.4  649.48
  4382.1  646.84  4585.1  644.67  4795.7  646.94  4885.9  631.19  4905.9  632.96
  4916.0  629.56  4936.0  633.80  4956.1  628.18  4983.1  627.00  4985.7  626.50
  5009.2  627.00  5013.7  639.63  5215.8  642.32  5614.9  637.92  5812.5  641.80
  5886.7  642.92  6189.3  654.80  6336.9  665.28  6397.0  672.41  6492.7  677.23
#Mann=10,-1,0
  2209.1    0.12       0  2382.2    0.05       0  3073.0    0.12       0
  3263.7    0.05       0  3404.8    0.12       0  3558.0    0.05       0
  4983.1   0.033       0  5009.2    0.05       0  5812.5    0.12       0
  5886.7    0.05       0
Bank Sta=4983.1,5009.2
Exp/Cntr=0.3,0.1

Type RM Length L Ch R = 1,41514,325,325,325
BEGIN DESCRIPTION:
Elizabeth Creek 41.0
END DESCRIPTION:
XS GIS Cut Line= 3
      2332033.18      7055299.72      2331743.23      7054568.53
      2331030.92      7053225.86
#Sta/Elev= 30
  4160.3  650.80  4618.2  646.53  4623.6  648.59  4923.8  647.57  4945.8  645.07
  4956.5  631.60  4963.8  629.36  4988.7  625.15  4991.3  624.65  5014.9  625.15
  5036.0  631.85  5058.4  633.83  5081.1  632.43  5090.7  635.33  5171.6  636.23
  5178.6  633.96  5184.3  636.16  5200.6  633.46  5206.3  636.45  5222.6  634.47
  5228.3  636.40  5296.1  637.80  5376.1  636.29  5411.7  635.21  5562.1  638.39
  5667.4  639.03  5739.0  635.35  5805.5  638.96  6043.3  639.93  6466.8  655.19
#Mann=7,-1,0
  4160.3    0.05       0  4963.8    0.12       0  4988.7    0.07       0
  5014.9    0.12       0  5376.1    0.05       0  5411.7    0.12       0
  5562.1    0.05       0
Bank Sta=4988.7,5014.9
Exp/Cntr=0.3,0.1

Type RM Length L Ch R = 1,41189,1126,1126,1126
BEGIN DESCRIPTION:
Elizabeth Creek 40.0
END DESCRIPTION:
XS GIS Cut Line= 3
      2332417.74      7055148.48      2332001.68      7054404.63
      2331516.28      7053288.84
#Sta/Elev= 30
  4058.4  648.43  4329.1  646.18  4428.7  647.63  4481.0  646.09  4562.1  646.85
  4668.7  645.77  4724.3  646.05  4843.0  641.94  4858.7  640.75  4908.1  630.38
  4910.5  628.65  4948.5  625.67  4977.9  625.67  4988.3  624.24  4990.9  623.74
  5014.5  624.24  5024.8  632.85  5035.7  633.68  5181.8  634.51  5275.5  637.02
  5471.9  636.71  5607.5  633.90  5706.7  636.63  5858.3  636.16  5881.7  637.96
  5910.6  637.57  6009.8  642.55  6056.7  648.47  6109.0  649.93  6127.5  649.31
#Mann=5,-1,0
  4058.4    0.05       0  4428.7   0.075       0  4668.7    0.05       0
  4988.3    0.05       0  5014.5    0.05       0
Bank Sta=4988.3,5014.5
Exp/Cntr=0.3,0.1

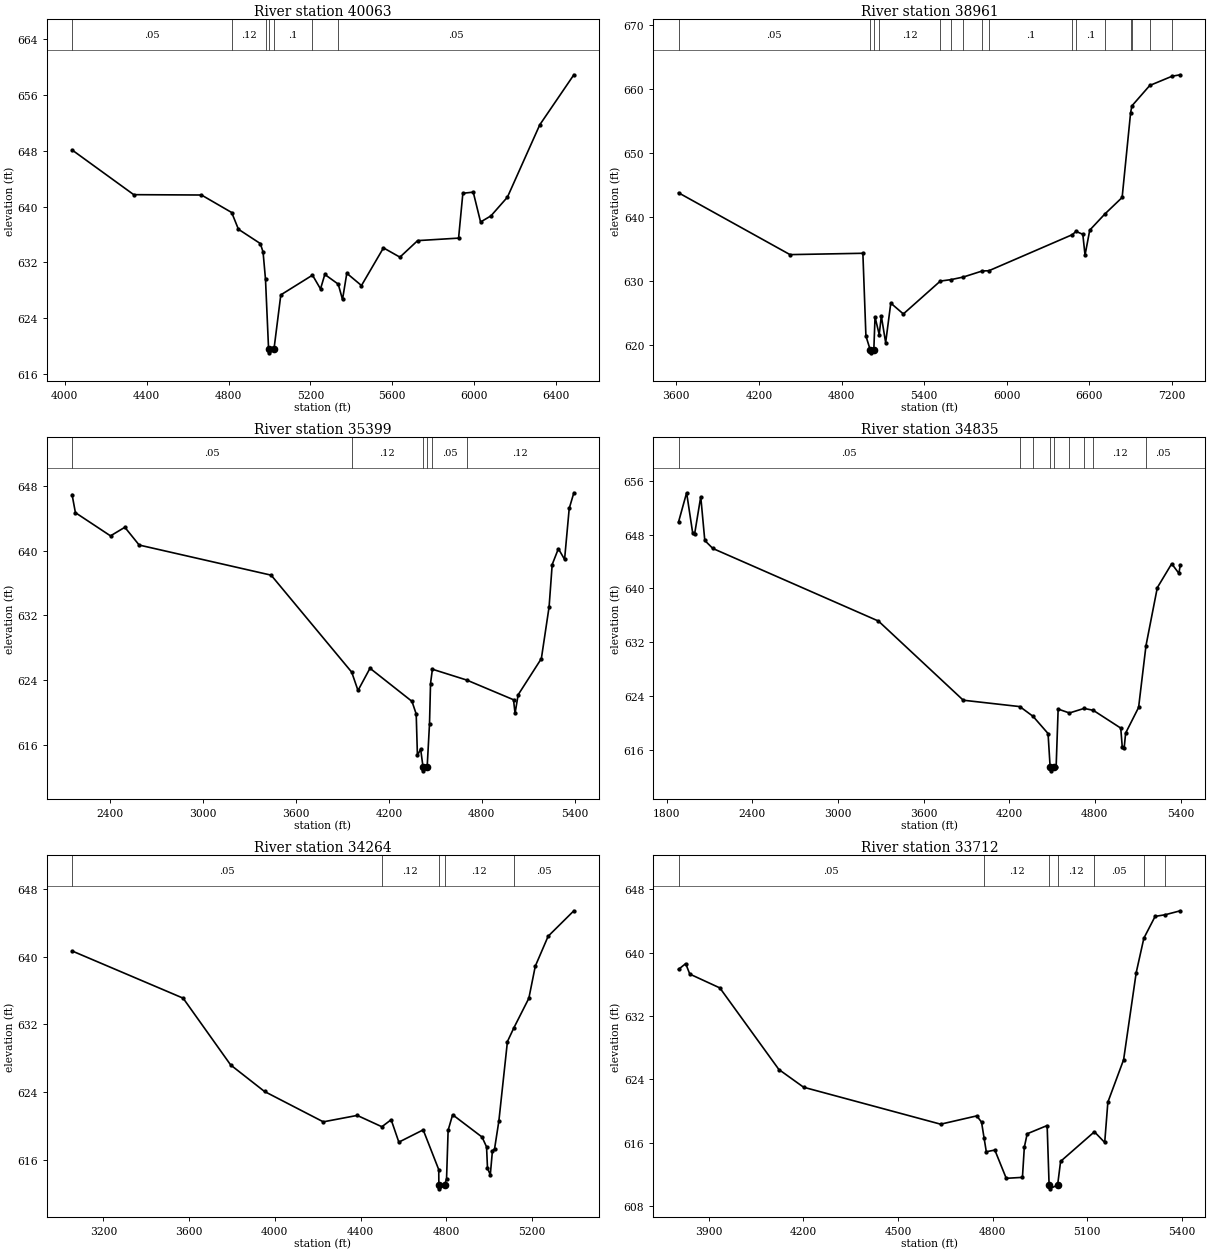
Type RM Length L Ch R = 1,40063,1102,1102,1102
BEGIN DESCRIPTION:
Elizabeth Creek 39.0
END DESCRIPTION:
XS GIS Cut Line= 3
      2333029.20      7054940.45      2332959.86      7053963.36
      2332122.14      7052754.02
#Sta/Elev= 30
  4035.8  648.13  4337.0  641.72  4667.8  641.67  4815.4  639.16  4848.3  636.76
  4955.2  634.71  4968.6  633.50  4980.5  629.58  4995.6  619.54  4998.2  619.04
  5021.8  619.54  5055.3  627.35  5210.0  630.18  5249.2  628.20  5270.2  630.28
  5335.7  628.89  5356.6  626.69  5377.6  630.45  5449.2  628.69  5556.6  634.09
  5637.0  632.76  5723.5  635.13  5923.5  635.49  5944.4  641.92  5995.1  642.08
  6030.9  637.80  6081.6  638.68  6162.0  641.36  6320.1  651.74  6486.5  658.91
#Mann=7,-1,0
  4035.8    0.05       0  4815.4    0.12       0  4980.5     0.1       0
  4995.6    0.07       0  5021.8     0.1       0  5210.0    0.12       0
  5335.7    0.05       0
Bank Sta=4995.6,5021.8
Exp/Cntr=0.3,0.1

Type RM Length L Ch R = 1,38961,3562,3562,3562
BEGIN DESCRIPTION:
Elizabeth Creek 38.5
END DESCRIPTION:
XS GIS Cut Line= 5
      2333281.34      7054763.97      2333924.34      7053685.99
      2333710.01      7053225.82      2333117.45      7052154.17
      2333067.03      7051498.59
#Sta/Elev= 30
  3616.2  643.76  4425.9  634.11  4955.2  634.32  4977.3  621.41  5008.1  619.28
  5010.7  618.78  5034.8  619.28  5043.5  624.38  5073.9  621.63  5089.2  624.52
  5120.7  620.37  5157.9  626.54  5249.3  624.85  5517.8  629.98  5596.1  630.21
  5684.4  630.61  5822.8  631.56  5870.0  631.59  6477.1  637.23  6502.9  637.74
  6552.8  637.28  6568.9  634.03  6603.1  637.93  6712.9  640.45  6838.4  643.03
  6900.0  656.27  6909.5  657.33  7039.1  660.51  7201.8  661.96  7261.1  662.18
#Mann=16,-1,0
  3616.2    0.05       0  5008.1   0.033       0  5034.8    0.05       0
  5073.9    0.12       0  5517.8     0.1       0  5596.1    0.12       0
  5684.4     0.1       0  5822.8    0.12       0  5870.0     0.1       0
  6477.1    0.12       0  6502.9     0.1       0  6712.9    0.12       0
  6900.0    0.05       0  6909.5   0.075       0  7039.1     0.1       0
  7201.8   0.075       0
Bank Sta=5008.1,5034.8
Exp/Cntr=0.3,0.1

Type RM Length L Ch R = 1,35399,564,564,564
BEGIN DESCRIPTION:
Elizabeth Creek 38.0
END DESCRIPTION:
XS GIS Cut Line= 3
      2333428.99      7054860.02      2335229.00      7052660.00
      2335229.00      7052259.96
#Sta/Elev= 30
  2152.2  646.89  2173.8  644.67  2400.6  641.81  2493.2  642.87  2585.8  640.68
  3438.5  636.97  3959.2  625.02  3999.9  622.76  4077.4  625.50  4348.7  621.42
  4376.0  619.86  4383.9  614.75  4404.7  615.54  4419.9  613.36  4422.6  612.86
  4446.9  613.36  4462.1  618.69  4468.6  623.62  4480.7  625.38  4701.9  624.05
  5004.8  621.62  5014.8  619.94  5034.8  622.23  5184.8  626.69  5234.8  633.07
  5254.8  638.28  5294.8  640.23  5334.8  638.91  5364.8  645.19  5394.8  647.12
#Mann=6,-1,0
  2152.2    0.05       0  3959.2    0.12       0  4419.9    0.07       0
  4446.9    0.12       0  4480.7    0.05       0  4701.9    0.12       0
Bank Sta=4419.9,4446.9
Exp/Cntr=0.3,0.1

Type RM Length L Ch R = 1,34835,571,571,571
BEGIN DESCRIPTION:
Elizabeth Creek 37.0
END DESCRIPTION:
XS GIS Cut Line= 3
      2333378.99      7055210.01      2335579.00      7053010.00
      2335979.00      7052960.00
#Sta/Elev= 30
  1884.2  649.86  1940.8  654.21  1983.2  648.24  1997.4  648.15  2039.8  653.63
  2068.1  647.11  2124.6  645.92  3284.3  635.12  3878.3  623.34  4274.5  622.39
  4367.2  620.94  4472.2  618.38  4487.0  613.33  4489.7  612.83  4514.0  613.33
  4528.8  613.40  4542.9  622.02  4621.9  621.44  4724.7  622.12  4788.6  621.84
  4981.3  619.19  4992.0  616.36  5005.6  616.30  5015.6  618.45  5106.3  622.26
  5158.1  631.46  5237.4  640.09  5338.1  643.65  5388.5  642.22  5398.6  643.49
#Mann=9,-1,0
  1884.2    0.05       0  4274.5    0.12       0  4367.2     0.1       0
  4487.0    0.07       0  4514.0     0.1       0  4621.9    0.12       0
  4724.7     0.1       0  4788.6    0.12       0  5158.1    0.05       0
Bank Sta=4487,4514
Exp/Cntr=0.3,0.1

Type RM Length L Ch R = 1,34264,552,552,552
BEGIN DESCRIPTION:
Elizabeth Creek 36.0
END DESCRIPTION:
XS GIS Cut Line= 3
      2334079.02      7054609.98      2335679.00      7053510.00
      2336078.98      7053510.00
#Sta/Elev= 30
  3053.8  640.69  3572.0  635.11  3794.0  627.21  3951.8  624.08  4226.2  620.49
  4384.5  621.25  4499.5  619.91  4542.8  620.74  4578.7  618.09  4692.3  619.54
  4764.9  614.84  4765.4  613.07  4768.0  612.57  4792.5  613.07  4801.3  613.74
  4808.7  619.50  4829.7  621.33  4967.0  618.69  4988.0  617.53  4992.4  615.01
  5005.4  614.21  5015.4  617.06  5025.4  617.30  5045.4  620.58  5085.4  629.98
  5115.6  631.61  5185.4  635.10  5215.4  638.89  5275.4  642.43  5395.4  645.44
#Mann=5,-1,0
  3053.8    0.05       0  4499.5    0.12       0  4765.4    0.07       0
  4792.5    0.12       0  5115.6    0.05       0
Bank Sta=4765.4,4792.5
Exp/Cntr=0.3,0.1

Type RM Length L Ch R = 1,33712,583,583,583
BEGIN DESCRIPTION:
Elizabeth Creek 35.0
END DESCRIPTION:
XS GIS Cut Line= 3
      2334629.04      7054659.98      2335629.00      7054010.00
      2336028.96      7054010.00
#Sta/Elev= 30
  3803.4  637.89  3826.1  638.61  3839.1  637.29  3934.6  635.54  4121.9  625.23
  4200.4  622.99  4635.3  618.32  4749.9  619.37  4765.1  618.58  4773.0  616.61
  4780.2  614.84  4807.3  615.05  4843.5  611.48  4894.9  611.60  4900.9  615.42
  4910.0  617.11  4973.3  618.15  4979.5  610.65  4982.2  610.15  5006.6  610.65
  5016.0  613.62  5123.3  617.36  5156.0  616.01  5166.0  621.10  5216.0  626.47
  5256.0  637.48  5280.3  641.83  5316.0  644.58  5348.1  644.79  5396.0  645.29
#Mann=7,-1,0
  3803.4    0.05       0  4773.0    0.12       0  4979.5    0.07       0
  5006.6    0.12       0  5123.3    0.05       0  5280.3    0.12       0
  5348.1    0.05       0
Bank Sta=4979.5,5006.6
Exp/Cntr=0.3,0.1

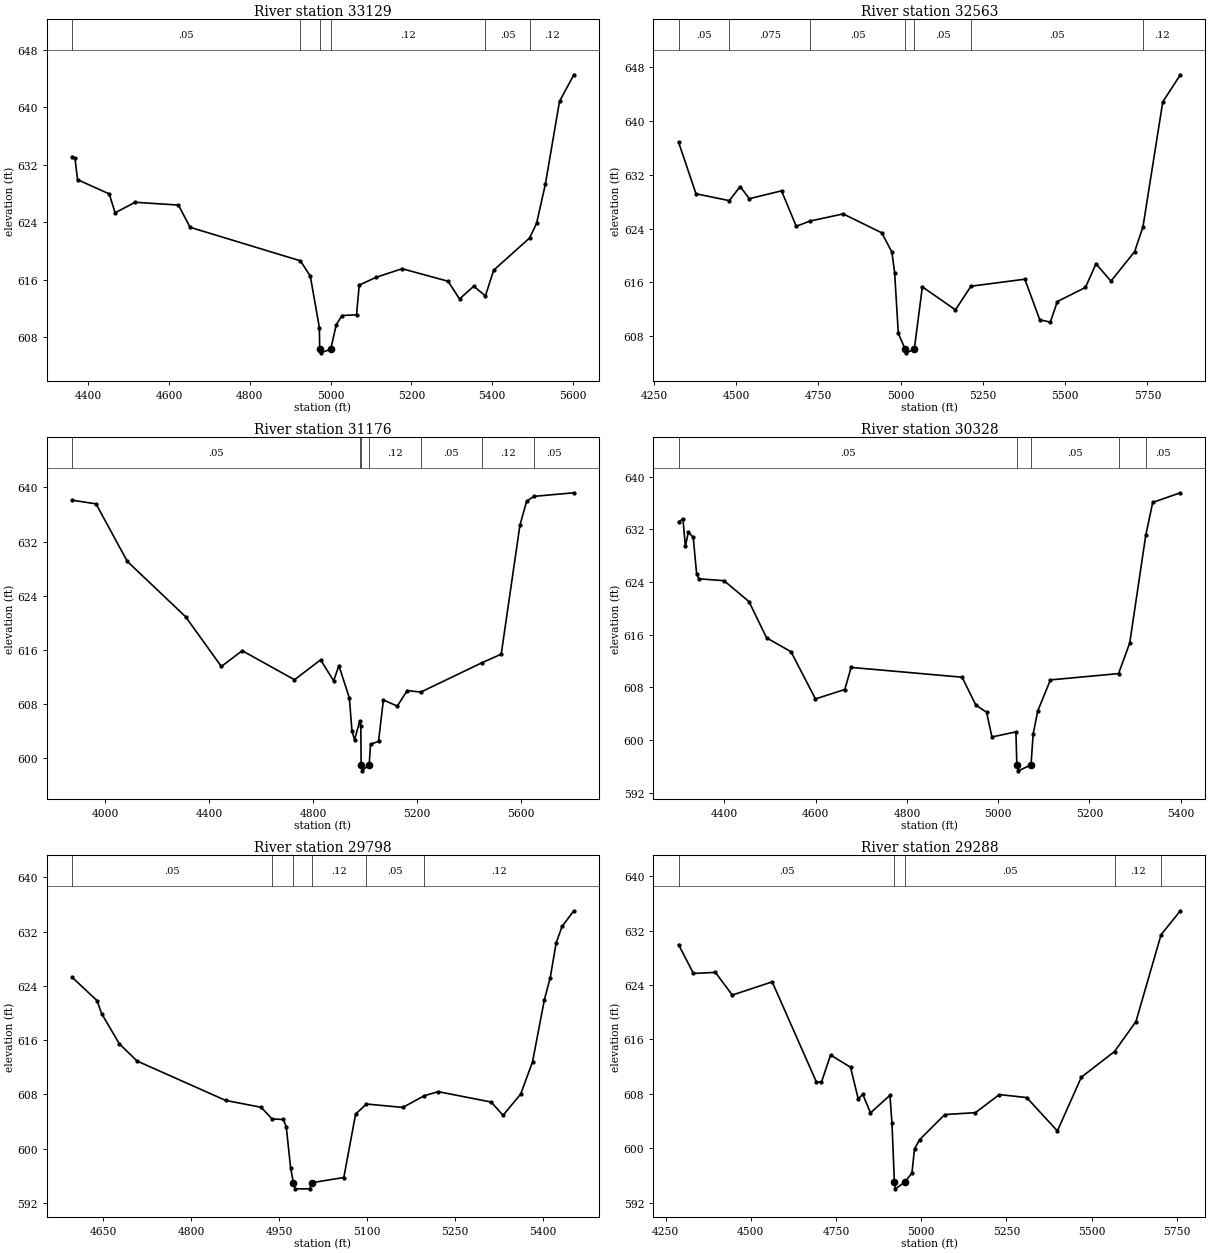
Type RM Length L Ch R = 1,33129,566,566,566
BEGIN DESCRIPTION:
Elizabeth Creek 34.0
END DESCRIPTION:
XS GIS Cut Line= 3
      2335128.98      7054960.02      2335629.00      7054560.00
      2336028.98      7054110.02
#Sta/Elev= 30
  4359.8  633.14  4367.0  632.90  4373.4  629.93  4451.9  627.95  4466.3  625.32
  4515.9  626.79  4623.2  626.40  4652.0  623.31  4925.3  618.65  4949.7  616.51
  4972.1  609.37  4972.9  606.36  4975.6  605.86  5000.2  606.36  5013.9  609.76
  5028.2  611.05  5064.1  611.14  5070.8  615.28  5113.5  616.38  5177.0  617.55
  5290.7  615.81  5319.2  613.35  5354.3  615.12  5383.2  613.77  5403.6  617.34
  5492.5  621.82  5509.8  623.84  5531.6  629.29  5566.7  640.82  5602.2  644.51
#Mann=6,-1,0
  4359.8    0.05       0  4925.3    0.12       0  4972.9    0.07       0
  5000.2    0.12       0  5383.2    0.05       0  5492.5    0.12       0
Bank Sta=4972.9,5000.2
Exp/Cntr=0.3,0.1

Type RM Length L Ch R = 1,32563,1387,1387,1387
BEGIN DESCRIPTION:
Elizabeth Creek 33.0
END DESCRIPTION:
XS GIS Cut Line= 3
      2335329.00      7055310.00      2335929.00      7055010.00
      2336228.99      7054210.02
#Sta/Elev= 30
  4324.9  636.84  4378.0  629.16  4479.3  628.14  4512.2  630.24  4540.1  628.43
  4637.9  629.60  4682.7  624.33  4724.8  625.11  4825.2  626.17  4942.6  623.36
  4973.4  620.50  4981.7  617.46  4992.9  608.43  5014.1  606.03  5016.8  605.53
  5041.4  606.03  5066.0  615.33  5166.6  611.92  5213.7  615.43  5377.5  616.47
  5422.9  610.44  5455.0  610.09  5476.3  613.15  5561.8  615.25  5593.8  618.76
  5639.2  616.18  5711.3  620.57  5736.7  624.29  5796.7  642.81  5850.1  646.84
#Mann=7,-1,0
  4324.9    0.05       0  4479.3   0.075       0  4724.8    0.05       0
  5014.1    0.04       0  5041.4    0.05       0  5213.7    0.05       0
  5736.7    0.12       0
Bank Sta=5014.1,5041.4
Exp/Cntr=0.3,0.1

Type RM Length L Ch R = 1,31176,848,848,848
BEGIN DESCRIPTION:
Elizabeth Creek 32.0
END DESCRIPTION:
XS GIS Cut Line= 3
      2336956.46      7056081.47      2337051.02      7054990.88
      2337233.84      7054177.66
#Sta/Elev= 30
  3873.7  638.11  3965.8  637.56  4086.0  629.06  4310.0  620.88  4447.3  613.53
  4527.6  615.86  4728.4  611.57  4828.7  614.51  4878.9  611.41  4899.0  613.66
  4939.2  608.88  4949.2  604.03  4959.2  602.67  4979.0  605.45  4983.3  604.77
  4984.5  599.01  4987.5  598.11  5015.5  599.01  5020.5  602.03  5051.3  602.47
  5069.9  608.58  5123.4  607.68  5161.6  609.97  5214.0  609.75  5447.3  614.06
  5522.8  615.35  5594.5  634.38  5620.2  637.93  5647.8  638.67  5801.9  639.20
#Mann=7,-1,0
  3873.7    0.05       0  4979.0    0.12       0  4984.5    0.07       0
  5015.5    0.12       0  5214.0    0.05       0  5447.3    0.12       0
  5647.8    0.05       0
Bank Sta=4984.5,5015.5
Exp/Cntr=0.3,0.1

Type RM Length L Ch R = 1,30328,530,530,530
BEGIN DESCRIPTION:
Elizabeth Creek 31.0
END DESCRIPTION:
XS GIS Cut Line= 3
      2337528.99      7055510.02      2337779.00      7054860.00
      2337829.01      7054459.96
#Sta/Elev= 30
  4299.5  633.15  4309.2  633.58  4314.5  629.42  4321.0  631.57  4331.7  630.78
  4339.2  625.20  4344.5  624.48  4399.2  624.20  4453.8  621.03  4492.4  615.52
  4546.0  613.40  4599.5  606.23  4663.8  607.66  4677.7  611.02  4920.9  609.53
  4950.9  605.30  4974.5  604.21  4986.3  600.45  5038.8  601.22  5040.9  596.20
  5043.9  595.30  5071.9  596.20  5076.6  600.88  5086.6  604.39  5114.4  609.12
  5263.8  610.08  5288.2  614.73  5323.3  631.08  5338.6  636.09  5399.1  637.56
#Mann=5,-1,0
  4299.5    0.05       0  5040.9   0.033       0  5071.9    0.05       0
  5263.8    0.12       0  5323.3    0.05       0
Bank Sta=5040.9,5071.9
Exp/Cntr=0.3,0.1

Type RM Length L Ch R = 1,29798,510,510,510
BEGIN DESCRIPTION:
Elizabeth Creek 30.0
END DESCRIPTION:
XS GIS Cut Line= 3
      2338179.00      7055409.99      2338229.00      7055010.00
      2338179.00      7054559.98
#Sta/Elev= 30
  4597.2  625.28  4640.0  621.81  4647.6  619.91  4677.8  615.47  4708.0  612.93
  4859.2  607.12  4919.7  606.11  4938.4  604.39  4957.5  604.31  4962.5  603.26
  4970.1  597.09  4974.7  594.99  4977.7  594.09  5002.7  594.09  5005.7  594.99
  5060.7  595.76  5080.8  605.10  5099.2  606.59  5161.3  606.09  5197.9  607.81
  5221.7  608.41  5312.2  606.88  5332.3  604.92  5362.5  608.07  5382.6  612.81
  5402.8  621.96  5412.8  625.21  5422.9  630.33  5433.0  632.77  5453.1  635.07
#Mann=6,-1,0
  4597.2    0.05       0  4938.4    0.12       0  4974.7    0.07       0
  5005.7    0.12       0  5099.2    0.05       0  5197.9    0.12       0
Bank Sta=4974.7,5005.7
Exp/Cntr=0.3,0.1

Type RM Length L Ch R = 1,29288,557,557,557
BEGIN DESCRIPTION:
Elizabeth Creek 29.0
END DESCRIPTION:
XS GIS Cut Line= 3
      2338278.99      7055710.02      2338679.00      7055110.00
      2338629.00      7054360.00
#Sta/Elev= 30
  4287.8  629.93  4331.4  625.69  4396.0  625.84  4445.6  622.51  4562.7  624.45
  4691.9  609.79  4707.0  609.66  4734.0  613.70  4792.6  611.90  4815.1  607.26
  4828.7  607.89  4851.2  605.19  4908.3  607.77  4914.3  603.63  4921.3  595.02
  4924.3  594.02  4952.3  595.02  4972.9  596.37  4980.4  599.89  4995.4  601.25
  5069.1  604.94  5159.3  605.22  5229.4  607.88  5309.6  607.44  5399.8  602.53
  5470.0  610.43  5567.5  614.21  5630.3  618.61  5704.1  631.38  5760.6  634.90
#Mann=5,-1,0
  4287.8    0.05       0  4921.3    0.04       0  4952.3    0.05       0
  5567.5    0.12       0  5704.1    0.05       0
Bank Sta=4921.3,4952.3
Exp/Cntr=0.3,0.1