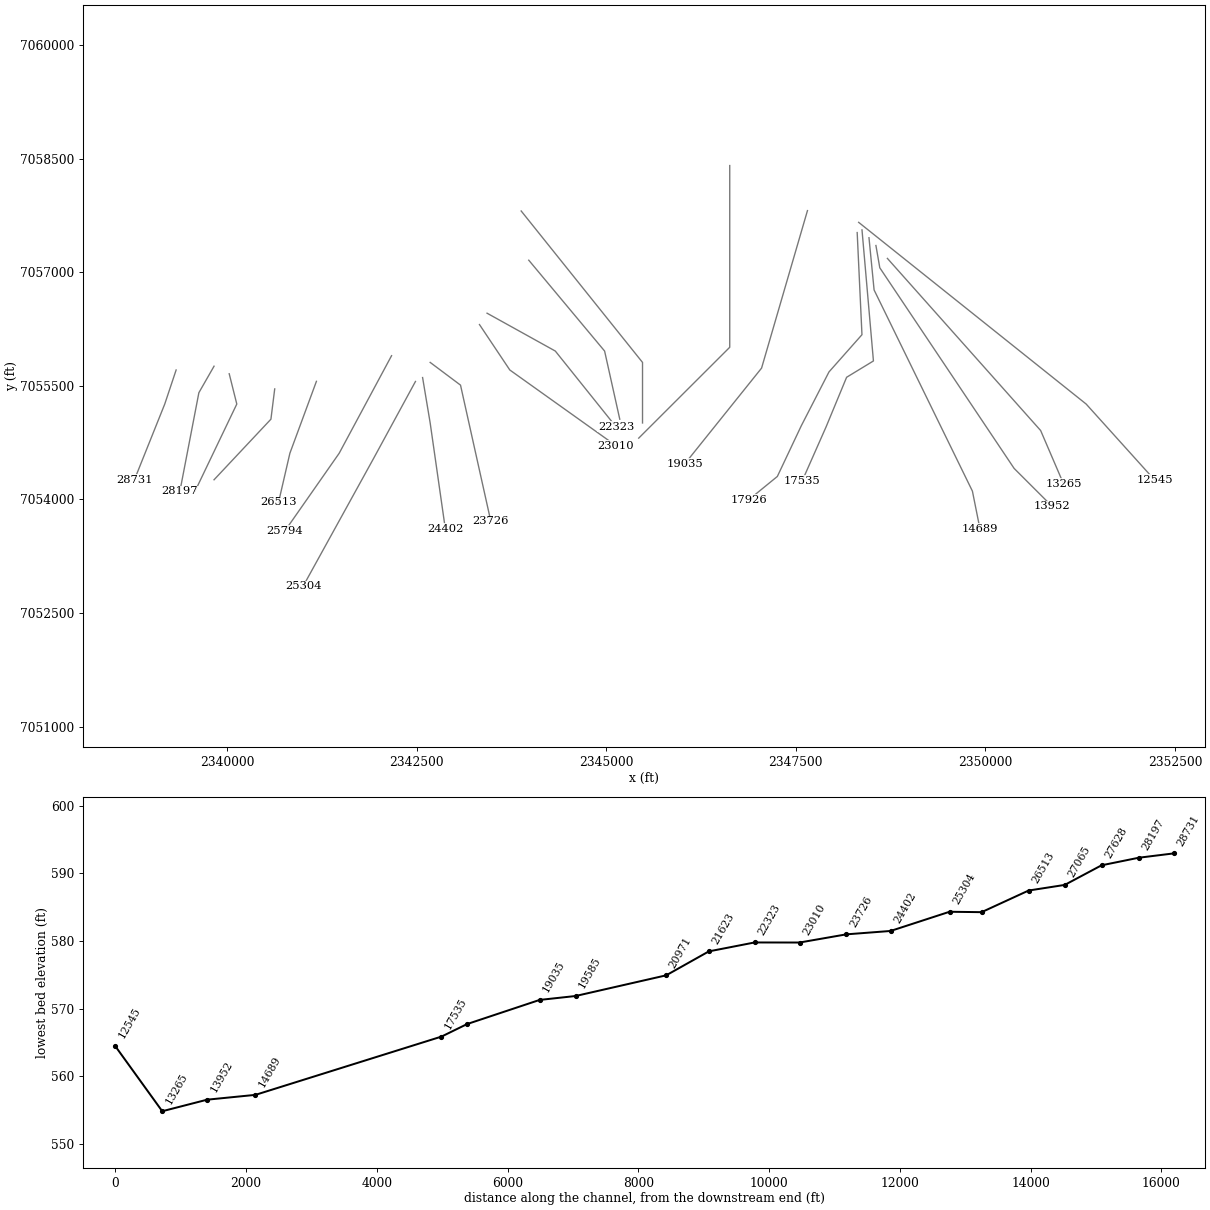
HEC-RAS study Elizabeth Creek.prj: Elizabeth Creek Base Level Engineering

--- Elizabeth Creek.g01 (geometry) --- (continued)

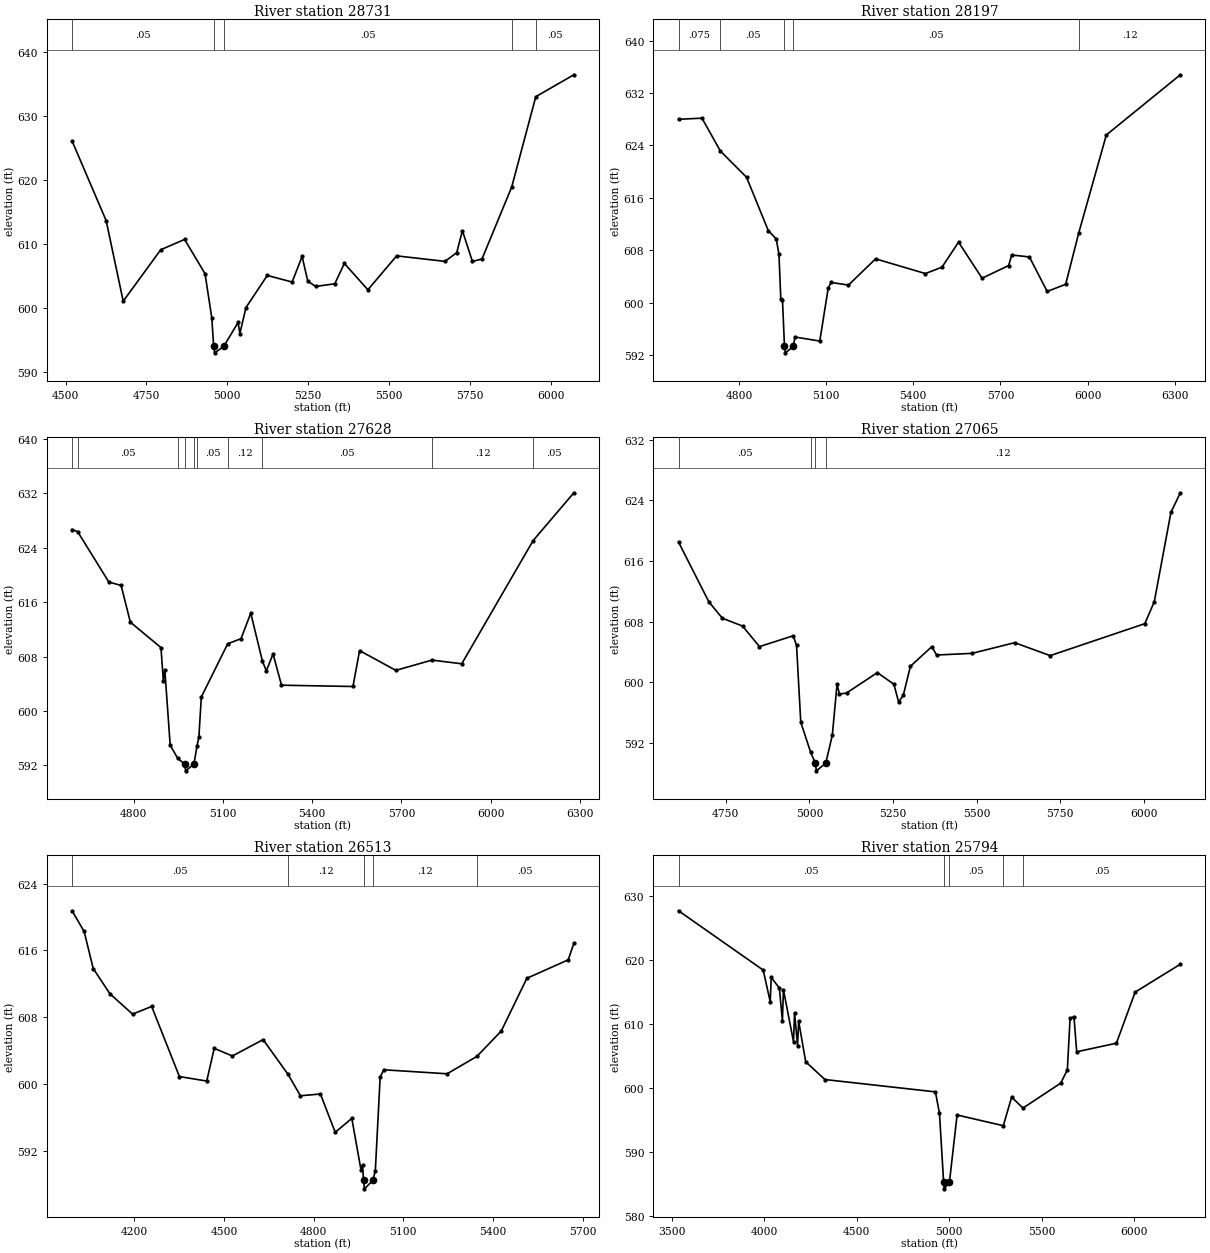
Type RM Length L Ch R = 1,28731,534,534,534
BEGIN DESCRIPTION:
Elizabeth Creek 28.0
END DESCRIPTION:
XS GIS Cut Line= 3
      2339328.99      7055709.96      2339179.00      7055260.00
      2338779.01      7054260.03
#Sta/Elev= 30
  4520.0  626.06  4625.4  613.61  4678.1  601.03  4794.0  609.06  4867.8  610.68
  4931.1  605.32  4952.1  598.37  4957.7  593.96  4960.7  592.96  4988.7  593.96
  5033.3  597.70  5038.7  595.97  5057.6  600.03  5123.5  605.05  5200.3  604.02
  5231.2  608.02  5248.7  604.16  5273.0  603.33  5332.2  603.75  5361.8  606.93
  5434.5  602.81  5523.4  608.11  5672.8  607.25  5709.2  608.61  5726.7  612.05
  5757.6  607.24  5787.3  607.62  5879.2  618.88  5953.6  632.98  6071.3  636.40
#Mann=5,-1,0
  4520.0    0.05       0  4957.7   0.033       0  4988.7    0.05       0
  5879.2    0.12       0  5953.6    0.05       0
Bank Sta=4957.7,4988.7
Exp/Cntr=0.3,0.1

Type RM Length L Ch R = 1,28197,569,569,569
BEGIN DESCRIPTION:
Elizabeth Creek 27.0
END DESCRIPTION:
XS GIS Cut Line= 3
      2339829.02      7055760.03      2339629.00      7055410.00
      2339378.99      7054109.97
#Sta/Elev= 30
  4592.3  628.00  4673.0  628.17  4736.4  623.14  4826.3  619.15  4901.1  611.00
  4928.5  609.72  4937.9  607.37  4944.3  600.57  4950.1  600.37  4956.9  593.32
  4959.9  592.32  4987.9  593.32  4992.6  594.74  5078.4  594.12  5107.5  602.23
  5117.6  603.07  5177.2  602.67  5270.4  606.68  5442.0  604.43  5499.0  605.41
  5556.0  609.23  5637.0  603.72  5728.6  605.66  5738.8  607.27  5799.9  606.97
  5861.0  601.70  5924.7  602.79  5969.8  610.66  6064.7  625.61  6319.3  634.80
#Mann=5,-1,0
  4592.3   0.075       0  4736.4    0.05       0  4956.9    0.04       0
  4987.9    0.05       0  5969.8    0.12       0
Bank Sta=4956.9,4987.9
Exp/Cntr=0.3,0.1

Type RM Length L Ch R = 1,27628,563,563,563
BEGIN DESCRIPTION:
Elizabeth Creek 26.0
END DESCRIPTION:
XS GIS Cut Line= 3
      2340029.00      7055660.01      2340129.00      7055260.00
      2339578.99      7054109.98
#Sta/Elev= 30
  4592.7  626.68  4611.5  626.36  4716.4  618.95  4757.6  618.46  4788.6  613.06
  4891.6  609.32  4899.4  604.47  4904.5  606.05  4922.6  594.98  4948.0  593.02
  4971.5  592.20  4974.5  591.20  5002.5  592.20  5013.0  594.92  5019.1  596.17
  5027.2  602.05  5116.0  609.88  5160.7  610.63  5193.5  614.38  5232.5  607.35
  5245.9  605.90  5268.5  608.39  5296.8  603.79  5537.1  603.60  5559.3  608.88
  5681.2  605.97  5802.7  607.48  5902.9  606.94  6142.8  625.05  6279.8  632.08
#Mann=10,-1,0
  4592.7   0.075       0  4611.5    0.05       0  4948.0    0.12       0
  4971.5    0.07       0  5002.5    0.12       0  5013.0    0.05       0
  5116.0    0.12       0  5232.5    0.05       0  5802.7    0.12       0
  6142.8    0.05       0
Bank Sta=4971.5,5002.5
Exp/Cntr=0.3,0.1

Type RM Length L Ch R = 1,27065,552,552,552
BEGIN DESCRIPTION:
Elizabeth Creek 25.0
END DESCRIPTION:
XS GIS Cut Line= 3
      2340629.00      7055460.01      2340579.00      7055060.00
      2339829.01      7054260.01
#Sta/Elev= 30
  4608.9  618.50  4699.6  610.61  4739.9  608.45  4800.4  607.41  4850.8  604.70
  4951.6  606.13  4961.6  604.87  4974.2  594.72  5003.5  590.78  5017.8  589.30
  5020.8  588.30  5048.8  589.30  5068.5  593.00  5082.6  599.72  5089.9  598.44
  5110.9  598.57  5203.2  601.27  5252.6  599.73  5266.8  597.36  5280.9  598.32
  5301.9  602.10  5365.9  604.70  5380.1  603.59  5486.1  603.81  5613.5  605.22
  5719.6  603.51  6002.4  607.73  6030.7  610.61  6080.5  622.42  6108.6  625.01
#Mann=4,-1,0
  4608.9    0.05       0  5003.5    0.12       0  5017.8   0.033       0
  5048.8    0.12       0
Bank Sta=5017.8,5048.8
Exp/Cntr=0.3,0.1

Type RM Length L Ch R = 1,26513,719,719,719
BEGIN DESCRIPTION:
Elizabeth Creek 24.0
END DESCRIPTION:
XS GIS Cut Line= 3
      2341179.00      7055560.01      2340829.00      7054610.00
      2340679.00      7053960.02
#Sta/Elev= 30
  3991.4  620.75  4031.8  618.27  4062.2  613.84  4117.8  610.83  4193.9  608.38
  4257.8  609.30  4350.7  600.91  4442.1  600.37  4467.2  604.28  4528.1  603.37
  4630.8  605.33  4714.5  601.16  4755.7  598.61  4822.7  598.82  4872.1  594.23
  4927.7  595.90  4958.2  589.78  4963.5  590.32  4967.0  588.47  4970.0  587.47
  4998.0  588.47  5006.4  589.64  5022.6  600.84  5034.6  601.72  5246.7  601.24
  5346.3  603.32  5428.0  606.36  5513.6  612.67  5652.1  614.88  5670.9  616.85
#Mann=5,-1,0
  3991.4    0.05       0  4714.5    0.12       0  4967.0    0.07       0
  4998.0    0.12       0  5346.3    0.05       0
Bank Sta=4967,4998
Exp/Cntr=0.3,0.1

Type RM Length L Ch R = 1,25794,490,490,490
BEGIN DESCRIPTION:
Elizabeth Creek 23.0
END DESCRIPTION:
XS GIS Cut Line= 3
      2342169.71      7055898.63      2341479.00      7054610.00
      2340763.97      7053585.16
#Sta/Elev= 30
  3537.9  627.65  3995.2  618.40  4033.4  613.47  4039.0  617.25  4082.9  615.59
  4099.2  610.48  4104.8  615.33  4159.3  607.21  4164.9  611.74  4181.2  606.59
  4186.9  610.45  4225.1  604.09  4329.0  601.32  4926.1  599.40  4948.0  596.04
  4970.6  585.27  4973.6  584.27  5001.7  585.27  5043.2  595.79  5293.0  594.12
  5338.0  598.58  5399.3  596.87  5603.2  600.76  5639.0  602.82  5653.8  610.85
  5674.8  611.13  5689.6  605.65  5904.2  606.99  6005.4  614.96  6249.6  619.31
#Mann=5,-1,0
  3537.9    0.05       0  4970.6   0.033       0  5001.7    0.05       0
  5293.0    0.12       0  5399.3    0.05       0
Bank Sta=4970.6,5001.7
Exp/Cntr=0.3,0.1

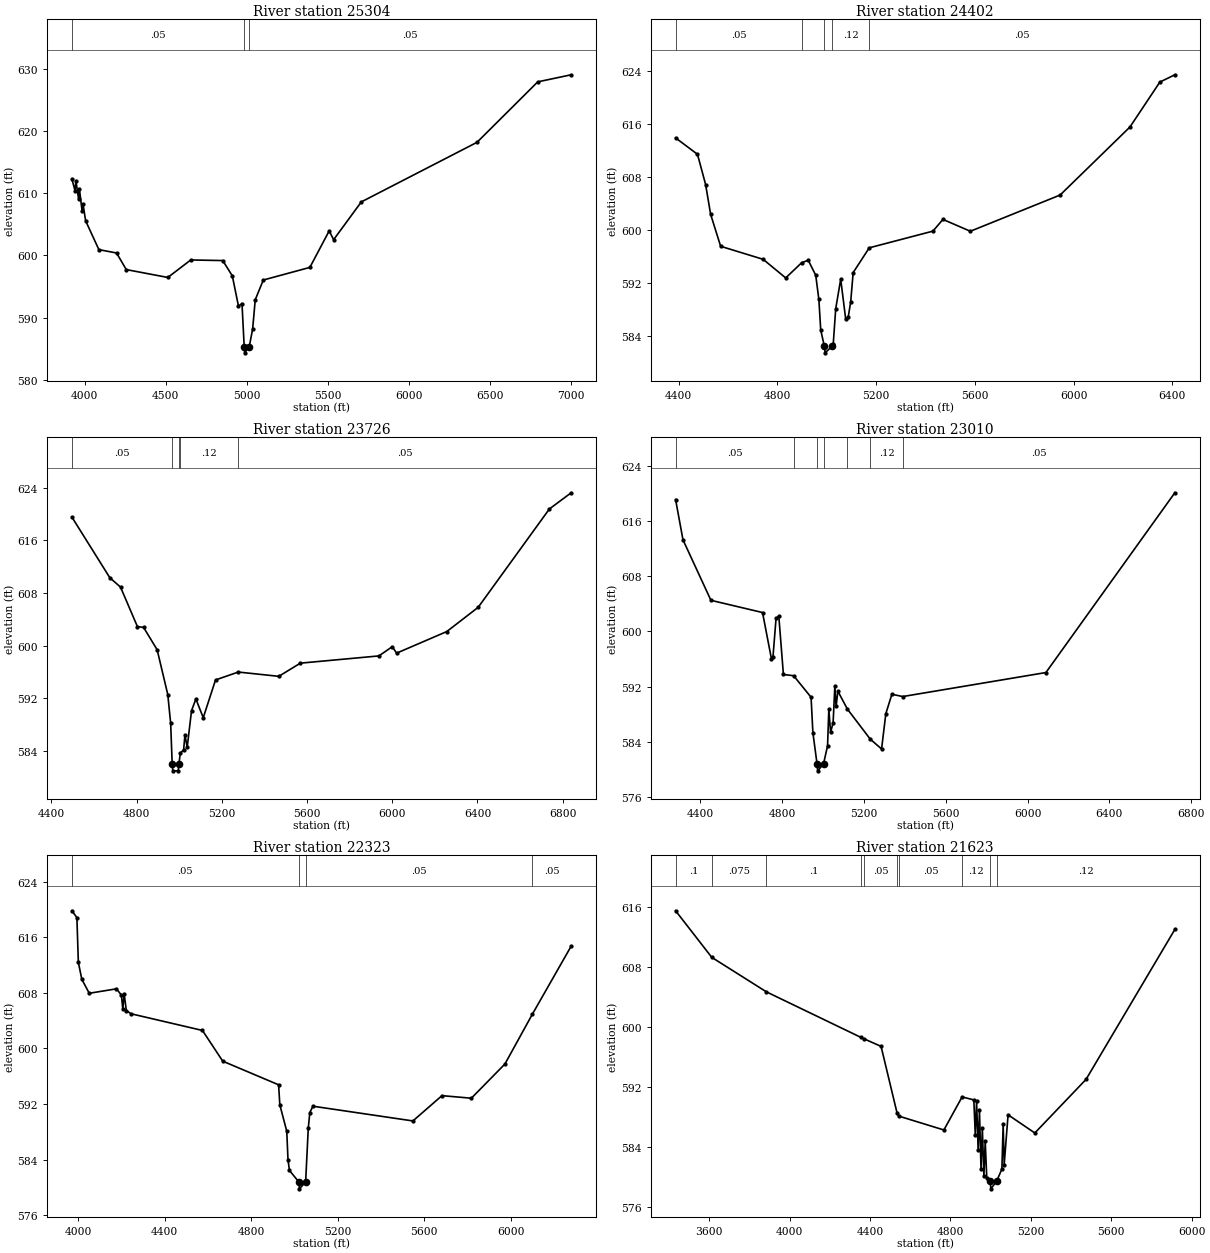
Type RM Length L Ch R = 1,25304,902,902,902
BEGIN DESCRIPTION:
Elizabeth Creek 22.0
END DESCRIPTION:
XS GIS Cut Line= 3
      2342484.91      7055558.26      2341930.16      7054537.01
      2341004.05      7052854.90
#Sta/Elev= 30
  3920.5  612.28  3939.5  610.44  3945.2  611.98  3961.3  609.14  3967.0  610.62
  3983.2  607.17  3988.9  608.28  4005.0  605.58  4086.8  600.94  4196.0  600.40
  4255.9  597.73  4512.5  596.46  4654.1  599.28  4851.7  599.18  4910.7  596.72
  4948.7  591.85  4970.5  592.26  4984.0  585.33  4987.1  584.33  5015.2  585.33
  5036.1  588.14  5052.3  592.88  5102.1  596.05  5389.5  598.08  5508.8  603.96
  5536.2  602.54  5707.1  608.62  6421.5  618.21  6796.5  627.94  7002.9  629.08
#Mann=3,-1,0
  3920.5    0.05       0  4984.0   0.033       0  5015.2    0.05       0
Bank Sta=4984,5015.2
Exp/Cntr=0.3,0.1

Type RM Length L Ch R = 1,24402,676,676,676
BEGIN DESCRIPTION:
Elizabeth Creek 21.0
END DESCRIPTION:
XS GIS Cut Line= 3
      2342579.00      7055609.98      2342679.00      7055010.00
      2342879.00      7053609.97
#Sta/Elev= 30
  4387.2  613.95  4475.9  611.47  4508.8  606.91  4529.1  602.41  4569.7  597.58
  4742.0  595.61  4833.3  592.80  4897.6  595.09  4924.5  595.48  4954.9  593.21
  4967.6  589.55  4975.2  584.93  4989.8  582.49  4992.9  581.49  5021.3  582.49
  5025.8  582.80  5035.9  588.16  5056.1  592.61  5076.3  586.60  5086.4  586.87
  5096.5  589.16  5106.6  593.61  5171.8  597.35  5429.8  599.87  5470.2  601.64
  5581.3  599.85  5945.0  605.32  6227.8  615.59  6349.1  622.38  6409.7  623.48
#Mann=5,-1,0
  4387.2    0.05       0  4897.6    0.12       0  4989.8    0.07       0
  5021.3    0.12       0  5171.8    0.05       0
Bank Sta=4989.8,5021.3
Exp/Cntr=0.3,0.1

Type RM Length L Ch R = 1,23726,716,716,716
BEGIN DESCRIPTION:
Elizabeth Creek 20.0
END DESCRIPTION:
XS GIS Cut Line= 3
      2342679.00      7055810.00      2343079.00      7055510.00
      2343479.00      7053710.01
#Sta/Elev= 30
  4496.0  619.51  4674.1  610.30  4724.1  608.89  4803.3  602.90  4832.5  602.76
  4896.0  599.38  4946.0  592.57  4959.5  588.20  4966.7  581.99  4969.8  580.99
  4995.1  580.99  4998.2  581.99  5004.7  583.67  5020.3  584.18  5026.7  586.48
  5037.0  584.54  5057.5  590.13  5077.9  591.90  5112.5  589.06  5170.1  594.79
  5276.9  595.99  5467.2  595.34  5568.4  597.34  5937.2  598.44  5999.9  599.84
  6020.4  598.86  6256.0  602.14  6403.3  605.82  6737.5  620.75  6839.9  623.21
#Mann=5,-1,0
  4496.0    0.05       0  4966.7   0.033       0  4998.2    0.05       0
  5004.7    0.12       0  5276.9    0.05       0
Bank Sta=4966.7,4998.2
Exp/Cntr=0.5,0.3

Type RM Length L Ch R = 1,23010,687,687,687
BEGIN DESCRIPTION:
Elizabeth Creek 19.0
END DESCRIPTION:
XS GIS Cut Line= 3
      2343329.00      7056310.00      2343729.00      7055710.00
      2345129.02      7054709.99
#Sta/Elev= 30
  4278.9  619.11  4315.0  613.27  4451.7  604.50  4704.1  602.73  4747.6  596.02
  4755.1  596.28  4770.2  601.87  4783.7  602.19  4806.2  593.75  4856.1  593.57
  4941.4  590.45  4950.4  585.31  4970.7  580.78  4973.8  579.78  5002.3  580.78
  5022.1  583.41  5028.3  588.69  5036.9  585.37  5049.2  586.75  5057.8  592.04
  5063.9  589.11  5072.5  591.33  5118.9  588.74  5231.1  584.37  5286.3  582.95
  5307.2  588.08  5336.7  590.88  5389.8  590.55  6090.0  594.03  6720.5  620.09
#Mann=7,-1,0
  4278.9    0.05       0  4856.1    0.12       0  4970.7    0.07       0
  5002.3    0.12       0  5118.9    0.05       0  5231.1    0.12       0
  5389.8    0.05       0
Bank Sta=4970.7,5002.3
Exp/Cntr=0.3,0.1

Type RM Length L Ch R = 1,22323,700,700,700
BEGIN DESCRIPTION:
Elizabeth Creek 18.0
END DESCRIPTION:
XS GIS Cut Line= 3
      2343429.02      7056459.99      2344329.00      7055960.00
      2345129.02      7054959.98
#Sta/Elev= 30
  3970.5  619.80  3993.4  618.82  4000.2  612.37  4016.2  609.94  4050.6  607.93
  4176.4  608.57  4199.3  607.67  4206.1  605.60  4211.9  607.89  4222.2  605.45
  4243.9  604.98  4574.5  602.58  4668.3  598.16  4926.8  594.76  4932.5  591.88
  4964.6  588.07  4970.3  583.97  4977.2  582.43  5020.3  580.79  5023.4  579.79
  5051.9  580.79  5064.1  588.50  5071.3  590.77  5085.7  591.68  5548.3  589.56
  5682.8  593.20  5818.8  592.83  5974.1  597.75  6100.9  604.91  6280.7  614.71
#Mann=4,-1,0
  3970.5    0.05       0  5020.3   0.033       0  5051.9    0.05       0
  6100.9    0.05       0
Bank Sta=5020.3,5051.9
Exp/Cntr=0.3,0.1

Type RM Length L Ch R = 1,21623,652,652,652
BEGIN DESCRIPTION:
Elizabeth Creek 17.0
END DESCRIPTION:
XS GIS Cut Line= 3
      2343979.03      7057159.96      2344979.00      7055960.00
      2345179.01      7055059.96
#Sta/Elev= 30
  3432.3  615.46  3612.4  609.26  3884.5  604.67  4354.2  598.62  4369.7  598.43
  4454.7  597.42  4533.9  588.59  4542.3  588.15  4767.2  586.30  4857.8  590.70
  4916.2  590.30  4923.4  585.64  4929.9  590.13  4937.7  583.65  4944.2  588.94
  4952.0  581.09  4958.5  586.55  4966.3  580.13  4972.8  584.82  4980.6  579.90
  4997.7  579.47  5000.8  578.47  5029.4  579.47  5055.8  581.10  5062.2  587.09
  5067.3  581.69  5086.5  588.32  5219.7  585.90  5474.5  593.03  5916.3  612.97
#Mann=10,-1,0
  3432.3     0.1       0  3612.4   0.075       0  3884.5     0.1       0
  4354.2   0.075       0  4369.7    0.05       0  4533.9     0.1       0
  4542.3    0.05       0  4857.8    0.12       0  4997.7    0.07       0
  5029.4    0.12       0
Bank Sta=4997.7,5029.4
Exp/Cntr=0.3,0.1

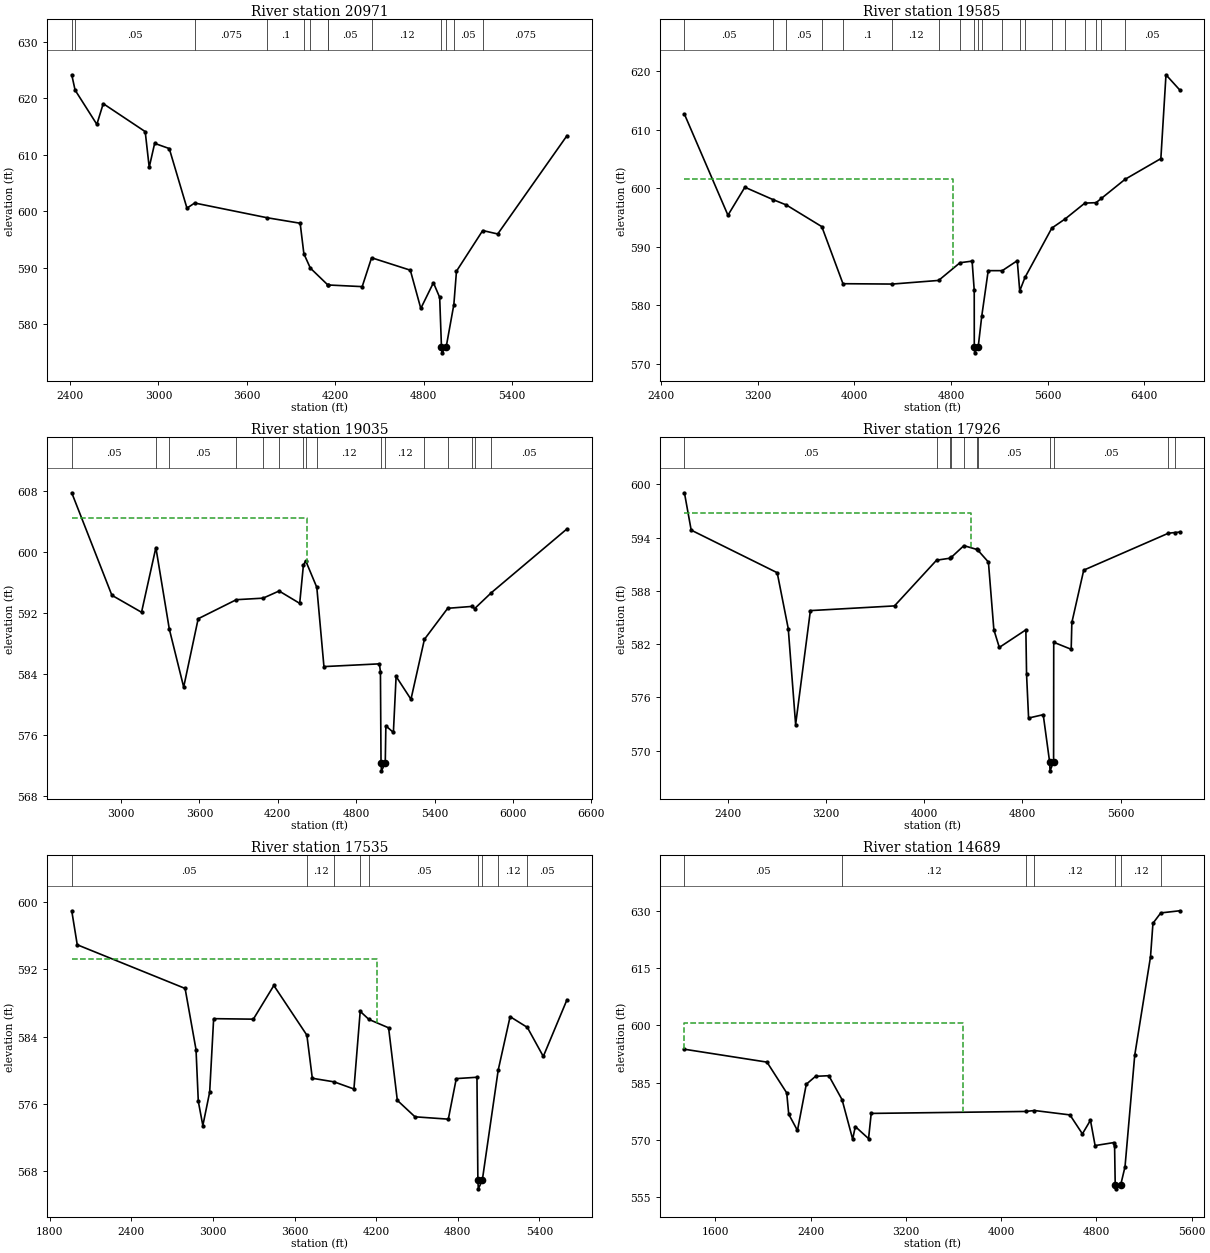
Type RM Length L Ch R = 1,20971,1386,1386,1386
BEGIN DESCRIPTION:
Elizabeth Creek 16.0
END DESCRIPTION:
XS GIS Cut Line= 3
      2343879.01      7057809.99      2345479.00      7055810.00
      2345479.00      7055010.04
#Sta/Elev= 30
  2411.6  624.15  2434.3  621.44  2582.1  615.37  2625.3  619.04  2910.2  614.09
  2937.4  607.77  2974.3  612.01  3073.5  611.09  3193.6  600.54  3245.9  601.45
  3738.6  598.84  3961.9  597.87  3987.1  592.47  4031.0  589.93  4150.8  586.92
  4153.9  586.94  4382.9  586.65  4446.6  591.76  4709.5  589.56  4780.7  582.79
  4866.4  587.34  4908.8  584.74  4921.0  575.93  4924.1  574.93  4952.7  575.93
  5005.0  583.47  5022.8  589.38  5201.0  596.58  5302.8  595.97  5772.8  613.37
#Mann=13,-1,0
  2411.6   0.075       0  2434.3    0.05       0  3245.9   0.075       0
  3738.6     0.1       0  3987.1   0.075       0  4031.0    0.05       0
  4150.8    0.12       0  4153.9    0.05       0  4446.6    0.12       0
  4921.0    0.07       0  4952.7    0.12       0  5005.0    0.05       0
  5201.0   0.075       0
Bank Sta=4921,4952.7
Exp/Cntr=0.3,0.1

Type RM Length L Ch R = 1,19585,550,550,550
BEGIN DESCRIPTION:
Elizabeth Creek 15.0
END DESCRIPTION:
XS GIS Cut Line= 3
      2346629.00      7058410.01      2346629.00      7056010.00
      2345428.98      7054809.98
#Sta/Elev= 30
  2595.4  612.64  2955.4  595.38  3095.4  600.16  3329.0  598.04  3438.4  597.13
  3731.9  593.43  3907.0  583.68  4315.2  583.62  4698.3  584.24  4874.8  587.26
  4975.4  587.54  4992.9  582.55  4993.4  572.87  4996.7  571.87  5025.7  572.87
  5055.1  578.13  5108.5  585.91  5224.9  585.91  5349.0  587.61  5369.3  582.44
  5412.6  584.74  5634.8  593.18  5746.7  594.77  5908.1  597.45  6000.5  597.52
  6044.8  598.25  6240.6  601.51  6536.9  605.05  6579.3  619.37  6692.5  616.79
#Mann=20,-1,0
  2595.4    0.05       0  3329.0    0.12       0  3438.4    0.05       0
  3731.9    0.12       0  3907.0     0.1       0  4315.2    0.12       0
  4698.3    0.05       0  4874.8    0.12       0  4993.4    0.07       0
  5025.7    0.12       0  5055.1    0.12       0  5224.9     0.1       0
  5369.3    0.12       0  5412.6    0.05       0  5634.8   0.075       0
  5746.7   0.075       0  5908.1    0.05       0  6000.5   0.075       0
  6044.8    0.05       0  6240.6    0.05       0
#XS Ineff=2,0
    0.00 4818.90  601.51               0
Permanent Ineff=
       F       F
Bank Sta=4993.4,5025.7
Exp/Cntr=0.3,0.1

Type RM Length L Ch R = 1,19035,1109,1109,1109
BEGIN DESCRIPTION:
Elizabeth Creek 14.5
END DESCRIPTION:
XS GIS Cut Line= 3
      2347654.01      7057815.02      2347048.84      7055734.73
      2346033.95      7054467.70
#Sta/Elev= 30
  2623.0  607.78  2930.2  594.33  3157.1  592.10  3266.9  600.59  3369.6  589.90
  3479.6  582.28  3590.6  591.25  3882.7  593.75  4087.0  593.95  4209.9  594.89
  4367.5  593.27  4395.8  598.27  4413.3  598.86  4498.4  595.37  4553.0  584.97
  4977.3  585.33  4985.3  584.32  4989.9  572.29  4993.2  571.29  5022.2  572.29
  5026.9  577.19  5084.5  576.33  5105.3  583.68  5219.0  580.68  5322.0  588.55
  5500.1  592.62  5687.8  592.87  5705.6  592.57  5834.4  594.67  6412.9  603.04
#Mann=16,-1,0
  2623.0    0.05       0  3266.9    0.12       0  3369.6    0.05       0
  3882.7   0.075       0  4087.0    0.05       0  4209.9   0.075       0
  4395.8    0.05       0  4413.3     0.1       0  4498.4    0.12       0
  4989.9    0.07       0  5022.2    0.12       0  5322.0    0.05       0
  5500.1   0.075       0  5687.8    0.05       0  5705.6   0.075       0
  5834.4    0.05       0
#XS Ineff=2,0
    0.00 4420.80  604.42               0
Permanent Ineff=
       F       F
Bank Sta=4989.9,5022.2
Exp/Cntr=0.3,0.1

Type RM Length L Ch R = 1,17926,391,391,391
BEGIN DESCRIPTION:
Elizabeth Creek 14.2
END DESCRIPTION:
XS GIS Cut Line= 6
      2348309.60      7057524.96      2348372.63      7056175.99
      2347937.67      7055684.30      2347572.05      7054971.97
      2347256.86      7054303.77      2346878.74      7053994.97
#Sta/Elev= 30
  2047.2  599.06  2102.2  594.85  2803.0  590.05  2893.1  583.74  2953.1  572.94
  3073.3  585.78  3758.6  586.31  4101.1  591.46  4212.4  591.69  4220.9  591.78
  4323.8  593.10  4427.7  592.68  4435.2  592.63  4523.7  591.25  4568.1  583.62
  4612.5  581.63  4828.8  583.61  4834.5  578.58  4851.0  573.67  4970.2  574.05
  5022.4  568.72  5025.7  567.72  5054.7  568.72  5055.8  582.21  5198.0  581.42
  5203.5  584.44  5300.2  590.34  5989.6  594.50  6042.6  594.58  6081.8  594.63
#Mann=11,-1,0
  2047.2    0.05       0  4101.1   0.075       0  4212.4    0.05       0
  4220.9   0.075       0  4323.8    0.05       0  4427.7   0.075       0
  4435.2    0.05       0  5022.4    0.05       0  5054.7    0.05       0
  5989.6   0.075       0  6042.6    0.05       0
#XS Ineff=2,0
    0.00 4381.50  596.75               0
Permanent Ineff=
       F       F
Bank Sta=5022.4,5054.7
Exp/Cntr=0.3,0.1

Type RM Length L Ch R = 1,17535,2846,2846,2846
BEGIN DESCRIPTION:
Elizabeth Creek 14.0
END DESCRIPTION:
XS GIS Cut Line= 5
      2348373.08      7057560.39      2348523.92      7055829.28
      2348170.16      7055613.68      2347899.85      7054959.36
      2347584.28      7054244.42
#Sta/Elev= 30
  1962.0  598.99  2002.5  594.94  2795.5  589.74  2875.8  582.45  2892.6  576.29
  2926.0  573.41  2976.2  577.39  3005.4  586.14  3297.4  586.08  3448.0  590.09
  3691.0  584.17  3730.9  579.04  3891.9  578.61  4036.9  577.76  4083.0  587.01
  4147.1  586.05  4291.8  585.05  4356.0  576.41  4485.8  574.45  4730.9  574.17
  4789.5  579.00  4941.5  579.16  4948.3  566.87  4951.6  565.87  4980.6  566.87
  5097.7  580.01  5185.2  586.38  5311.9  585.10  5429.3  581.64  5603.4  588.39
#Mann=9,-1,0
  1962.0    0.05       0  3691.0    0.12       0  3891.9    0.05       0
  4083.0    0.12       0  4147.1    0.05       0  4948.3    0.05       0
  4980.6    0.05       0  5097.7    0.12       0  5311.9    0.05       0
#XS Ineff=2,0
    0.00 4205.60  593.29               0
Permanent Ineff=
       F       F
Bank Sta=4948.3,4980.6
Exp/Cntr=0.3,0.1

Type RM Length L Ch R = 1,14689,737,737,737
BEGIN DESCRIPTION:
Elizabeth Creek 13.0
END DESCRIPTION:
XS GIS Cut Line= 4
      2348465.23      7057456.77      2348532.64      7056766.81
      2349829.00      7054110.00      2349929.01      7053609.96
#Sta/Elev= 30
  1340.1  593.75  2033.4  590.38  2199.2  582.33  2216.1  576.75  2289.3  572.51
  2363.6  584.60  2441.4  586.67  2552.8  586.83  2664.2  580.55  2753.0  570.24
  2775.3  573.53  2886.6  570.38  2908.8  576.97  4205.6  577.48  4279.8  577.73
  4577.9  576.58  4682.6  571.62  4750.2  575.18  4789.3  568.56  4945.1  569.34
  4953.0  568.32  4958.2  558.25  4962.6  557.25  5004.0  558.25  5040.5  563.02
  5122.1  592.18  5254.7  617.94  5275.1  626.68  5340.9  629.39  5499.5  629.95
#Mann=7,-1,0
  1340.1    0.05       0  2664.2    0.12       0  4205.6    0.05       0
  4279.8    0.12       0  4958.2    0.07       0  5004.0    0.12       0
  5340.9    0.05       0
#XS Ineff=2,0
    0.00 3675.60  600.48               0
Permanent Ineff=
       F       F
Bank Sta=4958.2,5004
Exp/Cntr=0.3,0.1

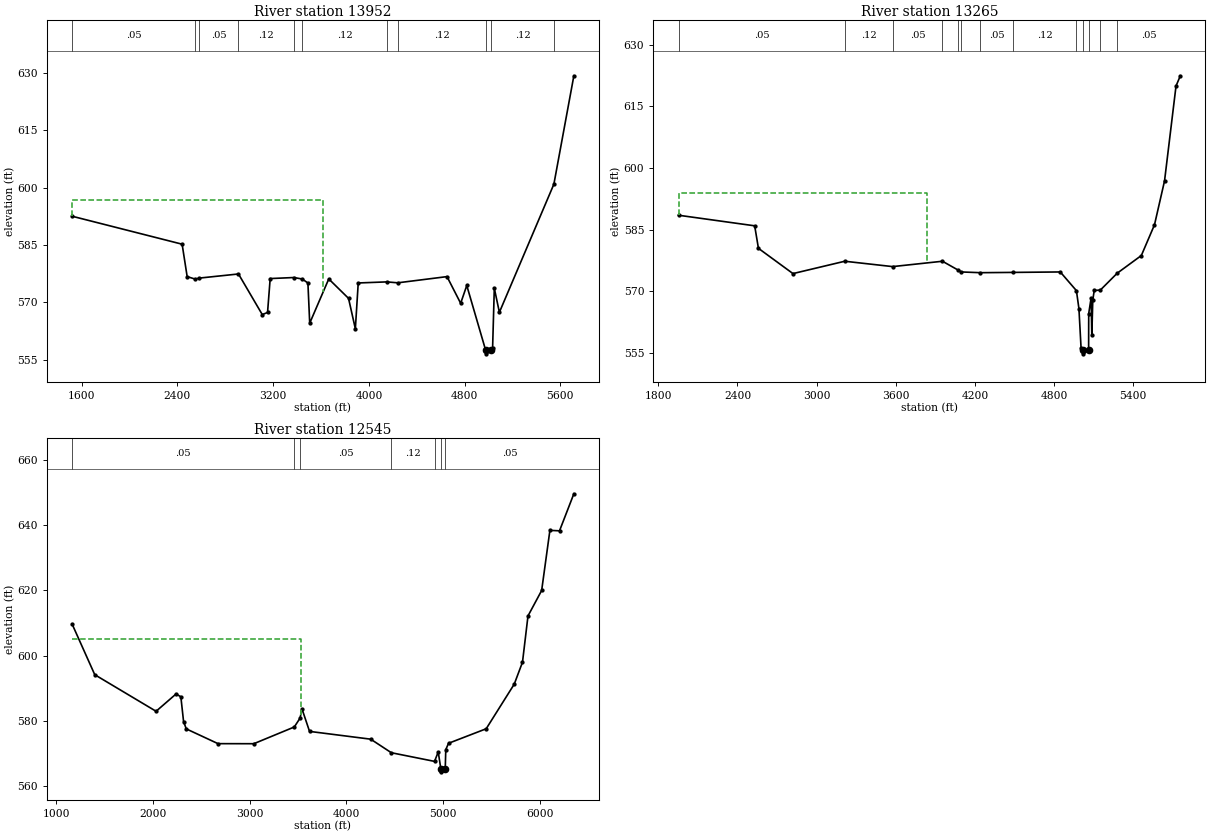
Type RM Length L Ch R = 1,13952,687,687,687
BEGIN DESCRIPTION:
Elizabeth Creek 12.0
END DESCRIPTION:
XS GIS Cut Line= 4
      2348556.70      7057353.87      2348607.75      7057059.78
      2350379.00      7054410.00      2350879.03      7053909.97
#Sta/Elev= 30
  1519.9  592.50  2439.5  585.19  2481.6  576.72  2548.9  576.07  2582.0  576.33
  2910.4  577.41  3109.2  566.80  3153.3  567.35  3175.3  576.21  3373.3  576.48
  3443.5  576.09  3490.6  575.05  3505.6  564.55  3664.8  576.11  3830.0  571.04
  3887.0  563.09  3911.0  575.06  4149.1  575.34  4241.4  575.10  4652.8  576.72
  4766.9  569.75  4818.0  574.40  4975.2  557.54  4979.6  556.54  5021.0  557.54
  5033.9  558.15  5048.1  573.68  5090.5  567.39  5545.9  600.88  5712.8  629.20
#Mann=11,-1,0
  1519.9    0.05       0  2548.9    0.12       0  2582.0    0.05       0
  2910.4    0.12       0  3373.3    0.05       0  3443.5    0.12       0
  4149.1    0.05       0  4241.4    0.12       0  4975.2    0.07       0
  5021.0    0.12       0  5545.9    0.05       0
#XS Ineff=2,0
    0.00 3616.40  596.84               0
Permanent Ineff=
       F       F
Bank Sta=4975.2,5021
Exp/Cntr=0.3,0.1

Type RM Length L Ch R = 1,13265,720,720,720
BEGIN DESCRIPTION:
Elizabeth Creek 11.0
END DESCRIPTION:
XS GIS Cut Line= 3
      2348708.03      7057183.59      2350729.00      7054910.00
      2351028.98      7054210.04
#Sta/Elev= 30
  1953.5  588.51  2530.7  585.94  2559.1  580.47  2820.9  574.33  3213.5  577.33
  3576.2  576.03  3954.0  577.33  4073.0  575.18  4096.5  574.73  4242.0  574.55
  4491.7  574.62  4847.0  574.73  4969.3  570.19  4988.4  565.84  5004.5  556.31
  5016.1  555.83  5020.5  554.83  5061.9  555.83  5062.6  564.62  5080.7  568.39
  5086.1  559.29  5093.4  567.87  5104.3  570.23  5150.9  570.33  5278.8  574.43
  5461.5  578.72  5561.2  586.19  5637.4  596.87  5724.4  619.92  5757.0  622.40
#Mann=13,-1,0
  1953.5    0.05       0  3213.5    0.12       0  3576.2    0.05       0
  3954.0    0.12       0  4073.0    0.05       0  4096.5    0.12       0
  4242.0    0.05       0  4491.7    0.12       0  4969.3     0.1       0
  5016.1    0.07       0  5061.9     0.1       0  5150.9    0.12       0
  5278.8    0.05       0
#XS Ineff=2,0
    0.00 3835.80  593.85               0
Permanent Ineff=
       F       F
Bank Sta=5016.1,5061.9
Exp/Cntr=0.3,0.1

Type RM Length L Ch R = 1,12545,1092,1092,1092
BEGIN DESCRIPTION:
Elizabeth Creek 10.0
END DESCRIPTION:
XS GIS Cut Line= 3
      2348328.99      7057660.01      2351329.00      7055260.00
      2352228.97      7054260.04
#Sta/Elev= 30
  1163.2  609.75  1397.7  594.22  2031.6  583.02  2238.1  588.32  2287.8  587.45
  2315.8  579.88  2343.8  577.63  2671.9  573.11  3041.7  573.09  3460.2  578.21
  3520.0  580.92  3539.6  583.79  3618.0  576.86  4250.3  574.48  4463.7  570.33
  4910.4  567.68  4948.3  570.57  4974.9  565.48  4979.3  564.48  5020.9  565.48
  5026.4  571.28  5054.8  573.22  5444.2  577.67  5734.2  591.33  5819.4  598.05
  5876.2  612.21  6017.5  620.00  6102.7  638.41  6202.1  638.27  6350.4  649.61
#Mann=7,-1,0
  1163.2    0.05       0  3460.2   0.075       0  3520.0    0.05       0
  4463.7    0.12       0  4910.4    0.05       0  4974.9   0.033       0
  5020.9    0.05       0
#XS Ineff=2,0
    0.00 3526.40  605.18               0
Permanent Ineff=
       F       F
Bank Sta=4974.9,5020.9
Exp/Cntr=0.3,0.1