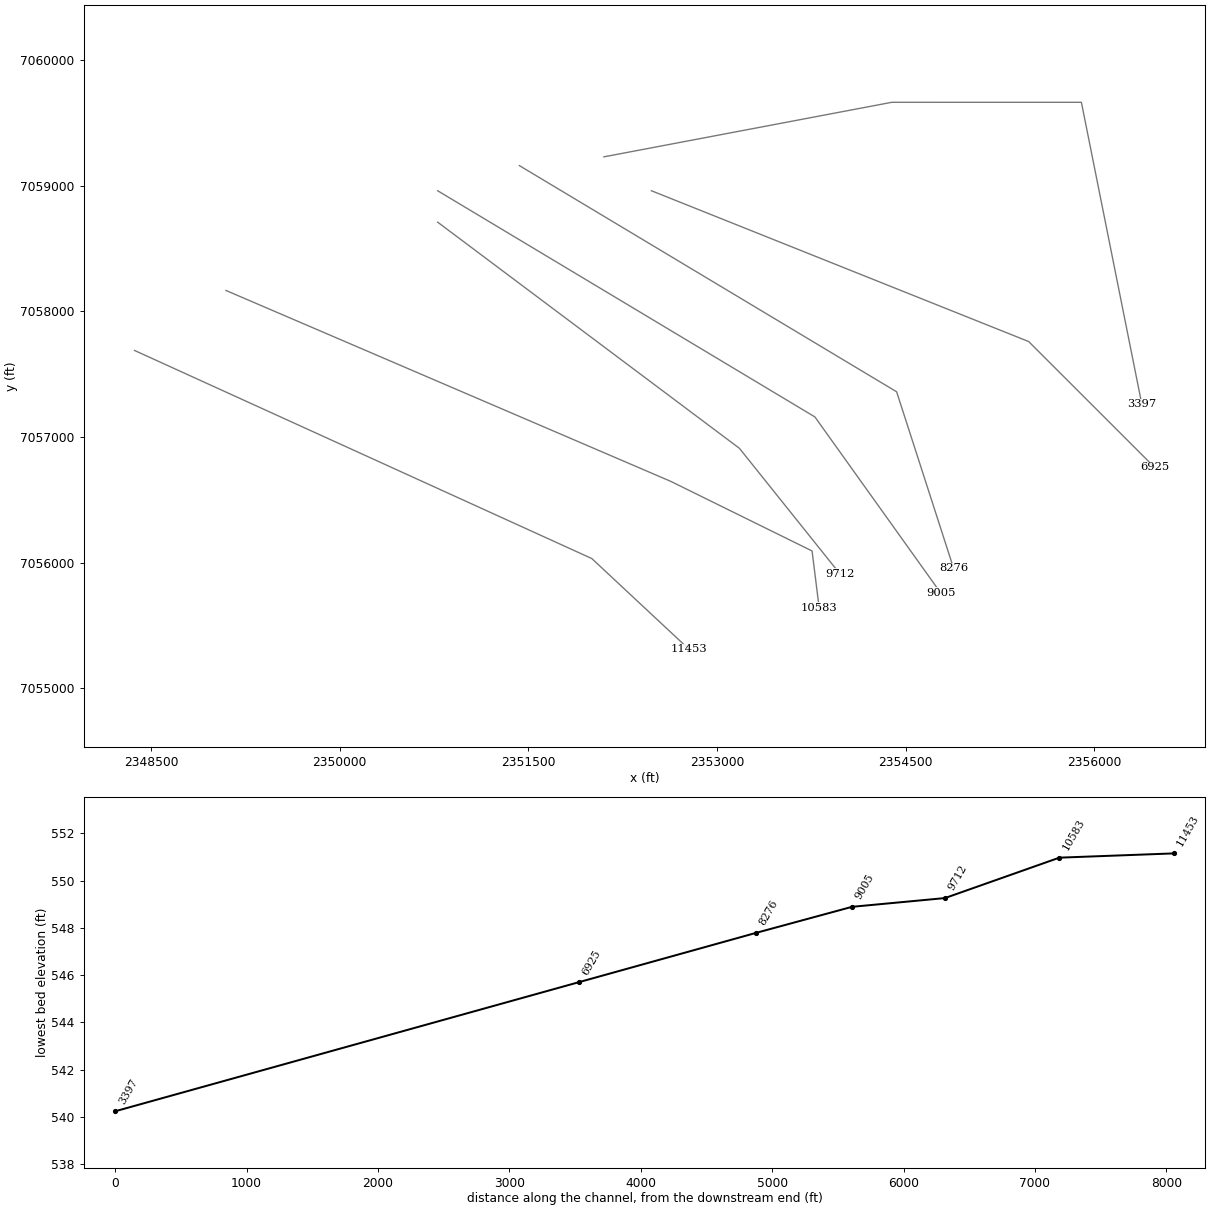
HEC-RAS study Elizabeth Creek.prj: Elizabeth Creek Base Level Engineering

--- Elizabeth Creek.g01 (geometry) --- (continued)

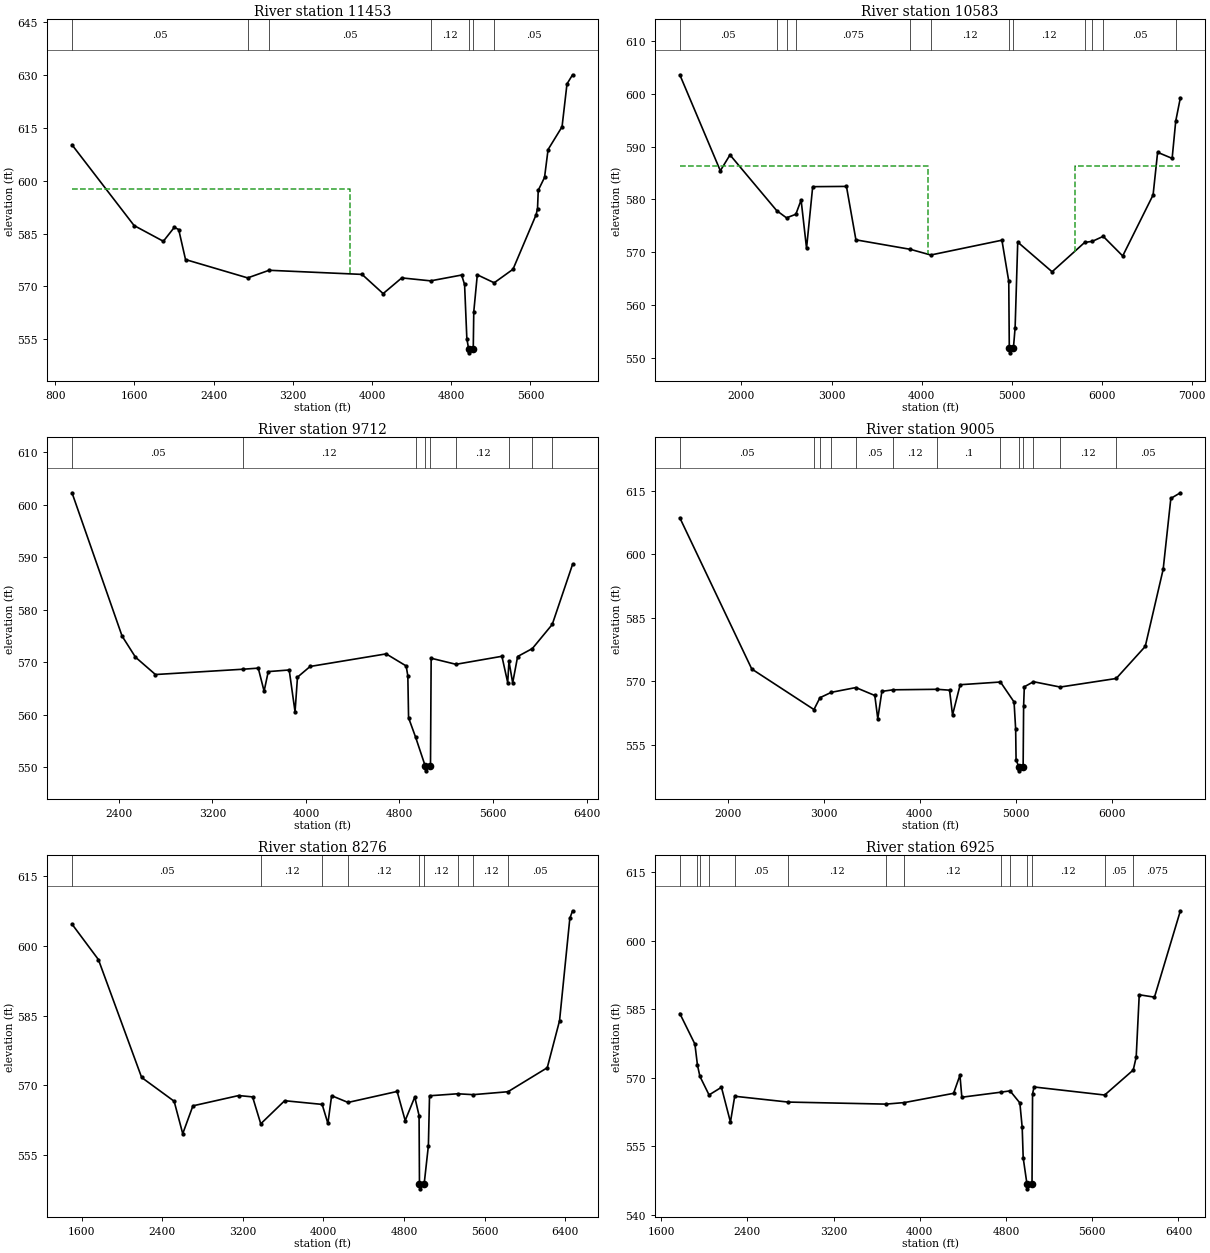
Type RM Length L Ch R = 1,11453,870,870,870
BEGIN DESCRIPTION:
Elizabeth Creek 9.0
END DESCRIPTION:
XS GIS Cut Line= 3
      2348368.40      7057689.07      2352005.21      7056032.84
      2352779.02      7055309.98
#Sta/Elev= 30
   970.8  610.16  1597.8  587.26  1893.2  582.80  2004.3  586.76  2048.3  586.12
  2117.2  577.61  2744.7  572.41  2960.9  574.57  3900.0  573.40  4112.9  567.95
  4300.9  572.41  4592.1  571.57  4905.2  573.22  4935.2  570.55  4958.2  555.17
  4976.8  552.15  4981.2  551.15  5022.8  552.15  5028.1  562.79  5063.7  573.29
  5234.3  571.02  5424.3  574.86  5657.8  590.34  5671.9  592.09  5679.3  597.27
  5742.8  600.91  5778.4  608.82  5919.6  615.28  5969.5  627.44  6025.9  630.03
#Mann=7,-1,0
   970.8    0.05       0  2744.7    0.12       0  2960.9    0.05       0
  4592.1    0.12       0  4976.8    0.07       0  5022.8    0.12       0
  5234.3    0.05       0
#XS Ineff=2,0
    0.00 3774.70  597.49               0
Permanent Ineff=
       F       F
Bank Sta=4976.8,5022.8
Exp/Cntr=0.3,0.1

Type RM Length L Ch R = 1,10583,871,871,871
BEGIN DESCRIPTION:
Elizabeth Creek 8.0
END DESCRIPTION:
XS GIS Cut Line= 4
      2349095.46      7058166.48      2352632.74      7056647.39
      2353756.53      7056093.40      2353813.07      7055639.10
#Sta/Elev= 30
  1315.0  603.58  1765.1  585.42  1872.4  588.42  2391.2  577.88  2500.2  576.51
  2603.9  577.19  2662.4  579.88  2722.8  570.76  2791.1  582.41  3166.1  582.46
  3271.2  572.35  3877.0  570.55  4102.4  569.48  4893.0  572.28  4969.1  564.51
  4974.9  551.97  4979.2  550.97  5021.3  551.97  5039.7  555.76  5068.7  571.92
  5450.4  566.31  5811.6  571.85  5897.7  572.07  6018.2  573.01  6234.7  569.30
  6572.2  580.84  6622.6  588.91  6783.8  587.76  6823.8  594.82  6875.4  599.24
#Mann=12,-1,0
  1315.0    0.05       0  2391.2   0.075       0  2500.2    0.05       0
  2603.9   0.075       0  3877.0    0.05       0  4102.4    0.12       0
  4974.9    0.07       0  5021.3    0.12       0  5811.6    0.05       0
  5897.7    0.12       0  6018.2    0.05       0  6823.8   0.075       0
#XS Ineff=2,0
    0.00 4066.70  586.28 5700.00    0.00  586.28
Permanent Ineff=
       F       F
Bank Sta=4974.9,5021.3
Exp/Cntr=0.3,0.1

Type RM Length L Ch R = 1,9712,707,707,707
BEGIN DESCRIPTION:
Elizabeth Creek 7.0
END DESCRIPTION:
XS GIS Cut Line= 3
      2350779.03      7058709.98      2353179.00      7056910.00
      2353979.00      7055909.99
#Sta/Elev= 30
  2000.0  602.30  2428.1  574.97  2542.7  570.94  2713.5  567.63  3460.1  568.64
  3592.7  568.85  3642.7  564.45  3678.1  568.19  3857.3  568.50  3907.3  560.51
  3928.1  567.13  4036.4  569.17  4686.4  571.57  4857.3  569.27  4871.8  567.37
  4878.1  559.38  4937.6  555.72  5019.2  550.26  5023.5  549.26  5065.6  550.26
  5071.2  570.74  5283.3  569.58  5676.3  571.11  5725.9  566.09  5736.6  570.17
  5768.3  566.04  5810.8  571.07  5936.3  572.58  6106.6  577.18  6280.6  588.65
#Mann=9,-1,0
  2000.0    0.05       0  3460.1    0.12       0  4937.6     0.1       0
  5019.2    0.07       0  5065.6     0.1       0  5283.3    0.12       0
  5736.6    0.05       0  5936.3    0.12       0  6106.6    0.05       0
Bank Sta=5019.2,5065.6
Exp/Cntr=0.3,0.1

Type RM Length L Ch R = 1,9005,729,729,729
BEGIN DESCRIPTION:
Elizabeth Creek 6.0
END DESCRIPTION:
XS GIS Cut Line= 3
      2350779.02      7058959.99      2353779.00      7057160.00
      2354778.99      7055760.01
#Sta/Elev= 30
  1497.2  608.60  2247.4  572.92  2895.8  563.35  2958.6  566.15  3077.7  567.42
  3332.9  568.54  3530.2  566.67  3561.3  561.20  3604.1  567.64  3721.1  568.01
  4180.6  568.13  4309.6  567.92  4340.7  562.08  4420.4  569.21  4840.3  569.85
  4982.1  565.14  4998.8  558.74  5003.1  551.53  5030.3  549.89  5034.7  548.89
  5076.7  549.89  5081.8  564.25  5089.1  568.72  5184.8  569.92  5463.1  568.66
  6046.9  570.68  6350.0  578.25  6536.8  596.45  6616.7  613.17  6716.2  614.50
#Mann=13,-1,0
  1497.2    0.05       0  2895.8    0.12       0  2958.6    0.05       0
  3077.7    0.12       0  3332.9    0.05       0  3721.1    0.12       0
  4180.6     0.1       0  4840.3    0.12       0  5030.3    0.07       0
  5076.7    0.12       0  5184.8     0.1       0  5463.1    0.12       0
  6046.9    0.05       0
Bank Sta=5030.3,5076.7
Exp/Cntr=0.3,0.1

Type RM Length L Ch R = 1,8276,1351,1351,1351
BEGIN DESCRIPTION:
Elizabeth Creek 5.0
END DESCRIPTION:
XS GIS Cut Line= 3
      2351429.01      7059159.99      2354429.00      7057360.00
      2354881.54      7055956.62
#Sta/Elev= 30
  1501.7  604.62  1764.1  597.01  2193.6  571.70  2516.3  566.60  2601.8  559.63
  2702.9  565.61  3157.7  567.82  3295.7  567.53  3376.8  561.75  3614.4  566.71
  3986.8  565.92  4044.0  561.83  4080.9  567.79  4243.9  566.34  4732.0  568.70
  4811.7  562.45  4907.0  567.50  4949.7  563.52  4953.7  548.79  4958.1  547.79
  5000.1  548.79  5042.3  557.06  5053.6  567.77  5332.6  568.20  5487.3  568.01
  5833.1  568.64  6223.2  573.79  6345.2  583.87  6447.6  605.88  6474.8  607.49
#Mann=9,-1,0
  1501.7    0.05       0  3376.8    0.12       0  3986.8     0.1       0
  4243.9    0.12       0  4953.7    0.07       0  5000.1    0.12       0
  5332.6     0.1       0  5487.3    0.12       0  5833.1    0.05       0
Bank Sta=4953.7,5000.1
Exp/Cntr=0.3,0.1

Type RM Length L Ch R = 1,6925,3528,3528,3528
BEGIN DESCRIPTION:
Elizabeth Creek 4.0
END DESCRIPTION:
XS GIS Cut Line= 3
      2352479.00      7058960.00      2355479.00      7057760.00
      2356478.99      7056760.01
#Sta/Elev= 30
  1772.7  584.07  1912.7  577.38  1936.3  572.80  1959.0  570.33  2044.1  566.25
  2159.1  567.92  2242.6  560.31  2282.2  565.96  2777.0  564.69  3685.5  564.24
  3857.3  564.58  4313.2  566.60  4372.4  570.56  4389.9  565.75  4752.6  566.85
  4837.4  567.14  4928.4  564.50  4950.0  559.14  4959.4  552.46  4994.7  546.70
  4999.0  545.70  5041.2  546.70  5046.2  566.50  5060.4  567.99  5715.5  566.23
  5980.5  571.70  6007.9  574.52  6036.2  588.17  6177.6  587.65  6418.0  606.55
#Mann=14,-1,0
  1772.7    0.05       0  1936.3    0.12       0  1959.0    0.05       0
  2044.1    0.12       0  2282.2    0.05       0  2777.0    0.12       0
  3685.5    0.05       0  3857.3    0.12       0  4752.6     0.1       0
  4837.4    0.12       0  4994.7    0.07       0  5041.2    0.12       0
  5715.5    0.05       0  5980.5   0.075       0
Bank Sta=4994.7,5041.2
Exp/Cntr=0.3,0.1

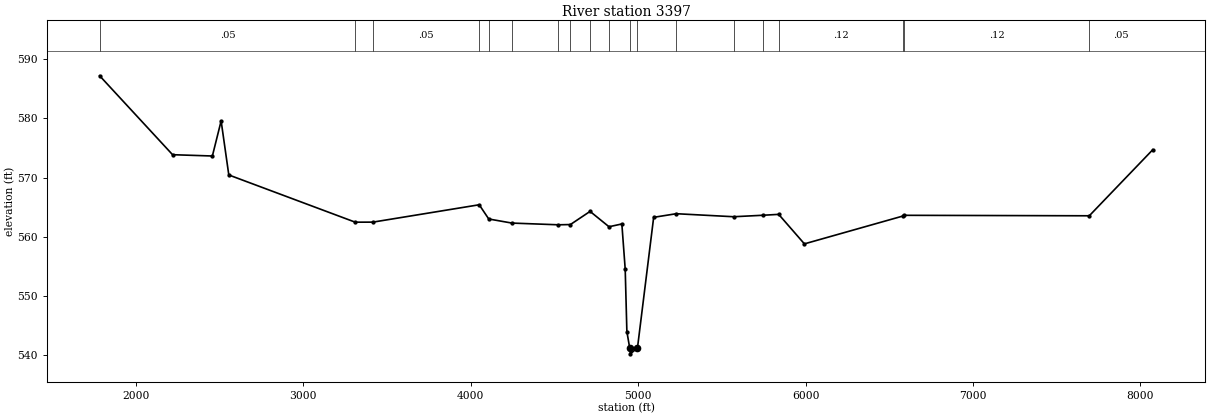
Type RM Length L Ch R = 1,3397,0,0,0
BEGIN DESCRIPTION:
Elizabeth Creek 3.0
END DESCRIPTION:
XS GIS Cut Line= 4
      2352101.05      7059229.86      2354390.56      7059663.89
      2355898.24      7059663.78      2356378.99      7057260.05
#Sta/Elev= 30
  1784.2  587.17  2219.8  573.85  2457.5  573.63  2509.8  579.55  2555.6  570.43
  3310.8  562.46  3416.3  562.47  4051.1  565.40  4108.0  563.00  4246.2  562.31
  4523.2  562.02  4595.6  562.06  4713.1  564.28  4826.2  561.69  4902.9  562.16
  4922.9  554.54  4932.9  544.00  4949.7  541.24  4954.0  540.24  4996.2  541.24
  5092.9  563.28  5228.0  563.89  5570.6  563.38  5745.9  563.63  5839.5  563.78
  5993.1  558.80  6581.4  563.50  6589.9  563.62  7694.5  563.54  8073.5  574.69
#Mann=19,-1,0
  1784.2    0.05       0  3310.8    0.12       0  3416.3    0.05       0
  4051.1    0.12       0  4108.0    0.05       0  4246.2    0.12       0
  4523.2    0.05       0  4595.6    0.12       0  4713.1    0.05       0
  4826.2    0.12       0  4949.7    0.07       0  4996.2    0.12       0
  5228.0     0.1       0  5570.6    0.12       0  5745.9     0.1       0
  5839.5    0.12       0  6581.4     0.1       0  6589.9    0.12       0
  7694.5    0.05       0
Bank Sta=4949.7,4996.2
Exp/Cntr=0.3,0.1

Chan Stop Cuts=-1