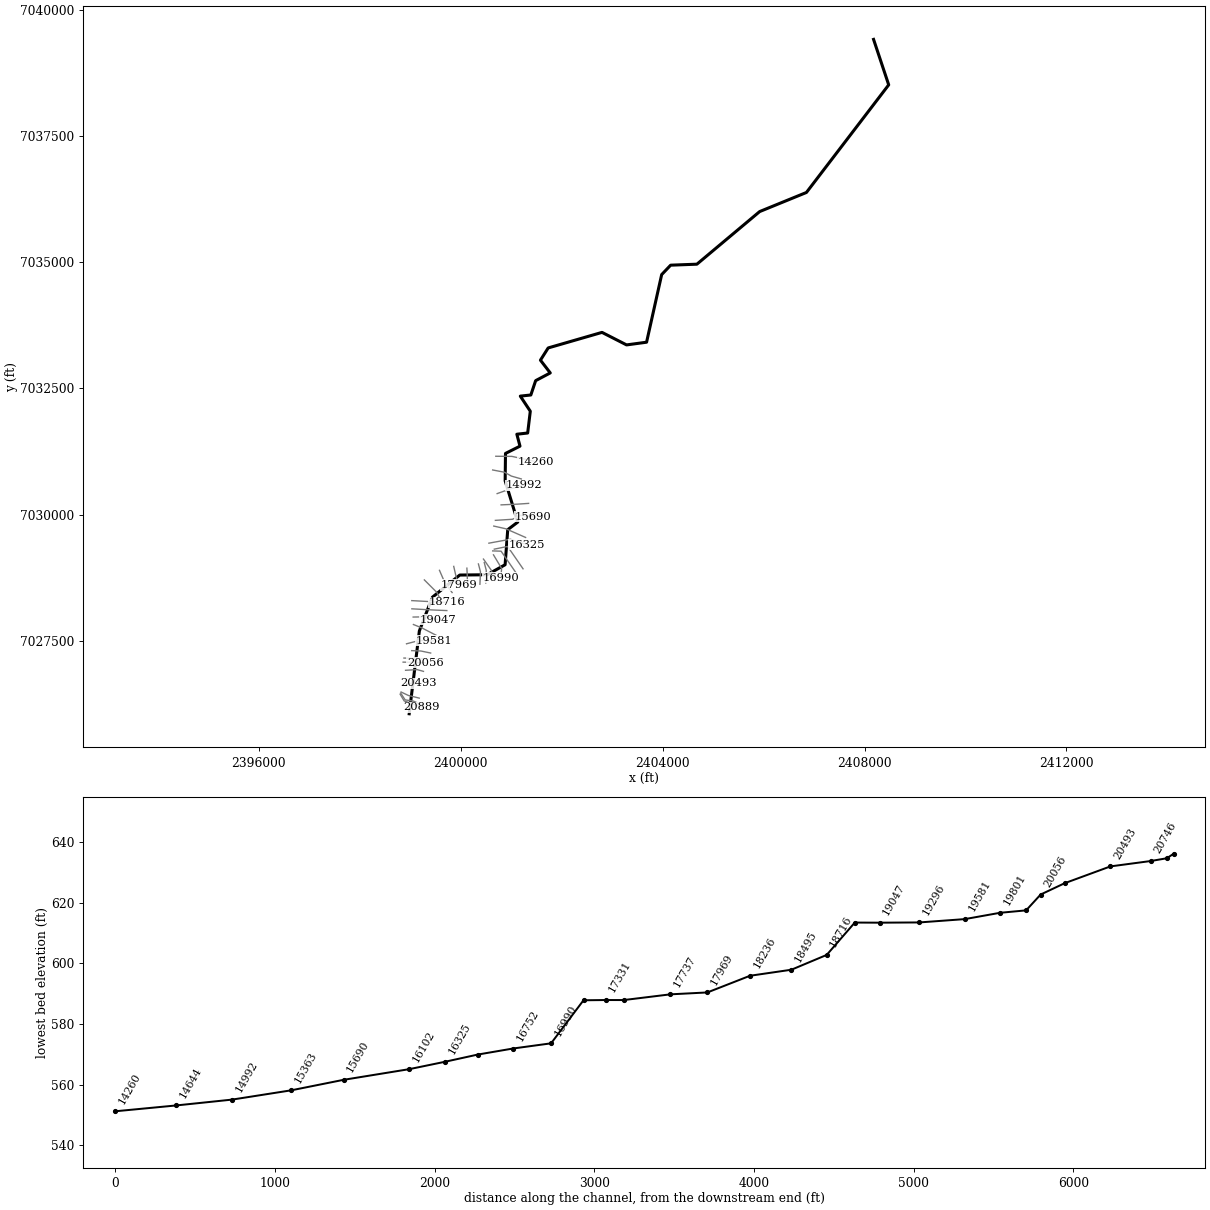
--- Farris Branch.prj (project) ---

Proj Title=Farris Branch Base Level Engineering
Current Plan=p01
Default Exp/Contr=0.3,0.1
English Units
Geom File=g01
Flow File=f01
Plan File=p01
Y Axis Title=Elevation
X Axis Title(PF)=Main Channel Distance
X Axis Title(XS)=Station
BEGIN DESCRIPTION:
Farris Branch
END DESCRIPTION:
DSS Export Rating Curves= 0
DSS Export Rating Curve Sorted= 0
DSS Export Volume Flow Curves= 0
DXF OffsetX= 0
DXF OffsetY= 0
DXF ScaleX= 1
DXF ScaleY= 10

--- Farris Branch.p01 (plan) ---

Plan Title=Multiple Run
Program Version=4.10
Short Identifier=Multiple
Geom File=g01
Flow File=f01
Subcritical Flow
K Sum by GR= 0
Std Step Tol= 0.01
Critical Tol= 0.01
Num of Std Step Trials= 20
Max Error Tol= 0.3
Flow Tol Ratio= 0.001
Split Flow NTrial= 30
Split Flow Tol= 0.02
Split Flow Ratio= 0.02
Log Output Level= 0
Friction Slope Method= 1
Unsteady Friction Slope Method= 2
Unsteady Bridges Friction Slope Method= 1
Parabolic Critical Depth
Global Vel Dist= 1 , 1 , 1
Global Log Level= 0
CheckData=True
Encroach Param=-1 ,0,0, 0
BEGIN DESCRIPTION:
Multiple Run
END DESCRIPTION:
Computation Interval=1HOUR
Output Interval=1HOUR
Run HTab= 0
Run UNet= 0
Run PostProcess= 0
Run WQNet= 0
UNET Theta= 1
UNET Theta Warmup= 1
UNET ZTol= 0.02
UNET ZSATol= 0.05
UNET MxIter= 20
UNET MaxInSteps= 0
UNET DtIC= 0
UNET DtMin= 0
UNET MaxCRTS= 20
UNET WFStab= 2
UNET SFStab= 1
UNET WFX= 1
UNET SFX= 1
UNET DSS MLevel= 4
UNET DZMax Abort= 100
UNET Convert EG Bridges= 0
UNET Use Existing IB Tables=-1
UNET Froude Reduction=False
UNET Froude Limit= 1
UNET Froude Power= 10
UNET Time Slicing=0,0, 5
UNET Junction Losses=0
Instantaneous Interval=1HOUR
Write IC File= 0
Write IC File at Sim End=0
Echo Input=False
Echo Parameters=False
Echo Output=False
Write Detailed= 0
WQ AD Non Conservative
WQ ULTIMATE=-1
WQ Max Comp Step=1HOUR
WQ Output Interval=15MIN
WQ Output Selected Increments= 0
WQ Output face flow=0
WQ Output face velocity=0
WQ Output face area=0
WQ Output face dispersion=0
WQ Output cell volume=0
WQ Output cell surface area=0
WQ Output cell continuity=0
WQ Output cumulative cell continuity=0
WQ Output face conc=0
WQ Output face dconc_dx=0
WQ Output face courant=0
WQ Output face peclet=0
WQ Output face adv mass=0
WQ Output face disp mass=0
WQ Output cell mass=0
WQ Output cell source sink temp=0
WQ Output cell source sink nsm=0
WQ Output MaxMinRange=-1
WQ Daily Max Min Mean=-1
WQ Daily Range=0
WQ Daily Time=0
WQ Create Restart=0
WQ Fixed Restart=0
WQ System Summary=0
WQ Use Fixed Temperature=0
Sorting and Armoring Iterations= 10
XS Update Threshold= 0.02
Hydraulics Update Threshold= 0.02
Energy Slope Method= 1
Volume Change Method= 0
XS Weighting Method= 0
Number of US Weighted Cross Sections= 1
Number of DS Weighted Cross Sections= 1
Upstream XS Weight=0.25
Main XS Weight=0.5
Downstream XS Weight=0.25
Number of DS XS's Weighted with US Boundary= 1
Upstream Boundary Weight= 1
Weight of XSs Associated with US Boundary= 0
Number of US XS's Weighted with DS Boundary= 1
Downstream Boundary Weight= 0.5
Weight of XSs Associated with DS Boundary= 0.5
Sediment Output Level= 4
Mass or Volume Output= 0
Output Increment Type= 1
Profile and TS Output Increment= 10
XS Output Flag= 0
XS Output Increment= 10
Disregard all LS=0
Disregard all Conn=0
Disregard all Breaches=0
Disregard all Pumps=0

--- Farris Branch.f01 (steady flow) ---

Flow Title=Multiple
Number of Profiles=7
Profile Names=10-year,25-year,50-year,1pct_min,100-year,1pct_plu,500-year
River Rch & RM= Farris Branch,Reach-1,20889
     354     470     564     336     671    1340     949
River Rch & RM= Farris Branch,Reach-1,16752
     721     993    1219     742    1480    2953    2181
River Rch & RM= Farris Branch,Reach-1,11243
     910    1271    1574     965    1925    3842    2883
River Rch & RM= Farris Branch,Reach-1,9941
    1021    1434    1782    1097    2189    4367    3301
River Rch & RM= Farris Branch,Reach-1,8957
    1469    2099    2638    1640    3272    6528    5034
River Rch & RM= Farris Branch,Reach-1,6338
    1803    2597    3281    2048    4085    8151    6341
River Rch & RM= Farris Branch,Reach-1,3699
    1899    2740    3465    2164    4317    8613    6709
Boundary for River Rch & Prof#=Farris Branch,Reach-1,1
Up Type=0
Dn Type=3
Dn Slope=0.005
Boundary for River Rch & Prof#=Farris Branch,Reach-1,2
Up Type=0
Dn Type=3
Dn Slope=0.005
Boundary for River Rch & Prof#=Farris Branch,Reach-1,3
Up Type=0
Dn Type=3
Dn Slope=0.005
Boundary for River Rch & Prof#=Farris Branch,Reach-1,4
Up Type=0
Dn Type=3
Dn Slope=0.005
Boundary for River Rch & Prof#=Farris Branch,Reach-1,5
Up Type=0
Dn Type=3
Dn Slope=0.005
Boundary for River Rch & Prof#=Farris Branch,Reach-1,6
Up Type=0
Dn Type=3
Dn Slope=0.005
Boundary for River Rch & Prof#=Farris Branch,Reach-1,7
Up Type=0
Dn Type=3
Dn Slope=0.005

--- Farris Branch.g01 (geometry) ---

Geom Title=Existing Conditions
Program Version=4.10

River Reach=Farris Branch   ,Reach-1
Reach XY= 30
        2398979.        7026060.      2399180.09      7027699.46
      2399436.86      7028366.17      2399980.55      7028806.25
      2400523.14      7028812.05        2400879.        7029010.
      2400931.07      7029704.16      2401129.87      7029854.89
      2400880.08      7030670.55      2400886.65       7031213.7
      2401173.94       7031357.7      2401111.68      7031593.73
      2401326.09      7031617.91      2401378.06      7032049.52
      2401179.98      7032348.31      2401388.83      7032370.47
      2401484.18      7032654.56      2401773.75      7032807.35
        2401579.        7033060.      2401732.35      7033301.91
      2402799.03      7033609.94      2403285.26      7033361.95
      2403681.74      7033415.34      2403981.06      7034754.15
      2404158.84      7034940.37        2404679.        7034960.
      2405922.95      7036001.84      2406849.09      7036379.79
        2408479.        7038510.        2408179.        7039410.

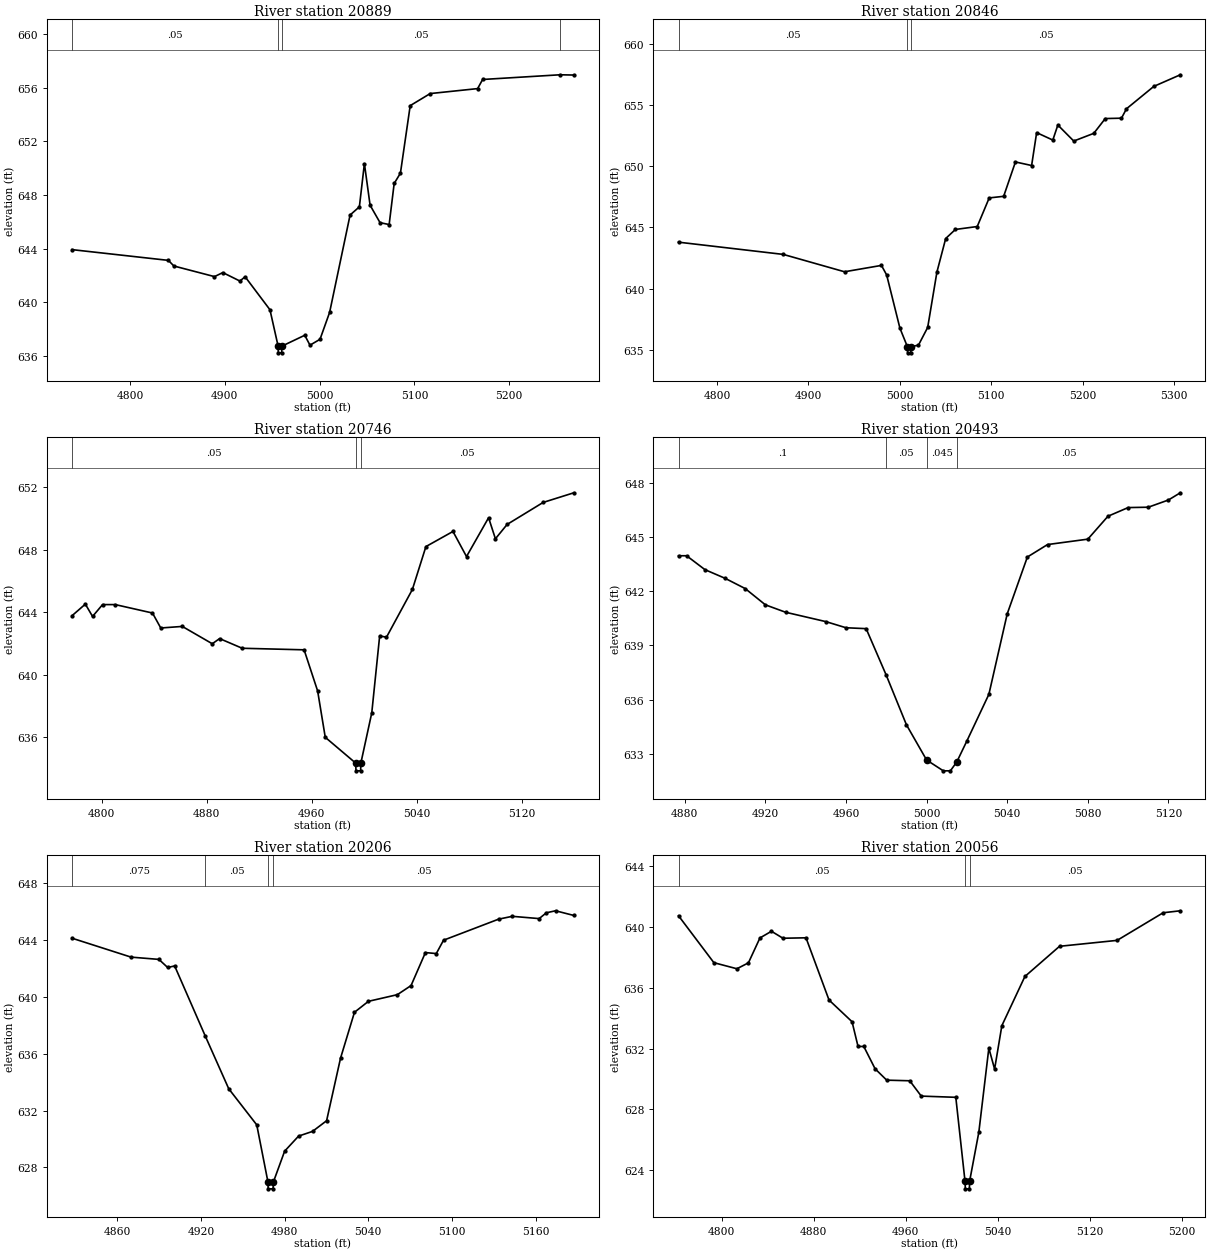
Type RM Length L Ch R = 1 ,20889   ,43,43,43
BEGIN DESCRIPTION:
Farris Branch 47.0
END DESCRIPTION:
XS GIS Cut Line= 4
      2398799.16      7026447.78      2398879.83      7026313.33
      2399054.58      7026254.18      2399232.03      7026192.34
#Sta/Elev= 30
  4738.9  643.93  4840.5  643.13  4846.3  642.71  4889.1  641.92  4897.9  642.22
  4915.9  641.59  4921.4  641.91  4947.6  639.45  4956.2  636.74  4956.4  636.24
  4959.9  636.24  4960.2  636.74  4984.3  637.55  4989.8  636.81  5000.4  637.25
  5010.5  639.25  5032.1  646.51  5041.9  647.12  5047.2  650.34  5053.2  647.24
  5063.7  645.94  5073.3   645.8  5078.6  648.86  5085.2  649.63  5095.5  654.66
  5116.6  655.56  5166.6  655.93  5171.9  656.61  5253.5  656.96  5268.1  656.94
#Mann= 4 ,-1 , 0
  4738.9     .05       0  4956.2     .05       0  4960.2     .05       0
  5253.5    .075       0
Bank Sta=4956.2,4960.2
XS Rating Curve= 0 ,0
Exp/Cntr=0.3,0.1

Type RM Length L Ch R = 1 ,20846   ,100,100,100
BEGIN DESCRIPTION:
Farris Branch 46.0
END DESCRIPTION:
XS GIS Cut Line= 4
      2398809.95      7026469.23      2398898.65      7026334.83
      2399062.64      7026310.64      2399265.47       7026219.9
#Sta/Elev= 30
  4757.9  643.79  4872.5  642.79  4939.5  641.37  4979.9  641.89  4985.6  641.11
  5000.1  636.76  5008.3  635.24  5008.5  634.74    5012  634.74  5012.3  635.24
  5020.4  635.37  5030.5  636.82  5040.6  641.35  5050.2  644.09  5060.8  644.83
  5084.7  645.07  5097.8  647.41  5113.6  647.54  5126.5  650.35  5144.2  650.06
  5149.7  652.75  5167.4  652.14  5172.9  653.37  5190.3  652.06  5212.2  652.69
  5224.8   653.9  5242.5  653.93    5248   654.7  5277.9  656.53  5306.9  657.48
#Mann= 3 ,-1 , 0
  4757.9     .05       0  5008.3     .05       0  5012.3     .05       0
Bank Sta=5008.3,5012.3
XS Rating Curve= 0 ,0
Exp/Cntr=0.3,0.1

Type RM Length L Ch R = 1 ,20746   ,253,253,253
BEGIN DESCRIPTION:
Farris Branch 45.0
END DESCRIPTION:
XS GIS Cut Line= 3
      2398817.98      7026490.77      2398960.48      7026423.55
      2399178.28      7026369.77
#Sta/Elev= 30
  4777.6  643.78  4787.7  644.52  4793.2  643.73  4800.8  644.49  4810.5  644.49
  4838.8  643.95  4845.1  642.99  4861.5  643.09  4884.3  641.98  4889.9  642.31
  4907.1  641.69  4954.2  641.59  4964.5  638.95  4970.3  635.98  4993.4  634.33
  4993.7  633.83  4997.2  633.83  4997.4  634.33  5005.7  637.55  5011.7  642.48
  5016.9   642.4  5036.6  645.46  5046.9  648.21  5067.5  649.18  5077.8  647.57
  5094.6  650.06  5099.8  648.71  5108.7  649.63  5136.1  651.04  5159.5  651.66
#Mann= 3 ,-1 , 0
  4777.6     .05       0  4993.4     .05       0  4997.4     .05       0
Bank Sta=4993.4,4997.4
XS Rating Curve= 0 ,0
Exp/Cntr=0.3,0.1

Type RM Length L Ch R = 1 ,20493   ,287,287,287
BEGIN DESCRIPTION:
Farris Branch 44.0
END DESCRIPTION:
XS GIS Cut Line= 3
       2398905.9      7026660.53      2399055.88      7026660.53
       2399154.9      7026660.53
#Sta/Elev= 27
  4876.9  643.97  4880.9  643.97    4890   643.2    4900  642.72    4910  642.15
    4920  641.25    4930  640.84    4950  640.32    4960  639.98    4970  639.93
  4979.9  637.37    4990   634.6    5000  632.65  5008.3  632.05  5011.8  632.05
    5015  632.55    5020  633.71  5030.9  636.29    5040  640.75    5050   643.9
    5060  644.59    5080  644.89    5090  646.16    5100  646.64    5110  646.66
    5120  647.06  5125.9  647.46
#Mann= 4 ,-1 , 0
  4876.9      .1       0  4979.9     .05       0    5000    .045       0
    5015     .05       0
Bank Sta=5000,5015
XS Rating Curve= 0 ,0
Exp/Cntr=0.3,0.1

Type RM Length L Ch R = 1 ,20206   ,150,150,150
BEGIN DESCRIPTION:
Farris Branch 43.0
END DESCRIPTION:
XS GIS Cut Line= 3
      2398906.76       7026920.9      2399135.23      7026934.33
      2399261.62      7026899.38
#Sta/Elev= 30
  4827.5  644.12  4869.8  642.79  4889.8  642.63  4896.1  642.06  4901.1  642.17
  4923.1  637.23  4939.9  633.53    4960  630.99    4968  626.99  4968.2  626.49
  4971.7  626.49    4972  626.99    4980  629.14    4990   630.2    5000  630.53
  5010.1  631.28  5020.1  635.68  5030.1  638.91  5040.1  639.68  5060.9  640.15
  5070.7  640.79    5081  643.11  5088.8  643.04    5094  643.98  5133.5  645.46
  5143.3  645.66  5162.6   645.5  5167.8  645.91  5174.4  646.05  5187.5  645.72
#Mann= 4 ,-1 , 0
  4827.5    .075       0  4923.1     .05       0    4968     .05       0
    4972     .05       0
Bank Sta=4968,4972
XS Rating Curve= 0 ,0
Exp/Cntr=0.3,0.1

Type RM Length L Ch R = 1 ,20056   ,91,91,91
BEGIN DESCRIPTION:
Farris Branch 42.7
END DESCRIPTION:
XS GIS Cut Line= 3
      2398858.29      7027082.19      2399014.25      7027079.51
      2399293.86      7027068.75
#Sta/Elev= 30
  4762.6  640.75  4793.3  637.66  4813.3  637.26  4823.3  637.65  4833.3  639.29
  4843.3  639.73  4853.3  639.27  4873.3   639.3  4893.3   635.2  4913.3  633.77
  4918.5  632.14  4923.5  632.14  4933.3  630.67  4943.4  629.92  4963.4  629.88
  4973.4  628.87  5003.4  628.79  5011.4  623.26  5011.7  622.76  5015.2  622.76
  5015.4  623.26  5023.4  626.49  5032.1  632.03  5037.1  630.65  5043.4  633.51
  5063.4  636.75  5093.5  638.74  5143.5  639.13  5183.5  640.95  5198.4  641.08
#Mann= 3 ,-1 , 0
  4762.6     .05       0  5011.4    .033       0  5015.4     .05       0
Bank Sta=5011.4,5015.4
XS Rating Curve= 0 ,0
Exp/Cntr=0.3,0.1

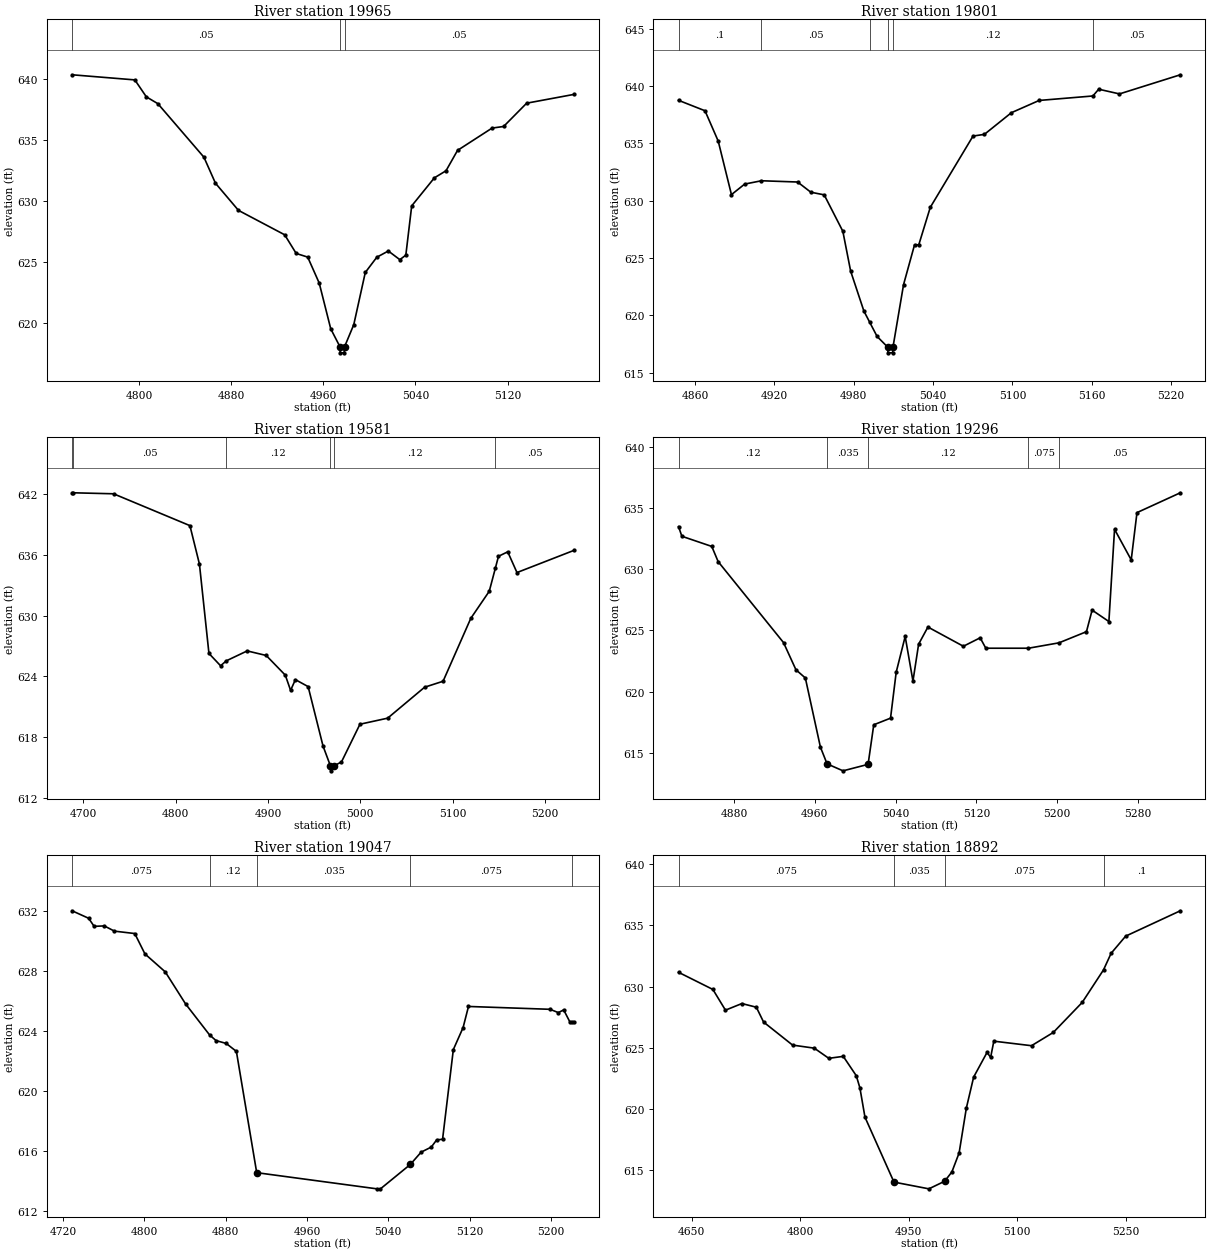
Type RM Length L Ch R = 1 ,19965   ,164,164,164
BEGIN DESCRIPTION:
Farris Branch 42.5
END DESCRIPTION:
XS GIS Cut Line= 3
      2398874.49      7027162.84      2399030.38      7027160.16
      2399309.96       7027149.4
#Sta/Elev= 30
  4741.9  640.33  4796.4  639.91  4806.4  638.52  4816.4  637.96  4856.4  633.57
  4866.4  631.44  4886.4  629.21  4926.5  627.21  4936.5  625.68  4946.5  625.38
  4956.5  623.25  4966.5   619.5  4974.5  618.03  4974.7  617.53  4978.2  617.53
  4978.5  618.03  4986.5  619.84  4996.5  624.12  5006.5  625.37  5016.5  625.88
  5026.5  625.17  5031.7  625.54  5036.8  629.58  5056.5  631.88  5066.6  632.46
  5076.6  634.13  5106.6  635.96  5116.6  636.09  5136.6     638  5177.6  638.72
#Mann= 3 ,-1 , 0
  4741.9     .05       0  4974.5    .033       0  4978.5     .05       0
Bank Sta=4974.5,4978.5
XS Rating Curve= 0 ,0
Exp/Cntr=0.3,0.1

Type RM Length L Ch R = 1 ,19801   ,220,220,220
BEGIN DESCRIPTION:
Farris Branch 42.0
END DESCRIPTION:
XS GIS Cut Line= 3
      2399029.04        7027310.       2399210.5      7027302.64
      2399404.03      7027262.32
#Sta/Elev= 30
  4847.6  638.76  4867.6  637.85  4877.6   635.2  4887.6  630.53  4897.6  631.45
  4910.3  631.74  4937.6  631.63  4947.6  630.74  4957.7  630.51  4971.8  627.33
  4977.7  623.85  4987.7  620.37  4992.1  619.39  4997.7  618.15  5005.7  617.22
  5005.9  616.72  5009.4  616.72  5009.7  617.22  5017.7  622.68    5026  626.15
  5029.2  626.15  5037.9  629.42  5070.2  635.64  5078.8  635.79  5099.2  637.68
  5120.2  638.75  5160.8  639.14  5165.2  639.73  5180.9  639.32  5226.9  640.99
#Mann= 6 ,-1 , 0
  4847.6      .1       0  4910.3     .05       0  4992.1     .12       0
  5005.7     .07       0  5009.7     .12       0  5160.8     .05       0
Bank Sta=5005.7,5009.7
XS Rating Curve= 0 ,0
Exp/Cntr=0.3,0.1

Type RM Length L Ch R = 1 ,19581   ,285,285,285
BEGIN DESCRIPTION:
Farris Branch 41.0
END DESCRIPTION:
XS GIS Cut Line= 3
      2398925.57      7027445.13      2399172.86      7027509.64
      2399460.54      7027504.26
#Sta/Elev= 30
  4687.9  642.14  4688.6  642.14  4732.8  642.04  4815.5  638.89  4825.8  635.09
  4836.1  626.25  4848.7  625.03  4854.9  625.52  4877.5   626.5  4898.1  626.05
  4918.8   624.1  4924.5   622.6  4929.7  623.66  4943.5  622.97  4959.6   617.1
  4967.6  615.14  4967.9  614.64  4971.6  615.14  4979.6  615.52  4999.6  619.25
  5029.6  619.85  5069.6  622.91  5089.6   623.5  5119.6  629.72  5139.6   632.4
  5146.2  634.68  5149.6  635.86  5159.6   636.3  5169.6  634.25  5231.2  636.44
#Mann= 6 ,-1 , 0
  4687.9      .1       0  4688.6     .05       0  4854.9     .12       0
  4967.6     .07       0  4971.6     .12       0  5146.2     .05       0
Bank Sta=4967.6,4971.6
XS Rating Curve= 0 ,0
Exp/Cntr=0.3,0.1

Type RM Length L Ch R = 1 ,19296   ,249,249,249
BEGIN DESCRIPTION:
Farris Branch 40.0
END DESCRIPTION:
XS GIS Cut Line= 3
       2399062.6      7027826.88        2399229.        7027760.
      2399511.06      7027614.76
#Sta/Elev= 30
  4825.2  633.48  4828.5  632.69  4858.1  631.86  4864.4  630.62  4929.1  624.01
  4941.4  621.79  4950.7  621.12  4965.6  615.48  4972.2  614.11    4988  613.54
  5012.8  614.07  5018.4   617.3    5035  617.84  5040.6  621.59  5049.5  624.51
  5057.2  620.87  5062.8  623.88    5072  625.28  5107.1  623.71  5123.7   624.4
  5129.3  623.55  5171.5  623.55  5201.7  623.99  5228.9   624.9  5234.5  626.66
  5251.1  625.73  5256.7  633.26  5273.2  630.76  5278.9  634.62  5321.8  636.24
#Mann= 5 ,-1 , 0
  4825.2     .12       0  4972.2    .035       0  5012.8     .12       0
  5171.5    .075       0  5201.7     .05       0
Bank Sta=4972.2,5012.8
XS Rating Curve= 0 ,0
Exp/Cntr=0.3,0.1

Type RM Length L Ch R = 1 ,19047   ,155,155,155
BEGIN DESCRIPTION:
Farris Branch 39.0
END DESCRIPTION:
XS GIS Cut Line= 3
       2399057.3      7027974.73      2399369.11       7027980.1
      2399541.17      7027920.96
#Sta/Elev= 30
  4728.8  632.03  4745.1  631.53  4750.5  630.99  4760.5  631.02  4770.5  630.67
  4790.5  630.51  4800.5  629.15  4820.5  627.95  4840.5  625.81  4864.1  623.74
  4870.5  623.36  4880.5  623.17  4890.5  622.64  4910.5  614.54  5028.8  613.46
  5032.3  613.46  5061.7  615.09  5072.3  615.91  5082.3  616.25  5087.6  616.73
  5093.4  616.77    5104  622.76  5113.6  624.23  5118.9  625.64  5199.2  625.45
  5207.3  625.23  5212.6  625.41  5218.8  624.59  5220.5  624.59  5222.6  624.59
#Mann= 5 ,-1 , 0
  4728.8    .075       0  4864.1     .12       0  4910.5    .035       0
  5061.7    .075       0  5220.5      .1       0
Bank Sta=4910.5,5061.7
XS Rating Curve= 0 ,0
Exp/Cntr=0.3,0.1

Type RM Length L Ch R = 1 ,18892   ,176,176,176
BEGIN DESCRIPTION:
Farris Branch 38.3
END DESCRIPTION:
XS GIS Cut Line= 3
      2399031.54      7028137.61      2399449.76      7028114.52
      2399724.56      7028102.95
#Sta/Elev= 30
  4631.8  631.17  4679.3  629.77  4696.7  628.08  4719.4  628.62  4739.4  628.32
  4749.4  627.11  4789.5  625.23  4819.5  624.98  4839.6  624.15  4859.6  624.31
  4877.6  622.73  4882.6  621.74  4889.6  619.35  4929.7  614.05    4978   613.5
  4999.8  614.12  5009.8  614.88  5019.8  616.43  5029.8  620.09  5039.9  622.62
  5058.4  624.63  5063.4  624.23  5067.8  625.55  5119.9  625.18    5150  626.26
    5190  628.71  5219.5  631.37    5230  632.72  5250.1  634.12  5325.7  636.19
#Mann= 4 ,-1 , 0
  4631.8    .075       0  4929.7    .035       0  4999.8    .075       0
  5219.5      .1       0
Bank Sta=4929.7,4999.8
XS Rating Curve= 0 ,0
Exp/Cntr=0.3,0.1

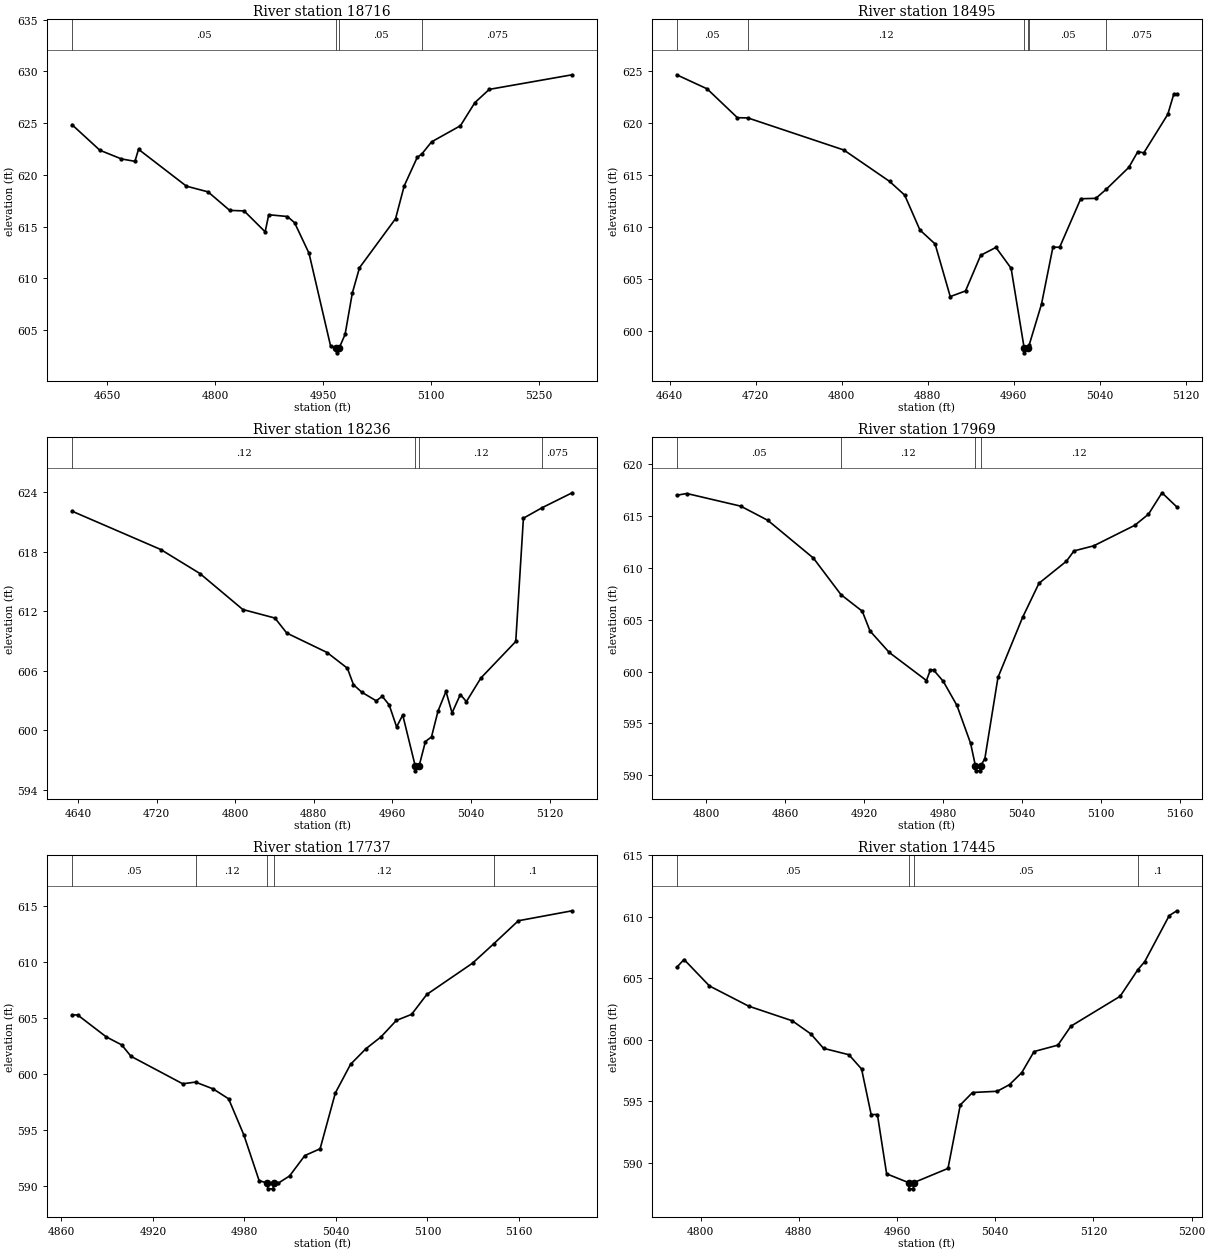
Type RM Length L Ch R = 1 ,18716   ,221,221,221
BEGIN DESCRIPTION:
Farris Branch 38.0
END DESCRIPTION:
XS GIS Cut Line= 3
      2399030.38      7028300.01      2399468.58      7028275.82
      2399723.98      7028265.07
#Sta/Elev= 30
  4601.2  624.85  4639.9  622.38  4669.9  621.54  4688.6  621.31  4693.6  622.47
  4760.1  618.91  4790.1  618.36  4820.2  616.57  4840.2  616.52  4869.4   614.5
  4874.4  616.15  4900.3  615.98  4910.3  615.38  4930.3  612.43  4960.4  603.43
  4968.4  603.31  4968.6  602.81  4972.4  603.31  4980.4  604.59  4990.4  608.57
  5000.4  611.03  5050.5  615.77  5062.5  618.94  5080.5  621.68  5087.2  622.04
  5100.5  623.19  5140.6  624.75  5160.6  626.98  5180.6  628.26  5295.7  629.67
#Mann= 4 ,-1 , 0
  4601.2     .05       0  4968.4     .05       0  4972.4     .05       0
  5087.2    .075       0
Bank Sta=4968.4,4972.4
XS Rating Curve= 0 ,0
Exp/Cntr=0.3,0.1

Type RM Length L Ch R = 1 ,18495   ,259,259,259
BEGIN DESCRIPTION:
Farris Branch 37.0
END DESCRIPTION:
XS GIS Cut Line= 3
      2399279.02      7028709.98        2399529.        7028460.
      2399578.98      7028360.03
#Sta/Elev= 30
  4646.5  624.61  4674.8  623.26    4703  620.49  4712.7  620.47    4802  617.39
  4844.5  614.38  4858.6  613.06  4872.8  609.71  4886.9  608.37    4901  603.32
  4915.2  603.86  4929.3  607.28  4943.5  608.04  4957.6  606.04  4969.7  598.42
    4970  597.92  4973.7  598.42  4974.3  598.63  4985.9   602.6  4996.5  608.06
  5002.8  608.06  5022.4  612.71  5036.4  612.75  5045.9   613.6  5067.1  615.72
  5075.5  617.23  5081.1  617.12  5103.4  620.82    5109  622.78  5111.8  622.78
#Mann= 6 ,-1 , 0
  4646.5     .05       0  4712.7     .12       0  4969.7     .05       0
  4973.7     .12       0  4974.3     .05       0  5045.9    .075       0
Bank Sta=4969.7,4973.7
XS Rating Curve= 0 ,0
Exp/Cntr=0.3,0.1

Type RM Length L Ch R = 1 ,18236   ,267,267,267
BEGIN DESCRIPTION:
Farris Branch 36.0
END DESCRIPTION:
XS GIS Cut Line= 3
      2399578.82      7028899.49      2399683.65      7028657.56
      2399828.98      7028460.03
#Sta/Elev= 30
    4634  622.07  4724.3  618.21  4764.2  615.79  4807.8  612.17  4840.5  611.31
  4852.5   609.8  4893.6  607.84  4914.2  606.26  4920.4   604.6  4928.8  603.85
  4943.5  602.98  4949.7  603.43  4956.7  602.57  4964.3  600.35  4970.5  601.55
  4983.2  596.43  4983.4  595.93  4987.2  596.43  4993.6  598.88  4999.8  599.35
  5006.4  601.94  5014.5  603.93  5020.7  601.76  5029.1  603.61  5035.3   602.9
    5050  605.27  5085.5  608.95  5093.3  621.36  5112.2  622.41  5142.9  623.92
#Mann= 4 ,-1 , 0
    4634     .12       0  4983.2     .07       0  4987.2     .12       0
  5112.2    .075       0
Bank Sta=4983.2,4987.2
XS Rating Curve= 0 ,0
Exp/Cntr=0.3,0.1

Type RM Length L Ch R = 1 ,17969   ,232,232,232
BEGIN DESCRIPTION:
Farris Branch 35.0
END DESCRIPTION:
XS GIS Cut Line= 3
      2399861.07      7028977.52      2399904.09      7028789.29
      2399955.17      7028609.18
#Sta/Elev= 30
  4777.4  617.02  4785.1  617.19  4826.1  615.97  4846.7   614.6  4881.4  610.95
  4902.3  607.43  4918.5  605.83  4924.4  603.92    4939  601.85  4967.3  599.14
  4970.3  600.16  4972.7  600.16  4980.1  599.06  4990.5  596.73  5000.9  593.07
  5004.5  590.92  5004.7  590.42  5008.2  590.42  5008.5  590.92  5011.7  591.58
  5021.7  599.44  5040.4  605.23  5052.9  608.53  5073.7  610.65  5079.5  611.65
  5094.5  612.14  5125.7  614.12  5136.1  615.19  5146.4  617.26  5157.7  615.89
#Mann= 4 ,-1 , 0
  4777.4     .05       0  4902.3     .12       0  5004.5     .07       0
  5008.5     .12       0
Bank Sta=5004.5,5008.5
XS Rating Curve= 0 ,0
Exp/Cntr=0.3,0.1

Type RM Length L Ch R = 1 ,17737   ,292,292,292
BEGIN DESCRIPTION:
Farris Branch 34.0
END DESCRIPTION:
XS GIS Cut Line= 3
      2400121.85      7028942.51        2400129.        7028810.
       2400132.6      7028614.73
#Sta/Elev= 30
  4866.9   605.3  4870.6   605.3  4889.4  603.34  4899.5  602.63  4905.6  601.61
  4939.5  599.16  4947.9  599.31  4959.5   598.7  4969.6  597.82  4979.6   594.6
  4989.6  590.53  4995.1  590.29  4995.3  589.79  4998.8  589.79  4999.1  590.29
  5002.1  590.29  5009.6  590.94  5019.6  592.76  5029.6  593.36  5039.6  598.34
  5049.6   600.9  5059.6  602.28  5069.6  603.35  5079.6  604.81  5089.6  605.35
  5099.6  607.13  5129.6  609.92  5143.5  611.65  5159.6   613.7  5194.9  614.59
#Mann= 5 ,-1 , 0
  4866.9     .05       0  4947.9     .12       0  4995.1     .07       0
  4999.1     .12       0  5143.5      .1       0
Bank Sta=4995.1,4999.1
XS Rating Curve= 0 ,0
Exp/Cntr=0.3,0.1

Type RM Length L Ch R = 1 ,17445   ,114,114,114
BEGIN DESCRIPTION:
Farris Branch 33.0
END DESCRIPTION:
XS GIS Cut Line= 3
      2400350.37      7029025.84      2400390.68      7028869.94
      2400379.98       7028623.8
#Sta/Elev= 30
  4780.5   605.9  4786.5  606.54  4807.2  604.39  4839.1  602.75  4874.6  601.56
  4889.8  600.49  4900.1  599.32  4920.8   598.8  4931.1  597.64  4938.9  593.94
    4944  593.94  4951.5  589.12  4969.5   588.4  4969.7   587.9  4973.2   587.9
  4973.5   588.4  5001.5  589.56  5011.5  594.72  5021.5  595.73  5041.6  595.83
  5051.6  596.37  5061.6  597.35  5071.6  599.06    5091  599.58  5101.6  601.12
  5141.7  603.55  5156.2  605.72  5161.7  606.36  5181.7  610.11  5187.9   610.5
#Mann= 4 ,-1 , 0
  4780.5     .05       0  4969.5    .033       0  4973.5     .05       0
  5156.2      .1       0
Bank Sta=4969.5,4973.5
XS Rating Curve= 0 ,0
Exp/Cntr=0.3,0.1

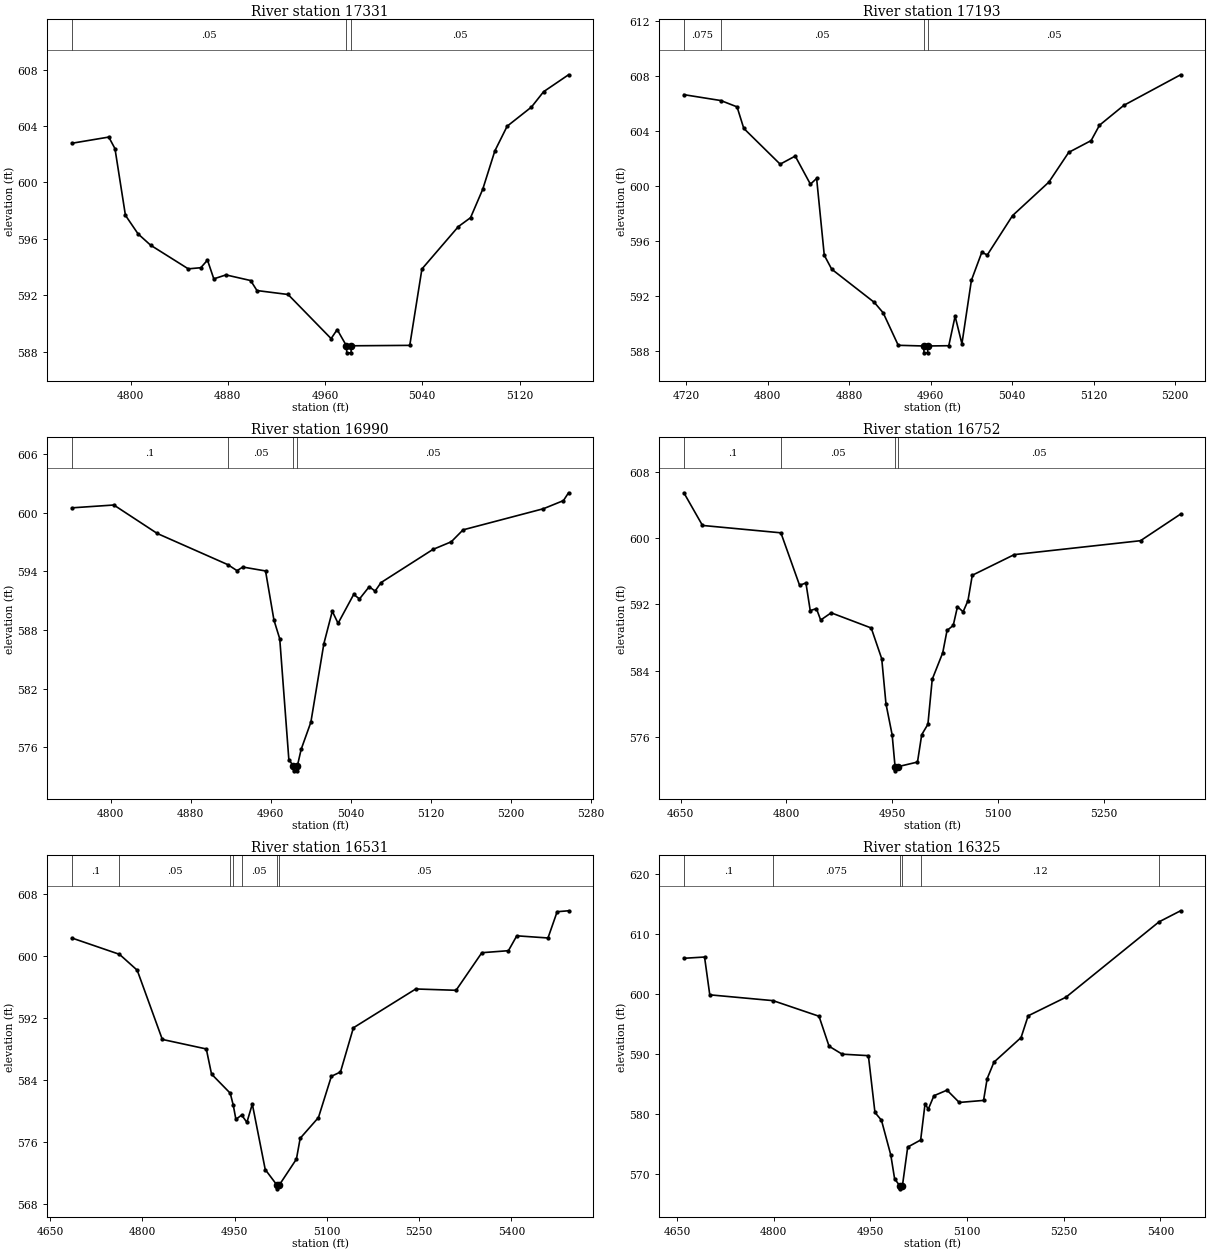
Type RM Length L Ch R = 1 ,17331   ,138,138,138
BEGIN DESCRIPTION:
Farris Branch 32.8
END DESCRIPTION:
XS GIS Cut Line= 3
      2400465.96      7029052.74      2400506.28      7028896.83
      2400495.53       7028649.5
#Sta/Elev= 30
  4751.7  602.78  4782.1  603.22  4787.2   602.4  4795.8  597.67  4806.2  596.35
  4816.5  595.55  4847.5  593.87  4857.8  593.95  4863.3  594.49  4868.5  593.16
  4878.5  593.44  4898.8  593.04    4904  592.33  4929.6  592.05    4965  588.92
    4970  589.56  4977.6  588.41  4977.9  587.91  4981.4  587.91  4981.6  588.41
  5029.7  588.44  5039.7  593.86  5069.7  596.87  5079.7   597.5  5089.7  599.51
  5099.7  602.24  5109.8  603.99  5129.8  605.35  5139.8  606.44  5160.3  607.64
#Mann= 3 ,-1 , 0
  4751.7     .05       0  4977.6    .033       0  4981.6     .05       0
Bank Sta=4977.6,4981.6
XS Rating Curve= 0 ,0
Exp/Cntr=0.3,0.1

Type RM Length L Ch R = 1 ,17193   ,203,203,203
BEGIN DESCRIPTION:
Farris Branch 32.0
END DESCRIPTION:
XS GIS Cut Line= 3
      2400449.82      7029122.66      2400603.06      7028904.89
      2400681.04      7028697.87
#Sta/Elev= 30
  4717.7  606.66    4754  606.23  4769.9  605.77  4776.5   604.2  4812.2  601.59
    4827  602.18  4841.9  600.13    4848  600.55  4855.5  594.95  4862.8  593.93
  4904.6  591.51  4913.3  590.75  4928.1  588.38  4953.1  588.33  4953.4  587.83
  4956.9  587.83  4957.1  588.33  4977.7  588.35  4983.9   590.5  4990.6  588.49
  4999.9  593.12  5010.1  595.16  5015.5  594.97  5040.3  597.84  5075.9  600.28
  5095.4  602.45  5117.4  603.31  5125.6  604.43  5149.5  605.88  5205.2  608.11
#Mann= 4 ,-1 , 0
  4717.7    .075       0    4754     .05       0  4953.1    .033       0
  4957.1     .05       0
Bank Sta=4953.1,4957.1
XS Rating Curve= 0 ,0
Exp/Cntr=0.3,0.1

Type RM Length L Ch R = 1 ,16990   ,238,238,238
BEGIN DESCRIPTION:
Farris Branch 31.0
END DESCRIPTION:
XS GIS Cut Line= 3
      2400648.75      7029206.01      2400810.07      7028937.15
      2400793.99        7028755.
#Sta/Elev= 30
  4761.3  600.49  4803.3  600.78  4846.7  597.87  4917.3  594.68  4926.4  594.07
  4932.2  594.44  4954.9  594.04  4963.3  589.02  4969.1   587.1  4978.2  574.76
  4982.7  574.11  4982.9  573.61  4986.4  573.61  4986.7  574.11  4990.5  575.81
  5000.2  578.58  5013.2  586.61  5021.6  589.92  5027.4  588.69    5043  591.64
  5048.8  591.18  5058.5  592.43  5064.4  591.98  5070.3  592.85  5122.2  596.24
  5140.5  597.02  5152.3  598.24  5232.6   600.4  5252.6  601.23  5257.7  602.03
#Mann= 4 ,-1 , 0
  4761.3      .1       0  4917.3     .05       0  4982.7     .05       0
  4986.7     .05       0
Bank Sta=4982.7,4986.7
XS Rating Curve= 0 ,0
Exp/Cntr=0.3,0.1

Type RM Length L Ch R = 1 ,16752   ,221,221,221
BEGIN DESCRIPTION:
Farris Branch 30.6
END DESCRIPTION:
XS GIS Cut Line= 3
       2400632.6      7029283.95      2400799.31      7029278.57
       2401104.9      7028836.27
#Sta/Elev= 30
  4654.6  605.44    4681   601.5  4792.2  600.61  4818.7  594.28  4827.7  594.56
  4833.8  591.23  4842.6  591.47  4848.6  590.09  4863.5  590.96  4920.3  589.13
  4935.2  585.42  4941.2  579.99    4950  576.23  4954.1   572.4  4954.4   571.9
  4958.1   572.4  4985.9  572.96  4991.9  576.26  5000.7  577.52  5006.8  582.94
  5021.7  586.14  5027.8  588.83  5036.6  589.44  5042.6   591.7  5050.6  591.08
  5057.5  592.43  5063.6  595.49  5123.1  597.98  5302.2  599.66    5359  602.87
#Mann= 4 ,-1 , 0
  4654.6      .1       0  4792.2     .05       0  4954.1     .05       0
  4958.1     .05       0
Bank Sta=4954.1,4958.1
XS Rating Curve= 0 ,0
Exp/Cntr=0.3,0.1

Type RM Length L Ch R = 1 ,16531   ,206,206,206
BEGIN DESCRIPTION:
Farris Branch 30.4
END DESCRIPTION:
XS GIS Cut Line= 3
      2400664.86      7029318.89      2400928.35      7029372.66
      2401234.44      7028929.65
#Sta/Elev= 30
  4685.5  602.27    4763  600.16  4791.8  598.11  4832.6  589.18  4904.1  587.95
  4912.6  584.71    4943  582.24    4948  580.67  4952.2  578.87  4961.6  579.42
  4970.1  578.48  4978.9  580.84  4999.9  572.39  5018.8   570.4  5019.1   569.9
  5022.8   570.4  5050.6  573.74  5056.7  576.42  5086.4   579.1  5107.4  584.42
  5122.2  584.98  5143.2  590.68  5244.6  595.69  5310.1  595.52    5352  600.37
  5395.2  600.63  5408.8  602.55  5459.5  602.27  5474.4  605.66  5492.9  605.78
#Mann= 7 ,-1 , 0
  4685.5      .1       0    4763     .05       0    4943    .075       0
    4948     .12       0  4961.6     .05       0  5018.8     .05       0
  5022.8     .05       0
Bank Sta=5018.8,5022.8
XS Rating Curve= 0 ,0
Exp/Cntr=0.3,0.1

Type RM Length L Ch R = 1 ,16325   ,223,223,223
BEGIN DESCRIPTION:
Farris Branch 30.0
END DESCRIPTION:
XS GIS Cut Line= 3
      2400557.39      7029437.19      2400982.12      7029515.15
       2401304.4      7029410.41
#Sta/Elev= 30
  4660.6  605.94  4692.7  606.15  4700.8  599.85    4799  598.88  4870.3  596.28
  4885.9  591.28  4906.2  589.96  4946.9  589.71  4957.1  580.24  4967.2  578.94
  4981.7  573.13  4987.6  569.18  4995.7  568.01    4996  567.51  4999.7  568.01
  5007.9  574.47    5028  575.65  5034.8  581.66  5039.9   580.8  5048.6  583.03
  5068.9  583.96  5087.9  581.91  5125.6  582.25  5131.2  585.88  5141.7  588.62
  5183.8  592.73  5194.8  596.35  5253.4  599.45  5397.8  612.01  5431.3  613.86
#Mann= 6 ,-1 , 0
  4660.6      .1       0    4799    .075       0  4995.7     .07       0
  4999.7    .075       0    5028     .12       0  5397.8     .05       0
Bank Sta=4995.7,4999.7
XS Rating Curve= 0 ,0
Exp/Cntr=0.3,0.1

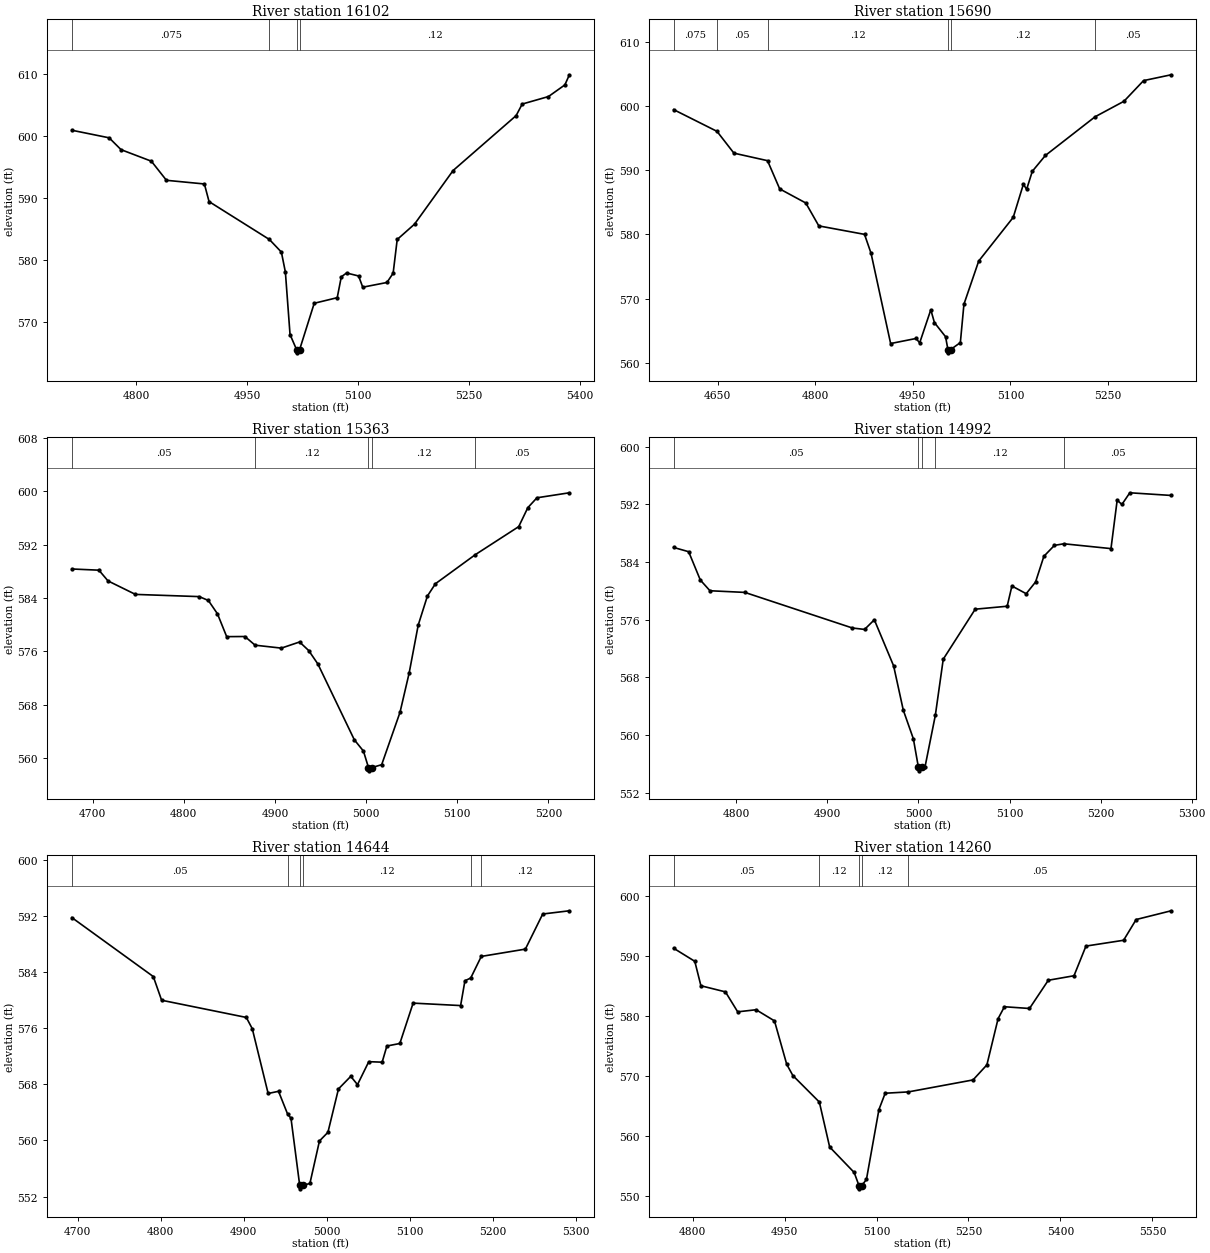
Type RM Length L Ch R = 1 ,16102   ,412,412,412
BEGIN DESCRIPTION:
Farris Branch 29.0
END DESCRIPTION:
XS GIS Cut Line= 3
      2400654.16      7029775.91      2400893.41      7029722.15
      2401284.93      7029550.52
#Sta/Elev= 30
  4713.2  600.96  4763.6  599.74  4779.7  597.83  4820.7  595.97  4841.1  592.89
  4892.4   592.3  4898.7  589.46  4980.3  583.35  4996.5  581.32  5001.9   578.1
  5008.2  568.03  5017.1  565.58  5017.4  565.08  5021.1  565.58  5040.9  573.07
    5072  573.97  5077.5  577.33  5084.6  577.95  5100.9  577.47  5106.5  575.66
  5139.2  576.42  5147.6  577.91  5153.1  583.35  5176.5  585.82  5228.7  594.47
  5313.9  603.32  5322.1  605.18  5357.6  606.39  5379.8  608.27  5385.9   609.9
#Mann= 4 ,-1 , 0
  4713.2    .075       0  4980.3     .12       0  5017.1     .07       0
  5021.1     .12       0
Bank Sta=5017.1,5021.1
XS Rating Curve= 0 ,0
Exp/Cntr=0.3,0.1

Type RM Length L Ch R = 1 ,15690   ,327,327,327
BEGIN DESCRIPTION:
Farris Branch 28.0
END DESCRIPTION:
XS GIS Cut Line= 4
      2400686.41      7029888.83      2401025.13      7029910.33
      2401185.67      7029987.21      2401431.12      7029961.41
#Sta/Elev= 30
  4582.6  599.47  4649.2  596.08  4675.2  592.68  4726.8  591.51  4745.5  587.11
  4785.6  584.91  4805.6  581.34  4875.8  580.02  4885.8  577.08  4915.9     563
    4955  563.79  4960.5   563.1  4977.6  568.26  4983.2  566.26  5000.3  564.06
  5003.9  562.05  5004.1  561.55  5007.9  562.05    5023  563.15  5028.5  569.13
  5051.2  575.86  5104.2  582.67  5119.8  587.83  5124.8  587.04  5133.5  589.85
  5153.6  592.32  5229.9  598.35  5274.3  600.77  5304.4  603.99  5346.8   604.9
#Mann= 6 ,-1 , 0
  4582.6    .075       0  4649.2     .05       0  4726.8     .12       0
  5003.9     .07       0  5007.9     .12       0  5229.9     .05       0
Bank Sta=5003.9,5007.9
XS Rating Curve= 0 ,0
Exp/Cntr=0.3,0.1

Type RM Length L Ch R = 1 ,15363   ,371,371,371
BEGIN DESCRIPTION:
Farris Branch 27.0
END DESCRIPTION:
XS GIS Cut Line= 3
      2400799.31       7030195.3        2401129.        7030210.
      2401344.47      7030224.83
#Sta/Elev= 30
  4677.1  588.34  4706.8  588.16  4716.8  586.55  4746.9  584.53  4816.9   584.2
  4826.9  583.62  4836.9  581.62    4847   578.2    4867  578.22  4878.2  576.92
    4907  576.48    4927   577.4    4937  576.12  4947.1   574.1  4987.1  562.74
  4997.1  561.05  5002.6  558.59  5002.9  558.09  5006.6  558.59  5017.1  559.01
  5037.2  566.85  5047.2  572.71  5057.2  579.93  5067.3  584.29  5076.1  586.13
  5119.8  590.48  5167.5  594.69  5177.5  597.53  5187.5  599.01  5223.1  599.76
#Mann= 5 ,-1 , 0
  4677.1     .05       0  4878.2     .12       0  5002.6     .07       0
  5006.6     .12       0  5119.8     .05       0
Bank Sta=5002.6,5006.6
XS Rating Curve= 0 ,0
Exp/Cntr=0.3,0.1

Type RM Length L Ch R = 1 ,14992   ,348,348,348
BEGIN DESCRIPTION:
Farris Branch 26.0
END DESCRIPTION:
XS GIS Cut Line= 3
      2400721.37      7030418.44        2400979.        7030510.
      2401242.92      7030579.74
#Sta/Elev= 30
  4731.1  586.03  4747.6  585.44  4760.4  581.51    4771  580.02  4809.3  579.79
  4927.4  574.85  4940.8  574.65  4951.5  575.99  4972.7  569.59  4983.3  563.45
  4994.4  559.46  4999.9  555.52  5000.1  555.02  5003.9  555.52  5007.1  555.52
  5018.5  562.72  5027.2  570.52  5062.3  577.46  5097.4  577.87  5102.6  580.68
  5118.3  579.61  5128.6  581.24  5137.7   584.8  5149.3  586.32  5159.7  586.54
  5211.4  585.87  5218.2  592.59  5223.4     592  5232.1  593.62  5277.5  593.25
#Mann= 5 ,-1 , 0
  4731.1     .05       0  4999.9     .05       0  5003.9     .05       0
  5018.5     .12       0  5159.7     .05       0
Bank Sta=4999.9,5003.9
XS Rating Curve= 0 ,0
Exp/Cntr=0.3,0.1

Type RM Length L Ch R = 1 ,14644   ,384,384,384
BEGIN DESCRIPTION:
Farris Branch 25.0
END DESCRIPTION:
XS GIS Cut Line= 4
      2400632.63       7030886.2      2400865.74      7030841.63
      2401003.63      7030765.23      2401199.89      7030708.77
#Sta/Elev= 30
  4692.9  591.73    4791  583.33    4801  579.96    4903  577.51  4910.2   575.9
  4929.3  566.68  4941.8  566.99  4952.8  563.73  4956.8  563.16  4967.3   553.6
  4967.5   553.1  4971.3   553.6  4979.6  553.87  4991.1  559.92  5001.3  561.15
    5014  567.33  5028.8  569.12  5036.9  567.94  5050.5  571.21  5066.6  571.14
  5072.3  573.44  5087.9   573.8  5103.9  579.55  5161.1   579.2  5166.3  582.73
  5173.3  583.13    5186   586.2  5239.1  587.24    5260  592.24  5292.1   592.7
#Mann= 6 ,-1 , 0
  4692.9     .05       0  4952.8     .12       0  4967.3     .07       0
  4971.3     .12       0  5173.3     .05       0    5186     .12       0
Bank Sta=4967.3,4971.3
XS Rating Curve= 0 ,0
Exp/Cntr=0.3,0.1

Type RM Length L Ch R = 1 ,14260   ,352,352,352
BEGIN DESCRIPTION:
Farris Branch 24.0
END DESCRIPTION:
XS GIS Cut Line= 3
      2400694.47      7031157.73      2401014.38      7031155.04
      2401494.79      7031050.37
#Sta/Elev= 30
    4769   591.3  4803.5  589.12  4813.5  585.04  4853.5  584.02  4873.5  580.69
  4903.5  581.04  4933.5  579.18  4953.5  571.93  4963.5  570.06  5006.7  565.64
  5023.5  558.14  5063.5  553.89  5071.5  551.66  5071.8  551.16  5075.5  551.66
  5083.5  552.72  5103.9  564.39  5114.1  567.11  5151.8  567.33  5257.4  569.33
    5280  571.84  5298.3  579.56  5308.6  581.54  5349.5  581.25  5380.2  585.96
  5422.1  586.71  5441.6  591.66    5503  592.63  5523.5  596.09  5580.6  597.55
#Mann= 5 ,-1 , 0
    4769     .05       0  5006.7     .12       0  5071.5     .05       0
  5075.5     .12       0  5151.8     .05       0
Bank Sta=5071.5,5075.5
XS Rating Curve= 0 ,0
Exp/Cntr=0.3,0.1