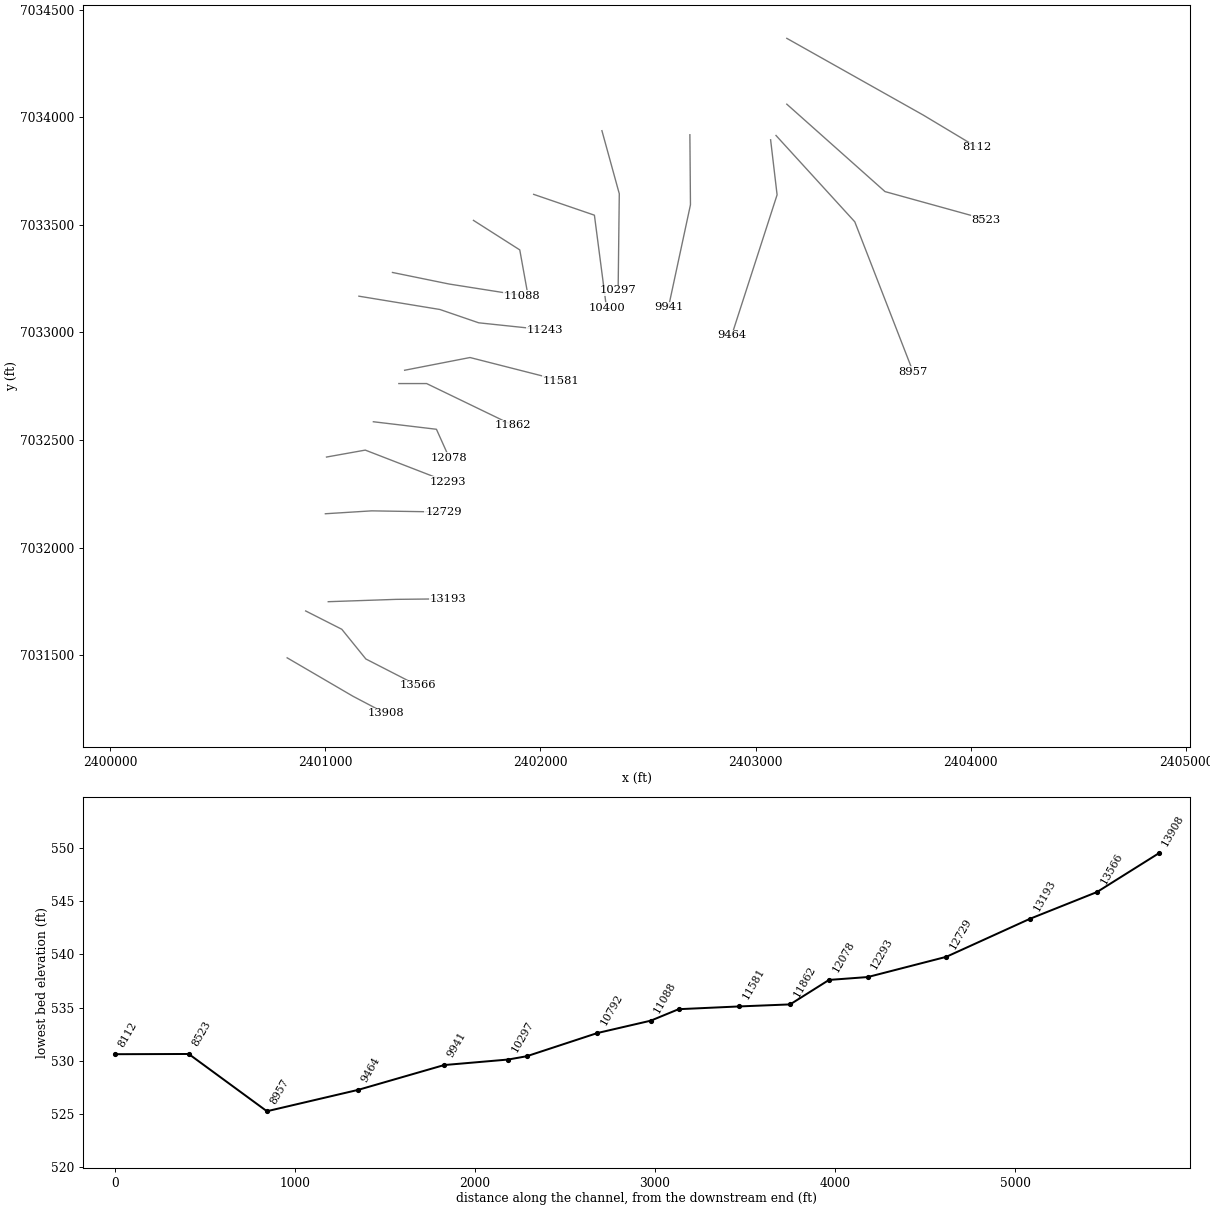
HEC-RAS study Farris Branch.prj: Farris Branch Base Level Engineering

--- Farris Branch.g01 (geometry) --- (continued)

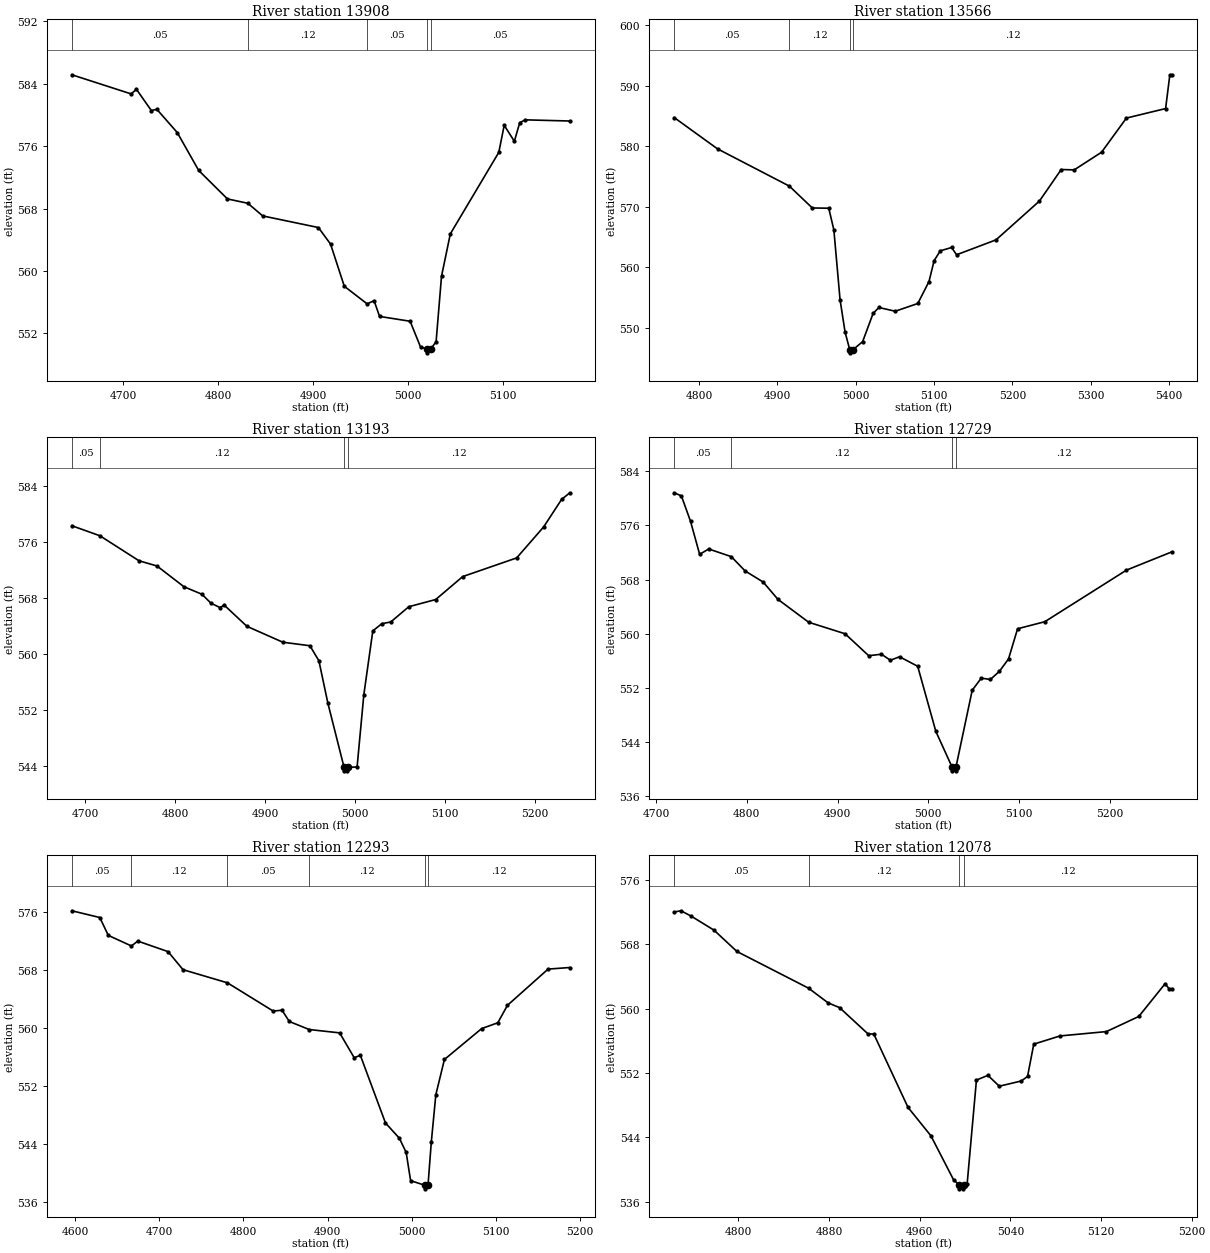
Type RM Length L Ch R = 1 ,13908   ,342,342,342
BEGIN DESCRIPTION:
Farris Branch 23.0
END DESCRIPTION:
XS GIS Cut Line= 3
       2400823.5       7031488.4        2401129.        7031310.
      2401280.55       7031230.3
#Sta/Elev= 30
  4645.7  585.15  4708.1   582.7  4713.8  583.28  4729.5  580.56  4735.3  580.72
  4756.8  577.74  4779.4  572.88  4809.7  569.23  4831.2  568.67  4846.9  567.05
  4905.6  565.56  4918.4  563.44  4932.9  558.03    4957  555.77  4964.3  556.18
  4970.1  554.16  5002.3  553.54  5013.3  550.24  5020.1  549.99  5020.3  549.49
  5024.1  549.99  5029.7  550.92  5035.4  559.31  5044.7  564.75  5095.8   575.2
  5101.5  578.67  5112.2  576.62  5117.9  579.02  5123.8  579.37  5170.7  579.22
#Mann= 5 ,-1 , 0
  4645.7     .05       0  4831.2     .12       0    4957     .05       0
  5020.1    .033       0  5024.1     .05       0
Bank Sta=5020.1,5024.1
XS Rating Curve= 0 ,0
Exp/Cntr=0.3,0.1

Type RM Length L Ch R = 1 ,13566   ,373,373,373
BEGIN DESCRIPTION:
Farris Branch 22.0
END DESCRIPTION:
XS GIS Cut Line= 4
      2400909.54      7031706.14      2401077.37      7031621.06
      2401189.12      7031483.02      2401429.04      7031359.98
#Sta/Elev= 30
  4768.3  584.73  4823.7  579.55  4915.3   573.4  4944.6  569.79  4965.6  569.75
  4972.1  566.16    4980  554.64  4986.4  549.29  4992.4  546.36  4992.6  545.86
  4996.4  546.36  5008.8  547.71  5022.2  552.38  5029.6  553.35  5050.4  552.73
  5079.2  554.01  5093.5  557.64    5100  561.08  5107.9  562.71  5122.3  563.26
  5128.7  562.06    5179  564.52  5234.4  570.93  5262.2  576.14  5278.8  576.08
  5313.7     579  5345.4  584.64  5395.4  586.21  5400.8  591.79  5403.7  591.79
#Mann= 4 ,-1 , 0
  4768.3     .05       0  4915.3     .12       0  4992.4     .07       0
  4996.4     .12       0
Bank Sta=4992.4,4996.4
XS Rating Curve= 0 ,0
Exp/Cntr=0.3,0.1

Type RM Length L Ch R = 1 ,13193   ,464,464,464
BEGIN DESCRIPTION:
Farris Branch 21.0
END DESCRIPTION:
XS GIS Cut Line= 3
       2401014.4      7031749.16        2401329.        7031760.
       2401568.2       7031762.6
#Sta/Elev= 30
  4685.2  578.29  4716.4  576.86  4759.8   573.3  4779.9  572.55  4809.9  569.59
  4829.9  568.52  4839.9  567.25  4849.8  566.63  4854.8  566.96  4879.9  563.95
  4919.9  561.68    4950  561.18    4960  559.04    4970  552.99    4988  543.84
  4988.2  543.34  4991.7  543.34    4992  543.84  5002.5  543.89    5010  554.19
    5020   563.3    5030  564.32    5040  564.57    5060  566.74    5090  567.77
    5120  571.04    5180   573.7    5210  578.11    5230  582.04  5239.2  582.99
#Mann= 4 ,-1 , 0
  4685.2     .05       0  4716.4     .12       0    4988     .07       0
    4992     .12       0
Bank Sta=4988,4992
XS Rating Curve= 0 ,0
Exp/Cntr=0.3,0.1

Type RM Length L Ch R = 1 ,12729   ,436,436,436
BEGIN DESCRIPTION:
Farris Branch 20.0
END DESCRIPTION:
XS GIS Cut Line= 3
      2401000.98      7032157.79      2401216.01      7032171.23
      2401549.32      7032165.86
#Sta/Elev= 30
  4719.9  580.83  4727.9  580.37    4738   576.6    4748  571.74    4758  572.53
  4782.9   571.4  4798.1  569.29  4818.1  567.64  4834.3  565.09  4868.2  561.71
  4908.3  560.01  4934.3  556.77  4948.3  556.99  4958.3   556.1  4968.3  556.62
  4988.3  555.21  5008.3   545.6  5026.4  540.27  5026.6  539.77  5030.1  539.77
  5030.4  540.27  5048.4  551.67  5058.4  553.46  5068.4  553.26  5078.4  554.47
  5088.4  556.29  5098.4  560.75  5128.4  561.79  5218.4  569.41  5268.7  572.12
#Mann= 4 ,-1 , 0
  4719.9     .05       0  4782.9     .12       0  5026.4     .07       0
  5030.4     .12       0
Bank Sta=5026.4,5030.4
XS Rating Curve= 0 ,0
Exp/Cntr=0.3,0.1

Type RM Length L Ch R = 1 ,12293   ,215,215,215
BEGIN DESCRIPTION:
Farris Branch 19.0
END DESCRIPTION:
XS GIS Cut Line= 3
      2401006.35      7032421.26      2401186.43      7032453.51
      2401568.15      7032305.66
#Sta/Elev= 30
  4595.9   576.2  4629.1  575.27  4639.2  572.81  4666.7  571.35  4674.3  572.02
  4710.3  570.57  4728.1  568.08  4780.9  566.27  4835.3  562.38  4845.9  562.49
  4854.5  560.94  4878.2  559.83  4914.4  559.37  4931.7  555.94    4939  556.28
  4968.9  546.95  4985.4  544.85  4993.5  542.89  4998.8     539  5015.5  538.37
  5015.8  537.87  5019.5  538.37  5023.4   544.3  5028.8  550.84    5039   555.7
  5083.3  559.96  5102.5  560.76    5114  563.17  5162.3  568.16  5188.2  568.38
#Mann= 6 ,-1 , 0
  4595.9     .05       0  4666.7     .12       0  4780.9     .05       0
  4878.2     .12       0  5015.5     .07       0  5019.5     .12       0
Bank Sta=5015.5,5019.5
XS Rating Curve= 0 ,0
Exp/Cntr=0.3,0.1

Type RM Length L Ch R = 1 ,12078   ,216,216,216
BEGIN DESCRIPTION:
Farris Branch 18.0
END DESCRIPTION:
XS GIS Cut Line= 3
      2401224.03      7032585.24       2401517.1      7032550.29
      2401576.23       7032418.6
#Sta/Elev= 30
  4743.2  572.02  4749.2  572.17  4758.3   571.5  4778.4  569.76  4798.6  567.11
  4861.8  562.55  4879.1  560.72  4889.2  560.13  4914.3  556.86  4919.4  556.85
  4949.6  547.73  4969.8   544.2  4989.9   538.7  4994.8   538.1    4995   537.6
  4998.5   537.6  4998.8   538.1  5001.8  538.21    5010  551.12  5020.1  551.71
  5030.2  550.36  5049.6  551.01  5055.1  551.57  5060.6  555.59  5083.8  556.61
  5124.7  557.15  5153.3  559.03  5176.5   563.1    5180  562.48  5182.7  562.48
#Mann= 4 ,-1 , 0
  4743.2     .05       0  4861.8     .12       0  4994.8     .07       0
  4998.8     .12       0
Bank Sta=4994.8,4998.8
XS Rating Curve= 0 ,0
Exp/Cntr=0.3,0.1

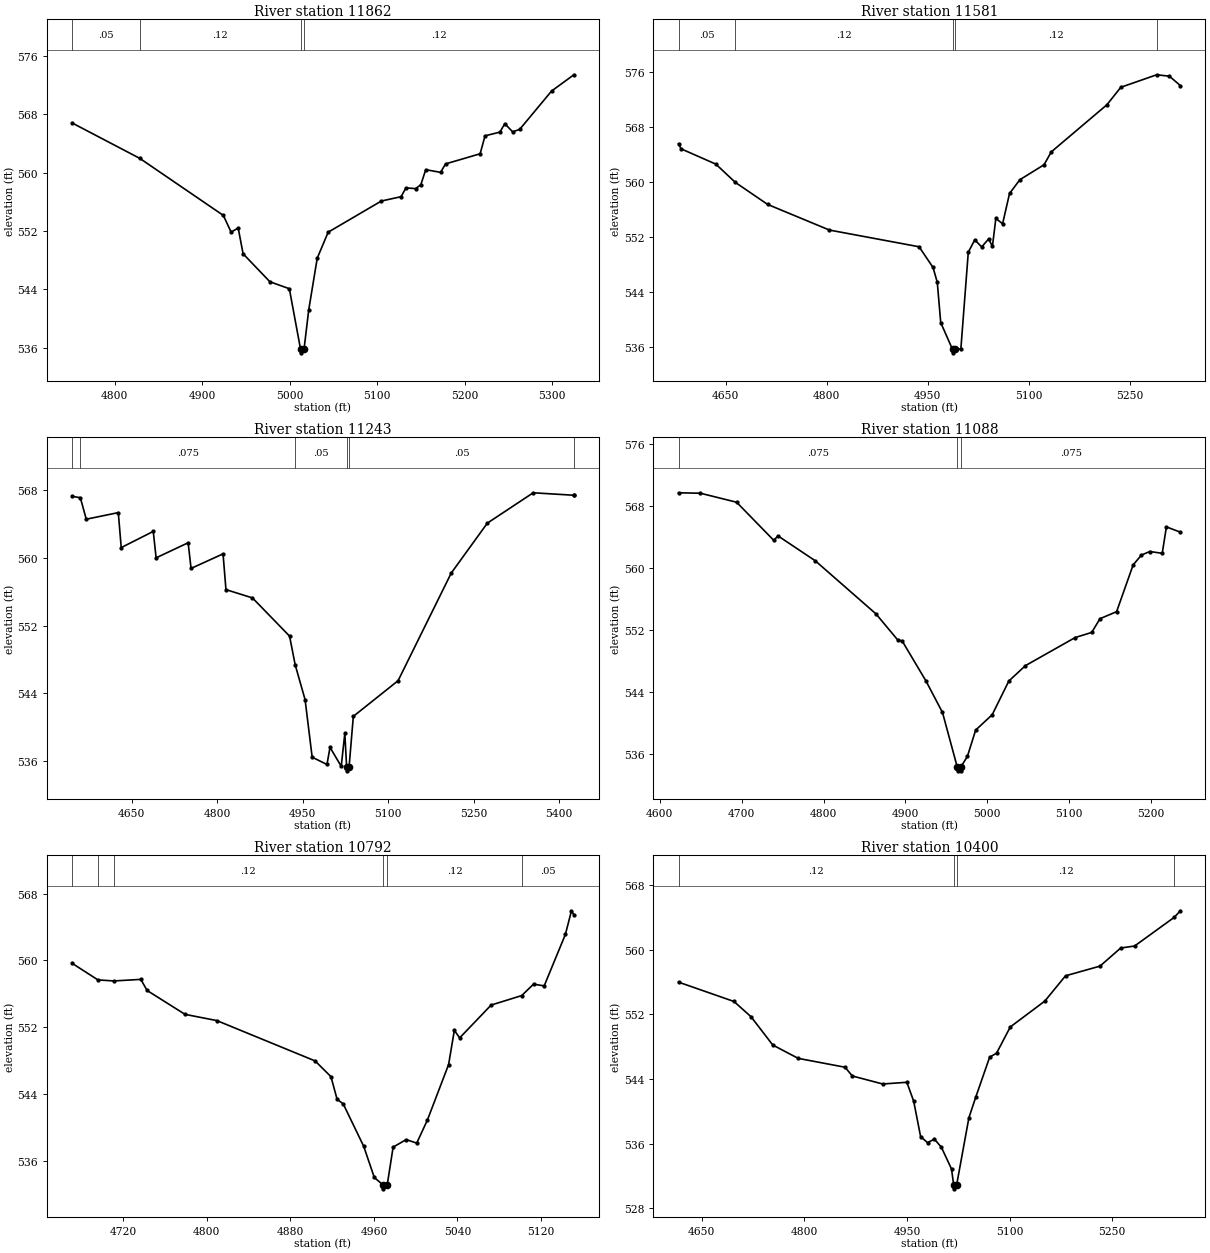
Type RM Length L Ch R = 1 ,11862   ,281,281,281
BEGIN DESCRIPTION:
Farris Branch 17.5
END DESCRIPTION:
XS GIS Cut Line= 3
      2401342.41      7032762.67       2401471.4      7032762.67
      2401871.99      7032569.09
#Sta/Elev= 30
  4751.1  566.82  4828.7  561.95  4924.1  554.14    4933  551.85  4941.1  552.41
  4946.7  548.88  4977.4  545.04  4999.6  544.09  5012.4   535.8  5012.7   535.3
  5016.4   535.8  5021.8  541.22  5031.5  548.28    5044  551.84  5104.8  556.11
  5127.4  556.71    5133  557.92    5144  557.81    5150  558.35  5155.6  560.41
  5172.6  560.04  5178.2   561.2  5217.8  562.59  5223.4  565.05  5240.4  565.56
    5246  566.71    5255   565.6    5263  565.93  5299.5  571.19    5325  573.42
#Mann= 4 ,-1 , 0
  4751.1     .05       0  4828.7     .12       0  5012.4     .07       0
  5016.4     .12       0
Bank Sta=5012.4,5016.4
XS Rating Curve= 0 ,0
Exp/Cntr=0.3,0.1

Type RM Length L Ch R = 1 ,11581   ,338,338,338
BEGIN DESCRIPTION:
Farris Branch 17.0
END DESCRIPTION:
XS GIS Cut Line= 3
      2401369.23       7032824.5      2401673.03      7032883.64
      2402094.56      7032776.25
#Sta/Elev= 30
  4580.1  565.54  4583.8  564.79  4635.5  562.56  4664.3  559.91  4712.3   556.7
    4804  552.97    4937  550.54  4957.7  547.53    4964  545.37  4969.1  539.51
  4986.6  535.61  4986.9  535.11  4990.6  535.61    4999   535.7    5010  549.75
  5019.6  551.54  5029.9  550.52  5040.2  551.68  5045.8  550.59  5050.9  554.67
  5060.9  553.88  5071.2  558.29  5086.6   560.3  5122.4  562.47  5133.1  564.34
  5215.7   571.2  5236.3  573.74  5289.5  575.56  5308.5  575.35  5324.6  573.99
#Mann= 5 ,-1 , 0
  4580.1     .05       0  4664.3     .12       0  4986.6     .07       0
  4990.6     .12       0  5289.5     .05       0
Bank Sta=4986.6,4990.6
XS Rating Curve= 0 ,0
Exp/Cntr=0.3,0.1

Type RM Length L Ch R = 1 ,11243   ,155,155,155
BEGIN DESCRIPTION:
Farris Branch 16.2
END DESCRIPTION:
XS GIS Cut Line= 4
      2401156.82      7033168.62      2401533.23      7033106.78
      2401713.35      7033044.94      2402019.86      7033012.68
#Sta/Elev= 30
  4545.6  567.25  4560.1  567.09  4570.5  564.55  4626.7  565.33  4631.8   561.2
    4688  563.11    4693  559.99  4749.2  561.77  4754.3  558.74  4810.4  560.46
  4815.5  556.24    4862  555.26  4927.1  550.75  4936.9  547.37  4954.3  543.25
  4966.7  536.46  4992.7   535.6    4998  537.62  5017.7  535.38    5024  539.29
  5027.1  535.35  5027.5  534.85  5031.5  535.35  5038.9  541.28  5117.4  545.49
  5210.6  558.19    5274  564.09  5354.4  567.67  5425.4  567.38  5425.7  567.38
#Mann= 6 ,-1 , 0
  4545.6     .05       0  4560.1    .075       0  4936.9     .05       0
  5027.1     .05       0  5031.5     .05       0  5425.4     .12       0
Bank Sta=5027.1,5031.5
XS Rating Curve= 0 ,0
Exp/Cntr=0.3,0.1

Type RM Length L Ch R = 1 ,11088   ,296,296,296
BEGIN DESCRIPTION:
Farris Branch 16.0
END DESCRIPTION:
XS GIS Cut Line= 3
      2401312.79      7033278.83      2401576.25      7033225.06
      2401915.87      7033171.58
#Sta/Elev= 30
  4622.9  569.65  4649.7  569.59  4693.8  568.43  4739.2  563.51  4744.3  564.09
  4789.8  560.88    4864  554.02  4890.6  550.65  4895.9  550.54  4924.9  545.39
  4945.2   541.3  4963.2  534.27  4963.6  533.77  4967.2  533.77  4967.6  534.27
  4975.6  535.63  4985.7  539.03  5005.9  541.01  5026.2  545.36  5046.4  547.34
  5107.2  550.97  5127.4  551.63  5137.5   553.4  5157.8  554.31    5178  560.35
  5188.1  561.61  5198.3  562.07  5213.5  561.84  5218.6  565.25  5235.6  564.57
#Mann= 3 ,-1 , 0
  4622.9    .075       0  4963.2     .07       0  4967.6    .075       0
Bank Sta=4963.2,4967.6
XS Rating Curve= 0 ,0
Exp/Cntr=0.3,0.1

Type RM Length L Ch R = 1 ,10792   ,392,392,392
BEGIN DESCRIPTION:
Farris Branch 15.0
END DESCRIPTION:
XS GIS Cut Line= 3
      2401689.13       7033520.8      2401904.22      7033383.68
      2401944.28      7033162.05
#Sta/Elev= 30
  4671.1  559.64  4695.8  557.65    4711  557.52  4736.9  557.71  4742.9  556.38
  4779.2  553.52  4809.7  552.77  4903.7  547.94  4918.9  546.05  4924.8  543.33
  4930.6   542.8  4950.2  537.72  4960.4  533.97  4968.4  533.11  4968.8  532.61
  4972.8  533.11  4978.4  537.61  4990.9  538.51    5001  538.09  5011.2  540.85
  5031.5   547.5    5037   551.6  5042.1   550.7  5072.2  554.63  5101.5  555.77
  5112.8  557.14    5123  556.93  5143.3   563.1  5149.1  565.93  5151.4  565.47
#Mann= 6 ,-1 , 0
  4671.1     .12       0  4695.8     .05       0    4711     .12       0
  4968.4     .07       0  4972.8     .12       0  5101.5     .05       0
Bank Sta=4968.4,4972.8
XS Rating Curve= 0 ,0
Exp/Cntr=0.3,0.1

Type RM Length L Ch R = 1 ,10400   ,103,103,103
BEGIN DESCRIPTION:
Farris Branch 14.5
END DESCRIPTION:
XS GIS Cut Line= 3
      2401968.76      7033641.75      2402251.02      7033544.98
      2402307.28      7033113.62
#Sta/Elev= 30
  4616.1  555.98  4697.1  553.59  4722.1   551.7  4753.8  548.21  4790.9  546.56
  4859.5  545.46  4870.1  544.38  4914.5  543.39  4949.8   543.6  4959.8  541.26
  4969.9  536.89    4980  536.14  4990.1  536.57  5000.2  535.58  5015.1  532.88
  5018.2  530.93  5018.6  530.43  5022.6  530.93  5040.5  539.22  5050.6  541.79
  5070.8   546.7  5080.9   547.2    5101  550.44  5151.5  553.64  5181.7  556.76
  5232.1  557.96  5262.4   560.2  5282.6  560.44  5340.6  563.99  5349.5   564.8
#Mann= 4 ,-1 , 0
  4616.1     .12       0  5018.2     .07       0  5022.6     .12       0
  5340.6    .075       0
Bank Sta=5018.2,5022.6
XS Rating Curve= 0 ,0
Exp/Cntr=0.3,0.1

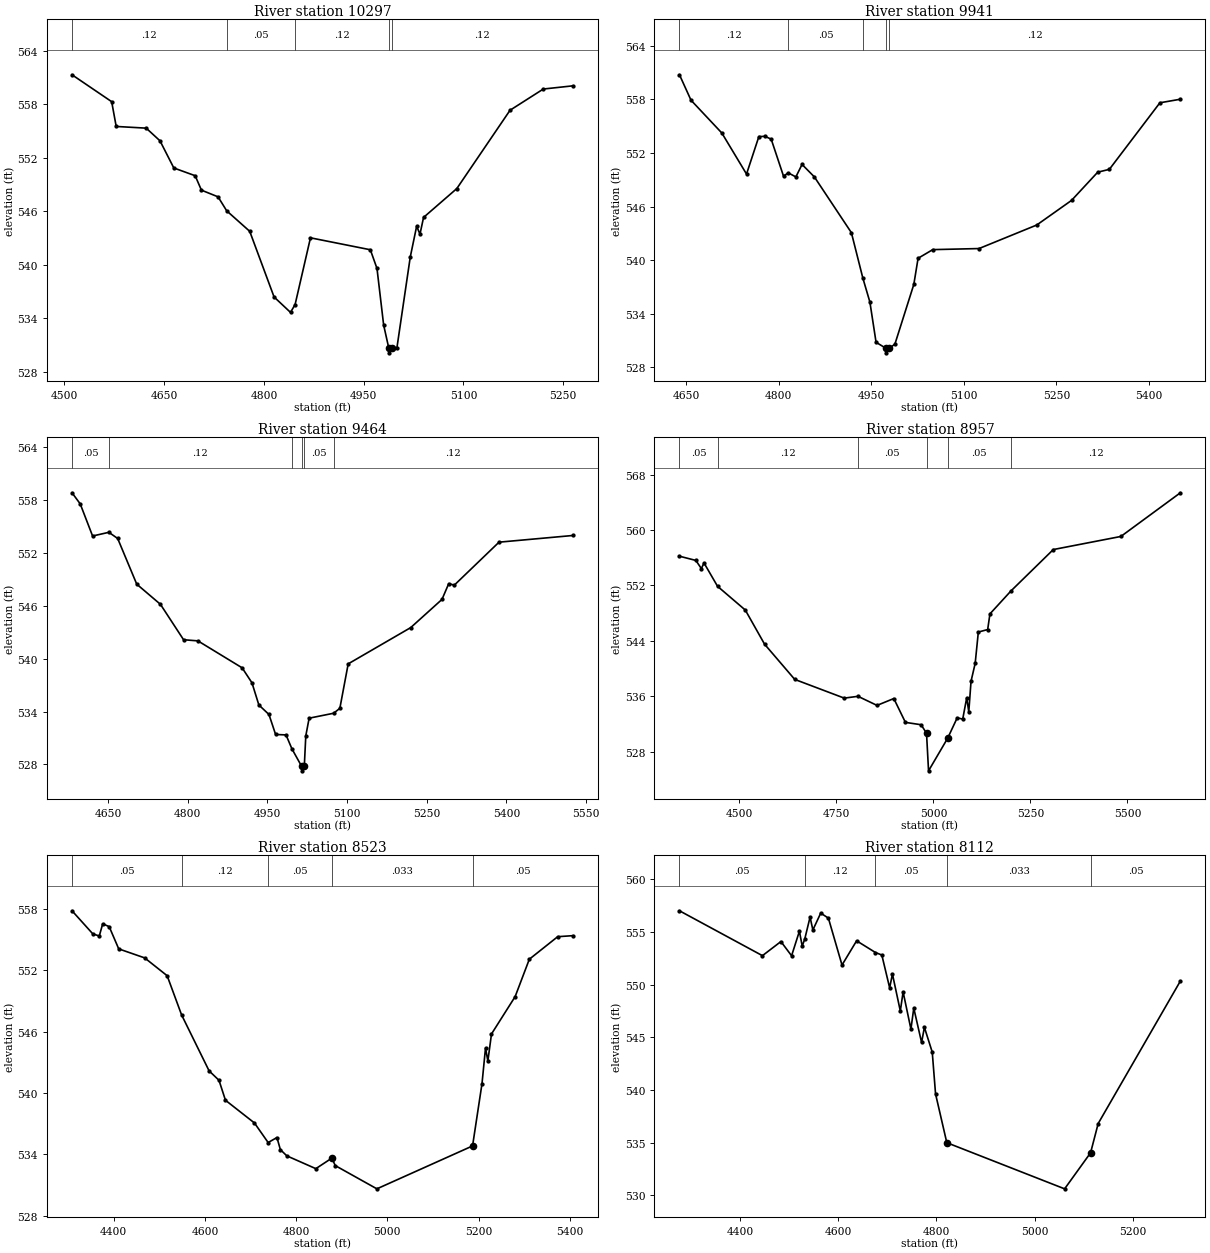
Type RM Length L Ch R = 1 ,10297   ,356,356,356
BEGIN DESCRIPTION:
Farris Branch 14.0
END DESCRIPTION:
XS GIS Cut Line= 3
      2402285.96      7033937.49      2402366.62      7033644.45
      2402361.24      7033195.52
#Sta/Elev= 30
  4511.6  561.33  4571.2  558.31    4578  555.53  4623.1  555.34  4643.8  553.92
  4664.6  550.87  4696.7     550  4706.1  548.38  4731.1  547.63  4744.1  546.06
  4778.7  543.76  4815.3  536.39    4840  534.66  4846.9  535.54    4870  543.03
    4960  541.69    4970  539.59    4980  533.24  4987.8  530.62  4988.2  530.12
  4992.2  530.62    5000  530.71    5020  540.87  5029.6  544.33  5034.6  543.44
    5040  545.32    5090  548.56    5170  557.35    5220  559.73  5264.5  560.09
#Mann= 5 ,-1 , 0
  4511.6     .12       0  4744.1     .05       0  4846.9     .12       0
  4987.8     .07       0  4992.2     .12       0
Bank Sta=4987.8,4992.2
XS Rating Curve= 0 ,0
Exp/Cntr=0.3,0.1

Type RM Length L Ch R = 1 ,9941    ,477,477,477
BEGIN DESCRIPTION:
Farris Branch 13.0
END DESCRIPTION:
XS GIS Cut Line= 3
       2402694.6      7033918.65      2402697.29      7033593.37
      2402595.12      7033117.51
#Sta/Elev= 30
  4638.9  560.77  4657.6  557.92  4707.6  554.24  4747.6  549.64  4767.6  553.84
  4777.6  553.87  4787.6  553.55  4807.6   549.4  4815.1  549.78  4827.6  549.32
  4837.6  550.72  4857.6  549.32  4917.6  543.07  4936.2  537.97  4947.6  535.29
  4957.6  530.78  4973.9   530.1  4974.5   529.6  4978.7   530.1  4988.1  530.57
  5018.8  537.27  5025.7   540.2  5049.5  541.17  5124.5  541.29  5218.1  543.93
  5274.5  546.69  5316.9  549.85  5335.8  550.17  5417.7  557.63  5450.9  558.03
#Mann= 5 ,-1 , 0
  4638.9     .12       0  4815.1     .05       0  4936.2     .12       0
  4973.9     .07       0  4978.7     .12       0
Bank Sta=4973.9,4978.7
XS Rating Curve= 0 ,0
Exp/Cntr=0.3,0.1

Type RM Length L Ch R = 1 ,9464    ,507,507,507
BEGIN DESCRIPTION:
Farris Branch 12.0
END DESCRIPTION:
XS GIS Cut Line= 3
      2403069.69      7033895.27      2403099.78      7033639.51
      2402889.17      7032987.62
#Sta/Elev= 30
  4582.5  558.85  4597.9  557.59  4621.2  553.94  4651.8  554.36  4668.4  553.66
  4704.3  548.47  4748.9  546.18  4792.4  542.16  4819.4  542.03  4902.6  538.97
  4921.1  537.27  4934.1  534.75  4953.1  533.67  4965.6   531.4  4985.2  531.35
  4996.3  529.77  5014.7  527.77  5015.3  527.27  5019.6  527.77  5022.4  531.24
  5028.7  533.25  5074.7  533.81  5086.5  534.37  5102.2  539.42  5219.9  543.54
  5278.7  546.74  5291.4  548.53  5301.9  548.36    5386  553.24  5525.1     554
#Mann= 6 ,-1 , 0
  4582.5     .05       0  4651.8     .12       0  4996.3     .05       0
  5014.7    .033       0  5019.6     .05       0  5074.7     .12       0
Bank Sta=5014.7,5019.6
XS Rating Curve= 0 ,0
Exp/Cntr=0.3,0.1

Type RM Length L Ch R = 1 ,8957    ,434,434,434
BEGIN DESCRIPTION:
Farris Branch 11.0
END DESCRIPTION:
XS GIS Cut Line= 3
      2403094.73      7033915.35      2403460.83      7033514.14
      2403731.61      7032817.12
#Sta/Elev= 30
  4345.4  556.22  4387.7  555.61  4401.8  554.43  4408.6  555.25  4443.5  551.88
  4515.1  548.45  4564.7  543.53  4642.4  538.45    4770  535.75  4805.5  536.01
  4854.5   534.7  4897.8  535.69  4927.7  532.25  4968.1  531.91  4982.1  530.69
  4987.3  525.26  5036.6  529.97  5061.1   532.9  5075.4  532.73  5085.7  535.81
    5091  533.77  5096.8  538.18  5107.5  540.77  5115.6  545.28  5139.7  545.64
  5145.5   547.9  5199.7  551.21  5308.8  557.18    5483  559.07  5636.3  565.37
#Mann= 6 ,-1 , 0
  4345.4     .05       0  4443.5     .12       0  4805.5     .05       0
  4982.1    .033       0  5036.6     .05       0  5199.7     .12       0
Bank Sta=4982.1,5036.6
XS Rating Curve= 0 ,0
Exp/Cntr=0.3,0.1

Type RM Length L Ch R = 1 ,8523    ,411,411,411
BEGIN DESCRIPTION:
Farris Branch 10.0
END DESCRIPTION:
XS GIS Cut Line= 3
      2403144.89      7034060.75      2403601.24      7033654.55
      2404071.15      7033524.58
#Sta/Elev= 30
  4308.5  557.79  4354.2  555.53  4368.3  555.33  4375.8  556.52    4390  556.24
  4410.9  554.07  4467.8  553.19  4517.1  551.45  4548.8  547.62  4609.1  542.16
  4630.8  541.24    4645  539.29  4708.6  537.07  4738.6  535.16  4757.9  535.65
  4765.4  534.47  4779.6  533.86  4843.2  532.61  4878.3  533.64  4885.8  532.91
  4977.1  530.64  5186.9  534.83  5207.6  540.91  5215.3  544.39  5220.5  543.13
  5228.4  545.76  5280.3  549.41  5311.4  553.06  5373.6  555.26    5407  555.36
#Mann= 5 ,-1 , 0
  4308.5     .05       0  4548.8     .12       0  4738.6     .05       0
  4878.3    .033       0  5186.9     .05       0
Bank Sta=4878.3,5186.9
XS Rating Curve= 0 ,0
Exp/Cntr=0.3,0.1

Type RM Length L Ch R = 1 ,8112    ,407,407,407
BEGIN DESCRIPTION:
Farris Branch 9.0
END DESCRIPTION:
XS GIS Cut Line= 3
       2403144.9      7034366.63        2403779.        7034010.
      2404029.04      7033859.98
#Sta/Elev= 30
  4277.1  557.01  4445.9  552.75  4483.5  554.09  4505.2  552.74  4521.1  555.07
  4526.8  553.66  4531.9  554.31  4542.8  556.41  4548.5  555.19  4564.5  556.79
  4580.1  556.31  4607.8  551.86  4637.5  554.16  4675.8  553.05  4688.8  552.81
  4704.7   549.7  4710.4     551  4726.4   547.5  4732.1  549.31    4748  545.78
  4753.8  547.77  4769.7  544.51  4775.4  545.95  4791.4  543.59  4798.1  539.63
    4821     535  5060.7  530.62  5113.5  534.04    5129  536.82  5296.2  550.34
#Mann= 5 ,-1 , 0
  4277.1     .05       0  4531.9     .12       0  4675.8     .05       0
    4821    .033       0  5113.5     .05       0
Bank Sta=4821,5113.5
XS Rating Curve= 0 ,0
Exp/Cntr=0.3,0.1