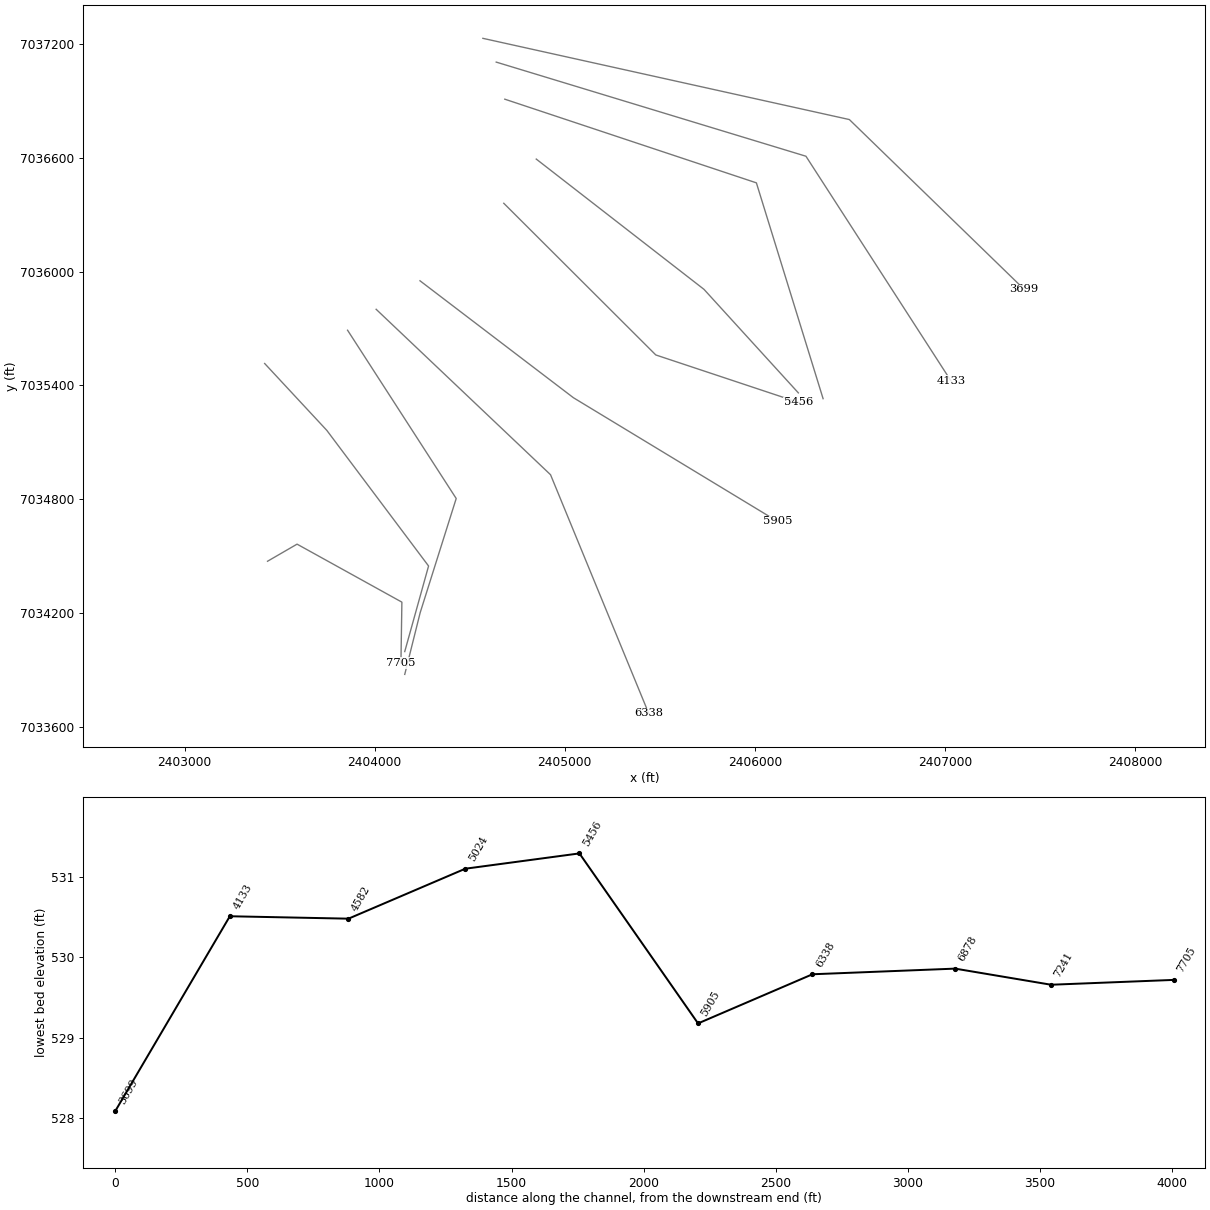
HEC-RAS study Farris Branch.prj: Farris Branch Base Level Engineering

--- Farris Branch.g01 (geometry) --- (continued)

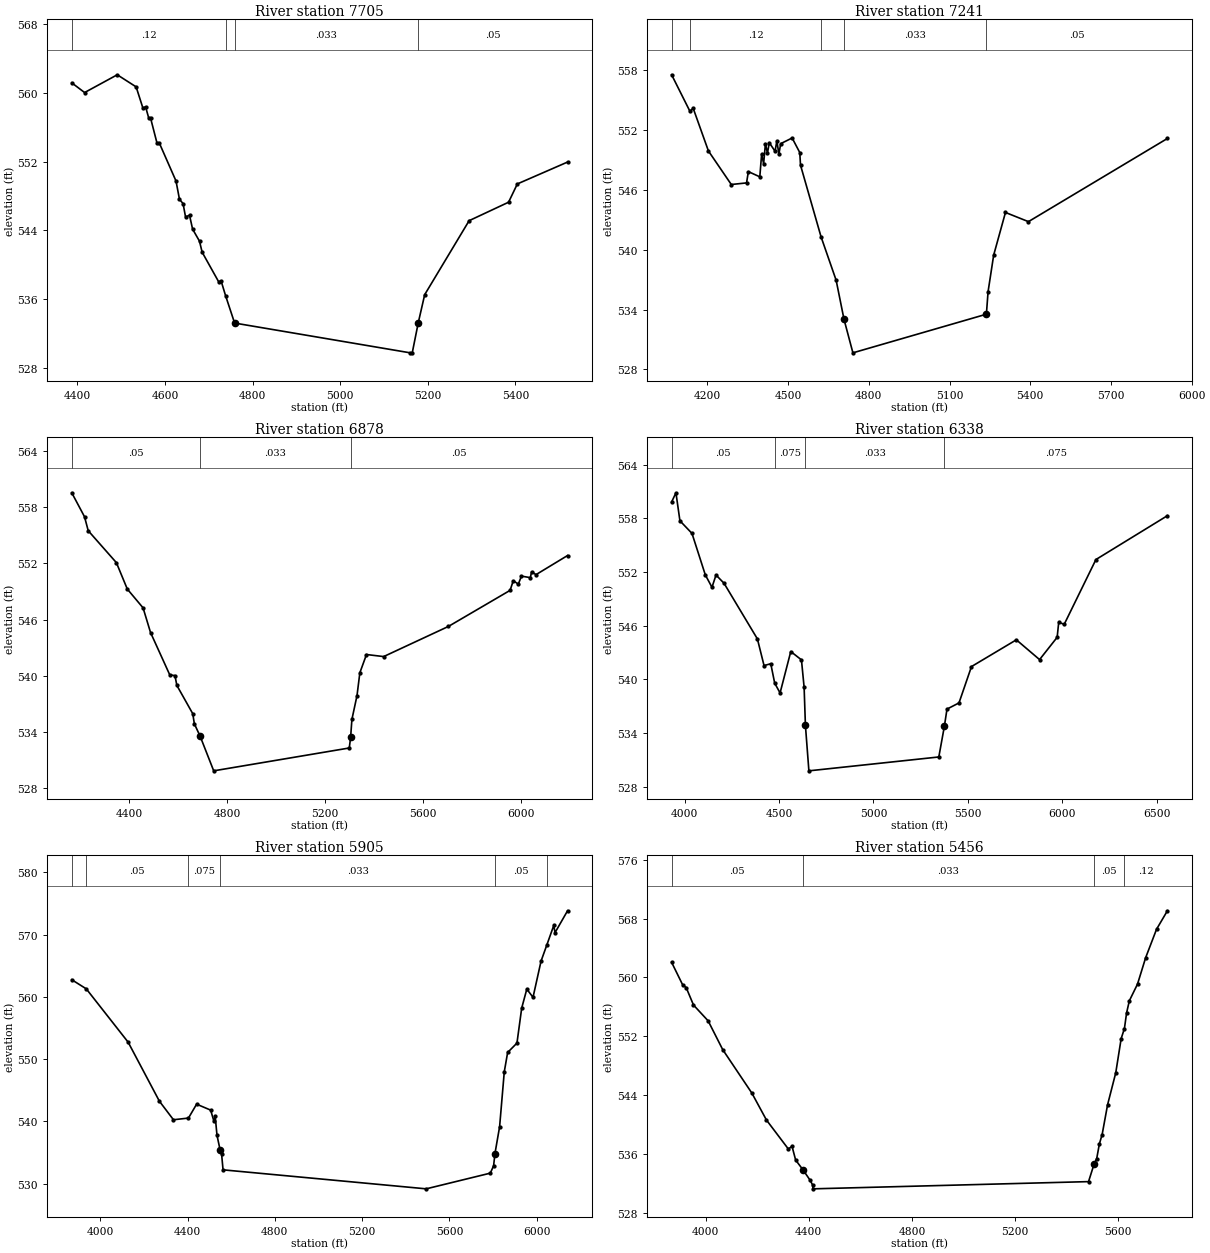
Type RM Length L Ch R = 1 ,7705    ,464,464,464
BEGIN DESCRIPTION:
Farris Branch 8.5
END DESCRIPTION:
XS GIS Cut Line= 4
      2403435.79      7034471.95      2403591.21      7034562.19
      2404142.81       7034256.3       2404137.8       7033935.4
#Sta/Elev= 30
  4387.5  561.18  4416.8  560.05  4491.3  562.12  4534.4  560.71  4550.1   558.2
  4555.9   558.4    4563   557.1  4567.2   557.1  4581.9  554.18  4587.7  554.12
  4625.4  549.74  4633.3  547.61  4641.5  547.11  4647.2  545.54  4656.2  545.76
  4663.2  544.14    4679  542.73    4685  541.45  4722.7     538  4728.4  538.08
  4738.4   536.4  4759.1  533.19    5160  529.72  5164.5  529.72  5178.2  533.22
  5192.9   536.5  5294.3  545.12  5384.3  547.27  5404.3   549.4  5518.9  551.95
#Mann= 4 ,-1 , 0
  4387.5     .12       0  4738.4     .05       0  4759.1    .033       0
  5178.2     .05       0
Bank Sta=4759.1,5178.2
XS Rating Curve= 0 ,0
Exp/Cntr=0.3,0.1

Type RM Length L Ch R = 1 ,7241    ,363,363,363
BEGIN DESCRIPTION:
Farris Branch 8.0
END DESCRIPTION:
XS GIS Cut Line= 4
      2403420.71      7035514.97      2403747.74      7035162.26
      2404283.22      7034446.86      2404157.86      7033995.55
#Sta/Elev= 30
  4066.8  557.51  4134.9  553.85  4146.9  554.16  4203.6  549.88  4288.6  546.52
  4345.3  546.68  4352.1  547.81  4394.6  547.29  4401.4  549.56  4408.8  548.61
  4415.6  550.61    4423  549.65  4429.8  550.71  4451.3  549.85  4458.1   550.9
  4465.5  549.56  4472.3  550.61  4514.8  551.18  4543.2  549.72  4545.9  548.46
  4622.3  541.28  4678.4  536.93  4707.6  533.02  4740.7  529.66  5236.9  533.53
  5243.2  535.79    5264  539.45  5307.8  543.72  5393.2   542.8  5909.8  551.13
#Mann= 5 ,-1 , 0
  4066.8     .05       0  4134.9     .12       0  4622.3     .05       0
  4707.6    .033       0  5236.9     .05       0
Bank Sta=4707.6,5236.9
XS Rating Curve= 0 ,0
Exp/Cntr=0.3,0.1

Type RM Length L Ch R = 1 ,6878    ,540,540,540
BEGIN DESCRIPTION:
Farris Branch 7.0
END DESCRIPTION:
XS GIS Cut Line= 4
        2403857.      7035690.44      2404428.65      7034802.89
      2404239.08      7034200.83      2404157.86      7033875.22
#Sta/Elev= 30
  4166.1  559.55  4218.1  556.99  4233.2   555.5  4348.1  552.09  4392.6  549.27
    4457  547.26  4487.4  544.63    4566   540.1  4587.1  540.03  4594.8  538.98
  4659.7  535.96  4666.2  534.88    4690  533.54  4745.1  529.86  5298.2   532.3
  5303.7  533.45  5308.9  535.35  5329.7  537.89  5341.3  540.33  5368.4  542.28
  5438.4  542.06  5702.7  545.28  5954.2  549.13  5967.2  550.16  5987.8   549.8
  6000.6  550.65  6036.8  550.49  6041.9  551.11    6060  550.81  6188.6  552.85
#Mann= 3 ,-1 , 0
  4166.1     .05       0    4690    .033       0  5303.7     .05       0
Bank Sta=4690,5303.7
XS Rating Curve= 0 ,0
Exp/Cntr=0.3,0.1

Type RM Length L Ch R = 1 ,6338    ,433,433,433
BEGIN DESCRIPTION:
Farris Branch 6.0
END DESCRIPTION:
XS GIS Cut Line= 3
       2404007.4      7035800.81      2404925.09      7034928.26
      2405441.59      7033669.61
#Sta/Elev= 30
  3930.5  559.83  3953.4  560.86  3974.5  557.73  4038.4  556.32  4109.1  551.68
  4144.3   550.3  4165.8  551.67  4208.2  550.75    4385  544.53  4420.2  541.55
  4455.8  541.76  4476.6  539.59  4505.1  538.49  4561.8  543.12  4618.4  542.19
  4632.5  539.13  4639.4  534.87  4657.8  529.79  5346.2  531.34  5375.8  534.79
  5389.5  536.69  5453.1  537.38  5519.2  541.44    5757  544.43    5880  542.22
  5973.2  544.71  5981.4  546.38  6010.8  546.17  6178.6   553.4  6557.3   558.3
#Mann= 4 ,-1 , 0
  3930.5     .05       0  4476.6    .075       0  4639.4    .033       0
  5375.8    .075       0
Bank Sta=4639.4,5375.8
XS Rating Curve= 0 ,0
Exp/Cntr=0.3,0.1

Type RM Length L Ch R = 1 ,5905    ,449,449,449
BEGIN DESCRIPTION:
Farris Branch 5.0
END DESCRIPTION:
XS GIS Cut Line= 3
      2404238.13       7035951.2      2405045.44      7035334.44
       2406118.6      7034682.52
#Sta/Elev= 30
  3869.6  562.75    3936  561.29  4127.8  552.73  4271.1  543.25  4335.5  540.27
  4404.2  540.54  4441.6  542.77    4506  541.82  4520.5  540.08  4526.8  540.81
    4535  537.78  4549.6  535.37  4555.9  534.83  4562.8  532.23  5493.5  529.18
  5787.3   531.7  5802.4  532.88  5808.6  534.85  5829.9  539.15  5851.3  547.97
  5866.7  551.07  5909.4  552.58  5931.1  558.19  5954.5  561.24    5983  559.93
  6019.8  565.74  6046.7  568.37    6078  571.46  6083.8  570.31  6141.2  573.82
#Mann= 6 ,-1 , 0
  3869.6    .075       0    3936     .05       0  4404.2    .075       0
  4549.6    .033       0  5808.6     .05       0  6046.7     .12       0
Bank Sta=4549.6,5808.6
XS Rating Curve= 0 ,0
Exp/Cntr=0.3,0.1

Type RM Length L Ch R = 1 ,5456    ,432,432,432
BEGIN DESCRIPTION:
Farris Branch 4.0
END DESCRIPTION:
XS GIS Cut Line= 3
      2404679.01      7036359.99        2405479.        7035560.
      2406228.97      7035310.01
#Sta/Elev= 30
  3868.6  562.05    3911  559.02  3925.2  558.61  3953.4  556.25    4010  554.11
  4066.6   550.2  4179.7  544.29  4236.3  540.63  4321.1   536.7  4335.3  537.07
  4349.4   535.2  4377.7  533.88    4406  532.43  4415.5  531.79  4416.8  531.29
  5484.8  532.27  5505.9  534.61  5516.5  535.41    5527  537.42  5537.5  538.66
  5558.6  542.71  5590.3  547.05  5611.3   551.7  5623.9  553.06  5632.4   555.2
    5643  556.83  5674.6  559.09  5706.2  562.68  5748.4  566.54  5790.5  569.05
#Mann= 4 ,-1 , 0
  3868.6     .05       0  4377.7    .033       0  5505.9     .05       0
  5623.9     .12       0
Bank Sta=4377.7,5505.9
XS Rating Curve= 0 ,0
Exp/Cntr=0.3,0.1

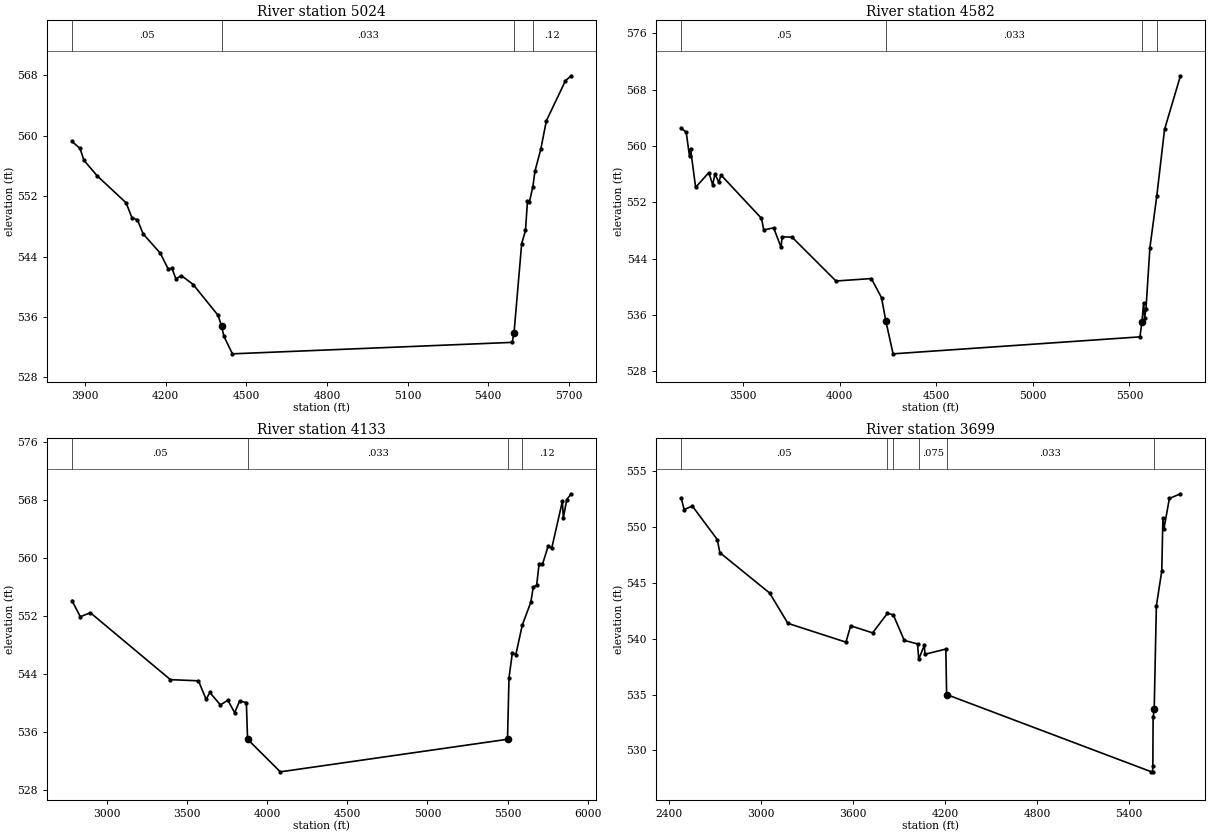
Type RM Length L Ch R = 1 ,5024    ,442,442,442
BEGIN DESCRIPTION:
Farris Branch 3.0
END DESCRIPTION:
XS GIS Cut Line= 3
      2404849.86      7036593.11      2405732.44       7035906.1
      2406229.03      7035359.97
#Sta/Elev= 30
  3851.7  559.26  3881.7  558.33  3896.2  556.76    3946  554.68  4053.4  551.11
  4074.5  549.16  4095.3  548.85  4116.7  546.99  4180.3  544.44  4209.3  542.37
  4223.8  542.42  4238.2  541.05    4259  541.47  4302.5  540.29  4395.5  536.19
  4408.3  534.75  4416.5  533.46  4448.4   531.1    5489  532.62  5495.7  533.89
  5524.1  545.69  5538.3  547.47  5545.7  551.36  5552.5  551.17  5565.9  553.28
  5573.4   555.3  5595.1  558.21    5616     562    5687  567.31  5708.3  567.96
#Mann= 4 ,-1 , 0
  3851.7     .05       0  4408.3    .033       0  5495.7     .05       0
  5565.9     .12       0
Bank Sta=4408.3,5495.7
XS Rating Curve= 0 ,0
Exp/Cntr=0.3,0.1

Type RM Length L Ch R = 1 ,4582    ,449,449,449
BEGIN DESCRIPTION:
Farris Branch 2.0
END DESCRIPTION:
XS GIS Cut Line= 3
      2404684.35      7036909.03      2406008.24      7036467.74
      2406359.26      7035329.43
#Sta/Elev= 30
  3177.9  562.52  3203.9  561.95    3221  558.52  3226.3  559.63  3252.6  554.12
  3321.1  556.21  3340.9  554.49  3352.7     556  3372.5  554.88  3384.4  555.86
  3593.9  549.72  3605.7  548.07  3657.1  548.37  3695.3   545.6  3700.6  547.09
    3752  547.05  3979.9  540.82  4163.1  541.17  4215.8  538.46  4238.2  535.14
  4275.7  530.48  5554.7  532.89  5565.2  535.04  5573.7  537.74    5579  535.63
  5586.1  536.91  5606.4  545.57  5641.9  552.88  5682.2  562.34  5764.6  569.96
#Mann= 4 ,-1 , 0
  3177.9     .05       0  4238.2    .033       0  5565.2     .05       0
  5641.9     .12       0
Bank Sta=4238.2,5565.2
XS Rating Curve= 0 ,0
Exp/Cntr=0.3,0.1

Type RM Length L Ch R = 1 ,4133    ,434,434,434
BEGIN DESCRIPTION:
Farris Branch 1.5
END DESCRIPTION:
XS GIS Cut Line= 3
      2404639.25      7037104.59        2406269.      7036608.14
      2407031.14      7035424.82
#Sta/Elev= 30
  2784.3  554.13  2836.3   551.9    2899  552.45  3398.1  543.22  3572.7  543.06
  3620.3  540.51  3643.7  541.45  3709.3  539.74  3756.2  540.38    3798  538.67
  3829.4  540.28  3871.2  540.05  3878.8     535  4082.8  530.51  5498.6     535
  5507.9  543.49    5529  546.94  5550.1  546.63  5590.7  550.75  5643.9   553.9
  5659.1  555.99  5680.2  556.22  5695.4   559.2  5716.5  559.12  5752.8   561.7
  5773.9  561.32  5840.6  567.82  5846.5  565.52  5867.7  568.05  5895.5  568.85
#Mann= 4 ,-1 , 0
  2784.3     .05       0  3878.8    .033       0  5498.6     .05       0
  5590.7     .12       0
Bank Sta=3878.8,5498.6
XS Rating Curve= 0 ,0
Exp/Cntr=0.3,0.1

Type RM Length L Ch R = 1 ,3699    ,0,0,0
BEGIN DESCRIPTION:
Farris Branch 1.0
END DESCRIPTION:
XS GIS Cut Line= 3
      2404569.04      7037229.96      2406497.44      7036801.58
      2407417.35      7035906.09
#Sta/Elev= 30
  2477.7  552.57  2496.8  551.53  2550.6  551.84  2713.3  548.85  2729.9  547.68
  3055.2  544.07  3174.2  541.36  3553.3  539.68    3584  541.14  3727.4  540.51
  3824.3  542.26  3862.8  542.11  3933.7  539.84  4020.8  539.52  4028.4  538.15
  4064.4  539.39  4069.5   538.6  4205.3  539.06  4210.4     535  5547.7  528.09
  5555.3  528.09  5556.7  528.59  5558.4  532.96  5565.6   533.7  5579.7  542.93
    5615  546.04  5622.2  550.78  5629.2  549.81  5664.6  552.52  5736.9  552.94
#Mann= 6 ,-1 , 0
  2477.7     .05       0  3824.3    .075       0  3862.8     .05       0
  4028.4    .075       0  4210.4    .033       0  5565.6     .05       0
Bank Sta=4210.4,5565.6
XS Rating Curve= 0 ,0
Exp/Cntr=0.3,0.1

Chan Stop Cuts=-1
Use User Specified Reach Order=0
Composite Channel Slope=5