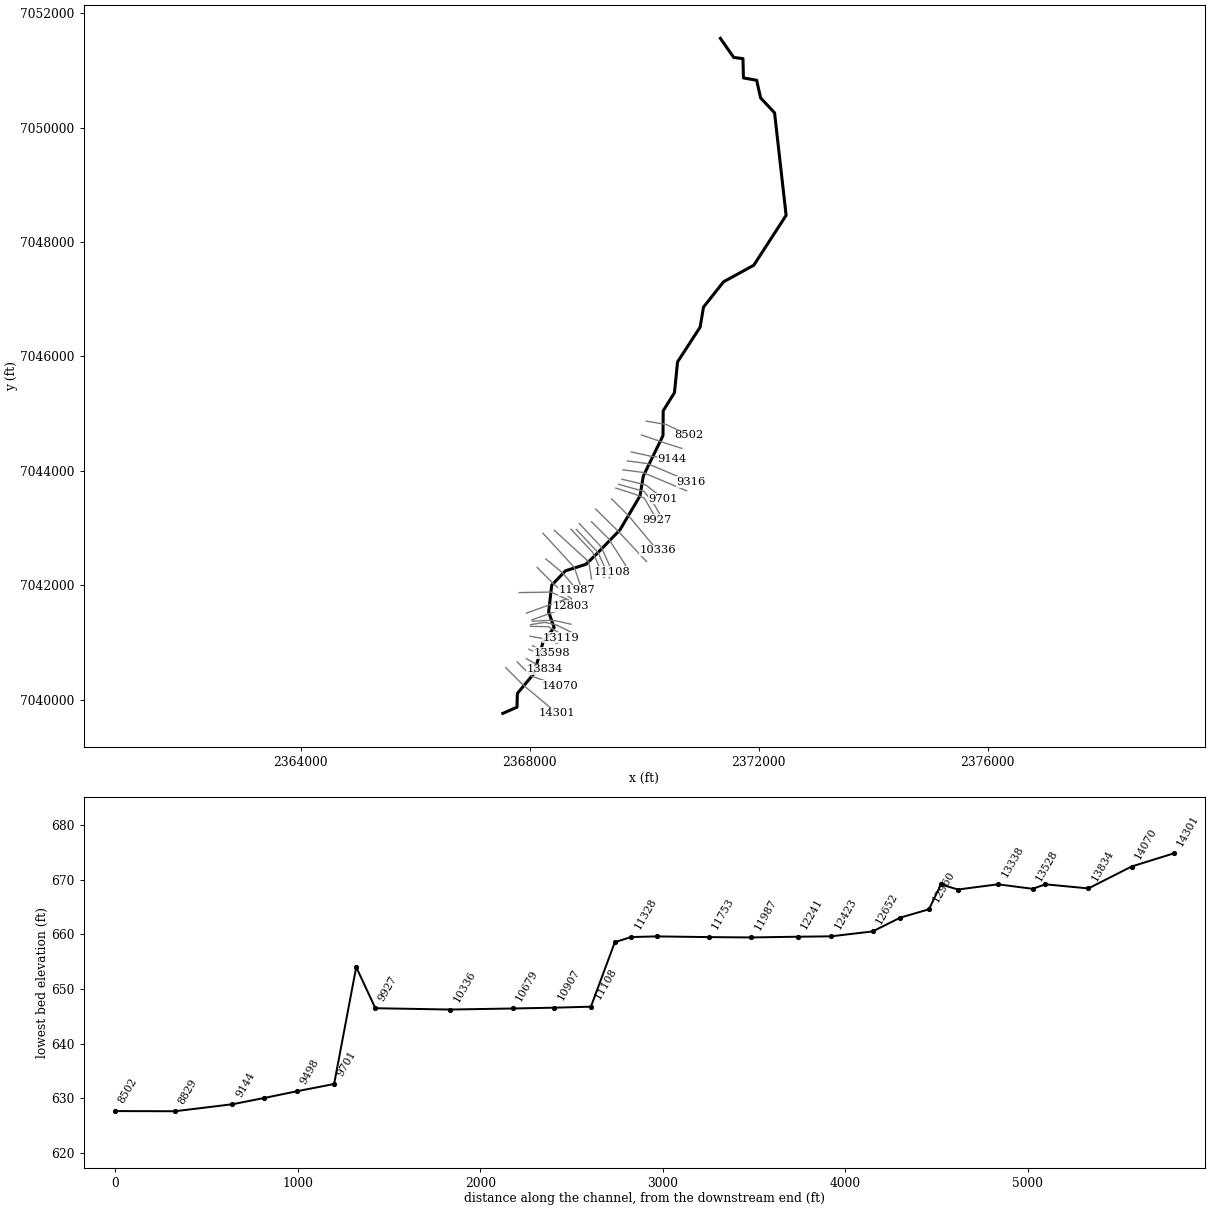
--- Golf Course Creek Tr 1.prj (project) ---

Proj Title=Golf Course Creek Tr 1 Base Level Engineering
Current Plan=p01
Default Exp/Contr=0.3,0.1
English Units
Geom File=g01
Flow File=f01
Plan File=p01
Y Axis Title=Elevation
X Axis Title(PF)=Main Channel Distance
X Axis Title(XS)=Station
BEGIN DESCRIPTION:
Golf Course Creek Tr 1
END DESCRIPTION:
DSS Export Rating Curves= 0
DSS Export Rating Curve Sorted= 0
DSS Export Volume Flow Curves= 0
DXF OffsetX= 0
DXF OffsetY= 0
DXF ScaleX= 1
DXF ScaleY= 10

--- Golf Course Creek Tr 1.p01 (plan) ---

Plan Title=Multiple Run
Program Version=4.10
Short Identifier=Multiple
Geom File=g01
Flow File=f01
Subcritical Flow
K Sum by GR= 0
Std Step Tol= 0.01
Critical Tol= 0.01
Num of Std Step Trials= 20
Max Error Tol= 0.3
Flow Tol Ratio= 0.001
Split Flow NTrial= 30
Split Flow Tol= 0.02
Split Flow Ratio= 0.02
Log Output Level= 0
Friction Slope Method= 1
Unsteady Friction Slope Method= 2
Unsteady Bridges Friction Slope Method= 1
Parabolic Critical Depth
Global Vel Dist= 1 , 1 , 1
Global Log Level= 0
CheckData=True
Encroach Param=-1 ,0,0, 0
BEGIN DESCRIPTION:
Multiple Run
END DESCRIPTION:
Computation Interval=1HOUR
Output Interval=1HOUR
Run HTab= 0
Run UNet= 0
Run PostProcess= 0
Run WQNet= 0
UNET Theta= 1
UNET Theta Warmup= 1
UNET ZTol= 0.02
UNET ZSATol= 0.05
UNET MxIter= 20
UNET MaxInSteps= 0
UNET DtIC= 0
UNET DtMin= 0
UNET MaxCRTS= 20
UNET WFStab= 2
UNET SFStab= 1
UNET WFX= 1
UNET SFX= 1
UNET DSS MLevel= 4
UNET DZMax Abort= 100
UNET Convert EG Bridges= 0
UNET Use Existing IB Tables=-1
UNET Froude Reduction=False
UNET Froude Limit= 1
UNET Froude Power= 10
UNET Time Slicing=0,0, 5
UNET Junction Losses=0
Instantaneous Interval=1HOUR
Write IC File= 0
Write IC File at Sim End=0
Echo Input=False
Echo Parameters=False
Echo Output=False
Write Detailed= 0
WQ AD Non Conservative
WQ ULTIMATE=-1
WQ Max Comp Step=1HOUR
WQ Output Interval=15MIN
WQ Output Selected Increments= 0
WQ Output face flow=0
WQ Output face velocity=0
WQ Output face area=0
WQ Output face dispersion=0
WQ Output cell volume=0
WQ Output cell surface area=0
WQ Output cell continuity=0
WQ Output cumulative cell continuity=0
WQ Output face conc=0
WQ Output face dconc_dx=0
WQ Output face courant=0
WQ Output face peclet=0
WQ Output face adv mass=0
WQ Output face disp mass=0
WQ Output cell mass=0
WQ Output cell source sink temp=0
WQ Output cell source sink nsm=0
WQ Output MaxMinRange=-1
WQ Daily Max Min Mean=-1
WQ Daily Range=0
WQ Daily Time=0
WQ Create Restart=0
WQ Fixed Restart=0
WQ System Summary=0
WQ Use Fixed Temperature=0
Sorting and Armoring Iterations= 10
XS Update Threshold= 0.02
Hydraulics Update Threshold= 0.02
Energy Slope Method= 1
Volume Change Method= 0
XS Weighting Method= 0
Number of US Weighted Cross Sections= 1
Number of DS Weighted Cross Sections= 1
Upstream XS Weight=0.25
Main XS Weight=0.5
Downstream XS Weight=0.25
Number of DS XS's Weighted with US Boundary= 1
Upstream Boundary Weight= 1
Weight of XSs Associated with US Boundary= 0
Number of US XS's Weighted with DS Boundary= 1
Downstream Boundary Weight= 0.5
Weight of XSs Associated with DS Boundary= 0.5
Sediment Output Level= 4
Mass or Volume Output= 0
Output Increment Type= 1
Profile and TS Output Increment= 10
XS Output Flag= 0
XS Output Increment= 10
Disregard all LS=0
Disregard all Conn=0
Disregard all Breaches=0
Disregard all Pumps=0

--- Golf Course Creek Tr 1.f01 (steady flow) ---

Flow Title=Multiple
Number of Profiles=7
Profile Names=10-year,25-year,50-year,1pct_min,100-year,1pct_plu,500-year
River Rch & RM= Golf Course Cree,Reach-1,14301
     487     651     784     468     934    1863    1324
River Rch & RM= Golf Course Cree,Reach-1,10336
     803    1108    1361     829    1653    3299    2438
River Rch & RM= Golf Course Cree,Reach-1,4800
    1083    1523    1893    1165    2325    4640    3508
Boundary for River Rch & Prof#=Golf Course Cree,Reach-1,1
Up Type=0
Dn Type=3
Dn Slope=0.005
Boundary for River Rch & Prof#=Golf Course Cree,Reach-1,2
Up Type=0
Dn Type=3
Dn Slope=0.005
Boundary for River Rch & Prof#=Golf Course Cree,Reach-1,3
Up Type=0
Dn Type=3
Dn Slope=0.005
Boundary for River Rch & Prof#=Golf Course Cree,Reach-1,4
Up Type=0
Dn Type=3
Dn Slope=0.005
Boundary for River Rch & Prof#=Golf Course Cree,Reach-1,5
Up Type=0
Dn Type=3
Dn Slope=0.005
Boundary for River Rch & Prof#=Golf Course Cree,Reach-1,6
Up Type=0
Dn Type=3
Dn Slope=0.005
Boundary for River Rch & Prof#=Golf Course Cree,Reach-1,7
Up Type=0
Dn Type=3
Dn Slope=0.005

--- Golf Course Creek Tr 1.g01 (geometry) ---

Geom Title=Existing Conditions
Program Version=4.10

River Reach=Golf Course Cree,Reach-1
Reach XY= 30
        2367529.        7039760.      2367775.94      7039868.28
      2367782.75      7040108.45      2368073.48      7040457.56
      2368232.75      7041008.45      2368425.47      7041261.47
      2368328.96      7041529.98      2368382.84      7042001.38
      2368622.94      7042251.86       2368981.3      7042365.83
      2369202.81      7042583.15      2369573.38      7042965.62
      2369925.24      7043561.56      2369982.55      7043908.53
      2370326.73      7044615.94      2370330.19       7045049.5
      2370526.76      7045365.93      2370581.07      7045904.13
      2370975.26      7046511.52      2371034.42      7046862.67
      2371384.62      7047304.38      2371912.35      7047593.33
      2372477.38      7048466.03      2372275.46      7050258.54
      2372032.09      7050518.31      2371962.55      7050827.14
       2371731.9      7050867.91      2371723.59      7051204.82
      2371561.86      7051226.28        2371329.        7051560.

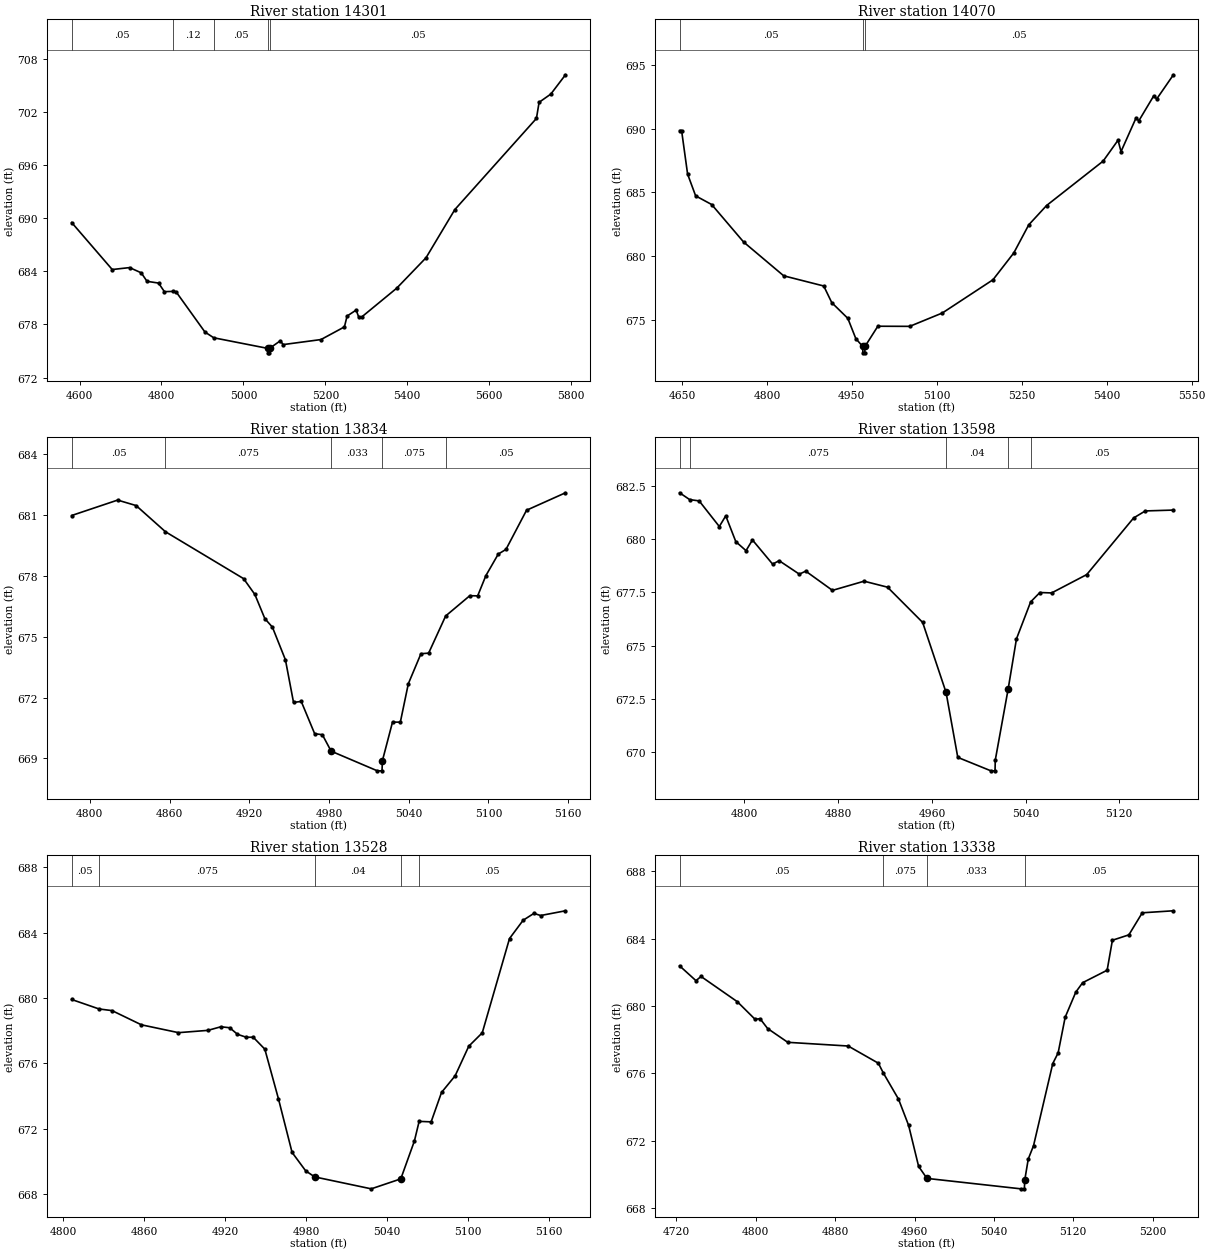
Type RM Length L Ch R = 1 ,14301   ,231,231,231
BEGIN DESCRIPTION:
Golf Course Creek Tr 1 40.0
END DESCRIPTION:
XS GIS Cut Line= 3
      2367578.99      7040560.01        2367879.        7040260.
        2368479.        7039760.
#Sta/Elev= 30
  4580.8  689.51  4679.8   684.2  4722.2  684.42  4750.5  683.83  4764.7  682.87
  4792.9  682.67  4807.1   681.7  4827.4  681.73  4835.4   681.7  4906.1  677.14
  4927.6  676.49  5059.7  675.29    5060  674.79  5063.5  674.79  5063.7  675.29
  5090.3  676.16  5096.8  675.72  5189.3  676.29  5246.5  677.72  5253.1  678.95
  5275.2  679.62  5281.7  678.79  5289.5  678.87  5374.1  682.09  5445.7  685.53
    5516  690.97  5715.2  701.27  5721.7  703.09  5750.3  704.02  5786.1   706.2
#Mann= 5 ,-1 , 0
  4580.8     .05       0  4827.4     .12       0  4927.6     .05       0
  5059.7    .033       0  5063.7     .05       0
Bank Sta=5059.7,5063.7
XS Rating Curve= 0 ,0
Exp/Cntr=0.3,0.1

Type RM Length L Ch R = 1 ,14070   ,236,236,236
BEGIN DESCRIPTION:
Golf Course Creek Tr 1 39.0
END DESCRIPTION:
XS GIS Cut Line= 3
      2367779.01      7040659.99        2368029.        7040410.
      2368520.44      7040245.14
#Sta/Elev= 30
  4645.9  689.85  4649.4  689.85    4660  686.43  4674.2  684.72  4702.5  684.04
    4759  681.09  4829.7  678.44  4900.4  677.64  4914.6  676.33  4942.9   675.1
    4957  673.51  4969.2  672.89  4969.4  672.39  4972.9  672.39  4973.2  672.89
  4995.9  674.48  5052.2  674.47  5109.8  675.52  5199.2  678.13    5236  680.24
  5262.3  682.44  5293.8  683.96  5393.7  687.45    5420  689.09  5425.3   688.2
  5451.5  690.81  5456.8  690.62  5483.1  692.58  5488.3  692.33  5517.8  694.23
#Mann= 3 ,-1 , 0
  4645.9     .05       0  4969.2    .033       0  4973.2     .05       0
Bank Sta=4969.2,4973.2
XS Rating Curve= 0 ,0
Exp/Cntr=0.3,0.1

Type RM Length L Ch R = 1 ,13834   ,236,236,236
BEGIN DESCRIPTION:
Golf Course Creek Tr 1 38.0
END DESCRIPTION:
XS GIS Cut Line= 3
      2367938.85      7040717.23        2368129.        7040610.
       2368260.2      7040530.52
#Sta/Elev= 30
  4786.3  680.97  4820.9  681.73  4834.8  681.46  4856.9  680.17  4915.7  677.86
  4924.2  677.08  4931.7  675.89  4937.4  675.47  4947.2  673.86  4953.3  671.76
  4959.1  671.81  4969.2  670.22    4975  670.17  4981.6  669.36  5016.4  668.39
  5019.9  668.39  5020.2  668.89  5027.8  670.79  5033.7  670.79  5039.7  672.68
  5049.2  674.16    5055  674.19  5067.8  676.02    5086  677.02  5091.9  677.01
  5098.1  678.01  5107.4  679.07  5113.2   679.3  5128.7  681.23    5158  682.09
#Mann= 5 ,-1 , 0
  4786.3     .05       0  4856.9    .075       0  4981.6    .033       0
  5020.2    .075       0  5067.8     .05       0
Bank Sta=4981.6,5020.2
XS Rating Curve= 0 ,0
Exp/Cntr=0.3,0.1

Type RM Length L Ch R = 1 ,13598   ,70,70,70
BEGIN DESCRIPTION:
Golf Course Creek Tr 1 37.2
END DESCRIPTION:
XS GIS Cut Line= 3
      2367985.57      7040880.55      2368118.36      7040817.74
      2368393.04      7040814.15
#Sta/Elev= 30
  4744.6  682.16  4753.2  681.84  4761.3  681.78  4778.5  680.58    4784  681.08
  4792.6  679.87  4801.3  679.45  4806.8  679.95    4824  678.82  4829.6  678.98
  4846.8  678.35  4852.3  678.49  4875.1  677.59  4902.1  678.02  4922.1  677.74
  4952.1  676.09  4972.1  672.81  4982.1  669.77  5010.4  669.14  5013.9  669.14
  5014.1  669.64  5025.1  672.97  5032.2  675.32  5044.3  677.05  5052.2  677.49
  5062.2  677.47  5092.2  678.33  5132.2  680.98  5142.2  681.31  5166.2  681.35
#Mann= 5 ,-1 , 0
  4744.6     .05       0  4753.2    .075       0  4972.1     .04       0
  5025.1    .075       0  5044.3     .05       0
Bank Sta=4972.1,5025.1
XS Rating Curve= 0 ,0
Exp/Cntr=0.3,0.1

Type RM Length L Ch R = 1 ,13528   ,190,190,190
BEGIN DESCRIPTION:
Golf Course Creek Tr 1 37.0
END DESCRIPTION:
XS GIS Cut Line= 3
      2368051.92      7040941.61      2368166.83      7040878.77
       2368400.2       7040907.5
#Sta/Elev= 30
  4806.2  679.91  4826.5  679.33  4836.1  679.23  4857.9  678.36  4885.4  677.88
  4907.2  678.02  4916.8  678.24  4923.4  678.18  4929.1  677.78  4935.6   677.6
  4940.8   677.6  4949.4  676.87  4959.5  673.83  4969.6  670.55  4979.7  669.42
  4986.4  669.05  5028.3  668.32  5050.2  668.93  5060.3  671.25  5063.8  672.45
  5072.7  672.42  5080.4  674.22  5090.5  675.24  5100.6  677.05  5110.6  677.87
  5130.8  683.64  5140.9  684.76  5148.9  685.18  5153.9  685.05  5172.3  685.34
#Mann= 5 ,-1 , 0
  4806.2     .05       0  4826.5    .075       0  4986.4     .04       0
  5050.2    .075       0  5063.8     .05       0
Bank Sta=4986.4,5050.2
XS Rating Curve= 0 ,0
Exp/Cntr=0.3,0.1

Type RM Length L Ch R = 1 ,13338   ,219,219,219
BEGIN DESCRIPTION:
Golf Course Creek Tr 1 36.0
END DESCRIPTION:
XS GIS Cut Line= 3
      2368001.67      7041108.54        2368279.        7041060.
      2368480.93       7040982.9
#Sta/Elev= 30
  4723.2  682.38  4739.7   681.5  4744.8  681.75  4781.4  680.25  4799.2  679.21
  4804.3  679.24  4811.9  678.66  4832.2  677.84  4893.1  677.62  4923.5   676.6
  4928.6  676.01  4943.8  674.47    4954  672.91  4964.1  670.47  4972.5  669.76
  5067.2  669.14  5070.7  669.14    5071  669.64  5074.6  670.91  5079.9   671.7
  5099.3  676.58  5104.7  677.21  5111.8  679.33  5122.5  680.82  5129.4  681.38
  5154.1  682.12  5159.4   683.9    5176  684.22  5189.5  685.53  5220.9  685.65
#Mann= 4 ,-1 , 0
  4723.2     .05       0  4928.6    .075       0  4972.5    .033       0
    5071     .05       0
Bank Sta=4972.5,5071
XS Rating Curve= 0 ,0
Exp/Cntr=0.3,0.1

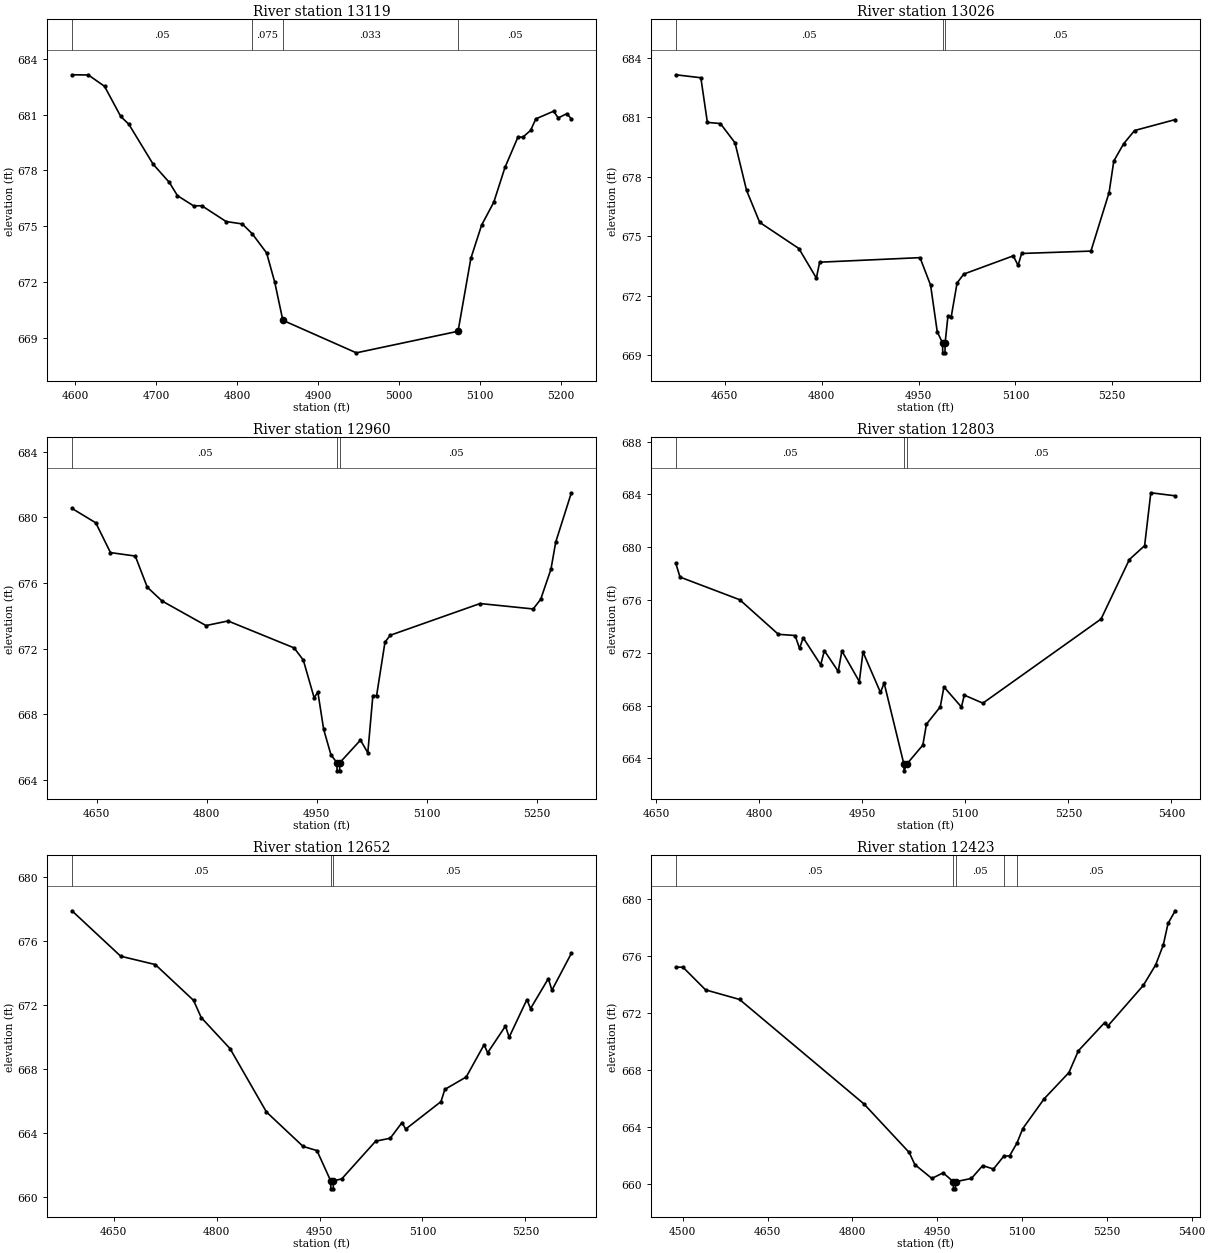
Type RM Length L Ch R = 1 ,13119   ,93,93,93
BEGIN DESCRIPTION:
Golf Course Creek Tr 1 35.4
END DESCRIPTION:
XS GIS Cut Line= 4
      2368008.85      7041280.86        2368323.      7041275.47
      2368495.32      7041176.75      2368544.34       7041085.7
#Sta/Elev= 30
  4596.3  683.14  4616.5  683.13  4636.5  682.52  4656.5   680.9  4666.5  680.48
  4696.5  678.33  4716.5  677.35  4726.5  676.64  4746.5  676.09  4756.5   676.1
  4786.5  675.25  4806.5  675.12  4818.8  674.59  4836.5  673.56  4846.5  671.99
  4856.5  669.94  4947.2  668.19  5072.7  669.35  5088.5  673.27  5101.8  675.06
  5116.8  676.29  5130.6  678.16  5146.8  679.81  5152.5  679.78  5162.2  680.15
  5168.7  680.77  5190.6  681.18  5196.3  680.82  5206.9  681.05  5212.5  680.77
#Mann= 4 ,-1 , 0
  4596.3     .05       0  4818.8    .075       0  4856.5    .033       0
  5072.7     .05       0
Bank Sta=4856.5,5072.7
XS Rating Curve= 0 ,0
Exp/Cntr=0.3,0.1

Type RM Length L Ch R = 1 ,13026   ,66,66,66
BEGIN DESCRIPTION:
Golf Course Creek Tr 1 35.2
END DESCRIPTION:
XS GIS Cut Line= 5
      2368010.68      7041311.38      2368265.56      7041350.86
      2368378.64      7041325.73      2368461.37      7041307.03
      2368744.56       7041169.5
#Sta/Elev= 30
  4574.1  683.14  4612.9  682.99    4623  680.74  4643.2  680.68  4665.8  679.71
  4683.7  677.31    4704   675.7  4764.7  674.38  4791.8  672.89  4796.9  673.69
  4952.3  673.92  4968.7  672.53    4979  670.18  4987.2  669.62  4987.5  669.12
    4991  669.12  4991.2  669.62  4995.5  670.96  5000.6  670.93  5009.7  672.64
    5020  673.09  5096.7  674.01  5104.2  673.53  5109.7  674.13    5217  674.25
  5245.1   677.2  5252.4  678.79  5267.6  679.66  5284.6  680.33  5347.5  680.88
#Mann= 3 ,-1 , 0
  4574.1     .05       0  4987.2    .033       0  4991.2     .05       0
Bank Sta=4987.2,4991.2
XS Rating Curve= 0 ,0
Exp/Cntr=0.3,0.1

Type RM Length L Ch R = 1 ,12960   ,157,157,157
BEGIN DESCRIPTION:
Golf Course Creek Tr 1 35.0
END DESCRIPTION:
XS GIS Cut Line= 4
      2368046.57      7041370.61       2368358.9      7041386.76
      2368457.62      7041377.79      2368719.73      7041318.55
#Sta/Elev= 30
  4616.4  680.54  4648.9  679.66  4668.9  677.85  4702.7  677.64    4719  675.75
    4739  674.91  4799.1  673.41  4829.1  673.69  4919.2  672.05  4931.7  671.31
  4946.5  669.01  4951.5  669.37  4959.4   667.1  4969.4  665.54  4977.5  665.07
  4977.7  664.57  4981.2  664.57  4981.5  665.07  5009.6  666.44  5019.6  665.67
  5026.5  669.15  5031.6  669.15    5043   672.4  5050.2  672.82  5172.6  674.75
    5245  674.42  5255.2  675.01  5269.2  676.84  5275.7  678.49    5297  681.49
#Mann= 3 ,-1 , 0
  4616.4     .05       0  4977.5    .033       0  4981.5     .05       0
Bank Sta=4977.5,4981.5
XS Rating Curve= 0 ,0
Exp/Cntr=0.3,0.1

Type RM Length L Ch R = 1 ,12803   ,151,151,151
BEGIN DESCRIPTION:
Golf Course Creek Tr 1 34.0
END DESCRIPTION:
XS GIS Cut Line= 3
      2368035.53      7041393.93      2368431.99      7041535.75
      2368721.06      7041635.32
#Sta/Elev= 30
  4678.7  678.79  4684.8  677.74  4771.8  676.02    4828   673.4  4852.3  673.31
  4858.8  672.33  4864.1  673.14  4889.6  671.09  4894.9  672.16  4915.1  670.59
  4920.4  672.14  4945.8  669.82  4951.1  672.06  4976.6  668.99  4981.9  669.71
  5010.7  663.55  5010.9  663.05  5014.7  663.55  5038.2     665  5043.5  666.59
  5063.6   667.9  5068.9  669.41  5094.4  667.89  5098.6  668.79  5125.6  668.18
  5297.6  674.56  5338.8  679.07    5361  680.12    5370  684.13  5405.5   683.9
#Mann= 3 ,-1 , 0
  4678.7     .05       0  5010.7    .033       0  5014.7     .05       0
Bank Sta=5010.7,5014.7
XS Rating Curve= 0 ,0
Exp/Cntr=0.3,0.1

Type RM Length L Ch R = 1 ,12652   ,229,229,229
BEGIN DESCRIPTION:
Golf Course Creek Tr 1 33.8
END DESCRIPTION:
XS GIS Cut Line= 3
      2367942.07       7041513.2      2368338.51      7041655.02
      2368628.64      7041754.95
#Sta/Elev= 30
  4589.1   677.9  4660.2  675.06  4710.6  674.54  4766.4   672.3  4777.5  671.23
  4819.5  669.29  4872.6  665.33    4926  663.18  4946.2  662.92  4966.2  661.03
  4966.4  660.53  4969.9  660.53  4970.2  661.03  4982.3  661.15  5031.8  663.51
    5053  663.69  5070.2  664.67  5075.5  664.26    5127  665.98  5132.6  666.74
  5163.8  667.52  5189.8  669.53    5195  669.03    5221   670.7  5226.3     670
  5252.2  672.35  5257.5  671.79  5283.4  673.66  5288.7  672.94    5317  675.24
#Mann= 3 ,-1 , 0
  4589.1     .05       0  4966.2    .033       0  4970.2     .05       0
Bank Sta=4966.2,4970.2
XS Rating Curve= 0 ,0
Exp/Cntr=0.3,0.1

Type RM Length L Ch R = 1 ,12423   ,182,182,182
BEGIN DESCRIPTION:
Golf Course Creek Tr 1 33.0
END DESCRIPTION:
XS GIS Cut Line= 3
      2367816.31      7041870.97      2368367.52      7041880.64
      2368670.55      7041745.25
#Sta/Elev= 30
  4487.6  675.19  4500.3  675.18  4540.3  673.59  4600.3  672.92  4820.3  665.59
  4900.4  662.18  4910.4  661.33  4940.4  660.36  4960.4  660.75  4978.4  660.13
  4978.6  659.63  4982.1  659.63  4982.4  660.13  5010.4  660.36  5030.4  661.26
  5049.4  661.02  5067.4  661.91    5078  661.95  5090.8  662.83  5101.3  663.86
  5139.1  665.95  5182.9  667.79  5199.6  669.32    5246  671.29  5251.5  671.05
  5314.3   673.9  5336.2  675.34  5349.8  676.75  5358.1  678.25  5370.8  679.14
#Mann= 5 ,-1 , 0
  4487.6     .05       0  4978.4    .033       0  4982.4     .05       0
  5067.4     .12       0  5090.8     .05       0
Bank Sta=4978.4,4982.4
XS Rating Curve= 0 ,0
Exp/Cntr=0.3,0.1

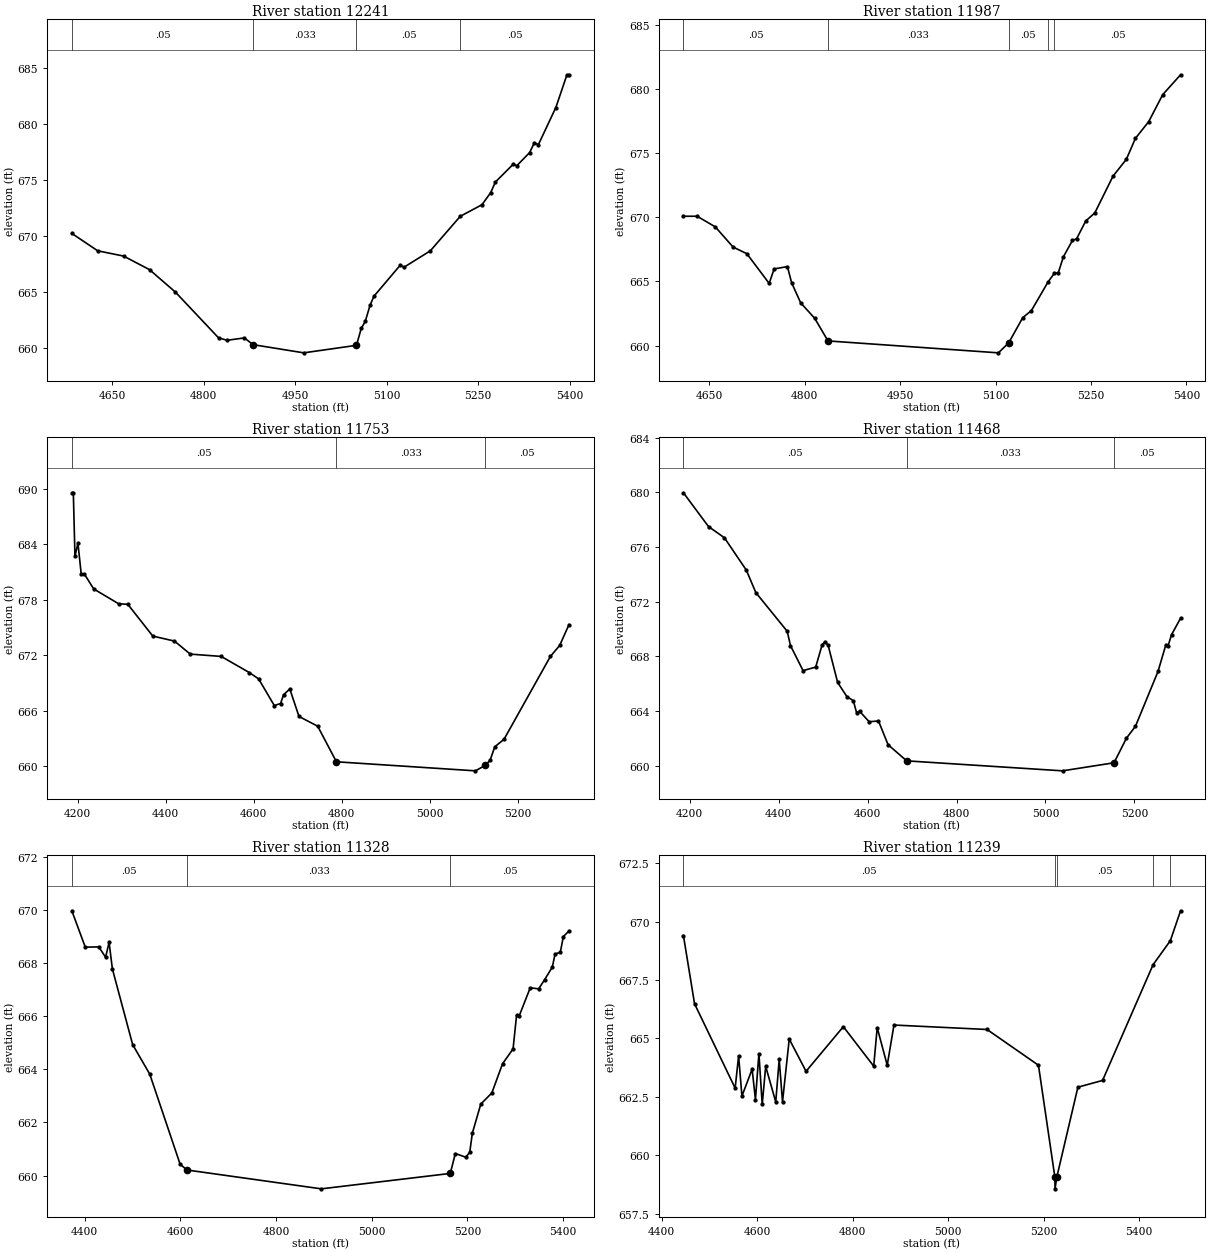
Type RM Length L Ch R = 1 ,12241   ,254,254,254
BEGIN DESCRIPTION:
Golf Course Creek Tr 1 32.0
END DESCRIPTION:
XS GIS Cut Line= 3
      2368129.02      7042309.98        2368429.        7042010.
      2368729.04      7041759.97
#Sta/Elev= 30
  4584.1  670.21  4626.5  668.66  4668.9  668.19  4711.4  666.98  4753.8  664.98
  4824.5   660.9  4838.6  660.68  4866.9  660.89  4881.1  660.29  4964.2  659.56
  5050.6  660.23  5058.5  661.75    5065  662.36  5072.8  663.79  5079.3  664.61
  5122.2  667.37  5128.7   667.2  5171.7  668.66  5220.8  671.74  5256.3  672.77
  5270.6  673.85  5278.4   674.8  5307.1  676.36  5313.6  676.26  5334.4  677.42
  5342.2   678.3  5348.7  678.12  5377.4  681.44  5395.6  684.36  5398.9  684.36
#Mann= 4 ,-1 , 0
  4584.1     .05       0  4881.1    .033       0  5050.6     .05       0
  5220.8     .05       0
Bank Sta=4881.1,5050.6
XS Rating Curve= 0 ,0
Exp/Cntr=0.3,0.1

Type RM Length L Ch R = 1 ,11987   ,234,234,234
BEGIN DESCRIPTION:
Golf Course Creek Tr 1 31.0
END DESCRIPTION:
XS GIS Cut Line= 3
        2368279.        7042460.        2368579.        7042210.
      2368828.99      7041910.02
#Sta/Elev= 30
  4609.7  670.09  4631.2  670.09  4659.8  669.26  4687.8  667.68  4709.3  667.17
  4744.4  664.85  4752.2  665.98  4773.1  666.16  4779.6  664.91  4793.9  663.33
    4816  662.12  4836.8  660.36  5104.5  659.43  5120.6   660.2  5142.7  662.17
  5156.4  662.73  5182.5  664.96  5192.3  665.63  5198.7  665.69  5206.5  666.91
  5220.8   668.2  5227.4  668.33  5241.7  669.72    5256  670.35  5284.6  673.22
  5305.5  674.53  5319.8  676.17  5340.6  677.47  5362.7  679.58  5390.7  681.13
#Mann= 5 ,-1 , 0
  4609.7     .05       0  4836.8    .033       0  5120.6     .05       0
  5182.5     .12       0  5192.3     .05       0
Bank Sta=4836.8,5120.6
XS Rating Curve= 0 ,0
Exp/Cntr=0.3,0.1

Type RM Length L Ch R = 1 ,11753   ,285,285,285
BEGIN DESCRIPTION:
Golf Course Creek Tr 1 30.0
END DESCRIPTION:
XS GIS Cut Line= 3
      2368228.99      7042910.01        2368779.        7042310.
      2368879.01      7042009.98
#Sta/Elev= 30
  4186.5   689.6  4189.9   689.6  4193.6  682.72  4200.4  684.14  4207.8   680.8
  4214.6  680.83  4236.2  679.19  4292.9  677.58  4313.8  677.52  4370.6  674.08
  4419.9  673.54  4455.7  672.13    4526  671.88  4590.1  670.13  4611.1  669.45
  4646.8  666.56    4661  666.78  4667.8  667.72    4682  668.36  4702.9  665.38
  4745.5  664.32    4788  660.47  5104.1  659.49  5126.9   660.1  5137.5  660.65
    5148  662.09  5169.1  662.91  5274.5  671.88  5295.6  673.07  5316.7  675.32
#Mann= 3 ,-1 , 0
  4186.5     .05       0    4788    .033       0  5126.9     .05       0
Bank Sta=4788,5126.9
XS Rating Curve= 0 ,0
Exp/Cntr=0.3,0.1

Type RM Length L Ch R = 1 ,11468   ,140,140,140
BEGIN DESCRIPTION:
Golf Course Creek Tr 1 29.0
END DESCRIPTION:
XS GIS Cut Line= 3
      2368429.01      7042959.99        2369029.        7042410.
      2369079.01      7042109.96
#Sta/Elev= 30
  4185.8  679.96  4242.2  677.49    4278  676.67  4327.3   674.3  4348.6  672.66
  4419.2  669.83  4426.6  668.78  4454.9  666.95  4483.3  667.21  4497.5  668.81
  4504.3  669.08  4511.4  668.79  4532.6  666.09  4553.6  665.04  4567.8  664.76
  4575.2  663.88    4582  663.98  4603.5  663.21  4624.5  663.27  4646.1  661.53
    4688  660.35  5038.5  659.62  5154.3  660.21  5182.2  662.01  5202.5  662.88
  5253.2  666.89  5270.9  668.85    5276  668.78  5283.6  669.58  5303.9  670.78
#Mann= 3 ,-1 , 0
  4185.8     .05       0    4688    .033       0  5154.3     .05       0
Bank Sta=4688,5154.3
XS Rating Curve= 0 ,0
Exp/Cntr=0.3,0.1

Type RM Length L Ch R = 1 ,11328   ,89,89,89
BEGIN DESCRIPTION:
Golf Course Creek Tr 1 28.4
END DESCRIPTION:
XS GIS Cut Line= 3
      2368718.83      7042979.81      2369099.21      7042573.65
       2369298.4      7042133.49
#Sta/Elev= 30
  4372.9  669.97    4401   668.6  4429.3  668.61  4443.5  668.22  4450.8  668.78
  4457.7  667.78  4500.1  664.93  4535.8  663.82  4599.3  660.43  4613.5  660.21
  4894.6   659.5  5164.3  660.08  5174.9  660.83  5196.8  660.69    5205  660.88
  5210.5   661.6  5228.1  662.69  5251.2  663.11  5273.6  664.21  5295.6  664.77
  5302.9  666.03  5308.4  666.01  5331.5  667.07  5349.1  667.03  5361.4  667.37
  5377.7  667.85  5383.4  668.34  5394.4  668.41  5400.8     669  5412.5  669.21
#Mann= 3 ,-1 , 0
  4372.9     .05       0  4613.5    .033       0  5164.3     .05       0
Bank Sta=4613.5,5164.3
XS Rating Curve= 0 ,0
Exp/Cntr=0.3,0.1

Type RM Length L Ch R = 1 ,11239   ,131,131,131
BEGIN DESCRIPTION:
Golf Course Creek Tr 1 28.2
END DESCRIPTION:
XS GIS Cut Line= 3
      2368812.33      7042976.57      2369192.68      7042570.43
      2369392.51      7042128.87
#Sta/Elev= 30
  4445.5   669.4  4468.8  666.48  4553.8  662.87  4561.1  664.25    4568  662.53
  4589.4  663.68  4596.3  662.38  4603.6  664.35  4610.5  662.17  4617.8   663.8
  4638.8  662.28  4646.1   664.1    4653  662.28  4667.1  664.97  4702.3  663.59
  4780.4   665.5    4844  663.81  4851.3  665.46  4872.3  663.85  4886.4  665.57
  5081.3  665.38    5189  663.85  5223.4  659.06  5223.7  658.56  5227.4  659.06
  5271.6  662.91  5323.3   663.2    5429  668.15  5465.2  669.18  5486.6  670.46
#Mann= 5 ,-1 , 0
  4445.5     .05       0  5223.4    .033       0  5227.4     .05       0
    5429     .12       0  5465.2     .05       0
Bank Sta=5223.4,5227.4
XS Rating Curve= 0 ,0
Exp/Cntr=0.3,0.1

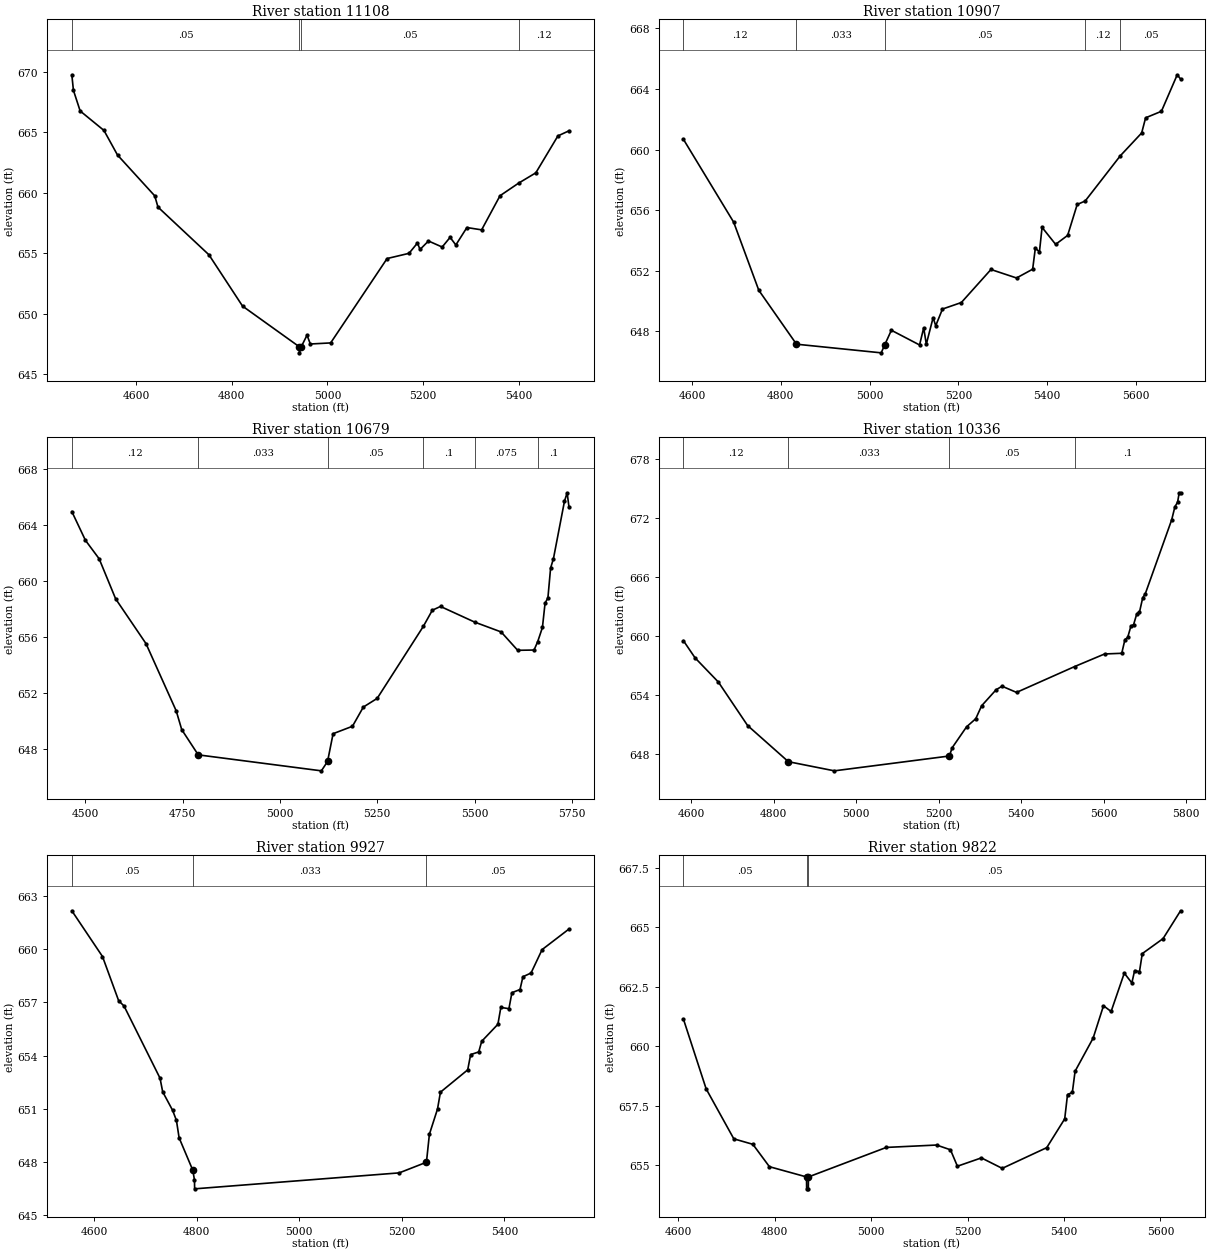
Type RM Length L Ch R = 1 ,11108   ,201,201,201
BEGIN DESCRIPTION:
Golf Course Creek Tr 1 28.0
END DESCRIPTION:
XS GIS Cut Line= 3
      2368863.92      7043079.69      2369244.25      7042673.57
      2369443.35      7042233.63
#Sta/Elev= 30
  4465.6  669.74  4468.9  668.46    4483  666.75  4532.8  665.14  4561.1  663.11
  4638.9  659.74  4645.7  658.81  4752.2  654.87  4822.5  650.63  4941.2  647.27
  4941.4  646.77  4945.2  647.27  4957.3  648.23  4964.2   647.5  5006.7  647.59
  5124.7  654.56  5170.5  654.99  5188.1  655.84  5193.6  655.31  5211.2  656.01
  5239.8  655.51  5256.4  656.31  5268.4  655.68  5291.5  657.12  5322.3  656.93
  5360.8  659.75  5399.7  660.79  5435.6  661.64  5481.8  664.69  5504.9  665.11
#Mann= 4 ,-1 , 0
  4465.6     .05       0  4941.2    .033       0  4945.2     .05       0
  5399.7     .12       0
Bank Sta=4941.2,4945.2
XS Rating Curve= 0 ,0
Exp/Cntr=0.3,0.1

Type RM Length L Ch R = 1 ,10907   ,228,228,228
BEGIN DESCRIPTION:
Golf Course Creek Tr 1 27.0
END DESCRIPTION:
XS GIS Cut Line= 3
      2369078.98      7043110.02        2369379.        7042810.
      2369752.68      7042223.65
#Sta/Elev= 30
  4580.8  660.68    4694  655.21  4750.5  650.72  4835.4  647.16  5026.2  646.59
  5033.9   647.1  5049.1  648.08  5112.6  647.11  5121.9  648.24  5127.8  647.16
  5143.1  648.91    5149  648.38  5164.2  649.48  5206.7  649.91  5273.4  652.09
    5331  651.53  5367.3  652.11  5373.3  653.49  5382.6  653.26  5388.5  654.87
    5419  653.75  5446.1  654.34  5467.6  656.38  5485.6  656.61  5564.6  659.59
  5612.8   661.1  5621.7   662.1  5657.3  662.53  5692.9  664.94  5700.4  664.66
#Mann= 5 ,-1 , 0
  4580.8     .12       0  4835.4    .033       0  5033.9     .05       0
  5485.6     .12       0  5564.6     .05       0
Bank Sta=4835.4,5033.9
XS Rating Curve= 0 ,0
Exp/Cntr=0.3,0.1

Type RM Length L Ch R = 1 ,10679   ,343,343,343
BEGIN DESCRIPTION:
Golf Course Creek Tr 1 26.0
END DESCRIPTION:
XS GIS Cut Line= 3
      2369150.79      7043331.11        2369529.        7042960.
      2370039.26      7042413.71
#Sta/Elev= 30
  4465.1  664.94    4500  662.89  4535.3  661.57  4577.7  658.71  4655.6  655.52
  4733.3  650.72  4747.5  649.38  4789.9  647.58  5106.3  646.44  5122.2  647.11
  5136.4  649.09  5186.2  649.62  5214.1  650.99  5249.7  651.61  5368.1  656.74
  5391.4   657.9  5412.4  658.17  5500.4  657.05  5568.2  656.35  5610.7  655.04
  5652.8  655.06  5662.2  655.66  5674.3  656.67  5681.1  658.41  5688.4  658.78
  5695.3  660.91  5702.6  661.58  5730.9  665.67  5737.8  666.28  5742.5  665.27
#Mann= 6 ,-1 , 0
  4465.1     .12       0  4789.9    .033       0  5122.2     .05       0
  5368.1      .1       0  5500.4    .075       0  5662.2      .1       0
Bank Sta=4789.9,5122.2
XS Rating Curve= 0 ,0
Exp/Cntr=0.3,0.1

Type RM Length L Ch R = 1 ,10336   ,409,409,409
BEGIN DESCRIPTION:
Golf Course Creek Tr 1 25.0
END DESCRIPTION:
XS GIS Cut Line= 3
      2369429.01      7043509.99        2369729.        7043210.
      2370229.02      7042609.98
#Sta/Elev= 30
  4580.8  659.49  4609.1  657.74  4665.6  655.28  4736.4  650.86  4835.3  647.18
  4946.7  646.25  5225.7  647.76  5232.2  648.59  5267.3  650.73  5289.5  651.55
  5303.8  652.87  5338.9   654.5  5353.3  654.86  5388.4  654.23  5529.3  656.86
  5601.9  658.14  5643.5  658.21  5651.3  659.61  5657.9  659.82  5665.7  660.97
  5672.2  661.12    5680  662.23  5686.5   662.4  5694.3  663.85  5700.8  664.29
  5764.6  671.79  5772.4  673.12  5778.9  673.58  5782.8  674.54  5786.1  674.54
#Mann= 4 ,-1 , 0
  4580.8     .12       0  4835.3    .033       0  5225.7     .05       0
  5529.3      .1       0
Bank Sta=4835.3,5225.7
XS Rating Curve= 0 ,0
Exp/Cntr=0.3,0.1

Type RM Length L Ch R = 1 ,9927    ,105,105,105
BEGIN DESCRIPTION:
Golf Course Creek Tr 1 24.0
END DESCRIPTION:
XS GIS Cut Line= 4
      2369502.12      7043698.57      2369850.23      7043585.76
      2370001.72      7043521.29      2370220.93      7043140.91
#Sta/Elev= 30
  4556.3  662.17  4616.1  659.59  4647.6   657.1  4658.1   656.8  4728.3  652.73
  4733.5  651.96  4752.8  650.92  4760.3  650.35  4765.5  649.37  4792.2  647.54
  4795.5  646.99  4795.8  646.49  5194.8  647.39  5247.9  647.99  5253.7  649.57
  5269.5  650.99  5275.2  651.94  5328.4   653.2  5334.1  654.06  5349.9  654.21
  5355.7  654.81  5387.3  655.77    5393  656.72  5408.8  656.65  5414.6  657.55
  5430.4  657.73  5436.1  658.45  5451.9  658.66  5473.5  659.98  5525.9  661.14
#Mann= 3 ,-1 , 0
  4556.3     .05       0  4792.2    .033       0  5247.9     .05       0
Bank Sta=4792.2,5247.9
XS Rating Curve= 0 ,0
Exp/Cntr=0.3,0.1

Type RM Length L Ch R = 1 ,9822    ,121,121,121
BEGIN DESCRIPTION:
Golf Course Creek Tr 1 23.5
END DESCRIPTION:
XS GIS Cut Line= 4
      2369553.64      7043763.05      2369995.28      7043640.55
      2370159.66      7043434.26      2370314.21      7043167.02
#Sta/Elev= 30
  4610.8  661.14  4657.9  658.21  4715.3  656.11  4754.8  655.88  4789.1  654.94
    4866  654.51  4866.3  654.01  4869.8  654.01    4870  654.51  5031.5  655.75
  5135.7  655.85  5164.5  655.65  5178.9  654.96  5228.6  655.31  5271.8  654.87
  5364.1  655.74  5401.4  656.95  5407.2  657.97  5417.2  658.06  5422.9  658.95
  5460.3  660.34  5481.8   661.7  5497.6  661.46  5524.9  663.07  5540.6  662.66
  5546.4  663.18  5556.4  663.13  5562.2  663.89  5605.3  664.52  5641.6  665.69
#Mann= 3 ,-1 , 0
  4610.8     .05       0    4866    .033       0    4870     .05       0
Bank Sta=4866,4870
XS Rating Curve= 0 ,0
Exp/Cntr=0.3,0.1

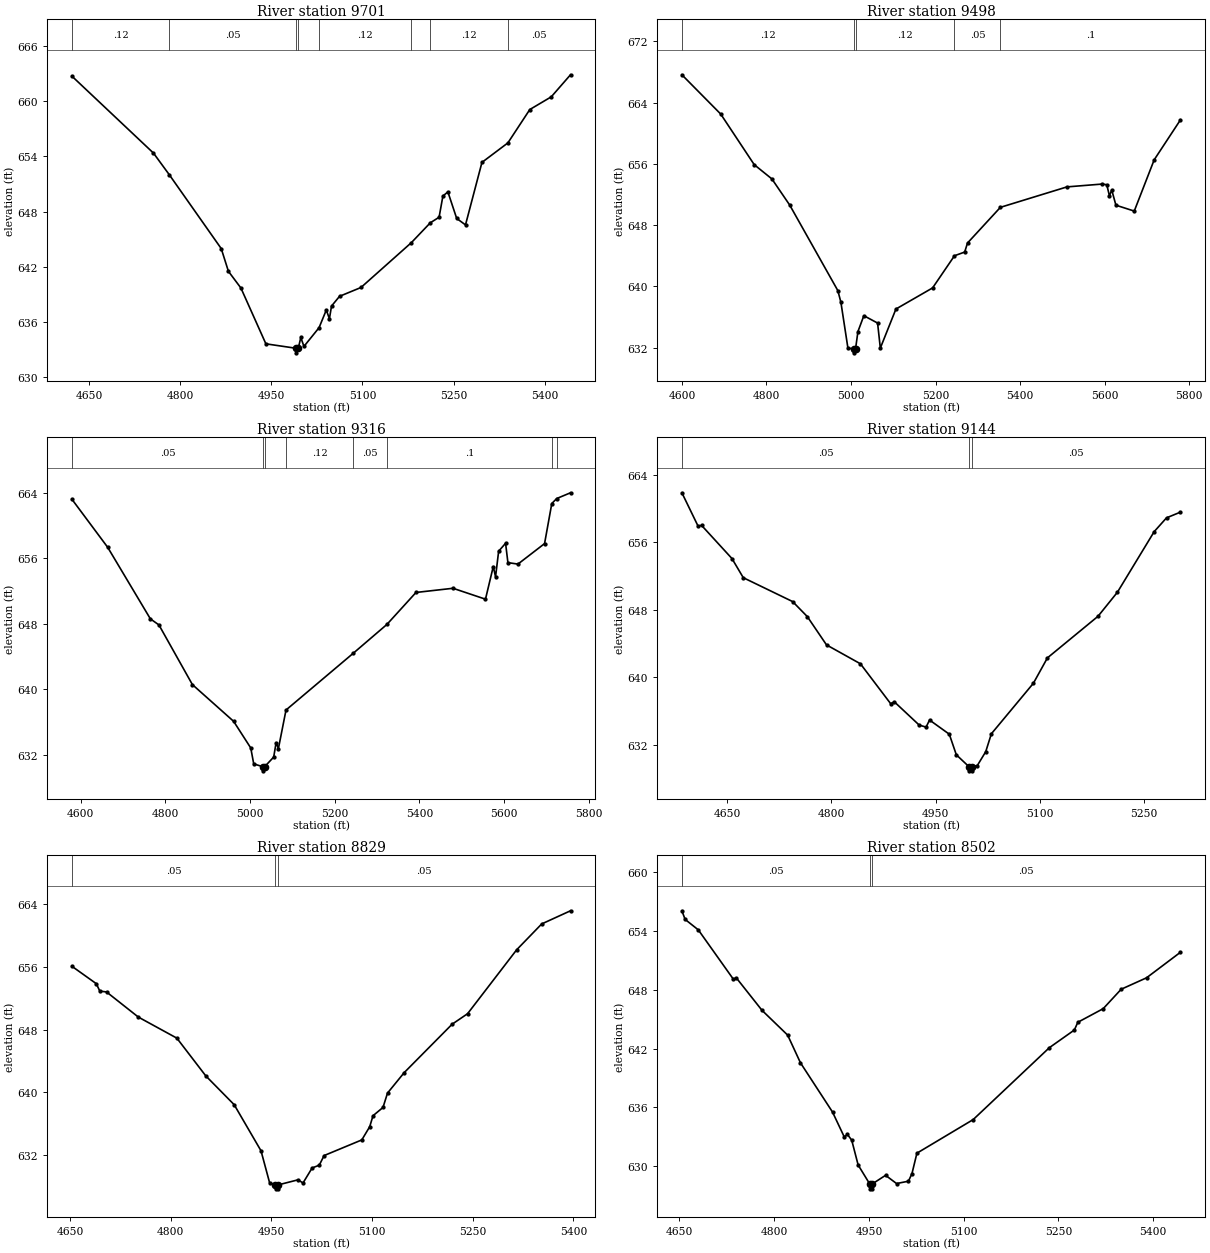
Type RM Length L Ch R = 1 ,9701    ,203,203,203
BEGIN DESCRIPTION:
Golf Course Creek Tr 1 23.0
END DESCRIPTION:
XS GIS Cut Line= 3
      2369608.44       7043853.3      2370024.29      7043753.37
      2370335.44      7043512.79
#Sta/Elev= 30
  4621.6  662.74  4755.9  654.37  4781.7  652.04  4867.5  643.98  4879.3  641.51
  4899.9  639.69    4941  633.62  4990.4  633.14  4990.7  632.64  4994.4  633.14
  4998.5  634.31  5003.7  633.34  5028.6  635.38  5040.5   637.3  5045.6  636.35
  5049.1  637.73  5062.3  638.79  5097.6  639.75  5180.6  644.63  5211.8  646.79
  5226.2  647.39  5232.5   649.7  5240.7  650.15  5255.2  647.26  5269.7  646.56
  5296.8  653.36  5339.5  655.48  5375.6  659.11  5410.9  660.49  5442.6  662.89
#Mann= 8 ,-1 , 0
  4621.6     .12       0  4781.7     .05       0  4990.4    .033       0
  4994.4     .05       0  5028.6     .12       0  5180.6     .05       0
  5211.8     .12       0  5339.5     .05       0
Bank Sta=4990.4,4994.4
XS Rating Curve= 0 ,0
Exp/Cntr=0.3,0.1

Type RM Length L Ch R = 1 ,9498    ,182,182,182
BEGIN DESCRIPTION:
Golf Course Creek Tr 1 22.7
END DESCRIPTION:
XS GIS Cut Line= 3
      2369627.83      7044017.68      2369972.71      7043972.55
      2370739.83      7043650.23
#Sta/Elev= 30
  4599.8  667.63  4691.7   662.5    4771  655.89  4812.8  654.03  4854.9  650.62
  4968.9  639.44  4976.1  637.92  4992.7  631.94  5006.7  631.82  5006.9  631.32
  5010.7  631.82  5016.4   634.1  5030.4  636.17  5062.9  635.21  5069.4  631.94
  5106.3  637.04  5193.1   639.8  5244.9     644    5269  644.48  5275.7  645.66
  5353.5  650.32  5511.1  652.99  5594.4  653.36  5605.3  653.27  5611.6  651.81
    5617  652.59  5626.9   650.6  5670.3  649.83  5717.5  656.53  5779.7  661.75
#Mann= 5 ,-1 , 0
  4599.8     .12       0  5006.7     .07       0  5010.7     .12       0
  5244.9     .05       0  5353.5      .1       0
Bank Sta=5006.7,5010.7
XS Rating Curve= 0 ,0
Exp/Cntr=0.3,0.1

Type RM Length L Ch R = 1 ,9316    ,172,172,172
BEGIN DESCRIPTION:
Golf Course Creek Tr 1 22.4
END DESCRIPTION:
XS GIS Cut Line= 3
      2369705.18      7044172.39      2370050.07      7044127.27
      2370815.52      7043805.65
#Sta/Elev= 30
  4578.9   663.2  4663.4  657.34  4764.3  648.61  4784.5  647.87  4863.6  640.59
    4961  636.11  5001.5  632.86  5008.5  630.92  5030.2  630.57  5030.5  630.07
  5034.2  630.57  5055.7  631.75  5061.4  633.51  5066.8  632.78  5084.8  637.49
  5243.6  644.41  5323.2  647.93  5391.9  651.83  5479.4  652.34  5556.1  651.01
  5574.5  654.99  5579.9  653.74  5587.2  656.86  5603.6  657.83  5609.1  655.47
  5632.8  655.29  5695.7  657.79  5712.8  662.68  5724.5  663.29    5757  663.99
#Mann= 8 ,-1 , 0
  4578.9     .05       0  5030.2    .033       0  5034.2     .05       0
  5084.8     .12       0  5243.6     .05       0  5323.2      .1       0
  5712.8     .05       0  5724.5      .1       0
Bank Sta=5030.2,5034.2
XS Rating Curve= 0 ,0
Exp/Cntr=0.3,0.1

Type RM Length L Ch R = 1 ,9144    ,315,315,315
BEGIN DESCRIPTION:
Golf Course Creek Tr 1 22.0
END DESCRIPTION:
XS GIS Cut Line= 3
      2369772.82      7044330.34      2370108.09       7044256.2
      2370478.96      7044210.01
#Sta/Elev= 30
  4585.1  661.88  4608.3  657.94  4613.4  658.02  4657.1  654.09  4673.4  651.82
  4744.4  648.99  4765.5  647.21  4793.1  643.86  4841.9  641.62  4885.5  636.88
  4890.6  637.12  4926.4  634.36  4936.3  634.12  4941.3  634.96  4969.7  633.28
  4979.8  630.84  4997.9  629.44  4998.2  628.94  5001.7  628.94  5001.9  629.44
    5010  629.57  5022.1  631.21  5030.2  633.33  5090.6  639.31  5110.8  642.32
  5183.6  647.25  5211.5   650.1  5264.4  657.28  5282.1  658.91  5302.2  659.59
#Mann= 3 ,-1 , 0
  4585.1     .05       0  4997.9     .05       0  5001.9     .05       0
Bank Sta=4997.9,5001.9
XS Rating Curve= 0 ,0
Exp/Cntr=0.3,0.1

Type RM Length L Ch R = 1 ,8829    ,327,327,327
BEGIN DESCRIPTION:
Golf Course Creek Tr 1 21.0
END DESCRIPTION:
XS GIS Cut Line= 3
      2369950.14      7044626.88      2370375.62      7044481.83
      2370654.98      7044391.92
#Sta/Elev= 30
  4652.6  656.09  4688.9  653.87  4694.2  652.92  4704.2  652.81  4751.6   649.6
    4809  646.91  4852.1  642.09  4894.4  638.41  4934.4  632.52  4947.2  628.44
  4955.8  628.16    4956  627.66  4959.5  627.66  4959.8  628.16  4989.5  628.81
    4997  628.41  5010.6  630.33  5021.2  630.68  5028.4  631.91  5084.6  633.91
  5096.4   635.6  5101.3     637  5116.2  638.06  5122.9  639.89  5147.7   642.5
  5219.2  648.69  5242.2  650.03  5315.4   658.2  5352.7   661.5  5395.6  663.18
#Mann= 3 ,-1 , 0
  4652.6     .05       0  4955.8    .033       0  4959.8     .05       0
Bank Sta=4955.8,4959.8
XS Rating Curve= 0 ,0
Exp/Cntr=0.3,0.1

Type RM Length L Ch R = 1 ,8502    ,381,381,381
BEGIN DESCRIPTION:
Golf Course Creek Tr 1 20.0
END DESCRIPTION:
XS GIS Cut Line= 3
      2370033.97      7044868.62        2370379.        7044810.
      2370777.06      7044624.34
#Sta/Elev= 30
    4654  656.07  4659.1  655.19    4680  654.12  4735.2  649.11  4740.3  649.21
  4780.8  645.91  4821.4  643.38  4841.7  640.55  4892.4  635.53    4911  632.99
  4916.1  633.24  4922.8  632.66    4933  630.12  4951.3  628.19  4951.5  627.69
    4955  627.69  4955.3  628.19  4976.4  629.07  4993.8  628.23  5012.6  628.47
  5018.2  629.25    5026  631.33  5115.1  634.76  5235.7   642.1  5275.2   643.9
  5280.7  644.69  5320.9  646.08  5349.3  648.06  5389.5  649.23  5443.2  651.84
#Mann= 3 ,-1 , 0
    4654     .05       0  4951.3    .033       0  4955.3     .05       0
Bank Sta=4951.3,4955.3
XS Rating Curve= 0 ,0
Exp/Cntr=0.3,0.1