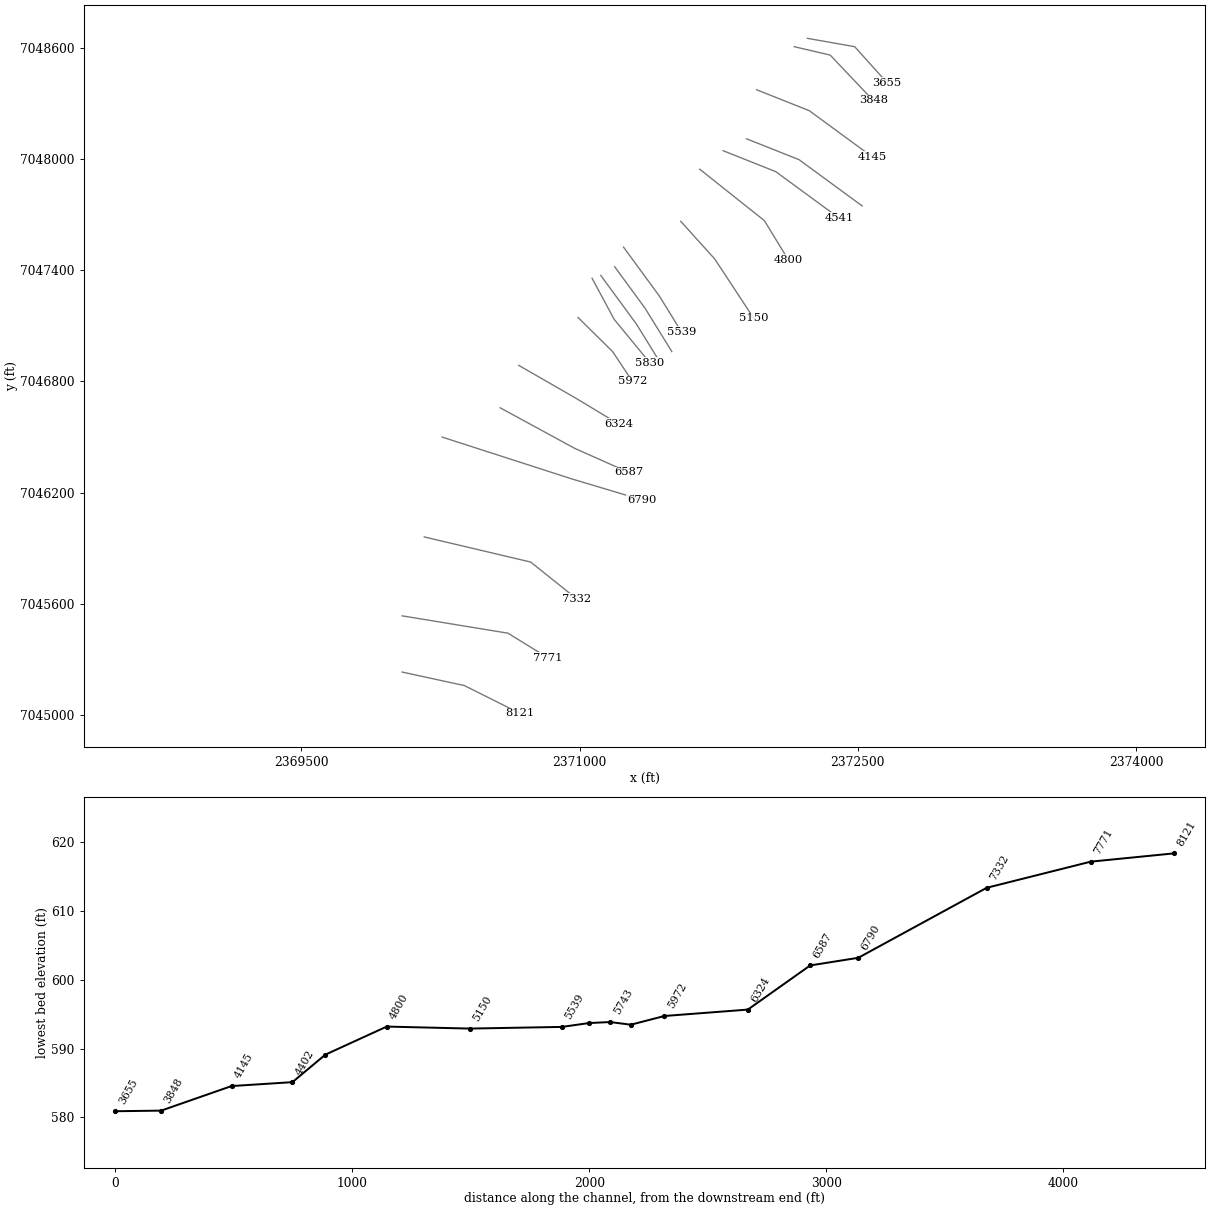
HEC-RAS study Golf Course Creek Tr 1.prj: Golf Course Creek Tr 1 Base Level Engineering

--- Golf Course Creek Tr 1.g01 (geometry) --- (continued)

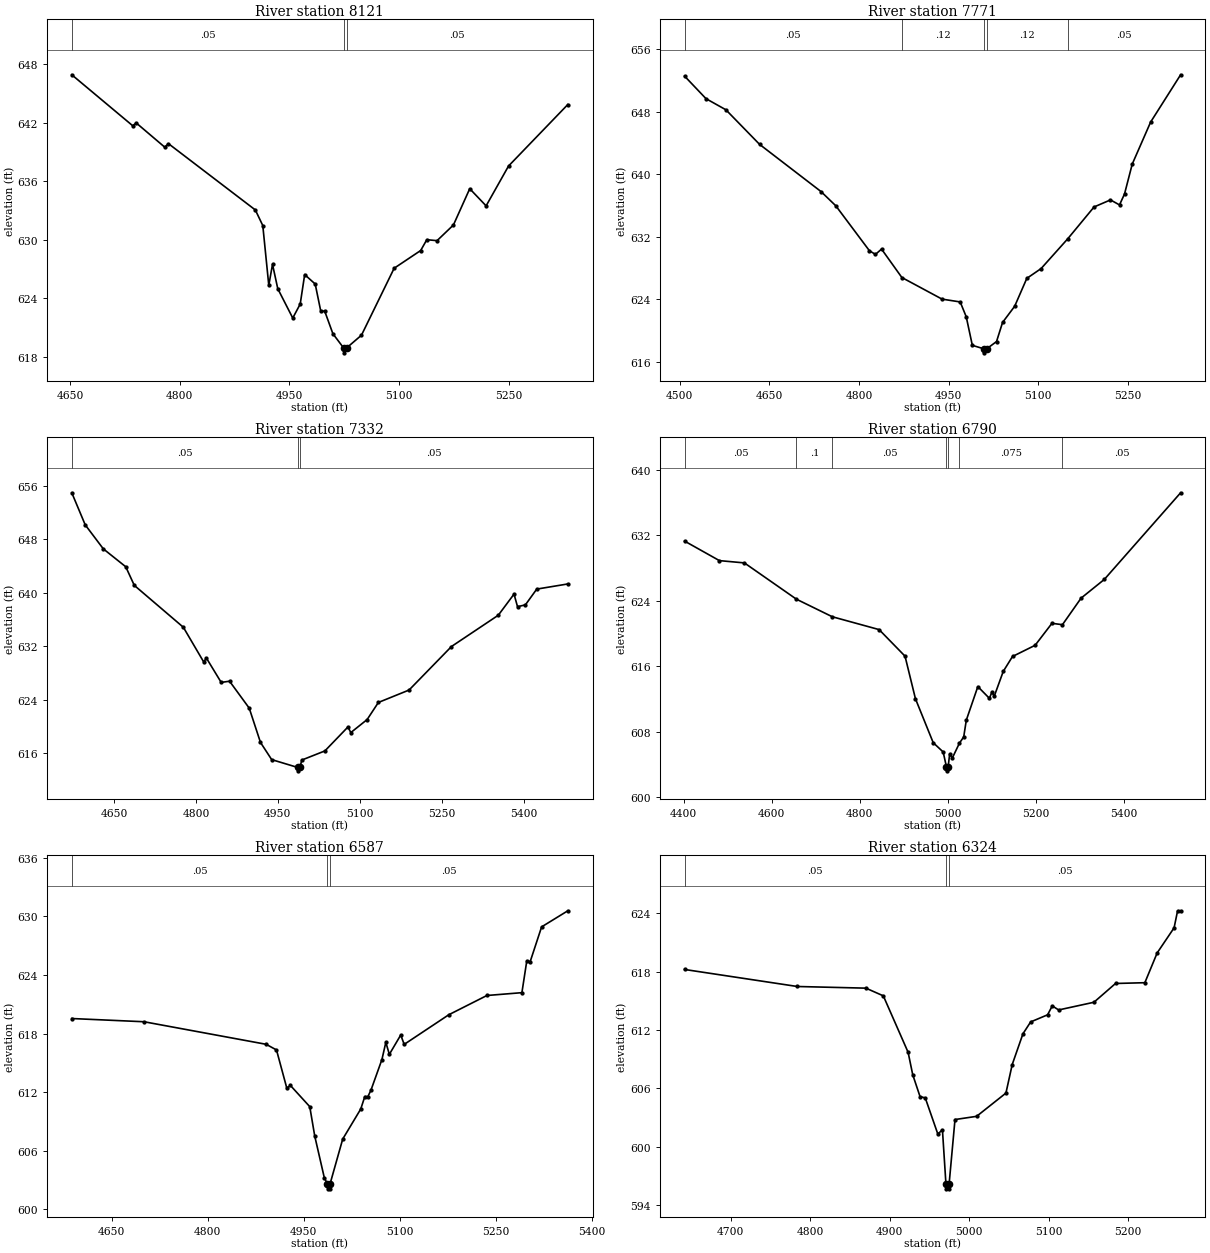
Type RM Length L Ch R = 1 ,8121    ,350,350,350
BEGIN DESCRIPTION:
Golf Course Creek Tr 1 19.0
END DESCRIPTION:
XS GIS Cut Line= 3
      2370043.64      7045232.85        2370379.        7045160.
        2370679.        7045010.
#Sta/Elev= 30
  4652.5  646.91  4735.7  641.69  4740.8  641.96  4779.7  639.48  4784.8  639.84
  4903.6  633.04  4913.8  631.44    4922  625.31  4927.1  627.46  4934.3  624.96
  4954.8  621.95    4965  623.39  4971.1  626.41  4985.5  625.44  4993.1  622.66
  4998.5  622.66  5009.7  620.34  5024.4  618.88  5024.7  618.38  5028.4  618.88
  5048.8  620.19  5093.5  627.06  5129.8  628.88  5138.2  629.99  5152.2  629.89
  5174.6   631.5  5196.9  635.22  5219.3  633.46    5250  637.55  5331.1  643.86
#Mann= 3 ,-1 , 0
  4652.5     .05       0  5024.4    .033       0  5028.4     .05       0
Bank Sta=5024.4,5028.4
XS Rating Curve= 0 ,0
Exp/Cntr=0.3,0.1

Type RM Length L Ch R = 1 ,7771    ,439,439,439
BEGIN DESCRIPTION:
Golf Course Creek Tr 1 18.0
END DESCRIPTION:
XS GIS Cut Line= 3
      2370043.58      7045535.85      2370614.15      7045442.36
      2370828.97      7045310.02
#Sta/Elev= 30
    4508  652.52  4543.9  649.64  4577.2  648.22  4633.5  643.81  4736.4  637.78
  4761.2  635.96  4817.5  630.22  4827.6  629.75  4837.8  630.43  4871.8   626.8
  4939.1  624.04  4969.5  623.68  4979.6  621.78  4989.8  618.14  5009.6  617.68
  5009.8  617.18  5013.6  617.68  5030.3  618.62  5040.4  621.06  5060.7  623.13
    5081  626.69  5104.9  627.94  5149.6  631.75  5193.6  635.81  5221.1  636.71
  5236.2  636.07  5244.6  637.47  5257.5  641.28  5288.3  646.65  5338.5  652.69
#Mann= 5 ,-1 , 0
    4508     .05       0  4871.8     .12       0  5009.6     .07       0
  5013.6     .12       0  5149.6     .05       0
Bank Sta=5009.6,5013.6
XS Rating Curve= 0 ,0
Exp/Cntr=0.3,0.1

Type RM Length L Ch R = 1 ,7332    ,542,542,542
BEGIN DESCRIPTION:
Golf Course Creek Tr 1 17.0
END DESCRIPTION:
XS GIS Cut Line= 3
      2370162.85      7045961.32      2370736.63      7045825.93
      2370985.31      7045626.99
#Sta/Elev= 30
  4572.8  654.98  4597.4  650.18  4630.5  646.59  4671.6  643.91  4687.2  641.13
    4777  634.86  4814.2  629.68  4819.3  630.24  4846.3  626.61  4861.6  626.79
  4897.6  622.76  4918.2  617.63  4938.7  615.06  4986.6  613.88  4986.8  613.38
  4990.6  613.88  4993.7  614.99  5036.1  616.36  5078.4  619.95  5083.5   619.1
  5113.4  621.05    5134  623.61  5190.2  625.47  5267.8  631.98  5353.5  636.66
  5382.3  639.82  5388.7  637.94  5403.1  638.21  5423.9  640.57  5480.8  641.34
#Mann= 3 ,-1 , 0
  4572.8     .05       0  4986.6     .05       0  4990.6     .05       0
Bank Sta=4986.6,4990.6
XS Rating Curve= 0 ,0
Exp/Cntr=0.3,0.1

Type RM Length L Ch R = 1 ,6790    ,203,203,203
BEGIN DESCRIPTION:
Golf Course Creek Tr 1 16.0
END DESCRIPTION:
XS GIS Cut Line= 3
      2370259.55      7046499.61      2370959.04      7046273.97
      2371335.09      7046161.47
#Sta/Elev= 30
  4401.8  631.31    4481  628.92  4537.8  628.64  4656.1   624.2  4737.7  622.05
    4844  620.48  4902.9  617.23  4926.6  612.02    4967  606.64  4989.6  605.51
    4997   603.7  4997.3   603.2    5001   603.7  5004.3  605.24  5010.6  604.79
  5026.6  606.59  5036.3  607.35  5042.2   609.4  5068.4  613.51  5094.7  612.07
  5100.4  612.84  5105.7  612.33  5126.2  615.37  5147.2  617.19  5198.6  618.56
  5236.9  621.25  5260.7  621.08  5303.1  624.33  5355.9  626.62  5529.3  637.22
#Mann= 7 ,-1 , 0
  4401.8     .05       0  4656.1      .1       0  4737.7     .05       0
    4997    .033       0    5001     .05       0  5026.6    .075       0
  5260.7     .05       0
Bank Sta=4997,5001
XS Rating Curve= 0 ,0
Exp/Cntr=0.3,0.1

Type RM Length L Ch R = 1 ,6587    ,263,263,263
BEGIN DESCRIPTION:
Golf Course Creek Tr 1 15.0
END DESCRIPTION:
XS GIS Cut Line= 3
      2370572.24      7046657.54      2370975.15      7046438.36
      2371264.58      7046309.72
#Sta/Elev= 30
  4587.5  619.54  4700.4  619.21  4891.3   616.9  4907.5  616.32  4923.6  612.41
  4929.3  612.68  4959.5  610.51  4967.3  607.49  4982.3  603.21  4987.2  602.59
  4987.4  602.09  4990.9  602.09  4991.2  602.59    5011  607.19  5039.2  610.27
  5045.5  611.54  5050.3  611.54  5055.1  612.19  5072.3  615.34  5078.4   617.1
  5083.9  615.87  5101.7  617.85  5107.1  616.89  5176.9  619.93  5236.4   621.9
  5291.1  622.19  5298.6  625.39  5304.1  625.38  5321.9  628.93  5362.9  630.58
#Mann= 3 ,-1 , 0
  4587.5     .05       0  4987.2    .033       0  4991.2     .05       0
Bank Sta=4987.2,4991.2
XS Rating Curve= 0 ,0
Exp/Cntr=0.3,0.1

Type RM Length L Ch R = 1 ,6324    ,352,352,352
BEGIN DESCRIPTION:
Golf Course Creek Tr 1 14.0
END DESCRIPTION:
XS GIS Cut Line= 3
      2370672.16      7046886.39        2370979.        7046710.
      2371210.48      7046570.49
#Sta/Elev= 30
  4641.9  618.21  4783.8  616.46  4870.1  616.29    4892   615.5  4923.2   609.7
    4929   607.4  4938.2  605.15  4944.8  605.01  4960.6   601.3  4966.4  601.74
  4970.8  596.17    4971  595.67  4974.5  595.67  4974.8  596.17  4982.2  602.79
  5009.4  603.12  5046.3  605.51  5054.2  608.44  5067.7   611.6  5077.4  612.82
  5098.7  613.55  5104.6  614.47  5112.6  614.05    5157  614.84  5184.2  616.77
  5221.1  616.85  5236.6  619.91  5257.9  622.49  5262.3  624.24  5266.1  624.24
#Mann= 3 ,-1 , 0
  4641.9     .05       0  4970.8    .033       0  4974.8     .05       0
Bank Sta=4970.8,4974.8
XS Rating Curve= 0 ,0
Exp/Cntr=0.3,0.1

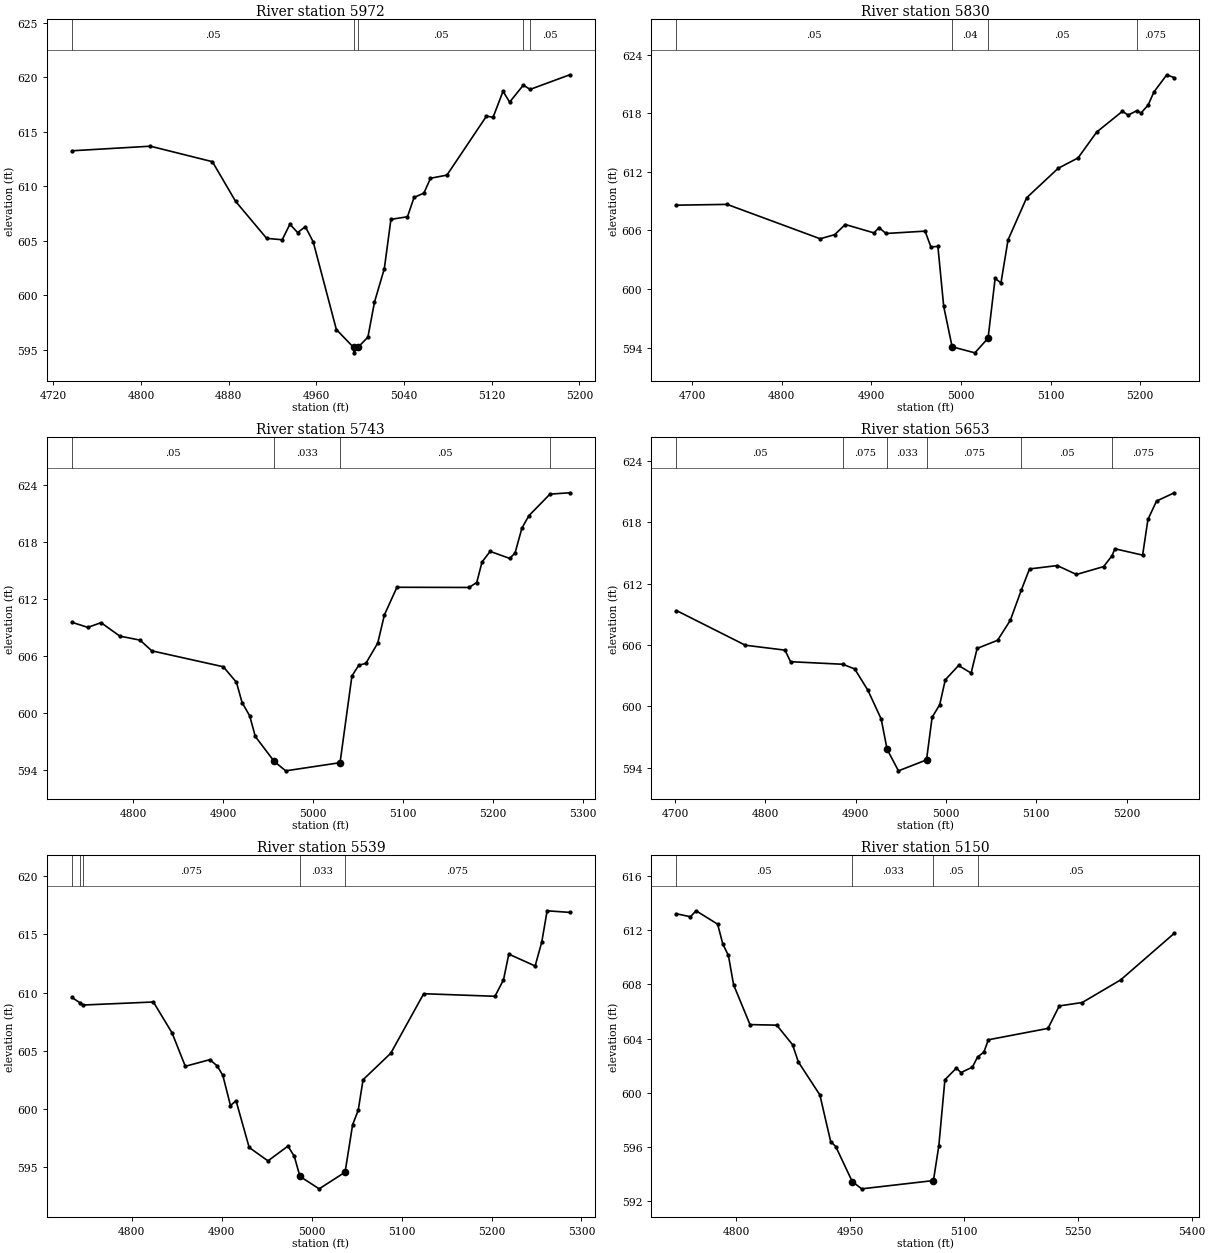
Type RM Length L Ch R = 1 ,5972    ,142,142,142
BEGIN DESCRIPTION:
Golf Course Creek Tr 1 13.0
END DESCRIPTION:
XS GIS Cut Line= 3
      2370992.21      7047144.48        2371179.        7046960.
      2371284.98      7046800.18
#Sta/Elev= 30
    4737  613.27  4808.6  613.69  4865.2  612.27  4886.4  608.63  4914.7  605.24
  4928.9  605.11  4935.9  606.53    4943  605.77    4950  606.31  4957.2  604.92
  4978.3  596.88    4994  595.24  4994.3  594.74    4998  595.24  5007.1  596.18
  5013.1  599.39  5022.1  602.47  5028.1  606.98  5043.2  607.22  5049.2  608.99
  5058.2  609.39  5064.2  610.75  5079.2  611.04  5115.3  616.45  5121.3  616.34
  5130.4  618.73  5136.4  617.73  5148.9  619.29  5155.1   618.9  5191.3  620.24
#Mann= 5 ,-1 , 0
    4737     .05       0    4994    .033       0    4998     .05       0
  5148.9    .075       0  5155.1     .05       0
Bank Sta=4994,4998
XS Rating Curve= 0 ,0
Exp/Cntr=0.3,0.1

Type RM Length L Ch R = 1 ,5830    ,87,87,87
BEGIN DESCRIPTION:
Golf Course Creek Tr 1 12.8
END DESCRIPTION:
XS GIS Cut Line= 3
      2371067.76      7047355.99      2371186.96      7047134.38
      2371380.03      7046899.34
#Sta/Elev= 30
  4682.3  608.59  4738.9  608.67  4842.8  605.15    4859  605.57  4870.8  606.61
  4902.9  605.75  4908.5   606.3  4916.2  605.69  4959.9  605.93  4966.4  604.31
  4974.2  604.37  4980.7  598.22  4990.1  594.09  5015.5  593.47  5030.2  594.97
  5038.1  601.09  5044.6  600.63  5052.5  605.03  5073.3  609.35  5108.4  612.36
  5130.7  613.43  5151.5  616.08  5180.2   618.2  5186.6  617.81    5196  618.25
    5201  618.03  5208.9  618.84  5215.3  620.17  5229.7  621.94  5238.1  621.64
#Mann= 4 ,-1 , 0
  4682.3     .05       0  4990.1     .04       0  5030.2     .05       0
    5196    .075       0
Bank Sta=4990.1,5030.2
XS Rating Curve= 0 ,0
Exp/Cntr=0.3,0.1

Type RM Length L Ch R = 1 ,5743    ,90,90,90
BEGIN DESCRIPTION:
Golf Course Creek Tr 1 12.6
END DESCRIPTION:
XS GIS Cut Line= 3
      2371114.78      7047371.07      2371307.82      7047107.52
      2371426.87       7046914.7
#Sta/Elev= 30
  4731.8  609.52  4749.6  608.98  4764.2  609.48  4785.1  608.06  4807.5  607.64
  4820.6  606.51  4900.1  604.83  4914.7  603.19  4920.9  601.06  4929.4  599.66
  4935.6  597.49  4956.5  594.87  4969.4  593.86  5029.8  594.72    5043  603.86
  5050.6  604.99  5058.5  605.19  5071.7  607.33  5079.1   610.3    5093  613.21
  5173.1  613.19  5181.7  613.71  5187.6  615.88  5196.6  616.99  5218.4  616.25
  5224.3  616.83  5231.9  619.45  5239.6  620.75  5263.1  623.03  5285.1  623.17
#Mann= 4 ,-1 , 0
  4731.8     .05       0  4956.5    .033       0  5029.8     .05       0
  5263.1    .075       0
Bank Sta=4956.5,5029.8
XS Rating Curve= 0 ,0
Exp/Cntr=0.3,0.1

Type RM Length L Ch R = 1 ,5653    ,114,114,114
BEGIN DESCRIPTION:
Golf Course Creek Tr 1 12.2
END DESCRIPTION:
XS GIS Cut Line= 3
      2371189.67      7047417.99      2371353.15      7047194.81
      2371497.59      7046960.85
#Sta/Elev= 30
  4701.3  609.37  4777.7  605.98  4821.6   605.5  4827.8  604.37  4885.7  604.12
  4898.9  603.66  4913.5  601.57  4928.2  598.77  4934.7  595.82  4947.3  593.71
  4978.4  594.78  4984.6  598.94    4993  600.17  4999.2   602.6  5013.9     604
  5027.8  603.26  5034.5  605.67  5057.1  606.46  5071.2  608.41  5083.3  611.34
  5092.5  613.43  5123.2  613.76  5144.5  612.89  5174.6  613.66  5183.9  614.72
  5187.1   615.4  5217.8  614.78  5223.7  618.27  5233.2  620.06  5252.9  620.87
#Mann= 6 ,-1 , 0
  4701.3     .05       0  4885.7    .075       0  4934.7    .033       0
  4978.4    .075       0  5083.3     .05       0  5183.9    .075       0
Bank Sta=4934.7,4978.4
XS Rating Curve= 0 ,0
Exp/Cntr=0.3,0.1

Type RM Length L Ch R = 1 ,5539    ,389,389,389
BEGIN DESCRIPTION:
Golf Course Creek Tr 1 12.0
END DESCRIPTION:
XS GIS Cut Line= 3
      2371237.34      7047523.79      2371430.36      7047260.28
      2371549.54      7047067.25
#Sta/Elev= 30
  4733.5  609.58  4742.4  609.13    4746  608.93  4824.1  609.19  4844.9  606.53
  4859.6  603.67  4886.9  604.24  4895.1   603.7  4901.3  602.89  4909.8   600.3
    4916  600.71  4930.6   596.7  4951.5  595.55  4973.7  596.82  4980.8  595.93
    4987  594.22  5008.4  593.15  5037.2  594.58  5045.6  598.66  5051.8  599.89
  5057.2  602.52    5088  604.79  5124.6   609.9  5203.8  609.68  5213.3  611.09
  5219.2   613.3  5248.5  612.28  5255.9  614.36  5261.8  617.02    5287  616.88
#Mann= 5 ,-1 , 0
  4733.5    .075       0  4742.4     .05       0    4746    .075       0
    4987    .033       0  5037.2    .075       0
Bank Sta=4987,5037.2
XS Rating Curve= 0 ,0
Exp/Cntr=0.3,0.1

Type RM Length L Ch R = 1 ,5150    ,350,350,350
BEGIN DESCRIPTION:
Golf Course Creek Tr 1 11.0
END DESCRIPTION:
XS GIS Cut Line= 3
      2371545.67      7047663.21        2371729.        7047460.
      2371938.89      7047141.06
#Sta/Elev= 30
  4721.6  613.21  4740.1  612.99  4747.5  613.43  4775.9  612.44  4782.7  610.98
  4790.1  610.13  4796.9  607.97  4818.5  605.03  4853.7  604.99  4874.6  603.54
  4882.1  602.28  4910.5  599.84  4924.7   596.4  4931.4  596.03  4953.1  593.45
  4965.5  592.91    5060  593.52  5067.1  596.09  5075.1  600.96  5090.2  601.82
  5096.2  601.49  5111.3  601.89  5118.1  602.64  5126.4     603  5132.3  603.91
  5210.8  604.75  5225.7  606.41  5255.9  606.66  5306.5  608.33  5377.1  611.77
#Mann= 4 ,-1 , 0
  4721.6     .05       0  4953.1    .033       0    5060     .05       0
  5118.1     .05       0
Bank Sta=4953.1,5060
XS Rating Curve= 0 ,0
Exp/Cntr=0.3,0.1

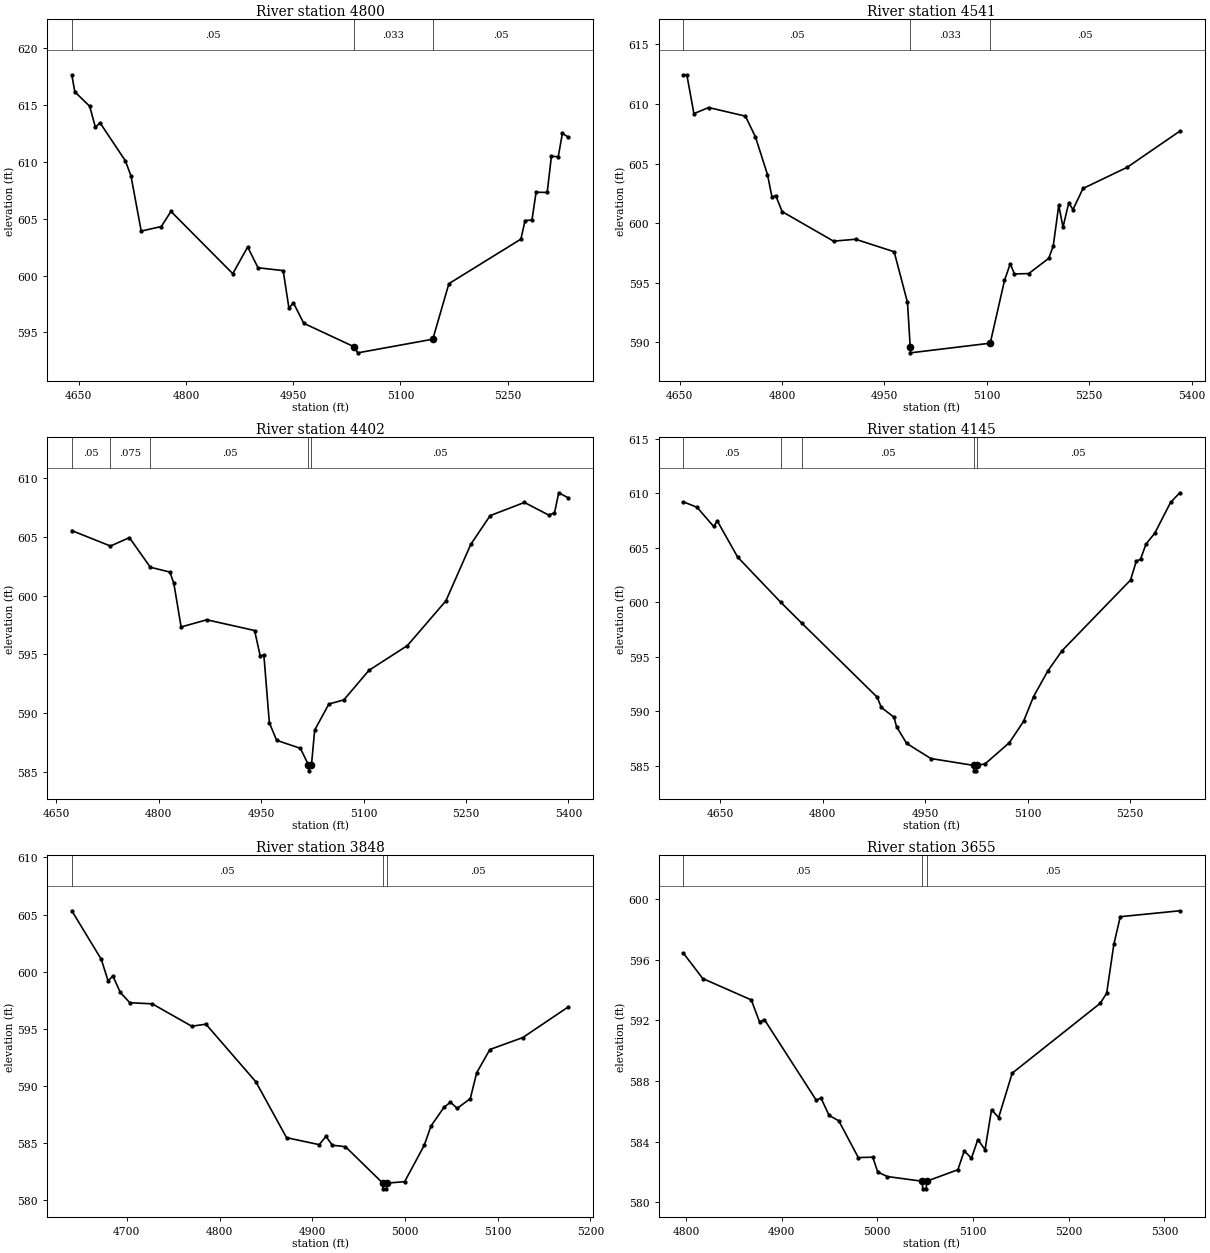
Type RM Length L Ch R = 1 ,4800    ,259,259,259
BEGIN DESCRIPTION:
Golf Course Creek Tr 1 10.0
END DESCRIPTION:
XS GIS Cut Line= 3
      2371648.16      7047944.01      2371996.93      7047666.42
      2372126.53       7047454.1
#Sta/Elev= 30
  4640.3  617.68  4644.5  616.18  4665.3  614.91  4673.3  613.06  4679.7  613.46
    4715  610.13    4723   608.8  4737.4  603.92  4765.5  604.32    4779  605.65
  4865.5  600.17  4886.3  602.52  4900.8  600.69    4936  600.44    4944  597.15
  4950.4  597.59  4964.8   595.8  5035.3  593.73  5040.4   593.2  5145.3   594.4
  5167.8  599.29  5268.5  603.21  5274.4  604.85    5284  604.89  5289.8  607.34
  5305.3  607.32  5311.2   610.5  5320.8  610.47  5326.6  612.53  5334.8  612.19
#Mann= 3 ,-1 , 0
  4640.3     .05       0  5035.3    .033       0  5145.3     .05       0
Bank Sta=5035.3,5145.3
XS Rating Curve= 0 ,0
Exp/Cntr=0.3,0.1

Type RM Length L Ch R = 1 ,4541    ,139,139,139
BEGIN DESCRIPTION:
Golf Course Creek Tr 1 9.6
END DESCRIPTION:
XS GIS Cut Line= 3
      2371774.56      7048043.53      2372058.17      7047930.73
      2372398.49      7047681.23
#Sta/Elev= 30
  4655.4  612.45  4660.5  612.45  4670.9  609.19  4692.5   609.7  4746.3  608.98
    4761  607.24  4778.6  604.08  4785.3  602.18  4790.7  602.32  4800.1  600.97
  4875.4  598.49  4907.7  598.65  4964.2   597.6  4983.7  593.35  4987.7  589.62
  4988.1  589.12  5104.9  589.93  5125.8  595.19  5134.2  596.59  5140.4  595.74
  5161.3  595.77  5190.6  597.05  5197.2  598.08  5205.3   601.5  5211.5  599.66
  5219.9   601.7  5226.1  601.14  5240.8  602.91  5305.6  604.69  5382.6  607.72
#Mann= 3 ,-1 , 0
  4655.4     .05       0  4987.7    .033       0  5104.9     .05       0
Bank Sta=4987.7,5104.9
XS Rating Curve= 0 ,0
Exp/Cntr=0.3,0.1

Type RM Length L Ch R = 1 ,4402    ,257,257,257
BEGIN DESCRIPTION:
Golf Course Creek Tr 1 9.4
END DESCRIPTION:
XS GIS Cut Line= 3
      2371900.22      7048108.02      2372183.88       7047995.2
      2372524.07      7047745.79
#Sta/Elev= 30
  4672.6  605.51  4729.2   604.2    4757  604.91  4787.6   602.4  4816.3  601.99
    4822  601.04  4832.7  597.33  4870.3  597.94  4940.3  597.03  4948.5  594.88
  4953.9  594.95  4961.9   589.2  4972.6  587.71  5007.4  587.03  5019.2  585.62
  5019.6  585.12  5023.6  585.62  5028.3  588.58  5049.1  590.79    5071  591.14
  5107.8  593.65  5164.1  595.75  5220.5  599.55    5257  604.35  5285.3  606.78
  5335.5   607.9    5371  606.83  5379.5     607  5385.7  608.72  5399.7  608.29
#Mann= 5 ,-1 , 0
  4672.6     .05       0  4729.2    .075       0  4787.6     .05       0
  5019.2     .05       0  5023.6     .05       0
Bank Sta=5019.2,5023.6
XS Rating Curve= 0 ,0
Exp/Cntr=0.3,0.1

Type RM Length L Ch R = 1 ,4145    ,297,297,297
BEGIN DESCRIPTION:
Golf Course Creek Tr 1 9.0
END DESCRIPTION:
XS GIS Cut Line= 3
      2371955.07       7048372.3      2372238.68      7048259.51
        2372579.        7048010.
#Sta/Elev= 30
  4595.7  609.21  4615.8  608.71  4640.1  606.95  4645.4  607.46  4675.3  604.14
  4738.1  600.02    4769   598.1  4879.7   591.3  4885.6  590.37  4904.2  589.47
    4908   588.6  4922.7  587.07  4958.2  585.68  5020.8  585.05  5021.2  584.55
  5024.8  584.55  5025.3  585.05  5037.7  585.19  5073.2  587.13    5094  589.08
  5108.7  591.36  5129.6  593.71  5150.4  595.56  5250.7  602.04  5259.2  603.77
  5265.4  603.95  5273.3  605.33  5286.3  606.34  5309.4  609.16  5322.9  610.04
#Mann= 5 ,-1 , 0
  4595.7     .05       0  4738.1    .075       0    4769     .05       0
  5020.8    .033       0  5025.3     .05       0
Bank Sta=5020.8,5025.3
XS Rating Curve= 0 ,0
Exp/Cntr=0.3,0.1

Type RM Length L Ch R = 1 ,3848    ,193,193,193
BEGIN DESCRIPTION:
Golf Course Creek Tr 1 8.3
END DESCRIPTION:
XS GIS Cut Line= 3
      2372158.05      7048604.41      2372351.49      7048559.27
      2372583.24      7048314.65
#Sta/Elev= 30
  4640.6  605.33  4672.4  601.08  4679.8  599.18  4684.9  599.63  4692.9  598.18
  4703.2  597.28  4727.4  597.18    4770  595.22  4785.3   595.4  4839.2  590.35
  4872.3  585.46  4907.5  584.85  4914.8  585.57  4921.7   584.8  4935.8  584.67
  4976.1  581.48  4976.5  580.98  4980.1  580.98  4980.6  581.48  4999.7  581.61
  5020.8  584.79  5028.1  586.48  5042.2  588.13  5049.1  588.56  5056.4  588.03
  5070.5  588.88  5077.4  591.14  5091.6  593.18  5127.2  594.23  5176.2  596.91
#Mann= 3 ,-1 , 0
  4640.6     .05       0  4976.1    .033       0  4980.6     .05       0
Bank Sta=4976.1,4980.6
XS Rating Curve= 0 ,0
Exp/Cntr=0.3,0.1

Type RM Length L Ch R = 1 ,3655    ,262,262,262
BEGIN DESCRIPTION:
Golf Course Creek Tr 1 8.0
END DESCRIPTION:
XS GIS Cut Line= 3
      2372229.05      7048649.52      2372483.65       7048604.4
      2372657.67      7048411.04
#Sta/Elev= 30
  4797.3  596.44  4817.6  594.76  4868.3  593.35  4876.9   591.9    4882  592.05
  4936.1  586.74  4941.1  586.88  4949.6  585.73  4959.7  585.38  4980.1  582.95
  4995.2  582.98  5000.4     582  5010.5   581.7    5047  581.39  5047.4  580.89
    5051  580.89  5051.5  581.39  5084.1  582.15  5090.8  583.39  5098.3  582.91
    5105  584.14  5112.5  583.47  5119.3  586.11  5126.7  585.59  5140.9  588.52
  5232.9  593.13  5239.6   593.8  5247.1  597.02  5253.8  598.84    5316  599.23
#Mann= 3 ,-1 , 0
  4797.3     .05       0    5047     .05       0  5051.5     .05       0
Bank Sta=5047,5051.5
XS Rating Curve= 0 ,0
Exp/Cntr=0.3,0.1