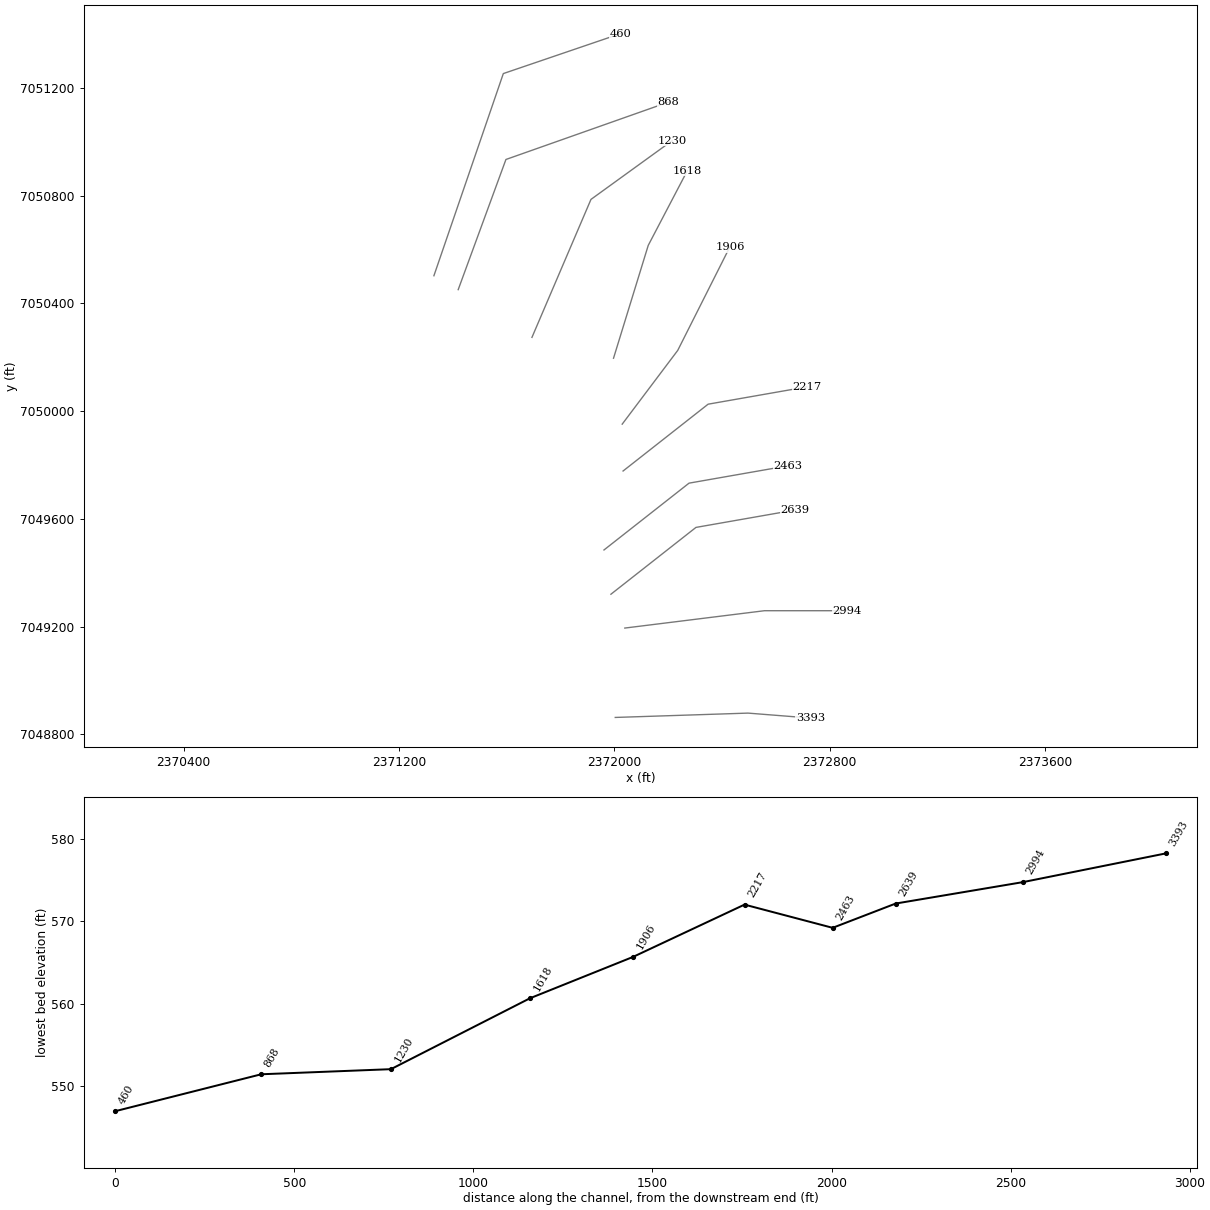
HEC-RAS study Golf Course Creek Tr 1.prj: Golf Course Creek Tr 1 Base Level Engineering

--- Golf Course Creek Tr 1.g01 (geometry) --- (continued)

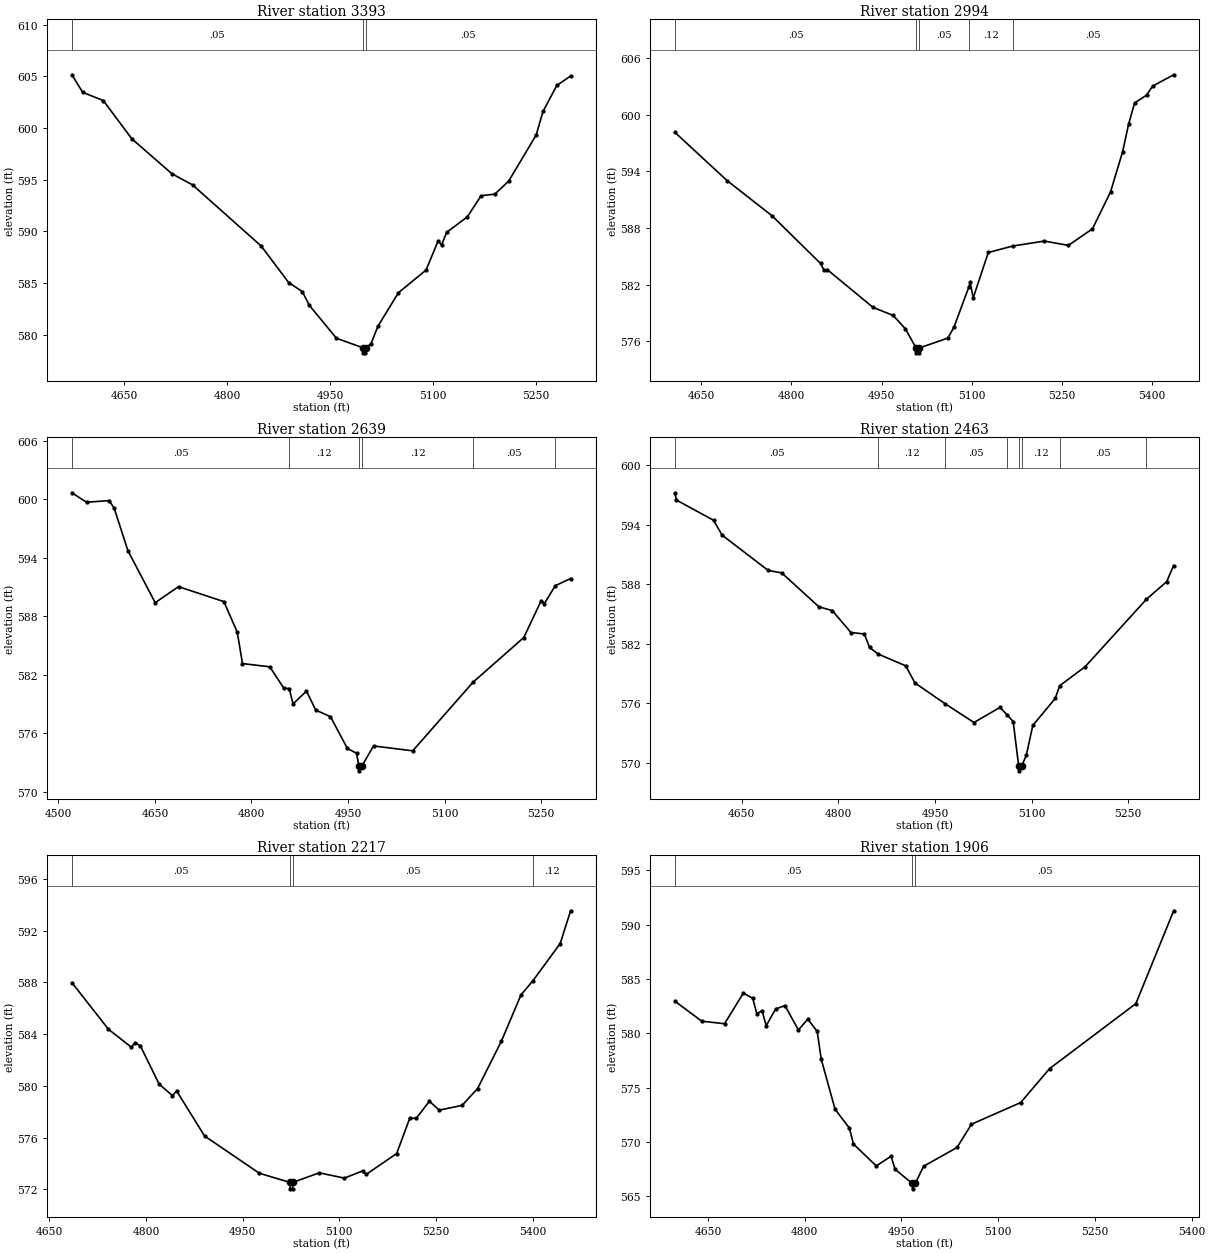
Type RM Length L Ch R = 1 ,3393    ,399,399,399
BEGIN DESCRIPTION:
Golf Course Creek Tr 1 7.0
END DESCRIPTION:
XS GIS Cut Line= 3
      2372003.33      7048862.26      2372496.54      7048878.38
      2372729.05        7048860.
#Sta/Elev= 30
  4573.7  605.14  4589.4  603.44  4619.4  602.65    4661  598.95  4719.4  595.57
  4749.5  594.49  4849.5  588.58  4889.5  585.05  4909.5  584.17  4919.6  582.85
  4959.2  579.66  4997.3  578.75  4997.8  578.25  5001.4  578.25  5001.9  578.75
  5009.6  579.14  5019.6  580.82  5049.6  584.07  5089.7  586.25  5107.4  589.08
  5112.4  588.69  5119.8   589.9  5149.9   591.4  5169.9  593.44    5190   593.6
  5210.1  594.85  5250.2  599.31  5260.2  601.59  5280.3  604.11  5300.4  605.02
#Mann= 3 ,-1 , 0
  4573.7     .05       0  4997.3    .033       0  5001.9     .05       0
Bank Sta=4997.3,5001.9
XS Rating Curve= 0 ,0
Exp/Cntr=0.3,0.1

Type RM Length L Ch R = 1 ,2994    ,355,355,355
BEGIN DESCRIPTION:
Golf Course Creek Tr 1 6.0
END DESCRIPTION:
XS GIS Cut Line= 3
      2372038.82      7049194.26      2372557.78      7049258.72
      2372864.03      7049258.72
#Sta/Elev= 30
  4606.4  598.13  4692.9  593.03  4767.8  589.29  4848.4  584.24  4854.6  583.49
  4859.7  583.58  4935.5  579.59  4969.3  578.72  4989.5  577.31  5007.4  575.26
  5007.8  574.76  5011.5  574.76    5012  575.26    5060  576.32  5070.1  577.45
  5095.1  581.75  5097.2  582.23  5102.3  580.59  5127.4   585.4  5168.5  586.09
  5220.6  586.61  5260.6  586.15  5300.6  587.91  5330.6  591.81  5350.6  596.05
  5360.6  598.98  5370.6  601.24  5390.6  602.08  5400.6  603.04  5435.6  604.24
#Mann= 5 ,-1 , 0
  4606.4     .05       0  5007.4    .033       0    5012     .05       0
  5095.1     .12       0  5168.5     .05       0
Bank Sta=5007.4,5012
XS Rating Curve= 0 ,0
Exp/Cntr=0.3,0.1

Type RM Length L Ch R = 1 ,2639    ,176,176,176
BEGIN DESCRIPTION:
Golf Course Creek Tr 1 5.6
END DESCRIPTION:
XS GIS Cut Line= 3
      2371987.28      7049319.98      2372303.14      7049568.16
      2372670.64      7049632.63
#Sta/Elev= 30
  4521.1  600.65  4543.9  599.68  4579.1  599.85  4586.9  599.05    4608  594.73
  4650.5  589.39  4686.7  591.03  4757.2   589.5    4778  586.37  4786.1  583.15
  4828.5  582.82  4850.3  580.63  4858.7  580.59  4864.7  579.02  4885.5  580.33
    4900  578.38  4922.8  577.71    4949  574.46  4963.3  573.96    4967  572.66
  4967.5  572.16  4971.7  572.66  4989.7  574.71  5050.6  574.21  5144.3  581.24
  5223.2  585.82  5250.2   589.6  5255.2   589.3  5272.1  591.13  5295.9  591.86
#Mann= 6 ,-1 , 0
  4521.1     .05       0  4858.7     .12       0    4967     .07       0
  4971.7     .12       0  5144.3     .05       0  5272.1     .12       0
Bank Sta=4967,4971.7
XS Rating Curve= 0 ,0
Exp/Cntr=0.3,0.1

Type RM Length L Ch R = 1 ,2463    ,246,246,246
BEGIN DESCRIPTION:
Golf Course Creek Tr 1 5.4
END DESCRIPTION:
XS GIS Cut Line= 3
      2371961.47      7049484.35      2372277.36      7049732.54
      2372644.43      7049796.94
#Sta/Elev= 30
  4546.2  597.23  4548.3   596.5  4606.1  594.46  4619.4  592.96  4691.1   589.4
  4711.9  589.16  4769.7  585.74  4790.5  585.36  4819.4  583.15  4840.3     583
  4848.3  581.65  4861.6  580.98  4904.4   579.8  4918.9  578.06  4965.3  575.99
  5010.5  574.08  5051.1  575.61    5062  574.84  5071.4  574.18  5079.9  569.71
  5080.4  569.21  5084.6  569.71  5091.7  570.76  5101.9  573.79  5136.6   576.5
  5143.7  577.79  5183.1   579.7  5278.3   586.5  5309.7  588.27  5320.6   589.9
#Mann= 8 ,-1 , 0
  4546.2     .05       0  4861.6     .12       0  4965.3     .05       0
    5062     .12       0  5079.9    .033       0  5084.6     .12       0
  5143.7     .05       0  5278.3     .12       0
Bank Sta=5079.9,5084.6
XS Rating Curve= 0 ,0
Exp/Cntr=0.3,0.1

Type RM Length L Ch R = 1 ,2217    ,311,311,311
BEGIN DESCRIPTION:
Golf Course Creek Tr 1 5.0
END DESCRIPTION:
XS GIS Cut Line= 3
      2372032.36      7049777.65      2372348.27      7050025.86
      2372714.91      7050090.18
#Sta/Elev= 30
  4685.1  587.99  4741.8  584.38  4777.1     583  4783.4  583.35  4791.5  583.08
  4820.4  580.14  4841.2  579.24  4847.6  579.61    4891  576.12  4975.9  573.24
  5023.3  572.53  5023.8  572.03  5027.5  572.03    5028  572.53    5069  573.27
  5107.9  572.86  5136.5  573.42  5141.6  573.14  5189.1  574.76  5209.4  577.49
  5219.6  577.49  5239.9  578.81  5255.3  578.12  5290.7  578.49  5314.7  579.79
  5351.6  583.45    5382  587.03  5400.8  588.15  5442.9  591.01  5459.1  593.55
#Mann= 4 ,-1 , 0
  4685.1     .05       0  5023.3    .033       0    5028     .05       0
  5400.8     .12       0
Bank Sta=5023.3,5028
XS Rating Curve= 0 ,0
Exp/Cntr=0.3,0.1

Type RM Length L Ch R = 1 ,1906    ,288,288,288
BEGIN DESCRIPTION:
Golf Course Creek Tr 1 4.0
END DESCRIPTION:
XS GIS Cut Line= 3
      2372029.17      7049951.74      2372235.45       7050225.7
      2372428.99      7050609.98
#Sta/Elev= 30
  4598.8  582.96  4640.3  581.12  4675.7  580.89  4704.8  583.71  4719.4  583.23
  4725.6  581.82  4733.9  582.08  4740.2   580.7  4754.8  582.24  4769.3  582.56
  4790.2  580.31  4804.7  581.31  4819.3  580.18  4825.6  577.62    4847  573.01
  4869.3  571.27  4875.5  569.81  4910.9  567.79  4933.8  568.68  4940.1  567.48
  4966.6  566.18  4967.1  565.68  4971.3  566.18  4984.4  567.76  5036.1  569.49
  5058.5  571.63  5134.9  573.63  5179.6  576.75  5313.4  582.74    5372  591.29
#Mann= 3 ,-1 , 0
  4598.8     .05       0  4966.6     .04       0  4971.3     .05       0
Bank Sta=4966.6,4971.3
XS Rating Curve= 0 ,0
Exp/Cntr=0.3,0.1

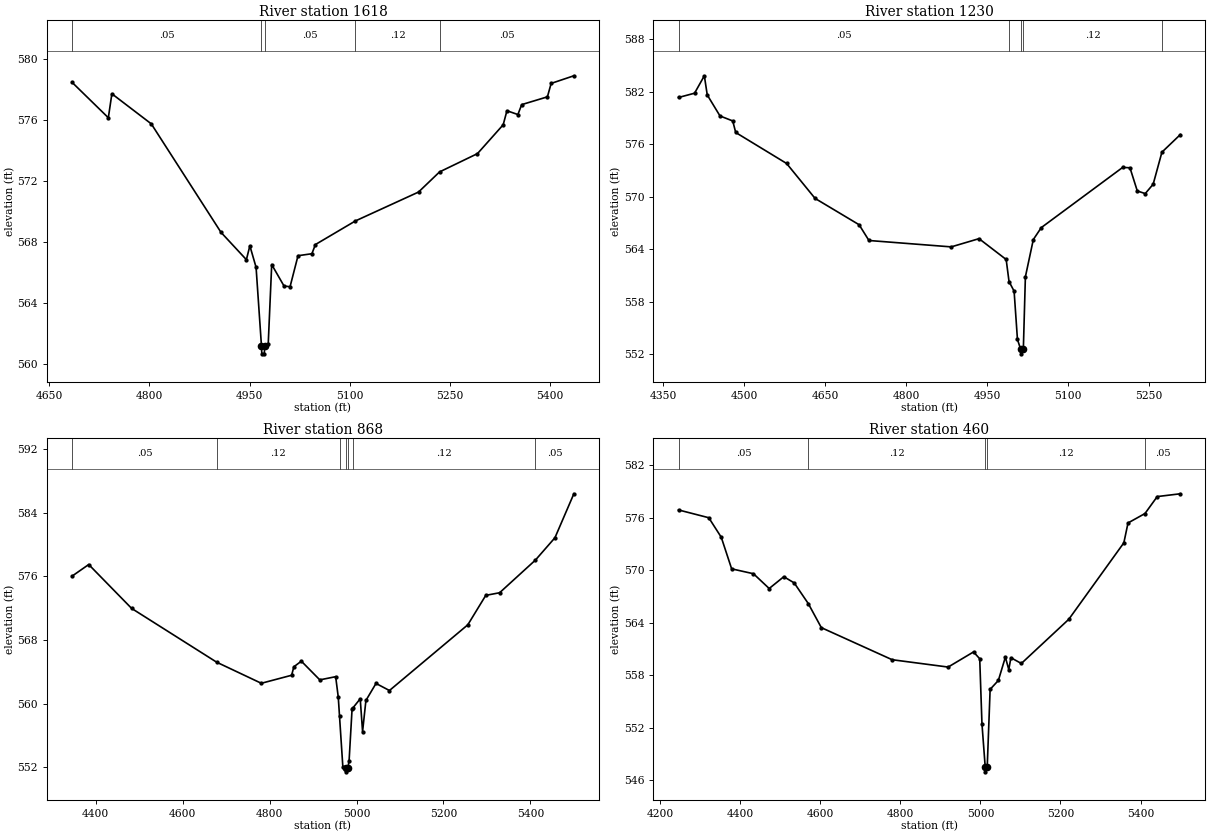
Type RM Length L Ch R = 1 ,1618    ,388,388,388
BEGIN DESCRIPTION:
Golf Course Creek Tr 1 3.0
END DESCRIPTION:
XS GIS Cut Line= 3
      2371996.92      7050196.65      2372125.86      7050615.72
       2372270.9      7050892.91
#Sta/Elev= 30
  4684.3  578.44  4738.6  576.12  4743.9  577.69  4802.9  575.72  4907.3  568.61
  4945.3  566.82  4950.5  567.73  4959.8  566.32  4967.9  561.15  4968.4  560.65
  4972.1  560.65  4972.7  561.15    4978  561.31  4983.2   566.5  5001.7  565.09
  5010.7  565.05  5022.6  567.08  5043.4  567.21  5048.6  567.81  5108.6  569.36
    5203  571.25  5234.5  572.57  5291.3  573.77  5329.8  575.66  5335.4  576.58
  5351.8  576.33  5357.5  576.98    5396  577.49  5401.6  578.37  5435.6  578.87
#Mann= 5 ,-1 , 0
  4684.3     .05       0  4967.9    .033       0  4972.7     .05       0
  5108.6     .12       0  5234.5     .05       0
Bank Sta=4967.9,4972.7
XS Rating Curve= 0 ,0
Exp/Cntr=0.3,0.1

Type RM Length L Ch R = 1 ,1230    ,362,362,362
BEGIN DESCRIPTION:
Golf Course Creek Tr 1 2.5
END DESCRIPTION:
XS GIS Cut Line= 3
      2371693.93      7050274.02      2371913.13      7050786.55
      2372214.58      7051004.63
#Sta/Elev= 30
  4378.4  581.33  4408.1  581.82  4426.2  583.81  4431.6  581.62  4455.2  579.22
  4478.8  578.65  4484.3  577.33  4578.6  573.79  4631.3   569.8  4712.9  566.79
  4731.1  564.99  4883.5  564.26    4935   565.2  4985.3  562.82  4990.6   560.3
    5000   559.2  5006.2  553.68  5012.3  552.54  5012.9  552.04  5017.1  552.54
  5020.9  560.84  5035.6   565.1  5050.3  566.46  5201.1  573.34  5214.6   573.3
  5228.2  570.65  5242.9  570.35  5257.6  571.42  5273.8  575.08  5307.9  577.09
#Mann= 5 ,-1 , 0
  4378.4     .05       0  4990.6     .12       0  5012.3     .07       0
  5017.1     .12       0  5273.8     .05       0
Bank Sta=5012.3,5017.1
XS Rating Curve= 0 ,0
Exp/Cntr=0.3,0.1

Type RM Length L Ch R = 1 ,868     ,408,408,408
BEGIN DESCRIPTION:
Golf Course Creek Tr 1 2.0
END DESCRIPTION:
XS GIS Cut Line= 3
      2371419.97      7050451.34      2371597.24      7050934.83
      2372200.04      7051147.58
#Sta/Elev= 30
  4345.7  576.04    4384   577.5  4482.7  571.98  4678.4  565.21    4781  562.56
  4850.7  563.57  4855.9  564.64  4873.1  565.34  4915.5  562.99    4952  563.39
    4958  560.82  4960.9   558.4  4968.6  551.99  4975.2  551.92  4975.8  551.42
  4980.1  551.92  4982.9  552.81  4989.8  559.37  4992.2   559.5  5008.5  560.61
  5013.9  556.49  5021.6   560.4  5044.8  562.54  5075.7  561.65    5256  569.92
  5297.3  573.62  5329.1  573.95  5411.5  578.06  5456.4  580.87  5499.9   586.4
#Mann= 7 ,-1 , 0
  4345.7     .05       0  4678.4     .12       0  4960.9     .05       0
  4975.2     .07       0  4980.1     .05       0  4992.2     .12       0
  5411.5     .05       0
Bank Sta=4975.2,4980.1
XS Rating Curve= 0 ,0
Exp/Cntr=0.3,0.1

Type RM Length L Ch R = 1 ,460     ,0,0,0
BEGIN DESCRIPTION:
Golf Course Creek Tr 1 1.0
END DESCRIPTION:
XS GIS Cut Line= 3
      2371329.73      7050502.95      2371587.57      7051253.93
       2372022.7      7051402.19
#Sta/Elev= 30
  4245.7   576.9  4321.2  576.01  4352.4  573.78  4378.4  570.16  4432.9   569.6
  4472.2  567.91  4508.7  569.26  4534.7  568.55  4569.8  566.19  4602.5  563.43
  4779.4  559.76  4919.3  558.92  4982.7  560.65  4998.2  559.87  5003.8  552.42
    5012  547.43  5012.6  546.93  5016.9  547.43  5024.2  556.37  5044.8  557.39
  5062.3  560.06  5070.8  558.63  5076.1  559.99  5102.2  559.33  5220.8  564.39
  5358.3  573.14  5368.7  575.41  5411.1  576.49  5441.7  578.43  5499.4  578.75
#Mann= 5 ,-1 , 0
  4245.7     .05       0  4569.8     .12       0    5012     .07       0
  5016.9     .12       0  5411.1     .05       0
Bank Sta=5012,5016.9
XS Rating Curve= 0 ,0
Exp/Cntr=0.3,0.1

Chan Stop Cuts=-1
Use User Specified Reach Order=0
Composite Channel Slope=5