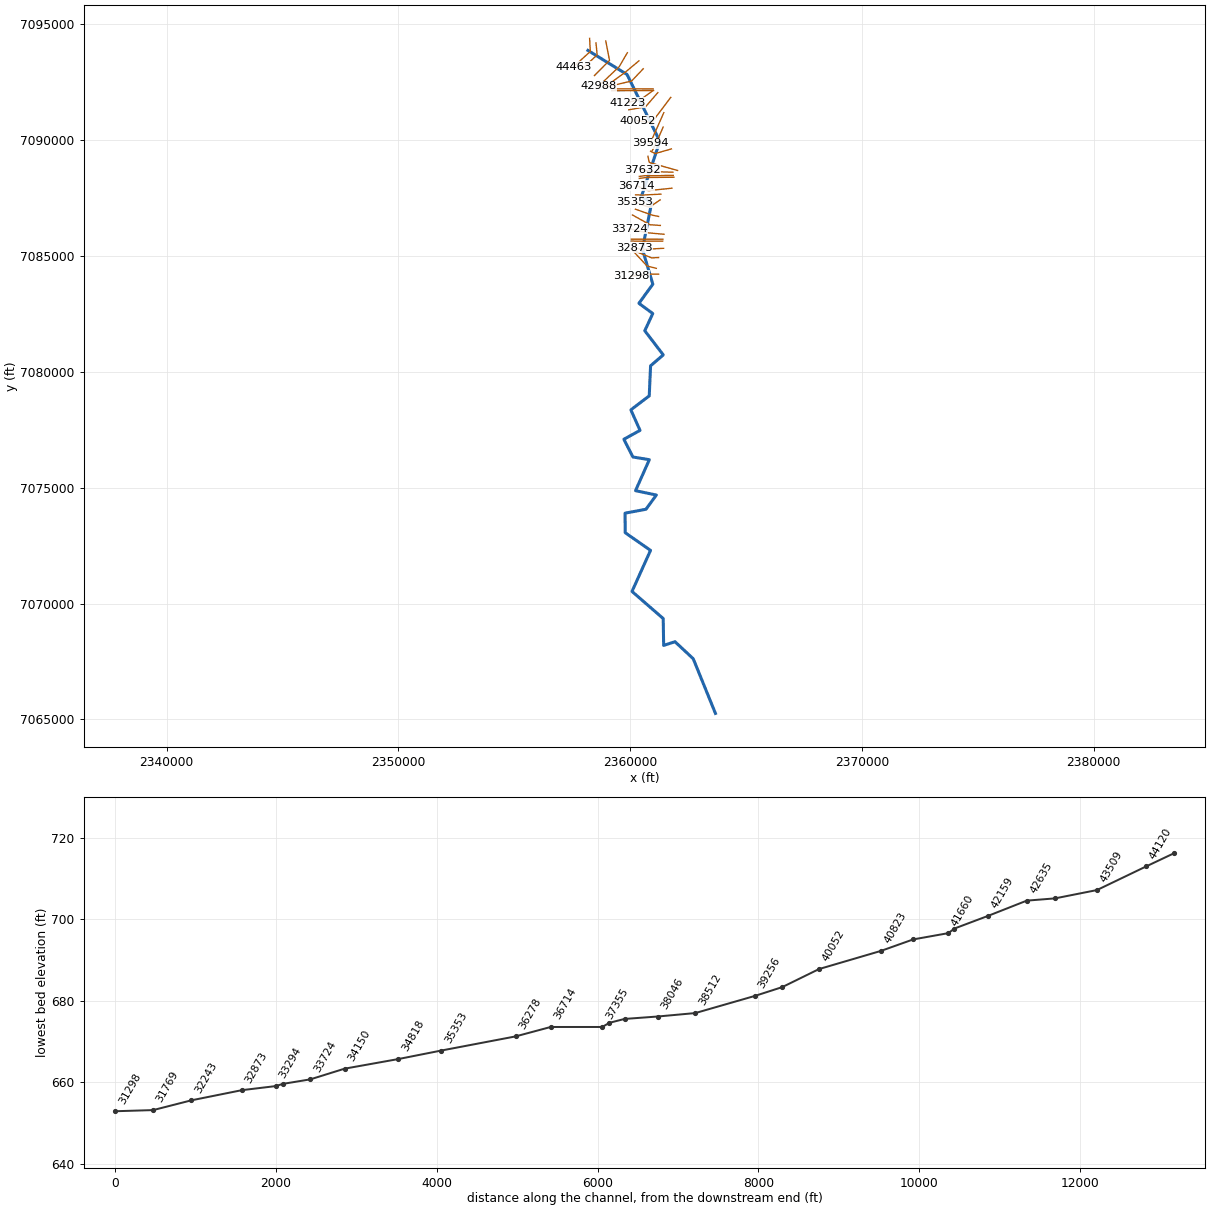
--- Graham Branch.prj (project) ---

Proj Title=Graham Branch Base Level Engineering
Current Plan=p01
Default Exp/Contr=0.3,0.1
English Units
Geom File=g01
Flow File=f01
Plan File=p01
Y Axis Title=Elevation
X Axis Title(PF)=Main Channel Distance
X Axis Title(XS)=Station
BEGIN DESCRIPTION:
Graham Branch
END DESCRIPTION:
DSS Export Rating Curves= 0
DSS Export Rating Curve Sorted= 0
DSS Export Volume Flow Curves= 0
DXF OffsetX= 0
DXF OffsetY= 0
DXF ScaleX= 1
DXF ScaleY= 10

--- Graham Branch.p01 (plan) ---

Plan Title=Multiple Run
Short Identifier=Multiple
Geom File=g01
Flow File=f01
Subcritical Flow
K Sum by GR= 0
Std Step Tol= 0.01
Critical Tol= 0.01
Num of Std Step Trials= 20
Max Error Tol= 0.3
Flow Tol Ratio= 0.001
Split Flow NTrial= 30
Split Flow Tol= 0.02
Split Flow Ratio= 0.02
Log Output Level= 0
Friction Slope Method= 1
Unsteady Friction Slope Method= 2
Unsteady Bridges Friction Slope Method= 1
Parabolic Critical Depth
Global Vel Dist=  1 , 1 , 1
Global Log Level= 0
CheckData=True
Encroach Param= -1, 0, 0, 0
BEGIN DESCRIPTION:
Multiple Run
END DESCRIPTION:

--- Graham Branch.f01 (steady flow) ---

Flow Title=Multiple
Program Version=4.10
Number of Profiles= 7
Profile Names=10-year,25-year,50-year,1pct_min,100-year,1pct_plu,500-year
River Rch & RM=Graham Branch,Reach-1         ,44463
     221     282     328     190     380     758     509
River Rch & RM=Graham Branch,Reach-1         ,42988
     515     694     838     503    1003    2001    1438
River Rch & RM=Graham Branch,Reach-1         ,39594
     703     961    1173     710    1417    2827    2072
River Rch & RM=Graham Branch,Reach-1         ,37632
     872    1206    1484     905    1806    3603    2680
River Rch & RM=Graham Branch,Reach-1         ,37355
     957    1328    1638    1000    1996    3982    2972
River Rch & RM=Graham Branch,Reach-1         ,34818
    1157    1621    2010    1234    2463    4914    3707
River Rch & RM=Graham Branch,Reach-1         ,31298
    1426    2019    2522    1558    3110    6204    4742
River Rch & RM=Graham Branch,Reach-1         ,28453
    1594    2266    2840    1759    3511    7005    5383
River Rch & RM=Graham Branch,Reach-1         ,25959
    1765    2519    3165    1965    3922    7825    6041
River Rch & RM=Graham Branch,Reach-1         ,22614
    2032    2917    3678    2292    4572    9123    7089
River Rch & RM=Graham Branch,Reach-1         ,19738
    2110    3031    3824    2384    4756    9490    7381
River Rch & RM=Graham Branch,Reach-1         ,16436
    2201    3167    3999    2495    4978    9931    7737
River Rch & RM=Graham Branch,Reach-1         ,11252
    2296    3309    4183    2612    5212   10399    8117
River Rch & RM=Graham Branch,Reach-1         ,10511
    2389    3447    4361    2726    5438   10850    8483
River Rch & RM=Graham Branch,Reach-1         ,7442
    2474    3575    4528    2832    5650   11274    8828
River Rch & RM=Graham Branch,Reach-1         ,2480
    2551    3692    4680    2930    5845   11663    9149
River Rch & RM=Graham Branch,Reach-1         ,590
    2692    3903    4955    3105    6196   12362    9721
Boundary for River Rch & Prof#=Graham Branch,Reach-1         , 1
Up Type= 0
Dn Type= 3
Dn Slope=0.00505
Boundary for River Rch & Prof#=Graham Branch,Reach-1         , 2
Up Type= 0
Dn Type= 3
Dn Slope=0.00505
Boundary for River Rch & Prof#=Graham Branch,Reach-1         , 3
Up Type= 0
Dn Type= 3
Dn Slope=0.00505
Boundary for River Rch & Prof#=Graham Branch,Reach-1         , 4
Up Type= 0
Dn Type= 3
Dn Slope=0.00505
Boundary for River Rch & Prof#=Graham Branch,Reach-1         , 5
Up Type= 0
Dn Type= 3
Dn Slope=0.00505
Boundary for River Rch & Prof#=Graham Branch,Reach-1         , 6
Up Type= 0
Dn Type= 3
Dn Slope=0.00505
Boundary for River Rch & Prof#=Graham Branch,Reach-1         , 7
Up Type= 0
Dn Type= 3
Dn Slope=0.00505
DSS Import GetInterval= 0
DSS Import GetPeak= 0
DSS Import FillOption= 0

--- Graham Branch.g01 (geometry) ---

Geom Title=Existing Conditions
Program Version=4.10

River Reach=Graham Branch   ,Reach-1
Reach XY= 30
        2358179.        7093860.      2359868.22      7092819.68
      2361279.21      7089939.95      2360486.53      7087559.99
      2360929.14      7087294.59      2360528.37      7085284.91
      2360978.49      7083775.21       2360378.2      7082949.95
      2360975.88      7082509.01      2360631.06      7081765.86
      2361428.69      7080725.12      2360881.23      7080254.07
      2360823.55      7078957.34      2360031.16      7078354.02
      2360425.76      7077467.96      2359728.49      7077085.04
      2360118.89       7076320.3      2360827.42      7076203.95
      2360232.32      7074868.05       2361129.4      7074678.48
      2360681.45      7074065.46      2359780.42      7073897.85
      2359787.13      7073053.92      2360879.37      7072291.59
      2360079.98      7070520.28      2361426.08      7069351.36
      2361445.49      7068192.95      2361935.54      7068350.77
      2362721.27       7067616.5        2363679.        7065260.

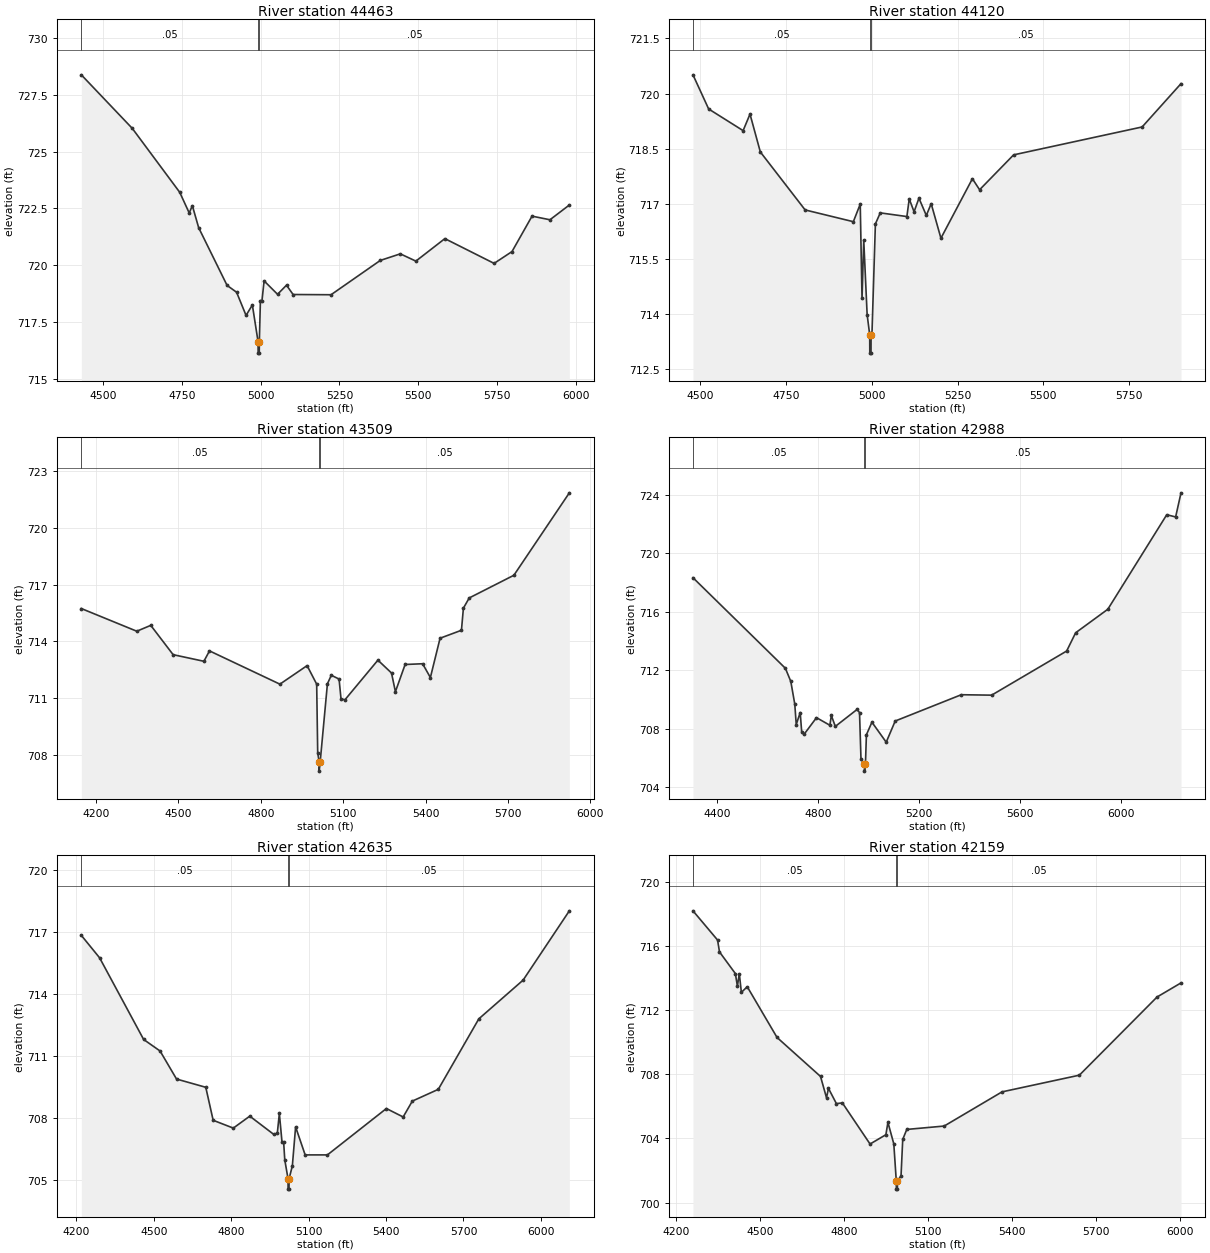
Type RM Length L Ch R = 1 ,44463   ,343,343,343
BEGIN DESCRIPTION:
Graham Branch 81.0
END DESCRIPTION:
XS GIS Cut Line= 3
      2358251.02      7094381.49      2358280.68      7093814.06
      2357557.36      7093154.62
#Sta/Elev= 30
  4431.8  728.38  4593.5  726.02  4743.7  723.21  4773.8   722.3  4783.8  722.62
  4803.8  721.65  4893.9  719.11    4924  718.81    4954  717.79    4974  718.25
  4992.1  716.63  4992.3  716.13  4995.8  716.13  4996.1  716.63  4999.5  718.44
  5004.5  718.44  5011.2  719.31  5053.8  718.72  5082.2  719.12  5103.1  718.71
  5223.4   718.7  5379.5  720.21    5443   720.5  5492.3  720.18  5584.2  721.17
  5740.3  720.08    5797   720.6  5860.5  722.16  5917.3     722  5978.8  722.65
#Mann= 3 ,-1 , 0
  4431.8     .05       0  4992.1    .033       0  4996.1     .05       0
Bank Sta=4992.1,4996.1
XS Rating Curve= 0 ,0
Exp/Cntr=0.3,0.1

Type RM Length L Ch R = 1 ,44120   ,611,611,611
BEGIN DESCRIPTION:
Graham Branch 80.0
END DESCRIPTION:
XS GIS Cut Line= 3
      2358525.76       7094185.5      2358576.81       7093666.1
      2357915.13      7093053.98
#Sta/Elev= 30
  4478.1  720.51  4523.8  719.58  4624.3  718.99  4644.4  719.44  4674.5  718.41
  4805.2  716.83  4945.8  716.51  4965.9  716.99  4971.1  714.42  4976.1  716.01
    4986  713.98  4993.5  713.43  4993.8  712.93  4997.3  712.93  4997.5  713.43
    5000  713.43  5010.1  716.45  5024.3  716.75  5101.9  716.65  5108.8  717.13
  5122.9  716.78  5137.1  717.15  5158.6  716.68  5172.8     717  5201.2  716.06
    5293  717.68    5314  717.38  5413.2  718.33    5788  719.09  5901.4  720.27
#Mann= 3 ,-1 , 0
  4478.1     .05       0  4993.5    .033       0  4997.5     .05       0
Bank Sta=4993.5,4997.5
XS Rating Curve= 0 ,0
Exp/Cntr=0.3,0.1

Type RM Length L Ch R = 1 ,43509   ,521,521,521
BEGIN DESCRIPTION:
Graham Branch 79.0
END DESCRIPTION:
XS GIS Cut Line= 3
      2358948.72      7094268.26      2359109.11      7093430.27
      2358458.26      7092775.24
#Sta/Elev= 30
  4146.8  715.74  4348.7  714.54  4399.6  714.85    4481   713.3    4593  712.95
  4613.4   713.5  4869.7  711.74  4968.7  712.72  5003.6  711.74  5007.3  708.12
  5012.4  707.64  5012.7  707.14  5016.4  707.64  5042.7  711.76  5056.8  712.21
  5085.1  712.01  5092.2  710.96  5106.3  710.91  5226.5  713.01    5276  712.33
  5290.2  711.34  5325.5  712.78  5389.2  712.82  5417.5  712.09  5452.8  714.17
  5530.6  714.59  5537.7  715.76  5558.9   716.3  5721.5   717.5  5923.4  721.86
#Mann= 3 ,-1 , 0
  4146.8     .05       0  5012.4    .033       0  5016.4     .05       0
Bank Sta=5012.4,5016.4
XS Rating Curve= 0 ,0
Exp/Cntr=0.3,0.1

Type RM Length L Ch R = 1 ,42988   ,353,353,353
BEGIN DESCRIPTION:
Graham Branch 77.0
END DESCRIPTION:
XS GIS Cut Line= 3
      2359879.01      7093760.01        2359529.        7093160.
      2358628.98      7092309.98
#Sta/Elev= 30
  4305.4  718.34  4671.3  712.14  4692.8  711.24  4708.5  709.69  4714.3  708.29
    4730  709.11  4735.8   707.8  4745.3  707.62  4794.5  708.76  4847.5  708.24
  4853.3  708.91    4869  708.16    4955  709.32  4964.9  709.11  4970.7  705.91
  4984.4   705.6  4984.6   705.1  4988.4   705.6  4992.2  707.59    5014  708.45
  5070.6  707.08  5106.2  708.53    5368  710.33  5488.1   710.3  5785.1  713.32
  5820.7  714.57  5948.1  716.18  6181.5  722.65  6216.7   722.5    6238  724.15
#Mann= 3 ,-1 , 0
  4305.4     .05       0  4984.4    .033       0  4988.4     .05       0
Bank Sta=4984.4,4988.4
XS Rating Curve= 0 ,0
Exp/Cntr=0.3,0.1

Type RM Length L Ch R = 1 ,42635   ,476,476,476
BEGIN DESCRIPTION:
Graham Branch 76.0
END DESCRIPTION:
XS GIS Cut Line= 3
        2360379.        7093410.        2359779.        7092910.
        2358879.        7092260.
#Sta/Elev= 30
    4219  716.85  4289.9  715.76  4460.5   711.8  4524.2  711.24    4588  709.88
  4701.3  709.48  4729.9  707.88    4808   707.5  4871.8  708.08  4964.2   707.2
  4978.5  707.25  4986.4  708.21  4996.8  706.81  5003.1  706.81  5007.4  705.96
  5020.1  705.04  5020.3  704.54  5023.8  704.54  5024.1  705.04  5036.8  705.67
  5049.4  707.56  5086.4   706.2  5172.7   706.2  5401.2  708.45  5466.2  708.04
  5501.7  708.81  5602.3  709.38  5759.4   712.8  5931.1  714.68  6110.2  718.04
#Mann= 3 ,-1 , 0
    4219     .05       0  5020.1    .033       0  5024.1     .05       0
Bank Sta=5020.1,5024.1
XS Rating Curve= 0 ,0
Exp/Cntr=0.3,0.1

Type RM Length L Ch R = 1 ,42159   ,423,423,423
BEGIN DESCRIPTION:
Graham Branch 75.0
END DESCRIPTION:
XS GIS Cut Line= 3
      2360564.81      7093068.35      2360062.24       7092539.7
      2359075.62      7092307.88
#Sta/Elev= 30
  4259.5  718.18  4347.3  716.36  4354.2  715.62  4410.9  714.27  4418.1  713.49
    4425  714.26  4432.3   713.1  4453.3  713.45  4559.7  710.29    4715  707.86
  4736.4  706.53  4743.3  707.12  4771.6  706.17  4793.1  706.21  4891.9  703.65
  4948.4  704.23  4955.7     705  4976.7  703.66  4985.6  701.34  4985.9  700.84
  4989.4  700.84  4989.6  701.34  5002.5  701.67  5008.6  703.94  5023.1  704.56
  5156.6  704.77  5363.2   706.9  5639.4  707.94  5916.8  712.81  6002.4  713.69
#Mann= 3 ,-1 , 0
  4259.5     .05       0  4985.6    .033       0  4989.6     .05       0
Bank Sta=4985.6,4989.6
XS Rating Curve= 0 ,0
Exp/Cntr=0.3,0.1

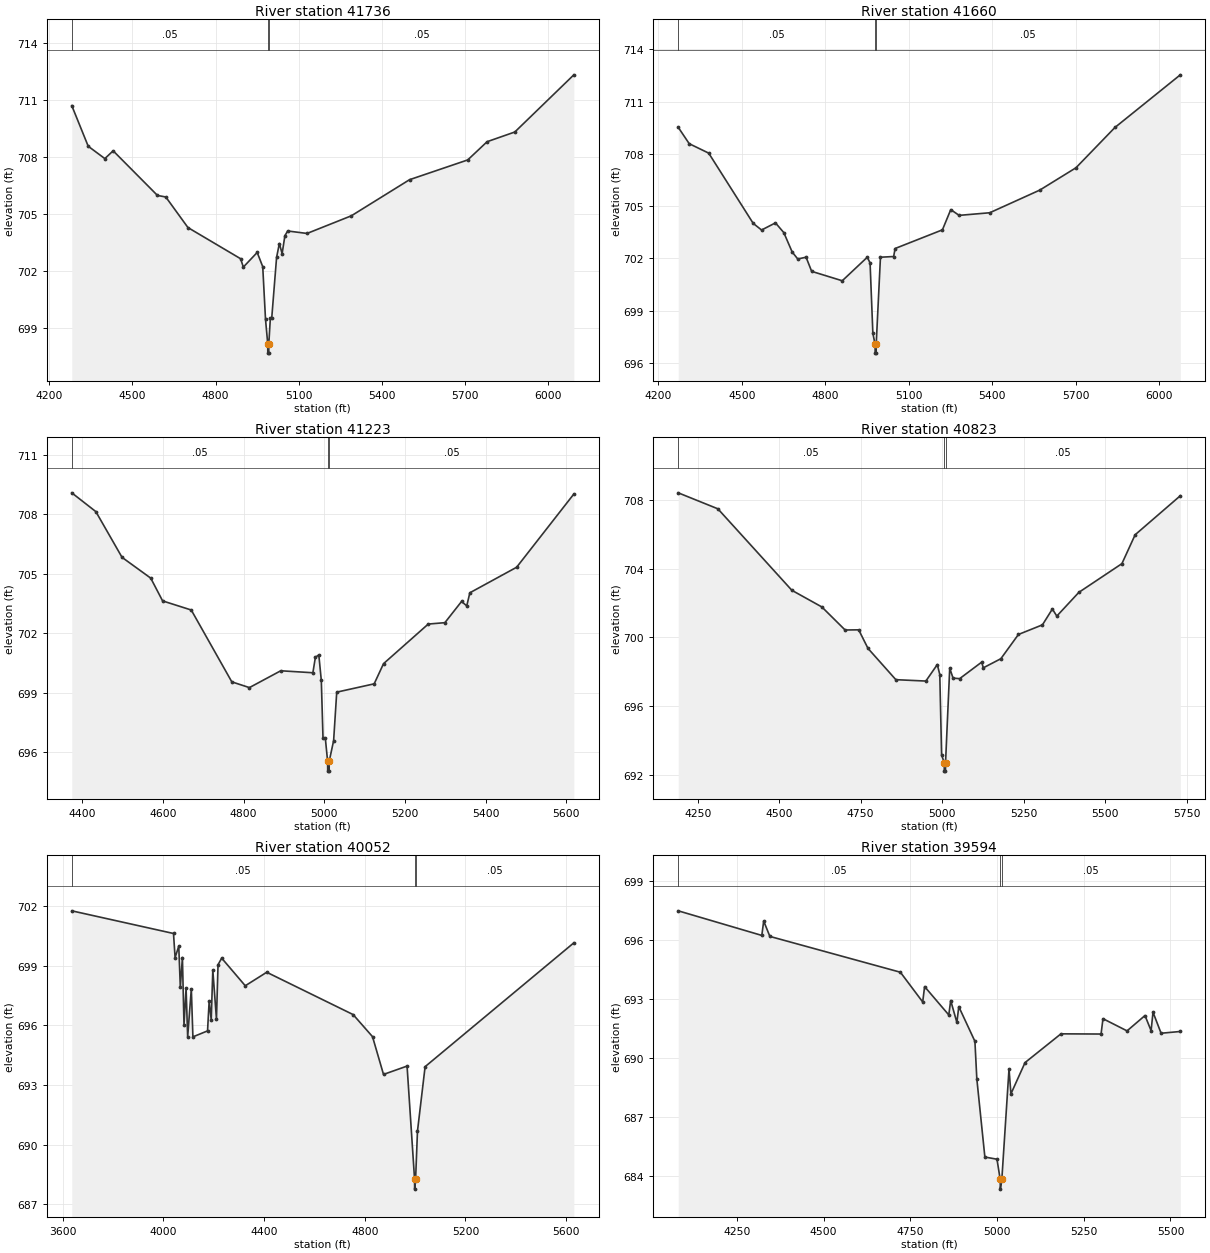
Type RM Length L Ch R = 1 ,41736   ,76,76,76
BEGIN DESCRIPTION:
Graham Branch 74.0
END DESCRIPTION:
XS GIS Cut Line= 3
       2360998.4      7092198.57       2360279.2      7092201.19
      2359185.91      7092203.78
#Sta/Elev= 30
  4280.8  710.73  4340.2  708.59  4400.2  707.94  4430.2  708.35  4590.2     706
  4620.2  705.92  4700.2  704.31  4890.2  702.67  4900.2  702.23  4950.2     703
  4970.2  702.25  4980.2  699.48  4988.2   698.2  4988.5   697.7    4992   697.7
  4992.2   698.2  4997.6  699.53  5002.6  699.53  5020.2  702.74  5030.2  703.47
  5040.2  702.94  5050.2  703.88  5060.2  704.13  5130.2     704  5290.2  704.93
  5500.2  706.83  5710.2  707.87  5780.2  708.83  5880.2  709.34  6093.3  712.35
#Mann= 3 ,-1 , 0
  4280.8     .05       0  4988.2    .033       0  4992.2     .05       0
Bank Sta=4988.2,4992.2
XS Rating Curve= 0 ,0
Exp/Cntr=0.3,0.1

Type RM Length L Ch R = 1 ,41660   ,437,437,437
BEGIN DESCRIPTION:
Graham Branch 73.0
END DESCRIPTION:
XS GIS Cut Line= 3
      2361008.51      7092129.81      2360279.52      7092125.22
      2359204.04      7092120.04
#Sta/Elev= 30
    4271  709.52  4310.5  708.58  4380.5  708.04  4540.5  704.01  4570.5  703.63
  4620.5  704.04  4650.5  703.48  4680.5  702.37  4700.5  701.97  4730.5  702.07
  4750.5  701.26  4860.5  700.72  4950.5  702.07  4960.5  701.74  4970.5  697.71
  4978.5  697.07  4978.8  696.57  4982.3  696.57  4982.5  697.07  4997.8  702.07
  5045.2  702.11  5050.5  702.57  5220.5  703.64  5250.5   704.8  5280.5  704.47
  5390.5  704.62  5570.5  705.92  5700.5   707.2  5840.5  709.51  6075.5  712.53
#Mann= 3 ,-1 , 0
    4271     .05       0  4978.5    .033       0  4982.5     .05       0
Bank Sta=4978.5,4982.5
XS Rating Curve= 0 ,0
Exp/Cntr=0.3,0.1

Type RM Length L Ch R = 1 ,41223   ,400,400,400
BEGIN DESCRIPTION:
Graham Branch 72.0
END DESCRIPTION:
XS GIS Cut Line= 3
      2360984.91       7092128.2        2360479.        7091760.
      2359878.98      7091609.99
#Sta/Elev= 30
  4374.3  709.09    4434  708.14  4498.9  705.83    4570  704.78  4599.4  703.63
  4670.4  703.17  4770.9  699.54  4814.5  699.25  4892.2   700.1  4971.8     700
    4978  700.78  4986.5   700.9  4992.7  699.61  4996.9   696.7  5002.6   696.7
  5008.3  695.53  5008.6  695.03  5012.1  695.03  5012.3  695.53  5023.2  696.57
  5030.9  699.02  5123.7  699.44  5146.9  700.46  5257.7  702.46  5298.9  702.53
  5340.2   703.6  5353.1  703.38  5360.8  704.04  5476.7  705.33  5618.5  709.03
#Mann= 3 ,-1 , 0
  4374.3     .05       0  5008.3    .033       0  5012.3     .05       0
Bank Sta=5008.3,5012.3
XS Rating Curve= 0 ,0
Exp/Cntr=0.3,0.1

Type RM Length L Ch R = 1 ,40823   ,771,771,771
BEGIN DESCRIPTION:
Graham Branch 71.0
END DESCRIPTION:
XS GIS Cut Line= 3
       2361192.8      7092037.93      2360662.17       7091426.6
      2359942.54      7091298.15
#Sta/Elev= 30
  4190.5  708.41  4312.1  707.48  4539.1  702.74  4631.2  701.77  4702.5  700.43
  4744.2  700.44  4772.7  699.36  4858.2  697.54  4950.3  697.46  4985.4  698.42
    4993  697.84  4998.6  693.15  5006.7  692.72  5006.9  692.22  5010.4  692.22
  5010.7  692.72  5023.5  698.21  5033.7  697.63    5054   697.6  5121.5  698.56
  5126.6  698.23  5180.4  698.76  5234.3  700.17    5308  700.73  5338.4  701.65
  5352.1  701.24  5419.7  702.62  5551.8  704.29  5592.4  705.97    5731  708.24
#Mann= 3 ,-1 , 0
  4190.5     .05       0  5006.7    .033       0  5010.7     .05       0
Bank Sta=5006.7,5010.7
XS Rating Curve= 0 ,0
Exp/Cntr=0.3,0.1

Type RM Length L Ch R = 1 ,40052   ,458,458,458
BEGIN DESCRIPTION:
Graham Branch 70.0
END DESCRIPTION:
XS GIS Cut Line= 3
      2361750.97      7091833.37      2360928.34      7090744.73
      2360304.03        7090835.
#Sta/Elev= 30
  3635.5  701.76  4039.8  700.62  4046.1  699.41  4060.7  699.98  4066.9  697.92
  4075.2  699.41  4081.5  696.03  4089.8  697.86  4096.1  695.42  4110.6  697.84
  4116.9  695.42  4175.1  695.72  4181.4   697.2  4189.7  696.28    4196  698.78
  4210.5  696.32  4216.8  699.05  4231.3  699.38    4325  697.99  4410.3  698.67
  4753.7  696.54  4830.7  695.43  4874.4  693.53    4968  693.95  4997.8  688.26
  4998.1  687.76  5001.9  688.26  5009.4  690.68  5039.7  693.92  5630.8  700.15
#Mann= 3 ,-1 , 0
  3635.5     .05       0  4997.8    .033       0  5001.9     .05       0
Bank Sta=4997.8,5001.9
XS Rating Curve= 0 ,0
Exp/Cntr=0.3,0.1

Type RM Length L Ch R = 1 ,39594   ,338,338,338
BEGIN DESCRIPTION:
Graham Branch 69.0
END DESCRIPTION:
XS GIS Cut Line= 4
      2361452.06      7091174.55        2361079.        7090335.
      2360890.55      7089917.59      2360862.13      7089853.16
#Sta/Elev= 30
  4081.3  697.47  4322.2  696.22  4327.6  696.95  4345.4  696.17  4721.6  694.35
  4785.9  692.84  4791.4  693.62  4861.1  692.18  4866.6  692.91  4884.4   691.8
  4889.9   692.6  4936.4  690.84  4941.9  688.93  4965.1  684.96    5000  684.85
  5009.2  683.83  5009.7  683.33    5014  683.83  5034.7  689.44  5040.2  688.17
  5080.9  689.76  5184.4  691.22    5300  691.21  5305.5  691.99  5374.9  691.37
  5426.6  692.15  5444.2  691.38  5449.7  692.32    5473  691.25  5528.4  691.34
#Mann= 3 ,-1 , 0
  4081.3     .05       0  5009.2     .05       0    5014     .05       0
Bank Sta=5009.2,5014
XS Rating Curve= 0 ,0
Exp/Cntr=0.3,0.1

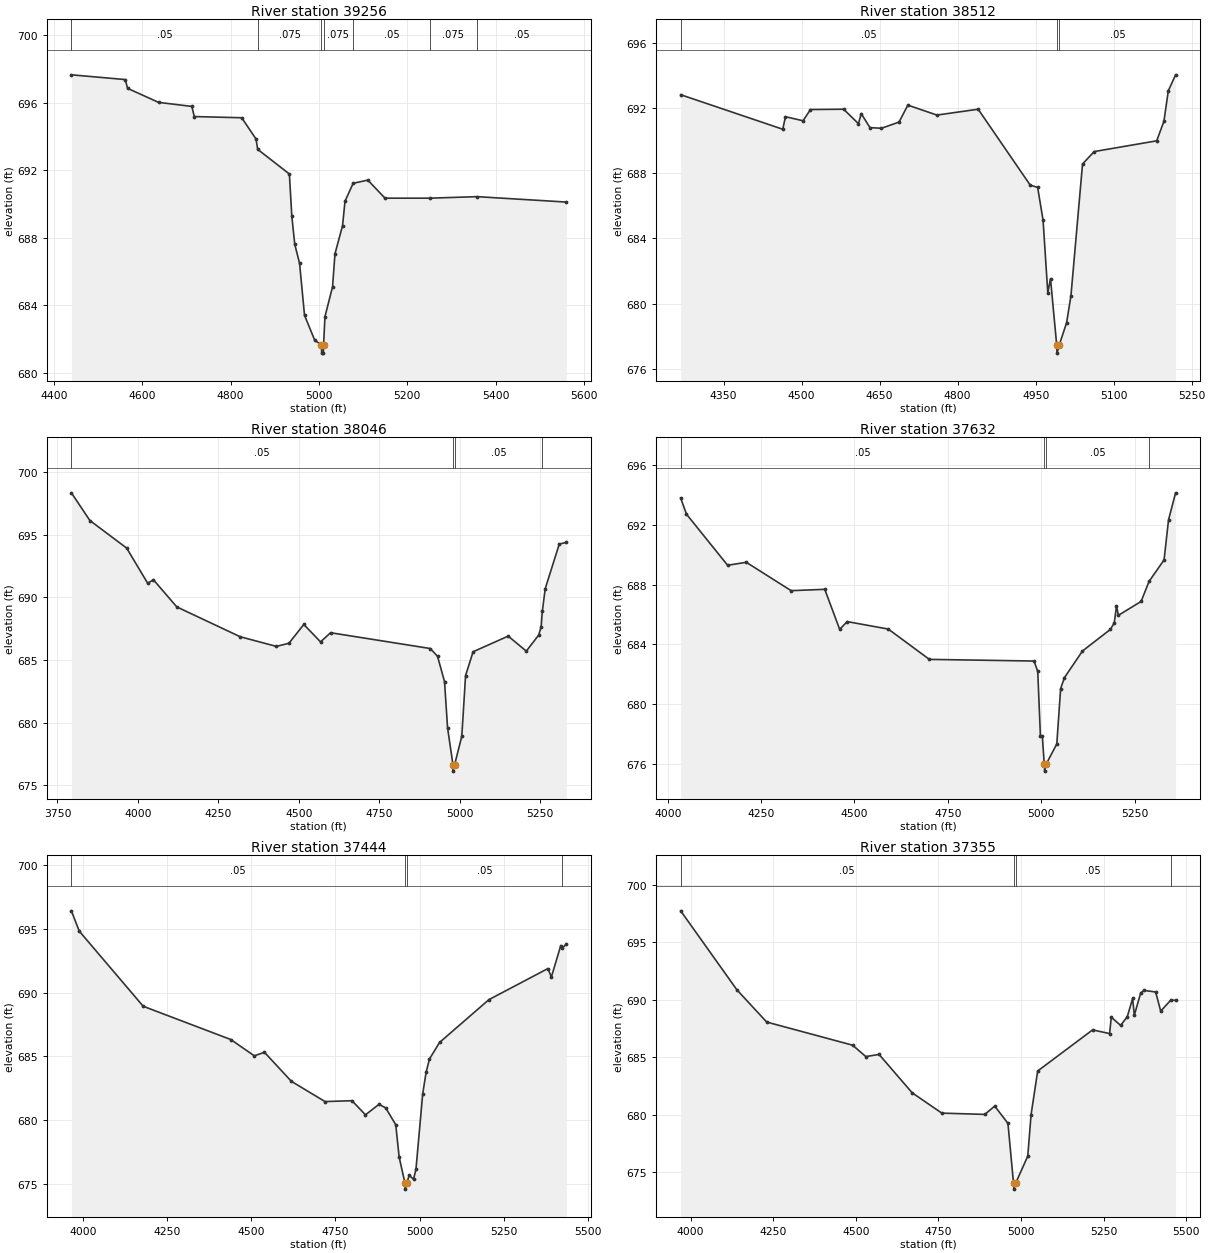
Type RM Length L Ch R = 1 ,39256   ,744,744,744
BEGIN DESCRIPTION:
Graham Branch 68.0
END DESCRIPTION:
XS GIS Cut Line= 4
       2361424.7      7090552.99      2361198.67      7090039.86
      2360994.77      7089614.56      2360953.36      7089536.18
#Sta/Elev= 30
  4439.3  697.65  4561.2  697.37  4566.6  696.85  4636.6  696.02  4712.1  695.78
  4717.6  695.18    4825  695.11  4857.5  693.85  4861.2  693.24    4933  691.78
  4938.5  689.29  4945.2  687.62  4956.1  686.49  4967.3  683.42  4990.6  681.93
  5005.6  681.68  5006.2  681.18  5009.9  681.18  5010.5  681.68  5013.6  683.34
  5030.8  685.11  5036.3  687.06  5053.4  688.72    5059  690.17  5077.4  691.23
  5110.7  691.42  5149.6  690.35  5250.7  690.35  5358.3  690.44  5560.3  690.12
#Mann= 7 ,-1 , 0
  4439.3     .05       0  4861.2    .075       0  5005.6     .07       0
  5010.5    .075       0  5077.4     .05       0  5250.7    .075       0
  5358.3     .05       0
Bank Sta=5005.6,5010.5
XS Rating Curve= 0 ,0
Exp/Cntr=0.3,0.1

Type RM Length L Ch R = 1 ,38512   ,466,466,466
BEGIN DESCRIPTION:
Graham Branch 67.0
END DESCRIPTION:
XS GIS Cut Line= 3
      2361778.99        7089610.        2361079.        7089410.
      2360879.01        7089510.
#Sta/Elev= 30
  4267.4  692.82  4463.7   690.7  4468.9  691.47  4502.7  691.22    4517  691.91
  4580.7  691.93  4609.3  691.04  4614.5  691.66  4631.4   690.8  4653.5  690.76
  4687.3  691.14  4704.2  692.18  4760.1  691.57  4839.4  691.93  4939.5  687.27
  4953.8  687.13  4964.2  685.12  4973.3  680.66  4978.5  681.53  4990.4  677.46
    4991  676.96  4995.3  677.46  5009.4  678.82  5017.8  680.48  5040.1  688.57
  5062.5  689.33  5182.7  689.99  5196.6  691.19    5205  693.06    5219  694.04
#Mann= 3 ,-1 , 0
  4267.4     .05       0  4990.4    .033       0  4995.3     .05       0
Bank Sta=4990.4,4995.3
XS Rating Curve= 0 ,0
Exp/Cntr=0.3,0.1

Type RM Length L Ch R = 1 ,38046   ,414,414,414
BEGIN DESCRIPTION:
Graham Branch 66.0
END DESCRIPTION:
XS GIS Cut Line= 4
      2362044.29      7088681.24        2360879.        7089010.
      2360820.55      7089035.53      2360769.31      7089294.35
#Sta/Elev= 30
  3793.4  698.34  3850.8  696.13  3965.1  693.93  4030.5  691.12  4048.3   691.4
    4121  689.23    4318  686.85  4430.4  686.08  4469.6  686.33  4515.8  687.83
  4567.8  686.44    4599  687.17  4908.8  685.91  4931.4  685.29  4953.2  683.27
  4962.6  679.58  4979.5  676.62  4980.1  676.12  4984.4  676.62  5006.9  678.91
  5018.6  683.75    5042  685.65  5151.1   686.9  5207.4   685.7  5245.8  686.98
  5253.5  687.63  5257.3   688.9  5266.2  690.69  5309.9  694.25  5331.8  694.38
#Mann= 4 ,-1 , 0
  3793.4     .05       0  4979.5    .033       0  4984.4     .05       0
  5257.3    .075       0
Bank Sta=4979.5,4984.4
XS Rating Curve= 0 ,0
Exp/Cntr=0.3,0.1

Type RM Length L Ch R = 1 ,37632   ,188,188,188
BEGIN DESCRIPTION:
Graham Branch 65.0
END DESCRIPTION:
XS GIS Cut Line= 3
      2361844.63      7088607.46       2360879.6      7088630.05
        2360529.        7088710.
#Sta/Elev= 30
  4034.7   693.8  4050.3  692.72  4160.4   689.3  4210.4   689.5  4330.4   687.6
  4420.4  687.69  4460.4  685.01  4480.5  685.53  4590.5  685.03  4700.5     683
  4980.6  682.89  4990.6   682.2  4997.8  677.85  5002.9  677.85  5007.9  676.02
  5008.9  675.52  5013.8  676.02  5041.6  677.34  5051.9  681.05  5062.1  681.78
  5110.3  683.56  5185.2  685.01  5195.5  685.45  5201.4  686.57  5206.5  685.95
  5267.3  686.88  5288.6  688.22  5328.8  689.66  5340.7  692.34  5359.6  694.15
#Mann= 4 ,-1 , 0
  4034.7     .05       0  5007.9     .04       0  5013.8     .05       0
  5288.6    .075       0
Bank Sta=5007.9,5013.8
XS Rating Curve= 0 ,0
Exp/Cntr=0.3,0.1

Type RM Length L Ch R = 1 ,37444   ,89,89,89
BEGIN DESCRIPTION:
Mapping XS d4375e09
END DESCRIPTION:
XS GIS Cut Line= 6
      2361862.19      7088468.53      2360846.36      7088457.72
      2360744.36      7088457.72      2360642.36      7088457.72
      2360557.73      7088446.87      2360394.98        7088423.
#Sta/Elev= 30
    3966  696.41  3989.2  694.82  4179.2  688.92  4439.2  686.31  4509.2  685.03
  4539.2  685.31  4619.2  683.03  4719.2  681.44  4799.2  681.51  4839.2   680.4
  4879.2  681.22  4899.2  680.95  4929.2  679.62  4939.2  677.09  4956.3  675.07
  4957.2  674.57  4962.2  675.07  4969.2  675.66  4981.9  675.34  4989.2  676.13
  5009.2  682.05  5019.2  683.73  5029.2  684.78  5059.2  686.08  5205.8  689.44
  5381.1  691.88  5391.2  691.21  5419.2  693.68  5423.7  693.49  5435.7   693.8
#Mann= 4 ,-1 , 0
    3966     .05       0  4956.3    .033       0  4962.2     .05       0
  5423.7    .075       0
Bank Sta=4956.3,4962.2
XS Rating Curve= 0 ,0
Exp/Cntr=0.3,0.1

Type RM Length L Ch R = 1 ,37355   ,641,641,641
BEGIN DESCRIPTION:
Graham Branch 64.0
END DESCRIPTION:
XS GIS Cut Line= 4
      2361889.37      7088388.27      2360859.21      7088379.83
      2360641.93      7088372.65       2360394.5      7088336.18
#Sta/Elev= 30
  3969.8  697.72  4140.2  690.85  4230.2  688.06  4490.2  686.05  4530.2  685.06
  4570.2  685.25  4670.2  681.92  4760.2  680.15  4890.2  680.04  4920.2  680.76
  4960.2  679.26  4977.1  674.05  4978.1  673.55  4983.3  674.05  5020.2  676.42
  5030.2  680.02  5050.2  683.81  5216.4  687.38  5267.8  687.06  5272.9  688.48
  5301.2  687.77  5321.4  688.53  5337.5  690.11  5342.6  688.65  5361.9  690.59
    5372  690.81  5407.2  690.67  5422.5  689.01  5452.8  689.96  5467.5  689.95
#Mann= 4 ,-1 , 0
  3969.8     .05       0  4977.1    .033       0  4983.3     .05       0
  5452.8    .075       0
Bank Sta=4977.1,4983.3
XS Rating Curve= 0 ,0
Exp/Cntr=0.3,0.1

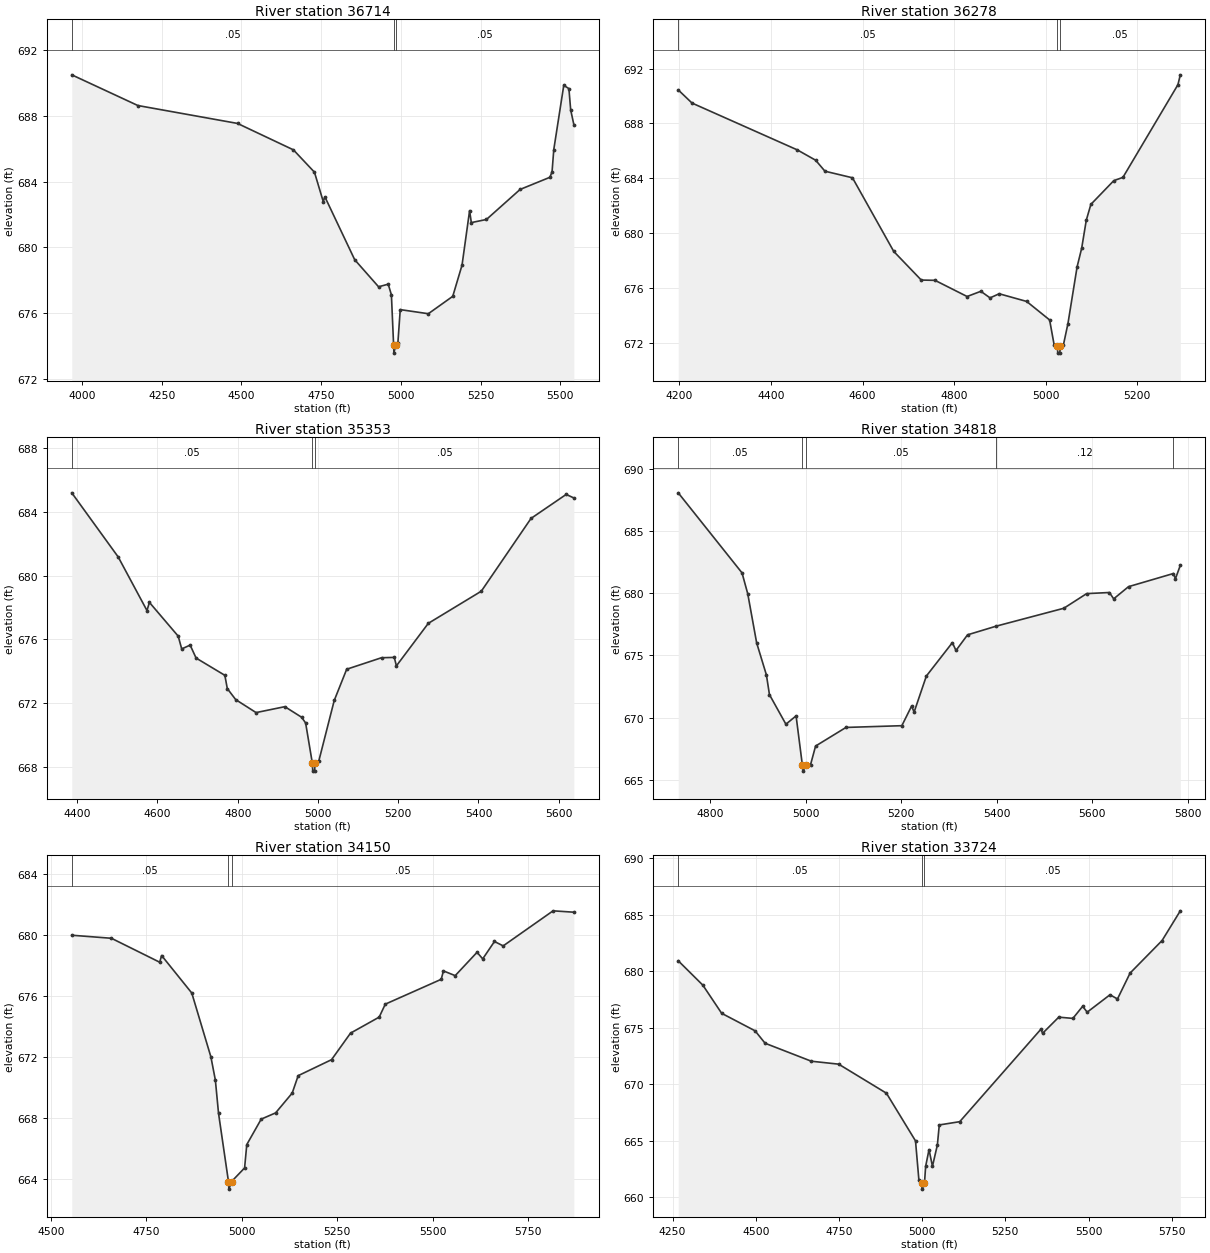
Type RM Length L Ch R = 1 ,36714   ,436,436,436
BEGIN DESCRIPTION:
Graham Branch 63.0
END DESCRIPTION:
XS GIS Cut Line= 3
      2361805.96      7087916.92        2360779.        7087810.
      2360279.91       7088021.1
#Sta/Elev= 30
    3968   690.5  4175.3  688.63  4487.7  687.54  4663.1  685.93    4729  684.57
  4756.6  682.78  4761.7  683.07  4855.2  679.24  4930.1  677.59  4960.3  677.75
  4970.3   677.1  4977.2  674.05  4978.2  673.55  4983.5  674.05  4990.5  674.14
    4998   676.2  5086.1  675.95  5162.7  677.01  5191.8  678.91  5215.5  682.23
  5220.9   681.5  5268.3  681.69  5373.9  683.52  5467.4  684.26  5474.1   684.6
  5479.5  685.95  5510.8  689.86  5526.9  689.66  5532.5  688.36  5542.4  687.47
#Mann= 3 ,-1 , 0
    3968     .05       0  4977.2     .04       0  4983.5     .05       0
Bank Sta=4977.2,4983.5
XS Rating Curve= 0 ,0
Exp/Cntr=0.3,0.1

Type RM Length L Ch R = 1 ,36278   ,925,925,925
BEGIN DESCRIPTION:
Graham Branch 62.0
END DESCRIPTION:
XS GIS Cut Line= 3
      2361329.02        7087660.       2360527.5       7087620.5
      2360233.77      7087630.64
#Sta/Elev= 30
  4197.5  690.44  4227.6  689.48  4457.8  686.06  4497.6  685.31  4517.9  684.51
    4578  684.03  4668.1  678.66  4728.2  676.57  4758.2  676.55  4828.3  675.37
  4858.3  675.75  4878.4  675.27  4898.4  675.57  4958.4  675.01  5008.5  673.66
  5018.5  671.82  5025.3  671.74  5026.4  671.24  5030.7  671.24  5031.7  671.74
  5038.5  671.82  5048.5  673.39  5068.5  677.53  5078.5  678.89  5088.6  680.94
  5098.6  682.09  5148.6  683.82  5168.6  684.06  5288.7  690.82  5293.9  691.54
#Mann= 3 ,-1 , 0
  4197.5     .05       0  5025.3     .04       0  5031.7     .05       0
Bank Sta=5025.3,5031.7
XS Rating Curve= 0 ,0
Exp/Cntr=0.3,0.1

Type RM Length L Ch R = 1 ,35353   ,535,535,535
BEGIN DESCRIPTION:
Graham Branch 61.0
END DESCRIPTION:
XS GIS Cut Line= 4
      2361294.91      7087413.66      2360843.49      7087102.87
        2360779.        7087110.      2360176.85      7087321.62
#Sta/Elev= 30
  4386.5  685.17  4502.2  681.16  4573.9  677.81    4580  678.32  4651.7  676.21
  4660.5  675.41  4681.5  675.65  4696.3  674.84    4768  673.76  4774.1  672.93
  4795.1  672.24  4845.8  671.43  4917.5   671.8  4959.2  671.14  4969.3  670.78
    4986  668.27  4987.1  667.77  4991.7  667.77  4992.7  668.27  5002.1   668.4
  5040.6  672.19  5071.6  674.14  5158.4  674.86  5190.2  674.88  5195.5  674.35
    5275  677.01  5407.1  679.02    5531  683.57  5618.6  685.07  5637.7  684.85
#Mann= 3 ,-1 , 0
  4386.5     .05       0    4986    .033       0  4992.7     .05       0
Bank Sta=4986,4992.7
XS Rating Curve= 0 ,0
Exp/Cntr=0.3,0.1

Type RM Length L Ch R = 1 ,34818   ,668,668,668
BEGIN DESCRIPTION:
Graham Branch 60.0
END DESCRIPTION:
XS GIS Cut Line= 3
      2361229.81      7086696.62      2360968.68      7086749.83
        2360229.        7087010.
#Sta/Elev= 30
  4733.5   688.1    4867  681.65    4879  679.96  4897.6  676.01    4918  673.43
  4924.4  671.84  4958.8  669.46  4980.1  670.13  4993.2  666.18  4994.4  665.68
  5001.3  666.18  5010.3  666.19  5020.9   667.7  5084.5   669.2  5201.4  669.34
  5221.8  670.92  5227.1  670.44  5252.7  673.34  5307.1  676.03  5314.7   675.4
  5338.9  676.66  5398.9  677.36  5540.3   678.8  5588.1  679.98  5635.7  680.07
  5644.7  679.56  5675.7  680.54  5769.6   681.6  5773.9  681.18  5784.1  682.26
#Mann= 5 ,-1 , 0
  4733.5     .05       0  4993.2    .033       0  5001.3     .05       0
  5398.9     .12       0  5769.6     .05       0
Bank Sta=4993.2,5001.3
XS Rating Curve= 0 ,0
Exp/Cntr=0.3,0.1

Type RM Length L Ch R = 1 ,34150   ,426,426,426
BEGIN DESCRIPTION:
Graham Branch 59.0
END DESCRIPTION:
XS GIS Cut Line= 3
      2361302.67      7086308.61      2360858.49      7086340.13
        2360097.      7086761.71
#Sta/Elev= 30
  4554.7  679.97  4658.6  679.77  4785.1   678.2  4790.1  678.64  4869.2  676.18
  4919.3  671.99    4931  670.47  4939.3  668.29  4965.3  663.82  4966.5  663.32
  4973.5  663.82  5007.6  664.71  5013.3  666.24  5051.1  667.91  5088.9  668.32
  5132.4  669.62    5148  670.76  5235.5  671.81  5285.2  673.55  5360.3   674.6
  5376.3  675.45  5522.9  677.08  5528.6  677.63  5559.5  677.32  5616.7  678.85
  5631.6  678.42  5662.4  679.56  5685.2  679.27    5816  681.57  5870.4  681.48
#Mann= 3 ,-1 , 0
  4554.7     .05       0  4965.3    .033       0  4973.5     .05       0
Bank Sta=4965.3,4973.5
XS Rating Curve= 0 ,0
Exp/Cntr=0.3,0.1

Type RM Length L Ch R = 1 ,33724   ,342,342,342
BEGIN DESCRIPTION:
Graham Branch 58.0
END DESCRIPTION:
XS GIS Cut Line= 3
      2361458.97      7085928.39      2360729.19      7085994.92
      2359972.99      7086167.74
#Sta/Elev= 30
  4267.2  680.91  4341.2  678.75  4397.7  676.26  4498.1  674.71  4528.2  673.61
  4667.1  672.02  4749.2  671.76  4892.7  669.19  4980.1  664.97  4990.2  661.53
  4998.7   661.2  4999.9   660.7    5007   661.2  5010.5  662.71  5020.7   664.2
    5031  662.72  5045.8  664.61  5051.5  666.38    5113  666.67  5356.8  674.85
  5361.9  674.49  5410.5  675.92  5452.9  675.81  5482.3  676.88  5495.9  676.36
  5564.4   677.9  5586.9  677.53  5624.8  679.82  5720.9   682.7  5775.7  685.33
#Mann= 3 ,-1 , 0
  4267.2     .05       0  4998.7    .033       0    5007     .05       0
Bank Sta=4998.7,5007
XS Rating Curve= 0 ,0
Exp/Cntr=0.3,0.1

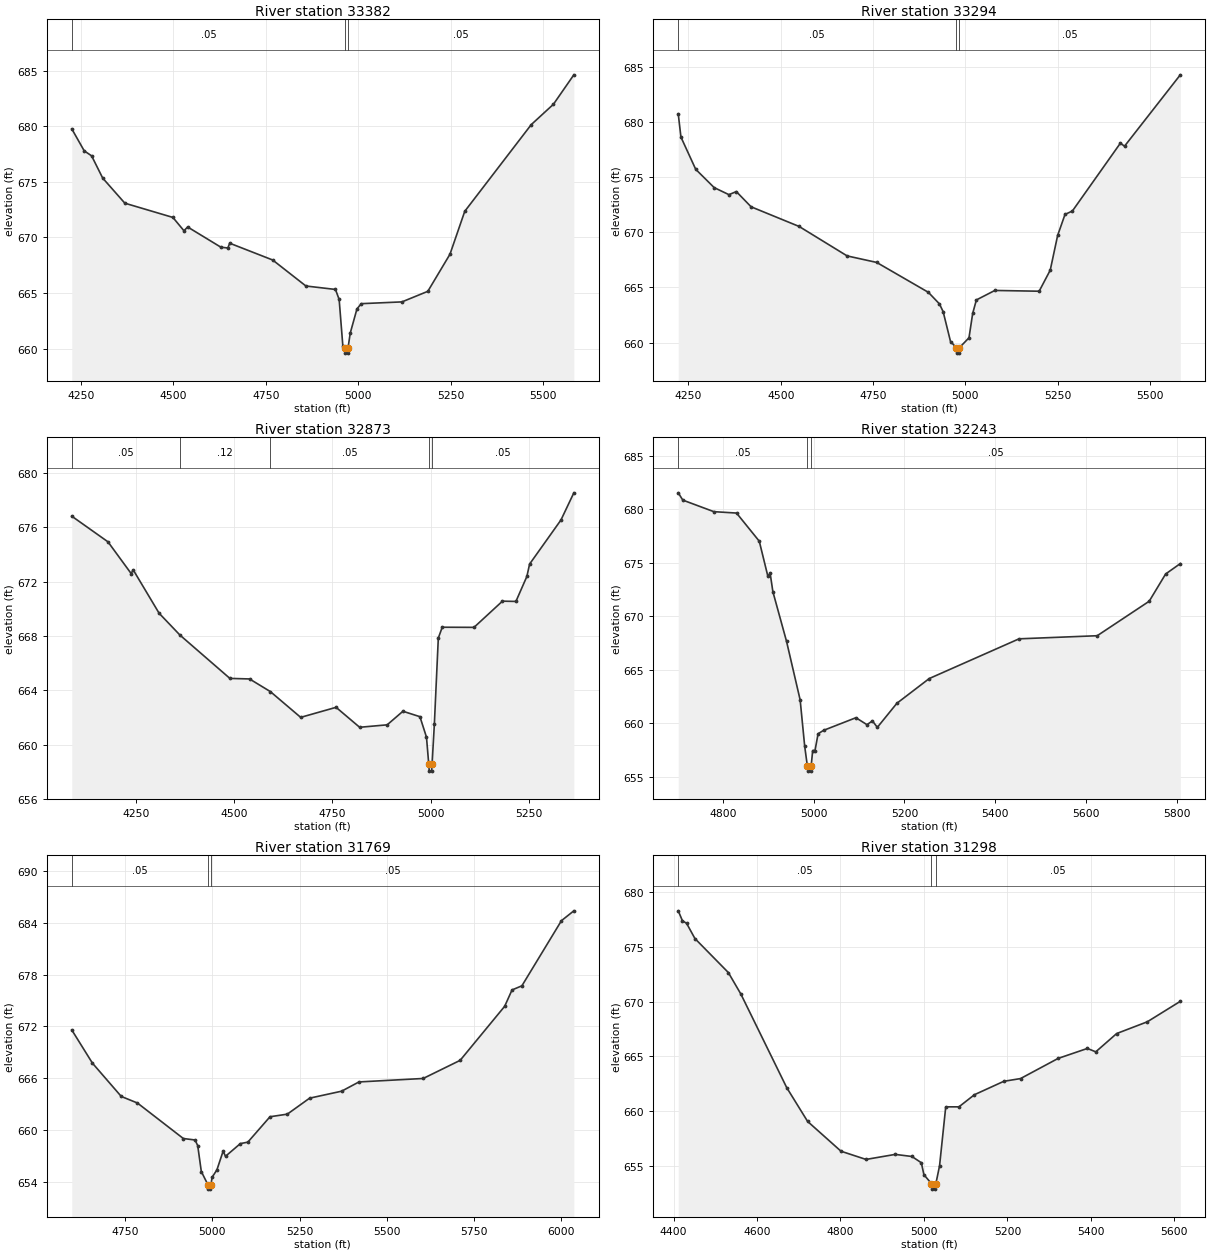
Type RM Length L Ch R = 1 ,33382   ,88,88,88
BEGIN DESCRIPTION:
Graham Branch 57.0
END DESCRIPTION:
XS GIS Cut Line= 3
      2361412.75      7085713.55      2360637.45      7085716.19
      2360053.65      7085716.16
#Sta/Elev= 30
  4224.7  679.77  4258.4  677.79  4278.4  677.34  4308.4  675.34  4368.4  673.08
  4498.4   671.8  4528.4   670.6  4538.4  670.94  4628.4  669.12  4647.2  669.05
  4652.2  669.48  4768.5  667.97  4858.5  665.63  4938.5  665.32  4948.5  664.42
  4958.5  660.23  4964.3  660.09  4965.5  659.59  4971.4  659.59  4972.7  660.09
  4978.5  661.39  4996.7  663.57  5008.5  664.04  5118.5   664.2  5188.5  665.15
  5248.5  668.49  5288.5  672.35  5468.5  680.15  5528.5  681.98  5583.8  684.63
#Mann= 3 ,-1 , 0
  4224.7     .05       0  4964.3    .033       0  4972.7     .05       0
Bank Sta=4964.3,4972.7
XS Rating Curve= 0 ,0
Exp/Cntr=0.3,0.1

Type RM Length L Ch R = 1 ,33294   ,421,421,421
BEGIN DESCRIPTION:
Mapping XS 86951b9f
END DESCRIPTION:
XS GIS Cut Line= 3
      2361406.26      7085631.52      2360630.17      7085630.22
      2360046.79      7085636.73
#Sta/Elev= 30
  4222.5  680.74  4229.8  678.63  4269.8  675.71  4319.8  674.05  4359.8  673.41
  4379.8  673.69  4419.8  672.31  4549.8  670.53  4679.8  667.86  4759.8  667.27
  4899.8  664.56  4929.8  663.51  4939.8  662.81  4959.8   660.1  4975.6  659.55
  4976.8  659.05  4982.7  659.05    4984  659.55  5009.8  660.44  5019.8  662.65
  5029.8  663.87  5079.8  664.73  5199.8  664.66  5229.8  666.57  5249.8  669.71
  5269.8  671.62  5289.8  671.93  5419.8  678.08  5430.9   677.8    5582  684.27
#Mann= 3 ,-1 , 0
  4222.5     .05       0  4975.6    .033       0    4984     .05       0
Bank Sta=4975.6,4984
XS Rating Curve= 0 ,0
Exp/Cntr=0.3,0.1

Type RM Length L Ch R = 1 ,32873   ,630,630,630
BEGIN DESCRIPTION:
Mapping XS 517af55b
END DESCRIPTION:
XS GIS Cut Line= 4
      2361441.13      7085322.76      2360555.75      7085278.49
      2360443.77      7085281.09      2360173.49      7085353.86
#Sta/Elev= 30
  4086.3  676.83  4178.5  674.94  4237.6   672.6  4242.6  672.88  4308.7  669.68
  4361.8  668.07  4488.9  664.88    4539  664.84  4591.9  663.91  4669.2  662.01
  4759.3  662.75  4819.3  661.28  4889.4  661.46  4929.5  662.46  4972.8  662.06
  4989.5  660.55  4995.3  658.55  4996.6  658.05  5002.5  658.05  5003.7  658.55
  5009.5  661.49  5019.6  667.85  5029.6  668.65  5110.5  668.64  5182.9  670.57
  5217.2  670.55  5245.1  672.39    5252   673.3  5331.9  676.55  5364.7  678.55
#Mann= 5 ,-1 , 0
  4086.3     .05       0  4361.8     .12       0  4591.9     .05       0
  4995.3    .033       0  5003.7     .05       0
Bank Sta=4995.3,5003.7
XS Rating Curve= 0 ,0
Exp/Cntr=0.3,0.1

Type RM Length L Ch R = 1 ,32243   ,474,474,474
BEGIN DESCRIPTION:
Graham Branch 55.0
END DESCRIPTION:
XS GIS Cut Line= 3
      2361227.36      7084925.36        2360929.        7084910.
      2360179.03      7085209.99
#Sta/Elev= 30
  4701.4  681.55  4711.5  680.87  4779.9  679.79  4829.9  679.66    4880  677.03
  4898.9  673.76    4904  674.02    4910  672.31  4940.1  667.67  4970.1   662.2
  4980.1  657.87  4985.9  656.05  4987.1  655.55  4993.1  655.55  4994.4  656.05
  4997.7  657.47  5002.8  657.47  5009.6  659.04  5021.7  659.36    5093  660.54
  5117.3  659.89  5129.4  660.24  5140.2  659.64  5183.3  661.89  5254.6   664.2
  5452.5  667.91  5624.8   668.2  5739.3  671.42  5775.6  673.97  5807.9  674.94
#Mann= 3 ,-1 , 0
  4701.4     .05       0  4985.9    .033       0  4994.4     .05       0
Bank Sta=4985.9,4994.4
XS Rating Curve= 0 ,0
Exp/Cntr=0.3,0.1

Type RM Length L Ch R = 1 ,31769   ,471,471,471
BEGIN DESCRIPTION:
Graham Branch 54.0
END DESCRIPTION:
XS GIS Cut Line= 3
      2361129.03      7084459.99        2360729.        7084560.
      2360028.97      7085310.03
#Sta/Elev= 30
  4597.5  671.59  4656.8  667.74  4739.3  663.89  4785.6  663.13  4917.1  659.02
  4950.6  658.85  4958.3   658.2  4968.6   655.2  4987.6  653.66  4988.8  653.16
  4994.8  653.16  4996.1  653.66  4999.5  654.53  5013.3  655.39  5031.1  657.56
  5037.9  656.96  5080.4  658.43  5101.9   658.6  5165.4  661.54    5215  661.84
  5278.8  663.69  5370.6   664.5  5420.2  665.57  5604.1  665.97  5710.1  668.07
  5837.7  674.33  5858.7  676.22    5887   676.7  6000.3  684.24  6035.8  685.38
#Mann= 3 ,-1 , 0
  4597.5     .05       0  4987.6    .033       0  4996.1     .05       0
Bank Sta=4987.6,4996.1
XS Rating Curve= 0 ,0
Exp/Cntr=0.3,0.1

Type RM Length L Ch R = 1 ,31298   ,487,487,487
BEGIN DESCRIPTION:
Graham Branch 53.0
END DESCRIPTION:
XS GIS Cut Line= 4
      2361228.97        7084210.        2360677.        7084210.
      2360568.49       7084162.6      2360036.77      7084130.05
#Sta/Elev= 30
  4411.3  678.28  4421.3  677.38  4431.3  677.14  4451.3  675.75  4531.3  672.65
  4561.3  670.69  4671.3  662.14  4721.3  659.06  4801.3  656.34  4861.3  655.59
  4931.3  656.05  4971.2  655.86  4993.8  655.29    5000   654.2  5018.1  653.38
  5019.6  652.88  5027.3  652.88  5028.7  653.38  5037.5  655.01  5052.3  660.39
  5083.9  660.39  5121.2   661.5  5191.4  662.72  5231.5  662.97  5321.6  664.81
  5391.7  665.72  5411.8  665.41  5461.9  667.08  5535.2  668.15  5614.4  670.02
#Mann= 3 ,-1 , 0
  4411.3     .05       0  5018.1    .033       0  5028.7     .05       0
Bank Sta=5018.1,5028.7
XS Rating Curve= 0 ,0
Exp/Cntr=0.3,0.1