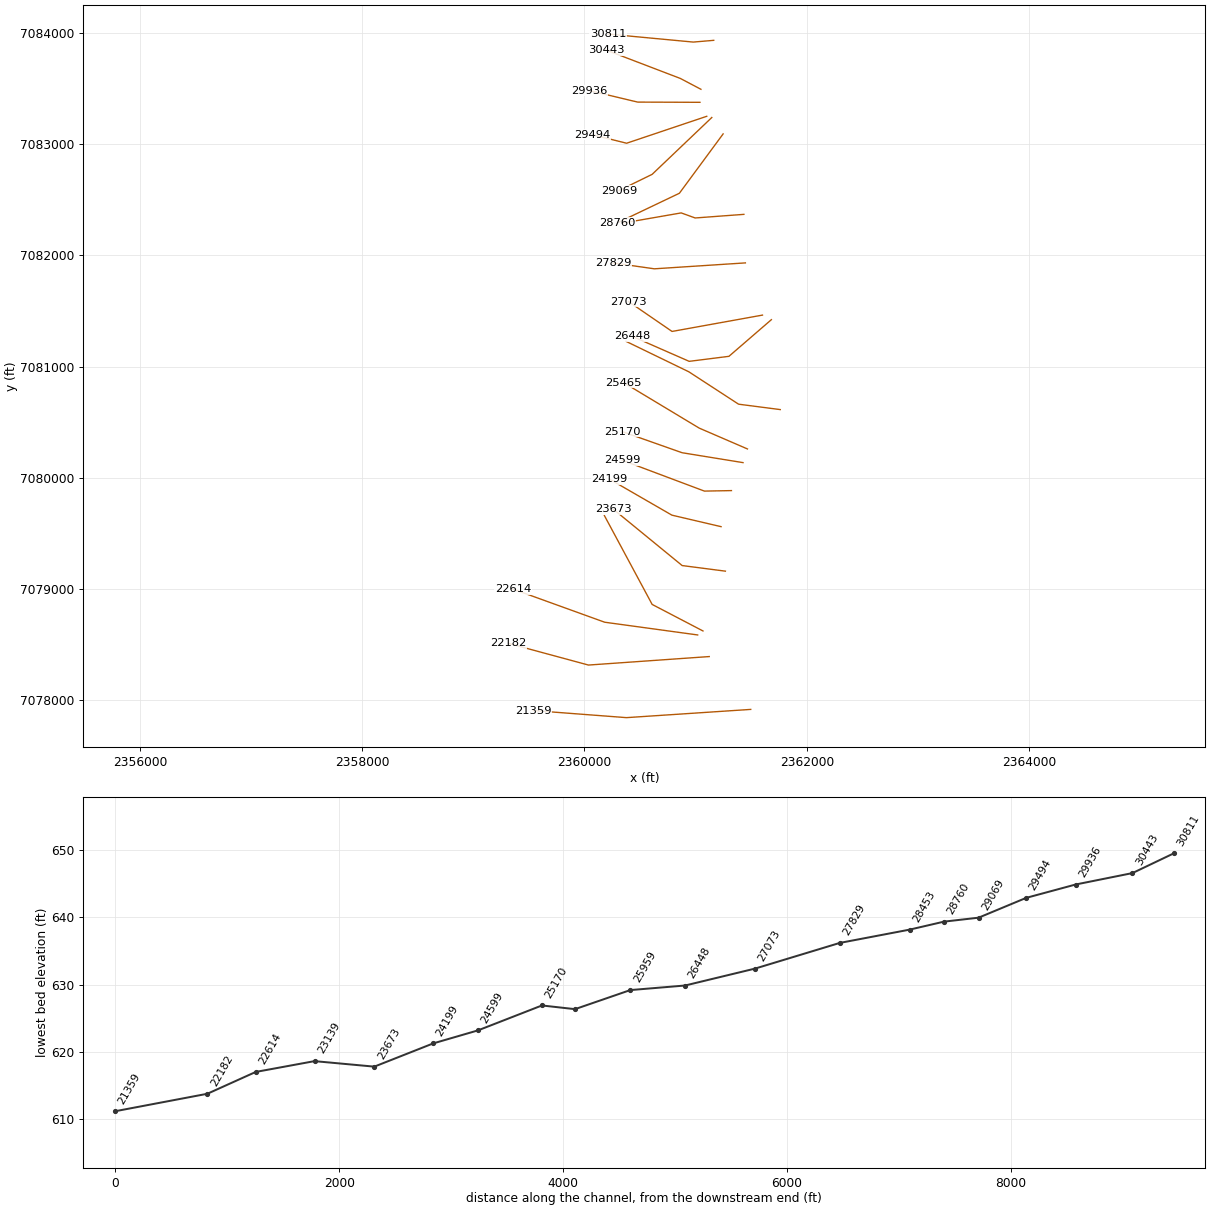
HEC-RAS study Graham Branch.prj: Graham Branch Base Level Engineering

--- Graham Branch.g01 (geometry) --- (continued)

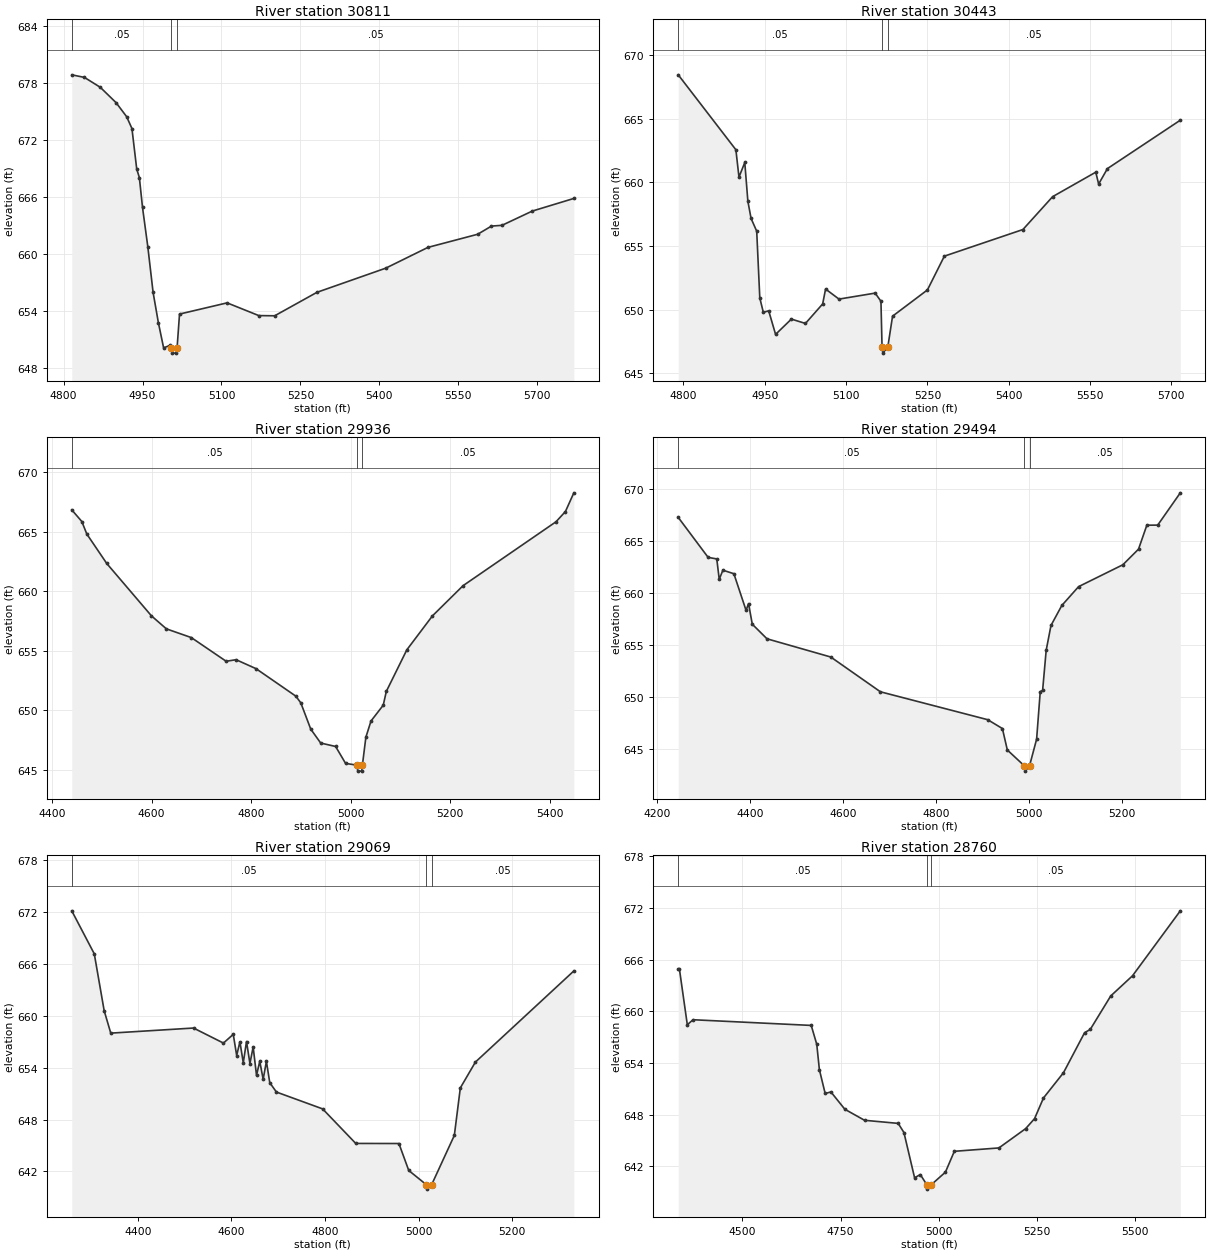
Type RM Length L Ch R = 1 ,30811   ,368,368,368
BEGIN DESCRIPTION:
Graham Branch 52.0
END DESCRIPTION:
XS GIS Cut Line= 3
       2361162.9      7083935.85      2360979.17      7083920.15
      2360213.15       7083992.2
#Sta/Elev= 30
  4815.6  678.81  4839.6  678.54  4869.7   677.5  4899.8  675.88  4919.9   674.4
  4929.9  673.16    4939  668.89    4944     668    4950  664.85    4960  660.74
  4970.1  655.91  4980.1  652.73  4990.1  650.07  5002.6  650.35  5004.9  650.02
  5006.4  649.52  5014.1  649.52  5015.6  650.02  5020.3  653.63  5110.7  654.81
  5170.9  653.47  5201.1  653.45  5281.4  655.92    5412  658.46  5492.3  660.65
  5586.7  662.03  5612.9  662.89  5632.9  662.97  5690.4  664.47  5769.4   665.8
#Mann= 3 ,-1 , 0
  4815.6     .05       0  5004.9    .033       0  5015.6     .05       0
Bank Sta=5004.9,5015.6
XS Rating Curve= 0 ,0
Exp/Cntr=0.3,0.1

Type RM Length L Ch R = 1 ,30443   ,507,507,507
BEGIN DESCRIPTION:
Graham Branch 51.0
END DESCRIPTION:
XS GIS Cut Line= 3
      2361047.85      7083495.33      2360862.58      7083592.92
      2360193.44      7083848.81
#Sta/Elev= 30
  4790.6  668.43  4896.9  662.55  4902.6   660.4  4913.3  661.55    4919  658.51
  4924.9  657.16  4935.3  656.16    4941  650.92  4947.5  649.79  4957.4  649.91
  4970.1  648.06  4999.2  649.26  5025.2  648.92  5056.9  650.45  5062.3  651.62
    5087  650.83  5153.7   651.3  5164.4  650.66  5166.4  647.09  5167.9  646.59
  5177.1  647.09  5185.8  649.49  5250.1  651.55  5281.3   654.2  5426.2  656.29
    5481  658.87  5560.5  660.79  5565.8  659.86    5582  661.07  5716.4  664.87
#Mann= 3 ,-1 , 0
  4790.6     .05       0  5166.4    .033       0  5177.1     .05       0
Bank Sta=5166.4,5177.1
XS Rating Curve= 0 ,0
Exp/Cntr=0.3,0.1

Type RM Length L Ch R = 1 ,29936   ,442,442,442
BEGIN DESCRIPTION:
Graham Branch 50.0
END DESCRIPTION:
XS GIS Cut Line= 3
      2361039.19      7083378.12      2360478.79      7083380.07
      2360042.52      7083484.08
#Sta/Elev= 30
  4439.6  666.84  4459.8  665.86  4469.8  664.81  4509.8  662.34  4599.8  657.93
  4629.8  656.84  4679.8  656.11  4749.8  654.12  4769.8  654.25  4809.8   653.5
  4889.8  651.19  4899.8  650.63  4919.8  648.42  4939.8  647.25  4969.8  646.96
  4989.8  645.54  5012.8  645.39  5014.3  644.89  5022.2  644.89  5023.6  645.39
  5030.6  647.74  5040.9   649.1  5065.5  650.43  5071.7  651.59  5112.9  655.08
  5164.3  657.93  5225.9  660.47  5412.7  665.84  5431.6   666.7  5448.5  668.27
#Mann= 3 ,-1 , 0
  4439.6     .05       0  5012.8    .033       0  5023.6     .05       0
Bank Sta=5012.8,5023.6
XS Rating Curve= 0 ,0
Exp/Cntr=0.3,0.1

Type RM Length L Ch R = 1 ,29494   ,425,425,425
BEGIN DESCRIPTION:
Graham Branch 49.0
END DESCRIPTION:
XS GIS Cut Line= 3
        2361100.      7083252.26        2360379.        7083010.
      2360069.11      7083087.33
#Sta/Elev= 30
  4244.7  667.27    4309  663.43  4327.6  663.28  4332.9  661.32  4340.7   662.2
  4364.4  661.86  4390.6  658.34  4395.9  658.99    4404  657.01  4435.6  655.61
  4572.8  653.86  4679.6  650.52  4910.4  647.84    4942  646.99  4952.6  644.93
  4989.4   643.4  4990.9   642.9  5000.3   643.4  5015.6  645.97  5023.4  650.53
  5028.5  650.65  5036.2  654.51  5046.5  656.89  5069.8  658.81  5105.9  660.62
  5201.1  662.72  5234.8  664.22  5252.7  666.52  5276.1  666.53  5324.7  669.63
#Mann= 3 ,-1 , 0
  4244.7     .05       0  4989.4    .033       0  5000.3     .05       0
Bank Sta=4989.4,5000.3
XS Rating Curve= 0 ,0
Exp/Cntr=0.3,0.1

Type RM Length L Ch R = 1 ,29069   ,309,309,309
BEGIN DESCRIPTION:
Graham Branch 48.0
END DESCRIPTION:
XS GIS Cut Line= 3
       2361145.5      7083241.37      2360609.11      7082730.27
       2360311.2      7082584.42
#Sta/Elev= 30
  4259.1  672.17  4307.2  667.19  4328.3  660.61  4342.4  658.01  4519.2   658.6
  4583.1  656.86  4604.1  657.87  4611.4  655.42  4618.3  657.01  4625.5  654.58
  4632.4  657.04  4639.7  654.49  4646.6  656.41  4653.8  653.12  4660.7  654.75
    4668  652.67  4674.9  654.74  4682.1  652.27  4696.3  651.19    4795  649.24
  4865.8  645.24    4958  645.23    4979  642.11  5016.9  640.45  5018.4  639.95
  5027.8  640.45  5076.4  646.17  5089.2  651.67  5121.4  654.66  5331.7  665.21
#Mann= 3 ,-1 , 0
  4259.1     .05       0  5016.9    .033       0  5027.8     .05       0
Bank Sta=5016.9,5027.8
XS Rating Curve= 0 ,0
Exp/Cntr=0.3,0.1

Type RM Length L Ch R = 1 ,28760   ,307,307,307
BEGIN DESCRIPTION:
Graham Branch 47.0
END DESCRIPTION:
XS GIS Cut Line= 3
      2361247.53      7083093.83      2360853.97      7082559.91
      2360299.17      7082295.22
#Sta/Elev= 30
  4336.7  664.91  4339.7  664.91  4359.8  658.44  4374.4  659.02  4675.2  658.36
  4689.3  656.17    4696  653.22  4710.7  650.46  4725.3  650.64  4760.8  648.63
  4810.9  647.35  4896.6  646.99  4911.2  645.93  4938.3  640.68  4952.9  641.05
  4969.6  639.86  4971.1  639.36  4980.5  639.86  5016.8  641.33  5039.5  643.75
  5152.9  644.14    5221  646.38  5243.7  647.54  5266.4  649.94  5317.3  652.87
  5371.1  657.52  5385.4  657.89  5437.6  661.78    5493  664.12  5614.7  671.66
#Mann= 3 ,-1 , 0
  4336.7     .05       0  4969.6    .033       0  4980.5     .05       0
Bank Sta=4969.6,4980.5
XS Rating Curve= 0 ,0
Exp/Cntr=0.3,0.1

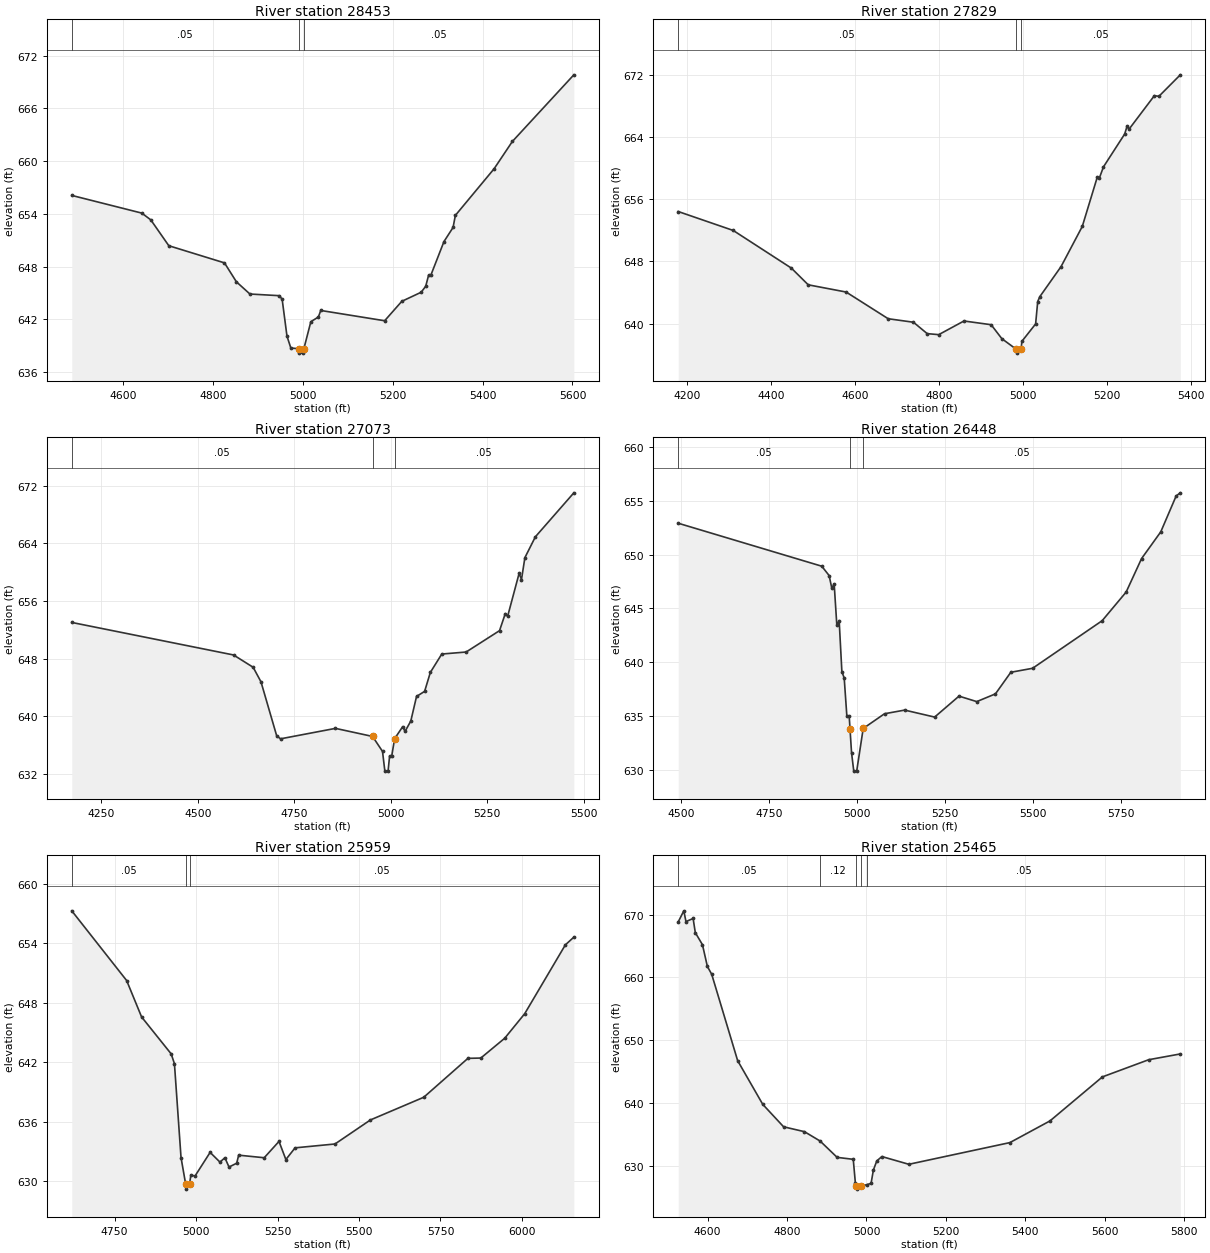
Type RM Length L Ch R = 1 ,28453   ,624,624,624
BEGIN DESCRIPTION:
Mapping XS 8db0944b
END DESCRIPTION:
XS GIS Cut Line= 4
      2361434.39      7082370.07      2360996.01      7082337.52
      2360870.14      7082383.09      2360334.16      7082289.78
#Sta/Elev= 30
  4485.6   656.1  4641.4  654.09  4661.5  653.32  4701.6  650.38  4825.5  648.43
    4852  646.28  4882.1  644.89  4947.9   644.7  4953.9  644.28  4964.6   640.1
  4973.2  638.75  4990.8  638.67  4992.3  638.17  5000.6  638.17  5002.2  638.67
  5017.7  641.74  5034.5  642.28  5039.8  643.02    5182  641.85  5220.2  644.06
  5263.2  645.09  5273.4  645.77  5279.8  647.03  5284.9  647.04    5314  650.85
  5334.3  652.46  5339.4  653.83  5425.6  659.13  5466.2  662.23  5603.1  669.81
#Mann= 3 ,-1 , 0
  4485.6     .05       0  4990.8    .033       0  5002.2     .05       0
Bank Sta=4990.8,5002.2
XS Rating Curve= 0 ,0
Exp/Cntr=0.3,0.1

Type RM Length L Ch R = 1 ,27829   ,756,756,756
BEGIN DESCRIPTION:
Graham Branch 46.0
END DESCRIPTION:
XS GIS Cut Line= 3
      2361447.87      7081933.29       2360628.8      7081880.06
      2360257.93      7081932.81
#Sta/Elev= 30
  4179.2  654.43  4310.2  651.99  4448.6  647.14  4488.7  644.99  4578.9  644.06
  4679.1  640.62  4739.2  640.17    4772   638.7  4799.4  638.57  4859.5  640.33
  4924.2  639.85  4949.7  638.05    4984  636.69  4985.6  636.19  4995.5  636.69
  4997.4  637.71  5030.1  639.95  5035.1  642.84  5040.2  643.47  5090.7  647.34
  5141.2  652.51  5176.8  658.84  5181.9  658.75  5191.7  660.19  5242.2  664.42
  5247.7   665.4  5252.7  665.05  5312.9  669.36  5323.6  669.27  5374.6  672.04
#Mann= 3 ,-1 , 0
  4179.2     .05       0    4984    .033       0  4995.5     .05       0
Bank Sta=4984,4995.5
XS Rating Curve= 0 ,0
Exp/Cntr=0.3,0.1

Type RM Length L Ch R = 1 ,27073   ,625,625,625
BEGIN DESCRIPTION:
Graham Branch 45.0
END DESCRIPTION:
XS GIS Cut Line= 3
      2361601.61      7081463.58      2360787.89      7081316.51
      2360396.83      7081585.08
#Sta/Elev= 30
  4173.1  653.03  4592.4  648.51  4643.2   646.8  4663.5  644.78  4704.2  637.28
  4714.3  636.86  4856.6  638.31  4952.7  637.19  4978.5  635.11  4984.6  632.37
  4992.9  632.37  4996.9  634.48  5002.4  634.48  5009.9  636.88  5030.8  638.55
  5036.9  637.89  5051.8  639.33  5066.7  642.75  5087.6  643.45  5102.5  646.09
  5132.1  648.64  5195.2  648.92  5281.8  651.89  5296.7  654.26  5302.8  653.88
  5332.6  659.86  5338.7  658.99  5347.5  662.03  5374.7  664.93  5474.4  671.04
#Mann= 3 ,-1 , 0
  4173.1     .05       0  4952.7    .033       0  5009.9     .05       0
Bank Sta=4952.7,5009.9
XS Rating Curve= 0 ,0
Exp/Cntr=0.3,0.1

Type RM Length L Ch R = 1 ,26448   ,489,489,489
BEGIN DESCRIPTION:
Mapping XS f3854f5f
END DESCRIPTION:
XS GIS Cut Line= 4
      2361681.64      7081422.45      2361299.68      7081092.58
      2360942.04      7081047.44      2360428.18      7081273.13
#Sta/Elev= 30
    4493  652.92  4900.8  648.92  4921.7  648.05  4929.3  646.87    4936  647.28
  4943.6  643.41  4950.2  643.86  4957.9  639.11  4964.5  638.52  4972.1  634.95
  4978.7  634.96    4981 633.789  4985.4  631.55  4991.7  629.85    5000  629.85
  5018.5  633.82    5079  635.19  5136.3  635.53  5221.5  634.88  5290.7  636.83
  5341.1  636.32  5394.2  637.04  5437.9  639.05  5499.7  639.42  5697.4  643.85
  5765.6  646.52  5809.3  649.63  5863.9  652.12  5907.6  655.46  5919.4  655.75
#Mann= 3 ,-1 , 0
    4493     .05       0    4981    .033       0  5018.5     .05       0
Bank Sta=4981,5018.5
XS Rating Curve= 0 ,0
Exp/Cntr=0.3,0.1

Type RM Length L Ch R = 1 ,25959   ,494,494,494
BEGIN DESCRIPTION:
Mapping XS 8954eb3b
END DESCRIPTION:
XS GIS Cut Line= 4
      2361761.53      7080613.41      2361386.49      7080662.02
      2360938.57      7080953.69      2360373.26      7081227.68
#Sta/Elev= 30
  4618.4  657.28  4786.8  650.24  4832.7  646.56  4923.5  642.83  4933.5  641.84
  4953.7  632.36    4968  629.67  4969.6  629.17  4979.8  629.67    4984   630.6
  4996.6  630.49    5043  632.88  5073.2   631.9  5088.4  632.34    5101   631.4
  5124.6  631.79  5130.6   632.6    5209  632.34  5254.4  633.99  5275.5  632.16
  5303.8  633.34  5426.3  633.73  5535.1  636.16  5698.7  638.45  5834.2  642.38
  5873.8  642.41  5947.1  644.41  6008.5  646.89  6133.2  653.84  6159.3  654.62
#Mann= 3 ,-1 , 0
  4618.4     .05       0    4968    .033       0  4979.8     .05       0
Bank Sta=4968,4979.8
XS Rating Curve= 0 ,0
Exp/Cntr=0.3,0.1

Type RM Length L Ch R = 1 ,25465   ,295,295,295
BEGIN DESCRIPTION:
Mapping XS 157e4a16
END DESCRIPTION:
XS GIS Cut Line= 3
      2361466.38      7080259.23      2361032.32      7080446.75
      2360354.08      7080855.07
#Sta/Elev= 30
  4525.9  668.83  4539.9  670.59  4545.4  668.88  4563.4  669.37  4568.9  667.12
  4586.9   665.2  4599.3  661.74  4610.2   660.5  4675.6  646.75  4738.8  639.81
  4791.3  636.24  4843.7  635.47  4883.2  633.98  4926.1  631.38  4966.7  631.07
  4972.1  627.25  4974.6  626.83  4976.2  626.33  4986.6  626.83  5000.8  627.03
  5011.6  627.25  5017.4  629.37    5026  630.82  5038.8  631.51  5106.7  630.28
  5361.2  633.73  5462.2  637.18  5594.2  644.18  5710.7  646.91  5790.4  647.83
#Mann= 5 ,-1 , 0
  4525.9     .05       0  4883.2     .12       0  4974.6     .07       0
  4986.6     .12       0  5000.8     .05       0
Bank Sta=4974.6,4986.6
XS Rating Curve= 0 ,0
Exp/Cntr=0.3,0.1

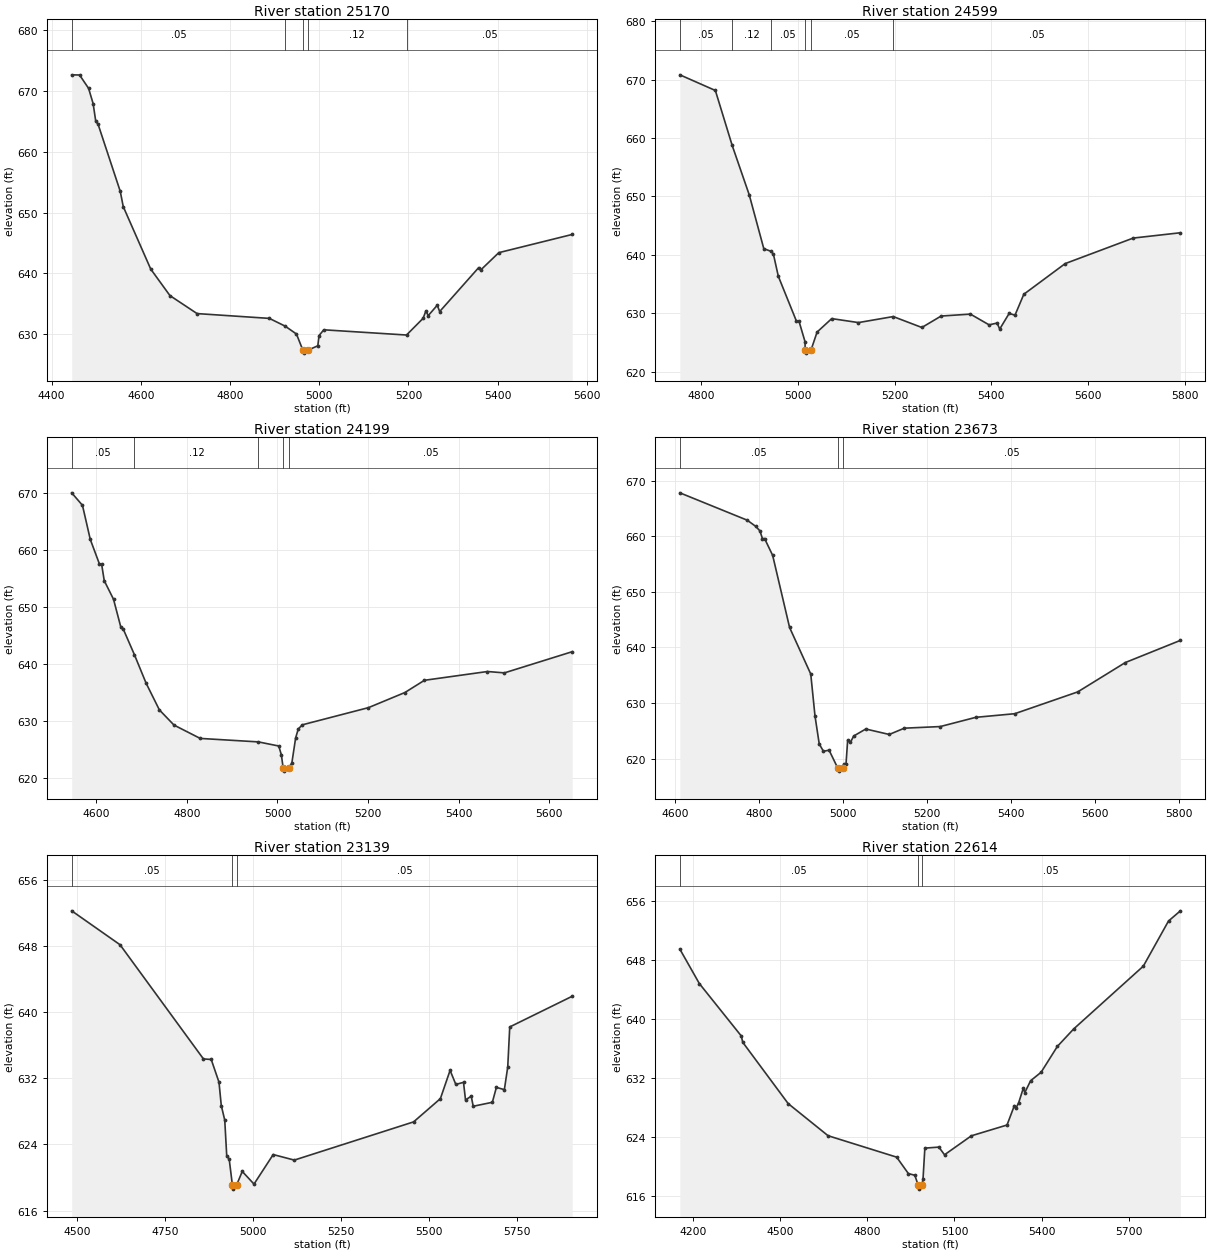
Type RM Length L Ch R = 1 ,25170   ,571,571,571
BEGIN DESCRIPTION:
Graham Branch 42.0
END DESCRIPTION:
XS GIS Cut Line= 3
      2361426.45      7080136.22      2360878.52      7080225.16
      2360343.76      7080413.93
#Sta/Elev= 30
  4444.9   672.7  4462.6  672.67  4482.8  670.47    4493  667.95  4498.9  665.03
  4503.9   664.6  4553.8  653.51  4560.5     651  4622.1  640.72  4665.2  636.35
    4726  633.39  4888.1   632.6  4923.6  631.32  4948.9  630.02  4963.1  627.38
  4964.8  626.88  4975.1  627.38  4996.7  628.09  4999.5  629.77  5010.1  630.72
  5195.6  629.86  5232.8  632.61    5239  633.82  5244.3  633.06  5264.6  634.77
  5269.9  633.72  5357.4  640.96  5362.7  640.62  5402.5  643.42  5567.1  646.42
#Mann= 5 ,-1 , 0
  4444.9     .05       0  4923.6     .12       0  4963.1     .07       0
  4975.1     .12       0  5195.6     .05       0
Bank Sta=4963.1,4975.1
XS Rating Curve= 0 ,0
Exp/Cntr=0.3,0.1

Type RM Length L Ch R = 1 ,24599   ,400,400,400
BEGIN DESCRIPTION:
Graham Branch 41.0
END DESCRIPTION:
XS GIS Cut Line= 3
       2361322.3      7079884.48      2361079.04      7079879.98
      2360339.23      7080157.92
#Sta/Elev= 30
  4756.7  670.82    4830  668.14  4864.7  658.74    4900  650.26    4930  641.06
  4945.5  640.58    4950  640.07    4960  636.33  4997.5  628.63  5002.7  628.63
  5015.2  625.12  5015.4  623.67  5017.1  623.17  5027.4  623.67  5040.1  626.78
  5070.3  629.08  5125.5   628.4  5197.3  629.43  5256.4  627.56  5296.2  629.52
  5356.7  629.85  5395.3  628.01  5411.8  628.32  5417.2  627.29  5436.7  629.97
  5448.7  629.66    5467  633.25  5552.4   638.5  5692.9  642.87  5790.3  643.78
#Mann= 6 ,-1 , 0
  4756.7     .05       0  4864.7     .12       0  4945.5     .05       0
  5015.4    .033       0  5027.4     .05       0  5197.3     .05       0
Bank Sta=5015.4,5027.4
XS Rating Curve= 0 ,0
Exp/Cntr=0.3,0.1

Type RM Length L Ch R = 1 ,24199   ,526,526,526
BEGIN DESCRIPTION:
Graham Branch 40.0
END DESCRIPTION:
XS GIS Cut Line= 3
      2361228.96      7079560.01      2360786.52      7079663.57
       2360222.7        7079989.
#Sta/Elev= 30
  4545.6  669.98  4569.4  667.79  4586.6  661.83  4606.7  657.55  4611.8  657.43
  4617.5  654.59    4638  651.33  4654.3   646.4  4659.5  646.11  4684.2  641.61
  4709.9  636.64  4739.3  631.95  4771.5   629.3  4829.4  626.96  4957.9  626.35
  5002.9  625.63  5008.7  624.07  5012.7  621.73  5014.3  621.23  5024.7  621.73
  5031.8  622.65  5040.2  627.05    5046  628.61  5054.9  629.34    5201  632.35
  5281.5     635  5324.6  637.14  5463.9  638.68  5501.2  638.44    5651  642.15
#Mann= 5 ,-1 , 0
  4545.6     .05       0  4684.2     .12       0  4957.9     .05       0
  5012.7    .033       0  5024.7     .05       0
Bank Sta=5012.7,5024.7
XS Rating Curve= 0 ,0
Exp/Cntr=0.3,0.1

Type RM Length L Ch R = 1 ,23673   ,534,534,534
BEGIN DESCRIPTION:
Graham Branch 39.0
END DESCRIPTION:
XS GIS Cut Line= 3
      2361268.06      7079159.65        2360879.        7079210.
      2360260.41      7079716.17
#Sta/Elev= 30
  4612.1  667.79  4772.5  662.87  4792.7  661.76  4802.7  660.95  4808.7  659.55
  4813.7  659.58    4833  656.55  4873.3  643.59  4923.7  635.22  4933.8  627.69
  4943.9  622.65    4954  621.33  4967.3  621.54  4988.3  618.27    4990  617.77
  5000.3  618.27  5001.9  618.99  5007.6  618.99  5011.6  623.36    5018  622.92
  5025.9  624.08  5054.7  625.34  5110.6  624.36  5146.5  625.49    5232  625.78
  5316.7  627.44  5409.3  628.09  5559.3  632.01  5672.7  637.29  5803.7  641.27
#Mann= 3 ,-1 , 0
  4612.1     .05       0  4988.3    .033       0  5000.3     .05       0
Bank Sta=4988.3,5000.3
XS Rating Curve= 0 ,0
Exp/Cntr=0.3,0.1

Type RM Length L Ch R = 1 ,23139   ,525,525,525
BEGIN DESCRIPTION:
Graham Branch 38.0
END DESCRIPTION:
XS GIS Cut Line= 3
      2361066.18      7078621.48      2360608.89      7078860.31
      2360179.01      7079659.99
#Sta/Elev= 30
  4484.1  652.24  4621.6  648.14  4858.9  634.33    4881  634.27  4903.1  631.52
  4909.6   628.7  4919.5  626.93  4925.1  622.63  4932.2   622.2  4941.2  619.09
  4942.9  618.59  4953.2  619.09  4969.3  620.73  5002.7   619.2  5057.3  622.77
  5117.4   622.1  5456.7  626.72  5532.9  629.53  5560.5  632.95  5576.8  631.25
  5598.7   631.5  5604.4  629.37  5620.6  629.83  5626.3  628.61  5680.7  629.09
  5692.2  630.89  5714.9  630.62  5724.5  633.36  5730.2   638.2  5907.9  641.91
#Mann= 3 ,-1 , 0
  4484.1     .05       0  4941.2    .033       0  4953.2     .05       0
Bank Sta=4941.2,4953.2
XS Rating Curve= 0 ,0
Exp/Cntr=0.3,0.1

Type RM Length L Ch R = 1 ,22614   ,432,432,432
BEGIN DESCRIPTION:
Mapping XS 4c174dbb
END DESCRIPTION:
XS GIS Cut Line= 3
      2361018.47      7078585.63      2360181.63      7078700.22
      2359355.27      7078998.82
#Sta/Elev= 30
  4154.5  649.47  4221.6  644.81  4365.9  637.72    4371  636.86  4527.4  628.56
  4664.8  624.21  4900.9  621.31  4941.2  619.09  4963.6  618.85  4975.2  617.48
    4977  616.98    4988  617.48  4991.7  618.36    4998  622.53  5046.2  622.67
  5065.7  621.63  5158.2   624.2  5280.9  625.66  5306.2  628.29  5311.5  627.93
  5320.9  628.67  5336.9  630.63  5342.2  630.06  5362.2  631.66  5398.2   632.8
  5454.2   636.3  5510.2  638.66  5750.2  647.17  5836.9  653.28  5877.8  654.66
#Mann= 3 ,-1 , 0
  4154.5     .05       0  4975.2    .033       0    4988     .05       0
Bank Sta=4975.2,4988
XS Rating Curve= 0 ,0
Exp/Cntr=0.3,0.1

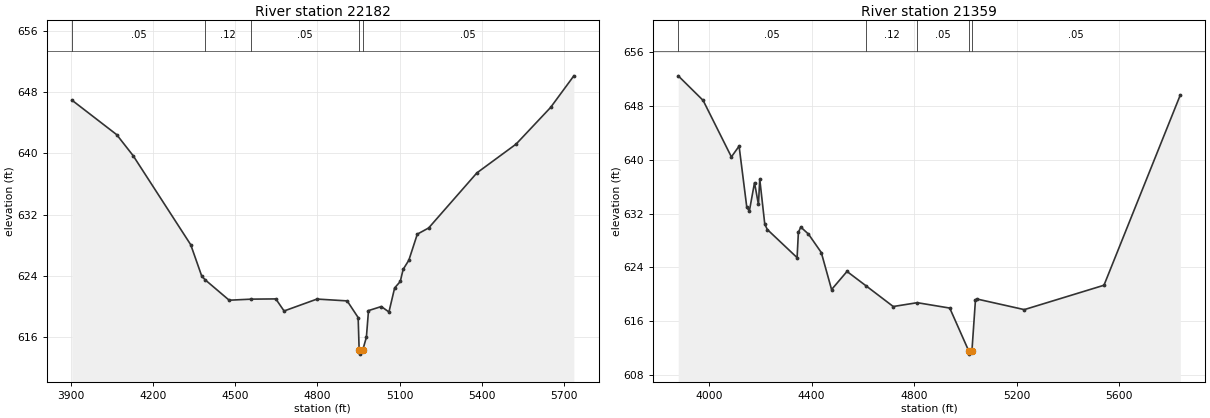
Type RM Length L Ch R = 1 ,22182   ,823,823,823
BEGIN DESCRIPTION:
Mapping XS a5d6b042
END DESCRIPTION:
XS GIS Cut Line= 3
      2361122.55      7078391.19      2360035.79       7078314.8
      2359317.07      7078509.24
#Sta/Elev= 30
  3902.7     647  4066.7  642.47  4126.8  639.72  4337.3  628.05  4377.4  623.95
  4390.6  623.44  4477.7  620.79  4558.8  620.93  4648.1  620.96  4678.2  619.38
  4798.5  620.94  4908.7   620.7  4948.8  618.52  4952.5  614.23  4954.3  613.73
  4965.3  614.23  4978.9  615.94  4986.6  619.43  5033.3  619.96  5061.3  619.25
  5082.1   622.4  5102.7  623.24  5113.1  624.83  5133.9  626.02  5164.9  629.44
  5206.4  630.25  5382.5  637.46  5525.7  641.23  5651.8  646.03  5736.7  650.17
#Mann= 5 ,-1 , 0
  3902.7     .05       0  4390.6     .12       0  4558.8     .05       0
  4952.5    .033       0  4965.3     .05       0
Bank Sta=4952.5,4965.3
XS Rating Curve= 0 ,0
Exp/Cntr=0.3,0.1

Type RM Length L Ch R = 1 ,21359   ,872,872,872
BEGIN DESCRIPTION:
Graham Branch 36.0
END DESCRIPTION:
XS GIS Cut Line= 3
      2361495.91      7077915.73      2360378.27      7077841.61
      2359542.08      7077905.17
#Sta/Elev= 30
  3879.9  652.46    3977  648.81  4087.3  640.42  4117.3  642.02  4147.4  632.93
  4157.4  632.39  4177.5  636.59  4192.8  633.36  4197.9  637.11  4217.6  630.41
  4227.6  629.63  4343.6  625.46  4348.6   629.2  4357.9     630  4387.9  628.96
    4438  626.22  4478.1  620.72  4538.3  623.41    4612  621.29  4718.7   618.2
  4812.4  618.77  4939.1  617.97  5012.9  611.63  5014.7  611.13  5025.7  611.63
  5039.4  619.17  5044.6  619.32  5229.9  617.74  5540.8  621.36  5838.6  649.62
#Mann= 5 ,-1 , 0
  3879.9     .05       0    4612     .12       0  4812.4     .05       0
  5012.9    .033       0  5025.7     .05       0
Bank Sta=5012.9,5025.7
XS Rating Curve= 0 ,0
Exp/Cntr=0.3,0.1